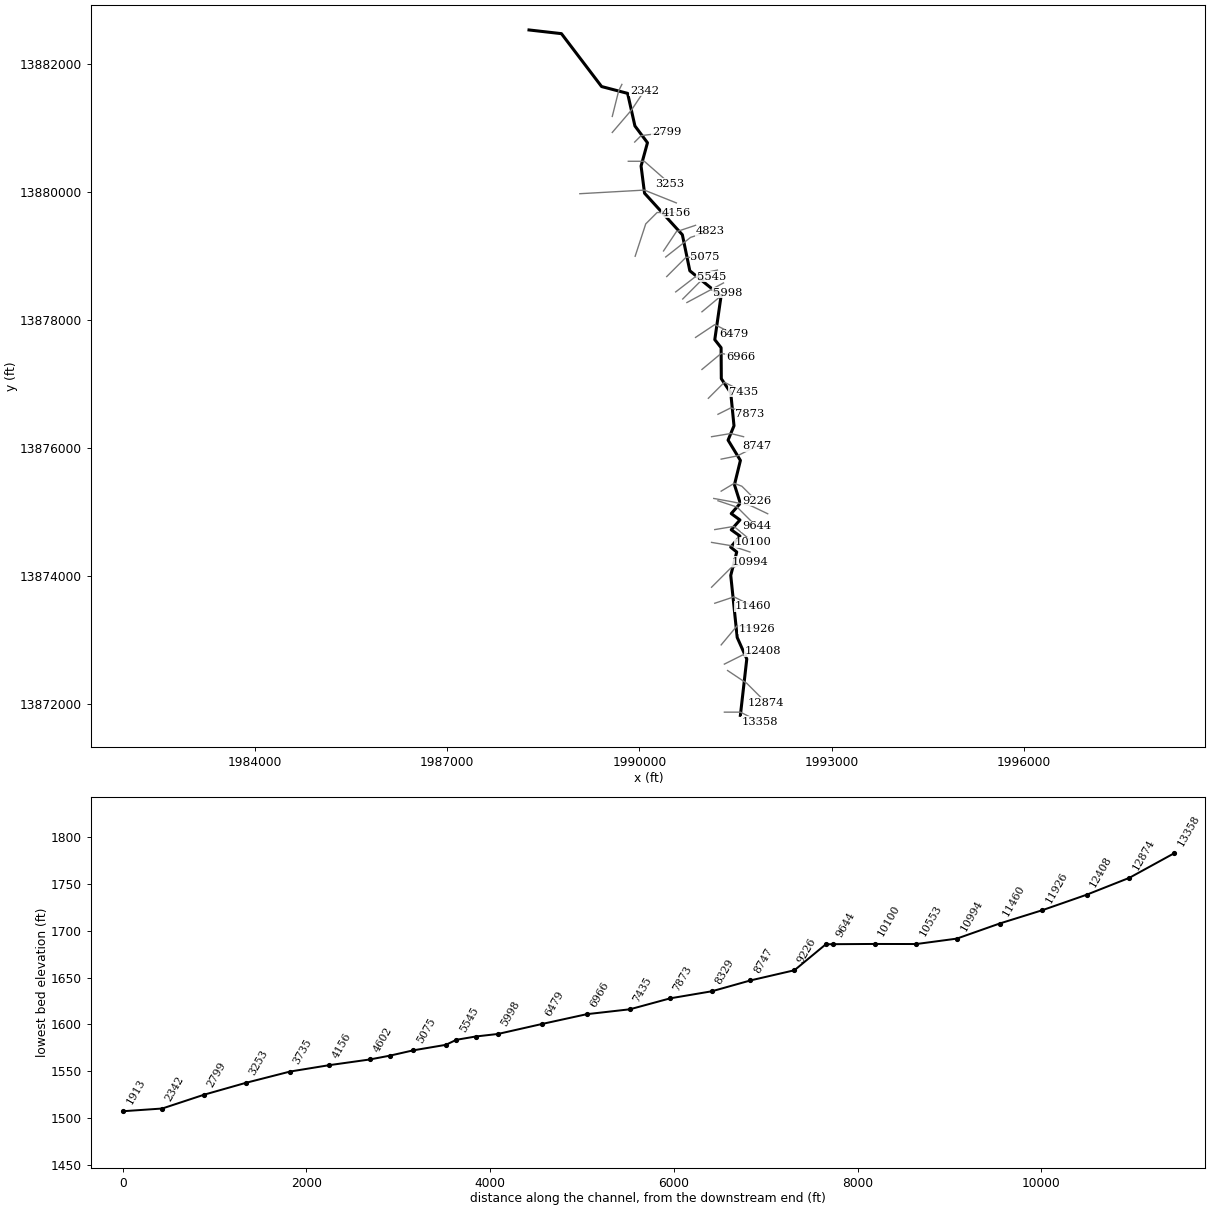
--- Stream0220.prj (project) ---

Proj Title=Stream0220 Base Level Engineering
Current Plan=p01
Default Exp/Contr=0.3,0.1
English Units
Geom File=g01
Flow File=f01
Plan File=p01
Y Axis Title=Elevation
X Axis Title(PF)=Main Channel Distance
X Axis Title(XS)=Station
BEGIN DESCRIPTION:
Stream0220
END DESCRIPTION:
DSS Export Rating Curves= 0
DSS Export Rating Curve Sorted= 0
DSS Export Volume Flow Curves= 0
DXF OffsetX= 0
DXF OffsetY= 0
DXF ScaleX= 1
DXF ScaleY= 10

--- Stream0220.p01 (plan) ---

Plan Title=Multiple Run
Short Identifier=Multiple
Geom File=g01
Flow File=f01
Subcritical Flow
K Sum by GR= 0
Std Step Tol= 0.01
Critical Tol= 0.01
Num of Std Step Trials= 20
Max Error Tol= 0.3
Flow Tol Ratio= 0.001
Split Flow NTrial= 30
Split Flow Tol= 0.02
Split Flow Ratio= 0.02
Log Output Level= 0
Friction Slope Method= 1
Unsteady Friction Slope Method= 2
Unsteady Bridges Friction Slope Method= 1
Parabolic Critical Depth
Global Vel Dist=  1 , 1 , 1
Global Log Level= 0
CheckData=True
Encroach Param= -1, 0, 0, 0
BEGIN DESCRIPTION:
Multiple Run
END DESCRIPTION:

--- Stream0220.f01 (steady flow) ---

Flow Title=Multiple
Number of Profiles=7
Profile Names=10-year,25-year,50-year,1pct_min,100-year,1pct_plu,500-year
River Rch & RM= Stream0220,Reach-1,13358
     240     373     490     315     629    1255    1017
River Rch & RM= Stream0220,Reach-1,12408
     765    1290    1788    1205    2404    4796    4293
River Rch & RM= Stream0220,Reach-1,8747
    1085    1861    2608    1773    3538    7059    6442
River Rch & RM= Stream0220,Reach-1,3253
    1553    2719    3862    2657    5302   10579    9895
Boundary for River Rch & Prof#=Stream0220,Reach-1,1
Up Type=0
Dn Type=3
Dn Slope=0.005
Boundary for River Rch & Prof#=Stream0220,Reach-1,2
Up Type=0
Dn Type=3
Dn Slope=0.005
Boundary for River Rch & Prof#=Stream0220,Reach-1,3
Up Type=0
Dn Type=3
Dn Slope=0.005
Boundary for River Rch & Prof#=Stream0220,Reach-1,4
Up Type=0
Dn Type=3
Dn Slope=0.005
Boundary for River Rch & Prof#=Stream0220,Reach-1,5
Up Type=0
Dn Type=3
Dn Slope=0.005
Boundary for River Rch & Prof#=Stream0220,Reach-1,6
Up Type=0
Dn Type=3
Dn Slope=0.005
Boundary for River Rch & Prof#=Stream0220,Reach-1,7
Up Type=0
Dn Type=3
Dn Slope=0.005

--- Stream0220.g01 (geometry) ---

Geom Title=Existing Conditions
Program Version=4.10

River Reach=Stream0220      ,Reach-1
Reach XY= 30
        1991575.       13871825.      1991674.94     13872704.97
      1991525.52     13873040.22      1991424.57     13874009.82
      1991517.97     13874375.21      1991424.39     13874449.92
      1991568.01     13874625.21      1991432.49     13874721.42
      1991568.01     13874875.21      1991431.99     13874974.79
      1991573.96     13875135.44      1991482.53     13875424.99
      1991575.39     13875804.87      1991382.81     13876121.59
      1991475.28     13876345.18      1991424.61     13876859.84
      1991277.24     13877080.93      1991273.94     13877564.56
      1991175.39     13877690.16      1991273.04      13878369.5
      1990785.76     13878765.32      1990669.24     13879327.53
      1990078.75     13879976.55      1990024.73     13880400.31
       1990124.4     13880764.38      1989928.55     13881026.47
      1989814.39     13881535.06      1989408.25     13881641.46
      1988781.48     13882467.31        1988275.       13882525.

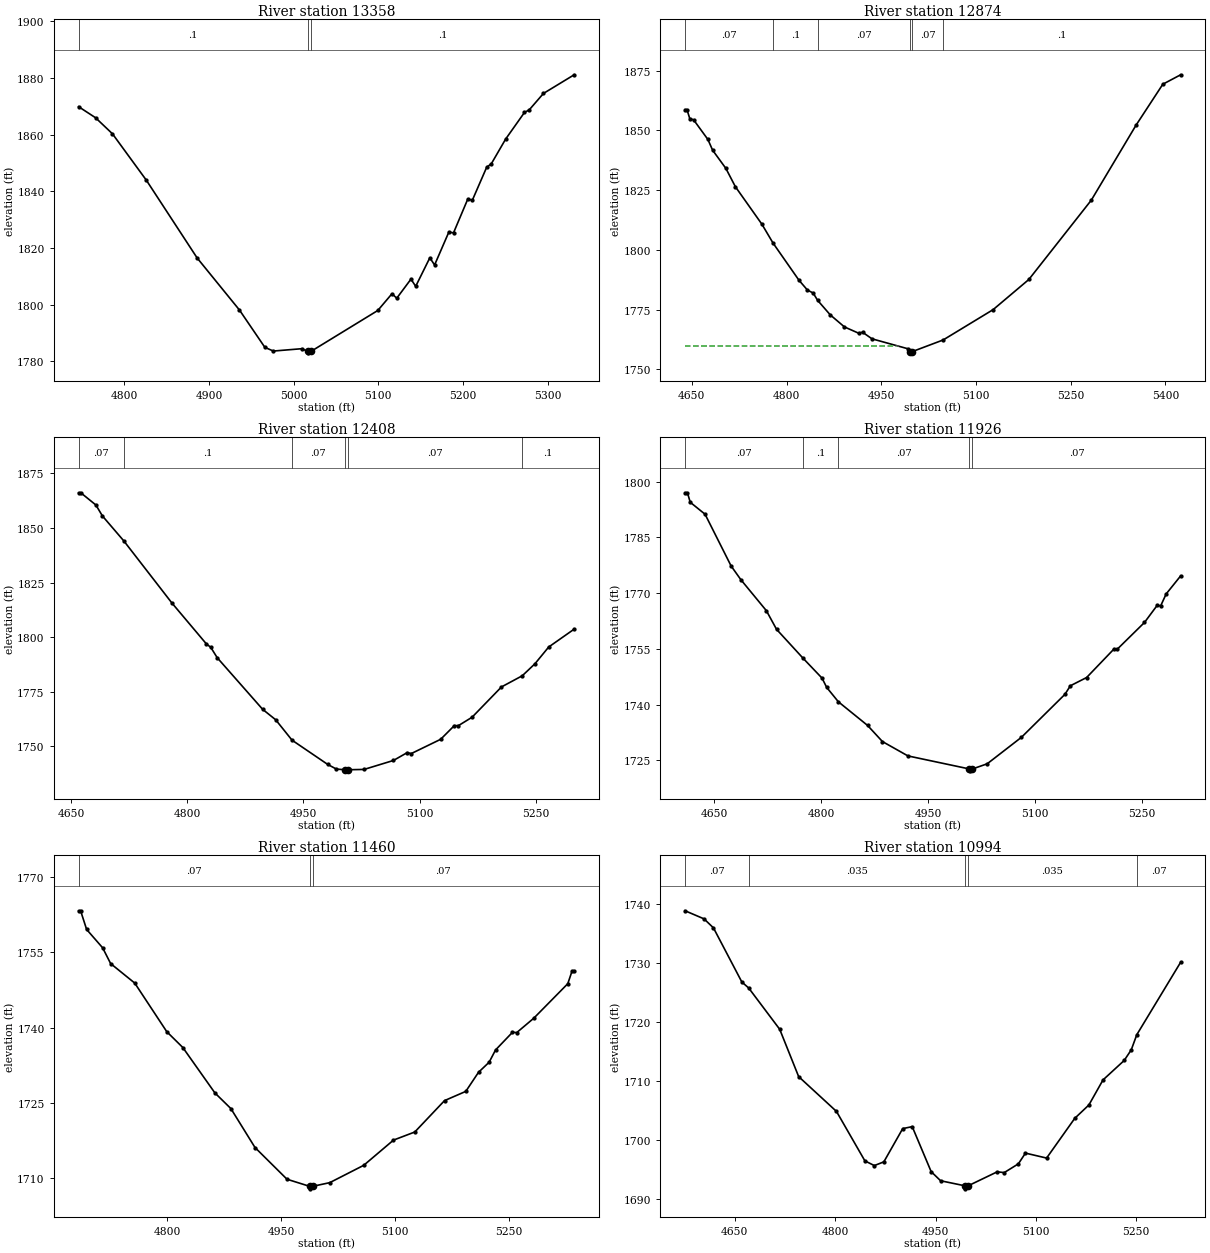
Type RM Length L Ch R = 1 ,13358   ,484,484,484
BEGIN DESCRIPTION:
Stream0220 29.0
END DESCRIPTION:
XS GIS Cut Line= 3
      1991324.97       13871875.        1991575.       13871875.
      1991874.97     13871725.02
#Sta/Elev= 30
    4746 1869.86    4766 1865.96    4786 1860.28    4826 1843.91    4886 1816.46
    4936 1798.08    4966 1784.91    4976  1783.6    5010 1784.44  5016.4 1783.47
  5016.6 1782.97  5020.4 1783.47  5099.4 1797.92  5116.2 1803.84  5121.8 1802.25
  5138.6 1808.99  5144.2 1806.45  5160.9 1816.53  5166.5 1813.98  5183.3 1825.57
  5188.9 1825.35  5205.7 1837.24  5211.2 1836.91    5228 1848.46  5233.6 1849.75
  5250.4 1858.41  5272.7 1867.84  5278.3 1868.74  5295.1 1874.54  5331.4 1881.13
#Mann= 3 ,-1 , 0
    4746      .1       0  5016.4     .05       0  5020.4      .1       0
Bank Sta=5016.4,5020.4
XS Rating Curve= 0 ,0
Exp/Cntr=0.3,0.1

Type RM Length L Ch R = 1 ,12874   ,466,466,466
BEGIN DESCRIPTION:
Stream0220 28.0
END DESCRIPTION:
XS GIS Cut Line= 3
      1991374.98     13872525.01        1991675.       13872325.
      1991974.97     13872025.03
#Sta/Elev= 30
  4639.3  1858.6  4642.3  1858.6  4646.8 1854.81  4652.8 1854.37  4675.4 1846.16
  4682.9 1841.66  4703.9 1834.04  4718.9  1826.4    4761 1810.67  4778.5 1802.84
  4819.6 1787.27  4833.1 1783.13  4842.1 1781.91  4849.2 1778.84  4869.2 1772.76
  4891.7 1767.71  4914.2 1765.09  4920.3 1765.51  4935.3 1762.74  4992.4 1758.57
  4994.9 1757.38  4995.1 1756.88  4998.9 1757.38    5048 1762.27  5127.2 1774.97
  5183.7 1787.57  5282.7 1820.79  5353.4  1852.1  5395.9 1869.27  5424.1 1873.22
#Mann= 6 ,-1 , 0
  4639.3     .07       0  4778.5      .1       0  4849.2     .07       0
  4994.9     .05       0  4998.9     .07       0    5048      .1       0
#XS Ineff= 2 , 0
         4977.29 1759.71
Permanent Ineff=
       F       F
Bank Sta=4994.9,4998.9
XS Rating Curve= 0 ,0
Exp/Cntr=0.3,0.1

Type RM Length L Ch R = 1 ,12408   ,482,482,482
BEGIN DESCRIPTION:
Stream0220 27.0
END DESCRIPTION:
XS GIS Cut Line= 3
      1991325.03     13872625.02        1991625.       13872775.
      1991924.99       13872825.
#Sta/Elev= 30
  4659.9 1866.16  4662.7 1866.16  4682.2 1860.55  4690.6 1855.54  4718.3 1844.07
  4780.1 1815.73  4824.8 1796.89  4830.4 1795.35  4838.7  1790.6  4897.4 1766.93
  4914.2 1762.15  4935.3  1752.8  4981.3  1741.7  4992.5 1739.56  5003.4 1739.25
  5003.7 1738.75  5007.4 1739.25  5028.2 1739.39  5066.2 1743.51    5084 1747.11
  5089.1 1746.65  5127.1  1753.2  5144.8 1759.49  5149.9 1759.44  5167.6  1763.3
  5205.6  1777.2  5232.4 1782.31  5248.7 1787.78  5266.5 1795.48  5299.4 1803.68
#Mann= 6 ,-1 , 0
  4659.9     .07       0  4718.3      .1       0  4935.3     .07       0
  5003.4     .05       0  5007.4     .07       0  5232.4      .1       0
Bank Sta=5003.4,5007.4
XS Rating Curve= 0 ,0
Exp/Cntr=0.3,0.1

Type RM Length L Ch R = 1 ,11926   ,466,466,466
BEGIN DESCRIPTION:
Stream0220 26.0
END DESCRIPTION:
XS GIS Cut Line= 3
      1991274.99     13872924.98        1991525.       13873225.
      1991825.03       13873175.
#Sta/Elev= 30
  4609.5 1796.97  4612.8 1796.97  4616.7 1794.42  4637.5  1791.2    4674 1777.29
  4687.6 1773.62  4723.4 1765.28  4737.7 1760.26  4774.8  1752.5  4801.5 1747.13
    4808 1744.64  4824.4 1740.77  4865.3 1734.42  4886.1 1730.09  4921.9 1726.22
  5008.2 1722.71  5008.4 1722.21  5012.2 1722.71    5033  1724.1  5081.1 1731.24
    5142 1742.78  5149.6 1745.08  5172.4  1747.3  5210.4  1754.9  5215.5 1754.94
  5253.5  1762.1  5271.2 1766.67  5276.3  1766.6  5283.9 1769.77  5304.2 1774.62
#Mann= 5 ,-1 , 0
  4609.5     .07       0  4774.8      .1       0  4824.4     .07       0
  5008.2     .05       0  5012.2     .07       0
Bank Sta=5008.2,5012.2
XS Rating Curve= 0 ,0
Exp/Cntr=0.3,0.1

Type RM Length L Ch R = 1 ,11460   ,466,466,466
BEGIN DESCRIPTION:
Stream0220 25.0
END DESCRIPTION:
XS GIS Cut Line= 3
      1991175.03     13873575.01        1991475.       13873675.
        1991775.       13873525.
#Sta/Elev= 30
  4683.9 1763.21  4686.5 1763.21  4694.4  1759.5  4715.5 1755.84    4726 1752.71
  4757.7 1748.83  4799.8 1739.17  4820.9 1736.02  4863.1 1726.99  4884.1 1723.88
  4915.8 1716.14  4957.9 1709.83  4987.6 1708.42  4987.8 1707.92  4991.6 1708.42
  5014.1 1709.15  5058.8  1712.6  5097.9 1717.61  5125.9 1719.22    5165 1725.46
    5193  1727.3  5209.7 1731.09  5223.7  1733.1  5232.1 1735.53  5254.4 1739.05
    5260 1738.99  5282.4 1741.85  5327.1 1748.71  5332.7 1751.22  5335.5 1751.22
#Mann= 3 ,-1 , 0
  4683.9     .07       0  4987.6     .05       0  4991.6     .07       0
Bank Sta=4987.6,4991.6
XS Rating Curve= 0 ,0
Exp/Cntr=0.3,0.1

Type RM Length L Ch R = 1 ,10994   ,441,441,441
BEGIN DESCRIPTION:
Stream0220 24.0
END DESCRIPTION:
XS GIS Cut Line= 3
      1991125.02     13873825.02        1991425.       13874125.
      1991725.04     13874225.01
#Sta/Elev= 30
  4575.8 1738.85  4604.1 1737.48  4618.2 1735.95  4660.6 1726.79  4670.8 1725.78
  4717.2 1718.78  4745.5 1710.77    4802 1704.88  4844.5  1696.5  4858.6 1695.71
  4872.8 1696.34    4901 1701.97  4915.2  1702.3  4943.5 1694.68  4957.6 1693.14
  4994.5 1692.27  4994.7 1691.77  4998.5 1692.27  5042.2 1694.65  5052.7 1694.52
  5073.8    1696  5084.4 1697.82    5116 1696.98  5158.1 1703.71  5179.2 1705.97
  5200.3 1710.21  5231.9  1713.5  5242.5  1715.3  5250.8 1717.87  5316.3 1730.13
#Mann= 5 ,-1 , 0
  4575.8     .07       0  4670.8    .035       0  4994.5    .035       0
  4998.5    .035       0  5250.8     .07       0
Bank Sta=4994.5,4998.5
XS Rating Curve= 0 ,0
Exp/Cntr=0.3,0.1

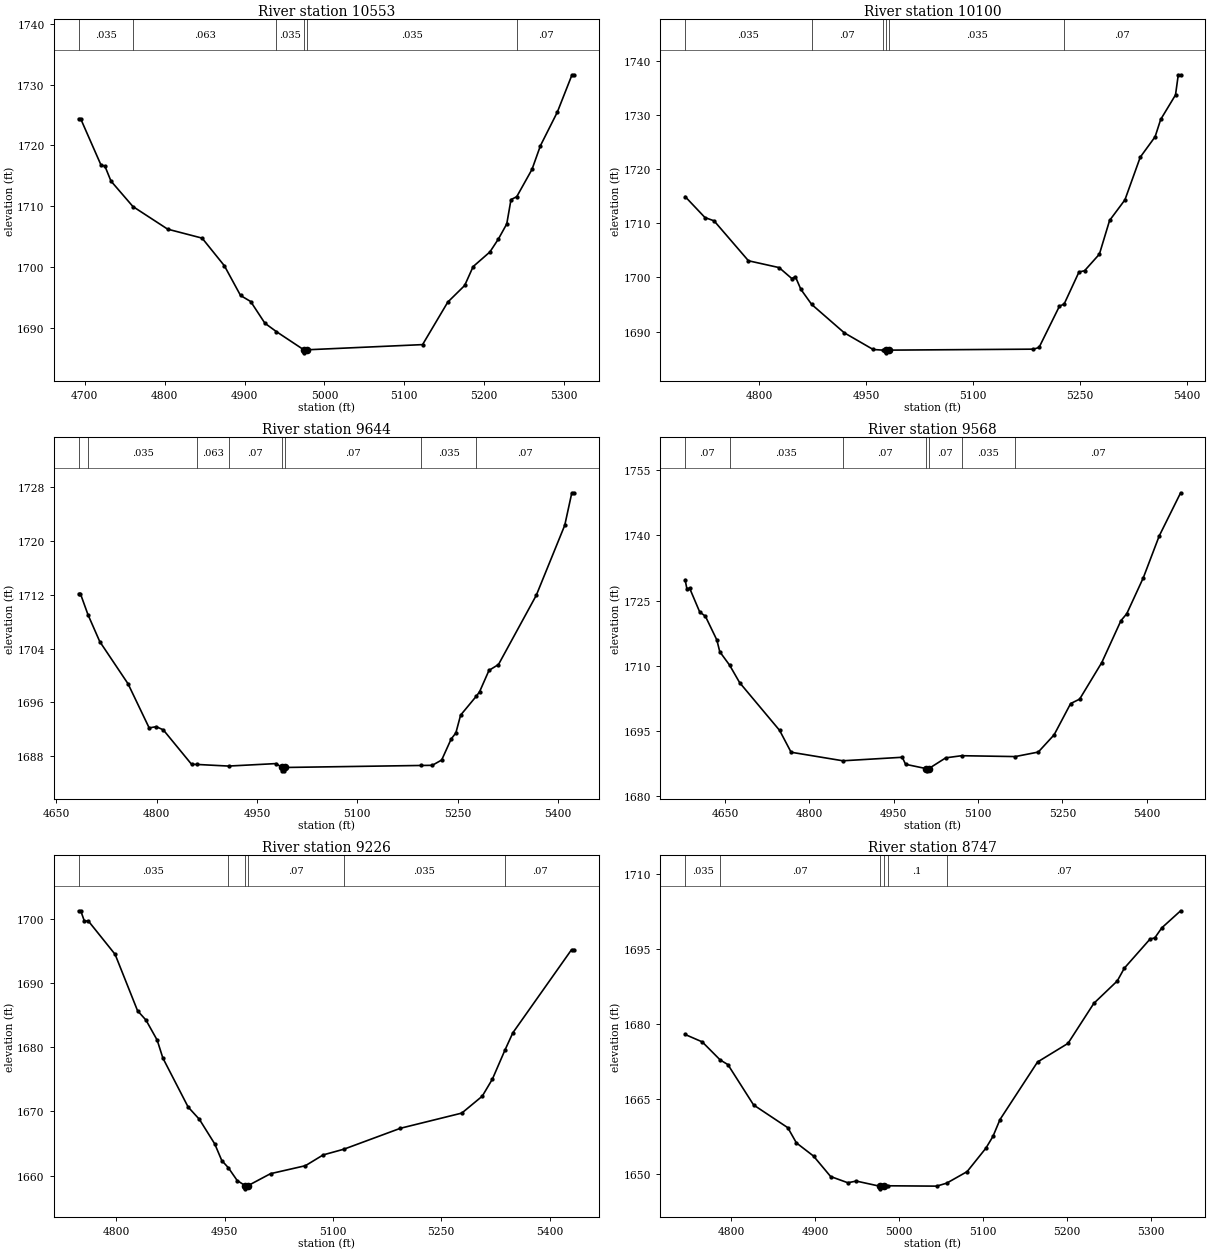
Type RM Length L Ch R = 1 ,10553   ,453,453,453
BEGIN DESCRIPTION:
Stream0220 23.0
END DESCRIPTION:
XS GIS Cut Line= 3
      1991125.01       13874525.        1991425.       13874475.
      1991725.04     13874374.99
#Sta/Elev= 30
  4692.3  1724.4  4694.8  1724.4  4720.2 1716.82  4725.2 1716.61  4732.8 1714.16
  4760.3 1709.98  4803.8 1706.27  4846.9  1704.8  4874.8 1700.26    4895 1695.39
  4907.7  1694.4  4925.5 1690.84    4940 1689.45  4974.2 1686.48  4974.4 1685.98
  4978.2 1686.48  5122.9 1687.33  5154.5 1694.31  5175.6 1697.03  5186.2 1700.13
  5207.2 1702.53  5217.8 1704.65  5228.3 1707.13  5233.6 1711.12  5240.8  1711.6
  5259.9 1716.08  5270.5 1719.98  5291.6 1725.47    5310  1731.6  5312.7  1731.6
#Mann= 6 ,-1 , 0
  4692.3    .035       0  4760.3    .063       0    4940    .035       0
  4974.2    .035       0  4978.2    .035       0  5240.8     .07       0
Bank Sta=4974.2,4978.2
XS Rating Curve= 0 ,0
Exp/Cntr=0.3,0.1

Type RM Length L Ch R = 1 ,10100   ,456,456,456
BEGIN DESCRIPTION:
Stream0220 22.0
END DESCRIPTION:
XS GIS Cut Line= 3
      1991174.96     13874724.99        1991475.       13874775.
        1991775.       13874525.
#Sta/Elev= 30
  4696.4 1714.91  4724.3 1711.03    4737 1710.43  4785.2 1703.06  4828.2  1701.8
    4846 1699.78    4851 1700.13  4858.7 1697.79  4873.8 1695.01  4919.5 1689.77
    4960 1686.69  4973.2 1686.57  4978.3 1686.57  4978.6 1686.07  4982.3 1686.57
  5184.8 1686.75  5192.6 1687.06  5221.2 1694.68  5227.8 1695.08  5248.6 1700.99
  5256.4 1701.22  5277.2 1704.28  5291.5  1710.5    5313  1714.3  5334.5 1722.18
  5355.3 1725.94  5363.1 1729.13  5383.9 1733.66  5387.8 1737.38  5391.1 1737.38
#Mann= 6 ,-1 , 0
  4696.4    .035       0  4873.8     .07       0  4973.2    .035       0
  4978.3    .035       0  4982.3    .035       0  5227.8     .07       0
Bank Sta=4978.3,4982.3
XS Rating Curve= 0 ,0
Exp/Cntr=0.3,0.1

Type RM Length L Ch R = 1 ,9644    ,76,76,76
BEGIN DESCRIPTION:
Stream0220 21.0
END DESCRIPTION:
XS GIS Cut Line= 3
      1991224.99       13875175.        1991525.       13875075.
        1991825.       13874775.
#Sta/Elev= 30
  4683.5  1712.2  4686.1  1712.2  4697.5 1709.05  4715.1 1705.05  4757.3 1698.78
  4788.9 1692.21  4799.5 1692.39    4810 1691.92  4852.2  1686.8  4860.7 1686.77
  4907.5 1686.53  4978.7  1686.9  4987.2 1686.32  4987.4 1685.82  4990.9 1685.82
  4991.2 1686.32    5195 1686.62  5211.9 1686.64    5226 1687.43  5240.2 1690.56
  5247.2 1691.46  5254.3 1694.11  5277.7 1696.92  5282.6 1697.58  5296.7 1700.77
  5310.9 1701.64  5367.4 1711.95  5409.9 1722.36  5420.5  1727.2    5424  1727.2
#Mann= 8 ,-1 , 0
  4683.5     .07       0  4697.5    .035       0  4860.7    .063       0
  4907.5     .07       0  4987.2     .05       0  4991.2     .07       0
    5195    .035       0  5277.7     .07       0
Bank Sta=4987.2,4991.2
XS Rating Curve= 0 ,0
Exp/Cntr=0.3,0.1

Type RM Length L Ch R = 1 ,9568    ,342,342,342
BEGIN DESCRIPTION:
Stream0220 D
END DESCRIPTION:
XS GIS Cut Line= 4
      1991159.43     13875210.99      1991440.66     13875160.22
      1991736.23     13875099.02      1992001.56     13874972.18
#Sta/Elev= 30
  4578.7  1729.8  4581.8 1727.77  4586.9  1727.8  4604.7 1722.36  4614.8 1721.38
  4635.2  1715.9  4640.4 1713.19    4658 1710.07  4675.8 1706.05  4746.9 1695.04
  4767.3 1690.01  4859.4 1688.04  4965.1 1688.85    4971 1687.23  5008.1 1686.22
  5008.4 1685.72  5012.1 1686.22  5042.5 1688.72  5070.8 1689.21  5166.1 1689.01
  5207.1 1690.05  5235.3 1694.03  5264.7 1701.24  5280.7 1702.26  5320.1  1710.7
  5354.2 1720.36  5364.5 1721.95    5394 1730.26  5422.3  1739.9  5460.4 1749.85
#Mann= 7 ,-1 , 0
  4578.7     .07       0    4658    .035       0  4859.4     .07       0
  5008.1     .05       0  5012.1     .07       0  5070.8    .035       0
  5166.1     .07       0
Bank Sta=5008.1,5012.1
XS Rating Curve= 0 ,0
Exp/Cntr=0.3,0.1

Type RM Length L Ch R = 1 ,9226    ,479,479,479
BEGIN DESCRIPTION:
Stream0220 20.0
END DESCRIPTION:
XS GIS Cut Line= 4
        1991275.       13875325.      1991478.91     13875447.35
      1991598.74     13875401.26      1991825.03     13875174.97
#Sta/Elev= 30
  4747.8 1701.21  4750.7 1701.21  4755.6 1699.65  4761.4  1699.6  4798.3 1694.43
  4829.4 1685.65  4841.1 1684.19  4856.6 1681.07  4864.4  1678.3  4899.4 1670.67
    4915 1668.75  4936.3 1664.92    4946 1662.34    4955 1661.23  4967.4 1659.22
  4978.4 1658.43  4978.7 1657.93  4982.4 1658.43  5013.5 1660.29  5061.8 1661.53
  5086.4 1663.21  5115.1  1664.1  5193.5 1667.36  5278.4 1669.72  5306.7 1672.35
  5320.8 1675.02    5338 1679.49  5349.1 1682.22  5430.4 1695.16    5434 1695.16
#Mann= 6 ,-1 , 0
  4747.8    .035       0    4955     .07       0  4978.4     .05       0
  4982.4     .07       0  5115.1    .035       0    5338     .07       0
Bank Sta=4978.4,4982.4
XS Rating Curve= 0 ,0
Exp/Cntr=0.3,0.1

Type RM Length L Ch R = 1 ,8747    ,418,418,418
BEGIN DESCRIPTION:
Stream0220 19.0
END DESCRIPTION:
XS GIS Cut Line= 3
      1991274.98       13875825.        1991525.       13875875.
      1991825.02     13876025.01
#Sta/Elev= 30
    4745 1677.87  4765.4 1676.39  4786.8 1672.78    4796 1671.85  4826.6 1663.79
  4867.4 1659.24  4877.6 1656.21    4898 1653.58  4918.4 1649.49  4938.8 1648.25
    4949 1648.58  4977.6 1647.53  4977.8 1647.03  4981.6 1647.53  4986.6 1647.64
  5044.7 1647.57  5056.6 1648.16    5081 1650.47  5103.4 1655.16  5111.8 1657.51
  5120.2 1660.88  5164.9 1672.37  5201.2 1676.09    5232 1684.09  5259.9 1688.56
  5268.3 1691.11    5299 1696.94  5304.6 1697.16    5313 1699.18  5335.4 1702.58
#Mann= 6 ,-1 , 0
    4745    .035       0  4786.8     .07       0  4977.6     .05       0
  4981.6     .07       0  4986.6      .1       0  5056.6     .07       0
Bank Sta=4977.6,4981.6
XS Rating Curve= 0 ,0
Exp/Cntr=0.3,0.1

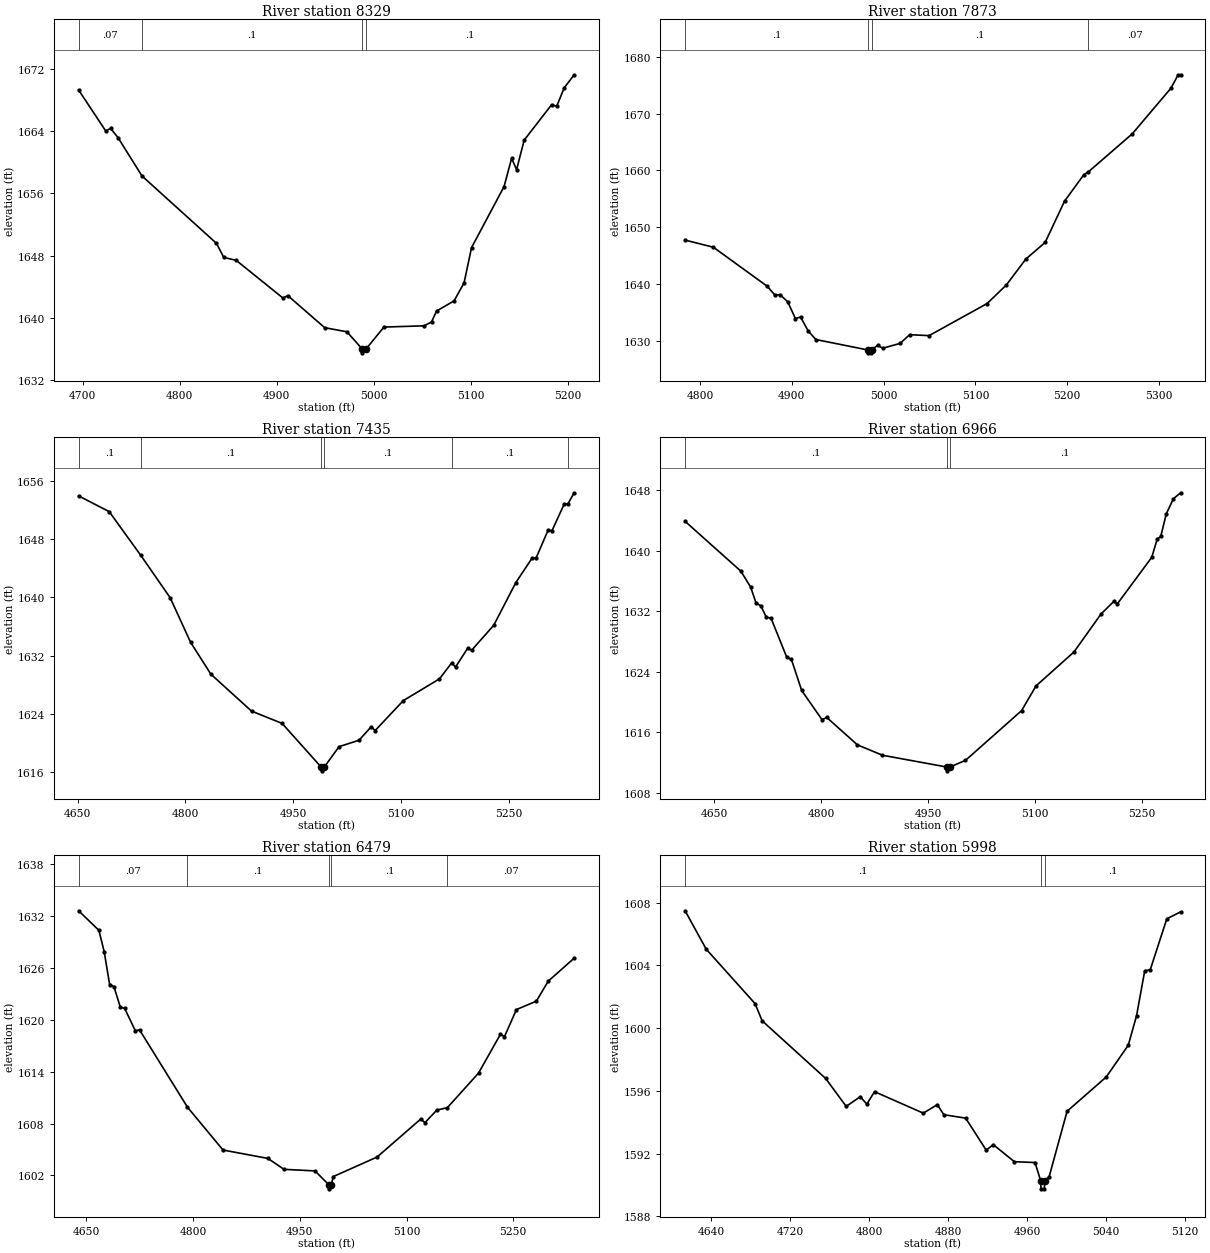
Type RM Length L Ch R = 1 ,8329    ,456,456,456
BEGIN DESCRIPTION:
Stream0220 18.0
END DESCRIPTION:
XS GIS Cut Line= 3
        1991125.       13876175.        1991425.       13876225.
      1991625.01       13876175.
#Sta/Elev= 30
  4695.9 1669.33  4723.8 1664.05  4728.8 1664.38  4736.4 1663.21  4761.1 1658.26
  4837.8 1649.58  4845.4 1647.76  4858.1 1647.39  4906.3 1642.53  4911.3 1642.84
  4949.3 1638.71  4972.2 1638.18  4987.9 1635.97  4988.1 1635.47  4991.9 1635.97
  5010.3 1638.79  5051.6 1638.95  5059.3 1639.44  5064.5 1640.86  5082.5 1642.16
  5092.8 1644.48  5100.5 1649.02    5134 1656.89  5141.8 1660.53  5146.9 1659.07
  5154.7 1662.87    5183 1667.44  5188.2 1667.23  5195.9  1669.6  5206.2 1671.29
#Mann= 4 ,-1 , 0
  4695.9     .07       0  4761.1      .1       0  4987.9     .05       0
  4991.9      .1       0
Bank Sta=4987.9,4991.9
XS Rating Curve= 0 ,0
Exp/Cntr=0.3,0.1

Type RM Length L Ch R = 1 ,7873    ,438,438,438
BEGIN DESCRIPTION:
Stream0220 17.0
END DESCRIPTION:
XS GIS Cut Line= 3
      1991224.97     13876524.99        1991425.       13876625.
      1991725.03     13876524.99
#Sta/Elev= 30
  4783.7 1647.73  4814.5 1646.47  4873.2  1639.6  4881.6 1638.03  4887.1 1638.13
  4895.5 1636.86  4903.9 1633.91  4909.5 1634.18  4917.9 1631.69  4926.3 1630.21
    4983 1628.37  4983.2 1627.87  4986.7 1627.87    4987 1628.37  4993.4 1629.21
    4999 1628.68  5017.9 1629.53  5028.4 1631.07  5049.5  1630.9  5112.7 1636.55
  5133.8 1639.84  5154.9 1644.38    5176 1647.32  5197.1 1654.59  5218.2 1659.26
    5223 1659.74  5270.9 1666.45    5313 1674.48  5320.9 1676.85  5323.6 1676.85
#Mann= 4 ,-1 , 0
  4783.7      .1       0    4983     .05       0    4987      .1       0
    5223     .07       0
Bank Sta=4983,4987
XS Rating Curve= 0 ,0
Exp/Cntr=0.3,0.1

Type RM Length L Ch R = 1 ,7435    ,469,469,469
BEGIN DESCRIPTION:
Stream0220 16.0
END DESCRIPTION:
XS GIS Cut Line= 3
      1991074.98     13876774.98        1991325.       13877025.
        1991625.       13876875.
#Sta/Elev= 30
  4651.5 1653.95    4694 1651.79  4737.7 1645.81  4778.8 1639.95  4807.1 1633.84
  4835.4 1629.44  4891.9 1624.37  4934.4 1622.68  4988.9 1616.66  4989.2 1616.16
  4992.9 1616.66  5013.5 1619.48  5041.4 1620.37  5058.2 1622.21  5063.8  1621.7
  5102.9 1625.81  5153.2  1628.8  5170.2    1631  5175.6 1630.43  5192.4 1633.01
  5197.9 1632.73  5228.7 1636.17  5259.4 1642.04  5281.8 1645.37  5287.4 1645.38
  5304.2 1649.23  5309.7 1649.18  5326.5  1652.8  5331.9 1652.86  5340.5 1654.38
#Mann= 6 ,-1 , 0
  4651.5      .1       0  4737.7      .1       0  4988.9     .05       0
  4992.9      .1       0  5170.2      .1       0  5331.9     .07       0
Bank Sta=4988.9,4992.9
XS Rating Curve= 0 ,0
Exp/Cntr=0.3,0.1

Type RM Length L Ch R = 1 ,6966    ,487,487,487
BEGIN DESCRIPTION:
Stream0220 15.0
END DESCRIPTION:
XS GIS Cut Line= 3
        1990975.       13877225.        1991275.       13877475.
      1991574.96     13877425.01
#Sta/Elev= 30
  4609.4 1643.86  4687.5 1637.29  4701.2  1635.2    4709 1633.04  4715.5 1632.74
  4723.3 1631.19  4729.8 1631.09  4751.9 1625.92  4758.4 1625.64  4772.8 1621.54
  4801.4 1617.67  4807.9 1617.98  4850.9 1614.36    4886 1612.99  4976.4 1611.43
  4976.7 1610.93  4980.4 1611.43  5002.4 1612.31    5081 1618.87  5101.3 1622.14
  5154.5 1626.62  5192.5 1631.64  5210.3 1633.29  5215.3 1632.97  5263.5 1639.11
  5271.1  1641.5  5276.2 1641.89  5283.8 1644.83  5293.9 1646.85    5304 1647.63
#Mann= 3 ,-1 , 0
  4609.4      .1       0  4976.4     .05       0  4980.4      .1       0
Bank Sta=4976.4,4980.4
XS Rating Curve= 0 ,0
Exp/Cntr=0.3,0.1

Type RM Length L Ch R = 1 ,6479    ,481,481,481
BEGIN DESCRIPTION:
Stream0220 14.0
END DESCRIPTION:
XS GIS Cut Line= 3
      1990875.01       13877725.        1991175.       13877925.
      1991475.04     13877774.98
#Sta/Elev= 30
  4639.5 1632.55    4668 1630.29  4675.5 1627.79  4683.1 1624.01  4689.1  1623.8
  4698.1 1621.41  4704.1 1621.29  4719.1 1618.71  4725.1  1618.8  4792.4 1609.88
  4842.3 1604.94  4905.4 1603.97  4927.9 1602.71  4971.5 1602.53  4990.5 1600.96
  4990.8 1600.46  4994.5 1600.96    4997 1601.87  5058.7 1604.13  5120.2 1608.53
  5125.8 1608.09  5142.6 1609.55  5157.4 1609.83  5201.3 1613.83    5232 1618.31
  5237.6 1618.02  5254.4 1621.15  5282.4 1622.12  5299.1 1624.43  5335.5 1627.08
#Mann= 5 ,-1 , 0
  4639.5     .07       0  4792.4      .1       0  4990.5     .05       0
  4994.5      .1       0  5157.4     .07       0
Bank Sta=4990.5,4994.5
XS Rating Curve= 0 ,0
Exp/Cntr=0.3,0.1

Type RM Length L Ch R = 1 ,5998    ,242,242,242
BEGIN DESCRIPTION:
Stream0220 13.0
END DESCRIPTION:
XS GIS Cut Line= 3
      1990975.03     13878125.03        1991275.       13878375.
      1991375.02     13878425.01
#Sta/Elev= 30
  4613.4 1607.49  4634.8 1605.04  4684.3 1601.57  4691.5 1600.47  4755.9 1596.79
  4776.7 1595.01    4791 1595.63  4797.6 1595.15  4805.4 1595.95  4854.8 1594.58
  4869.1 1595.12  4875.7 1594.48  4897.8 1594.26  4918.6 1592.22  4925.8 1592.57
  4947.2 1591.48  4968.1 1591.43  4973.9 1590.25  4974.1 1589.75  4977.6 1589.75
  4977.9 1590.25  4982.4 1590.52  5000.6  1594.7  5040.2 1596.88  5062.6 1598.91
    5071 1600.79  5079.3 1603.66  5084.9 1603.73  5101.7 1606.98  5115.7 1607.42
#Mann= 3 ,-1 , 0
  4613.4      .1       0  4973.9     .05       0  4977.9      .1       0
Bank Sta=4973.9,4977.9
XS Rating Curve= 0 ,0
Exp/Cntr=0.3,0.1

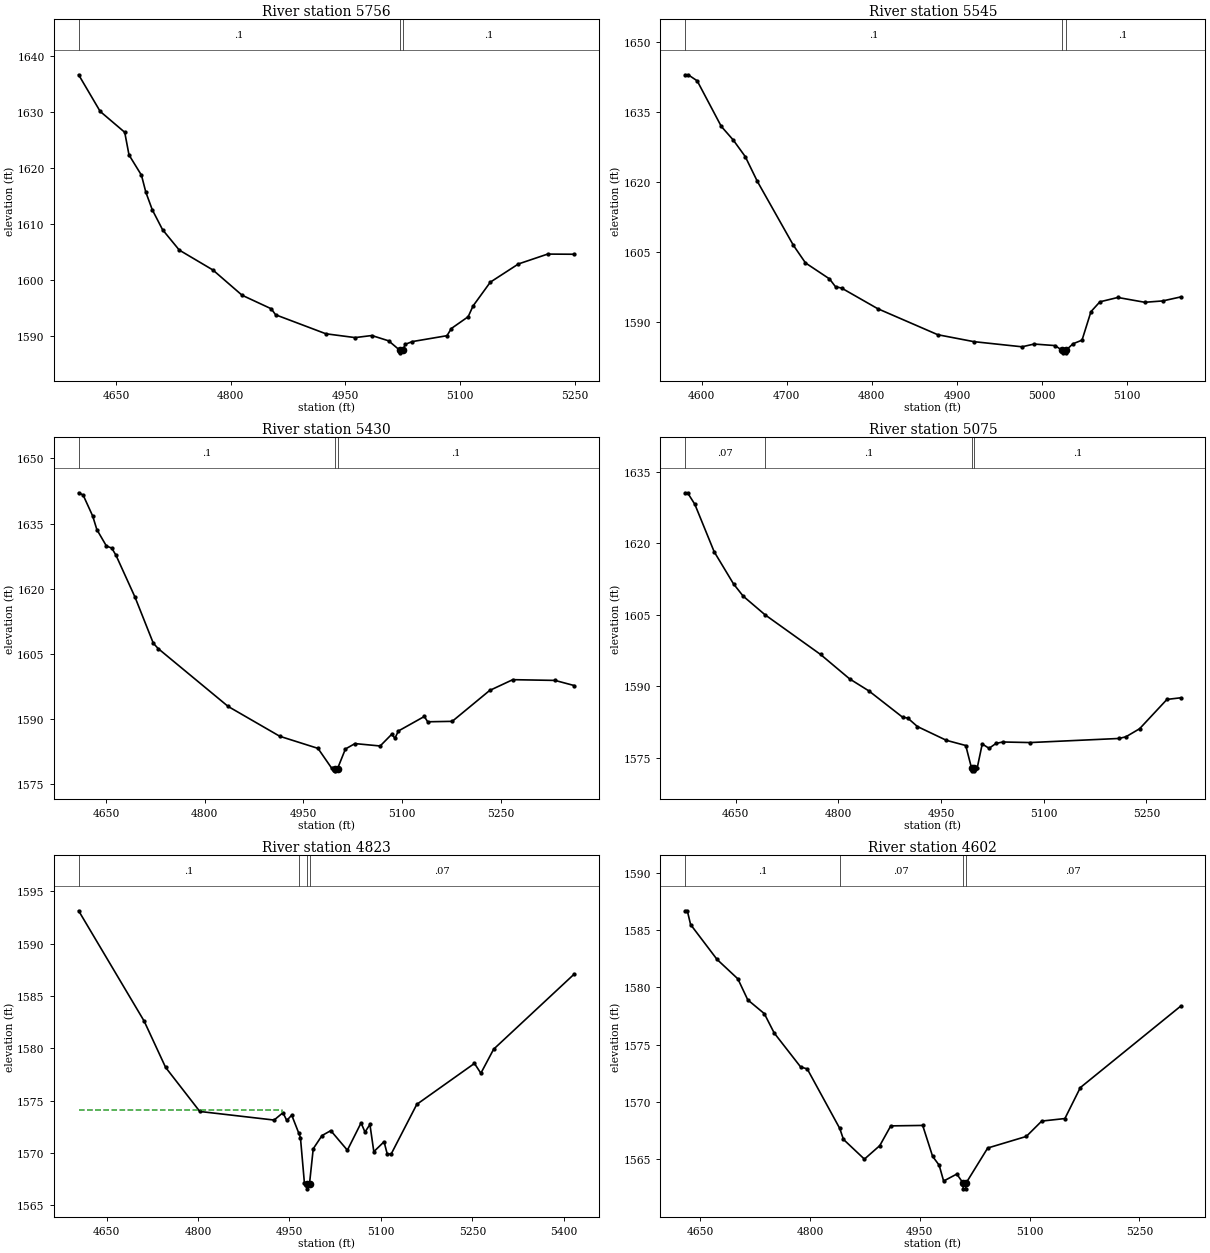
Type RM Length L Ch R = 1 ,5756    ,211,211,211
BEGIN DESCRIPTION:
Mapping XS b0f89bb9
END DESCRIPTION:
XS GIS Cut Line= 2
      1990740.14      13878269.8      1991311.67     13878575.81
#Sta/Elev= 30
  4601.1 1636.64  4629.3  1630.1  4661.4 1626.38    4667 1622.34  4683.3 1618.72
    4689  1615.7  4697.4 1612.57  4710.9    1609  4732.8 1605.36  4776.8 1601.81
  4814.9 1597.31  4853.1 1594.89  4858.8 1593.82  4924.6 1590.43  4962.8 1589.75
  4984.7 1590.12  5006.7 1589.17  5020.9 1587.53  5021.2 1587.03  5024.9 1587.53
  5028.6 1588.56  5037.7 1589.04    5083 1590.09  5088.7 1591.37  5110.7 1593.47
  5117.1 1595.39  5139.7 1599.64  5176.5 1602.89  5214.7 1604.65  5249.4 1604.62
#Mann= 3 ,-1 , 0
  4601.1      .1       0  5020.9     .05       0  5024.9      .1       0
Bank Sta=5020.9,5024.9
XS Rating Curve= 0 ,0
Exp/Cntr=0.3,0.1

Type RM Length L Ch R = 1 ,5545    ,115,115,115
BEGIN DESCRIPTION:
Stream0220 12.0
END DESCRIPTION:
XS GIS Cut Line= 3
      1990674.97     13878324.97        1990975.       13878625.
      1991124.98     13878674.99
#Sta/Elev= 30
  4580.5 1642.91  4584.1 1642.91  4594.7 1641.62    4623 1631.89  4637.1 1628.97
  4651.2 1625.43  4665.4 1620.14  4707.8 1606.47    4722 1602.71  4750.2  1599.3
  4757.3 1597.62  4764.4 1597.34  4806.8 1592.94  4877.5 1587.37  4919.9 1585.89
  4976.5 1584.79  4990.7 1585.38  5015.3 1585.05  5023.9    1584  5024.1  1583.5
  5027.6  1583.5  5027.9    1584  5036.4 1585.44    5047 1586.21  5057.5  1592.3
    5068  1594.4  5089.1 1595.33  5120.8  1594.3  5141.8 1594.59  5162.9 1595.44
#Mann= 3 ,-1 , 0
  4580.5      .1       0  5023.9     .05       0  5027.9      .1       0
Bank Sta=5023.9,5027.9
XS Rating Curve= 0 ,0
Exp/Cntr=0.3,0.1

Type RM Length L Ch R = 1 ,5430    ,355,355,355
BEGIN DESCRIPTION:
Mapping XS 4ec9fc3e
END DESCRIPTION:
XS GIS Cut Line= 3
      1990565.12      13878435.4      1990927.85     13878715.34
      1991216.24     13878776.51
#Sta/Elev= 30
  4608.5 1642.09  4615.3 1641.58  4629.8 1636.76  4636.2 1633.62  4650.7 1629.84
  4658.8 1629.36  4665.2 1627.73  4694.2 1618.06    4722 1607.46  4729.5 1606.22
  4835.7 1592.92  4914.2 1586.05  4972.2 1583.27  4993.1 1578.69  4997.9  1578.6
  4998.2  1578.1  5001.9  1578.6  5013.9 1583.13  5028.4 1584.37  5066.7 1583.82
  5084.1 1586.49  5089.2 1585.63  5094.4 1587.27  5133.8 1590.61  5138.9 1589.39
  5176.2 1589.49  5233.1  1596.6  5268.2 1599.08  5332.4 1598.91  5361.5 1597.73
#Mann= 3 ,-1 , 0
  4608.5      .1       0  4997.9     .05       0  5001.9      .1       0
Bank Sta=4997.9,5001.9
XS Rating Curve= 0 ,0
Exp/Cntr=0.3,0.1

Type RM Length L Ch R = 1 ,5075    ,252,252,252
BEGIN DESCRIPTION:
Stream0220 11.0
END DESCRIPTION:
XS GIS Cut Line= 3
      1990424.97     13878674.97        1990725.       13878975.
      1991024.99       13878975.
#Sta/Elev= 30
  4575.8 1630.61  4579.4 1630.61    4590  1628.2  4618.3 1618.22  4646.6 1611.47
  4660.7  1608.9  4692.6 1604.99  4773.8 1596.65  4816.3 1591.52  4844.5 1588.99
    4894 1583.44  4901.1 1583.31  4915.3 1581.52  4957.7 1578.62    4986 1577.53
  4994.6 1572.71  4994.8 1572.21  4998.3 1572.21  4998.6 1572.71  5002.6 1572.71
  5010.1 1577.85  5020.1 1576.94  5030.1 1577.96  5040.1 1578.27  5080.1 1578.15
  5210.1 1579.01  5220.1 1579.36  5240.1 1581.05  5280.1 1587.21  5300.1 1587.55
#Mann= 4 ,-1 , 0
  4575.8     .07       0  4692.6      .1       0  4994.6     .05       0
  4998.6      .1       0
#XS Ineff= 2 , 0
                         5010.07         1577.79
Permanent Ineff=
       F       F
Bank Sta=4994.6,4998.6
XS Rating Curve= 0 ,0
Exp/Cntr=0.3,0.1

Type RM Length L Ch R = 1 ,4823    ,221,221,221
BEGIN DESCRIPTION:
Mapping XS af7fd200
END DESCRIPTION:
XS GIS Cut Line= 3
       1990409.1     13878980.74      1990797.75     13879286.83
      1991100.77     13879384.22
#Sta/Elev= 30
  4604.1 1593.13  4711.6 1582.59  4746.8 1578.17  4802.9 1573.96  4924.8 1573.14
  4939.3 1573.84  4945.6  1573.1  4953.7 1573.61    4965 1571.93    4968 1571.47
  4974.5 1567.14  4978.9 1567.07  4979.1 1566.57  4982.9 1567.07    4989  1570.4
  5003.4 1571.66  5017.8 1572.13    5045 1570.26  5067.5 1572.87  5073.9 1571.99
    5082 1572.72  5088.4 1570.12  5105.2 1571.07  5110.4  1569.9  5116.9  1569.9
  5158.9 1574.64  5253.5 1578.55    5264 1577.61    5285 1579.91  5417.1 1587.08
#Mann= 4 ,-1 , 0
  4604.1      .1       0    4965     .07       0  4978.9     .05       0
  4982.9     .07       0
#XS Ineff= 2 , 0
         4938.56 1574.06
Permanent Ineff=
       F       F
Bank Sta=4978.9,4982.9
XS Rating Curve= 0 ,0
Exp/Cntr=0.3,0.1

Type RM Length L Ch R = 1 ,4602    ,446,446,446
BEGIN DESCRIPTION:
Stream0220 10.0
END DESCRIPTION:
XS GIS Cut Line= 3
      1990374.99     13879074.99        1990575.       13879375.
        1990875.       13879475.
#Sta/Elev= 30
  4629.4 1586.69  4632.4 1586.69  4636.9 1585.49    4673 1582.45  4701.5 1580.75
    4715 1578.92  4737.6 1577.72  4751.1 1576.03  4787.2 1573.07  4796.2  1572.9
  4840.6 1567.71  4845.7 1566.75  4874.3 1565.03  4895.3 1566.21  4910.3 1567.93
  4953.9 1567.97  4967.4 1565.28  4976.4  1564.5  4982.5 1563.12  5000.5 1563.73
  5009.1 1562.94  5009.3 1562.44  5012.8 1562.44  5013.1 1562.94  5042.7    1566
  5095.4 1567.01  5116.5 1568.35  5148.1 1568.57  5169.2 1571.27  5306.2 1578.37
#Mann= 4 ,-1 , 0
  4629.4      .1       0  4840.6     .07       0  5009.1     .05       0
  5013.1     .07       0
Bank Sta=5009.1,5013.1
XS Rating Curve= 0 ,0
Exp/Cntr=0.3,0.1

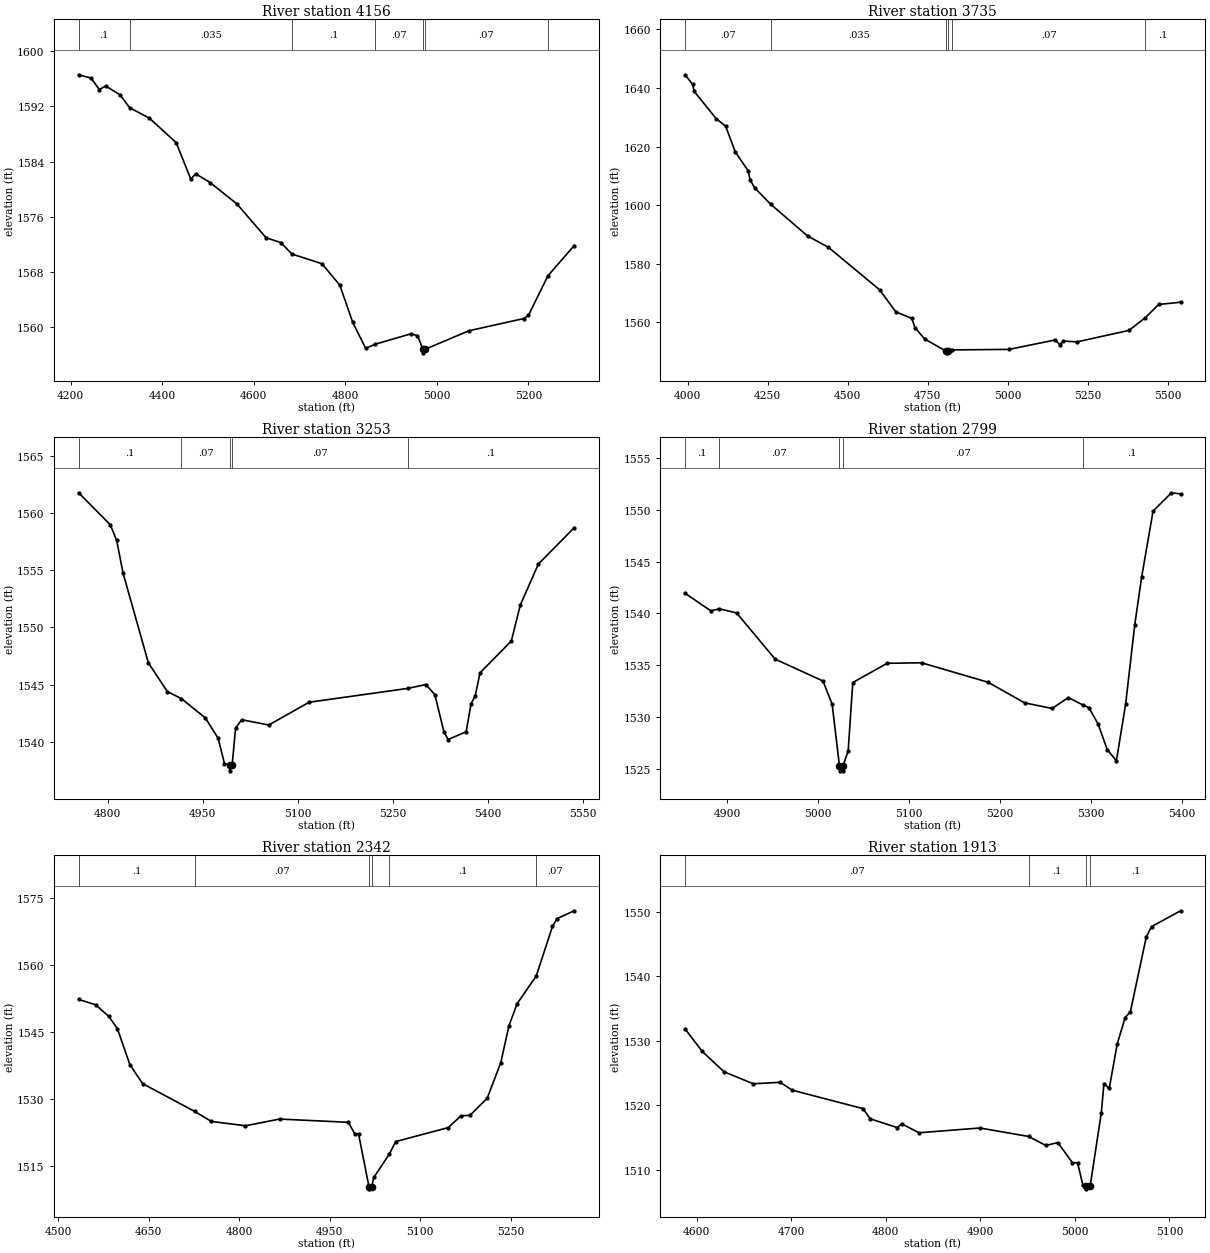
Type RM Length L Ch R = 1 ,4156    ,421,421,421
BEGIN DESCRIPTION:
Stream0220 9.0
END DESCRIPTION:
XS GIS Cut Line= 4
      1989932.25     13878992.04      1990097.41     13879497.41
        1990275.       13879675.      1990574.98       13879675.
#Sta/Elev= 30
  4217.2 1596.58  4244.4  1596.1  4262.4 1594.44  4276.3 1594.96  4308.1 1593.65
  4328.5 1591.82  4371.9 1590.29  4430.4 1586.74  4462.3 1581.45  4472.8 1582.24
  4504.7 1580.96  4563.1 1577.86  4626.9 1572.96  4658.8 1572.27  4683.3 1570.61
  4748.9  1569.2  4787.9  1566.1  4816.2 1560.69  4844.5 1556.94  4865.1 1557.54
  4943.5 1559.05  4957.6 1558.78  4969.7 1556.79    4970 1556.29  4973.7 1556.79
    5070 1559.49    5190 1561.26    5200 1561.71  5242.7 1567.46    5300 1571.83
#Mann= 7 ,-1 , 0
  4217.2      .1       0  4328.5    .035       0  4683.3      .1       0
  4865.1     .07       0  4969.7     .05       0  4973.7     .07       0
  5242.7      .1       0
Bank Sta=4969.7,4973.7
XS Rating Curve= 0 ,0
Exp/Cntr=0.3,0.1

Type RM Length L Ch R = 1 ,3735    ,482,482,482
BEGIN DESCRIPTION:
Stream0220 8.0
END DESCRIPTION:
XS GIS Cut Line= 3
      1989068.57     13879968.57        1990075.       13880025.
      1990574.98     13879825.01
#Sta/Elev= 30
  3992.4 1644.53  4015.9 1641.24  4020.9 1638.84    4089 1629.58    4119 1626.94
  4149.1 1618.19  4189.1 1611.73  4195.3 1608.61  4209.2 1605.95  4259.3 1600.31
  4374.8 1589.45  4439.5  1585.6  4599.8 1571.04  4649.9 1563.55  4699.9 1561.29
    4710 1558.08    4740 1554.28  4808.1 1550.04  4808.4 1549.54  4812.1 1550.04
  4825.3 1550.54  5003.1 1550.72  5147.2 1553.93    5162 1552.31  5171.4 1553.57
  5215.8 1553.29  5377.4  1557.2  5428.8 1561.56  5470.3 1566.07  5538.9 1566.83
#Mann= 6 ,-1 , 0
  3992.4     .07       0  4259.3    .035       0  4808.1     .05       0
  4812.1    .035       0  4825.3     .07       0  5428.8      .1       0
Bank Sta=4808.1,4812.1
XS Rating Curve= 0 ,0
Exp/Cntr=0.3,0.1

Type RM Length L Ch R = 1 ,3253    ,454,454,454
BEGIN DESCRIPTION:
Stream0220 7.0
END DESCRIPTION:
XS GIS Cut Line= 3
      1989824.96       13880475.        1990075.       13880475.
      1990474.96     13880125.03
#Sta/Elev= 30
  4754.3 1561.77  4804.3 1558.97  4814.3  1557.6  4824.3 1554.76  4864.3 1546.89
  4894.3 1544.38  4916.5 1543.76  4954.3 1542.07  4974.3  1540.3  4984.3 1538.09
  4992.3 1537.95  4992.5 1537.45  4996.4 1537.95  5001.8 1541.19  5011.5 1541.92
  5054.2 1541.46  5117.8 1543.45  5273.4 1544.66  5301.9    1545  5316.1 1544.11
  5330.4 1540.86    5337 1540.19  5365.5 1540.87  5373.1  1543.3  5379.7    1544
  5387.3 1546.02  5436.7 1548.81  5450.9 1551.96  5479.4 1555.54  5535.8 1558.71
#Mann= 5 ,-1 , 0
  4754.3      .1       0  4916.5     .07       0  4992.3     .05       0
  4996.4     .07       0  5273.4      .1       0
Bank Sta=4992.3,4996.4
XS Rating Curve= 0 ,0
Exp/Cntr=0.3,0.1

Type RM Length L Ch R = 1 ,2799    ,457,457,457
BEGIN DESCRIPTION:
Stream0220 6.0
END DESCRIPTION:
XS GIS Cut Line= 3
      1989924.98     13880774.98        1990025.       13880875.
      1990425.03       13880925.
#Sta/Elev= 30
    4854 1541.95  4882.3 1540.25  4891.6 1540.45  4910.6 1540.05    4953 1535.58
  5005.5 1533.47  5015.6 1531.23  5023.6 1525.28  5023.9 1524.78  5027.5 1524.78
  5027.7 1525.28  5033.2  1526.7  5038.3 1533.32  5076.1 1535.18  5113.9 1535.23
  5186.9 1533.35  5227.2 1531.35  5257.5 1530.81  5275.1 1531.87  5290.9 1531.16
  5297.8 1530.89  5307.9 1529.31  5317.9 1526.84    5328 1525.75  5338.1 1531.21
  5348.2 1538.91  5355.7  1543.5  5368.3  1549.9  5388.5 1551.67  5398.6 1551.56
#Mann= 5 ,-1 , 0
    4854      .1       0  4891.6     .07       0  5023.6     .05       0
  5027.7     .07       0  5290.9      .1       0
Bank Sta=5023.6,5027.7
XS Rating Curve= 0 ,0
Exp/Cntr=0.3,0.1

Type RM Length L Ch R = 1 ,2342    ,429,429,429
BEGIN DESCRIPTION:
Stream0220 5.0
END DESCRIPTION:
XS GIS Cut Line= 3
      1989575.01     13880925.01        1989875.       13881275.
      1990074.99     13881574.99
#Sta/Elev= 30
  4533.9 1552.28  4561.9  1551.1  4583.8  1548.5  4598.1 1545.77  4618.9 1537.71
  4639.8 1533.48    4726 1527.28  4753.9 1525.02  4810.5 1524.05    4867 1525.55
  4981.1 1524.83  4991.6 1522.26  4997.9 1522.26  5015.2 1510.46  5015.5 1509.96
  5019.6 1510.46  5023.4 1512.53  5048.9 1517.71  5059.5 1520.52  5146.6 1523.64
  5167.6 1526.27  5182.7 1526.39  5211.2  1530.2  5233.7 1538.14  5247.3  1546.4
  5260.8 1551.33  5292.5 1557.51  5319.4 1568.58  5326.9 1570.33  5355.4 1572.09
#Mann= 6 ,-1 , 0
  4533.9      .1       0    4726     .07       0  5015.2     .05       0
  5019.6     .07       0  5048.9      .1       0  5292.5     .07       0
Bank Sta=5015.2,5019.6
XS Rating Curve= 0 ,0
Exp/Cntr=0.3,0.1

Type RM Length L Ch R = 1 ,1913    ,476,476,476
BEGIN DESCRIPTION:
Stream0220 4.0
END DESCRIPTION:
XS GIS Cut Line= 3
      1989575.01     13881175.03        1989675.       13881575.
      1989725.01     13881675.02
#Sta/Elev= 30
  4587.7 1531.83  4605.7 1528.36  4628.9 1525.19  4659.8 1523.33  4688.2 1523.56
    4701 1522.34  4775.8 1519.48  4783.5  1517.9  4811.9 1516.55    4817  1517.1
  4835.1 1515.74  4899.5 1516.48  4950.9 1515.17  4969.1 1513.78  4981.9 1514.21
  4997.4 1511.09  5002.8 1511.09  5008.4 1507.63  5011.8 1507.55  5012.1 1507.05
  5016.2 1507.55  5027.9 1518.84  5030.7 1523.37  5036.3  1522.6  5044.7  1529.5
  5053.1 1533.57  5058.7 1534.52  5075.4 1546.05    5081 1547.69  5111.8 1550.14
#Mann= 4 ,-1 , 0
  4587.7     .07       0  4950.9      .1       0  5011.8     .05       0
  5016.2      .1       0
Bank Sta=5011.8,5016.2
XS Rating Curve= 0 ,0
Exp/Cntr=0.3,0.1