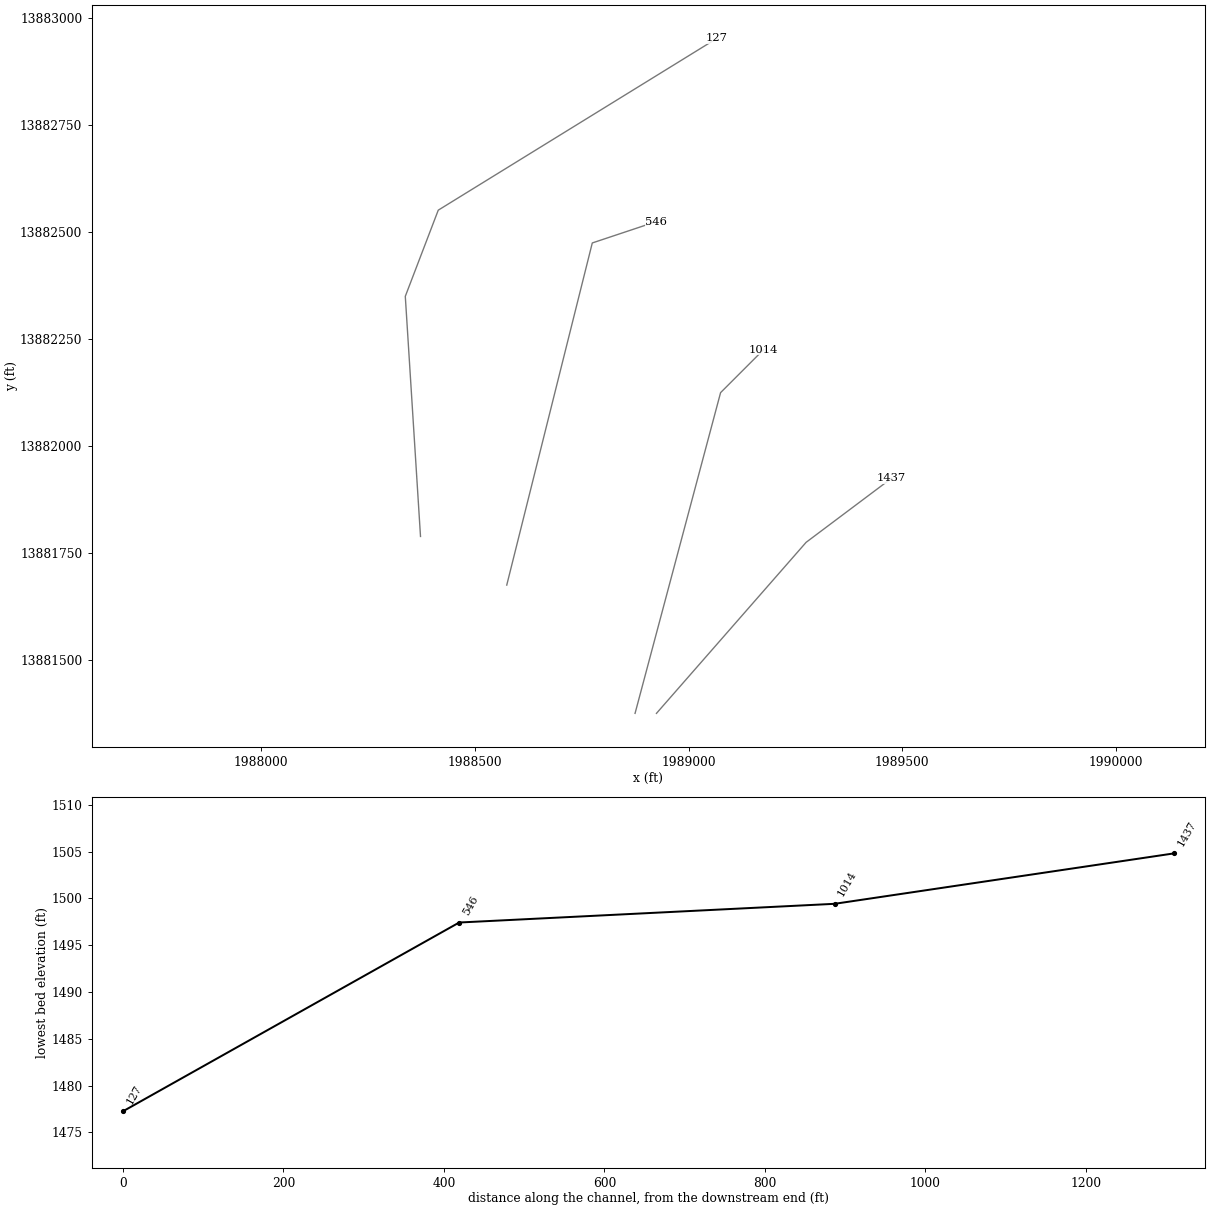
HEC-RAS study Stream0220.prj: Stream0220 Base Level Engineering

--- Stream0220.g01 (geometry) --- (continued)

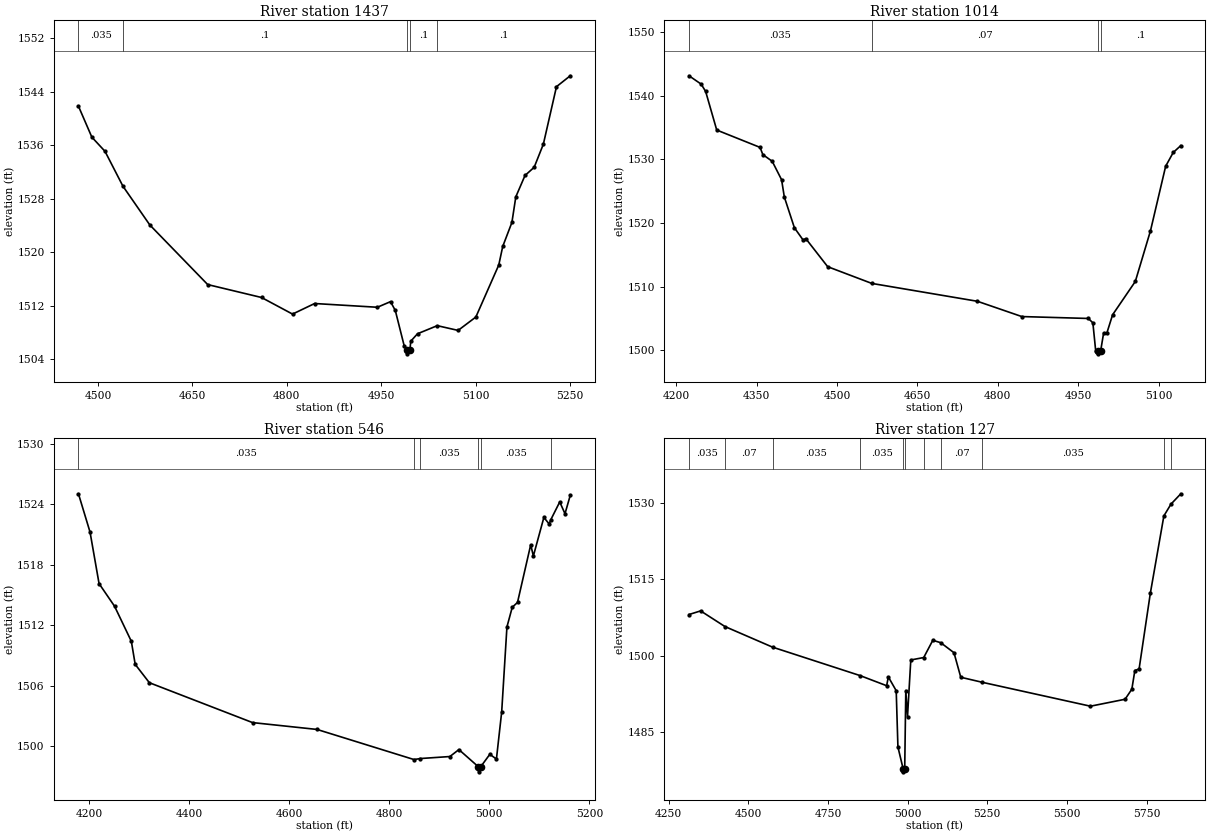
Type RM Length L Ch R = 1 ,1437    ,423,423,423
BEGIN DESCRIPTION:
Stream0220 3.0
END DESCRIPTION:
XS GIS Cut Line= 3
      1988925.03     13881375.03        1989275.       13881775.
      1989475.02     13881925.02
#Sta/Elev= 30
  4468.8 1541.83  4490.1  1537.2    4511 1535.08  4539.5 1529.87  4582.2 1524.08
  4674.2 1515.17  4759.7 1513.24    4809 1510.76  4844.1 1512.34  4943.8 1511.78
  4964.7 1512.62  4972.3  1511.3  4986.5 1505.99  4990.9 1505.32  4991.2 1504.82
  4995.4 1505.32  4996.9 1506.71  5007.6 1507.82    5039 1509.03  5072.1 1508.32
  5100.3 1510.32  5136.7 1518.09    5143 1520.86  5157.6 1524.46  5163.8 1528.28
  5178.4 1531.47    5193  1532.7  5207.6 1536.16  5228.4 1544.74  5250.3 1546.37
#Mann= 5 ,-1 , 0
  4468.8    .035       0  4539.5      .1       0  4990.9     .05       0
  4995.4      .1       0    5039      .1       0
Bank Sta=4990.9,4995.4
XS Rating Curve= 0 ,0
Exp/Cntr=0.3,0.1

Type RM Length L Ch R = 1 ,1014    ,468,468,468
BEGIN DESCRIPTION:
Stream0220 2.0
END DESCRIPTION:
XS GIS Cut Line= 3
      1988875.01     13881375.04        1989075.       13882125.
      1989175.01     13882225.01
#Sta/Elev= 30
  4223.8 1543.14  4246.4 1541.83  4254.8 1540.68  4275.5 1534.61  4356.4 1531.88
  4361.5 1530.75    4379  1529.7  4396.5  1526.8  4401.6 1524.09  4420.4 1519.25
  4436.6 1517.33  4441.7 1517.54  4482.5 1513.13  4564.8  1510.5  4761.9 1507.69
  4844.7 1505.29  4968.9 1504.99  4977.3  1504.3  4982.5 1499.95  4987.4 1499.93
  4987.7 1499.43  4991.9 1499.93  4997.4 1502.73  5003.5 1502.73  5014.1 1505.57
  5056.5 1510.81  5084.8 1518.78  5113.1 1528.92  5127.2 1531.08  5141.4 1532.17
#Mann= 4 ,-1 , 0
  4223.8    .035       0  4564.8     .07       0  4987.4     .05       0
  4991.9      .1       0
Bank Sta=4987.4,4991.9
XS Rating Curve= 0 ,0
Exp/Cntr=0.3,0.1

Type RM Length L Ch R = 1 ,546     ,419,419,419
BEGIN DESCRIPTION:
Stream0220 1.0
END DESCRIPTION:
XS GIS Cut Line= 3
        1988575.       13881675.        1988775.       13882475.
      1988924.96     13882524.99
#Sta/Elev= 30
  4179.1 1525.04  4202.3 1521.23  4220.3 1516.12  4251.3 1513.87  4284.8 1510.39
  4292.5  1508.1  4320.8 1506.28    4527 1502.32  4655.8 1501.64  4849.6 1498.65
  4862.1 1498.75  4921.3 1498.95  4939.3 1499.64  4978.3 1497.93  4978.6 1497.43
  4982.8 1497.93  5001.1 1499.17  5014.3  1498.7  5024.8 1503.38  5035.3 1511.82
  5045.9 1513.77  5056.4 1514.25  5082.8 1519.98  5088.1 1518.86  5109.1 1522.69
  5119.7 1522.04  5123.1 1522.48  5140.8 1524.23  5151.3 1523.06  5161.8 1524.88
#Mann= 6 ,-1 , 0
  4179.1    .035       0  4849.6     .07       0  4862.1    .035       0
  4978.3    .035       0  4982.8    .035       0  5123.1      .1       0
Bank Sta=4978.3,4982.8
XS Rating Curve= 0 ,0
Exp/Cntr=0.3,0.1

Type RM Length L Ch R = 1 ,127     ,0,0,0
BEGIN DESCRIPTION:
Stream0220 0.0
END DESCRIPTION:
XS GIS Cut Line= 4
      1988373.34      13881788.7      1988337.77     13882350.19
      1988414.84     13882551.66      1989066.51     13882953.45
#Sta/Elev= 30
  4313.8 1508.12  4350.2 1508.83  4426.6 1505.76  4575.9 1501.72  4851.1 1496.13
  4934.2 1494.15  4939.5 1495.88  4964.2 1493.17  4969.6 1482.13  4986.3 1477.75
  4986.7 1477.25  4990.9 1477.75  4994.3  1493.2  4999.7 1488.09    5010  1499.2
  5050.6 1499.68  5079.1 1503.06    5104 1502.59  5145.6 1500.62  5166.9 1495.81
  5234.3 1494.82    5574 1490.13  5682.6 1491.49  5703.9 1493.46  5713.4 1497.13
  5726.7 1497.44  5761.9 1512.26  5804.5 1527.47  5826.8 1529.78  5857.7 1531.81
#Mann= 11 ,-1 , 0
  4313.8    .035       0  4426.6     .07       0  4575.9    .035       0
  4851.1    .035       0  4986.3    .035       0  4990.9    .035       0
  5050.6    .035       0    5104     .07       0  5234.3    .035       0
  5804.5      .1       0  5826.8     .07       0
Bank Sta=4986.3,4990.9
XS Rating Curve= 0 ,0
Exp/Cntr=0.3,0.1

Chan Stop Cuts=-1
Use User Specified Reach Order=0
Composite Channel Slope=5