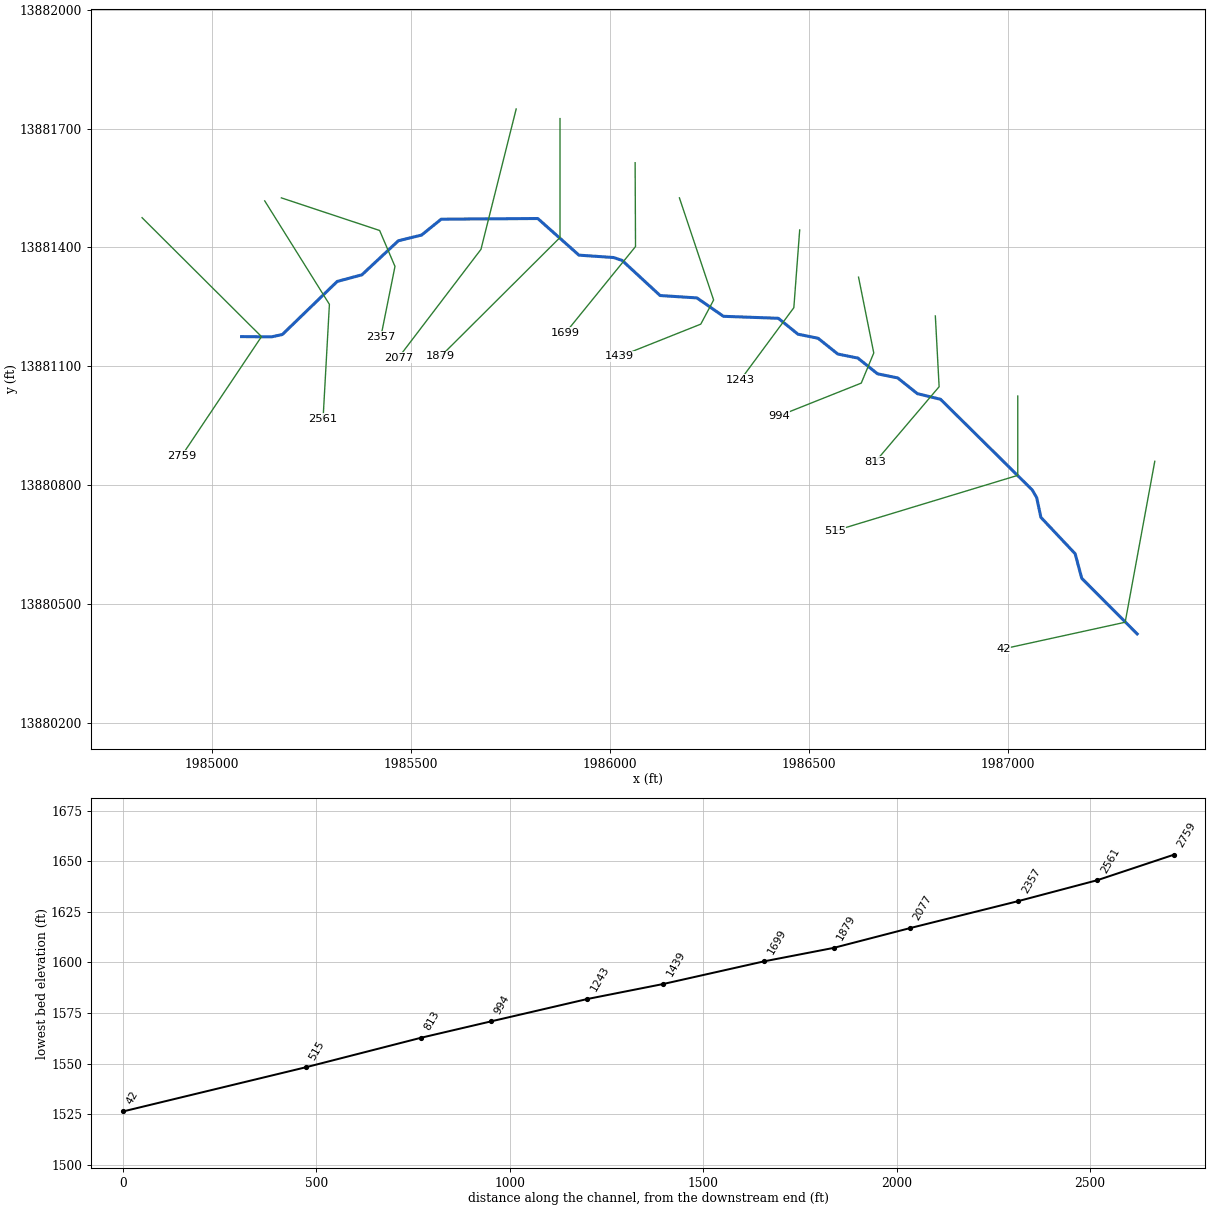
--- Stream0253.prj (project) ---

Proj Title=Stream0253 Base Level Engineering
Current Plan=p01
Default Exp/Contr=0.3,0.1
English Units
Geom File=g01
Flow File=f01
Plan File=p01
Y Axis Title=Elevation
X Axis Title(PF)=Main Channel Distance
X Axis Title(XS)=Station
BEGIN DESCRIPTION:
Stream0253
END DESCRIPTION:
DSS Export Rating Curves= 0
DSS Export Rating Curve Sorted= 0
DSS Export Volume Flow Curves= 0
DXF OffsetX= 0
DXF OffsetY= 0
DXF ScaleX= 1
DXF ScaleY= 10

--- Stream0253.p01 (plan) ---

Plan Title=Multiple Run
Short Identifier=Multiple
Geom File=g01
Flow File=f01
Subcritical Flow
K Sum by GR= 0
Std Step Tol= 0.01
Critical Tol= 0.01
Num of Std Step Trials= 20
Max Error Tol= 0.3
Flow Tol Ratio= 0.001
Split Flow NTrial= 30
Split Flow Tol= 0.02
Split Flow Ratio= 0.02
Log Output Level= 0
Friction Slope Method= 1
Unsteady Friction Slope Method= 2
Unsteady Bridges Friction Slope Method= 1
Parabolic Critical Depth
Global Vel Dist=  1 , 1 , 1
Global Log Level= 0
CheckData=True
Encroach Param= -1, 0, 0, 0
BEGIN DESCRIPTION:
Multiple Run
END DESCRIPTION:

--- Stream0253.f01 (steady flow) ---

Flow Title=Multiple
Program Version=4.10
Number of Profiles= 7
Profile Names=10-year,25-year,50-year,1pct_min,100-year,1pct_plu,500-year
River Rch & RM=Stream0253,Reach-1         ,2759
     234     362     474     304     606    1209     971
Boundary for River Rch & Prof#=Stream0253,Reach-1         , 1
Up Type= 0
Dn Type= 3
Dn Slope=0.005
Boundary for River Rch & Prof#=Stream0253,Reach-1         , 2
Up Type= 0
Dn Type= 3
Dn Slope=0.005
Boundary for River Rch & Prof#=Stream0253,Reach-1         , 3
Up Type= 0
Dn Type= 3
Dn Slope=0.005
Boundary for River Rch & Prof#=Stream0253,Reach-1         , 4
Up Type= 0
Dn Type= 3
Dn Slope=0.005
Boundary for River Rch & Prof#=Stream0253,Reach-1         , 5
Up Type= 0
Dn Type= 3
Dn Slope=0.005
Boundary for River Rch & Prof#=Stream0253,Reach-1         , 6
Up Type= 0
Dn Type= 3
Dn Slope=0.005
Boundary for River Rch & Prof#=Stream0253,Reach-1         , 7
Up Type= 0
Dn Type= 3
Dn Slope=0.005
DSS Import GetInterval= 0
DSS Import GetPeak= 0
DSS Import FillOption= 0

--- Stream0253.g01 (geometry) ---

Geom Title=Existing Conditions
Program Version=4.10

River Reach=Stream0253      ,Reach-1
Reach XY= 30
        1985075.       13881175.      1985150.25     13881174.41
       1985177.5     13881180.35      1985315.32     13881314.22
      1985377.28     13881330.87      1985468.95     13881416.84
      1985527.17     13881431.14      1985576.55     13881471.25
      1985819.14     13881472.93      1985922.58     13881380.54
      1986009.78     13881374.47      1986031.16     13881367.12
       1986126.5     13881278.62      1986219.02     13881272.64
      1986285.51     13881226.23      1986423.44     13881221.24
      1986472.82     13881181.12      1986523.28     13881170.84
       1986572.8     13881131.08      1986623.28     13881120.84
       1986672.8     13881081.08      1986723.28     13881070.84
      1986772.81      13881031.1      1986831.06     13881016.86
      1987061.37     13880788.21      1987072.47     13880768.95
      1987083.18     13880718.96      1987169.13     13880627.28
      1987185.77     13880565.32        1987325.       13880425.

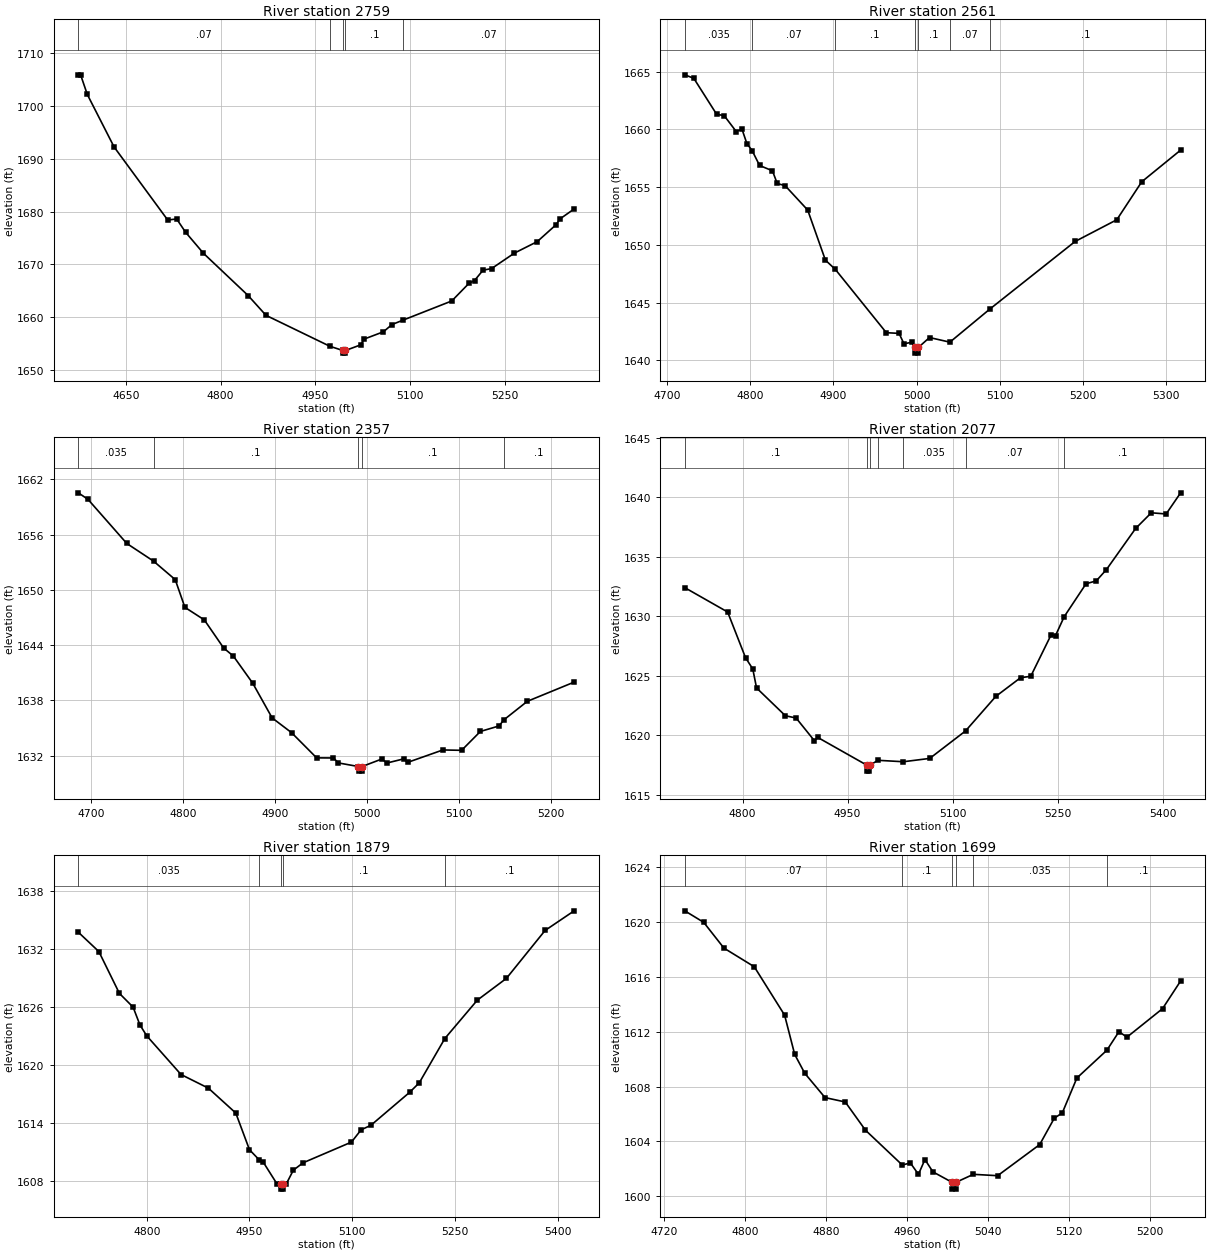
Type RM Length L Ch R = 1 ,2759    ,198,198,198
BEGIN DESCRIPTION:
Stream0253 6.0
END DESCRIPTION:
XS GIS Cut Line= 3
      1984824.98     13881475.02        1985125.       13881175.
      1984925.03     13880875.04
#Sta/Elev= 30
  4574.9 1705.91  4578.5 1705.91  4589.1 1702.19  4631.5 1692.25  4716.4 1678.41
  4730.5 1678.62  4744.6 1676.11  4772.9 1672.12  4843.6 1664.12  4871.9 1660.37
  4973.2  1654.5  4993.7 1653.71  4993.9 1653.21  4997.4 1653.21  4997.7 1653.71
  5021.7 1654.77  5027.7 1655.89  5057.8 1657.25  5071.3 1658.62  5089.5 1659.49
    5166 1663.09    5193  1666.4    5202 1666.96  5215.5 1668.92    5229 1669.22
  5265.1 1672.15  5301.2 1674.32  5331.2 1677.54  5337.2 1678.62  5359.7 1680.51
#Mann= 5 ,-1 , 0
  4574.9     .07       0  4973.2      .1       0  4993.7     .05       0
  4997.7      .1       0  5089.5     .07       0
Bank Sta=4993.7,4997.7
XS Rating Curve= 0 ,0
Exp/Cntr=0.3,0.1

Type RM Length L Ch R = 1 ,2561    ,204,204,204
BEGIN DESCRIPTION:
Mapping XS c5be8cd0
END DESCRIPTION:
XS GIS Cut Line= 3
      1985133.18     13881517.44      1985295.66      13881256.4
      1985279.77     13880968.41
#Sta/Elev= 30
  4721.3 1664.72  4732.1 1664.42  4759.5 1661.31  4768.7 1661.18  4783.1 1659.81
    4790 1660.02  4795.9 1658.77  4802.2 1658.16  4811.2 1656.87  4826.6 1656.41
  4832.4 1655.31  4841.9 1655.12    4869 1653.01  4890.3 1648.67    4902 1647.89
  4963.5 1642.39  4978.8 1642.33  4984.7 1641.43  4994.2 1641.56  4998.1 1641.12
  4998.3 1640.62  5001.8 1640.62  5002.1 1641.12  5015.4 1641.97  5039.9 1641.57
    5088 1644.44  5190.4 1650.29  5240.5 1652.17  5270.5 1655.46  5317.2  1658.2
#Mann= 7 ,-1 , 0
  4721.3    .035       0  4802.2     .07       0    4902      .1       0
  4998.1     .05       0  5002.1      .1       0  5039.9     .07       0
    5088      .1       0
Bank Sta=4998.1,5002.1
XS Rating Curve= 0 ,0
Exp/Cntr=0.3,0.1

Type RM Length L Ch R = 1 ,2357    ,280,280,280
BEGIN DESCRIPTION:
Stream0253 5.0
END DESCRIPTION:
XS GIS Cut Line= 4
      1985175.02     13881524.99      1985421.86     13881442.71
      1985460.41     13881352.06      1985424.99     13881174.97
#Sta/Elev= 30
  4686.1 1660.54  4696.6 1659.83  4738.8 1655.04  4767.9 1653.12  4791.5 1651.11
    4802  1648.1  4823.1 1646.74  4844.2 1643.68  4854.7 1642.81  4875.8 1639.86
  4896.9 1636.09    4918 1634.49  4945.3 1631.75  4963.6 1631.74    4969  1631.2
  4990.7 1630.81  4990.9 1630.31  4994.4 1630.31  4994.7 1630.81  5016.3 1631.63
  5021.7 1631.19    5040 1631.64  5044.3 1631.26  5082.6 1632.61    5103 1632.57
  5123.4 1634.62  5143.8 1635.22  5148.7 1635.86  5174.4 1637.89  5225.4 1639.98
#Mann= 5 ,-1 , 0
  4686.1    .035       0  4767.9      .1       0  4990.7     .05       0
  4994.7      .1       0  5148.7      .1       0
Bank Sta=4990.7,4994.7
XS Rating Curve= 0 ,0
Exp/Cntr=0.3,0.1

Type RM Length L Ch R = 1 ,2077    ,198,198,198
BEGIN DESCRIPTION:
Mapping XS 8b51a215
END DESCRIPTION:
XS GIS Cut Line= 3
      1985764.89     13881749.24      1985676.41     13881395.15
      1985468.95     13881121.59
#Sta/Elev= 30
  4717.4 1632.41  4778.6 1630.36  4804.2 1626.51  4814.5 1625.57  4819.9 1623.97
  4861.1 1621.63  4876.4 1621.44  4902.4 1619.54  4907.5  1619.8  4977.5 1617.47
  4977.7 1616.97  4981.2 1616.97  4981.5 1617.47  4993.6 1617.88  5029.6 1617.76
  5067.3 1618.04  5118.4 1620.35  5161.7 1623.26    5197 1624.83  5211.6 1624.95
  5240.7 1628.44    5247 1628.38  5259.4 1629.97  5290.6 1632.74  5305.2 1632.98
  5319.7 1633.93  5361.4 1637.39  5383.8 1638.71    5405 1638.61  5425.7 1640.39
#Mann= 7 ,-1 , 0
  4717.4      .1       0  4977.5     .05       0  4981.5      .1       0
  4993.6     .07       0  5029.6    .035       0  5118.4     .07       0
  5259.4      .1       0
Bank Sta=4977.5,4981.5
XS Rating Curve= 0 ,0
Exp/Cntr=0.3,0.1

Type RM Length L Ch R = 1 ,1879    ,180,180,180
BEGIN DESCRIPTION:
Stream0253 4.0
END DESCRIPTION:
XS GIS Cut Line= 3
        1985875.     13881724.99        1985875.       13881425.
      1985574.97     13881124.97
#Sta/Elev= 30
    4700 1633.71    4730 1631.71    4760 1627.39    4780 1625.97    4790 1624.13
    4800    1623    4850 1619.01    4890  1617.6    4930 1615.03    4950 1611.24
  4964.4 1610.18    4970 1609.97    4990 1607.73  4995.5 1607.67  4995.7 1607.17
  4999.2 1607.17  4999.5 1607.67  5003.5 1607.67  5014.1 1609.13  5028.3 1609.89
    5099 1612.03  5113.1  1613.3  5127.3 1613.76  5183.8 1617.16    5198 1618.15
  5235.4 1622.73  5282.8 1626.69  5325.3 1628.94  5381.8 1633.89  5424.3 1635.92
#Mann= 5 ,-1 , 0
    4700    .035       0  4964.4      .1       0  4995.5     .05       0
  4999.5      .1       0  5235.4      .1       0
Bank Sta=4995.5,4999.5
XS Rating Curve= 0 ,0
Exp/Cntr=0.3,0.1

Type RM Length L Ch R = 1 ,1699    ,260,260,260
BEGIN DESCRIPTION:
Mapping XS 1d9c72e9
END DESCRIPTION:
XS GIS Cut Line= 3
      1986063.72      13881613.7      1986064.71     13881402.17
      1985889.42     13881185.28
#Sta/Elev= 30
  4740.3 1620.83    4759 1619.99    4779 1618.11    4809 1616.75    4839 1613.22
    4849 1610.35    4859 1608.97    4879  1607.2    4899 1606.88    4919 1604.82
  4955.4 1602.28  4963.4 1602.43  4971.4  1601.6  4977.8 1602.68  4985.7 1601.78
  5004.6 1601.02  5004.8 1600.52  5008.3 1600.52  5008.6 1601.02  5025.7  1601.6
  5049.7  1601.5  5091.3 1603.77  5105.7 1605.69  5113.7 1606.09  5128.1 1608.63
  5157.8 1610.66  5169.7 1612.01  5177.6 1611.61  5212.8 1613.69  5230.7 1615.71
#Mann= 6 ,-1 , 0
  4740.3     .07       0  4955.4      .1       0  5004.6     .05       0
  5008.6      .1       0  5025.7    .035       0  5157.8      .1       0
Bank Sta=5004.6,5008.6
XS Rating Curve= 0 ,0
Exp/Cntr=0.3,0.1

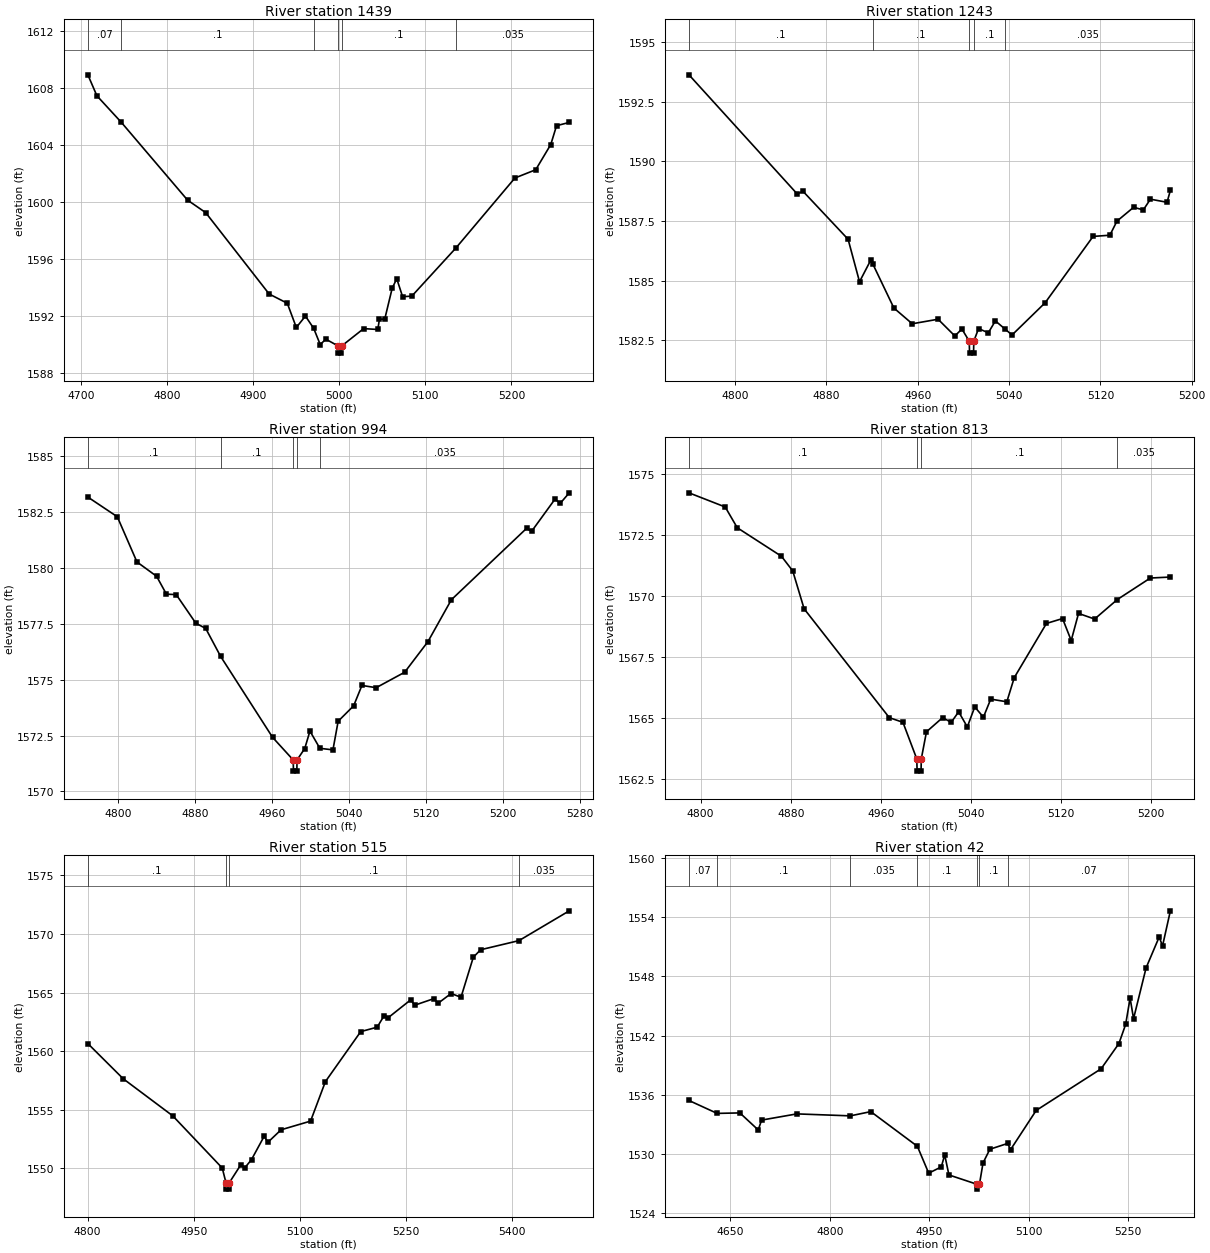
Type RM Length L Ch R = 1 ,1439    ,196,196,196
BEGIN DESCRIPTION:
Stream0253 3.0
END DESCRIPTION:
XS GIS Cut Line= 4
        1986175.       13881525.      1986260.91     13881267.28
      1986228.66     13881206.46      1986025.04     13881125.02
#Sta/Elev= 30
  4707.5 1608.89    4718 1607.42  4746.5 1605.55  4823.4  1600.1  4844.5 1599.22
  4918.3 1593.51  4939.4 1592.86  4949.9 1591.16  4960.5 1591.96  4970.1  1591.1
  4977.7 1589.96  4984.2 1590.34  4998.6 1589.86  4998.8 1589.36  5002.3 1589.36
  5002.6 1589.86  5028.2 1591.08  5044.6 1591.02  5046.6 1591.74  5052.7 1591.74
  5061.4 1593.92  5066.7 1594.58  5073.5 1593.32  5084.2 1593.36  5135.5 1596.74
  5204.1 1601.65  5228.3 1602.23  5245.8    1604  5252.5 1605.32  5267.3 1605.55
#Mann= 6 ,-1 , 0
  4707.5     .07       0  4746.5      .1       0  4970.1      .1       0
  4998.6     .05       0  5002.6      .1       0  5135.5    .035       0
Bank Sta=4998.6,5002.6
XS Rating Curve= 0 ,0
Exp/Cntr=0.3,0.1

Type RM Length L Ch R = 1 ,1243    ,249,249,249
BEGIN DESCRIPTION:
Mapping XS a8c0b292
END DESCRIPTION:
XS GIS Cut Line= 3
      1986477.13     13881444.02      1986462.44     13881248.02
      1986329.04     13881066.65
#Sta/Elev= 30
  4759.6 1593.62  4854.4 1588.63  4859.5 1588.74    4899 1586.73    4909 1584.95
  4919.1 1585.88  4920.8 1585.68  4939.1 1583.85  4955.2 1583.19  4977.8 1583.38
  4992.5 1582.68  4998.7 1582.97  5005.1 1582.46  5005.4 1581.96  5008.9 1581.96
  5009.1 1582.46  5013.3 1582.99  5021.8 1582.81    5028 1583.31  5036.7 1582.96
  5042.6 1582.72  5071.6 1584.07  5113.6 1586.85  5128.3  1586.9  5134.5 1587.49
  5149.1 1588.07  5157.6 1587.96  5163.8 1588.41  5178.4 1588.28  5181.3 1588.78
#Mann= 5 ,-1 , 0
  4759.6      .1       0  4920.8      .1       0  5005.1     .05       0
  5009.1      .1       0  5036.7    .035       0
Bank Sta=5005.1,5009.1
XS Rating Curve= 0 ,0
Exp/Cntr=0.3,0.1

Type RM Length L Ch R = 1 ,994     ,181,181,181
BEGIN DESCRIPTION:
Stream0253 2.0
END DESCRIPTION:
XS GIS Cut Line= 4
        1986625.     13881325.02      1986663.26     13881133.71
      1986631.81     13881057.72      1986424.98     13880974.99
#Sta/Elev= 30
  4768.9 1583.16  4799.5 1582.28  4819.9 1580.26  4840.3 1579.62  4850.5 1578.82
  4860.7  1578.8  4881.1 1577.52  4891.3 1577.29  4906.8 1576.04  4960.8 1572.42
  4982.2 1571.41  4982.5 1570.91    4986 1570.91  4986.2 1571.41  4994.2 1571.92
  4999.6  1572.7  5009.9 1571.93  5023.5 1571.86  5028.9 1573.14    5045 1573.83
  5053.6 1574.74  5068.4 1574.64    5098 1575.33  5122.2  1576.7  5146.5 1578.57
  5224.6 1581.76  5229.9 1581.63  5254.2 1583.07  5259.6 1582.88    5269 1583.35
#Mann= 5 ,-1 , 0
  4768.9      .1       0  4906.8      .1       0  4982.2     .05       0
  4986.2      .1       0  5009.9    .035       0
Bank Sta=4982.2,4986.2
XS Rating Curve= 0 ,0
Exp/Cntr=0.3,0.1

Type RM Length L Ch R = 1 ,813     ,298,298,298
BEGIN DESCRIPTION:
Mapping XS e037bb13
END DESCRIPTION:
XS GIS Cut Line= 3
      1986817.94     13881227.11      1986827.45     13881048.63
       1986666.6      13880858.6
#Sta/Elev= 30
  4789.6 1574.22  4821.8 1573.64  4832.5 1572.79  4871.8 1571.62  4881.8 1571.02
  4891.9 1569.47  4967.6 1565.01  4979.7 1564.82    4992 1563.32  4992.3 1562.82
  4995.8 1562.82    4996 1563.32  5000.6 1564.43  5014.9 1565.01  5022.6 1564.82
  5029.2 1565.25  5036.9 1564.63  5043.5 1565.45  5051.2 1565.03  5057.7 1565.77
    5072 1565.66  5078.6 1566.65  5107.2 1568.87  5121.5 1569.07  5129.2 1568.17
  5135.7 1569.28    5150 1569.05  5170.2 1569.85  5199.5 1570.73  5217.3 1570.77
#Mann= 4 ,-1 , 0
  4789.6      .1       0    4992     .05       0    4996      .1       0
  5170.2    .035       0
Bank Sta=4992,4996
XS Rating Curve= 0 ,0
Exp/Cntr=0.3,0.1

Type RM Length L Ch R = 1 ,515     ,473,473,473
BEGIN DESCRIPTION:
Stream0253 1.0
END DESCRIPTION:
XS GIS Cut Line= 3
        1987025.     13881025.02        1987025.       13880825.
      1986565.19      13880684.9
#Sta/Elev= 30
  4800.3 1560.65  4850.3 1557.65  4920.3 1554.49  4990.3 1550.04  4995.8 1548.74
  4996.1 1548.24  4999.6 1548.24  4999.8 1548.74  5016.7 1550.33    5022 1550.04
  5031.7 1550.76  5049.6 1552.75  5054.8 1552.23  5073.5  1553.3  5115.2 1554.04
  5136.2 1557.41  5186.1 1561.67  5209.4 1562.05    5219 1563.01  5224.2 1562.82
    5257 1564.39  5262.3 1563.92  5289.9 1564.49  5295.1 1564.07  5313.9 1564.92
  5327.9  1564.6  5345.3 1568.01  5355.6 1568.65  5409.9 1569.43    5481 1571.97
#Mann= 4 ,-1 , 0
  4800.3      .1       0  4995.8     .05       0  4999.8      .1       0
  5409.9    .035       0
Bank Sta=4995.8,4999.8
XS Rating Curve= 0 ,0
Exp/Cntr=0.3,0.1

Type RM Length L Ch R = 1 ,42      ,0,0,0
BEGIN DESCRIPTION:
Stream0253 0.0
END DESCRIPTION:
XS GIS Cut Line= 3
      1987369.23     13880860.46      1987294.86     13880454.46
       1986989.2     13880387.33
#Sta/Elev= 30
  4587.8  1535.4  4630.3 1534.09  4664.5 1534.14  4692.2 1532.41  4697.3 1533.41
  4750.5 1534.04    4831 1533.84  4861.9 1534.27  4932.1 1530.75  4949.2 1528.02
  4968.2 1528.66  4973.3 1529.88  4979.7 1527.84  5021.7  1526.9  5021.9  1526.4
  5025.7  1526.9  5031.1 1529.06  5041.4 1530.45  5068.2 1531.04  5072.6 1530.41
  5111.2 1534.39  5209.1 1538.62  5235.9 1541.18  5246.1 1543.13  5252.8  1545.8
    5258 1543.71  5276.9 1548.87  5296.6    1552  5301.7  1551.1  5313.5 1554.66
#Mann= 7 ,-1 , 0
  4587.8     .07       0  4630.3      .1       0    4831    .035       0
  4932.1      .1       0  5021.7     .05       0  5025.7      .1       0
  5068.2     .07       0
Bank Sta=5021.7,5025.7
XS Rating Curve= 0 ,0
Exp/Cntr=0.3,0.1

Chan Stop Cuts=-1
Use User Specified Reach Order=0
Composite Channel Slope=5