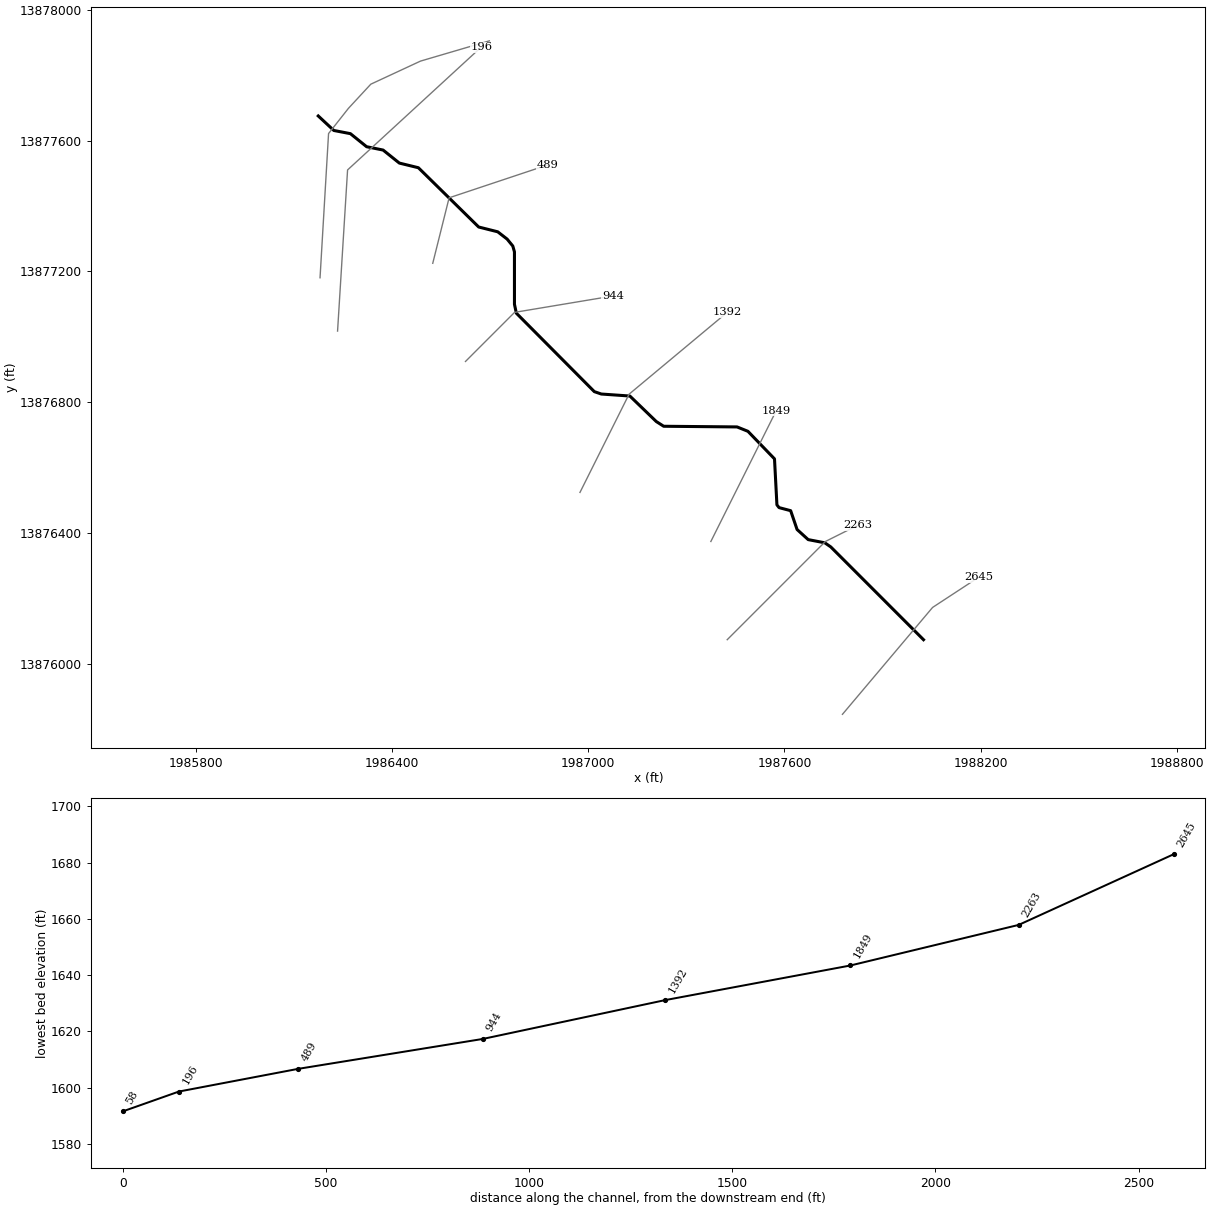
--- Stream0276.prj (project) ---

Proj Title=Stream0276 Base Level Engineering
Current Plan=p01
Default Exp/Contr=0.3,0.1
English Units
Geom File=g01
Flow File=f01
Plan File=p01
BEGIN DESCRIPTION:
Stream0276
END DESCRIPTION:

--- Stream0276.p01 (plan) ---

Plan Title=Multiple Run
Short Identifier=Multiple
Geom File=g01
Flow File=f01
Subcritical Flow
K Sum by GR= 0
Std Step Tol= 0.01
Critical Tol= 0.01
Num of Std Step Trials= 20
Max Error Tol= 0.3
Flow Tol Ratio= 0.001
Split Flow NTrial= 30
Split Flow Tol= 0.02
Split Flow Ratio= 0.02
Log Output Level= 0
Friction Slope Method= 1
Unsteady Friction Slope Method= 2
Unsteady Bridges Friction Slope Method= 1
Parabolic Critical Depth
Global Vel Dist=  1 , 1 , 1
Global Log Level= 0
CheckData=True
Encroach Param= -1, 0, 0, 0
BEGIN DESCRIPTION:
Multiple Run
END DESCRIPTION:

--- Stream0276.f01 (steady flow) ---

Flow Title=Multiple
Number of Profiles=7
Profile Names=10-year,25-year,50-year,1pct_min,100-year,1pct_plu,500-year
River Rch & RM= Stream0276,Reach-1,2645
     602     999    1371     916    1828    3647    3204
River Rch & RM= Stream0276,Reach-1,58
    1208    2099    2971    2040    4071    8123    7564
Boundary for River Rch & Prof#=Stream0276,Reach-1,1
Up Type=0
Dn Type=3
Dn Slope=0.005
Boundary for River Rch & Prof#=Stream0276,Reach-1,2
Up Type=0
Dn Type=3
Dn Slope=0.005
Boundary for River Rch & Prof#=Stream0276,Reach-1,3
Up Type=0
Dn Type=3
Dn Slope=0.005
Boundary for River Rch & Prof#=Stream0276,Reach-1,4
Up Type=0
Dn Type=3
Dn Slope=0.005
Boundary for River Rch & Prof#=Stream0276,Reach-1,5
Up Type=0
Dn Type=3
Dn Slope=0.005
Boundary for River Rch & Prof#=Stream0276,Reach-1,6
Up Type=0
Dn Type=3
Dn Slope=0.005
Boundary for River Rch & Prof#=Stream0276,Reach-1,7
Up Type=0
Dn Type=3
Dn Slope=0.005

--- Stream0276.g01 (geometry) ---

Geom Title=Existing Conditions

River Reach=Stream0276,Reach-1
Reach XY= 30
      1988025.00     13876075.00      1987741.66     13876358.35
      1987723.33     13876371.02      1987672.48     13876380.79
      1987638.55     13876411.65      1987618.93     13876469.17
      1987583.49     13876478.54      1987576.93     13876486.95
      1987569.54     13876627.46      1987488.35     13876711.64
      1987455.02     13876725.04      1987230.86     13876727.07
      1987208.25     13876741.47      1987127.42     13876819.46
      1987040.22     13876825.53      1987018.83     13876832.86
      1986780.46     13877072.55      1986774.71     13877099.88
      1986774.67     13877259.97      1986769.64     13877277.70
      1986752.30     13877298.90      1986723.60     13877321.13
      1986665.34     13877335.79      1986481.06     13877516.86
      1986422.81     13877531.10      1986373.28     13877570.84
      1986322.80     13877581.07      1986273.33     13877620.96
      1986222.64     13877630.67      1986175.00     13877675.00

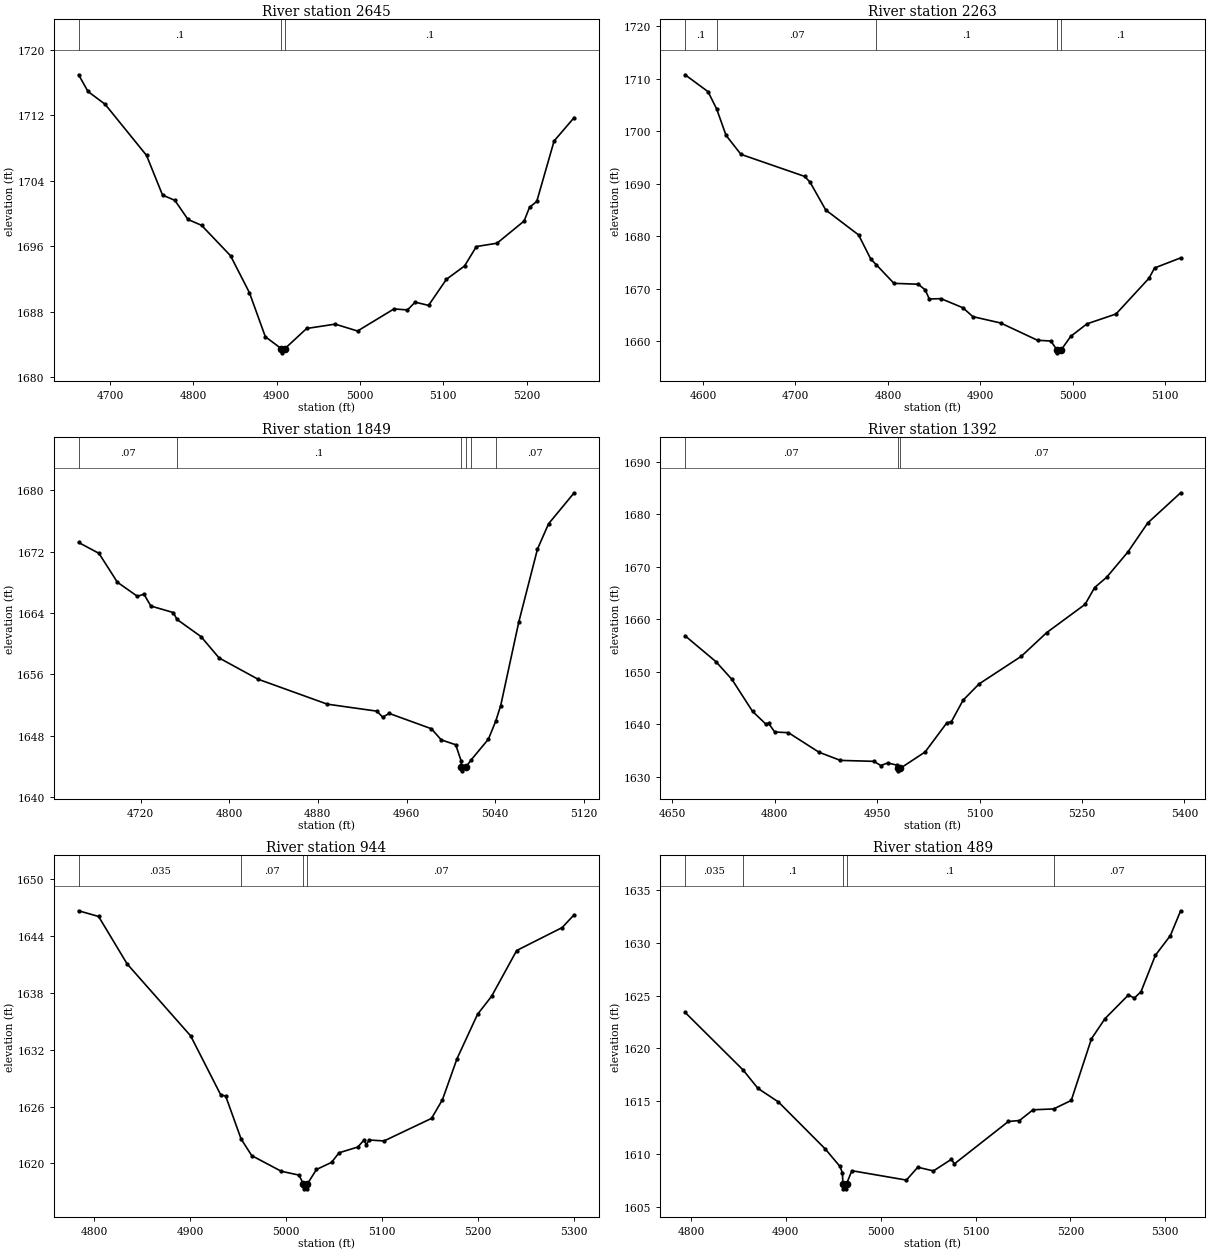
Type RM Length L Ch R = 1,2645,382,382,382
BEGIN DESCRIPTION:
Stream0276 6.0
END DESCRIPTION:
XS GIS Cut Line= 3
      1987777.22     13875847.06      1988052.70     13876173.55
      1988192.94     13876265.35
#Sta/Elev= 30
  4662.4 1716.98  4673.6 1714.94  4694.2 1713.37  4743.9 1707.12  4763.1 1702.27
  4777.9 1701.62  4793.7 1699.28  4809.9 1698.57  4844.7 1694.85  4867.4 1690.33
  4886.5 1684.94  4905.8 1683.47  4906.1 1682.97  4909.8 1683.47  4936.1 1685.95
  4970.3 1686.48  4997.2 1685.64  5040.9 1688.34  5057.1 1688.22  5066.4 1689.17
  5082.4 1688.77  5103.9 1691.97  5125.6 1693.59  5139.8 1695.97  5164.6 1696.38
  5197.1 1699.09  5203.6 1700.77  5212.3 1701.49  5233.1 1708.88  5257.2 1711.75
#Mann=3,-1,0
  4662.4     0.1       0  4905.8    0.05       0  4909.8     0.1       0
Bank Sta=4905.8,4909.8
Exp/Cntr=0.3,0.1

Type RM Length L Ch R = 1,2263,414,414,414
BEGIN DESCRIPTION:
Stream0276 5.0
END DESCRIPTION:
XS GIS Cut Line= 3
      1987425.02     13876075.02      1987725.00     13876375.00
      1987824.97     13876424.98
#Sta/Elev= 30
  4580.6 1710.74  4605.4 1707.53  4614.8 1704.21  4624.9 1699.21  4641.0 1695.60
  4709.8 1691.41  4715.7 1690.32  4732.7 1685.02  4768.3 1680.26  4781.5 1675.65
  4787.4 1674.60  4806.5 1671.05  4832.8 1670.89  4840.4 1669.79  4844.7 1668.08
  4857.4 1668.14  4881.2 1666.40  4891.8 1664.72  4921.9 1663.51  4961.8 1660.22
  4976.2 1660.08  4983.1 1658.33  4983.4 1657.83  4987.1 1658.33  4997.8 1660.98
  5015.3 1663.35  5046.7 1665.22  5082.4 1672.03  5088.4 1673.98  5116.6 1675.90
#Mann=5,-1,0
  4580.6     0.1       0  4614.8    0.07       0  4787.4     0.1       0
  4983.1    0.05       0  4987.1     0.1       0
Bank Sta=4983.1,4987.1
Exp/Cntr=0.3,0.1

Type RM Length L Ch R = 1,1849,457,457,457
BEGIN DESCRIPTION:
Stream0276 4.0
END DESCRIPTION:
XS GIS Cut Line= 3
      1987375.01     13876375.02      1987525.00     13876675.00
      1987575.01     13876775.01
#Sta/Elev= 30
  4664.1 1673.18  4682.4 1671.77  4699.1 1668.00  4717.2 1666.16  4723.0 1666.45
  4729.3 1664.90  4749.5 1664.05  4752.9 1663.15  4774.5 1660.92  4790.9 1658.13
  4825.9 1655.37  4888.5 1652.11  4933.2 1651.20  4938.5 1650.42  4944.4 1650.90
  4982.4 1648.91  4991.4 1647.45  5004.4 1646.82  5009.3 1644.71  5009.5 1643.92
  5009.7 1643.42  5013.5 1643.92  5018.6 1644.89  5033.9 1647.55  5040.5 1649.89
  5045.0 1651.93  5061.4 1662.87  5078.2 1672.33  5088.2 1675.62  5111.3 1679.66
#Mann=6,-1,0
  4664.1    0.07       0  4752.9     0.1       0  5009.5    0.05       0
  5013.5     0.1       0  5018.6   0.035       0  5040.5    0.07       0
Bank Sta=5009.5,5013.5
Exp/Cntr=0.3,0.1

Type RM Length L Ch R = 1,1392,448,448,448
BEGIN DESCRIPTION:
Stream0276 3.0
END DESCRIPTION:
XS GIS Cut Line= 3
      1986974.98     13876524.96      1987125.00     13876825.00
      1987425.02     13877075.02
#Sta/Elev= 30
  4668.5 1656.82  4713.7 1651.89  4737.2 1648.50  4767.3 1642.42  4786.4 1640.05
  4790.9 1640.13  4799.8 1638.49  4819.9 1638.36  4864.6 1634.64  4896.0 1633.08
  4945.1 1632.90  4955.2 1632.10  4965.2 1632.59  4978.7 1632.18  4980.0 1631.59
  4980.3 1631.09  4984.0 1631.59  5020.2 1634.69  5051.8 1640.21  5058.7 1640.47
  5075.7 1644.54  5099.2 1647.65  5161.1 1652.92  5198.2 1657.42  5254.5 1662.81
  5268.5 1666.01  5286.1 1667.97  5317.3 1672.80  5346.3 1678.32  5394.5 1684.07
#Mann=3,-1,0
  4668.5    0.07       0  4980.0    0.05       0  4984.0    0.07       0
Bank Sta=4980,4984
Exp/Cntr=0.3,0.1

Type RM Length L Ch R = 1,944,455,455,455
BEGIN DESCRIPTION:
Stream0276 2.0
END DESCRIPTION:
XS GIS Cut Line= 3
      1986625.01     13876925.01      1986775.00     13877075.00
      1987075.05     13877125.01
#Sta/Elev= 30
  4783.9 1646.64  4804.7 1646.04  4834.4 1641.04  4900.6 1633.45  4932.0 1627.22
  4937.1 1627.10  4953.2 1622.57  4964.3 1620.82  4995.1 1619.17  5013.5 1618.77
  5018.1 1617.82  5018.3 1617.32  5021.8 1617.32  5022.1 1617.82  5031.7 1619.36
  5047.4 1620.11  5055.2 1621.12  5074.8 1621.73  5080.9 1622.43  5083.8 1621.99
  5086.5 1622.47  5102.1 1622.37  5151.6 1624.75  5163.0 1626.73  5178.2 1631.06
  5199.5 1635.72  5214.2 1637.63  5240.3 1642.45  5287.7 1644.87  5300.2 1646.23
#Mann=4,-1,0
  4783.9   0.035       0  4953.2    0.07       0  5018.1    0.05       0
  5022.1    0.07       0
Bank Sta=5018.1,5022.1
Exp/Cntr=0.3,0.1

Type RM Length L Ch R = 1,489,293,293,293
BEGIN DESCRIPTION:
Stream0276 1.0
END DESCRIPTION:
XS GIS Cut Line= 3
      1986524.99     13877224.95      1986575.00     13877425.00
      1986874.97     13877524.99
#Sta/Elev= 30
  4793.8 1623.42  4854.9 1617.96  4870.6 1616.21  4892.1 1614.93  4941.6 1610.46
  4957.1 1608.80  4959.7 1608.18  4960.1 1607.18  4960.4 1606.68  4963.9 1606.68
  4964.1 1607.18  4969.6 1608.40  5027.1 1607.51  5039.1 1608.73  5055.6 1608.38
  5074.5 1609.48  5077.7 1609.05  5134.6 1613.07  5146.3 1613.16  5160.6 1614.18
  5182.3 1614.26  5200.9 1615.07  5222.2 1620.92  5236.4 1622.82  5261.1 1625.07
  5267.4 1624.78  5274.4 1625.38  5289.6 1628.84  5305.4 1630.71  5316.2 1633.06
#Mann=5,-1,0
  4793.8   0.035       0  4854.9     0.1       0  4960.1    0.05       0
  4964.1     0.1       0  5182.3    0.07       0
Bank Sta=4960.1,4964.1
Exp/Cntr=0.3,0.1

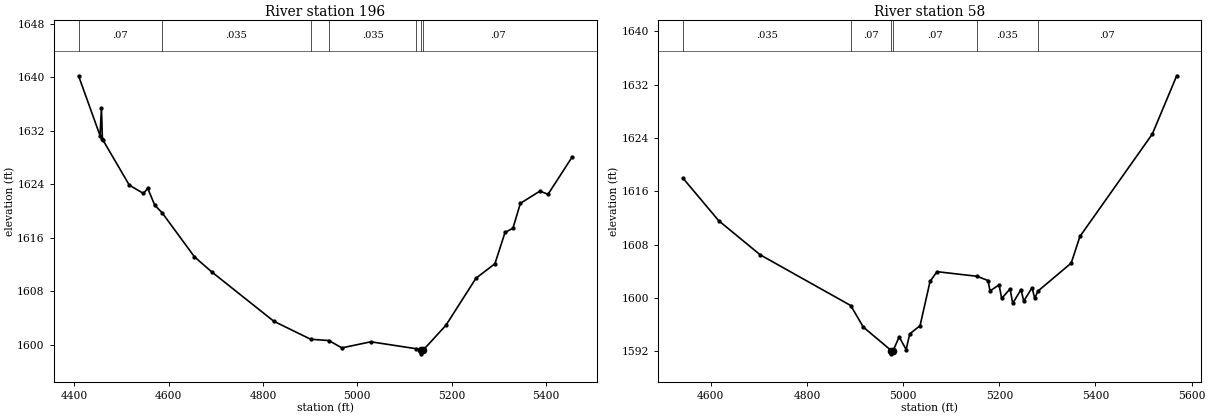
Type RM Length L Ch R = 1,196,138,138,138
BEGIN DESCRIPTION:
Stream0276 0.0
END DESCRIPTION:
XS GIS Cut Line= 3
      1986234.03     13877017.84      1986264.64     13877510.13
      1986672.72     13877885.05
#Sta/Elev= 30
  4408.7 1640.21  4454.3 1631.26  4457.3 1635.43  4459.3 1630.78  4459.8 1630.68
  4516.4 1623.86  4546.5 1622.61  4555.5 1623.38  4570.5 1620.84  4585.9 1619.74
  4654.7 1613.13  4690.8 1610.91  4823.0 1603.50  4901.2 1600.81  4939.8 1600.62
  4967.2 1599.52  5028.8 1600.43  5125.6 1599.39  5135.1 1599.13  5135.4 1598.63
  5139.1 1599.13  5188.1 1602.90  5251.8 1609.93  5292.1 1612.11  5313.5 1616.78
  5330.3 1617.42  5346.1 1621.14  5387.7 1622.97  5404.7 1622.48  5456.1 1628.09
#Mann=7,-1,0
  4408.7    0.07       0  4585.9   0.035       0  4901.2    0.07       0
  4939.8   0.035       0  5125.6    0.07       0  5135.1   0.035       0
  5139.1    0.07       0
Bank Sta=5135.1,5139.1
Exp/Cntr=0.3,0.1

Type RM Length L Ch R = 1,58,0,0,0
BEGIN DESCRIPTION:
Stream0276 T
END DESCRIPTION:
XS GIS Cut Line= 6
      1986180.46     13877180.69      1986206.50     13877621.26
      1986267.27     13877698.30      1986335.62     13877772.09
      1986487.53     13877842.62      1986698.01     13877904.46
#Sta/Elev= 30
  4542.0 1617.97  4616.4 1611.58  4702.6 1606.46  4891.0 1598.84  4917.0 1595.61
  4975.1 1592.09  4975.3 1591.59  4979.1 1592.09  4991.7 1594.12  5006.2 1592.24
  5013.6 1594.58  5035.1 1595.82  5055.9 1602.47  5070.3 1603.93  5153.4 1603.24
  5176.5 1602.60  5180.6 1601.03  5199.4 1601.95  5204.9 1599.91  5222.3 1601.35
  5227.8 1599.18  5245.2 1601.25  5250.7 1599.51  5268.1 1601.52  5273.6 1599.91
  5280.1 1601.00  5349.5 1605.22  5367.7 1609.23  5518.2 1624.60  5568.9 1633.35
#Mann=6,-1,0
  4542.0   0.035       0  4891.0    0.07       0  4975.1    0.05       0
  4979.1    0.07       0  5153.4   0.035       0  5280.1    0.07       0
Bank Sta=4975.1,4979.1
Exp/Cntr=0.3,0.1

Chan Stop Cuts=-1