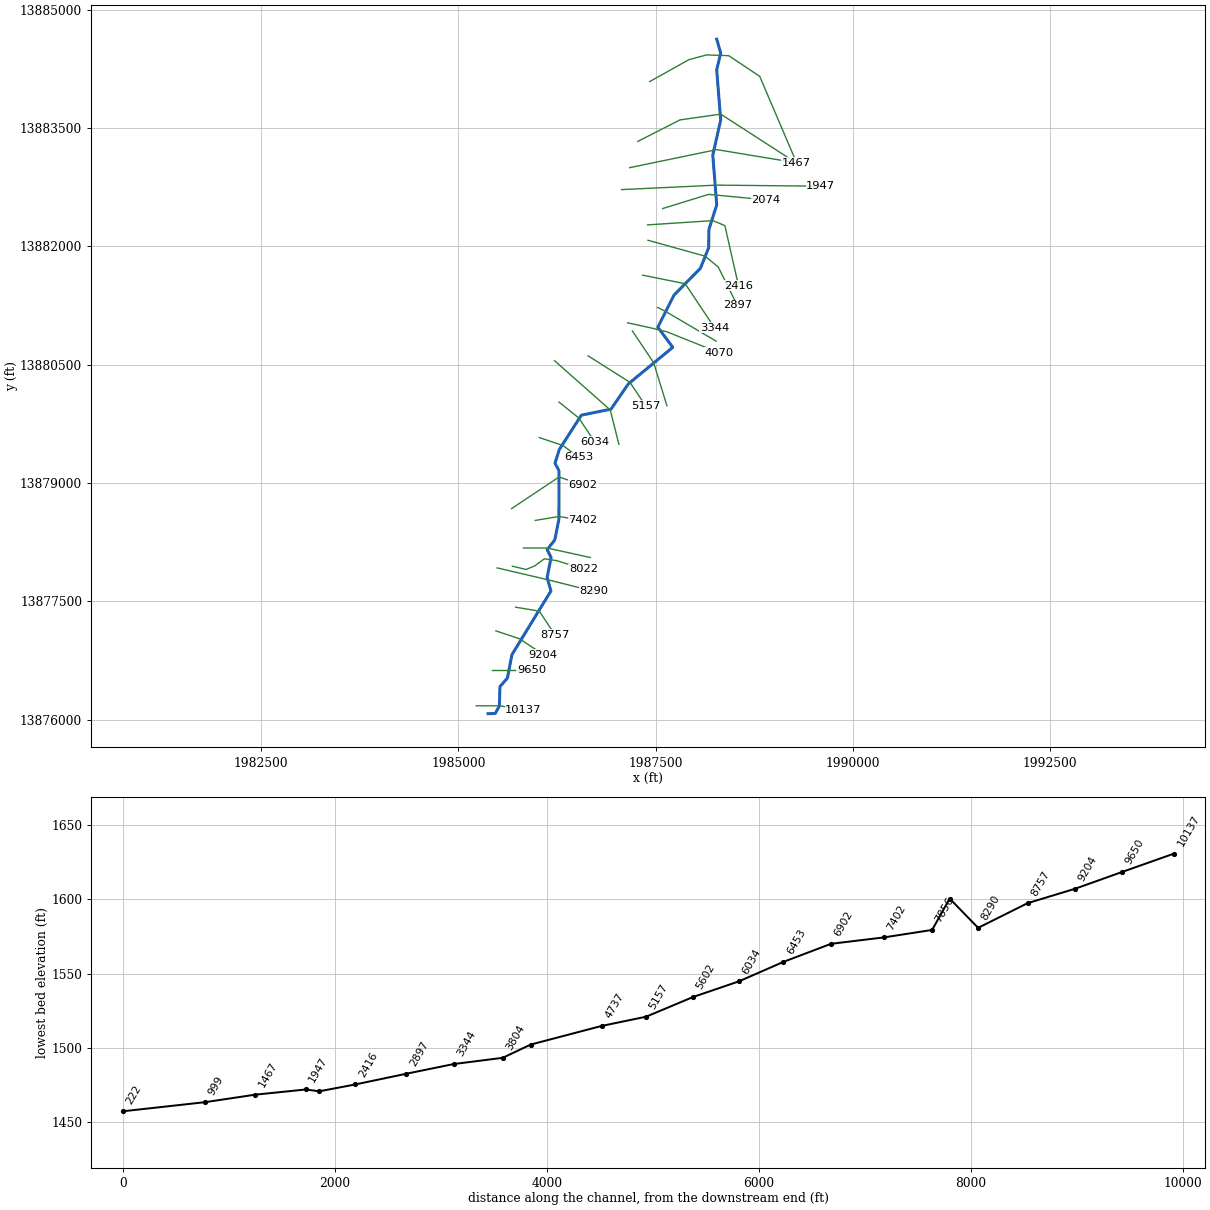
--- Stream0278.prj (project) ---

Proj Title=Stream0278 Base Level Engineering
Current Plan=p01
Default Exp/Contr=0.3,0.1
English Units
Geom File=g01
Flow File=f01
Plan File=p01
BEGIN DESCRIPTION:
Stream0278
END DESCRIPTION:

--- Stream0278.p01 (plan) ---

Plan Title=Multiple Run
Short Identifier=Multiple
Geom File=g01
Flow File=f01
Subcritical Flow
K Sum by GR= 0
Std Step Tol= 0.01
Critical Tol= 0.01
Num of Std Step Trials= 20
Max Error Tol= 0.3
Flow Tol Ratio= 0.001
Split Flow NTrial= 30
Split Flow Tol= 0.02
Split Flow Ratio= 0.02
Log Output Level= 0
Friction Slope Method= 1
Unsteady Friction Slope Method= 2
Unsteady Bridges Friction Slope Method= 1
Parabolic Critical Depth
Global Vel Dist=  1 , 1 , 1
Global Log Level= 0
CheckData=True
Encroach Param= -1, 0, 0, 0
BEGIN DESCRIPTION:
Multiple Run
END DESCRIPTION:

--- Stream0278.f01 (steady flow) ---

Flow Title=Multiple
Number of Profiles=7
Profile Names=10-year,25-year,50-year,1pct_min,100-year,1pct_plu,500-year
River Rch & RM= Stream0278,Reach-1,10137
     775    1309    1817    1227    2447    4883    4384
River Rch & RM= Stream0278,Reach-1,8290
    1208    2099    2971    2040    4071    8123    7564
River Rch & RM= Stream0278,Reach-1,7856
    1560    2744    3912    2703    5394   10762   10150
River Rch & RM= Stream0278,Reach-1,4737
    1706    3009    4296    2971    5928   11828   11177
River Rch & RM= Stream0278,Reach-1,2074
    2650    4768    6900    4827    9631   19216   18593
Boundary for River Rch & Prof#=Stream0278,Reach-1,1
Up Type=0
Dn Type=3
Dn Slope=0.005
Boundary for River Rch & Prof#=Stream0278,Reach-1,2
Up Type=0
Dn Type=3
Dn Slope=0.005
Boundary for River Rch & Prof#=Stream0278,Reach-1,3
Up Type=0
Dn Type=3
Dn Slope=0.005
Boundary for River Rch & Prof#=Stream0278,Reach-1,4
Up Type=0
Dn Type=3
Dn Slope=0.005
Boundary for River Rch & Prof#=Stream0278,Reach-1,5
Up Type=0
Dn Type=3
Dn Slope=0.005
Boundary for River Rch & Prof#=Stream0278,Reach-1,6
Up Type=0
Dn Type=3
Dn Slope=0.005
Boundary for River Rch & Prof#=Stream0278,Reach-1,7
Up Type=0
Dn Type=3
Dn Slope=0.005

--- Stream0278.g01 (geometry) ---

Geom Title=Existing Conditions

River Reach=Stream0278,Reach-1
Reach XY= 30
      1985375.00     13876075.00      1985466.92     13876077.81
      1985519.31     13876172.61      1985527.07     13876419.14
      1985621.44     13876526.47      1985678.83     13876823.42
      1986173.31     13877631.15      1986124.53     13877800.00
      1986174.92     13878054.97      1986124.61     13878154.87
      1986221.45     13878276.47      1986274.48     13878540.22
      1986274.91     13879154.97      1986224.60     13879250.00
      1986278.83     13879423.42      1986558.23     13879858.57
      1986934.81     13879935.51      1987153.78     13880254.61
      1987717.55     13880718.95      1987528.11     13880973.35
      1987733.14     13881381.06      1988067.14     13881718.83
      1988172.76     13881980.93      1988176.22     13882214.50
      1988275.00     13882525.00      1988224.91     13883154.90
      1988325.20     13883599.92      1988274.54     13884235.18
      1988325.23     13884450.08      1988275.00     13884625.00

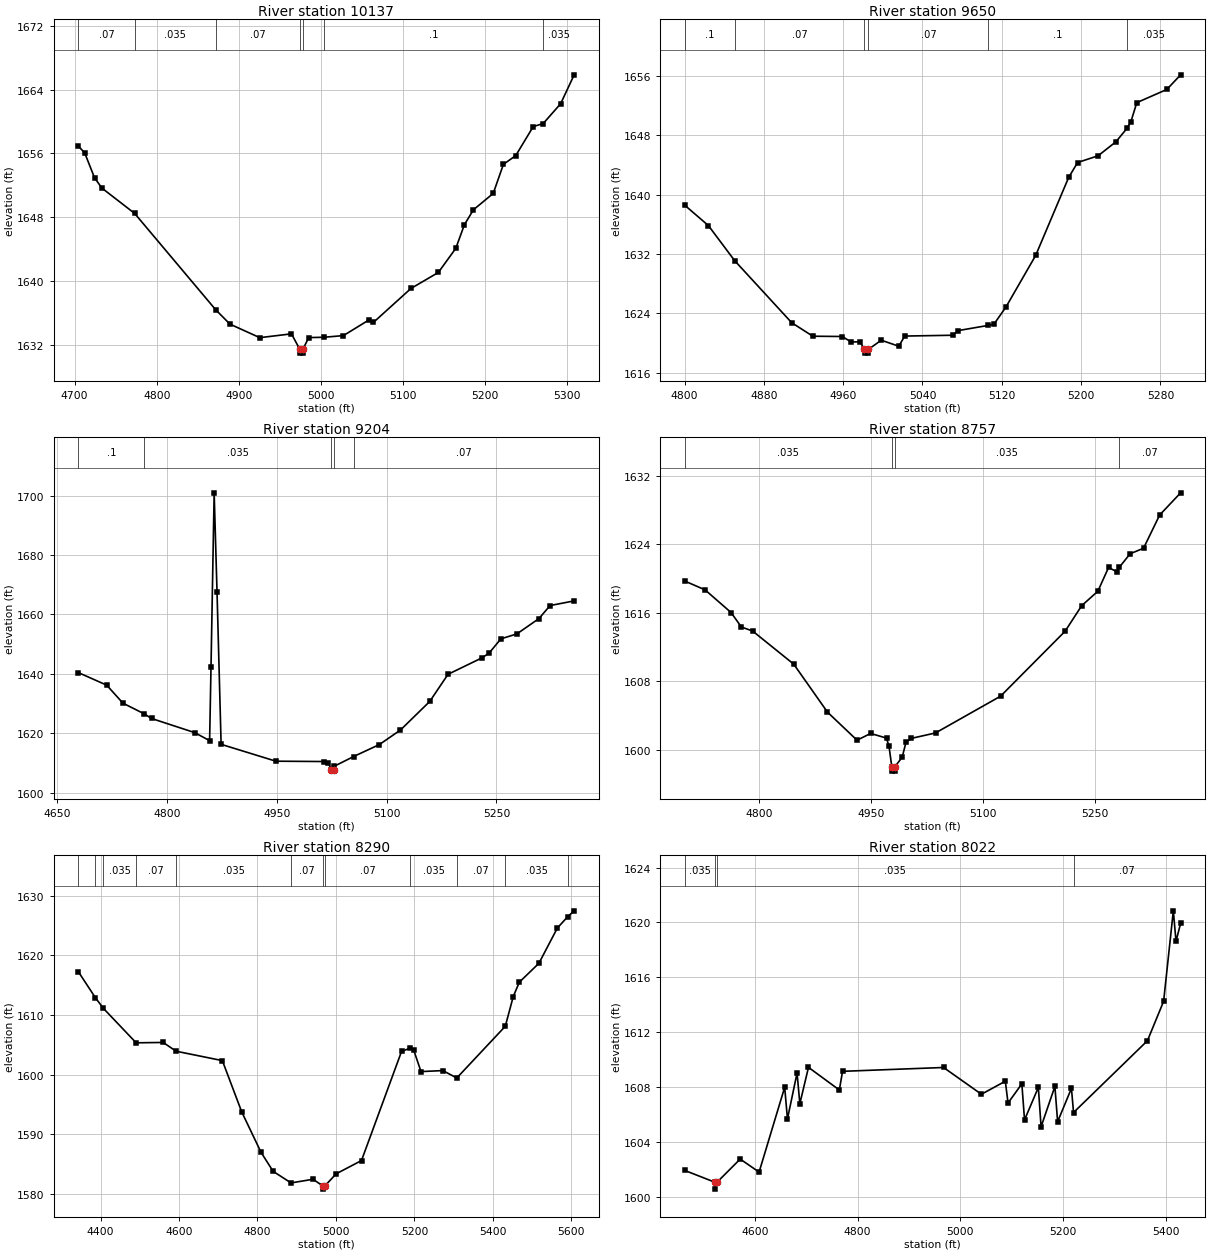
Type RM Length L Ch R = 1,10137,487,487,487
BEGIN DESCRIPTION:
Stream0278 21.0
END DESCRIPTION:
XS GIS Cut Line= 3
      1985225.01     13876175.00      1985525.00     13876175.00
      1985824.97     13876125.01
#Sta/Elev= 30
  4704.5 1656.92  4712.2 1656.09  4724.2 1652.96  4733.2 1651.66  4773.1 1648.48
  4871.7 1636.41  4889.2 1634.59  4925.6 1632.89  4964.2 1633.37  4974.2 1631.45
  4974.5 1630.95  4978.0 1630.95  4978.2 1631.45  4985.2 1632.90  5003.7 1632.94
  5027.5 1633.15  5058.2 1635.09  5064.0 1634.80  5109.7 1639.06  5143.1 1641.07
  5164.4 1644.10  5174.9 1647.07  5185.9 1648.94  5210.0 1650.99  5222.4 1654.64
  5237.4 1655.73  5258.7 1659.37  5270.9 1659.76  5292.1 1662.24  5308.6 1665.87
#Mann=7,-1,0
  4704.5    0.07       0  4773.1   0.035       0  4871.7    0.07       0
  4974.2    0.05       0  4978.2    0.07       0  5003.7     0.1       0
  5270.9   0.035       0
Bank Sta=4974.2,4978.2
Exp/Cntr=0.3,0.1

Type RM Length L Ch R = 1,9650,446,446,446
BEGIN DESCRIPTION:
Stream0278 20.0
END DESCRIPTION:
XS GIS Cut Line= 3
      1985424.97     13876625.00      1985625.00     13876625.00
      1985924.97     13876625.00
#Sta/Elev= 30
  4800.3 1638.55  4824.1 1635.81  4850.6 1631.08  4908.1 1622.72  4929.4 1620.90
  4959.1 1620.86  4968.1 1620.12  4977.1 1620.15  4981.4 1619.12  4981.7 1618.62
  4985.2 1618.62  4985.4 1619.12  4998.4 1620.36  5016.1 1619.55  5022.1 1620.92
  5070.4 1621.03  5076.1 1621.66  5106.4 1622.36  5112.1 1622.53  5124.1 1624.82
  5154.1 1631.78  5187.4 1642.30  5196.4 1644.31  5217.1 1645.22  5235.1 1647.11
  5246.1 1648.90  5250.1 1649.79  5256.1 1652.38  5286.4 1654.16  5300.3 1656.13
#Mann=6,-1,0
  4800.3     0.1       0  4850.6    0.07       0  4981.4    0.05       0
  4985.4    0.07       0  5106.4     0.1       0  5246.1   0.035       0
Bank Sta=4981.4,4985.4
Exp/Cntr=0.3,0.1

Type RM Length L Ch R = 1,9204,447,447,447
BEGIN DESCRIPTION:
Stream0278 19.0
END DESCRIPTION:
XS GIS Cut Line= 3
      1985474.96     13877125.01      1985775.00     13877025.00
      1986074.98     13876825.01
#Sta/Elev= 30
  4679.3 1640.42  4718.0 1636.19  4740.2 1630.12  4769.2 1626.53  4779.2 1624.96
  4838.2 1620.19  4858.5 1617.49  4860.4 1642.27  4864.7 1700.99  4868.6 1667.71
  4874.2 1616.25  4948.9 1610.57  5014.5 1610.45  5020.4 1609.94  5024.8 1607.72
  5025.1 1607.22  5028.8 1607.72  5028.9 1608.90  5055.1 1612.14  5090.2 1616.17
  5119.0 1621.07  5159.0 1630.70  5183.9 1639.84  5230.8 1645.45  5240.1 1647.02
  5256.1 1651.79  5277.9 1653.45  5308.1 1658.63  5323.2 1663.01  5356.1 1664.58
#Mann=5,-1,0
  4679.3     0.1       0  4769.2   0.035       0  5024.8   0.035       0
  5028.8   0.035       0  5055.1    0.07       0
Bank Sta=5024.8,5028.8
Exp/Cntr=0.3,0.1

Type RM Length L Ch R = 1,8757,467,467,467
BEGIN DESCRIPTION:
Stream0278 18.0
END DESCRIPTION:
XS GIS Cut Line= 3
      1985725.00     13877425.00      1986025.00     13877375.00
      1986225.00     13877075.00
#Sta/Elev= 30
  4700.3 1619.71  4727.4 1618.69  4762.3 1616.04  4776.1 1614.35  4791.3 1613.87
  4846.4 1610.00  4891.6 1604.40  4931.2 1601.12  4949.4 1601.91  4970.7 1601.37
  4974.1 1600.40  4977.8 1598.01  4978.1 1597.51  4981.6 1597.51  4981.8 1598.01
  4991.7 1599.13  4996.9 1600.90  5004.2 1601.34  5036.4 1601.97  5123.7 1606.27
  5210.2 1613.86  5232.4 1616.84  5254.0 1618.52  5268.4 1621.30  5279.2 1620.81
  5282.7 1621.31  5297.3 1622.90  5315.3 1623.55  5336.9 1627.43  5365.0 1630.02
#Mann=4,-1,0
  4700.3   0.035       0  4977.8   0.035       0  4981.8   0.035       0
  5282.7    0.07       0
Bank Sta=4977.8,4981.8
Exp/Cntr=0.3,0.1

Type RM Length L Ch R = 1,8290,268,268,268
BEGIN DESCRIPTION:
Stream0278 17.0
END DESCRIPTION:
XS GIS Cut Line= 3
      1985490.31     13877923.34      1986125.00     13877775.00
      1986718.22     13877625.74
#Sta/Elev= 30
  4343.5 1617.25  4386.7 1612.92  4407.2 1611.12  4490.8 1605.34  4559.6 1605.40
  4592.8 1603.93  4710.5 1602.36  4759.8 1593.78  4809.1 1587.00  4839.9 1583.82
  4885.5 1581.88  4941.6 1582.49  4967.3 1581.34  4967.6 1580.84  4971.3 1581.34
  5000.2 1583.39  5065.1 1585.63  5167.2 1603.91  5189.7 1604.46  5198.3 1604.09
  5216.7 1600.52  5272.4 1600.69  5307.9 1599.45  5431.5 1608.11  5451.8 1613.09
  5467.3 1615.49  5517.1 1618.65  5564.1 1624.55  5590.7 1626.47  5607.0 1627.44
#Mann=12,-1,0
  4343.5   0.035       0  4386.7    0.07       0  4407.2   0.035       0
  4490.8    0.07       0  4592.8   0.035       0  4885.5    0.07       0
  4967.3    0.05       0  4971.3    0.07       0  5189.7   0.035       0
  5307.9    0.07       0  5431.5   0.035       0  5590.7    0.07       0
Bank Sta=4967.3,4971.3
Exp/Cntr=0.3,0.1

Type RM Length L Ch R = 1,8022,166,166,166
BEGIN DESCRIPTION:
Stream0278 D
END DESCRIPTION:
XS GIS Cut Line= 6
      1985683.80     13877944.83      1985857.40     13877903.16
      1985968.51     13877948.30      1986090.04     13878038.58
      1986249.76     13878014.27      1986586.57     13877906.63
#Sta/Elev= 30
  4463.8 1601.94  4522.5 1601.08  4522.7 1600.58  4526.5 1601.08  4571.6 1602.77
  4608.4 1601.82  4658.2 1608.00  4663.6 1605.69  4682.3 1609.04  4687.7 1606.80
  4704.5 1609.45  4764.6 1607.80  4770.8 1609.16  4967.4 1609.44  5041.1 1607.49
  5087.6 1608.44  5092.9 1606.85  5119.8 1608.25  5125.0 1605.62  5151.9 1607.99
  5157.2 1605.12  5184.1 1608.06  5189.4 1605.49  5216.3 1607.92  5220.4 1606.16
  5364.2 1611.39  5395.7 1614.26  5414.6 1620.85  5419.8 1618.63  5428.8 1619.94
#Mann=4,-1,0
  4463.8   0.035       0  4522.5   0.035       0  4526.5   0.035       0
  5220.4    0.07       0
Bank Sta=4522.5,4526.5
Exp/Cntr=0.3,0.1

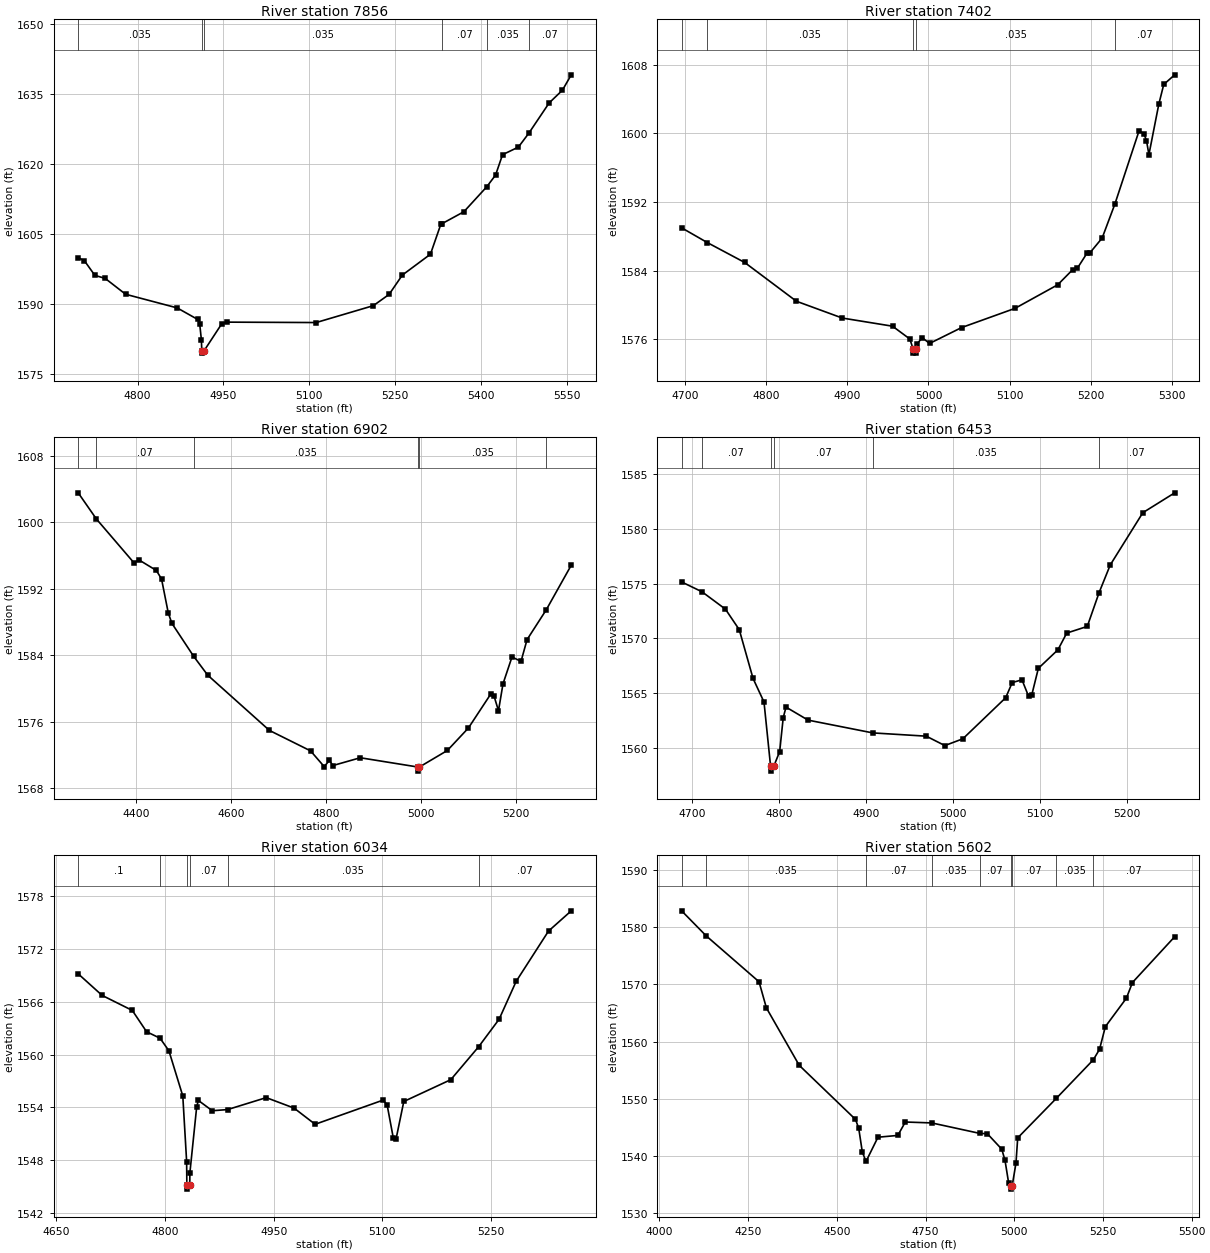
Type RM Length L Ch R = 1,7856,454,454,454
BEGIN DESCRIPTION:
Stream0278 16.0
END DESCRIPTION:
XS GIS Cut Line= 3
      1985824.95     13878175.00      1986125.00     13878175.00
      1986672.88     13878054.59
#Sta/Elev= 30
  4696.3 1599.86  4707.1 1599.22  4725.4 1596.08  4743.4 1595.43  4779.1 1592.03
  4869.1 1589.11  4905.1 1586.63  4908.4 1585.76  4911.4 1582.30  4912.1 1579.92
  4912.3 1579.42  4916.1 1579.92  4947.1 1585.73  4956.1 1586.06  5111.8 1585.97
  5211.7 1589.59  5239.2 1592.00  5262.3 1596.14  5311.4 1600.61  5329.8 1607.12
  5332.0 1607.18  5369.8 1609.71  5409.6 1615.04  5425.1 1617.56  5437.3 1621.93
  5465.0 1623.56  5483.4 1626.57  5518.7 1633.02  5541.8 1635.74  5557.3 1639.04
#Mann=6,-1,0
  4696.3   0.035       0  4912.1   0.035       0  4916.1   0.035       0
  5332.0    0.07       0  5409.6   0.035       0  5483.4    0.07       0
Bank Sta=4912.1,4916.1
Exp/Cntr=0.3,0.1

Type RM Length L Ch R = 1,7402,500,500,500
BEGIN DESCRIPTION:
Stream0278 15.0
END DESCRIPTION:
XS GIS Cut Line= 3
      1985975.02     13878525.00      1986275.00     13878575.00
      1986575.05     13878524.99
#Sta/Elev= 30
  4695.5 1589.00  4727.2 1587.28  4773.3 1584.96  4837.1 1580.44  4893.7 1578.48
  4955.7 1577.53  4977.0 1576.04  4981.1 1574.89  4981.4 1574.39  4984.9 1574.39
  4985.1 1574.89  4986.2 1575.47  4992.2 1576.20  5001.4 1575.52  5040.9 1577.37
  5106.8 1579.61  5159.5 1582.36  5177.8 1584.11  5183.8 1584.30  5196.0 1586.10
  5199.0 1586.06  5214.3 1587.81  5230.0 1591.77  5259.9 1600.33  5266.0 1599.93
  5269.0 1599.17  5272.0 1597.54  5284.2 1603.42  5290.3 1605.72  5303.8 1606.84
#Mann=5,-1,0
  4695.5    0.07       0  4727.2   0.035       0  4981.1   0.035       0
  4985.1   0.035       0  5230.0    0.07       0
Bank Sta=4981.1,4985.1
Exp/Cntr=0.3,0.1

Type RM Length L Ch R = 1,6902,449,449,449
BEGIN DESCRIPTION:
Stream0278 14.0
END DESCRIPTION:
XS GIS Cut Line= 3
      1985675.01     13878675.01      1986275.00     13879075.00
      1986574.97     13878975.01
#Sta/Elev= 30
  4278.8 1603.55  4317.1 1600.40  4396.2 1595.12  4406.5 1595.48  4443.1 1594.21
  4454.1 1593.19  4468.3 1589.09  4475.9 1587.84  4521.7 1583.87  4551.3 1581.60
  4681.1 1574.95  4767.6 1572.49  4796.4 1570.59  4807.3 1571.35  4814.5 1570.72
  4872.2 1571.66  4992.8 1570.55  4993.0 1570.05  4996.8 1570.55  5055.5 1572.54
  5099.7 1575.24  5147.2 1579.37  5153.5 1579.11  5163.0 1577.32  5172.5 1580.56
  5191.4 1583.79  5210.4 1583.26  5223.1 1585.88  5263.6 1589.48  5316.1 1594.84
#Mann=6,-1,0
  4278.8   0.035       0  4317.1    0.07       0  4521.7   0.035       0
  4992.8   0.035       0  4996.8   0.035       0  5263.6    0.07       0
Bank Sta=4992.8,4996.8
Exp/Cntr=0.3,0.1

Type RM Length L Ch R = 1,6453,419,419,419
BEGIN DESCRIPTION:
Stream0278 13.0
END DESCRIPTION:
XS GIS Cut Line= 3
      1986024.96     13879575.01      1986325.00     13879475.00
      1986525.03     13879324.98
#Sta/Elev= 30
  4688.3 1575.16  4711.7 1574.26  4738.6 1572.67  4754.5 1570.79  4770.3 1566.33
  4782.9 1564.17  4790.4 1558.34  4790.6 1557.84  4794.4 1558.34  4800.9 1559.63
  4805.0 1562.74  4808.2 1563.70  4833.5 1562.51  4907.8 1561.34  4969.3 1561.04
  4990.6 1560.18  5011.3 1560.80  5060.5 1564.56  5068.0 1565.95  5079.2 1566.20
  5086.7 1564.71  5090.5 1564.83  5098.0 1567.25  5120.5 1568.95  5130.6 1570.48
  5154.2 1571.09  5167.8 1574.19  5180.6 1576.72  5218.0 1581.50  5254.6 1583.32
#Mann=6,-1,0
  4688.3   0.035       0  4711.7    0.07       0  4790.4   0.035       0
  4794.4    0.07       0  4907.8   0.035       0  5167.8    0.07       0
Bank Sta=4790.4,4794.4
Exp/Cntr=0.3,0.1

Type RM Length L Ch R = 1,6034,432,432,432
BEGIN DESCRIPTION:
Stream0278 12.0
END DESCRIPTION:
XS GIS Cut Line= 3
      1986274.99     13880025.01      1986525.00     13879825.00
      1986724.99     13879525.02
#Sta/Elev= 30
  4680.1 1569.18  4713.1 1566.73  4754.8 1565.02  4774.5 1562.60  4793.1 1561.86
  4805.3 1560.44  4824.5 1555.30  4829.8 1547.85  4830.1 1545.21  4830.4 1544.71
  4834.1 1545.21  4834.3 1546.57  4843.7 1554.07  4846.0 1554.79  4865.2 1553.62
  4886.3 1553.75  4939.7 1555.11  4978.1 1553.92  5007.2 1552.08  5100.8 1554.82
  5106.5 1554.32  5115.1 1550.53  5118.8 1550.36  5129.6 1554.67  5194.5 1557.15
  5232.9 1560.89  5261.2 1564.02  5284.7 1568.32  5329.4 1574.04  5360.8 1576.34
#Mann=6,-1,0
  4680.1     0.1       0  4793.1    0.07       0  4830.1   0.035       0
  4834.1    0.07       0  4886.3   0.035       0  5232.9    0.07       0
Bank Sta=4830.1,4834.1
Exp/Cntr=0.3,0.1

Type RM Length L Ch R = 1,5602,445,445,445
BEGIN DESCRIPTION:
Stream0278 11.0
END DESCRIPTION:
XS GIS Cut Line= 3
      1986219.08     13880548.88      1986925.00     13879925.00
      1987034.51     13879490.90
#Sta/Elev= 30
  4062.4 1582.88  4131.6 1578.50  4280.6 1570.46  4301.3 1565.89  4393.9 1555.83
  4552.4 1546.37  4561.5 1544.84  4571.7 1540.66  4582.1 1539.00  4615.8 1543.25
  4671.8 1543.56  4692.9 1545.91  4767.3 1545.75  4902.6 1543.92  4924.1 1543.86
  4964.7 1541.16  4973.8 1539.23  4984.1 1535.26  4989.9 1534.66  4990.1 1534.16
  4993.9 1534.66  5004.8 1538.70  5009.7 1543.13  5118.2 1550.03  5222.9 1556.81
  5240.3 1558.63  5256.8 1562.61  5316.1 1567.59  5333.1 1570.33  5452.2 1578.35
#Mann=9,-1,0
  4062.4    0.07       0  4131.6   0.035       0  4582.1    0.07       0
  4767.3   0.035       0  4902.6    0.07       0  4989.9    0.05       0
  4993.9    0.07       0  5118.2   0.035       0  5222.9    0.07       0
Bank Sta=4989.9,4993.9
Exp/Cntr=0.3,0.1

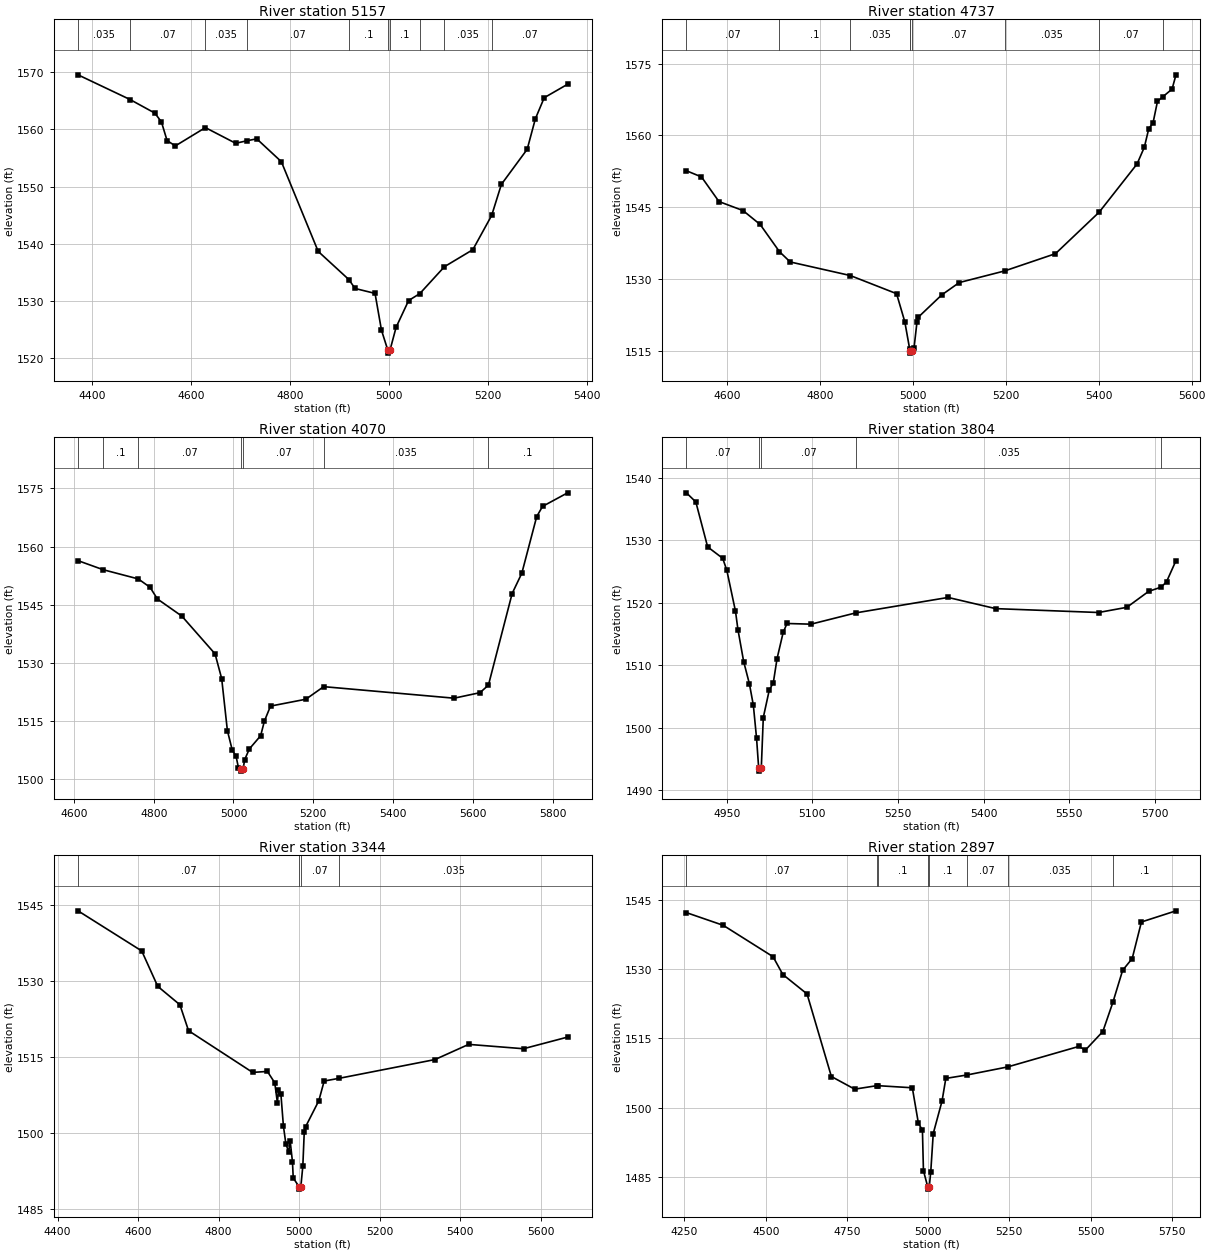
Type RM Length L Ch R = 1,5157,420,420,420
BEGIN DESCRIPTION:
Stream0278 10.0
END DESCRIPTION:
XS GIS Cut Line= 3
      1986643.51     13880611.57      1987175.00     13880275.00
      1987375.02     13879974.96
#Sta/Elev= 30
  4370.9 1569.58  4476.1 1565.25  4526.2 1562.87  4539.5 1561.33  4550.9 1558.06
  4567.6 1557.12  4628.4 1560.33  4689.6 1557.58  4712.6 1558.03  4732.2 1558.36
  4781.9 1554.36  4856.4 1538.63  4918.3 1533.70  4931.0 1532.13  4971.3 1531.27
  4984.3 1524.83  4997.2 1521.30  4997.5 1520.80  5001.5 1521.30  5013.9 1525.33
  5039.2 1530.02  5061.8 1531.23  5111.6 1535.95  5169.0 1538.93  5207.1 1544.94
  5226.7 1550.38  5278.9 1556.53  5295.4 1561.87  5313.3 1565.57  5360.6 1567.93
#Mann=10,-1,0
  4370.9   0.035       0  4476.1    0.07       0  4628.4   0.035       0
  4712.6    0.07       0  4918.3     0.1       0  4997.2    0.05       0
  5001.5     0.1       0  5061.8    0.07       0  5111.6   0.035       0
  5207.1    0.07       0
Bank Sta=4997.2,5001.5
Exp/Cntr=0.3,0.1

Type RM Length L Ch R = 1,4737,667,667,667
BEGIN DESCRIPTION:
Stream0278 9.0
END DESCRIPTION:
XS GIS Cut Line= 3
      1987205.44     13880926.31      1987475.00     13880525.00
      1987643.31     13879979.20
#Sta/Elev= 30
  4511.7 1552.63  4544.2 1551.34  4581.8 1546.20  4633.6 1544.32  4670.6 1541.41
  4712.2 1535.73  4735.3 1533.59  4864.6 1530.76  4964.4 1526.97  4982.1 1521.12
  4992.7 1515.38  4993.6 1515.06  4993.9 1514.56  4998.1 1515.06  5002.1 1515.72
  5008.4 1521.08  5011.4 1522.08  5061.7 1526.71  5099.4 1529.29  5196.9 1531.71
  5306.7 1535.32  5400.9 1543.99  5482.4 1554.04  5498.1 1557.54  5507.5 1561.35
  5516.9 1562.65  5526.4 1567.11  5538.5 1568.12  5557.8 1569.67  5566.3 1572.65
#Mann=9,-1,0
  4511.7    0.07       0  4712.2     0.1       0  4864.6   0.035       0
  4992.7    0.07       0  4993.6    0.05       0  4998.1    0.07       0
  5196.9   0.035       0  5400.9    0.07       0  5538.5   0.035       0
Bank Sta=4993.6,4998.1
Exp/Cntr=0.3,0.1

Type RM Length L Ch R = 1,4070,266,266,266
BEGIN DESCRIPTION:
Stream0278 8.0
END DESCRIPTION:
XS GIS Cut Line= 4
      1987144.32     13881030.00      1987434.98     13880966.36
      1987643.26     13880915.33      1988307.65     13880649.73
#Sta/Elev= 30
  4610.2 1556.36  4673.3 1554.02  4761.3 1551.64  4790.8 1549.48  4809.2 1546.47
  4870.6 1542.03  4953.8 1532.29  4970.4 1525.90  4984.7 1512.47  4997.1 1507.37
  5006.3 1505.92  5012.4 1502.91  5019.5 1502.52  5019.8 1502.02  5024.1 1502.52
  5027.9 1504.95  5039.8 1507.76  5068.1 1511.16  5077.4 1514.91  5092.8 1518.81
  5181.4 1520.58  5226.1 1523.83  5553.1 1520.85  5618.1 1522.28  5639.2 1524.23
  5698.6 1547.87  5722.9 1553.12  5760.2 1567.74  5774.9 1570.37  5837.7 1573.87
#Mann=7,-1,0
  4610.2    0.07       0  4673.3     0.1       0  4761.3    0.07       0
  5019.5    0.05       0  5024.1    0.07       0  5226.1   0.035       0
  5639.2     0.1       0
Bank Sta=5019.5,5024.1
Exp/Cntr=0.3,0.1

Type RM Length L Ch R = 1,3804,460,460,460
BEGIN DESCRIPTION:
Stream0278 7.0
END DESCRIPTION:
XS GIS Cut Line= 3
      1987524.99     13881225.00      1987625.00     13881175.00
      1988267.95     13880796.90
#Sta/Elev= 30
  4879.5 1537.61  4896.0 1536.15  4916.7 1528.95  4943.1 1527.12  4950.3 1525.20
  4965.5 1518.63  4969.8 1515.69  4979.8 1510.59  4989.9 1507.00  4996.8 1503.57
  5002.4 1498.30  5006.1 1493.53  5006.4 1493.03  5010.7 1493.53  5014.2 1501.62
  5024.6 1505.98  5031.8 1507.22  5038.3 1511.05  5049.0 1515.24  5055.7 1516.68
  5097.7 1516.57  5176.3 1518.38  5337.9 1520.85  5421.4 1519.06  5601.5 1518.44
  5651.1 1519.27  5689.2 1521.82  5711.6 1522.52  5720.7 1523.38  5737.2 1526.76
#Mann=5,-1,0
  4879.5    0.07       0  5006.1    0.05       0  5010.7    0.07       0
  5176.3   0.035       0  5711.6     0.1       0
Bank Sta=5006.1,5010.7
Exp/Cntr=0.3,0.1

Type RM Length L Ch R = 1,3344,447,447,447
BEGIN DESCRIPTION:
Stream0278 6.0
END DESCRIPTION:
XS GIS Cut Line= 3
      1987336.49     13881633.35      1987875.00     13881525.00
      1988245.42     13880970.20
#Sta/Elev= 30
  4450.7 1543.79  4609.0 1535.87  4648.8 1528.88  4703.8 1525.25  4725.3 1520.13
  4884.5 1511.90  4921.2 1512.09  4939.5 1509.85  4946.0 1505.93  4948.7 1508.39
  4954.8 1507.58  4961.0 1501.31  4967.1 1497.81  4974.0 1496.21  4977.9 1498.28
  4983.5 1494.24  4985.4 1491.06  4999.7 1489.36  5000.0 1488.86  5004.3 1489.36
  5009.2 1493.36  5012.8 1500.15  5016.4 1501.22  5048.9 1506.30  5062.3 1510.20
  5100.0 1510.74  5337.4 1514.43  5421.3 1517.43  5557.5 1516.57  5667.1 1518.87
#Mann=4,-1,0
  4450.7    0.07       0  4999.7    0.05       0  5004.3    0.07       0
  5100.0   0.035       0
Bank Sta=4999.7,5004.3
Exp/Cntr=0.3,0.1

Type RM Length L Ch R = 1,2897,481,481,481
BEGIN DESCRIPTION:
Stream0278 5.0
END DESCRIPTION:
XS GIS Cut Line= 4
      1987403.72     13882075.76      1988125.00     13881875.00
      1988293.85     13881737.54      1988534.49     13881253.26
#Sta/Elev= 30
  4255.9 1542.23  4369.3 1539.48  4522.6 1532.68  4552.8 1528.82  4627.3 1524.61
  4702.2 1506.72  4773.9 1503.98  4842.6 1504.74  4844.3 1504.74  4951.4 1504.28
  4970.1 1496.59  4982.5 1495.08  4985.6 1486.32  4998.8 1482.82  4999.2 1482.32
  5003.5 1482.82  5008.1 1486.04  5015.8 1494.37  5042.9 1501.42  5054.5 1506.31
  5118.5 1507.04  5244.4 1508.79  5464.0 1513.24  5484.2 1512.45  5537.9 1516.47
  5568.7 1522.77  5598.8 1529.73  5628.3 1532.29  5656.6 1540.20  5763.1 1542.62
#Mann=8,-1,0
  4255.9    0.07       0  4842.6   0.035       0  4844.3     0.1       0
  4998.8    0.05       0  5003.5     0.1       0  5118.5    0.07       0
  5244.4   0.035       0  5568.7     0.1       0
Bank Sta=4998.8,5003.5
Exp/Cntr=0.3,0.1

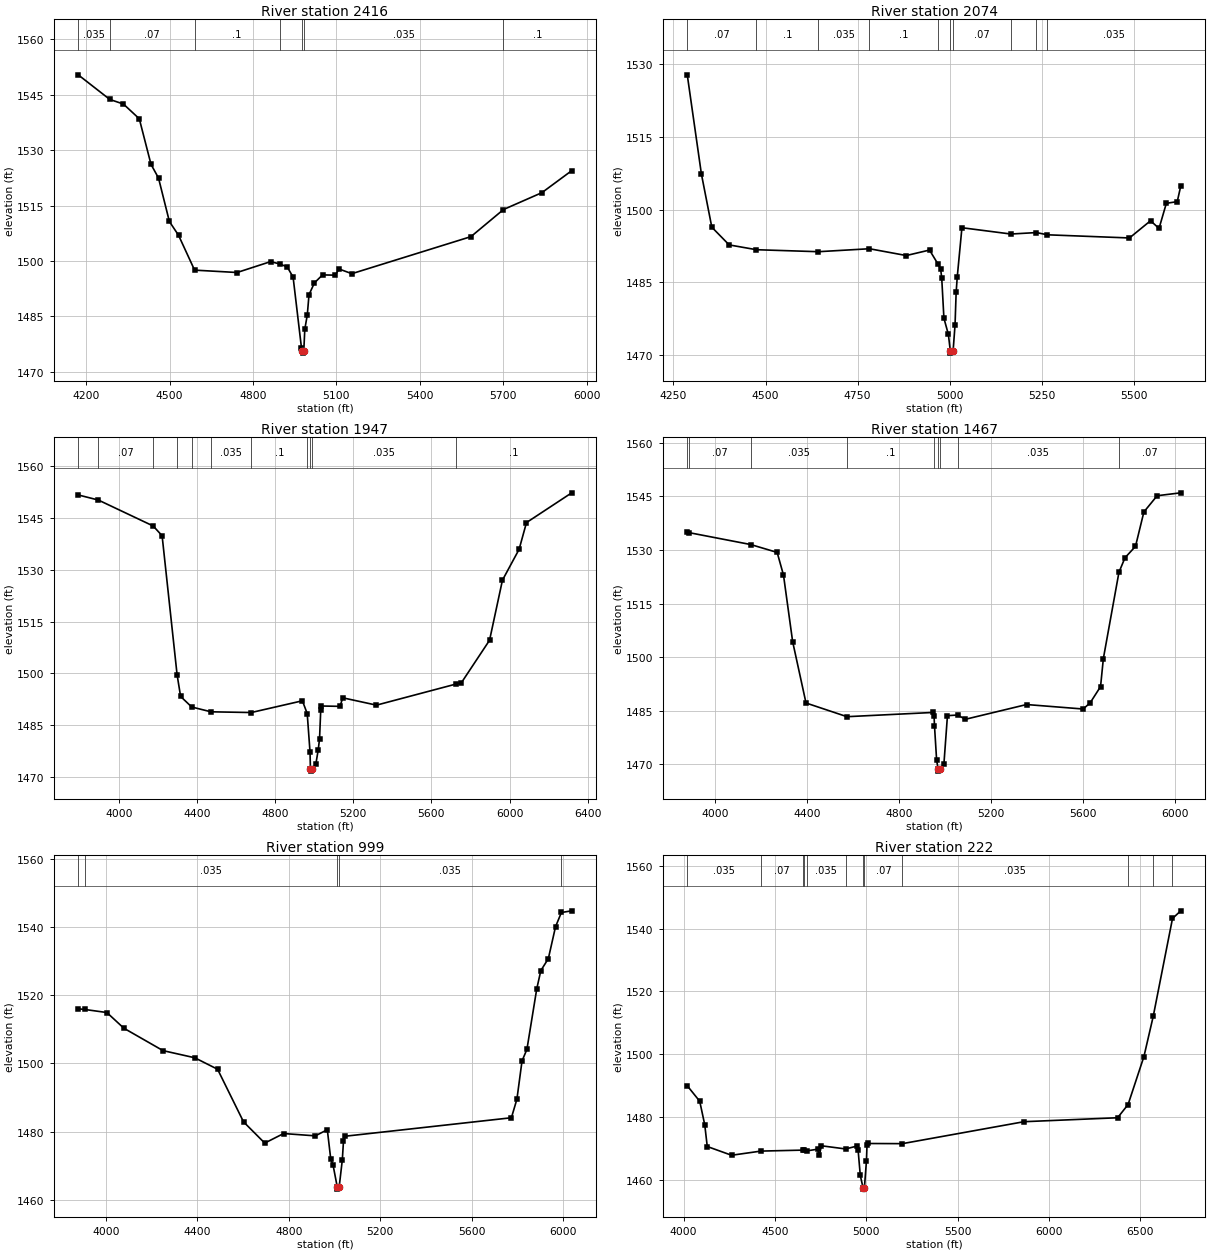
Type RM Length L Ch R = 1,2416,342,342,342
BEGIN DESCRIPTION:
Stream0278 4.0
END DESCRIPTION:
XS GIS Cut Line= 4
      1987398.51     13882270.76      1988225.00     13882325.00
      1988378.06     13882262.36      1988550.69     13881500.32
#Sta/Elev= 30
  4171.3 1550.43  4285.0 1543.76  4333.9 1542.52  4391.0 1538.53  4433.1 1526.19
  4460.1 1522.49  4499.2 1510.72  4532.2 1506.98  4589.9 1497.55  4742.7 1496.91
  4863.0 1499.85  4895.8 1499.24  4923.1 1498.41  4944.2 1495.67  4974.2 1476.58
  4977.9 1475.58  4978.2 1475.08  4982.6 1475.58  4986.3 1481.53  4995.3 1485.45
  5001.4 1490.89  5020.9 1494.10  5050.0 1496.26  5096.2 1496.19  5109.1 1497.87
  5155.5 1496.59  5583.9 1506.62  5700.9 1513.96  5839.0 1518.52  5946.3 1524.48
#Mann=7,-1,0
  4171.3   0.035       0  4285.0    0.07       0  4589.9     0.1       0
  4895.8   0.035       0  4977.9   0.035       0  4982.6   0.035       0
  5700.9     0.1       0
Bank Sta=4977.9,4982.6
Exp/Cntr=0.3,0.1

Type RM Length L Ch R = 1,2074,127,127,127
BEGIN DESCRIPTION:
Mapping XS 3e0f380b
END DESCRIPTION:
XS GIS Cut Line= 3
      1987589.96     13882478.09      1988171.63     13882657.66
      1988900.08     13882588.27
#Sta/Elev= 30
  4287.4 1527.76  4325.8 1507.34  4354.1 1496.38  4401.2 1492.73  4475.3 1491.74
  4643.5 1491.33  4782.3 1491.94  4882.4 1490.54  4945.5 1491.67  4968.0 1488.84
  4975.6 1487.82  4978.6 1485.95  4984.6 1477.63  4996.7 1474.29  5001.9 1470.94
  5002.4 1470.44  5009.6 1470.94  5014.8 1476.25  5017.8 1482.94  5020.8 1486.13
  5033.5 1496.27  5166.6 1494.97  5235.9 1495.27  5265.9 1494.81  5488.6 1494.16
  5545.9 1497.71  5568.9 1496.12  5588.8 1501.30  5618.4 1501.64  5627.9 1504.85
#Mann=10,-1,0
  4287.4    0.07       0  4475.3     0.1       0  4643.5   0.035       0
  4782.3     0.1       0  4968.0    0.07       0  5001.9    0.05       0
  5009.6    0.07       0  5166.6   0.035       0  5235.9    0.07       0
  5265.9   0.035       0
Bank Sta=5001.9,5009.6
Exp/Cntr=0.3,0.1

Type RM Length L Ch R = 1,1947,480,480,480
BEGIN DESCRIPTION:
Stream0278 3.0
END DESCRIPTION:
XS GIS Cut Line= 3
      1987068.74     13882718.35      1988275.00     13882775.00
      1989592.74     13882761.42
#Sta/Elev= 30
  3792.4 1551.69  3895.4 1550.21  4176.1 1542.69  4221.7 1539.87  4298.4 1499.59
  4316.4 1493.30  4373.2 1490.24  4471.7 1488.85  4678.1 1488.64  4939.6 1492.04
  4964.3 1488.34  4978.7 1477.17  4980.8 1472.16  4981.3 1471.66  4988.5 1472.16
  5008.7 1473.79  5020.7 1477.84  5027.4 1481.03  5033.4 1489.27  5036.4 1490.53
  5132.4 1490.43  5145.9 1492.91  5318.7 1490.78  5726.4 1496.90  5753.4 1497.28
  5897.4 1509.58  5963.4 1526.99  6048.7 1535.94  6086.4 1543.68  6317.8 1552.30
#Mann=11,-1,0
  3792.4     0.1       0  3895.4    0.07       0  4176.1   0.035       0
  4298.4    0.07       0  4373.2     0.1       0  4471.7   0.035       0
  4678.1     0.1       0  4964.3   0.035       0  4980.8   0.035       0
  4988.5   0.035       0  5726.4     0.1       0
Bank Sta=4980.8,4988.5
Exp/Cntr=0.3,0.1

Type RM Length L Ch R = 1,1467,468,468,468
BEGIN DESCRIPTION:
Stream0278 2.0
END DESCRIPTION:
XS GIS Cut Line= 3
      1987171.45     13882996.22      1988275.00     13883225.00
      1989282.77     13883058.15
#Sta/Elev= 30
  3878.2 1535.17  3886.9 1534.84  4154.6 1531.52  4269.6 1529.32  4297.2 1522.97
  4337.0 1504.36  4395.2 1487.19  4573.6 1483.36  4946.7 1484.54  4952.8 1483.42
  4954.6 1480.81  4963.8 1471.27  4970.4 1468.63  4970.9 1468.13  4978.1 1468.63
  4995.7 1470.21  5011.0 1483.65  5054.8 1483.82  5089.5 1482.64  5355.5 1486.76
  5601.6 1485.51  5632.0 1487.20  5677.6 1491.78  5689.8 1499.63  5757.7 1523.77
  5784.1 1527.84  5829.7 1531.01  5866.2 1540.64  5924.0 1545.18  6026.7 1545.99
#Mann=9,-1,0
  3878.2     0.1       0  3886.9    0.07       0  4154.6   0.035       0
  4573.6     0.1       0  4954.6    0.07       0  4970.4    0.05       0
  4978.1    0.07       0  5054.8   0.035       0  5757.7    0.07       0
Bank Sta=4970.4,4978.1
Exp/Cntr=0.3,0.1

Type RM Length L Ch R = 1,999,777,777,777
BEGIN DESCRIPTION:
Stream0278 1.0
END DESCRIPTION:
XS GIS Cut Line= 4
      1987275.17     13883329.34      1987809.32     13883601.87
      1988325.00     13883675.00      1989195.82     13883113.21
#Sta/Elev= 30
  3879.4 1515.98  3907.8 1515.79  4004.6 1514.89  4078.7 1510.30  4250.0 1503.72
  4388.6 1501.63  4488.5 1498.26  4601.9 1482.84  4694.6 1476.61  4777.1 1479.41
  4915.8 1478.73  4968.1 1480.53  4983.1 1471.94  4993.1 1470.21  5011.9 1463.61
  5012.4 1463.11  5019.7 1463.61  5033.7 1471.71  5038.7 1477.09  5044.3 1478.61
  5772.7 1484.04  5796.8 1489.50  5819.1 1500.69  5840.5 1504.09  5883.4 1521.81
  5901.2 1527.18  5934.1 1530.69  5965.5 1540.04  5991.1 1544.22  6036.2 1544.71
#Mann=5,-1,0
  3879.4    0.07       0  3907.8   0.035       0  5011.9   0.035       0
  5019.7   0.035       0  5991.1    0.07       0
Bank Sta=5011.9,5019.7
Exp/Cntr=0.3,0.1

Type RM Length L Ch R = 1,222,0,0,0
BEGIN DESCRIPTION:
Stream0278 0.0
END DESCRIPTION:
XS GIS Cut Line= 6
      1987426.16     13884088.12      1987924.18     13884366.13
      1988146.96     13884425.43      1988426.59     13884415.92
      1988819.63     13884154.25      1989269.92     13883099.19
#Sta/Elev= 30
  4020.5 1489.90  4088.7 1484.96  4116.2 1477.45  4129.9 1470.53  4262.9 1467.74
  4423.8 1469.07  4654.7 1469.38  4660.5 1469.45  4676.3 1469.15  4733.2 1469.67
  4742.5 1467.74  4754.9 1470.76  4886.8 1469.75  4949.2 1470.67  4955.2 1469.42
  4967.2 1461.31  4982.0 1457.44  4982.5 1456.94  4989.8 1457.44  5000.9 1465.93
  5003.9 1471.02  5007.1 1471.49  5197.3 1471.44  5862.9 1478.44  6375.0 1479.70
  6432.4 1483.92  6519.0 1499.21  6569.9 1512.02  6675.4 1543.24  6720.5 1545.68
#Mann=12,-1,0
  4020.5   0.035       0  4423.8    0.07       0  4654.7   0.035       0
  4660.5    0.07       0  4676.3   0.035       0  4886.8    0.07       0
  4982.0    0.05       0  4989.8    0.07       0  5197.3   0.035       0
  6432.4     0.1       0  6569.9   0.035       0  6675.4    0.07       0
Bank Sta=4982,4989.8
Exp/Cntr=0.3,0.1

Chan Stop Cuts=-1