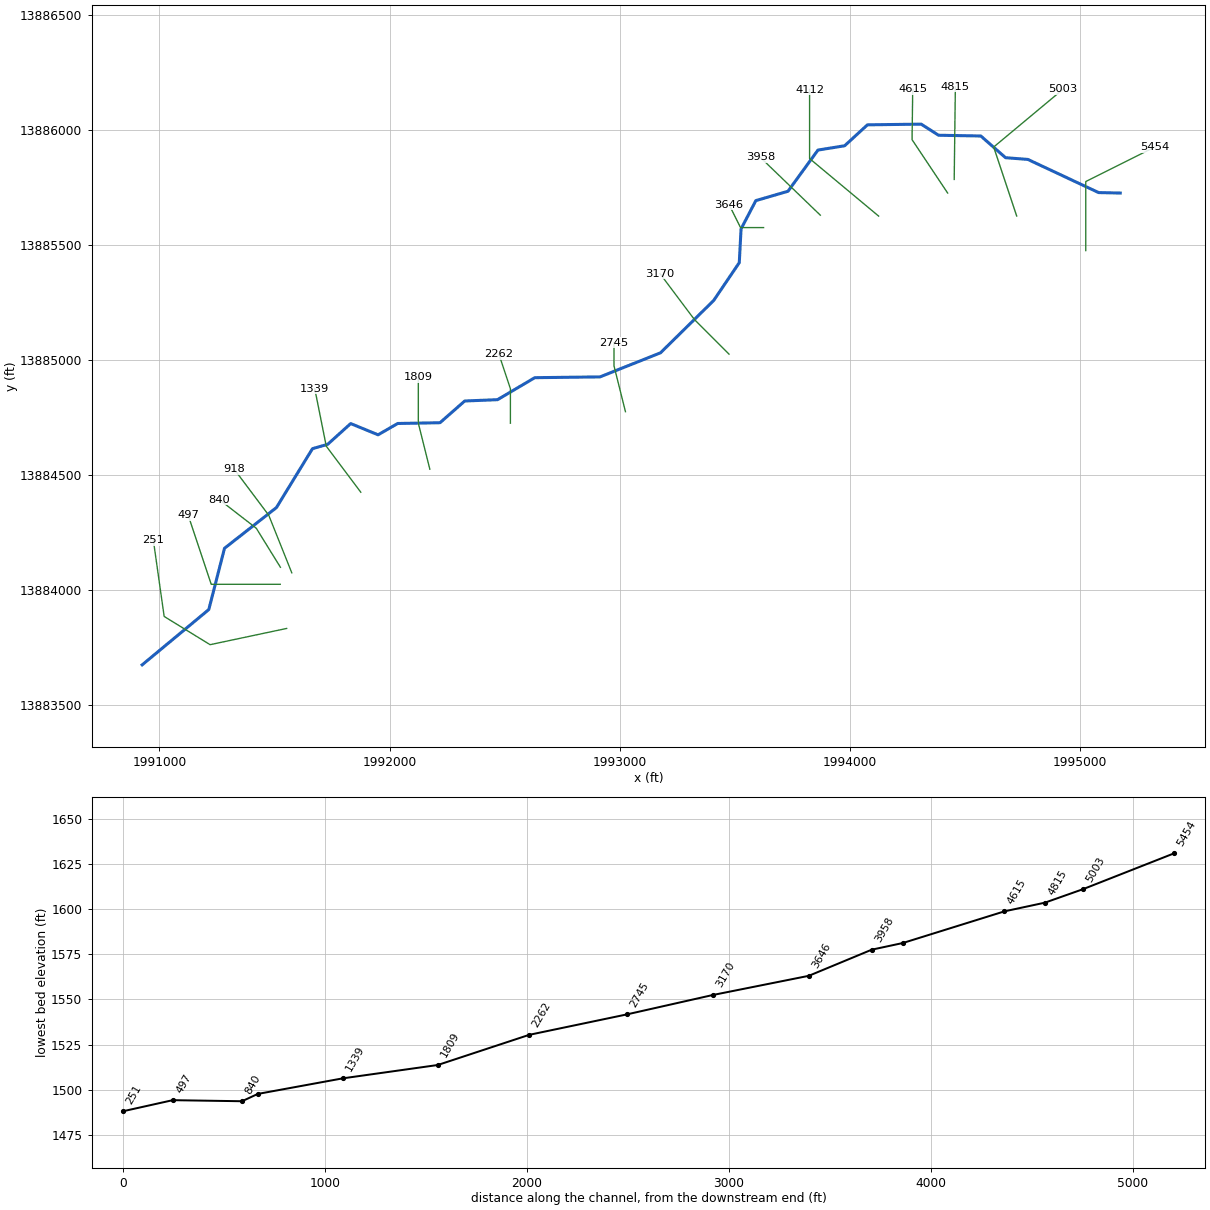
--- Stream0279.prj (project) ---

Proj Title=Stream0279 Base Level Engineering
Current Plan=p01
Default Exp/Contr=0.3,0.1
English Units
Geom File=g01
Flow File=f01
Plan File=p01
BEGIN DESCRIPTION:
Stream0279
END DESCRIPTION:

--- Stream0279.p01 (plan) ---

Plan Title=Multiple Run
Short Identifier=Multiple
Geom File=g01
Flow File=f01
Subcritical Flow
K Sum by GR= 0
Std Step Tol= 0.01
Critical Tol= 0.01
Num of Std Step Trials= 20
Max Error Tol= 0.3
Flow Tol Ratio= 0.001
Split Flow NTrial= 30
Split Flow Tol= 0.02
Split Flow Ratio= 0.02
Log Output Level= 0
Friction Slope Method= 1
Unsteady Friction Slope Method= 2
Unsteady Bridges Friction Slope Method= 1
Parabolic Critical Depth
Global Vel Dist=  1 , 1 , 1
Global Log Level= 0
CheckData=True
Encroach Param= -1, 0, 0, 0
BEGIN DESCRIPTION:
Multiple Run
END DESCRIPTION:

--- Stream0279.f01 (steady flow) ---

Flow Title=Multiple
Number of Profiles=7
Profile Names=10-year,25-year,50-year,1pct_min,100-year,1pct_plu,500-year
River Rch & RM= Stream0279,Reach-1,5454
     650    1082    1485     992    1979    3950    3472
Boundary for River Rch & Prof#=Stream0279,Reach-1,1
Up Type=0
Dn Type=3
Dn Slope=0.005
Boundary for River Rch & Prof#=Stream0279,Reach-1,2
Up Type=0
Dn Type=3
Dn Slope=0.005
Boundary for River Rch & Prof#=Stream0279,Reach-1,3
Up Type=0
Dn Type=3
Dn Slope=0.005
Boundary for River Rch & Prof#=Stream0279,Reach-1,4
Up Type=0
Dn Type=3
Dn Slope=0.005
Boundary for River Rch & Prof#=Stream0279,Reach-1,5
Up Type=0
Dn Type=3
Dn Slope=0.005
Boundary for River Rch & Prof#=Stream0279,Reach-1,6
Up Type=0
Dn Type=3
Dn Slope=0.005
Boundary for River Rch & Prof#=Stream0279,Reach-1,7
Up Type=0
Dn Type=3
Dn Slope=0.005

--- Stream0279.g01 (geometry) ---

Geom Title=Existing Conditions

River Reach=Stream0279,Reach-1
Reach XY= 30
      1995175.00     13885725.00      1995080.87     13885727.10
      1994773.41     13885871.17      1994676.50     13885878.62
      1994569.14     13885972.93      1994385.51     13885976.22
      1994309.78     13886024.48      1994076.47     13886021.45
      1993977.42     13885930.54      1993861.35     13885911.74
      1993731.19     13885732.86      1993591.45     13885692.13
      1993527.25     13885569.07      1993519.52     13885422.56
      1993408.35     13885258.33      1993177.30     13885030.83
      1992914.50     13884926.22      1992630.93     13884922.76
      1992469.07     13884827.25      1992326.47     13884821.44
      1992219.14     13884727.07      1992035.50     13884723.76
      1991950.00     13884674.61      1991831.04     13884723.37
      1991731.02     13884633.19      1991665.00     13884614.35
      1991508.35     13884358.33      1991282.74     13884181.45
      1991214.49     13883915.19      1990925.00     13883675.00

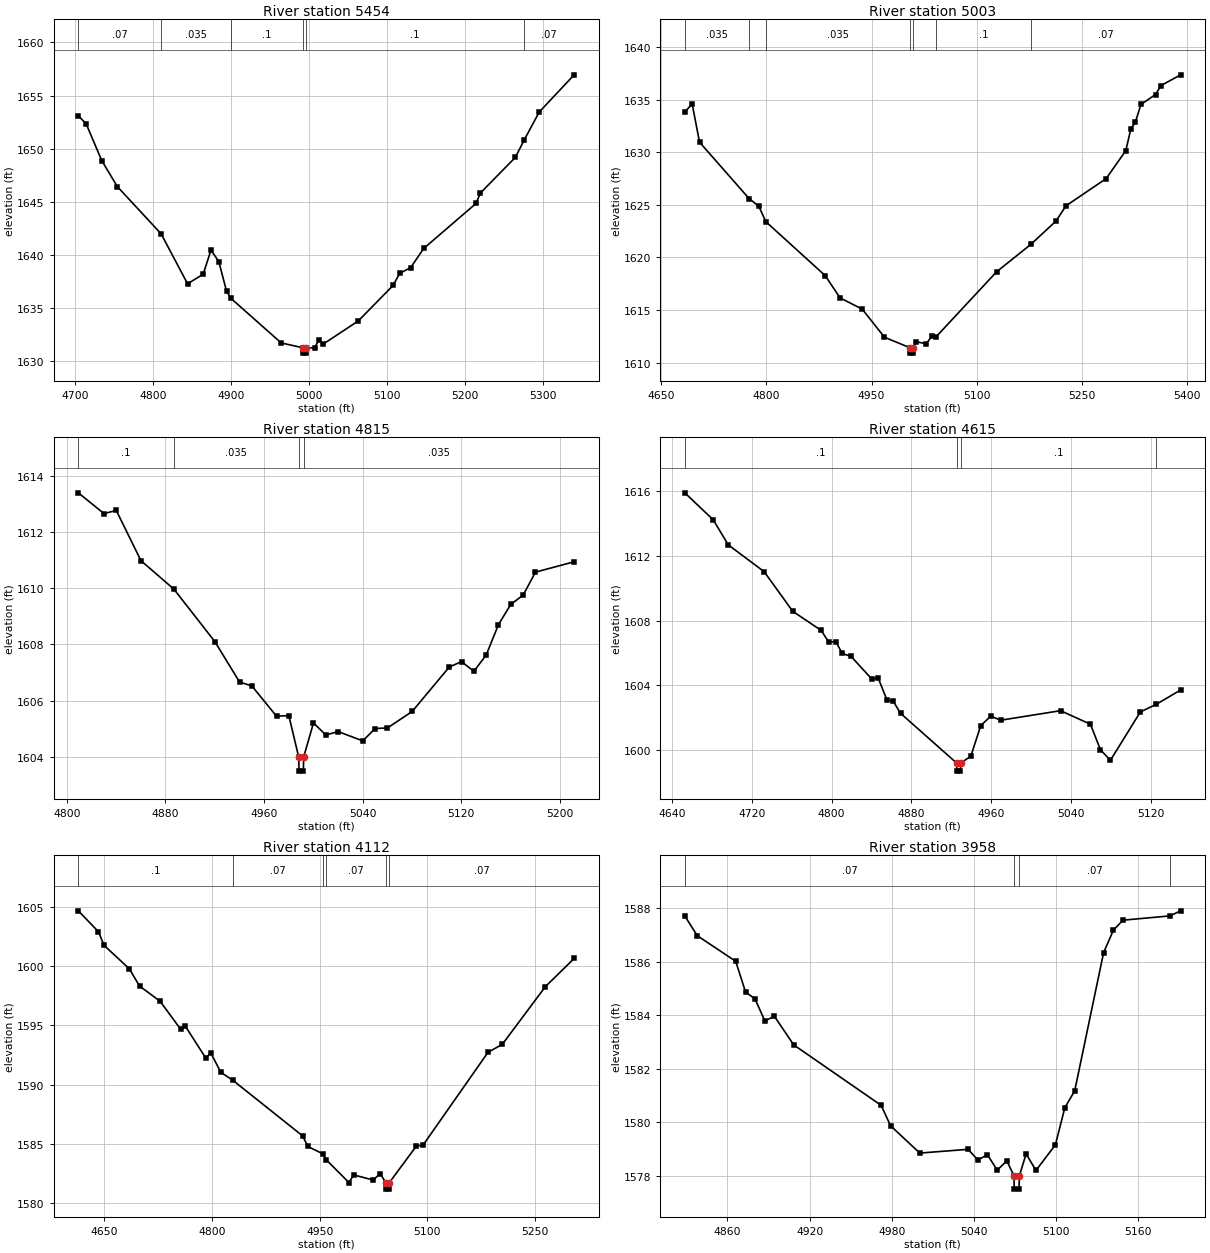
Type RM Length L Ch R = 1,5454,451,451,451
BEGIN DESCRIPTION:
Stream0279 12.0
END DESCRIPTION:
XS GIS Cut Line= 3
      1995025.00     13885474.99      1995025.00     13885775.00
      1995324.98     13885924.99
#Sta/Elev= 30
  4704.6 1653.09  4714.6 1652.34  4734.6 1648.87  4754.6 1646.42  4810.7 1641.97
  4844.6 1637.26  4864.6 1638.17  4874.6 1640.44  4884.6 1639.36  4894.6 1636.55
  4900.3 1635.88  4964.6 1631.69  4992.6 1631.23  4992.9 1630.73  4996.4 1630.73
  4996.6 1631.23  5007.4 1631.23  5013.0 1631.99  5018.6 1631.59  5063.3 1633.76
  5108.0 1637.11  5116.4 1638.25  5130.4 1638.78  5147.2 1640.59  5214.2 1644.83
  5219.8 1645.81  5264.6 1649.17  5276.1 1650.83  5295.3 1653.45  5340.0 1656.95
#Mann=6,-1,0
  4704.6    0.07       0  4810.7   0.035       0  4900.3     0.1       0
  4992.6    0.05       0  4996.6     0.1       0  5276.1    0.07       0
Bank Sta=4992.6,4996.6
Exp/Cntr=0.3,0.1

Type RM Length L Ch R = 1,5003,188,188,188
BEGIN DESCRIPTION:
Stream0279 11.0
END DESCRIPTION:
XS GIS Cut Line= 3
      1994724.99     13885625.04      1994625.00     13885925.00
      1994925.00     13886175.00
#Sta/Elev= 30
  4683.8 1633.83  4694.3 1634.59  4704.8 1630.96  4775.4 1625.60  4789.2 1624.88
  4799.2 1623.41  4884.0 1618.27  4905.1 1616.16  4936.7 1615.09  4968.4 1612.42
  5005.1 1611.41  5005.4 1610.91  5008.9 1610.91  5009.1 1611.41  5013.7 1611.99
  5028.0 1611.80  5035.8 1612.51  5041.4 1612.42  5128.2 1618.64  5177.3 1621.26
  5212.8 1623.46  5227.1 1624.91  5284.4 1627.50  5312.4 1630.16  5319.6 1632.24
  5326.1 1632.88  5333.9 1634.54  5354.7 1635.49  5362.5 1636.34  5390.5 1637.36
#Mann=7,-1,0
  4683.8   0.035       0  4775.4     0.1       0  4799.2   0.035       0
  5005.1   0.035       0  5009.1   0.035       0  5041.4     0.1       0
  5177.3    0.07       0
Bank Sta=5005.1,5009.1
Exp/Cntr=0.3,0.1

Type RM Length L Ch R = 1,4815,200,200,200
BEGIN DESCRIPTION:
Mapping XS 93d7a404
END DESCRIPTION:
XS GIS Cut Line= 2
      1994453.40     13885784.17      1994458.45     13886186.44
#Sta/Elev= 30
  4809.3 1613.41  4830.1 1612.67  4840.1 1612.78  4860.1 1610.99  4886.9 1609.97
  4920.1 1608.10  4940.1 1606.66  4950.1 1606.52  4970.1 1605.44  4980.1 1605.46
  4988.1 1603.98  4988.4 1603.48  4991.9 1603.48  4992.1 1603.98  5000.1 1605.20
  5010.1 1604.77  5020.1 1604.89  5040.1 1604.56  5050.1 1605.00  5060.1 1605.02
  5080.2 1605.61  5110.2 1607.19  5120.2 1607.39  5130.2 1607.04  5140.2 1607.62
  5150.2 1608.71  5160.2 1609.43  5170.2 1609.76  5180.2 1610.58  5211.6 1610.95
#Mann=4,-1,0
  4809.3     0.1       0  4886.9   0.035       0  4988.1   0.035       0
  4992.1   0.035       0
Bank Sta=4988.1,4992.1
Exp/Cntr=0.3,0.1

Type RM Length L Ch R = 1,4615,503,503,503
BEGIN DESCRIPTION:
Stream0279 10.0
END DESCRIPTION:
XS GIS Cut Line= 4
      1994424.99     13885725.01      1994270.32     13885957.01
      1994273.06     13886169.18      1994275.02     13886175.05
#Sta/Elev= 30
  4652.8 1615.91  4681.3 1614.24  4696.4 1612.69  4732.4 1611.03  4761.0 1608.58
  4789.5 1607.40  4797.0 1606.69  4804.5 1606.69  4810.5 1605.97  4819.5 1605.79
  4840.6 1604.37  4846.6 1604.47  4855.6 1603.08  4861.6 1603.04  4869.1 1602.27
  4925.4 1599.19  4925.7 1598.69  4929.2 1598.69  4929.4 1599.19  4939.6 1599.61
  4949.6 1601.51  4959.6 1602.09  4969.6 1601.84  5029.6 1602.43  5059.6 1601.59
  5069.6 1600.01  5079.6 1599.36  5109.6 1602.35  5125.7 1602.83  5150.0 1603.71
#Mann=4,-1,0
  4652.8     0.1       0  4925.4    0.05       0  4929.4     0.1       0
  5125.7    0.07       0
Bank Sta=4925.4,4929.4
Exp/Cntr=0.3,0.1

Type RM Length L Ch R = 1,4112,154,154,154
BEGIN DESCRIPTION:
Stream0279 9.0
END DESCRIPTION:
XS GIS Cut Line= 3
      1994125.02     13885624.98      1993825.00     13885875.00
      1993825.00     13886174.96
#Sta/Elev= 30
  4613.9 1604.66  4641.9 1602.90  4649.7 1601.75  4684.9 1599.77  4699.2 1598.31
  4727.8 1597.03  4756.5 1594.66  4763.0 1594.92  4791.6 1592.22  4798.1 1592.70
  4812.4 1591.03  4828.7 1590.38  4926.3 1585.67  4933.5 1584.78  4954.6 1584.15
  4959.4 1583.64  4990.8 1581.73  4997.3 1582.38  5024.4 1581.95  5034.4 1582.49
  5042.4 1581.68  5042.7 1581.18  5046.2 1581.18  5046.4 1581.68  5084.4 1584.79
  5094.4 1584.93  5184.4 1592.72  5204.4 1593.40  5264.4 1598.27  5304.4 1600.64
#Mann=6,-1,0
  4613.9     0.1       0  4828.7    0.07       0  4954.6     0.1       0
  4959.4    0.07       0  5042.4    0.05       0  5046.4    0.07       0
Bank Sta=5042.4,5046.4
Exp/Cntr=0.3,0.1

Type RM Length L Ch R = 1,3958,312,312,312
BEGIN DESCRIPTION:
Mapping XS b37a6b1c
END DESCRIPTION:
XS GIS Cut Line= 2
      1993871.62     13885628.87      1993610.81     13885880.35
#Sta/Elev= 30
  4828.8 1587.72  4837.9 1586.98  4866.0 1586.02  4873.2 1584.87  4880.1 1584.61
  4887.3 1583.79  4894.3 1583.96  4908.4 1582.89  4972.2 1580.63  4979.2 1579.86
  5000.5 1578.84  5035.8 1578.98  5043.0 1578.58  5049.9 1578.78  5057.1 1578.20
  5064.1 1578.55  5069.3 1577.99  5069.5 1577.49  5073.0 1577.49  5073.3 1577.99
  5078.2 1578.81  5085.4 1578.19  5099.6 1579.15  5106.5 1580.54  5113.7 1581.17
  5134.8 1586.34  5142.0 1587.19  5149.0 1587.56  5183.2 1587.72  5191.1 1587.91
#Mann=4,-1,0
  4828.8    0.07       0  5069.3    0.05       0  5073.3    0.07       0
  5183.2   0.035       0
Bank Sta=5069.3,5073.3
Exp/Cntr=0.3,0.1

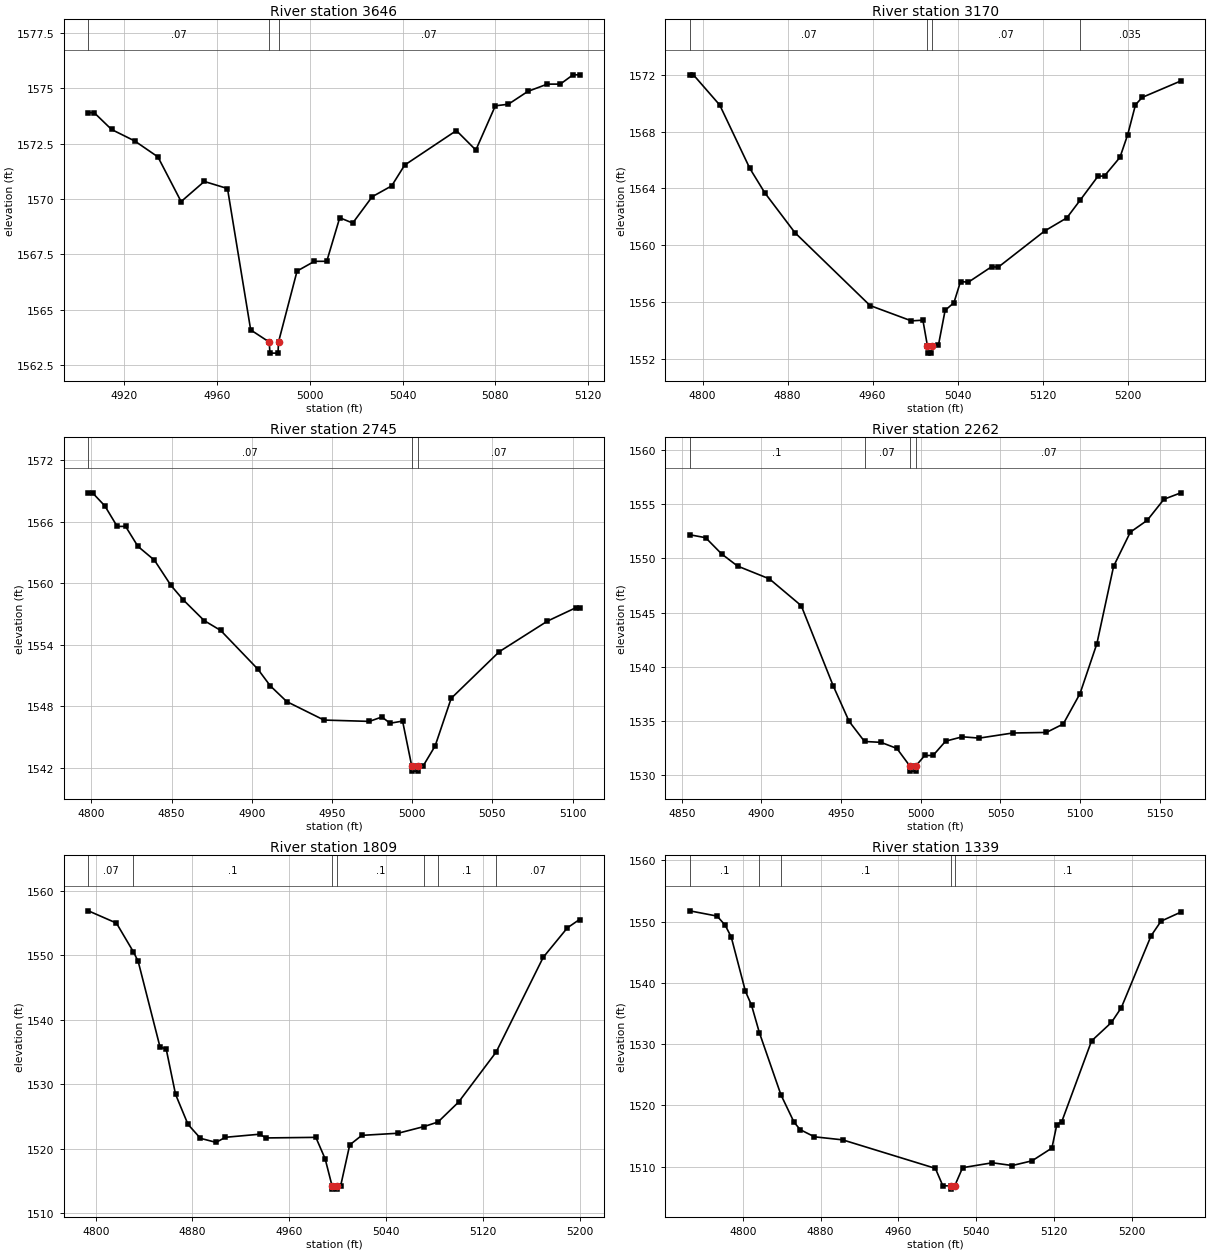
Type RM Length L Ch R = 1,3646,476,476,476
BEGIN DESCRIPTION:
Stream0279 8.0
END DESCRIPTION:
XS GIS Cut Line= 3
      1993625.04     13885575.00      1993525.00     13885575.00
      1993475.02     13885674.96
#Sta/Elev= 30
  4904.5 1573.90  4907.0 1573.90  4914.5 1573.14  4924.5 1572.62  4934.5 1571.90
  4944.5 1569.88  4954.5 1570.79  4964.5 1570.47  4974.5 1564.08  4982.5 1563.53
  4982.8 1563.03  4986.3 1563.03  4986.5 1563.53  4994.5 1566.74  5002.0 1567.18
  5007.3 1567.18  5012.9 1569.15  5018.5 1568.91  5026.9 1570.10  5035.3 1570.59
  5040.9 1571.53  5063.2 1573.09  5071.6 1572.21  5080.0 1574.21  5085.6 1574.28
  5094.0 1574.86  5102.4 1575.19  5108.0 1575.19  5113.5 1575.61  5116.3 1575.61
#Mann=3,-1,0
  4904.5    0.07       0  4982.5    0.05       0  4986.5    0.07       0
Bank Sta=4982.5,4986.5
Exp/Cntr=0.3,0.1

Type RM Length L Ch R = 1,3170,425,425,425
BEGIN DESCRIPTION:
Stream0279 7.0
END DESCRIPTION:
XS GIS Cut Line= 3
      1993475.00     13885025.00      1993325.00     13885175.00
      1993175.02     13885374.97
#Sta/Elev= 30
  4787.9 1571.99  4791.4 1571.99  4816.2 1569.86  4844.5 1565.40  4858.6 1563.68
  4886.9 1560.88  4957.6 1555.75  4996.5 1554.67  5007.3 1554.72  5011.6 1552.90
  5011.8 1552.40  5015.3 1552.40  5015.6 1552.90  5021.9 1552.95  5028.2 1555.41
  5036.5 1555.95  5042.7 1557.44  5050.0 1557.39  5071.9 1558.48  5078.2 1558.45
  5121.9 1561.00  5142.7 1561.92  5155.1 1563.15  5171.9 1564.84  5178.2 1564.88
  5192.7 1566.18  5200.0 1567.78  5207.3 1569.88  5213.6 1570.40  5250.0 1571.56
#Mann=4,-1,0
  4787.9    0.07       0  5011.6    0.05       0  5015.6    0.07       0
  5155.1   0.035       0
Bank Sta=5011.6,5015.6
Exp/Cntr=0.3,0.1

Type RM Length L Ch R = 1,2745,483,483,483
BEGIN DESCRIPTION:
Stream0279 6.0
END DESCRIPTION:
XS GIS Cut Line= 3
      1993025.00     13884774.99      1992975.00     13884975.00
      1992975.00     13885075.03
#Sta/Elev= 30
  4798.1 1568.83  4800.7 1568.83  4808.4 1567.55  4816.1 1565.55  4821.3 1565.56
  4829.0 1563.61  4839.3 1562.26  4849.6 1559.80  4857.4 1558.37  4870.3 1556.37
  4880.6 1555.41  4903.8 1551.63  4911.5 1550.01  4921.8 1548.47  4945.0 1546.67
  4973.3 1546.54  4981.1 1546.97  4986.2 1546.36  4994.0 1546.57  4999.7 1542.19
  4999.9 1541.69  5003.4 1541.69  5003.7 1542.19  5006.8 1542.19  5014.3 1544.15
  5024.3 1548.79  5054.3 1553.34  5084.3 1556.32  5101.8 1557.61  5104.3 1557.61
#Mann=3,-1,0
  4798.1    0.07       0  4999.7    0.05       0  5003.7    0.07       0
Bank Sta=4999.7,5003.7
Exp/Cntr=0.3,0.1

Type RM Length L Ch R = 1,2262,453,453,453
BEGIN DESCRIPTION:
Stream0279 5.0
END DESCRIPTION:
XS GIS Cut Line= 3
      1992525.00     13884724.96      1992525.00     13884875.00
      1992474.99     13885025.04
#Sta/Elev= 30
  4855.0 1552.16  4865.0 1551.89  4875.0 1550.40  4885.0 1549.28  4905.0 1548.10
  4925.0 1545.63  4945.0 1538.27  4955.0 1534.99  4964.7 1533.13  4975.0 1533.05
  4985.0 1532.49  4993.0 1530.90  4993.3 1530.40  4996.8 1530.40  4997.0 1530.90
  5002.5 1531.84  5007.7 1531.84  5015.6 1533.16  5026.1 1533.56  5036.7 1533.44
  5057.7 1533.91  5078.8 1533.96  5089.4 1534.74  5099.9 1537.53  5110.5 1542.13
  5121.0 1549.26  5131.5 1552.40  5142.1 1553.49  5152.6 1555.43  5163.2 1556.02
#Mann=4,-1,0
  4855.0     0.1       0  4964.7    0.07       0  4993.0    0.05       0
  4997.0    0.07       0
Bank Sta=4993,4997
Exp/Cntr=0.3,0.1

Type RM Length L Ch R = 1,1809,470,470,470
BEGIN DESCRIPTION:
Stream0279 4.0
END DESCRIPTION:
XS GIS Cut Line= 3
      1992174.99     13884525.04      1992125.00     13884725.00
      1992125.00     13884924.98
#Sta/Elev= 30
  4793.9 1556.88  4817.1 1554.98  4831.1 1550.53  4835.1 1549.04  4853.1 1535.79
  4858.3 1535.41  4866.0 1528.41  4876.3 1523.75  4886.6 1521.59  4899.5 1520.96
  4907.2 1521.75  4935.6 1522.23  4940.7 1521.65  4982.0 1521.74  4989.7 1518.40
  4995.4 1514.21  4995.7 1513.71  4999.2 1513.71  4999.4 1514.21  5002.5 1514.21
  5010.0 1520.57  5020.0 1522.05  5050.0 1522.38  5071.5 1523.42  5083.0 1524.12
  5100.0 1527.21  5131.1 1534.98  5170.0 1549.67  5190.0 1554.25  5200.0 1555.53
#Mann=7,-1,0
  4793.9    0.07       0  4831.1     0.1       0  4995.4    0.05       0
  4999.4     0.1       0  5071.5    0.07       0  5083.0     0.1       0
  5131.1    0.07       0
Bank Sta=4995.4,4999.4
Exp/Cntr=0.3,0.1

Type RM Length L Ch R = 1,1339,421,421,421
BEGIN DESCRIPTION:
Stream0279 3.0
END DESCRIPTION:
XS GIS Cut Line= 3
      1991875.02     13884424.98      1991725.00     13884625.00
      1991675.00     13884875.02
#Sta/Elev= 30
  4745.5 1551.76  4773.7 1550.90  4782.0 1549.41  4788.2 1547.49  4802.8 1538.63
  4809.1 1536.35  4817.1 1531.90  4839.3 1521.74  4852.8 1517.26  4859.1 1516.05
  4873.7 1514.88  4902.8 1514.38  4998.1 1509.73  5005.7 1506.91  5013.9 1506.84
  5014.2 1506.34  5017.9 1506.84  5026.1 1509.84  5056.7 1510.64  5077.1 1510.19
  5097.5 1510.96  5117.9 1513.04  5123.0 1516.88  5128.1 1517.37  5158.7 1530.53
  5179.1 1533.54  5189.3 1535.96  5219.9 1547.69  5230.1 1550.07  5250.5 1551.55
#Mann=5,-1,0
  4745.5     0.1       0  4817.1    0.07       0  4839.3     0.1       0
  5013.9    0.05       0  5017.9     0.1       0
Bank Sta=5013.9,5017.9
Exp/Cntr=0.3,0.1

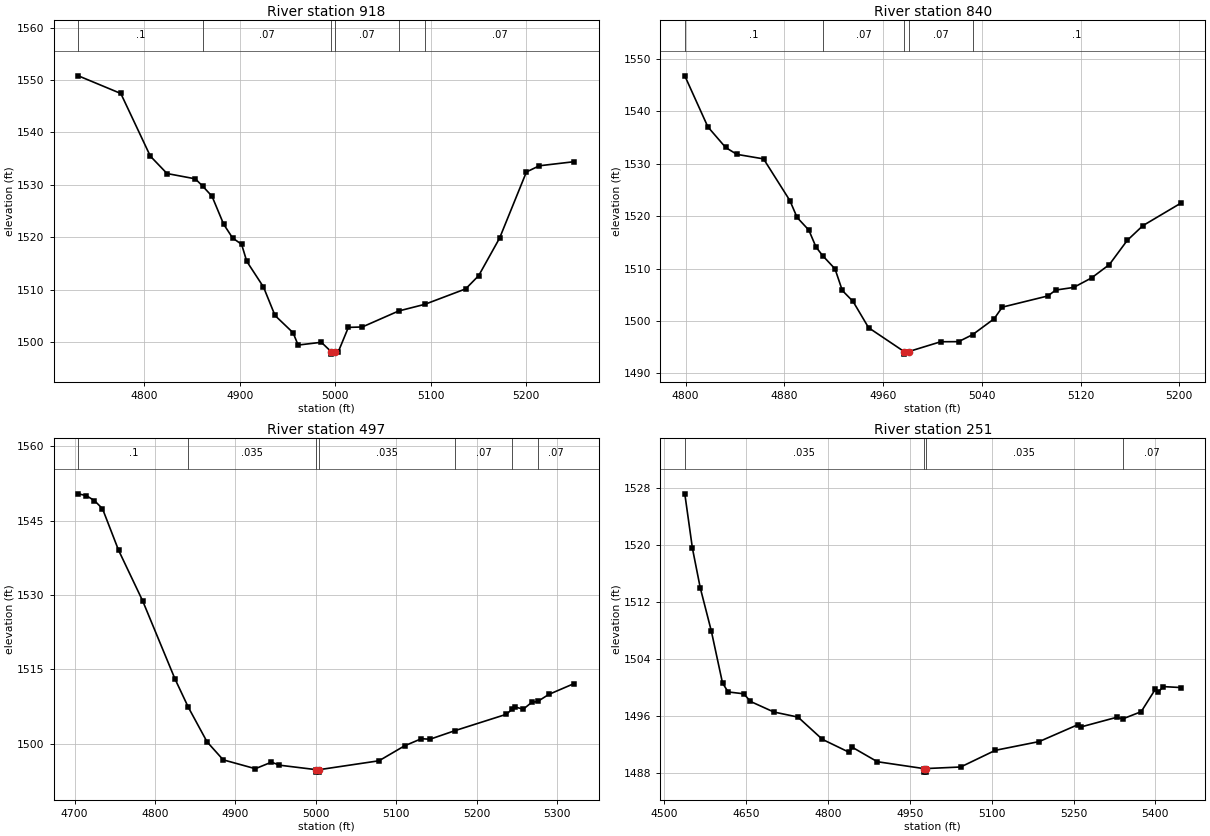
Type RM Length L Ch R = 1,918,78,78,78
BEGIN DESCRIPTION:
Stream0279 2.0
END DESCRIPTION:
XS GIS Cut Line= 3
      1991575.01     13884074.98      1991475.00     13884325.00
      1991324.99     13884525.01
#Sta/Elev= 30
  4731.0 1550.81  4775.5 1547.44  4806.4 1535.49  4823.9 1532.17  4853.5 1531.16
  4861.1 1529.79  4871.0 1527.84  4883.2 1522.50  4892.6 1519.87  4902.0 1518.67
  4907.4 1515.42  4924.9 1510.53  4937.0 1505.09  4955.9 1501.80  4961.2 1499.45
  4985.5 1499.98  4995.6 1498.22  4995.8 1497.72  4999.6 1498.22  5003.4 1498.22
  5013.8 1502.82  5028.4 1502.90  5066.5 1505.95  5093.9 1507.22  5136.7 1510.17
  5150.3 1512.69  5172.2 1519.85  5200.3 1532.47  5213.8 1533.65  5250.3 1534.43
#Mann=6,-1,0
  4731.0     0.1       0  4861.1    0.07       0  4995.6    0.05       0
  4999.6    0.07       0  5066.5     0.1       0  5093.9    0.07       0
Bank Sta=4995.6,4999.6
Exp/Cntr=0.3,0.1

Type RM Length L Ch R = 1,840,343,343,343
BEGIN DESCRIPTION:
Mapping XS 2caafc8d
END DESCRIPTION:
XS GIS Cut Line= 3
      1991525.67     13884099.11      1991420.86     13884268.51
      1991260.81     13884392.56
#Sta/Elev= 30
  4799.4 1546.76  4818.1 1537.02  4832.5 1533.09  4841.6 1531.78  4863.2 1530.92
  4884.5 1522.98  4890.4 1519.74  4899.9 1517.33  4905.7 1514.10  4911.1 1512.46
  4921.1 1509.94  4927.0 1505.82  4935.7 1503.73  4948.3 1498.72  4977.0 1494.18
  4977.3 1493.68  4981.0 1494.18  5006.7 1496.04  5021.2 1496.06  5032.6 1497.40
  5050.0 1500.42  5056.6 1502.64  5093.6 1504.78  5099.9 1505.90  5114.4 1506.40
  5128.9 1508.21  5143.4 1510.77  5157.8 1515.36  5170.5 1518.18  5201.1 1522.45
#Mann=5,-1,0
  4799.4     0.1       0  4911.1    0.07       0  4977.0    0.05       0
  4981.0    0.07       0  5032.6     0.1       0
Bank Sta=4977,4981
Exp/Cntr=0.3,0.1

Type RM Length L Ch R = 1,497,246,246,246
BEGIN DESCRIPTION:
Stream0279 1.0
END DESCRIPTION:
XS GIS Cut Line= 3
      1991524.95     13884025.00      1991225.00     13884025.00
      1991124.99     13884325.02
#Sta/Elev= 30
  4704.7 1550.38  4714.7 1550.01  4724.7 1549.01  4734.7 1547.39  4754.7 1539.01
  4784.7 1528.78  4824.7 1513.10  4841.5 1507.31  4864.7 1500.37  4884.7 1496.75
  4924.7 1494.96  4944.7 1496.28  4954.7 1495.67  5000.2 1494.77  5000.4 1494.27
  5003.9 1494.27  5004.2 1494.77  5078.4 1496.56  5110.1 1499.57  5131.1 1501.01
  5141.7 1500.90  5172.9 1502.64  5236.6 1505.93  5243.7 1506.94  5247.1 1507.43
  5257.6 1506.95  5268.2 1508.34  5275.5 1508.51  5289.3 1509.93  5320.9 1512.13
#Mann=7,-1,0
  4704.7     0.1       0  4841.5   0.035       0  5000.2   0.035       0
  5004.2   0.035       0  5172.9    0.07       0  5243.7   0.035       0
  5275.5    0.07       0
Bank Sta=5000.2,5004.2
Exp/Cntr=0.3,0.1

Type RM Length L Ch R = 1,251,0,0,0
BEGIN DESCRIPTION:
Stream0279 0.0
END DESCRIPTION:
XS GIS Cut Line= 4
      1991552.64     13883833.11      1991220.13     13883762.64
      1991020.62     13883885.23      1990973.56     13884216.54
#Sta/Elev= 30
  4537.5 1527.20  4551.5 1519.55  4565.8 1514.02  4586.2 1507.92  4606.6 1500.66
  4616.9 1499.40  4645.7 1499.14  4657.8 1498.07  4700.5 1496.59  4745.0 1495.87
  4789.6 1492.75  4839.3 1490.91  4844.4 1491.64  4890.4 1489.61  4975.3 1488.65
  4975.6 1488.15  4979.1 1488.15  4979.3 1488.65  5043.1 1488.87  5106.6 1491.21
  5187.1 1492.44  5258.0 1494.81  5263.0 1494.48  5328.9 1495.84  5340.4 1495.63
  5373.9 1496.63  5399.8 1499.77  5404.8 1499.33  5414.3 1500.15  5446.2 1500.02
#Mann=4,-1,0
  4537.5   0.035       0  4975.3   0.035       0  4979.3   0.035       0
  5340.4    0.07       0
Bank Sta=4975.3,4979.3
Exp/Cntr=0.3,0.1

Chan Stop Cuts=-1