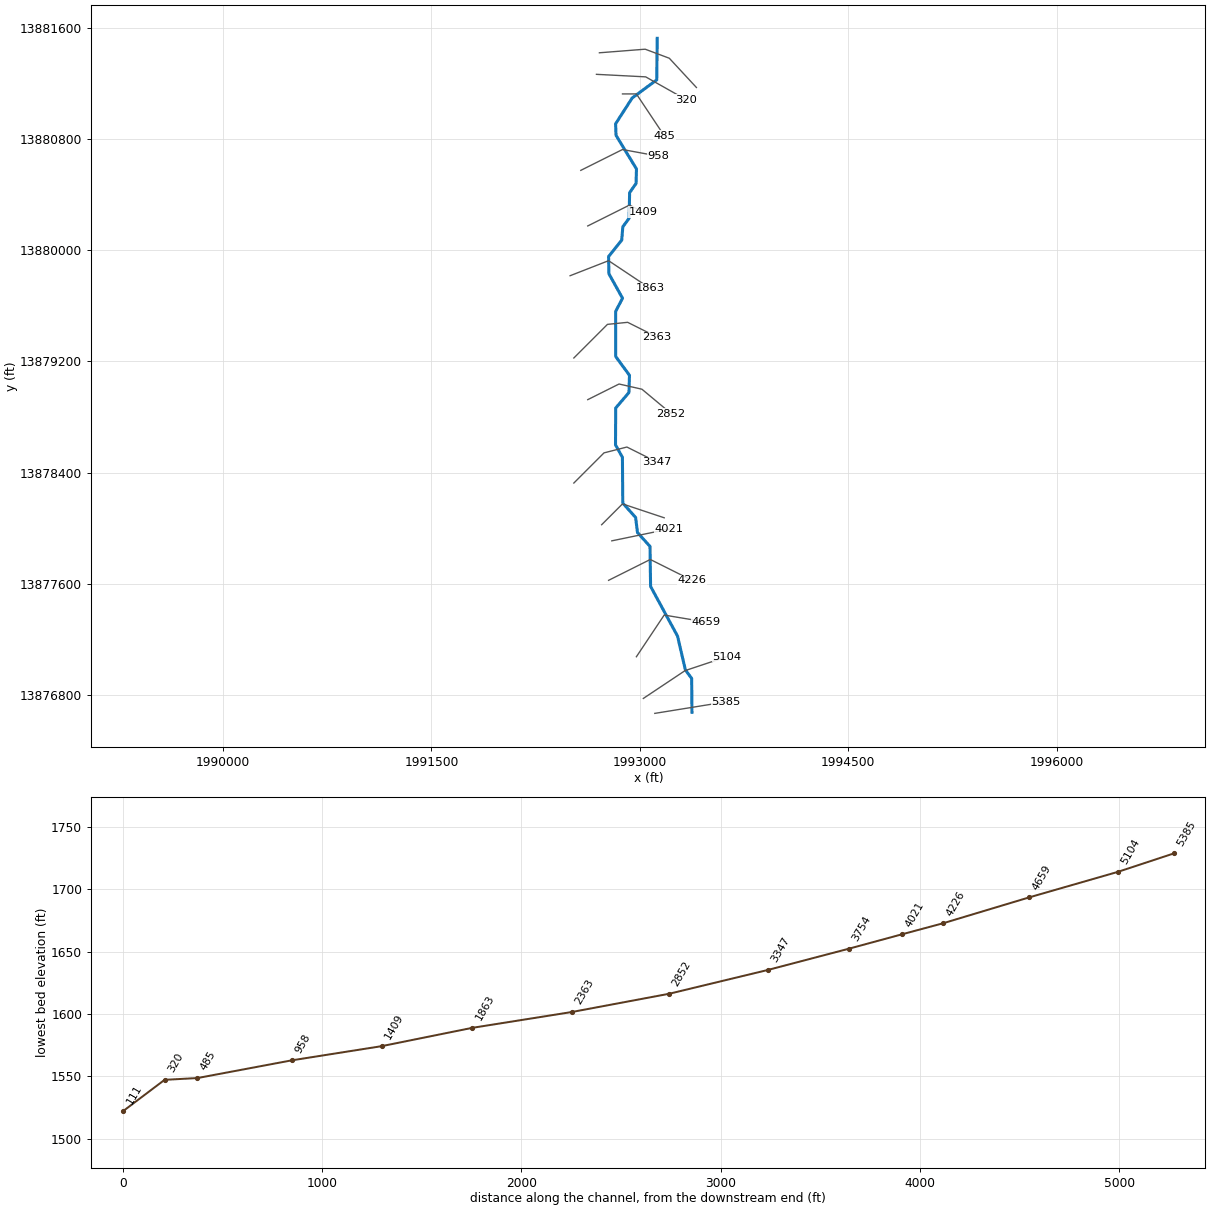
--- Stream0280.prj (project) ---

Proj Title=Stream0280 Base Level Engineering
Current Plan=p01
Default Exp/Contr=0.3,0.1
English Units
Geom File=g01
Flow File=f01
Plan File=p01
BEGIN DESCRIPTION:
Stream0280
END DESCRIPTION:

--- Stream0280.p01 (plan) ---

Plan Title=Multiple Run
Short Identifier=Multiple
Geom File=g01
Flow File=f01
Subcritical Flow
K Sum by GR= 0
Std Step Tol= 0.01
Critical Tol= 0.01
Num of Std Step Trials= 20
Max Error Tol= 0.3
Flow Tol Ratio= 0.001
Split Flow NTrial= 30
Split Flow Tol= 0.02
Split Flow Ratio= 0.02
Log Output Level= 0
Friction Slope Method= 1
Unsteady Friction Slope Method= 2
Unsteady Bridges Friction Slope Method= 1
Parabolic Critical Depth
Global Vel Dist=  1 , 1 , 1
Global Log Level= 0
CheckData=True
Encroach Param= -1, 0, 0, 0
BEGIN DESCRIPTION:
Multiple Run
END DESCRIPTION:

--- Stream0280.f01 (steady flow) ---

Flow Title=Multiple
Number of Profiles=7
Profile Names=10-year,25-year,50-year,1pct_min,100-year,1pct_plu,500-year
River Rch & RM= Stream0280,Reach-1,5385
     155     232     297     187     373     743     574
River Rch & RM= Stream0280,Reach-1,4659
     561     925    1264     841    1679    3349    2920
Boundary for River Rch & Prof#=Stream0280,Reach-1,1
Up Type=0
Dn Type=3
Dn Slope=0.005
Boundary for River Rch & Prof#=Stream0280,Reach-1,2
Up Type=0
Dn Type=3
Dn Slope=0.005
Boundary for River Rch & Prof#=Stream0280,Reach-1,3
Up Type=0
Dn Type=3
Dn Slope=0.005
Boundary for River Rch & Prof#=Stream0280,Reach-1,4
Up Type=0
Dn Type=3
Dn Slope=0.005
Boundary for River Rch & Prof#=Stream0280,Reach-1,5
Up Type=0
Dn Type=3
Dn Slope=0.005
Boundary for River Rch & Prof#=Stream0280,Reach-1,6
Up Type=0
Dn Type=3
Dn Slope=0.005
Boundary for River Rch & Prof#=Stream0280,Reach-1,7
Up Type=0
Dn Type=3
Dn Slope=0.005

--- Stream0280.g01 (geometry) ---

Geom Title=Existing Conditions

River Reach=Stream0280,Reach-1
Reach XY= 30
      1993375.00     13876675.00      1993372.74     13876919.06
      1993327.36     13876980.98      1993271.17     13877223.42
      1993077.24     13877580.93      1993072.93     13877869.14
      1992982.88     13877968.84      1992969.46     13878077.42
      1992877.07     13878180.86      1992874.48     13878509.78
      1992824.80     13878599.92      1992826.06     13878864.56
      1992921.46     13878976.47      1992925.32     13879100.11
      1992826.06     13879235.44      1992825.54     13879559.79
      1992875.29     13879654.83      1992777.23     13879830.93
      1992774.94     13879955.01      1992869.46     13880072.58
      1992877.36     13880169.02      1992922.74     13880230.94
      1992926.22     13880414.49      1992972.75     13880480.94
      1992975.55     13880585.19      1992828.67     13880826.59
      1992825.25     13880909.78      1992944.63     13881095.47
      1993121.47     13881226.45      1993125.00     13881525.00

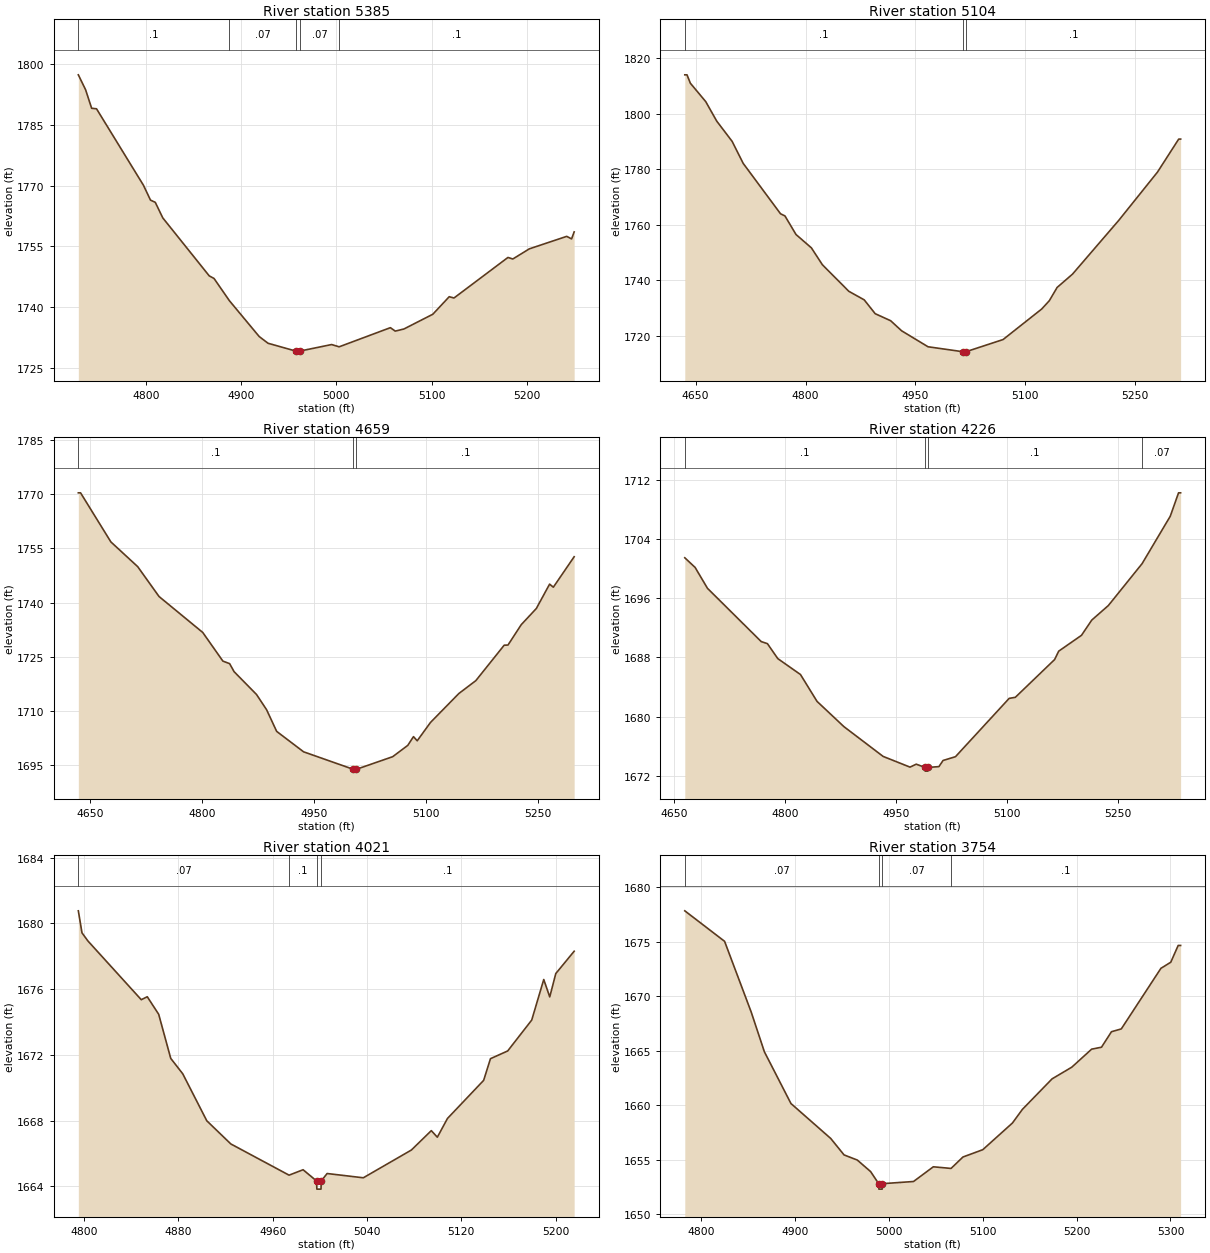
Type RM Length L Ch R = 1,5385,281,281,281
BEGIN DESCRIPTION:
Stream0280 12.0
END DESCRIPTION:
XS GIS Cut Line= 2
      1993107.48     13876667.55      1993621.51     13876750.62
#Sta/Elev= 30
  4729.0 1797.38  4736.6 1793.71  4743.0 1789.11  4748.1 1788.99  4797.4 1770.09
  4804.8 1766.42  4809.8 1765.88  4817.7 1762.03  4866.5 1747.70  4871.5 1747.07
  4887.6 1741.59  4918.9 1732.73  4928.2 1731.06  4957.5 1729.12  4957.7 1728.62
  4961.5 1729.12  4995.0 1730.74  5002.9 1730.18  5056.7 1734.91  5061.8 1734.06
  5070.9 1734.58  5101.3 1738.23  5118.5 1742.56  5123.5 1742.24  5180.2 1752.26
  5185.3 1751.88  5202.6 1754.38  5241.9 1757.47  5247.0 1756.84  5249.7 1758.57
#Mann=5,-1,0
  4729.0     0.1       0  4887.6    0.07       0  4957.5    0.05       0
  4961.5    0.07       0  5002.9     0.1       0
Bank Sta=4957.5,4961.5
Exp/Cntr=0.3,0.1

Type RM Length L Ch R = 1,5104,445,445,445
BEGIN DESCRIPTION:
Stream0280 11.0
END DESCRIPTION:
XS GIS Cut Line= 3
      1993024.97     13876774.98      1993325.00     13876975.00
      1993624.98     13877074.99
#Sta/Elev= 30
  4635.2 1813.98  4638.2 1813.98  4642.8 1810.96  4663.8 1804.33  4678.8 1797.32
  4699.8 1790.04  4714.9 1782.12  4765.9 1763.97  4771.9 1763.21  4787.0 1756.52
  4808.0 1751.71  4823.0 1745.64  4859.1 1736.08  4880.1 1733.00  4895.1 1728.02
  4916.2 1725.49  4931.2 1721.86  4967.2 1716.12  5014.9 1714.33  5015.1 1713.83
  5018.9 1714.33  5069.6 1718.71  5122.3 1729.69  5132.8 1732.70  5143.4 1737.46
  5164.4 1742.25  5227.7 1761.65  5280.4 1778.97  5309.4 1790.86  5312.0 1790.86
#Mann=3,-1,0
  4635.2     0.1       0  5014.9    0.05       0  5018.9     0.1       0
Bank Sta=5014.9,5018.9
Exp/Cntr=0.3,0.1

Type RM Length L Ch R = 1,4659,433,433,433
BEGIN DESCRIPTION:
Stream0280 10.0
END DESCRIPTION:
XS GIS Cut Line= 3
      1992974.99     13877074.98      1993175.00     13877375.00
      1993474.99     13877325.00
#Sta/Elev= 30
  4633.9 1770.37  4636.9 1770.37  4677.5 1756.80  4713.5 1749.95  4742.1 1741.69
  4800.7 1731.75  4827.7 1723.83  4836.7 1723.13  4842.7 1720.91  4872.8 1714.59
  4886.3 1710.38  4899.8 1704.39  4935.9 1698.74  5002.6 1693.90  5002.9 1693.40
  5006.6 1693.90  5055.3 1697.39  5075.6 1700.53  5083.2 1702.94  5088.2 1701.79
  5106.0 1706.86  5144.0 1714.86  5166.8 1718.43  5204.8 1728.23  5209.9 1728.27
  5227.6 1733.89  5247.9 1738.38  5265.7 1745.12  5270.7 1744.27  5298.6 1752.69
#Mann=3,-1,0
  4633.9     0.1       0  5002.6    0.05       0  5006.6     0.1       0
Bank Sta=5002.6,5006.6
Exp/Cntr=0.3,0.1

Type RM Length L Ch R = 1,4226,205,205,205
BEGIN DESCRIPTION:
Stream0280 9.0
END DESCRIPTION:
XS GIS Cut Line= 3
      1992775.00     13877625.00      1993075.00     13877775.00
      1993374.98     13877625.01
#Sta/Elev= 30
  4664.5 1701.46  4678.5 1700.15  4695.2 1697.33  4767.9 1690.13  4776.3 1689.85
  4790.3 1687.83  4821.0 1685.68  4843.4 1682.05  4879.7 1678.64  4932.8 1674.61
  4969.2 1673.16  4977.6 1673.56  4989.5 1673.12  4989.8 1672.62  4993.3 1672.62
  4993.5 1673.12  5008.3 1673.23  5013.9 1674.06  5030.7 1674.57  5103.3 1682.45
  5111.7 1682.60  5164.8 1687.70  5170.4 1688.84  5201.2 1690.98  5215.1 1693.04
  5237.5 1695.00  5283.2 1700.67  5321.3 1707.08  5332.5 1710.24  5335.3 1710.24
#Mann=4,-1,0
  4664.5     0.1       0  4989.5    0.05       0  4993.5     0.1       0
  5283.2    0.07       0
Bank Sta=4989.5,4993.5
Exp/Cntr=0.3,0.1

Type RM Length L Ch R = 1,4021,267,267,267
BEGIN DESCRIPTION:
Mapping XS 8de30222
END DESCRIPTION:
XS GIS Cut Line= 2
      1992798.24     13877909.10      1993210.24     13877994.20
#Sta/Elev= 30
  4795.1 1680.77  4798.2 1679.43  4803.3 1678.93  4848.5 1675.36  4853.6 1675.54
  4863.3 1674.47  4873.5 1671.79  4883.7 1670.85  4904.1 1667.99  4924.5 1666.58
  4973.9 1664.68  4985.8 1665.01  4997.2 1664.33  4997.5 1663.83  5001.0 1663.83
  5001.2 1664.33  5006.2 1664.78  5036.9 1664.52  5077.7 1666.21  5094.6 1667.39
  5099.7 1666.99  5108.3 1668.13  5139.0 1670.45  5144.8 1671.77  5159.4 1672.24
  5179.8 1674.12  5190.0 1676.59  5195.1 1675.53  5200.2 1676.95  5215.8 1678.31
#Mann=4,-1,0
  4795.1    0.07       0  4973.9     0.1       0  4997.2    0.05       0
  5001.2     0.1       0
Bank Sta=4997.2,5001.2
Exp/Cntr=0.3,0.1

Type RM Length L Ch R = 1,3754,407,407,407
BEGIN DESCRIPTION:
Stream0280 8.0
END DESCRIPTION:
XS GIS Cut Line= 3
      1992725.01     13878025.01      1992875.00     13878175.00
      1993174.96     13878075.01
#Sta/Elev= 30
  4782.5 1677.83  4824.9 1675.03  4853.2 1668.55  4867.3 1664.89  4895.6 1660.14
  4938.0 1656.93  4952.2 1655.42  4966.3 1654.95  4980.5 1653.89  4989.1 1652.78
  4989.3 1652.28  4992.8 1652.28  4993.1 1652.78  5026.2 1652.98  5047.3 1654.33
  5066.2 1654.18  5078.9 1655.23  5100.0 1655.90  5131.6 1658.35  5142.2 1659.60
  5173.8 1662.40  5194.9 1663.48  5216.0 1665.13  5226.5 1665.31  5237.1 1666.73
  5247.6 1666.99  5289.8 1672.55  5300.3 1673.11  5308.2 1674.65  5310.8 1674.65
#Mann=4,-1,0
  4782.5    0.07       0  4989.1    0.05       0  4993.1    0.07       0
  5066.2     0.1       0
Bank Sta=4989.1,4993.1
Exp/Cntr=0.3,0.1

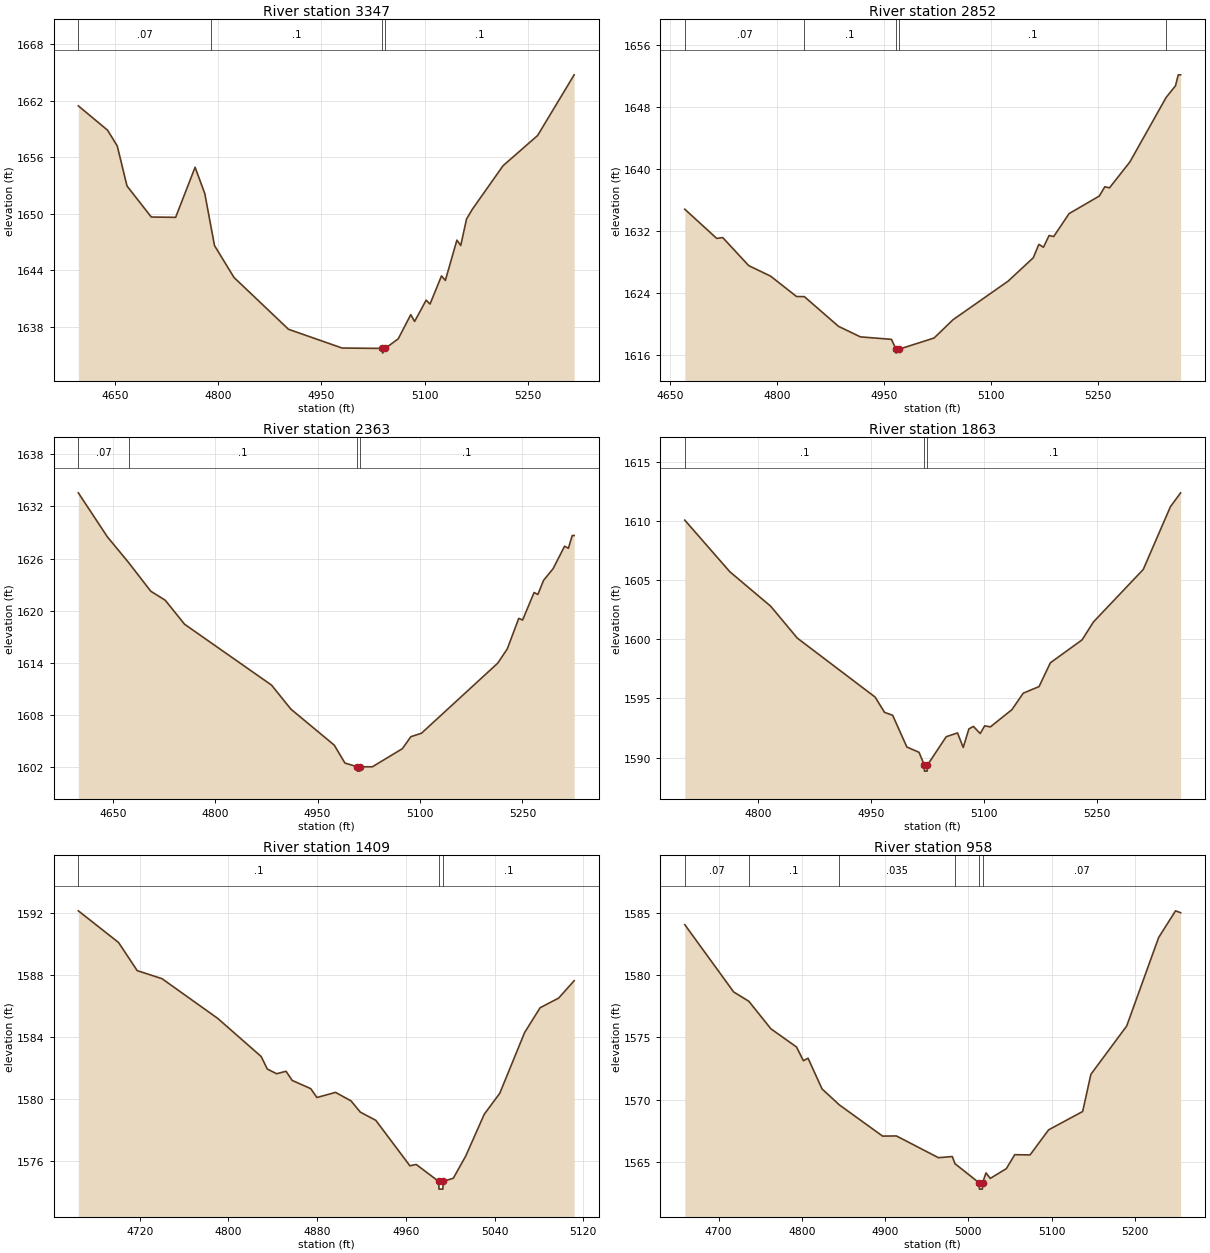
Type RM Length L Ch R = 1,3347,495,495,495
BEGIN DESCRIPTION:
Stream0280 7.0
END DESCRIPTION:
XS GIS Cut Line= 4
      1992524.97     13878324.97      1992742.11     13878542.11
      1992906.79     13878584.10      1993125.00     13878475.00
#Sta/Elev= 30
  4596.6 1661.45  4639.1 1658.87  4653.2 1657.20  4667.4 1652.95  4702.7 1649.66
  4738.1 1649.63  4766.4 1654.94  4780.5 1652.15  4789.8 1648.52  4794.6 1646.64
  4822.9 1643.26  4902.2 1637.76  4980.1 1635.77  5038.8 1635.73  5039.1 1635.23
  5042.8 1635.73  5061.8 1636.75  5080.0 1639.31  5085.6 1638.59  5102.4 1640.85
  5108.0 1640.43  5124.7 1643.42  5130.3 1642.94  5147.1 1647.21  5152.7 1646.64
  5161.1 1649.45  5169.5 1650.48  5214.2 1655.10  5264.5 1658.31  5317.6 1664.74
#Mann=4,-1,0
  4596.6    0.07       0  4789.8     0.1       0  5038.8    0.05       0
  5042.8     0.1       0
Bank Sta=5038.8,5042.8
Exp/Cntr=0.3,0.1

Type RM Length L Ch R = 1,2852,489,489,489
BEGIN DESCRIPTION:
Stream0280 6.0
END DESCRIPTION:
XS GIS Cut Line= 4
      1992625.03     13878925.02      1992850.24     13879037.62
      1993014.74     13879000.22      1993225.01     13878824.99
#Sta/Elev= 30
  4671.0 1634.77  4715.7 1631.00  4724.1 1631.11  4760.4 1627.49  4791.2 1626.12
  4827.5 1623.49  4838.4 1623.48  4886.2 1619.64  4916.9 1618.28  4960.4 1617.96
  4966.7 1616.68  4966.9 1616.18  4970.7 1616.68  5020.0 1618.13  5046.5 1620.49
  5123.7 1625.48  5158.9 1628.50  5166.7 1630.23  5173.2 1629.86  5181.0 1631.37
  5187.5 1631.24  5209.0 1634.20  5251.3 1636.47  5259.1 1637.67  5265.6 1637.53
  5294.2 1640.88  5344.9 1649.21  5358.0 1650.71  5361.9 1652.13  5365.2 1652.13
#Mann=5,-1,0
  4671.0    0.07       0  4838.4     0.1       0  4966.7    0.05       0
  4970.7     0.1       0  5344.9    0.07       0
Bank Sta=4966.7,4970.7
Exp/Cntr=0.3,0.1

Type RM Length L Ch R = 1,2363,500,500,500
BEGIN DESCRIPTION:
Stream0280 5.0
END DESCRIPTION:
XS GIS Cut Line= 4
      1992524.97     13879224.97      1992766.74     13879466.74
      1992912.02     13879481.49      1993125.04     13879374.98
#Sta/Elev= 30
  4599.6 1633.56  4642.1 1628.50  4673.1 1625.55  4705.7 1622.24  4726.9 1621.20
  4755.2 1618.44  4882.5 1611.44  4910.8 1608.68  4974.4 1604.53  4990.0 1602.47
  5008.1 1602.04  5008.4 1601.54  5011.9 1601.54  5012.1 1602.04  5030.2 1602.04
  5074.1 1604.12  5086.5 1605.50  5102.1 1605.90  5213.9 1613.97  5227.8 1615.61
  5244.6 1619.12  5250.2 1618.92  5267.0 1622.09  5272.6 1621.87  5280.9 1623.49
  5294.9 1624.84  5311.7 1627.42  5317.3 1627.18  5322.9 1628.65  5325.7 1628.65
#Mann=4,-1,0
  4599.6    0.07       0  4673.1     0.1       0  5008.1    0.05       0
  5012.1     0.1       0
Bank Sta=5008.1,5012.1
Exp/Cntr=0.3,0.1

Type RM Length L Ch R = 1,1863,454,454,454
BEGIN DESCRIPTION:
Stream0280 4.0
END DESCRIPTION:
XS GIS Cut Line= 3
      1992498.14     13879816.81      1992775.00     13879925.00
      1993075.00     13879725.00
#Sta/Elev= 30
  4703.3 1610.07  4763.0 1605.71  4817.3 1602.79  4852.5 1600.10  4955.8 1595.11
  4968.3 1593.82  4979.1 1593.57  4997.9 1590.89  5014.1 1590.44  5021.1 1589.35
  5021.3 1588.85  5024.8 1588.85  5025.1 1589.35  5050.1 1591.76  5065.1 1592.08
  5072.7 1590.85  5080.2 1592.42  5086.2 1592.63  5095.2 1592.03  5101.2 1592.68
  5108.7 1592.59  5137.3 1594.05  5152.3 1595.44  5173.3 1596.00  5188.3 1598.01
  5230.4 1599.95  5245.4 1601.46  5311.5 1605.90  5347.6 1611.21  5361.1 1612.38
#Mann=3,-1,0
  4703.3     0.1       0  5021.1    0.05       0  5025.1     0.1       0
Bank Sta=5021.1,5025.1
Exp/Cntr=0.3,0.1

Type RM Length L Ch R = 1,1409,451,451,451
BEGIN DESCRIPTION:
Stream0280 3.0
END DESCRIPTION:
XS GIS Cut Line= 3
      1992625.01     13880175.00      1992925.00     13880325.00
      1993024.99     13880275.00
#Sta/Elev= 30
  4664.6 1592.12  4700.9 1590.08  4717.7 1588.27  4740.1 1587.75  4790.4 1585.19
  4829.5 1582.74  4835.1 1581.93  4843.5 1581.63  4851.9 1581.79  4857.5 1581.20
  4874.2 1580.67  4879.8 1580.10  4896.6 1580.43  4910.6 1579.88  4918.9 1579.16
  4932.9 1578.63  4963.7 1575.70  4969.3 1575.79  4989.6 1574.70  4989.9 1574.20
  4993.4 1574.20  4993.6 1574.70  5002.8 1574.90  5014.0 1576.33  5030.7 1579.02
  5044.7 1580.37  5067.1 1584.28  5081.1 1585.88  5097.8 1586.50  5111.8 1587.62
#Mann=3,-1,0
  4664.6     0.1       0  4989.6    0.05       0  4993.6     0.1       0
Bank Sta=4989.6,4993.6
Exp/Cntr=0.3,0.1

Type RM Length L Ch R = 1,958,473,473,473
BEGIN DESCRIPTION:
Stream0280 2.0
END DESCRIPTION:
XS GIS Cut Line= 3
      1992575.00     13880575.00      1992875.00     13880725.00
      1993130.97     13880677.74
#Sta/Elev= 30
  4659.3 1584.03  4718.0 1578.64  4736.3 1577.89  4762.7 1575.69  4793.5 1574.23
  4801.8 1573.13  4807.4 1573.33  4824.2 1570.87  4844.8 1569.60  4896.9 1567.09
  4913.6 1567.10  4964.0 1565.36  4980.7 1565.45  4983.9 1564.88  5013.0 1563.34
  5013.3 1562.84  5016.8 1562.84  5017.0 1563.34  5021.2 1564.14  5026.3 1563.70
  5045.6 1564.48  5055.7 1565.60  5074.1 1565.58  5096.4 1567.59  5137.3 1569.06
  5147.2 1572.04  5190.2 1575.91  5228.6 1583.00  5248.9 1585.14  5255.0 1584.99
#Mann=6,-1,0
  4659.3    0.07       0  4736.3     0.1       0  4844.8   0.035       0
  4983.9    0.07       0  5013.0    0.05       0  5017.0    0.07       0
Bank Sta=5013,5017
Exp/Cntr=0.3,0.1

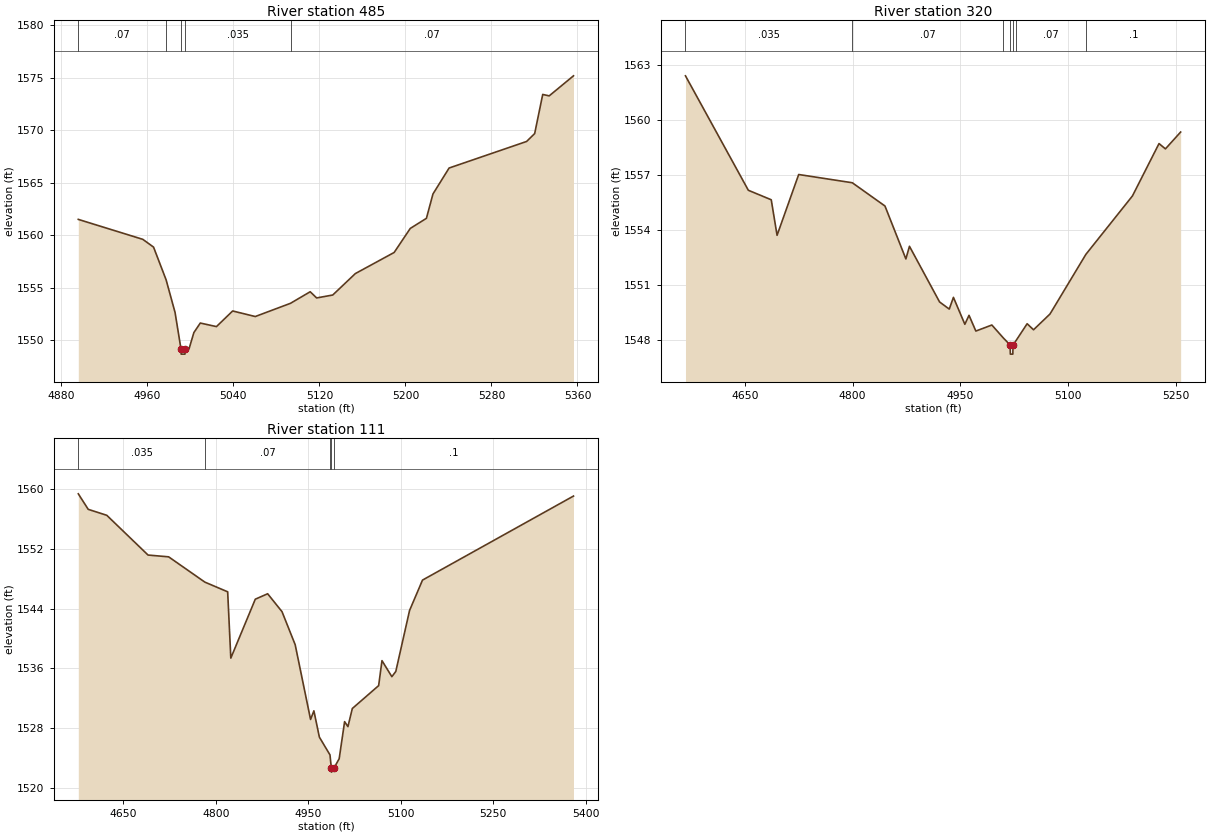
Type RM Length L Ch R = 1,485,165,165,165
BEGIN DESCRIPTION:
Stream0280 1.0
END DESCRIPTION:
XS GIS Cut Line= 3
      1992875.00     13881125.00      1992975.00     13881125.00
      1993175.03     13880824.96
#Sta/Elev= 30
  4895.7 1561.50  4955.7 1559.60  4965.7 1558.86  4977.4 1555.74  4985.7 1552.64
  4991.2 1549.17  4991.4 1548.67  4994.9 1548.67  4995.2 1549.17  4998.7 1549.17
  5003.2 1550.72  5009.2 1551.63  5024.2 1551.29  5039.3 1552.78  5060.3 1552.25
  5093.1 1553.51  5111.4 1554.61  5117.4 1554.02  5132.4 1554.30  5153.4 1556.34
  5189.5 1558.35  5204.5 1560.64  5219.5 1561.60  5225.6 1563.92  5240.6 1566.39
  5312.7 1568.92  5320.2 1569.67  5327.7 1573.40  5333.7 1573.26  5356.3 1575.17
#Mann=5,-1,0
  4895.7    0.07       0  4977.4   0.035       0  4991.2   0.035       0
  4995.2   0.035       0  5093.1    0.07       0
Bank Sta=4991.2,4995.2
Exp/Cntr=0.3,0.1

Type RM Length L Ch R = 1,320,209,209,209
BEGIN DESCRIPTION:
Mapping XS 708552e2
END DESCRIPTION:
XS GIS Cut Line= 3
      1992687.65     13881265.98      1993041.83     13881247.75
      1993333.50     13881083.69
#Sta/Elev= 30
  4567.4 1562.43  4654.9 1556.18  4686.8 1555.66  4694.9 1553.72  4725.0 1557.04
  4799.6 1556.59  4845.1 1555.32  4874.2 1552.43  4879.2 1553.12  4921.1 1550.08
  4934.6 1549.69  4940.4 1550.33  4956.3 1548.86  4962.1 1549.35  4971.6 1548.49
  4993.9 1548.82  5009.7 1548.12  5019.3 1547.73  5019.6 1547.23  5023.1 1547.23
  5023.3 1547.73  5026.9 1547.93  5043.0 1548.89  5051.9 1548.56  5074.8 1549.42
  5124.8 1552.68  5189.6 1555.87  5226.6 1558.73  5235.5 1558.44  5256.7 1559.36
#Mann=7,-1,0
  4567.4   0.035       0  4799.6    0.07       0  5009.7     0.1       0
  5019.3    0.05       0  5023.3     0.1       0  5026.9    0.07       0
  5124.8     0.1       0
Bank Sta=5019.3,5023.3
Exp/Cntr=0.3,0.1

Type RM Length L Ch R = 1,111,0,0,0
BEGIN DESCRIPTION:
Stream0280 0.0
END DESCRIPTION:
XS GIS Cut Line= 4
      1992708.92     13881421.03      1993038.24     13881446.85
      1993211.91     13881381.78      1993407.06     13881171.19
#Sta/Elev= 30
  4577.0 1559.40  4593.1 1557.32  4623.2 1556.52  4690.1 1551.19  4723.5 1550.95
  4782.2 1547.56  4819.2 1546.26  4824.3 1537.37  4864.0 1545.27  4884.0 1546.00
  4907.3 1543.60  4928.7 1539.16  4953.6 1529.14  4959.0 1530.30  4967.9 1526.77
  4985.1 1524.39  4987.3 1522.58  4987.5 1522.08  4991.3 1522.58  5000.0 1523.88
  5008.8 1528.85  5014.2 1528.18  5021.3 1530.61  5064.0 1533.68  5069.4 1537.03
  5085.4 1534.88  5091.8 1535.58  5114.1 1543.75  5135.1 1547.83  5379.9 1559.10
#Mann=5,-1,0
  4577.0   0.035       0  4782.2    0.07       0  4985.1     0.1       0
  4987.3    0.05       0  4991.3     0.1       0
Bank Sta=4987.3,4991.3
Exp/Cntr=0.3,0.1

Chan Stop Cuts=-1