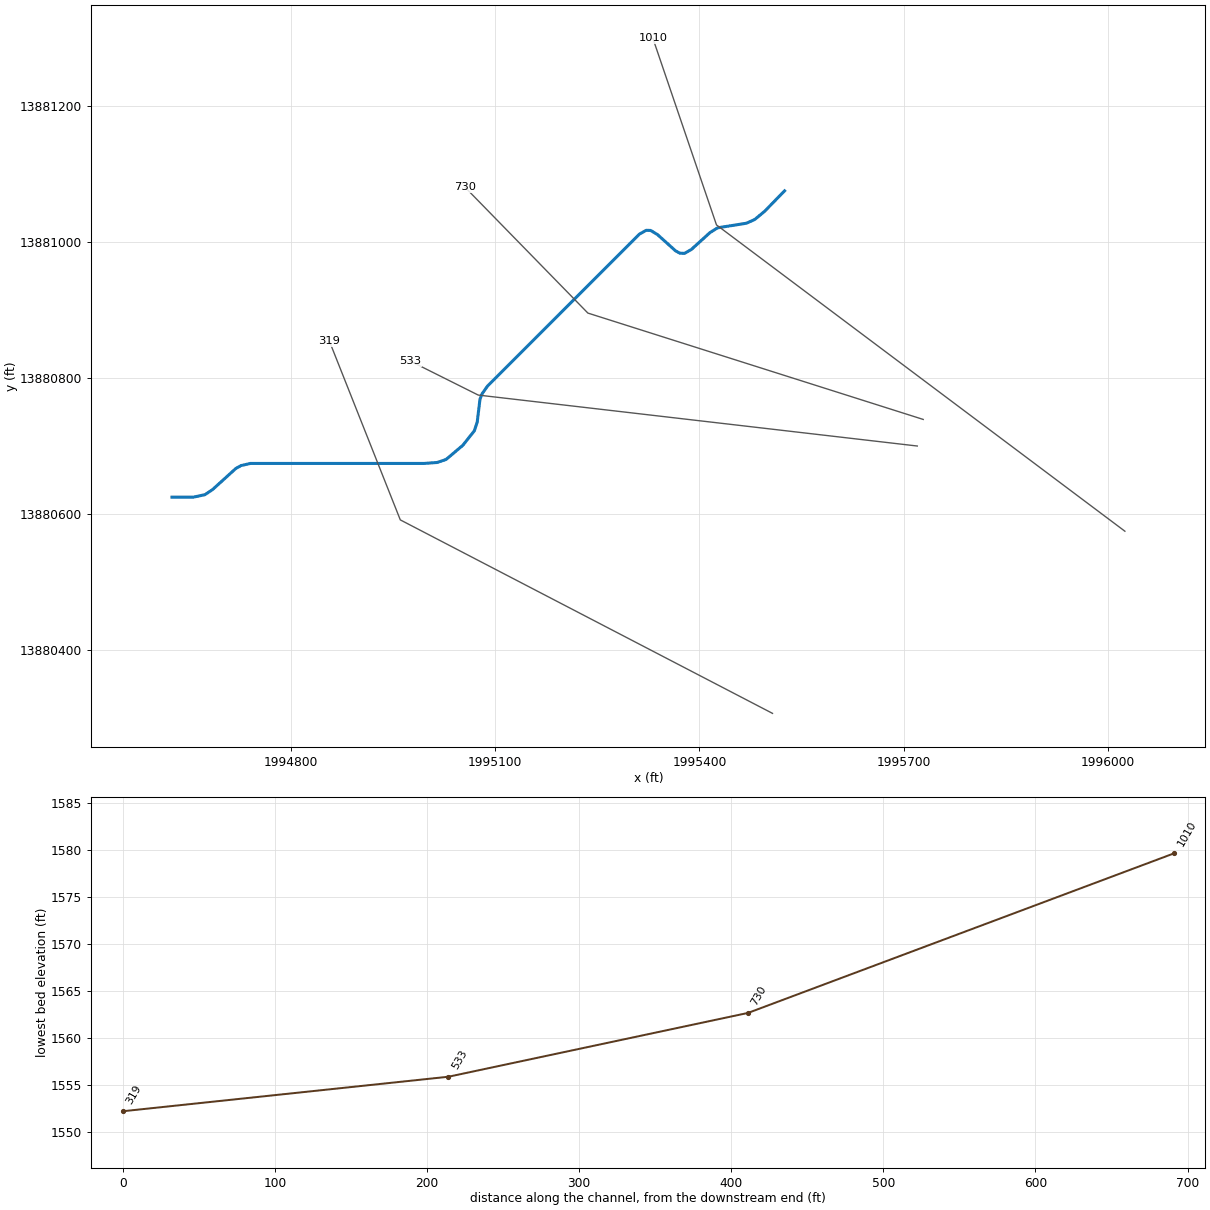
--- Stream0282.prj (project) ---

Proj Title=Stream0282 Base Level Engineering
Current Plan=p01
Default Exp/Contr=0.3,0.1
English Units
Geom File=g01
Flow File=f01
Plan File=p01
BEGIN DESCRIPTION:
Stream0282
END DESCRIPTION:

--- Stream0282.p01 (plan) ---

Plan Title=Multiple Run
Short Identifier=Multiple
Geom File=g01
Flow File=f01
Subcritical Flow
K Sum by GR= 0
Std Step Tol= 0.01
Critical Tol= 0.01
Num of Std Step Trials= 20
Max Error Tol= 0.3
Flow Tol Ratio= 0.001
Split Flow NTrial= 30
Split Flow Tol= 0.02
Split Flow Ratio= 0.02
Log Output Level= 0
Friction Slope Method= 1
Unsteady Friction Slope Method= 2
Unsteady Bridges Friction Slope Method= 1
Parabolic Critical Depth
Global Vel Dist=  1 , 1 , 1
Global Log Level= 0
CheckData=True
Encroach Param= -1, 0, 0, 0
BEGIN DESCRIPTION:
Multiple Run
END DESCRIPTION:

--- Stream0282.f01 (steady flow) ---

Flow Title=Multiple
Number of Profiles=7
Profile Names=10-year,25-year,50-year,1pct_min,100-year,1pct_plu,500-year
River Rch & RM= Stream0282,Reach-1,1010
     341     543     725     472     942    1879    1565
Boundary for River Rch & Prof#=Stream0282,Reach-1,1
Up Type=0
Dn Type=3
Dn Slope=0.005
Boundary for River Rch & Prof#=Stream0282,Reach-1,2
Up Type=0
Dn Type=3
Dn Slope=0.005
Boundary for River Rch & Prof#=Stream0282,Reach-1,3
Up Type=0
Dn Type=3
Dn Slope=0.005
Boundary for River Rch & Prof#=Stream0282,Reach-1,4
Up Type=0
Dn Type=3
Dn Slope=0.005
Boundary for River Rch & Prof#=Stream0282,Reach-1,5
Up Type=0
Dn Type=3
Dn Slope=0.005
Boundary for River Rch & Prof#=Stream0282,Reach-1,6
Up Type=0
Dn Type=3
Dn Slope=0.005
Boundary for River Rch & Prof#=Stream0282,Reach-1,7
Up Type=0
Dn Type=3
Dn Slope=0.005

--- Stream0282.g01 (geometry) ---

Geom Title=Existing Conditions

River Reach=Stream0282,Reach-1
Reach XY= 30
      1995525.00     13881075.00      1995495.91     13881045.13
      1995481.14     13881032.88      1995468.94     13881027.46
      1995426.58     13881020.68      1995415.29     13881013.55
      1995388.19     13880988.97      1995378.23     13880983.23
      1995371.59     13880983.33      1995364.95     13880986.83
      1995338.32     13881010.78      1995328.33     13881016.86
      1995321.66     13881017.01      1995311.66     13881011.36
      1995088.64     13880788.20      1995080.87     13880777.26
      1995077.55     13880768.91      1995073.52     13880735.47
      1995069.26     13880722.42      1995052.19     13880701.03
      1995027.70     13880680.36      1995014.72     13880675.99
      1994995.25     13880674.54      1994740.19     13880674.55
      1994726.49     13880671.40      1994718.84     13880667.11
      1994684.56     13880636.06      1994673.49     13880628.65
      1994656.80     13880625.12      1994625.00     13880625.00

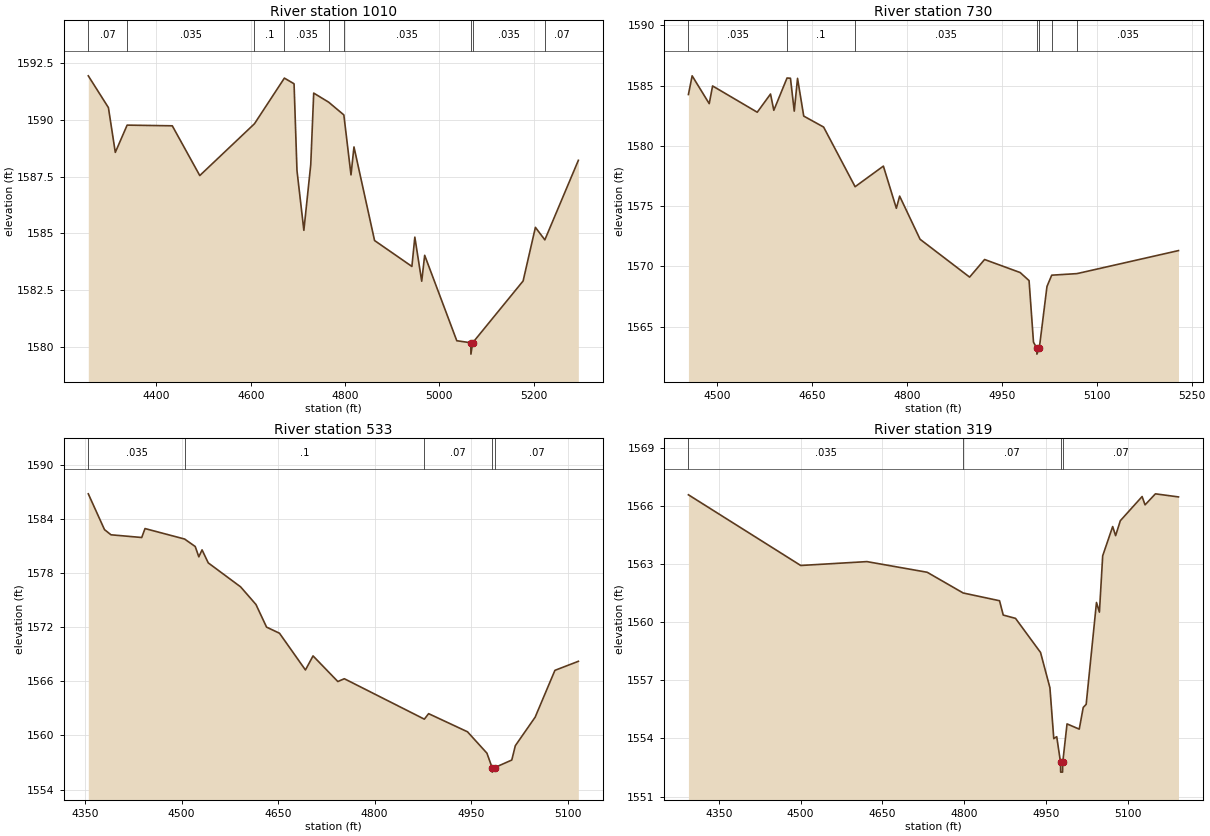
Type RM Length L Ch R = 1,1010,280,280,280
BEGIN DESCRIPTION:
Stream0282 2.0
END DESCRIPTION:
XS GIS Cut Line= 3
      1996025.02     13880574.98      1995425.00     13881025.00
      1995331.57     13881299.09
#Sta/Elev= 30
  4255.5 1591.94  4298.2 1590.54  4312.8 1588.57  4337.9 1589.77  4433.7 1589.74
  4492.0 1587.55  4608.0 1589.83  4671.5 1591.84  4692.0 1591.59  4698.2 1587.77
  4712.8 1585.14  4727.4 1588.03  4733.7 1591.18  4765.4 1590.78  4797.6 1590.22
  4812.8 1587.58  4819.1 1588.81  4862.8 1584.69  4942.0 1583.55  4948.2 1584.84
  4962.8 1582.90  4969.1 1584.04  5037.2 1580.28  5066.9 1580.19  5067.2 1579.69
  5070.9 1580.19  5177.9 1582.91  5204.0 1585.27  5224.0 1584.72  5295.1 1588.22
#Mann=9,-1,0
  4255.5    0.07       0  4337.9   0.035       0  4608.0     0.1       0
  4671.5   0.035       0  4765.4     0.1       0  4797.6   0.035       0
  5066.9   0.035       0  5070.9   0.035       0  5224.0    0.07       0
Bank Sta=5066.9,5070.9
Exp/Cntr=0.3,0.1

Type RM Length L Ch R = 1,730,197,197,197
BEGIN DESCRIPTION:
Stream0282 3.0
END DESCRIPTION:
XS GIS Cut Line= 3
      1995728.74     13880739.20      1995236.08     13880895.46
      1995055.94     13881079.95
#Sta/Elev= 30
  4454.4 1584.26  4460.3 1585.81  4487.3 1583.50  4492.6 1584.97  4563.2 1582.79
  4584.2 1584.30  4589.4 1582.95  4610.3 1585.63  4615.7 1585.61  4621.7 1582.88
  4626.9 1585.60  4636.7 1582.47  4668.1 1581.56  4717.9 1576.61  4762.6 1578.32
  4783.1 1574.82  4788.3 1575.83  4820.6 1572.25  4898.9 1569.11  4922.6 1570.57
  4978.8 1569.49  4992.9 1568.82  4999.9 1563.71  5005.1 1563.22  5005.3 1562.72
  5009.1 1563.22  5021.2 1568.33  5028.7 1569.27  5068.7 1569.40  5229.1 1571.31
#Mann=7,-1,0
  4454.4   0.035       0  4610.3     0.1       0  4717.9   0.035       0
  5005.1   0.035       0  5009.1   0.035       0  5028.7     0.1       0
  5068.7   0.035       0
Bank Sta=5005.1,5009.1
Exp/Cntr=0.3,0.1

Type RM Length L Ch R = 1,533,214,214,214
BEGIN DESCRIPTION:
Stream0282 1.0
END DESCRIPTION:
XS GIS Cut Line= 3
      1995720.04     13880700.14      1995075.00     13880775.00
      1994974.97     13880825.01
#Sta/Elev= 30
  4355.2 1586.77  4380.4 1582.80  4390.5 1582.23  4438.2 1581.93  4443.3 1582.92
  4504.8 1581.76  4521.3 1580.93  4526.9 1579.79  4531.9 1580.56  4541.5 1579.12
  4591.8 1576.46  4615.6 1574.51  4632.1 1572.00  4652.2 1571.32  4692.5 1567.25
  4704.3 1568.81  4742.8 1565.97  4752.9 1566.28  4877.2 1561.80  4883.8 1562.41
  4944.2 1560.40  4974.4 1558.03  4982.4 1556.43  4982.7 1555.93  4986.4 1556.43
  5013.0 1557.27  5018.5 1558.86  5049.3 1562.02  5080.0 1567.21  5116.4 1568.21
#Mann=5,-1,0
  4355.2   0.035       0  4504.8     0.1       0  4877.2    0.07       0
  4982.4    0.05       0  4986.4    0.07       0
Bank Sta=4982.4,4986.4
Exp/Cntr=0.3,0.1

Type RM Length L Ch R = 1,319,0,0,0
BEGIN DESCRIPTION:
Stream0282 0.0
END DESCRIPTION:
XS GIS Cut Line= 3
      1995507.32     13880307.37      1994960.48     13880591.64
      1994856.31     13880854.21
#Sta/Elev= 30
  4294.1 1566.58  4500.1 1562.93  4621.5 1563.13  4732.0 1562.58  4798.0 1561.51
  4864.7 1561.11  4871.5 1560.37  4894.0 1560.20  4939.9 1558.44  4957.1 1556.62
  4964.2 1553.99  4969.6 1554.09  4976.6 1552.76  4976.8 1552.26  4980.3 1552.26
  4980.6 1552.76  4988.5 1554.75  5010.9 1554.48  5018.2 1555.60  5023.6 1555.76
  5042.5 1561.02  5047.9 1560.52  5053.9 1563.43  5072.2 1564.94  5077.6 1564.47
  5086.2 1565.24  5126.2 1566.49  5131.6 1566.06  5150.6 1566.63  5192.9 1566.47
#Mann=4,-1,0
  4294.1   0.035       0  4798.0    0.07       0  4976.6    0.05       0
  4980.6    0.07       0
Bank Sta=4976.6,4980.6
Exp/Cntr=0.3,0.1

Chan Stop Cuts=-1