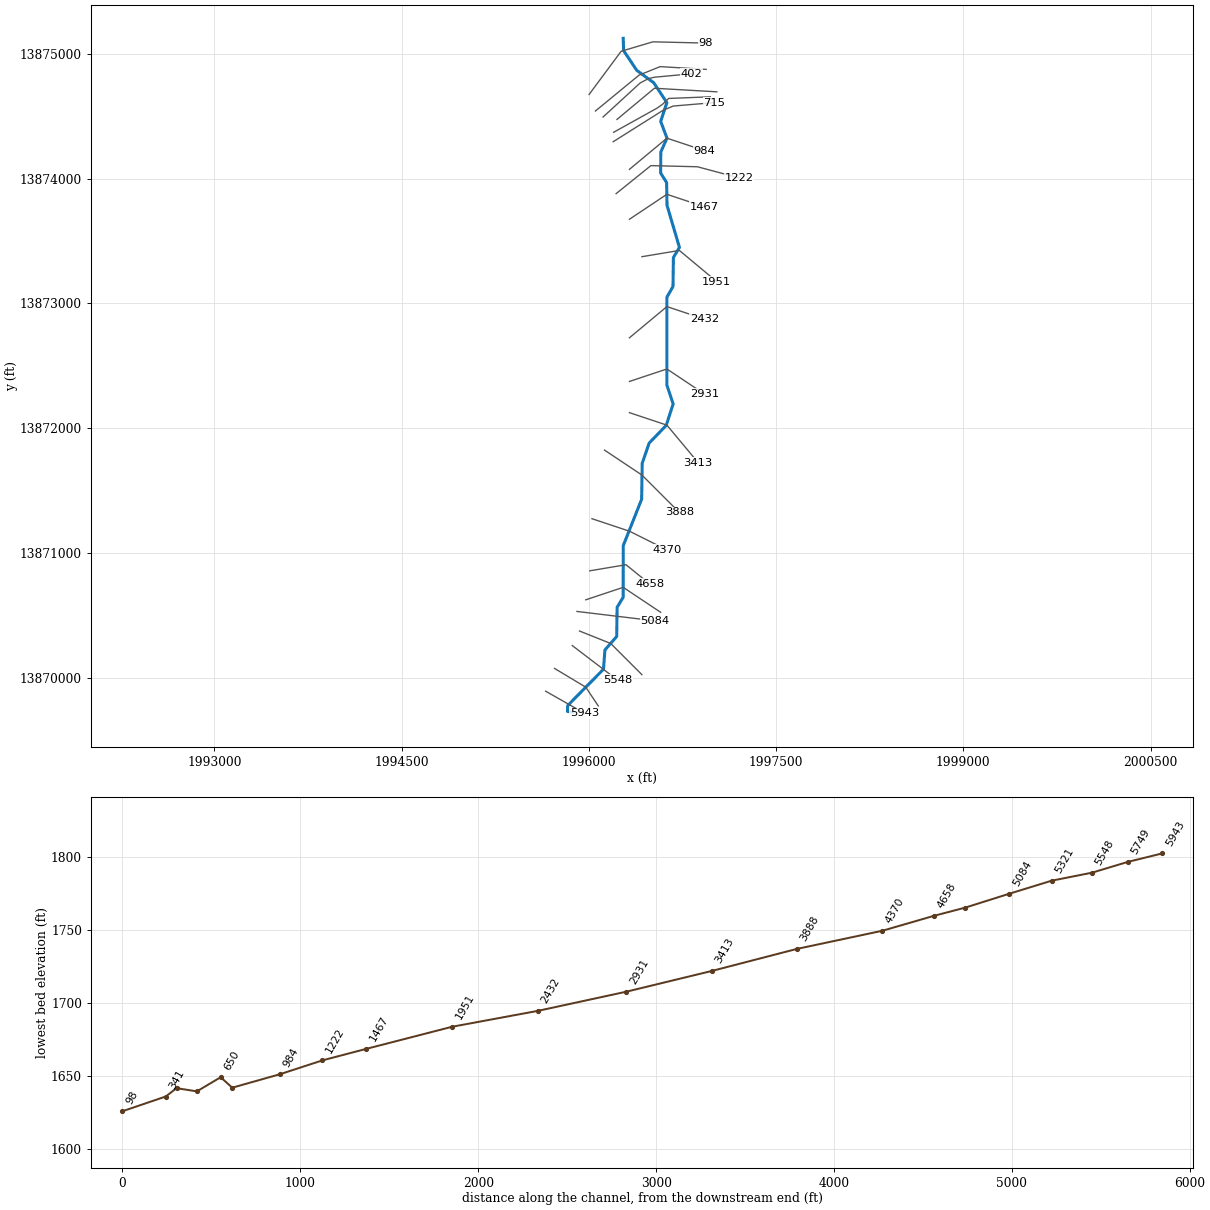
--- Stream0285.prj (project) ---

Proj Title=Stream0285 Base Level Engineering
Current Plan=p01
Default Exp/Contr=0.3,0.1
English Units
Geom File=g01
Flow File=f01
Plan File=p01
BEGIN DESCRIPTION:
Stream0285
END DESCRIPTION:

--- Stream0285.p01 (plan) ---

Plan Title=Multiple Run
Short Identifier=Multiple
Geom File=g01
Flow File=f01
Subcritical Flow
K Sum by GR= 0
Std Step Tol= 0.01
Critical Tol= 0.01
Num of Std Step Trials= 20
Max Error Tol= 0.3
Flow Tol Ratio= 0.001
Split Flow NTrial= 30
Split Flow Tol= 0.02
Split Flow Ratio= 0.02
Log Output Level= 0
Friction Slope Method= 1
Unsteady Friction Slope Method= 2
Unsteady Bridges Friction Slope Method= 1
Parabolic Critical Depth
Global Vel Dist=  1 , 1 , 1
Global Log Level= 0
CheckData=True
Encroach Param= -1, 0, 0, 0
BEGIN DESCRIPTION:
Multiple Run
END DESCRIPTION:

--- Stream0285.f01 (steady flow) ---

Flow Title=Multiple
Number of Profiles=7
Profile Names=10-year,25-year,50-year,1pct_min,100-year,1pct_plu,500-year
River Rch & RM= Stream0285,Reach-1,5943
     141     209     266     166     331     661     503
River Rch & RM= Stream0285,Reach-1,5548
     382     612     820     536    1070    2134    1793
River Rch & RM= Stream0285,Reach-1,2432
     645    1072    1472     983    1961    3913    3439
Boundary for River Rch & Prof#=Stream0285,Reach-1,1
Up Type=0
Dn Type=3
Dn Slope=0.005
Boundary for River Rch & Prof#=Stream0285,Reach-1,2
Up Type=0
Dn Type=3
Dn Slope=0.005
Boundary for River Rch & Prof#=Stream0285,Reach-1,3
Up Type=0
Dn Type=3
Dn Slope=0.005
Boundary for River Rch & Prof#=Stream0285,Reach-1,4
Up Type=0
Dn Type=3
Dn Slope=0.005
Boundary for River Rch & Prof#=Stream0285,Reach-1,5
Up Type=0
Dn Type=3
Dn Slope=0.005
Boundary for River Rch & Prof#=Stream0285,Reach-1,6
Up Type=0
Dn Type=3
Dn Slope=0.005
Boundary for River Rch & Prof#=Stream0285,Reach-1,7
Up Type=0
Dn Type=3
Dn Slope=0.005

--- Stream0285.g01 (geometry) ---

Geom Title=Existing Conditions

River Reach=Stream0285,Reach-1
Reach XY= 30
      1995875.00     13869725.00      1995828.93     13869729.92
      1995829.98     13869777.13      1996117.18     13870068.81
      1996128.56     13870223.53      1996222.93     13870330.86
      1996226.22     13870564.50      1996274.93     13870645.03
      1996275.52     13871059.78      1996422.74     13871430.94
      1996427.26     13871719.06      1996482.86     13871881.17
      1996619.48     13872022.57      1996675.10     13872195.10
      1996625.07     13872345.03      1996624.80     13873050.08
      1996673.78     13873135.50      1996677.29     13873369.07
      1996725.40     13873450.00      1996626.22     13873785.51
      1996622.74     13873969.06      1996575.07     13874045.03
      1996576.22     13874214.50      1996625.81     13874325.00
      1996575.09     13874459.61      1996624.75     13874609.78
      1996519.38     13874769.38      1996383.15     13874868.93
      1996278.39     13875026.41      1996275.00     13875125.00

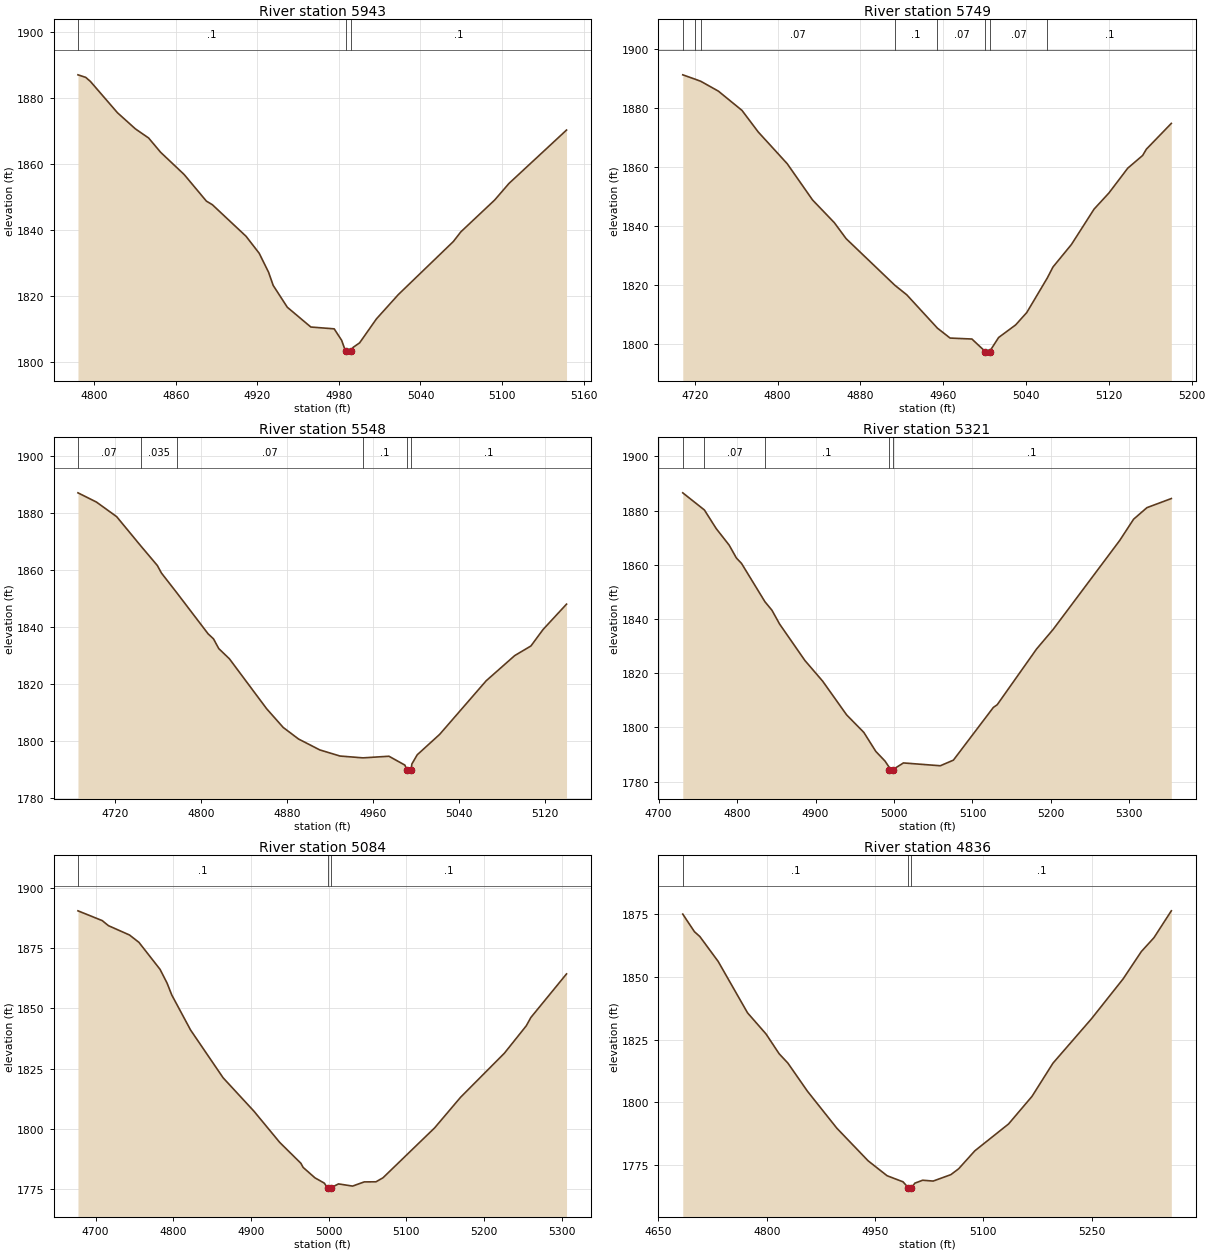
Type RM Length L Ch R = 1,5943,194,194,194
BEGIN DESCRIPTION:
Stream0285 13.0
END DESCRIPTION:
XS GIS Cut Line= 2
      1995653.59     13869892.78      1995966.07     13869714.84
#Sta/Elev= 30
  4787.9 1887.06  4793.6 1886.29  4797.0 1885.08  4817.0 1875.54  4830.2 1870.65
  4839.9 1867.89  4848.8 1863.53  4866.1 1856.79  4882.4 1848.74  4886.8 1847.65
  4911.6 1838.07  4921.3 1832.90  4928.2 1827.14  4931.6 1823.14  4942.0 1816.52
  4959.3 1810.52  4976.5 1809.97  4982.0 1806.47  4984.9 1803.10  4985.1 1802.60
  4988.9 1803.10  4990.3 1804.31  4995.2 1805.72  5007.6 1813.00  5023.7 1820.37
  5064.2 1836.47  5069.7 1839.40  5094.6 1849.06  5105.1 1854.08  5147.5 1870.30
#Mann=3,-1,0
  4787.9     0.1       0  4984.9    0.05       0  4988.9     0.1       0
Bank Sta=4984.9,4988.9
Exp/Cntr=0.3,0.1

Type RM Length L Ch R = 1,5749,201,201,201
BEGIN DESCRIPTION:
Stream0285 12.0
END DESCRIPTION:
XS GIS Cut Line= 3
      1995724.96     13870075.02      1995975.00     13869925.00
      1996075.02     13869774.97
#Sta/Elev= 30
  4708.4 1891.14  4720.1 1889.69  4725.8 1888.95  4742.8 1885.61  4765.6 1879.08
  4781.3 1871.76  4809.3 1861.00  4833.8 1848.69  4854.8 1841.01  4866.2 1835.58
  4913.2 1819.80  4924.8 1816.54  4954.4 1805.23  4966.6 1801.88  4987.7 1801.55
  5000.7 1797.27  5000.9 1796.77  5004.7 1797.27  5013.5 1802.07  5029.9 1806.33
  5040.7 1810.55  5060.5 1822.25  5066.0 1825.98  5083.8 1833.60  5105.7 1845.61
  5120.1 1851.10  5138.2 1859.48  5152.6 1863.80  5156.2 1865.93  5180.3 1874.67
#Mann=8,-1,0
  4708.4     0.1       0  4720.1   0.035       0  4725.8    0.07       0
  4913.2     0.1       0  4954.4    0.07       0  5000.7    0.05       0
  5004.7    0.07       0  5060.5     0.1       0
Bank Sta=5000.7,5004.7
Exp/Cntr=0.3,0.1

Type RM Length L Ch R = 1,5548,227,227,227
BEGIN DESCRIPTION:
Mapping XS 75d22c69
END DESCRIPTION:
XS GIS Cut Line= 2
      1995866.86     13870258.51      1996227.84     13869982.84
#Sta/Elev= 30
  4685.9 1886.94  4703.1 1883.70  4721.9 1878.58  4744.1 1868.43  4759.7 1861.46
  4763.5 1858.83  4777.6 1852.00  4806.9 1837.51  4811.9 1835.76  4816.8 1832.34
  4826.7 1828.76  4861.3 1811.26  4876.7 1804.70  4891.0 1800.64  4910.7 1796.83
  4929.5 1794.68  4950.9 1794.04  4975.0 1794.61  4989.8 1791.51  4991.7 1789.89
  4992.0 1789.39  4995.7 1789.89  4996.3 1791.88  5001.3 1795.12  5022.2 1802.29
  5065.4 1821.06  5091.9 1829.88  5107.0 1833.26  5118.3 1839.04  5140.1 1847.92
#Mann=6,-1,0
  4685.9    0.07       0  4744.1   0.035       0  4777.6    0.07       0
  4950.9     0.1       0  4991.7    0.05       0  4995.7     0.1       0
Bank Sta=4991.7,4995.7
Exp/Cntr=0.3,0.1

Type RM Length L Ch R = 1,5321,237,237,237
BEGIN DESCRIPTION:
Stream0285 11.0
END DESCRIPTION:
XS GIS Cut Line= 3
      1995924.97     13870375.01      1996175.00     13870275.00
      1996424.97     13870025.03
#Sta/Elev= 30
  4730.7 1886.52  4758.3 1880.19  4773.3 1873.35  4789.9 1867.21  4799.1 1862.47
  4805.6 1860.49  4835.5 1846.34  4844.4 1843.22  4854.1 1838.15  4886.4 1824.69
  4909.0 1817.08  4939.6 1804.63  4961.5 1798.18  4976.8 1791.16  4988.4 1787.64
  4993.8 1785.34  4994.2 1784.39  4994.5 1783.89  4998.2 1784.39  5012.0 1786.91
  5059.0 1785.87  5075.7 1787.94  5126.6 1807.37  5131.5 1808.36  5181.7 1828.92
  5202.9 1836.17  5287.8 1868.99  5305.4 1876.79  5322.4 1881.05  5353.5 1884.41
#Mann=5,-1,0
  4730.7     0.1       0  4758.3    0.07       0  4835.5     0.1       0
  4994.2    0.05       0  4998.2     0.1       0
Bank Sta=4994.2,4998.2
Exp/Cntr=0.3,0.1

Type RM Length L Ch R = 1,5084,248,248,248
BEGIN DESCRIPTION:
Mapping XS 95ad706b
END DESCRIPTION:
XS GIS Cut Line= 2
      1995904.54     13870531.74      1996529.04     13870456.64
#Sta/Elev= 30
  4677.4 1890.47  4708.6 1886.42  4716.6 1884.32  4743.8 1880.43  4755.9 1877.39
  4783.1 1866.18  4792.1 1860.49  4798.2 1855.53  4822.4 1841.01  4864.3 1821.18
  4904.0 1807.32  4937.2 1794.37  4964.4 1785.72  4967.3 1784.01  4982.5 1779.69
  4994.6 1777.48  4998.7 1775.50  4998.9 1775.00  5002.7 1775.50  5012.8 1777.17
  5030.9 1776.26  5046.0 1778.00  5061.1 1778.04  5070.2 1779.73  5136.6 1800.42
  5170.0 1813.11  5226.4 1831.40  5254.5 1842.73  5260.5 1846.22  5306.4 1864.30
#Mann=3,-1,0
  4677.4     0.1       0  4998.7    0.05       0  5002.7     0.1       0
Bank Sta=4998.7,5002.7
Exp/Cntr=0.3,0.1

Type RM Length L Ch R = 1,4836,178,178,178
BEGIN DESCRIPTION:
Stream0285 10.0
END DESCRIPTION:
XS GIS Cut Line= 3
      1995975.03     13870625.01      1996275.00     13870725.00
      1996574.96     13870525.03
#Sta/Elev= 30
  4683.7 1874.99  4699.9 1867.98  4707.4 1866.05  4732.7 1856.16  4773.4 1835.68
  4799.1 1827.23  4817.2 1819.37  4829.3 1815.66  4856.4 1804.45  4897.1 1789.73
  4940.5 1776.72  4966.7 1770.80  4988.8 1768.37  4996.3 1765.96  4996.6 1765.46
  5000.3 1765.96  5005.2 1767.84  5016.0 1769.00  5030.5 1768.67  5055.0 1771.22
  5065.8 1773.56  5088.2 1780.71  5135.0 1791.42  5167.5 1802.43  5196.4 1815.60
  5249.7 1833.27  5293.7 1849.22  5318.9 1860.09  5336.3 1865.58  5360.4 1876.30
#Mann=3,-1,0
  4683.7     0.1       0  4996.3    0.05       0  5000.3     0.1       0
Bank Sta=4996.3,5000.3
Exp/Cntr=0.3,0.1

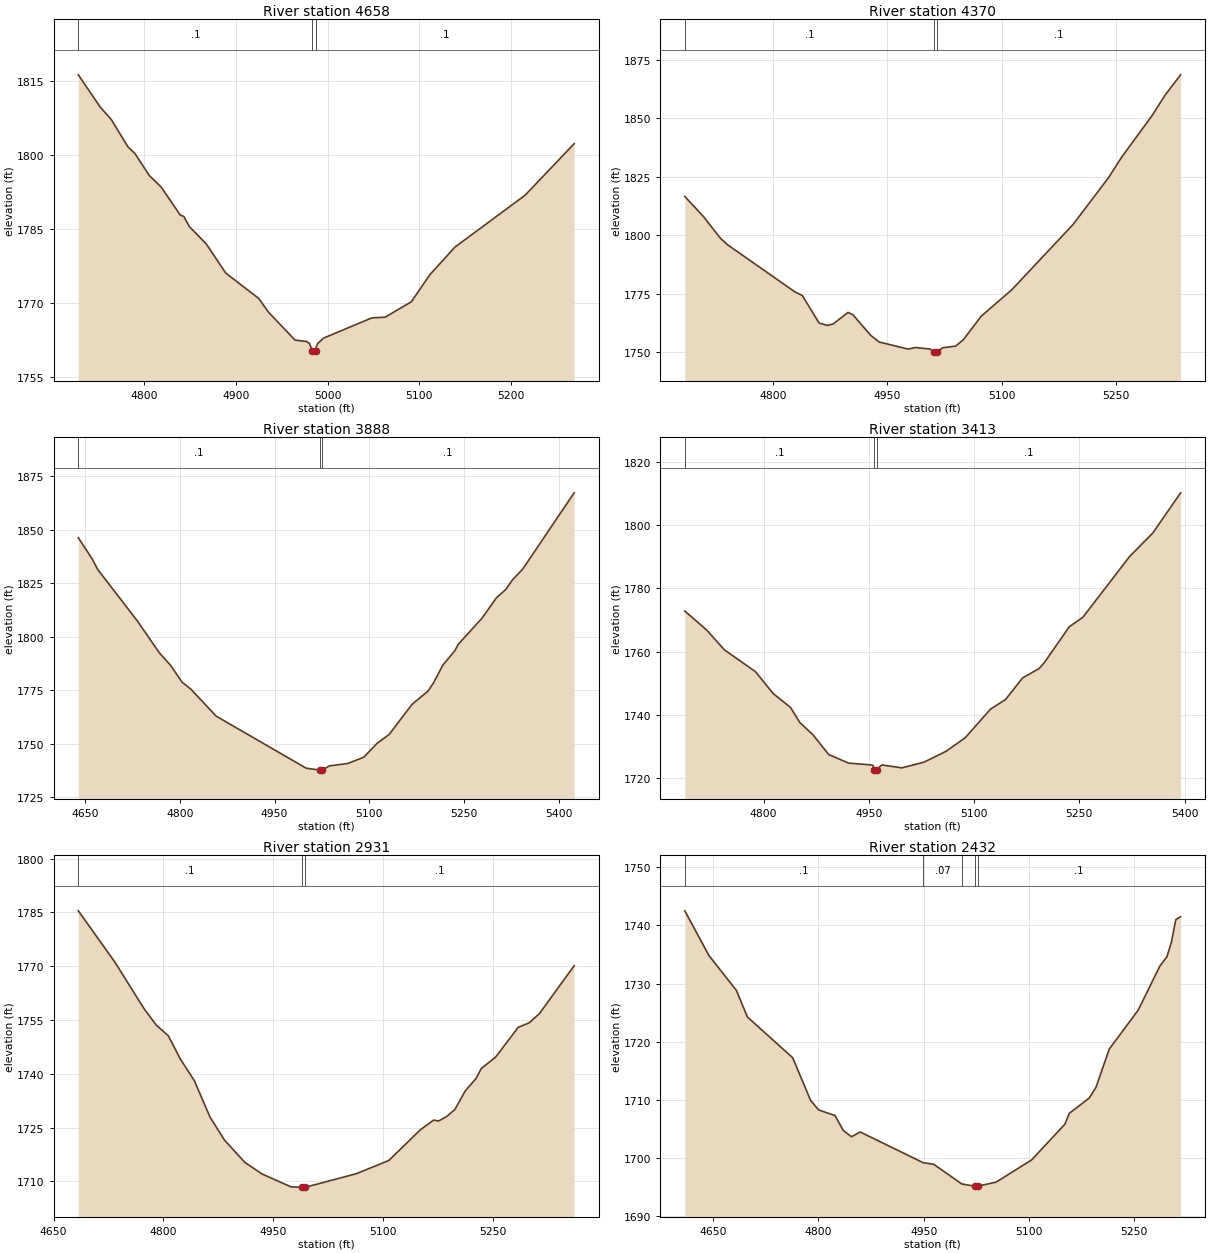
Type RM Length L Ch R = 1,4658,288,288,288
BEGIN DESCRIPTION:
Mapping XS b66a3873
END DESCRIPTION:
XS GIS Cut Line= 3
      1996007.07     13870857.27      1996297.21     13870906.30
      1996488.60     13870751.20
#Sta/Elev= 30
  4728.3 1816.16  4752.1 1809.64  4764.1 1807.13  4782.5 1801.54  4790.1 1800.19
  4805.7 1795.75  4818.7 1793.40  4839.5 1787.73  4843.3 1787.47  4849.4 1785.38
  4867.7 1781.92  4889.0 1775.99  4925.0 1770.84  4935.8 1768.03  4964.5 1762.41
  4977.2 1762.11  4980.3 1761.71  4983.3 1760.26  4983.5 1759.76  4987.3 1760.26
  4987.8 1761.12  4989.4 1761.72  4995.5 1762.79  5048.4 1766.91  5062.7 1767.04
  5091.3 1770.15  5111.7 1775.68  5138.9 1781.24  5215.6 1791.79  5268.9 1802.21
#Mann=3,-1,0
  4728.3     0.1       0  4983.3    0.05       0  4987.3     0.1       0
Bank Sta=4983.3,4987.3
Exp/Cntr=0.3,0.1

Type RM Length L Ch R = 1,4370,482,482,482
BEGIN DESCRIPTION:
Stream0285 9.0
END DESCRIPTION:
XS GIS Cut Line= 3
      1996025.03     13871274.99      1996325.00     13871175.00
      1996624.90     13871025.05
#Sta/Elev= 30
  4683.8 1816.52  4708.5 1807.87  4730.7 1798.63  4740.2 1795.84  4828.7 1775.71
  4838.2 1774.21  4860.3 1762.41  4871.2 1761.44  4878.6 1762.04  4898.3 1766.97
  4904.6 1766.01  4928.4 1757.09  4939.4 1754.33  4977.3 1751.31  4986.8 1751.99
  5006.1 1751.34  5010.9 1750.09  5011.1 1749.59  5014.9 1750.09  5022.9 1751.89
  5039.7 1752.60  5049.8 1755.30  5073.2 1765.35  5113.5 1776.67  5194.0 1804.56
  5240.5 1824.52  5257.7 1833.25  5298.0 1851.18  5314.7 1859.74  5335.3 1868.49
#Mann=3,-1,0
  4683.8     0.1       0  5010.9    0.05       0  5014.9     0.1       0
Bank Sta=5010.9,5014.9
Exp/Cntr=0.3,0.1

Type RM Length L Ch R = 1,3888,475,475,475
BEGIN DESCRIPTION:
Stream0285 8.0
END DESCRIPTION:
XS GIS Cut Line= 3
      1996124.97     13871825.02      1996425.00     13871625.00
      1996724.96     13871325.04
#Sta/Elev= 30
  4639.5 1846.19  4661.5 1836.24  4670.1 1831.40  4732.9 1807.29  4767.5 1792.50
  4785.6 1786.51  4803.6 1778.70  4818.0 1775.30  4857.7 1762.79  5000.1 1738.48
  5021.4 1737.60  5021.7 1737.10  5025.4 1737.60  5037.2 1739.58  5065.9 1740.66
  5091.3 1743.62  5112.5 1750.12  5131.6 1754.28  5167.7 1768.32  5193.1 1774.55
  5201.6 1778.30  5216.4 1786.63  5235.6 1793.43  5240.8 1796.35  5278.0 1808.43
  5301.3 1818.11  5316.2 1822.03  5326.7 1826.50  5342.7 1831.44  5424.3 1867.17
#Mann=3,-1,0
  4639.5     0.1       0  5021.4    0.05       0  5025.4     0.1       0
Bank Sta=5021.4,5025.4
Exp/Cntr=0.3,0.1

Type RM Length L Ch R = 1,3413,482,482,482
BEGIN DESCRIPTION:
Stream0285 7.0
END DESCRIPTION:
XS GIS Cut Line= 3
      1996324.99     13872125.00      1996625.00     13872025.00
      1996874.97     13871725.04
#Sta/Elev= 30
  4687.7 1772.85  4718.8 1766.83  4744.1 1760.54  4788.4 1753.63  4813.7 1746.68
  4838.3 1742.31  4851.6 1737.52  4870.6 1733.55  4892.8 1727.35  4921.2 1724.63
  4954.2 1724.04  4956.0 1723.90  4957.1 1722.59  4957.4 1722.09  4961.1 1722.59
  4968.6 1724.06  4997.1 1723.12  5028.6 1724.93  5059.9 1728.35  5087.5 1732.70
  5123.5 1741.75  5144.8 1744.78  5169.2 1751.64  5192.6 1754.60  5200.4 1756.56
  5235.6 1767.83  5255.1 1770.87  5321.5 1790.07  5354.6 1797.53  5394.4 1810.31
#Mann=3,-1,0
  4687.7     0.1       0  4957.1    0.05       0  4961.1     0.1       0
Bank Sta=4957.1,4961.1
Exp/Cntr=0.3,0.1

Type RM Length L Ch R = 1,2931,499,499,499
BEGIN DESCRIPTION:
Stream0285 6.0
END DESCRIPTION:
XS GIS Cut Line= 3
      1996325.02     13872375.01      1996625.00     13872475.00
      1996925.03     13872274.98
#Sta/Elev= 30
  4683.8 1785.44  4733.8 1771.11  4773.5 1758.15  4790.1 1753.59  4806.6 1750.60
  4823.3 1744.03  4842.3 1738.01  4863.5 1727.95  4883.1 1721.55  4911.1 1715.28
  4934.8 1712.02  4974.2 1708.45  4989.2 1708.32  4989.5 1707.82  4993.2 1708.32
  5063.1 1712.11  5107.6 1715.80  5150.8 1724.40  5168.9 1727.08  5175.6 1726.83
  5186.9 1728.11  5197.7 1730.02  5212.1 1735.27  5226.6 1738.66  5233.8 1741.46
  5253.4 1744.64  5284.2 1752.93  5299.2 1754.21  5313.1 1756.75  5360.6 1770.13
#Mann=3,-1,0
  4683.8     0.1       0  4989.2    0.05       0  4993.2     0.1       0
Bank Sta=4989.2,4993.2
Exp/Cntr=0.3,0.1

Type RM Length L Ch R = 1,2432,481,481,481
BEGIN DESCRIPTION:
Stream0285 5.0
END DESCRIPTION:
XS GIS Cut Line= 3
      1996324.99     13872725.00      1996625.00     13872975.00
      1996924.95     13872875.02
#Sta/Elev= 30
  4609.6 1742.52  4644.0 1734.83  4683.2 1728.82  4698.8 1724.26  4763.4 1717.24
  4788.9 1709.91  4800.3 1708.27  4823.7 1707.30  4835.5 1704.73  4847.2 1703.65
  4859.6 1704.47  4949.5 1699.18  4964.3 1698.92  5004.4 1695.53  5022.9 1695.14
  5023.1 1694.64  5026.9 1695.14  5053.4 1695.85  5103.9 1699.66  5151.2 1705.79
  5157.7 1707.69  5186.2 1710.32  5195.7 1712.17  5214.6 1718.74  5255.7 1725.41
  5286.7 1733.01  5296.8 1734.62  5303.2 1737.15  5309.5 1741.02  5316.3 1741.51
#Mann=5,-1,0
  4609.6     0.1       0  4949.5    0.07       0  5004.4     0.1       0
  5022.9    0.05       0  5026.9     0.1       0
Bank Sta=5022.9,5026.9
Exp/Cntr=0.3,0.1

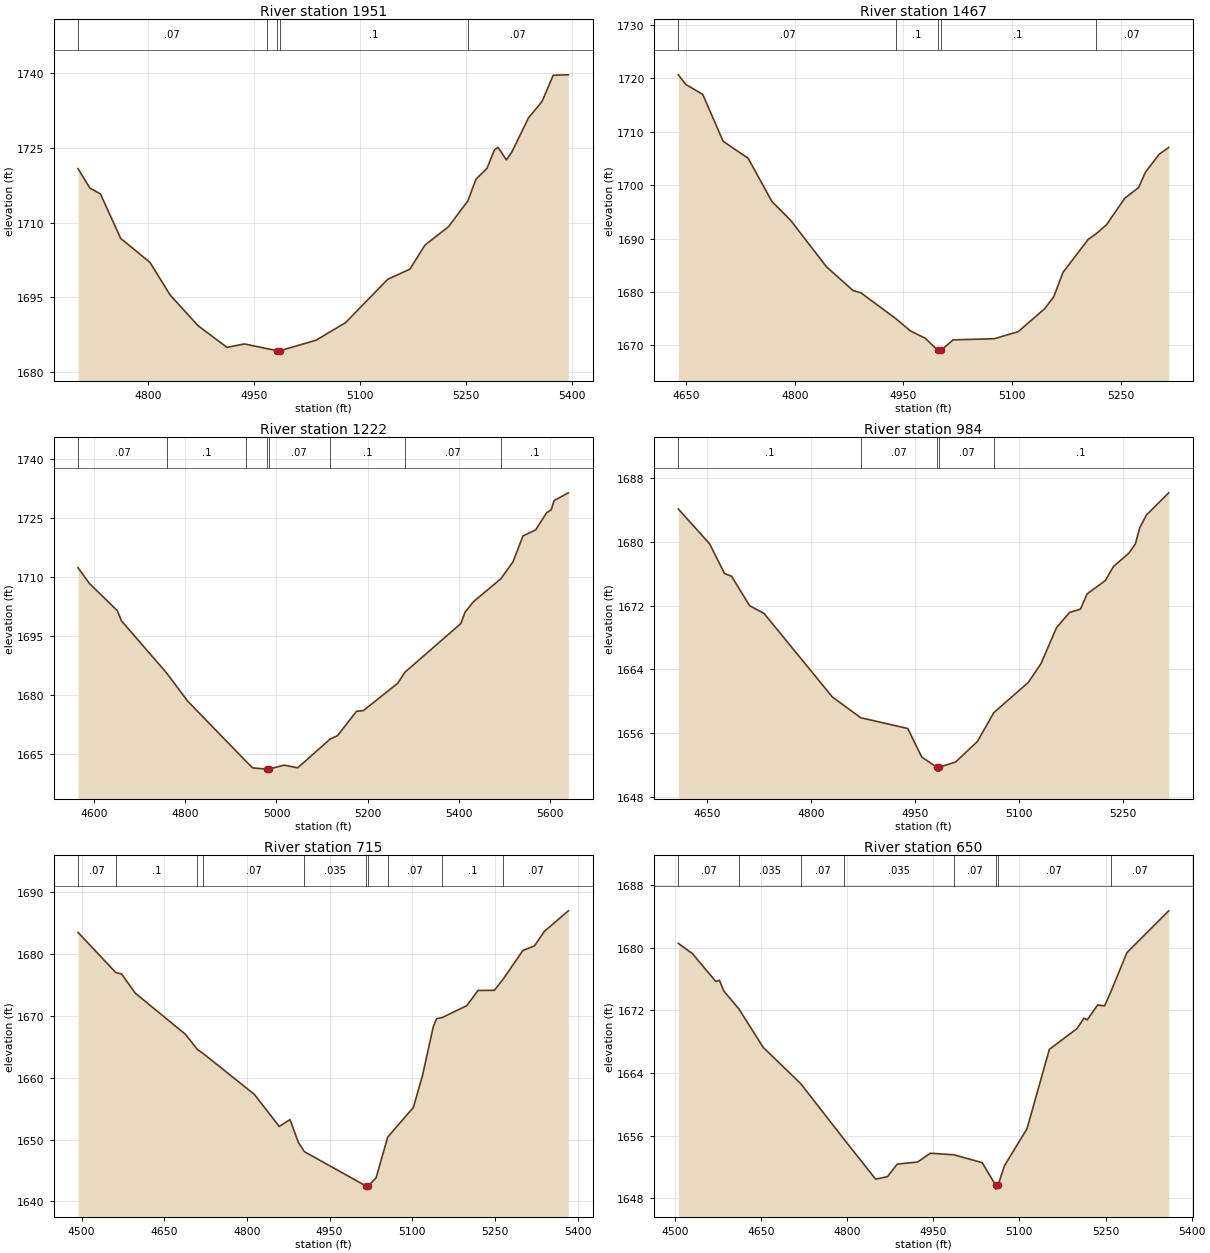
Type RM Length L Ch R = 1,1951,484,484,484
BEGIN DESCRIPTION:
Stream0285 4.0
END DESCRIPTION:
XS GIS Cut Line= 3
      1996425.02     13873375.00      1996725.00     13873425.00
      1997024.97     13873175.02
#Sta/Elev= 30
  4700.6 1720.85  4717.3 1716.95  4732.3 1715.77  4761.0 1706.83  4802.5 1702.00
  4831.3 1695.41  4870.5 1689.30  4911.6 1684.93  4936.3 1685.62  4967.6 1684.69
  4983.0 1684.27  4983.2 1683.77  4987.0 1684.27  5037.9 1686.37  5079.6 1689.90
  5139.4 1698.62  5170.7 1700.64  5192.1 1705.49  5225.4 1709.18  5252.8 1714.35
  5264.4 1718.74  5280.0 1720.91  5290.5 1724.62  5295.7 1725.12  5307.4 1722.61
  5315.2 1724.19  5338.6 1731.02  5358.1 1734.37  5373.8 1739.62  5395.2 1739.70
#Mann=5,-1,0
  4700.6    0.07       0  4967.6     0.1       0  4983.0    0.05       0
  4987.0     0.1       0  5252.8    0.07       0
Bank Sta=4983,4987
Exp/Cntr=0.3,0.1

Type RM Length L Ch R = 1,1467,245,245,245
BEGIN DESCRIPTION:
Stream0285 3.0
END DESCRIPTION:
XS GIS Cut Line= 3
      1996324.96     13873674.97      1996625.00     13873875.00
      1996924.97     13873775.01
#Sta/Elev= 30
  4639.4 1720.61  4649.7 1718.80  4673.0 1716.95  4701.1 1708.19  4735.7 1705.00
  4768.6 1696.90  4794.2 1693.43  4843.9 1684.70  4880.7 1680.25  4891.2 1679.86
  4940.1 1674.96  4959.7 1672.72  4980.2 1671.35  4997.7 1669.07  4997.9 1668.57
  5001.7 1669.07  5018.5 1671.05  5075.4 1671.26  5108.4 1672.58  5144.9 1676.87
  5157.6 1679.12  5170.2 1683.65  5205.0 1689.83  5215.3 1690.81  5230.3 1692.56
  5255.6 1697.54  5274.6 1699.52  5284.1 1702.40  5303.1 1705.77  5316.2 1707.02
#Mann=5,-1,0
  4639.4    0.07       0  4940.1     0.1       0  4997.7    0.05       0
  5001.7     0.1       0  5215.3    0.07       0
Bank Sta=4997.7,5001.7
Exp/Cntr=0.3,0.1

Type RM Length L Ch R = 1,1222,238,238,238
BEGIN DESCRIPTION:
Mapping XS 83256838
END DESCRIPTION:
XS GIS Cut Line= 4
      1996218.33     13873880.34      1996496.79     13874104.82
      1996869.56     13874095.73      1997203.73     13874006.27
#Sta/Elev= 30
  4564.3 1712.37  4589.1 1708.39  4650.6 1701.45  4659.5 1698.89  4758.7 1685.65
  4804.7 1678.54  4933.7 1663.15  4947.7 1661.56  4978.7 1661.23  4979.0 1660.73
  4982.7 1661.23  5016.7 1662.25  5046.7 1661.58  5117.5 1668.84  5133.8 1669.72
  5175.8 1675.92  5190.8 1676.09  5266.4 1683.06  5281.8 1685.81  5404.8 1698.19
  5413.8 1701.04  5432.5 1703.74  5492.8 1709.58  5519.4 1713.88  5541.2 1720.43
  5569.1 1721.96  5593.4 1726.35  5603.3 1727.07  5609.5 1729.39  5640.8 1731.37
#Mann=8,-1,0
  4564.3    0.07       0  4758.7     0.1       0  4933.7    0.07       0
  4978.7    0.05       0  4982.7    0.07       0  5117.5     0.1       0
  5281.8    0.07       0  5492.8     0.1       0
Bank Sta=4978.7,4982.7
Exp/Cntr=0.3,0.1

Type RM Length L Ch R = 1,984,269,269,269
BEGIN DESCRIPTION:
Stream0285 2.0
END DESCRIPTION:
XS GIS Cut Line= 3
      1996324.98     13874074.98      1996625.00     13874325.00
      1996925.03     13874224.99
#Sta/Elev= 30
  4608.6 1684.09  4653.7 1679.73  4675.0 1676.03  4685.2 1675.68  4711.3 1671.99
  4732.1 1671.02  4830.5 1660.56  4871.4 1657.96  4939.2 1656.61  4959.4 1653.04
  4980.9 1651.77  4981.1 1651.27  4984.6 1651.27  4984.9 1651.77  5008.2 1652.41
  5039.7 1654.99  5063.2 1658.59  5112.9 1662.37  5131.4 1664.75  5153.6 1669.23
  5172.5 1671.15  5188.2 1671.56  5197.8 1673.47  5224.0 1675.14  5235.8 1676.90
  5257.9 1678.57  5267.4 1679.73  5273.7 1681.77  5283.3 1683.35  5315.4 1686.13
#Mann=5,-1,0
  4608.6     0.1       0  4871.4    0.07       0  4980.9    0.05       0
  4984.9    0.07       0  5063.2     0.1       0
Bank Sta=4980.9,4984.9
Exp/Cntr=0.3,0.1

Type RM Length L Ch R = 1,715,65,65,65
BEGIN DESCRIPTION:
Mapping XS 43122639
END DESCRIPTION:
XS GIS Cut Line= 4
      1996194.70     13874296.29      1996596.57     13874549.53
      1996676.59     13874582.41      1997003.71     13874609.94
#Sta/Elev= 30
  4493.5 1683.49  4562.0 1677.00  4572.5 1676.77  4597.3 1673.68  4688.9 1666.98
  4710.2 1664.55  4720.3 1663.94  4813.6 1657.30  4858.6 1652.12  4878.2 1653.23
  4893.4 1649.52  4904.4 1648.04  5016.2 1642.49  5016.4 1641.99  5020.2 1642.49
  5034.4 1643.81  5055.5 1650.40  5102.1 1655.20  5118.5 1660.30  5138.2 1668.24
  5144.2 1669.55  5154.1 1669.71  5199.0 1671.65  5219.5 1674.11  5249.0 1674.13
  5265.2 1675.96  5300.8 1680.57  5321.9 1681.32  5339.9 1683.67  5383.3 1686.98
#Mann=10,-1,0
  4493.5    0.07       0  4562.0     0.1       0  4710.2   0.035       0
  4720.3    0.07       0  4904.4   0.035       0  5016.2   0.035       0
  5020.2   0.035       0  5055.5    0.07       0  5154.1     0.1       0
  5265.2    0.07       0
Bank Sta=5016.2,5020.2
Exp/Cntr=0.3,0.1

Type RM Length L Ch R = 1,650,134,134,134
BEGIN DESCRIPTION:
Stream0285 1.2
END DESCRIPTION:
XS GIS Cut Line= 5
      1996198.42     13874372.05      1996545.60     13874565.17
      1996589.00     13874595.55      1996638.91     13874643.30
      1996973.13     13874656.32
#Sta/Elev= 30
  4506.2 1680.57  4530.3 1679.29  4571.5 1675.70  4577.6 1675.87  4585.3 1674.49
  4611.9 1672.16  4653.9 1667.28  4719.4 1662.63  4795.0 1655.50  4849.6 1650.44
  4870.2 1650.75  4887.3 1652.36  4922.9 1652.63  4944.9 1653.75  4985.8 1653.55
  5035.1 1652.55  5058.8 1649.66  5059.0 1649.16  5062.8 1649.66  5074.2 1652.18
  5113.2 1656.87  5152.2 1667.03  5200.2 1669.68  5212.3 1671.00  5218.3 1670.81
  5236.3 1672.71  5248.3 1672.58  5258.7 1674.29  5287.3 1679.40  5360.0 1684.74
#Mann=8,-1,0
  4506.2    0.07       0  4611.9   0.035       0  4719.4    0.07       0
  4795.0   0.035       0  4985.8    0.07       0  5058.8    0.05       0
  5062.8    0.07       0  5258.7    0.07       0
Bank Sta=5058.8,5062.8
Exp/Cntr=0.3,0.1

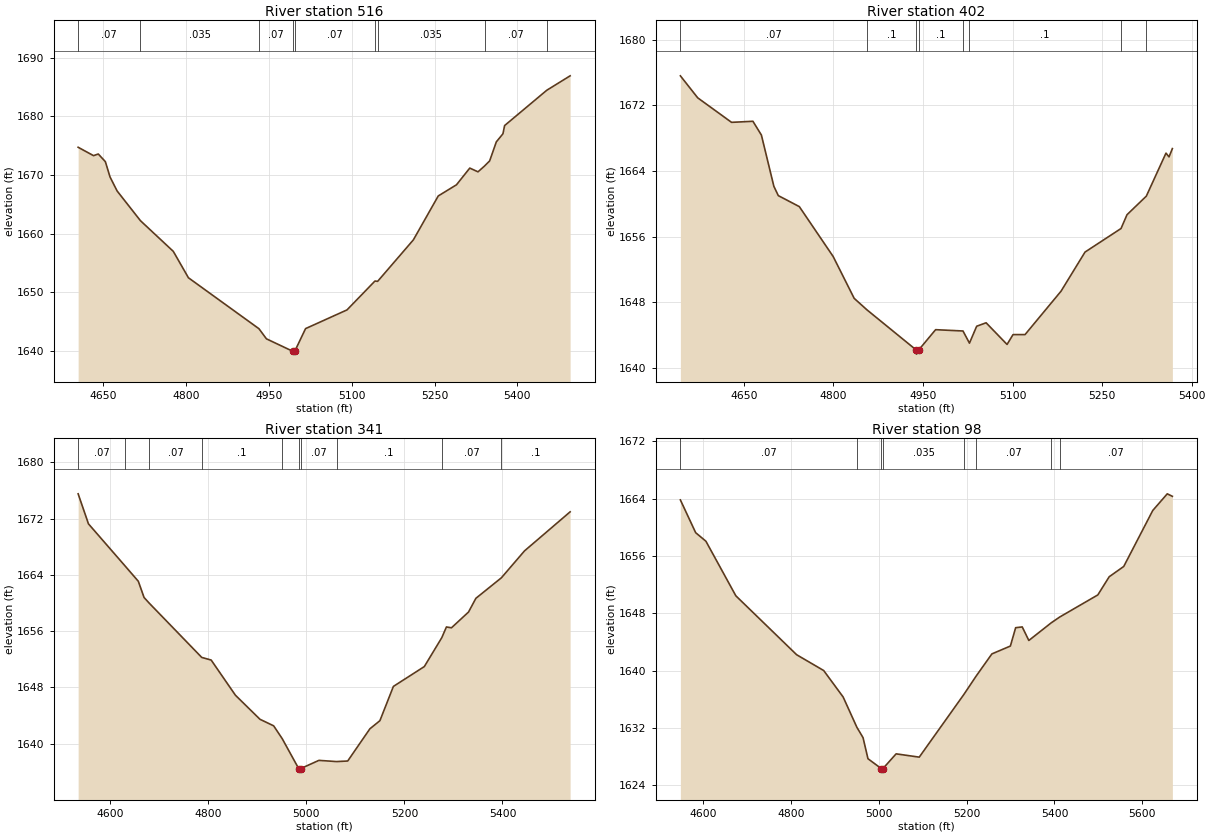
Type RM Length L Ch R = 1,516,114,114,114
BEGIN DESCRIPTION:
Stream0285 1.0
END DESCRIPTION:
XS GIS Cut Line= 3
      1996225.04     13874475.03      1996525.00     13874725.00
      1997025.02     13874696.38
#Sta/Elev= 30
  4604.3 1674.75  4632.2 1673.32  4640.8 1673.60  4653.6 1672.30  4662.1 1669.68
  4674.9 1667.30  4717.2 1662.23  4776.7 1657.00  4804.1 1652.50  4931.9 1643.81
  4945.4 1642.09  4992.8 1639.98  4993.0 1639.48  4996.8 1639.98  5016.3 1643.83
  5091.4 1647.02  5142.0 1651.94  5146.9 1651.89  5211.6 1658.96  5256.7 1666.45
  5289.7 1668.35  5313.8 1671.20  5328.7 1670.56  5340.6 1671.56  5349.8 1672.42
  5361.9 1675.67  5373.9 1677.05  5376.9 1678.45  5453.3 1684.47  5495.6 1686.93
#Mann=9,-1,0
  4604.3    0.07       0  4717.2   0.035       0  4931.9    0.07       0
  4992.8    0.05       0  4996.8    0.07       0  5142.0     0.1       0
  5146.9   0.035       0  5340.6    0.07       0  5453.3     0.1       0
Bank Sta=4992.8,4996.8
Exp/Cntr=0.3,0.1

Type RM Length L Ch R = 1,402,61,61,61
BEGIN DESCRIPTION:
Stream0285 D
END DESCRIPTION:
XS GIS Cut Line= 5
      1996113.94     13874494.69      1996410.83     13874767.27
      1996476.80     13874801.99      1996524.54     13874813.28
      1996820.70     13874840.99
#Sta/Elev= 30
  4543.6 1675.60  4572.6 1672.92  4629.3 1669.93  4665.1 1670.06  4679.3 1668.38
  4700.2 1662.13  4707.6 1661.00  4742.8 1659.66  4799.5 1653.58  4834.7 1648.48
  4855.9 1647.09  4938.7 1642.18  4939.0 1641.68  4942.7 1642.18  4971.1 1644.66
  5017.0 1644.50  5027.8 1643.02  5039.9 1645.08  5055.7 1645.50  5090.8 1642.86
  5100.8 1644.06  5120.9 1644.06  5181.2 1649.35  5221.4 1654.12  5281.7 1656.99
  5291.7 1658.67  5324.1 1660.94  5357.0 1666.18  5362.1 1665.72  5367.7 1666.73
#Mann=8,-1,0
  4543.6    0.07       0  4855.9     0.1       0  4938.7    0.05       0
  4942.7     0.1       0  5017.0    0.07       0  5027.8     0.1       0
  5281.7    0.07       0  5324.1     0.1       0
Bank Sta=4938.7,4942.7
Exp/Cntr=0.3,0.1

Type RM Length L Ch R = 1,341,243,243,243
BEGIN DESCRIPTION:
Mapping XS a43b76e1
END DESCRIPTION:
XS GIS Cut Line= 4
      1996052.64     13874542.62      1996402.39     13874830.33
      1996571.10     13874898.30      1996939.47     13874876.19
#Sta/Elev= 30
  4534.3 1675.51  4555.4 1671.24  4629.3 1665.32  4657.1 1663.08  4668.8 1660.78
  4678.7 1660.02  4786.5 1652.26  4805.7 1651.89  4855.2 1646.89  4905.3 1643.47
  4933.2 1642.54  4950.8 1640.70  4984.3 1636.46  4984.6 1635.96  4988.3 1636.46
  5025.5 1637.63  5061.5 1637.46  5084.3 1637.54  5129.6 1642.12  5150.0 1643.27
  5177.5 1648.14  5240.6 1650.96  5276.2 1655.06  5285.7 1656.59  5296.0 1656.47
  5330.8 1658.71  5345.8 1660.66  5397.9 1663.58  5445.0 1667.40  5538.1 1672.95
#Mann=10,-1,0
  4534.3    0.07       0  4629.3     0.1       0  4678.7    0.07       0
  4786.5     0.1       0  4950.8    0.07       0  4984.3    0.05       0
  4988.3    0.07       0  5061.5     0.1       0  5276.2    0.07       0
  5397.9     0.1       0
Bank Sta=4984.3,4988.3
Exp/Cntr=0.3,0.1

Type RM Length L Ch R = 1,98,0,0,0
BEGIN DESCRIPTION:
Stream0285 0.0
END DESCRIPTION:
XS GIS Cut Line= 4
      1996001.87     13874675.12      1996258.58     13875021.33
      1996513.07     13875097.07      1996936.13     13875086.91
#Sta/Elev= 30
  4548.6 1663.82  4583.4 1659.25  4606.7 1658.06  4674.8 1650.45  4813.2 1642.23
  4874.7 1640.03  4919.0 1636.34  4950.3 1632.11  4964.3 1630.67  4975.5 1627.73
  5005.7 1626.36  5005.9 1625.86  5009.7 1626.36  5039.6 1628.41  5092.2 1627.95
  5194.2 1636.73  5221.9 1639.27  5257.6 1642.35  5299.6 1643.44  5311.6 1646.00
  5326.6 1646.11  5341.6 1644.22  5392.6 1646.68  5411.9 1647.49  5498.6 1650.57
  5524.6 1653.11  5557.6 1654.54  5623.7 1662.35  5656.7 1664.67  5668.3 1664.32
#Mann=8,-1,0
  4548.6    0.07       0  4950.3   0.035       0  5005.7   0.035       0
  5009.7   0.035       0  5194.2     0.1       0  5221.9    0.07       0
  5392.6   0.035       0  5411.9    0.07       0
Bank Sta=5005.7,5009.7
Exp/Cntr=0.3,0.1

Chan Stop Cuts=-1