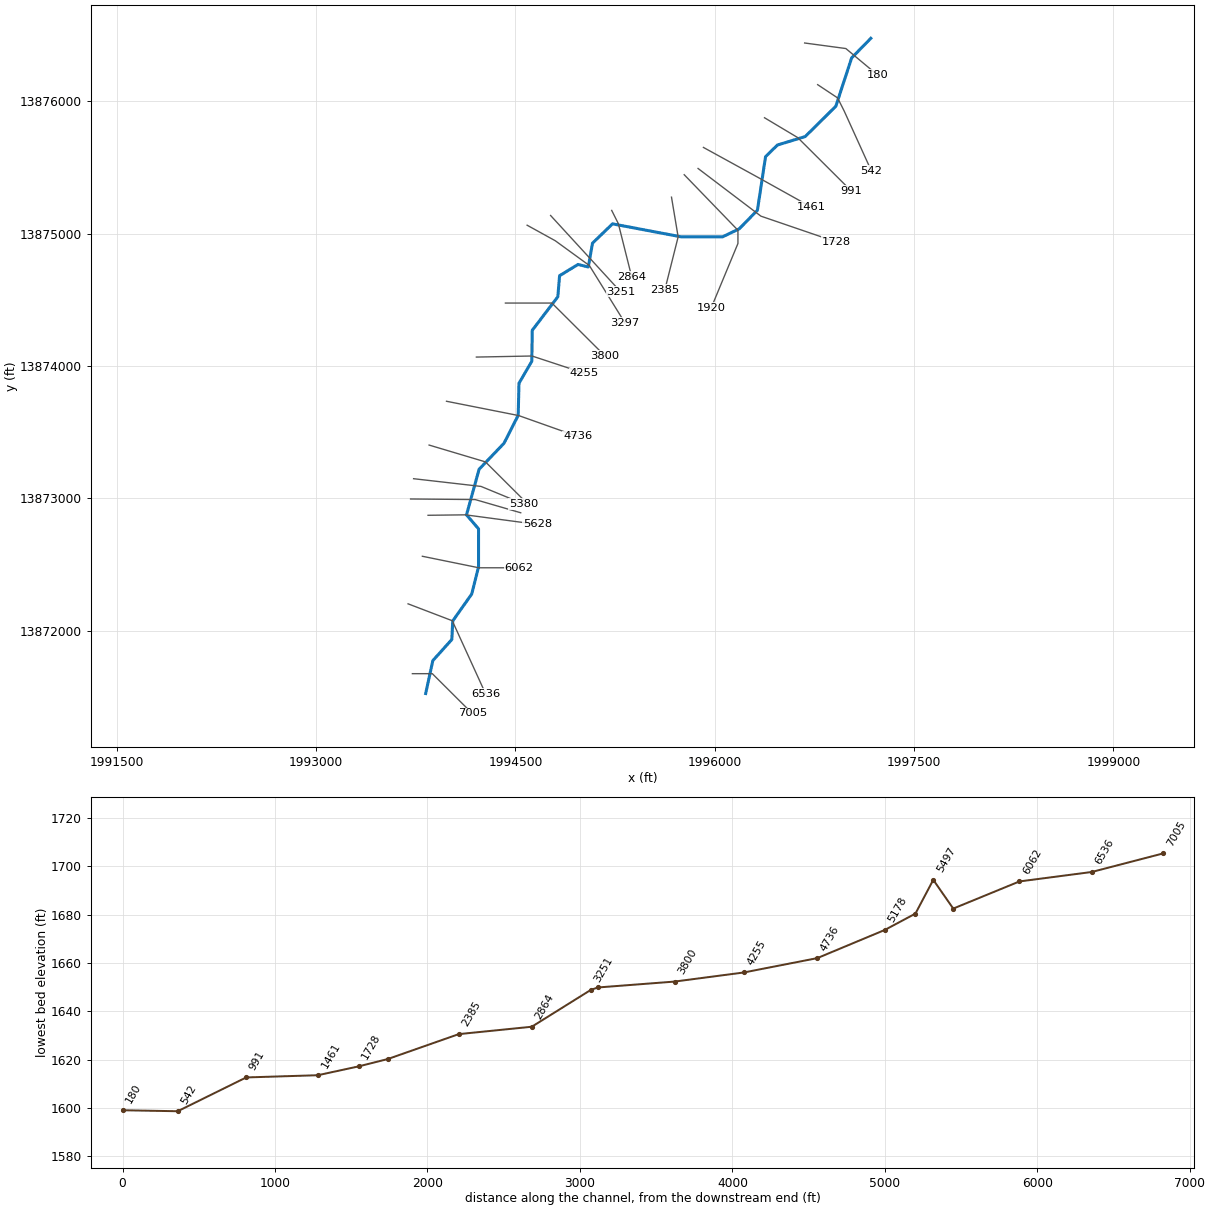
--- Stream0291.prj (project) ---

Proj Title=Stream0291 Base Level Engineering
Current Plan=p01
Default Exp/Contr=0.3,0.1
English Units
Geom File=g01
Flow File=f01
Plan File=p01
BEGIN DESCRIPTION:
Stream0291
END DESCRIPTION:

--- Stream0291.p01 (plan) ---

Plan Title=Multiple Run
Short Identifier=Multiple
Geom File=g01
Flow File=f01
Subcritical Flow
K Sum by GR= 0
Std Step Tol= 0.01
Critical Tol= 0.01
Num of Std Step Trials= 20
Max Error Tol= 0.3
Flow Tol Ratio= 0.001
Split Flow NTrial= 30
Split Flow Tol= 0.02
Split Flow Ratio= 0.02
Log Output Level= 0
Friction Slope Method= 1
Unsteady Friction Slope Method= 2
Unsteady Bridges Friction Slope Method= 1
Parabolic Critical Depth
Global Vel Dist=  1 , 1 , 1
Global Log Level= 0
CheckData=True
Encroach Param= -1, 0, 0, 0
BEGIN DESCRIPTION:
Multiple Run
END DESCRIPTION:

--- Stream0291.f01 (steady flow) ---

Flow Title=Multiple
Number of Profiles=7
Profile Names=10-year,25-year,50-year,1pct_min,100-year,1pct_plu,500-year
River Rch & RM= Stream0291,Reach-1,7005
    1245    2148    3022    2061    4112    8205    7537
River Rch & RM= Stream0291,Reach-1,4736
    1442    2504    3539    2422    4832    9641    8921
River Rch & RM= Stream0291,Reach-1,1728
    1801    3166    4509    3107    6200   12370   11611
Boundary for River Rch & Prof#=Stream0291,Reach-1,1
Up Type=0
Dn Type=3
Dn Slope=0.005
Boundary for River Rch & Prof#=Stream0291,Reach-1,2
Up Type=0
Dn Type=3
Dn Slope=0.005
Boundary for River Rch & Prof#=Stream0291,Reach-1,3
Up Type=0
Dn Type=3
Dn Slope=0.005
Boundary for River Rch & Prof#=Stream0291,Reach-1,4
Up Type=0
Dn Type=3
Dn Slope=0.005
Boundary for River Rch & Prof#=Stream0291,Reach-1,5
Up Type=0
Dn Type=3
Dn Slope=0.005
Boundary for River Rch & Prof#=Stream0291,Reach-1,6
Up Type=0
Dn Type=3
Dn Slope=0.005
Boundary for River Rch & Prof#=Stream0291,Reach-1,7
Up Type=0
Dn Type=3
Dn Slope=0.005

--- Stream0291.g01 (geometry) ---

Geom Title=Existing Conditions

River Reach=Stream0291,Reach-1
Reach XY= 30
      1993825.00     13871525.00      1993878.76     13871773.44
      1994021.90     13871933.31      1994028.76     13872073.44
      1994171.45     13872276.47      1994222.74     13872480.94
      1994222.93     13872769.15      1994132.33     13872874.90
      1994227.03     13873219.16      1994414.30     13873415.29
      1994521.25     13873626.55      1994527.24     13873869.07
      1994623.80     13874035.50      1994627.06     13874269.14
      1994819.52     13874522.56      1994832.70     13874681.48
      1994971.78     13874766.75      1995048.83     13874747.31
      1995080.47     13874927.45      1995231.03     13875073.38
      1995749.92     13874974.80      1996059.79     13874975.51
      1996184.71     13875035.70      1996321.71     13875176.36
      1996382.85     13875581.19      1996472.69     13875669.18
      1996681.17     13875732.86      1996911.60     13875961.70
      1997030.83     13876327.30      1997175.00     13876475.00

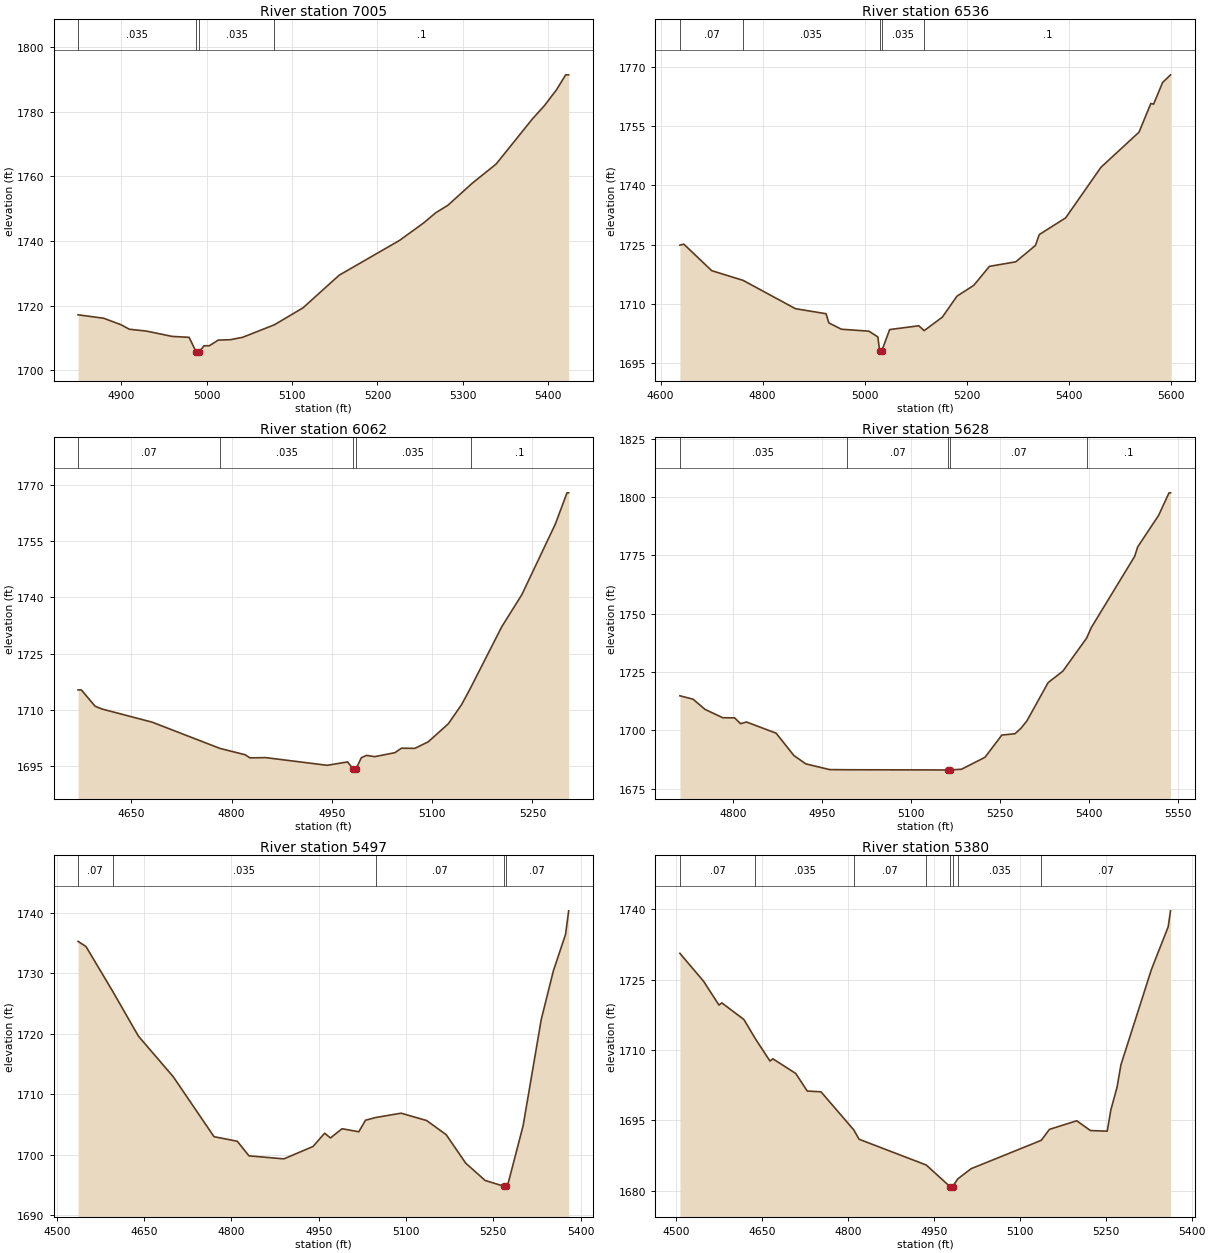
Type RM Length L Ch R = 1,7005,469,469,469
BEGIN DESCRIPTION:
Stream0291 15.0
END DESCRIPTION:
XS GIS Cut Line= 3
      1993724.97     13871675.00      1993875.00     13871675.00
      1994175.00     13871375.00
#Sta/Elev= 30
  4849.5 1717.14  4879.5 1716.07  4899.5 1714.09  4909.5 1712.67  4929.5 1712.10
  4959.5 1710.46  4979.5 1710.16  4987.5 1705.78  4987.8 1705.28  4991.3 1705.28
  4991.5 1705.78  4997.0 1707.56  5003.1 1707.56  5013.7 1709.31  5027.8 1709.44
  5042.0 1710.16  5079.4 1714.06  5112.7 1719.27  5155.1 1729.38  5225.8 1740.15
  5254.1 1745.57  5268.2 1748.71  5282.4 1751.02  5310.7 1757.79  5338.9 1763.78
  5381.4 1777.75  5395.5 1781.88  5409.7 1786.81  5420.3 1791.38  5423.8 1791.38
#Mann=4,-1,0
  4849.5   0.035       0  4987.5   0.035       0  4991.5   0.035       0
  5079.4     0.1       0
Bank Sta=4987.5,4991.5
Exp/Cntr=0.3,0.1

Type RM Length L Ch R = 1,6536,474,474,474
BEGIN DESCRIPTION:
Stream0291 14.0
END DESCRIPTION:
XS GIS Cut Line= 3
      1993692.55     13872202.60      1994025.00     13872075.00
      1994275.61     13871524.01
#Sta/Elev= 30
  4638.0 1724.90  4645.6 1725.16  4700.3 1718.45  4761.9 1715.99  4864.4 1708.83
  4924.4 1707.56  4929.8 1705.24  4954.4 1703.64  5008.4 1703.14  5025.9 1701.69
  5029.4 1698.09  5029.7 1697.59  5033.4 1698.09  5049.0 1703.55  5106.1 1704.51
  5116.6 1703.28  5152.2 1706.69  5180.9 1712.00  5213.8 1714.73  5244.5 1719.54
  5296.1 1720.69  5334.7 1724.84  5342.2 1727.58  5393.9 1731.81  5463.0 1744.59
  5537.7 1753.49  5560.8 1760.74  5566.3 1760.58  5583.8 1766.04  5599.4 1767.99
#Mann=5,-1,0
  4638.0    0.07       0  4761.9   0.035       0  5029.4   0.035       0
  5033.4   0.035       0  5116.6     0.1       0
Bank Sta=5029.4,5033.4
Exp/Cntr=0.3,0.1

Type RM Length L Ch R = 1,6062,434,434,434
BEGIN DESCRIPTION:
Stream0291 13.0
END DESCRIPTION:
XS GIS Cut Line= 3
      1993800.08     13872561.96      1994225.00     13872475.00
      1994524.97     13872475.00
#Sta/Elev= 30
  4570.5 1715.32  4575.4 1715.32  4595.9 1710.99  4606.1 1710.24  4681.4 1706.72
  4782.7 1699.73  4820.5 1698.04  4827.6 1697.21  4851.1 1697.28  4943.0 1695.23
  4973.6 1696.13  4982.1 1694.18  4982.4 1693.68  4985.9 1693.68  4986.1 1694.18
  4994.0 1697.24  5001.7 1697.87  5014.2 1697.54  5044.2 1698.59  5054.2 1699.79
  5074.2 1699.75  5094.2 1701.49  5124.2 1706.29  5144.2 1711.44  5157.4 1715.82
  5204.2 1732.17  5234.2 1740.71  5284.2 1759.48  5301.7 1767.83  5304.2 1767.83
#Mann=5,-1,0
  4570.5    0.07       0  4782.7   0.035       0  4982.1   0.035       0
  4986.1   0.035       0  5157.4     0.1       0
Bank Sta=4982.1,4986.1
Exp/Cntr=0.3,0.1

Type RM Length L Ch R = 1,5628,131,131,131
BEGIN DESCRIPTION:
Stream0291 12.0
END DESCRIPTION:
XS GIS Cut Line= 3
      1993842.84     13872871.61      1994125.00     13872875.00
      1994664.90     13872802.64
#Sta/Elev= 30
  4710.3 1714.75  4732.5 1713.29  4752.5 1708.94  4782.5 1705.34  4802.5 1705.29
  4812.5 1702.79  4822.5 1703.51  4872.5 1698.71  4902.5 1689.11  4922.5 1685.56
  4962.5 1683.11  4991.8 1683.04  5162.0 1682.95  5162.2 1682.45  5166.0 1682.95
  5185.0 1683.27  5224.5 1688.38  5252.9 1697.92  5275.0 1698.47  5285.1 1700.81
  5295.2 1704.01  5330.9 1720.40  5355.7 1725.30  5395.8 1739.49  5403.8 1744.05
  5476.8 1774.54  5481.8 1778.55  5517.1 1792.08  5534.7 1801.76  5537.2 1801.76
#Mann=5,-1,0
  4710.3   0.035       0  4991.8    0.07       0  5162.0    0.05       0
  5166.0    0.07       0  5395.8     0.1       0
Bank Sta=5162,5166
Exp/Cntr=0.3,0.1

Type RM Length L Ch R = 1,5497,117,117,117
BEGIN DESCRIPTION:
Stream0291 11.3
END DESCRIPTION:
XS GIS Cut Line= 3
      1993711.36     13872994.71      1994197.51     13872990.37
      1994540.21     13872890.60
#Sta/Elev= 30
  4536.5 1735.28  4550.1 1734.43  4595.7 1727.08  4640.1 1719.64  4700.1 1712.91
  4770.1 1703.01  4810.1 1702.25  4830.2 1699.84  4890.2 1699.34  4940.2 1701.38
  4960.2 1703.58  4970.2 1702.80  4990.2 1704.32  5018.9 1703.82  5030.5 1705.73
  5048.4 1706.18  5091.6 1706.89  5135.6 1705.67  5169.1 1703.34  5202.6 1698.64
  5236.1 1695.77  5267.6 1694.84  5267.9 1694.34  5271.6 1694.84  5274.8 1695.01
  5301.3 1704.81  5332.5 1722.39  5353.3 1730.40  5374.2 1736.43  5379.6 1740.33
#Mann=5,-1,0
  4536.5    0.07       0  4595.7   0.035       0  5048.4    0.07       0
  5267.6   0.035       0  5271.6    0.07       0
Bank Sta=5267.6,5271.6
Exp/Cntr=0.3,0.1

Type RM Length L Ch R = 1,5380,202,202,202
BEGIN DESCRIPTION:
Mapping XS 3793e5e1
END DESCRIPTION:
XS GIS Cut Line= 3
      1993734.02     13873147.98      1994241.35     13873089.68
      1994561.31     13872957.40
#Sta/Elev= 30
  4506.2 1730.59  4547.5 1724.65  4574.4 1719.58  4579.4 1720.04  4617.9 1716.51
  4637.8 1712.44  4663.5 1707.65  4668.5 1708.13  4708.5 1705.01  4728.6 1701.26
  4752.6 1701.10  4809.8 1692.99  4819.2 1690.99  4936.4 1685.51  4978.3 1680.87
  4978.5 1680.37  4982.3 1680.87  4991.5 1682.55  5014.8 1684.72  5137.4 1690.77
  5151.5 1693.09  5199.3 1694.93  5223.2 1692.85  5252.5 1692.72  5258.9 1697.27
  5269.7 1702.06  5276.4 1706.82  5329.7 1727.15  5359.0 1736.24  5363.1 1739.65
#Mann=8,-1,0
  4506.2    0.07       0  4637.8   0.035       0  4809.8    0.07       0
  4936.4     0.1       0  4978.3   0.035       0  4982.3     0.1       0
  4991.5   0.035       0  5137.4    0.07       0
Bank Sta=4978.3,4982.3
Exp/Cntr=0.3,0.1

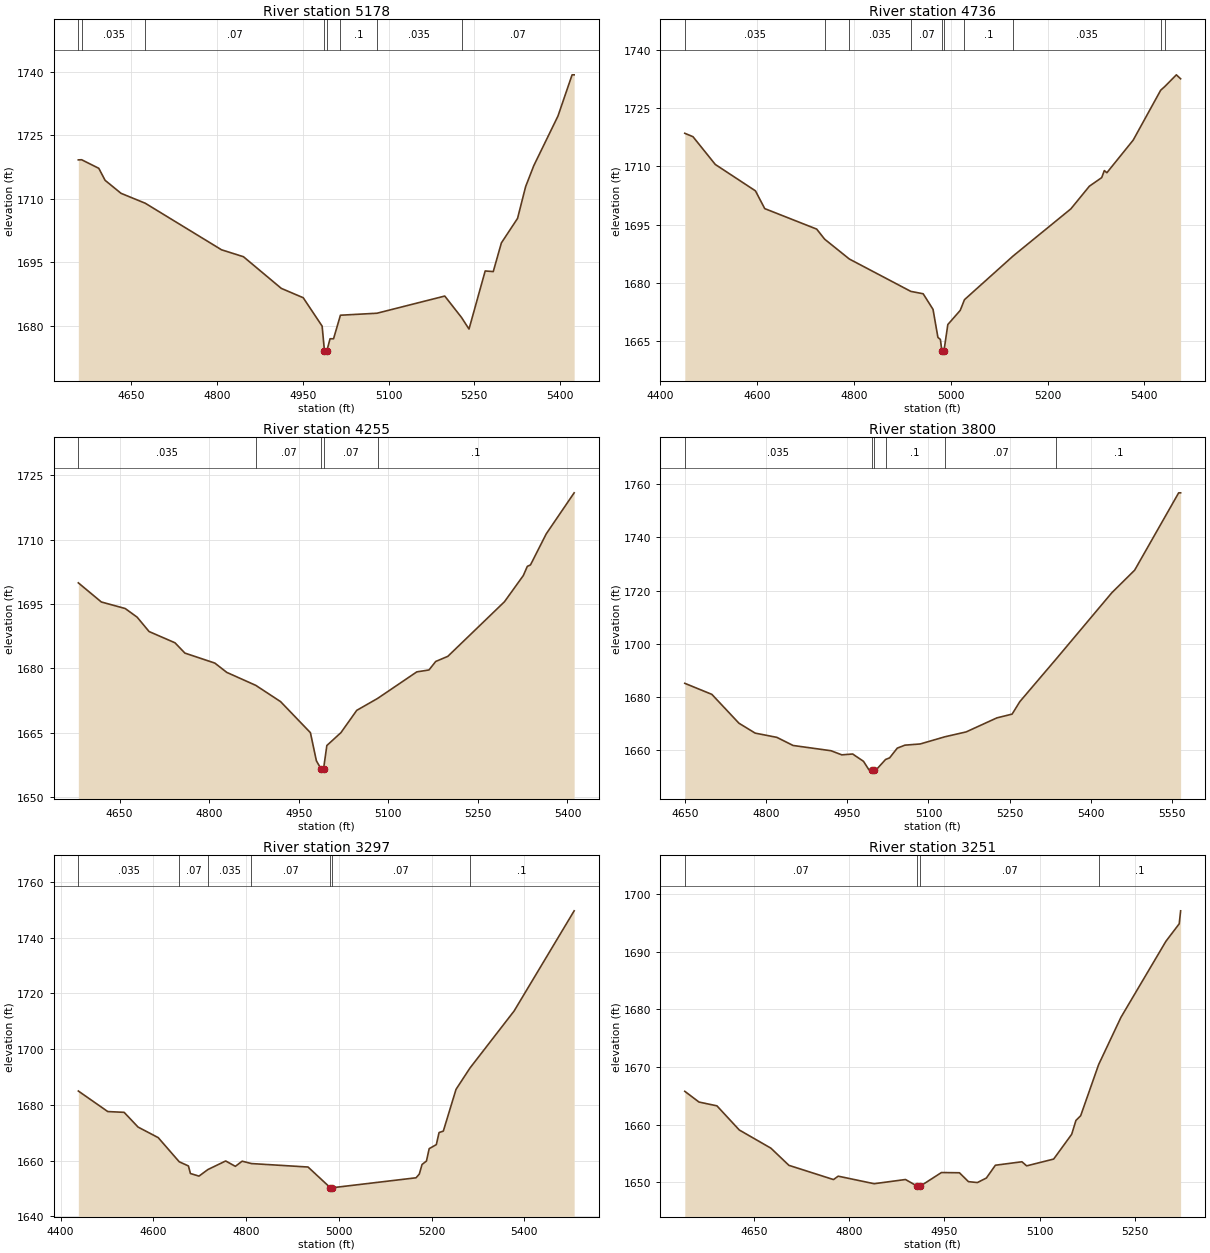
Type RM Length L Ch R = 1,5178,442,442,442
BEGIN DESCRIPTION:
Stream0291 11.0
END DESCRIPTION:
XS GIS Cut Line= 3
      1993850.74     13873402.13      1994275.00     13873275.00
      1994575.03     13872974.97
#Sta/Elev= 30
  4557.5 1719.16  4563.3 1719.19  4593.3 1717.17  4604.3 1714.34  4632.2 1711.27
  4674.6 1708.93  4808.0 1697.95  4846.3 1696.32  4912.5 1688.85  4950.8 1686.65
  4983.9 1679.95  4988.0 1674.08  4988.2 1673.58  4992.0 1674.08  4997.8 1676.97
  5003.9 1676.97  5015.9 1682.52  5079.8 1682.99  5198.4 1687.04  5227.7 1681.99
  5240.8 1679.26  5269.1 1692.96  5283.2 1692.81  5297.4 1699.57  5325.7 1705.36
  5339.8 1712.84  5354.0 1717.77  5396.4 1729.50  5421.1 1739.22  5424.7 1739.22
#Mann=8,-1,0
  4557.5    0.07       0  4563.3   0.035       0  4674.6    0.07       0
  4988.0    0.05       0  4992.0    0.07       0  5015.9     0.1       0
  5079.8   0.035       0  5227.7    0.07       0
Bank Sta=4988,4992
Exp/Cntr=0.3,0.1

Type RM Length L Ch R = 1,4736,481,481,481
BEGIN DESCRIPTION:
Stream0291 10.0
END DESCRIPTION:
XS GIS Cut Line= 3
      1993981.83     13873732.99      1994525.00     13873625.00
      1994968.66     13873467.16
#Sta/Elev= 30
  4450.4 1718.49  4467.3 1717.62  4513.4 1710.48  4596.4 1703.69  4615.6 1699.12
  4723.0 1693.85  4739.3 1691.27  4790.4 1686.16  4917.5 1677.83  4943.0 1677.22
  4963.4 1673.21  4973.5 1666.01  4978.6 1665.46  4981.8 1662.45  4982.0 1661.95
  4985.9 1662.45  4994.0 1669.30  5019.6 1672.94  5028.4 1675.70  5128.9 1686.93
  5248.3 1699.06  5286.5 1704.88  5312.0 1707.09  5317.4 1708.90  5322.7 1708.35
  5377.1 1716.74  5433.9 1729.57  5442.5 1730.53  5466.3 1733.53  5475.1 1732.51
#Mann=10,-1,0
  4450.4   0.035       0  4739.3    0.07       0  4790.4   0.035       0
  4917.5    0.07       0  4981.8    0.05       0  4985.9    0.07       0
  5028.4     0.1       0  5128.9   0.035       0  5433.9     0.1       0
  5442.5    0.07       0
Bank Sta=4981.8,4985.9
Exp/Cntr=0.3,0.1

Type RM Length L Ch R = 1,4255,455,455,455
BEGIN DESCRIPTION:
Stream0291 9.0
END DESCRIPTION:
XS GIS Cut Line= 3
      1994206.48     13874066.90      1994625.00     13874075.00
      1995015.82     13873945.86
#Sta/Elev= 30
  4581.0 1699.94  4619.5 1695.48  4659.5 1693.95  4679.5 1691.93  4699.5 1688.58
  4742.8 1685.96  4759.5 1683.55  4809.6 1681.22  4829.6 1679.05  4878.1 1676.03
  4919.6 1672.24  4969.6 1664.99  4979.6 1658.43  4987.5 1656.52  4987.8 1656.02
  4991.6 1656.52  4997.1 1661.99  5020.7 1665.00  5047.2 1670.20  5082.1 1672.98
  5147.7 1679.17  5168.1 1679.62  5179.4 1681.60  5199.7 1682.80  5294.5 1695.53
  5326.1 1701.65  5332.8 1703.79  5338.1 1704.13  5364.5 1711.38  5411.2 1720.94
#Mann=5,-1,0
  4581.0   0.035       0  4878.1    0.07       0  4987.5    0.05       0
  4991.6    0.07       0  5082.1     0.1       0
Bank Sta=4987.5,4991.6
Exp/Cntr=0.3,0.1

Type RM Length L Ch R = 1,3800,503,503,503
BEGIN DESCRIPTION:
Stream0291 8.0
END DESCRIPTION:
XS GIS Cut Line= 3
      1994425.03     13874475.00      1994775.00     13874475.00
      1995175.03     13874074.97
#Sta/Elev= 30
  4650.0 1685.22  4700.0 1681.07  4750.0 1670.24  4780.0 1666.52  4820.0 1664.93
  4850.0 1661.88  4920.0 1659.91  4940.0 1658.36  4960.0 1658.68  4980.0 1655.94
  4990.0 1652.77  4995.3 1652.75  4995.6 1652.25  4999.6 1652.75  5003.5 1652.75
  5020.7 1656.61  5028.3 1657.24  5042.4 1660.88  5056.5 1662.00  5084.8 1662.45
  5130.3 1665.14  5169.7 1666.98  5226.2 1672.23  5254.5 1673.66  5268.7 1678.33
  5335.9 1694.37  5438.4 1719.17  5480.8 1727.70  5562.1 1756.74  5565.7 1756.74
#Mann=6,-1,0
  4650.0   0.035       0  4995.3   0.035       0  4999.6   0.035       0
  5020.7     0.1       0  5130.3    0.07       0  5335.9     0.1       0
Bank Sta=4995.3,4999.6
Exp/Cntr=0.3,0.1

Type RM Length L Ch R = 1,3297,46,46,46
BEGIN DESCRIPTION:
Stream0291 7.0
END DESCRIPTION:
XS GIS Cut Line= 4
      1994588.56     13875063.09      1994800.06     13874945.91
      1995057.01     13874758.41      1995325.02     13874324.96
#Sta/Elev= 30
  4438.2 1685.01  4501.7 1677.64  4537.0 1677.36  4567.0 1672.08  4610.5 1668.29
  4655.8 1659.63  4675.7 1658.12  4680.0 1655.41  4698.5 1654.48  4717.6 1656.83
  4756.0 1659.91  4776.9 1657.99  4791.6 1659.84  4811.6 1658.98  4933.7 1657.74
  4981.8 1650.31  4982.1 1649.81  4986.1 1650.31  5166.7 1653.88  5173.7 1655.21
  5179.6 1658.66  5189.1 1659.88  5195.0 1664.33  5210.4 1665.78  5216.3 1670.11
  5225.5 1670.63  5252.9 1685.61  5282.8 1693.22  5378.3 1713.75  5507.7 1749.66
#Mann=7,-1,0
  4438.2   0.035       0  4655.8    0.07       0  4717.6   0.035       0
  4811.6    0.07       0  4981.8    0.05       0  4986.1    0.07       0
  5282.8     0.1       0
Bank Sta=4981.8,4986.1
Exp/Cntr=0.3,0.1

Type RM Length L Ch R = 1,3251,387,387,387
BEGIN DESCRIPTION:
Mapping XS 45442467
END DESCRIPTION:
XS GIS Cut Line= 2
      1994765.09     13875136.69      1995292.72     13874559.66
#Sta/Elev= 30
  4540.5 1665.78  4562.9 1663.92  4591.2 1663.26  4626.4 1659.07  4676.3 1655.91
  4704.7 1652.93  4775.0 1650.46  4782.4 1651.05  4839.1 1649.74  4888.5 1650.47
  4907.3 1649.30  4907.6 1648.80  4911.6 1649.30  4945.2 1651.68  4973.6 1651.64
  4987.8 1650.10  5001.9 1649.94  5016.1 1650.73  5030.3 1652.95  5072.2 1653.55
  5079.6 1652.84  5122.2 1654.02  5150.6 1658.32  5157.3 1660.72  5164.8 1661.55
  5193.1 1670.42  5228.3 1678.63  5299.2 1691.83  5320.2 1694.87  5322.4 1697.12
#Mann=4,-1,0
  4540.5    0.07       0  4907.3    0.05       0  4911.6    0.07       0
  5193.1     0.1       0
Bank Sta=4907.3,4911.6
Exp/Cntr=0.3,0.1

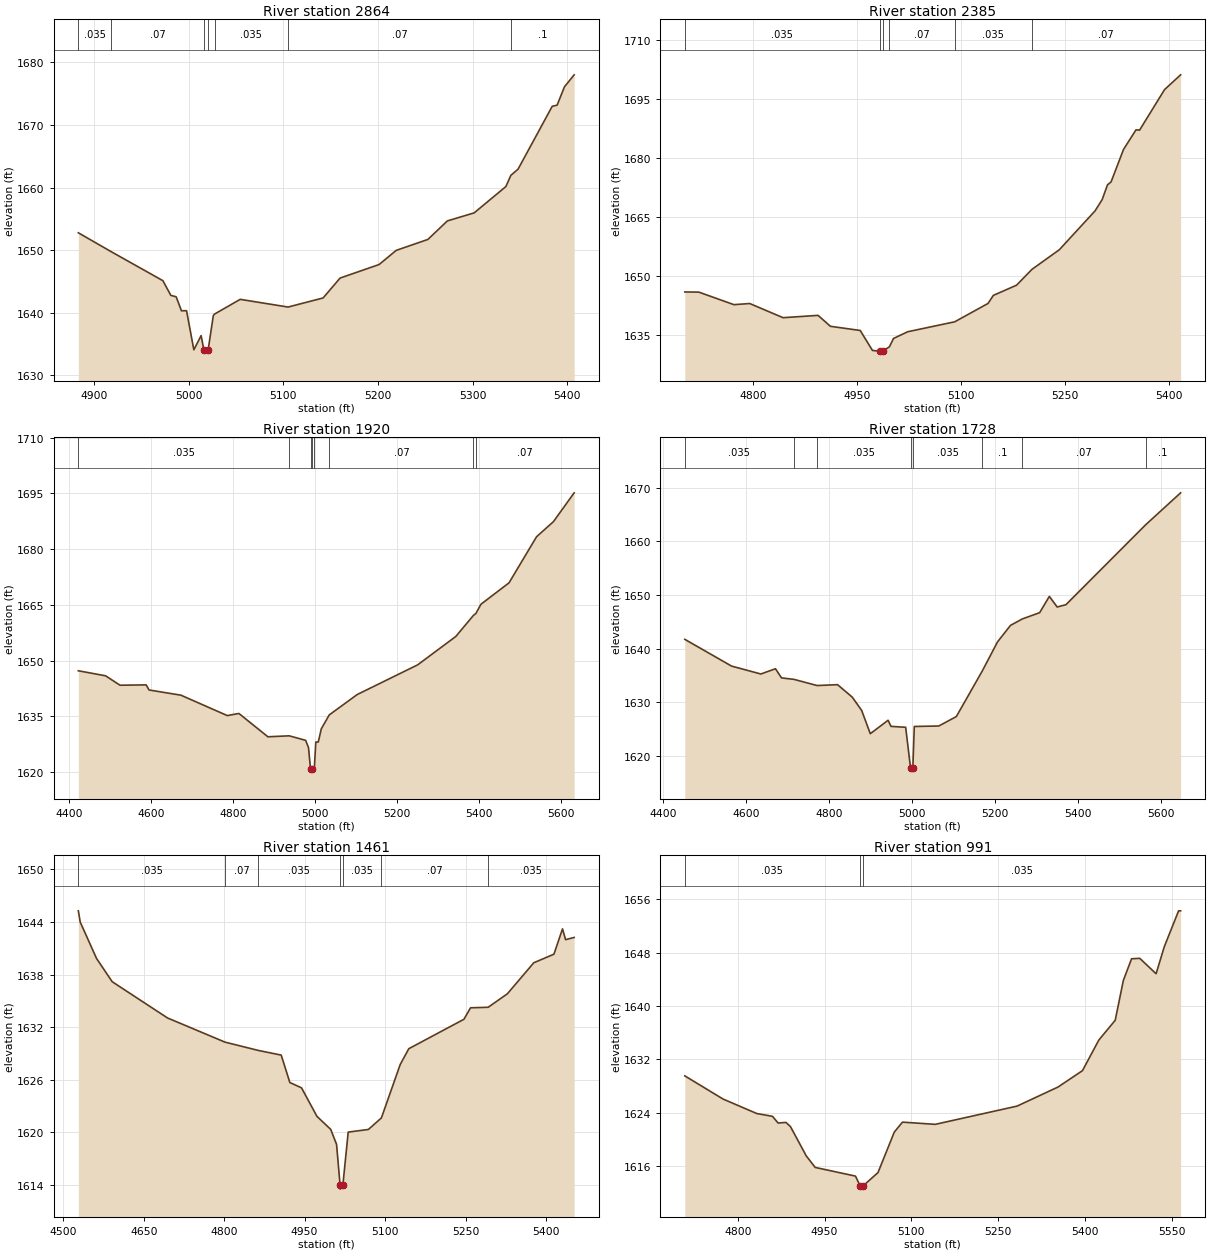
Type RM Length L Ch R = 1,2864,479,479,479
BEGIN DESCRIPTION:
Stream0291 6.0
END DESCRIPTION:
XS GIS Cut Line= 3
      1995225.01     13875174.99      1995275.00     13875075.00
      1995375.00     13874675.00
#Sta/Elev= 30
  4883.2 1652.79  4918.1 1649.76  4972.6 1645.14  4981.0 1642.79  4986.6 1642.57
  4992.2 1640.34  4997.6 1640.34  5005.3 1634.10  5013.0 1636.37  5015.9 1634.07
  5016.2 1633.57  5020.4 1634.07  5025.9 1639.58  5027.3 1639.82  5054.3 1642.16
  5104.9 1640.93  5141.9 1642.38  5159.9 1645.56  5201.1 1647.72  5219.2 1649.98
  5252.7 1651.73  5273.3 1654.69  5301.6 1655.97  5335.1 1660.17  5340.4 1661.97
  5348.0 1662.95  5384.1 1672.99  5389.3 1673.18  5397.0 1676.09  5407.3 1678.02
#Mann=7,-1,0
  4883.2   0.035       0  4918.1    0.07       0  5015.9    0.05       0
  5020.4    0.07       0  5027.3   0.035       0  5104.9    0.07       0
  5340.4     0.1       0
Bank Sta=5015.9,5020.4
Exp/Cntr=0.3,0.1

Type RM Length L Ch R = 1,2385,465,465,465
BEGIN DESCRIPTION:
Stream0291 5.0
END DESCRIPTION:
XS GIS Cut Line= 3
      1995675.00     13875275.02      1995725.00     13874975.00
      1995624.99     13874574.97
#Sta/Elev= 30
  4700.9 1646.06  4721.2 1646.02  4771.9 1642.83  4794.7 1643.12  4842.9 1639.52
  4893.5 1640.11  4911.3 1637.33  4954.4 1636.27  4972.1 1631.19  4982.5 1631.01
  4982.8 1630.51  4987.0 1631.01  4996.6 1632.12  5002.5 1634.24  5023.1 1635.95
  5090.9 1638.47  5139.1 1643.14  5146.8 1645.19  5180.3 1647.78  5202.6 1651.81
  5242.1 1656.79  5293.7 1666.66  5304.0 1669.53  5311.7 1673.28  5316.9 1674.04
  5334.9 1682.30  5352.9 1687.27  5358.1 1687.20  5394.2 1697.51  5417.4 1701.26
#Mann=6,-1,0
  4700.9   0.035       0  4982.5    0.05       0  4987.0   0.035       0
  4996.6    0.07       0  5090.9   0.035       0  5202.6    0.07       0
Bank Sta=4982.5,4987
Exp/Cntr=0.3,0.1

Type RM Length L Ch R = 1,1920,192,192,192
BEGIN DESCRIPTION:
Stream0291 4.0
END DESCRIPTION:
XS GIS Cut Line= 4
      1995770.71     13875444.63      1996175.00     13875025.00
      1996175.00     13874925.00      1995973.72     13874438.27
#Sta/Elev= 30
  4422.0 1647.24  4488.5 1645.89  4523.7 1643.35  4587.5 1643.44  4594.5 1642.07
  4672.2 1640.67  4785.4 1635.17  4813.7 1635.74  4884.4 1629.46  4936.4 1629.72
  4976.5 1628.50  4983.5 1626.52  4988.4 1620.71  4988.7 1620.21  4993.0 1620.71
  4997.8 1621.21  5001.2 1628.04  5007.2 1628.04  5014.7 1631.62  5034.0 1635.35
  5102.2 1640.84  5249.7 1648.84  5342.8 1656.49  5385.8 1662.17  5391.6 1662.66
  5404.0 1665.16  5472.6 1670.94  5539.7 1683.35  5580.8 1687.41  5631.4 1695.18
#Mann=8,-1,0
  4422.0   0.035       0  4936.4    0.07       0  4988.4   0.035       0
  4993.0    0.07       0  4997.8   0.035       0  5034.0    0.07       0
  5385.8     0.1       0  5391.6    0.07       0
Bank Sta=4988.4,4993
Exp/Cntr=0.3,0.1

Type RM Length L Ch R = 1,1728,267,267,267
BEGIN DESCRIPTION:
Mapping XS 87e5740c
END DESCRIPTION:
XS GIS Cut Line= 3
      1995874.94     13875491.74      1996348.00     13875131.52
      1996916.59     13874936.20
#Sta/Elev= 30
  4452.3 1641.75  4565.0 1636.76  4635.7 1635.28  4671.0 1636.26  4685.6 1634.55
  4715.6 1634.28  4771.2 1633.13  4820.7 1633.29  4856.1 1630.97  4878.9 1628.48
  4899.7 1624.14  4942.6 1626.65  4949.6 1625.51  4985.0 1625.34  4996.9 1617.66
  4997.3 1617.16  5002.2 1617.66  5005.8 1625.49  5064.9 1625.58  5107.2 1627.34
  5169.5 1635.81  5206.5 1641.27  5237.8 1644.35  5266.6 1645.56  5308.1 1646.72
  5331.5 1649.76  5350.4 1647.78  5371.5 1648.21  5563.5 1663.10  5648.1 1669.08
#Mann=8,-1,0
  4452.3   0.035       0  4715.6    0.07       0  4771.2   0.035       0
  4996.9   0.035       0  5002.2   0.035       0  5169.5     0.1       0
  5266.6    0.07       0  5563.5     0.1       0
Bank Sta=4996.9,5002.2
Exp/Cntr=0.3,0.1

Type RM Length L Ch R = 1,1461,470,470,470
BEGIN DESCRIPTION:
Stream0291 3.0
END DESCRIPTION:
XS GIS Cut Line= 3
      1995915.34     13875650.77      1996325.00     13875425.00
      1996723.63     13875202.04
#Sta/Elev= 30
  4528.1 1645.28  4531.6 1644.00  4562.0 1639.85  4591.2 1637.19  4694.4 1633.05
  4801.6 1630.29  4863.9 1629.34  4906.4 1628.81  4922.5 1625.68  4944.3 1625.07
  4973.0 1621.82  4998.7 1620.33  5009.6 1618.62  5016.1 1614.01  5016.5 1613.51
  5021.4 1614.01  5031.3 1620.02  5068.9 1620.32  5093.2 1621.64  5128.3 1627.74
  5144.3 1629.54  5247.1 1632.90  5259.4 1634.21  5292.3 1634.27  5328.1 1635.81
  5377.3 1639.35  5414.9 1640.33  5430.9 1643.22  5436.6 1641.99  5452.6 1642.24
#Mann=7,-1,0
  4528.1   0.035       0  4801.6    0.07       0  4863.9   0.035       0
  5016.1   0.035       0  5021.4   0.035       0  5093.2    0.07       0
  5292.3   0.035       0
Bank Sta=5016.1,5021.4
Exp/Cntr=0.3,0.1

Type RM Length L Ch R = 1,991,449,449,449
BEGIN DESCRIPTION:
Stream0291 2.0
END DESCRIPTION:
XS GIS Cut Line= 3
      1996375.01     13875874.99      1996625.00     13875725.00
      1997024.99     13875325.01
#Sta/Elev= 30
  4708.4 1629.55  4774.5 1626.08  4832.8 1623.91  4860.0 1623.49  4869.7 1622.49
  4883.3 1622.58  4891.1 1621.95  4918.3 1617.58  4933.8 1615.84  5003.5 1614.54
  5011.4 1613.09  5011.8 1612.59  5016.4 1612.59  5016.8 1613.09  5042.4 1615.07
  5070.6 1621.13  5084.8 1622.62  5141.4 1622.29  5282.8 1625.02  5353.5 1627.87
  5395.9 1630.33  5424.2 1634.91  5452.5 1637.87  5466.6 1643.84  5480.8 1647.08
  5494.9 1647.15  5523.2 1644.84  5537.3 1648.87  5562.1 1654.26  5565.6 1654.26
#Mann=3,-1,0
  4708.4   0.035       0  5011.4   0.035       0  5016.8   0.035       0
Bank Sta=5011.4,5016.8
Exp/Cntr=0.3,0.1

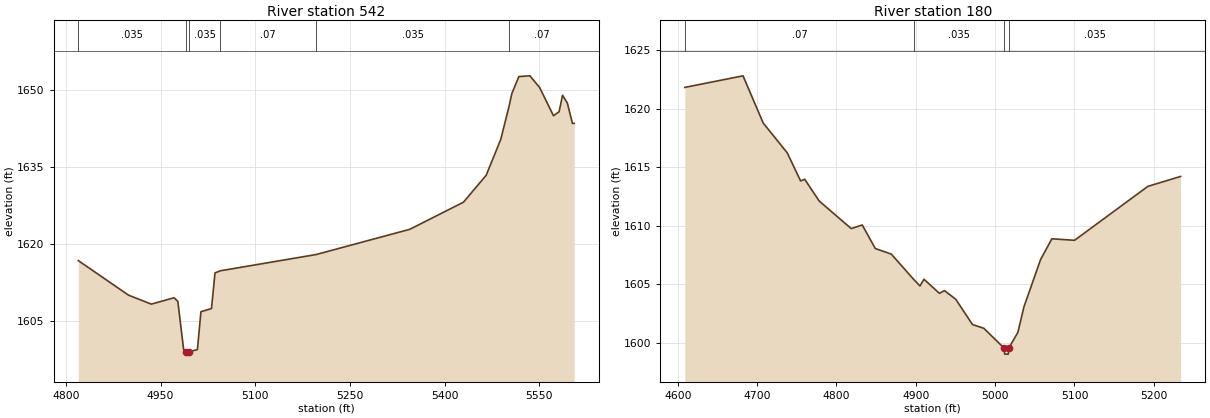
Type RM Length L Ch R = 1,542,362,362,362
BEGIN DESCRIPTION:
Stream0291 1.0
END DESCRIPTION:
XS GIS Cut Line= 4
      1996775.00     13876125.00      1996925.00     13876025.00
      1996975.00     13875925.00      1997178.43     13875475.14
#Sta/Elev= 30
  4819.6 1616.77  4899.2 1610.06  4935.3 1608.32  4971.3 1609.56  4977.3 1608.86
  4986.4 1599.57  4989.6 1599.11  4990.1 1598.61  4995.1 1599.11  5008.3 1599.47
  5013.9 1606.85  5030.6 1607.46  5036.2 1614.38  5044.5 1614.79  5196.4 1617.95
  5344.9 1622.85  5430.0 1628.12  5466.0 1633.35  5489.1 1640.32  5502.2 1646.73
  5506.7 1649.24  5517.8 1652.52  5535.3 1652.66  5550.7 1650.39  5572.6 1644.92
  5581.5 1645.67  5587.0 1648.89  5594.6 1647.39  5602.7 1643.42  5605.4 1643.42
#Mann=6,-1,0
  4819.6   0.035       0  4989.6   0.035       0  4995.1   0.035       0
  5044.5    0.07       0  5196.4   0.035       0  5502.2    0.07       0
Bank Sta=4989.6,4995.1
Exp/Cntr=0.3,0.1

Type RM Length L Ch R = 1,180,0,0,0
BEGIN DESCRIPTION:
Stream0291 0.0
END DESCRIPTION:
XS GIS Cut Line= 3
      1996677.09     13876439.80      1996987.13     13876397.91
      1997226.44     13876197.50
#Sta/Elev= 30
  4608.8 1621.82  4682.2 1622.81  4707.6 1618.78  4737.9 1616.23  4754.8 1613.82
  4759.9 1613.97  4778.2 1612.11  4818.6 1609.75  4832.5 1610.06  4848.9 1608.05
  4869.1 1607.57  4897.7 1605.38  4905.2 1604.85  4910.3 1605.42  4929.7 1604.22
  4936.2 1604.45  4950.5 1603.70  4971.4 1601.55  4985.7 1601.23  5011.5 1599.52
  5012.0 1599.02  5016.6 1599.02  5017.0 1599.52  5028.6 1600.87  5036.3 1603.06
  5057.2 1607.09  5071.5 1608.88  5100.1 1608.75  5192.5 1613.36  5233.8 1614.21
#Mann=4,-1,0
  4608.8    0.07       0  4897.7   0.035       0  5011.5   0.035       0
  5017.0   0.035       0
Bank Sta=5011.5,5017
Exp/Cntr=0.3,0.1

Chan Stop Cuts=-1