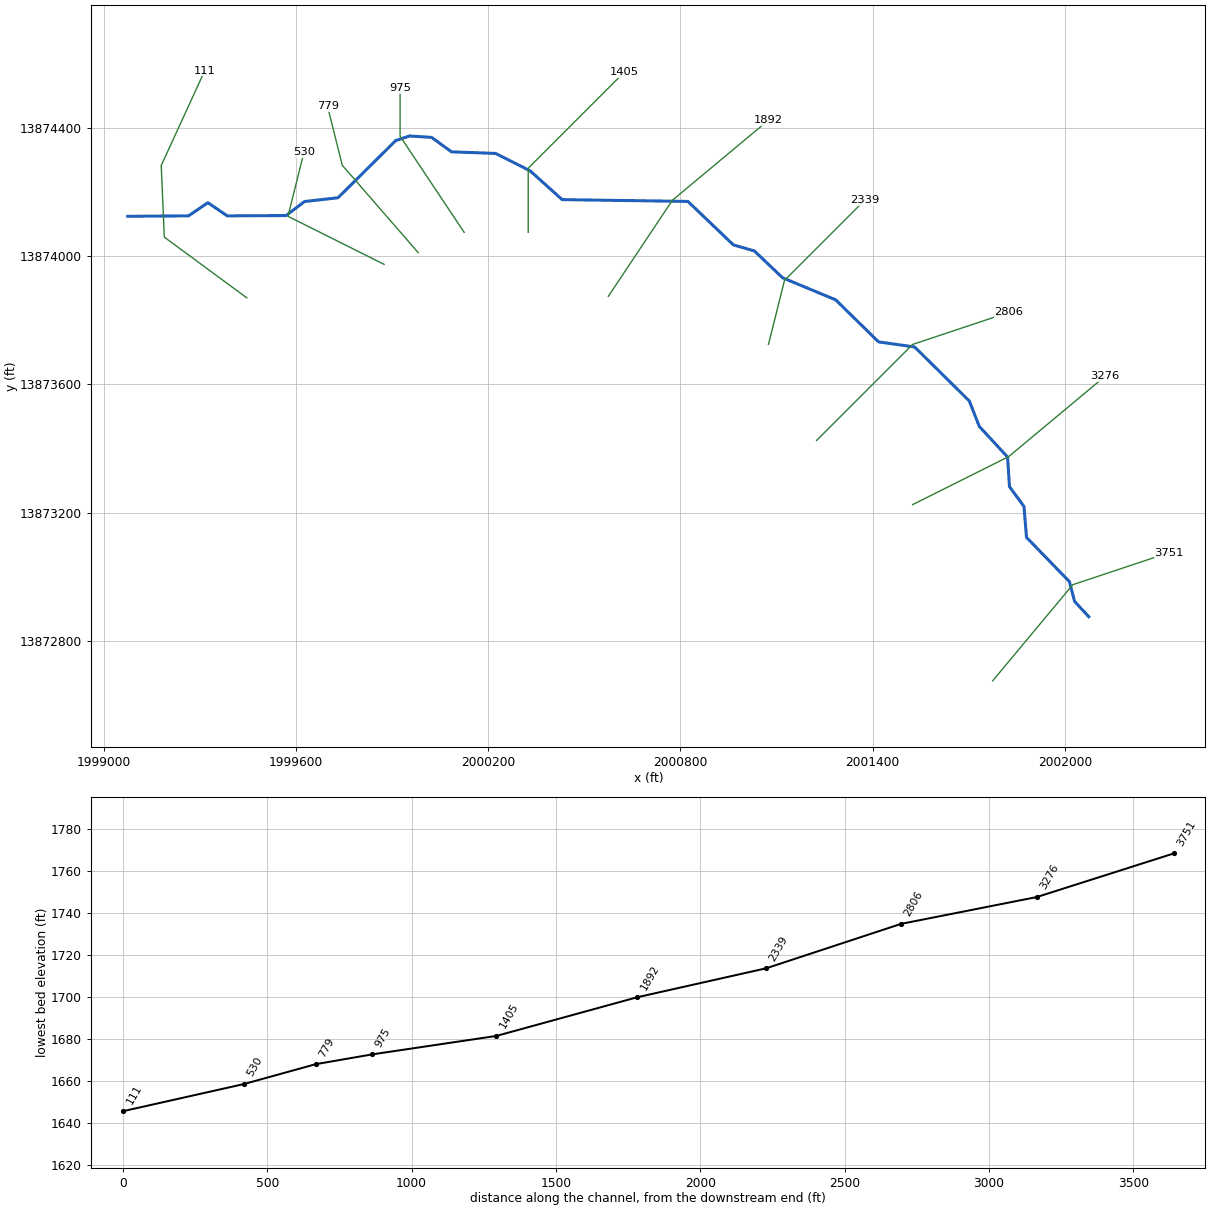
--- Stream0293.prj (project) ---

Proj Title=Stream0293 Base Level Engineering
Current Plan=p01
Default Exp/Contr=0.3,0.1
English Units
Geom File=g01
Flow File=f01
Plan File=p01
BEGIN DESCRIPTION:
Stream0293
END DESCRIPTION:

--- Stream0293.p01 (plan) ---

Plan Title=Multiple Run
Short Identifier=Multiple
Geom File=g01
Flow File=f01
Subcritical Flow
K Sum by GR= 0
Std Step Tol= 0.01
Critical Tol= 0.01
Num of Std Step Trials= 20
Max Error Tol= 0.3
Flow Tol Ratio= 0.001
Split Flow NTrial= 30
Split Flow Tol= 0.02
Split Flow Ratio= 0.02
Log Output Level= 0
Friction Slope Method= 1
Unsteady Friction Slope Method= 2
Unsteady Bridges Friction Slope Method= 1
Parabolic Critical Depth
Global Vel Dist=  1 , 1 , 1
Global Log Level= 0
CheckData=True
Encroach Param= -1, 0, 0, 0
BEGIN DESCRIPTION:
Multiple Run
END DESCRIPTION:

--- Stream0293.f01 (steady flow) ---

Flow Title=Multiple
Number of Profiles=7
Profile Names=10-year,25-year,50-year,1pct_min,100-year,1pct_plu,500-year
River Rch & RM= Stream0293,Reach-1,3751
     296     466     617     399     796    1589    1305
River Rch & RM= Stream0293,Reach-1,2806
     514     841    1142     756    1508    3009    2593
Boundary for River Rch & Prof#=Stream0293,Reach-1,1
Up Type=0
Dn Type=3
Dn Slope=0.005
Boundary for River Rch & Prof#=Stream0293,Reach-1,2
Up Type=0
Dn Type=3
Dn Slope=0.005
Boundary for River Rch & Prof#=Stream0293,Reach-1,3
Up Type=0
Dn Type=3
Dn Slope=0.005
Boundary for River Rch & Prof#=Stream0293,Reach-1,4
Up Type=0
Dn Type=3
Dn Slope=0.005
Boundary for River Rch & Prof#=Stream0293,Reach-1,5
Up Type=0
Dn Type=3
Dn Slope=0.005
Boundary for River Rch & Prof#=Stream0293,Reach-1,6
Up Type=0
Dn Type=3
Dn Slope=0.005
Boundary for River Rch & Prof#=Stream0293,Reach-1,7
Up Type=0
Dn Type=3
Dn Slope=0.005

--- Stream0293.g01 (geometry) ---

Geom Title=Existing Conditions

River Reach=Stream0293,Reach-1
Reach XY= 30
      2002075.00     13872875.00      2002030.71     13872922.65
      2002014.30     13872984.71      2001880.52     13873122.57
      2001872.64     13873219.02      2001827.36     13873280.98
      2001821.38     13873373.50      2001733.18     13873468.96
      2001701.99     13873548.47      2001531.17     13873717.14
      2001418.83     13873732.86      2001284.68     13873864.23
      2001118.95     13873933.16      2001031.04     13874016.82
      2000965.32     13874035.78      2000823.54     13874171.46
      2000430.86     13874177.06      2000331.05     13874266.84
      2000223.44     13874321.24      2000085.51     13874326.23
      2000023.40     13874371.30      1999954.92     13874375.67
      1999911.70     13874361.66      1999731.17     13874182.86
      1999626.60     13874171.14      1999569.06     13874127.26
      1999385.44     13874126.38      1999325.00     13874167.44
      1999264.57     13874126.37      1999075.00     13874125.00

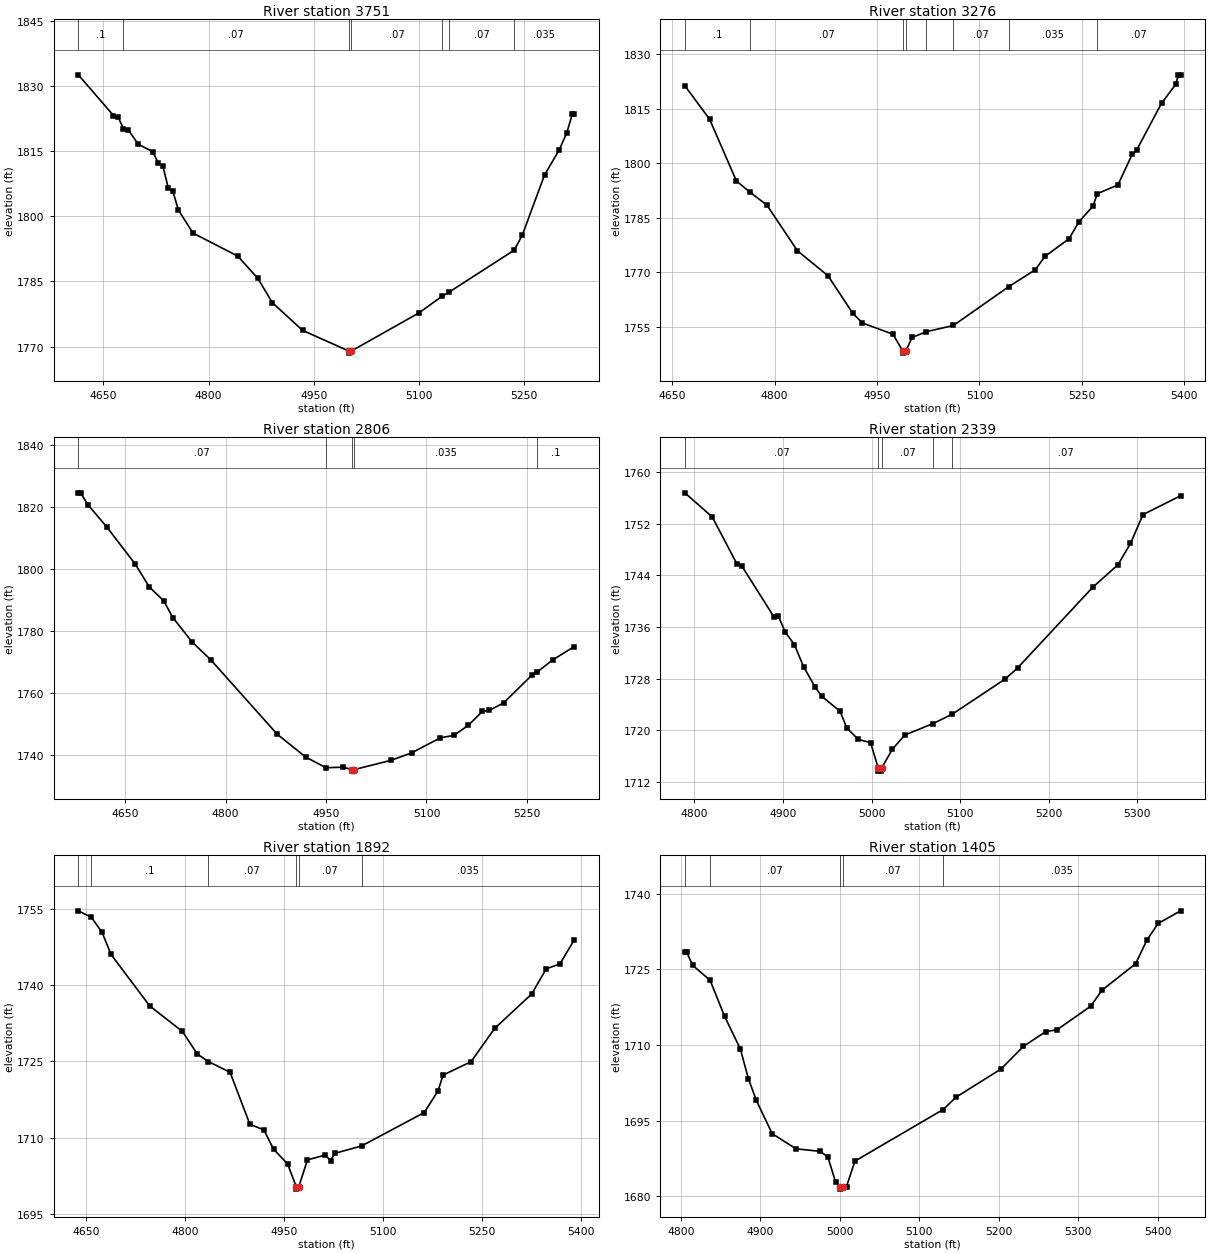
Type RM Length L Ch R = 1,3751,475,475,475
BEGIN DESCRIPTION:
Stream0293 8.0
END DESCRIPTION:
XS GIS Cut Line= 3
      2001774.99     13872674.98      2002025.00     13872975.00
      2002325.04     13873075.01
#Sta/Elev= 30
  4614.3 1832.53  4664.4 1823.17  4670.9 1822.81  4678.6 1820.17  4685.3 1819.93
  4699.6 1816.57  4720.4 1814.84  4728.2 1812.26  4734.7 1811.61  4742.5 1806.53
  4749.0 1805.76  4756.9 1801.43  4777.7 1796.12  4841.5 1790.82  4870.1 1785.71
  4890.9 1780.10  4933.9 1773.73  4999.6 1768.99  4999.8 1768.49  5003.6 1768.99
  5099.7 1777.73  5132.9 1781.59  5143.2 1782.57  5235.7 1792.19  5247.3 1795.69
  5278.9 1809.49  5300.0 1815.32  5310.5 1819.16  5318.4 1823.44  5321.1 1823.44
#Mann=7,-1,0
  4614.3     0.1       0  4678.6    0.07       0  4999.6    0.05       0
  5003.6    0.07       0  5132.9   0.035       0  5143.2    0.07       0
  5235.7   0.035       0
Bank Sta=4999.6,5003.6
Exp/Cntr=0.3,0.1

Type RM Length L Ch R = 1,3276,470,470,470
BEGIN DESCRIPTION:
Stream0293 7.0
END DESCRIPTION:
XS GIS Cut Line= 3
      2001524.96     13873224.98      2001825.00     13873375.00
      2002125.03     13873625.02
#Sta/Elev= 30
  4668.5 1821.32  4704.9 1812.05  4744.0 1795.10  4764.4 1791.92  4788.7 1788.43
  4833.5 1775.84  4878.2 1768.97  4914.5 1758.63  4928.5 1755.97  4973.2 1752.89
  4988.0 1748.17  4988.2 1747.67  4992.0 1748.17  5001.2 1751.98  5022.4 1753.58
  5061.7 1755.28  5143.0 1765.99  5181.6 1770.61  5196.0 1774.33  5231.1 1779.15
  5245.4 1783.79  5266.2 1788.15  5272.5 1791.57  5302.7 1793.98  5323.5 1802.37
  5330.0 1803.55  5366.5 1816.45  5387.3 1821.66  5391.2 1824.30  5394.5 1824.30
#Mann=8,-1,0
  4668.5     0.1       0  4764.4    0.07       0  4988.0    0.05       0
  4992.0    0.07       0  5022.4   0.035       0  5061.7    0.07       0
  5143.0   0.035       0  5272.5    0.07       0
Bank Sta=4988,4992
Exp/Cntr=0.3,0.1

Type RM Length L Ch R = 1,2806,467,467,467
BEGIN DESCRIPTION:
Stream0293 6.0
END DESCRIPTION:
XS GIS Cut Line= 3
      2001225.00     13873425.00      2001525.00     13873725.00
      2001825.01     13873825.00
#Sta/Elev= 30
  4580.1 1824.57  4583.6 1824.57  4594.2 1820.78  4622.5 1813.59  4665.0 1801.62
  4686.2 1794.20  4707.4 1789.82  4721.5 1784.29  4749.8 1776.56  4778.1 1770.70
  4877.1 1746.78  4919.5 1739.44  4949.9 1735.98  4976.1 1736.15  4988.2 1735.38
  4988.5 1734.88  4992.0 1734.88  4992.2 1735.38  5046.5 1738.33  5078.2 1740.79
  5120.3 1745.57  5141.4 1746.44  5162.5 1749.65  5183.6 1754.12  5194.1 1754.47
  5215.2 1756.86  5257.3 1765.77  5264.6 1766.70  5289.0 1770.78  5320.6 1775.00
#Mann=5,-1,0
  4580.1    0.07       0  4949.9   0.035       0  4988.2   0.035       0
  4992.2   0.035       0  5264.6     0.1       0
Bank Sta=4988.2,4992.2
Exp/Cntr=0.3,0.1

Type RM Length L Ch R = 1,2339,447,447,447
BEGIN DESCRIPTION:
Stream0293 5.0
END DESCRIPTION:
XS GIS Cut Line= 3
      2001075.01     13873725.04      2001125.00     13873925.00
      2001375.02     13874175.02
#Sta/Elev= 30
  4789.1 1756.77  4820.0 1753.05  4848.3 1745.68  4853.5 1745.44  4889.6 1737.60
  4894.7 1737.70  4902.4 1735.24  4912.8 1733.29  4923.1 1729.88  4935.9 1726.79
  4943.7 1725.27  4964.3 1722.98  4972.0 1720.38  4984.9 1718.60  4998.8 1718.12
  5007.4 1714.20  5007.6 1713.70  5011.1 1713.70  5011.4 1714.20  5023.5 1717.11
  5037.6 1719.29  5069.2 1721.06  5090.5 1722.47  5150.8 1727.96  5164.9 1729.69
  5249.8 1742.18  5278.1 1745.64  5292.2 1748.94  5306.3 1753.40  5348.8 1756.32
#Mann=5,-1,0
  4789.1    0.07       0  5007.4    0.05       0  5011.4    0.07       0
  5069.2   0.035       0  5090.5    0.07       0
Bank Sta=5007.4,5011.4
Exp/Cntr=0.3,0.1

Type RM Length L Ch R = 1,1892,487,487,487
BEGIN DESCRIPTION:
Stream0293 4.0
END DESCRIPTION:
XS GIS Cut Line= 3
      2000575.02     13873875.03      2000775.00     13874175.00
      2001074.98     13874424.98
#Sta/Elev= 30
  4638.8 1754.61  4658.6 1753.33  4674.8 1750.37  4688.3 1746.04  4746.9 1735.91
  4796.5 1730.88  4819.0 1726.45  4835.7 1724.97  4868.6 1722.86  4898.7 1712.62
  4919.7 1711.54  4934.7 1707.70  4955.7 1704.85  4968.8 1700.38  4969.0 1699.88
  4972.8 1700.38  4985.8 1705.63  5013.0 1706.59  5020.8 1705.49  5027.3 1706.92
  5067.7 1708.36  5162.7 1714.94  5183.5 1719.16  5191.3 1722.31  5233.6 1724.94
  5269.4 1731.49  5325.4 1738.24  5347.5 1743.20  5368.3 1744.18  5389.8 1748.86
#Mann=6,-1,0
  4638.8    0.07       0  4658.6     0.1       0  4835.7    0.07       0
  4968.8    0.05       0  4972.8    0.07       0  5067.7   0.035       0
Bank Sta=4968.8,4972.8
Exp/Cntr=0.3,0.1

Type RM Length L Ch R = 1,1405,430,430,430
BEGIN DESCRIPTION:
Stream0293 3.0
END DESCRIPTION:
XS GIS Cut Line= 3
      2000325.00     13874074.96      2000325.00     13874275.00
      2000624.99     13874574.99
#Sta/Elev= 30
  4804.7 1728.34  4807.2 1728.34  4814.7 1725.79  4836.6 1722.82  4854.7 1715.73
  4874.7 1709.20  4884.7 1703.37  4894.7 1699.06  4914.7 1692.45  4944.7 1689.45
  4974.7 1688.95  4984.7 1687.89  4994.7 1682.80  5000.2 1681.96  5000.5 1681.46
  5004.2 1681.96  5008.3 1681.96  5018.9 1687.01  5130.0 1697.23  5146.2 1699.67
  5202.7 1705.24  5231.0 1709.73  5259.3 1712.67  5273.4 1713.03  5315.9 1717.71
  5330.0 1720.87  5372.4 1726.12  5386.6 1730.81  5400.7 1734.09  5429.0 1736.59
#Mann=5,-1,0
  4804.7     0.1       0  4836.6    0.07       0  5000.2    0.05       0
  5004.2    0.07       0  5130.0   0.035       0
Bank Sta=5000.2,5004.2
Exp/Cntr=0.3,0.1

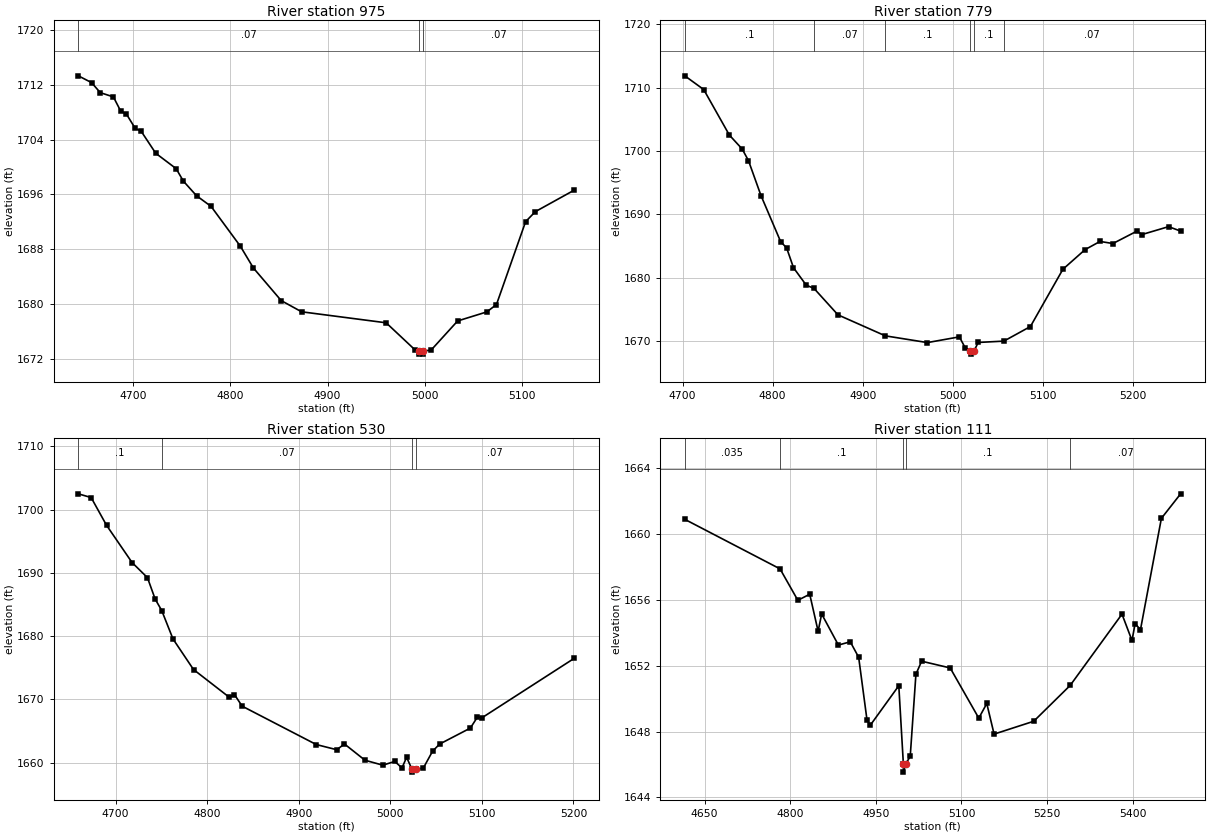
Type RM Length L Ch R = 1,975,196,196,196
BEGIN DESCRIPTION:
Stream0293 2.0
END DESCRIPTION:
XS GIS Cut Line= 3
      2000125.02     13874074.97      1999925.00     13874375.00
      1999925.00     13874525.01
#Sta/Elev= 30
  4643.3 1713.35  4656.9 1712.36  4665.9 1710.89  4679.4 1710.27  4686.9 1708.20
  4692.9 1707.74  4701.9 1705.66  4707.9 1705.27  4723.0 1702.03  4744.0 1699.78
  4751.5 1697.95  4765.0 1695.82  4780.0 1694.26  4810.1 1688.45  4823.6 1685.25
  4852.2 1680.49  4873.2 1678.85  4960.3 1677.24  4990.4 1673.23  4994.4 1673.16
  4994.6 1672.66  4998.1 1672.66  4998.4 1673.16  5006.4 1673.22  5033.9 1677.51
  5063.9 1678.83  5073.9 1679.91  5103.9 1692.03  5113.9 1693.49  5153.9 1696.63
#Mann=3,-1,0
  4643.3    0.07       0  4994.4    0.05       0  4998.4    0.07       0
Bank Sta=4994.4,4998.4
Exp/Cntr=0.3,0.1

Type RM Length L Ch R = 1,779,249,249,249
BEGIN DESCRIPTION:
Mapping XS d2626dc7
END DESCRIPTION:
XS GIS Cut Line= 3
      1999981.53     13874011.62      1999744.48     13874284.43
      1999698.55     13874467.96
#Sta/Elev= 30
  4702.5 1711.84  4723.5 1709.68  4752.0 1702.50  4766.2 1700.31  4773.2 1698.48
  4787.1 1692.97  4808.9 1685.72  4815.6 1684.71  4823.2 1681.60  4837.4 1678.84
  4845.9 1678.35  4872.6 1674.17  4925.2 1670.86  4971.9 1669.80  5007.4 1670.70
  5014.0 1668.94  5019.7 1668.48  5019.9 1667.98  5023.7 1668.48  5028.3 1669.82
  5056.8 1670.03  5086.3 1672.33  5122.4 1681.36  5147.0 1684.45  5163.6 1685.74
  5177.9 1685.41  5204.8 1687.38  5210.0 1686.82  5239.7 1688.07  5253.1 1687.37
#Mann=6,-1,0
  4702.5     0.1       0  4845.9    0.07       0  4925.2     0.1       0
  5019.7    0.05       0  5023.7     0.1       0  5056.8    0.07       0
Bank Sta=5019.7,5023.7
Exp/Cntr=0.3,0.1

Type RM Length L Ch R = 1,530,419,419,419
BEGIN DESCRIPTION:
Stream0293 1.0
END DESCRIPTION:
XS GIS Cut Line= 3
      1999875.00     13873975.00      1999575.00     13874125.00
      1999625.01     13874325.03
#Sta/Elev= 30
  4659.2 1702.48  4673.2 1701.89  4690.0 1697.51  4717.9 1691.62  4734.7 1689.23
  4743.1 1685.85  4750.3 1684.03  4762.6 1679.54  4785.0 1674.71  4824.1 1670.32
  4829.7 1670.76  4838.1 1668.92  4919.1 1662.85  4941.5 1662.03  4949.9 1662.94
  4972.3 1660.37  4991.8 1659.59  5004.9 1660.18  5012.7 1659.15  5017.8 1660.83
  5023.5 1658.99  5023.8 1658.49  5027.5 1658.99  5035.8 1659.07  5046.2 1661.81
  5053.9 1662.93  5087.4 1665.45  5095.1 1667.18  5100.3 1667.10  5200.8 1676.47
#Mann=4,-1,0
  4659.2     0.1       0  4750.3    0.07       0  5023.5    0.05       0
  5027.5    0.07       0
Bank Sta=5023.5,5027.5
Exp/Cntr=0.3,0.1

Type RM Length L Ch R = 1,111,0,0,0
BEGIN DESCRIPTION:
Stream0293 0.0
END DESCRIPTION:
XS GIS Cut Line= 4
      1999446.47     13873870.46      1999189.03     13874059.94
      1999179.32     13874283.53      1999314.89     13874578.85
#Sta/Elev= 30
  4615.4 1660.90  4782.2 1657.89  4813.4 1655.98  4834.2 1656.35  4848.9 1654.10
  4855.1 1655.15  4884.4 1653.26  4905.2 1653.46  4919.9 1652.52  4934.5 1648.71
  4940.1 1648.38  4990.2 1650.79  4998.2 1646.04  4998.4 1645.54  5002.2 1646.04
  5010.2 1646.49  5020.2 1651.49  5030.2 1652.28  5080.2 1651.87  5130.3 1648.82
  5144.3 1649.71  5157.1 1647.85  5226.5 1648.63  5290.4 1650.81  5381.1 1655.14
  5398.6 1653.54  5404.1 1654.56  5413.5 1654.20  5450.1 1660.96  5483.8 1662.45
#Mann=5,-1,0
  4615.4   0.035       0  4782.2     0.1       0  4998.2    0.05       0
  5002.2     0.1       0  5290.4    0.07       0
Bank Sta=4998.2,5002.2
Exp/Cntr=0.3,0.1

Chan Stop Cuts=-1