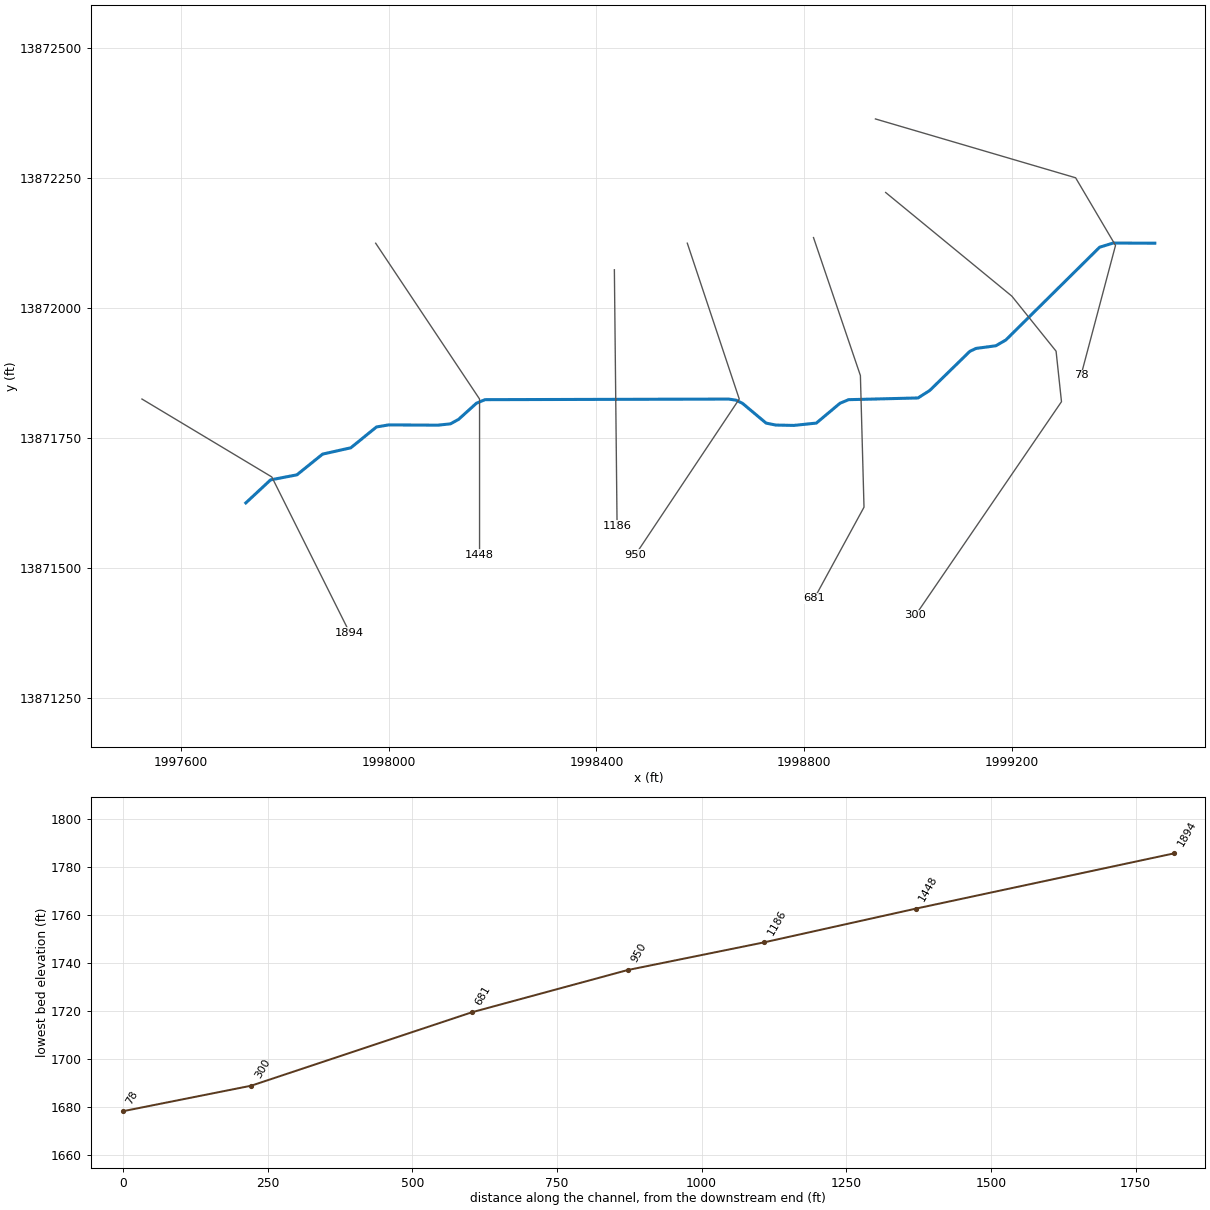
--- Stream0302.prj (project) ---

Proj Title=Stream0302 Base Level Engineering
Current Plan=p01
Default Exp/Contr=0.3,0.1
English Units
Geom File=g01
Flow File=f01
Plan File=p01
BEGIN DESCRIPTION:
Stream0302
END DESCRIPTION:

--- Stream0302.p01 (plan) ---

Plan Title=Multiple Run
Short Identifier=Multiple
Geom File=g01
Flow File=f01
Subcritical Flow
K Sum by GR= 0
Std Step Tol= 0.01
Critical Tol= 0.01
Num of Std Step Trials= 20
Max Error Tol= 0.3
Flow Tol Ratio= 0.001
Split Flow NTrial= 30
Split Flow Tol= 0.02
Split Flow Ratio= 0.02
Log Output Level= 0
Friction Slope Method= 1
Unsteady Friction Slope Method= 2
Unsteady Bridges Friction Slope Method= 1
Parabolic Critical Depth
Global Vel Dist=  1 , 1 , 1
Global Log Level= 0
CheckData=True
Encroach Param= -1, 0, 0, 0
BEGIN DESCRIPTION:
Multiple Run
END DESCRIPTION:

--- Stream0302.f01 (steady flow) ---

Flow Title=Multiple
Number of Profiles=7
Profile Names=10-year,25-year,50-year,1pct_min,100-year,1pct_plu,500-year
River Rch & RM= Stream0302,Reach-1,1894
     229     353     462     296     590    1177     945
Boundary for River Rch & Prof#=Stream0302,Reach-1,1
Up Type=0
Dn Type=3
Dn Slope=0.005
Boundary for River Rch & Prof#=Stream0302,Reach-1,2
Up Type=0
Dn Type=3
Dn Slope=0.005
Boundary for River Rch & Prof#=Stream0302,Reach-1,3
Up Type=0
Dn Type=3
Dn Slope=0.005
Boundary for River Rch & Prof#=Stream0302,Reach-1,4
Up Type=0
Dn Type=3
Dn Slope=0.005
Boundary for River Rch & Prof#=Stream0302,Reach-1,5
Up Type=0
Dn Type=3
Dn Slope=0.005
Boundary for River Rch & Prof#=Stream0302,Reach-1,6
Up Type=0
Dn Type=3
Dn Slope=0.005
Boundary for River Rch & Prof#=Stream0302,Reach-1,7
Up Type=0
Dn Type=3
Dn Slope=0.005

--- Stream0302.g01 (geometry) ---

Geom Title=Existing Conditions

River Reach=Stream0302,Reach-1
Reach XY= 30
      1997725.00     13871625.00      1997772.64     13871669.33
      1997823.33     13871679.04      1997872.80     13871718.93
      1997927.18     13871731.12      1997976.56     13871771.24
      1997999.92     13871775.19      1998095.13     13871774.68
      1998119.06     13871777.27      1998134.64     13871785.86
      1998168.94     13871816.86      1998185.50     13871823.78
      1998654.97     13871824.93      1998669.06     13871822.74
      1998681.06     13871816.85      1998726.60     13871778.70
      1998745.10     13871774.91      1998780.03     13871774.19
      1998823.40     13871778.70      1998868.94     13871816.85
      1998885.51     13871823.77      1999019.14     13871827.07
      1999041.75     13871841.46      1999118.96     13871916.82
      1999131.05     13871922.46      1999168.95     13871927.53
      1999188.21     13871938.63      1999368.78     13872117.26
      1999394.86     13872125.33      1999475.00     13872125.00

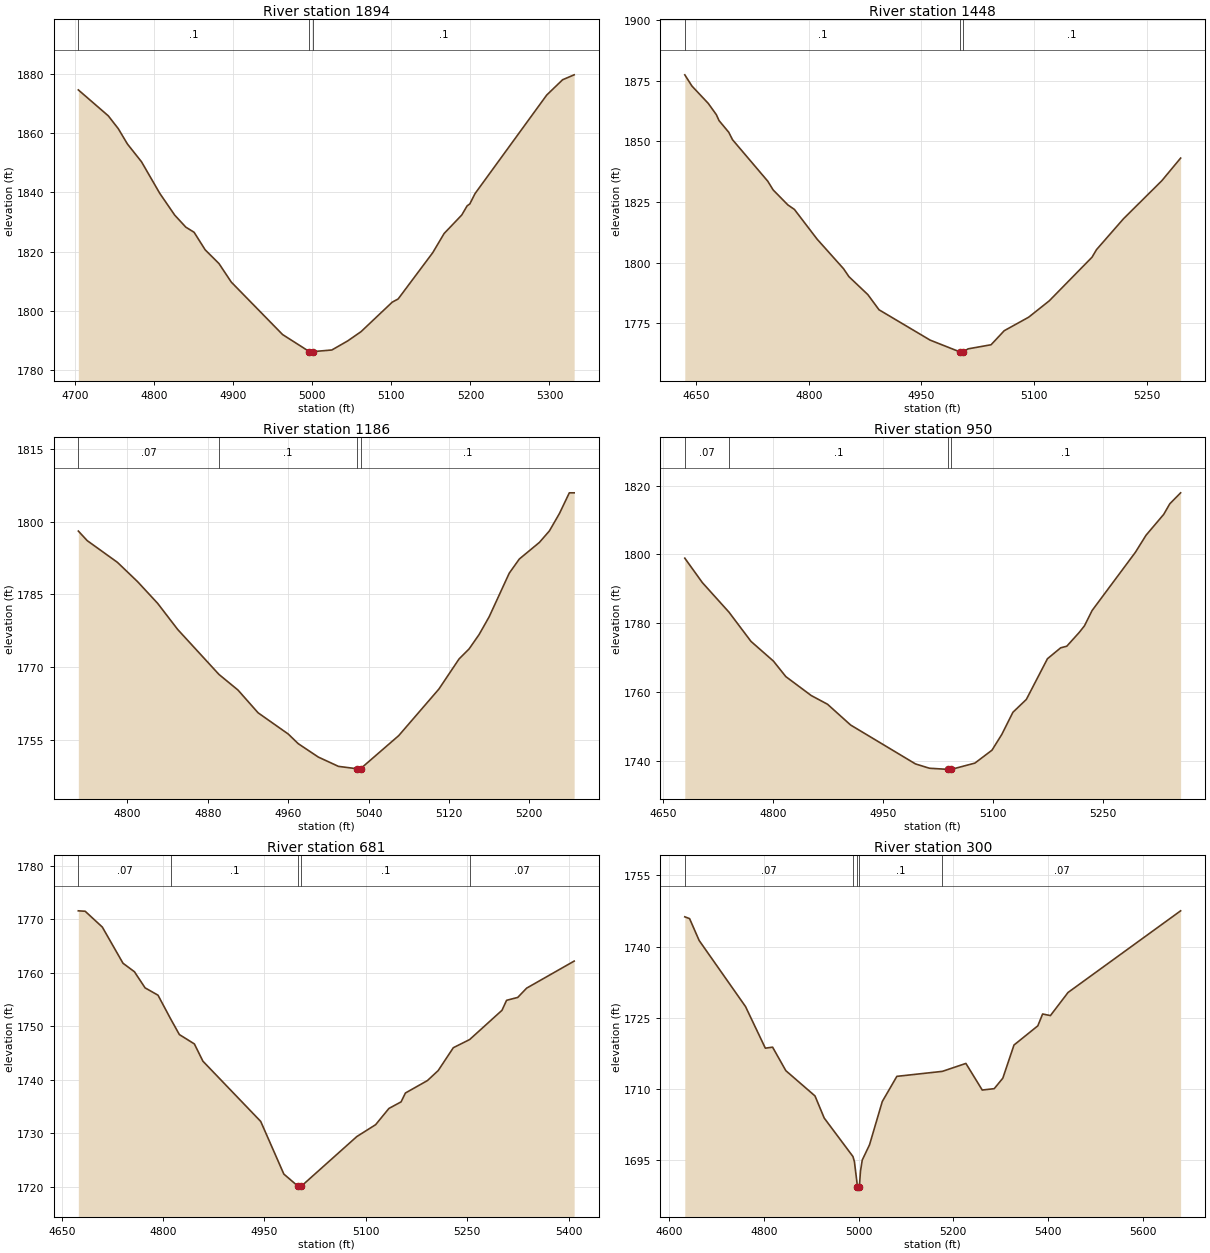
Type RM Length L Ch R = 1,1894,446,446,446
BEGIN DESCRIPTION:
Stream0302 3.0
END DESCRIPTION:
XS GIS Cut Line= 3
      1997524.98     13871825.01      1997775.00     13871675.00
      1997925.01     13871374.98
#Sta/Elev= 30
  4704.2 1874.68  4742.1 1865.91  4754.7 1861.58  4766.3 1856.38  4784.1 1850.37
  4807.2 1839.69  4826.1 1832.33  4840.1 1828.27  4850.6 1826.53  4864.6 1820.60
  4882.1 1815.93  4897.7 1809.66  4962.5 1791.94  4996.4 1786.16  4996.6 1785.66
  5000.4 1786.16  5024.8 1786.72  5044.9 1789.80  5061.7 1792.92  5101.2 1802.91
  5108.6 1803.97  5152.3 1819.60  5166.8 1826.13  5189.1 1832.38  5195.9 1835.49
  5199.2 1836.10  5205.9 1839.63  5296.5 1872.94  5316.6 1878.12  5331.2 1879.78
#Mann=3,-1,0
  4704.2     0.1       0  4996.4    0.05       0  5000.4     0.1       0
Bank Sta=4996.4,5000.4
Exp/Cntr=0.3,0.1

Type RM Length L Ch R = 1,1448,262,262,262
BEGIN DESCRIPTION:
Stream0302 2.0
END DESCRIPTION:
XS GIS Cut Line= 3
      1997975.01     13872124.98      1998175.00     13871825.00
      1998175.00     13871525.03
#Sta/Elev= 30
  4634.9 1877.41  4644.4 1872.79  4666.1 1865.65  4676.9 1861.00  4680.5 1858.55
  4693.5 1853.70  4698.5 1850.65  4745.4 1833.56  4752.6 1829.95  4772.2 1823.77
  4780.9 1821.92  4811.2 1809.64  4846.4 1797.45  4853.6 1794.17  4878.8 1786.77
  4893.6 1780.54  4961.7 1768.03  5001.4 1763.16  5001.6 1762.66  5005.4 1763.16
  5012.4 1764.43  5042.9 1766.11  5060.4 1771.90  5092.9 1777.46  5120.4 1784.22
  5177.4 1802.22  5183.4 1805.35  5219.4 1818.10  5270.4 1833.76  5295.4 1843.08
#Mann=3,-1,0
  4634.9     0.1       0  5001.4    0.05       0  5005.4     0.1       0
Bank Sta=5001.4,5005.4
Exp/Cntr=0.3,0.1

Type RM Length L Ch R = 1,1186,236,236,236
BEGIN DESCRIPTION:
Stream0302 A
END DESCRIPTION:
XS GIS Cut Line= 2
      1998434.57     13872073.89      1998439.78     13871580.42
#Sta/Elev= 30
  4751.1 1798.05  4760.0 1796.07  4790.0 1791.61  4810.0 1787.65  4830.0 1783.18
  4850.0 1777.79  4891.1 1768.53  4910.0 1765.32  4930.0 1760.64  4960.0 1756.27
  4970.0 1754.28  4990.0 1751.52  5010.0 1749.61  5028.0 1749.13  5028.3 1748.63
  5031.8 1748.63  5032.0 1749.13  5070.0 1755.94  5110.0 1765.53  5130.0 1771.71
  5140.0 1773.78  5150.0 1776.75  5160.0 1780.40  5180.0 1789.38  5190.0 1792.29
  5210.0 1795.71  5220.0 1798.09  5230.0 1801.68  5239.8 1805.92  5244.6 1805.92
#Mann=4,-1,0
  4751.1    0.07       0  4891.1     0.1       0  5028.0    0.05       0
  5032.0     0.1       0
Bank Sta=5028,5032
Exp/Cntr=0.3,0.1

Type RM Length L Ch R = 1,950,269,269,269
BEGIN DESCRIPTION:
Stream0302 1.0
END DESCRIPTION:
XS GIS Cut Line= 3
      1998574.98     13872125.05      1998675.00     13871825.00
      1998475.02     13871525.03
#Sta/Elev= 30
  4679.5 1798.91  4703.5 1791.81  4739.8 1783.24  4769.9 1774.74  4800.5 1769.03
  4817.4 1764.53  4852.1 1759.03  4874.3 1756.51  4905.9 1750.47  4994.4 1739.18
  5013.4 1737.93  5039.1 1737.59  5039.4 1737.09  5043.1 1737.59  5075.5 1739.42
  5098.8 1743.17  5112.2 1747.74  5127.4 1754.18  5145.7 1757.90  5174.5 1769.71
  5192.6 1772.89  5200.9 1773.35  5217.8 1777.33  5225.0 1779.26  5235.5 1783.72
  5294.6 1800.63  5309.1 1805.57  5333.2 1811.62  5341.5 1814.69  5356.3 1817.88
#Mann=4,-1,0
  4679.5    0.07       0  4739.8     0.1       0  5039.1    0.05       0
  5043.1     0.1       0
Bank Sta=5039.1,5043.1
Exp/Cntr=0.3,0.1

Type RM Length L Ch R = 1,681,381,381,381
BEGIN DESCRIPTION:
Stream0302 4.0
END DESCRIPTION:
XS GIS Cut Line= 4
      1998817.97     13872135.84      1998908.24     13871870.24
      1998915.18     13871616.77      1998819.72     13871441.47
#Sta/Elev= 30
  4674.6 1771.61  4684.7 1771.53  4710.1 1768.57  4740.7 1761.80  4757.6 1760.21
  4773.4 1757.19  4792.5 1755.82  4811.0 1751.43  4824.1 1748.45  4846.3 1746.70
  4859.0 1743.46  4944.5 1732.19  4978.7 1722.34  5000.1 1720.02  5000.4 1719.52
  5004.1 1720.02  5086.7 1729.36  5114.5 1731.58  5134.2 1734.62  5152.2 1735.85
  5158.6 1737.51  5191.2 1739.84  5207.1 1741.71  5229.5 1745.99  5253.7 1747.52
  5301.5 1752.99  5308.3 1754.86  5324.8 1755.40  5338.0 1757.14  5408.3 1762.20
#Mann=5,-1,0
  4674.6    0.07       0  4811.0     0.1       0  5000.1    0.05       0
  5004.1     0.1       0  5253.7    0.07       0
Bank Sta=5000.1,5004.1
Exp/Cntr=0.3,0.1

Type RM Length L Ch R = 1,300,222,222,222
BEGIN DESCRIPTION:
Stream0302 0.0
END DESCRIPTION:
XS GIS Cut Line= 5
      1998956.86     13872222.66      1999199.90     13872023.02
      1999284.97     13871917.12      1999295.39     13871819.89
      1999014.16     13871408.47
#Sta/Elev= 30
  4633.3 1746.27  4643.4 1745.89  4663.6 1741.29  4761.5 1727.38  4803.3 1718.63
  4818.6 1718.84  4846.6 1713.89  4908.1 1708.58  4927.6 1703.92  4988.2 1695.83
  4991.3 1694.75  4997.8 1689.47  4998.1 1688.97  5001.8 1689.47  5004.0 1692.67
  5007.8 1695.08  5023.2 1698.30  5050.1 1707.40  5080.9 1712.70  5176.9 1713.75
  5226.6 1715.42  5261.1 1709.82  5286.4 1710.11  5304.5 1712.31  5328.1 1719.29
  5378.4 1723.33  5388.5 1725.82  5405.0 1725.49  5442.2 1730.35  5679.8 1747.53
#Mann=5,-1,0
  4633.3    0.07       0  4988.2     0.1       0  4997.8    0.05       0
  5001.8     0.1       0  5176.9    0.07       0
Bank Sta=4997.8,5001.8
Exp/Cntr=0.3,0.1

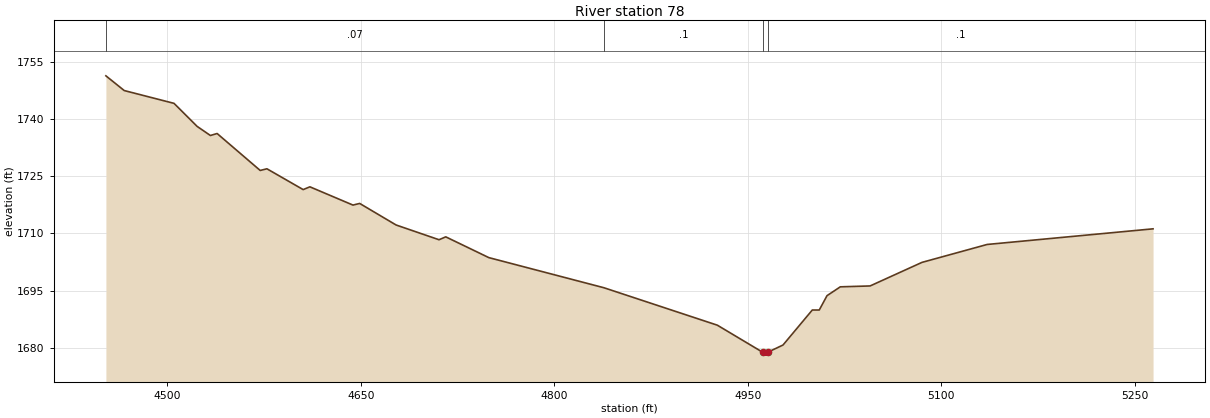
Type RM Length L Ch R = 1,78,0,0,0
BEGIN DESCRIPTION:
Stream0302 T
END DESCRIPTION:
XS GIS Cut Line= 4
      1998937.17     13872364.26      1999322.59     13872250.98
      1999399.41     13872120.77      1999333.00     13871870.75
#Sta/Elev= 30
  4452.5 1751.32  4466.7 1747.46  4505.3 1744.10  4523.2 1738.06  4533.5 1735.67
  4538.7 1736.19  4572.1 1726.50  4577.3 1726.94  4605.4 1721.48  4610.6 1722.21
  4644.0 1717.42  4649.2 1717.85  4677.4 1712.20  4710.7 1708.33  4715.9 1709.09
  4749.3 1703.64  4838.5 1695.74  4926.4 1685.92  4961.5 1678.83  4961.8 1678.33
  4965.5 1678.83  4977.3 1680.72  5000.0 1689.90  5005.4 1689.90  5011.4 1693.66
  5021.7 1695.98  5044.8 1696.21  5085.0 1702.39  5135.5 1707.09  5264.1 1711.19
#Mann=4,-1,0
  4452.5    0.07       0  4838.5     0.1       0  4961.5    0.05       0
  4965.5     0.1       0
Bank Sta=4961.5,4965.5
Exp/Cntr=0.3,0.1

Chan Stop Cuts=-1