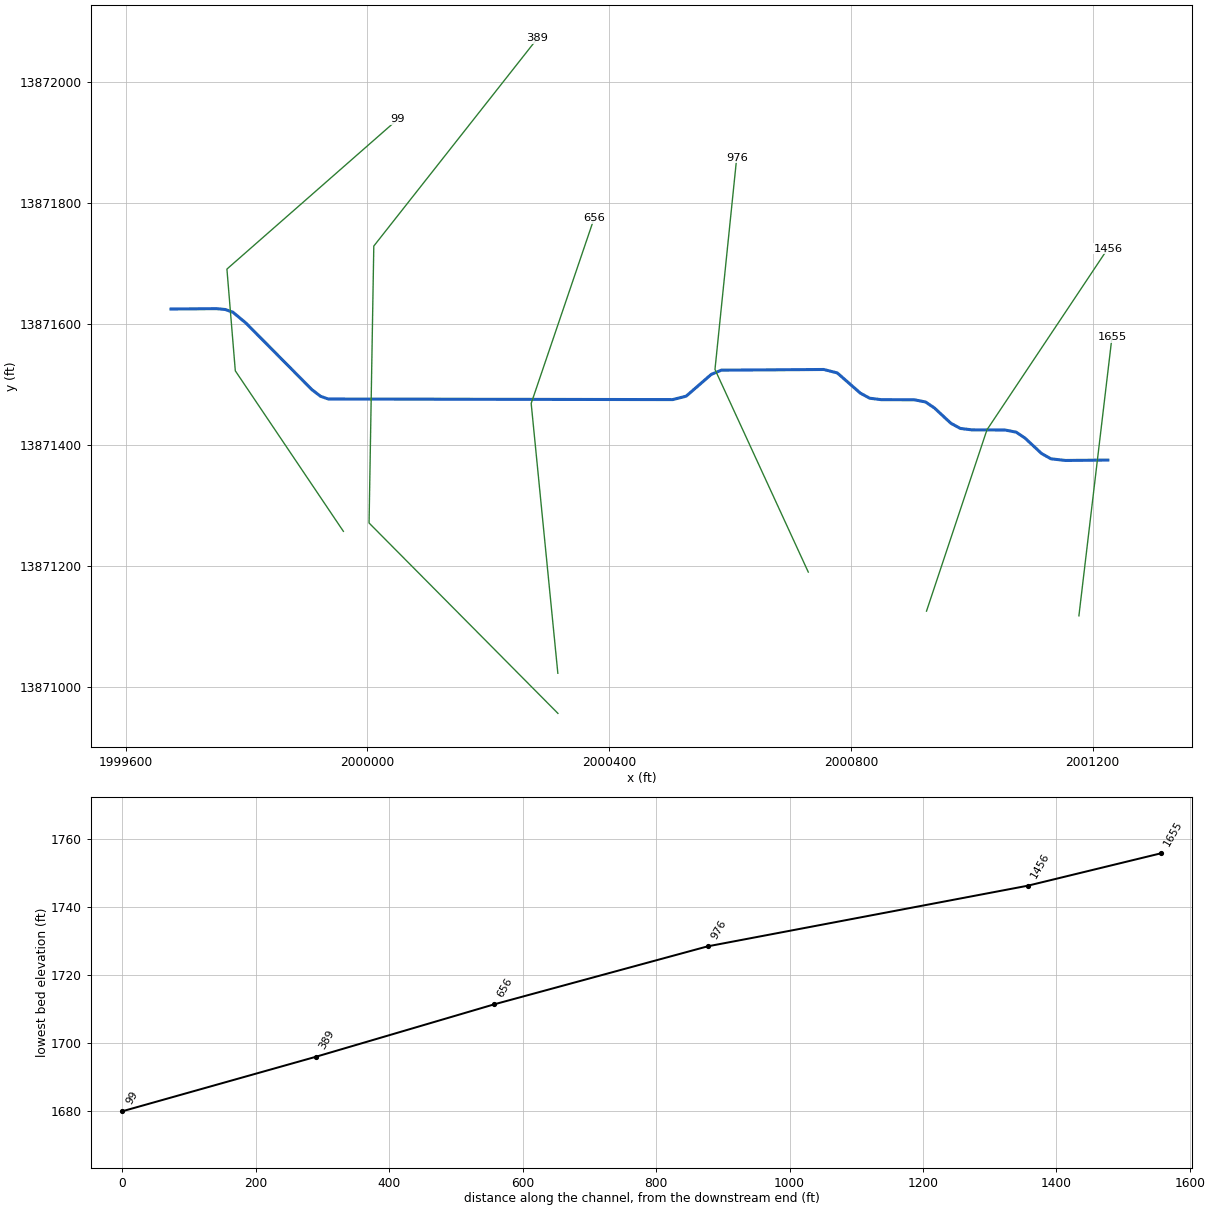
--- Stream0312.prj (project) ---

Proj Title=Stream0312 Base Level Engineering
Current Plan=p01
Default Exp/Contr=0.3,0.1
English Units
Geom File=g01
Flow File=f01
Plan File=p01
Y Axis Title=Elevation
X Axis Title(PF)=Main Channel Distance
X Axis Title(XS)=Station
BEGIN DESCRIPTION:
Stream0312
END DESCRIPTION:
DSS Export Rating Curves= 0
DSS Export Rating Curve Sorted= 0
DSS Export Volume Flow Curves= 0
DXF OffsetX= 0
DXF OffsetY= 0
DXF ScaleX= 1
DXF ScaleY= 10

--- Stream0312.p01 (plan) ---

Plan Title=Multiple Run
Short Identifier=Multiple
Geom File=g01
Flow File=f01
Subcritical Flow
K Sum by GR= 0
Std Step Tol= 0.01
Critical Tol= 0.01
Num of Std Step Trials= 20
Max Error Tol= 0.3
Flow Tol Ratio= 0.001
Split Flow NTrial= 30
Split Flow Tol= 0.02
Split Flow Ratio= 0.02
Log Output Level= 0
Friction Slope Method= 1
Unsteady Friction Slope Method= 2
Unsteady Bridges Friction Slope Method= 1
Parabolic Critical Depth
Global Vel Dist=  1 , 1 , 1
Global Log Level= 0
CheckData=True
Encroach Param= -1, 0, 0, 0
BEGIN DESCRIPTION:
Multiple Run
END DESCRIPTION:

--- Stream0312.f01 (steady flow) ---

Flow Title=Multiple
Number of Profiles=7
Profile Names=10-year,25-year,50-year,1pct_min,100-year,1pct_plu,500-year
River Rch & RM= Stream0312,Reach-1,1655
     271     425     562     362     723    1443    1180
Boundary for River Rch & Prof#=Stream0312,Reach-1,1
Up Type=0
Dn Type=3
Dn Slope=0.005
Boundary for River Rch & Prof#=Stream0312,Reach-1,2
Up Type=0
Dn Type=3
Dn Slope=0.005
Boundary for River Rch & Prof#=Stream0312,Reach-1,3
Up Type=0
Dn Type=3
Dn Slope=0.005
Boundary for River Rch & Prof#=Stream0312,Reach-1,4
Up Type=0
Dn Type=3
Dn Slope=0.005
Boundary for River Rch & Prof#=Stream0312,Reach-1,5
Up Type=0
Dn Type=3
Dn Slope=0.005
Boundary for River Rch & Prof#=Stream0312,Reach-1,6
Up Type=0
Dn Type=3
Dn Slope=0.005
Boundary for River Rch & Prof#=Stream0312,Reach-1,7
Up Type=0
Dn Type=3
Dn Slope=0.005

--- Stream0312.g01 (geometry) ---

Geom Title=Existing Conditions
Program Version=4.10

River Reach=Stream0312      ,Reach-1
Reach XY= 30
        2001225.       13871375.      2001154.74     13871374.36
      2001130.87      13871377.1      2001115.35     13871385.85
      2001088.15     13871411.23      2001073.42     13871421.17
       2001054.9     13871424.77        2001000.       13871425.
      2000980.97     13871427.35      2000965.37     13871435.89
      2000938.13     13871461.18       2000923.4     13871471.15
       2000904.9     13871474.76        2000850.       13871475.
      2000830.98     13871477.36      2000815.37     13871485.89
      2000777.34     13871519.26      2000754.97     13871524.93
      2000585.51     13871523.78      2000568.94     13871516.86
      2000527.33     13871480.75      2000504.97     13871475.07
      1999935.43     13871476.05      1999922.55     13871480.46
      1999908.24     13871491.43      1999798.52     13871602.12
       1999777.5     13871619.65      1999764.66     13871624.19
      1999750.25     13871625.59        1999675.       13871625.

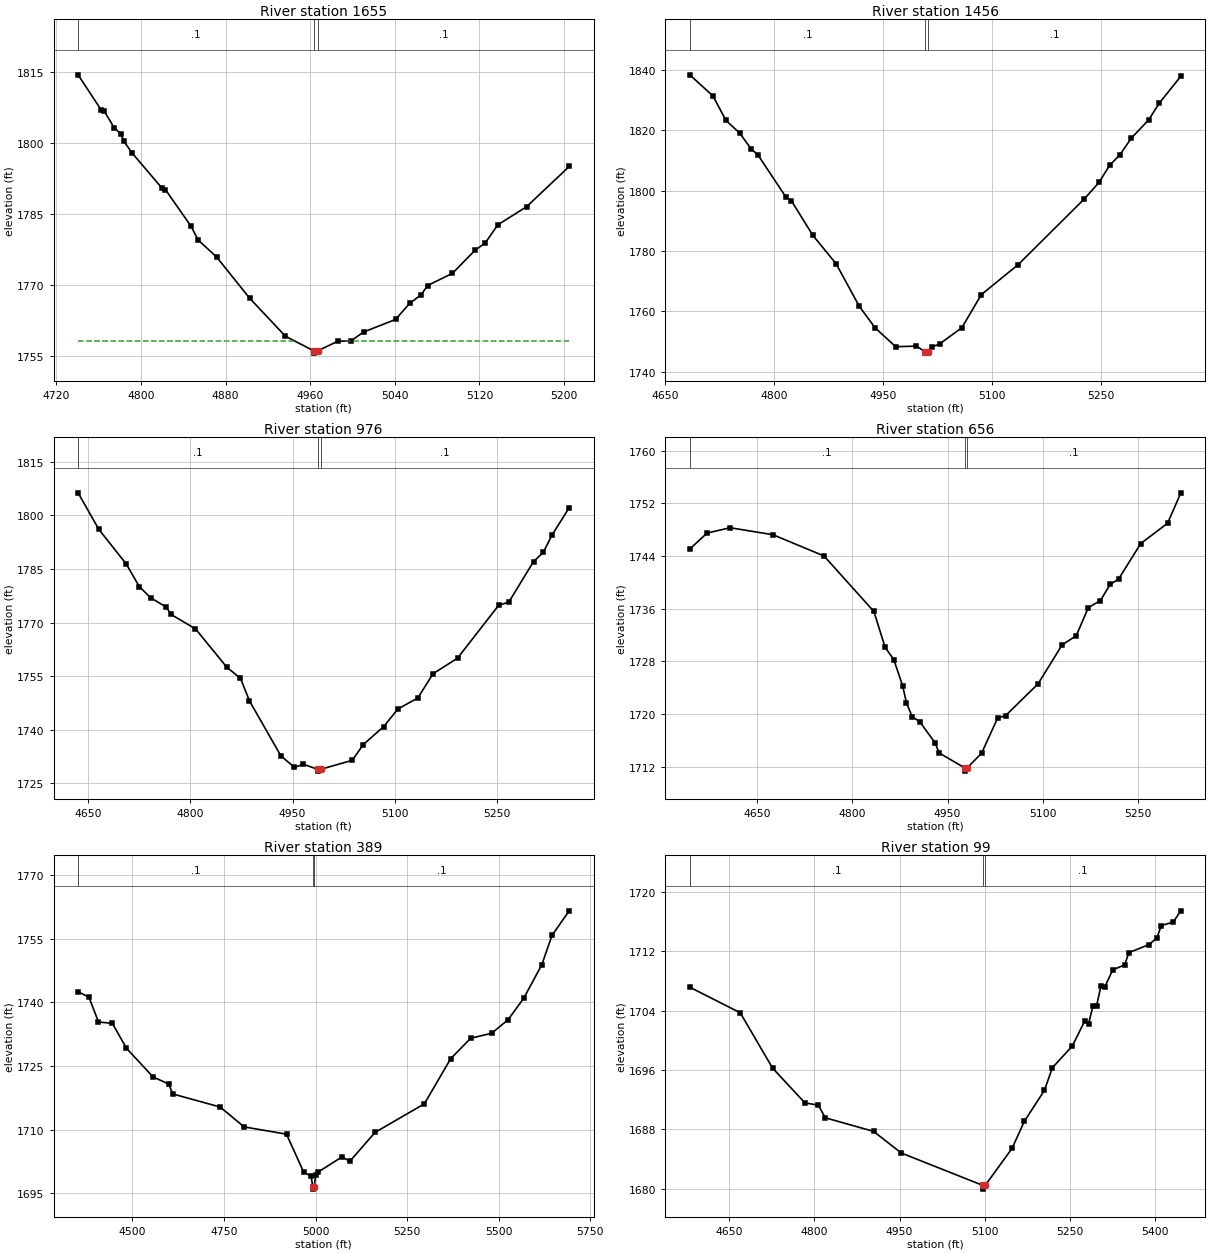
Type RM Length L Ch R = 1 ,1655    ,199,199,199
BEGIN DESCRIPTION:
Stream0312 4.0
END DESCRIPTION:
XS GIS Cut Line= 2
      2001177.15     13871117.23      2001231.85      13871578.2
#Sta/Elev= 30
  4740.6 1814.41  4762.3 1807.04    4765 1806.85  4774.9 1803.17  4780.9 1801.98
  4783.8 1800.39    4792 1797.81  4820.2 1790.42  4823.2 1790.16  4847.4 1782.43
  4854.1 1779.53  4871.5 1775.96  4902.7 1767.27  4936.6 1759.22  4963.2 1756.16
  4963.4 1755.66  4967.2 1756.16  4986.3 1758.19  4998.4 1758.22  5010.5 1760.12
  5040.7 1762.77    5054 1766.17  5064.9 1767.97  5070.9 1769.93  5094.5 1772.51
  5116.1 1777.45  5125.3 1778.87  5137.4 1782.75  5164.6 1786.58  5204.8 1795.06
#Mann= 3 ,-1 , 0
  4740.6      .1       0  4963.2     .05       0  4967.2      .1       0
#XS Ineff= 2 , 0
          4946.2 1758.23 4992.98         1758.24
Permanent Ineff=
       F       F
Bank Sta=4963.2,4967.2
XS Rating Curve= 0 ,0
Exp/Cntr=0.3,0.1

Type RM Length L Ch R = 1 ,1456    ,480,480,480
BEGIN DESCRIPTION:
Stream0312 3.0
END DESCRIPTION:
XS GIS Cut Line= 3
      2000925.01     13871125.03        2001025.       13871425.
      2001225.02     13871725.04
#Sta/Elev= 30
  4683.8 1838.43  4715.8 1831.41  4733.6 1823.33  4752.6  1819.1    4768    1814
  4777.9 1811.82  4815.8 1798.09  4823.7 1796.75  4853.4 1785.23  4885.4 1775.83
  4917.4 1761.72  4939.1 1754.61  4967.6  1748.3  4996.1 1748.51  5007.9 1746.68
  5008.2 1746.18  5011.9 1746.68  5017.1 1748.21    5028 1749.19  5058.8 1754.62
  5085.6 1765.57  5136.1 1775.46  5227.5 1797.28  5247.9 1802.79  5262.3 1808.39
  5276.7 1811.96  5292.4 1817.46  5316.4 1823.54  5330.7 1828.99  5360.6 1837.97
#Mann= 3 ,-1 , 0
  4683.8      .1       0  5007.9     .05       0  5011.9      .1       0
Bank Sta=5007.9,5011.9
XS Rating Curve= 0 ,0
Exp/Cntr=0.3,0.1

Type RM Length L Ch R = 1 ,976     ,320,320,320
BEGIN DESCRIPTION:
Stream0312 2.0
END DESCRIPTION:
XS GIS Cut Line= 3
      2000729.37     13871189.62        2000575.       13871525.
      2000610.97     13871875.35
#Sta/Elev= 30
  4634.9 1806.34  4665.3 1796.11  4705.6 1786.42  4724.8 1780.08  4741.3 1776.96
  4764.5  1774.3  4771.5 1772.26  4807.3 1768.24  4853.6 1757.43  4873.4 1754.39
  4886.6 1748.07  4932.8 1732.64  4952.7 1729.43  4965.9 1730.29    4987 1728.87
  4987.2 1728.37    4991 1728.87  5037.7  1731.4  5053.6 1735.76  5083.8 1740.86
  5104.9 1745.81  5133.9 1748.85  5156.2 1755.64  5192.3 1760.03  5252.7 1774.83
  5267.7 1775.73  5303.9 1787.08  5318.2 1789.64  5331.1 1794.51  5356.3 1802.17
#Mann= 3 ,-1 , 0
  4634.9      .1       0    4987     .05       0    4991      .1       0
Bank Sta=4987,4991
XS Rating Curve= 0 ,0
Exp/Cntr=0.3,0.1

Type RM Length L Ch R = 1 ,656     ,267,267,267
BEGIN DESCRIPTION:
Stream0312 1.0
END DESCRIPTION:
XS GIS Cut Line= 3
      2000315.01     13871022.21       2000270.9     13871468.78
      2000375.01     13871775.02
#Sta/Elev= 30
  4544.7 1745.06  4571.9 1747.48  4608.1 1748.29  4675.5 1747.23  4755.8    1744
  4834.2 1735.58  4851.8 1730.15  4865.5 1728.27  4879.4  1724.3  4885.4 1721.72
  4894.4 1719.61  4906.5 1718.82  4930.6 1715.61  4936.7 1714.11  4976.9 1711.84
  4977.1 1711.34  4980.9 1711.84  5003.5 1714.05  5028.8  1719.4  5041.5 1719.78
  5092.2 1724.58  5130.2 1730.51  5152.4  1731.9  5171.4 1736.17  5190.4 1737.23
  5205.8  1739.7  5218.9 1740.49  5253.8 1745.89    5296 1748.97  5316.9 1753.59
#Mann= 3 ,-1 , 0
  4544.7      .1       0  4976.9     .05       0  4980.9      .1       0
Bank Sta=4976.9,4980.9
XS Rating Curve= 0 ,0
Exp/Cntr=0.3,0.1

Type RM Length L Ch R = 1 ,389     ,290,290,290
BEGIN DESCRIPTION:
Stream0312 0.0
END DESCRIPTION:
XS GIS Cut Line= 4
      2000315.15     13870955.79      2000002.67     13871270.87
      2000010.49      13871729.2      2000281.34     13872072.97
#Sta/Elev= 30
  4352.3 1742.48    4382 1741.19  4407.9 1735.35  4445.9 1735.02  4484.2 1729.16
  4556.7 1722.41  4599.3 1720.73  4610.7 1718.38  4739.8 1715.31  4805.4 1710.62
  4920.9 1708.91  4967.5    1700  4988.2 1698.98  4992.5 1696.46  4992.7 1695.96
  4996.5 1696.46  5000.5 1699.38  5006.5 1699.95  5072.5 1703.57  5093.5  1702.5
  5162.5 1709.33    5297 1716.06  5368.8 1726.69  5423.1  1731.5  5480.8  1732.7
  5525.6  1735.9  5568.3 1740.98  5617.5 1748.85  5645.1 1755.73  5692.1 1761.54
#Mann= 3 ,-1 , 0
  4352.3      .1       0  4992.5     .05       0  4996.5      .1       0
Bank Sta=4992.5,4996.5
XS Rating Curve= 0 ,0
Exp/Cntr=0.3,0.1

Type RM Length L Ch R = 1 ,99      ,0,0,0
BEGIN DESCRIPTION:
Stream0312 T
END DESCRIPTION:
XS GIS Cut Line= 4
      1999960.16     13871257.08      1999781.36     13871522.68
      1999767.47     13871691.08      2000050.22     13871939.14
#Sta/Elev= 30
  4580.4 1707.15  4669.3 1703.71  4726.3 1696.26  4783.3 1691.58  4806.9 1691.27
  4819.2 1689.57  4904.3 1687.74  4953.1 1684.83  5096.9 1680.47  5097.1 1679.97
  5100.9 1680.47  5148.2 1685.45    5170 1689.11  5205.2 1693.25  5219.4 1696.32
  5254.5 1699.24  5276.3  1702.6    5283 1702.19  5290.6 1704.58  5297.2 1704.65
  5304.8 1707.27  5311.5 1707.15  5325.7 1709.49  5346.6 1710.15  5354.1  1711.8
  5389.3 1712.88  5403.5 1713.77  5411.1 1715.45    5432  1715.9  5445.7 1717.43
#Mann= 3 ,-1 , 0
  4580.4      .1       0  5096.9     .05       0  5100.9      .1       0
Bank Sta=5096.9,5100.9
XS Rating Curve= 0 ,0
Exp/Cntr=0.3,0.1

Chan Stop Cuts=-1
Use User Specified Reach Order=0
Composite Channel Slope=5