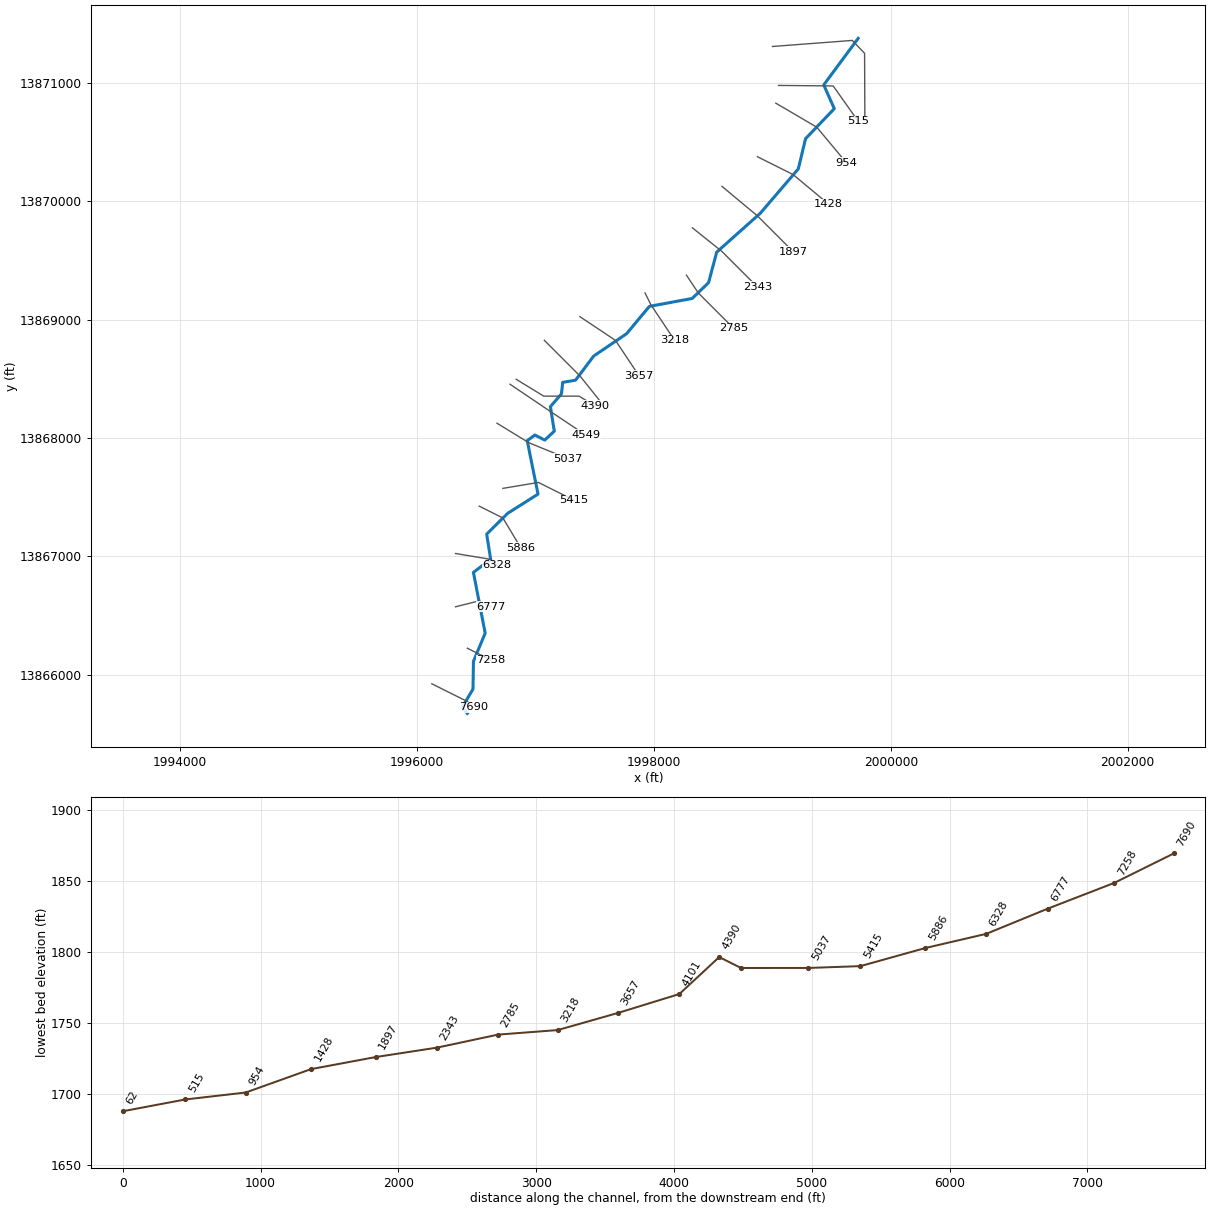
--- Stream0366.prj (project) ---

Proj Title=Stream0366 Base Level Engineering
Current Plan=p01
Default Exp/Contr=0.3,0.1
English Units
Geom File=g01
Flow File=f01
Plan File=p01
Y Axis Title=Elevation
X Axis Title(PF)=Main Channel Distance
X Axis Title(XS)=Station
BEGIN DESCRIPTION:
Stream0366
END DESCRIPTION:
DSS Export Rating Curves= 0
DSS Export Rating Curve Sorted= 0
DSS Export Volume Flow Curves= 0
DXF OffsetX= 0
DXF OffsetY= 0
DXF ScaleX= 1
DXF ScaleY= 10

--- Stream0366.p01 (plan) ---

Plan Title=Multiple Run
Short Identifier=Multiple
Geom File=g01
Flow File=f01
Subcritical Flow
K Sum by GR= 0
Std Step Tol= 0.01
Critical Tol= 0.01
Num of Std Step Trials= 20
Max Error Tol= 0.3
Flow Tol Ratio= 0.001
Split Flow NTrial= 30
Split Flow Tol= 0.02
Split Flow Ratio= 0.02
Log Output Level= 0
Friction Slope Method= 1
Unsteady Friction Slope Method= 2
Unsteady Bridges Friction Slope Method= 1
Parabolic Critical Depth
Global Vel Dist=  1 , 1 , 1
Global Log Level= 0
CheckData=True
Encroach Param= -1, 0, 0, 0
BEGIN DESCRIPTION:
Multiple Run
END DESCRIPTION:

--- Stream0366.f01 (steady flow) ---

Flow Title=Multiple
Program Version=4.10
Number of Profiles= 7
Profile Names=10-year,25-year,50-year,1pct_min,100-year,1pct_plu,500-year
River Rch & RM=Stream0366,Reach-1         ,7690
     187     285     370     235     469     936     740
River Rch & RM=Stream0366,Reach-1         ,6777
     734    1233    1705    1146    2287    4563    4065
River Rch & RM=Stream0366,Reach-1         ,3218
     969    1650    2302    1559    3111    6207    5617
Boundary for River Rch & Prof#=Stream0366,Reach-1         , 1
Up Type= 0
Dn Type= 3
Dn Slope=0.005
Boundary for River Rch & Prof#=Stream0366,Reach-1         , 2
Up Type= 0
Dn Type= 3
Dn Slope=0.005
Boundary for River Rch & Prof#=Stream0366,Reach-1         , 3
Up Type= 0
Dn Type= 3
Dn Slope=0.005
Boundary for River Rch & Prof#=Stream0366,Reach-1         , 4
Up Type= 0
Dn Type= 3
Dn Slope=0.005
Boundary for River Rch & Prof#=Stream0366,Reach-1         , 5
Up Type= 0
Dn Type= 3
Dn Slope=0.005
Boundary for River Rch & Prof#=Stream0366,Reach-1         , 6
Up Type= 0
Dn Type= 3
Dn Slope=0.005
Boundary for River Rch & Prof#=Stream0366,Reach-1         , 7
Up Type= 0
Dn Type= 3
Dn Slope=0.005
DSS Import GetInterval= 0
DSS Import GetPeak= 0
DSS Import FillOption= 0

--- Stream0366.g01 (geometry) ---

Geom Title=Existing Conditions
Program Version=4.10

River Reach=Stream0366      ,Reach-1
Reach XY= 30
        1996425.       13865675.      1996382.58      13865728.2
      1996472.65     13865880.52      1996476.22      13866114.5
       1996575.5     13866352.25      1996476.03     13866865.52
      1996621.63     13866976.28      1996588.04     13867188.54
       1996765.3     13867364.24      1997021.55     13867526.48
       1996930.3     13867977.75      1996995.04     13868025.37
      1997078.42     13867982.81      1997158.78     13868058.25
       1997126.1     13868265.36      1997219.43     13868372.64
      1997230.11     13868469.89       1997338.3     13868488.41
      1997491.42     13868692.08      1997769.38     13868880.62
      1997961.68     13869111.63       1998323.5     13869178.61
       1998461.6     13869311.69      1998530.26     13869569.53
       1998898.7     13869898.18      1999219.48     13870272.57
      1999280.52     13870527.43      1999523.39     13870781.04
      1999434.13     13870981.72        1999725.       13871375.

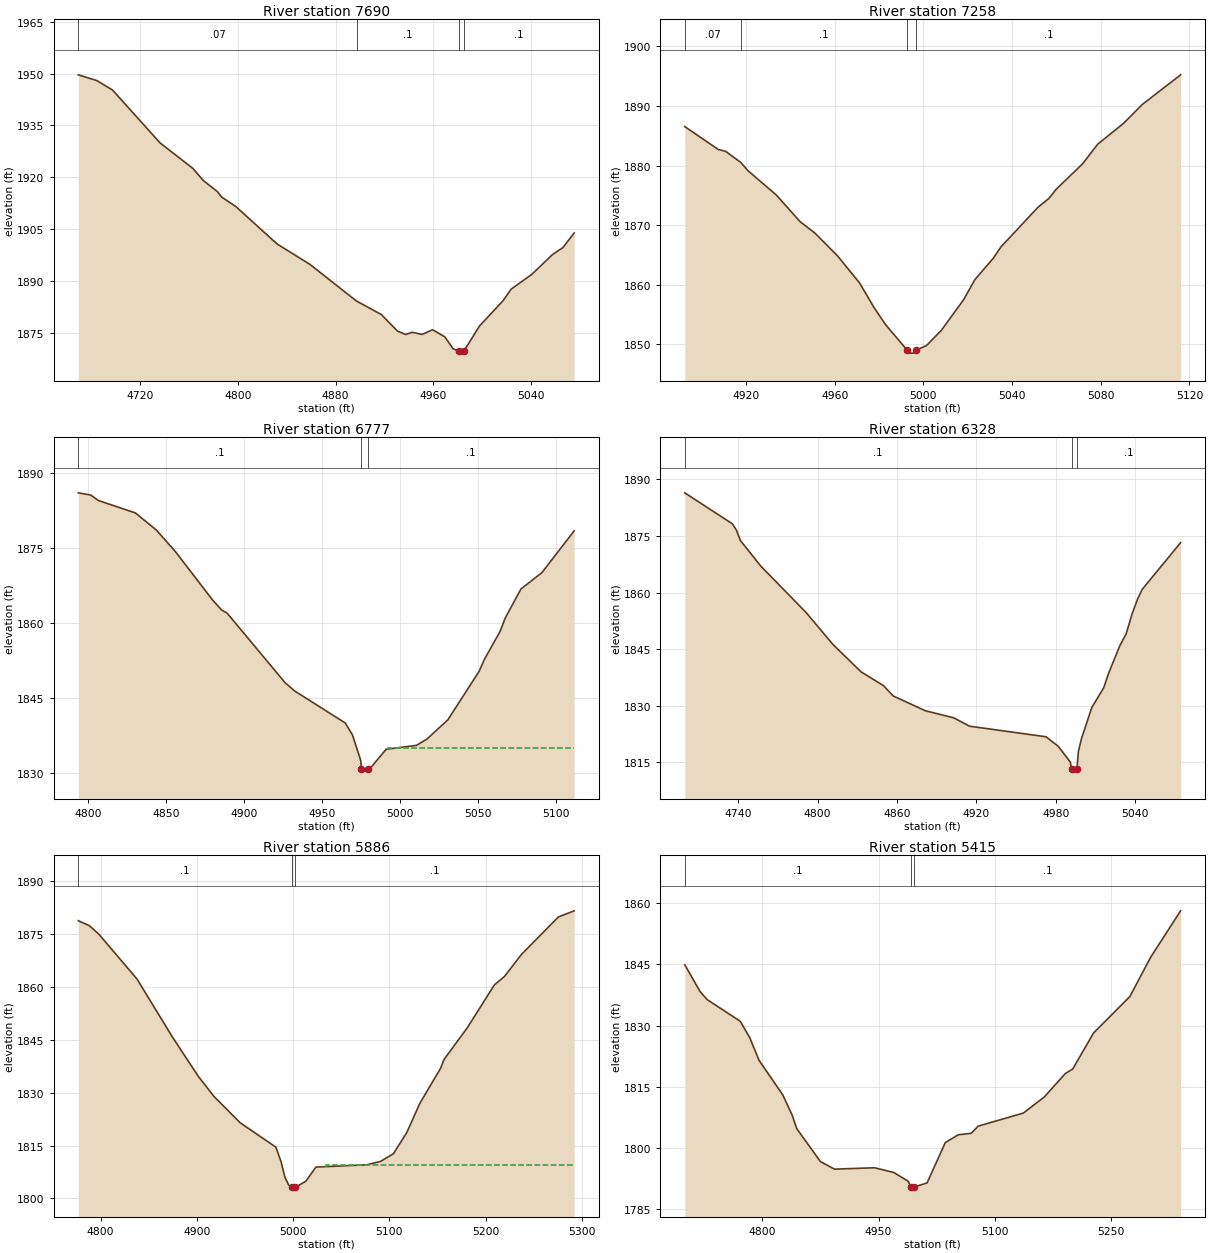
Type RM Length L Ch R = 1 ,7690    ,432,432,432
BEGIN DESCRIPTION:
Stream0366 17.0
END DESCRIPTION:
XS GIS Cut Line= 3
      1996124.96     13865925.02        1996425.       13865775.
      1996475.02     13865724.98
#Sta/Elev= 30
  4669.2 1949.63  4684.3 1947.98  4697.2 1945.25  4736.2 1929.96  4763.1  1922.6
  4771.6  1919.1  4783.2 1915.89  4786.6 1914.34  4798.4 1911.55  4831.9 1900.82
  4858.8 1894.93  4897.1 1884.31  4917.4 1880.42  4930.8  1875.6  4937.5 1874.64
  4942.6 1875.29  4950.9 1874.68  4959.4 1876.02  4969.4 1873.99  4976.2 1870.56
  4980.9 1869.77  4981.1 1869.27  4984.9 1869.77  4997.9 1877.13  5017.3 1884.47
  5023.8 1887.75  5040.7 1892.01  5057.7 1897.75  5066.2 1899.74  5075.4 1903.97
#Mann= 4 ,-1 , 0
  4669.2     .07       0  4897.1      .1       0  4980.9     .05       0
  4984.9      .1       0
Bank Sta=4980.9,4984.9
XS Rating Curve= 0 ,0
Exp/Cntr=0.3,0.1

Type RM Length L Ch R = 1 ,7258    ,481,481,481
BEGIN DESCRIPTION:
Stream0366 16.0
END DESCRIPTION:
XS GIS Cut Line= 3
        1996425.       13866225.        1996525.       13866175.
        1996625.       13866125.
#Sta/Elev= 30
  4892.4 1886.55  4907.5 1882.71  4910.8  1882.4  4917.6 1880.55  4920.9 1879.15
  4933.7 1875.06  4944.4  1870.6  4951.1 1868.67  4961.2 1864.89  4971.2 1860.32
  4977.9 1856.09    4983 1853.29  4992.7 1849.03  4992.9 1848.53  4996.4 1848.53
  4996.7 1849.03  5001.4  1849.8  5008.1 1852.36  5018.2 1857.53  5023.2 1860.86
  5031.6 1864.49  5034.9 1866.33  5051.7 1873.02  5056.7 1874.53    5060 1876.08
  5071.8 1880.31  5078.6  1883.6  5090.3 1887.11  5098.7 1890.26    5116 1895.24
#Mann= 4 ,-1 , 0
  4892.4     .07       0  4917.6      .1       0  4992.7     .05       0
  4996.7      .1       0
Bank Sta=4992.7,4996.7
XS Rating Curve= 0 ,0
Exp/Cntr=0.3,0.1

Type RM Length L Ch R = 1 ,6777    ,449,449,449
BEGIN DESCRIPTION:
Stream0366 15.0
END DESCRIPTION:
XS GIS Cut Line= 3
      1996324.95     13866574.99        1996525.       13866625.
      1996624.99       13866575.
#Sta/Elev= 30
  4793.7 1886.11  4801.6 1885.67  4806.6 1884.57  4830.3 1882.09  4843.7 1878.68
    4856 1874.34  4879.8 1864.68  4885.7 1862.64  4889.1 1862.06  4926.2 1848.18
  4932.4 1846.49  4964.9 1840.08  4969.5  1837.7  4974.8 1832.61  4975.3 1830.95
  4975.5 1830.45    4979 1830.45  4979.3 1830.95  4981.9 1831.38  4991.1 1834.82
  5010.5  1835.6  5017.2 1836.84  5030.7 1840.71  5050.8 1850.44  5054.1 1852.78
  5064.2  1858.4  5067.5 1861.07  5077.6 1866.89    5091 1870.15  5111.7  1878.5
#Mann= 3 ,-1 , 0
  4793.7      .1       0  4975.3     .05       0  4979.3      .1       0
#XS Ineff= 2 , 0
                         4992.16         1835.15
Permanent Ineff=
       F       F
Bank Sta=4975.3,4979.3
XS Rating Curve= 0 ,0
Exp/Cntr=0.3,0.1

Type RM Length L Ch R = 1 ,6328    ,442,442,442
BEGIN DESCRIPTION:
Stream0366 14.0
END DESCRIPTION:
XS GIS Cut Line= 3
      1996324.99       13867025.        1996625.       13866975.
      1996675.03     13866924.97
#Sta/Elev= 30
  4699.6 1886.46  4735.6 1878.23  4738.6  1876.6  4741.7 1873.78  4756.9 1867.08
  4791.5 1854.63  4811.6 1846.23  4832.9 1838.95  4849.9 1835.29  4857.2 1832.55
  4881.6 1828.62  4902.9 1826.76    4915 1824.53  4972.8 1821.72    4982 1819.19
  4991.1 1815.01  4992.1 1813.11  4992.4 1812.61  4996.1 1813.11  4997.2 1817.82
  4999.5 1821.18  5007.3 1829.47  5016.4 1834.76    5020 1838.54  5028.5 1845.87
  5033.4 1849.11  5037.6 1854.12  5041.9 1858.22  5045.5 1860.86  5074.5 1873.24
#Mann= 3 ,-1 , 0
  4699.6      .1       0  4992.1     .05       0  4996.1      .1       0
Bank Sta=4992.1,4996.1
XS Rating Curve= 0 ,0
Exp/Cntr=0.3,0.1

Type RM Length L Ch R = 1 ,5886    ,471,471,471
BEGIN DESCRIPTION:
Stream0366 13.0
END DESCRIPTION:
XS GIS Cut Line= 3
      1996524.97     13867425.02        1996725.       13867325.
        1996875.     13867074.99
#Sta/Elev= 30
  4776.8 1878.82  4788.4 1877.39  4798.2 1874.97  4837.8 1862.25  4874.7 1845.75
  4901.5 1834.63  4917.6 1828.99  4945.1 1821.44    4982 1814.56  4987.4 1810.48
  4991.4 1806.04  4995.4 1803.77  4998.4 1803.13  4998.7 1802.63  5002.4 1803.13
  5013.2 1804.88  5023.7 1808.89  5076.2 1809.53  5090.8  1810.5  5104.2 1812.67
  5118.2 1818.74  5131.6 1826.95  5153.2 1836.92  5156.7 1839.39  5181.2 1848.52
  5209.1  1860.6  5219.6 1862.99  5237.1  1869.2  5275.6 1879.88    5292 1881.62
#Mann= 3 ,-1 , 0
  4776.8      .1       0  4998.4     .05       0  5002.4      .1       0
#XS Ineff= 2 , 0
                          5034.3         1809.47
Permanent Ineff=
       F       F
Bank Sta=4998.4,5002.4
XS Rating Curve= 0 ,0
Exp/Cntr=0.3,0.1

Type RM Length L Ch R = 1 ,5415    ,378,378,378
BEGIN DESCRIPTION:
Stream0366 12.0
END DESCRIPTION:
XS GIS Cut Line= 3
      1996725.02       13867575.        1997025.       13867625.
      1997324.97     13867475.01
#Sta/Elev= 30
  4700.1  1844.9  4719.8 1838.33    4729 1836.36  4771.6 1831.05  4783.7  1827.1
  4795.9 1821.46  4826.3 1813.05  4838.5 1808.08  4844.5 1804.72    4875 1796.65
  4893.2 1794.79  4944.9 1795.13  4969.9 1793.95  4988.2 1791.82  4991.6 1790.39
  4991.8 1789.89  4995.6 1790.39  5012.6 1791.42  5036.1  1801.3  5052.9 1803.22
  5069.6 1803.58  5078.4 1805.33  5136.7 1808.53  5163.5 1812.44    5191 1818.25
  5200.4 1819.33  5227.3 1828.17  5274.2 1837.14  5301.1  1846.8  5339.6 1858.13
#Mann= 3 ,-1 , 0
  4700.1      .1       0  4991.6     .05       0  4995.6      .1       0
Bank Sta=4991.6,4995.6
XS Rating Curve= 0 ,0
Exp/Cntr=0.3,0.1

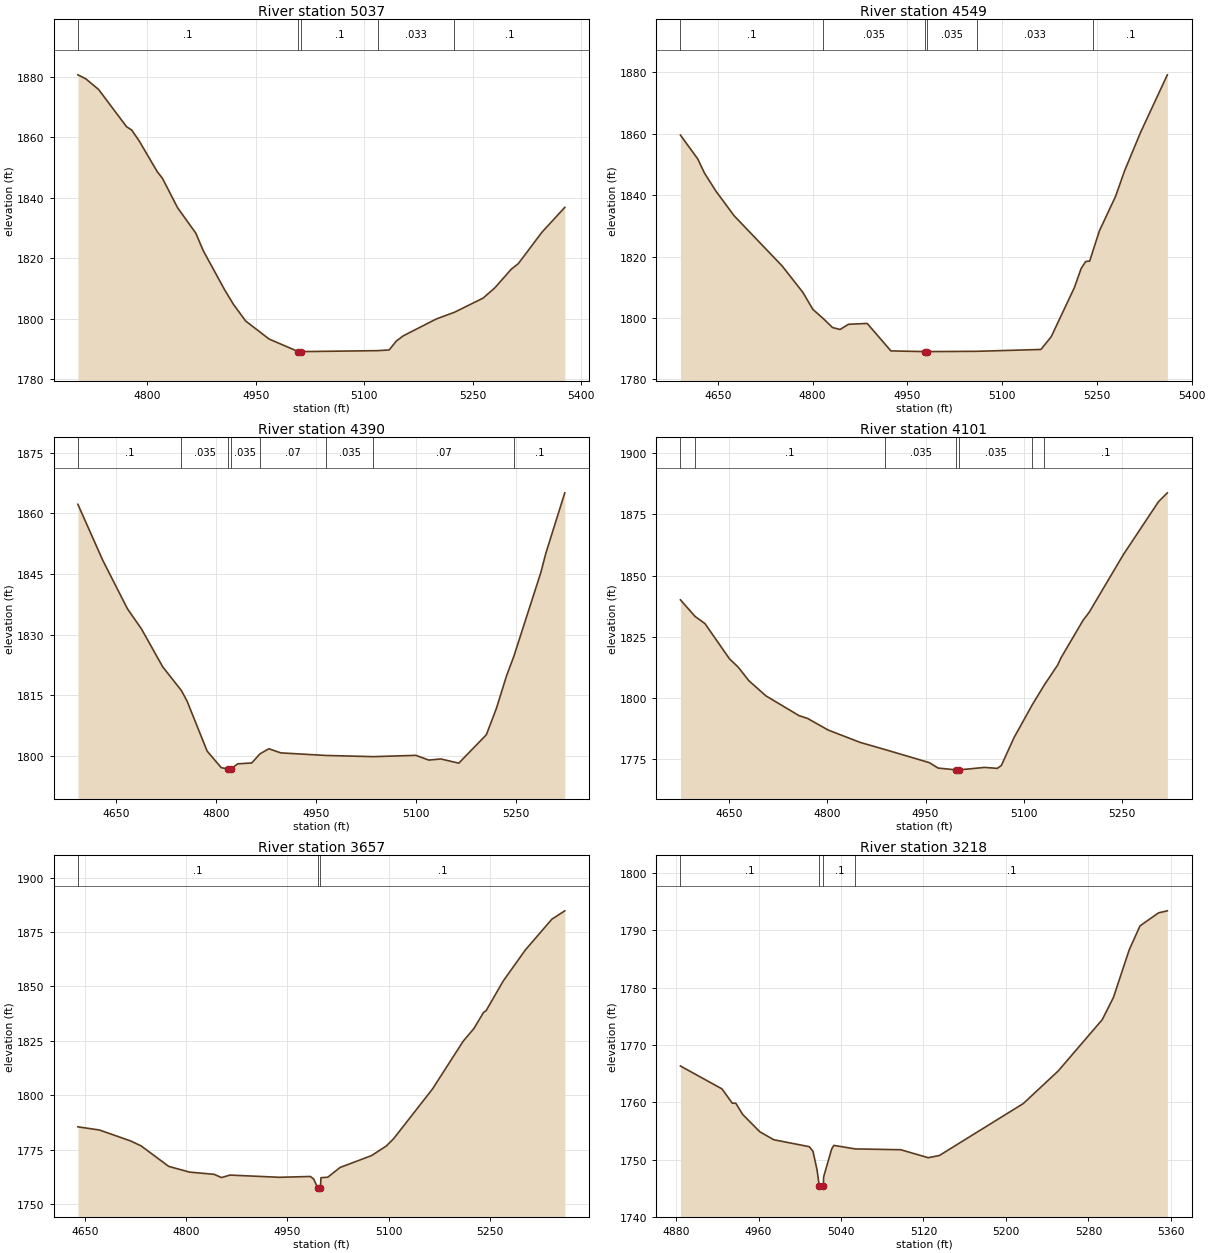
Type RM Length L Ch R = 1 ,5037    ,488,488,488
BEGIN DESCRIPTION:
Stream0366 11.0
END DESCRIPTION:
XS GIS Cut Line= 3
      1996675.04     13868124.98      1996945.47      13867959.7
      1997274.97     13867825.01
#Sta/Elev= 30
  4704.3 1880.56  4715.4 1879.22    4733  1875.7  4771.6 1863.41  4778.7 1862.31
  4789.2 1858.65  4813.8 1848.63  4821.2 1846.35    4842 1836.68  4867.2 1828.27
  4877.7 1822.39  4907.4  1809.4  4919.3 1804.71  4936.2 1799.21  4968.5 1793.26
    5009  1789.1  5009.3  1788.6    5013  1789.1  5119.1 1789.42  5134.5 1789.65
  5144.4 1792.59  5154.1 1794.33  5199.5 1799.87  5224.7  1802.1  5264.3 1806.78
  5280.5 1810.16  5303.2 1816.32    5313 1818.17  5345.4 1828.49  5377.2 1836.76
#Mann= 5 ,-1 , 0
  4704.3      .1       0    5009     .05       0    5013      .1       0
  5119.1    .033       0  5224.7      .1       0
Bank Sta=5009,5013
XS Rating Curve= 0 ,0
Exp/Cntr=0.3,0.1

Type RM Length L Ch R = 1 ,4549    ,159,159,159
BEGIN DESCRIPTION:
Stream0366 10.0
END DESCRIPTION:
XS GIS Cut Line= 3
      1996785.03     13868454.31        1997125.       13868225.
      1997424.97     13868025.02
#Sta/Elev= 30
  4590.9 1859.52  4618.2 1851.81  4628.9 1847.18    4647 1841.32  4675.9 1833.27
  4751.9 1816.94  4784.5  1808.4  4800.6 1802.79  4816.8 1799.86  4831.5 1796.92
  4843.5 1796.27  4856.8 1797.96  4886.5 1798.24    4924  1789.3  4977.9 1789.08
  4978.1 1788.58  4981.9 1789.08  5059.5 1789.17  5161.4 1789.77  5177.6 1793.87
  5214.3 1809.87  5225.1 1816.12  5232.3 1818.39  5238.6 1818.53  5244.4 1822.28
    5254 1828.38  5279.7 1839.66  5293.6 1847.78  5318.9 1860.31  5361.5 1879.14
#Mann= 6 ,-1 , 0
  4590.9      .1       0  4816.8    .035       0  4977.9     .05       0
  4981.9    .035       0  5059.5    .033       0  5244.4      .1       0
Bank Sta=4977.9,4981.9
XS Rating Curve= 0 ,0
Exp/Cntr=0.3,0.1

Type RM Length L Ch R = 1 ,4390    ,289,289,289
BEGIN DESCRIPTION:
Stream0366 9.1
END DESCRIPTION:
XS GIS Cut Line= 4
      1996837.08       13868496.      1997069.76     13868353.61
      1997368.37     13868353.61      1997503.79     13868270.28
#Sta/Elev= 30
  4592.9 1862.24  4630.3 1848.37  4667.2 1836.42  4688.4 1831.39    4720 1822.09
  4748.2 1816.18  4756.8 1813.54  4786.8 1801.21  4807.9 1797.13  4818.1 1796.76
  4818.3 1796.26  4822.1 1796.76  4832.6 1798.06  4853.7 1798.28    4866 1800.53
  4879.4 1801.79  4897.4 1800.77  4964.5 1800.14  5036.2 1799.84  5099.9 1800.16
  5119.4 1798.99  5137.4 1799.27  5164.3 1798.23  5205.7 1805.27  5220.8 1811.81
    5236 1819.87  5246.8 1824.61  5287.5 1845.43  5294.8 1850.09  5323.3 1865.08
#Mann= 8 ,-1 , 0
  4592.9      .1       0  4748.2    .035       0  4818.1    .035       0
  4822.1    .035       0    4866     .07       0  4964.5    .035       0
  5036.2     .07       0  5246.8      .1       0
Bank Sta=4818.1,4822.1
XS Rating Curve= 0 ,0
Exp/Cntr=0.3,0.1

Type RM Length L Ch R = 1 ,4101    ,444,444,444
BEGIN DESCRIPTION:
Stream0366 9.0
END DESCRIPTION:
XS GIS Cut Line= 3
      1997074.97     13868825.03        1997375.       13868525.
      1997575.02     13868274.98
#Sta/Elev= 30
  4575.2 1840.08  4597.6 1833.31  4612.7  1830.4  4650.1 1816.06  4663.6 1812.62
  4679.8 1807.11  4706.1  1800.9  4756.6 1792.86  4769.7 1791.72  4801.1 1786.99
  4850.3 1781.93  4888.1 1779.03  4955.6 1773.72  4969.1  1771.5  4996.8 1770.74
  4997.1 1770.24  5000.8 1770.74  5040.4 1771.76  5059.7 1771.36  5065.9 1772.54
  5085.2 1783.86  5113.2 1797.31  5131.6 1805.38  5151.9 1813.46  5157.2 1816.48
  5190.8 1831.71  5200.4 1835.11  5252.4 1858.51  5306.1 1880.08  5319.7 1883.72
#Mann= 7 ,-1 , 0
  4575.2     .07       0  4597.6      .1       0  4888.1    .035       0
  4996.8    .035       0  5000.8    .035       0  5113.2     .07       0
  5131.6      .1       0
Bank Sta=4996.8,5000.8
XS Rating Curve= 0 ,0
Exp/Cntr=0.3,0.1

Type RM Length L Ch R = 1 ,3657    ,439,439,439
BEGIN DESCRIPTION:
Stream0366 8.0
END DESCRIPTION:
XS GIS Cut Line= 3
      1997374.98     13869025.01        1997675.       13868825.
      1997874.98     13868525.03
#Sta/Elev= 30
  4639.6 1785.56  4671.5  1784.1  4717.8 1779.06  4733.3 1776.79  4774.1  1767.4
  4804.9 1764.77  4841.5 1763.74  4852.3 1762.26  4864.9  1763.4  4938.3 1762.38
  4983.9 1762.76  4988.8 1761.59  4994.9 1757.45  4995.2 1756.95  4998.9 1757.45
  4999.6 1762.19  5009.7 1762.42  5027.8 1766.88  5074.6 1772.36  5096.3 1776.75
  5107.1 1780.06  5164.8 1802.95  5210.2 1824.86  5226.1 1830.69  5240.5 1838.15
  5244.1 1838.84  5269.3 1852.42  5302.1  1866.7  5341.5 1880.88  5360.7 1884.75
#Mann= 3 ,-1 , 0
  4639.6      .1       0  4994.9     .05       0  4998.9      .1       0
Bank Sta=4994.9,4998.9
XS Rating Curve= 0 ,0
Exp/Cntr=0.3,0.1

Type RM Length L Ch R = 1 ,3218    ,433,433,433
BEGIN DESCRIPTION:
Stream0366 7.0
END DESCRIPTION:
XS GIS Cut Line= 3
      1997924.98     13869225.04        1997975.       13869125.
        1998175.       13868825.
#Sta/Elev= 30
  4884.2 1766.32  4924.5 1762.33  4934.5 1759.84  4937.9 1759.83  4944.6 1757.87
  4961.3 1754.84  4974.8 1753.46  5009.2 1752.25  5012.8 1751.45  5016.8 1748.15
  5018.9 1745.35  5019.1 1744.85  5022.6 1744.85  5022.9 1745.35  5023.1  1746.9
  5023.6 1747.29  5030.9 1751.83    5033 1752.48  5053.9 1751.86  5097.9 1751.72
  5124.6 1750.33  5135.4 1750.71  5216.9 1759.78  5250.8 1765.47  5293.5 1774.42
  5304.3 1778.28  5319.6 1786.57  5330.1 1790.76  5348.1 1793.03  5356.6 1793.38
#Mann= 4 ,-1 , 0
  4884.2      .1       0  5018.9     .05       0  5022.9      .1       0
  5053.9      .1       0
Bank Sta=5018.9,5022.9
XS Rating Curve= 0 ,0
Exp/Cntr=0.3,0.1

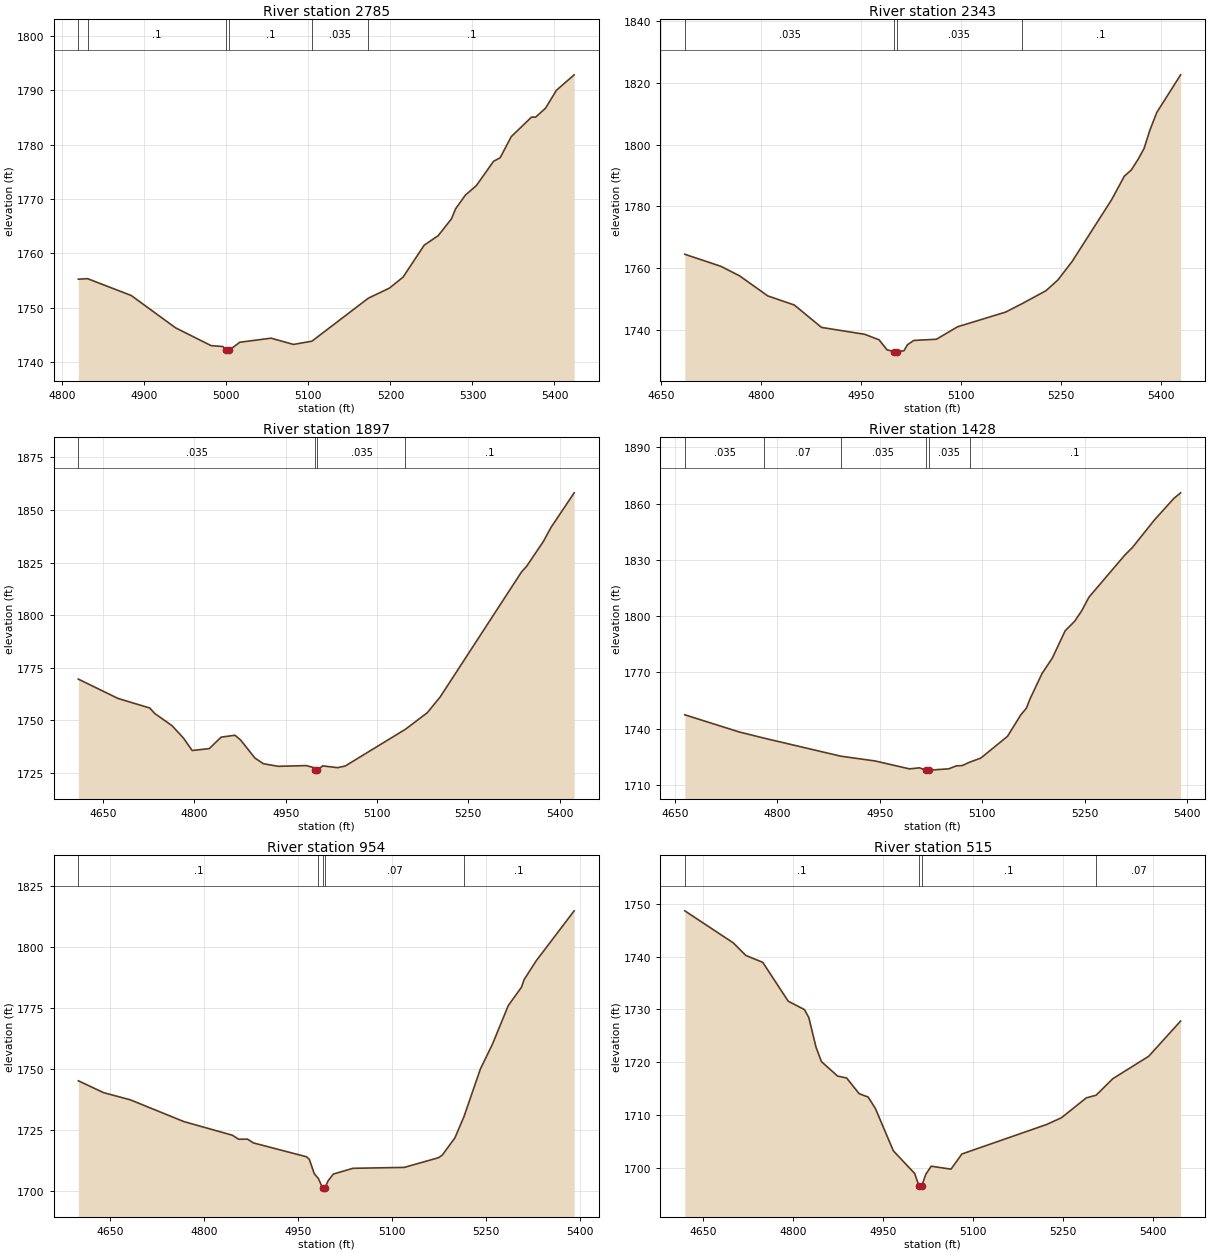
Type RM Length L Ch R = 1 ,2785    ,442,442,442
BEGIN DESCRIPTION:
Stream0366 6.0
END DESCRIPTION:
XS GIS Cut Line= 3
      1998275.02     13869374.97        1998375.       13869225.
        1998675.       13868925.
#Sta/Elev= 30
  4819.5 1755.25  4830.7 1755.35    4884 1752.25  4938.1  1746.3  4981.4 1743.03
  4995.8 1742.86  4999.1 1742.15  4999.4 1741.65  5003.1 1742.15  5016.3 1743.65
  5054.5  1744.4  5081.8 1743.25  5104.3 1743.85  5173.1 1751.76  5198.8 1753.61
  5215.4 1755.63  5241.2 1761.51  5258.2 1763.25  5274.4 1766.35  5279.4 1768.18
  5291.4 1770.72  5304.8 1772.47  5325.7 1776.93  5333.8 1777.59  5347.3 1781.47
    5372 1785.06    5377 1785.06    5389 1786.68  5402.4    1790    5424 1792.84
#Mann= 6 ,-1 , 0
  4819.5    .035       0  4830.7      .1       0  4999.1     .05       0
  5003.1      .1       0  5104.3    .035       0  5173.1      .1       0
Bank Sta=4999.1,5003.1
XS Rating Curve= 0 ,0
Exp/Cntr=0.3,0.1

Type RM Length L Ch R = 1 ,2343    ,446,446,446
BEGIN DESCRIPTION:
Stream0366 5.0
END DESCRIPTION:
XS GIS Cut Line= 3
      1998324.97     13869775.03        1998575.       13869575.
      1998875.03     13869274.97
#Sta/Elev= 30
  4685.3  1764.5  4739.4 1760.61  4767.6 1757.51  4809.9 1751.02  4849.8 1748.07
  4890.6 1740.82  4955.5 1738.59    4977 1736.81  4989.1 1733.55    5000    1733
  5000.2  1732.5    5004    1733  5014.3 1733.25  5019.6 1735.21  5029.2 1736.61
  5063.1 1736.99  5094.9 1741.03  5167.1 1745.79  5191.2 1748.45  5227.5 1752.68
  5245.5 1756.18  5266.8 1762.14  5326.2 1782.17  5345.3 1789.78  5355.9 1791.82
  5366.5 1795.43    5375  1798.8  5383.4 1804.53    5394  1810.4  5429.8 1822.58
#Mann= 4 ,-1 , 0
  4685.3    .035       0    5000    .035       0    5004    .035       0
  5191.2      .1       0
Bank Sta=5000,5004
XS Rating Curve= 0 ,0
Exp/Cntr=0.3,0.1

Type RM Length L Ch R = 1 ,1897    ,469,469,469
BEGIN DESCRIPTION:
Stream0366 4.0
END DESCRIPTION:
XS GIS Cut Line= 3
      1998574.96     13870125.03        1998875.       13869875.
      1999174.98     13869575.02
#Sta/Elev= 30
  4609.2 1769.59  4674.4  1760.4  4726.7 1755.84  4734.5 1753.32  4763.5 1747.37
  4782.2 1741.46  4796.3 1735.63  4824.4 1736.56  4843.9    1742  4866.6 1742.91
    4876 1740.59  4899.4 1732.06  4913.4 1729.36  4937.6 1728.13  4983.7 1728.47
  4996.2 1727.51  4998.1 1726.34  4998.4 1725.84  5002.1 1726.34  5010.7 1728.33
  5035.1 1727.49  5047.8 1728.27  5146.8 1745.76  5182.5 1753.56  5203.8 1761.09
  5337.4  1820.5  5345.9 1823.23  5373.5 1835.08  5386.2 1841.81    5424 1858.16
#Mann= 4 ,-1 , 0
  4609.2    .035       0  4998.1    .035       0  5002.1    .035       0
  5146.8      .1       0
Bank Sta=4998.1,5002.1
XS Rating Curve= 0 ,0
Exp/Cntr=0.3,0.1

Type RM Length L Ch R = 1 ,1428    ,474,474,474
BEGIN DESCRIPTION:
Stream0366 3.0
END DESCRIPTION:
XS GIS Cut Line= 3
      1998874.96     13870375.02        1999175.       13870225.
      1999475.02     13869974.98
#Sta/Elev= 30
  4664.3 1747.38  4743.7 1738.27  4780.7 1734.91  4892.6 1725.33    4943 1722.77
  4993.3 1718.56  5007.9 1719.12  5017.6 1717.86  5017.9 1717.36  5021.6 1717.86
  5050.8 1718.59  5061.8 1720.16  5070.4 1720.31  5081.5 1722.14  5097.7 1724.31
  5136.8  1735.9  5156.3 1747.35  5164.5 1750.93  5169.6 1755.72  5187.5 1769.46
  5202.4 1777.59  5221.2 1792.14  5235.2 1797.28  5245.4 1802.78  5256.1 1810.09
  5308.6 1832.51  5319.6  1836.5  5351.9 1851.22  5380.5 1862.75  5390.3 1865.69
#Mann= 6 ,-1 , 0
  4664.3    .035       0  4780.7     .07       0  4892.6    .035       0
  5017.6    .035       0  5021.6    .035       0  5081.5      .1       0
Bank Sta=5017.6,5021.6
XS Rating Curve= 0 ,0
Exp/Cntr=0.3,0.1

Type RM Length L Ch R = 1 ,954     ,439,439,439
BEGIN DESCRIPTION:
Stream0366 2.0
END DESCRIPTION:
XS GIS Cut Line= 3
      1999029.29     13870827.68        1999375.       13870625.
      1999625.03     13870324.97
#Sta/Elev= 30
  4599.3 1745.24  4639.8 1740.36  4682.2 1737.45  4767.7 1728.54    4845 1722.96
  4855.3 1721.31  4869.3 1721.34  4878.9 1719.79  4963.2 1714.14  4967.9 1713.12
  4975.9 1707.16  4982.4 1705.22  4989.1 1701.38  4989.3 1700.88  4993.1 1701.38
  4997.6 1704.16  5006.2 1707.04  5037.5  1709.4  5119.5 1709.78  5174.1 1713.74
  5180.1 1714.81  5200.3 1721.87  5214.8  1730.6    5241 1750.09    5260 1760.11
  5285.5 1776.05  5306.6 1783.57  5310.8  1786.7  5330.3 1794.46  5390.6 1814.82
#Mann= 5 ,-1 , 0
  4599.3      .1       0  4982.4     .07       0  4989.1     .05       0
  4993.1     .07       0  5214.8      .1       0
Bank Sta=4989.1,4993.1
XS Rating Curve= 0 ,0
Exp/Cntr=0.3,0.1

Type RM Length L Ch R = 1 ,515     ,453,453,453
BEGIN DESCRIPTION:
Stream0366 1.0
END DESCRIPTION:
XS GIS Cut Line= 3
      1999052.44     13870977.31      1999514.01     13870972.97
        1999725.       13870675.
#Sta/Elev= 30
  4619.9 1748.65  4700.7 1742.59  4721.7  1740.2  4749.9  1738.9  4792.3 1731.55
  4819.5 1729.95  4826.7 1728.44  4838.7 1722.84  4847.7 1720.11  4874.7 1717.37
  4889.7 1717.01  4910.7 1714.03  4925.6  1713.4  4937.7 1711.23  4967.7 1703.21
  5003.2 1698.93  5010.7 1696.47    5011 1695.97  5014.7 1696.47  5021.7 1698.78
  5030.7 1700.31  5063.7 1699.75  5081.9 1702.62  5223.3 1708.21    5248 1709.49
  5289.4 1713.25  5305.6 1713.74  5333.6 1716.88  5393.4 1721.12  5446.6 1727.79
#Mann= 4 ,-1 , 0
  4619.9      .1       0  5010.7     .05       0  5014.7      .1       0
  5305.6     .07       0
Bank Sta=5010.7,5014.7
XS Rating Curve= 0 ,0
Exp/Cntr=0.3,0.1

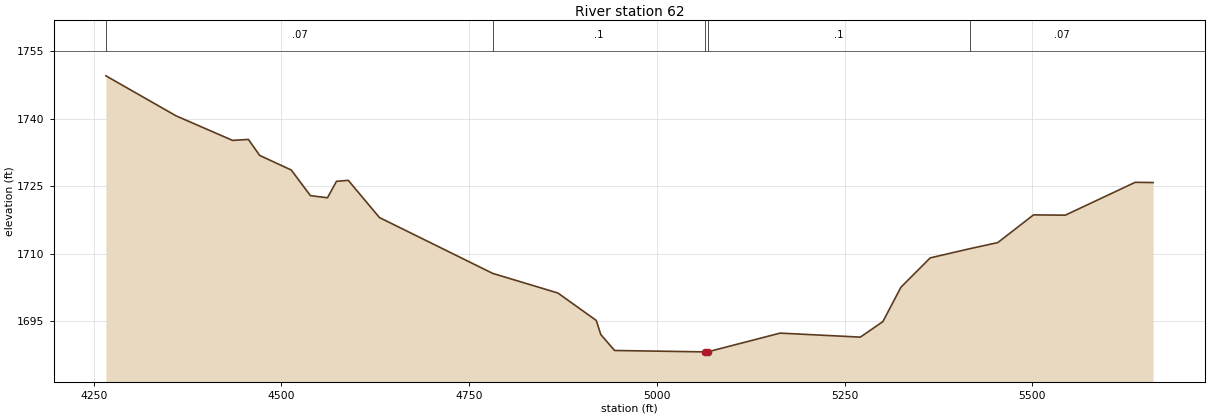
Type RM Length L Ch R = 1 ,62      ,0,0,0
BEGIN DESCRIPTION:
Stream0366 0.0
END DESCRIPTION:
XS GIS Cut Line= 4
      1999001.04     13871306.18      1999675.55     13871357.37
      1999778.99     13871248.42      1999781.48      13870680.5
#Sta/Elev= 30
  4266.3 1749.55  4359.8 1740.65    4435  1735.2  4456.1 1735.41  4471.1 1731.86
  4513.2 1728.61  4538.7 1722.92  4561.4 1722.44  4573.4  1726.1  4589.1 1726.32
  4630.6 1718.05  4781.5 1705.63  4868.2 1701.28  4919.4 1695.18  4925.4 1692.04
  4943.8  1688.5  5063.6 1688.19  5063.9 1687.69  5067.6 1688.19  5164.2 1692.36
  5271.1 1691.47  5301.1 1694.92  5325.1 1702.56  5364.1 1709.08    5417 1711.13
  5454.1 1712.48  5501.7 1718.64  5544.1 1718.58  5637.1 1725.88  5660.9 1725.83
#Mann= 5 ,-1 , 0
  4266.3     .07       0  4781.5      .1       0  5063.6     .05       0
  5067.6      .1       0    5417     .07       0
Bank Sta=5063.6,5067.6
XS Rating Curve= 0 ,0
Exp/Cntr=0.3,0.1

Chan Stop Cuts=-1
Use User Specified Reach Order=0
Composite Channel Slope=5