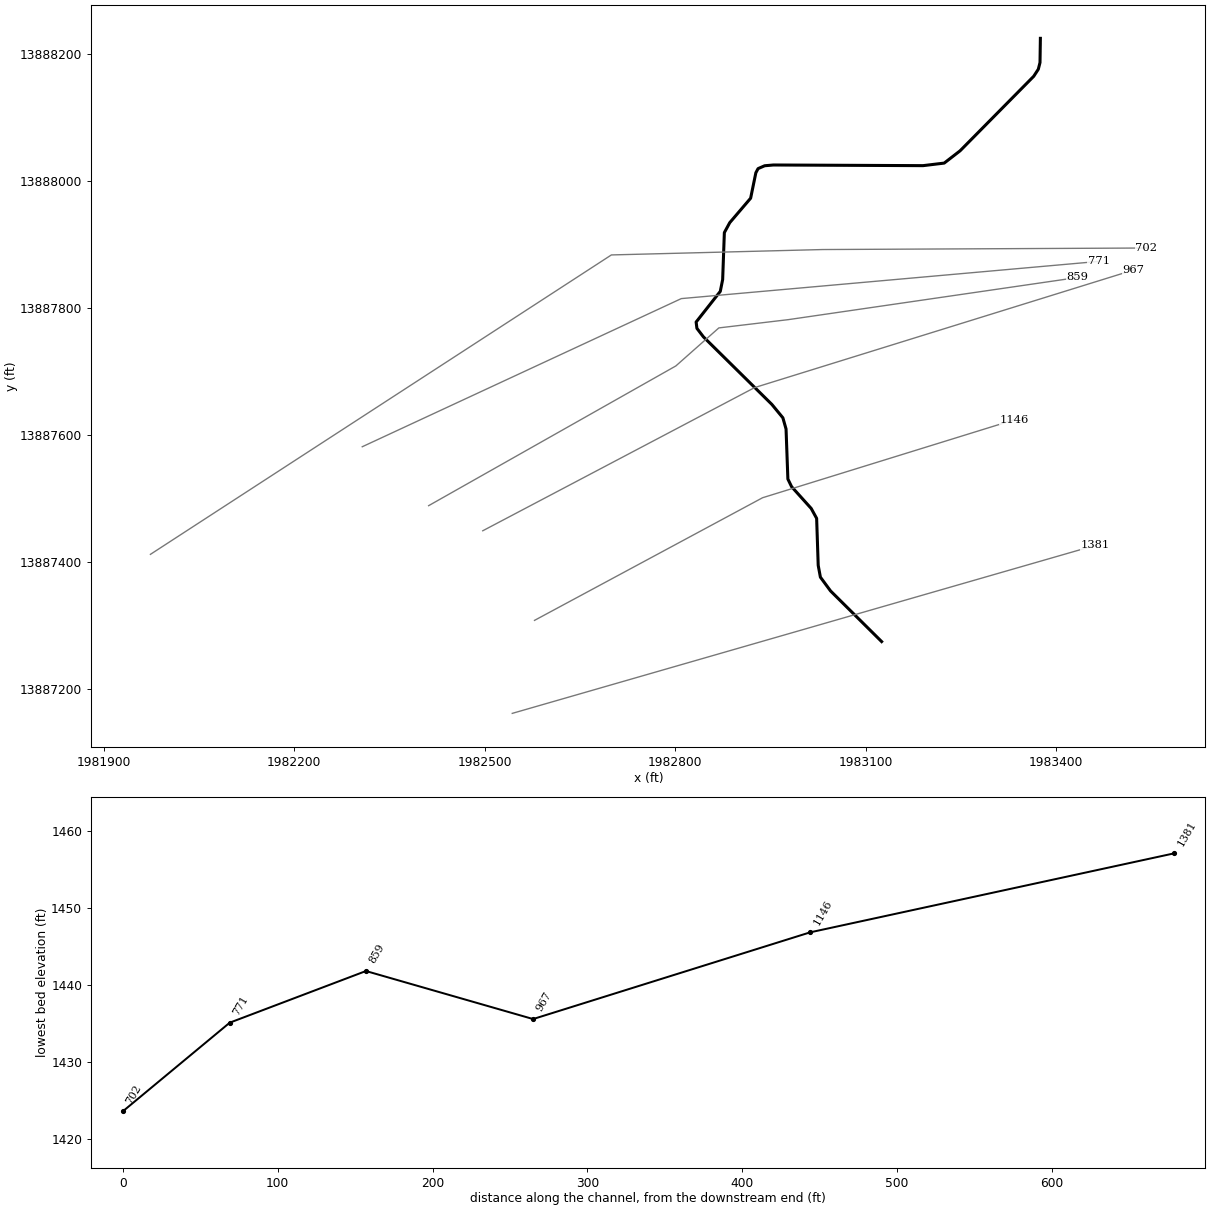
--- Stream0373.prj (project) ---

Proj Title=Stream0373 Base Level Engineering
Current Plan=p01
Default Exp/Contr=0.3,0.1
English Units
Geom File=g01
Flow File=f01
Plan File=p01
BEGIN DESCRIPTION:
Stream0373
END DESCRIPTION:

--- Stream0373.p01 (plan) ---

Plan Title=Multiple Run
Short Identifier=Multiple
Geom File=g01
Flow File=f01
Subcritical Flow
K Sum by GR= 0
Std Step Tol= 0.01
Critical Tol= 0.01
Num of Std Step Trials= 20
Max Error Tol= 0.3
Flow Tol Ratio= 0.001
Split Flow NTrial= 30
Split Flow Tol= 0.02
Split Flow Ratio= 0.02
Log Output Level= 0
Friction Slope Method= 1
Unsteady Friction Slope Method= 2
Unsteady Bridges Friction Slope Method= 1
Parabolic Critical Depth
Global Vel Dist=  1 , 1 , 1
Global Log Level= 0
CheckData=True
Encroach Param= -1, 0, 0, 0
BEGIN DESCRIPTION:
Multiple Run
END DESCRIPTION:

--- Stream0373.f01 (steady flow) ---

Flow Title=Multiple
Number of Profiles=7
Profile Names=10-year,25-year,50-year,1pct_min,100-year,1pct_plu,500-year
River Rch & RM= Stream0373,Reach-1,1381
     640    1065    1465     981    1957    3904    3445
Boundary for River Rch & Prof#=Stream0373,Reach-1,1
Up Type=0
Dn Type=3
Dn Slope=0.005
Boundary for River Rch & Prof#=Stream0373,Reach-1,2
Up Type=0
Dn Type=3
Dn Slope=0.005
Boundary for River Rch & Prof#=Stream0373,Reach-1,3
Up Type=0
Dn Type=3
Dn Slope=0.005
Boundary for River Rch & Prof#=Stream0373,Reach-1,4
Up Type=0
Dn Type=3
Dn Slope=0.005
Boundary for River Rch & Prof#=Stream0373,Reach-1,5
Up Type=0
Dn Type=3
Dn Slope=0.005
Boundary for River Rch & Prof#=Stream0373,Reach-1,6
Up Type=0
Dn Type=3
Dn Slope=0.005
Boundary for River Rch & Prof#=Stream0373,Reach-1,7
Up Type=0
Dn Type=3
Dn Slope=0.005

--- Stream0373.g01 (geometry) ---

Geom Title=Existing Conditions

River Reach=Stream0373,Reach-1
Reach XY= 30
      1983125.00     13887275.00      1983044.52     13887354.80
      1983028.56     13887376.48      1983025.12     13887395.05
      1983022.65     13887469.02      1983014.11     13887484.63
      1982983.19     13887518.96      1982977.36     13887530.98
      1982974.48     13887609.78      1982969.48     13887627.43
      1982952.12     13887648.52      1982844.29     13887754.97
      1982834.13     13887768.26      1982832.87     13887778.22
      1982870.90     13887826.50      1982874.64     13887845.05
      1982877.32     13887919.06      1982885.81     13887934.71
      1982918.70     13887973.22      1982926.93     13888013.33
      1982930.41     13888019.83      1982940.82     13888024.35
      1982954.56     13888025.54      1983190.20     13888024.51
      1983223.54     13888028.53      1983248.53     13888047.86
      1983364.49     13888165.21      1983371.73     13888176.35
      1983374.41     13888186.84      1983375.00     13888225.00

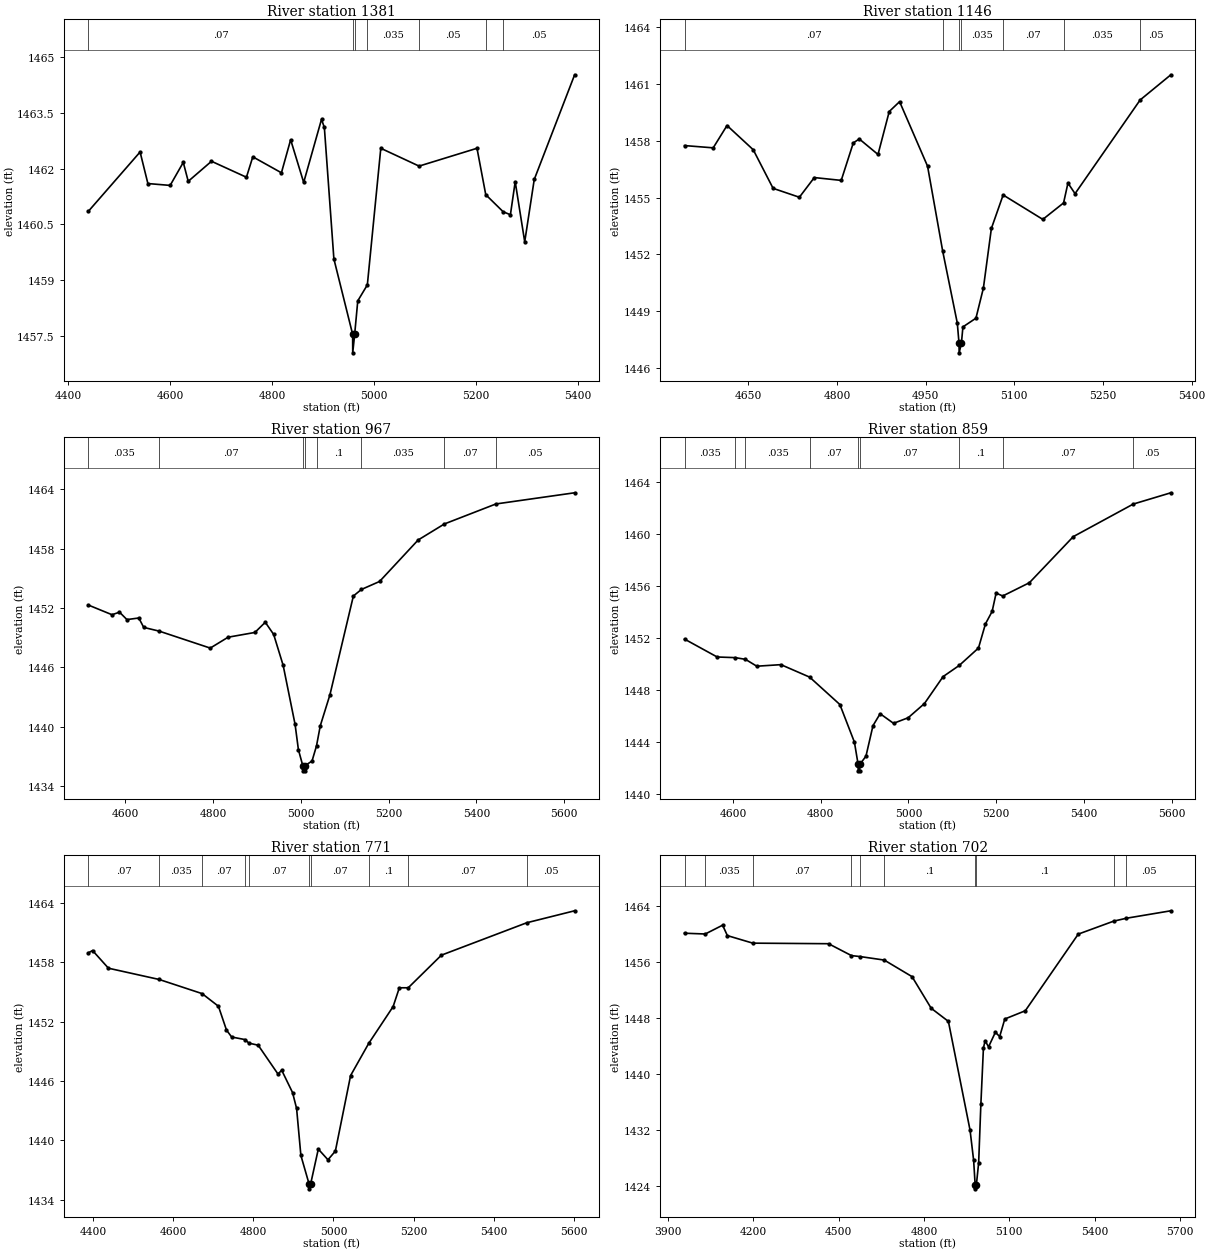
Type RM Length L Ch R = 1,1381,235,235,235
BEGIN DESCRIPTION:
Stream0373 2.0
END DESCRIPTION:
XS GIS Cut Line= 2
      1982543.31     13887161.95      1983460.89     13887426.32
#Sta/Elev= 30
  4439.0 1460.85  4540.7 1462.45  4556.0 1461.60  4599.7 1461.55  4625.5 1462.17
  4635.2 1461.66  4680.9 1462.20  4749.5 1461.77  4762.0 1462.32  4818.2 1461.89
  4836.3 1462.78  4861.9 1461.63  4896.9 1463.33  4902.5 1463.11  4921.2 1459.57
  4958.0 1457.54  4958.2 1457.04  4962.0 1457.54  4968.1 1458.44  4986.9 1458.87
  5013.3 1462.55  5088.5 1462.07  5202.2 1462.55  5219.4 1461.30  5253.6 1460.84
  5267.8 1460.76  5277.2 1461.65  5295.9 1460.03  5314.6 1461.71  5393.9 1464.53
#Mann=7,-1,0
  4439.0    0.07       0  4958.0   0.035       0  4962.0    0.07       0
  4986.9   0.035       0  5088.5    0.05       0  5219.4   0.035       0
  5253.6    0.05       0
Bank Sta=4958,4962
Exp/Cntr=0.3,0.1

Type RM Length L Ch R = 1,1146,179,179,179
BEGIN DESCRIPTION:
Mapping XS 97720e9c
END DESCRIPTION:
XS GIS Cut Line= 3
      1982578.36     13887308.40      1982937.54     13887501.55
      1983333.58     13887624.16
#Sta/Elev= 30
  4542.3 1457.75  4590.8 1457.63  4614.2 1458.81  4658.5 1457.53  4692.1 1455.49
  4736.5 1455.02  4761.8 1456.06  4807.3 1455.91  4827.7 1457.89  4837.8 1458.10
  4869.5 1457.28  4888.5 1459.55  4906.0 1460.07  4953.3 1456.66  4978.9 1452.17
  5003.6 1448.37  5006.5 1447.30  5006.7 1446.80  5010.5 1447.30  5013.1 1448.17
  5035.1 1448.63  5047.7 1450.22  5061.2 1453.37  5081.1 1455.14  5148.2 1453.85
  5183.3 1454.72  5190.7 1455.77  5202.7 1455.21  5312.8 1460.16  5364.7 1461.49
#Mann=7,-1,0
  4542.3    0.07       0  4978.9   0.035       0  5006.5   0.035       0
  5010.5   0.035       0  5081.1    0.07       0  5183.3   0.035       0
  5312.8    0.05       0
Bank Sta=5006.5,5010.5
Exp/Cntr=0.3,0.1

Type RM Length L Ch R = 1,967,108,108,108
BEGIN DESCRIPTION:
Stream0373 1.0
END DESCRIPTION:
XS GIS Cut Line= 3
      1982496.85     13887449.50      1982925.00     13887675.00
      1983521.25     13887860.02
#Sta/Elev= 30
  4515.8 1452.30  4569.9 1451.32  4586.9 1451.58  4603.8 1450.83  4630.9 1450.99
  4642.1 1450.04  4677.6 1449.66  4793.7 1447.95  4834.4 1449.05  4895.4 1449.53
  4919.1 1450.56  4938.2 1449.33  4959.8 1446.21  4987.0 1440.24  4994.6 1437.68
  5004.7 1436.05  5005.0 1435.55  5008.5 1435.55  5008.7 1436.05  5025.6 1436.54
  5035.8 1438.07  5044.4 1440.10  5066.4 1443.23  5119.8 1453.21  5138.0 1453.87
  5179.5 1454.68  5267.4 1458.87  5327.2 1460.49  5444.6 1462.51  5624.0 1463.64
#Mann=8,-1,0
  4515.8   0.035       0  4677.6    0.07       0  5004.7    0.05       0
  5008.7    0.07       0  5035.8     0.1       0  5138.0   0.035       0
  5327.2    0.07       0  5444.6    0.05       0
Bank Sta=5004.7,5008.7
Exp/Cntr=0.3,0.1

Type RM Length L Ch R = 1,859,88,88,88
BEGIN DESCRIPTION:
Stream0373 1.1
END DESCRIPTION:
XS GIS Cut Line= 5
      1982411.62     13887489.03      1982800.94     13887709.08
      1982868.64     13887768.98      1982978.02     13887782.00
      1983433.76     13887848.40
#Sta/Elev= 30
  4489.7 1451.93  4564.1 1450.55  4605.2 1450.50  4628.5 1450.37  4654.4 1449.84
  4709.4 1449.96  4774.8 1449.00  4843.7 1446.89  4876.9 1443.99  4885.3 1442.28
  4885.5 1441.78  4889.0 1441.78  4889.3 1442.28  4903.2 1442.91  4919.2 1445.26
  4935.5 1446.18  4966.0 1445.44  4999.4 1445.87  5036.4 1446.96  5079.0 1449.04
  5115.8 1449.90  5159.6 1451.24  5175.5 1453.10  5190.7 1454.06  5199.8 1455.47
  5214.9 1455.25  5275.6 1456.27  5375.6 1459.82  5512.3 1462.33  5598.0 1463.20
#Mann=9,-1,0
  4489.7   0.035       0  4605.2    0.07       0  4628.5   0.035       0
  4774.8    0.07       0  4885.3    0.05       0  4889.3    0.07       0
  5115.8     0.1       0  5214.9    0.07       0  5512.3    0.05       0
Bank Sta=4885.3,4889.3
Exp/Cntr=0.3,0.1

Type RM Length L Ch R = 1,771,69,69,69
BEGIN DESCRIPTION:
Mapping XS 5e200e5d
END DESCRIPTION:
XS GIS Cut Line= 3
      1982307.08     13887581.83      1982809.51     13887815.13
      1983467.05     13887873.73
#Sta/Elev= 30
  4387.9 1458.95  4398.5 1459.19  4438.2 1457.40  4564.9 1456.26  4672.0 1454.83
  4712.8 1453.55  4732.9 1451.14  4745.8 1450.44  4779.1 1450.18  4788.9 1449.82
  4812.0 1449.61  4861.5 1446.69  4870.7 1447.08  4897.8 1444.82  4907.9 1443.21
  4918.6 1438.46  4939.0 1435.58  4939.2 1435.08  4943.0 1435.58  4962.1 1439.10
  4986.2 1438.02  5004.7 1438.90  5042.7 1446.54  5087.9 1449.79  5148.9 1453.52
  5164.4 1455.42  5186.6 1455.42  5269.4 1458.72  5482.6 1462.00  5602.0 1463.21
#Mann=10,-1,0
  4387.9    0.07       0  4564.9   0.035       0  4672.0    0.07       0
  4779.1   0.035       0  4788.9    0.07       0  4939.0    0.05       0
  4943.0    0.07       0  5087.9     0.1       0  5186.6    0.07       0
  5482.6    0.05       0
Bank Sta=4939,4943
Exp/Cntr=0.3,0.1

Type RM Length L Ch R = 1,702,0,0,0
BEGIN DESCRIPTION:
Stream0373 0.0
END DESCRIPTION:
XS GIS Cut Line= 4
      1981973.49     13887412.38      1982699.42     13887883.90
      1983032.24     13887892.40      1983541.98     13887894.81
#Sta/Elev= 30
  3958.9 1460.15  4031.8 1460.04  4092.7 1461.30  4109.4 1459.81  4198.8 1458.73
  4464.8 1458.65  4545.3 1456.95  4576.1 1456.81  4660.5 1456.31  4758.1 1453.94
  4825.3 1449.42  4885.8 1447.54  4961.9 1431.98  4974.5 1427.65  4979.9 1424.09
  4980.1 1423.59  4983.9 1424.09  4992.1 1427.32  4999.9 1435.72  5008.9 1443.76
  5014.9 1444.76  5026.9 1443.90  5050.9 1445.99  5065.9 1445.36  5083.9 1447.88
  5155.9 1449.06  5341.9 1460.02  5466.6 1461.88  5510.7 1462.29  5667.2 1463.36
#Mann=10,-1,0
  3958.9   0.045       0  4031.8   0.035       0  4198.8    0.07       0
  4545.3   0.035       0  4576.1    0.07       0  4660.5     0.1       0
  4979.9    0.05       0  4983.9     0.1       0  5466.6    0.07       0
  5510.7    0.05       0
Bank Sta=4979.9,4983.9
Exp/Cntr=0.3,0.1

Chan Stop Cuts=-1