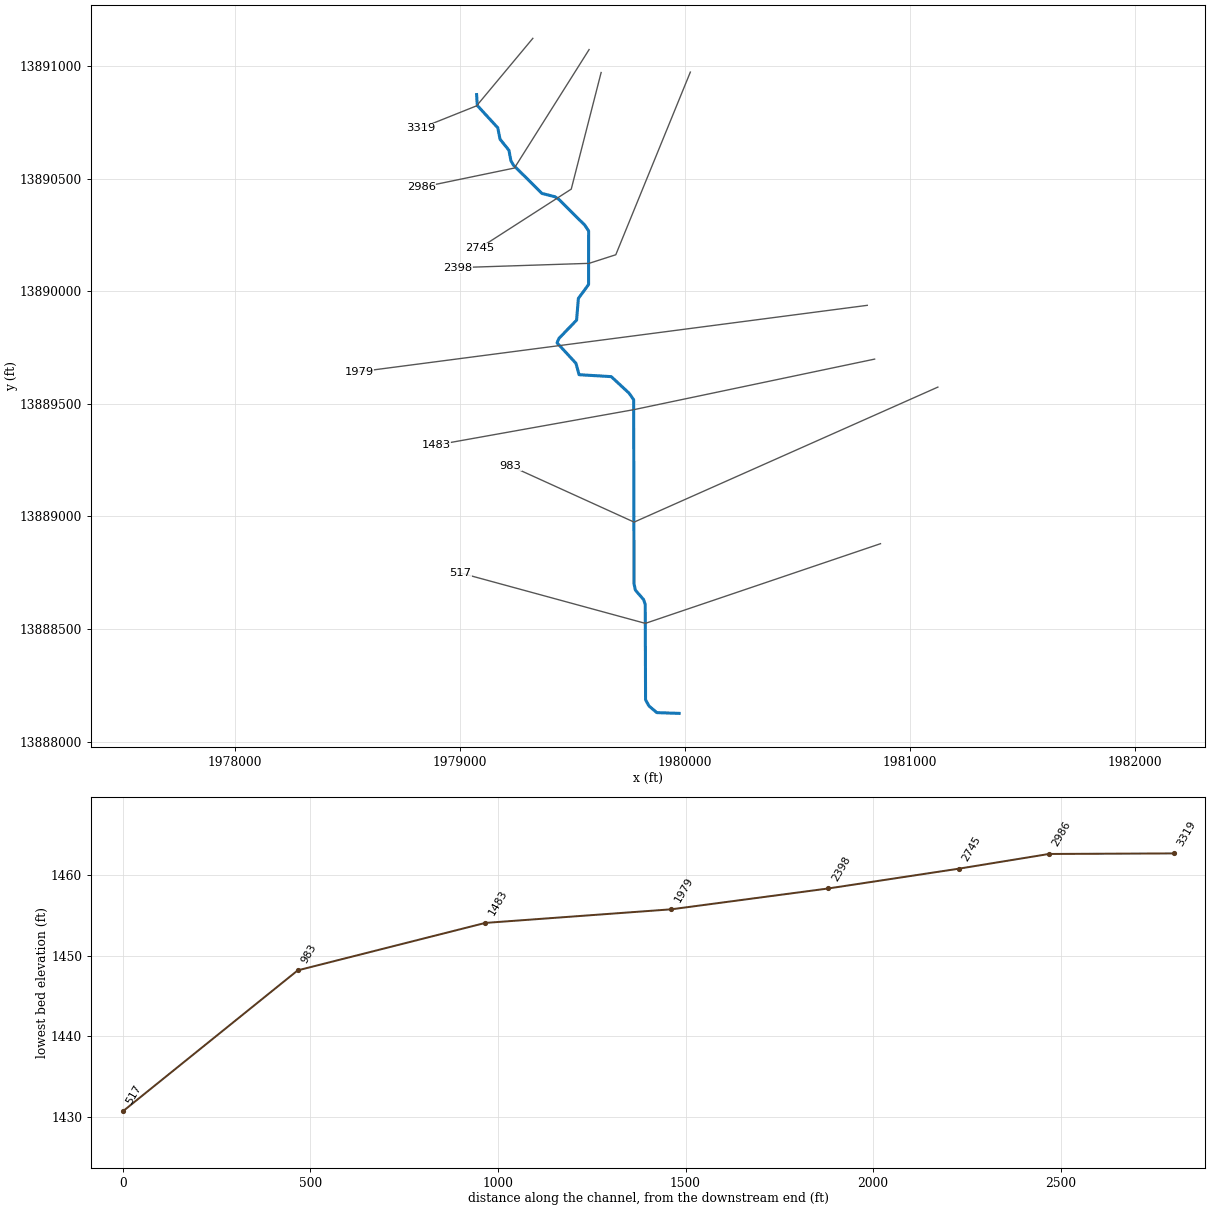
--- Stream0382.prj (project) ---

Proj Title=Stream0382 Base Level Engineering
Current Plan=p01
Default Exp/Contr=0.3,0.1
English Units
Geom File=g01
Flow File=f01
Plan File=p01
Y Axis Title=Elevation
X Axis Title(PF)=Main Channel Distance
X Axis Title(XS)=Station
BEGIN DESCRIPTION:
Stream0382
END DESCRIPTION:
DSS Export Rating Curves= 0
DSS Export Rating Curve Sorted= 0
DSS Export Volume Flow Curves= 0
DXF OffsetX= 0
DXF OffsetY= 0
DXF ScaleX= 1
DXF ScaleY= 10

--- Stream0382.p01 (plan) ---

Plan Title=Multiple Run
Short Identifier=Multiple
Geom File=g01
Flow File=f01
Subcritical Flow
K Sum by GR= 0
Std Step Tol= 0.01
Critical Tol= 0.01
Num of Std Step Trials= 20
Max Error Tol= 0.3
Flow Tol Ratio= 0.001
Split Flow NTrial= 30
Split Flow Tol= 0.02
Split Flow Ratio= 0.02
Log Output Level= 0
Friction Slope Method= 1
Unsteady Friction Slope Method= 2
Unsteady Bridges Friction Slope Method= 1
Parabolic Critical Depth
Global Vel Dist=  1 , 1 , 1
Global Log Level= 0
CheckData=True
Encroach Param= -1, 0, 0, 0
BEGIN DESCRIPTION:
Multiple Run
END DESCRIPTION:

--- Stream0382.f01 (steady flow) ---

Flow Title=Multiple
Program Version=4.10
Number of Profiles= 7
Profile Names=10-year,25-year,50-year,1pct_min,100-year,1pct_plu,500-year
River Rch & RM=Stream0382,Reach-1         ,3319
     776    1281    1747    1155    2304    4598    3967
River Rch & RM=Stream0382,Reach-1         ,2986
     862    1432    1962    1302    2598    5183    4508
Boundary for River Rch & Prof#=Stream0382,Reach-1         , 1
Up Type= 0
Dn Type= 3
Dn Slope=0.008
Boundary for River Rch & Prof#=Stream0382,Reach-1         , 2
Up Type= 0
Dn Type= 3
Dn Slope=0.008
Boundary for River Rch & Prof#=Stream0382,Reach-1         , 3
Up Type= 0
Dn Type= 3
Dn Slope=0.008
Boundary for River Rch & Prof#=Stream0382,Reach-1         , 4
Up Type= 0
Dn Type= 3
Dn Slope=0.008
Boundary for River Rch & Prof#=Stream0382,Reach-1         , 5
Up Type= 0
Dn Type= 3
Dn Slope=0.008
Boundary for River Rch & Prof#=Stream0382,Reach-1         , 6
Up Type= 0
Dn Type= 3
Dn Slope=0.008
Boundary for River Rch & Prof#=Stream0382,Reach-1         , 7
Up Type= 0
Dn Type= 3
Dn Slope=0.008
DSS Import GetInterval= 0
DSS Import GetPeak= 0
DSS Import FillOption= 0

--- Stream0382.g01 (geometry) ---

Geom Title=Existing Conditions
Program Version=4.10

River Reach=Stream0382      ,Reach-1
Reach XY= 30
        1979075.       13890875.      1979078.29     13890826.36
      1979169.16      13890727.3      1979179.19     13890676.73
       1979218.9     13890627.19       1979227.5     13890581.03
      1979238.62     13890561.78      1979365.32     13890435.78
      1979423.35     13890421.02      1979441.67     13890408.35
       1979555.4     13890295.17      1979572.94     13890269.15
      1979572.74     13890030.94      1979527.36     13889969.02
      1979519.45     13889872.57      1979441.23     13889791.65
      1979432.61     13889771.67      1979516.66      13889680.7
      1979530.44     13889630.19      1979673.54     13889621.46
      1979752.16     13889548.59      1979772.95     13889519.16
       1979774.8     13888699.92      1979780.75     13888672.67
      1979816.86     13888631.06      1979824.48     13888609.78
      1979825.97     13888185.27      1979841.21     13888157.78
      1979876.11     13888128.26        1979975.       13888125.

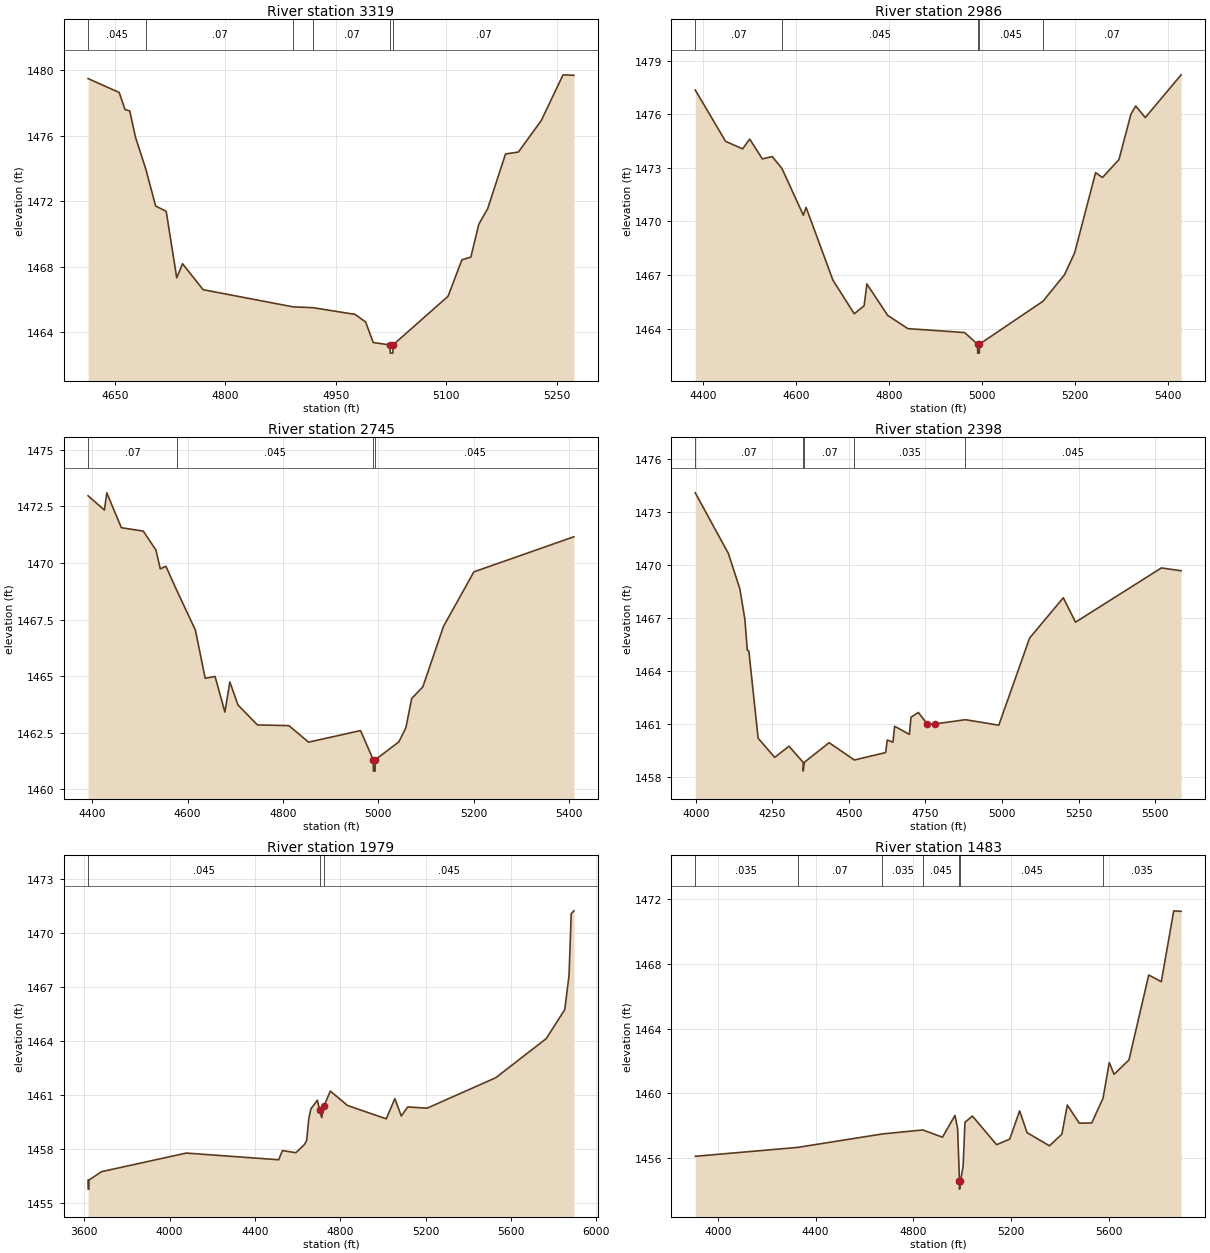
Type RM Length L Ch R = 1 ,3319    ,333,333,333
BEGIN DESCRIPTION:
Stream0382 6.0
END DESCRIPTION:
XS GIS Cut Line= 3
      1979324.98     13891124.97        1979075.       13890825.
      1978825.03     13890725.01
#Sta/Elev= 30
  4613.7  1479.5    4656 1478.65  4663.8 1477.61  4670.3 1477.52  4678.1 1475.91
  4692.1 1473.96  4705.4 1471.71  4719.8 1471.38  4734.1 1467.31  4741.9 1468.18
  4769.9 1466.59  4892.1 1465.54  4918.8 1465.49  4976.2 1465.08  4990.5 1464.62
  5000.9 1463.36  5023.7 1463.21    5024 1462.71  5027.5 1462.71  5027.7 1463.21
  5102.5 1466.19  5121.3 1468.42  5133.4 1468.58  5144.2 1470.59  5156.3 1471.55
  5180.5 1474.89    5198 1475.01    5229 1476.93  5258.6 1479.73  5273.4  1479.7
#Mann= 6 ,-1 , 0
  4613.7    .045       0  4692.1     .07       0  4892.1    .035       0
  4918.8     .07       0  5023.7     .05       0  5027.7     .07       0
Bank Sta=5023.7,5027.7
XS Rating Curve= 0 ,0
Exp/Cntr=0.3,0.1

Type RM Length L Ch R = 1 ,2986    ,241,241,241
BEGIN DESCRIPTION:
Stream0382 5.0
END DESCRIPTION:
XS GIS Cut Line= 3
      1979574.98     13891074.97      1979243.08     13890548.59
      1978829.48     13890462.74
#Sta/Elev= 30
  4383.5 1477.35  4448.8 1474.48  4485.3 1474.06  4500.6 1474.61  4527.7  1473.5
    4549 1473.63    4570 1472.96  4615.9 1470.35  4621.8 1470.79  4679.5 1466.72
  4725.4 1464.84  4746.6 1465.29  4752.5 1466.51  4797.2 1464.75  4840.7 1464.01
  4962.7 1463.79  4990.6 1463.14  4990.8 1462.64  4994.3 1462.64  4994.6 1463.14
  5131.1 1465.54  5177.4 1467.02  5199.3 1468.25  5244.3 1472.73  5259.2 1472.46
  5294.5 1473.46  5320.4 1476.01  5330.6 1476.46  5351.1 1475.81  5428.2  1478.2
#Mann= 5 ,-1 , 0
  4383.5     .07       0    4570    .045       0  4990.6    .045       0
  4994.6    .045       0  5131.1     .07       0
#Block Obstruct= 2 , 0
         4756.55 1465.97
Bank Sta=4990.6,4994.6
XS Rating Curve= 0 ,0
Exp/Cntr=0.3,0.1

Type RM Length L Ch R = 1 ,2745    ,347,347,347
BEGIN DESCRIPTION:
Stream0382 7.0
END DESCRIPTION:
XS GIS Cut Line= 3
       1979628.5     13890973.05      1979495.69     13890454.84
      1979088.44     13890192.85
#Sta/Elev= 30
  4391.3 1472.97  4425.5 1472.34  4430.6  1473.1  4461.1 1471.56    4507 1471.41
  4533.8 1470.57  4542.7 1469.74  4554.5 1469.86  4577.2  1468.8  4616.4 1467.04
    4637 1464.91  4657.7 1464.99  4678.3 1463.42  4688.7 1464.75  4705.8 1463.73
  4746.6 1462.85  4812.5 1462.82  4853.8 1462.09  4962.8  1462.6  4989.6 1461.31
  4989.8 1460.81  4993.3 1460.81  4993.6 1461.31  5043.1  1462.1  5057.9 1462.72
  5070.2 1464.02  5093.5 1464.53  5136.8  1467.2  5200.6 1469.61  5410.5 1471.16
#Mann= 4 ,-1 , 0
  4391.3     .07       0  4577.2    .045       0  4989.6    .045       0
  4993.6    .045       0
#Block Obstruct= 2 , 0
         4689.14 1464.63
Bank Sta=4989.6,4993.6
XS Rating Curve= 0 ,0
Exp/Cntr=0.3,0.1

Type RM Length L Ch R = 1 ,2398    ,419,419,419
BEGIN DESCRIPTION:
Stream0382 4.0
END DESCRIPTION:
XS GIS Cut Line= 4
      1980025.02     13890975.04       1979693.6     13890163.17
        1979575.       13890125.      1978990.52     13890105.88
#Sta/Elev= 30
  3998.6 1474.11  4106.7 1470.68  4144.3 1468.67  4160.7 1466.94  4168.3 1465.22
  4173.7 1465.14  4203.9 1460.22  4257.9 1459.14  4304.7 1459.77  4350.8 1458.86
    4351 1458.36  4354.8 1458.86  4435.7 1459.97    4518 1458.99  4620.1 1459.41
  4625.5 1460.12  4644.1    1460  4649.5  1460.9  4697.6 1460.44    4703 1461.41
    4727 1461.68  4756.4 1461.02  4780.5 1461.03  4880.7 1461.27  4989.6 1460.96
  5090.2 1465.89  5200.2 1468.17  5240.2 1466.79  5520.4 1469.86  5584.9  1469.7
#Mann= 5 ,-1 , 0
  3998.6     .07       0  4350.8    .045       0  4354.8     .07       0
    4518    .035       0  4880.7    .045       0
#Block Obstruct= 2 , 0
         4723.18  1461.5 4745.81         1459.65
Bank Sta=4756.4,4780.5
XS Rating Curve= 0 ,0
Exp/Cntr=0.3,0.1

Type RM Length L Ch R = 1 ,1979    ,496,496,496
BEGIN DESCRIPTION:
Stream0382 7.1
END DESCRIPTION:
XS GIS Cut Line= 2
      1980811.29     13889938.39      1978552.32     13889642.99
#Sta/Elev= 30
  3617.6 1456.27  3617.9 1455.77  3621.4 1455.77  3621.6 1456.27  3680.9 1456.74
  4077.8 1457.77  4511.4  1457.4  4528.6 1457.91  4592.1 1457.79  4632.5 1458.25
  4642.5 1458.47  4652.6 1459.69  4662.7 1460.23    4693  1460.7  4703.1 1460.16
  4713.1 1459.74  4723.2 1460.37  4753.5 1461.21  4834.1 1460.41  5015.7 1459.67
    5056 1460.79  5086.3 1459.83  5116.5 1460.33  5207.3 1460.26  5529.1 1461.95
  5765.8 1464.12  5852.8 1465.73  5872.9 1467.64    5883 1471.05  5895.8 1471.21
#Mann= 3 ,-1 , 0
  3617.6    .045       0  4703.1    .045       0  4723.2    .045       0
#Block Obstruct= 2 , 0
         4685.34 1460.47
Bank Sta=4703.1,4723.2
XS Rating Curve= 0 ,0
Exp/Cntr=0.3,0.1

Type RM Length L Ch R = 1 ,1483    ,500,500,500
BEGIN DESCRIPTION:
Stream0382 3.0
END DESCRIPTION:
XS GIS Cut Line= 3
      1980843.95      13889699.4        1979775.       13889475.
      1978895.24     13889317.47
#Sta/Elev= 30
  3908.2 1456.11  4326.4 1456.66  4672.5 1457.49  4838.4 1457.74  4918.7 1457.29
  4969.8 1458.64  4980.6 1457.84  4988.2 1454.58  4988.5 1454.08  4992.2 1454.58
    5003 1455.48  5010.6 1458.21  5041.1  1458.6  5139.9 1456.83  5193.5 1457.17
  5234.1 1458.92  5264.6 1457.57    5356 1456.76  5406.8 1457.48  5429.1 1459.28
  5477.8 1458.16  5528.7 1458.17  5575.1 1459.71  5600.5 1461.91  5620.1 1461.18
  5681.1 1462.07  5761.8 1467.32  5813.2 1466.91    5864 1471.29  5894.2 1471.26
#Mann= 7 ,-1 , 0
  3908.2    .035       0  4326.4     .07       0  4672.5    .035       0
  4838.4    .045       0  4988.2    .045       0  4992.2    .045       0
  5575.1    .035       0
#Block Obstruct= 2 , 0
         4966.97  1458.6
Bank Sta=4988.2,4992.2
XS Rating Curve= 0 ,0
Exp/Cntr=0.3,0.1

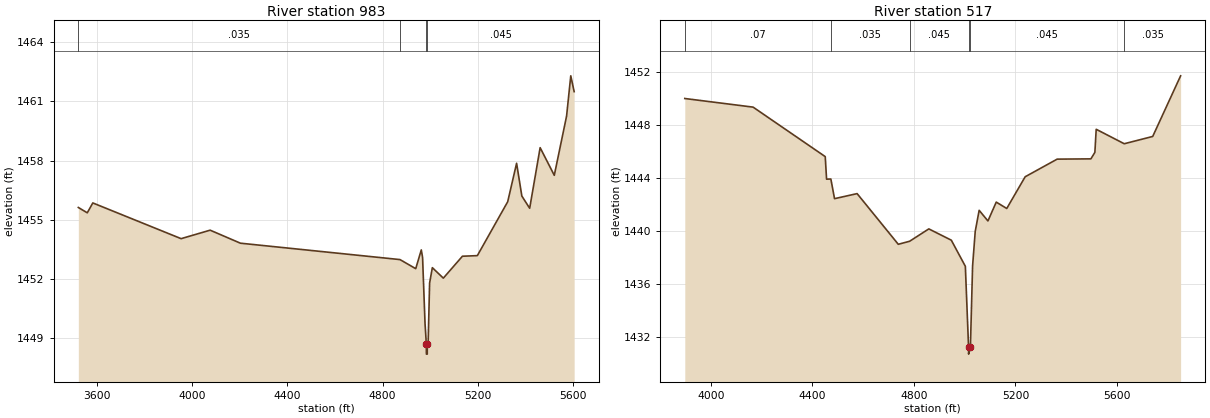
Type RM Length L Ch R = 1 ,983     ,466,466,466
BEGIN DESCRIPTION:
Stream0382 2.0
END DESCRIPTION:
XS GIS Cut Line= 3
      1981124.97     13889574.99        1979775.       13888975.
      1979225.04     13889224.98
#Sta/Elev= 30
  3522.7 1455.62  3560.3 1455.35  3583.5 1455.85  3954.2 1454.04    4076 1454.47
  4203.2 1453.81  4872.9 1452.98  4939.1 1452.52  4962.4 1453.47  4967.8 1453.09
  4978.1 1449.74  4983.6 1448.69  4983.9 1448.19  4987.4 1448.19  4987.6 1448.69
  4991.1 1448.73  4997.3 1451.79  5008.8 1452.57  5054.9 1452.04  5135.1 1453.15
  5197.7 1453.18  5325.1 1455.91  5362.5 1457.86  5384.5  1456.2  5417.4 1455.58
  5461.3 1458.65  5520.7 1457.25  5572.3 1460.25  5589.9 1462.29  5604.1 1461.49
#Mann= 4 ,-1 , 0
  3522.7    .035       0  4872.9    .045       0  4983.6    .045       0
  4987.6    .045       0
Bank Sta=4983.6,4987.6
XS Rating Curve= 0 ,0
Exp/Cntr=0.3,0.1

Type RM Length L Ch R = 1 ,517     ,0,0,0
BEGIN DESCRIPTION:
Stream0382 1.0
END DESCRIPTION:
XS GIS Cut Line= 3
      1980870.03      13888879.1        1979825.       13888525.
      1979003.76     13888748.88
#Sta/Elev= 30
  3896.7 1449.97    4166 1449.32  4450.3 1445.59  4455.6 1443.89  4472.5  1443.9
    4487 1442.42    4576  1442.8  4738.3 1438.98  4783.1 1439.21  4858.7 1440.14
  4947.3 1439.29  5002.7 1437.32  5015.4  1431.2  5015.6  1430.7  5019.4  1431.2
  5022.6 1431.22  5031.2 1437.34  5041.6 1439.95  5057.1 1441.54  5091.7 1440.74
  5124.5 1442.16  5165.9 1441.68  5238.5 1444.07  5364.7  1445.4  5497.6 1445.42
  5513.3 1445.91  5518.5 1447.65  5629.1 1446.56  5741.3 1447.11  5851.3 1451.68
#Mann= 6 ,-1 , 0
  3896.7     .07       0  4472.5    .035       0  4783.1    .045       0
  5015.4    .045       0  5019.4    .045       0  5629.1    .035       0
Bank Sta=5015.4,5019.4
XS Rating Curve= 0 ,0
Exp/Cntr=0.3,0.1

Chan Stop Cuts=-1
Use User Specified Reach Order=0
Composite Channel Slope=5