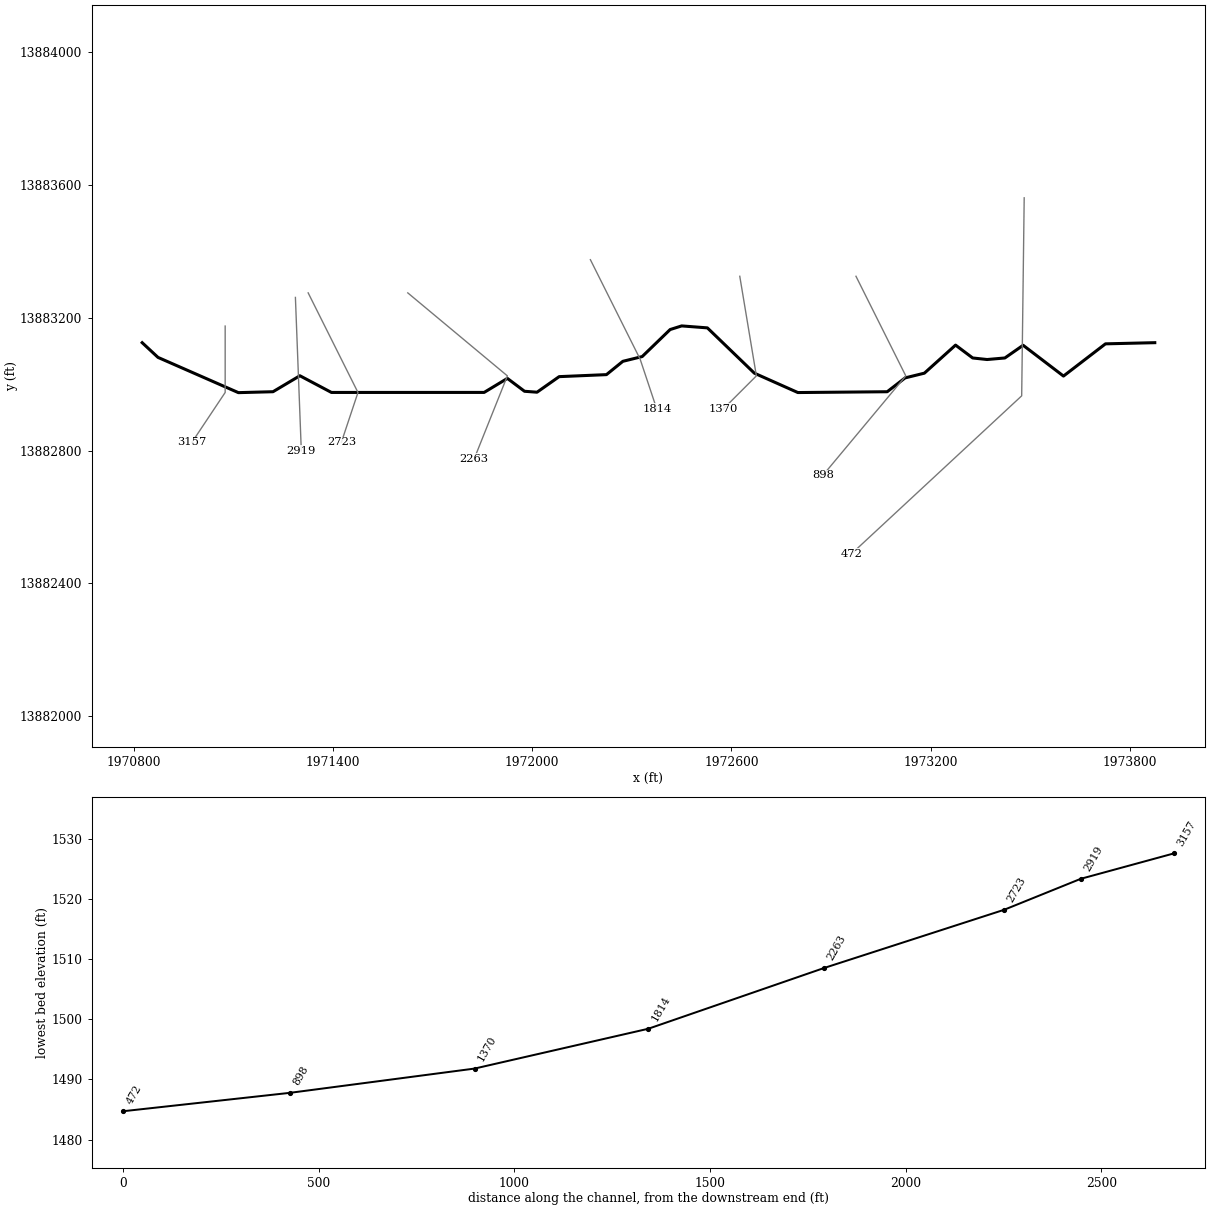
--- Stream0392.prj (project) ---

Proj Title=Stream0392 Base Level Engineering
Current Plan=p01
Default Exp/Contr=0.3,0.1
English Units
Geom File=g01
Flow File=f01
Plan File=p01
BEGIN DESCRIPTION:
Stream0392
END DESCRIPTION:

--- Stream0392.p01 (plan) ---

Plan Title=Multiple Run
Short Identifier=Multiple
Geom File=g01
Flow File=f01
Subcritical Flow
K Sum by GR= 0
Std Step Tol= 0.01
Critical Tol= 0.01
Num of Std Step Trials= 20
Max Error Tol= 0.3
Flow Tol Ratio= 0.001
Split Flow NTrial= 30
Split Flow Tol= 0.02
Split Flow Ratio= 0.02
Log Output Level= 0
Friction Slope Method= 1
Unsteady Friction Slope Method= 2
Unsteady Bridges Friction Slope Method= 1
Parabolic Critical Depth
Global Vel Dist=  1 , 1 , 1
Global Log Level= 0
CheckData=True
Encroach Param= -1, 0, 0, 0
BEGIN DESCRIPTION:
Multiple Run
END DESCRIPTION:

--- Stream0392.f01 (steady flow) ---

Flow Title=Multiple
Number of Profiles=7
Profile Names=10-year,25-year,50-year,1pct_min,100-year,1pct_plu,500-year
River Rch & RM= Stream0392,Reach-1,3157
     521     848    1147     753    1503    2999    2552
Boundary for River Rch & Prof#=Stream0392,Reach-1,1
Up Type=0
Dn Type=3
Dn Slope=0.005
Boundary for River Rch & Prof#=Stream0392,Reach-1,2
Up Type=0
Dn Type=3
Dn Slope=0.005
Boundary for River Rch & Prof#=Stream0392,Reach-1,3
Up Type=0
Dn Type=3
Dn Slope=0.005
Boundary for River Rch & Prof#=Stream0392,Reach-1,4
Up Type=0
Dn Type=3
Dn Slope=0.005
Boundary for River Rch & Prof#=Stream0392,Reach-1,5
Up Type=0
Dn Type=3
Dn Slope=0.005
Boundary for River Rch & Prof#=Stream0392,Reach-1,6
Up Type=0
Dn Type=3
Dn Slope=0.005
Boundary for River Rch & Prof#=Stream0392,Reach-1,7
Up Type=0
Dn Type=3
Dn Slope=0.005

--- Stream0392.g01 (geometry) ---

Geom Title=Existing Conditions

River Reach=Stream0392,Reach-1
Reach XY= 30
      1970825.00     13883125.00      1970872.64     13883080.67
      1971114.83     13882974.50      1971219.07     13882977.28
      1971300.00     13883025.40      1971395.03     13882975.09
      1971855.02     13882975.18      1971925.01     13883017.41
      1971976.64     13882978.61      1972014.29     13882975.82
      1972080.93     13883022.70      1972223.44     13883028.76
      1972272.83     13883068.86      1972331.05     13883083.16
      1972415.22     13883164.55      1972449.97     13883175.50
      1972527.43     13883169.60      1972668.94     13883033.14
      1972799.91     13882974.79      1973069.07     13882977.24
      1973122.83     13883018.86      1973181.06     13883033.18
      1973274.90     13883117.67      1973326.50     13883078.95
      1973369.96     13883074.26      1973423.50     13883078.95
      1973478.41     13883117.19      1973600.00     13883024.42
      1973726.45     13883121.49      1973875.00     13883125.00

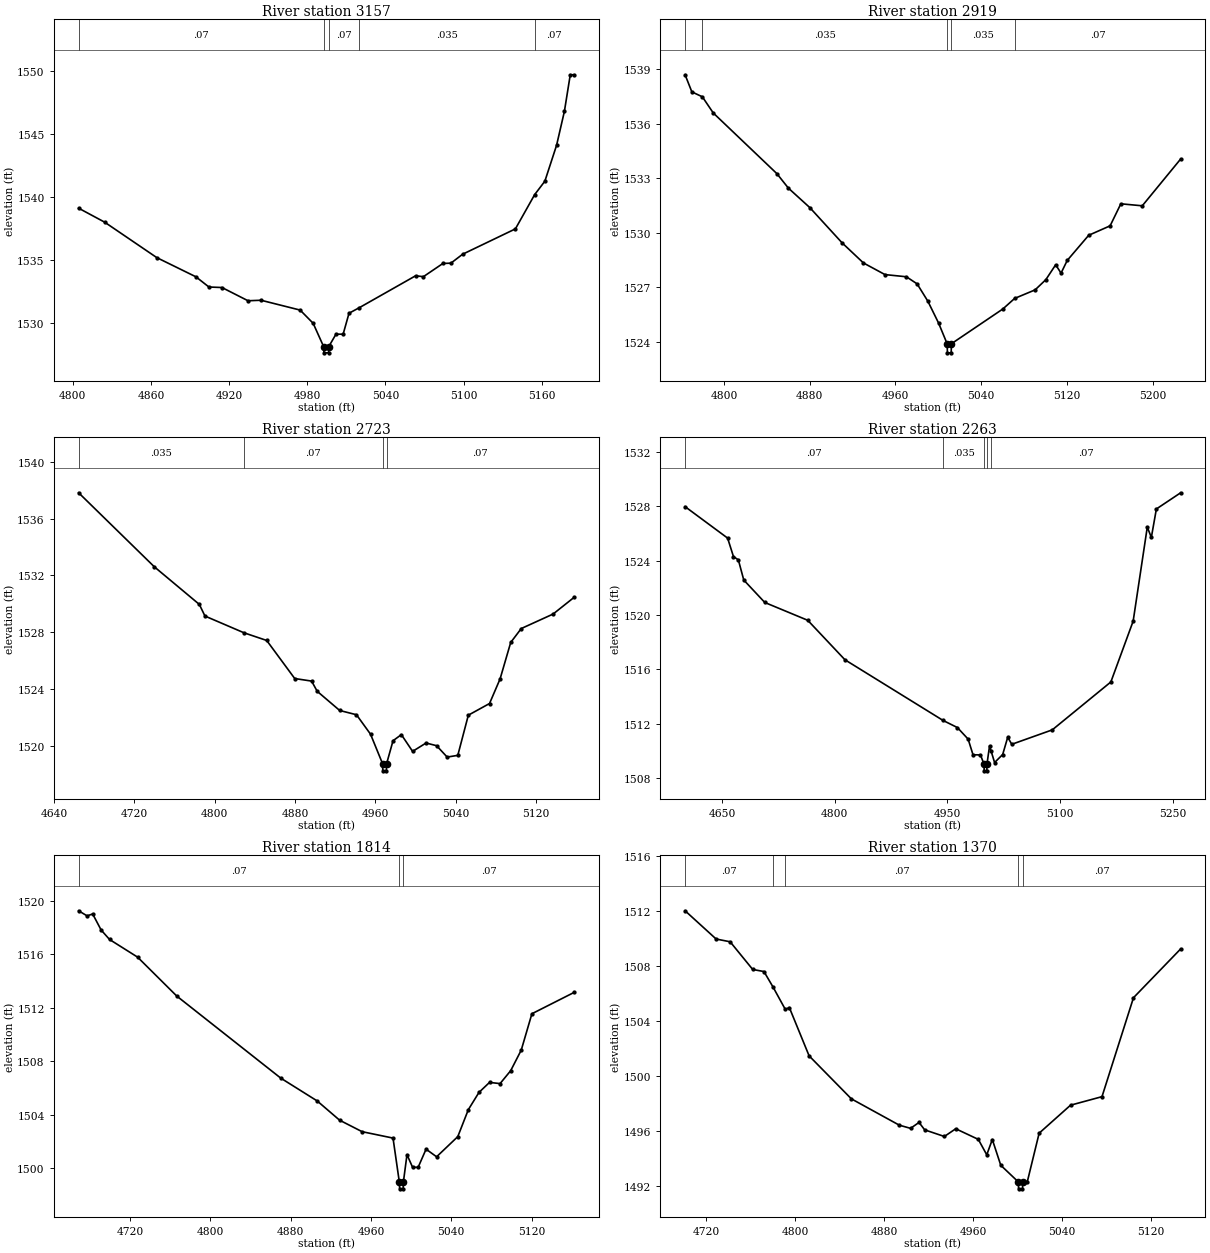
Type RM Length L Ch R = 1,3157,238,238,238
BEGIN DESCRIPTION:
Stream0392 6.0
END DESCRIPTION:
XS GIS Cut Line= 3
      1971075.00     13883175.02      1971075.00     13882975.00
      1970975.00     13882825.00
#Sta/Elev= 30
  4804.5 1539.10  4824.5 1537.99  4864.5 1535.18  4894.5 1533.66  4904.5 1532.85
  4914.5 1532.81  4934.5 1531.76  4944.5 1531.80  4974.5 1531.02  4984.5 1529.97
  4992.5 1528.13  4992.8 1527.63  4996.3 1527.63  4996.5 1528.13  5002.0 1529.11
  5007.5 1529.11  5012.0 1530.77  5019.9 1531.21  5063.1 1533.74  5069.1 1533.67
  5084.1 1534.72  5090.2 1534.74  5099.2 1535.45  5139.7 1537.46  5154.5 1540.18
  5162.3 1541.24  5171.3 1544.09  5177.3 1546.78  5181.8 1549.68  5184.8 1549.68
#Mann=5,-1,0
  4804.5    0.07       0  4992.5    0.05       0  4996.5    0.07       0
  5019.9   0.035       0  5154.5    0.07       0
Bank Sta=4992.5,4996.5
Exp/Cntr=0.3,0.1

Type RM Length L Ch R = 1,2919,196,196,196
BEGIN DESCRIPTION:
Mapping XS e3d8ecf0
END DESCRIPTION:
XS GIS Cut Line= 2
      1971286.55     13883261.32      1971304.32     13882799.26
#Sta/Elev= 30
  4763.8 1538.68  4770.1 1537.74  4779.9 1537.47  4790.1 1536.58  4849.4 1533.25
  4860.2 1532.45  4880.2 1531.38  4910.2 1529.45  4930.2 1528.34  4950.3 1527.70
  4970.3 1527.58  4980.3 1527.19  4990.3 1526.24  5000.3 1525.04  5008.3 1523.90
  5008.6 1523.40  5012.1 1523.40  5012.3 1523.90  5060.3 1525.81  5071.3 1526.39
  5090.4 1526.86  5100.4 1527.42  5109.6 1528.24  5114.6 1527.78  5120.4 1528.48
  5140.4 1529.86  5160.4 1530.38  5170.4 1531.59  5190.4 1531.48  5226.2 1534.05
#Mann=5,-1,0
  4763.8    0.07       0  4779.9   0.035       0  5008.3   0.035       0
  5012.3   0.035       0  5071.3    0.07       0
Bank Sta=5008.3,5012.3
Exp/Cntr=0.3,0.1

Type RM Length L Ch R = 1,2723,460,460,460
BEGIN DESCRIPTION:
Stream0392 5.0
END DESCRIPTION:
XS GIS Cut Line= 3
      1971325.00     13883275.01      1971475.00     13882975.00
      1971425.01     13882825.03
#Sta/Elev= 30
  4664.5 1537.82  4740.0 1532.60  4784.7 1529.96  4790.3 1529.14  4829.2 1527.96
  4851.8 1527.42  4879.7 1524.74  4896.5 1524.56  4902.1 1523.84  4924.5 1522.49
  4941.2 1522.19  4955.2 1520.82  4967.2 1518.74  4967.4 1518.24  4970.9 1518.24
  4971.2 1518.74  4977.6 1520.36  4985.9 1520.79  4997.1 1519.61  5010.5 1520.20
  5021.0 1520.01  5031.5 1519.21  5042.1 1519.33  5052.6 1522.16  5073.7 1522.98
  5084.2 1524.71  5094.8 1527.28  5105.3 1528.26  5137.0 1529.28  5158.0 1530.46
#Mann=4,-1,0
  4664.5   0.035       0  4829.2    0.07       0  4967.2    0.05       0
  4971.2    0.07       0
Bank Sta=4967.2,4971.2
Exp/Cntr=0.3,0.1

Type RM Length L Ch R = 1,2263,449,449,449
BEGIN DESCRIPTION:
Stream0392 4.0
END DESCRIPTION:
XS GIS Cut Line= 3
      1971625.03     13883274.98      1971925.00     13883025.00
      1971825.01     13882775.03
#Sta/Elev= 30
  4600.8 1527.96  4657.4 1525.65  4665.2 1524.29  4671.7 1524.05  4678.9 1522.57
  4706.9 1520.92  4764.1 1519.61  4813.6 1516.71  4944.3 1512.25  4963.3 1511.73
  4977.6 1510.88  4984.1 1509.73  4994.0 1509.72  4998.7 1509.05  4999.0 1508.55
  5002.5 1508.55  5002.7 1509.05  5006.1 1510.38  5008.1 1510.02  5012.8 1509.16
  5023.6 1509.75  5030.3 1511.02  5035.7 1510.50  5089.6 1511.56  5167.6 1515.08
  5197.3 1519.55  5216.1 1526.46  5221.5 1525.70  5228.2 1527.79  5260.5 1528.98
#Mann=5,-1,0
  4600.8    0.07       0  4944.3   0.035       0  4998.7   0.035       0
  5002.7   0.035       0  5008.1    0.07       0
Bank Sta=4998.7,5002.7
Exp/Cntr=0.3,0.1

Type RM Length L Ch R = 1,1814,444,444,444
BEGIN DESCRIPTION:
Stream0392 3.0
END DESCRIPTION:
XS GIS Cut Line= 3
      1972175.00     13883375.00      1972325.00     13883075.00
      1972374.99     13882925.03
#Sta/Elev= 30
  4668.9 1519.26  4677.3 1518.88  4682.9 1519.02  4691.3 1517.82  4699.7 1517.11
  4727.6 1515.79  4766.7 1512.87  4870.2 1506.73  4906.5 1505.02  4928.8 1503.58
  4951.2 1502.72  4982.0 1502.24  4988.3 1498.94  4988.6 1498.44  4992.1 1498.44
  4992.3 1498.94  4995.9 1501.00  5001.5 1500.05  5007.0 1500.05  5014.9 1501.41
  5025.4 1500.84  5046.5 1502.35  5057.0 1504.37  5067.6 1505.66  5078.1 1506.41
  5088.6 1506.32  5099.2 1507.29  5109.7 1508.83  5120.3 1511.55  5162.4 1513.15
#Mann=3,-1,0
  4668.9    0.07       0  4988.3    0.05       0  4992.3    0.07       0
Bank Sta=4988.3,4992.3
Exp/Cntr=0.3,0.1

Type RM Length L Ch R = 1,1370,472,472,472
BEGIN DESCRIPTION:
Stream0392 2.0
END DESCRIPTION:
XS GIS Cut Line= 3
      1972625.00     13883324.97      1972675.00     13883025.00
      1972575.02     13882925.02
#Sta/Elev= 30
  4701.1 1511.99  4729.0 1509.94  4741.6 1509.74  4761.9 1507.73  4772.0 1507.58
  4780.2 1506.45  4791.2 1504.83  4794.8 1504.97  4812.6 1501.46  4850.6 1498.34
  4893.7 1496.43  4903.8 1496.20  4911.4 1496.63  4916.5 1496.09  4934.2 1495.61
  4944.4 1496.17  4964.7 1495.40  4972.3 1494.28  4977.3 1495.39  4984.9 1493.52
  5000.7 1492.31  5000.9 1491.81  5004.4 1491.81  5004.7 1492.31  5008.7 1492.31
  5019.4 1495.85  5047.6 1497.88  5075.9 1498.50  5104.2 1505.68  5146.6 1509.22
#Mann=5,-1,0
  4701.1    0.07       0  4780.2     0.1       0  4791.2    0.07       0
  5000.7    0.05       0  5004.7    0.07       0
Bank Sta=5000.7,5004.7
Exp/Cntr=0.3,0.1

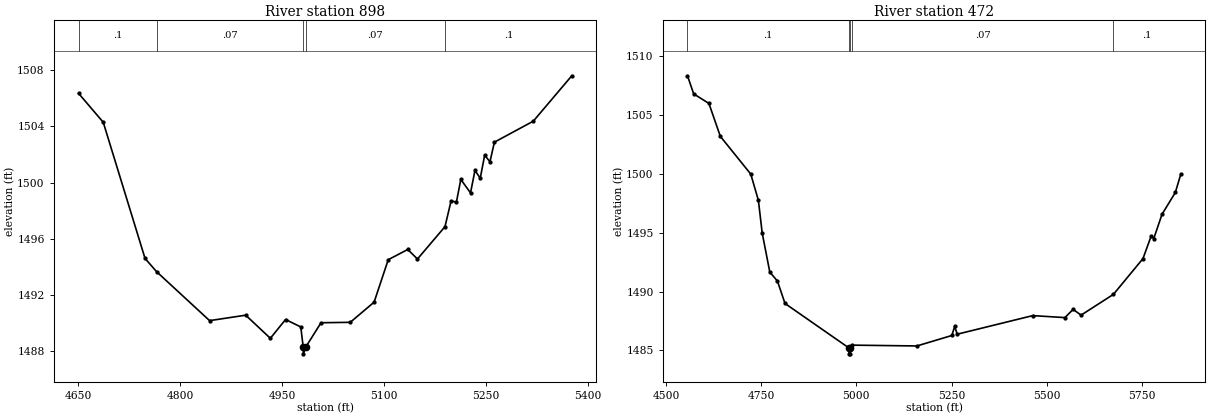
Type RM Length L Ch R = 1,898,426,426,426
BEGIN DESCRIPTION:
Stream0392 1.0
END DESCRIPTION:
XS GIS Cut Line= 3
      1972974.99     13883325.02      1973125.00     13883025.00
      1972875.03     13882725.04
#Sta/Elev= 30
  4650.6 1506.37  4687.0 1504.30  4748.5 1494.58  4765.6 1493.63  4843.5 1490.14
  4896.6 1490.53  4932.9 1488.88  4955.3 1490.22  4977.7 1489.69  4981.2 1488.27
  4981.5 1487.77  4985.2 1488.27  5007.5 1489.99  5050.5 1490.02  5085.6 1491.46
  5106.4 1494.49  5135.1 1495.22  5149.4 1494.54  5189.9 1496.85  5198.9 1498.69
  5206.7 1498.60  5213.2 1500.22  5227.5 1499.26  5234.0 1500.86  5241.8 1500.31
  5248.3 1501.95  5256.1 1501.48  5262.6 1502.88  5319.9 1504.38  5376.5 1507.62
#Mann=5,-1,0
  4650.6     0.1       0  4765.6    0.07       0  4981.2    0.05       0
  4985.2    0.07       0  5189.9     0.1       0
Bank Sta=4981.2,4985.2
Exp/Cntr=0.3,0.1

Type RM Length L Ch R = 1,472,0,0,0
BEGIN DESCRIPTION:
Stream0392 0.0
END DESCRIPTION:
XS GIS Cut Line= 3
      1973481.67     13883561.30      1973474.10     13882964.89
      1972961.24     13882488.83
#Sta/Elev= 30
  4556.2 1508.35  4572.5 1506.81  4612.5 1506.00  4642.5 1503.20  4722.5 1499.99
  4742.5 1497.76  4752.5 1494.99  4772.5 1491.66  4792.5 1490.90  4812.5 1488.99
  4980.5 1485.21  4980.8 1484.71  4984.3 1484.71  4984.5 1485.21  4987.9 1485.45
  5159.0 1485.38  5250.9 1486.27  5258.2 1487.04  5265.1 1486.38  5463.5 1487.96
  5548.0 1487.79  5569.5 1488.49  5590.5 1488.00  5675.6 1489.77  5753.2 1492.81
  5774.7 1494.73  5781.5 1494.51  5803.1 1496.57  5838.2 1498.43  5852.4 1499.97
#Mann=5,-1,0
  4556.2     0.1       0  4980.5    0.05       0  4984.5     0.1       0
  4987.9    0.07       0  5675.6     0.1       0
Bank Sta=4980.5,4984.5
Exp/Cntr=0.3,0.1

Chan Stop Cuts=-1