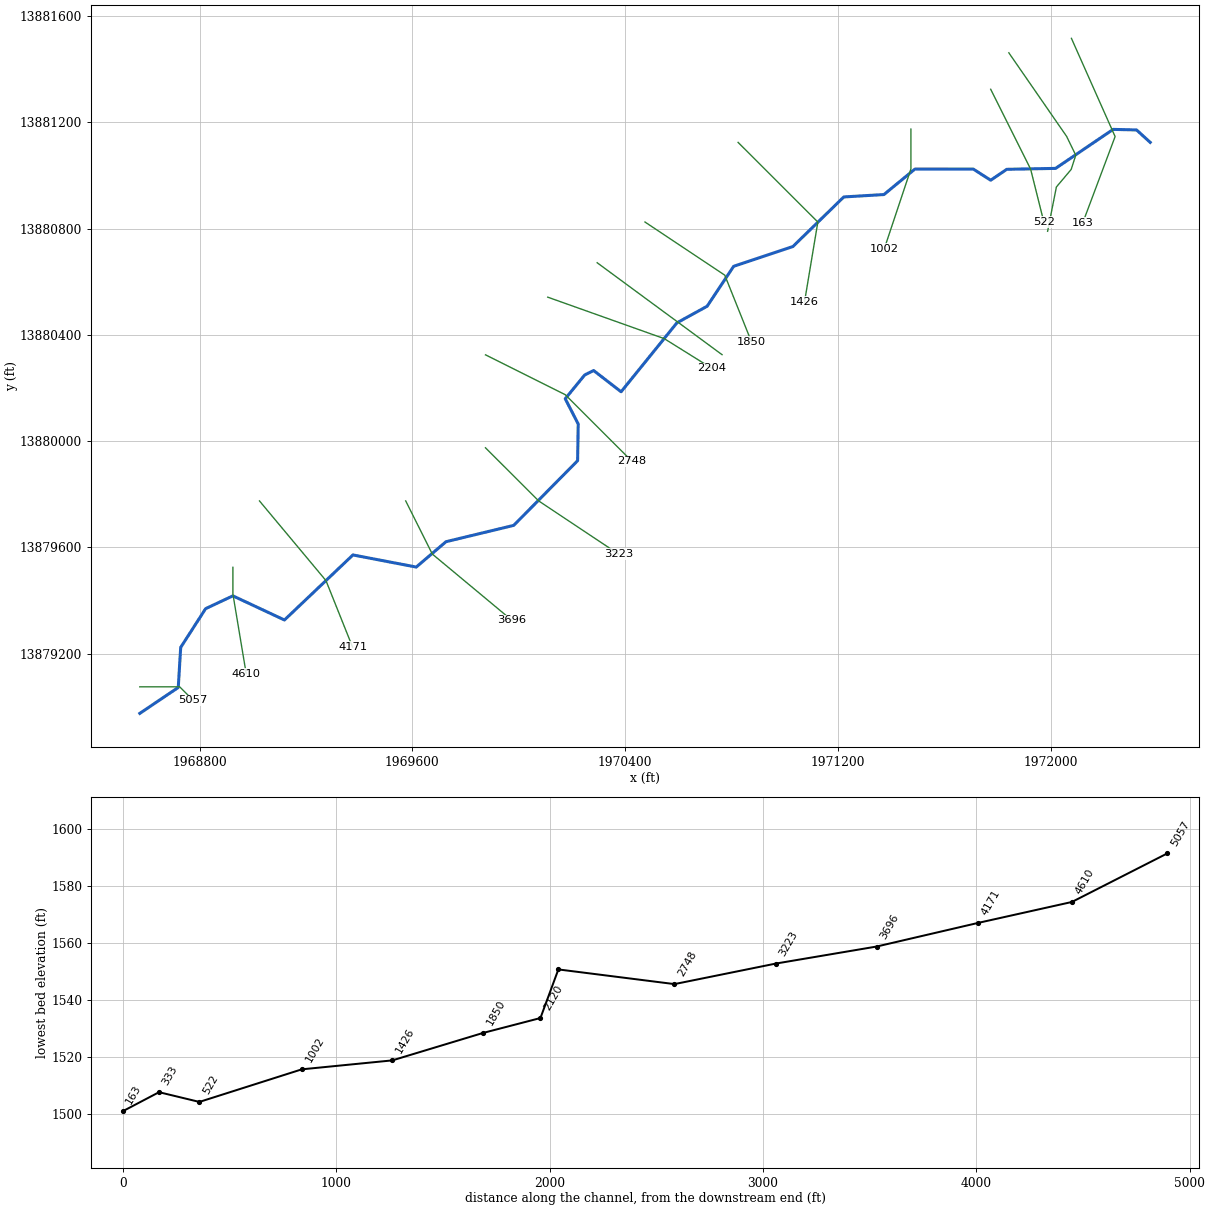
--- Stream0396.prj (project) ---

Proj Title=Stream0396 Base Level Engineering
Current Plan=p01
Default Exp/Contr=0.3,0.1
English Units
Geom File=g01
Flow File=f01
Plan File=p01
Y Axis Title=Elevation
X Axis Title(PF)=Main Channel Distance
X Axis Title(XS)=Station
BEGIN DESCRIPTION:
Stream0396
END DESCRIPTION:
DSS Export Rating Curves= 0
DSS Export Rating Curve Sorted= 0
DSS Export Volume Flow Curves= 0
DXF OffsetX= 0
DXF OffsetY= 0
DXF ScaleX= 1
DXF ScaleY= 10

--- Stream0396.p01 (plan) ---

Plan Title=Multiple Run
Short Identifier=Multiple
Geom File=g01
Flow File=f01
Subcritical Flow
K Sum by GR= 0
Std Step Tol= 0.01
Critical Tol= 0.01
Num of Std Step Trials= 20
Max Error Tol= 0.3
Flow Tol Ratio= 0.001
Split Flow NTrial= 30
Split Flow Tol= 0.02
Split Flow Ratio= 0.02
Log Output Level= 0
Friction Slope Method= 1
Unsteady Friction Slope Method= 2
Unsteady Bridges Friction Slope Method= 1
Parabolic Critical Depth
Global Vel Dist=  1 , 1 , 1
Global Log Level= 0
CheckData=True
Encroach Param= -1, 0, 0, 0
BEGIN DESCRIPTION:
Multiple Run
END DESCRIPTION:

--- Stream0396.f01 (steady flow) ---

Flow Title=Multiple
Program Version=4.10
Number of Profiles= 7
Profile Names=10-year,25-year,50-year,1pct_min,100-year,1pct_plu,500-year
River Rch & RM=Stream0396,Reach-1         ,5057
     147     216     272     168     335     668     495
River Rch & RM=Stream0396,Reach-1         ,4610
     405     653     878     574    1146    2287    1929
River Rch & RM=Stream0396,Reach-1         ,2748
     642    1064    1458     971    1937    3864    3377
Boundary for River Rch & Prof#=Stream0396,Reach-1         , 1
Up Type= 0
Dn Type= 3
Dn Slope=0.01
Boundary for River Rch & Prof#=Stream0396,Reach-1         , 2
Up Type= 0
Dn Type= 3
Dn Slope=0.01
Boundary for River Rch & Prof#=Stream0396,Reach-1         , 3
Up Type= 0
Dn Type= 3
Dn Slope=0.01
Boundary for River Rch & Prof#=Stream0396,Reach-1         , 4
Up Type= 0
Dn Type= 3
Dn Slope=0.01
Boundary for River Rch & Prof#=Stream0396,Reach-1         , 5
Up Type= 0
Dn Type= 3
Dn Slope=0.01
Boundary for River Rch & Prof#=Stream0396,Reach-1         , 6
Up Type= 0
Dn Type= 3
Dn Slope=0.01
Boundary for River Rch & Prof#=Stream0396,Reach-1         , 7
Up Type= 0
Dn Type= 3
Dn Slope=0.01
DSS Import GetInterval= 0
DSS Import GetPeak= 0
DSS Import FillOption= 0

--- Stream0396.g01 (geometry) ---

Geom Title=Existing Conditions
Program Version=4.10

River Reach=Stream0396      ,Reach-1
Reach XY= 30
        1968575.       13878975.      1968719.55     13879072.53
      1968728.76     13879223.44      1968822.46      13879369.3
        1968925.      13879417.5      1969118.96     13879326.61
       1969376.5     13879571.54      1969614.52     13879525.94
       1969726.5     13879621.38      1969981.17     13879682.86
      1970221.47     13879926.47      1970223.77      13880064.5
      1970174.95     13880159.68      1970248.26     13880249.36
      1970281.66     13880266.01      1970385.02     13880185.95
      1970594.84     13880445.38       1970708.5     13880507.95
      1970808.29     13880658.37      1971031.17     13880732.86
      1971222.55     13880919.53      1971373.53     13880928.56
      1971490.16     13881024.61      1971709.84     13881024.34
        1971775.     13880982.56      1971835.44     13881023.62
      1972019.14     13881027.07      1972235.53     13881173.93
       1972323.6     13881171.81        1972375.       13881125.

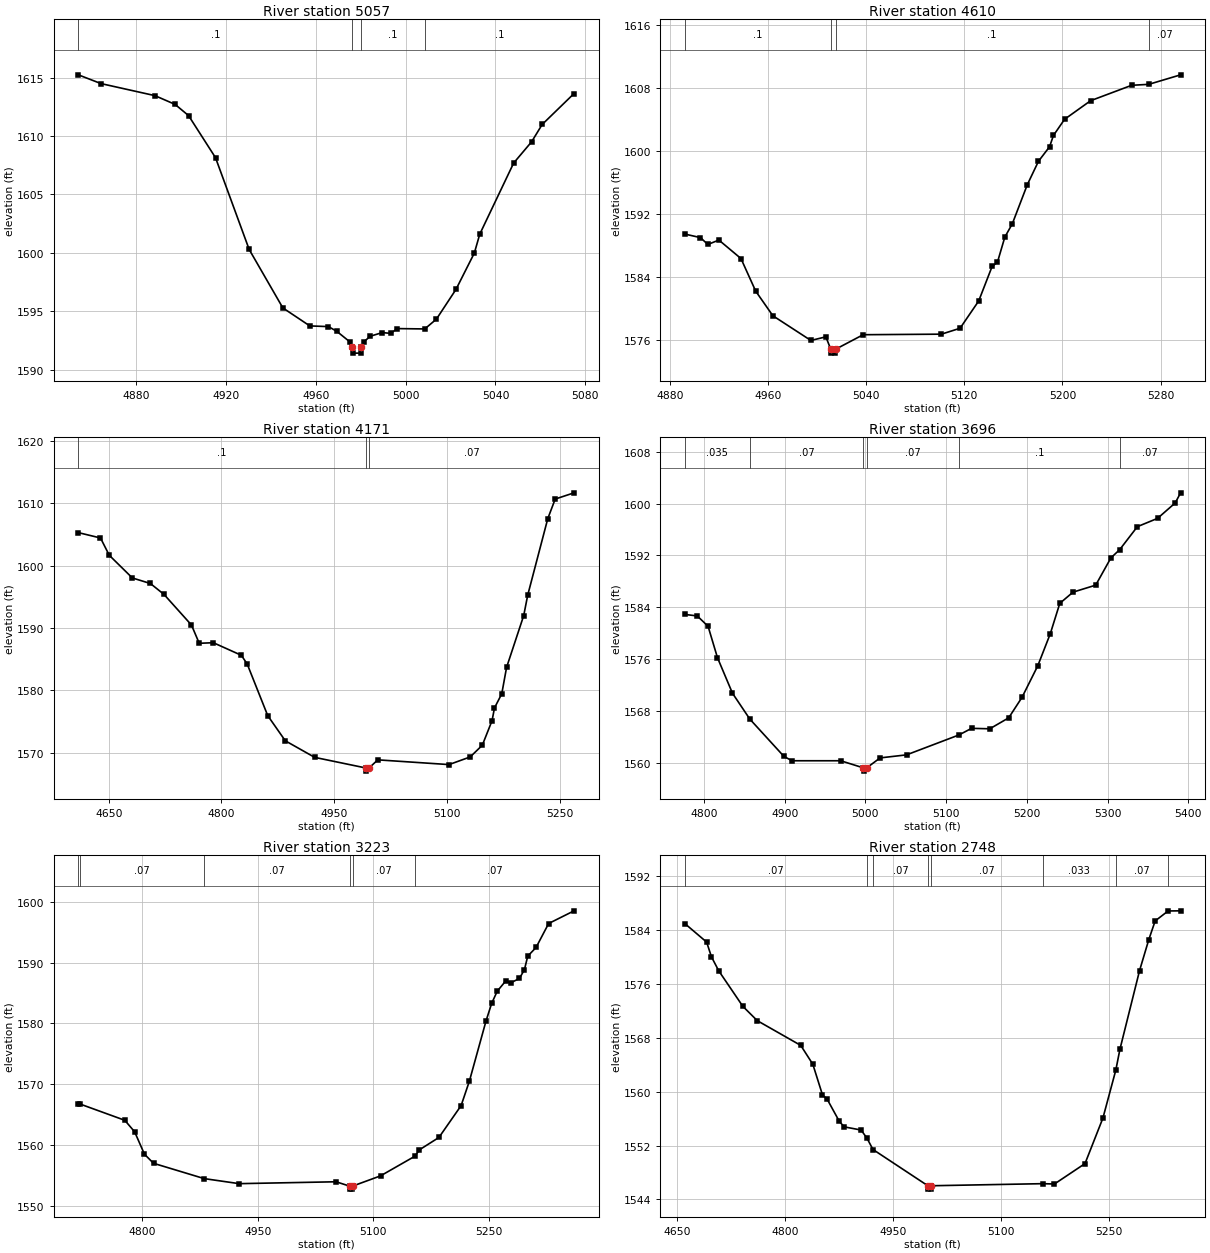
Type RM Length L Ch R = 1 ,5057    ,447,447,447
BEGIN DESCRIPTION:
Stream0396 11.0
END DESCRIPTION:
XS GIS Cut Line= 3
      1968574.96       13879075.        1968725.       13879075.
      1968775.03     13879024.97
#Sta/Elev= 30
  4854.2 1615.23  4864.3 1614.48  4888.3 1613.45  4897.3  1612.7  4903.3 1611.74
  4915.3 1608.14  4930.3 1600.28  4945.3 1595.28  4957.3 1593.74  4965.6 1593.68
  4969.3 1593.28  4975.3 1592.35  4976.3 1591.91  4976.5 1591.41    4980 1591.41
  4980.3 1591.91  4981.3 1592.37  4984.3 1592.86  4989.6 1593.17  4993.3  1593.1
  4996.3 1593.51  5008.5 1593.48  5013.7 1594.32  5022.4 1596.86  5030.6 1599.98
    5033 1601.59  5048.1 1607.68  5056.1  1609.5  5060.8 1610.98    5075 1613.63
#Mann= 4 ,-1 , 0
  4854.2      .1       0  4976.3     .05       0  4980.3      .1       0
  5008.5      .1       0
Bank Sta=4976.3,4980.3
XS Rating Curve= 0 ,0
Exp/Cntr=0.3,0.1

Type RM Length L Ch R = 1 ,4610    ,439,439,439
BEGIN DESCRIPTION:
Stream0396 10.0
END DESCRIPTION:
XS GIS Cut Line= 3
        1968925.     13879524.99        1968925.       13879425.
      1968974.99     13879125.03
#Sta/Elev= 30
  4892.2 1589.49  4904.9 1589.04  4910.9 1588.17  4919.9 1588.73  4937.9 1586.38
  4949.9 1582.24  4963.9 1579.11  4994.9 1575.97  5007.1 1576.43  5011.1 1574.86
  5011.4 1574.36  5014.9 1574.36  5015.1 1574.86  5037.5  1576.7  5101.3 1576.77
  5116.5 1577.52  5131.7 1580.99  5142.6 1585.37    5147 1585.93    5153 1589.11
  5159.1  1590.8  5171.3 1595.76  5180.4 1598.74  5189.5  1600.6  5192.6 1602.02
  5201.7 1604.08  5222.9 1606.44  5256.4  1608.4  5270.3 1608.52  5296.3 1609.73
#Mann= 4 ,-1 , 0
  4892.2      .1       0  5011.1     .05       0  5015.1      .1       0
  5270.3     .07       0
Bank Sta=5011.1,5015.1
XS Rating Curve= 0 ,0
Exp/Cntr=0.3,0.1

Type RM Length L Ch R = 1 ,4171    ,475,475,475
BEGIN DESCRIPTION:
Stream0396 9.0
END DESCRIPTION:
XS GIS Cut Line= 3
      1969024.98     13879775.02        1969275.       13879475.
        1969375.       13879225.
#Sta/Elev= 30
  4609.5 1605.32    4639 1604.46  4650.7 1601.68  4681.4 1598.04  4705.4 1597.15
  4723.6 1595.39  4760.1 1590.48  4770.4 1587.55  4789.2 1587.64  4826.5 1585.62
  4834.3 1584.21  4861.6 1575.93    4885 1571.89  4924.1 1569.23  4992.4 1567.52
  4992.6 1567.02  4996.4 1567.52  5008.1 1568.83  5102.9 1568.07  5131.1  1569.3
  5147.2 1571.18  5160.2 1575.14  5163.4 1577.17  5173.1 1579.44  5179.5 1583.68
  5202.3    1592  5207.6 1595.26  5234.3 1607.55  5244.2 1610.71  5269.3 1611.71
#Mann= 3 ,-1 , 0
  4609.5      .1       0  4992.4     .05       0  4996.4     .07       0
Bank Sta=4992.4,4996.4
XS Rating Curve= 0 ,0
Exp/Cntr=0.3,0.1

Type RM Length L Ch R = 1 ,3696    ,473,473,473
BEGIN DESCRIPTION:
Stream0396 8.0
END DESCRIPTION:
XS GIS Cut Line= 3
      1969575.01     13879774.98        1969675.       13879575.
        1969975.       13879325.
#Sta/Elev= 30
  4776.4  1582.9  4791.7 1582.67  4805.1 1581.07  4816.7 1576.24  4835.3 1570.75
  4856.8 1566.76    4899 1561.01    4909 1560.33  4969.4 1560.33  4997.6 1559.23
  4997.9 1558.73  5001.6 1559.23  5018.2 1560.77    5051 1561.24  5115.9 1564.31
  5131.5 1565.33  5154.1 1565.26  5177.5 1566.95    5194 1570.11  5213.5 1574.97
  5229.1 1579.95  5240.8 1584.61  5257.2 1586.34  5285.3 1587.42  5304.1 1591.62
  5315.1 1592.91  5336.9 1596.44  5361.9 1597.72  5383.7 1600.09  5390.5 1601.66
#Mann= 6 ,-1 , 0
  4776.4    .035       0  4856.8     .07       0  4997.6     .05       0
  5001.6     .07       0  5115.9      .1       0  5315.1     .07       0
Bank Sta=4997.6,5001.6
XS Rating Curve= 0 ,0
Exp/Cntr=0.3,0.1

Type RM Length L Ch R = 1 ,3223    ,475,475,475
BEGIN DESCRIPTION:
Stream0396 7.0
END DESCRIPTION:
XS GIS Cut Line= 3
      1969874.99     13879975.01        1970075.       13879775.
      1970374.99     13879575.01
#Sta/Elev= 30
  4717.1 1566.76  4719.4 1566.74  4777.4 1564.07  4790.2 1562.17  4802.9 1558.49
  4814.7 1556.99  4880.5 1554.47  4925.9 1553.64  5051.6 1553.95  5069.1 1553.24
  5069.4 1552.74  5072.9 1552.74  5073.1 1553.24  5109.3 1554.92    5154 1558.16
  5159.8 1559.21  5185.1 1561.24  5213.9 1566.48  5224.7 1570.53  5246.3 1580.44
  5253.6 1583.32  5260.8 1585.31  5271.6 1586.97  5278.8 1586.72  5289.6 1587.41
  5296.1 1588.86  5300.4 1591.08  5311.2 1592.51  5327.5 1596.45  5360.5 1598.54
#Mann= 6 ,-1 , 0
  4717.1    .035       0  4719.4     .07       0  4880.5     .07       0
  5069.1     .05       0  5073.1     .07       0    5154     .07       0
Bank Sta=5069.1,5073.1
XS Rating Curve= 0 ,0
Exp/Cntr=0.3,0.1

Type RM Length L Ch R = 1 ,2748    ,544,544,544
BEGIN DESCRIPTION:
Stream0396 6.0
END DESCRIPTION:
XS GIS Cut Line= 3
      1969874.99     13880325.01        1970175.       13880175.
      1970425.01     13879924.99
#Sta/Elev= 30
  4660.7 1584.93  4690.9 1582.19  4697.6    1580  4707.7 1577.93  4741.2 1572.66
  4761.3 1570.53  4821.7 1566.86  4838.5 1564.06  4851.9 1559.52  4858.6 1558.84
  4875.4 1555.57  4882.1 1554.77  4905.6  1554.3  4913.8 1553.08  4922.1 1551.41
  4998.4 1546.03  4998.6 1545.53  5002.1 1545.53  5002.4 1546.03  5158.1 1546.34
  5174.3 1546.29  5216.8 1549.32  5241.7 1556.08  5259.6 1563.19  5265.3 1566.27
  5292.6 1577.96  5305.4 1582.54  5314.3 1585.33  5332.3 1586.81  5349.7 1586.83
#Mann= 8 ,-1 , 0
  4660.7     .07       0  4913.8    .035       0  4922.1     .07       0
  4998.4     .05       0  5002.4     .07       0  5158.1    .033       0
  5259.6     .07       0  5332.3      .1       0
Bank Sta=4998.4,5002.4
XS Rating Curve= 0 ,0
Exp/Cntr=0.3,0.1

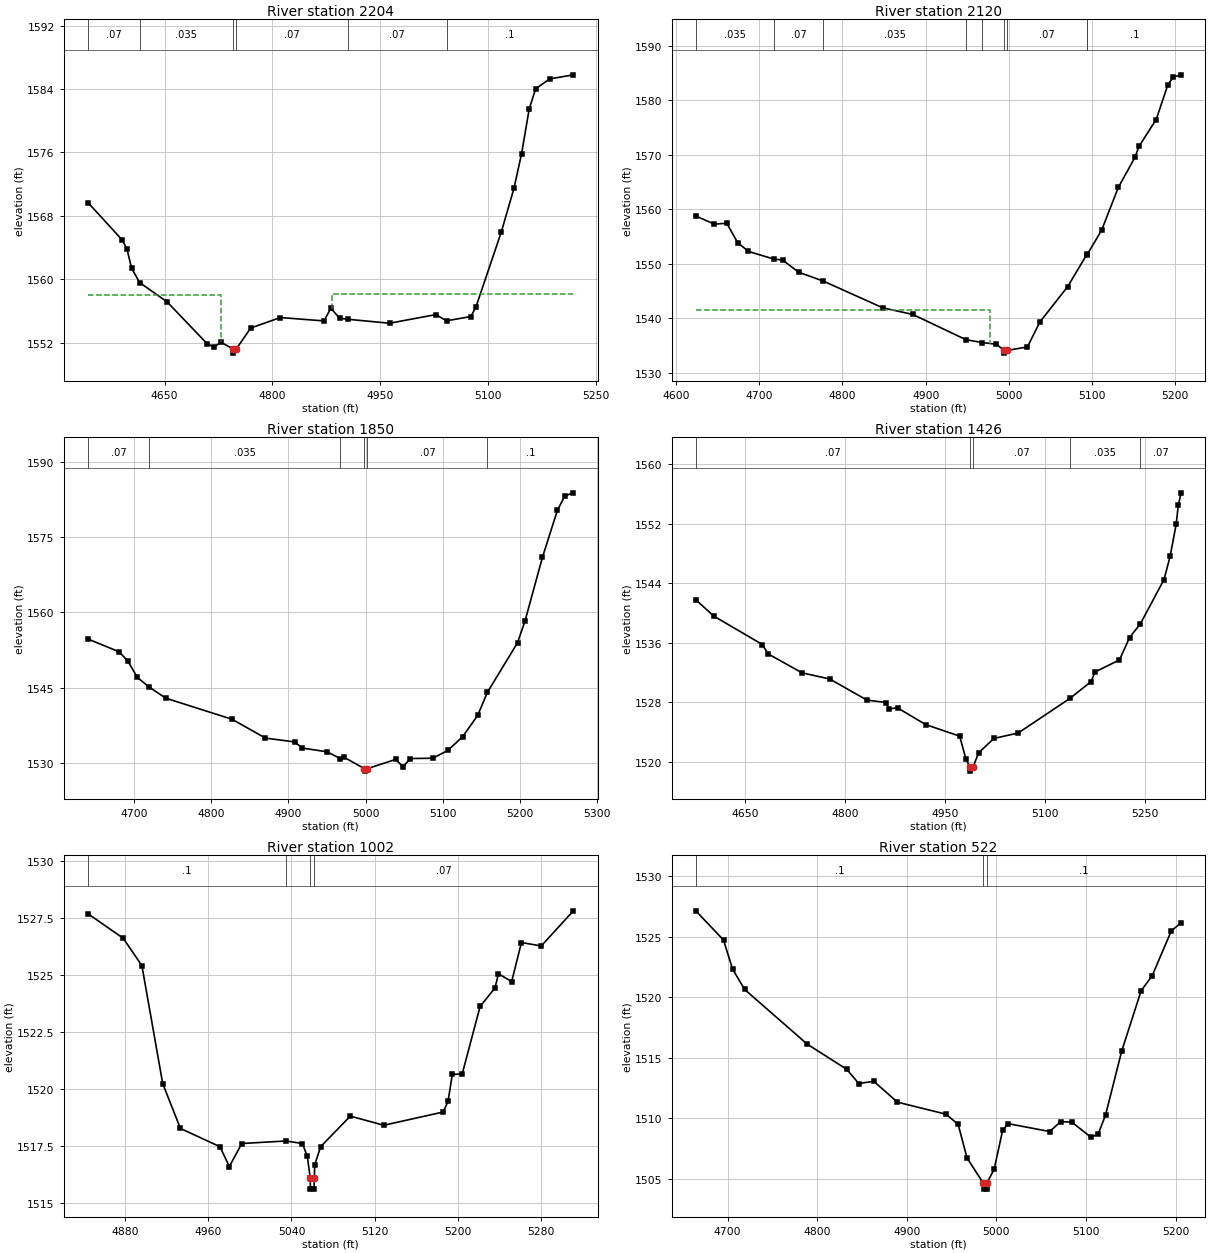
Type RM Length L Ch R = 1 ,2204    ,84,84,84
BEGIN DESCRIPTION:
Stream0396 5.0
END DESCRIPTION:
XS GIS Cut Line= 3
      1970108.99     13880542.26      1970547.41     13880385.99
      1970725.04     13880274.98
#Sta/Elev= 30
  4543.7 1569.66  4591.5 1564.92  4597.9 1563.77  4604.2  1561.4  4615.4 1559.58
  4653.7 1557.14  4709.3 1551.86  4718.9 1551.44  4728.4 1552.07  4745.6 1551.18
  4745.8 1550.68  4749.6 1551.18  4769.8 1553.84  4811.2 1555.17  4871.8 1554.74
  4881.3 1556.34  4893.6 1555.08  4904.9 1554.95  4962.9 1554.45  5027.3 1555.54
  5042.2 1554.76  5075.9 1555.29    5083 1556.48  5118.3 1565.94    5136 1571.48
  5146.5 1575.81  5157.2  1581.5  5166.2 1584.02  5185.5 1585.26  5218.6 1585.78
#Mann= 6 ,-1 , 0
  4543.7     .07       0  4615.4    .035       0  4745.6     .05       0
  4749.6     .07       0  4904.9     .07       0  5042.2      .1       0
#XS Ineff= 2 , 0
         4728.57 1557.98 4882.82         1558.14
Permanent Ineff=
       F       F
Bank Sta=4745.6,4749.6
XS Rating Curve= 0 ,0
Exp/Cntr=0.3,0.1

Type RM Length L Ch R = 1 ,2120    ,270,270,270
BEGIN DESCRIPTION:
Mapping XS cdafad7d
END DESCRIPTION:
XS GIS Cut Line= 2
      1970295.09     13880671.76      1970764.78     13880325.56
#Sta/Elev= 30
  4623.7 1558.77    4646 1557.29  4660.9 1557.45    4674  1553.9    4687 1552.28
  4717.4 1550.88    4728  1550.7  4747.4 1548.46  4777.1 1546.83  4848.6 1541.92
  4884.5 1540.72  4948.5 1536.08  4968.1 1535.56  4985.1 1535.25  4994.3 1534.12
  4994.5 1533.62  4998.3 1534.12  5022.4 1534.76  5037.3 1539.32  5070.8 1545.83
  5093.5 1551.65  5094.5 1551.77  5111.5 1556.15  5131.7 1564.03  5151.9 1569.61
  5156.5 1571.55  5177.2 1576.48  5191.1 1582.81  5197.5 1584.25  5207.2 1584.68
#Mann= 9 ,-1 , 0
  4623.7    .035       0  4717.4     .07       0  4777.1    .035       0
  4948.5     .07       0  4968.1     .07       0  4994.3     .05       0
  4998.3     .07       0  5093.5     .07       0  5094.5      .1       0
#XS Ineff= 2 , 0
         4977.62  1541.5
Permanent Ineff=
       F       F
Bank Sta=4994.3,4998.3
XS Rating Curve= 0 ,0
Exp/Cntr=0.3,0.1

Type RM Length L Ch R = 1 ,1850    ,424,424,424
BEGIN DESCRIPTION:
Stream0396 4.0
END DESCRIPTION:
XS GIS Cut Line= 3
      1970474.99     13880825.01        1970775.       13880625.
      1970874.99     13880375.02
#Sta/Elev= 30
  4639.9 1554.67  4680.1 1552.14  4691.6 1550.27  4703.9 1547.02  4718.6 1545.18
  4740.6  1542.9  4826.8 1538.69  4870.1 1534.94  4907.9 1534.18    4918 1532.95
    4950 1532.21  4967.1 1530.87  4971.6 1531.16  4998.5 1528.86  4998.7 1528.36
  5002.5 1528.86  5038.9 1530.69  5048.6 1529.25  5058.3 1530.87  5087.3 1530.93
  5106.7 1532.47  5126.1 1535.24  5145.5 1539.46  5158.1 1544.05  5197.2 1553.94
  5206.9 1558.26  5229.5 1570.94  5248.9 1580.29  5258.6  1583.2  5269.7  1583.8
#Mann= 6 ,-1 , 0
  4639.9     .07       0  4718.6    .035       0  4967.1     .07       0
  4998.5     .05       0  5002.5     .07       0  5158.1      .1       0
Bank Sta=4998.5,5002.5
XS Rating Curve= 0 ,0
Exp/Cntr=0.3,0.1

Type RM Length L Ch R = 1 ,1426    ,424,424,424
BEGIN DESCRIPTION:
Stream0396 3.0
END DESCRIPTION:
XS GIS Cut Line= 3
      1970824.99     13881125.01        1971125.       13880825.
        1971075.     13880525.02
#Sta/Elev= 30
  4575.7 1541.77  4602.6 1539.58  4675.6 1535.76  4684.1 1534.51    4735 1531.96
  4776.6 1531.13  4832.6 1528.29  4861.4 1527.97  4865.6 1527.12  4878.4 1527.25
  4920.8    1525  4971.7 1523.45  4981.1 1520.37  4987.6 1519.25  4987.9 1518.75
  4991.6 1519.25    5000 1521.19    5023 1523.14  5059.5 1523.87  5137.5 1528.54
  5168.9 1530.78    5175 1532.08  5211.5 1533.69  5226.7  1536.7  5242.9 1538.54
  5278.4 1544.49  5287.6 1547.63  5296.7 1551.94  5299.7 1554.44  5304.1 1556.14
#Mann= 5 ,-1 , 0
  4575.7     .07       0  4987.6     .05       0  4991.6     .07       0
  5137.5    .035       0  5242.9     .07       0
Bank Sta=4987.6,4991.6
XS Rating Curve= 0 ,0
Exp/Cntr=0.3,0.1

Type RM Length L Ch R = 1 ,1002    ,480,480,480
BEGIN DESCRIPTION:
Stream0396 2.0
END DESCRIPTION:
XS GIS Cut Line= 3
        1971475.     13881175.01        1971475.       13881025.
      1971375.01     13880725.04
#Sta/Elev= 30
  4844.6 1527.68  4878.3 1526.61  4896.3 1525.41  4916.3 1520.24  4933.3 1518.27
  4971.3 1517.47  4980.3  1516.6  4992.3 1517.61  5034.6 1517.72  5050.5 1517.61
  5055.2 1517.05    5058 1516.11  5058.2 1515.61  5061.7 1515.61    5062 1516.11
  5062.3 1516.67    5068 1517.47  5096.5 1518.81  5128.7 1518.41  5185.7 1518.99
  5190.4 1519.46  5194.5 1520.64    5204 1520.66  5221.2 1523.62  5235.5 1524.43
  5238.8 1525.05  5251.5 1524.71  5260.9 1526.42  5279.9 1526.27  5310.8 1527.81
#Mann= 4 ,-1 , 0
  4844.6      .1       0  5034.6     .07       0    5058     .05       0
    5062     .07       0
Bank Sta=5058,5062
XS Rating Curve= 0 ,0
Exp/Cntr=0.3,0.1

Type RM Length L Ch R = 1 ,522     ,189,189,189
BEGIN DESCRIPTION:
Stream0396 1.0
END DESCRIPTION:
XS GIS Cut Line= 3
      1971775.01     13881324.99        1971925.       13881025.
      1971974.99     13880825.05
#Sta/Elev= 30
  4664.6 1527.12  4695.5 1524.71  4705.6 1522.32    4719 1520.64    4789 1516.12
    4833 1514.05  4846.4 1512.88  4863.2 1513.06  4889.6 1511.34  4943.7 1510.35
  4957.3 1509.51  4967.2 1506.74  4985.3 1504.67  4985.6 1504.17  4989.1 1504.17
  4989.3 1504.67  4997.4 1505.79  5006.9 1509.01    5013 1509.57  5059.4 1508.92
  5071.8 1509.74  5084.2 1509.69  5105.8 1508.43  5113.6 1508.72  5121.8 1510.29
  5139.8 1515.56  5161.5 1520.54  5173.8 1521.77  5195.2 1525.48  5206.1 1526.13
#Mann= 3 ,-1 , 0
  4664.6      .1       0  4985.3     .05       0  4989.3      .1       0
Bank Sta=4985.3,4989.3
XS Rating Curve= 0 ,0
Exp/Cntr=0.3,0.1

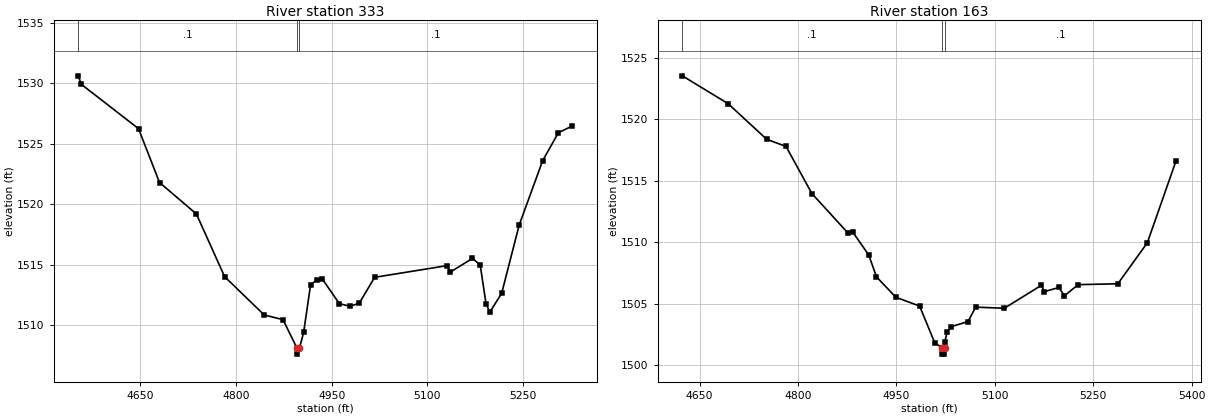
Type RM Length L Ch R = 1 ,333     ,170,170,170
BEGIN DESCRIPTION:
Stream0396 0.1
END DESCRIPTION:
XS GIS Cut Line= 6
      1971843.29     13881462.21      1972060.28       13881148.
        1972095.     13881076.82      1972077.64       13881023.
      1972022.09     13880957.02      1971989.09     13880790.31
#Sta/Elev= 30
  4552.8  1530.6  4557.6  1529.9  4647.3 1526.23  4680.2 1521.78    4738 1519.18
  4782.3 1513.99  4844.3 1510.83  4873.8 1510.44  4895.6 1508.09  4895.8 1507.59
  4899.6 1508.09  4906.2 1509.41    4917 1513.33  4927.1 1513.74  4935.4  1513.8
  4962.1 1511.76  4978.8 1511.55  4993.3  1511.8  5017.4 1513.94  5131.4 1514.91
  5135.9 1514.37  5170.6  1515.5  5182.8 1514.98    5192 1511.75  5198.1 1511.07
  5216.5 1512.62    5244 1518.27  5280.7 1523.58  5305.4  1525.9  5326.6 1526.44
#Mann= 3 ,-1 , 0
  4552.8      .1       0  4895.6     .05       0  4899.6      .1       0
Bank Sta=4895.6,4899.6
XS Rating Curve= 0 ,0
Exp/Cntr=0.3,0.1

Type RM Length L Ch R = 1 ,163     ,0,0,0
BEGIN DESCRIPTION:
Stream0396 0.0
END DESCRIPTION:
XS GIS Cut Line= 3
      1972078.65     13881516.77      1972242.95     13881146.95
      1972120.97     13880821.31
#Sta/Elev= 30
  4623.8 1523.53  4693.7 1521.26  4752.3 1518.37  4781.8 1517.79  4821.2 1513.96
    4876 1510.76  4883.6 1510.82  4907.9 1508.96  4919.7 1507.18  4949.3 1505.52
  4985.4 1504.81  5008.3 1501.84  5019.5  1501.4  5019.7  1500.9  5023.2  1500.9
  5023.5  1501.4  5023.6 1501.88  5027.5  1502.7  5033.6 1503.13  5059.2 1503.55
  5070.8 1504.72  5114.5 1504.63  5171.1  1506.5  5175.4 1505.98  5197.8 1506.32
    5206 1505.64    5227 1506.55  5287.5 1506.62  5332.4 1509.95  5376.2 1516.62
#Mann= 3 ,-1 , 0
  4623.8      .1       0  5019.5     .05       0  5023.5      .1       0
Bank Sta=5019.5,5023.5
XS Rating Curve= 0 ,0
Exp/Cntr=0.3,0.1

Chan Stop Cuts=-1
Use User Specified Reach Order=0
Composite Channel Slope=5