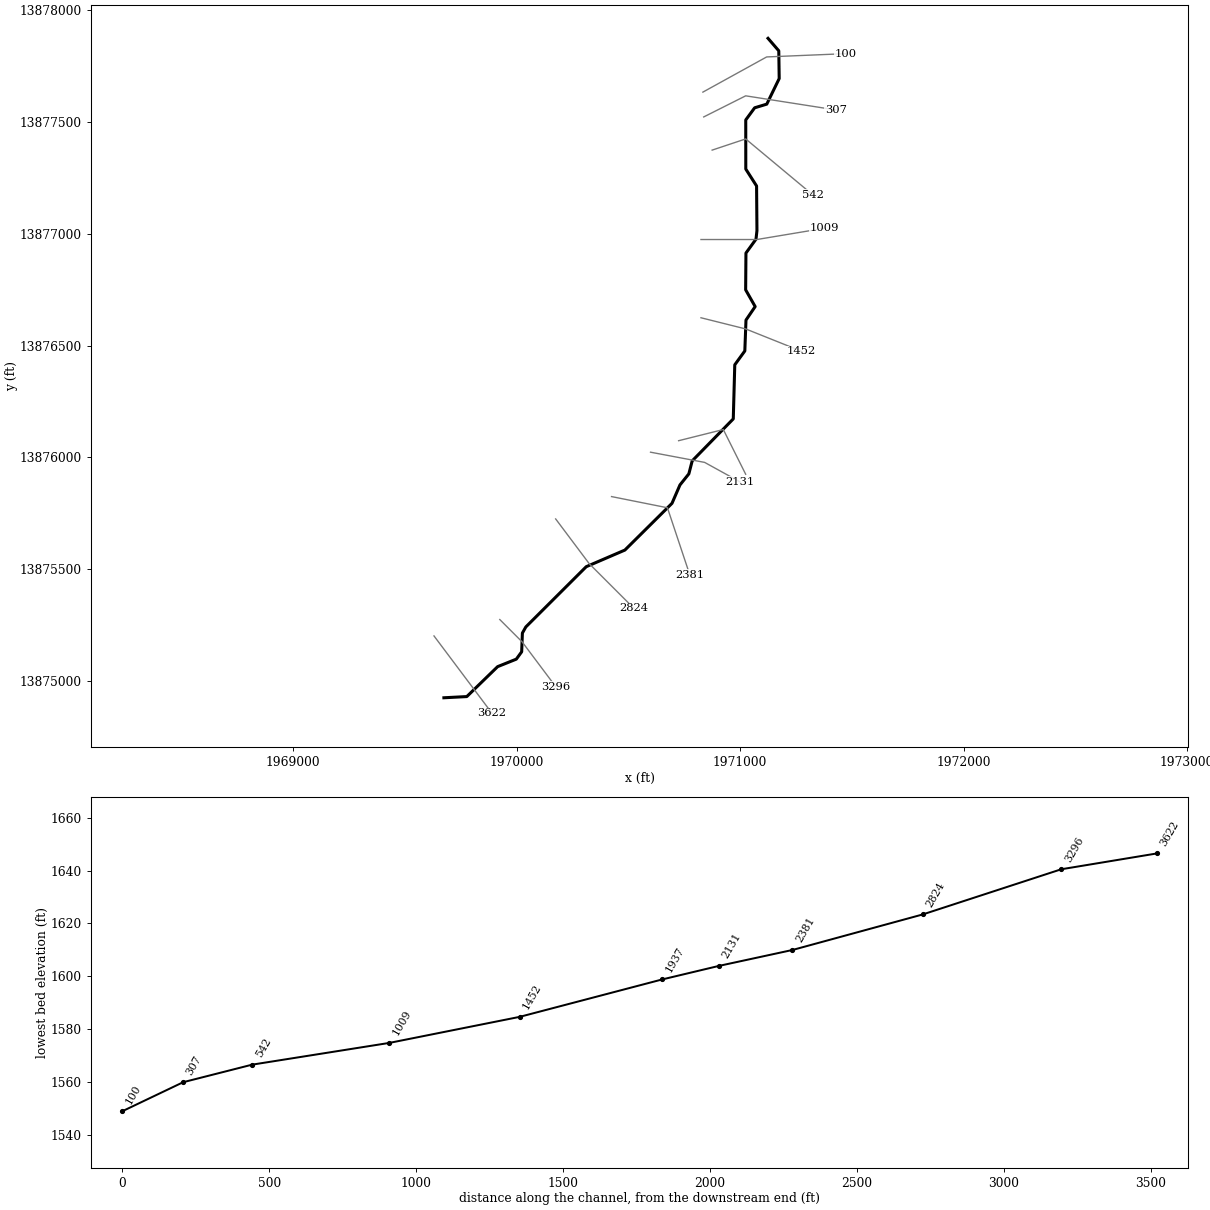
--- Stream0404.prj (project) ---

Proj Title=Stream0404 Base Level Engineering
Current Plan=p01
Default Exp/Contr=0.3,0.1
English Units
Geom File=g01
Flow File=f01
Plan File=p01
BEGIN DESCRIPTION:
Stream0404
END DESCRIPTION:

--- Stream0404.p01 (plan) ---

Plan Title=Multiple Run
Short Identifier=Multiple
Geom File=g01
Flow File=f01
Subcritical Flow
K Sum by GR= 0
Std Step Tol= 0.01
Critical Tol= 0.01
Num of Std Step Trials= 20
Max Error Tol= 0.3
Flow Tol Ratio= 0.001
Split Flow NTrial= 30
Split Flow Tol= 0.02
Split Flow Ratio= 0.02
Log Output Level= 0
Friction Slope Method= 1
Unsteady Friction Slope Method= 2
Unsteady Bridges Friction Slope Method= 1
Parabolic Critical Depth
Global Vel Dist=  1 , 1 , 1
Global Log Level= 0
CheckData=True
Encroach Param= -1, 0, 0, 0
BEGIN DESCRIPTION:
Multiple Run
END DESCRIPTION:

--- Stream0404.f01 (steady flow) ---

Flow Title=Multiple
Number of Profiles=7
Profile Names=10-year,25-year,50-year,1pct_min,100-year,1pct_plu,500-year
River Rch & RM= Stream0404,Reach-1,3622
     178     270     349     221     441     881     692
River Rch & RM= Stream0404,Reach-1,3296
     503     823    1120     742    1480    2953    2550
Boundary for River Rch & Prof#=Stream0404,Reach-1,1
Up Type=0
Dn Type=3
Dn Slope=0.005
Boundary for River Rch & Prof#=Stream0404,Reach-1,2
Up Type=0
Dn Type=3
Dn Slope=0.005
Boundary for River Rch & Prof#=Stream0404,Reach-1,3
Up Type=0
Dn Type=3
Dn Slope=0.005
Boundary for River Rch & Prof#=Stream0404,Reach-1,4
Up Type=0
Dn Type=3
Dn Slope=0.005
Boundary for River Rch & Prof#=Stream0404,Reach-1,5
Up Type=0
Dn Type=3
Dn Slope=0.005
Boundary for River Rch & Prof#=Stream0404,Reach-1,6
Up Type=0
Dn Type=3
Dn Slope=0.005
Boundary for River Rch & Prof#=Stream0404,Reach-1,7
Up Type=0
Dn Type=3
Dn Slope=0.005

--- Stream0404.g01 (geometry) ---

Geom Title=Existing Conditions

River Reach=Stream0404,Reach-1
Reach XY= 30
      1969675.00     13874925.00      1969777.50     13874930.35
      1969915.34     13875064.21      1969998.95     13875097.81
      1970022.92     13875130.71      1970026.17     13875214.51
      1970041.46     13875241.75      1970311.79     13875511.38
      1970484.68     13875585.76      1970695.39     13875794.84
      1970731.10     13875877.19      1970770.81     13875926.74
      1970785.76     13875984.68      1970969.54     13876172.55
      1970976.22     13876414.50      1971021.21     13876476.57
      1971026.40     13876614.56      1971067.44     13876675.00
      1971024.89     13876749.88      1971026.22     13876914.49
      1971071.22     13876976.57      1971075.45     13877014.81
      1971073.78     13877214.50      1971025.52     13877290.22
      1971025.34     13877509.96      1971065.21     13877564.27
      1971119.38     13877580.62      1971174.97     13877695.02
      1971173.12     13877819.21      1971125.00     13877875.00

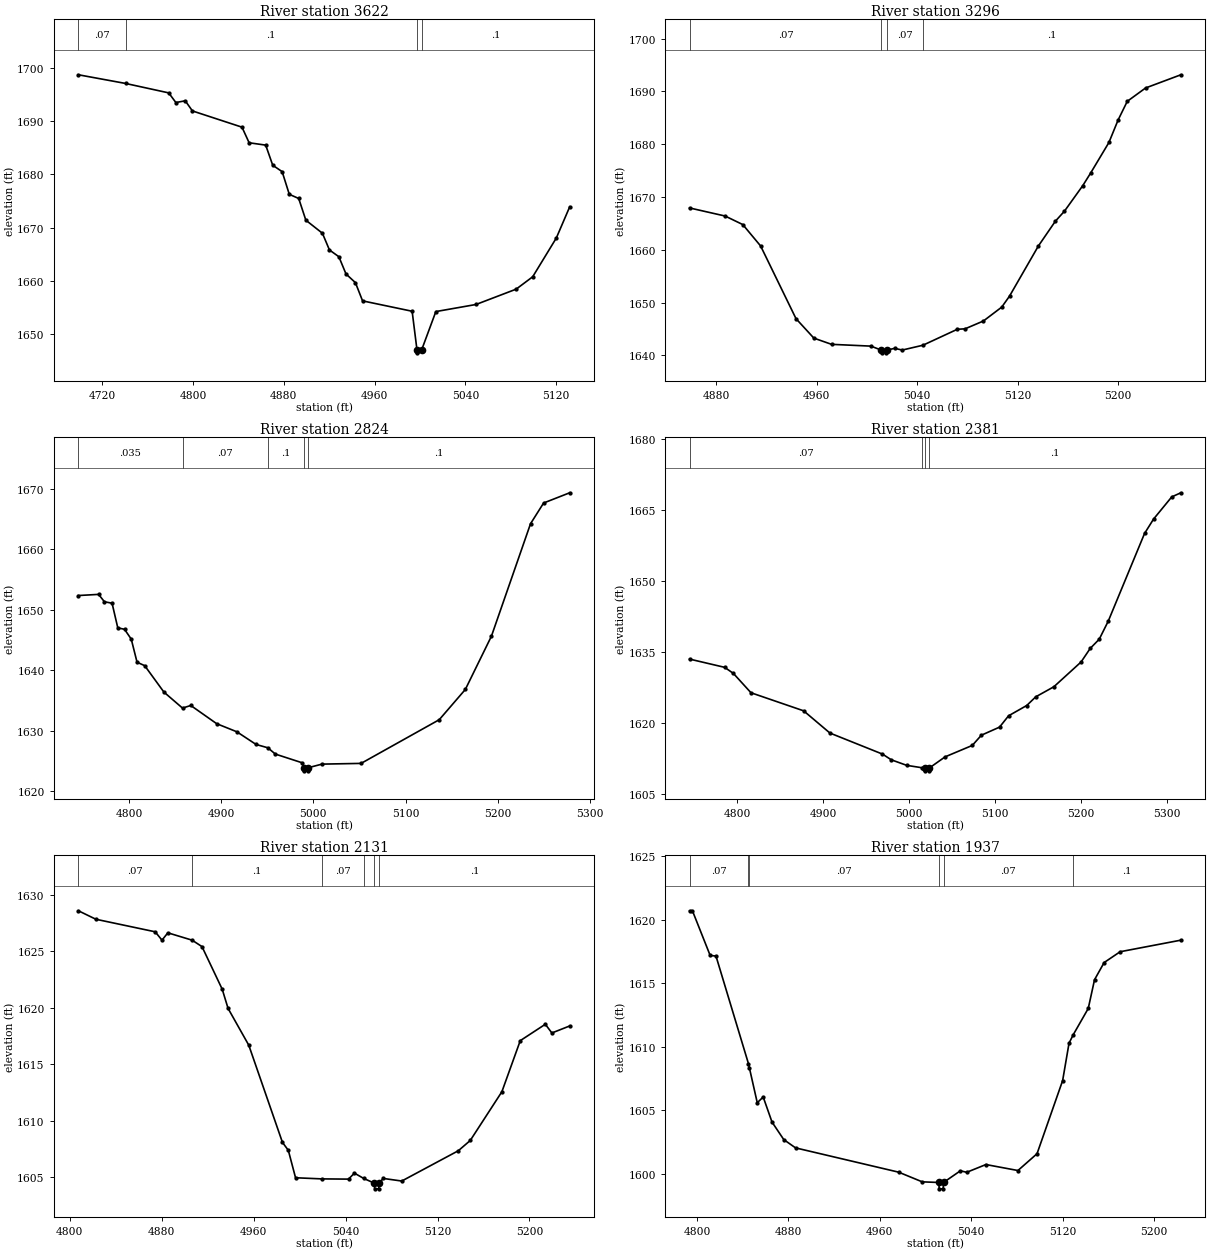
Type RM Length L Ch R = 1,3622,326,326,326
BEGIN DESCRIPTION:
Stream0404 8.0
END DESCRIPTION:
XS GIS Cut Line= 2
      1969630.68     13875201.67      1969890.54     13874855.19
#Sta/Elev= 30
  4698.9 1698.70  4740.5 1697.07  4778.5 1695.30  4784.8 1693.49  4793.1 1693.81
  4799.4 1691.91  4843.1 1688.86  4849.4 1685.93  4864.0 1685.49  4870.2 1681.71
  4878.5 1680.51  4884.8 1676.25  4893.1 1675.47  4899.4 1671.39  4914.0 1668.94
  4920.2 1665.80  4928.5 1664.53  4934.8 1661.29  4943.1 1659.66  4949.4 1656.24
  4993.1 1654.29  4997.4 1646.98  4997.6 1646.48  5001.4 1646.98  5014.0 1654.23
  5049.4 1655.56  5084.8 1658.44  5099.4 1660.77  5120.2 1668.04  5132.0 1673.90
#Mann=4,-1,0
  4698.9    0.07       0  4740.5     0.1       0  4997.4    0.05       0
  5001.4     0.1       0
Bank Sta=4997.4,5001.4
Exp/Cntr=0.3,0.1

Type RM Length L Ch R = 1,3296,472,472,472
BEGIN DESCRIPTION:
Stream0404 7.0
END DESCRIPTION:
XS GIS Cut Line= 3
      1969925.01     13875274.99      1970025.00     13875175.00
      1970175.00     13874975.00
#Sta/Elev= 30
  4858.6 1667.93  4886.9 1666.40  4901.0 1664.78  4915.2 1660.73  4943.4 1646.96
  4957.6 1643.28  4971.7 1642.10  5003.1 1641.76  5011.5 1640.99  5011.8 1640.49
  5015.3 1640.49  5015.5 1640.99  5021.9 1641.34  5028.1 1641.02  5044.5 1641.93
  5071.9 1644.95  5078.1 1645.04  5092.7 1646.52  5107.3 1649.15  5113.5 1651.23
  5136.5 1660.73  5150.0 1665.41  5157.3 1667.33  5171.9 1672.17  5178.1 1674.53
  5192.7 1680.33  5200.0 1684.58  5207.3 1688.12  5221.9 1690.65  5250.0 1693.15
#Mann=4,-1,0
  4858.6    0.07       0  5011.5    0.05       0  5015.5    0.07       0
  5044.5     0.1       0
Bank Sta=5011.5,5015.5
Exp/Cntr=0.3,0.1

Type RM Length L Ch R = 1,2824,443,443,443
BEGIN DESCRIPTION:
Stream0404 6.0
END DESCRIPTION:
XS GIS Cut Line= 3
      1970174.98     13875725.02      1970325.00     13875525.00
      1970525.02     13875324.98
#Sta/Elev= 30
  4745.2 1652.37  4767.1 1652.56  4773.4 1651.34  4781.7 1651.10  4787.9 1647.03
  4795.2 1646.79  4802.5 1645.17  4808.8 1641.35  4817.1 1640.78  4837.9 1636.42
  4858.1 1633.77  4867.1 1634.20  4895.2 1631.19  4917.1 1629.85  4937.9 1627.76
  4950.7 1627.21  4958.8 1626.17  4987.9 1624.73  4990.1 1623.90  4990.4 1623.40
  4993.9 1623.40  4994.1 1623.90  5009.4 1624.51  5051.8 1624.63  5136.6 1631.85
  5164.9 1636.85  5193.2 1645.65  5235.6 1664.23  5249.8 1667.66  5278.1 1669.35
#Mann=5,-1,0
  4745.2   0.035       0  4858.1    0.07       0  4950.7     0.1       0
  4990.1    0.05       0  4994.1     0.1       0
Bank Sta=4990.1,4994.1
Exp/Cntr=0.3,0.1

Type RM Length L Ch R = 1,2381,250,250,250
BEGIN DESCRIPTION:
Stream0404 5.0
END DESCRIPTION:
XS GIS Cut Line= 3
      1970425.01     13875825.00      1970675.00     13875775.00
      1970775.01     13875474.97
#Sta/Elev= 30
  4744.8 1633.55  4785.6 1631.81  4795.8 1630.52  4816.2 1626.45  4877.4 1622.64
  4908.0 1617.95  4969.1 1613.51  4979.3 1612.31  4997.2 1611.14  5015.1 1610.63
  5018.8 1610.48  5019.1 1609.98  5022.6 1609.98  5022.8 1610.48  5041.9 1612.93
  5073.5 1615.34  5084.1 1617.50  5105.2 1619.20  5115.7 1621.59  5136.8 1623.76
  5147.3 1625.59  5168.4 1627.72  5200.0 1632.94  5210.6 1635.80  5221.1 1637.74
  5231.6 1641.56  5273.8 1660.05  5284.3 1663.09  5305.4 1667.76  5316.0 1668.63
#Mann=4,-1,0
  4744.8    0.07       0  5015.1     0.1       0  5018.8    0.05       0
  5022.8     0.1       0
Bank Sta=5018.8,5022.8
Exp/Cntr=0.3,0.1

Type RM Length L Ch R = 1,2131,194,194,194
BEGIN DESCRIPTION:
Mapping XS 65ce2cde
END DESCRIPTION:
XS GIS Cut Line= 3
      1970599.35     13876023.62      1970841.44     13875977.96
      1970999.99     13875890.57
#Sta/Elev= 30
  4807.6 1628.57  4822.8 1627.82  4874.4 1626.71  4880.3 1625.97  4885.4 1626.62
  4906.5 1625.97  4915.1 1625.40  4932.7 1621.63  4937.8 1619.93  4955.8 1616.68
  4985.1 1608.08  4990.2 1607.38  4996.5 1604.95  5019.4 1604.85  5042.6 1604.83
  5047.7 1605.36  5055.8 1604.89  5065.1 1604.47  5065.3 1603.97  5068.8 1603.97
  5069.1 1604.47  5072.8 1604.89  5088.9 1604.66  5138.1 1607.34  5148.5 1608.25
  5176.0 1612.56  5192.0 1617.08  5213.8 1618.53  5219.5 1617.76  5235.0 1618.38
#Mann=6,-1,0
  4807.6    0.07       0  4906.5     0.1       0  5019.4    0.07       0
  5055.8     0.1       0  5065.1    0.05       0  5069.1     0.1       0
Bank Sta=5065.1,5069.1
Exp/Cntr=0.3,0.1

Type RM Length L Ch R = 1,1937,485,485,485
BEGIN DESCRIPTION:
Stream0404 4.0
END DESCRIPTION:
XS GIS Cut Line= 3
      1970725.05     13876075.01      1970925.00     13876125.00
      1971024.99     13875925.01
#Sta/Elev= 30
  4793.6 1620.69  4796.1 1620.69  4811.6 1617.18  4816.7 1617.13  4845.1 1608.67
  4845.9 1608.35  4852.8 1605.60  4858.0 1606.05  4865.7 1604.08  4876.0 1602.70
  4886.3 1602.05  4976.5 1600.14  4997.1 1599.38  5011.7 1599.33  5011.9 1598.83
  5015.4 1598.83  5015.7 1599.33  5030.5 1600.25  5036.0 1600.13  5052.8 1600.74
  5080.8 1600.27  5097.5 1601.59  5119.9 1607.34  5125.5 1610.28  5129.2 1610.95
  5142.3 1613.01  5147.8 1615.27  5156.2 1616.62  5170.2 1617.47  5223.3 1618.38
#Mann=6,-1,0
  4793.6    0.07       0  4845.1     0.1       0  4845.9    0.07       0
  5011.7    0.05       0  5015.7    0.07       0  5129.2     0.1       0
Bank Sta=5011.7,5015.7
Exp/Cntr=0.3,0.1

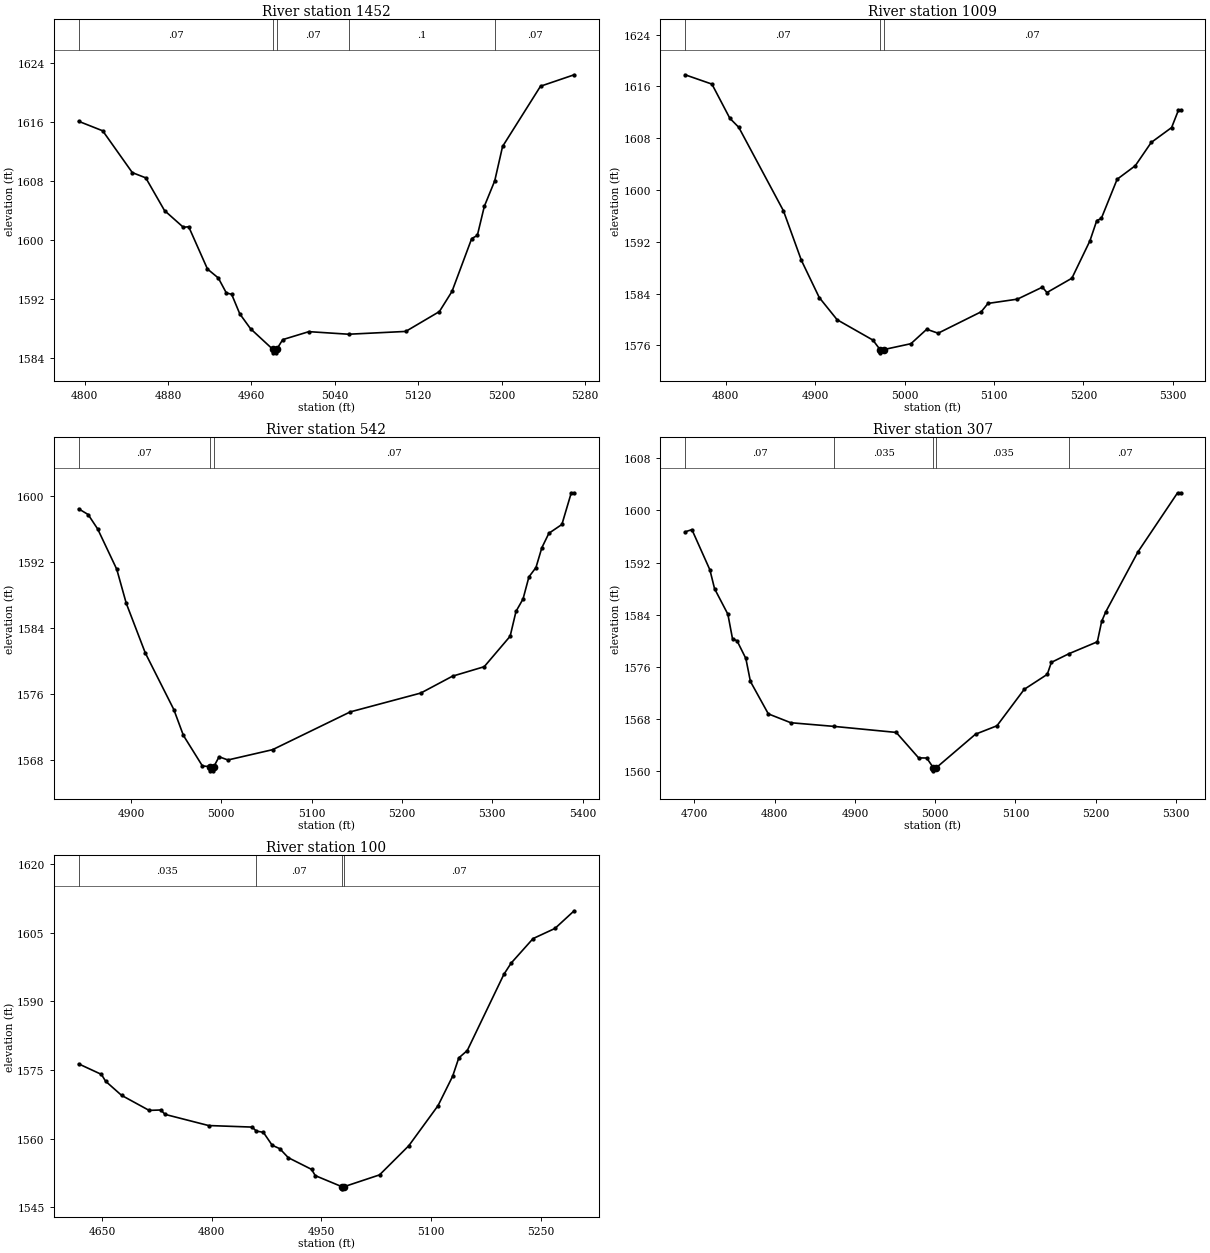
Type RM Length L Ch R = 1,1452,443,443,443
BEGIN DESCRIPTION:
Stream0404 3.0
END DESCRIPTION:
XS GIS Cut Line= 3
      1970825.04     13876624.99      1971025.00     13876575.00
      1971275.03     13876474.99
#Sta/Elev= 30
  4794.2 1616.05  4817.3 1614.76  4845.7 1609.10  4858.6 1608.39  4876.6 1603.96
  4894.7 1601.69  4899.8 1601.77  4917.8 1596.04  4928.2 1594.83  4935.9 1592.80
  4941.0 1592.62  4948.8 1589.97  4959.1 1587.96  4980.3 1585.19  4980.5 1584.69
  4984.0 1584.69  4984.3 1585.19  4990.0 1586.48  5015.1 1587.56  5053.2 1587.21
  5108.0 1587.59  5140.3 1590.28  5152.4 1593.01  5171.3 1600.17  5176.7 1600.59
  5183.4 1604.53  5193.4 1607.99  5200.9 1612.64  5237.3 1620.80  5269.6 1622.35
#Mann=5,-1,0
  4794.2    0.07       0  4980.3    0.05       0  4984.3    0.07       0
  5053.2     0.1       0  5193.4    0.07       0
Bank Sta=4980.3,4984.3
Exp/Cntr=0.3,0.1

Type RM Length L Ch R = 1,1009,467,467,467
BEGIN DESCRIPTION:
Stream0404 2.0
END DESCRIPTION:
XS GIS Cut Line= 3
      1970825.03     13876975.00      1971075.00     13876975.00
      1971374.99     13877025.00
#Sta/Elev= 30
  4754.6 1617.79  4784.6 1616.35  4804.6 1611.08  4814.6 1609.68  4864.6 1596.78
  4884.6 1589.15  4904.6 1583.40  4924.6 1579.97  4964.6 1576.83  4972.6 1575.36
  4972.8 1574.86  4976.6 1575.36  5007.1 1576.27  5024.8 1578.50  5037.5 1577.89
  5085.7 1581.20  5093.3 1582.49  5126.2 1583.15  5154.1 1585.00  5159.2 1584.17
  5187.1 1586.38  5207.3 1592.16  5214.9 1595.28  5220.0 1595.61  5237.7 1601.66
  5258.0 1603.75  5275.8 1607.34  5298.6 1609.64  5306.2 1612.31  5308.7 1612.31
#Mann=3,-1,0
  4754.6    0.07       0  4972.6    0.05       0  4976.6    0.07       0
Bank Sta=4972.6,4976.6
Exp/Cntr=0.3,0.1

Type RM Length L Ch R = 1,542,235,235,235
BEGIN DESCRIPTION:
Stream0404 1.0
END DESCRIPTION:
XS GIS Cut Line= 3
      1970875.00     13877375.00      1971025.00     13877425.00
      1971324.98     13877175.02
#Sta/Elev= 30
  4842.0 1598.47  4852.5 1597.78  4863.1 1596.02  4884.2 1591.13  4894.7 1587.00
  4915.8 1580.96  4947.4 1574.08  4958.0 1570.94  4979.0 1567.24  4987.6 1567.14
  4987.8 1566.64  4991.3 1566.64  4991.6 1567.14  4997.5 1568.35  5007.3 1567.96
  5056.7 1569.21  5142.7 1573.80  5220.8 1576.09  5255.9 1578.14  5291.0 1579.29
  5319.7 1582.99  5326.2 1586.01  5334.0 1587.52  5340.5 1590.20  5348.3 1591.34
  5354.8 1593.74  5362.6 1595.50  5377.0 1596.57  5387.4 1600.42  5390.6 1600.42
#Mann=3,-1,0
  4842.0    0.07       0  4987.6    0.05       0  4991.6    0.07       0
Bank Sta=4987.6,4991.6
Exp/Cntr=0.3,0.1

Type RM Length L Ch R = 1,307,207,207,207
BEGIN DESCRIPTION:
Mapping XS 5758bf74
END DESCRIPTION:
XS GIS Cut Line= 3
      1970837.37     13877523.40      1971025.06     13877617.80
      1971427.58     13877554.87
#Sta/Elev= 30
  4688.4 1596.71  4696.9 1597.05  4719.3 1590.87  4725.1 1587.98  4741.7 1584.06
  4747.5 1580.27  4753.1 1579.98  4764.1 1577.26  4769.8 1573.73  4792.1 1568.75
  4820.1 1567.39  4873.7 1566.83  4951.5 1565.90  4979.4 1561.99  4989.5 1561.97
  4997.6 1560.50  4997.9 1560.00  5001.6 1560.50  5050.3 1565.63  5077.0 1566.92
  5111.0 1572.52  5139.7 1574.82  5144.8 1576.66  5166.9 1578.00  5202.1 1579.82
  5207.5 1582.96  5212.6 1584.42  5252.7 1593.63  5302.1 1602.71  5305.9 1602.71
#Mann=5,-1,0
  4688.4    0.07       0  4873.7   0.035       0  4997.6   0.035       0
  5001.6   0.035       0  5166.9    0.07       0
Bank Sta=4997.6,5001.6
Exp/Cntr=0.3,0.1

Type RM Length L Ch R = 1,100,0,0,0
BEGIN DESCRIPTION:
Stream0404 0.0
END DESCRIPTION:
XS GIS Cut Line= 3
      1970833.58     13877634.41      1971118.87     13877791.78
      1971471.25     13877806.41
#Sta/Elev= 30
  4617.6 1576.35  4648.8 1574.05  4654.5 1572.56  4676.3 1569.48  4714.1 1566.18
  4730.2 1566.27  4735.9 1565.31  4795.5 1562.87  4855.1 1562.53  4860.9 1561.66
  4870.5 1561.39  4882.6 1558.56  4893.0 1557.81  4904.7 1555.84  4936.5 1553.29
  4941.6 1551.92  4977.6 1549.53  4977.8 1549.03  4981.6 1549.53  5029.6 1552.08
  5069.7 1558.46  5109.7 1567.22  5129.7 1573.65  5138.1 1577.65  5149.7 1579.26
  5199.8 1595.91  5209.8 1598.38  5239.8 1603.74  5269.8 1605.96  5296.1 1609.82
#Mann=4,-1,0
  4617.6   0.035       0  4860.9    0.07       0  4977.6    0.05       0
  4981.6    0.07       0
Bank Sta=4977.6,4981.6
Exp/Cntr=0.3,0.1

Chan Stop Cuts=-1