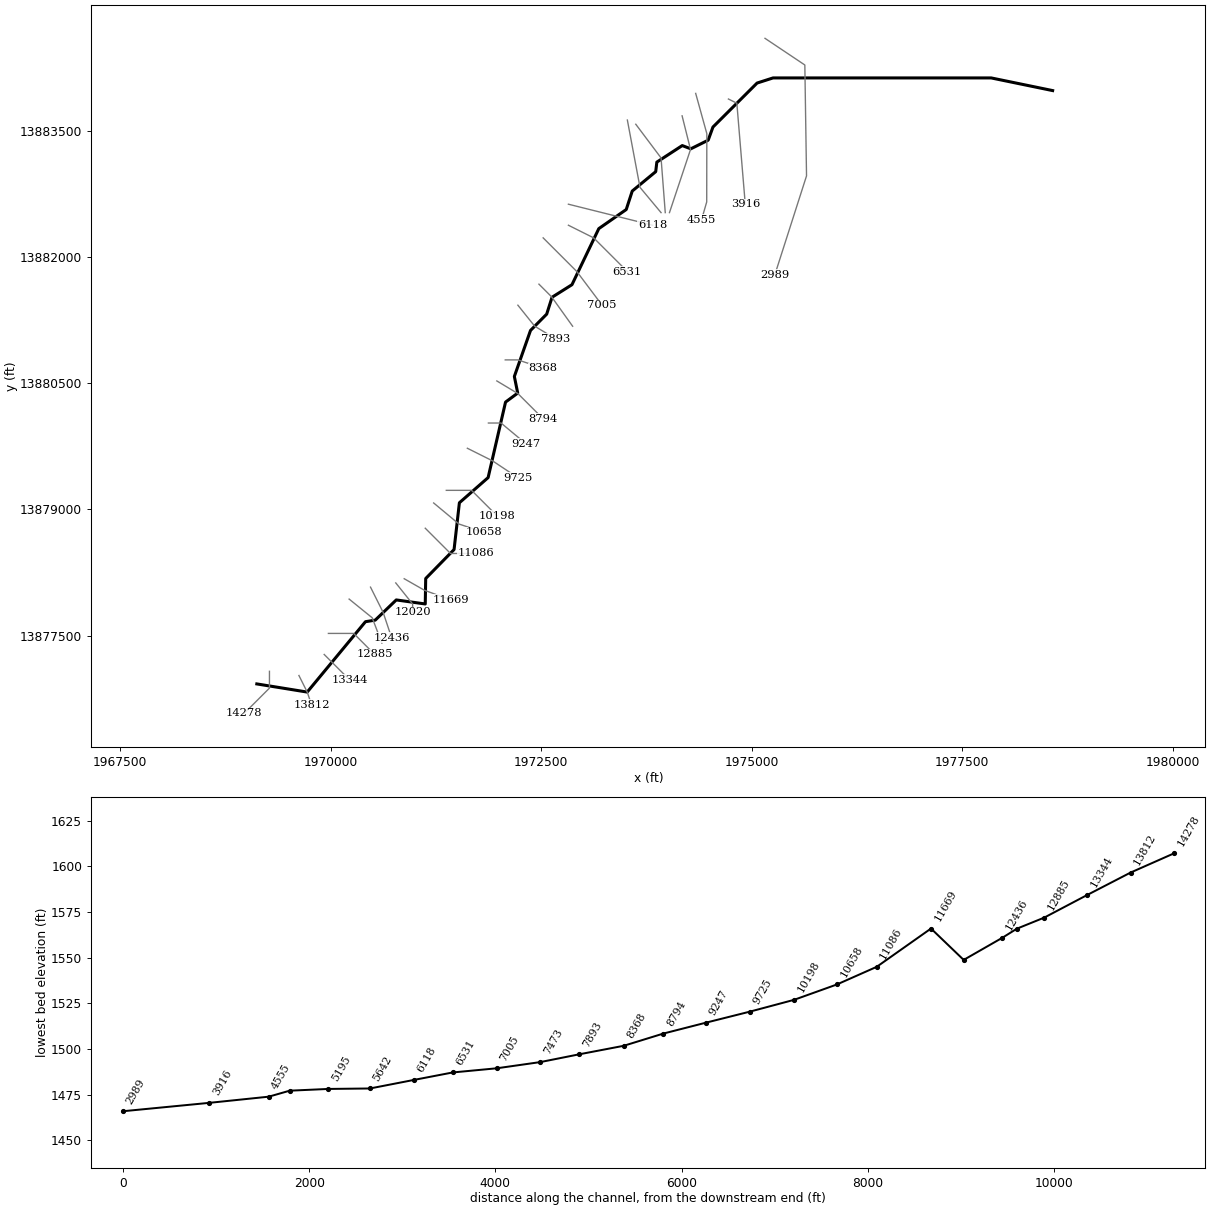
--- Stream0412.prj (project) ---

Proj Title=Stream0412 Base Level Engineering
Current Plan=p01
Default Exp/Contr=0.3,0.1
English Units
Geom File=g01
Flow File=f01
Plan File=p01
BEGIN DESCRIPTION:
Stream0412
END DESCRIPTION:

--- Stream0412.p01 (plan) ---

Plan Title=Multiple Run
Short Identifier=Multiple
Geom File=g01
Flow File=f01
Subcritical Flow
K Sum by GR= 0
Std Step Tol= 0.01
Critical Tol= 0.01
Num of Std Step Trials= 20
Max Error Tol= 0.3
Flow Tol Ratio= 0.001
Split Flow NTrial= 30
Split Flow Tol= 0.02
Split Flow Ratio= 0.02
Log Output Level= 0
Friction Slope Method= 1
Unsteady Friction Slope Method= 2
Unsteady Bridges Friction Slope Method= 1
Parabolic Critical Depth
Global Vel Dist=  1 , 1 , 1
Global Log Level= 0
CheckData=True
Encroach Param= -1, 0, 0, 0
BEGIN DESCRIPTION:
Multiple Run
END DESCRIPTION:

--- Stream0412.f01 (steady flow) ---

Flow Title=Multiple
Number of Profiles=7
Profile Names=10-year,25-year,50-year,1pct_min,100-year,1pct_plu,500-year
River Rch & RM= Stream0412,Reach-1,14278
     304     481     640     415     828    1652    1367
River Rch & RM= Stream0412,Reach-1,13812
     501     820    1116     738    1473    2939    2535
River Rch & RM= Stream0412,Reach-1,11669
    1047    1793    2511    1706    3405    6793    6192
River Rch & RM= Stream0412,Reach-1,7893
    1560    2728    3874    2664    5315   10605    9908
River Rch & RM= Stream0412,Reach-1,5195
    2107    3726    5329    3685    7353   14671   13869
Boundary for River Rch & Prof#=Stream0412,Reach-1,1
Up Type=0
Dn Type=3
Dn Slope=0.005
Boundary for River Rch & Prof#=Stream0412,Reach-1,2
Up Type=0
Dn Type=3
Dn Slope=0.005
Boundary for River Rch & Prof#=Stream0412,Reach-1,3
Up Type=0
Dn Type=3
Dn Slope=0.005
Boundary for River Rch & Prof#=Stream0412,Reach-1,4
Up Type=0
Dn Type=3
Dn Slope=0.005
Boundary for River Rch & Prof#=Stream0412,Reach-1,5
Up Type=0
Dn Type=3
Dn Slope=0.005
Boundary for River Rch & Prof#=Stream0412,Reach-1,6
Up Type=0
Dn Type=3
Dn Slope=0.005
Boundary for River Rch & Prof#=Stream0412,Reach-1,7
Up Type=0
Dn Type=3
Dn Slope=0.005

--- Stream0412.g01 (geometry) ---

Geom Title=Existing Conditions

River Reach=Stream0412,Reach-1
Reach XY= 30
      1969125.00     13876925.00      1969723.37     13876828.13
      1970415.21     13877664.48      1970531.17     13877682.86
      1970780.86     13877922.95      1971125.00     13877875.00
      1971130.45     13878177.47      1971467.16     13878521.62
      1971530.46     13879077.45      1971871.46     13879376.46
      1972078.45     13880273.75      1972223.03     13880380.68
      1972183.08     13880578.30      1972375.00     13881125.00
      1972567.14     13881318.83      1972630.59     13881519.39
      1972867.25     13881668.55      1973185.77     13882334.70
      1973511.61     13882561.67      1973583.02     13882781.34
      1973861.65     13883011.67      1973875.00     13883125.00
      1974176.73     13883321.63      1974278.31     13883283.07
      1974484.73     13883385.76      1974541.38     13883541.70
      1975065.21     13884064.48      1975254.85     13884125.36
      1977845.15     13884125.36      1978575.00     13883975.00

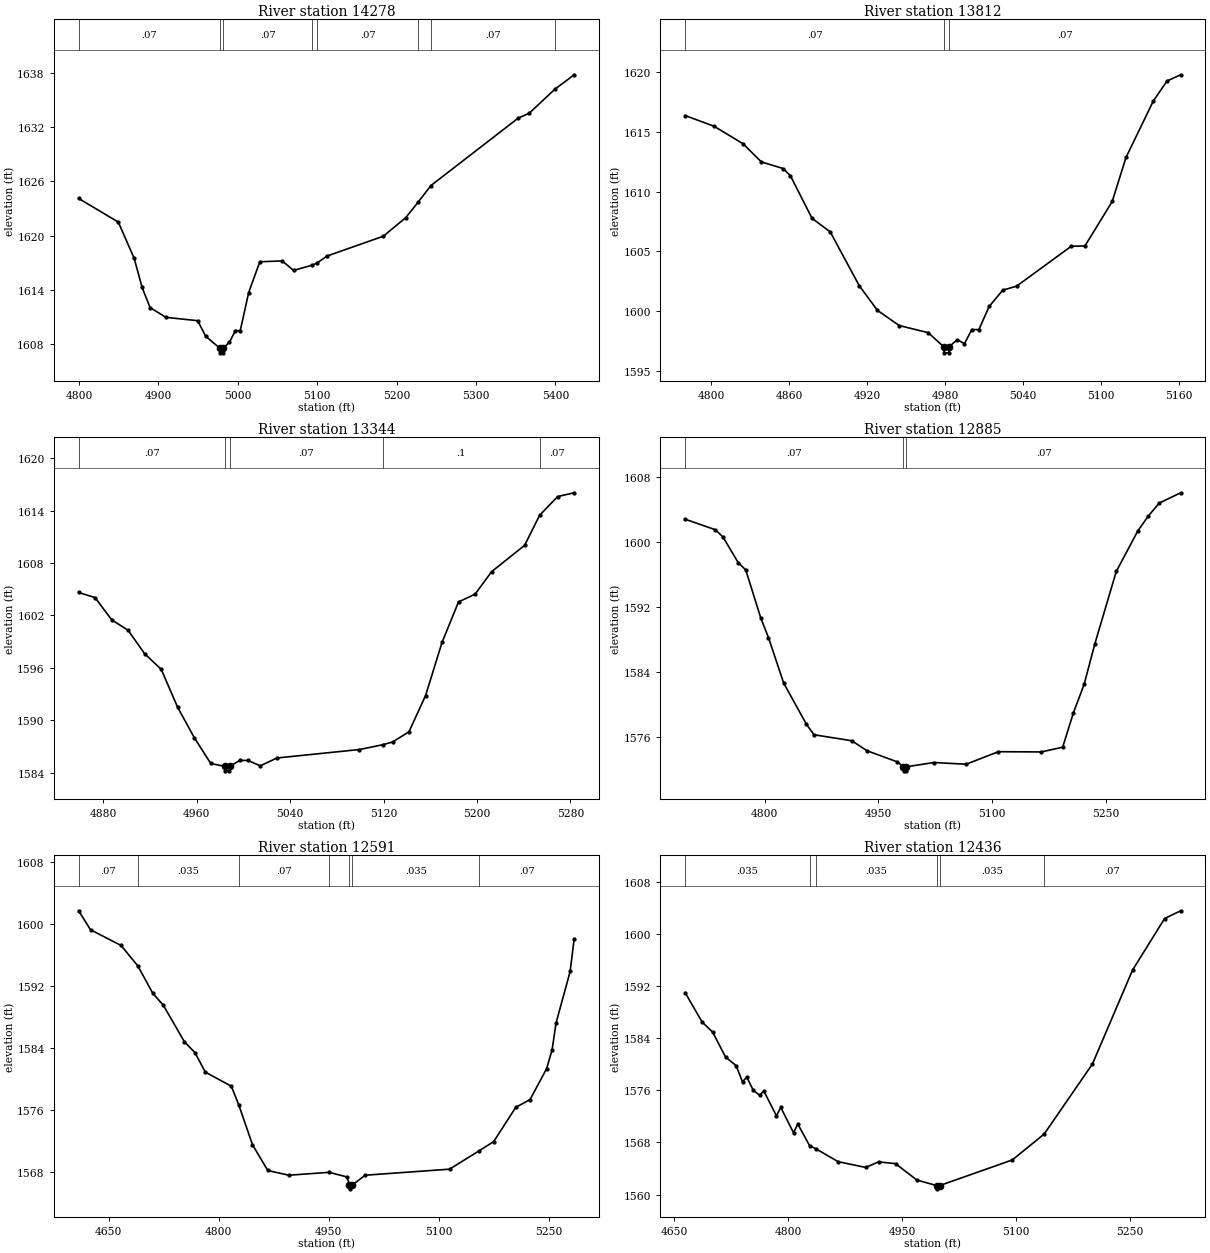
Type RM Length L Ch R = 1,14278,466,466,466
BEGIN DESCRIPTION:
Stream0412 23.0
END DESCRIPTION:
XS GIS Cut Line= 3
      1969275.00     13877075.03      1969275.00     13876875.00
      1968974.99     13876574.99
#Sta/Elev= 30
  4799.4 1624.10  4849.4 1621.49  4869.4 1617.48  4879.4 1614.27  4889.4 1612.05
  4909.4 1610.97  4949.4 1610.60  4959.4 1608.89  4977.4 1607.55  4977.7 1607.05
  4981.2 1607.05  4981.4 1607.55  4989.4 1608.22  4996.9 1609.50  5003.0 1609.50
  5013.6 1613.70  5027.7 1617.11  5056.0 1617.20  5070.1 1616.15  5093.9 1616.74
  5099.7 1616.97  5112.6 1617.75  5183.3 1619.93  5211.6 1621.99  5226.9 1623.67
  5243.3 1625.53  5353.0 1632.96  5367.1 1633.52  5399.7 1636.19  5423.7 1637.76
#Mann=8,-1,0
  4799.4    0.07       0  4977.4    0.05       0  4981.4    0.07       0
  5093.9   0.035       0  5099.7    0.07       0  5226.9   0.035       0
  5243.3    0.07       0  5399.7   0.035       0
Bank Sta=4977.4,4981.4
Exp/Cntr=0.3,0.1

Type RM Length L Ch R = 1,13812,468,468,468
BEGIN DESCRIPTION:
Stream0412 22.0
END DESCRIPTION:
XS GIS Cut Line= 3
      1969624.99     13877025.02      1969725.00     13876825.00
      1969774.99     13876675.04
#Sta/Elev= 30
  4779.9 1616.34  4802.3 1615.44  4824.6 1613.98  4838.6 1612.47  4855.4 1611.92
  4861.0 1611.32  4877.7 1607.76  4891.7 1606.63  4914.1 1602.13  4928.1 1600.08
  4944.8 1598.82  4967.2 1598.22  4979.2 1597.04  4979.4 1596.54  4982.9 1596.54
  4983.2 1597.04  4989.6 1597.64  4995.1 1597.30  5000.7 1598.48  5006.2 1598.48
  5014.1 1600.41  5024.6 1601.77  5035.2 1602.10  5077.3 1605.43  5087.9 1605.46
  5108.9 1609.17  5119.5 1612.84  5140.6 1617.56  5151.1 1619.22  5161.6 1619.74
#Mann=3,-1,0
  4779.9    0.07       0  4979.2    0.05       0  4983.2    0.07       0
Bank Sta=4979.2,4983.2
Exp/Cntr=0.3,0.1

Type RM Length L Ch R = 1,13344,459,459,459
BEGIN DESCRIPTION:
Stream0412 21.0
END DESCRIPTION:
XS GIS Cut Line= 3
      1969925.01     13877274.99      1970025.00     13877175.00
      1970224.97     13876975.03
#Sta/Elev= 30
  4859.0 1604.62  4873.1 1604.03  4887.3 1601.49  4901.4 1600.29  4915.5 1597.61
  4929.7 1595.83  4943.8 1591.47  4958.0 1588.01  4972.1 1585.05  4984.3 1584.71
  4984.5 1584.21  4988.0 1584.21  4988.3 1584.71  4996.9 1585.40  5003.9 1585.40
  5014.5 1584.78  5028.7 1585.68  5099.4 1586.65  5119.5 1587.20  5127.7 1587.51
  5141.8 1588.68  5156.0 1592.83  5170.1 1598.91  5184.2 1603.54  5198.4 1604.43
  5212.5 1607.00  5240.8 1610.02  5253.6 1613.45  5269.1 1615.60  5283.2 1616.03
#Mann=5,-1,0
  4859.0    0.07       0  4984.3    0.05       0  4988.3    0.07       0
  5119.5     0.1       0  5253.6    0.07       0
Bank Sta=4984.3,4988.3
Exp/Cntr=0.3,0.1

Type RM Length L Ch R = 1,12885,294,294,294
BEGIN DESCRIPTION:
Stream0412 20.0
END DESCRIPTION:
XS GIS Cut Line= 3
      1969974.97     13877525.00      1970275.00     13877525.00
      1970525.01     13877274.99
#Sta/Elev= 30
  4695.2 1602.78  4735.2 1601.48  4745.2 1600.59  4765.2 1597.45  4775.2 1596.55
  4795.2 1590.60  4805.2 1588.24  4825.2 1582.67  4855.2 1577.61  4865.2 1576.32
  4915.2 1575.58  4935.2 1574.35  4975.2 1572.99  4983.2 1572.39  4983.5 1571.89
  4987.0 1571.89  4987.2 1572.39  5023.5 1572.91  5065.9 1572.70  5108.4 1574.24
  5164.9 1574.21  5193.2 1574.79  5207.4 1579.02  5221.5 1582.50  5235.6 1587.47
  5263.9 1596.36  5292.2 1601.32  5306.4 1603.19  5320.5 1604.75  5348.8 1606.02
#Mann=3,-1,0
  4695.2    0.07       0  4983.2    0.05       0  4987.2    0.07       0
Bank Sta=4983.2,4987.2
Exp/Cntr=0.3,0.1

Type RM Length L Ch R = 1,12591,155,155,155
BEGIN DESCRIPTION:
Mapping XS 2e691a33
END DESCRIPTION:
XS GIS Cut Line= 3
      1970221.04     13877933.14      1970495.15     13877710.81
      1970609.94     13877409.90
#Sta/Elev= 30
  4609.2 1601.73  4625.4 1599.28  4667.0 1597.25  4689.9 1594.60  4710.2 1591.08
  4724.5 1589.54  4753.3 1584.81  4767.7 1583.41  4781.7 1580.90  4817.2 1579.07
  4827.4 1576.64  4846.0 1571.53  4866.8 1568.19  4895.5 1567.58  4950.3 1567.95
  4974.7 1567.36  4978.1 1566.32  4978.3 1565.82  4982.1 1566.32  4999.5 1567.58
  5114.4 1568.36  5154.9 1570.74  5174.6 1571.93  5204.7 1576.35  5224.1 1577.35
  5246.6 1581.33  5254.1 1583.76  5259.5 1587.23  5278.7 1593.89  5284.2 1598.11
#Mann=7,-1,0
  4609.2    0.07       0  4689.9   0.035       0  4827.4    0.07       0
  4950.3   0.035       0  4978.1   0.035       0  4982.1   0.035       0
  5154.9    0.07       0
Bank Sta=4978.1,4982.1
Exp/Cntr=0.3,0.1

Type RM Length L Ch R = 1,12436,416,416,416
BEGIN DESCRIPTION:
Stream0412 19.0
END DESCRIPTION:
XS GIS Cut Line= 3
      1970474.98     13878075.04      1970625.00     13877775.00
      1970725.00     13877474.99
#Sta/Elev= 30
  4664.5 1590.99  4686.9 1586.46  4700.9 1584.90  4717.7 1581.09  4731.6 1579.78
  4740.0 1577.28  4745.6 1578.03  4754.0 1576.02  4762.4 1575.24  4768.0 1575.89
  4784.7 1572.06  4790.3 1573.38  4807.1 1569.48  4812.7 1570.83  4828.2 1567.51
  4836.9 1566.99  4865.8 1565.05  4902.1 1564.16  4918.9 1565.02  4941.3 1564.74
  4969.2 1562.24  4995.2 1561.38  4995.4 1560.88  4999.2 1561.38  5094.8 1565.31
  5136.7 1569.28  5200.2 1580.03  5252.9 1594.42  5295.1 1602.34  5316.2 1603.53
#Mann=6,-1,0
  4664.5   0.035       0  4828.2    0.07       0  4836.9   0.035       0
  4995.2   0.035       0  4999.2   0.035       0  5136.7    0.07       0
Bank Sta=4995.2,4999.2
Exp/Cntr=0.3,0.1

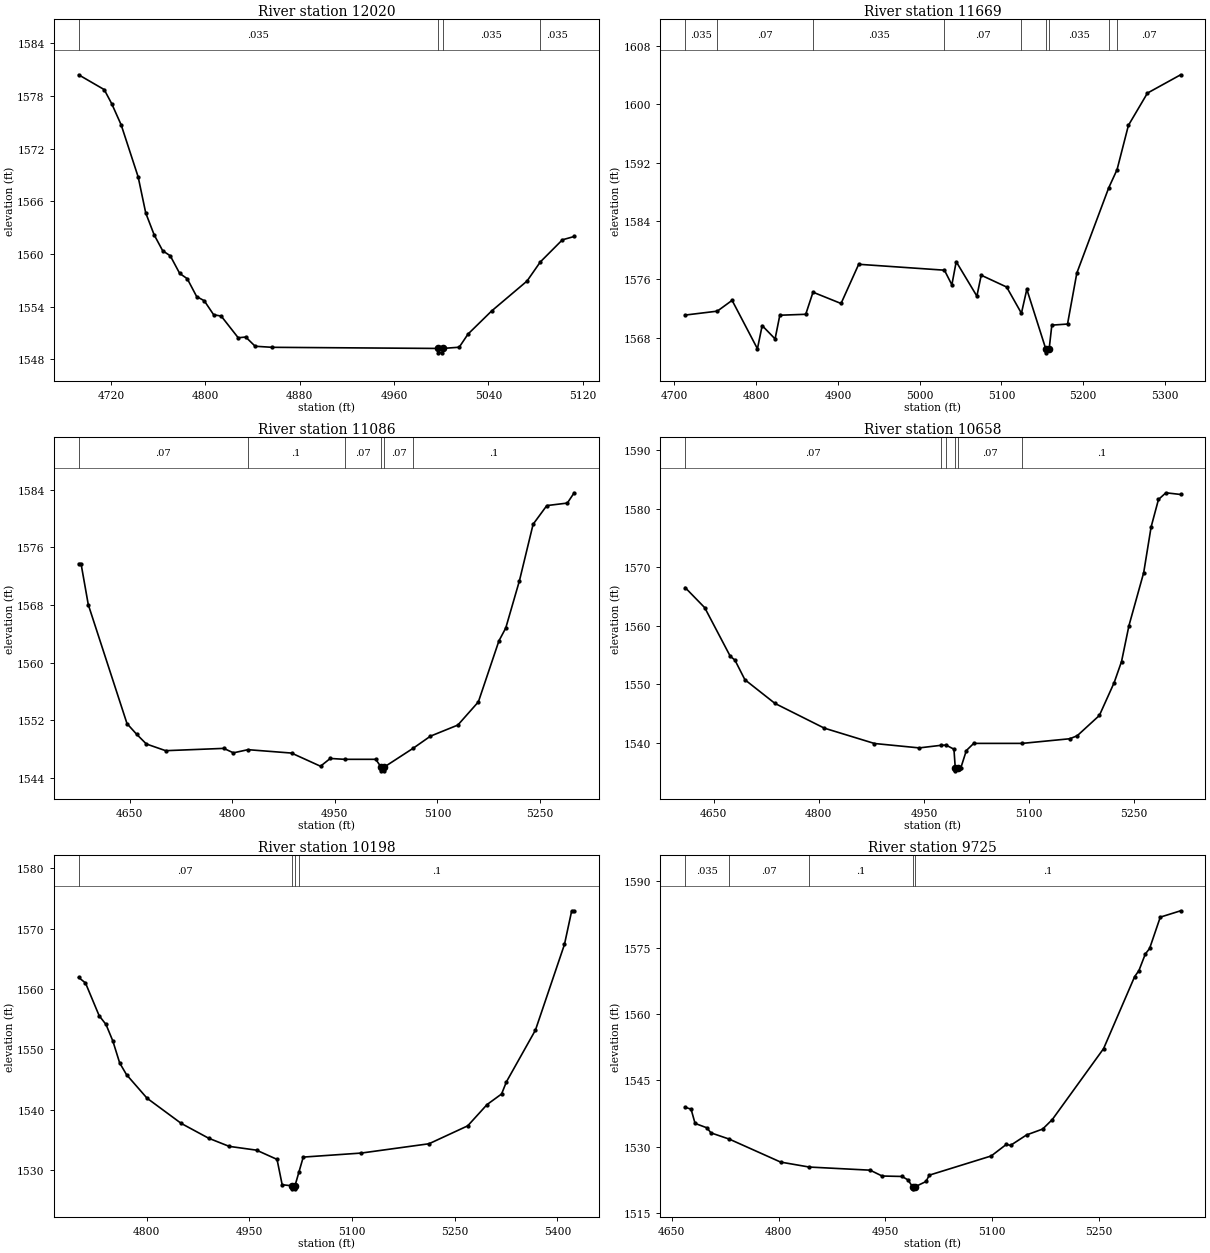
Type RM Length L Ch R = 1,12020,351,351,351
BEGIN DESCRIPTION:
Stream0412 18.0
END DESCRIPTION:
XS GIS Cut Line= 3
      1970774.98     13878125.03      1970975.00     13877875.00
      1970975.00     13877775.00
#Sta/Elev= 30
  4692.6 1580.42  4714.3 1578.73  4720.7 1577.11  4728.7 1574.70  4743.1 1568.77
  4749.5 1564.67  4756.7 1562.16  4763.9 1560.36  4770.3 1559.79  4778.3 1557.78
  4784.7 1557.18  4792.7 1555.14  4799.1 1554.67  4807.1 1553.07  4813.5 1552.92
  4827.9 1550.45  4834.3 1550.53  4842.3 1549.48  4856.7 1549.36  4997.2 1549.23
  4997.4 1548.73  5000.9 1548.73  5001.2 1549.23  5015.3 1549.37  5022.8 1550.87
  5042.8 1553.50  5072.8 1556.91  5084.1 1559.09  5102.8 1561.61  5112.8 1561.99
#Mann=4,-1,0
  4692.6   0.035       0  4997.2    0.05       0  5001.2   0.035       0
  5084.1   0.035       0
Bank Sta=4997.2,5001.2
Exp/Cntr=0.3,0.1

Type RM Length L Ch R = 1,11669,583,583,583
BEGIN DESCRIPTION:
Stream0412 17.0
END DESCRIPTION:
XS GIS Cut Line= 3
      1970875.03     13878174.98      1971115.98     13878037.46
      1971425.02     13877924.99
#Sta/Elev= 30
  4713.0 1571.09  4752.4 1571.63  4770.5 1573.11  4801.5 1566.47  4807.3 1569.65
  4823.1 1567.82  4828.9 1571.07  4860.6 1571.20  4869.5 1574.23  4903.8 1572.68
  4925.4 1578.06  5030.3 1577.25  5039.4 1575.24  5044.7 1578.42  5070.0 1573.69
  5075.3 1576.56  5106.4 1574.94  5124.5 1571.34  5131.1 1574.63  5154.4 1566.41
  5154.6 1565.91  5158.4 1566.41  5161.7 1569.71  5180.9 1569.86  5192.3 1576.86
  5231.3 1588.55  5241.5 1591.04  5255.4 1597.12  5278.7 1601.55  5319.3 1604.06
#Mann=9,-1,0
  4713.0   0.035       0  4752.4    0.07       0  4869.5   0.035       0
  5030.3    0.07       0  5124.5   0.035       0  5154.4   0.035       0
  5158.4   0.035       0  5231.3     0.1       0  5241.5    0.07       0
Bank Sta=5154.4,5158.4
Exp/Cntr=0.3,0.1

Type RM Length L Ch R = 1,11086,428,428,428
BEGIN DESCRIPTION:
Stream0412 16.0
END DESCRIPTION:
XS GIS Cut Line= 3
      1971125.03     13878774.97      1971425.00     13878475.00
      1971724.98     13878475.00
#Sta/Elev= 30
  4575.6 1573.74  4579.1 1573.74  4589.7 1568.04  4646.3 1551.51  4660.4 1550.03
  4674.6 1548.68  4702.8 1547.75  4787.7 1548.07  4801.8 1547.45  4823.1 1547.89
  4886.7 1547.42  4929.1 1545.59  4943.3 1546.67  4964.2 1546.55  5009.8 1546.55
  5017.8 1545.45  5018.1 1544.95  5021.6 1544.95  5021.8 1545.45  5064.7 1548.10
  5089.8 1549.77  5129.8 1551.31  5159.8 1554.53  5189.8 1563.00  5199.8 1564.79
  5219.8 1571.36  5239.8 1579.21  5259.8 1581.80  5289.8 1582.15  5299.8 1583.58
#Mann=6,-1,0
  4575.6    0.07       0  4823.1     0.1       0  4964.2    0.07       0
  5017.8    0.05       0  5021.8    0.07       0  5064.7     0.1       0
Bank Sta=5017.8,5021.8
Exp/Cntr=0.3,0.1

Type RM Length L Ch R = 1,10658,460,460,460
BEGIN DESCRIPTION:
Stream0412 15.0
END DESCRIPTION:
XS GIS Cut Line= 3
      1971224.99     13879075.00      1971525.00     13878825.00
      1971824.95     13878725.02
#Sta/Elev= 30
  4609.4 1566.53  4637.4 1563.09  4673.8 1554.81  4680.4 1554.17  4694.7 1550.81
  4737.6 1546.77  4807.9 1542.56  4879.5 1539.94  4943.3 1539.19  4974.2 1539.63
  4981.5 1539.67  4992.8 1538.97  4994.7 1535.78  4994.9 1535.28  4998.7 1535.78
  5002.6 1535.78  5010.5 1538.74  5021.0 1539.96  5090.2 1539.96  5158.0 1540.75
  5168.6 1541.26  5200.2 1544.72  5221.3 1550.32  5231.8 1553.91  5242.4 1560.04
  5263.4 1569.06  5274.0 1576.86  5284.5 1581.54  5295.1 1582.68  5316.1 1582.39
#Mann=6,-1,0
  4609.4    0.07       0  4974.2     0.1       0  4981.5    0.07       0
  4994.7    0.05       0  4998.7    0.07       0  5090.2     0.1       0
Bank Sta=4994.7,4998.7
Exp/Cntr=0.3,0.1

Type RM Length L Ch R = 1,10198,473,473,473
BEGIN DESCRIPTION:
Stream0412 14.0
END DESCRIPTION:
XS GIS Cut Line= 3
      1971374.99     13879225.00      1971675.00     13879225.00
      1971975.01     13878924.99
#Sta/Elev= 30
  4700.3 1561.90  4710.3 1560.99  4730.3 1555.56  4740.3 1554.11  4750.3 1551.37
  4760.3 1547.73  4770.3 1545.79  4800.3 1541.89  4850.3 1537.71  4890.3 1535.26
  4920.3 1533.91  4960.3 1533.28  4990.3 1531.75  4997.8 1527.55  5012.5 1527.37
  5012.7 1526.87  5016.2 1526.87  5016.5 1527.37  5022.5 1529.73  5028.6 1532.13
  5113.5 1532.80  5212.4 1534.34  5269.0 1537.31  5297.3 1540.84  5318.5 1542.59
  5325.6 1544.61  5368.0 1553.18  5410.4 1567.37  5421.0 1572.95  5424.6 1572.95
#Mann=4,-1,0
  4700.3    0.07       0  5012.5    0.05       0  5016.5    0.07       0
  5022.5     0.1       0
Bank Sta=5012.5,5016.5
Exp/Cntr=0.3,0.1

Type RM Length L Ch R = 1,9725,478,478,478
BEGIN DESCRIPTION:
Stream0412 13.0
END DESCRIPTION:
XS GIS Cut Line= 3
      1971625.01     13879725.00      1971925.00     13879575.00
      1972225.03     13879374.98
#Sta/Elev= 30
  4668.8 1538.88  4677.2 1538.45  4682.8 1535.23  4699.5 1534.23  4705.1 1533.09
  4731.1 1531.66  4803.0 1526.48  4843.1 1525.36  4928.7 1524.65  4945.5 1523.33
  4973.5 1523.23  4981.8 1522.45  4988.2 1520.93  4988.5 1520.43  4992.2 1520.93
  5007.2 1522.09  5011.7 1523.52  5098.8 1527.87  5119.9 1530.47  5125.9 1530.26
  5148.4 1532.62  5171.0 1533.95  5184.5 1536.09  5256.6 1552.15  5300.2 1568.43
  5306.2 1569.79  5315.2 1573.55  5321.2 1574.79  5336.2 1581.88  5364.8 1583.32
#Mann=5,-1,0
  4668.8   0.035       0  4731.1    0.07       0  4843.1     0.1       0
  4988.2    0.05       0  4992.2     0.1       0
Bank Sta=4988.2,4992.2
Exp/Cntr=0.3,0.1

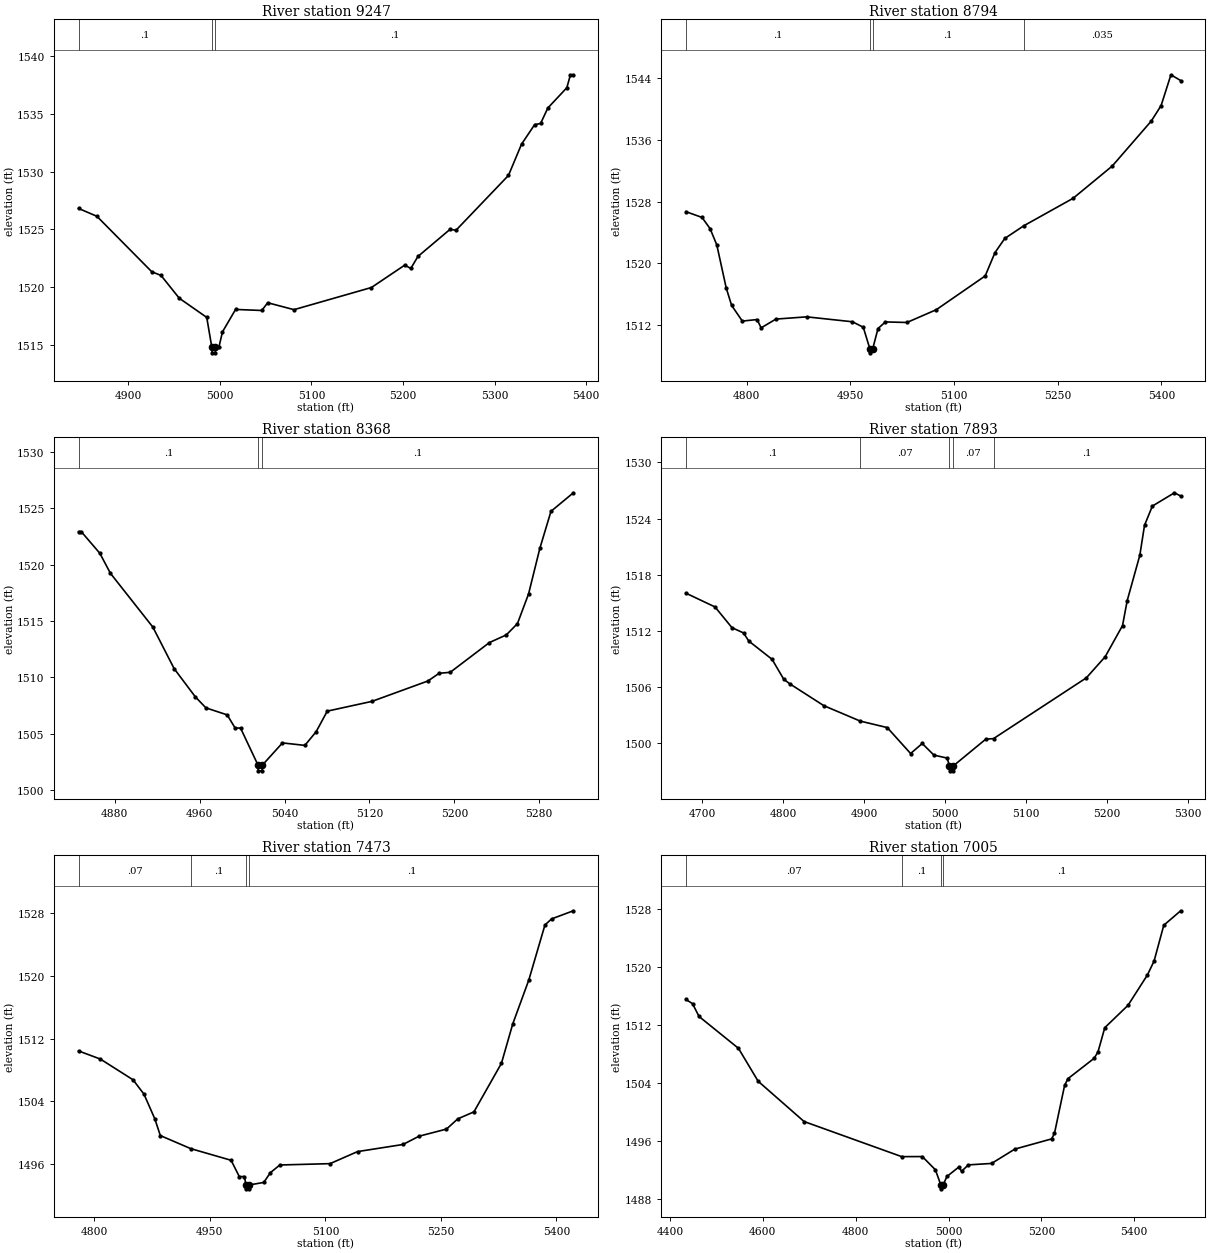
Type RM Length L Ch R = 1,9247,453,453,453
BEGIN DESCRIPTION:
Stream0412 12.0
END DESCRIPTION:
XS GIS Cut Line= 3
      1971874.98     13880025.00      1972025.00     13880025.00
      1972324.97     13879775.02
#Sta/Elev= 30
  4845.6 1526.82  4865.6 1526.14  4925.6 1521.33  4935.6 1521.02  4955.6 1519.04
  4985.6 1517.38  4991.1 1514.81  4991.4 1514.31  4994.9 1514.31  4995.1 1514.81
  4998.9 1514.81  5002.8 1516.13  5017.1 1518.07  5045.7 1517.98  5052.2 1518.65
  5080.9 1518.05  5165.5 1519.97  5201.9 1521.91  5208.5 1521.62  5216.3 1522.66
  5251.4 1525.01  5257.9 1524.93  5315.2 1529.68  5329.5 1532.39  5343.8 1534.08
  5350.3 1534.18  5358.2 1535.52  5379.0 1537.28  5382.9 1538.40  5386.1 1538.40
#Mann=3,-1,0
  4845.6     0.1       0  4991.1    0.05       0  4995.1     0.1       0
Bank Sta=4991.1,4995.1
Exp/Cntr=0.3,0.1

Type RM Length L Ch R = 1,8794,426,426,426
BEGIN DESCRIPTION:
Stream0412 11.0
END DESCRIPTION:
XS GIS Cut Line= 3
      1971975.00     13880525.00      1972225.00     13880375.00
      1972524.99     13880075.01
#Sta/Elev= 30
  4712.2 1526.72  4735.5 1525.97  4747.2 1524.51  4756.9 1522.40  4770.5 1516.82
  4778.3 1514.56  4793.8 1512.52  4815.2 1512.72  4821.0 1511.64  4842.4 1512.78
  4887.1 1513.07  4953.2 1512.43  4968.8 1511.72  4978.4 1508.90  4978.7 1508.40
  4982.4 1508.90  4990.1 1511.55  5000.8 1512.41  5032.0 1512.34  5074.5 1514.00
  5145.2 1518.38  5159.3 1521.40  5173.5 1523.24  5200.9 1524.88  5272.5 1528.46
  5329.0 1532.64  5385.6 1538.49  5399.7 1540.49  5413.9 1544.48  5428.0 1543.73
#Mann=4,-1,0
  4712.2     0.1       0  4978.4    0.05       0  4982.4     0.1       0
  5200.9   0.035       0
Bank Sta=4978.4,4982.4
Exp/Cntr=0.3,0.1

Type RM Length L Ch R = 1,8368,475,475,475
BEGIN DESCRIPTION:
Stream0412 10.0
END DESCRIPTION:
XS GIS Cut Line= 3
      1972075.03     13880775.00      1972225.00     13880775.00
      1972525.00     13880675.00
#Sta/Elev= 30
  4845.9 1522.94  4848.4 1522.94  4865.9 1521.02  4875.9 1519.24  4915.9 1514.46
  4935.9 1510.78  4955.9 1508.27  4965.9 1507.29  4985.9 1506.67  4993.4 1505.50
  4998.5 1505.50  5015.0 1502.20  5015.2 1501.70  5018.7 1501.70  5019.0 1502.20
  5038.0 1504.18  5059.1 1503.96  5069.7 1505.17  5080.2 1507.00  5122.4 1507.87
  5175.1 1509.68  5185.6 1510.36  5196.1 1510.45  5233.0 1513.09  5248.9 1513.77
  5259.4 1514.77  5269.9 1517.41  5280.5 1521.45  5291.0 1524.74  5312.1 1526.39
#Mann=3,-1,0
  4845.9     0.1       0  5015.0    0.05       0  5019.0     0.1       0
Bank Sta=5015,5019
Exp/Cntr=0.3,0.1

Type RM Length L Ch R = 1,7893,420,420,420
BEGIN DESCRIPTION:
Stream0412 9.0
END DESCRIPTION:
XS GIS Cut Line= 3
      1972224.98     13881425.02      1972425.00     13881175.00
      1972674.98     13881025.01
#Sta/Elev= 30
  4679.8 1516.04  4715.8 1514.57  4736.7 1512.36  4751.1 1511.79  4757.5 1510.93
  4786.3 1508.98  4800.7 1506.86  4807.9 1506.38  4850.3 1504.03  4895.4 1502.38
  4928.7 1501.69  4957.6 1498.92  4972.0 1499.99  4986.4 1498.75  5002.9 1498.43
  5005.6 1497.57  5005.9 1497.07  5009.7 1497.07  5010.0 1497.57  5050.5 1500.45
  5060.1 1500.51  5174.9 1507.00  5198.2 1509.26  5219.6 1512.58  5225.4 1515.25
  5241.0 1520.09  5246.8 1523.29  5256.5 1525.34  5283.8 1526.76  5291.5 1526.41
#Mann=5,-1,0
  4679.8     0.1       0  4895.4    0.07       0  5005.6    0.05       0
  5010.0    0.07       0  5060.1     0.1       0
Bank Sta=5005.6,5010
Exp/Cntr=0.3,0.1

Type RM Length L Ch R = 1,7473,468,468,468
BEGIN DESCRIPTION:
Stream0412 8.0
END DESCRIPTION:
XS GIS Cut Line= 3
      1972474.98     13881675.02      1972625.00     13881525.00
      1972875.02     13881174.98
#Sta/Elev= 30
  4779.6 1510.42  4807.9 1509.38  4850.3 1506.73  4864.5 1504.89  4878.6 1501.73
  4885.7 1499.60  4925.2 1497.93  4977.6 1496.44  4988.2 1494.36  4994.8 1494.36
  4996.9 1493.29  4997.2 1492.79  5001.0 1492.79  5001.3 1493.29  5020.0 1493.61
  5028.6 1494.86  5040.9 1495.84  5106.0 1496.01  5141.7 1497.55  5200.7 1498.46
  5221.6 1499.52  5257.2 1500.43  5271.9 1501.74  5292.8 1502.63  5328.5 1508.83
  5343.2 1513.87  5364.1 1519.50  5385.0 1526.52  5393.6 1527.30  5421.9 1528.34
#Mann=4,-1,0
  4779.6    0.07       0  4925.2     0.1       0  4996.9    0.05       0
  5001.3     0.1       0
Bank Sta=4996.9,5001.3
Exp/Cntr=0.3,0.1

Type RM Length L Ch R = 1,7005,474,474,474
BEGIN DESCRIPTION:
Stream0412 7.0
END DESCRIPTION:
XS GIS Cut Line= 3
      1972524.97     13882225.03      1972925.00     13881825.00
      1973224.99     13881425.02
#Sta/Elev= 30
  4434.3 1515.56  4448.5 1514.99  4462.6 1513.21  4547.5 1508.81  4589.9 1504.26
  4688.9 1498.69  4899.1 1493.84  4943.5 1493.85  4971.7 1492.02  4983.6 1489.89
  4983.9 1489.39  4988.1 1489.89  4996.5 1491.10  5021.9 1492.39  5028.1 1491.82
  5042.7 1492.70  5092.7 1492.90  5142.7 1494.88  5221.9 1496.29  5228.1 1497.04
  5250.0 1503.69  5257.3 1504.62  5313.6 1507.43  5321.9 1508.31  5336.5 1511.66
  5386.5 1514.75  5428.1 1518.92  5442.7 1520.87  5463.6 1525.82  5500.0 1527.82
#Mann=4,-1,0
  4434.3    0.07       0  4899.1     0.1       0  4983.6    0.05       0
  4988.1     0.1       0
Bank Sta=4983.6,4988.1
Exp/Cntr=0.3,0.1

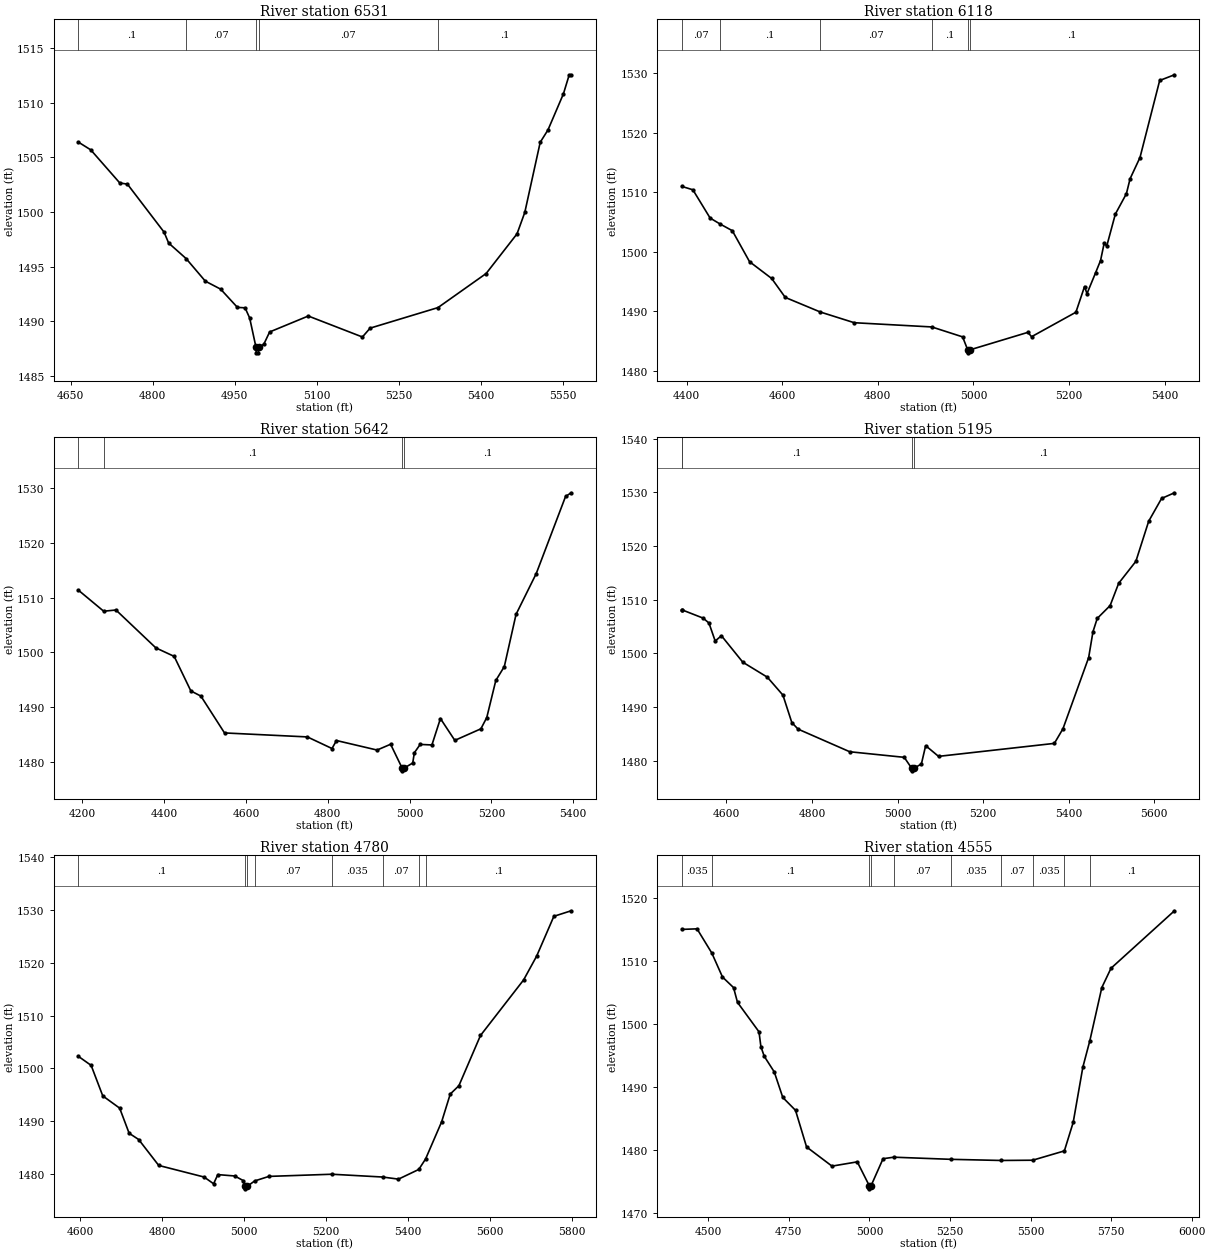
Type RM Length L Ch R = 1,6531,413,413,413
BEGIN DESCRIPTION:
Stream0412 6.0
END DESCRIPTION:
XS GIS Cut Line= 3
      1972824.98     13882375.01      1973125.00     13882225.00
      1973524.99     13881825.01
#Sta/Elev= 30
  4664.6 1506.38  4687.0 1505.68  4740.1 1502.65  4754.1 1502.54  4821.1 1498.15
  4829.5 1497.15  4861.4 1495.73  4896.6 1493.66  4924.6 1492.93  4955.3 1491.26
  4969.3 1491.22  4977.7 1490.29  4989.3 1487.60  4989.7 1487.10  4993.6 1487.10
  4993.9 1487.60  5003.6 1487.89  5014.2 1489.01  5084.9 1490.47  5183.9 1488.55
  5198.0 1489.36  5322.1 1491.24  5410.2 1494.36  5466.7 1497.99  5480.9 1499.95
  5509.1 1506.37  5523.3 1507.50  5551.6 1510.81  5562.2 1512.55  5565.7 1512.55
#Mann=5,-1,0
  4664.6     0.1       0  4861.4    0.07       0  4989.3    0.05       0
  4993.9    0.07       0  5322.1     0.1       0
Bank Sta=4989.3,4993.9
Exp/Cntr=0.3,0.1

Type RM Length L Ch R = 1,6118,476,476,476
BEGIN DESCRIPTION:
Stream0412 5.0
END DESCRIPTION:
XS GIS Cut Line= 3
      1972824.97     13882625.01      1973425.00     13882475.00
      1973825.00     13882375.00
#Sta/Elev= 30
  4389.9 1511.01  4413.1 1510.44  4449.2 1505.69  4470.3 1504.68  4495.6 1503.57
  4531.7 1498.36  4578.0 1495.54  4606.4 1492.36  4679.7 1489.91  4750.7 1488.11
  4913.0 1487.40  4977.5 1485.73  4988.1 1483.55  4988.4 1483.05  4992.7 1483.55
  5114.0 1486.49  5121.8 1485.76  5214.5 1489.87  5232.6 1494.19  5237.7 1492.99
  5255.8 1496.52  5266.1 1498.56  5273.8 1501.52  5279.0 1500.97  5297.0 1506.35
  5320.2 1509.79  5327.9 1512.30  5348.6 1515.86  5389.8 1528.80  5420.7 1529.76
#Mann=6,-1,0
  4389.9    0.07       0  4470.3     0.1       0  4679.7    0.07       0
  4913.0     0.1       0  4988.1    0.05       0  4992.7     0.1       0
Bank Sta=4988.1,4992.7
Exp/Cntr=0.3,0.1

Type RM Length L Ch R = 1,5642,447,447,447
BEGIN DESCRIPTION:
Stream0412 4.0
END DESCRIPTION:
XS GIS Cut Line= 3
      1973524.99     13883625.03      1973675.00     13882825.00
      1973925.01     13882524.99
#Sta/Elev= 30
  4190.5 1511.34  4252.1 1507.51  4282.1 1507.73  4379.6 1500.81  4424.5 1499.25
  4465.2 1492.94  4489.8 1491.99  4547.5 1485.26  4750.1 1484.53  4810.3 1482.41
  4821.3 1483.87  4920.5 1482.13  4953.6 1483.19  4981.8 1478.83  4982.1 1478.33
  4986.5 1478.83  5007.7 1479.76  5011.6 1481.63  5025.9 1483.16  5054.6 1483.06
  5075.4 1487.89  5110.6 1483.90  5174.3 1486.01  5188.7 1488.07  5210.8 1494.85
  5231.6 1497.39  5260.3 1506.94  5309.7 1514.40  5381.3 1528.48  5395.0 1529.16
#Mann=4,-1,0
  4190.5    0.07       0  4252.1     0.1       0  4981.8    0.05       0
  4986.5     0.1       0
Bank Sta=4981.8,4986.5
Exp/Cntr=0.3,0.1

Type RM Length L Ch R = 1,5195,415,415,415
BEGIN DESCRIPTION:
Stream0412 3.0
END DESCRIPTION:
XS GIS Cut Line= 3
      1973625.00     13883575.00      1973925.00     13883175.00
      1973975.00     13882525.02
#Sta/Elev= 30
  4495.5 1508.09  4496.5 1508.09  4545.5 1506.56  4559.0 1505.65  4573.6 1502.29
  4588.2 1503.28  4638.2 1498.34  4695.5 1495.55  4732.0 1492.20  4752.8 1487.08
  4767.4 1485.86  4888.2 1481.64  5015.6 1480.60  5032.9 1478.58  5033.3 1478.08
  5038.4 1478.58  5055.7 1479.35  5065.7 1482.78  5095.8 1480.78  5366.6 1483.20
  5386.7 1485.92  5446.8 1499.20  5456.9 1504.03  5466.9 1506.51  5497.0 1508.90
  5517.0 1513.06  5557.2 1517.15  5587.2 1524.64  5617.3 1528.88  5647.4 1529.94
#Mann=4,-1,0
  4495.5    0.07       0  4496.5     0.1       0  5032.9    0.05       0
  5038.4     0.1       0
Bank Sta=5032.9,5038.4
Exp/Cntr=0.3,0.1

Type RM Length L Ch R = 1,4780,225,225,225
BEGIN DESCRIPTION:
Stream0412 2.0
END DESCRIPTION:
XS GIS Cut Line= 3
      1974175.00     13883675.01      1974275.00     13883275.00
      1974025.00     13882524.99
#Sta/Elev= 30
  4595.8 1502.24  4626.7 1500.54  4655.1 1494.75  4696.3 1492.43  4719.5 1487.66
  4742.7 1486.48  4791.7 1481.56  4902.5 1479.36  4925.7 1478.08  4936.0 1479.82
  4977.2 1479.56  4997.8 1478.70  5002.7 1477.62  5003.2 1477.12  5008.3 1477.62
  5026.0 1478.62  5060.8 1479.48  5214.5 1479.89  5338.5 1479.36  5377.1 1478.96
  5426.7 1480.80  5443.3 1482.79  5482.5 1489.84  5503.5 1495.10  5524.6 1496.68
  5577.3 1506.21  5682.7 1516.76  5714.4 1521.26  5756.5 1528.82  5798.7 1529.87
#Mann=8,-1,0
  4595.8     0.1       0  5002.7    0.05       0  5008.3     0.1       0
  5026.0    0.07       0  5214.5   0.035       0  5338.5    0.07       0
  5426.7   0.035       0  5443.3     0.1       0
Bank Sta=5002.7,5008.3
Exp/Cntr=0.3,0.1

Type RM Length L Ch R = 1,4555,639,639,639
BEGIN DESCRIPTION:
Mapping XS 9ea124e7
END DESCRIPTION:
XS GIS Cut Line= 4
      1974336.29     13883941.61      1974468.59     13883463.70
      1974467.23     13882652.35      1974406.01     13882439.41
#Sta/Elev= 30
  4417.8 1515.08  4465.1 1515.17  4510.9 1511.33  4544.1 1507.51  4578.4 1505.83
  4590.7 1503.48  4657.4 1498.80  4663.3 1496.44  4673.7 1494.91  4704.8 1492.42
  4731.2 1488.37  4770.7 1486.32  4805.0 1480.50  4883.9 1477.45  4962.4 1478.13
  4999.6 1474.34  5000.0 1473.84  5005.2 1474.34  5042.4 1478.63  5075.8 1478.87
  5253.4 1478.53  5408.2 1478.35  5506.6 1478.39  5605.0 1479.87  5632.4 1484.40
  5662.4 1493.19  5684.0 1497.38  5721.2 1505.83  5749.7 1508.90  5946.6 1518.04
#Mann=10,-1,0
  4417.8   0.035       0  4510.9     0.1       0  4999.6    0.05       0
  5005.2     0.1       0  5075.8    0.07       0  5253.4   0.035       0
  5408.2    0.07       0  5506.6   0.035       0  5605.0    0.07       0
  5684.0     0.1       0
Bank Sta=4999.6,5005.2
Exp/Cntr=0.3,0.1

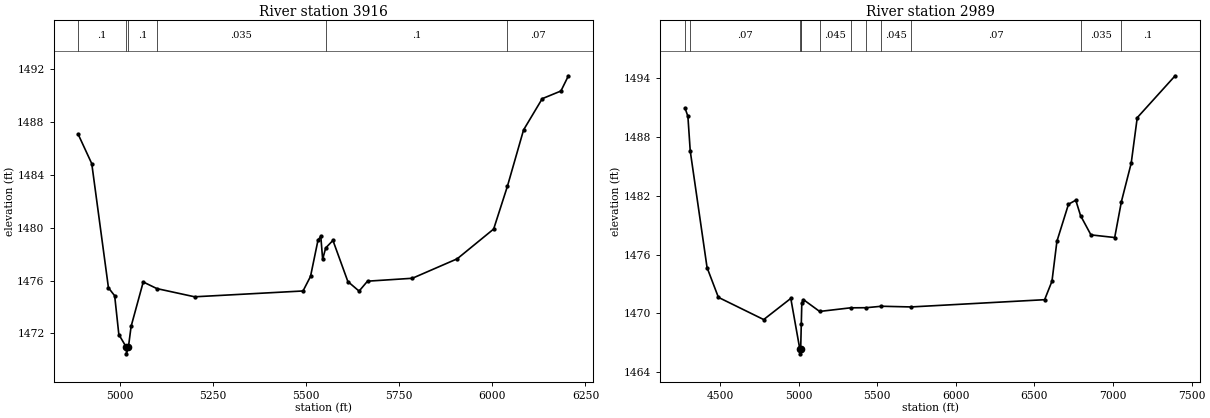
Type RM Length L Ch R = 1,3916,927,927,927
BEGIN DESCRIPTION:
Stream0412 1.0
END DESCRIPTION:
XS GIS Cut Line= 3
      1974724.99     13883875.00      1974825.00     13883825.00
      1974925.00     13882624.97
#Sta/Elev= 30
  4888.2 1487.04  4924.5 1484.83  4969.3 1475.45  4986.0 1474.85  4997.2 1471.92
  5017.3 1470.96  5017.7 1470.46  5022.9 1470.96  5030.1 1472.53  5062.7 1475.89
  5099.3 1475.39  5200.7 1474.77  5491.7 1475.21  5511.8 1476.31  5531.9 1479.05
  5539.4 1479.34  5544.4 1477.60  5552.5 1478.46  5572.0 1479.03  5612.1 1475.92
  5642.2 1475.20  5664.8 1475.95  5785.2 1476.17  5905.6 1477.64  6003.5 1479.89
  6040.4 1483.12  6083.8 1487.38  6133.9 1489.74  6184.1 1490.32  6204.2 1491.47
#Mann=6,-1,0
  4888.2     0.1       0  5017.3    0.05       0  5022.9     0.1       0
  5099.3   0.035       0  5552.5     0.1       0  6040.4    0.07       0
Bank Sta=5017.3,5022.9
Exp/Cntr=0.3,0.1

Type RM Length L Ch R = 1,2989,0,0,0
BEGIN DESCRIPTION:
Stream0412 0.0
END DESCRIPTION:
XS GIS Cut Line= 4
      1975159.35     13884595.83      1975632.40     13884279.07
      1975652.51     13882961.58      1975277.00     13881788.89
#Sta/Elev= 30
  4276.6 1490.99  4295.4 1490.13  4310.3 1486.59  4417.3 1474.68  4489.4 1471.64
  4777.6 1469.37  4950.0 1471.53  5007.2 1466.37  5007.6 1465.87  5012.9 1466.37
  5016.8 1468.92  5020.0 1471.02  5030.0 1471.41  5133.5 1470.20  5330.2 1470.57
  5428.5 1470.58  5526.9 1470.73  5715.0 1470.66  6564.8 1471.40  6611.5 1473.29
  6643.0 1477.37  6716.5 1481.15  6762.9 1481.56  6793.3 1479.99  6859.3 1478.02
  7010.5 1477.75  7053.2 1481.42  7115.5 1485.34  7153.9 1489.99  7394.9 1494.27
#Mann=12,-1,0
  4276.6   0.035       0  4310.3    0.07       0  5007.2    0.05       0
  5012.9    0.07       0  5016.8   0.035       0  5133.5   0.045       0
  5330.2   0.035       0  5428.5    0.07       0  5526.9   0.045       0
  5715.0    0.07       0  6793.3   0.035       0  7053.2     0.1       0
Bank Sta=5007.2,5012.9
Exp/Cntr=0.3,0.1

Chan Stop Cuts=-1