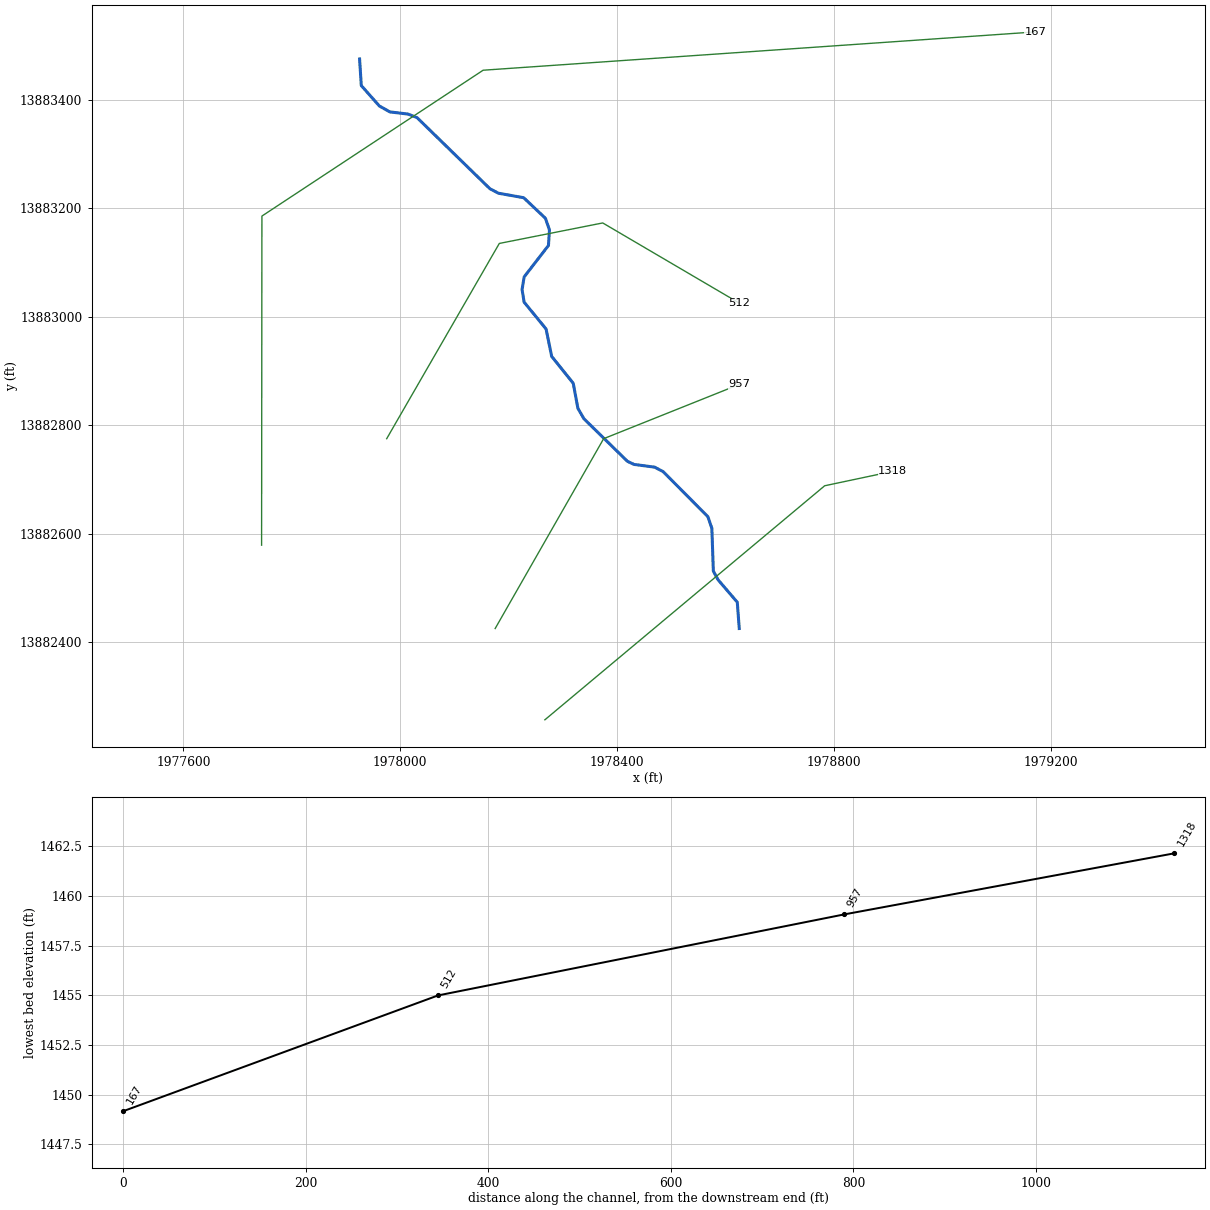
--- Stream0419.prj (project) ---

Proj Title=Stream0419 Base Level Engineering
Current Plan=p01
Default Exp/Contr=0.3,0.1
English Units
Geom File=g01
Flow File=f01
Plan File=p01
BEGIN DESCRIPTION:
Stream0419
END DESCRIPTION:

--- Stream0419.p01 (plan) ---

Plan Title=Multiple Run
Short Identifier=Multiple
Geom File=g01
Flow File=f01
Subcritical Flow
K Sum by GR= 0
Std Step Tol= 0.01
Critical Tol= 0.01
Num of Std Step Trials= 20
Max Error Tol= 0.3
Flow Tol Ratio= 0.001
Split Flow NTrial= 30
Split Flow Tol= 0.02
Split Flow Ratio= 0.02
Log Output Level= 0
Friction Slope Method= 1
Unsteady Friction Slope Method= 2
Unsteady Bridges Friction Slope Method= 1
Parabolic Critical Depth
Global Vel Dist=  1 , 1 , 1
Global Log Level= 0
CheckData=True
Encroach Param= -1, 0, 0, 0
BEGIN DESCRIPTION:
Multiple Run
END DESCRIPTION:

--- Stream0419.f01 (steady flow) ---

Flow Title=Multiple
Number of Profiles=7
Profile Names=10-year,25-year,50-year,1pct_min,100-year,1pct_plu,500-year
River Rch & RM= Stream0419,Reach-1,1318
    1393    2428    3440    2363    4714    9406    8762
Boundary for River Rch & Prof#=Stream0419,Reach-1,1
Up Type=0
Dn Type=3
Dn Slope=0.005
Boundary for River Rch & Prof#=Stream0419,Reach-1,2
Up Type=0
Dn Type=3
Dn Slope=0.005
Boundary for River Rch & Prof#=Stream0419,Reach-1,3
Up Type=0
Dn Type=3
Dn Slope=0.005
Boundary for River Rch & Prof#=Stream0419,Reach-1,4
Up Type=0
Dn Type=3
Dn Slope=0.005
Boundary for River Rch & Prof#=Stream0419,Reach-1,5
Up Type=0
Dn Type=3
Dn Slope=0.005
Boundary for River Rch & Prof#=Stream0419,Reach-1,6
Up Type=0
Dn Type=3
Dn Slope=0.005
Boundary for River Rch & Prof#=Stream0419,Reach-1,7
Up Type=0
Dn Type=3
Dn Slope=0.005

--- Stream0419.g01 (geometry) ---

Geom Title=Existing Conditions

River Reach=Stream0419,Reach-1
Reach XY= 30
      1978625.00     13882425.00      1978621.36     13882473.49
      1978585.62     13882515.26      1978577.23     13882530.92
      1978574.49     13882609.79      1978567.15     13882631.19
      1978484.70     13882714.23      1978468.96     13882722.47
      1978431.04     13882727.53      1978418.94     13882733.15
      1978338.61     13882811.76      1978327.50     13882831.03
      1978318.90     13882877.18      1978279.15     13882926.72
      1978268.84     13882977.20      1978228.34     13883026.72
      1978224.60     13883050.00      1978228.40     13883073.28
      1978273.21     13883131.16      1978275.09     13883159.79
      1978267.63     13883181.34      1978227.61     13883219.25
      1978181.09     13883227.55      1978165.34     13883235.79
      1978031.04     13883366.85      1978014.34     13883373.48
      1977980.90     13883377.46      1977961.46     13883388.39
      1977928.14     13883426.03      1977925.00     13883475.00

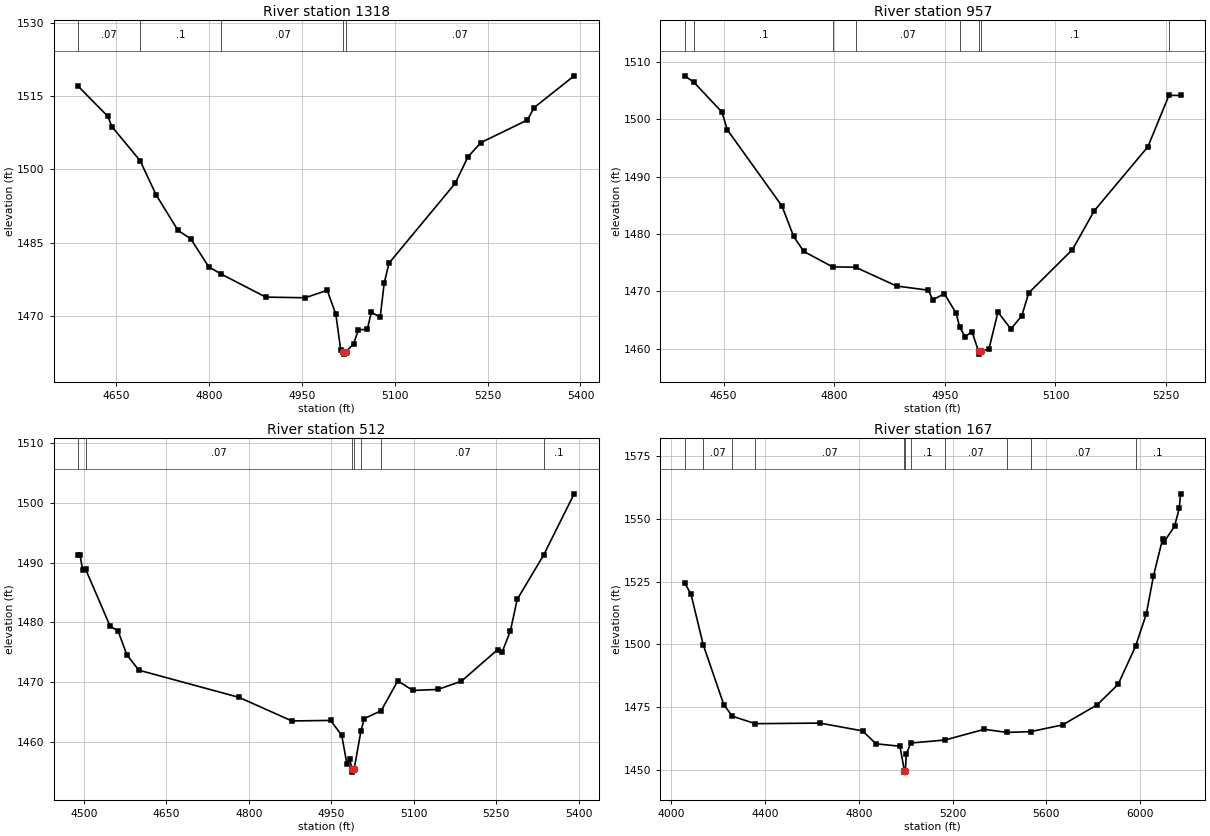
Type RM Length L Ch R = 1,1318,361,361,361
BEGIN DESCRIPTION:
Stream0419 3.0
END DESCRIPTION:
XS GIS Cut Line= 3
      1978266.63     13882256.69      1978782.48     13882688.18
      1978908.07     13882714.78
#Sta/Elev= 30
  4588.9 1516.99  4636.6 1510.85  4643.1 1508.75  4688.6 1501.79  4714.7 1494.74
  4749.8 1487.50  4770.7 1485.74  4799.3 1480.06  4820.0 1478.52  4891.7 1473.82
  4955.4 1473.69  4990.9 1475.22  5004.9 1470.29  5012.7 1462.99  5017.2 1462.64
  5017.5 1462.14  5021.2 1462.64  5033.5 1464.24  5041.3 1467.14  5055.6 1467.20
  5062.1 1470.69  5076.5 1469.75  5083.0 1476.71  5090.8 1480.80  5197.5 1497.11
  5218.3 1502.56  5239.1 1505.48  5314.2 1510.10  5325.3 1512.67  5389.8 1519.16
#Mann=5,-1,0
  4588.9    0.07       0  4688.6     0.1       0  4820.0    0.07       0
  5017.2    0.05       0  5021.2    0.07       0
Bank Sta=5017.2,5021.2
Exp/Cntr=0.3,0.1

Type RM Length L Ch R = 1,957,445,445,445
BEGIN DESCRIPTION:
Stream0419 2.0
END DESCRIPTION:
XS GIS Cut Line= 3
      1978174.98     13882424.97      1978375.00     13882775.00
      1978624.99     13882875.00
#Sta/Elev= 30
  4597.3 1507.60  4609.9 1506.44  4647.7 1501.27  4654.9 1498.20  4729.1 1484.89
  4744.9 1479.60  4758.6 1476.98  4797.6 1474.29  4828.9 1474.22  4884.6 1470.94
  4927.7 1470.22  4933.5 1468.53  4949.3 1469.61  4965.2 1466.22  4970.2 1463.72
  4977.4 1462.14  4986.8 1462.97  4995.6 1459.57  4995.8 1459.07  4999.6 1459.57
  5009.9 1460.05  5022.0 1466.41  5039.5 1463.45  5054.3 1465.75  5063.7 1469.74
  5123.0 1477.30  5152.6 1484.07  5225.3 1495.23  5253.9 1504.20  5269.7 1504.17
#Mann=8,-1,0
  4597.3    0.07       0  4609.9     0.1       0  4797.6   0.035       0
  4828.9    0.07       0  4970.2     0.1       0  4995.6    0.05       0
  4999.6     0.1       0  5253.9    0.07       0
Bank Sta=4995.6,4999.6
Exp/Cntr=0.3,0.1

Type RM Length L Ch R = 1,512,345,345,345
BEGIN DESCRIPTION:
Stream0419 1.0
END DESCRIPTION:
XS GIS Cut Line= 4
      1977975.00     13882775.00      1978182.59     13883134.95
      1978373.29     13883172.77      1978624.99     13883025.01
#Sta/Elev= 30
  4489.8 1491.32  4492.7 1491.32  4497.7 1488.80  4503.0 1488.90  4547.5 1479.40
  4562.3 1478.53  4578.1 1474.58  4599.7 1472.03  4782.1 1467.48  4878.3 1463.54
  4948.6 1463.63  4968.9 1461.13  4978.4 1456.29  4983.5 1457.16  4987.3 1455.49
  4987.6 1454.99  4991.4 1455.49  5003.7 1461.80  5009.7 1463.93  5040.6 1465.25
  5070.9 1470.25  5098.1 1468.64  5143.5 1468.80  5186.5 1470.18  5252.5 1475.46
  5260.7 1475.07  5275.7 1478.61  5288.0 1483.85  5336.0 1491.25  5391.6 1501.49
#Mann=7,-1,0
  4489.8     0.1       0  4503.0    0.07       0  4987.3    0.05       0
  4991.4    0.07       0  5003.7     0.1       0  5040.6    0.07       0
  5336.0     0.1       0
Bank Sta=4987.3,4991.4
Exp/Cntr=0.3,0.1

Type RM Length L Ch R = 1,167,0,0,0
BEGIN DESCRIPTION:
Stream0419 0.1
END DESCRIPTION:
XS GIS Cut Line= 4
      1977744.33     13882578.67      1977744.92     13883185.42
      1978152.79     13883454.34      1979170.95     13883524.97
#Sta/Elev= 30
  4057.6 1524.37  4083.9 1520.06  4136.0 1499.93  4223.9 1476.06  4260.2 1471.43
  4358.5 1468.45  4633.9 1468.68  4816.1 1465.58  4873.3 1460.44  4975.7 1459.47
  4994.7 1449.66  4995.0 1449.16  4998.8 1449.66  5002.7 1456.25  5021.8 1460.75
  5167.6 1461.94  5335.5 1466.20  5432.1 1464.97  5533.0 1465.27  5669.8 1467.96
  5817.2 1475.95  5906.9 1484.11  5981.3 1499.29  6027.2 1512.17  6057.3 1527.14
  6097.0 1542.16  6102.0 1540.72  6147.5 1547.01  6167.5 1554.16  6173.5 1559.95
#Mann=11,-1,0
  4057.6     0.1       0  4136.0    0.07       0  4260.2   0.035       0
  4358.5    0.07       0  4994.7    0.05       0  4998.8    0.07       0
  5021.8     0.1       0  5167.6    0.07       0  5432.1   0.035       0
  5533.0    0.07       0  5981.3     0.1       0
Bank Sta=4994.7,4998.8
Exp/Cntr=0.3,0.1

Chan Stop Cuts=-1