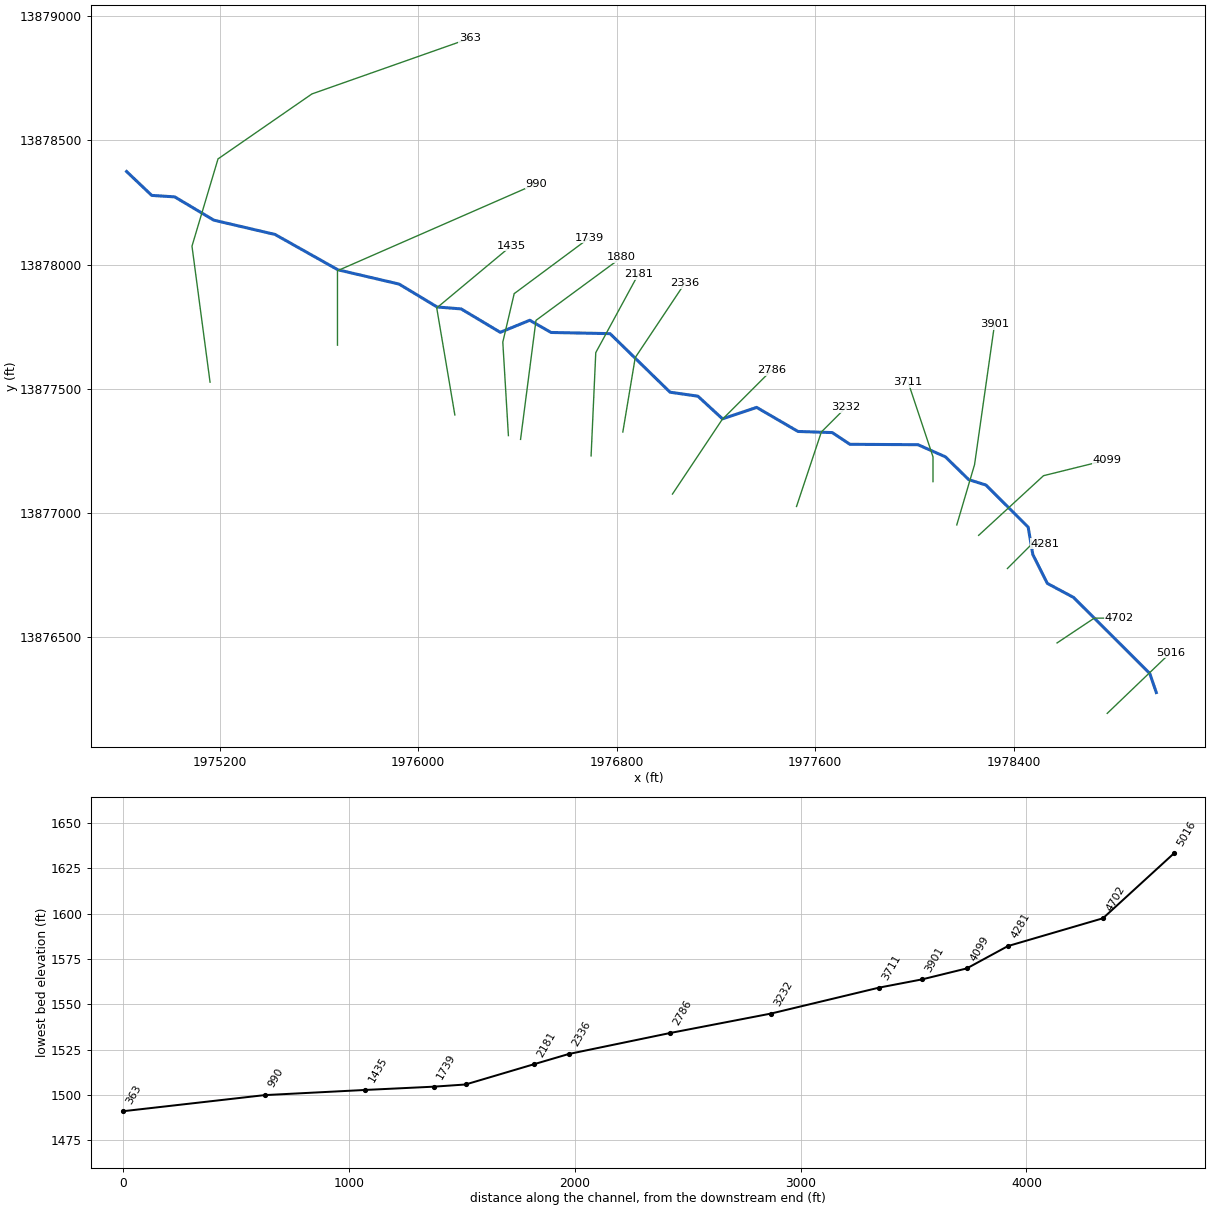
--- Stream0429.prj (project) ---

Proj Title=Stream0429 Base Level Engineering
Current Plan=p01
Default Exp/Contr=0.3,0.1
English Units
Geom File=g01
Flow File=f01
Plan File=p01
Y Axis Title=Elevation
X Axis Title(PF)=Main Channel Distance
X Axis Title(XS)=Station
BEGIN DESCRIPTION:
Stream0429
END DESCRIPTION:
DSS Export Rating Curves= 0
DSS Export Rating Curve Sorted= 0
DSS Export Volume Flow Curves= 0
DXF OffsetX= 0
DXF OffsetY= 0
DXF ScaleX= 1
DXF ScaleY= 10

--- Stream0429.p01 (plan) ---

Plan Title=Multiple Run
Short Identifier=Multiple
Geom File=g01
Flow File=f01
Subcritical Flow
K Sum by GR= 0
Std Step Tol= 0.01
Critical Tol= 0.01
Num of Std Step Trials= 20
Max Error Tol= 0.3
Flow Tol Ratio= 0.001
Split Flow NTrial= 30
Split Flow Tol= 0.02
Split Flow Ratio= 0.02
Log Output Level= 0
Friction Slope Method= 1
Unsteady Friction Slope Method= 2
Unsteady Bridges Friction Slope Method= 1
Parabolic Critical Depth
Global Vel Dist=  1 , 1 , 1
Global Log Level= 0
CheckData=True
Encroach Param= -1, 0, 0, 0
BEGIN DESCRIPTION:
Multiple Run
END DESCRIPTION:

--- Stream0429.f01 (steady flow) ---

Flow Title=Multiple
Program Version=4.10
Number of Profiles= 7
Profile Names=10-year,25-year,50-year,1pct_min,100-year,1pct_plu,500-year
River Rch & RM=Stream0429,Reach-1         ,5016
     526     866    1183     787    1571    3134    2732
River Rch & RM=Stream0429,Reach-1         ,2786
     724    1215    1680    1129    2252    4494    4000
Boundary for River Rch & Prof#=Stream0429,Reach-1         , 1
Up Type= 0
Dn Type= 3
Dn Slope=0.008
Boundary for River Rch & Prof#=Stream0429,Reach-1         , 2
Up Type= 0
Dn Type= 3
Dn Slope=0.008
Boundary for River Rch & Prof#=Stream0429,Reach-1         , 3
Up Type= 0
Dn Type= 3
Dn Slope=0.008
Boundary for River Rch & Prof#=Stream0429,Reach-1         , 4
Up Type= 0
Dn Type= 3
Dn Slope=0.008
Boundary for River Rch & Prof#=Stream0429,Reach-1         , 5
Up Type= 0
Dn Type= 3
Dn Slope=0.008
Boundary for River Rch & Prof#=Stream0429,Reach-1         , 6
Up Type= 0
Dn Type= 3
Dn Slope=0.008
Boundary for River Rch & Prof#=Stream0429,Reach-1         , 7
Up Type= 0
Dn Type= 3
Dn Slope=0.008
DSS Import GetInterval= 0
DSS Import GetPeak= 0
DSS Import FillOption= 0

--- Stream0429.g01 (geometry) ---

Geom Title=Existing Conditions
Program Version=4.10

River Reach=Stream0429      ,Reach-1
Reach XY= 30
        1978975.       13876275.      1978948.65      13876351.8
      1978641.66     13876658.34      1978535.63       13876715.
      1978477.33     13876830.97      1978458.54     13876941.75
      1978288.21     13877111.37      1978218.93     13877133.11
        1978125.       13877225.      1978014.54     13877273.88
      1977740.22     13877275.52      1977669.06     13877322.73
      1977530.93     13877327.25      1977364.31     13877424.25
      1977226.64     13877378.14      1977127.42     13877469.46
      1977015.21     13877485.52      1976773.54     13877721.46
       1976535.5     13877726.24        1976450.     13877775.39
      1976331.11      13877726.8      1976173.42     13877821.17
      1976076.58     13877828.83      1975923.42     13877921.17
      1975676.58     13877978.83      1975423.42     13878121.17
      1975176.58     13878178.83      1975019.03     13878272.67
      1974926.48     13878278.56        1974825.       13878375.

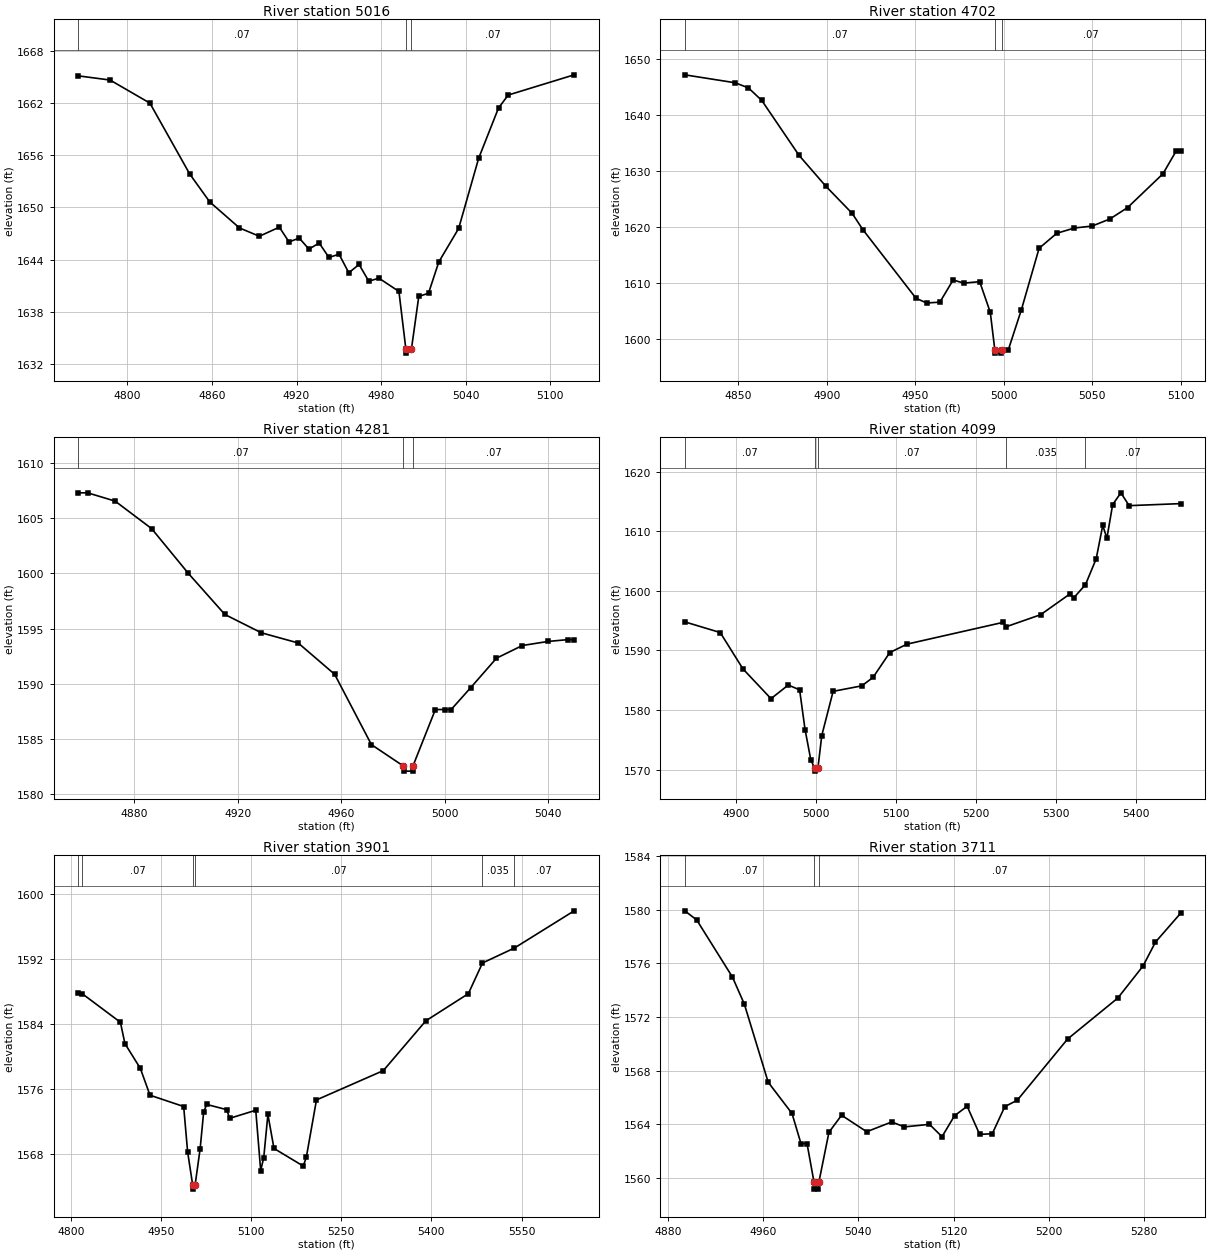
Type RM Length L Ch R = 1 ,5016    ,314,314,314
BEGIN DESCRIPTION:
Stream0429 3.1
END DESCRIPTION:
XS GIS Cut Line= 2
      1978777.19     13876191.12      1979031.22     13876434.78
#Sta/Elev= 30
  4765.1 1665.17  4787.6 1664.69  4815.9 1662.03  4844.2 1653.85  4858.4 1650.64
  4879.5 1647.64  4893.6 1646.68  4907.8 1647.73  4914.7 1646.02  4921.9 1646.48
  4928.8  1645.2  4936.1  1645.9    4943 1644.24  4950.2 1644.61  4957.1 1642.47
  4964.4 1643.43  4971.3  1641.5  4978.5 1641.85  4992.7 1640.32  4997.6 1633.71
  4997.8 1633.21  5001.6 1633.71  5006.8 1639.75  5013.7 1640.11    5021 1643.72
  5035.1 1647.58  5049.3 1655.67  5063.4 1661.47  5070.3 1662.96  5117.1 1665.29
#Mann= 3 ,-1 , 0
  4765.1     .07       0  4997.6     .05       0  5001.6     .07       0
Bank Sta=4997.6,5001.6
XS Rating Curve= 0 ,0
Exp/Cntr=0.3,0.1

Type RM Length L Ch R = 1 ,4702    ,421,421,421
BEGIN DESCRIPTION:
Stream0428 2.0
END DESCRIPTION:
XS GIS Cut Line= 3
      1978575.02     13876475.01        1978725.       13876575.
      1978825.04       13876575.
#Sta/Elev= 30
  4819.7 1647.14  4848.2 1645.72  4855.7  1644.8  4863.2 1642.57  4884.3 1632.75
  4899.3 1627.29  4914.3  1622.4  4920.3 1619.51  4950.4 1607.23  4956.4 1606.39
  4963.9 1606.53  4971.4  1610.5  4977.4 1609.93  4986.4  1610.2  4992.4 1604.71
    4995 1597.93  4995.2 1597.43  4998.7 1597.43    4999 1597.93  5002.5 1597.93
    5010  1605.2    5020 1616.16    5030 1618.84    5040 1619.78    5050 1620.13
    5060 1621.39    5070 1623.42    5090 1629.46  5097.5 1633.54    5100 1633.54
#Mann= 3 ,-1 , 0
  4819.7     .07       0    4995     .05       0    4999     .07       0
Bank Sta=4995,4999
XS Rating Curve= 0 ,0
Exp/Cntr=0.3,0.1

Type RM Length L Ch R = 1 ,4281    ,182,182,182
BEGIN DESCRIPTION:
Stream0428 1.0
END DESCRIPTION:
XS GIS Cut Line= 3
      1978374.98     13876774.98        1978475.       13876875.
      1978525.05       13876875.
#Sta/Elev= 23
  4858.5 1607.29  4862.1 1607.29  4872.7 1606.54  4886.8 1604.05    4901 1599.99
  4915.1 1596.27  4929.2 1594.61  4943.4 1593.69  4957.5 1590.85  4971.7 1584.48
  4983.8 1582.58  4984.1 1582.08  4987.6 1582.08  4987.8 1582.58  4996.4 1587.66
    5000 1587.66  5002.5 1587.66    5010 1589.63    5020 1592.31    5030 1593.46
    5040 1593.83  5047.5 1593.99    5050 1593.99
#Mann= 3 ,-1 , 0
  4858.5     .07       0  4983.8     .05       0  4987.8     .07       0
Bank Sta=4983.8,4987.8
XS Rating Curve= 0 ,0
Exp/Cntr=0.3,0.1

Type RM Length L Ch R = 1 ,4099    ,198,198,198
BEGIN DESCRIPTION:
Mapping XS 23c395c4
END DESCRIPTION:
XS GIS Cut Line= 3
      1978258.93     13876908.57       1978520.4     13877149.02
      1978777.52     13877212.64
#Sta/Elev= 30
  4835.4 1594.79  4879.7    1593  4908.1 1586.91  4943.2 1581.91  4964.8  1584.2
    4979 1583.39  4985.8 1576.73  4993.1 1571.58  4997.9 1570.26  4998.2 1569.76
  5001.9 1570.26  5006.7 1575.73  5020.9 1583.14  5056.7 1584.06  5070.8 1585.47
  5091.8 1589.65  5113.4 1591.06  5233.9 1594.72  5237.2 1593.97  5280.4 1595.99
  5316.7 1599.44  5321.9 1598.83  5336.5 1601.03  5349.9 1605.37  5358.1 1610.96
  5363.3 1608.82  5370.5 1614.46  5380.8 1616.43  5391.1 1614.28  5455.5 1614.62
#Mann= 5 ,-1 , 0
  4835.4     .07       0  4997.9     .05       0  5001.9     .07       0
  5237.2    .035       0  5336.5     .07       0
Bank Sta=4997.9,5001.9
XS Rating Curve= 0 ,0
Exp/Cntr=0.3,0.1

Type RM Length L Ch R = 1 ,3901    ,190,190,190
BEGIN DESCRIPTION:
Mapping XS 3b418c07
END DESCRIPTION:
XS GIS Cut Line= 3
      1978170.85     13876950.63      1978242.52     13877193.72
      1978323.07     13877759.28
#Sta/Elev= 30
  4812.7 1587.83  4819.1 1587.77  4882.7 1584.25  4890.2 1581.62  4915.8 1578.58
  4931.9 1575.27  4987.9 1573.88  4994.5 1568.29  5002.9 1564.21  5003.2 1563.71
  5006.9 1564.21  5015.3 1568.67  5021.2 1573.24  5026.4 1574.13  5059.7 1573.49
  5064.2 1572.42  5107.8 1573.42    5116    1566  5121.1  1567.6    5128  1572.9
  5138.1 1568.72  5186.8 1566.55  5191.9 1567.63  5208.8 1574.69    5320  1578.3
  5390.7 1584.43  5461.4 1587.77  5484.9 1591.55    5538 1593.39  5637.4 1597.97
#Mann= 6 ,-1 , 0
  4812.7    .035       0  4819.1     .07       0  5002.9     .05       0
  5006.9     .07       0  5484.9    .035       0    5538     .07       0
#XS Ineff= 2 , 0
                         5038.76         1573.57
Permanent Ineff=
       F       F
Bank Sta=5002.9,5006.9
XS Rating Curve= 0 ,0
Exp/Cntr=0.3,0.1

Type RM Length L Ch R = 1 ,3711    ,479,479,479
BEGIN DESCRIPTION:
Stream0429 7.0
END DESCRIPTION:
XS GIS Cut Line= 3
        1978075.     13877125.05        1978075.       13877225.
      1977974.99     13877525.02
#Sta/Elev= 30
  4894.3 1579.92  4904.3 1579.24  4934.3 1574.98  4944.3 1572.96  4964.3 1567.14
  4984.3 1564.81  4991.8 1562.57  4996.9 1562.57  5002.8 1559.67    5003 1559.17
  5006.5 1559.17  5006.8 1559.67  5015.3 1563.41  5025.9 1564.68    5047 1563.45
    5068 1564.18  5078.6 1563.81  5099.7    1564  5110.2 1563.08  5120.7 1564.64
  5131.3 1565.35  5141.8 1563.25  5152.4  1563.3  5162.9 1565.32  5173.4  1565.8
  5215.6 1570.36  5257.8 1573.42  5278.9  1575.8  5289.4 1577.59  5310.5 1579.74
#Mann= 3 ,-1 , 0
  4894.3     .07       0  5002.8     .05       0  5006.8     .07       0
Bank Sta=5002.8,5006.8
XS Rating Curve= 0 ,0
Exp/Cntr=0.3,0.1

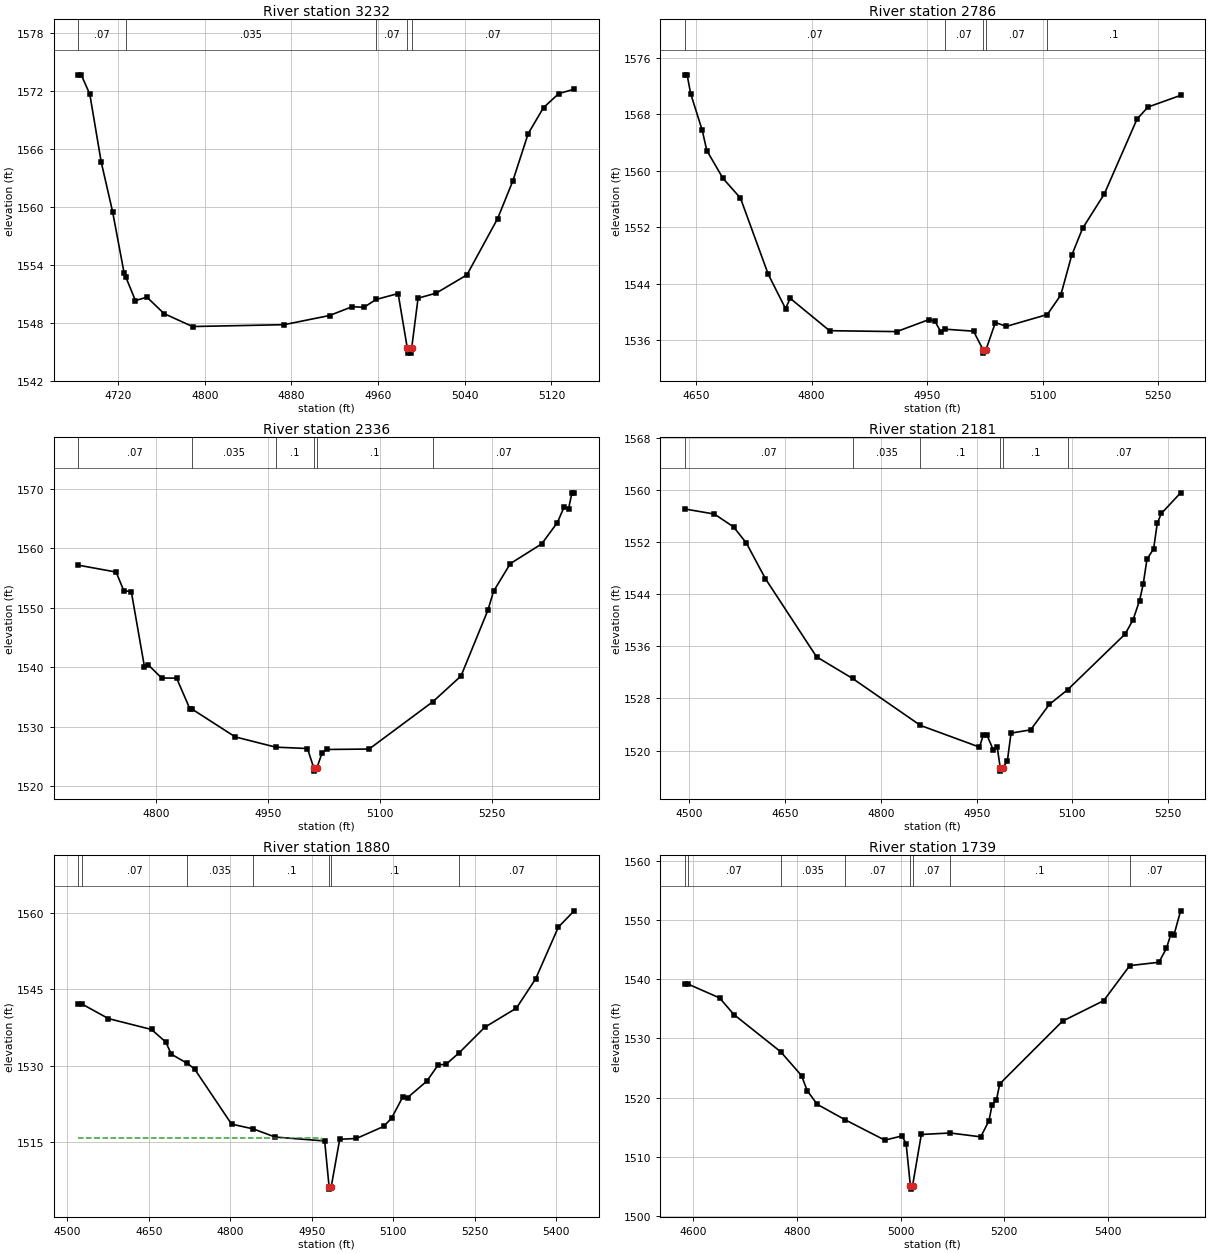
Type RM Length L Ch R = 1 ,3232    ,446,446,446
BEGIN DESCRIPTION:
Stream0429 6.0
END DESCRIPTION:
XS GIS Cut Line= 3
      1977524.99     13877024.97        1977625.       13877325.
      1977725.02     13877425.02
#Sta/Elev= 30
  4683.3 1573.63    4686 1573.63  4693.9 1571.62  4704.4 1564.62  4714.9 1559.49
  4725.5 1553.17  4727.2  1552.7    4736 1550.28  4746.6 1550.64  4762.4 1548.94
  4788.7  1547.6  4873.1 1547.79  4915.2 1548.74  4936.3 1549.66  4946.8 1549.58
  4958.2  1550.4  4978.5 1551.01    4987 1545.35  4987.3 1544.85  4990.8 1544.85
    4991 1545.35  4996.9 1550.53  5013.7 1551.06    5042 1552.94  5070.3 1558.75
  5084.4 1562.66  5098.5 1567.53  5112.7 1570.24  5126.8 1571.69    5141 1572.14
#Mann= 5 ,-1 , 0
  4683.3     .07       0  4727.2    .035       0  4958.2     .07       0
    4987     .05       0    4991     .07       0
Bank Sta=4987,4991
XS Rating Curve= 0 ,0
Exp/Cntr=0.3,0.1

Type RM Length L Ch R = 1 ,2786    ,450,450,450
BEGIN DESCRIPTION:
Stream0429 5.0
END DESCRIPTION:
XS GIS Cut Line= 3
      1977024.98     13877074.96        1977225.       13877375.
      1977424.97     13877574.97
#Sta/Elev= 30
  4635.5 1573.58  4638.5 1573.58  4643.1 1570.92  4658.1 1565.72  4664.1 1562.84
  4685.1  1558.9  4707.7 1556.12  4743.7 1545.33  4766.2 1540.45  4772.3  1541.9
  4823.3 1537.32  4910.5 1537.19  4952.5  1538.9    4960 1538.68  4967.6 1537.18
  4973.6 1537.53  5010.2 1537.25  5022.4 1534.64  5022.6 1534.14  5026.4 1534.64
  5038.5 1538.48  5052.7 1537.93  5105.9 1539.61  5123.4 1542.37  5137.5 1547.98
  5151.7 1551.83  5179.9  1556.7  5222.4 1567.33  5236.5 1569.01  5278.9 1570.67
#Mann= 5 ,-1 , 0
  4635.5     .07       0  4973.6     .07       0  5022.4     .05       0
  5026.4     .07       0  5105.9      .1       0
Bank Sta=5022.4,5026.4
XS Rating Curve= 0 ,0
Exp/Cntr=0.3,0.1

Type RM Length L Ch R = 1 ,2336    ,155,155,155
BEGIN DESCRIPTION:
Stream0429 4.0
END DESCRIPTION:
XS GIS Cut Line= 3
      1976824.99     13877324.96        1976875.       13877625.
      1977074.98     13877924.97
#Sta/Elev= 30
  4695.8 1557.14  4746.5 1555.98  4756.7 1552.85  4766.8  1552.7  4784.5 1540.01
  4789.6 1540.38  4807.4 1538.18  4827.6 1538.14  4845.4 1532.97  4847.9 1532.97
  4906.2 1528.27  4960.4 1526.55    5003 1526.32  5011.5 1523.02  5011.7 1522.52
  5015.5 1523.02  5022.5 1525.58  5028.5 1526.16  5085.6 1526.23  5171.3 1534.21
  5208.8 1538.51  5244.9 1549.58  5252.4 1552.74  5274.9  1557.4    5317 1560.72
    5338  1564.3    5347 1566.91    5353 1566.61  5357.5  1569.3  5360.5  1569.3
#Mann= 6 ,-1 , 0
  4695.8     .07       0  4847.9    .035       0  4960.4      .1       0
  5011.5     .05       0  5015.5      .1       0  5171.3     .07       0
Bank Sta=5011.5,5015.5
XS Rating Curve= 0 ,0
Exp/Cntr=0.3,0.1

Type RM Length L Ch R = 1 ,2181    ,301,301,301
BEGIN DESCRIPTION:
Mapping XS e40c0186
END DESCRIPTION:
XS GIS Cut Line= 3
      1976697.11     13877228.79      1976715.95     13877644.97
      1976887.84     13877961.51
#Sta/Elev= 30
  4492.7 1557.11    4539 1556.33    4569 1554.36    4589  1551.9    4619  1546.4
  4699.1  1534.4  4755.6 1531.07  4861.9 1523.86  4954.4 1520.53  4960.1 1522.33
  4966.2 1522.35  4976.3 1520.02    4982 1520.59    4987 1517.34  4987.2 1516.84
    4991 1517.34  4998.1 1518.45  5003.8 1522.68  5034.5 1523.18  5063.7 1527.08
  5092.7 1529.36  5182.4 1537.88  5194.9 1540.07  5205.2 1543.05    5211 1545.61
  5216.7 1549.37  5227.2 1550.99  5232.9 1554.92  5239.3 1556.42  5269.5 1559.59
#Mann= 6 ,-1 , 0
  4492.7     .07       0  4755.6    .035       0  4861.9      .1       0
    4987     .05       0    4991      .1       0  5092.7     .07       0
Bank Sta=4987,4991
XS Rating Curve= 0 ,0
Exp/Cntr=0.3,0.1

Type RM Length L Ch R = 1 ,1880    ,141,141,141
BEGIN DESCRIPTION:
Stream0429 3.0
END DESCRIPTION:
XS GIS Cut Line= 3
      1976412.85     13877295.28        1976475.       13877775.
      1976820.58     13878029.31
#Sta/Elev= 30
  4520.3 1542.18  4526.8  1542.1  4575.7 1539.23    4655 1537.09  4681.4 1534.61
  4691.4 1532.24  4721.1 1530.42  4734.2 1529.34  4802.4  1518.5  4842.7 1517.55
  4882.6 1515.96  4973.8 1515.19  4981.9 1506.23  4982.1 1505.73  4985.9 1506.23
  5001.5 1515.52  5032.2 1515.68  5082.3 1518.04    5097 1519.68  5117.8 1523.89
  5126.3  1523.7  5161.8 1526.93  5182.6 1530.12  5197.3 1530.26  5221.5 1532.52
  5268.3 1537.51  5326.8 1541.29  5362.3 1547.06    5404  1557.2  5433.1  1560.4
#Mann= 7 ,-1 , 0
  4520.3      .1       0  4526.8     .07       0  4721.1    .035       0
  4842.7      .1       0  4981.9     .05       0  4985.9      .1       0
  5221.5     .07       0
#XS Ineff= 2 , 0
         4967.03 1515.79
Permanent Ineff=
       F       F
Bank Sta=4981.9,4985.9
XS Rating Curve= 0 ,0
Exp/Cntr=0.3,0.1

Type RM Length L Ch R = 1 ,1739    ,304,304,304
BEGIN DESCRIPTION:
Mapping XS 53d4a874
END DESCRIPTION:
XS GIS Cut Line= 4
      1976363.87     13877310.49      1976341.28      13877687.4
      1976387.16     13877882.65      1976690.14     13878107.57
#Sta/Elev= 30
  4584.2 1539.26  4589.9 1539.21  4651.3 1536.84  4678.9 1534.03  4768.9 1527.75
  4809.1 1523.72  4820.1 1521.17  4839.2 1518.87  4892.8 1516.26  4969.6  1512.8
  5002.7 1513.51  5010.7 1512.21    5019 1505.02  5019.2 1504.52    5023 1505.02
    5040 1513.76  5095.8 1514.01  5154.5 1513.36  5170.3 1516.07  5176.5  1518.8
  5184.6 1519.52  5191.1 1522.31  5312.1 1532.92  5391.4 1536.38  5441.7 1542.31
  5497.8 1542.87  5512.4 1545.22  5520.8 1547.61    5527 1547.53  5539.7 1551.57
#Mann= 8 ,-1 , 0
  4584.2      .1       0  4589.9     .07       0  4768.9    .035       0
  4892.8     .07       0    5019     .05       0    5023     .07       0
  5095.8      .1       0  5441.7     .07       0
#XS Ineff= 2 , 0
          4998.2 1513.41
Permanent Ineff=
       F       F
Bank Sta=5019,5023
XS Rating Curve= 0 ,0
Exp/Cntr=0.3,0.1

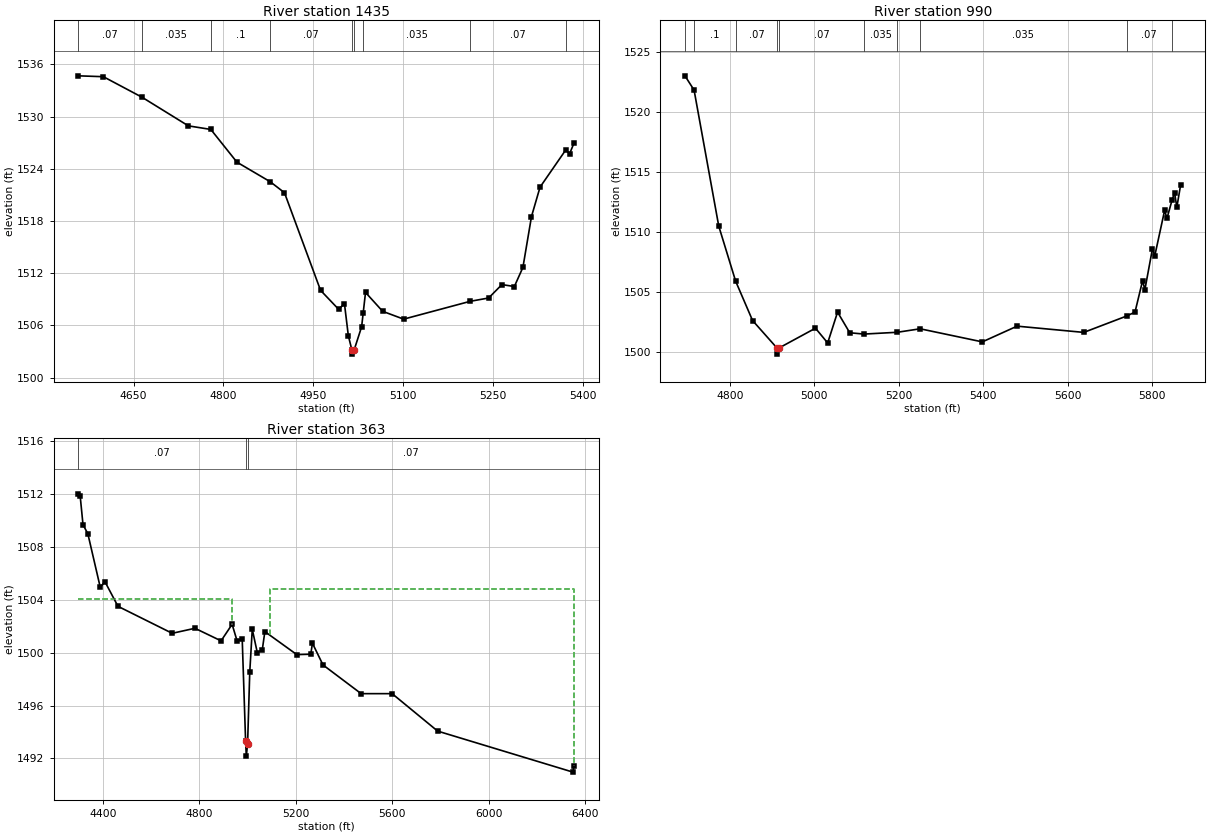
Type RM Length L Ch R = 1 ,1435    ,445,445,445
BEGIN DESCRIPTION:
Stream0429 2.0
END DESCRIPTION:
XS GIS Cut Line= 3
      1976148.01     13877393.78        1976075.       13877825.
      1976375.02     13878075.02
#Sta/Elev= 30
  4557.8 1534.69  4599.6 1534.59  4664.2 1532.23  4741.6 1528.94  4779.1 1528.53
  4822.7 1524.77  4878.3 1522.52  4902.1 1521.26  4962.4 1510.04  4992.6 1507.86
  5002.3 1508.51  5008.8 1504.82  5014.6 1503.21  5014.9 1502.71  5018.6 1503.21
    5031 1505.86  5033.6 1507.44  5037.5  1509.8  5066.1 1507.63  5101.2 1506.73
  5212.4 1508.78  5243.1 1509.16  5265.3  1510.7  5286.1 1510.48  5300.4 1512.68
  5314.7 1518.52    5329  1521.9  5371.7 1526.15  5378.5 1525.76  5385.7 1526.96
#Mann= 9 ,-1 , 0
  4557.8     .07       0  4664.2    .035       0  4779.1      .1       0
  4878.3     .07       0  5014.6     .05       0  5018.6     .07       0
  5033.6    .035       0  5212.4     .07       0  5371.7      .1       0
Bank Sta=5014.6,5018.6
XS Rating Curve= 0 ,0
Exp/Cntr=0.3,0.1

Type RM Length L Ch R = 1 ,990     ,627,627,627
BEGIN DESCRIPTION:
Stream0429 1.0
END DESCRIPTION:
XS GIS Cut Line= 3
        1975675.     13877675.02        1975675.       13877975.
      1976475.01       13878325.
#Sta/Elev= 30
  4693.9 1523.04  4715.5 1521.85  4773.9 1510.52  4813.8 1505.94  4853.9 1502.66
  4911.9 1500.36  4912.1 1499.86  4915.9 1500.36  5002.8 1502.02  5031.7 1500.79
  5055.1 1503.36  5083.9 1501.64  5117.4 1501.53  5196.5 1501.68  5250.5 1501.97
  5397.7 1500.88    5480 1502.19  5637.9 1501.67  5739.1 1503.03  5759.1 1503.36
    5777 1505.97  5782.5 1505.23  5800.4 1508.64  5805.9 1508.05  5829.3 1511.85
  5834.7 1511.16  5846.7 1512.68  5852.7 1513.31  5858.1 1512.09  5867.1 1513.96
#Mann= 10 ,-1 , 0
  4693.9    .035       0  4715.5      .1       0  4813.8     .07       0
  4911.9     .05       0  4915.9     .07       0  5117.4    .035       0
  5196.5     .07       0  5250.5    .035       0  5739.1     .07       0
  5846.7      .1       0
Bank Sta=4911.9,4915.9
XS Rating Curve= 0 ,0
Exp/Cntr=0.3,0.1

Type RM Length L Ch R = 1 ,363     ,0,0,0
BEGIN DESCRIPTION:
Stream0429 0.0
END DESCRIPTION:
XS GIS Cut Line= 5
      1975161.44     13877525.82      1975088.63     13878074.13
      1975193.58     13878425.69      1975572.01     13878687.53
       1976208.1      13878911.6
#Sta/Elev= 30
  4298.4    1512    4306 1511.85  4317.8 1509.67  4337.9 1508.98  4389.4 1504.93
  4408.5 1505.37  4462.7  1503.5  4687.6 1501.46  4781.8 1501.84  4890.1 1500.89
  4935.9 1502.14  4956.4 1500.89  4977.7 1501.04 4991.76 1493.32  4994.7 1492.18
    5000  1493.1    5009 1498.53  5019.4 1501.76  5040.3    1500    5061 1500.22
  5071.6 1501.59    5204 1499.85  5261.9 1499.88  5268.8 1500.71  5312.6 1499.07
  5470.7  1496.9  5599.1  1496.9  5787.8 1494.07  6348.8 1490.97    6353 1491.47
#Mann= 3 ,-1 , 0
  4298.4     .07       0 4991.76     .05       0    5000     .07       0
#XS Ineff= 2 , 0
         4936.56 1504.02 5093.91         1504.82
Permanent Ineff=
       F       F
#Block Obstruct= 2 , 0
                         5268.73         1500.53
Bank Sta=4991.76,5000
XS Rating Curve= 0 ,0
Exp/Cntr=0.3,0.1

Chan Stop Cuts=-1
Use User Specified Reach Order=0
Composite Channel Slope=5