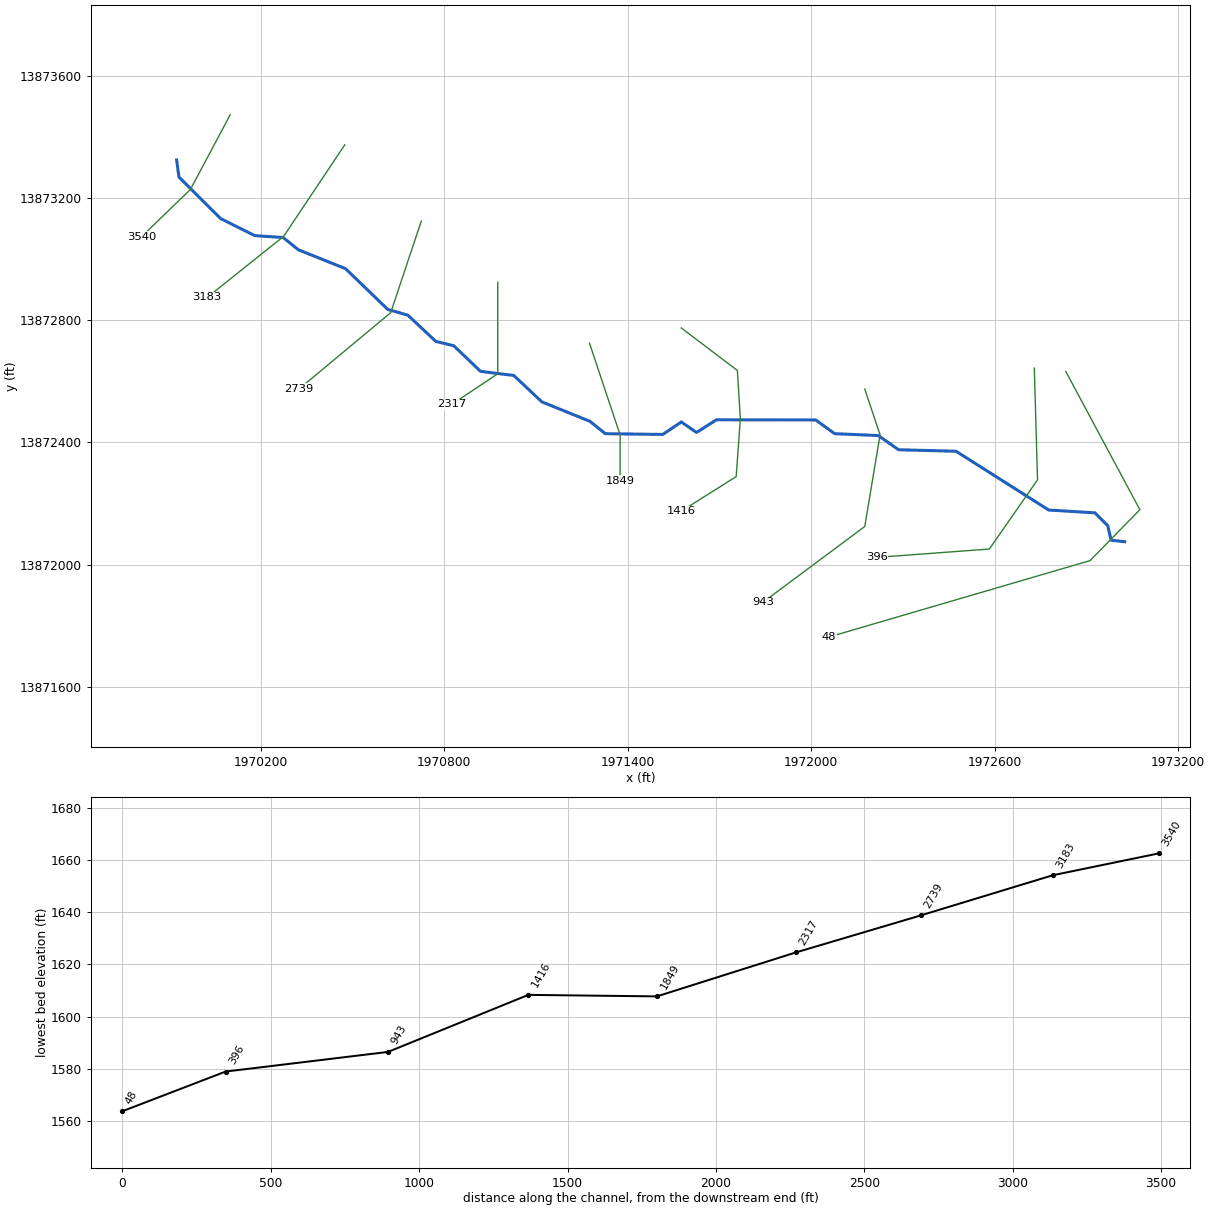
--- Stream0430.prj (project) ---

Proj Title=Stream0430 Base Level Engineering
Current Plan=p01
Default Exp/Contr=0.3,0.1
English Units
Geom File=g01
Flow File=f01
Plan File=p01
BEGIN DESCRIPTION:
Stream0430
END DESCRIPTION:

--- Stream0430.p01 (plan) ---

Plan Title=Multiple Run
Short Identifier=Multiple
Geom File=g01
Flow File=f01
Subcritical Flow
K Sum by GR= 0
Std Step Tol= 0.01
Critical Tol= 0.01
Num of Std Step Trials= 20
Max Error Tol= 0.3
Flow Tol Ratio= 0.001
Split Flow NTrial= 30
Split Flow Tol= 0.02
Split Flow Ratio= 0.02
Log Output Level= 0
Friction Slope Method= 1
Unsteady Friction Slope Method= 2
Unsteady Bridges Friction Slope Method= 1
Parabolic Critical Depth
Global Vel Dist=  1 , 1 , 1
Global Log Level= 0
CheckData=True
Encroach Param= -1, 0, 0, 0
BEGIN DESCRIPTION:
Multiple Run
END DESCRIPTION:

--- Stream0430.f01 (steady flow) ---

Flow Title=Multiple
Number of Profiles=7
Profile Names=10-year,25-year,50-year,1pct_min,100-year,1pct_plu,500-year
River Rch & RM= Stream0430,Reach-1,3540
     173     261     336     213     424     847     662
River Rch & RM= Stream0430,Reach-1,3183
     504     824    1119     741    1478    2948    2541
River Rch & RM= Stream0430,Reach-1,48
    1874    3301    4708    3249    6483   12936   12179
Boundary for River Rch & Prof#=Stream0430,Reach-1,1
Up Type=0
Dn Type=3
Dn Slope=0.005
Boundary for River Rch & Prof#=Stream0430,Reach-1,2
Up Type=0
Dn Type=3
Dn Slope=0.005
Boundary for River Rch & Prof#=Stream0430,Reach-1,3
Up Type=0
Dn Type=3
Dn Slope=0.005
Boundary for River Rch & Prof#=Stream0430,Reach-1,4
Up Type=0
Dn Type=3
Dn Slope=0.005
Boundary for River Rch & Prof#=Stream0430,Reach-1,5
Up Type=0
Dn Type=3
Dn Slope=0.005
Boundary for River Rch & Prof#=Stream0430,Reach-1,6
Up Type=0
Dn Type=3
Dn Slope=0.005
Boundary for River Rch & Prof#=Stream0430,Reach-1,7
Up Type=0
Dn Type=3
Dn Slope=0.005

--- Stream0430.g01 (geometry) ---

Geom Title=Existing Conditions

River Reach=Stream0430,Reach-1
Reach XY= 30
      1969925.00     13873325.00      1969932.76     13873268.79
      1970068.94     13873133.14      1970180.97     13873077.33
      1970273.42     13873071.17      1970322.82     13873031.12
      1970477.30     13872969.17      1970615.32     13872835.78
      1970681.04     13872816.82      1970772.72     13872730.87
      1970831.04     13872716.82      1970918.84     13872632.88
      1971027.42     13872619.46      1971118.95     13872533.16
      1971277.18     13872468.88      1971326.55     13872428.75
      1971514.57     13872426.37      1971575.10     13872467.21
      1971624.90     13872432.79      1971690.16     13872474.35
      1972014.50     13872473.78      1972076.57     13872428.79
      1972219.06     13872422.73      1972285.51     13872376.22
      1972473.45     13872371.25      1972776.56     13872178.76
      1972927.69     13872169.63      1972969.42     13872127.46
      1972980.35     13872079.96      1973025.00     13872075.00

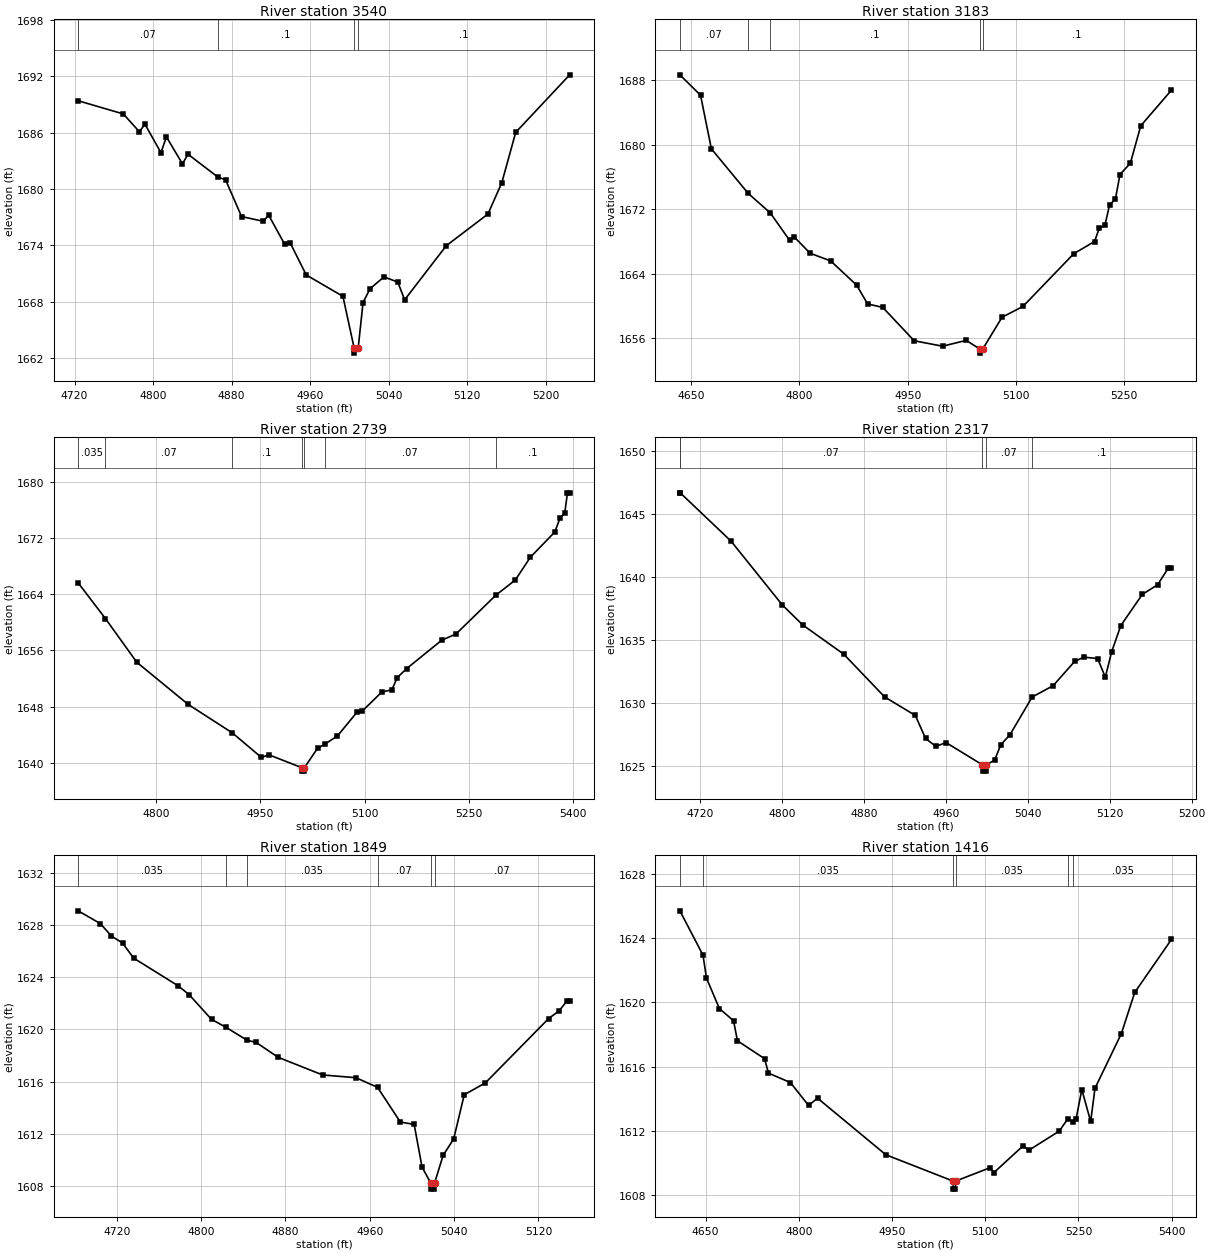
Type RM Length L Ch R = 1,3540,357,357,357
BEGIN DESCRIPTION:
Stream0430 7.0
END DESCRIPTION:
XS GIS Cut Line= 3
      1970100.28     13873473.25      1969970.06     13873228.43
      1969809.30     13873072.86
#Sta/Elev= 30
  4723.6 1689.41  4769.7 1688.00  4786.0 1686.11  4791.7 1686.91  4808.0 1683.88
  4813.6 1685.56  4829.9 1682.69  4835.6 1683.71  4866.0 1681.28  4873.9 1680.98
  4890.2 1677.07  4912.2 1676.57  4917.8 1677.22  4934.1 1674.12  4939.8 1674.25
  4956.1 1670.85  4993.5 1668.57  5005.0 1663.02  5005.2 1662.52  5009.0 1663.02
  5014.0 1667.91  5021.1 1669.38  5035.3 1670.64  5049.4 1670.09  5056.4 1668.20
  5098.8 1673.96  5141.3 1677.34  5155.4 1680.67  5169.6 1686.04  5224.6 1692.17
#Mann=4,-1,0
  4723.6    0.07       0  4866.0     0.1       0  5005.0    0.05       0
  5009.0     0.1       0
Bank Sta=5005,5009
Exp/Cntr=0.3,0.1

Type RM Length L Ch R = 1,3183,444,444,444
BEGIN DESCRIPTION:
Stream0430 6.0
END DESCRIPTION:
XS GIS Cut Line= 3
      1970475.02     13873375.04      1970275.00     13873075.00
      1970024.97     13872874.97
#Sta/Elev= 30
  4634.5 1688.64  4663.1 1686.11  4678.1 1679.47  4729.1 1673.95  4759.5 1671.55
  4786.3 1668.16  4792.3 1668.60  4814.8 1666.54  4843.4 1665.58  4879.4 1662.57
  4894.4 1660.26  4915.5 1659.82  4959.0 1655.69  4998.3 1655.02  5031.1 1655.74
  5049.9 1654.66  5050.2 1654.16  5053.9 1654.66  5080.7 1658.61  5109.6 1659.94
  5180.0 1666.48  5208.8 1667.99  5215.2 1669.61  5223.2 1670.02  5229.6 1672.53
  5237.6 1673.22  5244.0 1676.29  5258.4 1677.69  5272.8 1682.33  5315.3 1686.74
#Mann=5,-1,0
  4634.5    0.07       0  4729.1   0.035       0  4759.5     0.1       0
  5049.9    0.05       0  5053.9     0.1       0
Bank Sta=5049.9,5053.9
Exp/Cntr=0.3,0.1

Type RM Length L Ch R = 1,2739,422,422,422
BEGIN DESCRIPTION:
Stream0430 5.0
END DESCRIPTION:
XS GIS Cut Line= 3
      1970725.00     13873125.00      1970625.00     13872825.00
      1970325.03     13872575.03
#Sta/Elev= 30
  4688.1 1665.63  4727.4 1660.53  4772.4 1654.32  4846.2 1648.32  4909.9 1644.25
  4951.6 1640.76  4962.2 1641.14  5009.5 1639.31  5009.7 1638.81  5013.2 1638.81
  5013.5 1639.31  5032.3 1642.06  5042.5 1642.63  5061.0 1643.83  5089.6 1647.27
  5096.1 1647.31  5124.7 1650.08  5139.1 1650.38  5146.9 1652.13  5160.5 1653.42
  5210.7 1657.44  5231.5 1658.35  5288.5 1663.85  5316.7 1666.03  5338.2 1669.26
  5373.4 1672.86  5381.2 1674.91  5387.7 1675.54  5391.6 1678.44  5394.8 1678.44
#Mann=7,-1,0
  4688.1   0.035       0  4727.4    0.07       0  4909.9     0.1       0
  5009.5    0.05       0  5013.5     0.1       0  5042.5    0.07       0
  5288.5     0.1       0
Bank Sta=5009.5,5013.5
Exp/Cntr=0.3,0.1

Type RM Length L Ch R = 1,2317,468,468,468
BEGIN DESCRIPTION:
Stream0430 4.0
END DESCRIPTION:
XS GIS Cut Line= 3
      1970975.00     13872924.97      1970975.00     13872625.00
      1970825.04     13872525.03
#Sta/Elev= 30
  4700.0 1646.65  4700.3 1646.65  4750.0 1642.82  4800.0 1637.77  4820.0 1636.18
  4860.0 1633.87  4900.0 1630.48  4930.0 1629.01  4940.0 1627.19  4950.0 1626.56
  4960.0 1626.86  4995.5 1625.10  4995.7 1624.60  4999.2 1624.60  4999.5 1625.10
  5007.5 1625.48  5013.5 1626.69  5022.5 1627.49  5044.1 1630.47  5064.6 1631.37
  5085.6 1633.29  5094.6 1633.63  5108.1 1633.52  5115.6 1632.04  5121.7 1634.04
  5130.7 1636.13  5151.7 1638.60  5166.7 1639.37  5177.2 1640.70  5180.2 1640.70
#Mann=5,-1,0
  4700.0   0.035       0  4700.3    0.07       0  4995.5    0.05       0
  4999.5    0.07       0  5044.1     0.1       0
Bank Sta=4995.5,4999.5
Exp/Cntr=0.3,0.1

Type RM Length L Ch R = 1,1849,433,433,433
BEGIN DESCRIPTION:
Stream0430 3.0
END DESCRIPTION:
XS GIS Cut Line= 3
      1971275.01     13872724.96      1971375.00     13872425.00
      1971375.00     13872274.99
#Sta/Elev= 30
  4683.4 1629.07  4704.4 1628.10  4715.0 1627.14  4725.5 1626.61  4736.1 1625.45
  4778.2 1623.34  4788.8 1622.65  4809.9 1620.77  4823.5 1620.17  4843.7 1619.17
  4852.0 1619.02  4873.1 1617.87  4915.3 1616.52  4946.9 1616.31  4967.4 1615.57
  4989.0 1612.92  5002.1 1612.74  5009.6 1609.47  5017.6 1608.29  5017.8 1607.79
  5021.3 1607.79  5021.6 1608.29  5029.6 1610.38  5039.6 1611.63  5049.6 1615.01
  5069.6 1615.91  5129.6 1620.83  5139.6 1621.43  5147.1 1622.18  5149.6 1622.18
#Mann=6,-1,0
  4683.4   0.035       0  4823.5    0.07       0  4843.7   0.035       0
  4967.4    0.07       0  5017.6    0.05       0  5021.6    0.07       0
Bank Sta=5017.6,5021.6
Exp/Cntr=0.3,0.1

Type RM Length L Ch R = 1,1416,473,473,473
BEGIN DESCRIPTION:
Stream0430 2.0
END DESCRIPTION:
XS GIS Cut Line= 5
      1971575.00     13872775.00      1971758.44     13872635.89
      1971768.20     13872477.95      1971754.53     13872288.23
      1971575.03     13872175.02
#Sta/Elev= 30
  4608.7 1625.69  4645.9 1622.93  4651.4 1621.51  4672.2 1619.61  4695.0 1618.85
  4701.3 1617.60  4744.9 1616.49  4751.2 1615.59  4786.6 1615.00  4815.7 1613.58
  4830.2 1614.03  4940.0 1610.51  5048.3 1608.87  5048.5 1608.37  5052.0 1608.37
  5052.3 1608.87  5108.3 1609.71  5113.4 1609.38  5160.5 1611.05  5170.6 1610.80
  5219.0 1611.98  5232.6 1612.73  5241.9 1612.57  5246.1 1612.73  5255.4 1614.57
  5269.6 1612.58  5276.6 1614.65  5319.0 1618.05  5340.5 1620.61  5399.6 1623.91
#Mann=6,-1,0
  4608.7    0.07       0  4645.9   0.035       0  5048.3   0.035       0
  5052.3   0.035       0  5232.6    0.07       0  5241.9   0.035       0
Bank Sta=5048.3,5052.3
Exp/Cntr=0.3,0.1

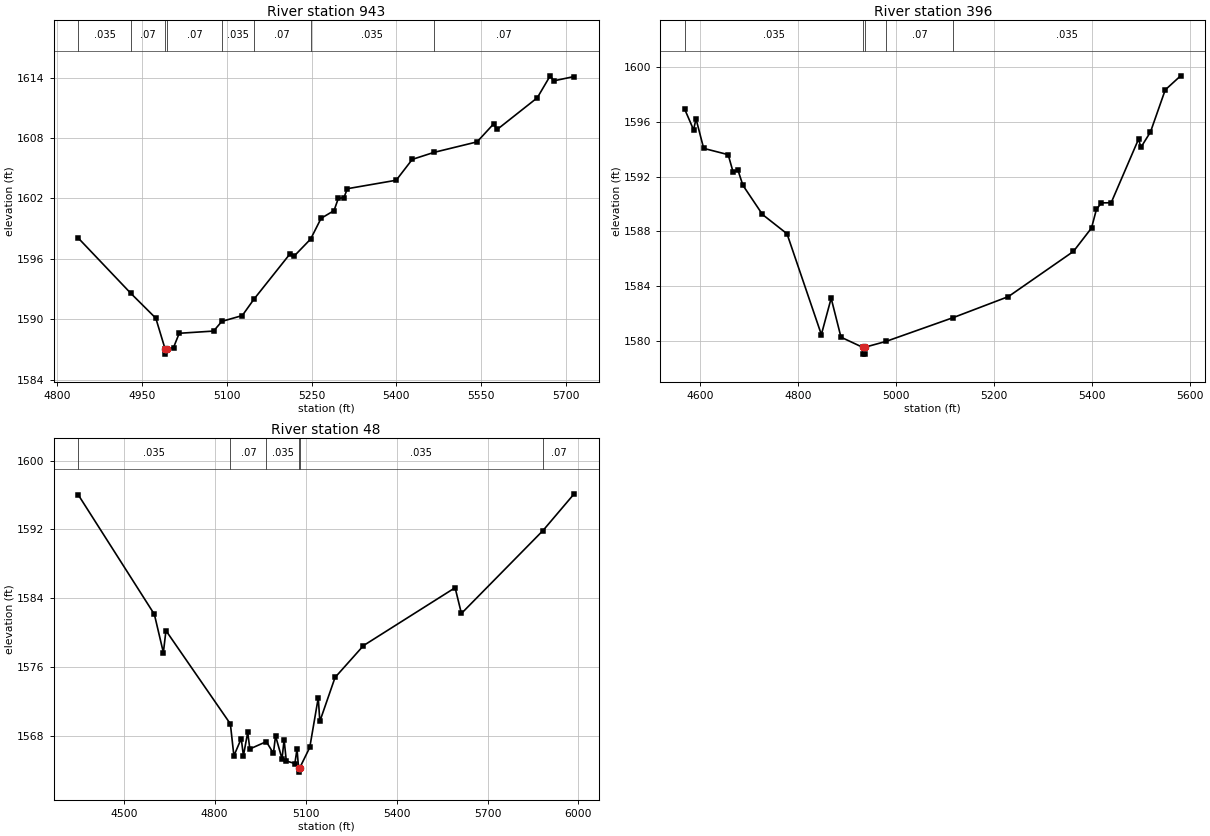
Type RM Length L Ch R = 1,943,547,547,547
BEGIN DESCRIPTION:
Stream0430 1.0
END DESCRIPTION:
XS GIS Cut Line= 4
      1972175.00     13872575.00      1972225.00     13872425.00
      1972175.00     13872125.00      1971842.72     13871877.13
#Sta/Elev= 30
  4837.6 1598.05  4930.4 1592.57  4974.6 1590.10  4991.1 1587.03  4991.3 1586.53
  4995.1 1587.03  5005.9 1587.18  5016.0 1588.60  5076.8 1588.82  5091.3 1589.78
  5127.5 1590.36  5148.2 1591.99  5211.1 1596.43  5218.8 1596.24  5248.4 1597.96
  5266.9 1600.02  5289.7 1600.78  5297.3 1601.99  5307.2 1602.07  5313.4 1602.96
  5399.7 1603.80  5428.1 1605.87  5466.1 1606.56  5542.7 1607.61  5571.9 1609.39
  5578.2 1608.84  5649.2 1611.99  5672.0 1614.17  5678.3 1613.67  5714.4 1614.10
#Mann=8,-1,0
  4837.6   0.035       0  4930.4    0.07       0  4991.1    0.05       0
  4995.1    0.07       0  5091.3   0.035       0  5148.2    0.07       0
  5248.4   0.035       0  5466.1    0.07       0
Bank Sta=4991.1,4995.1
Exp/Cntr=0.3,0.1

Type RM Length L Ch R = 1,396,348,348,348
BEGIN DESCRIPTION:
Stream0430 T
END DESCRIPTION:
XS GIS Cut Line= 4
      1972729.36     13872643.46      1972739.78     13872277.60
      1972582.23     13872051.04      1972213.70     13872023.69
#Sta/Elev= 30
  4569.5 1596.93  4587.4 1595.44  4592.4 1596.24  4608.0 1594.08  4658.0 1593.62
  4668.0 1592.35  4678.0 1592.48  4688.0 1591.38  4728.0 1589.24  4778.0 1587.83
  4848.1 1580.45  4868.1 1583.11  4888.1 1580.26  4932.3 1579.52  4932.6 1579.02
  4936.1 1579.02  4936.3 1579.52  4979.9 1579.95  5117.6 1581.70  5229.6 1583.23
  5362.4 1586.54  5399.2 1588.25  5409.2 1589.61  5419.3 1590.09  5439.3 1590.10
  5495.1 1594.75  5500.1 1594.16  5519.5 1595.28  5549.6 1598.36  5581.0 1599.39
#Mann=5,-1,0
  4569.5   0.035       0  4932.3    0.05       0  4936.3   0.035       0
  4979.9    0.07       0  5117.6   0.035       0
Bank Sta=4932.3,4936.3
Exp/Cntr=0.3,0.1

Type RM Length L Ch R = 1,48,0,0,0
BEGIN DESCRIPTION:
Stream0430 8.0
END DESCRIPTION:
XS GIS Cut Line= 4
      1972832.30     13872632.35      1973074.41     13872179.95
      1972911.65     13872013.28      1972058.14     13871763.10
#Sta/Elev= 30
  4350.3 1596.01  4601.1 1582.15  4630.8 1577.71  4639.3 1580.26  4851.8 1569.43
  4863.4 1565.72  4887.7 1567.73  4894.8 1565.73  4909.0 1568.45  4916.0 1566.52
  4970.4 1567.37  4993.8 1566.01  5000.8 1568.04  5022.1 1565.37  5029.1 1567.59
  5036.3 1565.12  5064.6 1564.83  5071.6 1566.53  5076.7 1564.33  5077.0 1563.83
  5080.7 1564.33  5113.7 1566.70  5141.7 1572.46  5146.9 1569.72  5197.1 1574.82
  5290.9 1578.52  5593.1 1585.24  5613.9 1582.25  5882.8 1591.87  5985.8 1596.14
#Mann=6,-1,0
  4350.3   0.035       0  4851.8    0.07       0  4970.4   0.035       0
  5076.7   0.035       0  5080.7   0.035       0  5882.8    0.07       0
Bank Sta=5076.7,5080.7
Exp/Cntr=0.3,0.1

Chan Stop Cuts=-1