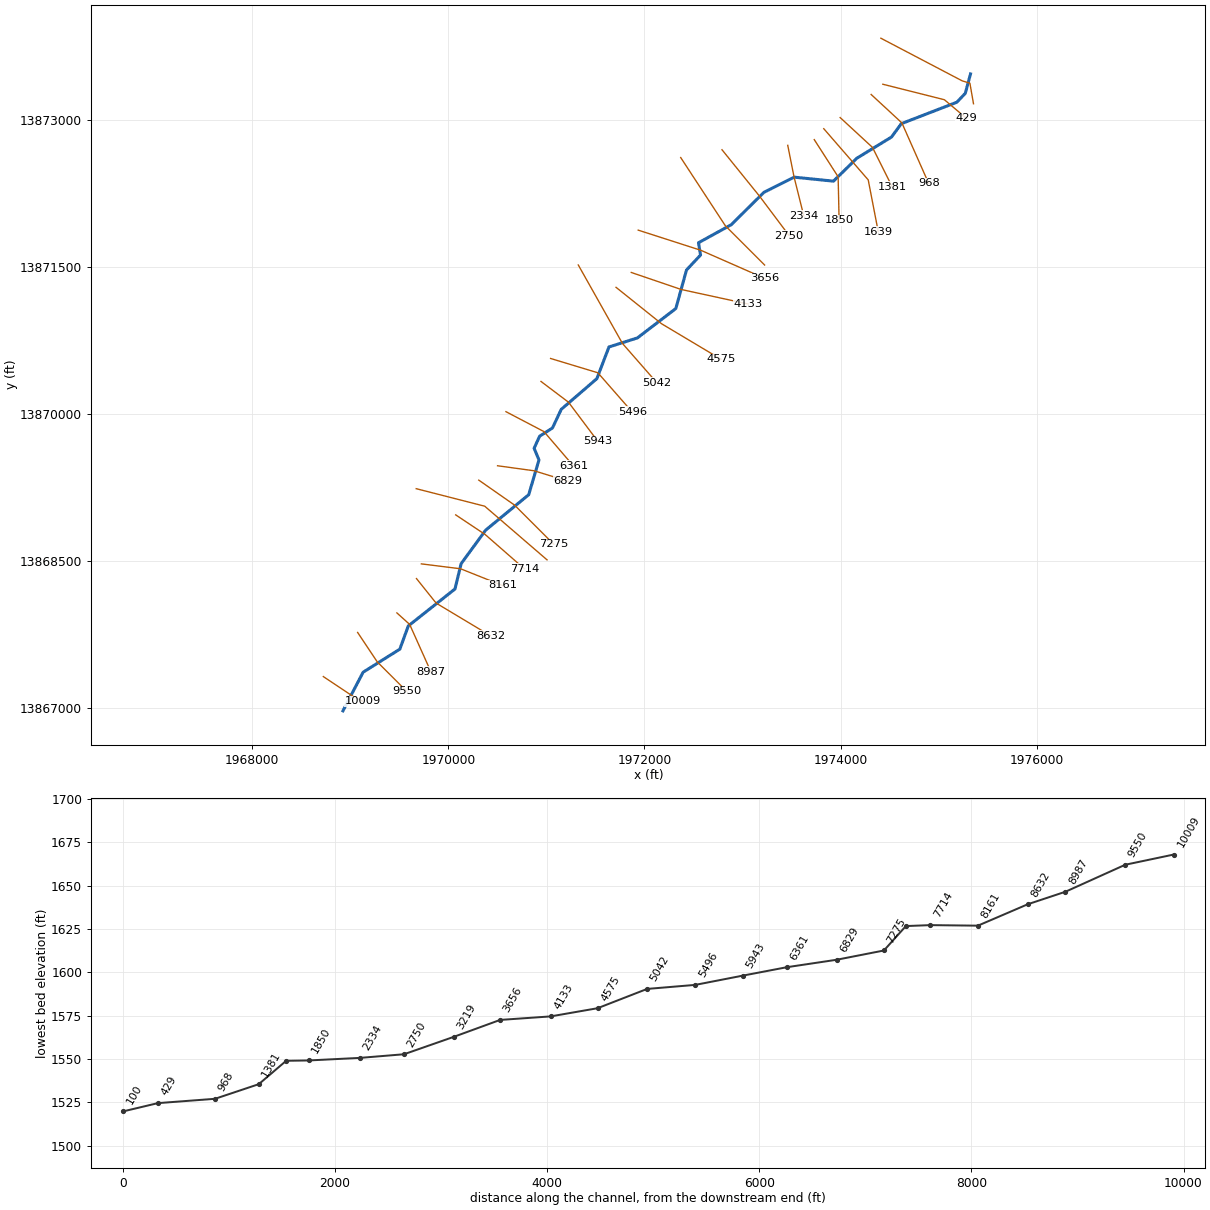
--- Stream0447.prj (project) ---

Proj Title=Stream0447 Base Level Engineering
Current Plan=p01
Default Exp/Contr=0.3,0.1
English Units
Geom File=g01
Flow File=f01
Plan File=p01
Y Axis Title=Elevation
X Axis Title(PF)=Main Channel Distance
X Axis Title(XS)=Station
BEGIN DESCRIPTION:
Stream0447
END DESCRIPTION:
DSS Export Rating Curves= 0
DSS Export Rating Curve Sorted= 0
DSS Export Volume Flow Curves= 0
DXF OffsetX= 0
DXF OffsetY= 0
DXF ScaleX= 1
DXF ScaleY= 10

--- Stream0447.p01 (plan) ---

Plan Title=Multiple Run
Short Identifier=Multiple
Geom File=g01
Flow File=f01
Subcritical Flow
K Sum by GR= 0
Std Step Tol= 0.01
Critical Tol= 0.01
Num of Std Step Trials= 20
Max Error Tol= 0.3
Flow Tol Ratio= 0.001
Split Flow NTrial= 30
Split Flow Tol= 0.02
Split Flow Ratio= 0.02
Log Output Level= 0
Friction Slope Method= 1
Unsteady Friction Slope Method= 2
Unsteady Bridges Friction Slope Method= 1
Parabolic Critical Depth
Global Vel Dist=  1 , 1 , 1
Global Log Level= 0
CheckData=True
Encroach Param= -1, 0, 0, 0
BEGIN DESCRIPTION:
Multiple Run
END DESCRIPTION:

--- Stream0447.f01 (steady flow) ---

Flow Title=Multiple
Number of Profiles=7
Profile Names=10-year,25-year,50-year,1pct_min,100-year,1pct_plu,500-year
River Rch & RM= Stream0447,Reach-1,10009
    1779    3116    4425    3039    6063   12098   11235
River Rch & RM= Stream0447,Reach-1,8632
    1874    3301    4708    3249    6483   12936   12179
River Rch & RM= Stream0447,Reach-1,2334
    2197    3899    5588    3873    7727   15418   14640
Boundary for River Rch & Prof#=Stream0447,Reach-1,1
Up Type=0
Dn Type=3
Dn Slope=0.005
Boundary for River Rch & Prof#=Stream0447,Reach-1,2
Up Type=0
Dn Type=3
Dn Slope=0.005
Boundary for River Rch & Prof#=Stream0447,Reach-1,3
Up Type=0
Dn Type=3
Dn Slope=0.005
Boundary for River Rch & Prof#=Stream0447,Reach-1,4
Up Type=0
Dn Type=3
Dn Slope=0.005
Boundary for River Rch & Prof#=Stream0447,Reach-1,5
Up Type=0
Dn Type=3
Dn Slope=0.005
Boundary for River Rch & Prof#=Stream0447,Reach-1,6
Up Type=0
Dn Type=3
Dn Slope=0.005
Boundary for River Rch & Prof#=Stream0447,Reach-1,7
Up Type=0
Dn Type=3
Dn Slope=0.005

--- Stream0447.g01 (geometry) ---

Geom Title=Existing Conditions
Program Version=4.10

River Reach=Stream0447      ,Reach-1
Reach XY= 30
        1968925.       13866975.      1969130.59     13867369.39
      1969505.24     13867604.87      1969591.46     13867841.75
      1970067.26     13868218.55      1970130.54     13868477.42
      1970380.62     13868819.38      1970819.41     13869180.61
      1970924.23     13869535.69      1970874.71     13869654.82
      1970930.73     13869777.55      1971061.52     13869861.44
      1971151.29     13870051.82      1971514.48     13870365.21
      1971637.97     13870688.48      1971927.42     13870780.54
      1972319.71     13871080.48      1972428.54     13871473.53
      1972571.84     13871626.65       1972550.7     13871751.75
      1972884.68     13871935.77      1973218.94     13872266.86
      1973526.55     13872421.25      1973927.45     13872380.45
      1974165.32     13872614.22      1974519.38     13872830.62
      1974618.93     13872966.87      1975184.81     13873185.51
      1975271.47     13873276.45        1975325.       13873475.

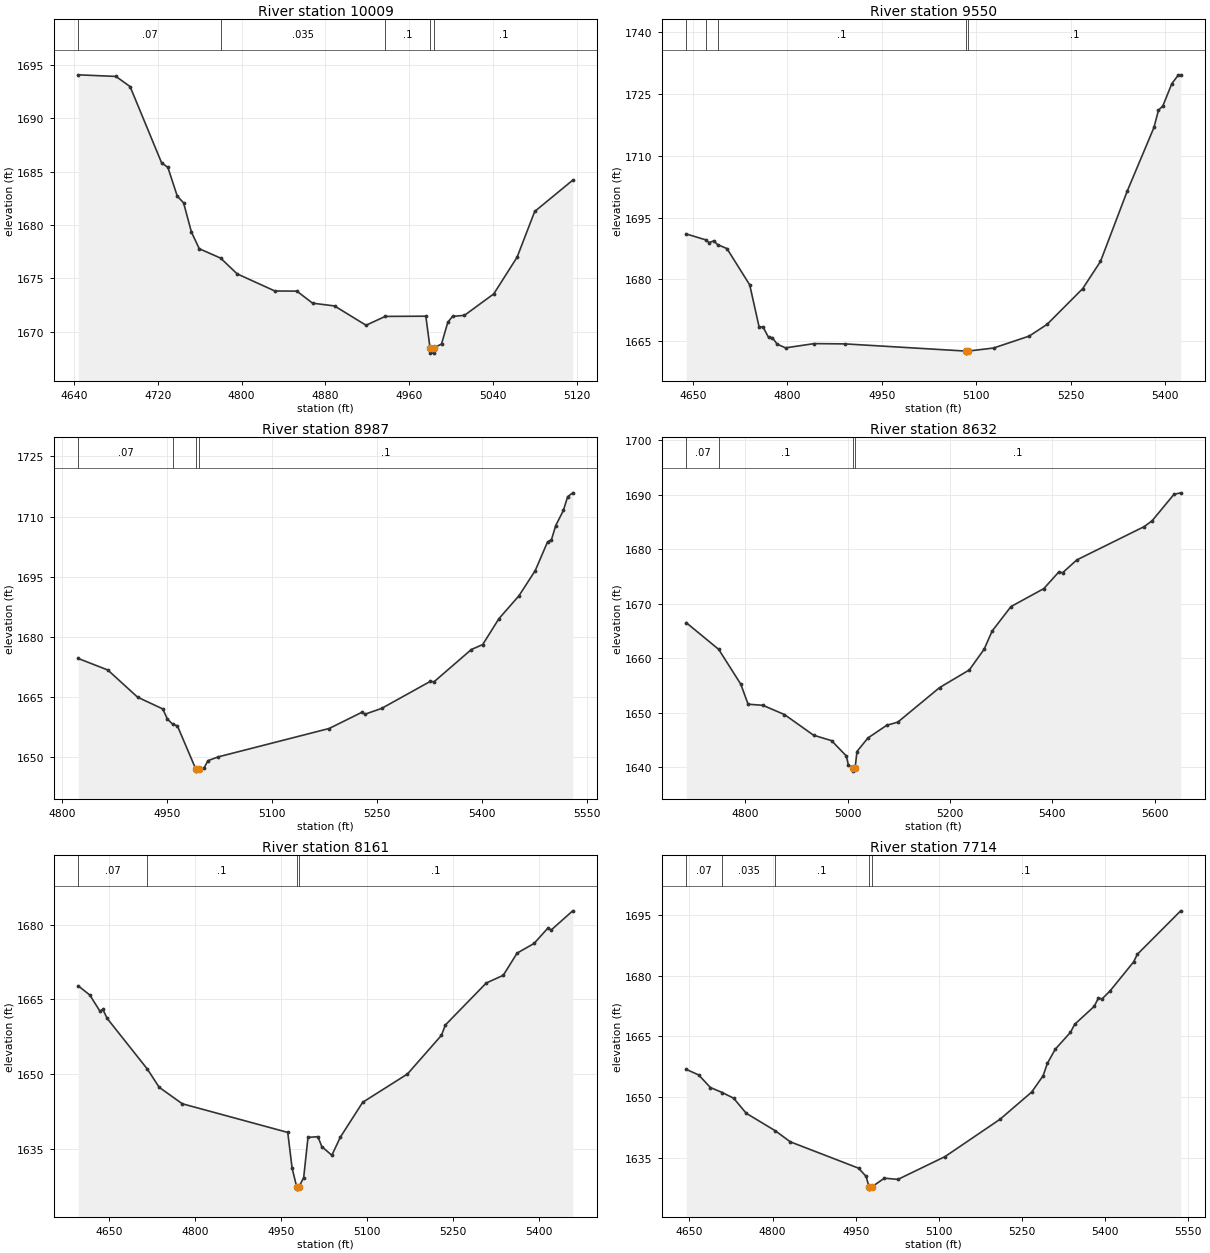
Type RM Length L Ch R = 1 ,10009   ,459,459,459
BEGIN DESCRIPTION:
Stream0447 22.0
END DESCRIPTION:
XS GIS Cut Line= 3
      1968725.03     13867324.98        1969025.       13867125.
      1969124.98     13867075.01
#Sta/Elev= 30
  4643.9 1694.07  4679.9 1693.92  4693.4 1692.97  4723.5 1685.83  4729.5  1685.4
  4738.5  1682.7  4744.5 1682.08    4752 1679.34  4759.5 1677.78  4779.9  1676.9
  4795.6 1675.43  4831.7 1673.82  4852.7 1673.81  4867.7 1672.68  4888.7 1672.42
  4918.8 1670.61  4937.1 1671.44  4975.9 1671.46  4979.9  1668.5  4980.1    1668
  4983.6    1668  4983.9  1668.5  4990.9 1668.86  4996.9 1670.89  5001.4 1671.44
  5012.8 1671.54  5040.8 1673.55  5063.1 1676.99  5079.9 1681.27  5116.2  1684.2
#Mann= 5 ,-1 , 0
  4643.9     .07       0  4779.9    .035       0  4937.1      .1       0
  4979.9     .05       0  4983.9      .1       0
Bank Sta=4979.9,4983.9
XS Rating Curve= 0 ,0
Exp/Cntr=0.3,0.1

Type RM Length L Ch R = 1 ,9550    ,563,563,563
BEGIN DESCRIPTION:
Stream0447 21.0
END DESCRIPTION:
XS GIS Cut Line= 3
        1969075.       13867775.        1969275.       13867475.
      1969574.99     13867175.01
#Sta/Elev= 30
  4639.7 1691.02  4670.4  1689.6  4675.8 1688.92  4683.3 1689.33  4689.4 1688.44
  4704.3 1687.47  4740.4 1678.67  4755.4 1668.41  4761.4 1668.49  4770.4 1665.89
  4776.4 1665.86  4783.9 1664.27  4797.4 1663.37  4842.5  1664.4  4892.1 1664.33
  5083.1 1662.59  5083.4 1662.09  5087.1 1662.59  5127.5 1663.33  5184.1 1666.23
  5212.4 1669.07    5269 1677.76  5297.2 1684.35  5339.7 1701.45  5382.1 1716.88
  5389.2 1721.06  5396.2  1722.1  5410.4 1727.51    5421 1729.65  5424.5 1729.65
#Mann= 5 ,-1 , 0
  4639.7    .035       0  4670.4     .07       0  4689.4      .1       0
  5083.1     .05       0  5087.1      .1       0
Bank Sta=5083.1,5087.1
XS Rating Curve= 0 ,0
Exp/Cntr=0.3,0.1

Type RM Length L Ch R = 1 ,8987    ,355,355,355
BEGIN DESCRIPTION:
Stream0447 20.0
END DESCRIPTION:
XS GIS Cut Line= 3
      1969475.01     13867974.99      1969605.44     13867857.19
       1969822.7     13867372.84
#Sta/Elev= 30
  4823.4 1674.62  4865.6 1671.75  4908.2 1664.97  4944.1 1662.05  4950.8 1659.52
  4958.7 1658.16    4965 1657.85  4991.4 1647.03  4991.6 1646.53  4995.4 1647.03
  5003.1 1647.31  5008.7 1649.13  5023.5 1650.09  5181.9 1657.16  5228.2 1661.16
  5233.7 1660.76  5256.9 1662.17  5326.4  1668.9  5331.9 1668.82  5385.1 1676.85
  5401.4  1678.1  5424.6 1684.56  5453.2 1690.26  5476.4 1696.52  5494.1 1703.71
  5499.6 1704.23  5505.7 1707.74  5516.7 1711.56  5522.8 1714.97    5530 1715.93
#Mann= 4 ,-1 , 0
  4823.4     .07       0  4958.7      .1       0  4991.4     .05       0
  4995.4      .1       0
Bank Sta=4991.4,4995.4
XS Rating Curve= 0 ,0
Exp/Cntr=0.3,0.1

Type RM Length L Ch R = 1 ,8632    ,471,471,471
BEGIN DESCRIPTION:
Stream0447 19.0
END DESCRIPTION:
XS GIS Cut Line= 3
      1969674.98     13868325.03        1969875.       13868075.
      1970429.29     13867742.04
#Sta/Elev= 30
  4684.4 1666.55  4747.8 1661.66  4790.9 1655.29  4805.3 1651.59  4834.1 1651.39
  4876.5 1649.69  4933.4  1645.9  4968.6  1644.9  4997.4 1642.09  5001.4 1640.45
  5010.3 1639.81  5010.6 1639.31  5014.5 1639.81  5018.2 1642.91  5039.6 1645.39
  5076.5 1647.73  5097.9 1648.29  5179.6 1654.63  5237.9 1657.88  5266.9 1661.69
  5282.5 1665.02  5319.4 1669.51  5383.5  1672.8  5412.9 1675.86  5420.4 1675.72
  5447.9 1678.06  5579.8 1684.18  5595.3 1685.25  5638.1 1690.11  5651.2 1690.38
#Mann= 4 ,-1 , 0
  4684.4     .07       0  4747.8      .1       0  5010.3     .05       0
  5014.5      .1       0
Bank Sta=5010.3,5014.5
XS Rating Curve= 0 ,0
Exp/Cntr=0.3,0.1

Type RM Length L Ch R = 1 ,8161    ,447,447,447
BEGIN DESCRIPTION:
Stream0447 18.0
END DESCRIPTION:
XS GIS Cut Line= 3
      1969724.98       13868475.        1970125.       13868425.
      1970551.25     13868254.55
#Sta/Elev= 30
  4596.9 1667.73  4617.1 1665.89  4634.7 1662.65  4639.8    1663  4647.3  1661.2
  4717.2 1651.06    4738 1647.38  4778.3 1644.07  4962.2 1638.32  4969.8 1631.16
  4977.7 1627.44    4978 1626.94    4982 1627.44    4990 1629.27  4997.5 1637.32
  5014.8 1637.47  5021.6 1635.47  5039.1 1633.74  5053.9 1637.37  5092.9 1644.37
    5171 1650.05  5230.3 1657.82    5237 1659.87  5308.4 1668.31    5338 1669.85
  5362.2 1674.31  5391.8 1676.25  5416.1 1679.36  5421.5 1678.93  5459.1 1682.79
#Mann= 4 ,-1 , 0
  4596.9     .07       0  4717.2      .1       0  4977.7     .05       0
    4982      .1       0
Bank Sta=4977.7,4982
XS Rating Curve= 0 ,0
Exp/Cntr=0.3,0.1

Type RM Length L Ch R = 1 ,7714    ,232,232,232
BEGIN DESCRIPTION:
Stream0447 17.0
END DESCRIPTION:
XS GIS Cut Line= 3
      1970075.03     13868974.98        1970375.       13868775.
      1970774.98     13868425.02
#Sta/Elev= 30
  4644.2 1656.87  4666.7 1655.48  4687.7 1652.38  4709.1 1651.14  4729.8 1649.73
  4752.3 1646.02  4804.6  1641.7    4832 1638.94  4955.1 1632.43  4968.7 1630.39
    4974 1627.75  4974.3 1627.25  4978.4 1627.75  5001.7 1629.96  5026.1 1629.66
    5111 1635.29  5210.2 1644.52  5267.2 1651.23    5288 1655.28  5295.6 1658.33
  5309.9 1661.85  5337.4 1666.03    5345 1668.02  5380.1 1672.43  5387.7 1674.49
  5394.3 1674.29  5408.6 1676.23  5451.3 1683.45  5457.9 1685.31  5536.2 1696.07
#Mann= 5 ,-1 , 0
  4644.2     .07       0  4709.1    .035       0  4804.6      .1       0
    4974     .05       0  4978.4      .1       0
Bank Sta=4974,4978.4
XS Rating Curve= 0 ,0
Exp/Cntr=0.3,0.1

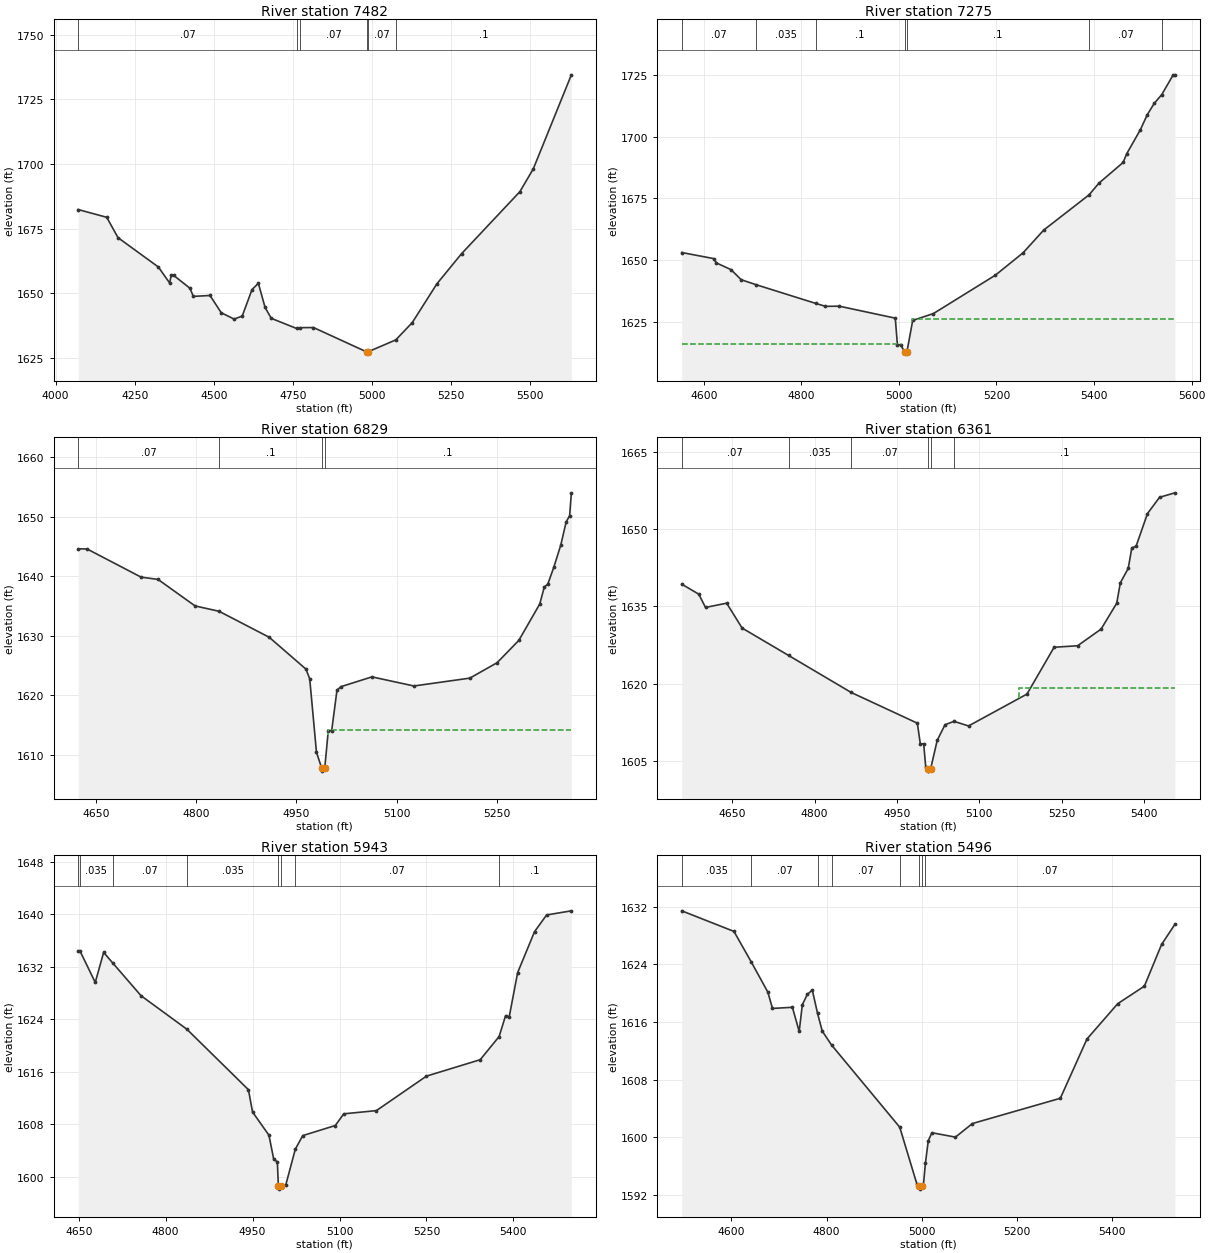
Type RM Length L Ch R = 1 ,7482    ,207,207,207
BEGIN DESCRIPTION:
Mapping XS 6a830ca7
END DESCRIPTION:
XS GIS Cut Line= 3
       1969672.4     13869242.32      1970370.98     13869063.63
      1971006.33     13868516.24
#Sta/Elev= 30
  4071.4 1682.35  4161.6 1679.35  4197.3 1671.46  4324.9 1660.09  4360.6 1653.89
  4365.7 1656.92  4373.4 1656.84    4425 1651.83  4435.4  1648.7  4488.2 1649.05
  4523.9 1642.35  4564.7 1639.89  4590.2 1641.09  4621.1 1651.35  4641.2 1653.76
  4662.4 1644.42    4682 1640.19  4761.9 1636.27    4774 1636.58  4815.5 1636.63
  4983.2 1627.21  4983.6 1626.71  4987.8 1627.21  5075.7 1631.83  5127.8 1638.53
    5206  1653.6  5283.9 1665.26  5468.2 1689.27  5510.6  1698.1  5631.1 1734.56
#Mann= 6 ,-1 , 0
  4071.4     .07       0  4761.9    .035       0    4774     .07       0
  4983.2     .05       0  4987.8     .07       0  5075.7      .1       0
Bank Sta=4983.2,4987.8
XS Rating Curve= 0 ,0
Exp/Cntr=0.3,0.1

Type RM Length L Ch R = 1 ,7275    ,446,446,446
BEGIN DESCRIPTION:
Stream0447 16.0
END DESCRIPTION:
XS GIS Cut Line= 3
       1970310.1     13869329.73        1970675.       13869075.
        1971075.       13868675.
#Sta/Elev= 30
    4555  1653.2  4620.1 1650.77  4626.2 1648.99  4655.9  1646.3  4676.8 1642.23
  4706.7 1640.26  4829.6 1632.67  4849.5 1631.49  4878.1 1631.54  4992.6 1626.72
    4997 1615.97  5003.6 1615.97  5011.9 1613.11  5012.2 1612.61  5016.5 1613.11
  5028.3  1625.8  5070.7 1628.56    5198 1644.09  5254.6  1653.1    5297 1662.29
  5389.8 1676.47  5410.1 1681.21  5459.6 1689.54  5466.7 1692.97    5495 1702.77
  5509.1 1708.82  5523.3 1713.36  5538.8 1716.93  5562.2 1724.89  5565.7 1724.89
#Mann= 7 ,-1 , 0
    4555     .07       0  4706.7    .035       0  4829.6      .1       0
  5011.9     .05       0  5016.5      .1       0  5389.8     .07       0
  5538.8      .1       0
#XS Ineff= 2 , 0
         5003.32 1616.27 5027.57         1626.23
Permanent Ineff=
       F       F
Bank Sta=5011.9,5016.5
XS Rating Curve= 0 ,0
Exp/Cntr=0.3,0.1

Type RM Length L Ch R = 1 ,6829    ,468,468,468
BEGIN DESCRIPTION:
Stream0447 15.0
END DESCRIPTION:
XS GIS Cut Line= 3
      1970501.81     13869476.28        1970875.       13869425.
      1971220.15      13869318.5
#Sta/Elev= 30
  4623.7 1644.59    4637 1644.57  4717.8 1639.84  4743.1 1639.46  4798.5 1635.01
  4834.6  1634.1  4909.5 1629.74  4964.4  1624.4  4970.1 1622.77  4980.2 1610.44
    4988 1607.76  4988.3 1607.26  4992.6 1607.76  4997.9 1614.08    5003 1614.08
  5010.9 1620.86  5016.7 1621.44  5063.2 1623.09    5126 1621.56  5209.7 1622.88
  5250.5 1625.47    5283 1629.22  5314.3 1635.33  5321.1 1638.18  5326.3 1638.66
  5335.3 1641.49  5345.7 1645.21  5353.8 1649.11    5359 1650.17  5361.6    1654
#Mann= 4 ,-1 , 0
  4623.7     .07       0  4834.6      .1       0    4988     .05       0
  4992.6      .1       0
#XS Ineff= 2 , 0
                          4997.2         1614.25
Permanent Ineff=
       F       F
Bank Sta=4988,4992.6
XS Rating Curve= 0 ,0
Exp/Cntr=0.3,0.1

Type RM Length L Ch R = 1 ,6361    ,418,418,418
BEGIN DESCRIPTION:
Stream0447 14.0
END DESCRIPTION:
XS GIS Cut Line= 3
      1970587.57     13870027.99        1970975.       13869825.
      1971275.02     13869474.97
#Sta/Elev= 30
  4558.1 1639.33  4589.1 1637.38  4601.4  1634.8  4639.9 1635.63  4668.1 1630.79
  4752.7 1625.47  4866.8 1618.27  4987.3  1612.3  4992.7 1608.29  4998.8 1608.29
  5002.6 1603.73  5006.9 1603.48  5007.2 1602.98  5011.6 1603.48  5023.5 1608.97
  5037.7    1612  5054.1 1612.66  5080.5 1611.76    5187 1617.96  5236.4 1627.06
  5279.2 1627.35    5322 1630.59  5350.5 1635.62  5357.1  1639.6  5371.4 1642.37
    5378 1646.39  5385.7 1646.68  5406.5 1653.04  5428.5 1656.21  5456.5 1657.08
#Mann= 6 ,-1 , 0
  4558.1     .07       0  4752.7    .035       0  4866.8     .07       0
  5006.9     .05       0  5011.6     .07       0  5054.1      .1       0
#XS Ineff= 2 , 0
                         5173.23         1619.16
Permanent Ineff=
       F       F
Bank Sta=5006.9,5011.6
XS Rating Curve= 0 ,0
Exp/Cntr=0.3,0.1

Type RM Length L Ch R = 1 ,5943    ,447,447,447
BEGIN DESCRIPTION:
Stream0447 13.0
END DESCRIPTION:
XS GIS Cut Line= 3
      1970944.98     13870336.51        1971225.       13870125.
      1971524.99     13869725.02
#Sta/Elev= 30
  4649.1 1634.41  4652.3 1634.38  4678.5  1629.6    4693 1634.18  4708.4  1632.6
  4757.5 1627.58  4836.6 1622.47  4942.8 1613.25  4949.9 1609.85  4978.2 1606.31
  4986.5 1602.63  4992.7 1602.26  4994.5 1598.59  4994.8 1598.09  4999.3 1598.59
  5007.3 1598.74  5023.7 1604.18  5036.5 1606.25  5092.7 1607.79  5107.3 1609.57
  5163.6 1610.06    5250 1615.32  5342.7 1617.82  5375.3 1621.35  5386.5 1624.54
  5392.7 1624.33  5407.3  1631.1  5436.5 1637.35  5457.3 1639.89    5500 1640.52
#Mann= 8 ,-1 , 0
  4649.1     .07       0  4652.3    .035       0  4708.4     .07       0
  4836.6    .035       0  4994.5    .035       0  4999.3    .035       0
  5023.7     .07       0  5375.3      .1       0
Bank Sta=4994.5,4999.3
XS Rating Curve= 0 ,0
Exp/Cntr=0.3,0.1

Type RM Length L Ch R = 1 ,5496    ,454,454,454
BEGIN DESCRIPTION:
Stream0447 12.0
END DESCRIPTION:
XS GIS Cut Line= 3
      1971042.64     13870571.03        1971525.       13870425.
      1971875.01     13870024.99
#Sta/Elev= 30
    4496 1631.45  4605.6 1628.59  4641.8 1624.36  4676.7 1620.16  4686.5 1617.88
  4728.3 1618.04  4742.6 1614.68  4749.2  1618.4  4759.7 1619.83  4770.1 1620.44
  4781.2 1617.18    4791 1614.73  4810.5  1612.8  4953.7 1601.37  4989.5 1593.52
  4994.9 1593.26  4995.3 1592.76  4999.8 1593.26  5003.3 1593.26  5007.7 1596.41
  5013.7 1599.51  5021.3  1600.6  5070.7 1599.99  5106.3 1601.88  5290.9 1605.39
  5346.9 1613.64  5411.4 1618.54  5467.4 1620.98  5503.5 1626.77  5531.5 1629.58
#Mann= 8 ,-1 , 0
    4496    .035       0  4641.8     .07       0  4781.2    .035       0
  4810.5     .07       0  4953.7    .035       0  4994.9    .035       0
  4999.8    .035       0  5007.7     .07       0
Bank Sta=4994.9,4999.8
XS Rating Curve= 0 ,0
Exp/Cntr=0.3,0.1

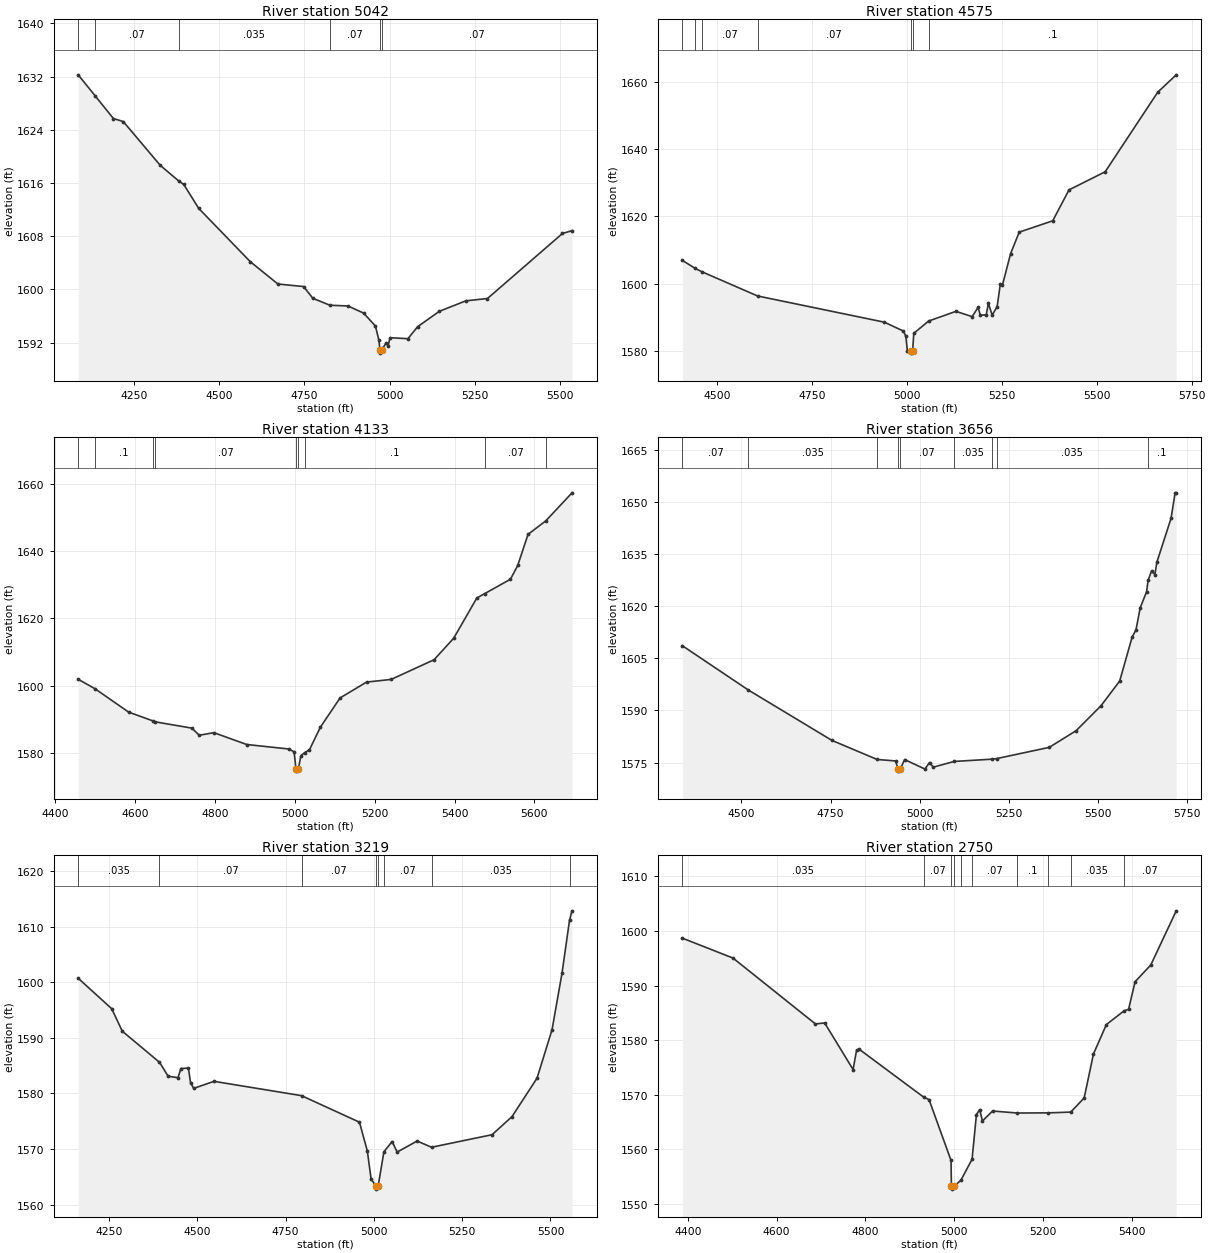
Type RM Length L Ch R = 1 ,5042    ,467,467,467
BEGIN DESCRIPTION:
Stream0447 11.0
END DESCRIPTION:
XS GIS Cut Line= 3
      1971324.98     13871525.03        1971775.       13870725.
      1972124.98     13870325.02
#Sta/Elev= 30
  4086.1 1632.27  4135.4 1629.13  4189.4  1625.7  4218.4 1625.24  4327.1 1618.65
  4381.2 1616.31  4395.9 1615.79  4439.6  1612.2  4591.3 1604.17  4672.2 1600.82
  4747.5 1600.44  4774.9 1598.67  4824.9 1597.63  4877.8 1597.52  4923.7 1596.45
  4958.4 1594.51  4968.6 1592.39  4971.8 1590.93  4972.2 1590.43    4977 1590.93
  4990.3 1591.98  4996.1 1591.57  5001.1 1592.75  5053.8  1592.6  5082.3  1594.4
  5145.9 1596.71  5223.7 1598.29  5287.3 1598.64  5507.5 1608.42  5535.5 1608.84
#Mann= 6 ,-1 , 0
  4086.1    .035       0  4135.4     .07       0  4381.2    .035       0
  4824.9     .07       0  4971.8     .05       0    4977     .07       0
Bank Sta=4971.8,4977
XS Rating Curve= 0 ,0
Exp/Cntr=0.3,0.1

Type RM Length L Ch R = 1 ,4575    ,442,442,442
BEGIN DESCRIPTION:
Stream0447 10.0
END DESCRIPTION:
XS GIS Cut Line= 3
      1971710.15     13871297.08        1972175.       13870925.
      1972779.76     13870563.67
#Sta/Elev= 30
  4409.5  1606.9  4442.9 1604.55  4460.8 1603.53  4607.3 1596.32  4940.9 1588.52
  4991.3 1585.87  4997.7 1584.26  5001.7 1579.87    5010  1579.8  5010.5  1579.3
  5015.4  1579.8  5018.5  1585.2  5057.7 1588.86  5129.4 1591.74  5172.2 1590.17
  5187.8 1592.93  5193.6  1590.6  5209.2  1590.7    5215 1594.11  5224.8 1590.63
  5237.9 1593.09  5246.2 1599.79    5252 1599.58  5273.4 1608.94  5296.1 1615.33
  5384.3 1618.71  5427.1 1627.91  5522.4 1633.31  5660.6 1656.99  5709.4 1662.18
#Mann= 7 ,-1 , 0
  4409.5      .1       0  4442.9    .035       0  4460.8     .07       0
  4607.3     .07       0    5010     .05       0  5015.4     .07       0
  5057.7      .1       0
Bank Sta=5010,5015.4
XS Rating Curve= 0 ,0
Exp/Cntr=0.3,0.1

Type RM Length L Ch R = 1 ,4133    ,477,477,477
BEGIN DESCRIPTION:
Stream0447 9.0
END DESCRIPTION:
XS GIS Cut Line= 3
      1971865.44     13871448.65        1972375.       13871275.
      1973057.94     13871126.67
#Sta/Elev= 30
    4457 1601.89  4498.6 1599.12  4583.3 1592.14  4643.5 1589.55  4649.5 1589.25
  4741.8 1587.37  4760.2 1585.25  4796.9 1586.02  4879.1  1582.5  4984.9 1581.16
  4997.9 1580.32  5002.8 1575.08  5003.3 1574.58  5008.3 1575.08  5014.8 1579.11
  5024.2 1580.08  5036.3 1580.92  5063.9 1587.69  5113.1 1596.36  5179.5 1601.07
  5240.9 1601.86  5348.5 1607.71  5397.7 1614.11  5455.8  1626.1  5475.8 1627.41
    5540 1631.67  5558.2 1635.77    5584 1645.01  5628.7 1649.05  5694.2 1657.37
#Mann= 9 ,-1 , 0
    4457     .07       0  4498.6      .1       0  4643.5     .07       0
  4649.5     .07       0  5002.8     .05       0  5008.3     .07       0
  5024.2      .1       0  5475.8     .07       0  5628.7      .1       0
Bank Sta=5002.8,5008.3
XS Rating Curve= 0 ,0
Exp/Cntr=0.3,0.1

Type RM Length L Ch R = 1 ,3656    ,437,437,437
BEGIN DESCRIPTION:
Stream0447 8.0
END DESCRIPTION:
XS GIS Cut Line= 3
      1971936.18     13871880.66        1972575.       13871675.
      1973228.34     13871387.51
#Sta/Elev= 30
  4334.5 1608.63  4518.9 1595.92  4753.5  1581.4  4880.4  1575.9  4932.1 1575.47
  4939.8 1573.04  4940.2 1572.54  4945.3 1573.04  4957.5 1575.88  5014.5 1573.14
  5027.5 1575.02  5037.9 1573.68  5096.8 1575.33  5202.4 1575.98  5215.7 1576.15
  5363.2 1579.38  5438.6 1584.18  5508.2 1591.33  5560.8 1598.47  5595.6 1611.09
  5606.5 1613.19  5618.4 1619.57  5636.3 1624.18  5640.5 1627.42  5650.2 1630.18
  5659.6 1629.14  5665.1 1632.68  5704.8 1645.29  5716.3 1652.66  5719.4 1652.66
#Mann= 9 ,-1 , 0
  4334.5     .07       0  4518.9    .035       0  4880.4     .07       0
  4939.8     .05       0  4945.3     .07       0  5096.8    .035       0
  5202.4     .07       0  5215.7    .035       0  5640.5      .1       0
Bank Sta=4939.8,4945.3
XS Rating Curve= 0 ,0
Exp/Cntr=0.3,0.1

Type RM Length L Ch R = 1 ,3219    ,469,469,469
BEGIN DESCRIPTION:
Stream0447 7.0
END DESCRIPTION:
XS GIS Cut Line= 3
      1972369.54     13872621.24        1972825.       13871925.
      1973225.03     13871524.97
#Sta/Elev= 30
  4163.2 1600.73  4257.8 1595.27    4288  1591.2  4393.1 1585.62  4417.7  1583.1
  4445.5 1582.83  4453.9 1584.48    4475 1584.57  4481.3  1581.9  4490.1 1580.91
  4547.4 1582.18  4795.2  1579.6  4959.3 1574.82  4981.6 1569.62  4992.2  1564.6
  5006.5 1563.27    5007 1562.77  5012.1 1563.27  5028.4 1569.49  5051.7 1571.34
  5065.9 1569.44  5122.5 1571.43  5163.3 1570.31  5334.6 1572.57  5391.2 1575.84
  5461.9 1582.75  5504.3 1591.45  5532.6 1601.65  5553.9  1611.2  5560.9 1612.88
#Mann= 8 ,-1 , 0
  4163.2    .035       0  4393.1     .07       0  4795.2     .07       0
  5006.5     .05       0  5012.1     .07       0  5028.4     .07       0
  5163.3    .035       0  5553.9      .1       0
Bank Sta=5006.5,5012.1
XS Rating Curve= 0 ,0
Exp/Cntr=0.3,0.1

Type RM Length L Ch R = 1 ,2750    ,416,416,416
BEGIN DESCRIPTION:
Stream0447 6.0
END DESCRIPTION:
XS GIS Cut Line= 3
      1972790.43     13872701.25        1973175.       13872225.
      1973474.98     13871825.03
#Sta/Elev= 30
  4388.1  1598.7  4502.1 1595.05  4687.6 1582.99  4708.4 1583.17  4772.4 1574.64
  4780.3 1578.18  4786.8 1578.32  4931.2 1569.59  4943.5 1569.13    4993 1557.99
  4993.9 1553.23  4994.4 1552.73  5000.1 1553.23  5015.4 1554.39  5040.4  1558.2
  5050.2 1566.37  5057.5  1567.3  5063.8 1565.22  5086.7 1567.04  5142.4 1566.67
  5211.9  1566.7  5262.6 1566.84  5292.9 1569.44  5313.8 1577.49  5342.9 1582.88
  5382.7 1585.39  5392.9 1585.67  5407.5 1590.72  5442.9 1593.79  5500.2 1603.71
#Mann= 10 ,-1 , 0
  4388.1    .035       0  4931.2     .07       0  4993.9     .05       0
  5000.1     .07       0  5015.4    .035       0  5040.4     .07       0
  5142.4      .1       0  5211.9     .07       0  5262.6    .035       0
  5382.7     .07       0
Bank Sta=4993.9,5000.1
XS Rating Curve= 0 ,0
Exp/Cntr=0.3,0.1

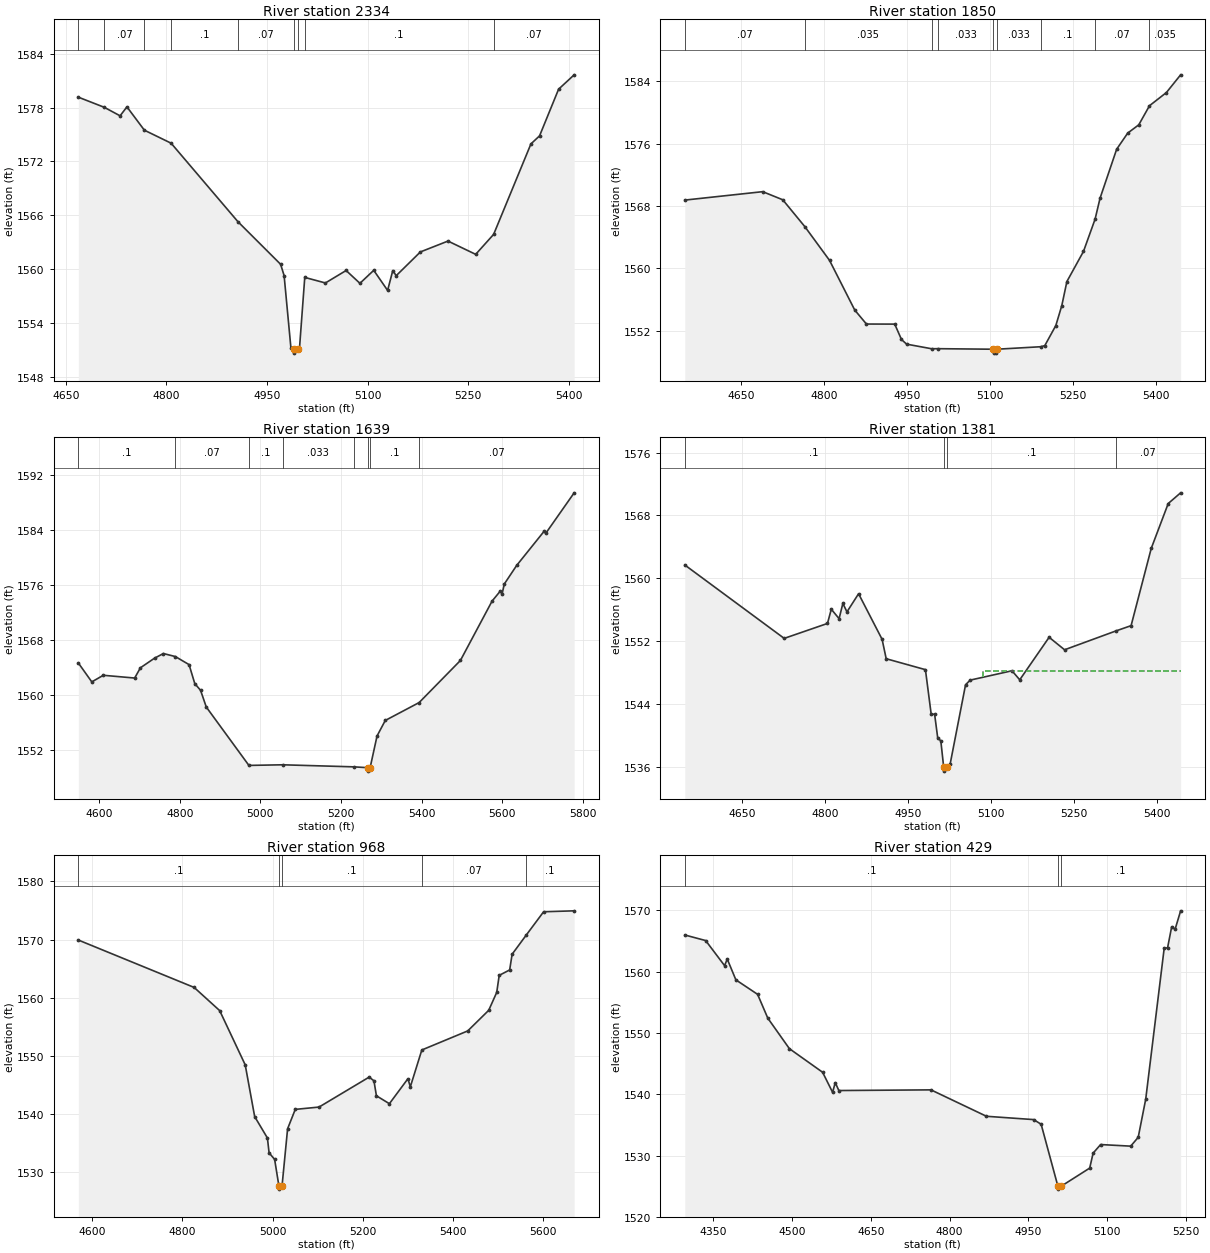
Type RM Length L Ch R = 1 ,2334    ,484,484,484
BEGIN DESCRIPTION:
Stream0447 5.0
END DESCRIPTION:
XS GIS Cut Line= 3
      1973461.12     13872746.06        1973525.       13872425.
      1973625.01     13872024.96
#Sta/Elev= 30
  4668.5 1579.16  4707.2 1578.03  4730.8 1577.08    4741 1578.08    4767 1575.48
  4806.9 1574.03  4906.6 1565.28  4970.3 1560.53  4975.5 1559.27  4985.7 1551.16
  4990.2 1551.13  4990.7 1550.63  4996.4 1551.13  4998.4 1551.13  5006.3 1559.07
  5037.1 1558.45    5068 1559.84  5088.6 1558.41  5109.2 1559.86  5129.9 1557.62
  5137.6 1559.83  5142.7 1559.26  5178.8 1561.91    5220 1563.12  5261.3 1561.64
  5288.1 1563.87  5343.7 1573.95  5356.6 1574.85    5385 1580.05  5408.2 1581.65
#Mann= 9 ,-1 , 0
  4668.5      .1       0  4707.2     .07       0    4767    .035       0
  4806.9      .1       0  4906.6     .07       0  4990.2     .05       0
  4996.4     .07       0  5006.3      .1       0  5288.1     .07       0
Bank Sta=4990.2,4996.4
XS Rating Curve= 0 ,0
Exp/Cntr=0.3,0.1

Type RM Length L Ch R = 1 ,1850    ,211,211,211
BEGIN DESCRIPTION:
Stream0447 4.0
END DESCRIPTION:
XS GIS Cut Line= 3
      1973731.28     13872804.53        1973975.       13872425.
      1973984.83     13871979.35
#Sta/Elev= 30
  4548.6 1568.77  4689.5 1569.85  4725.8 1568.81  4765.9 1565.35  4810.4 1561.04
    4856 1554.67  4877.1 1552.88  4928.3 1552.87  4940.5  1550.9  4949.8  1550.3
  4995.1 1549.71  5006.2 1549.72  5106.5 1549.65    5107 1549.15  5112.3 1549.15
  5112.8 1549.65  5192.4 1549.97  5199.7 1550.11  5219.7 1552.69  5230.5 1555.25
  5239.7 1558.33  5269.7 1562.19  5290.7 1566.33  5299.7 1569.02  5329.7 1575.29
  5349.7 1577.36  5369.7 1578.42  5389.1 1580.87  5419.7 1582.56  5445.4 1584.83
#Mann= 9 ,-1 , 0
  4548.6     .07       0  4765.9    .035       0  4995.1      .1       0
  5006.2    .033       0  5106.5     .05       0  5112.8    .033       0
  5192.4      .1       0  5290.7     .07       0  5389.1    .035       0
Bank Sta=5106.5,5112.8
XS Rating Curve= 0 ,0
Exp/Cntr=0.3,0.1

Type RM Length L Ch R = 1 ,1639    ,258,258,258
BEGIN DESCRIPTION:
Mapping XS eecc2510
END DESCRIPTION:
XS GIS Cut Line= 3
      1973828.53     13872915.65      1974281.76     13872393.36
      1974383.95     13871865.08
#Sta/Elev= 30
  4548.6 1564.67    4582 1561.92  4610.5 1562.88  4688.3 1562.48  4702.6 1563.97
  4737.7 1565.37  4759.6 1566.04  4789.2  1565.6  4823.2 1564.43  4837.4 1561.67
  4851.7  1560.7  4865.9 1558.27  4971.6 1549.79  5055.3 1549.88  5232.5 1549.58
  5265.8 1549.46  5266.3 1548.96  5272.2 1549.46  5289.4 1554.07  5309.8 1556.32
  5393.8 1558.92  5496.1 1565.03  5574.6 1573.65  5594.6 1575.08  5599.7 1574.75
  5605.1 1576.15  5635.7 1578.84  5703.3 1583.77  5708.4 1583.55  5778.2 1589.38
#Mann= 8 ,-1 , 0
  4548.6      .1       0  4789.2     .07       0  4971.6      .1       0
  5055.3    .033       0  5232.5      .1       0  5265.8     .05       0
  5272.2      .1       0  5393.8     .07       0
Bank Sta=5265.8,5272.2
XS Rating Curve= 0 ,0
Exp/Cntr=0.3,0.1

Type RM Length L Ch R = 1 ,1381    ,413,413,413
BEGIN DESCRIPTION:
Stream0447 3.0
END DESCRIPTION:
XS GIS Cut Line= 3
      1973995.44     13873029.43        1974325.       13872725.
      1974525.02     13872324.97
#Sta/Elev= 30
    4547  1561.7  4726.6 1552.36  4804.8 1554.26  4811.7 1556.07  4825.8 1554.87
  4832.6 1556.81    4840 1555.73    4861 1558.04  4903.5 1552.24  4910.9 1549.77
  4981.8 1548.38  4992.2 1542.71  4998.4 1542.71    5004 1539.69  5009.6 1539.32
  5014.8 1535.97  5015.3 1535.47  5021.2 1535.97  5026.4 1536.35  5054.3 1546.46
  5062.7 1547.05  5138.2 1548.24  5152.2 1547.09  5205.3  1552.5  5233.2 1550.91
  5326.1 1553.31  5353.4 1553.98  5389.8 1563.81  5420.5 1569.52  5442.9 1570.88
#Mann= 4 ,-1 , 0
    4547      .1       0  5014.8     .05       0  5021.2      .1       0
  5326.1     .07       0
#XS Ineff= 2 , 0
                         5085.71         1548.17
Permanent Ineff=
       F       F
Bank Sta=5014.8,5021.2
XS Rating Curve= 0 ,0
Exp/Cntr=0.3,0.1

Type RM Length L Ch R = 1 ,968     ,539,539,539
BEGIN DESCRIPTION:
Stream0447 2.0
END DESCRIPTION:
XS GIS Cut Line= 3
      1974311.62     13873264.93        1974625.       13872975.
      1974897.84     13872358.83
#Sta/Elev= 30
  4568.8 1569.91  4825.9 1561.75  4882.6 1557.76  4939.3 1548.42  4960.3 1539.51
  4988.6 1535.82  4992.3 1533.27  5004.6 1532.14  5014.2 1527.52  5014.7 1527.02
    5021 1527.52  5033.4 1537.41  5050.4 1540.75  5103.2 1541.15  5214.5 1546.31
  5225.1 1545.67  5230.6 1543.09  5259.4 1541.73  5300.5 1546.03  5305.9 1544.64
  5331.4 1550.98  5433.3 1554.26  5479.9 1557.81  5497.7  1560.9  5503.2 1563.83
  5526.4 1564.76  5531.9 1567.47  5562.7 1570.71  5601.8 1574.78  5669.6 1574.94
#Mann= 5 ,-1 , 0
  4568.8      .1       0  5014.2     .05       0    5021      .1       0
  5331.4     .07       0  5562.7      .1       0
#XS Ineff= 2 , 0
                         5216.78         1545.39
Permanent Ineff=
       F       F
Bank Sta=5014.2,5021
XS Rating Curve= 0 ,0
Exp/Cntr=0.3,0.1

Type RM Length L Ch R = 1 ,429     ,329,329,329
BEGIN DESCRIPTION:
Stream0447 1.0
END DESCRIPTION:
XS GIS Cut Line= 3
      1974430.73     13873369.52      1975058.46     13873211.45
      1975284.71     13873020.47
#Sta/Elev= 30
  4296.2 1565.97  4335.9 1565.06  4371.9 1560.97    4377 1562.04  4393.4 1558.65
  4434.7 1556.29  4454.1 1552.41  4495.2 1547.43  4558.4 1543.58  4577.4 1540.31
  4582.5 1541.89  4589.3  1540.6  4764.6 1540.71  4870.2  1536.4    4960 1535.86
  4974.2  1535.1    5006 1525.02  5006.5 1524.52  5012.8 1525.02  5066.6 1527.95
  5073.1 1530.39  5087.4 1531.79  5144.6 1531.53  5158.9 1532.97  5173.2  1539.2
  5208.3 1563.78  5214.8 1563.89  5222.6 1567.32  5229.1  1566.9  5239.6 1569.91
#Mann= 3 ,-1 , 0
  4296.2      .1       0    5006     .05       0  5012.8      .1       0
Bank Sta=5006,5012.8
XS Rating Curve= 0 ,0
Exp/Cntr=0.3,0.1

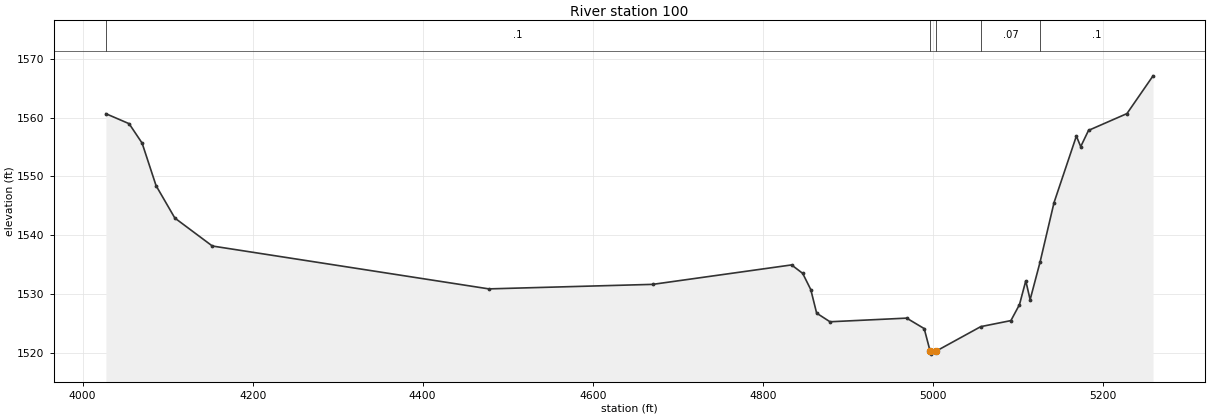
Type RM Length L Ch R = 1 ,100     ,0,0,0
BEGIN DESCRIPTION:
Stream0447 0.0
END DESCRIPTION:
XS GIS Cut Line= 4
      1974410.86     13873839.06      1975240.53     13873403.73
      1975318.65     13873380.26       1975355.4     13873170.27
#Sta/Elev= 30
  4027.4 1560.67  4054.7 1558.97    4070 1555.66  4086.4 1548.42  4108.5  1542.9
  4152.6 1538.14  4477.8 1530.84  4670.6 1531.61  4833.9 1534.92    4847 1533.48
  4856.5 1530.72  4863.4 1526.71  4879.1 1525.24  4969.3 1525.86  4989.9 1524.08
  4996.9 1520.23  4997.4 1519.73  5003.8 1520.23  5056.4 1524.41  5091.9 1525.44
    5102 1528.17  5109.4 1532.22  5114.5    1529  5126.2 1535.41  5142.6 1545.52
  5168.9 1556.86    5174 1555.06  5183.2 1557.83  5228.4 1560.69  5259.1 1567.12
#Mann= 5 ,-1 , 0
  4027.4      .1       0  4996.9     .05       0  5003.8      .1       0
  5056.4     .07       0  5126.2      .1       0
Bank Sta=4996.9,5003.8
XS Rating Curve= 0 ,0
Exp/Cntr=0.3,0.1

Chan Stop Cuts=-1
Use User Specified Reach Order=0
Composite Channel Slope=5