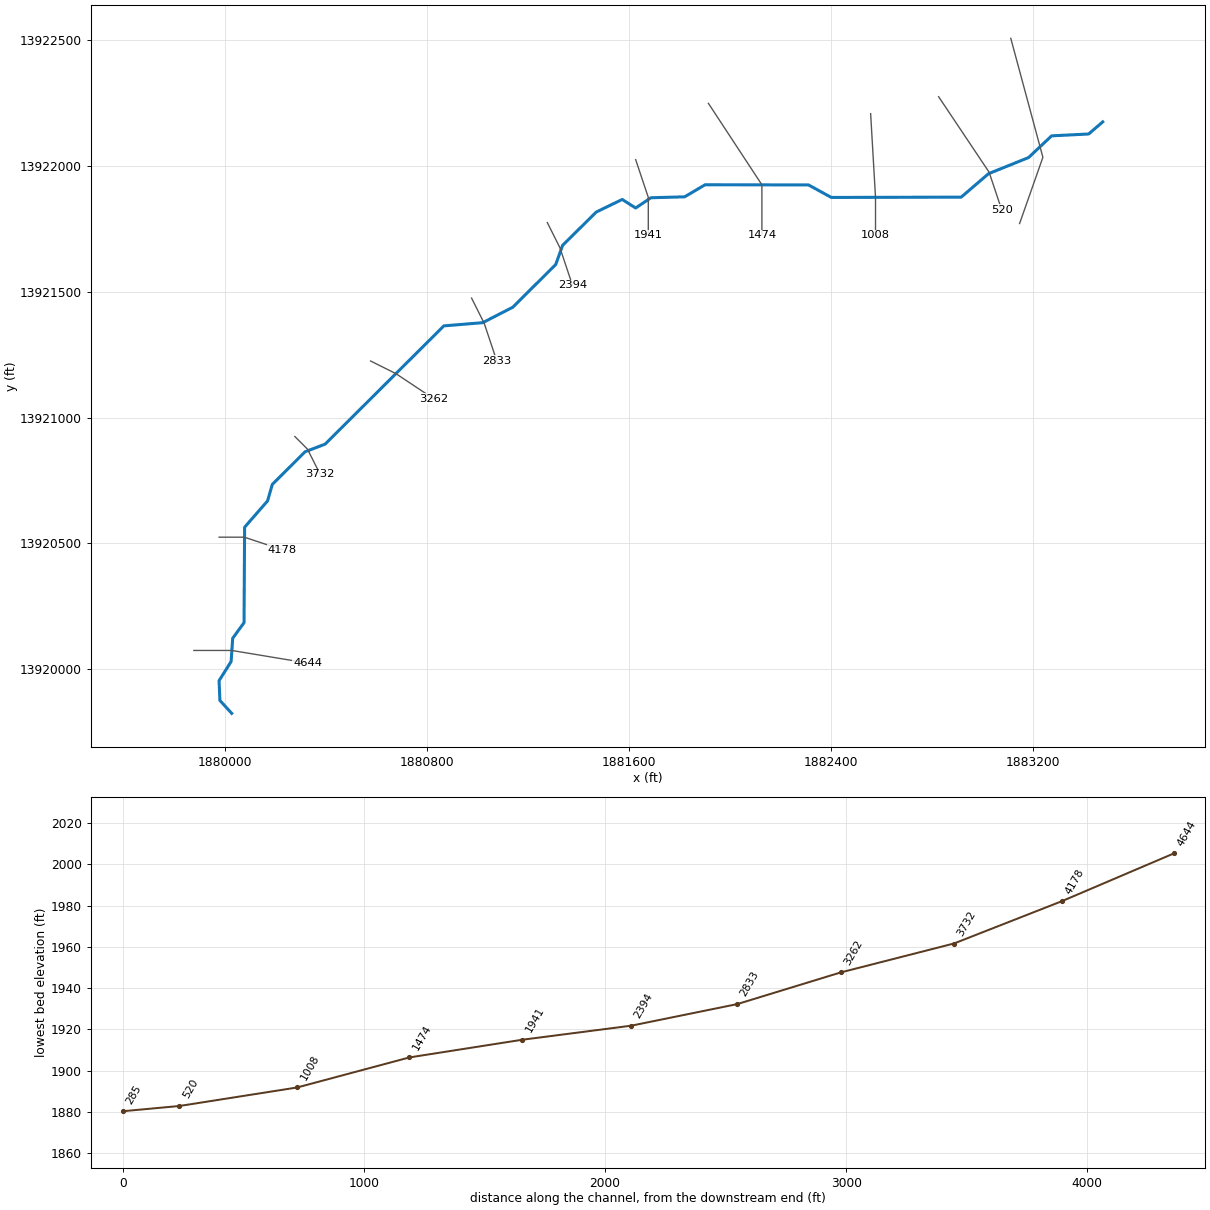
--- Stream0448.prj (project) ---

Proj Title=Stream0448 Base Level Engineering
Current Plan=p01
Default Exp/Contr=0.3,0.1
English Units
Geom File=g01
Flow File=f01
Plan File=p01
BEGIN DESCRIPTION:
Stream0448
END DESCRIPTION:

--- Stream0448.p01 (plan) ---

Plan Title=Multiple Run
Short Identifier=Multiple
Geom File=g01
Flow File=f01
Subcritical Flow
K Sum by GR= 0
Std Step Tol= 0.01
Critical Tol= 0.01
Num of Std Step Trials= 20
Max Error Tol= 0.3
Flow Tol Ratio= 0.001
Split Flow NTrial= 30
Split Flow Tol= 0.02
Split Flow Ratio= 0.02
Log Output Level= 0
Friction Slope Method= 1
Unsteady Friction Slope Method= 2
Unsteady Bridges Friction Slope Method= 1
Parabolic Critical Depth
Global Vel Dist=  1 , 1 , 1
Global Log Level= 0
CheckData=True
Encroach Param= -1, 0, 0, 0
BEGIN DESCRIPTION:
Multiple Run
END DESCRIPTION:

--- Stream0448.f01 (steady flow) ---

Flow Title=Multiple
Number of Profiles=7
Profile Names=10-year,25-year,50-year,1pct_min,100-year,1pct_plu,500-year
River Rch & RM= Stream0448,Reach-1,4644
    1035    1778    2494    1694    3380    6744    6126
Boundary for River Rch & Prof#=Stream0448,Reach-1,1
Up Type=0
Dn Type=3
Dn Slope=0.005
Boundary for River Rch & Prof#=Stream0448,Reach-1,2
Up Type=0
Dn Type=3
Dn Slope=0.005
Boundary for River Rch & Prof#=Stream0448,Reach-1,3
Up Type=0
Dn Type=3
Dn Slope=0.005
Boundary for River Rch & Prof#=Stream0448,Reach-1,4
Up Type=0
Dn Type=3
Dn Slope=0.005
Boundary for River Rch & Prof#=Stream0448,Reach-1,5
Up Type=0
Dn Type=3
Dn Slope=0.005
Boundary for River Rch & Prof#=Stream0448,Reach-1,6
Up Type=0
Dn Type=3
Dn Slope=0.005
Boundary for River Rch & Prof#=Stream0448,Reach-1,7
Up Type=0
Dn Type=3
Dn Slope=0.005

--- Stream0448.g01 (geometry) ---

Geom Title=Existing Conditions

River Reach=Stream0448,Reach-1
Reach XY= 30
      1880025.00     13919825.00      1879978.19     13919876.40
      1879974.89     13919954.92      1880022.64     13920030.97
      1880028.86     13920123.40      1880073.78     13920185.50
      1880076.05     13920564.56      1880166.82     13920668.96
      1880185.78     13920734.68      1880315.32     13920864.22
      1880395.09     13920894.79      1880865.20     13921364.52
      1881019.07     13921377.25      1881138.22     13921438.62
      1881308.35     13921608.33      1881335.78     13921684.68
      1881468.95     13921816.88      1881571.77     13921866.76
      1881624.90     13921832.80      1881685.44     13921873.61
      1881819.06     13921877.27      1881899.92     13921925.20
      1882309.78     13921924.48      1882399.92     13921874.80
      1882914.56     13921876.05      1883022.71     13921969.15
      1883181.05     13922033.16      1883272.55     13922119.52
      1883419.21     13922126.91      1883475.00     13922175.00

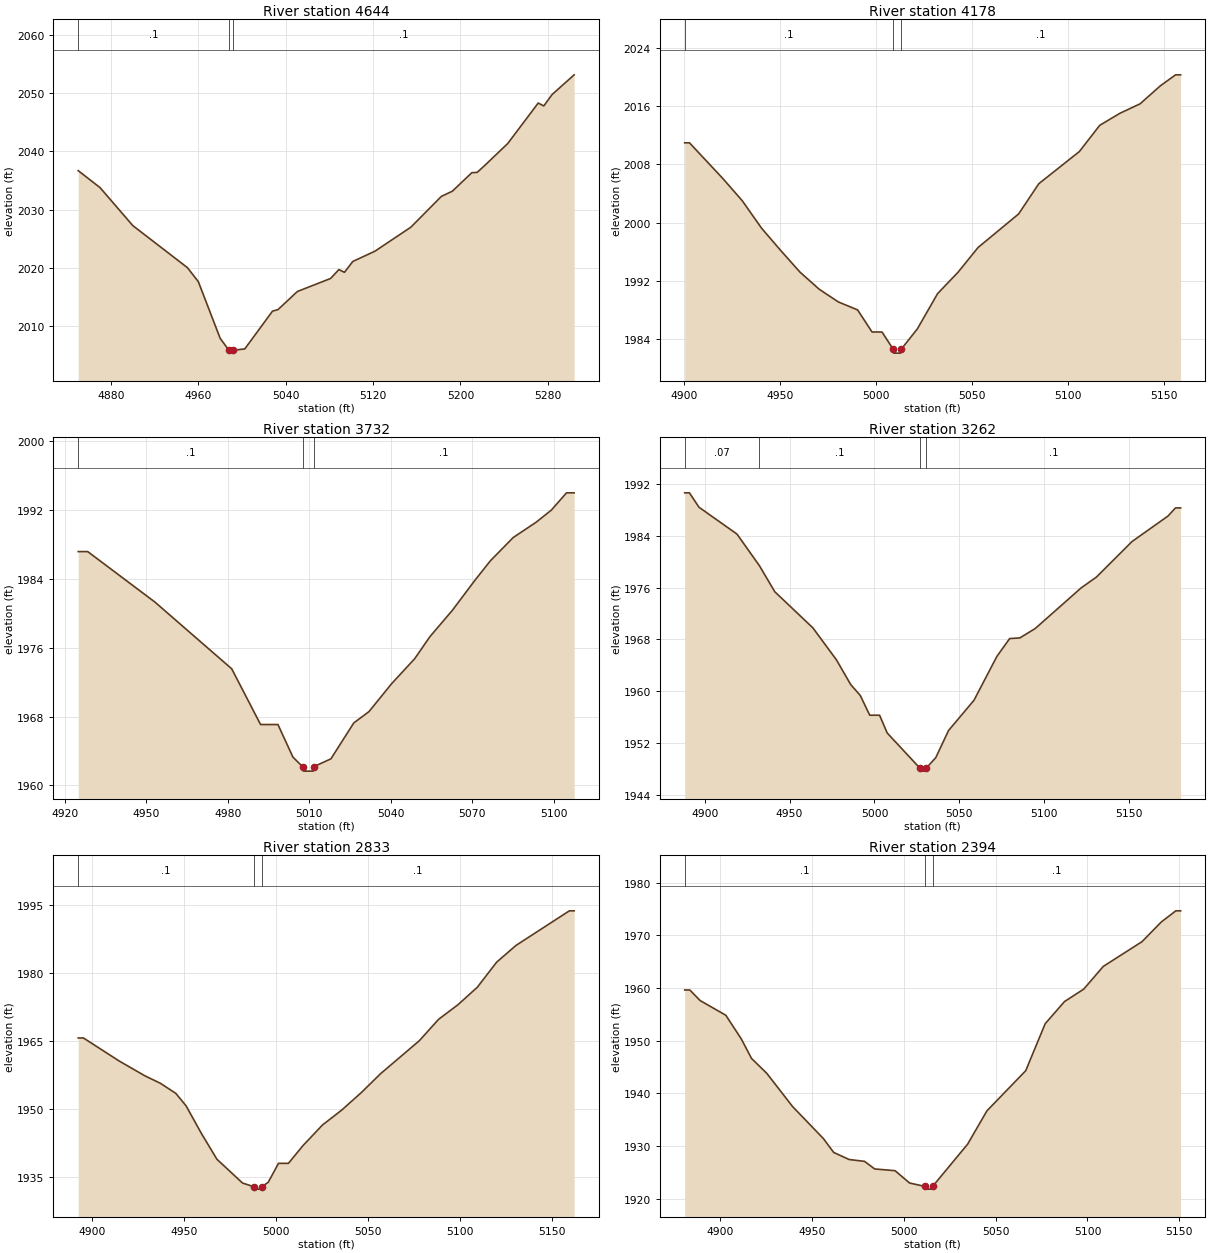
Type RM Length L Ch R = 1,4644,466,466,466
BEGIN DESCRIPTION:
Stream0448 10.0
END DESCRIPTION:
XS GIS Cut Line= 3
      1879875.00     13920075.00      1880025.00     13920075.00
      1880324.96     13920025.01
#Sta/Elev= 30
  4850.0 2036.69  4870.0 2033.77  4900.0 2027.24  4950.0 2020.01  4960.0 2017.60
  4980.0 2007.85  4988.0 2005.81  4988.3 2005.31  4991.8 2005.31  4992.0 2005.81
  5002.5 2006.03  5027.9 2012.53  5032.9 2012.79  5050.7 2015.91  5081.1 2018.15
  5088.7 2019.68  5093.8 2019.21  5101.4 2021.07  5121.7 2022.84  5154.6 2026.97
  5182.5 2032.26  5192.6 2033.16  5210.4 2036.34  5215.4 2036.40  5223.0 2037.72
  5243.3 2041.36  5271.2 2048.32  5276.3 2047.82  5283.9 2049.78  5304.1 2053.17
#Mann=3,-1,0
  4850.0     0.1       0  4988.0    0.05       0  4992.0     0.1       0
Bank Sta=4988,4992
Exp/Cntr=0.3,0.1

Type RM Length L Ch R = 1,4178,446,446,446
BEGIN DESCRIPTION:
Stream0448 9.0
END DESCRIPTION:
XS GIS Cut Line= 3
      1879974.98     13920525.00      1880075.00     13920525.00
      1880224.97     13920475.01
#Sta/Elev= 29
  4900.4 2010.95  4902.9 2010.95  4920.4 2006.01  4930.4 2002.99  4940.4 1999.24
  4950.4 1996.17  4960.4 1993.21  4970.4 1990.86  4980.4 1989.11  4990.4 1988.02
  4997.9 1984.99  5003.1 1984.99  5009.0 1982.59  5009.2 1982.09  5012.7 1982.09
  5013.0 1982.59  5021.5 1985.42  5032.0 1990.25  5042.6 1993.17  5053.1 1996.59
  5074.2 2001.19  5084.7 2005.34  5105.8 2009.75  5116.4 2013.35  5126.9 2015.00
  5137.4 2016.30  5148.0 2018.78  5155.9 2020.28  5158.5 2020.28
#Mann=3,-1,0
  4900.4     0.1       0  5009.0    0.05       0  5013.0     0.1       0
Bank Sta=5009,5013
Exp/Cntr=0.3,0.1

Type RM Length L Ch R = 1,3732,470,470,470
BEGIN DESCRIPTION:
Stream0448 8.0
END DESCRIPTION:
XS GIS Cut Line= 3
      1880275.03     13920924.97      1880325.00     13920875.00
      1880375.02     13920774.97
#Sta/Elev= 26
  4925.0 1987.18  4928.5 1987.18  4953.2 1981.32  4981.5 1973.55  4992.1 1967.08
  4995.7 1967.08  4998.5 1967.08  5004.0 1963.30  5007.6 1962.16  5007.9 1961.66
  5011.4 1961.66  5011.6 1962.16  5018.0 1963.09  5026.4 1967.26  5032.0 1968.58
  5040.4 1971.85  5048.8 1974.72  5054.4 1977.28  5062.7 1980.36  5071.1 1983.89
  5076.7 1986.12  5085.1 1988.82  5093.5 1990.59  5099.1 1992.00  5104.7 1994.01
  5107.5 1994.01
#Mann=3,-1,0
  4925.0     0.1       0  5007.6    0.05       0  5011.6     0.1       0
Bank Sta=5007.6,5011.6
Exp/Cntr=0.3,0.1

Type RM Length L Ch R = 1,3262,429,429,429
BEGIN DESCRIPTION:
Stream0448 7.0
END DESCRIPTION:
XS GIS Cut Line= 3
      1880574.99     13921225.00      1880675.00     13921175.00
      1880825.01     13921074.99
#Sta/Elev= 30
  4888.2 1990.63  4891.0 1990.63  4896.6 1988.41  4919.0 1984.26  4932.2 1979.38
  4941.3 1975.34  4963.7 1969.77  4977.6 1964.82  4986.0 1961.00  4991.6 1959.33
  4997.2 1956.27  5003.0 1956.27  5007.5 1953.52  5026.6 1948.13  5026.8 1947.63
  5030.3 1947.63  5030.6 1948.13  5036.1 1949.72  5043.6 1953.90  5058.6 1958.58
  5072.1 1965.36  5079.6 1968.11  5085.6 1968.21  5094.7 1969.67  5121.7 1975.94
  5130.7 1977.61  5151.7 1983.11  5172.8 1987.03  5177.3 1988.30  5180.3 1988.30
#Mann=4,-1,0
  4888.2    0.07       0  4932.2     0.1       0  5026.6    0.05       0
  5030.6     0.1       0
Bank Sta=5026.6,5030.6
Exp/Cntr=0.3,0.1

Type RM Length L Ch R = 1,2833,439,439,439
BEGIN DESCRIPTION:
Stream0448 6.0
END DESCRIPTION:
XS GIS Cut Line= 3
      1880975.00     13921474.99      1881025.00     13921375.00
      1881075.00     13921225.01
#Sta/Elev= 30
  4892.3 1965.61  4895.1 1965.61  4914.7 1960.50  4928.6 1957.26  4937.0 1955.62
  4945.4 1953.40  4951.0 1950.65  4959.4 1944.52  4967.8 1938.87  4981.7 1933.64
  4988.1 1932.79  4988.4 1932.29  4991.9 1932.29  4992.1 1932.79  4995.7 1933.79
  5001.3 1937.97  5006.7 1937.97  5014.6 1941.87  5025.2 1946.41  5035.7 1949.71
  5046.3 1953.54  5056.8 1957.71  5077.9 1964.98  5088.4 1969.70  5099.0 1972.94
  5109.5 1976.78  5120.0 1982.30  5130.6 1986.01  5159.6 1993.62  5162.2 1993.62
#Mann=3,-1,0
  4892.3     0.1       0  4988.1    0.05       0  4992.1     0.1       0
Bank Sta=4988.1,4992.1
Exp/Cntr=0.3,0.1

Type RM Length L Ch R = 1,2394,453,453,453
BEGIN DESCRIPTION:
Stream0448 5.0
END DESCRIPTION:
XS GIS Cut Line= 3
      1881274.99     13921775.02      1881325.00     13921675.00
      1881374.99     13921525.04
#Sta/Elev= 30
  4880.8 1959.64  4883.6 1959.64  4889.2 1957.64  4903.2 1954.84  4911.6 1950.36
  4917.2 1946.64  4925.5 1943.82  4939.5 1937.53  4956.3 1931.44  4961.9 1928.81
  4970.3 1927.47  4978.7 1927.12  4984.2 1925.68  4995.3 1925.35  5003.2 1923.01
  5011.7 1922.35  5012.0 1921.85  5015.5 1921.85  5015.7 1922.35  5034.8 1930.39
  5045.3 1936.71  5066.4 1944.32  5077.0 1953.24  5087.5 1957.44  5098.0 1959.81
  5108.6 1964.11  5129.7 1968.81  5140.2 1972.55  5148.1 1974.66  5150.7 1974.66
#Mann=3,-1,0
  4880.8     0.1       0  5011.7    0.05       0  5015.7     0.1       0
Bank Sta=5011.7,5015.7
Exp/Cntr=0.3,0.1

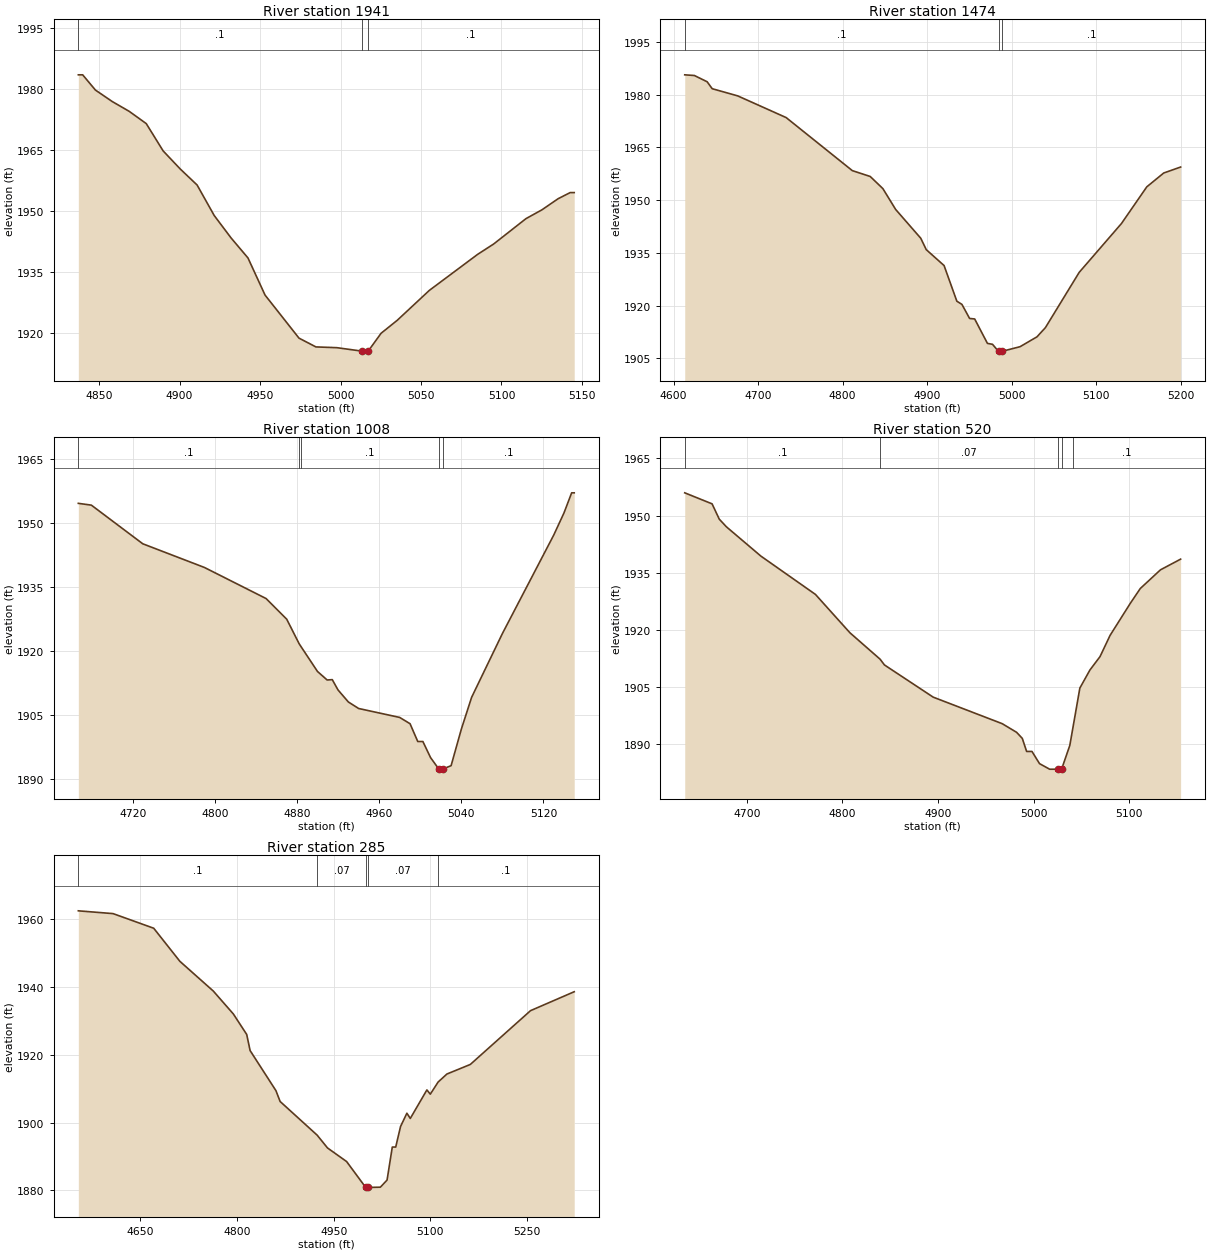
Type RM Length L Ch R = 1,1941,467,467,467
BEGIN DESCRIPTION:
Stream0448 4.0
END DESCRIPTION:
XS GIS Cut Line= 3
      1881624.99     13922025.03      1881675.00     13921875.00
      1881675.00     13921725.04
#Sta/Elev= 30
  4837.1 1983.49  4839.8 1983.49  4847.7 1979.75  4858.2 1976.91  4868.7 1974.51
  4879.3 1971.49  4889.8 1964.77  4900.4 1960.33  4910.9 1956.38  4921.5 1948.89
  4932.0 1943.36  4942.5 1938.44  4953.1 1929.31  4974.2 1918.71  4984.7 1916.55
  4997.7 1916.36  5013.2 1915.52  5013.5 1915.02  5017.0 1915.02  5017.2 1915.52
  5025.2 1919.90  5035.2 1923.08  5055.2 1930.46  5085.2 1939.32  5095.2 1941.88
  5115.2 1948.10  5125.2 1950.29  5135.2 1953.01  5142.7 1954.52  5145.2 1954.52
#Mann=3,-1,0
  4837.1     0.1       0  5013.2    0.05       0  5017.2     0.1       0
Bank Sta=5013.2,5017.2
Exp/Cntr=0.3,0.1

Type RM Length L Ch R = 1,1474,466,466,466
BEGIN DESCRIPTION:
Stream0448 3.0
END DESCRIPTION:
XS GIS Cut Line= 3
      1881913.13     13922248.64      1882125.00     13921925.00
      1882125.00     13921725.03
#Sta/Elev= 30
  4613.2 1985.64  4624.6 1985.45  4639.7 1983.67  4645.7 1981.69  4675.9 1979.65
  4733.2 1973.48  4811.5 1958.39  4832.7 1956.72  4847.7 1953.26  4862.8 1947.34
  4892.5 1939.15  4899.0 1935.91  4920.1 1931.38  4935.2 1921.24  4941.2 1920.34
  4950.3 1916.33  4956.3 1916.19  4971.4 1909.24  4977.4 1908.98  4984.5 1906.97
  4984.7 1906.47  4988.5 1906.97  5010.0 1908.30  5030.0 1911.10  5040.0 1913.72
  5080.0 1929.45  5130.0 1943.34  5160.0 1953.78  5180.0 1957.71  5200.0 1959.41
#Mann=3,-1,0
  4613.2     0.1       0  4984.5    0.05       0  4988.5     0.1       0
Bank Sta=4984.5,4988.5
Exp/Cntr=0.3,0.1

Type RM Length L Ch R = 1,1008,488,488,488
BEGIN DESCRIPTION:
Stream0448 2.0
END DESCRIPTION:
XS GIS Cut Line= 3
      1882555.71     13922207.72      1882575.00     13921875.00
      1882575.00     13921724.98
#Sta/Elev= 30
  4666.7 1954.54  4679.4 1954.12  4729.5 1945.08  4789.6 1939.54  4849.7 1932.27
  4869.8 1927.44  4881.9 1921.70  4883.4 1921.15  4899.8 1915.21  4909.2 1913.22
  4914.2 1913.30  4919.8 1910.89  4929.9 1908.07  4939.9 1906.55  4979.9 1904.46
  4990.0 1902.99  4997.5 1898.83  5002.5 1898.83  5010.0 1895.06  5018.0 1892.40
  5018.2 1891.90  5022.0 1892.40  5030.0 1893.17  5040.0 1901.73  5050.0 1909.16
  5080.0 1924.08  5130.0 1947.10  5140.0 1952.28  5147.5 1957.00  5150.0 1957.00
#Mann=5,-1,0
  4666.7     0.1       0  4881.9    0.07       0  4883.4     0.1       0
  5018.0    0.05       0  5022.0     0.1       0
Bank Sta=5018,5022
Exp/Cntr=0.3,0.1

Type RM Length L Ch R = 1,520,235,235,235
BEGIN DESCRIPTION:
Stream0448 1.0
END DESCRIPTION:
XS GIS Cut Line= 3
      1882824.98     13922275.03      1883025.00     13921975.00
      1883075.00     13921825.00
#Sta/Elev= 30
  4635.1 1955.96  4663.7 1953.07  4671.2 1949.06  4678.7 1947.04  4714.8 1939.35
  4771.8 1929.31  4807.9 1919.24  4839.4 1912.32  4844.0 1910.80  4895.0 1902.35
  4967.1 1895.40  4982.2 1893.13  4988.2 1891.53  4992.7 1888.11  4998.3 1888.11
  5006.2 1884.91  5016.8 1883.44  5025.3 1883.44  5025.6 1882.94  5029.3 1883.44
  5037.9 1889.69  5041.4 1894.70  5048.4 1904.73  5058.9 1909.46  5069.5 1912.99
  5080.0 1918.55  5101.1 1926.94  5111.6 1930.85  5132.7 1935.75  5153.8 1938.56
#Mann=5,-1,0
  4635.1     0.1       0  4839.4    0.07       0  5025.3    0.05       0
  5029.3    0.07       0  5041.4     0.1       0
Bank Sta=5025.3,5029.3
Exp/Cntr=0.3,0.1

Type RM Length L Ch R = 1,285,0,0,0
BEGIN DESCRIPTION:
Stream0448 0.0
END DESCRIPTION:
XS GIS Cut Line= 3
      1883110.78     13922506.95      1883237.99     13922034.26
      1883145.68     13921771.09
#Sta/Elev= 30
  4554.4 1962.30  4608.2 1961.48  4671.2 1957.18  4711.8 1947.43  4763.5 1938.70
  4794.6 1931.95  4815.3 1925.92  4820.6 1921.17  4860.6 1909.38  4867.1 1906.19
  4924.5 1896.28  4940.5 1892.52  4970.1 1888.52  4999.7 1880.90  5000.0 1880.40
  5003.7 1880.90  5022.4 1880.97  5032.8 1883.07  5040.9 1892.78  5046.2 1892.78
  5053.7 1898.83  5063.5 1902.74  5068.8 1901.20  5094.5 1909.59  5099.8 1908.35
  5111.9 1911.91  5125.5 1914.27  5161.8 1917.09  5255.1 1932.92  5322.8 1938.49
#Mann=5,-1,0
  4554.4     0.1       0  4924.5    0.07       0  4999.7    0.05       0
  5003.7    0.07       0  5111.9     0.1       0
Bank Sta=4999.7,5003.7
Exp/Cntr=0.3,0.1

Chan Stop Cuts=-1