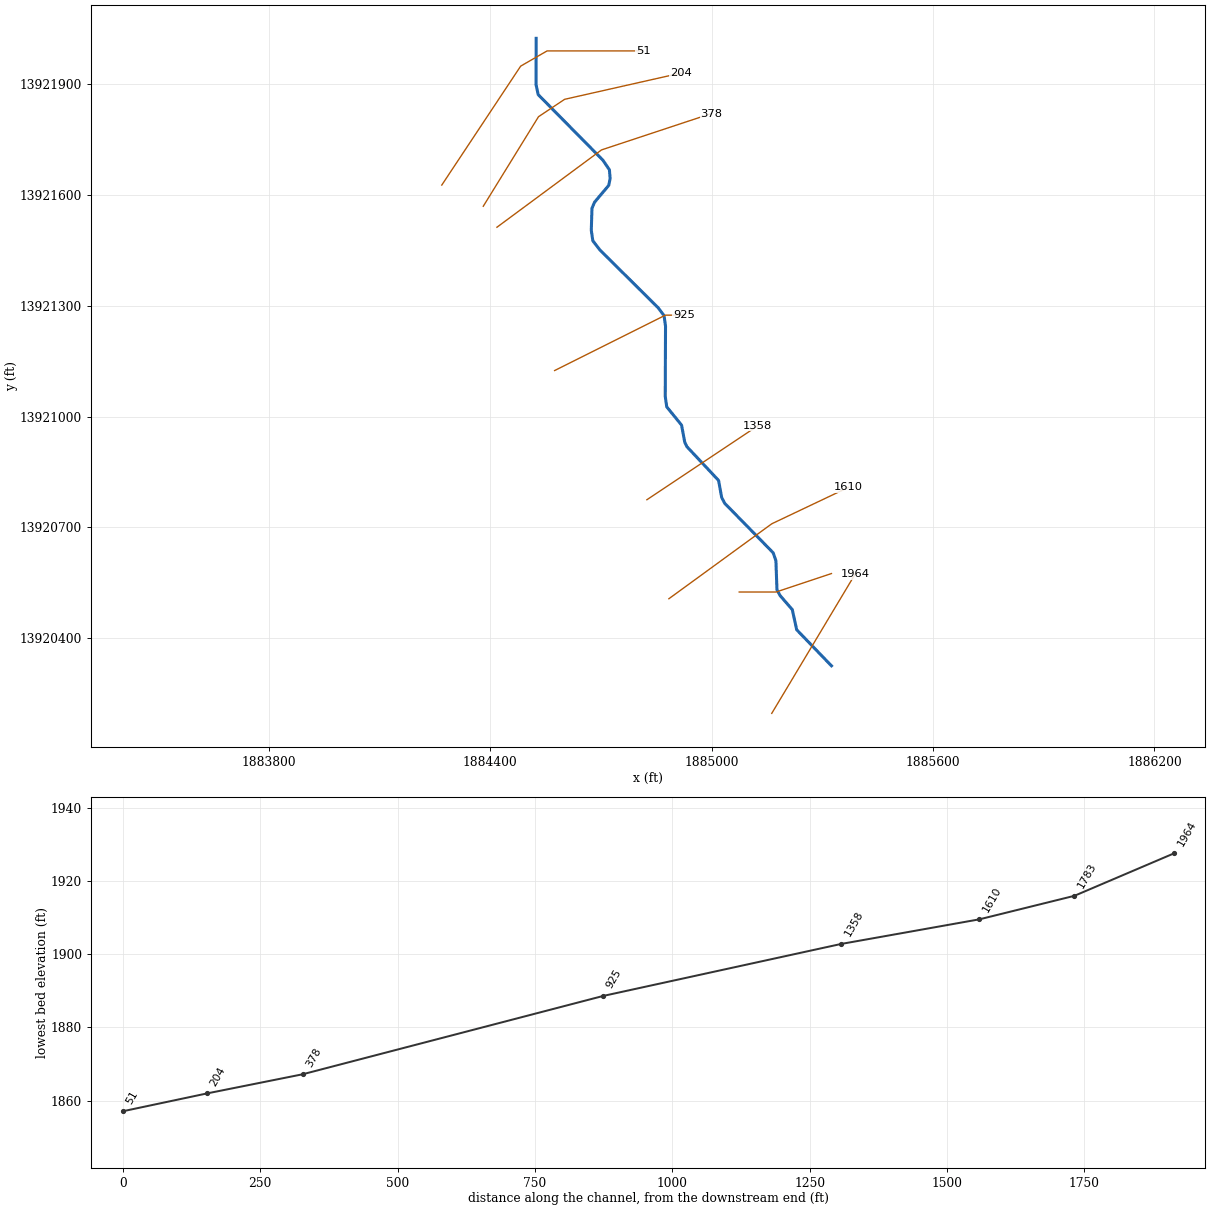
--- Stream0449.prj (project) ---

Proj Title=Stream0449 Base Level Engineering
Current Plan=p01
Default Exp/Contr=0.3,0.1
English Units
Geom File=g01
Flow File=f01
Plan File=p01
BEGIN DESCRIPTION:
Stream0449
END DESCRIPTION:

--- Stream0449.p01 (plan) ---

Plan Title=Multiple Run
Short Identifier=Multiple
Geom File=g01
Flow File=f01
Subcritical Flow
K Sum by GR= 0
Std Step Tol= 0.01
Critical Tol= 0.01
Num of Std Step Trials= 20
Max Error Tol= 0.3
Flow Tol Ratio= 0.001
Split Flow NTrial= 30
Split Flow Tol= 0.02
Split Flow Ratio= 0.02
Log Output Level= 0
Friction Slope Method= 1
Unsteady Friction Slope Method= 2
Unsteady Bridges Friction Slope Method= 1
Parabolic Critical Depth
Global Vel Dist=  1 , 1 , 1
Global Log Level= 0
CheckData=True
Encroach Param= -1, 0, 0, 0
BEGIN DESCRIPTION:
Multiple Run
END DESCRIPTION:

--- Stream0449.f01 (steady flow) ---

Flow Title=Multiple
Number of Profiles=7
Profile Names=10-year,25-year,50-year,1pct_min,100-year,1pct_plu,500-year
River Rch & RM= Stream0449,Reach-1,1964
     527     867    1183     784    1564    3121    2692
Boundary for River Rch & Prof#=Stream0449,Reach-1,1
Up Type=0
Dn Type=3
Dn Slope=0.005
Boundary for River Rch & Prof#=Stream0449,Reach-1,2
Up Type=0
Dn Type=3
Dn Slope=0.005
Boundary for River Rch & Prof#=Stream0449,Reach-1,3
Up Type=0
Dn Type=3
Dn Slope=0.005
Boundary for River Rch & Prof#=Stream0449,Reach-1,4
Up Type=0
Dn Type=3
Dn Slope=0.005
Boundary for River Rch & Prof#=Stream0449,Reach-1,5
Up Type=0
Dn Type=3
Dn Slope=0.005
Boundary for River Rch & Prof#=Stream0449,Reach-1,6
Up Type=0
Dn Type=3
Dn Slope=0.005
Boundary for River Rch & Prof#=Stream0449,Reach-1,7
Up Type=0
Dn Type=3
Dn Slope=0.005

--- Stream0449.g01 (geometry) ---

Geom Title=Existing Conditions

River Reach=Stream0449,Reach-1
Reach XY= 30
      1885325.00     13920325.00      1885230.79     13920422.68
      1885218.87     13920477.17      1885185.84     13920515.35
      1885177.33     13920530.97      1885174.48     13920609.78
      1885167.14     13920631.17      1885035.78     13920765.32
      1885027.53     13920781.05      1885019.13     13920827.28
      1884933.16     13920918.95      1884927.50     13920931.04
      1884918.86     13920977.17      1884878.75     13921026.55
      1884874.64     13921054.85      1884875.43     13921245.18
      1884871.46     13921273.54      1884855.40     13921295.16
      1884697.84     13921451.48      1884678.46     13921476.50
      1884674.33     13921504.92      1884676.12     13921564.45
      1884683.14     13921581.05      1884721.66     13921626.75
      1884725.36     13921645.21      1884723.38     13921668.97
      1884705.57     13921695.09      1884530.43     13921872.54
      1884524.62     13921899.84      1884525.00     13922025.00

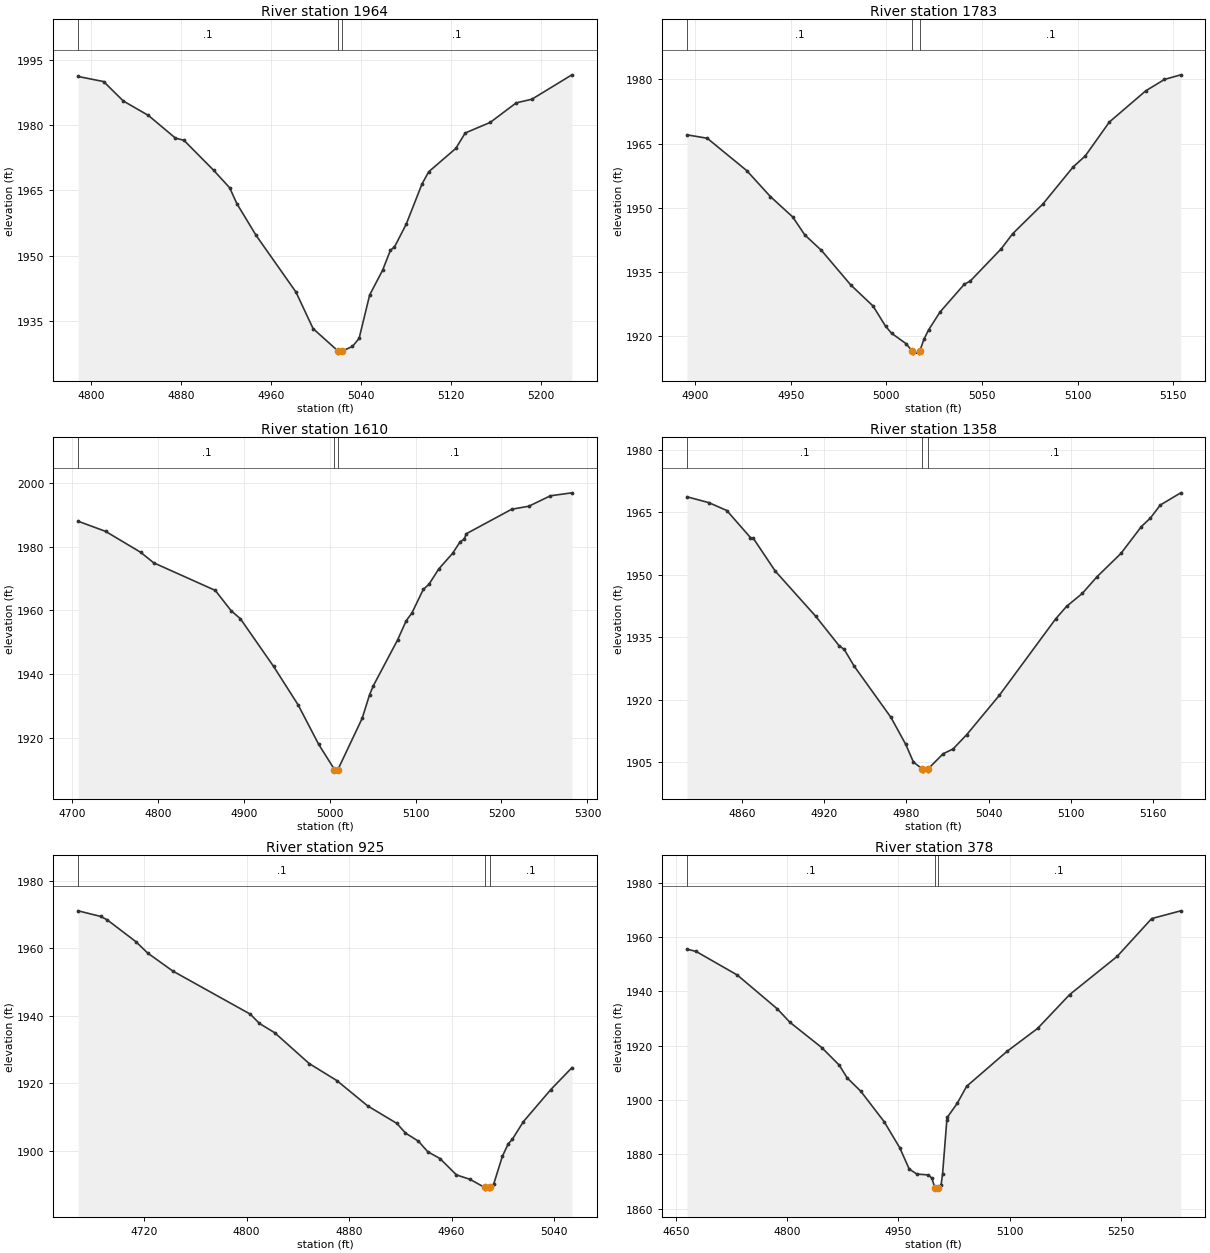
Type RM Length L Ch R = 1,1964,181,181,181
BEGIN DESCRIPTION:
Stream0449 5.0
END DESCRIPTION:
XS GIS Cut Line= 2
      1885163.24     13920196.18      1885388.90     13920573.09
#Sta/Elev= 30
  4788.5 1991.25  4811.2 1990.08  4828.7 1985.61  4851.1 1982.27  4875.1 1977.06
  4882.7 1976.55  4909.1 1969.65  4923.3 1965.64  4929.8 1961.95  4946.9 1954.65
  4982.3 1941.63  4997.6 1933.19  5019.7 1928.06  5019.9 1927.56  5023.7 1928.06
  5032.6 1929.11  5038.5 1930.95  5047.9 1940.96  5059.4 1946.64  5066.4 1951.28
  5069.9 1951.96  5080.4 1957.24  5094.4 1966.47  5100.4 1969.31  5124.5 1974.68
  5132.9 1978.24  5155.1 1980.67  5178.3 1985.18  5192.2 1986.01  5227.8 1991.63
#Mann=3,-1,0
  4788.5     0.1       0  5019.7    0.05       0  5023.7     0.1       0
Bank Sta=5019.7,5023.7
Exp/Cntr=0.3,0.1

Type RM Length L Ch R = 1,1783,173,173,173
BEGIN DESCRIPTION:
Stream0449 4.0
END DESCRIPTION:
XS GIS Cut Line= 3
      1885074.97     13920525.00      1885175.00     13920525.00
      1885324.96     13920574.99
#Sta/Elev= 30
  4895.8 1967.05  4906.4 1966.25  4927.1 1958.66  4939.4 1952.61  4951.1 1947.83
  4957.4 1943.63  4966.1 1940.01  4981.4 1931.93  4993.1 1926.98  4999.6 1922.28
  5002.8 1920.60  5010.3 1918.20  5013.5 1916.47  5013.7 1915.97  5017.2 1915.97
  5017.5 1916.47  5019.7 1919.24  5022.1 1921.40  5028.1 1925.60  5040.8 1932.10
  5043.9 1932.84  5060.1 1940.40  5066.0 1943.89  5081.9 1950.89  5097.7 1959.55
  5104.0 1962.11  5116.6 1970.05  5135.6 1977.34  5145.4 1980.01  5153.9 1981.09
#Mann=3,-1,0
  4895.8     0.1       0  5013.5    0.05       0  5017.5     0.1       0
Bank Sta=5013.5,5017.5
Exp/Cntr=0.3,0.1

Type RM Length L Ch R = 1,1610,252,252,252
BEGIN DESCRIPTION:
Mapping XS b8d6da67
END DESCRIPTION:
XS GIS Cut Line= 3
      1884884.66     13920506.83      1885163.25     13920709.80
      1885370.84     13920808.38
#Sta/Elev= 30
  4707.4 1988.04  4739.4 1984.85  4780.2 1978.28  4795.3 1974.98  4867.0 1966.31
  4885.5 1959.91  4896.2 1957.42  4934.9 1942.41  4963.5 1930.30  4987.3 1917.96
  5005.7 1910.04  5005.9 1909.54  5009.7 1910.04  5037.9 1926.12  5046.5 1933.51
  5050.8 1936.32  5079.1 1950.74  5089.0 1956.71  5095.8 1959.23  5109.0 1966.62
  5115.6 1968.23  5127.0 1973.04  5143.1 1977.95  5152.0 1981.63  5156.6 1982.35
  5159.0 1984.10  5211.9 1991.81  5231.8 1992.75  5256.9 1996.03  5281.9 1996.96
#Mann=3,-1,0
  4707.4     0.1       0  5005.7    0.05       0  5009.7     0.1       0
Bank Sta=5005.7,5009.7
Exp/Cntr=0.3,0.1

Type RM Length L Ch R = 1,1358,433,433,433
BEGIN DESCRIPTION:
Stream0449 3.0
END DESCRIPTION:
XS GIS Cut Line= 3
      1884824.98     13920774.99      1884975.00     13920875.00
      1885125.02     13920975.01
#Sta/Elev= 30
  4819.7 1968.73  4835.8 1967.31  4848.8 1965.43  4866.1 1958.92  4868.2 1958.73
  4884.2 1950.87  4913.7 1940.03  4930.8 1932.95  4934.6 1932.03  4941.7 1928.09
  4968.7 1915.70  4979.5 1909.22  4985.1 1904.97  4991.7 1903.30  4991.9 1902.80
  4995.4 1902.80  4995.7 1903.30  5006.8 1906.98  5014.0 1908.11  5024.0 1911.56
  5047.8 1921.00  5088.9 1939.36  5096.9 1942.38  5108.4 1945.50  5119.2 1949.53
  5136.6 1955.10  5151.6 1961.58  5158.2 1963.64  5165.4 1966.75  5180.3 1969.68
#Mann=3,-1,0
  4819.7     0.1       0  4991.7    0.05       0  4995.7     0.1       0
Bank Sta=4991.7,4995.7
Exp/Cntr=0.3,0.1

Type RM Length L Ch R = 1,925,547,547,547
BEGIN DESCRIPTION:
Stream0449 2.0
END DESCRIPTION:
XS GIS Cut Line= 3
      1884574.96     13921124.98      1884875.00     13921275.00
      1884925.04     13921275.00
#Sta/Elev= 30
  4668.4 1971.11  4685.9 1969.46  4691.0 1968.47  4713.4 1962.00  4722.8 1958.57
  4742.4 1953.24  4802.8 1940.48  4810.0 1937.71  4821.9 1934.96  4848.8 1925.83
  4870.4 1920.78  4894.5 1913.26  4917.3 1908.07  4924.0 1905.21  4934.1 1902.81
  4941.4 1899.67  4950.9 1897.67  4963.8 1892.80  4974.4 1891.49  4985.8 1889.09
  4986.0 1888.59  4989.5 1888.59  4989.8 1889.09  4992.9 1890.14  4999.6 1898.28
  5004.1 1901.95  5007.5 1903.43  5016.1 1908.63  5037.5 1918.13  5053.9 1924.59
#Mann=3,-1,0
  4668.4     0.1       0  4985.8    0.05       0  4989.8     0.1       0
Bank Sta=4985.8,4989.8
Exp/Cntr=0.3,0.1

Type RM Length L Ch R = 1,378,174,174,174
BEGIN DESCRIPTION:
Stream0449 1.0
END DESCRIPTION:
XS GIS Cut Line= 3
      1884418.73     13921513.22      1884702.07     13921722.74
      1884999.79     13921821.32
#Sta/Elev= 30
  4664.9 1955.55  4677.2 1954.72  4732.9 1946.01  4786.7 1933.58  4803.8 1928.62
  4846.7 1919.31  4870.3 1912.85  4881.0 1908.14  4899.4 1903.22  4930.9 1892.01
  4951.8 1882.48  4964.7 1874.57  4975.1 1872.72  4990.6 1872.41  4995.3 1871.18
  4999.2 1867.68  4999.4 1867.18  5003.2 1867.68  5007.6 1868.53  5009.7 1872.81
  5015.4 1892.54  5016.2 1893.67  5029.5 1898.81  5042.1 1905.04  5096.8 1917.96
  5137.9 1926.37  5181.1 1938.83  5245.1 1952.87  5291.7 1966.81  5330.9 1969.67
#Mann=3,-1,0
  4664.9     0.1       0  4999.2    0.05       0  5003.2     0.1       0
Bank Sta=4999.2,5003.2
Exp/Cntr=0.3,0.1

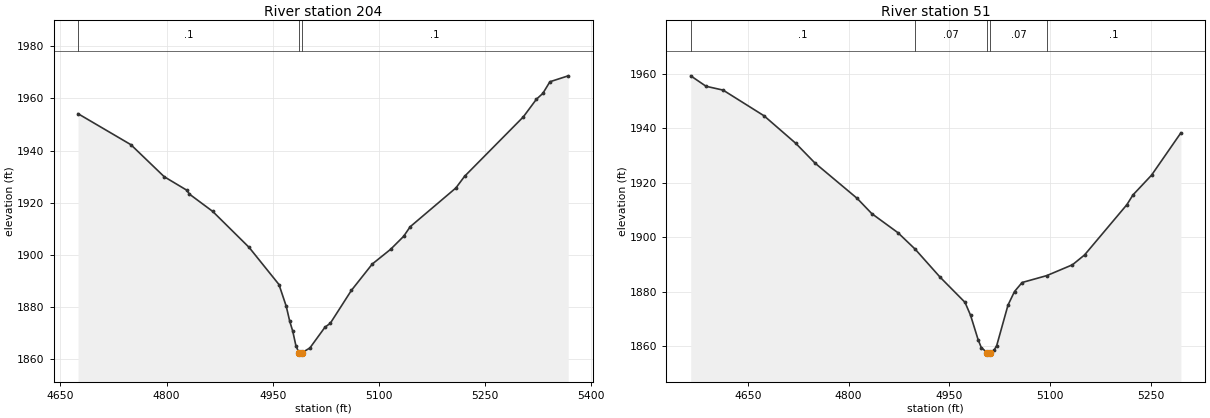
Type RM Length L Ch R = 1,204,153,153,153
BEGIN DESCRIPTION:
Stream0449 0.0
END DESCRIPTION:
XS GIS Cut Line= 4
      1884381.65     13921570.02      1884531.28     13921812.65
      1884602.14     13921859.82      1884916.45     13921930.75
#Sta/Elev= 30
  4674.9 1954.11  4749.5 1942.24  4796.6 1929.96  4828.4 1924.80  4832.3 1923.27
  4865.0 1916.68  4916.5 1902.87  4958.7 1888.63  4969.0 1880.27  4973.9 1874.55
  4978.2 1870.71  4982.6 1865.21  4987.0 1862.45  4987.3 1861.95  4991.0 1862.45
  5002.4 1864.32  5023.7 1872.28  5031.2 1873.78  5061.0 1886.39  5090.5 1896.49
  5116.3 1902.11  5134.8 1907.11  5144.0 1910.77  5208.6 1925.65  5220.9 1930.12
  5303.8 1952.88  5322.4 1959.68  5331.4 1961.89  5341.4 1966.36  5367.3 1968.63
#Mann=3,-1,0
  4674.9     0.1       0  4987.0    0.05       0  4991.0     0.1       0
Bank Sta=4987,4991
Exp/Cntr=0.3,0.1

Type RM Length L Ch R = 1,51,0,0,0
BEGIN DESCRIPTION:
Stream0449 0.1
END DESCRIPTION:
XS GIS Cut Line= 4
      1884269.26     13921627.46      1884483.00     13921949.71
      1884554.62     13921990.94      1884814.99     13921990.94
#Sta/Elev= 30
  4565.0 1959.17  4587.8 1955.34  4613.2 1953.93  4674.2 1944.50  4721.2 1934.45
  4750.0 1927.17  4812.8 1914.21  4834.5 1908.63  4873.5 1901.62  4899.0 1895.61
  4936.2 1885.32  4973.3 1876.08  4981.6 1871.32  4992.8 1862.40  4997.5 1859.51
  5006.5 1857.58  5006.7 1857.08  5010.5 1857.58  5017.0 1858.71  5020.5 1860.21
  5037.3 1875.06  5047.0 1880.04  5058.3 1883.35  5095.0 1885.88  5133.3 1889.86
  5151.3 1893.47  5214.3 1911.91  5223.3 1915.47  5251.0 1922.73  5294.7 1938.27
#Mann=5,-1,0
  4565.0     0.1       0  4899.0    0.07       0  5006.5    0.05       0
  5010.5    0.07       0  5095.0     0.1       0
Bank Sta=5006.5,5010.5
Exp/Cntr=0.3,0.1

Chan Stop Cuts=-1