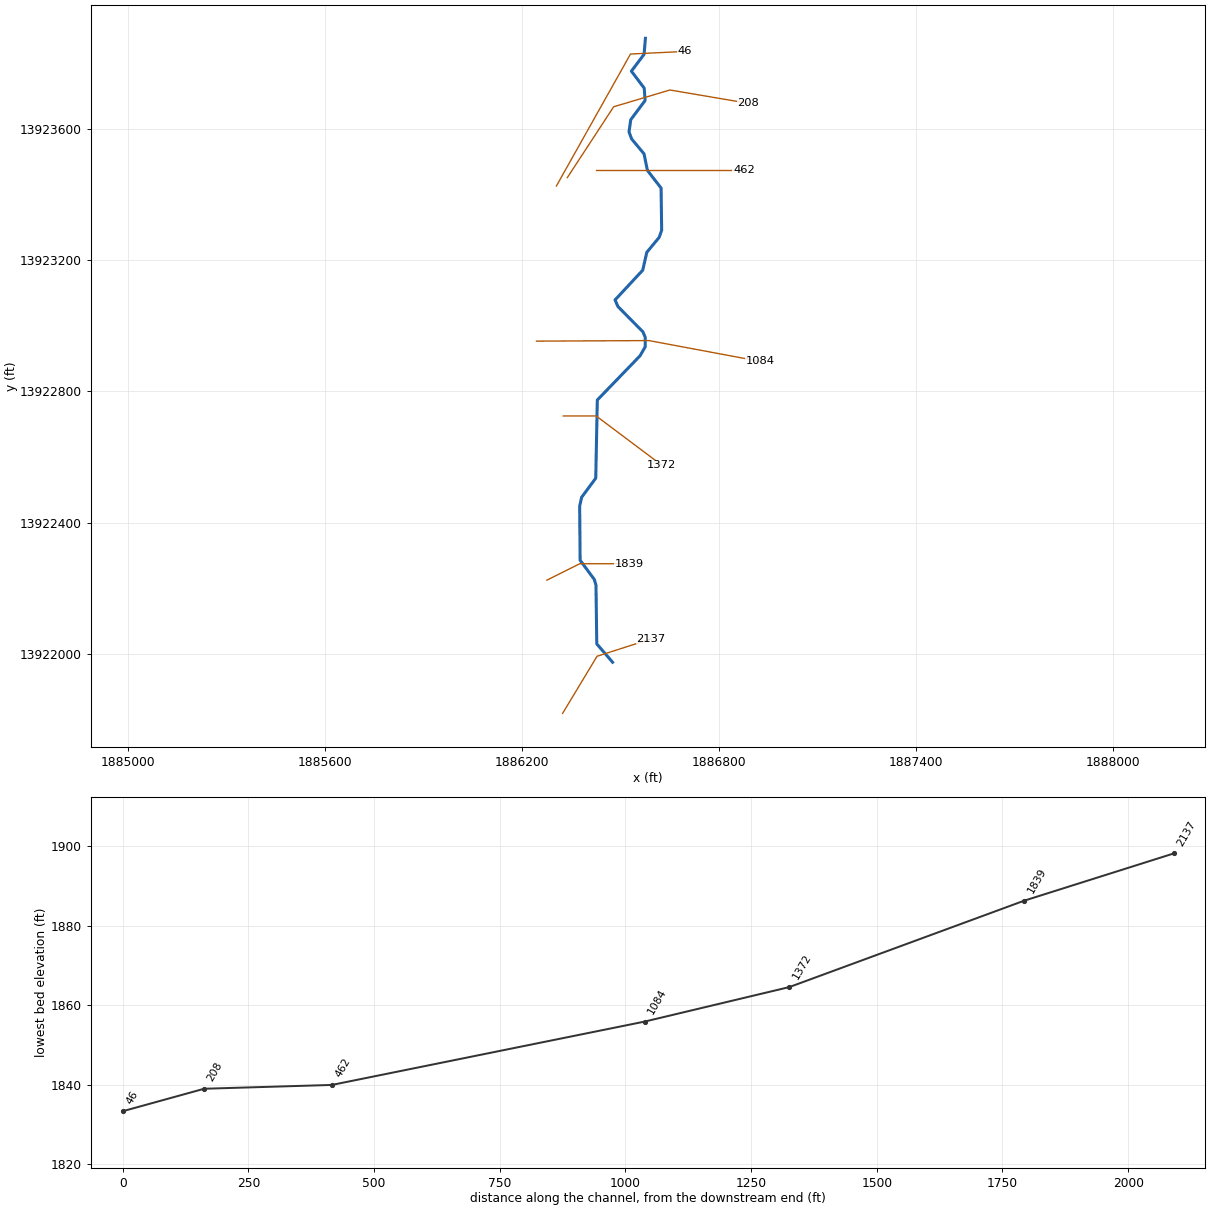
--- Stream0450.prj (project) ---

Proj Title=Stream0450 Base Level Engineering
Current Plan=p01
Default Exp/Contr=0.3,0.1
English Units
Geom File=g01
Flow File=f01
Plan File=p01
BEGIN DESCRIPTION:
Stream0450
END DESCRIPTION:

--- Stream0450.p01 (plan) ---

Plan Title=Multiple Run
Short Identifier=Multiple
Geom File=g01
Flow File=f01
Subcritical Flow
K Sum by GR= 0
Std Step Tol= 0.01
Critical Tol= 0.01
Num of Std Step Trials= 20
Max Error Tol= 0.3
Flow Tol Ratio= 0.001
Split Flow NTrial= 30
Split Flow Tol= 0.02
Split Flow Ratio= 0.02
Log Output Level= 0
Friction Slope Method= 1
Unsteady Friction Slope Method= 2
Unsteady Bridges Friction Slope Method= 1
Parabolic Critical Depth
Global Vel Dist=  1 , 1 , 1
Global Log Level= 0
CheckData=True
Encroach Param= -1, 0, 0, 0
BEGIN DESCRIPTION:
Multiple Run
END DESCRIPTION:

--- Stream0450.f01 (steady flow) ---

Flow Title=Multiple
Number of Profiles=7
Profile Names=10-year,25-year,50-year,1pct_min,100-year,1pct_plu,500-year
River Rch & RM= Stream0450,Reach-1,2137
     418     676     910     597    1191    2376    2003
Boundary for River Rch & Prof#=Stream0450,Reach-1,1
Up Type=0
Dn Type=3
Dn Slope=0.005
Boundary for River Rch & Prof#=Stream0450,Reach-1,2
Up Type=0
Dn Type=3
Dn Slope=0.005
Boundary for River Rch & Prof#=Stream0450,Reach-1,3
Up Type=0
Dn Type=3
Dn Slope=0.005
Boundary for River Rch & Prof#=Stream0450,Reach-1,4
Up Type=0
Dn Type=3
Dn Slope=0.005
Boundary for River Rch & Prof#=Stream0450,Reach-1,5
Up Type=0
Dn Type=3
Dn Slope=0.005
Boundary for River Rch & Prof#=Stream0450,Reach-1,6
Up Type=0
Dn Type=3
Dn Slope=0.005
Boundary for River Rch & Prof#=Stream0450,Reach-1,7
Up Type=0
Dn Type=3
Dn Slope=0.005

--- Stream0450.g01 (geometry) ---

Geom Title=Existing Conditions

River Reach=Stream0450,Reach-1
Reach XY= 30
      1886475.00     13921975.00      1886426.89     13922030.78
      1886424.48     13922209.78      1886419.25     13922227.33
      1886376.22     13922285.51      1886374.80     13922450.08
      1886380.75     13922477.33      1886423.78     13922535.50
      1886428.54     13922773.54      1886558.79     13922908.33
      1886574.45     13922935.64      1886574.44     13922964.36
      1886567.50     13922981.05      1886491.24     13923058.35
      1886482.61     13923078.33      1886566.82     13923168.94
      1886579.22     13923223.25      1886616.91     13923268.93
      1886624.51     13923290.22      1886622.77     13923419.07
      1886581.11     13923472.82      1886570.78     13923523.28
      1886532.77     13923569.06      1886525.08     13923590.39
      1886530.41     13923627.20      1886574.17     13923685.70
      1886571.41     13923723.36      1886532.35     13923775.03
      1886571.00     13923826.36      1886575.00     13923875.00

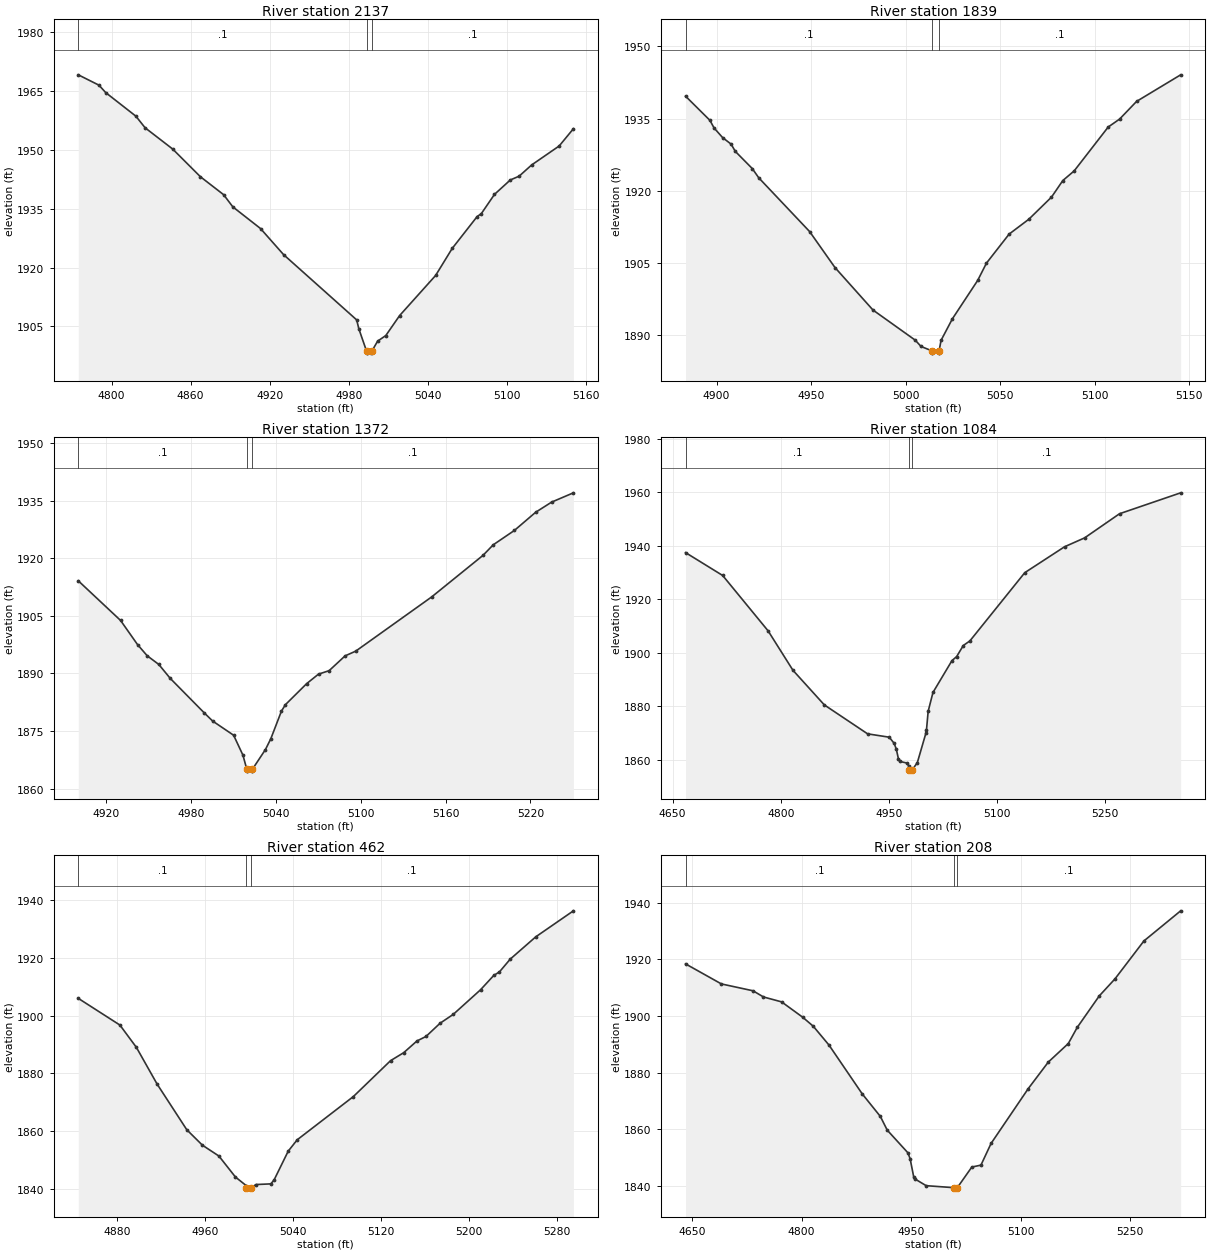
Type RM Length L Ch R = 1,2137,298,298,298
BEGIN DESCRIPTION:
Stream0450 5.0
END DESCRIPTION:
XS GIS Cut Line= 3
      1886322.87     13921819.22      1886427.75     13921993.12
      1886592.19     13922045.96
#Sta/Elev= 30
  4774.7 1969.15  4790.4 1966.51  4795.5 1964.62  4818.4 1958.61  4825.4 1955.65
  4846.4 1950.21  4867.4 1943.16  4885.0 1938.59  4892.0 1935.48  4913.0 1929.96
  4930.5 1923.31  4986.0 1906.66  4987.6 1904.43  4993.5 1898.69  4993.7 1898.19
  4997.2 1898.19  4997.5 1898.69  5001.9 1901.25  5008.1 1902.67  5018.6 1907.77
  5045.9 1917.99  5058.5 1924.89  5077.4 1933.00  5080.6 1933.76  5090.6 1938.67
  5102.6 1942.34  5109.3 1943.31  5118.8 1946.17  5139.7 1951.01  5150.5 1955.41
#Mann=3,-1,0
  4774.7     0.1       0  4993.5    0.05       0  4997.5     0.1       0
Bank Sta=4993.5,4997.5
Exp/Cntr=0.3,0.1

Type RM Length L Ch R = 1,1839,467,467,467
BEGIN DESCRIPTION:
Stream0450 4.0
END DESCRIPTION:
XS GIS Cut Line= 3
      1886274.98     13922224.99      1886375.00     13922275.00
      1886524.97     13922275.00
#Sta/Elev= 30
  4883.6 1939.67  4896.5 1934.64  4898.7 1933.05  4903.2 1931.06  4907.7 1929.70
  4909.9 1928.20  4918.9 1924.62  4922.3 1922.71  4949.2 1911.54  4962.6 1904.07
  4982.7 1895.24  5005.1 1888.96  5008.1 1887.67  5013.7 1886.78  5013.9 1886.28
  5017.4 1886.28  5017.7 1886.78  5018.7 1888.93  5024.7 1893.41  5038.1 1901.40
  5042.7 1904.97  5054.7 1911.01  5065.1 1914.09  5077.1 1918.69  5083.1 1922.14
  5089.1 1924.14  5107.1 1933.26  5113.1 1934.90  5122.1 1938.58  5145.4 1944.10
#Mann=3,-1,0
  4883.6     0.1       0  5013.7    0.05       0  5017.7     0.1       0
Bank Sta=5013.7,5017.7
Exp/Cntr=0.3,0.1

Type RM Length L Ch R = 1,1372,288,288,288
BEGIN DESCRIPTION:
Stream0450 3.0
END DESCRIPTION:
XS GIS Cut Line= 3
      1886324.97     13922725.00      1886425.00     13922725.00
      1886624.97     13922575.02
#Sta/Elev= 30
  4900.4 1914.16  4930.3 1903.82  4942.3 1897.52  4949.1 1894.62  4957.3 1892.36
  4965.4 1888.72  4989.4 1879.74  4995.4 1877.59  5010.2 1873.90  5016.8 1868.69
  5019.5 1865.04  5019.7 1864.54  5023.2 1864.54  5023.5 1865.04  5032.7 1870.17
  5036.5 1872.99  5044.0 1880.18  5046.8 1881.86  5061.8 1887.34  5070.2 1889.83
  5077.7 1890.73  5089.0 1894.59  5096.5 1895.82  5150.2 1909.96  5186.5 1920.80
  5193.7 1923.54  5208.7 1927.30  5223.7 1932.03  5235.0 1934.68  5250.4 1937.10
#Mann=3,-1,0
  4900.4     0.1       0  5019.5    0.05       0  5023.5     0.1       0
Bank Sta=5019.5,5023.5
Exp/Cntr=0.3,0.1

Type RM Length L Ch R = 1,1084,622,622,622
BEGIN DESCRIPTION:
Stream0450 2.0
END DESCRIPTION:
XS GIS Cut Line= 3
      1886243.38     13922952.84      1886585.82     13922954.56
      1886924.20     13922891.24
#Sta/Elev= 30
  4667.9 1937.44  4719.4 1928.89  4782.4 1908.22  4816.9 1893.49  4860.4 1880.57
  4920.4 1869.77  4950.4 1868.52  4957.2 1866.24  4960.2 1864.07  4963.2 1860.42
  4965.4 1859.45  4974.4 1858.91  4978.1 1857.63  4978.4 1856.35  4978.6 1855.85
  4982.4 1856.35  4989.4 1859.04  5001.4 1870.15  5002.0 1871.02  5004.4 1878.18
  5011.1 1885.24  5037.4 1897.10  5043.9 1898.61  5053.1 1902.74  5062.3 1904.47
  5138.4 1929.94  5193.5 1939.60  5221.4 1942.93  5269.8 1951.94  5354.6 1959.75
#Mann=3,-1,0
  4667.9     0.1       0  4978.4    0.05       0  4982.4     0.1       0
Bank Sta=4978.4,4982.4
Exp/Cntr=0.3,0.1

Type RM Length L Ch R = 1,462,254,254,254
BEGIN DESCRIPTION:
Stream0450 1.0
END DESCRIPTION:
XS GIS Cut Line= 3
      1886425.04     13923475.00      1886575.00     13923475.00
      1886875.04     13923475.00
#Sta/Elev= 30
  4845.0 1905.98  4882.8 1896.74  4897.8 1889.01  4916.6 1876.31  4943.6 1860.48
  4957.8 1855.13  4972.8 1851.37  4987.8 1844.11  4997.6 1841.13  4997.8 1840.41
  4998.0 1839.91  5001.8 1840.41  5006.6 1841.50  5020.0 1841.73  5023.0 1843.13
  5035.8 1853.07  5044.0 1857.01  5095.0 1871.97  5128.8 1884.40  5140.8 1887.18
  5152.8 1891.23  5161.0 1892.78  5173.8 1897.36  5185.8 1900.44  5210.6 1908.96
  5222.6 1913.92  5227.8 1915.16  5237.6 1919.58  5260.8 1927.30  5295.0 1936.30
#Mann=3,-1,0
  4845.0     0.1       0  4997.8    0.05       0  5001.8     0.1       0
Bank Sta=4997.8,5001.8
Exp/Cntr=0.3,0.1

Type RM Length L Ch R = 1,208,162,162,162
BEGIN DESCRIPTION:
Stream0450 0.0
END DESCRIPTION:
XS GIS Cut Line= 4
      1886337.20     13923450.83      1886478.32     13923666.56
      1886649.71     13923717.70      1886887.45     13923677.28
#Sta/Elev= 30
  4641.1 1918.44  4690.2 1911.36  4733.5 1908.94  4747.8 1906.76  4772.6 1905.03
  4801.6 1899.59  4816.0 1896.42  4837.5 1889.78  4883.1 1872.52  4907.8 1864.60
  4917.2 1859.77  4945.4 1851.80  4948.5 1849.73  4953.6 1843.08  4954.7 1842.61
  4970.5 1840.17  5009.1 1839.45  5009.3 1838.95  5013.1 1839.45  5033.0 1846.74
  5045.5 1847.42  5059.4 1855.09  5110.3 1874.43  5137.7 1883.78  5165.1 1890.33
  5177.3 1896.01  5207.5 1907.14  5229.0 1913.15  5268.6 1926.53  5318.9 1937.16
#Mann=3,-1,0
  4641.1     0.1       0  5009.1    0.05       0  5013.1     0.1       0
Bank Sta=5009.1,5013.1
Exp/Cntr=0.3,0.1

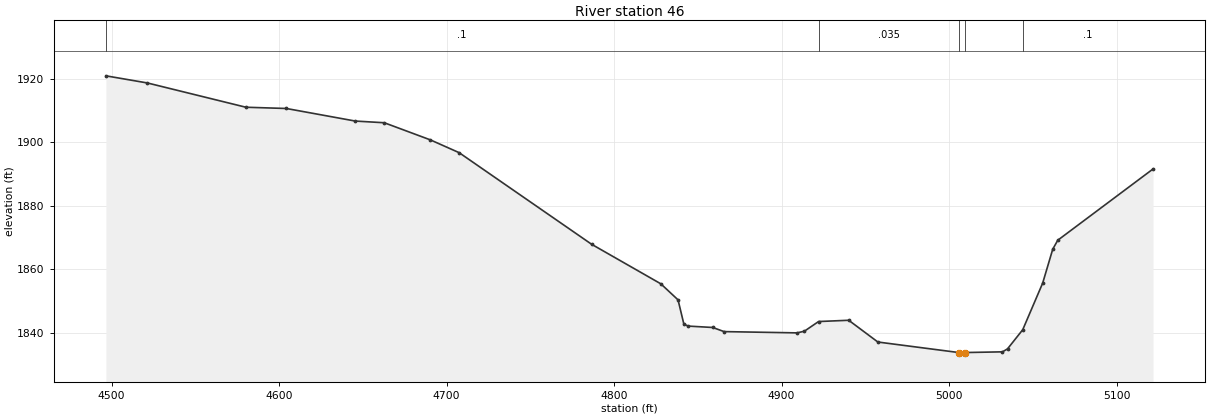
Type RM Length L Ch R = 1,46,0,0,0
BEGIN DESCRIPTION:
Stream0450 0.1
END DESCRIPTION:
XS GIS Cut Line= 3
      1886303.92     13923425.29      1886529.62     13923827.20
      1886693.68     13923835.02
#Sta/Elev= 30
  4496.6 1920.90  4521.4 1918.65  4580.2 1911.01  4604.3 1910.62  4645.5 1906.66
  4662.8 1906.13  4690.3 1900.74  4707.5 1896.71  4786.6 1867.87  4827.9 1855.43
  4838.2 1850.37  4841.7 1842.68  4844.4 1842.11  4858.9 1841.68  4865.7 1840.38
  4909.2 1839.98  4913.6 1840.50  4922.1 1843.55  4940.1 1843.95  4957.5 1837.10
  5005.8 1833.79  5006.1 1833.29  5009.8 1833.79  5031.9 1834.01  5034.9 1834.94
  5044.0 1840.98  5055.9 1855.65  5061.9 1866.31  5064.9 1869.14  5121.8 1891.58
#Mann=5,-1,0
  4496.6     0.1       0  4922.1   0.035       0  5005.8   0.035       0
  5009.8   0.035       0  5044.0     0.1       0
Bank Sta=5005.8,5009.8
Exp/Cntr=0.3,0.1

Chan Stop Cuts=-1