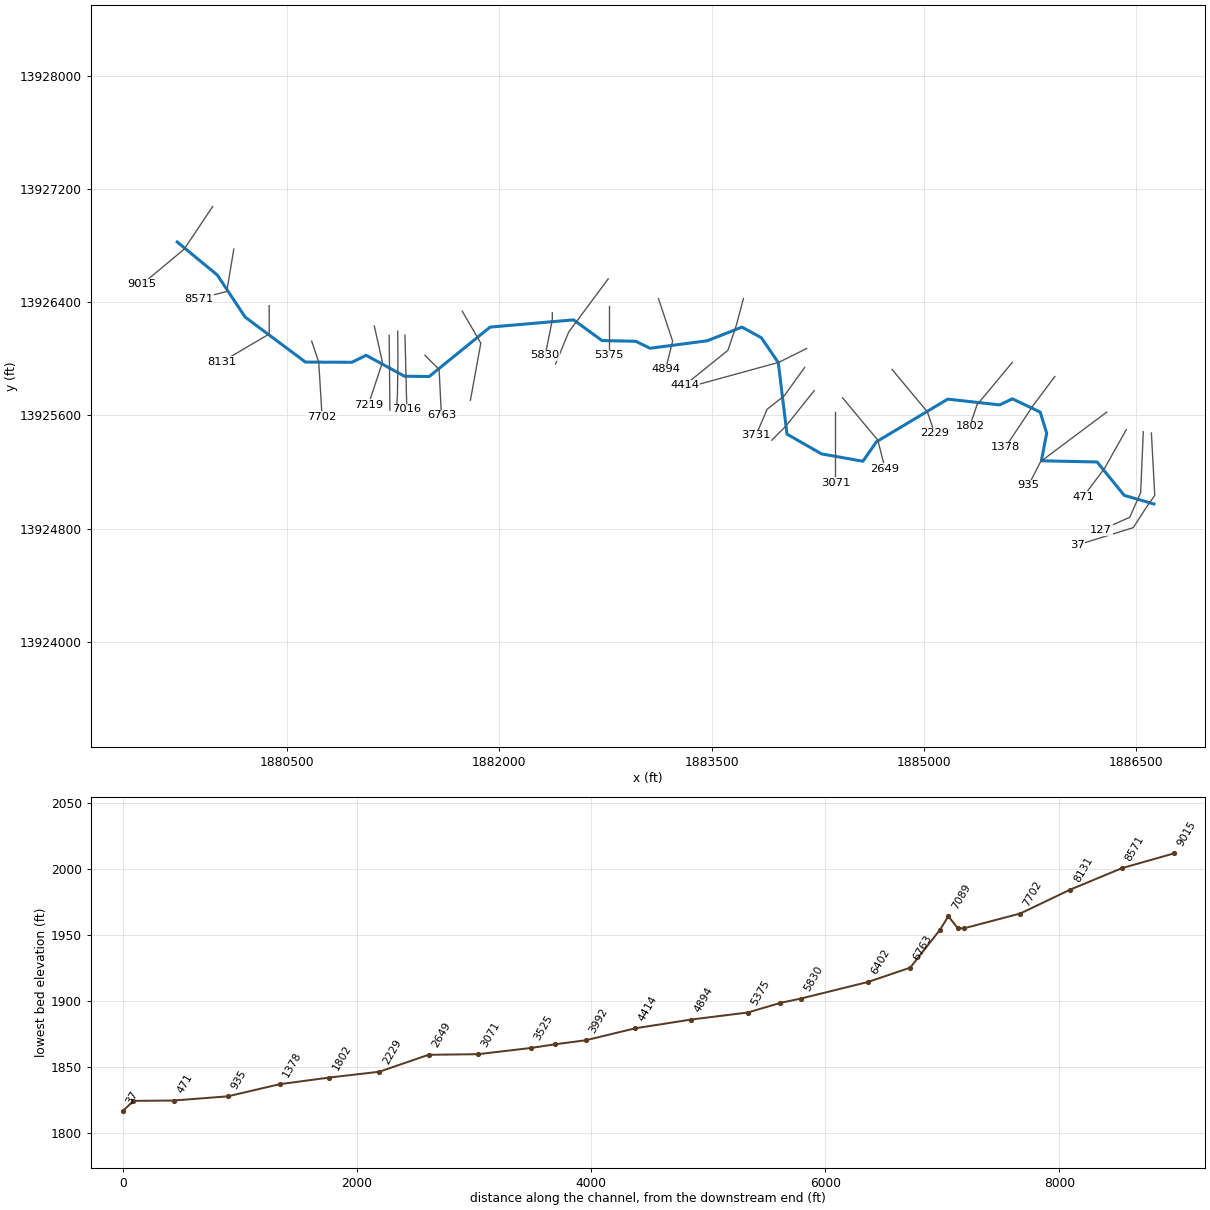
--- Stream0451.prj (project) ---

Proj Title=Stream0451 Base Level Engineering
Current Plan=p01
Default Exp/Contr=0.3,0.1
English Units
Geom File=g01
Flow File=f01
Plan File=p01
BEGIN DESCRIPTION:
Stream0451
END DESCRIPTION:

--- Stream0451.p01 (plan) ---

Plan Title=Multiple Run
Short Identifier=Multiple
Geom File=g01
Flow File=f01
Subcritical Flow
K Sum by GR= 0
Std Step Tol= 0.01
Critical Tol= 0.01
Num of Std Step Trials= 20
Max Error Tol= 0.3
Flow Tol Ratio= 0.001
Split Flow NTrial= 30
Split Flow Tol= 0.02
Split Flow Ratio= 0.02
Log Output Level= 0
Friction Slope Method= 1
Unsteady Friction Slope Method= 2
Unsteady Bridges Friction Slope Method= 1
Parabolic Critical Depth
Global Vel Dist=  1 , 1 , 1
Global Log Level= 0
CheckData=True
Encroach Param= -1, 0, 0, 0
BEGIN DESCRIPTION:
Multiple Run
END DESCRIPTION:

--- Stream0451.f01 (steady flow) ---

Flow Title=Multiple
Number of Profiles=7
Profile Names=10-year,25-year,50-year,1pct_min,100-year,1pct_plu,500-year
River Rch & RM= Stream0451,Reach-1,9015
     818    1383    1917    1289    2571    5130    4561
River Rch & RM= Stream0451,Reach-1,5655
    1183    2045    2877    1958    3907    7795    7116
River Rch & RM= Stream0451,Reach-1,3731
    1467    2559    3621    2476    4940    9856    9084
Boundary for River Rch & Prof#=Stream0451,Reach-1,1
Up Type=0
Dn Type=3
Dn Slope=0.005
Boundary for River Rch & Prof#=Stream0451,Reach-1,2
Up Type=0
Dn Type=3
Dn Slope=0.005
Boundary for River Rch & Prof#=Stream0451,Reach-1,3
Up Type=0
Dn Type=3
Dn Slope=0.005
Boundary for River Rch & Prof#=Stream0451,Reach-1,4
Up Type=0
Dn Type=3
Dn Slope=0.005
Boundary for River Rch & Prof#=Stream0451,Reach-1,5
Up Type=0
Dn Type=3
Dn Slope=0.005
Boundary for River Rch & Prof#=Stream0451,Reach-1,6
Up Type=0
Dn Type=3
Dn Slope=0.005
Boundary for River Rch & Prof#=Stream0451,Reach-1,7
Up Type=0
Dn Type=3
Dn Slope=0.005

--- Stream0451.g01 (geometry) ---

Geom Title=Existing Conditions

River Reach=Stream0451,Reach-1
Reach XY= 30
      1879725.00     13926825.00      1880008.36     13926591.71
      1880204.87     13926294.77      1880630.85     13925977.06
      1880959.79     13925975.54      1881059.61     13926024.91
      1881330.86     13925877.06      1881505.02     13925874.96
      1881935.43     13926223.95      1882525.00     13926275.00
      1882726.55     13926128.75      1882964.50     13926123.78
      1883064.83     13926074.50      1883469.07     13926127.24
      1883714.46     13926223.92      1883851.88     13926148.73
      1883971.26     13925973.45      1884032.68     13925468.48
      1884276.50     13925328.62      1884569.13     13925276.58
      1884665.01     13925414.35      1885168.45     13925715.42
      1885535.20     13925674.59      1885625.00     13925717.44
      1885821.49     13925623.75      1885867.44     13925475.00
      1885829.99     13925280.00      1886223.55     13925271.47
      1886415.29     13925035.75      1886625.00     13924975.00

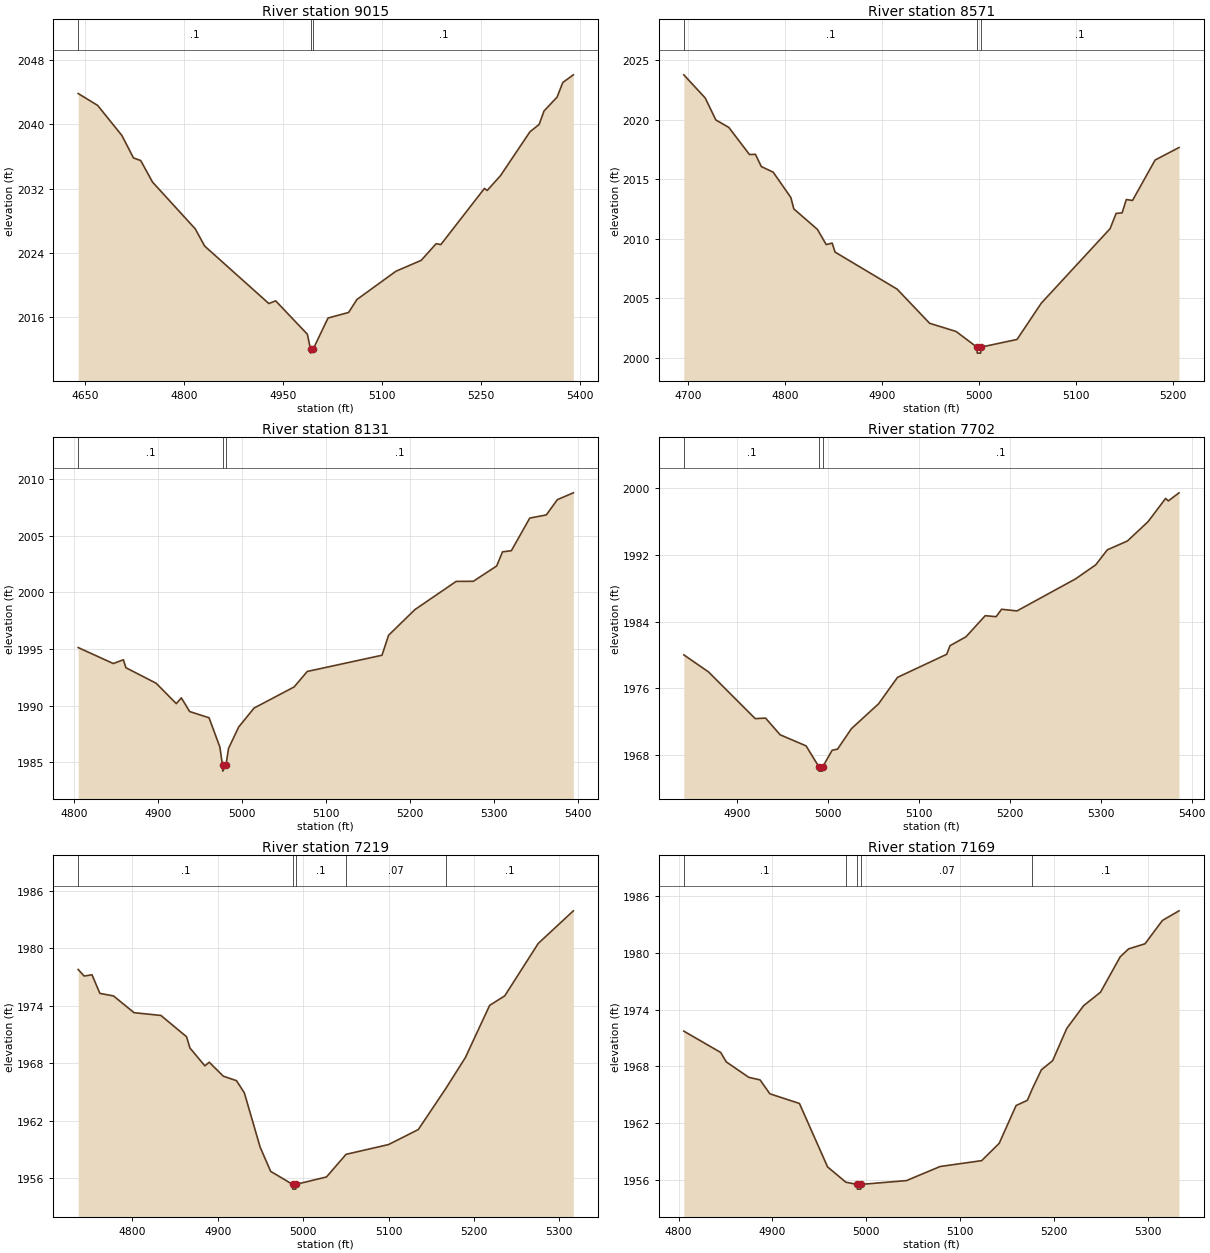
Type RM Length L Ch R = 1,9015,444,444,444
BEGIN DESCRIPTION:
Stream0451 20.0
END DESCRIPTION:
XS GIS Cut Line= 3
      1879975.00     13927075.01      1879775.00     13926775.00
      1879474.98     13926524.98
#Sta/Elev= 30
  4639.4 2043.80  4669.0 2042.32  4705.7 2038.59  4723.3 2035.80  4734.2 2035.48
  4752.2 2032.80  4817.1 2026.98  4831.2 2024.86  4928.6 2017.72  4939.0 2018.05
  4987.0 2013.91  4991.8 2012.06  4992.0 2011.56  4995.8 2012.06  5018.4 2015.92
  5049.6 2016.61  5062.2 2018.22  5121.4 2021.73  5159.7 2023.08  5182.4 2025.15
  5189.5 2025.04  5255.6 2032.01  5259.8 2031.76  5280.0 2033.60  5324.6 2039.04
  5338.6 2039.96  5346.0 2041.63  5365.8 2043.35  5374.5 2045.17  5390.5 2046.12
#Mann=3,-1,0
  4639.4     0.1       0  4991.8    0.05       0  4995.8     0.1       0
Bank Sta=4991.8,4995.8
Exp/Cntr=0.3,0.1

Type RM Length L Ch R = 1,8571,440,440,440
BEGIN DESCRIPTION:
Stream0451 19.0
END DESCRIPTION:
XS GIS Cut Line= 3
      1880125.00     13926774.97      1880075.00     13926475.00
      1879874.97     13926424.99
#Sta/Elev= 30
  4695.9 2023.77  4718.0 2021.82  4728.9 2019.98  4742.3 2019.35  4763.6 2017.07
  4769.7 2017.09  4775.8 2016.06  4788.0 2015.59  4806.2 2013.46  4809.3 2012.50
  4833.6 2010.78  4842.7 2009.50  4848.8 2009.63  4851.8 2008.87  4915.7 2005.76
  4949.2 2002.89  4976.5 2002.20  4998.0 2000.88  4998.3 2000.38  5001.8 2000.38
  5002.0 2000.88  5039.3 2001.53  5064.3 2004.58  5135.2 2010.84  5141.4 2012.12
  5147.6 2012.17  5151.9 2013.29  5158.3 2013.21  5181.6 2016.61  5206.2 2017.66
#Mann=3,-1,0
  4695.9     0.1       0  4998.0    0.05       0  5002.0     0.1       0
Bank Sta=4998,5002
Exp/Cntr=0.3,0.1

Type RM Length L Ch R = 1,8131,429,429,429
BEGIN DESCRIPTION:
Stream0451 18.0
END DESCRIPTION:
XS GIS Cut Line= 3
      1880375.00     13926374.98      1880375.00     13926175.00
      1880039.17     13925977.84
#Sta/Elev= 30
  4804.8 1995.13  4846.6 1993.72  4858.6 1994.05  4861.6 1993.35  4897.6 1991.98
  4921.6 1990.18  4927.6 1990.69  4937.5 1989.48  4960.6 1988.93  4973.5 1986.34
  4976.6 1984.72  4976.9 1984.22  4980.6 1984.72  4983.8 1986.23  4995.8 1988.11
  5014.2 1989.79  5061.8 1991.65  5077.5 1993.02  5166.4 1994.45  5174.3 1996.22
  5205.6 1998.48  5254.7 2000.97  5275.1 2000.98  5302.9 2002.33  5309.9 2003.58
  5320.4 2003.68  5342.3 2006.56  5362.0 2006.84  5375.2 2008.19  5394.2 2008.79
#Mann=3,-1,0
  4804.8     0.1       0  4976.6    0.05       0  4980.6     0.1       0
Bank Sta=4976.6,4980.6
Exp/Cntr=0.3,0.1

Type RM Length L Ch R = 1,7702,483,483,483
BEGIN DESCRIPTION:
Stream0451 17.0
END DESCRIPTION:
XS GIS Cut Line= 3
      1880675.00     13926125.00      1880725.00     13925975.00
      1880748.59     13925589.53
#Sta/Elev= 30
  4841.8 1980.01  4869.0 1977.96  4920.3 1972.36  4931.7 1972.42  4947.7 1970.42
  4976.2 1969.09  4990.4 1966.56  4990.6 1966.06  4994.1 1966.06  4994.4 1966.56
  5004.8 1968.56  5010.8 1968.70  5026.0 1971.15  5055.9 1974.14  5076.7 1977.31
  5130.8 1980.08  5134.4 1981.11  5152.0 1982.18  5173.1 1984.71  5185.1 1984.59
  5191.1 1985.48  5208.0 1985.28  5272.3 1989.12  5294.5 1990.80  5307.3 1992.61
  5329.4 1993.67  5352.1 1995.99  5371.4 1998.78  5374.4 1998.48  5386.1 1999.45
#Mann=3,-1,0
  4841.8     0.1       0  4990.4    0.05       0  4994.4     0.1       0
Bank Sta=4990.4,4994.4
Exp/Cntr=0.3,0.1

Type RM Length L Ch R = 1,7219,50,50,50
BEGIN DESCRIPTION:
Stream0451 16.0
END DESCRIPTION:
XS GIS Cut Line= 3
      1881117.39     13926231.98      1881175.00     13925975.00
      1881074.99     13925674.98
#Sta/Elev= 30
  4736.7 1977.80  4743.7 1977.11  4752.9 1977.24  4762.1 1975.30  4778.1 1975.03
  4802.1 1973.28  4833.6 1972.99  4863.6 1970.76  4867.5 1969.59  4885.0 1967.72
  4890.1 1968.10  4906.6 1966.64  4922.0 1966.17  4931.2 1964.90  4949.7 1959.22
  4962.0 1956.69  4987.6 1955.33  4987.9 1954.83  4991.4 1954.83  4991.6 1955.33
  5027.3 1956.10  5050.3 1958.47  5100.0 1959.49  5134.8 1961.06  5166.7 1965.31
  5189.8 1968.57  5218.3 1974.04  5236.0 1975.04  5275.2 1980.52  5316.3 1983.93
#Mann=5,-1,0
  4736.7     0.1       0  4987.6    0.05       0  4991.6     0.1       0
  5050.3    0.07       0  5166.7     0.1       0
Bank Sta=4987.6,4991.6
Exp/Cntr=0.3,0.1

Type RM Length L Ch R = 1,7169,80,80,80
BEGIN DESCRIPTION:
Mapping XS c452a1b3
END DESCRIPTION:
XS GIS Cut Line= 2
      1881222.42     13926165.45      1881227.68     13925637.47
#Sta/Elev= 30
  4805.5 1971.73  4844.8 1969.48  4850.8 1968.48  4874.8 1966.85  4886.8 1966.58
  4897.3 1965.11  4928.8 1964.09  4958.8 1957.39  4978.3 1955.77  4990.4 1955.54
  4990.6 1955.04  4994.1 1955.04  4994.4 1955.54  5042.9 1955.94  5078.8 1957.43
  5123.1 1958.05  5141.8 1959.88  5159.8 1963.87  5171.8 1964.42  5177.1 1965.64
  5186.8 1967.65  5198.8 1968.61  5213.8 1972.01  5231.8 1974.42  5249.8 1975.84
  5270.8 1979.58  5279.8 1980.42  5297.3 1980.96  5315.8 1983.42  5333.5 1984.44
#Mann=5,-1,0
  4805.5     0.1       0  4978.3    0.07       0  4990.4    0.05       0
  4994.4    0.07       0  5177.1     0.1       0
Bank Sta=4990.4,4994.4
Exp/Cntr=0.3,0.1

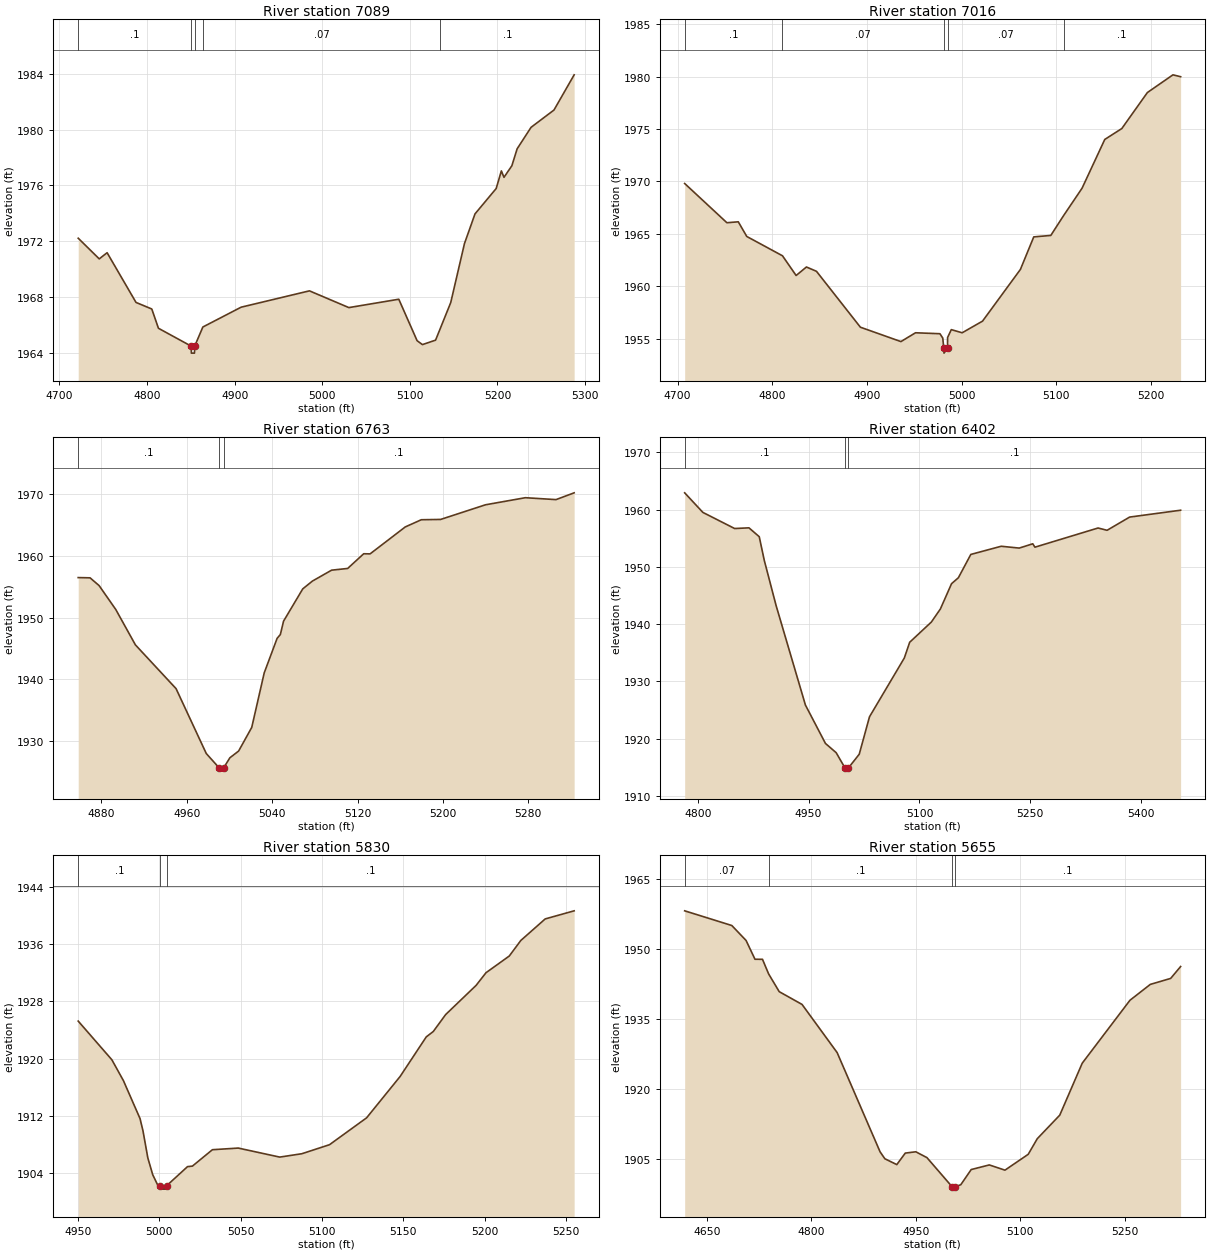
Type RM Length L Ch R = 1,7089,73,73,73
BEGIN DESCRIPTION:
Stream0451 16.1
END DESCRIPTION:
XS GIS Cut Line= 4
      1881282.66     13926195.13      1881284.39     13926000.67
      1881280.92     13925752.41      1881273.98     13925629.16
#Sta/Elev= 30
  4721.4 1972.22  4745.4 1970.74  4754.4 1971.18  4787.4 1967.62  4805.4 1967.15
  4813.0 1965.77  4850.4 1964.49  4850.6 1963.99  4854.1 1963.99  4854.4 1964.49
  4863.7 1965.86  4907.4 1967.28  4985.4 1968.45  5030.4 1967.25  5087.4 1967.85
  5108.3 1964.88  5114.4 1964.60  5129.4 1964.92  5135.0 1965.79  5146.7 1967.61
  5162.4 1971.84  5174.4 1973.96  5198.6 1975.78  5204.5 1977.04  5207.5 1976.58
  5216.5 1977.41  5222.5 1978.62  5238.4 1980.16  5264.6 1981.40  5287.6 1983.92
#Mann=5,-1,0
  4721.4     0.1       0  4850.4    0.05       0  4854.4     0.1       0
  4863.7    0.07       0  5135.0     0.1       0
Bank Sta=4850.4,4854.4
Exp/Cntr=0.3,0.1

Type RM Length L Ch R = 1,7016,253,253,253
BEGIN DESCRIPTION:
Mapping XS b39148f4
END DESCRIPTION:
XS GIS Cut Line= 2
      1881333.99     13926167.70      1881347.03     13925644.06
#Sta/Elev= 30
  4707.5 1969.80  4752.1 1966.06  4764.1 1966.15  4773.1 1964.75  4810.8 1962.91
  4825.2 1961.03  4836.1 1961.84  4846.7 1961.43  4893.1 1956.10  4935.9 1954.73
  4951.3 1955.57  4977.1 1955.48  4980.1 1955.06  4981.1 1954.13  4981.4 1953.63
  4985.1 1954.13  4985.2 1955.12  4989.1 1955.87  5000.6 1955.57  5022.1 1956.68
  5062.1 1961.61  5076.2 1964.71  5094.2 1964.85  5107.7 1966.74  5127.2 1969.35
  5151.2 1974.00  5169.2 1975.04  5196.2 1978.47  5223.2 1980.16  5231.3 1979.98
#Mann=5,-1,0
  4707.5     0.1       0  4810.8    0.07       0  4981.1    0.05       0
  4985.1    0.07       0  5107.7     0.1       0
Bank Sta=4981.1,4985.1
Exp/Cntr=0.3,0.1

Type RM Length L Ch R = 1,6763,361,361,361
BEGIN DESCRIPTION:
Stream0451 15.0
END DESCRIPTION:
XS GIS Cut Line= 3
      1881474.97     13926025.03      1881575.00     13925925.00
      1881591.50     13925602.19
#Sta/Elev= 30
  4858.2 1956.48  4869.3 1956.44  4877.8 1955.18  4893.4 1951.31  4911.8 1945.58
  4949.9 1938.49  4978.2 1927.98  4990.4 1925.63  4990.6 1925.13  4994.4 1925.63
  5000.3 1927.29  5008.5 1928.38  5020.8 1932.21  5032.5 1941.05  5044.6 1946.65
  5047.6 1947.25  5050.6 1949.42  5068.6 1954.65  5077.6 1955.91  5095.6 1957.68
  5110.7 1957.96  5125.7 1960.34  5131.7 1960.32  5164.7 1964.69  5179.7 1965.85
  5197.8 1965.90  5239.8 1968.27  5277.2 1969.42  5305.9 1969.11  5322.9 1970.21
#Mann=3,-1,0
  4858.2     0.1       0  4990.4    0.05       0  4994.4     0.1       0
Bank Sta=4990.4,4994.4
Exp/Cntr=0.3,0.1

Type RM Length L Ch R = 1,6402,572,572,572
BEGIN DESCRIPTION:
Stream0451 14.0
END DESCRIPTION:
XS GIS Cut Line= 3
      1881738.66     13926336.38      1881869.83     13926110.78
      1881796.43     13925707.27
#Sta/Elev= 30
  4782.3 1962.95  4806.9 1959.53  4849.9 1956.71  4869.3 1956.83  4883.2 1955.28
  4890.1 1951.10  4906.0 1943.25  4945.7 1925.85  4972.8 1919.14  4987.3 1917.52
  4999.5 1914.80  4999.8 1914.30  5003.5 1914.80  5018.5 1917.25  5032.4 1923.80
  5079.5 1934.07  5086.8 1936.83  5116.1 1940.36  5128.3 1942.64  5143.4 1947.06
  5152.7 1948.11  5169.5 1952.18  5210.6 1953.61  5235.0 1953.29  5253.3 1954.04
  5256.3 1953.45  5341.7 1956.80  5353.9 1956.40  5384.4 1958.71  5453.4 1959.91
#Mann=3,-1,0
  4782.3     0.1       0  4999.5    0.05       0  5003.5     0.1       0
Bank Sta=4999.5,5003.5
Exp/Cntr=0.3,0.1

Type RM Length L Ch R = 1,5830,175,175,175
BEGIN DESCRIPTION:
Stream0451 13.0
END DESCRIPTION:
XS GIS Cut Line= 3
      1882375.00     13926324.99      1882375.00     13926275.00
      1882325.01     13926025.04
#Sta/Elev= 30
  4950.1 1925.23  4970.8 1919.83  4977.9 1916.92  4988.1 1911.63  4989.9 1909.94
  4992.9 1906.14  4995.9 1903.80  4998.9 1902.38  5000.6 1902.28  5000.9 1901.78
  5004.4 1901.78  5004.6 1902.28  5017.3 1904.92  5020.3 1904.99  5032.6 1907.28
  5048.5 1907.51  5074.0 1906.25  5087.6 1906.72  5104.6 1907.98  5127.4 1911.73
  5148.0 1917.50  5164.1 1923.03  5168.4 1923.78  5176.0 1926.14  5194.7 1930.21
  5200.8 1931.98  5215.1 1934.31  5222.2 1936.48  5237.2 1939.49  5255.0 1940.62
#Mann=3,-1,0
  4950.1     0.1       0  5000.6    0.05       0  5004.6     0.1       0
Bank Sta=5000.6,5004.6
Exp/Cntr=0.3,0.1

Type RM Length L Ch R = 1,5655,280,280,280
BEGIN DESCRIPTION:
Stream0451 13.1
END DESCRIPTION:
XS GIS Cut Line= 3
      1882769.85     13926564.51      1882491.22     13926189.53
      1882397.45     13925962.93
#Sta/Elev= 30
  4618.0 1958.21  4685.7 1955.06  4706.2 1951.85  4719.0 1947.82  4729.8 1947.81
  4738.5 1944.70  4753.8 1940.87  4786.6 1938.13  4837.0 1927.80  4898.7 1906.51
  4905.6 1905.02  4922.7 1903.77  4934.9 1906.24  4950.0 1906.52  4966.0 1905.27
  5002.2 1899.01  5002.5 1898.51  5006.2 1899.01  5014.6 1899.45  5029.6 1902.71
  5055.6 1903.70  5078.1 1902.58  5111.5 1905.98  5124.5 1909.33  5156.8 1914.38
  5189.1 1925.53  5257.6 1939.02  5286.9 1942.43  5316.1 1943.71  5330.4 1946.26
#Mann=4,-1,0
  4618.0    0.07       0  4738.5     0.1       0  5002.2    0.05       0
  5006.2     0.1       0
Bank Sta=5002.2,5006.2
Exp/Cntr=0.3,0.1

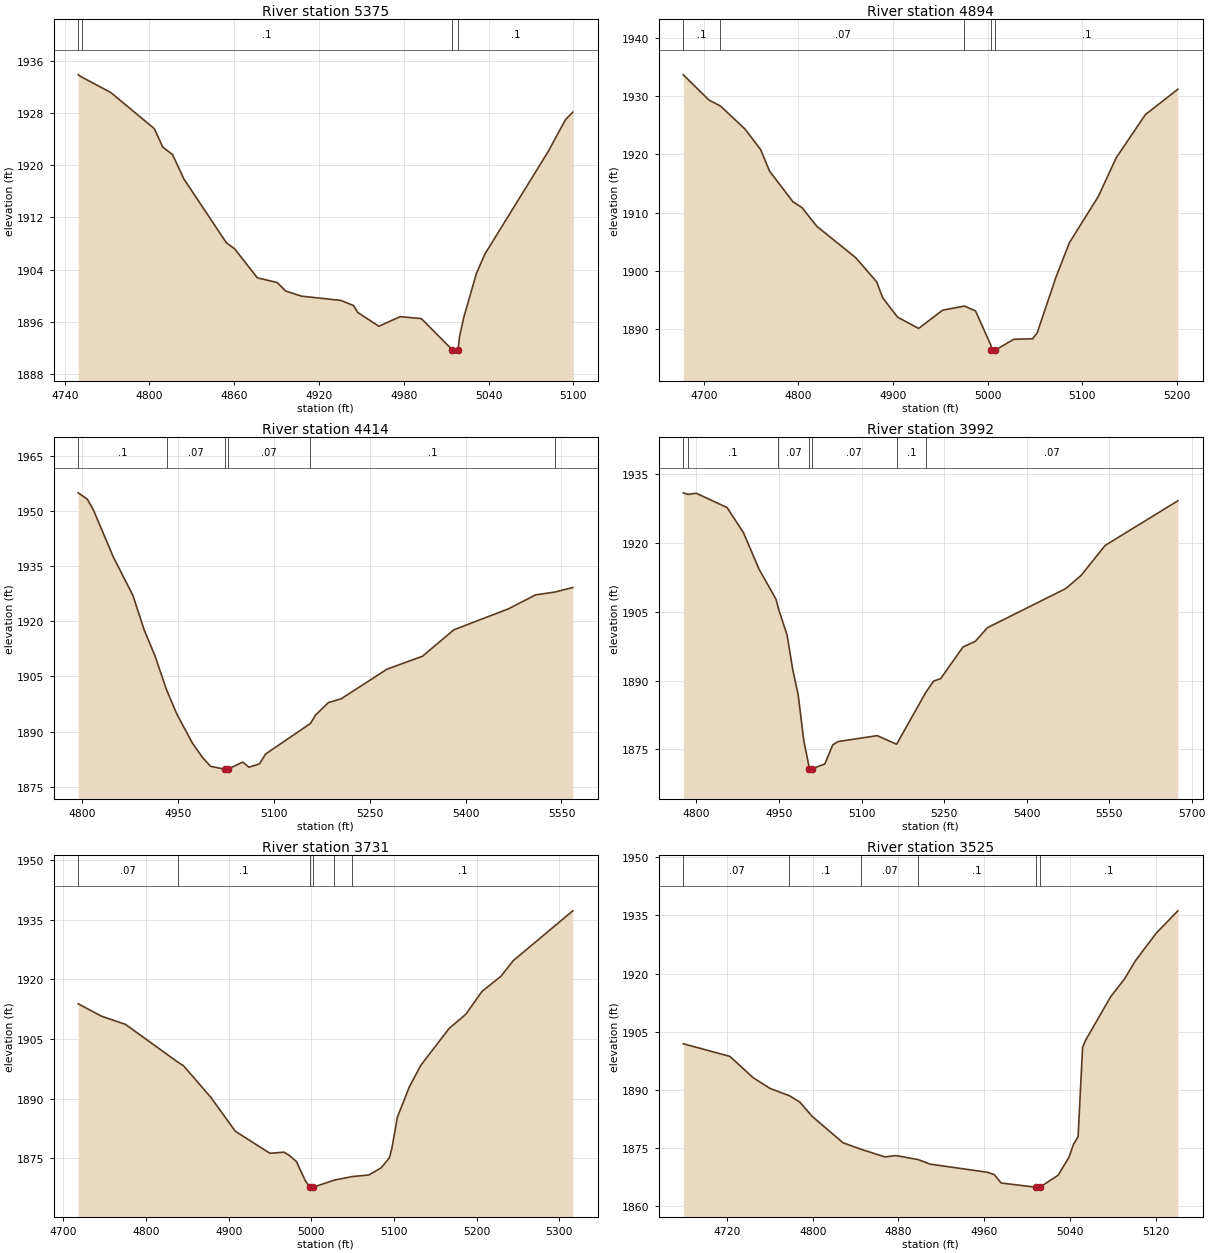
Type RM Length L Ch R = 1,5375,481,481,481
BEGIN DESCRIPTION:
Stream0451 12.0
END DESCRIPTION:
XS GIS Cut Line= 3
      1882775.00     13926375.00      1882775.00     13926125.00
      1882775.00     13926025.00
#Sta/Elev= 30
  4749.6 1933.89  4752.3 1933.52  4772.6 1931.18  4803.4 1925.64  4809.4 1922.80
  4816.3 1921.66  4824.4 1917.90  4854.4 1908.13  4860.4 1907.17  4876.3 1902.75
  4890.4 1902.02  4896.4 1900.72  4907.6 1899.93  4935.4 1899.28  4944.4 1898.49
  4947.4 1897.43  4962.4 1895.31  4977.4 1896.79  4992.4 1896.49  5014.4 1891.69
  5014.7 1891.19  5018.2 1891.19  5018.4 1891.69  5019.4 1893.66  5022.4 1896.64
  5031.4 1903.42  5037.4 1906.39  5082.4 1922.20  5094.4 1927.01  5099.6 1928.17
#Mann=4,-1,0
  4749.6    0.07       0  4752.3     0.1       0  5014.4    0.05       0
  5018.4     0.1       0
Bank Sta=5014.4,5018.4
Exp/Cntr=0.3,0.1

Type RM Length L Ch R = 1,4894,480,480,480
BEGIN DESCRIPTION:
Stream0451 11.0
END DESCRIPTION:
XS GIS Cut Line= 3
      1883125.01     13926424.98      1883225.00     13926125.00
      1883174.99     13925924.97
#Sta/Elev= 30
  4678.4 1933.64  4705.6 1929.30  4717.6 1928.30  4743.6 1924.34  4760.1 1920.82
  4769.6 1917.11  4794.2 1911.88  4803.7 1910.88  4819.5 1907.66  4860.6 1902.28
  4882.7 1898.14  4889.0 1895.41  4904.8 1892.09  4927.0 1890.15  4952.3 1893.28
  4975.3 1893.99  4987.1 1893.17  5003.5 1887.20  5003.8 1886.42  5004.0 1885.92
  5007.8 1886.42  5027.4 1888.29  5047.4 1888.38  5052.2 1889.38  5072.1 1898.96
  5086.2 1904.84  5116.7 1912.75  5135.7 1919.41  5166.6 1926.84  5200.8 1931.16
#Mann=5,-1,0
  4678.4     0.1       0  4717.6    0.07       0  4975.3     0.1       0
  5003.8    0.05       0  5007.8     0.1       0
Bank Sta=5003.8,5007.8
Exp/Cntr=0.3,0.1

Type RM Length L Ch R = 1,4414,422,422,422
BEGIN DESCRIPTION:
Stream0451 10.0
END DESCRIPTION:
XS GIS Cut Line= 4
      1883725.00     13926424.99      1883674.19     13926234.27
      1883615.25     13926059.72      1883309.56     13925813.69
#Sta/Elev= 30
  4793.7 1954.97  4808.0 1953.22  4817.3 1950.35  4848.4 1937.58  4879.4 1926.98
  4896.7 1917.75  4913.8 1910.60  4932.1 1901.28  4948.1 1894.73  4972.6 1886.80
  4988.1 1882.99  5000.7 1880.57  5023.4 1879.75  5023.6 1879.25  5027.4 1879.75
  5051.3 1881.72  5060.8 1880.32  5077.4 1881.23  5086.9 1883.91  5157.0 1892.21
  5165.3 1894.54  5185.2 1897.90  5205.3 1898.94  5277.0 1907.00  5332.4 1910.50
  5381.5 1917.70  5466.9 1923.40  5509.5 1927.20  5539.6 1927.97  5567.7 1929.22
#Mann=6,-1,0
  4793.7     0.1       0  4932.1    0.07       0  5023.4    0.05       0
  5027.4    0.07       0  5157.0     0.1       0  5539.6    0.07       0
Bank Sta=5023.4,5027.4
Exp/Cntr=0.3,0.1

Type RM Length L Ch R = 1,3992,261,261,261
BEGIN DESCRIPTION:
Stream0451 9.0
END DESCRIPTION:
XS GIS Cut Line= 3
      1884171.76     13926072.92      1883975.00     13925975.00
      1883320.12     13925795.57
#Sta/Elev= 30
  4776.1 1930.99  4784.7 1930.65  4799.7 1930.90  4855.7 1927.77  4885.5 1922.27
  4913.8 1914.32  4944.7 1907.73  4948.8 1905.78  4964.8 1899.89  4974.8 1892.52
  4984.9 1886.89  4994.9 1877.05  5005.4 1870.72  5005.7 1870.22  5009.4 1870.72
  5033.3 1871.78  5047.7 1875.95  5057.2 1876.67  5128.5 1877.97  5163.8 1876.10
  5217.0 1887.44  5231.1 1889.89  5243.9 1890.42  5284.3 1897.31  5306.8 1898.56
  5328.7 1901.53  5470.9 1910.06  5498.9 1912.92  5542.5 1919.48  5674.9 1929.25
#Mann=7,-1,0
  4776.1    0.07       0  4784.7     0.1       0  4948.8    0.07       0
  5005.4    0.05       0  5009.4    0.07       0  5163.8     0.1       0
  5217.0    0.07       0
Bank Sta=5005.4,5009.4
Exp/Cntr=0.3,0.1

Type RM Length L Ch R = 1,3731,206,206,206
BEGIN DESCRIPTION:
Stream0451 8.1
END DESCRIPTION:
XS GIS Cut Line= 4
      1884157.03     13925938.67      1884013.79     13925739.01
      1883892.27     13925643.53      1883814.14     13925461.24
#Sta/Elev= 30
  4717.9 1913.86  4745.6 1910.78  4775.1 1908.67  4838.1 1899.22  4845.3 1898.26
  4878.5 1890.26  4908.1 1881.74  4949.9 1876.21  4967.0 1876.49  4973.7 1875.60
  4982.0 1874.12  4992.8 1869.26  4998.4 1867.68  4998.7 1867.18  5002.4 1867.68
  5027.9 1869.45  5049.4 1870.34  5069.6 1870.74  5084.4 1872.52  5094.5 1875.06
  5097.4 1877.33  5104.2 1885.31  5118.6 1892.91  5132.5 1898.36  5166.8 1907.65
  5187.1 1911.25  5206.7 1917.01  5229.5 1920.78  5244.4 1924.73  5316.5 1937.28
#Mann=6,-1,0
  4717.9    0.07       0  4838.1     0.1       0  4998.4    0.05       0
  5002.4     0.1       0  5027.9    0.07       0  5049.4     0.1       0
Bank Sta=4998.4,5002.4
Exp/Cntr=0.3,0.1

Type RM Length L Ch R = 1,3525,454,454,454
BEGIN DESCRIPTION:
Stream0451 8.0
END DESCRIPTION:
XS GIS Cut Line= 3
      1884225.01     13925775.01      1884025.00     13925525.00
      1883924.99     13925424.99
#Sta/Elev= 30
  4679.2 1901.89  4722.7 1898.63  4744.3 1893.16  4760.3 1890.35  4778.3 1888.48
  4788.1 1886.81  4799.5 1883.17  4828.3 1876.35  4845.2 1874.67  4867.3 1872.71
  4877.7 1873.05  4898.6 1872.01  4909.5 1870.85  4963.1 1868.75  4969.5 1868.15
  4975.9 1865.98  5008.0 1864.90  5008.2 1864.40  5012.0 1864.90  5029.1 1867.99
  5039.2 1872.62  5043.4 1875.96  5047.7 1877.91  5051.9 1900.94  5054.5 1902.70
  5078.3 1914.11  5091.1 1918.63  5101.2 1923.30  5120.8 1930.46  5140.8 1936.17
#Mann=6,-1,0
  4679.2    0.07       0  4778.3     0.1       0  4845.2    0.07       0
  4898.6     0.1       0  5008.0    0.05       0  5012.0     0.1       0
Bank Sta=5008,5012
Exp/Cntr=0.3,0.1

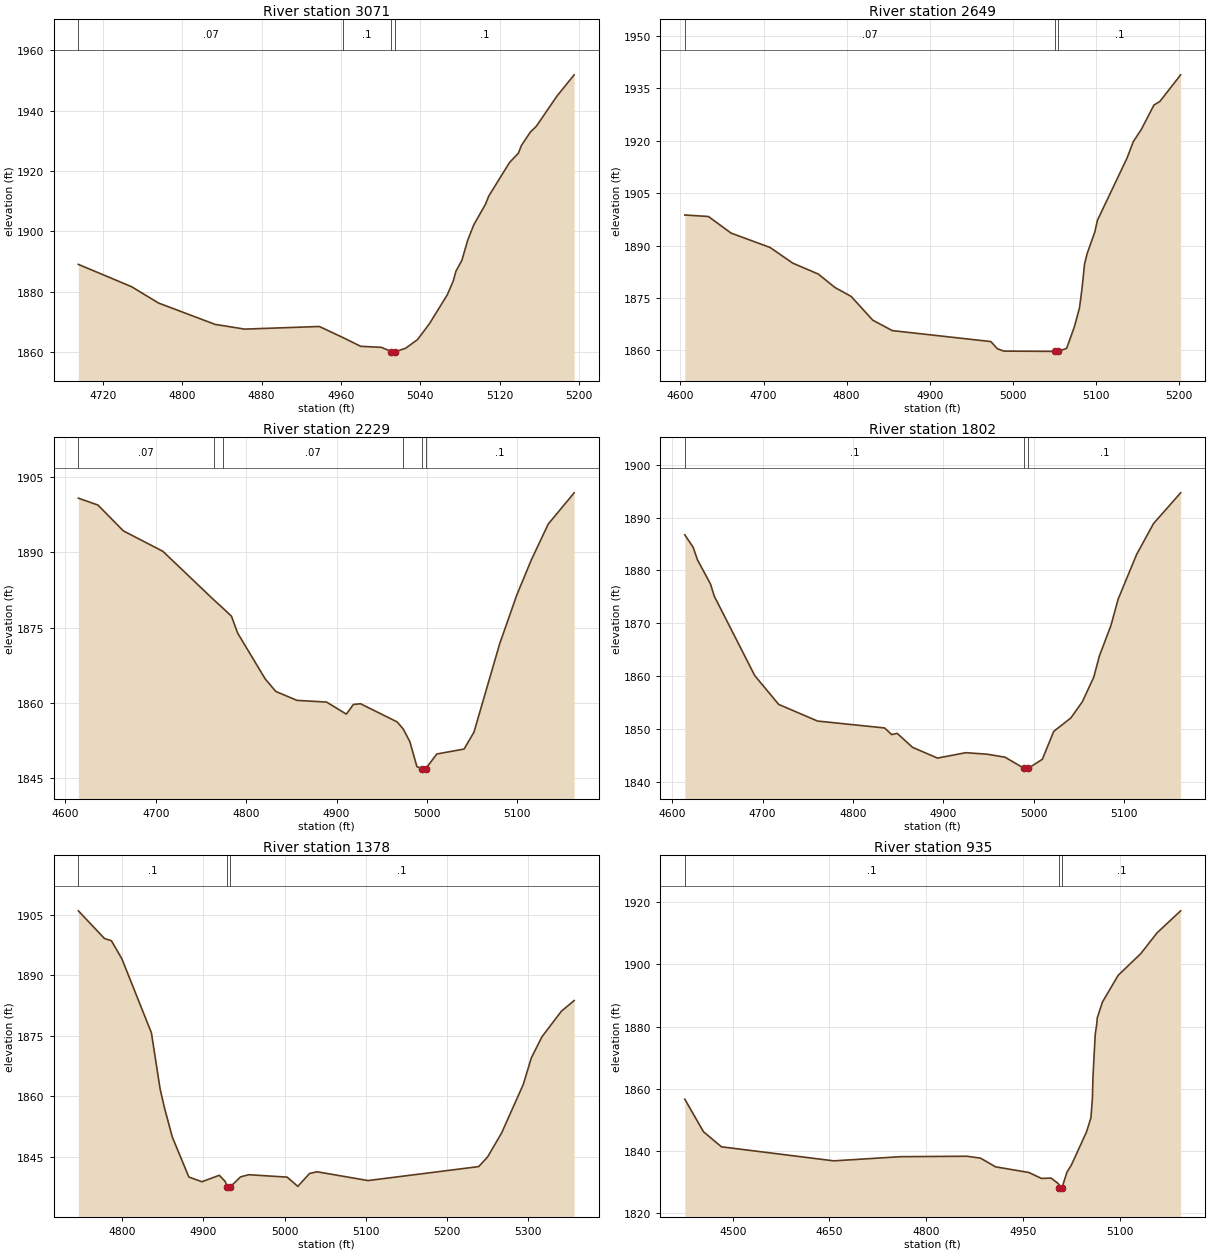
Type RM Length L Ch R = 1,3071,422,422,422
BEGIN DESCRIPTION:
Stream0451 7.0
END DESCRIPTION:
XS GIS Cut Line= 3
      1884375.00     13925624.96      1884375.00     13925325.00
      1884375.00     13925124.96
#Sta/Elev= 30
  4695.2 1889.07  4749.0 1881.66  4776.0 1876.28  4833.0 1869.21  4863.0 1867.63
  4938.2 1868.50  4961.7 1864.89  4980.0 1861.93  5000.8 1861.60  5011.0 1860.18
  5011.3 1859.68  5015.0 1860.18  5025.2 1861.29  5037.2 1864.15  5049.2 1869.39
  5067.2 1878.96  5073.2 1883.50  5076.0 1886.81  5082.0 1890.43  5087.8 1897.01
  5094.0 1902.17  5106.0 1909.11  5109.0 1911.64  5130.0 1922.78  5139.0 1925.90
  5142.0 1928.43  5151.0 1932.86  5157.0 1934.78  5178.0 1944.86  5195.2 1951.83
#Mann=4,-1,0
  4695.2    0.07       0  4961.7     0.1       0  5011.0    0.05       0
  5015.0     0.1       0
Bank Sta=5011,5015
Exp/Cntr=0.3,0.1

Type RM Length L Ch R = 1,2649,420,420,420
BEGIN DESCRIPTION:
Stream0451 6.0
END DESCRIPTION:
XS GIS Cut Line= 3
      1884425.01     13925724.98      1884675.00     13925425.00
      1884724.99     13925225.05
#Sta/Elev= 30
  4605.3 1898.73  4633.7 1898.30  4661.0 1893.55  4707.9 1889.44  4735.2 1884.96
  4765.9 1881.84  4786.0 1877.99  4805.5 1875.43  4831.5 1868.64  4855.0 1865.66
  4973.5 1862.53  4981.5 1860.46  4989.1 1859.80  5050.3 1859.72  5050.6 1859.22
  5054.3 1859.72  5064.7 1860.57  5074.0 1866.70  5080.2 1872.15  5083.2 1877.58
  5086.3 1884.69  5089.4 1887.68  5098.7 1893.89  5101.8 1897.22  5137.4 1915.00
  5145.1 1919.78  5154.4 1923.11  5169.8 1930.18  5176.9 1931.20  5201.9 1938.82
#Mann=3,-1,0
  4605.3    0.07       0  5050.3    0.05       0  5054.3     0.1       0
Bank Sta=5050.3,5054.3
Exp/Cntr=0.3,0.1

Type RM Length L Ch R = 1,2229,427,427,427
BEGIN DESCRIPTION:
Stream0451 5.0
END DESCRIPTION:
XS GIS Cut Line= 3
      1884774.97     13925925.03      1885025.00     13925625.00
      1885075.01     13925474.97
#Sta/Elev= 30
  4614.3 1900.76  4636.0 1899.39  4664.1 1894.25  4707.9 1890.17  4764.4 1880.48
  4774.3 1878.86  4783.8 1877.25  4790.6 1873.90  4821.1 1864.77  4832.8 1862.28
  4856.2 1860.50  4889.0 1860.16  4910.9 1857.76  4918.7 1859.68  4926.5 1859.83
  4967.0 1856.22  4973.8 1854.82  4981.2 1852.27  4989.0 1847.30  4994.8 1846.91
  4995.0 1846.41  4998.8 1846.91  5011.0 1849.82  5041.2 1850.81  5052.1 1854.16
  5080.6 1871.78  5099.6 1881.51  5115.4 1888.38  5134.3 1895.60  5163.0 1901.82
#Mann=6,-1,0
  4614.3    0.07       0  4764.4     0.1       0  4774.3    0.07       0
  4973.8     0.1       0  4994.8    0.05       0  4998.8     0.1       0
Bank Sta=4994.8,4998.8
Exp/Cntr=0.3,0.1

Type RM Length L Ch R = 1,1802,424,424,424
BEGIN DESCRIPTION:
Stream0451 4.0
END DESCRIPTION:
XS GIS Cut Line= 3
      1885624.98     13925974.98      1885375.00     13925675.00
      1885325.00     13925525.00
#Sta/Elev= 30
  4613.9 1886.75  4623.1 1884.41  4628.0 1882.00  4642.3 1877.45  4646.5 1875.15
  4691.3 1860.10  4717.8 1854.65  4760.8 1851.50  4835.0 1850.19  4842.8 1848.94
  4848.9 1849.17  4865.9 1846.52  4893.5 1844.49  4924.8 1845.51  4948.2 1845.23
  4968.2 1844.66  4989.6 1842.52  4989.9 1842.02  4993.6 1842.52  5009.5 1844.26
  5022.1 1849.54  5041.1 1852.09  5053.8 1855.16  5066.4 1859.81  5072.7 1863.86
  5085.4 1869.59  5093.4 1874.59  5113.8 1883.03  5132.5 1888.88  5162.5 1894.70
#Mann=3,-1,0
  4613.9     0.1       0  4989.6    0.05       0  4993.6     0.1       0
Bank Sta=4989.6,4993.6
Exp/Cntr=0.3,0.1

Type RM Length L Ch R = 1,1378,443,443,443
BEGIN DESCRIPTION:
Stream0451 3.0
END DESCRIPTION:
XS GIS Cut Line= 3
      1885925.02     13925875.03      1885775.00     13925675.00
      1885574.99     13925374.99
#Sta/Elev= 30
  4746.1 1905.92  4778.3 1899.07  4786.8 1898.52  4799.7 1894.05  4836.1 1875.71
  4846.8 1861.82  4852.2 1857.10  4861.8 1849.92  4882.2 1839.99  4898.3 1838.82
  4919.7 1840.42  4927.2 1838.84  4928.9 1837.49  4929.2 1836.99  4932.9 1837.49
  4945.9 1840.03  4956.1 1840.56  5003.3 1839.96  5016.4 1837.67  5030.8 1840.86
  5040.1 1841.29  5102.9 1839.11  5239.1 1842.57  5250.0 1844.93  5267.3 1850.88
  5294.0 1862.90  5304.0 1869.51  5317.0 1874.71  5340.9 1881.04  5356.7 1883.70
#Mann=3,-1,0
  4746.1     0.1       0  4928.9    0.05       0  4932.9     0.1       0
Bank Sta=4928.9,4932.9
Exp/Cntr=0.3,0.1

Type RM Length L Ch R = 1,935,464,464,464
BEGIN DESCRIPTION:
Stream0451 2.0
END DESCRIPTION:
XS GIS Cut Line= 3
      1886291.11     13925623.21      1885825.00     13925275.00
      1885739.69     13925108.05
#Sta/Elev= 30
  4425.5 1856.69  4454.5 1846.23  4482.4 1841.39  4656.8 1836.88  4760.1 1838.22
  4863.4 1838.36  4884.4 1837.75  4907.7 1834.96  4959.4 1833.14  4978.8 1831.24
  4993.8 1831.34  5004.5 1829.66  5006.6 1829.09  5006.8 1828.30  5007.1 1827.80
  5010.8 1828.30  5018.4 1833.22  5025.1 1835.45  5048.7 1846.13  5055.6 1850.69
  5057.9 1856.75  5058.8 1863.81  5062.3 1877.48  5064.5 1880.55  5065.5 1882.81
  5073.5 1887.89  5098.0 1896.49  5132.9 1903.42  5158.2 1910.10  5194.8 1917.18
#Mann=3,-1,0
  4425.5     0.1       0  5006.8    0.05       0  5010.8     0.1       0
Bank Sta=5006.8,5010.8
Exp/Cntr=0.3,0.1

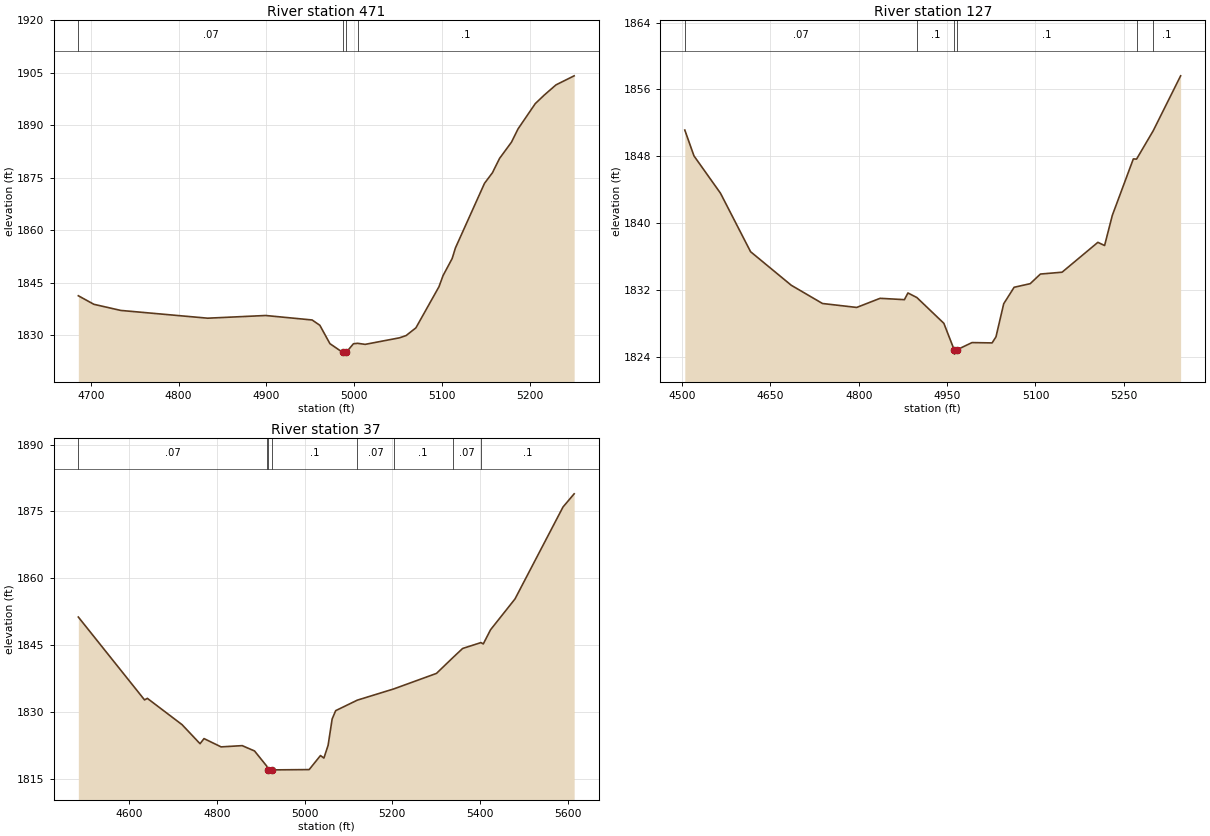
Type RM Length L Ch R = 1,471,344,344,344
BEGIN DESCRIPTION:
Stream0451 1.0
END DESCRIPTION:
XS GIS Cut Line= 3
      1886429.56     13925499.05      1886275.00     13925225.00
      1886125.02     13925025.02
#Sta/Elev= 30
  4685.9 1841.31  4703.6 1838.87  4734.2 1837.12  4833.2 1834.90  4899.2 1835.67
  4952.1 1834.39  4960.9 1832.88  4972.4 1827.62  4986.9 1825.13  4987.1 1824.63
  4990.9 1825.13  4999.2 1827.60  5004.0 1827.72  5012.5 1827.42  5051.6 1829.29
  5059.1 1829.93  5070.3 1832.14  5096.6 1843.91  5101.2 1847.07  5111.6 1851.96
  5115.3 1854.98  5148.4 1873.44  5157.5 1876.49  5165.5 1880.55  5179.1 1885.20
  5186.6 1889.00  5206.2 1896.22  5216.6 1898.70  5229.8 1901.58  5250.5 1904.17
#Mann=4,-1,0
  4685.9    0.07       0  4986.9    0.05       0  4990.9    0.07       0
  5004.0     0.1       0
Bank Sta=4986.9,4990.9
Exp/Cntr=0.3,0.1

Type RM Length L Ch R = 1,127,90,90,90
BEGIN DESCRIPTION:
Stream0451 0.0
END DESCRIPTION:
XS GIS Cut Line= 4
      1886549.96     13925484.74      1886531.30     13925055.47
      1886454.15     13924880.83      1886251.73     13924791.38
#Sta/Elev= 30
  4504.6 1851.15  4520.2 1848.06  4565.2 1843.60  4616.3 1836.61  4685.4 1832.60
  4738.4 1830.42  4796.5 1829.95  4836.2 1831.04  4877.5 1830.88  4883.5 1831.68
  4898.7 1831.13  4944.5 1828.05  4962.1 1824.87  4962.4 1824.37  4966.1 1824.87
  4992.3 1825.75  5026.4 1825.71  5033.0 1826.44  5046.1 1830.39  5063.8 1832.36
  5091.1 1832.79  5108.4 1833.94  5145.2 1834.16  5206.0 1837.73  5217.4 1837.35
  5230.5 1840.95  5266.2 1847.70  5271.7 1847.68  5300.0 1851.07  5346.5 1857.63
#Mann=6,-1,0
  4504.6    0.07       0  4898.7     0.1       0  4962.1    0.05       0
  4966.1     0.1       0  5271.7    0.07       0  5300.0     0.1       0
Bank Sta=4962.1,4966.1
Exp/Cntr=0.3,0.1

Type RM Length L Ch R = 1,37,0,0,0
BEGIN DESCRIPTION:
Stream0451 0.1
END DESCRIPTION:
XS GIS Cut Line= 5
      1886607.11     13925476.45      1886630.98     13925035.89
      1886565.88     13924942.57      1886479.07     13924808.02
      1886081.91     13924684.32
#Sta/Elev= 30
  4484.0 1851.31  4635.0 1832.73  4641.5 1833.07  4720.7 1827.17  4761.7 1822.90
  4770.7 1824.05  4809.7 1822.19  4857.8 1822.47  4885.9 1821.28  4913.8 1817.88
  4916.6 1817.03  4917.1 1816.53  4925.2 1817.03  5010.6 1817.10  5036.4 1820.25
  5044.2 1819.68  5053.8 1822.55  5063.0 1828.44  5071.1 1830.32  5120.4 1832.67
  5203.3 1835.18  5301.0 1838.67  5337.7 1842.14  5360.7 1844.26  5402.5 1845.58
  5407.8 1845.28  5424.4 1848.46  5480.1 1855.36  5589.7 1875.99  5615.1 1878.94
#Mann=8,-1,0
  4484.0    0.07       0  4913.8     0.1       0  4916.6    0.05       0
  4925.2     0.1       0  5120.4    0.07       0  5203.3     0.1       0
  5337.7    0.07       0  5402.5     0.1       0
Bank Sta=4916.6,4925.2
Exp/Cntr=0.3,0.1

Chan Stop Cuts=-1