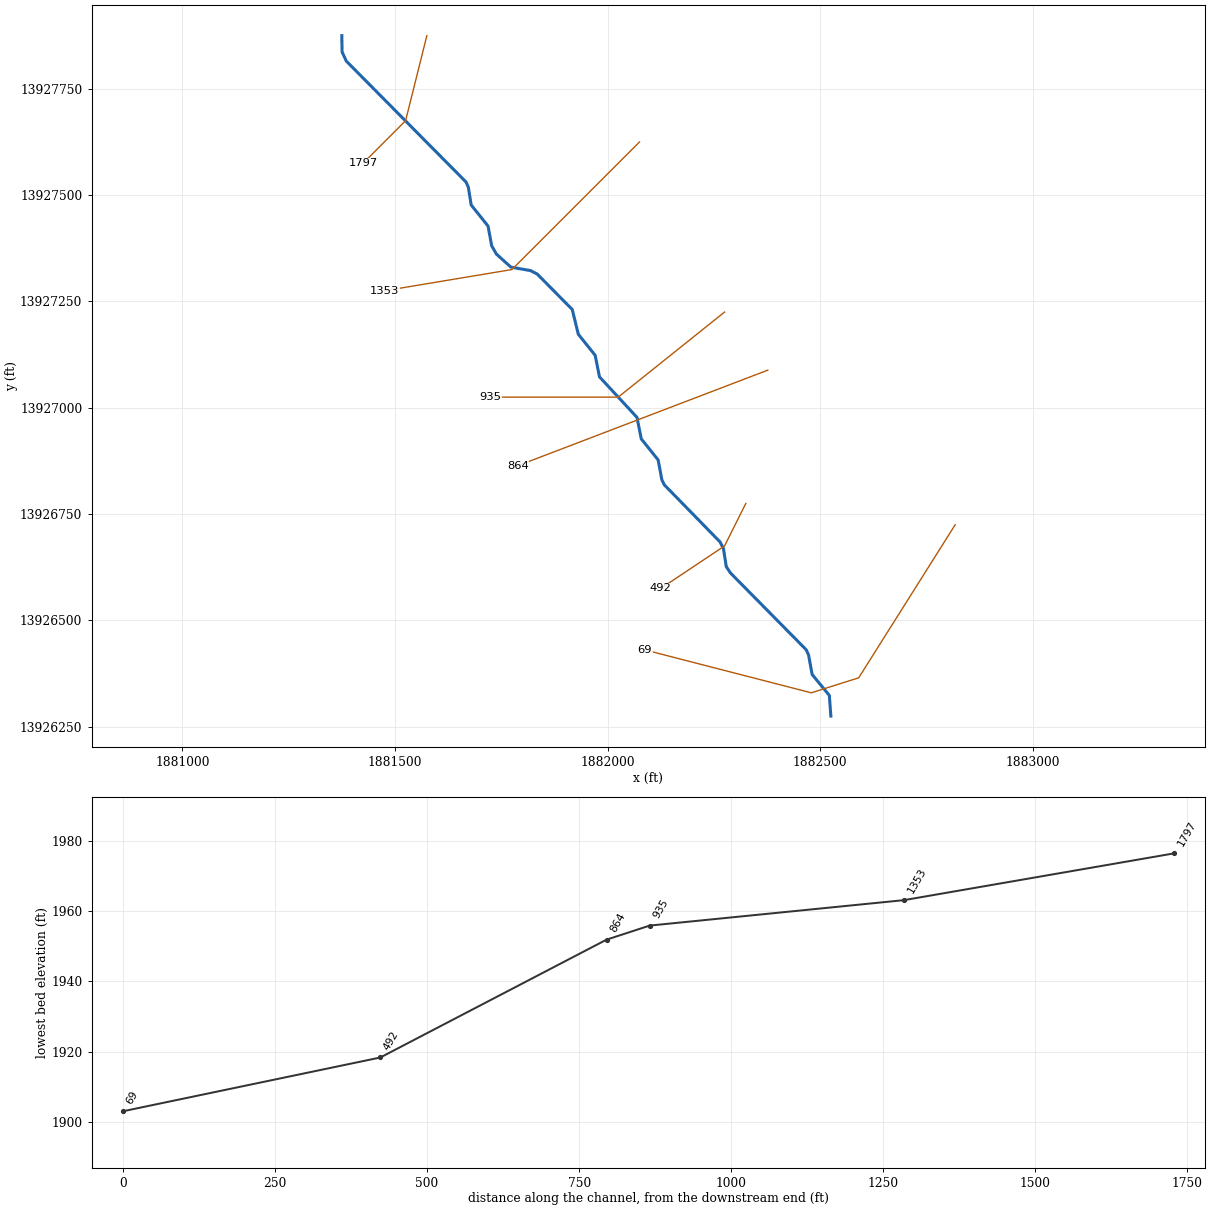
--- Stream0452.prj (project) ---

Proj Title=Stream0452 Base Level Engineering
Current Plan=p01
Default Exp/Contr=0.3,0.1
English Units
Geom File=g01
Flow File=f01
Plan File=p01
Y Axis Title=Elevation
X Axis Title(PF)=Main Channel Distance
X Axis Title(XS)=Station
BEGIN DESCRIPTION:
Stream0452
END DESCRIPTION:
DSS Export Rating Curves= 0
DSS Export Rating Curve Sorted= 0
DSS Export Volume Flow Curves= 0
DXF OffsetX= 0
DXF OffsetY= 0
DXF ScaleX= 1
DXF ScaleY= 10

--- Stream0452.p01 (plan) ---

Plan Title=Multiple Run
Short Identifier=Multiple
Geom File=g01
Flow File=f01
Subcritical Flow
K Sum by GR= 0
Std Step Tol= 0.01
Critical Tol= 0.01
Num of Std Step Trials= 20
Max Error Tol= 0.3
Flow Tol Ratio= 0.001
Split Flow NTrial= 30
Split Flow Tol= 0.02
Split Flow Ratio= 0.02
Log Output Level= 0
Friction Slope Method= 1
Unsteady Friction Slope Method= 2
Unsteady Bridges Friction Slope Method= 1
Parabolic Critical Depth
Global Vel Dist=  1 , 1 , 1
Global Log Level= 0
CheckData=True
Encroach Param= -1, 0, 0, 0
BEGIN DESCRIPTION:
Multiple Run
END DESCRIPTION:

--- Stream0452.f01 (steady flow) ---

Flow Title=Multiple
Number of Profiles=7
Profile Names=10-year,25-year,50-year,1pct_min,100-year,1pct_plu,500-year
River Rch & RM= Stream0452,Reach-1,1797
     394     632     845     550    1097    2189    1817
Boundary for River Rch & Prof#=Stream0452,Reach-1,1
Up Type=0
Dn Type=3
Dn Slope=0.005
Boundary for River Rch & Prof#=Stream0452,Reach-1,2
Up Type=0
Dn Type=3
Dn Slope=0.005
Boundary for River Rch & Prof#=Stream0452,Reach-1,3
Up Type=0
Dn Type=3
Dn Slope=0.005
Boundary for River Rch & Prof#=Stream0452,Reach-1,4
Up Type=0
Dn Type=3
Dn Slope=0.005
Boundary for River Rch & Prof#=Stream0452,Reach-1,5
Up Type=0
Dn Type=3
Dn Slope=0.005
Boundary for River Rch & Prof#=Stream0452,Reach-1,6
Up Type=0
Dn Type=3
Dn Slope=0.005
Boundary for River Rch & Prof#=Stream0452,Reach-1,7
Up Type=0
Dn Type=3
Dn Slope=0.005

--- Stream0452.g01 (geometry) ---

Geom Title=Existing Conditions
Program Version=4.10

River Reach=Stream0452      ,Reach-1
Reach XY= 30
        1881375.       13927875.      1881375.59     13927836.84
      1881385.51     13927815.21      1881666.86     13927531.06
       1881672.5     13927518.96      1881679.19     13927476.73
      1881718.89     13927427.16      1881727.42     13927380.85
      1881738.47     13927361.43      1881772.46     13927330.75
      1881818.92     13927322.45      1881834.68     13927314.22
      1881916.87     13927231.07       1881931.1     13927172.81
      1881970.81     13927123.27      1881980.85     13927072.71
      1882069.15     13926977.29      1882079.19     13926926.73
       1882118.9     13926877.19       1882127.5     13926831.04
      1882133.14     13926818.94      1882264.22     13926684.68
      1882272.46     13926668.95      1882278.98     13926626.65
      1882288.63     13926611.79      1882466.87     13926431.06
      1882472.53     13926418.98      1882480.97     13926372.76
       1882521.4     13926323.51        1882525.       13926275.

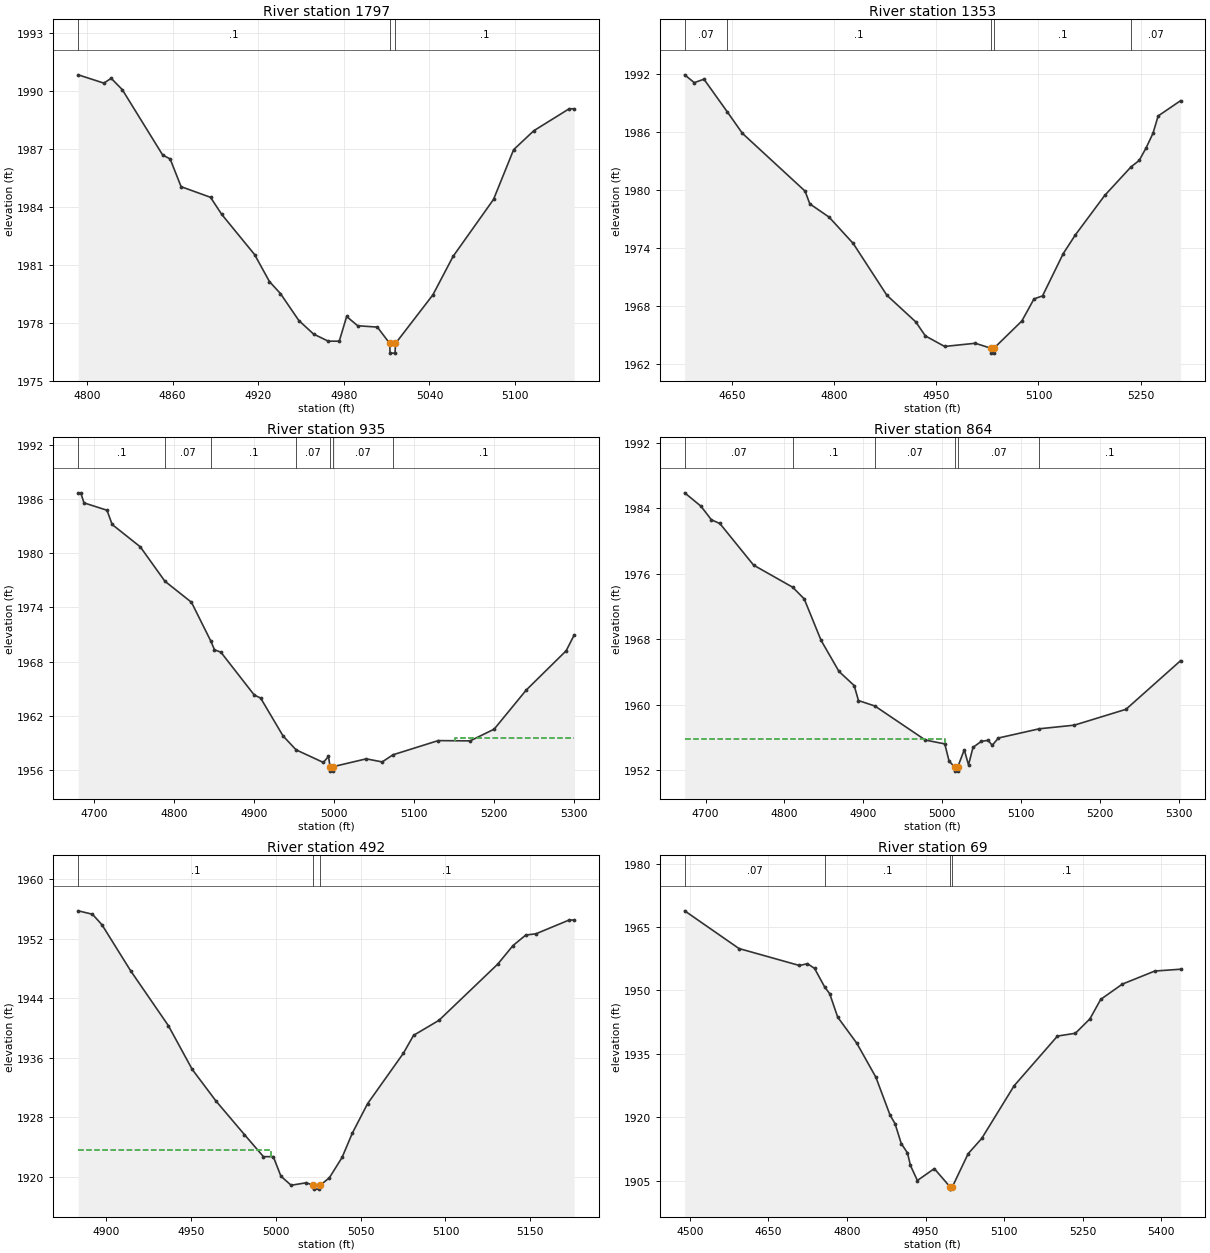
Type RM Length L Ch R = 1 ,1797    ,444,444,444
BEGIN DESCRIPTION:
Stream0452 4.0
END DESCRIPTION:
XS GIS Cut Line= 3
      1881574.99     13927874.96        1881525.       13927675.
      1881425.02     13927575.02
#Sta/Elev= 30
  4793.9 1990.85  4811.9 1990.42    4817 1990.67  4824.8 1990.08  4853.1 1986.69
  4858.3 1986.49    4866 1985.05  4886.6  1984.5  4894.4 1983.62  4917.5 1981.53
  4927.9 1980.13  4935.6 1979.51  4948.5 1978.11  4958.8 1977.41  4969.1 1977.04
  4976.8 1977.04    4982 1978.32  4989.7 1977.84  5003.5 1977.77  5012.2 1976.92
  5012.4 1976.42  5015.9 1976.42  5016.2 1976.92  5042.4 1979.44  5056.6 1981.44
  5084.9 1984.39    5099 1986.97  5113.1 1987.95  5137.9 1989.09  5141.4 1989.09
#Mann= 3 ,-1 , 0
  4793.9      .1       0  5012.2     .05       0  5016.2      .1       0
Bank Sta=5012.2,5016.2
XS Rating Curve= 0 ,0
Exp/Cntr=0.3,0.1

Type RM Length L Ch R = 1 ,1353    ,418,418,418
BEGIN DESCRIPTION:
Stream0452 3.0
END DESCRIPTION:
XS GIS Cut Line= 3
      1882074.99     13927624.99        1881775.       13927325.
      1881474.99       13927275.
#Sta/Elev= 30
  4580.4 1991.88  4594.5 1991.07  4608.7 1991.43  4642.9 1988.06  4665.2 1985.83
  4757.2 1979.86  4764.2 1978.54  4792.5 1977.17  4827.9 1974.45  4877.4 1969.09
  4919.8 1966.34  4933.9 1964.89  4962.2  1963.8  5007.2 1964.13  5030.5 1963.61
  5030.8 1963.11  5034.3 1963.11  5034.5 1963.61  5075.6 1966.43  5093.4 1968.71
    5106 1969.03  5136.4  1973.4  5154.2 1975.33  5197.3 1979.41  5235.9 1982.36
    5248 1983.03  5258.1 1984.33  5268.2 1985.83  5275.8 1987.63  5308.8 1989.21
#Mann= 5 ,-1 , 0
  4580.4     .07       0  4642.9      .1       0  5030.5     .05       0
  5034.5      .1       0  5235.9     .07       0
Bank Sta=5030.5,5034.5
XS Rating Curve= 0 ,0
Exp/Cntr=0.3,0.1

Type RM Length L Ch R = 1 ,935     ,71,71,71
BEGIN DESCRIPTION:
Stream0452 2.0
END DESCRIPTION:
XS GIS Cut Line= 3
      1882274.97     13927224.97        1882025.       13927025.
      1881725.01       13927025.
#Sta/Elev= 30
  4679.9 1986.69  4683.1 1986.69  4687.1 1985.58  4715.9 1984.76  4722.3 1983.19
  4757.5 1980.71  4788.3  1976.9  4821.5 1974.57  4845.6 1970.29  4850.3 1969.31
  4858.3 1969.04    4900  1964.3    4908 1963.96    4936 1959.77  4952.3 1958.23
  4986.4 1956.83  4992.8  1957.5  4994.8 1956.37  4995.1 1955.87  4998.6 1955.87
  4998.8 1956.37    5040 1957.23    5060 1956.89  5073.5 1957.68    5130 1959.25
    5170 1959.22    5200 1960.52    5240 1964.84    5290  1969.2    5300 1970.94
#Mann= 7 ,-1 , 0
  4679.9      .1       0  4788.3     .07       0  4845.6      .1       0
  4952.3     .07       0  4994.8     .05       0  4998.8     .07       0
  5073.5      .1       0
#XS Ineff= 2 , 0
                         5150.42         1959.55
Permanent Ineff=
       F       F
Bank Sta=4994.8,4998.8
XS Rating Curve= 0 ,0
Exp/Cntr=0.3,0.1

Type RM Length L Ch R = 1 ,864     ,372,372,372
BEGIN DESCRIPTION:
Mapping XS 761d3acd
END DESCRIPTION:
XS GIS Cut Line= 2
      1882376.64     13927088.38      1881789.09     13926863.81
#Sta/Elev= 30
  4673.4 1985.89    4694 1984.26  4707.3 1982.59    4718 1982.14  4760.8 1977.05
  4810.5 1974.34    4825 1972.92  4846.4 1967.85  4869.1 1964.05  4888.4 1962.32
  4893.8 1960.49  4914.7 1959.82  4978.6 1955.66  5003.3 1955.19  5008.7  1953.1
  5015.7 1952.36    5016 1951.86  5019.5 1951.86  5019.7 1952.36    5028 1954.47
  5033.4 1952.62  5039.1 1954.77  5049.8 1955.51  5058.1 1955.62  5063.5 1955.02
  5071.3 1955.91  5123.3 1957.04  5167.6 1957.48  5233.1 1959.42  5302.4 1965.37
#Mann= 6 ,-1 , 0
  4673.4     .07       0  4810.5      .1       0  4914.7     .07       0
  5015.7     .05       0  5019.7     .07       0  5123.3      .1       0
#XS Ineff= 2 , 0
         5003.17  1955.8
Permanent Ineff=
       F       F
Bank Sta=5015.7,5019.7
XS Rating Curve= 0 ,0
Exp/Cntr=0.3,0.1

Type RM Length L Ch R = 1 ,492     ,423,423,423
BEGIN DESCRIPTION:
Stream0452 1.0
END DESCRIPTION:
XS GIS Cut Line= 3
      1882325.02     13926775.04        1882275.       13926675.
      1882125.02     13926575.01
#Sta/Elev= 30
  4883.7 1955.76  4892.1  1955.3  4897.7 1953.88  4914.5 1947.72  4936.8 1940.31
  4950.8 1934.44  4964.8 1930.18  4981.6 1925.65  4992.8 1922.68  4998.6 1922.68
  5003.1 1920.05  5009.1 1918.83  5018.1 1919.17  5022.1 1918.81  5022.3 1918.31
  5025.8 1918.31  5026.1 1918.81  5031.6 1919.83  5039.1 1922.57  5045.1 1925.82
  5054.1  1929.8  5075.2 1936.59  5081.2    1939  5096.2 1941.03  5130.8 1948.59
  5139.8 1951.09  5147.3  1952.5  5153.3 1952.67  5172.8 1954.52  5175.8 1954.52
#Mann= 3 ,-1 , 0
  4883.7      .1       0  5022.1     .05       0  5026.1      .1       0
#XS Ineff= 2 , 0
         4997.04 1923.52
Permanent Ineff=
       F       F
Bank Sta=5022.1,5026.1
XS Rating Curve= 0 ,0
Exp/Cntr=0.3,0.1

Type RM Length L Ch R = 1 ,69      ,0,0,0
BEGIN DESCRIPTION:
Stream0452 0.0
END DESCRIPTION:
XS GIS Cut Line= 4
      1882817.26      13926724.7      1882590.43      13926364.9
      1882478.99     13926329.67       1882087.3     13926430.64
#Sta/Elev= 30
  4490.1 1968.83  4593.8 1959.91  4709.2  1955.9  4724.5 1956.33    4738 1955.22
  4757.7 1950.73  4766.9 1949.24  4782.2 1943.68  4818.7 1937.51  4855.1 1929.47
  4882.2  1920.5  4891.6 1918.52  4903.5 1913.79  4915.4 1911.58  4921.1  1908.6
  4934.3 1905.05  4966.6 1907.86  4996.9 1903.51  4997.2 1903.01  5000.9 1903.51
  5031.2 1911.39  5057.1 1914.99    5119 1927.46  5201.7 1939.21  5235.9 1939.87
  5263.6 1943.27  5284.3 1947.89  5325.6  1951.5  5387.5 1954.59  5436.8 1955.02
#Mann= 4 ,-1 , 0
  4490.1     .07       0  4757.7      .1       0  4996.9     .05       0
  5000.9      .1       0
Bank Sta=4996.9,5000.9
XS Rating Curve= 0 ,0
Exp/Cntr=0.3,0.1

Chan Stop Cuts=-1
Use User Specified Reach Order=0
Composite Channel Slope=5