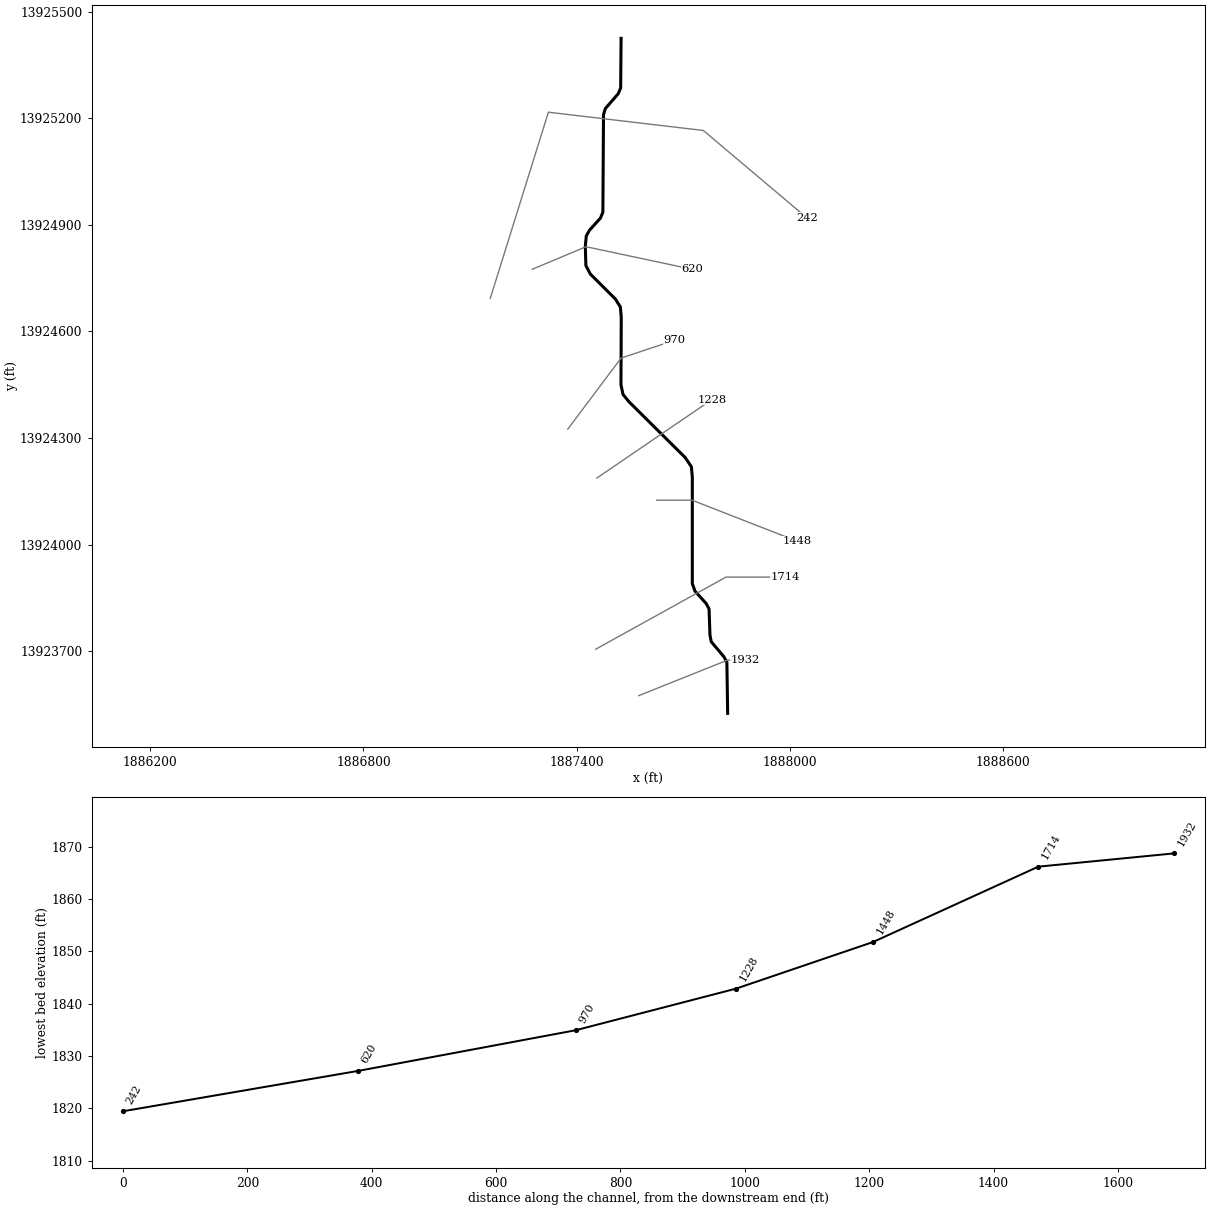
--- Stream0453.prj (project) ---

Proj Title=Stream0453 Base Level Engineering
Current Plan=p01
Default Exp/Contr=0.3,0.1
English Units
Geom File=g01
Flow File=f01
Plan File=p01
Y Axis Title=Elevation
X Axis Title(PF)=Main Channel Distance
X Axis Title(XS)=Station
BEGIN DESCRIPTION:
Stream0453
END DESCRIPTION:
DSS Export Rating Curves= 0
DSS Export Rating Curve Sorted= 0
DSS Export Volume Flow Curves= 0
DXF OffsetX= 0
DXF OffsetY= 0
DXF ScaleX= 1
DXF ScaleY= 10

--- Stream0453.p01 (plan) ---

Plan Title=Multiple Run
Short Identifier=Multiple
Geom File=g01
Flow File=f01
Subcritical Flow
K Sum by GR= 0
Std Step Tol= 0.01
Critical Tol= 0.01
Num of Std Step Trials= 20
Max Error Tol= 0.3
Flow Tol Ratio= 0.001
Split Flow NTrial= 30
Split Flow Tol= 0.02
Split Flow Ratio= 0.02
Log Output Level= 0
Friction Slope Method= 1
Unsteady Friction Slope Method= 2
Unsteady Bridges Friction Slope Method= 1
Parabolic Critical Depth
Global Vel Dist=  1 , 1 , 1
Global Log Level= 0
CheckData=True
Encroach Param= -1, 0, 0, 0
BEGIN DESCRIPTION:
Multiple Run
END DESCRIPTION:

--- Stream0453.f01 (steady flow) ---

Flow Title=Multiple
Program Version=4.10
Number of Profiles= 7
Profile Names=10-year,25-year,50-year,1pct_min,100-year,1pct_plu,500-year
River Rch & RM=Stream0453,Reach-1         ,1932
     360     574     766     497     993    1981    1639
Boundary for River Rch & Prof#=Stream0453,Reach-1         , 1
Up Type= 0
Dn Type= 3
Dn Slope=0.01
Boundary for River Rch & Prof#=Stream0453,Reach-1         , 2
Up Type= 0
Dn Type= 3
Dn Slope=0.01
Boundary for River Rch & Prof#=Stream0453,Reach-1         , 3
Up Type= 0
Dn Type= 3
Dn Slope=0.01
Boundary for River Rch & Prof#=Stream0453,Reach-1         , 4
Up Type= 0
Dn Type= 3
Dn Slope=0.01
Boundary for River Rch & Prof#=Stream0453,Reach-1         , 5
Up Type= 0
Dn Type= 3
Dn Slope=0.01
Boundary for River Rch & Prof#=Stream0453,Reach-1         , 6
Up Type= 0
Dn Type= 3
Dn Slope=0.01
Boundary for River Rch & Prof#=Stream0453,Reach-1         , 7
Up Type= 0
Dn Type= 3
Dn Slope=0.01
DSS Import GetInterval= 0
DSS Import GetPeak= 0
DSS Import FillOption= 0

--- Stream0453.g01 (geometry) ---

Geom Title=Existing Conditions

River Reach=Stream0453,Reach-1
Reach XY= 30
      1887825.00     13923525.00      1887822.78     13923669.08
      1887814.16     13923684.65      1887778.85     13923726.60
      1887775.24     13923745.10      1887772.64     13923819.02
      1887764.11     13923834.63      1887733.14     13923868.94
      1887725.52     13923890.22      1887725.49     13924190.20
      1887722.94     13924219.15      1887705.40     13924245.16
      1887547.86     13924401.47      1887530.46     13924422.55
      1887524.70     13924449.88      1887525.49     13924640.20
      1887522.93     13924669.14      1887508.53     13924691.75
      1887438.37     13924761.71      1887425.94     13924785.48
      1887424.27     13924840.06      1887427.16     13924869.02
      1887435.81     13924884.63      1887466.85     13924918.94
      1887473.78     13924935.50      1887475.52     13925209.78
      1887480.74     13925227.34      1887516.87     13925268.94
      1887523.83     13925285.48      1887525.00     13925425.00

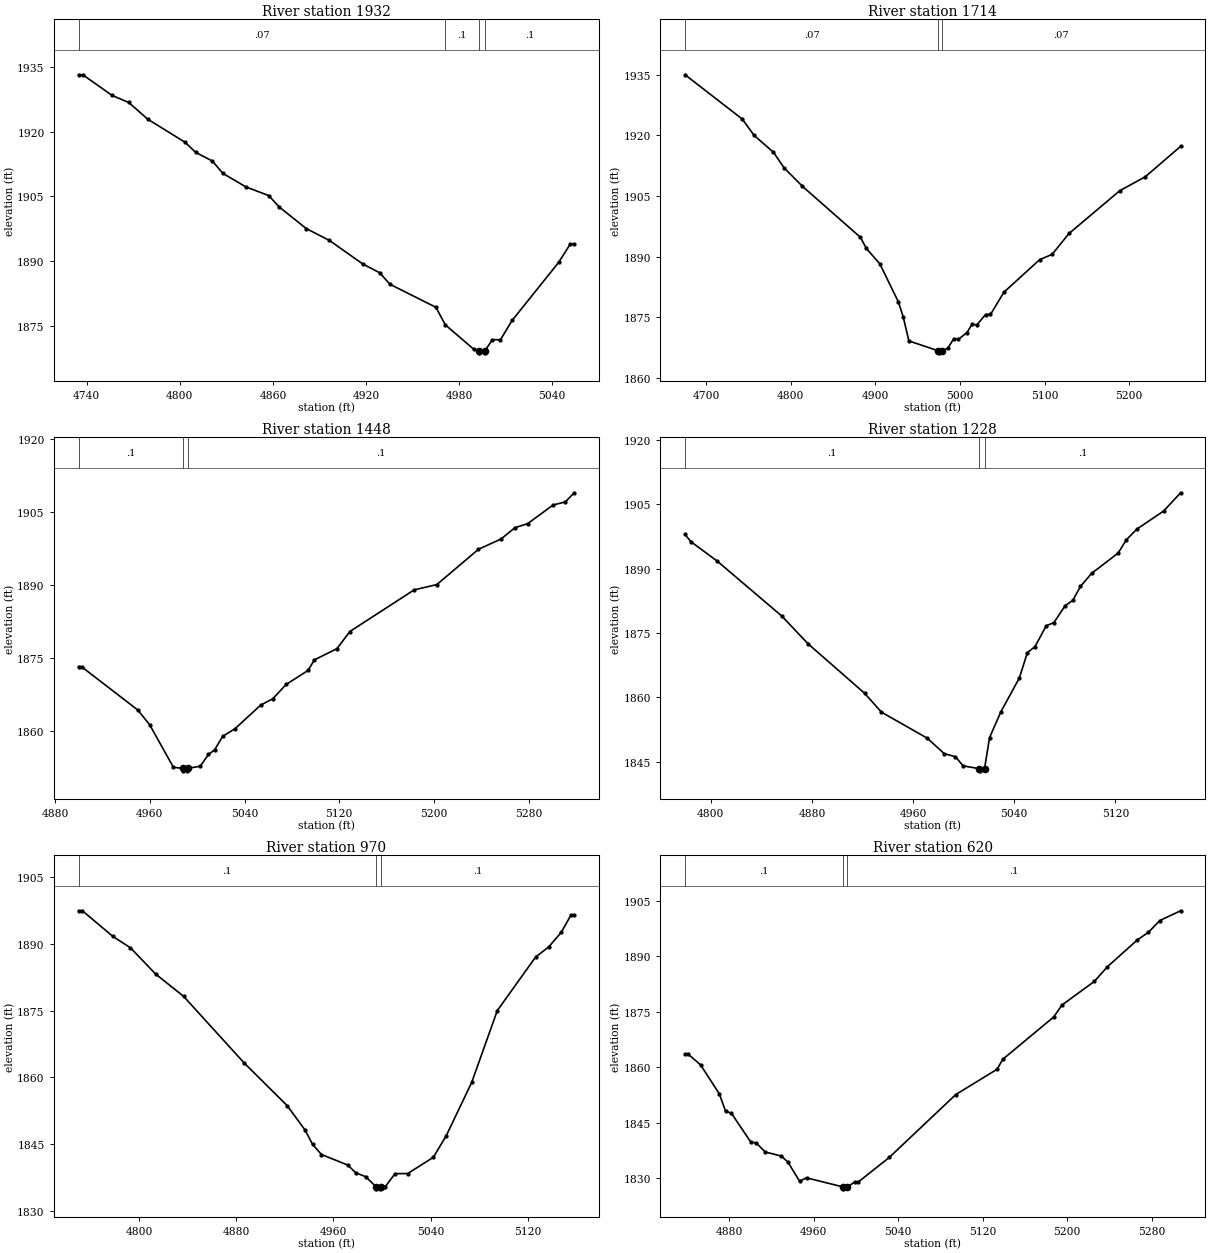
Type RM Length L Ch R = 1,1932,218,218,218
BEGIN DESCRIPTION:
Stream0453 4.0
END DESCRIPTION:
XS GIS Cut Line= 3
      1887575.00     13923575.00      1887825.00     13923675.00
      1887875.04     13923675.00
#Sta/Elev= 30
  4734.8 1933.19  4737.5 1933.19  4756.3 1928.41  4767.1 1926.76  4779.2 1922.92
  4803.5 1917.50  4810.2 1915.19  4821.0 1913.18  4827.7 1910.33  4842.5 1907.19
  4857.3 1905.17  4864.0 1902.54  4881.5 1897.51  4896.4 1894.76  4917.9 1889.30
  4928.7 1887.28  4935.4 1884.60  4965.0 1879.25  4971.1 1875.18  4989.3 1869.55
  4992.6 1869.19  4992.9 1868.69  4996.4 1868.69  4996.6 1869.19  5001.4 1871.73
  5006.6 1871.73  5014.1 1876.20  5044.1 1889.67  5051.6 1893.92  5054.1 1893.92
#Mann=4,-1,0
  4734.8    0.07       0  4971.1     0.1       0  4992.6    0.05       0
  4996.6     0.1       0
Bank Sta=4992.6,4996.6
Exp/Cntr=0.3,0.1

Type RM Length L Ch R = 1,1714,266,266,266
BEGIN DESCRIPTION:
Stream0453 6.0
END DESCRIPTION:
XS GIS Cut Line= 3
      1887453.70     13923705.64      1887820.21     13923908.58
      1887986.76     13923908.58
#Sta/Elev= 30
  4675.2 1935.04  4742.8 1924.06  4756.7 1920.03  4779.6 1915.85  4792.1 1912.00
  4813.9 1907.40  4882.4 1894.77  4889.4 1892.01  4905.3 1888.21  4927.2 1878.77
  4932.9 1875.09  4939.6 1869.11  4974.4 1866.66  4974.7 1866.16  4978.4 1866.66
  4985.3 1867.24  4992.4 1869.57  4998.2 1869.53  5008.2 1871.16  5014.2 1873.22
  5019.9 1873.09  5030.2 1875.65  5036.0 1875.66  5052.0 1881.20  5094.0 1889.22
  5108.9 1890.57  5128.9 1895.74  5188.9 1906.34  5218.9 1909.77  5260.7 1917.31
#Mann=3,-1,0
  4675.2    0.07       0  4974.4    0.05       0  4978.4    0.07       0
Bank Sta=4974.4,4978.4
Exp/Cntr=0.3,0.1

Type RM Length L Ch R = 1,1448,220,220,220
BEGIN DESCRIPTION:
Stream0453 3.0
END DESCRIPTION:
XS GIS Cut Line= 3
      1887624.98     13924125.00      1887725.00     13924125.00
      1888021.56     13924009.16
#Sta/Elev= 30
  4899.9 1873.15  4902.4 1873.15  4949.9 1864.25  4959.9 1861.22  4979.9 1852.50
  4987.9 1852.26  4988.2 1851.76  4991.7 1851.76  4991.9 1852.26  5002.6 1852.71
  5009.5 1855.12  5014.8 1856.09  5021.4 1858.82  5032.1 1860.45  5053.6 1865.27
  5063.8 1866.56  5075.1 1869.51  5093.6 1872.39  5099.0 1874.57  5118.0 1876.86
  5128.9 1880.39  5183.2 1888.95  5202.3 1890.03  5237.5 1897.29  5256.6 1899.41
  5268.3 1901.73  5279.0 1902.55  5300.5 1906.39  5310.9 1907.03  5318.3 1908.90
#Mann=3,-1,0
  4899.9     0.1       0  4987.9    0.05       0  4991.9     0.1       0
Bank Sta=4987.9,4991.9
Exp/Cntr=0.3,0.1

Type RM Length L Ch R = 1,1228,258,258,258
BEGIN DESCRIPTION:
Stream0453 5.0
END DESCRIPTION:
XS GIS Cut Line= 2
      1887456.70     13924187.23      1887780.44     13924408.09
#Sta/Elev= 30
  4779.7 1898.00  4784.2 1896.35  4805.1 1891.79  4856.0 1879.02  4876.9 1872.52
  4921.7 1860.95  4935.0 1856.56  4971.3 1850.47  4984.6 1846.89  4993.5 1846.16
  4999.6 1844.03  5012.5 1843.37  5012.7 1842.87  5016.5 1843.37  5020.5 1850.63
  5029.4 1856.62  5044.0 1864.50  5050.4 1870.45  5056.4 1871.83  5065.3 1876.71
  5071.4 1877.45  5080.2 1881.37  5086.3 1882.63  5092.4 1885.89  5101.2 1888.93
  5122.2 1893.67  5128.7 1896.78  5137.1 1899.28  5158.1 1903.46  5171.6 1907.73
#Mann=3,-1,0
  4779.7     0.1       0  5012.5    0.05       0  5016.5     0.1       0
Bank Sta=5012.5,5016.5
Exp/Cntr=0.3,0.1

Type RM Length L Ch R = 1,970,350,350,350
BEGIN DESCRIPTION:
Stream0453 2.0
END DESCRIPTION:
XS GIS Cut Line= 3
      1887375.03     13924325.04      1887525.00     13924525.00
      1887675.03     13924575.01
#Sta/Elev= 30
  4750.2 1897.48  4753.3 1897.48  4778.3 1891.73  4792.9 1889.15  4813.7 1883.23
  4836.6 1878.24  4886.6 1863.22  4922.0 1853.62  4936.6 1848.18  4942.9 1844.90
  4950.2 1842.64  4972.0 1840.25  4978.3 1838.54  4986.6 1837.66  4995.0 1835.42
  4995.3 1834.92  4998.8 1834.92  4999.0 1835.42  5002.8 1835.42  5010.7 1838.33
  5021.2 1838.36  5042.3 1842.01  5052.9 1846.85  5073.9 1858.86  5095.0 1875.03
  5126.6 1887.09  5137.2 1889.31  5147.7 1892.64  5155.6 1896.50  5158.3 1896.50
#Mann=3,-1,0
  4750.2     0.1       0  4995.0    0.05       0  4999.0     0.1       0
Bank Sta=4995,4999
Exp/Cntr=0.3,0.1

Type RM Length L Ch R = 1,620,378,378,378
BEGIN DESCRIPTION:
Stream0453 1.0
END DESCRIPTION:
XS GIS Cut Line= 3
      1887275.04     13924775.02      1887426.44     13924838.48
      1887725.00     13924775.00
#Sta/Elev= 30
  4838.2 1863.59  4840.9 1863.59  4852.8 1860.67  4870.7 1852.79  4876.5 1848.13
  4882.0 1847.60  4900.3 1839.85  4905.7 1839.52  4914.1 1837.10  4929.5 1836.01
  4935.7 1834.33  4946.6 1829.22  4953.3 1830.12  4988.0 1827.65  4988.2 1827.15
  4992.0 1827.65  4998.9 1829.03  5002.4 1829.03  5031.6 1835.64  5094.6 1852.63
  5133.8 1859.48  5139.1 1862.16  5187.4 1873.61  5195.1 1876.80  5225.8 1883.20
  5238.3 1887.19  5266.7 1894.45  5276.9 1896.43  5287.9 1899.67  5307.6 1902.30
#Mann=3,-1,0
  4838.2     0.1       0  4988.0    0.05       0  4992.0     0.1       0
Bank Sta=4988,4992
Exp/Cntr=0.3,0.1

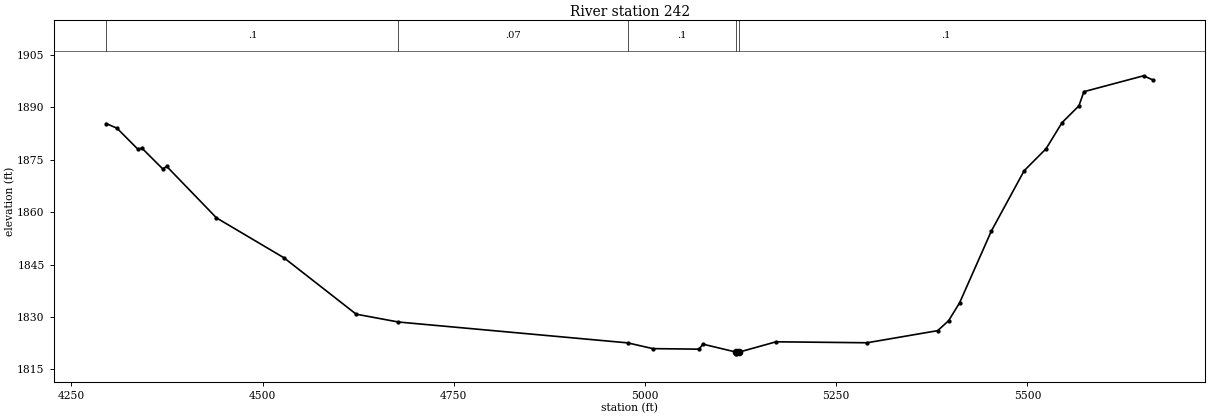
Type RM Length L Ch R = 1,242,0,0,0
BEGIN DESCRIPTION:
Stream0453 0.0
END DESCRIPTION:
XS GIS Cut Line= 4
      1887156.85     13924693.04      1887320.43     13925217.10
      1887756.60     13925165.61      1888047.41     13924920.23
#Sta/Elev= 30
  4295.6 1885.40  4309.8 1884.04  4337.0 1878.05  4342.3 1878.36  4369.5 1872.41
  4374.8 1873.11  4439.8 1858.38  4528.1 1846.94  4622.4 1830.81  4677.7 1828.56
  4977.5 1822.59  5010.3 1820.94  5070.7 1820.79  5075.8 1822.22  5119.1 1819.95
  5119.3 1819.45  5123.1 1819.95  5171.4 1822.90  5290.4 1822.62  5382.7 1826.09
  5397.0 1828.94  5411.3 1834.04  5453.0 1854.67  5495.8 1871.90  5524.4 1878.18
  5545.3 1885.66  5567.3 1890.45  5573.9 1894.52  5651.9 1899.07  5664.3 1897.85
#Mann=5,-1,0
  4295.6     0.1       0  4677.7    0.07       0  4977.5     0.1       0
  5119.1    0.05       0  5123.1     0.1       0
Bank Sta=5119.1,5123.1
Exp/Cntr=0.3,0.1

Chan Stop Cuts=-1