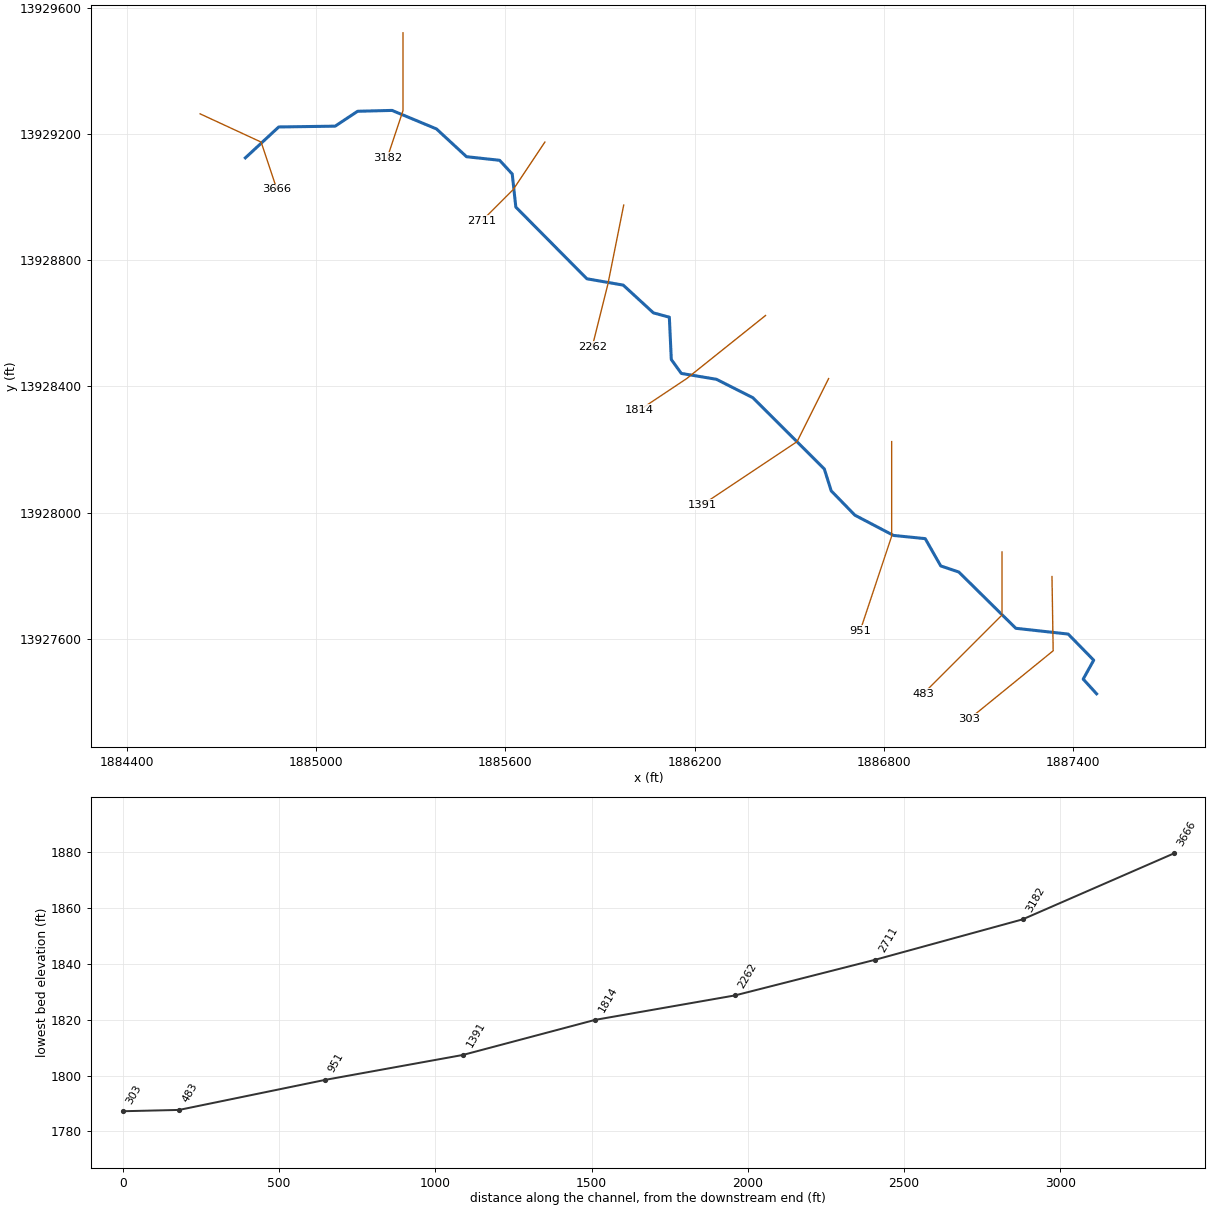
--- Stream0454.prj (project) ---

Proj Title=Stream0454 Base Level Engineering
Current Plan=p01
Default Exp/Contr=0.3,0.1
English Units
Geom File=g01
Flow File=f01
Plan File=p01
BEGIN DESCRIPTION:
Stream0454
END DESCRIPTION:

--- Stream0454.p01 (plan) ---

Plan Title=Multiple Run
Short Identifier=Multiple
Geom File=g01
Flow File=f01
Subcritical Flow
K Sum by GR= 0
Std Step Tol= 0.01
Critical Tol= 0.01
Num of Std Step Trials= 20
Max Error Tol= 0.3
Flow Tol Ratio= 0.001
Split Flow NTrial= 30
Split Flow Tol= 0.02
Split Flow Ratio= 0.02
Log Output Level= 0
Friction Slope Method= 1
Unsteady Friction Slope Method= 2
Unsteady Bridges Friction Slope Method= 1
Parabolic Critical Depth
Global Vel Dist=  1 , 1 , 1
Global Log Level= 0
CheckData=True
Encroach Param= -1, 0, 0, 0
BEGIN DESCRIPTION:
Multiple Run
END DESCRIPTION:

--- Stream0454.f01 (steady flow) ---

Flow Title=Multiple
Number of Profiles=7
Profile Names=10-year,25-year,50-year,1pct_min,100-year,1pct_plu,500-year
River Rch & RM= Stream0454,Reach-1,3666
     674    1123    1543    1028    2051    4092    3573
Boundary for River Rch & Prof#=Stream0454,Reach-1,1
Up Type=0
Dn Type=3
Dn Slope=0.005
Boundary for River Rch & Prof#=Stream0454,Reach-1,2
Up Type=0
Dn Type=3
Dn Slope=0.005
Boundary for River Rch & Prof#=Stream0454,Reach-1,3
Up Type=0
Dn Type=3
Dn Slope=0.005
Boundary for River Rch & Prof#=Stream0454,Reach-1,4
Up Type=0
Dn Type=3
Dn Slope=0.005
Boundary for River Rch & Prof#=Stream0454,Reach-1,5
Up Type=0
Dn Type=3
Dn Slope=0.005
Boundary for River Rch & Prof#=Stream0454,Reach-1,6
Up Type=0
Dn Type=3
Dn Slope=0.005
Boundary for River Rch & Prof#=Stream0454,Reach-1,7
Up Type=0
Dn Type=3
Dn Slope=0.005

--- Stream0454.g01 (geometry) ---

Geom Title=Existing Conditions

River Reach=Stream0454,Reach-1
Reach XY= 30
      1884775.00     13929125.00      1884880.84     13929222.98
      1885059.78     13929225.52      1885130.94     13929272.75
      1885240.16     13929275.48      1885381.05     13929216.84
      1885476.50     13929128.63      1885581.50     13929117.27
      1885621.49     13929073.75      1885632.86     13928968.83
      1885858.25     13928741.46      1885973.50     13928721.37
      1886069.31     13928633.32      1886119.81     13928619.56
      1886126.00     13928485.28      1886157.78     13928441.27
      1886269.03     13928422.66      1886384.68     13928364.24
      1886611.37     13928138.21      1886633.15     13928068.93
      1886708.29     13927991.63      1886830.97     13927927.33
      1886931.44     13927917.21      1886980.64     13927830.65
      1887037.98     13927811.28      1887218.81     13927632.82
      1887384.85     13927614.52      1887465.81     13927531.69
      1887432.52     13927471.67      1887475.00     13927425.00

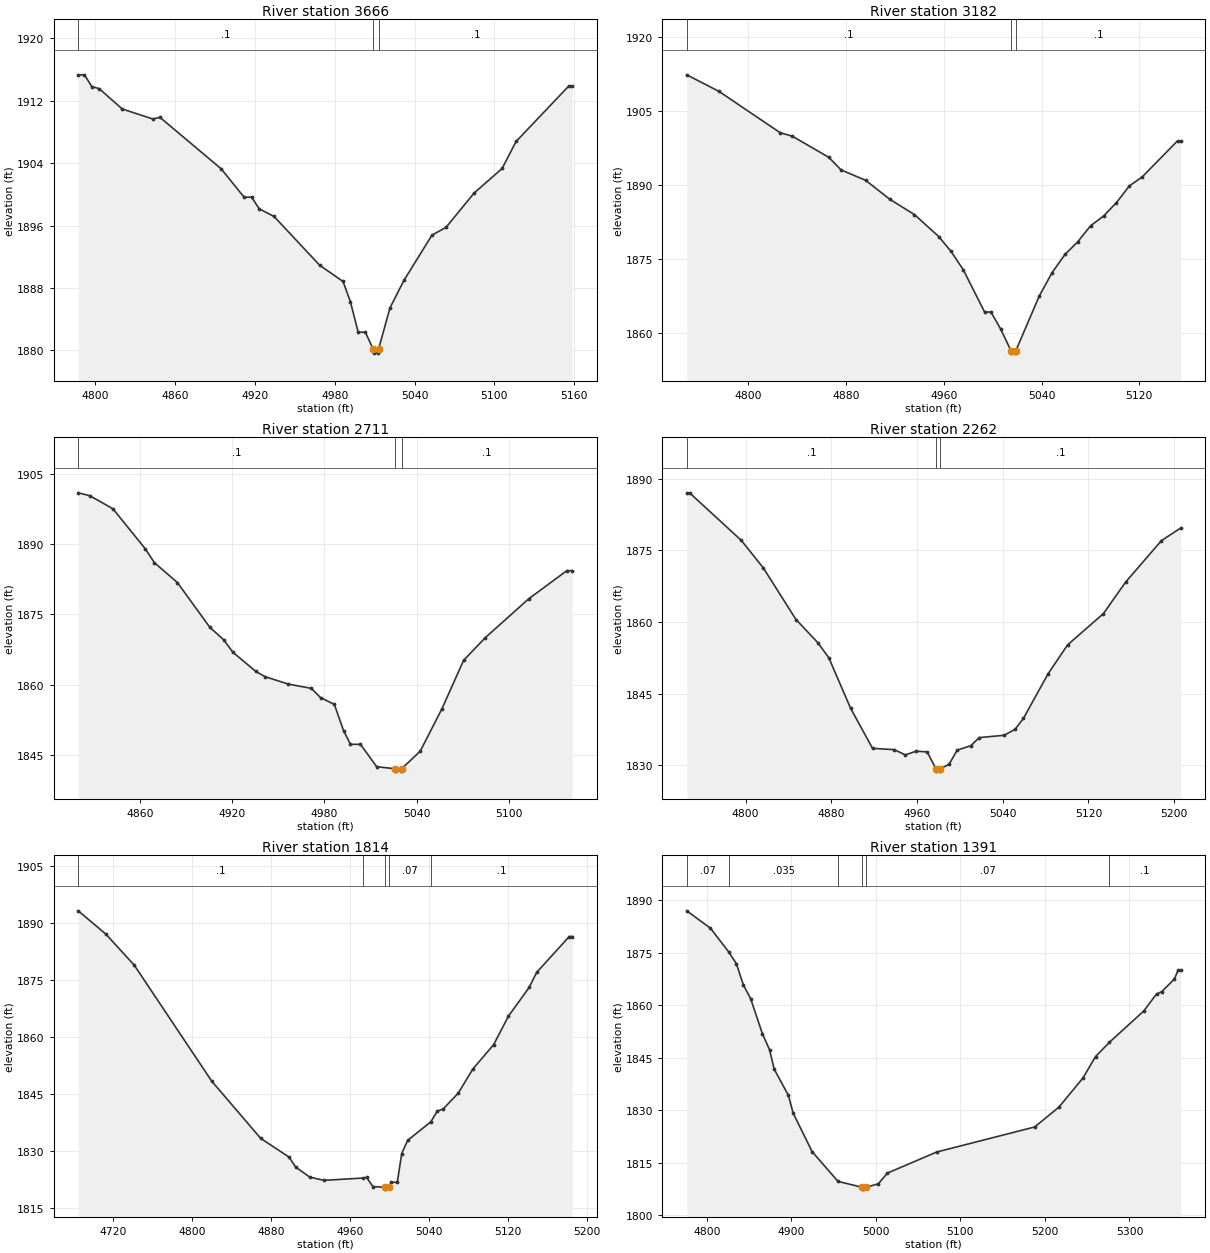
Type RM Length L Ch R = 1,3666,484,484,484
BEGIN DESCRIPTION:
Stream0454 8.0
END DESCRIPTION:
XS GIS Cut Line= 3
      1884631.47     13929264.61      1884825.00     13929175.00
      1884875.00     13929024.99
#Sta/Elev= 30
  4787.1 1915.33  4791.8 1915.33  4797.3 1913.82  4802.8 1913.56  4820.2 1910.95
  4843.1 1909.67  4848.6 1909.87  4894.5 1903.29  4911.9 1899.62  4917.4 1899.65
  4923.2 1898.14  4934.3 1897.17  4968.7 1890.90  4986.2 1888.83  4991.7 1886.26
  4997.6 1882.32  5003.0 1882.32  5008.9 1880.14  5009.2 1879.64  5012.7 1879.64
  5012.9 1880.14  5021.5 1885.45  5032.0 1888.97  5053.1 1894.78  5063.6 1895.76
  5084.7 1900.16  5105.8 1903.32  5116.3 1906.78  5155.8 1913.87  5158.5 1913.87
#Mann=3,-1,0
  4787.1     0.1       0  5008.9    0.05       0  5012.9     0.1       0
Bank Sta=5008.9,5012.9
Exp/Cntr=0.3,0.1

Type RM Length L Ch R = 1,3182,471,471,471
BEGIN DESCRIPTION:
Stream0454 7.0
END DESCRIPTION:
XS GIS Cut Line= 3
      1885275.01     13929521.42      1885275.00     13929275.00
      1885225.01     13929125.03
#Sta/Elev= 30
  4749.5 1912.26  4775.9 1908.91  4825.9 1900.57  4835.9 1899.86  4865.9 1895.57
  4875.9 1893.03  4895.9 1890.95  4915.9 1887.08  4935.9 1884.02  4955.9 1879.56
  4965.9 1876.57  4975.9 1872.87  4993.4 1864.31  4998.6 1864.31  5006.5 1860.90
  5015.0 1856.50  5015.2 1856.00  5018.7 1856.00  5019.0 1856.50  5038.1 1867.51
  5048.6 1872.25  5059.2 1875.94  5069.7 1878.51  5080.2 1881.75  5090.8 1883.71
  5101.3 1886.40  5111.9 1889.79  5122.4 1891.61  5151.4 1898.91  5154.0 1898.91
#Mann=3,-1,0
  4749.5     0.1       0  5015.0    0.05       0  5019.0     0.1       0
Bank Sta=5015,5019
Exp/Cntr=0.3,0.1

Type RM Length L Ch R = 1,2711,449,449,449
BEGIN DESCRIPTION:
Stream0454 6.0
END DESCRIPTION:
XS GIS Cut Line= 3
      1885725.01     13929175.02      1885625.00     13929025.00
      1885525.01     13928925.01
#Sta/Elev= 30
  4819.7 1900.89  4827.2 1900.28  4842.3 1897.49  4863.3 1888.98  4869.3 1885.99
  4884.3 1881.75  4905.4 1872.21  4914.4 1869.56  4920.4 1866.90  4935.4 1862.79
  4941.4 1861.68  4956.4 1860.11  4971.5 1859.19  4977.5 1857.22  4986.5 1855.77
  4992.5 1850.18  4997.0 1847.26  5003.5 1847.26  5014.1 1842.48  5026.3 1842.04
  5026.5 1841.54  5030.0 1841.54  5030.3 1842.04  5042.4 1845.78  5056.6 1854.86
  5070.7 1865.18  5084.9 1870.03  5113.1 1878.29  5137.9 1884.29  5141.4 1884.29
#Mann=3,-1,0
  4819.7     0.1       0  5026.3    0.05       0  5030.3     0.1       0
Bank Sta=5026.3,5030.3
Exp/Cntr=0.3,0.1

Type RM Length L Ch R = 1,2262,448,448,448
BEGIN DESCRIPTION:
Stream0454 5.0
END DESCRIPTION:
XS GIS Cut Line= 3
      1885975.01     13928975.03      1885925.00     13928725.00
      1885875.01     13928525.04
#Sta/Elev= 30
  4745.0 1887.08  4747.6 1887.08  4796.0 1877.09  4816.4 1871.36  4847.0 1860.52
  4867.4 1855.66  4877.6 1852.51  4898.0 1841.90  4918.4 1833.53  4938.8 1833.25
  4949.0 1832.15  4959.2 1832.93  4969.4 1832.78  4977.6 1829.25  4977.8 1828.75
  4981.3 1828.75  4981.6 1829.25  4989.8 1830.15  4997.4 1833.15  5010.3 1834.09
  5018.0 1835.78  5041.2 1836.26  5051.5 1837.51  5059.3 1839.82  5082.4 1849.19
  5100.5 1855.21  5134.0 1861.78  5154.6 1868.35  5188.1 1877.06  5206.1 1879.71
#Mann=3,-1,0
  4745.0     0.1       0  4977.6    0.05       0  4981.6     0.1       0
Bank Sta=4977.6,4981.6
Exp/Cntr=0.3,0.1

Type RM Length L Ch R = 1,1814,423,423,423
BEGIN DESCRIPTION:
Stream0454 4.0
END DESCRIPTION:
XS GIS Cut Line= 3
      1886425.00     13928625.00      1886175.00     13928425.00
      1886025.03     13928325.02
#Sta/Elev= 30
  4684.3 1893.26  4712.3 1887.13  4741.1 1878.93  4819.6 1848.38  4869.2 1833.32
  4898.0 1828.39  4904.4 1825.82  4918.8 1823.14  4933.2 1822.28  4972.8 1822.89
  4976.4 1823.07  4982.8 1820.63  4995.3 1820.47  4995.5 1819.97  4999.3 1820.47
  5001.3 1821.76  5007.5 1821.76  5012.0 1829.33  5018.0 1832.81  5041.5 1837.71
  5048.0 1840.50  5054.0 1841.08  5069.1 1845.20  5084.1 1851.61  5105.1 1858.01
  5120.1 1865.51  5141.2 1873.13  5148.7 1877.04  5181.7 1886.49  5184.7 1886.49
#Mann=5,-1,0
  4684.3     0.1       0  4972.8    0.07       0  4995.3    0.05       0
  4999.3    0.07       0  5041.5     0.1       0
Bank Sta=4995.3,4999.3
Exp/Cntr=0.3,0.1

Type RM Length L Ch R = 1,1391,440,440,440
BEGIN DESCRIPTION:
Stream0454 3.0
END DESCRIPTION:
XS GIS Cut Line= 3
      1886625.01     13928425.02      1886525.00     13928225.00
      1886224.99     13928024.99
#Sta/Elev= 30
  4776.4 1886.94  4804.4 1881.98  4826.3 1875.11  4835.1 1871.83  4843.5 1865.66
  4851.9 1861.88  4865.9 1851.78  4874.3 1847.25  4879.8 1841.69  4896.6 1834.21
  4902.2 1829.14  4924.6 1818.14  4955.2 1809.62  4984.1 1807.90  4984.3 1807.40
  4988.1 1807.90  5003.0 1808.93  5013.6 1811.97  5072.1 1818.01  5187.8 1825.16
  5216.4 1830.79  5244.9 1839.14  5259.9 1845.30  5276.3 1849.37  5317.0 1858.34
  5332.0 1863.18  5338.1 1863.83  5353.1 1867.44  5357.6 1870.04  5360.6 1870.04
#Mann=6,-1,0
  4776.4    0.07       0  4826.3   0.035       0  4955.2    0.07       0
  4984.1    0.05       0  4988.1    0.07       0  5276.3     0.1       0
Bank Sta=4984.1,4988.1
Exp/Cntr=0.3,0.1

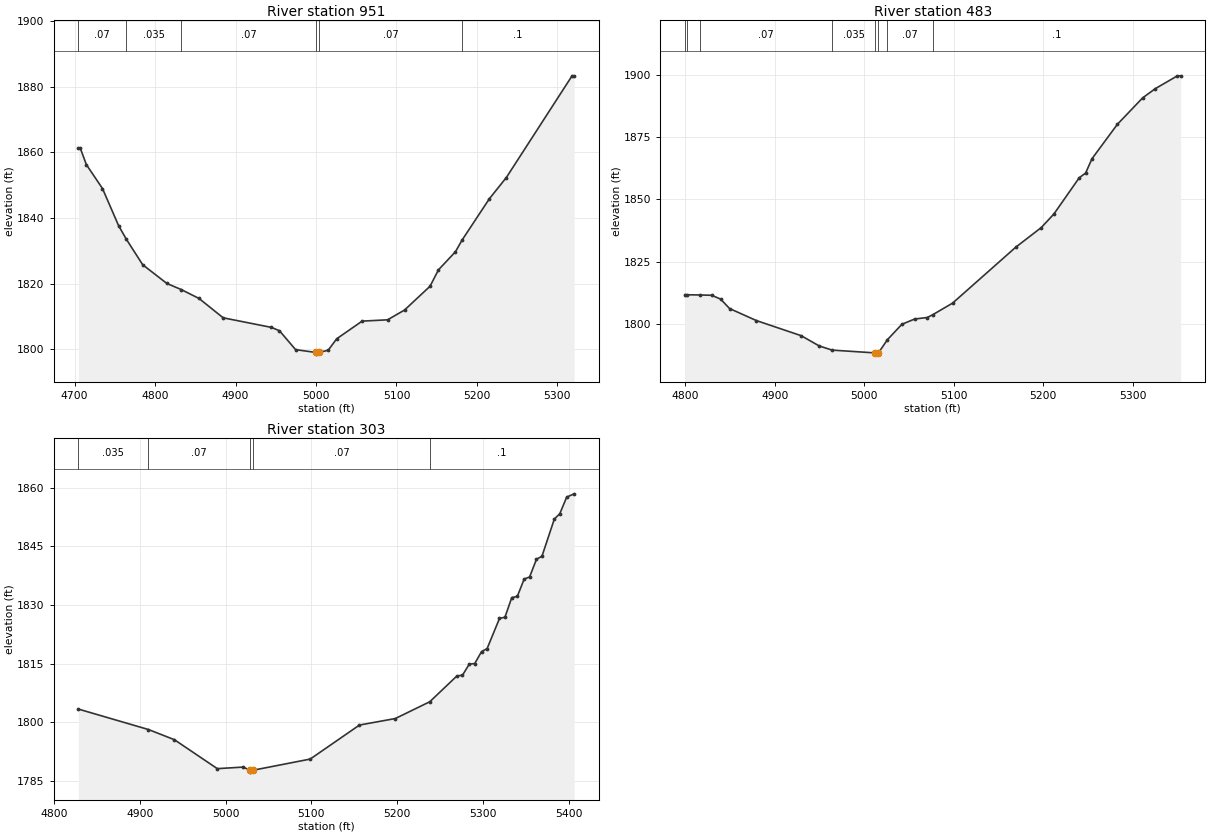
Type RM Length L Ch R = 1,951,468,468,468
BEGIN DESCRIPTION:
Stream0454 2.0
END DESCRIPTION:
XS GIS Cut Line= 3
      1886825.00     13928225.02      1886825.00     13927925.00
      1886725.01     13927625.04
#Sta/Elev= 30
  4704.6 1861.22  4707.1 1861.22  4714.6 1856.25  4734.6 1848.97  4754.6 1837.67
  4764.0 1833.61  4784.6 1825.73  4814.6 1820.03  4832.6 1818.15  4854.6 1815.45
  4884.6 1809.55  4944.6 1806.63  4954.6 1805.60  4974.6 1799.85  5000.1 1798.98
  5000.4 1798.48  5004.1 1798.98  5015.2 1799.69  5025.7 1803.16  5057.3 1808.54
  5088.9 1808.94  5110.0 1811.92  5141.7 1819.18  5152.2 1824.19  5173.3 1829.70
  5181.4 1833.21  5215.4 1845.84  5236.5 1852.31  5318.2 1883.32  5320.8 1883.32
#Mann=6,-1,0
  4704.6    0.07       0  4764.0   0.035       0  4832.6    0.07       0
  5000.1    0.05       0  5004.1    0.07       0  5181.4     0.1       0
Bank Sta=5000.1,5004.1
Exp/Cntr=0.3,0.1

Type RM Length L Ch R = 1,483,180,180,180
BEGIN DESCRIPTION:
Stream0454 1.0
END DESCRIPTION:
XS GIS Cut Line= 3
      1887175.00     13927875.01      1887175.00     13927675.00
      1886924.98     13927424.98
#Sta/Elev= 30
  4799.7 1811.61  4801.9 1811.61  4817.0 1811.53  4829.7 1811.41  4839.7 1809.86
  4849.7 1806.06  4879.7 1801.21  4929.7 1795.12  4949.7 1791.01  4964.1 1789.32
  5011.9 1788.20  5012.1 1787.70  5015.9 1788.20  5026.0 1793.55  5042.1 1799.72
  5056.3 1801.84  5070.4 1802.45  5076.6 1803.59  5098.7 1808.25  5169.4 1830.83
  5197.7 1838.68  5211.8 1844.15  5240.1 1858.75  5247.2 1860.63  5254.3 1866.40
  5282.6 1880.24  5310.8 1890.90  5325.0 1894.64  5349.7 1899.81  5353.3 1899.81
#Mann=8,-1,0
  4799.7    0.07       0  4801.9   0.035       0  4817.0    0.07       0
  4964.1   0.035       0  5011.9   0.035       0  5015.9   0.035       0
  5026.0    0.07       0  5076.6     0.1       0
Bank Sta=5011.9,5015.9
Exp/Cntr=0.3,0.1

Type RM Length L Ch R = 1,303,0,0,0
BEGIN DESCRIPTION:
Stream0454 0.0
END DESCRIPTION:
XS GIS Cut Line= 3
      1887333.51     13927796.90      1887337.29     13927561.53
      1887071.79     13927345.64
#Sta/Elev= 30
  4828.5 1803.37  4910.2 1798.13  4940.4 1795.53  4990.4 1788.12  5020.4 1788.52
  5028.4 1787.73  5028.7 1787.23  5032.4 1787.73  5098.6 1790.57  5156.0 1799.28
  5197.7 1800.94  5237.9 1805.24  5269.5 1811.84  5276.0 1812.03  5283.9 1814.86
  5290.3 1815.02  5298.2 1818.07  5304.7 1818.84  5319.1 1826.55  5325.5 1826.89
  5333.4 1831.89  5339.9 1832.20  5347.8 1836.62  5354.2 1837.18  5362.2 1841.71
  5368.6 1842.48  5383.0 1851.99  5389.4 1853.38  5397.4 1857.61  5406.1 1858.45
#Mann=5,-1,0
  4828.5   0.035       0  4910.2    0.07       0  5028.4    0.05       0
  5032.4    0.07       0  5237.9     0.1       0
Bank Sta=5028.4,5032.4
Exp/Cntr=0.3,0.1

Chan Stop Cuts=-1