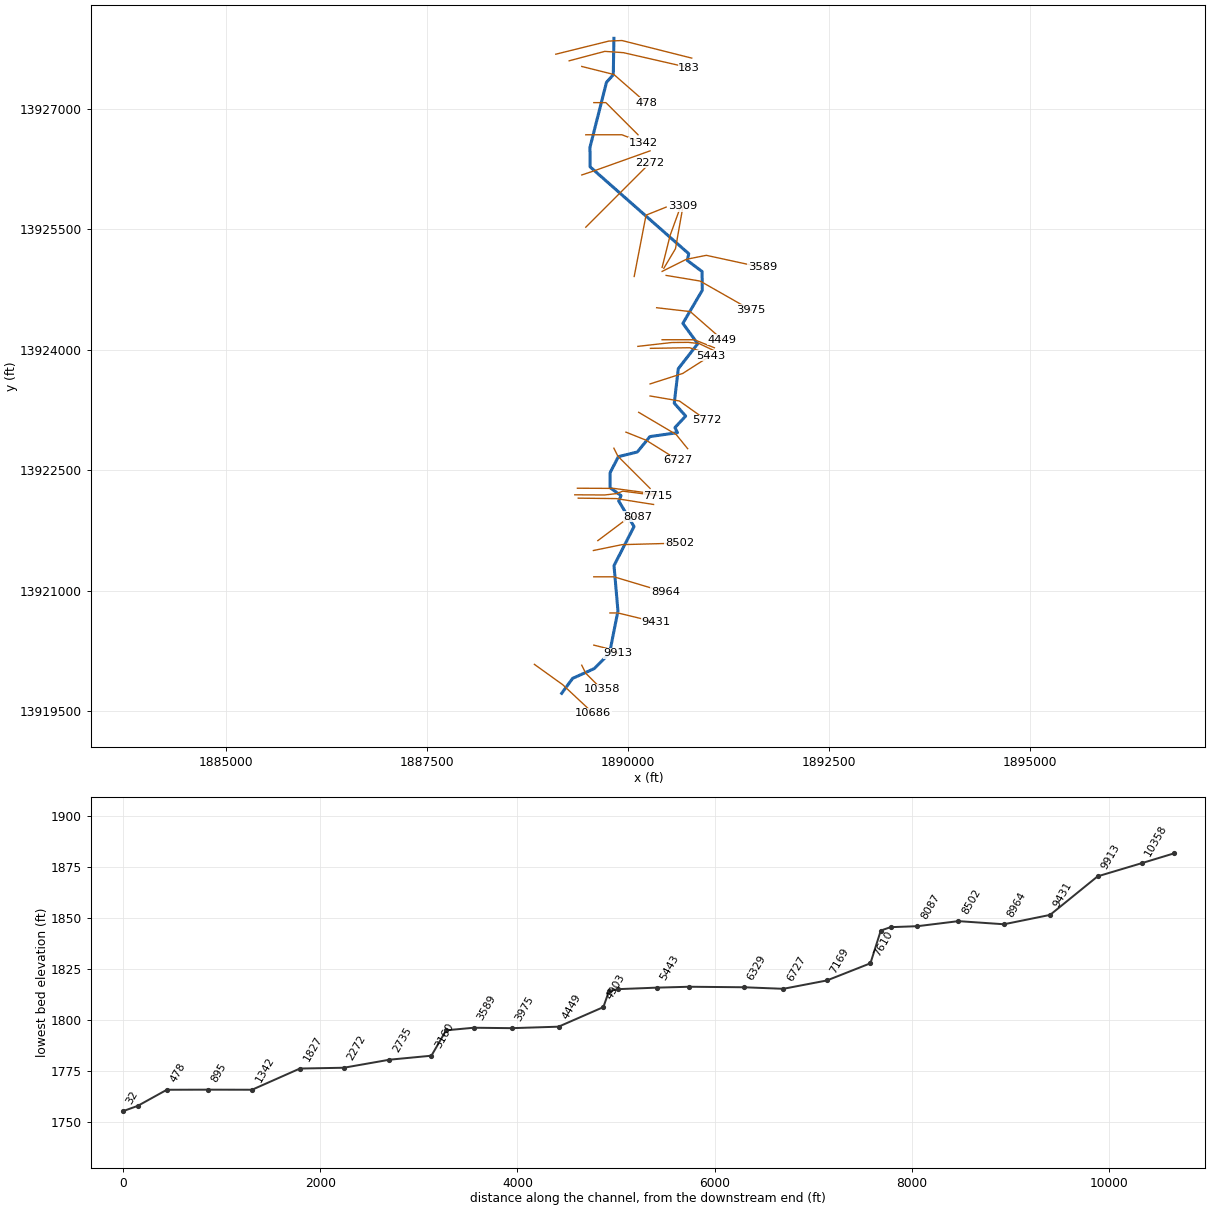
--- Stream0455.prj (project) ---

Proj Title=Stream0455 Base Level Engineering
Current Plan=p01
Default Exp/Contr=0.3,0.1
English Units
Geom File=g01
Flow File=f01
Plan File=p01
BEGIN DESCRIPTION:
Stream0455
END DESCRIPTION:

--- Stream0455.p01 (plan) ---

Plan Title=Multiple Run
Short Identifier=Multiple
Geom File=g01
Flow File=f01
Subcritical Flow
K Sum by GR= 0
Std Step Tol= 0.01
Critical Tol= 0.01
Num of Std Step Trials= 20
Max Error Tol= 0.3
Flow Tol Ratio= 0.001
Split Flow NTrial= 30
Split Flow Tol= 0.02
Split Flow Ratio= 0.02
Log Output Level= 0
Friction Slope Method= 1
Unsteady Friction Slope Method= 2
Unsteady Bridges Friction Slope Method= 1
Parabolic Critical Depth
Global Vel Dist=  1 , 1 , 1
Global Log Level= 0
CheckData=True
Encroach Param= -1, 0, 0, 0
BEGIN DESCRIPTION:
Multiple Run
END DESCRIPTION:

--- Stream0455.f01 (steady flow) ---

Flow Title=Multiple
Number of Profiles=7
Profile Names=10-year,25-year,50-year,1pct_min,100-year,1pct_plu,500-year
River Rch & RM= Stream0455,Reach-1,10686
    2348    4162    5952    4105    8191   16343   15330
River Rch & RM= Stream0455,Reach-1,2735
    2477    4414    6334    4381    8740   17439   16460
Boundary for River Rch & Prof#=Stream0455,Reach-1,1
Up Type=0
Dn Type=3
Dn Slope=0.005
Boundary for River Rch & Prof#=Stream0455,Reach-1,2
Up Type=0
Dn Type=3
Dn Slope=0.005
Boundary for River Rch & Prof#=Stream0455,Reach-1,3
Up Type=0
Dn Type=3
Dn Slope=0.005
Boundary for River Rch & Prof#=Stream0455,Reach-1,4
Up Type=0
Dn Type=3
Dn Slope=0.005
Boundary for River Rch & Prof#=Stream0455,Reach-1,5
Up Type=0
Dn Type=3
Dn Slope=0.005
Boundary for River Rch & Prof#=Stream0455,Reach-1,6
Up Type=0
Dn Type=3
Dn Slope=0.005
Boundary for River Rch & Prof#=Stream0455,Reach-1,7
Up Type=0
Dn Type=3
Dn Slope=0.005

--- Stream0455.g01 (geometry) ---

Geom Title=Existing Conditions

River Reach=Stream0455,Reach-1
Reach XY= 30
      1889175.00     13919725.00      1889311.76     13919911.39
      1889581.06     13920033.14      1889771.39     13920226.50
      1889875.20     13920749.92      1889826.20     13921314.50
      1890075.42     13921800.00      1889884.59     13922118.45
      1889913.77     13922185.02      1889778.07     13922283.30
      1889777.24     13922469.07      1889880.44     13922669.75
      1890116.66     13922728.16      1890272.55     13922919.54
      1890615.83     13922968.00      1890584.31     13923031.66
      1890717.93     13923175.00      1890575.93     13923335.48
      1890626.20     13923764.50      1890867.72     13924074.91
      1890683.01     13924328.28      1890924.90     13924740.40
      1890921.87     13924973.38      1890738.51     13925111.32
      1890755.79     13925195.38      1889528.53     13926276.45
      1889527.26     13926519.06      1889732.85     13927328.41
      1889817.18     13927421.58      1889825.00     13927875.00

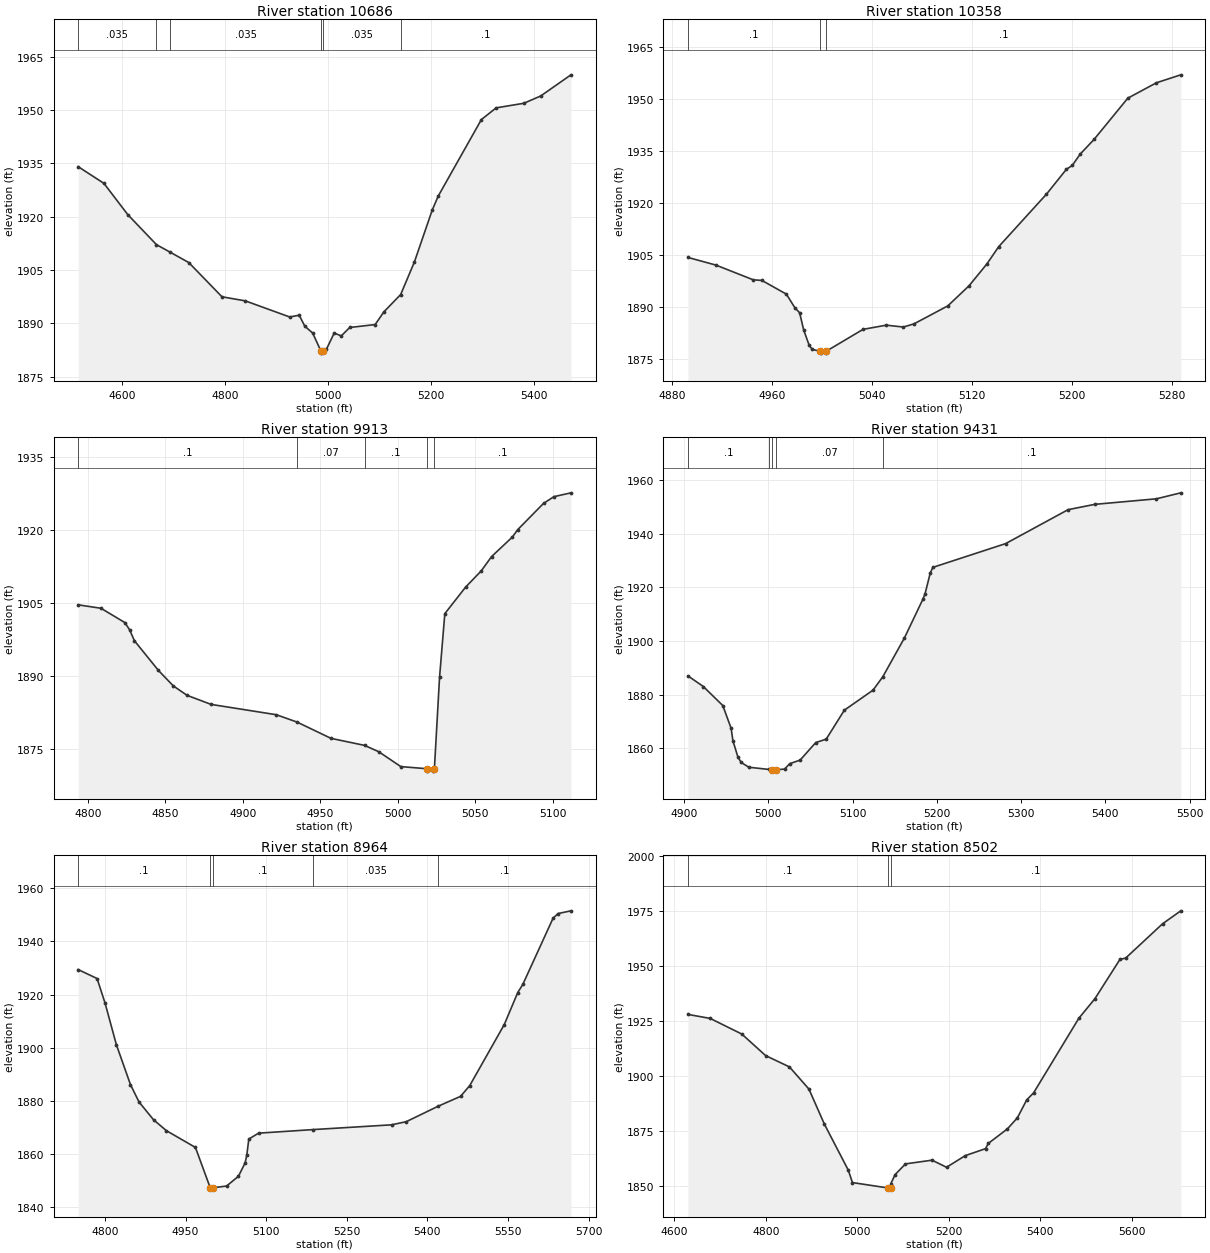
Type RM Length L Ch R = 1,10686,328,328,328
BEGIN DESCRIPTION:
Stream0455 24.0
END DESCRIPTION:
XS GIS Cut Line= 3
      1888835.23     13920085.82      1889187.63     13919832.68
      1889569.15     13919475.67
#Sta/Elev= 30
  4515.5 1934.05  4565.5 1929.36  4611.8 1920.57  4667.4 1912.14  4694.1 1910.01
  4730.2 1907.10  4794.6 1897.48  4839.8 1896.34  4926.0 1891.81  4944.5 1892.31
  4955.3 1889.22  4970.6 1887.30  4986.9 1882.15  4987.2 1881.65  4991.2 1882.15
  4997.3 1882.74  5012.4 1887.29  5026.1 1886.49  5042.5 1888.86  5091.8 1889.67
  5109.0 1893.27  5141.4 1898.12  5168.0 1907.25  5202.7 1921.87  5214.4 1925.82
  5298.1 1947.30  5326.8 1950.58  5380.3 1951.86  5413.1 1953.91  5471.9 1959.86
#Mann=6,-1,0
  4515.5   0.035       0  4667.4    0.07       0  4694.1   0.035       0
  4986.9   0.035       0  4991.2   0.035       0  5141.4     0.1       0
Bank Sta=4986.9,4991.2
Exp/Cntr=0.3,0.1

Type RM Length L Ch R = 1,10358,445,445,445
BEGIN DESCRIPTION:
Stream0455 23.0
END DESCRIPTION:
XS GIS Cut Line= 3
      1889424.99     13920075.03      1889475.00     13919975.00
      1889675.02     13919774.98
#Sta/Elev= 30
  4892.7 1904.37  4915.0 1902.18  4945.0 1897.93  4951.9 1897.76  4971.5 1893.81
  4978.2 1889.95  4982.1 1888.45  4985.4 1883.45  4989.7 1879.16  4992.1 1877.94
  4998.6 1877.33  4999.0 1876.83  5002.9 1876.83  5003.2 1877.33  5032.9 1883.67
  5051.5 1884.88  5065.2 1884.34  5073.7 1885.25  5100.8 1890.43  5117.8 1896.21
  5132.1 1902.50  5141.6 1907.49  5179.8 1922.58  5195.8 1929.75  5200.5 1930.86
  5206.9 1934.14  5217.9 1938.33  5245.0 1950.23  5267.9 1954.65  5287.4 1956.94
#Mann=3,-1,0
  4892.7     0.1       0  4998.6    0.05       0  5003.2     0.1       0
Bank Sta=4998.6,5003.2
Exp/Cntr=0.3,0.1

Type RM Length L Ch R = 1,9913,482,482,482
BEGIN DESCRIPTION:
Stream0455 22.0
END DESCRIPTION:
XS GIS Cut Line= 3
      1889575.00     13920325.00      1889775.00     13920275.00
      1889875.04     13920224.98
#Sta/Elev= 30
  4793.8 1904.56  4808.5 1903.86  4823.9 1900.92  4827.0 1899.43  4830.1 1897.18
  4845.6 1891.08  4855.2 1887.90  4864.1 1885.96  4879.6 1884.10  4921.7 1881.98
  4935.1 1880.46  4956.9 1877.13  4978.6 1875.68  4987.8 1874.37  5002.0 1871.32
  5018.6 1870.89  5019.0 1870.39  5022.9 1870.39  5023.2 1870.89  5023.7 1871.01
  5027.0 1889.66  5030.4 1902.75  5043.8 1908.20  5053.9 1911.54  5060.6 1914.49
  5074.0 1918.50  5077.4 1920.00  5094.1 1925.41  5100.8 1926.79  5111.8 1927.58
#Mann=5,-1,0
  4793.8     0.1       0  4935.1    0.07       0  4978.6     0.1       0
  5018.6    0.05       0  5023.2     0.1       0
Bank Sta=5018.6,5023.2
Exp/Cntr=0.3,0.1

Type RM Length L Ch R = 1,9431,467,467,467
BEGIN DESCRIPTION:
Stream0455 21.0
END DESCRIPTION:
XS GIS Cut Line= 3
      1889775.03     13920725.00      1889875.00     13920725.00
      1890346.32     13920610.91
#Sta/Elev= 30
  4904.6 1886.98  4922.8 1883.03  4945.9 1875.93  4955.8 1867.43  4957.9 1862.83
  4963.9 1856.67  4967.8 1854.69  4976.8 1852.91  5001.3 1852.07  5004.5 1851.96
  5004.8 1851.46  5009.3 1851.96  5019.2 1852.23  5025.4 1854.24  5037.7 1855.58
  5056.3 1862.14  5068.6 1863.37  5090.2 1874.21  5124.2 1881.67  5135.8 1886.66
  5161.4 1901.10  5183.6 1915.73  5185.9 1917.54  5192.1 1925.32  5195.2 1927.48
  5281.6 1936.35  5355.7 1949.01  5387.4 1951.00  5460.6 1953.07  5489.5 1955.30
#Mann=5,-1,0
  4904.6     0.1       0  5001.3    0.07       0  5004.5    0.05       0
  5009.3    0.07       0  5135.8     0.1       0
Bank Sta=5004.5,5009.3
Exp/Cntr=0.3,0.1

Type RM Length L Ch R = 1,8964,462,462,462
BEGIN DESCRIPTION:
Stream0455 20.0
END DESCRIPTION:
XS GIS Cut Line= 3
      1889575.00     13921175.00      1889825.00     13921175.00
      1890464.10     13920983.40
#Sta/Elev= 30
  4750.1 1929.37  4785.3 1926.00  4800.3 1916.65  4821.3 1901.07  4847.4 1886.16
  4863.3 1879.63  4890.3 1872.94  4914.3 1868.84  4968.3 1862.54  4995.9 1847.37
  4996.2 1846.87  5000.8 1847.37  5026.4 1848.04  5048.4 1851.71  5060.9 1856.76
  5064.0 1859.74  5067.7 1865.69  5085.9 1867.90  5187.2 1869.24  5333.4 1871.03
  5360.8 1872.22  5420.2 1878.03  5461.8 1881.73  5478.9 1885.77  5543.2 1908.72
  5568.3 1920.74  5577.7 1923.80  5634.0 1948.67  5643.4 1950.43  5667.3 1951.44
#Mann=5,-1,0
  4750.1     0.1       0  4995.9    0.05       0  5000.8     0.1       0
  5187.2   0.035       0  5420.2     0.1       0
Bank Sta=4995.9,5000.8
Exp/Cntr=0.3,0.1

Type RM Length L Ch R = 1,8502,415,415,415
BEGIN DESCRIPTION:
Stream0455 19.0
END DESCRIPTION:
XS GIS Cut Line= 3
      1889569.90     13921502.15      1889925.00     13921575.00
      1890640.05     13921594.19
#Sta/Elev= 30
  4629.9 1927.79  4678.4 1925.98  4747.6 1918.87  4799.7 1909.08  4851.8 1903.94
  4894.4 1893.87  4928.3 1877.90  4980.4 1857.06  4989.6 1851.38  5068.2 1848.90
  5068.6 1848.40  5073.1 1848.90  5073.7 1850.88  5082.7 1854.96  5105.6 1859.87
  5163.7 1861.56  5195.4 1858.33  5236.3 1863.62  5280.7 1866.79  5286.7 1869.17
  5328.7 1875.81  5350.3 1880.80  5370.7 1888.94  5385.8 1892.15  5484.7 1926.03
  5519.8 1934.91  5574.8 1952.84  5587.0 1953.37  5667.9 1968.99  5707.7 1974.87
#Mann=3,-1,0
  4629.9     0.1       0  5068.2    0.05       0  5073.1     0.1       0
Bank Sta=5068.2,5073.1
Exp/Cntr=0.3,0.1

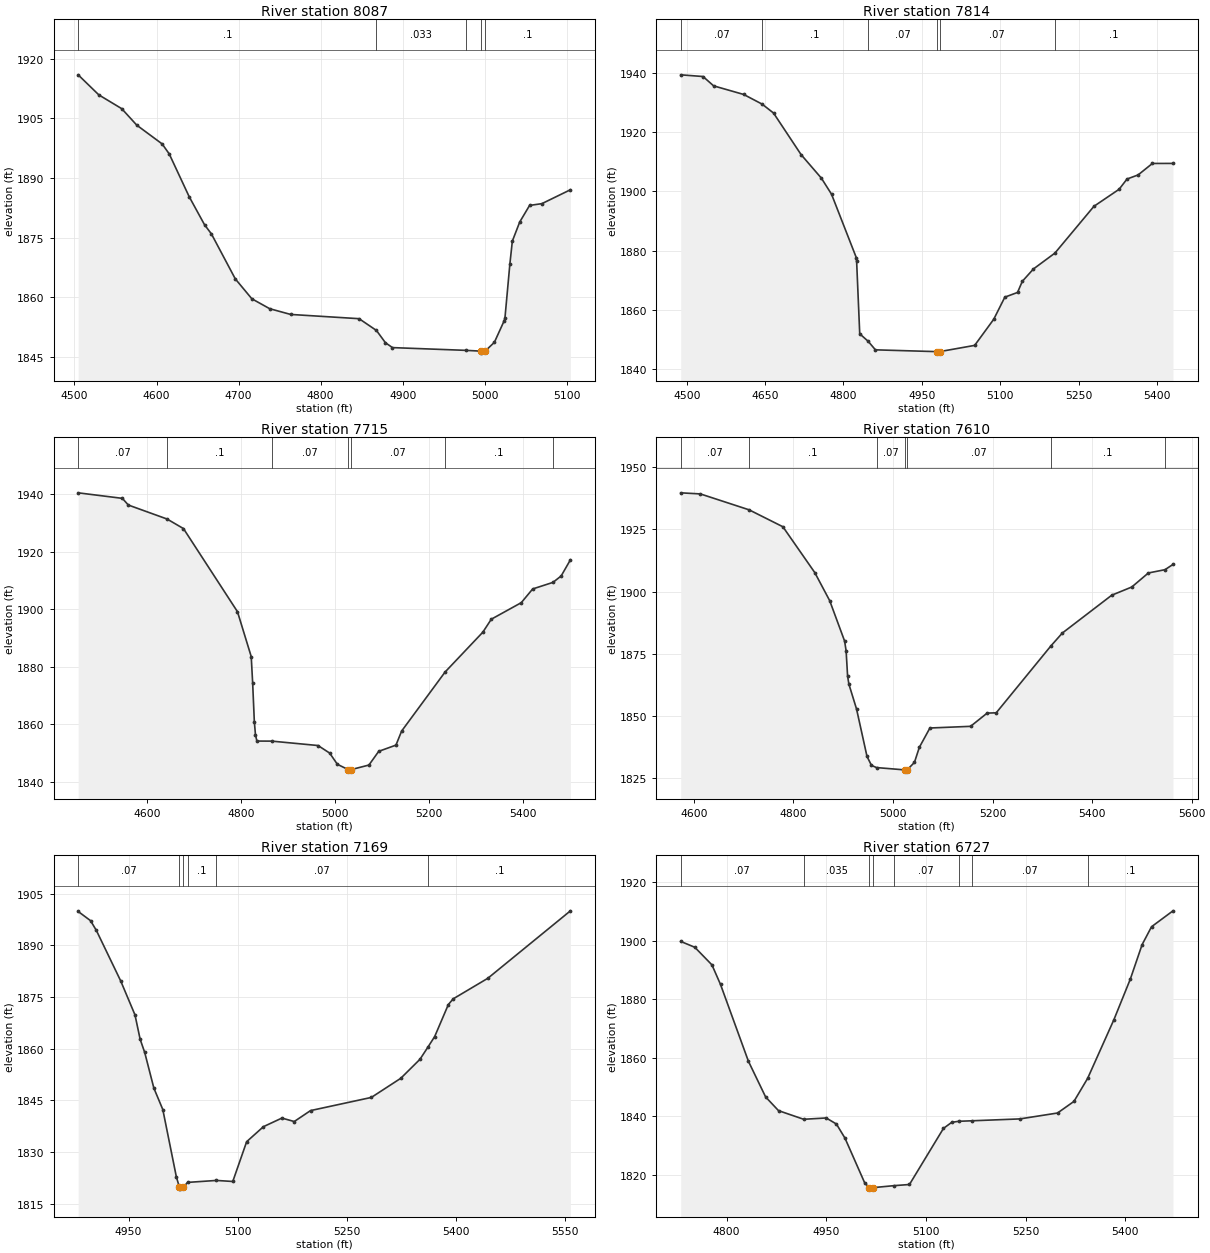
Type RM Length L Ch R = 1,8087,273,273,273
BEGIN DESCRIPTION:
Stream0455 18.0
END DESCRIPTION:
XS GIS Cut Line= 3
      1889625.00     13921625.00      1890025.00     13921925.00
      1890125.00     13921925.00
#Sta/Elev= 30
  4504.5 1915.98  4529.7 1910.93  4557.6 1907.46  4576.0 1903.30  4606.9 1898.58
  4615.5 1896.07  4639.8 1885.31  4658.5 1878.25  4666.9 1875.94  4696.0 1864.62
  4716.2 1859.60  4738.0 1857.10  4763.5 1855.66  4846.9 1854.59  4868.1 1851.62
  4879.0 1848.54  4887.6 1847.31  4976.7 1846.62  4995.5 1846.42  4995.9 1845.92
  5000.5 1846.42  5011.8 1848.64  5023.8 1854.09  5024.7 1854.79  5030.7 1868.38
  5033.7 1874.12  5042.7 1878.93  5054.7 1883.10  5069.7 1883.55  5104.5 1887.05
#Mann=5,-1,0
  4504.5     0.1       0  4868.1   0.033       0  4976.7     0.1       0
  4995.5    0.05       0  5000.5     0.1       0
Bank Sta=4995.5,5000.5
Exp/Cntr=0.3,0.1

Type RM Length L Ch R = 1,7814,99,99,99
BEGIN DESCRIPTION:
Mapping XS b6f5ba0e
END DESCRIPTION:
XS GIS Cut Line= 3
      1889381.53     13922153.56      1889854.86     13922148.13
      1890318.17     13922075.02
#Sta/Elev= 30
  4488.4 1939.24  4531.1 1938.67  4551.4 1935.52  4609.0 1932.62  4644.2 1929.37
  4666.1 1926.36  4718.9 1912.33  4757.7 1904.41  4777.1 1899.01  4824.5 1877.64
  4825.1 1876.63  4831.1 1851.95  4847.2 1849.44  4861.1 1846.55  4978.8 1845.94
  4979.2 1845.44  4983.9 1845.94  5051.1 1848.05  5087.7 1856.87  5108.9 1864.31
  5133.2 1865.89  5142.3 1869.63  5163.6 1873.80  5204.7 1879.15  5279.5 1894.93
  5327.6 1900.66  5342.8 1904.12  5364.0 1905.50  5391.4 1909.37  5430.8 1909.38
#Mann=6,-1,0
  4488.4    0.07       0  4644.2     0.1       0  4847.2    0.07       0
  4978.8    0.05       0  4983.9    0.07       0  5204.7     0.1       0
Bank Sta=4978.8,4983.9
Exp/Cntr=0.3,0.1

Type RM Length L Ch R = 1,7715,105,105,105
BEGIN DESCRIPTION:
Stream0455 17.1
END DESCRIPTION:
XS GIS Cut Line= 5
      1889338.63     13922195.31      1889709.74     13922193.14
      1889859.48     13922210.50      1889935.43     13922240.88
      1890373.75     13922184.46
#Sta/Elev= 30
  4454.4 1940.42  4548.3 1938.50  4561.0 1936.18  4643.3 1931.32  4678.1 1928.00
  4792.8 1899.14  4822.0 1883.56  4825.0 1874.54  4828.6 1860.99  4831.0 1856.45
  4834.0 1854.22  4865.6 1854.20  4963.9 1852.67  4988.6 1850.05  5005.0 1846.15
  5028.4 1844.28  5028.8 1843.78  5033.5 1844.28  5072.0 1845.89  5092.8 1850.65
  5129.4 1852.81  5141.5 1857.70  5233.8 1878.20  5314.0 1892.04  5331.9 1896.53
  5395.6 1902.28  5419.8 1907.04  5462.9 1909.32  5480.3 1911.55  5500.0 1917.17
#Mann=7,-1,0
  4454.4    0.07       0  4643.3     0.1       0  4865.6    0.07       0
  5028.4    0.05       0  5033.5    0.07       0  5233.8     0.1       0
  5462.9    0.07       0
Bank Sta=5028.4,5033.5
Exp/Cntr=0.3,0.1

Type RM Length L Ch R = 1,7610,441,441,441
BEGIN DESCRIPTION:
Stream0455 17.0
END DESCRIPTION:
XS GIS Cut Line= 3
      1889370.93     13922277.06      1889825.00     13922275.00
      1890355.29     13922203.96
#Sta/Elev= 30
  4573.4 1939.73  4612.9 1939.29  4710.9 1932.88  4778.7 1926.07  4842.7 1907.65
  4872.7 1896.34  4902.7 1880.06  4905.7 1876.16  4908.7 1865.96  4911.3 1862.71
  4926.7 1852.69  4947.7 1833.62  4956.7 1830.01  4966.9 1829.14  5023.2 1828.21
  5023.6 1827.71  5028.3 1828.21  5043.0 1831.23  5052.9 1837.31  5074.1 1845.07
  5155.8 1845.74  5189.1 1851.07  5207.3 1851.18  5317.2 1878.11  5340.1 1883.28
  5439.5 1898.53  5479.7 1901.82  5513.0 1907.47  5546.4 1908.79  5562.5 1910.91
#Mann=7,-1,0
  4573.4    0.07       0  4710.9     0.1       0  4966.9    0.07       0
  5023.2    0.05       0  5028.3    0.07       0  5317.2     0.1       0
  5546.4    0.07       0
Bank Sta=5023.2,5028.3
Exp/Cntr=0.3,0.1

Type RM Length L Ch R = 1,7169,442,442,442
BEGIN DESCRIPTION:
Stream0455 16.0
END DESCRIPTION:
XS GIS Cut Line= 3
      1889824.99     13922775.01      1889875.00     13922675.00
      1890275.00     13922275.00
#Sta/Elev= 30
  4880.6 1899.83  4897.6 1897.16  4905.6 1894.35  4939.1 1879.70  4958.8 1869.83
  4965.9 1862.77  4972.2 1858.92  4984.8 1848.58  4997.1 1842.37  5015.7 1822.90
  5020.0 1819.78  5020.4 1819.28  5025.2 1819.78  5031.1 1821.23  5070.9 1821.80
  5093.4 1821.50  5112.5 1833.04  5135.6 1837.40  5161.0 1839.89  5178.0 1838.89
  5200.4 1842.06  5284.1 1845.88  5324.6 1851.43  5351.0 1856.94  5362.3 1860.58
  5371.3 1863.55  5390.1 1872.83  5396.7 1874.47  5444.4 1880.44  5558.1 1900.01
#Mann=6,-1,0
  4880.6    0.07       0  5020.0    0.05       0  5025.2    0.07       0
  5031.1     0.1       0  5070.9    0.07       0  5362.3     0.1       0
Bank Sta=5020,5025.2
Exp/Cntr=0.3,0.1

Type RM Length L Ch R = 1,6727,398,398,398
BEGIN DESCRIPTION:
Stream0455 15.0
END DESCRIPTION:
XS GIS Cut Line= 3
      1889974.97     13922975.01      1890225.00     13922875.00
      1890625.01     13922624.99
#Sta/Elev= 30
  4731.0 1899.73  4752.2 1897.73  4778.0 1891.72  4790.9 1885.04  4832.9 1858.83
  4858.8 1846.64  4878.2 1841.97  4916.1 1839.02  4950.0 1839.47  4965.4 1837.39
  4978.3 1832.56  5008.1 1817.23  5015.0 1815.68  5015.4 1815.18  5020.2 1815.68
  5051.3 1816.35  5075.3 1816.76  5126.5 1835.91  5139.0 1837.99  5149.8 1838.34
  5170.0 1838.51  5241.6 1839.15  5298.2 1841.16  5322.9 1845.12  5343.5 1852.98
  5383.1 1873.04  5407.8 1886.89  5425.5 1898.63  5439.7 1904.74  5472.0 1910.17
#Mann=8,-1,0
  4731.0    0.07       0  4916.1   0.035       0  5015.0   0.035       0
  5020.2   0.035       0  5051.3    0.07       0  5149.8     0.1       0
  5170.0    0.07       0  5343.5     0.1       0
Bank Sta=5015,5020.2
Exp/Cntr=0.3,0.1

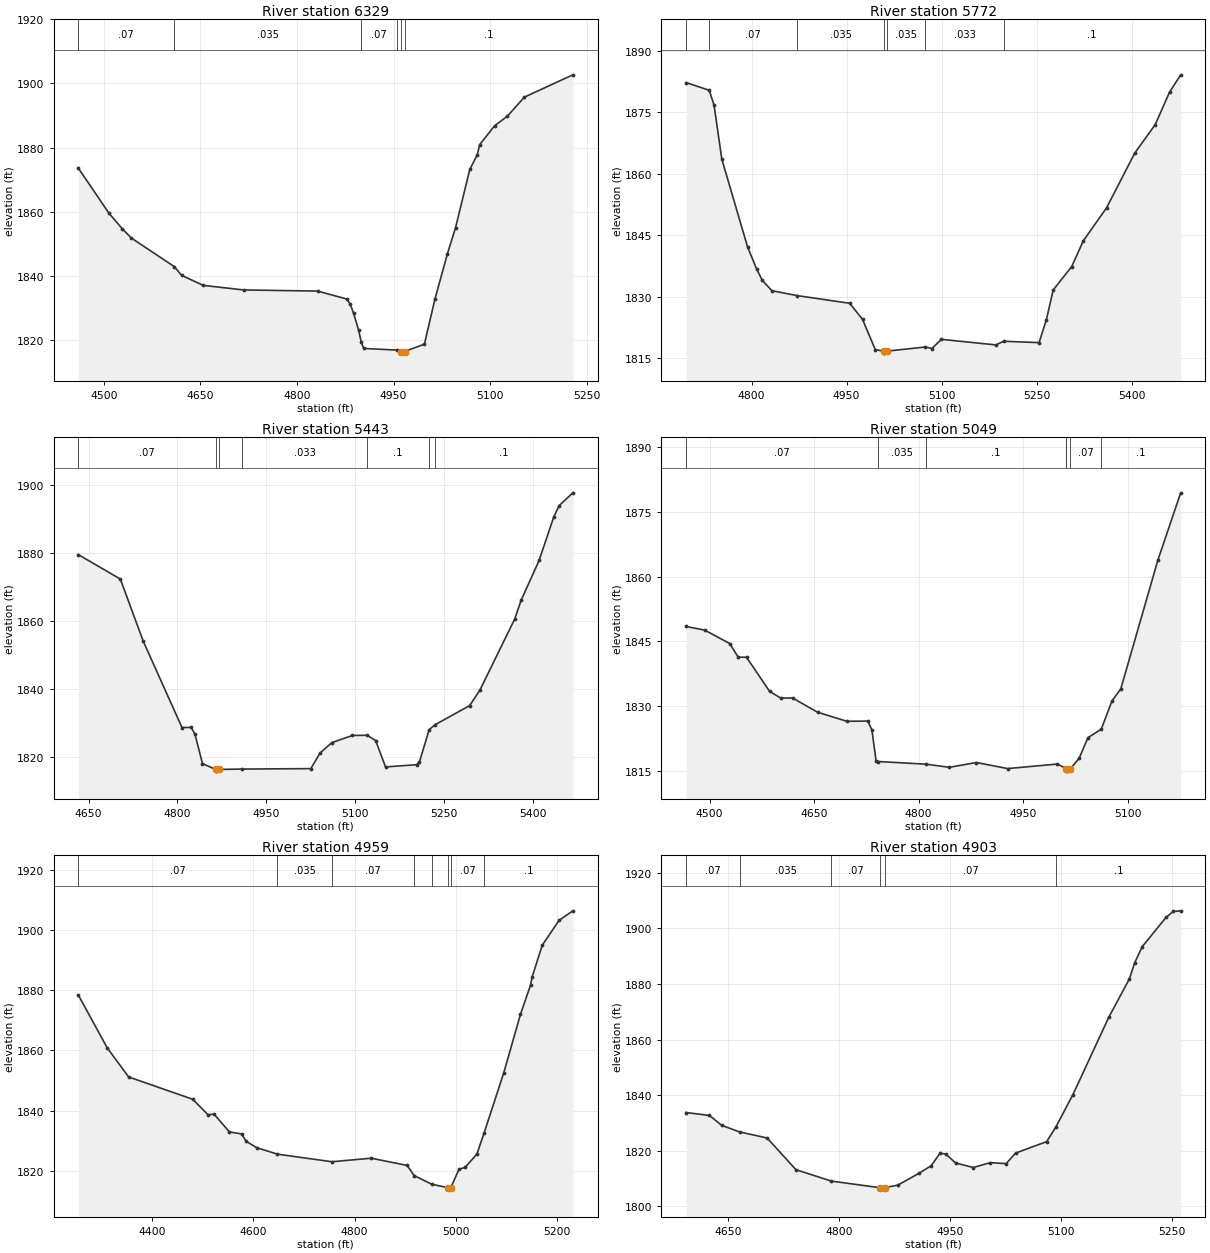
Type RM Length L Ch R = 1,6329,557,557,557
BEGIN DESCRIPTION:
Stream0455 14.0
END DESCRIPTION:
XS GIS Cut Line= 3
      1890133.48     13923221.50      1890598.66     13922946.40
      1890742.61     13922769.38
#Sta/Elev= 30
  4460.1 1873.64  4507.9 1859.53  4528.8 1854.64  4542.7 1851.80  4609.3 1842.91
  4620.8 1840.17  4654.3 1837.06  4717.0 1835.64  4832.0 1835.28  4877.3 1832.81
  4882.8 1831.20  4887.8 1828.42  4895.9 1823.02  4899.9 1819.30  4903.7 1817.41
  4955.8 1816.88  4961.8 1816.44  4962.3 1815.94  4967.1 1816.44  4998.0 1818.74
  5014.3 1832.75  5033.7 1846.88  5046.4 1855.06  5068.5 1873.19  5080.1 1877.76
  5083.9 1880.94  5107.1 1886.83  5126.5 1889.74  5153.5 1895.76  5228.7 1902.70
#Mann=6,-1,0
  4460.1    0.07       0  4609.3   0.035       0  4899.9    0.07       0
  4955.8     0.1       0  4961.8    0.05       0  4967.1     0.1       0
Bank Sta=4961.8,4967.1
Exp/Cntr=0.3,0.1

Type RM Length L Ch R = 1,5772,329,329,329
BEGIN DESCRIPTION:
Stream0455 13.0
END DESCRIPTION:
XS GIS Cut Line= 3
      1890275.00     13923425.00      1890639.93     13923362.74
      1890974.96     13923125.03
#Sta/Elev= 30
  4696.5 1882.29  4733.0 1880.41  4740.7 1876.77  4752.9 1863.60  4793.5 1842.18
  4807.7 1836.82  4816.8 1833.98  4832.0 1831.44  4871.9 1830.24  4954.9 1828.37
  4975.1 1824.44  4995.3 1817.03  5008.8 1816.69  5009.3 1816.19  5014.3 1816.69
  5074.4 1817.69  5084.7 1817.32  5099.6 1819.56  5185.6 1818.20  5198.1 1819.09
  5253.9 1818.75  5265.5 1824.40  5276.2 1831.63  5305.4 1837.33  5323.8 1843.64
  5360.6 1851.73  5405.0 1865.07  5437.3 1872.02  5459.9 1879.95  5477.5 1884.18
#Mann=7,-1,0
  4696.5     0.1       0  4733.0    0.07       0  4871.9   0.035       0
  5008.8   0.035       0  5014.3   0.035       0  5074.4   0.033       0
  5198.1     0.1       0
Bank Sta=5008.8,5014.3
Exp/Cntr=0.3,0.1

Type RM Length L Ch R = 1,5443,394,394,394
BEGIN DESCRIPTION:
Stream0455 12.0
END DESCRIPTION:
XS GIS Cut Line= 3
      1890275.00     13923575.00      1890681.56     13923705.39
      1891024.99     13923924.99
#Sta/Elev= 30
  4632.6 1879.61  4703.6 1872.39  4742.2 1854.08  4807.6 1828.61  4823.3 1828.63
  4829.6 1826.57  4842.2 1817.97  4864.6 1816.25  4865.0 1815.75  4870.1 1816.25
  4908.8 1816.36  5025.0 1816.49  5040.7 1821.12  5060.5 1824.16  5095.2 1826.26
  5120.1 1826.32  5134.4 1824.76  5151.1 1816.99  5203.9 1817.65  5208.2 1818.41
  5224.7 1827.96  5234.8 1829.45  5292.9 1835.06  5310.3 1839.62  5369.0 1860.59
  5379.8 1866.09  5410.2 1877.88  5435.1 1890.79  5444.2 1894.08  5467.2 1897.82
#Mann=7,-1,0
  4632.6    0.07       0  4864.6   0.033       0  4870.1    0.07       0
  4908.8   0.033       0  5120.1     0.1       0  5224.7   0.033       0
  5234.8     0.1       0
Bank Sta=4864.6,4870.1
Exp/Cntr=0.3,0.1

Type RM Length L Ch R = 1,5049,90,90,90
BEGIN DESCRIPTION:
Mapping XS f9f14f6a
END DESCRIPTION:
XS GIS Cut Line= 3
      1890279.82     13924017.63      1890766.16     13924025.27
      1890979.74     13923958.72
#Sta/Elev= 30
  4466.2 1848.47  4493.0 1847.62  4529.0 1844.51  4541.0 1841.37  4553.0 1841.35
  4586.0 1833.48  4602.1 1831.90  4619.0 1831.94  4655.0 1828.63  4697.0 1826.54
  4727.0 1826.59  4733.0 1824.53  4739.0 1817.38  4742.1 1817.23  4811.3 1816.61
  4844.0 1815.89  4883.0 1817.00  4927.9 1815.60  4999.2 1816.65  5011.6 1815.64
  5011.9 1815.51  5012.4 1815.01  5017.8 1815.51  5030.6 1818.01  5043.1 1822.75
  5062.2 1824.68  5077.7 1831.26  5090.3 1834.03  5143.7 1863.89  5176.3 1879.38
#Mann=7,-1,0
  4466.2    0.07       0  4742.1   0.035       0  4811.3     0.1       0
  5011.6    0.07       0  5011.9    0.05       0  5017.8    0.07       0
  5062.2     0.1       0
Bank Sta=5011.9,5017.8
Exp/Cntr=0.3,0.1

Type RM Length L Ch R = 1,4959,56,56,56
BEGIN DESCRIPTION:
Stream0455 11.1
END DESCRIPTION:
XS GIS Cut Line= 5
      1890123.56     13924042.27      1890544.55     13924090.01
      1890750.71     13924092.18      1890885.26     13924076.99
      1891078.37     13923985.86
#Sta/Elev= 30
  4253.3 1878.45  4310.7 1860.84  4353.0 1851.21  4479.8 1843.80  4510.0 1838.67
  4522.1 1838.85  4552.3 1832.96  4576.4 1832.29  4585.5 1829.84  4606.6 1827.71
  4647.5 1825.56  4755.1 1823.05  4833.0 1824.22  4904.2 1821.82  4917.9 1818.47
  4952.9 1815.56  4984.6 1814.45  4985.1 1813.95  4990.5 1814.45  5006.8 1820.56
  5019.0 1821.19  5042.2 1825.59  5056.3 1832.53  5095.3 1852.57  5128.4 1872.01
  5148.3 1881.70  5151.6 1884.47  5171.5 1894.98  5204.7 1903.20  5232.1 1906.39
#Mann=8,-1,0
  4253.3    0.07       0  4647.5   0.035       0  4755.1    0.07       0
  4917.9     0.1       0  4952.9    0.07       0  4984.6    0.05       0
  4990.5    0.07       0  5056.3     0.1       0
Bank Sta=4984.6,4990.5
Exp/Cntr=0.3,0.1

Type RM Length L Ch R = 1,4903,454,454,454
BEGIN DESCRIPTION:
Stream0455 11.0
END DESCRIPTION:
XS GIS Cut Line= 3
      1890425.02     13924125.00      1890825.00     13924125.00
      1891074.96     13924025.02
#Sta/Elev= 30
  4592.8 1833.76  4624.4 1832.70  4641.1 1829.13  4665.3 1826.77  4702.4 1824.60
  4741.4 1813.20  4789.4 1809.09  4855.4 1806.70  4855.9 1806.20  4861.3 1806.70
  4879.4 1807.65  4908.1 1811.92  4924.4 1814.63  4936.4 1819.10  4944.1 1818.85
  4957.4 1815.62  4981.4 1813.98  5004.4 1815.73  5025.8 1815.37  5038.7 1819.17
  5080.7 1823.30  5093.5 1828.73  5116.2 1840.20  5164.7 1868.03  5192.7 1881.89
  5199.7 1887.60  5209.9 1893.40  5242.2 1903.97  5251.9 1906.09  5262.0 1906.32
#Mann=6,-1,0
  4592.8    0.07       0  4665.3   0.035       0  4789.4    0.07       0
  4855.4    0.05       0  4861.3    0.07       0  5093.5     0.1       0
Bank Sta=4855.4,4861.3
Exp/Cntr=0.3,0.1

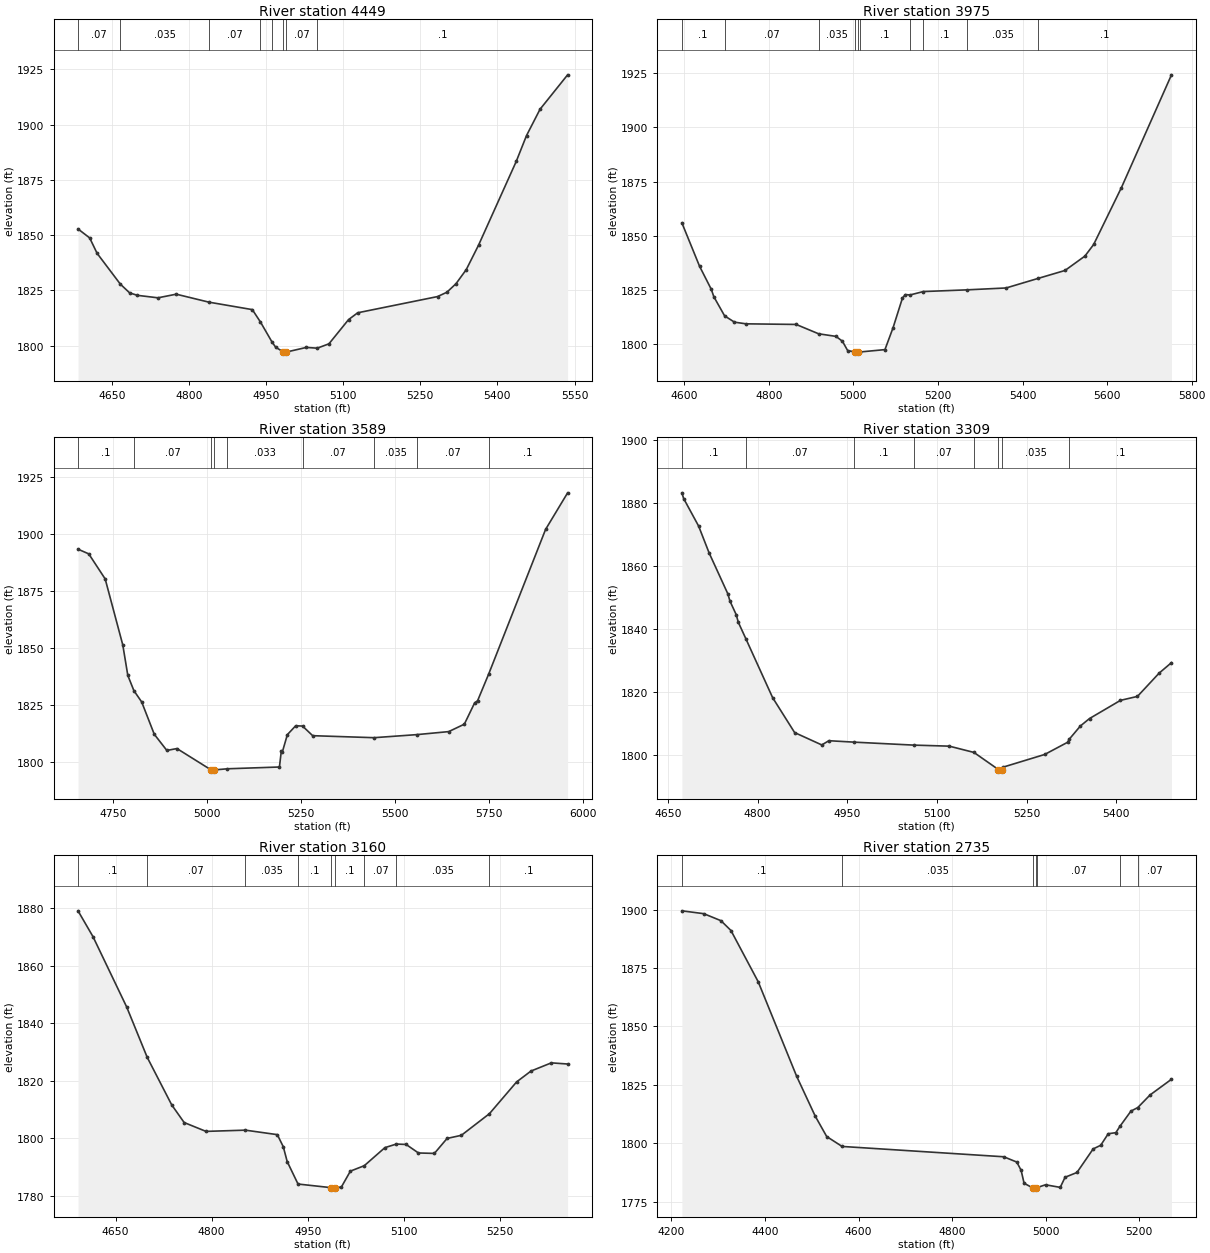
Type RM Length L Ch R = 1,4449,474,474,474
BEGIN DESCRIPTION:
Stream0455 10.0
END DESCRIPTION:
XS GIS Cut Line= 3
      1890356.75     13924523.02      1890775.00     13924475.00
      1891174.99     13924125.00
#Sta/Elev= 30
  4584.1 1852.76  4606.8 1848.70  4621.2 1841.74  4666.4 1827.81  4684.6 1823.83
  4699.7 1822.73  4739.6 1821.61  4775.2 1823.25  4838.7 1819.65  4923.2 1816.27
  4939.1 1810.64  4961.3 1801.70  4968.5 1799.29  4983.6 1797.09  4984.1 1796.59
  4989.6 1797.09  5028.3 1799.17  5049.5 1798.83  5072.3 1800.81  5110.4 1811.75
  5128.2 1814.84  5283.5 1822.17  5301.7 1824.13  5319.5 1828.01  5339.4 1834.37
  5363.3 1845.42  5436.6 1883.29  5456.6 1894.99  5482.9 1906.90  5536.6 1922.48
#Mann=8,-1,0
  4584.1    0.07       0  4666.4   0.035       0  4838.7    0.07       0
  4939.1   0.035       0  4961.3    0.07       0  4983.6    0.05       0
  4989.6    0.07       0  5049.5     0.1       0
Bank Sta=4983.6,4989.6
Exp/Cntr=0.3,0.1

Type RM Length L Ch R = 1,3975,386,386,386
BEGIN DESCRIPTION:
Stream0455 9.0
END DESCRIPTION:
XS GIS Cut Line= 3
      1890474.99     13924925.00      1890896.88     13924855.16
      1891531.59     13924494.20
#Sta/Elev= 30
  4594.5 1855.94  4636.2 1835.97  4664.1 1825.25  4670.1 1821.85  4695.5 1813.06
  4718.8 1810.14  4746.2 1809.37  4864.7 1809.09  4917.8 1804.78  4959.0 1803.58
  4974.2 1801.33  4986.4 1797.07  5004.6 1796.36  5005.1 1795.86  5010.7 1796.36
  5016.2 1796.40  5074.7 1797.48  5093.9 1807.57  5116.2 1821.32  5123.1 1822.85
  5134.1 1822.69  5165.4 1824.25  5268.7 1825.04  5361.2 1825.91  5436.8 1830.31
  5500.5 1833.98  5547.6 1840.61  5568.3 1845.97  5634.0 1872.22  5752.3 1924.20
#Mann=10,-1,0
  4594.5     0.1       0  4695.5    0.07       0  4917.8   0.035       0
  5004.6   0.035       0  5010.7   0.035       0  5016.2     0.1       0
  5134.1    0.07       0  5165.4     0.1       0  5268.7   0.035       0
  5436.8     0.1       0
Bank Sta=5004.6,5010.7
Exp/Cntr=0.3,0.1

Type RM Length L Ch R = 1,3589,280,280,280
BEGIN DESCRIPTION:
Stream0455 8.0
END DESCRIPTION:
XS GIS Cut Line= 4
      1890424.97     13924974.98      1890725.00     13925125.00
      1890975.00     13925175.00      1891671.98     13925023.75
#Sta/Elev= 30
  4656.6 1893.51  4685.2 1891.45  4728.9 1880.45  4775.8 1851.46  4789.2 1838.07
  4805.4 1831.39  4826.1 1826.44  4859.6 1812.26  4893.1 1805.15  4920.0 1805.98
  5011.3 1796.57  5011.8 1796.07  5017.5 1796.57  5054.5 1797.10  5192.9 1797.88
  5198.0 1805.06  5200.5 1804.40  5214.0 1812.09  5236.2 1815.99  5254.4 1815.85
  5281.4 1811.63  5444.8 1810.75  5559.1 1812.10  5643.6 1813.42  5685.2 1816.68
  5712.7 1826.06  5720.5 1826.98  5750.2 1838.77  5901.5 1902.18  5960.2 1918.25
#Mann=9,-1,0
  4656.6     0.1       0  4805.4    0.07       0  5011.3    0.05       0
  5017.5    0.07       0  5054.5   0.033       0  5254.4    0.07       0
  5444.8   0.035       0  5559.1    0.07       0  5750.2     0.1       0
Bank Sta=5011.3,5017.5
Exp/Cntr=0.3,0.1

Type RM Length L Ch R = 1,3309,149,149,149
BEGIN DESCRIPTION:
Mapping XS ddb4bc66
END DESCRIPTION:
XS GIS Cut Line= 3
      1890446.54     13925014.61      1890590.95     13925257.18
      1890684.55     13925785.65
#Sta/Elev= 30
  4673.4 1883.29  4676.4 1881.46  4701.4 1872.72  4718.9 1864.21  4750.3 1851.17
  4753.8 1848.87  4764.3 1844.55  4767.8 1842.12  4780.3 1836.95  4825.2 1818.17
  4862.0 1807.07  4907.4 1803.14  4919.3 1804.48  4961.0 1804.03  5061.4 1803.08
  5120.7 1802.75  5161.9 1800.76  5202.9 1795.31  5203.4 1794.81  5209.1 1795.31
  5210.4 1796.06  5280.2 1800.10  5318.8 1804.00  5321.5 1804.98  5340.1 1809.18
  5355.3 1811.53  5407.1 1817.31  5435.5 1818.57  5471.8 1825.98  5492.4 1829.30
#Mann=8,-1,0
  4673.4     0.1       0  4780.3    0.07       0  4961.0     0.1       0
  5061.4    0.07       0  5161.9   0.035       0  5202.9    0.05       0
  5209.1   0.035       0  5321.5     0.1       0
Bank Sta=5202.9,5209.1
Exp/Cntr=0.3,0.1

Type RM Length L Ch R = 1,3160,425,425,425
BEGIN DESCRIPTION:
Stream0455 7.0
END DESCRIPTION:
XS GIS Cut Line= 3
      1890425.00     13925025.00      1890525.00     13925425.00
      1890645.29     13925755.48
#Sta/Elev= 30
  4591.5 1879.03  4614.9 1870.04  4667.5 1845.59  4699.4 1828.16  4737.7 1811.61
  4757.1 1805.48  4791.2 1802.40  4852.7 1802.83  4902.5 1801.27  4911.8 1797.07
  4917.9 1791.92  4934.8 1784.11  4986.9 1782.84  4987.4 1782.34  4993.1 1782.84
  5002.4 1783.05  5016.5 1788.59  5038.2 1790.48  5070.4 1796.76  5088.3 1798.00
  5103.5 1797.86  5122.7 1794.90  5147.6 1794.75  5167.4 1799.95  5189.7 1801.04
  5233.5 1808.55  5275.9 1819.59  5298.3 1823.36  5330.1 1826.21  5355.5 1825.81
#Mann=9,-1,0
  4591.5     0.1       0  4699.4    0.07       0  4852.7   0.035       0
  4934.8     0.1       0  4986.9    0.05       0  4993.1     0.1       0
  5038.2    0.07       0  5088.3   0.035       0  5233.5     0.1       0
Bank Sta=4986.9,4993.1
Exp/Cntr=0.3,0.1

Type RM Length L Ch R = 1,2735,463,463,463
BEGIN DESCRIPTION:
Stream0455 6.0
END DESCRIPTION:
XS GIS Cut Line= 3
      1890077.34     13924911.73      1890225.00     13925675.00
      1890475.02     13925775.01
#Sta/Elev= 30
  4222.3 1899.49  4269.1 1898.27  4305.8 1895.27  4327.2 1891.07  4385.5 1869.12
  4467.7 1828.66  4507.4 1811.61  4531.9 1802.89  4564.8 1798.65  4910.4 1794.23
  4938.3 1791.96  4947.5 1788.45  4953.9 1782.89  4972.6 1780.88  4973.1 1780.38
  4979.1 1780.88  4981.0 1781.00  4999.7 1782.24  5031.2 1781.13  5041.5 1785.46
  5066.9 1787.50  5101.5 1797.58  5117.7 1799.15  5133.8 1804.09  5150.0 1804.54
  5158.8 1807.26  5182.3 1813.76  5197.0 1815.30  5223.3 1820.70  5269.0 1827.40
#Mann=7,-1,0
  4222.3     0.1       0  4564.8   0.035       0  4972.6    0.05       0
  4979.1   0.035       0  4981.0    0.07       0  5158.8   0.035       0
  5197.0    0.07       0
Bank Sta=4972.6,4979.1
Exp/Cntr=0.3,0.1

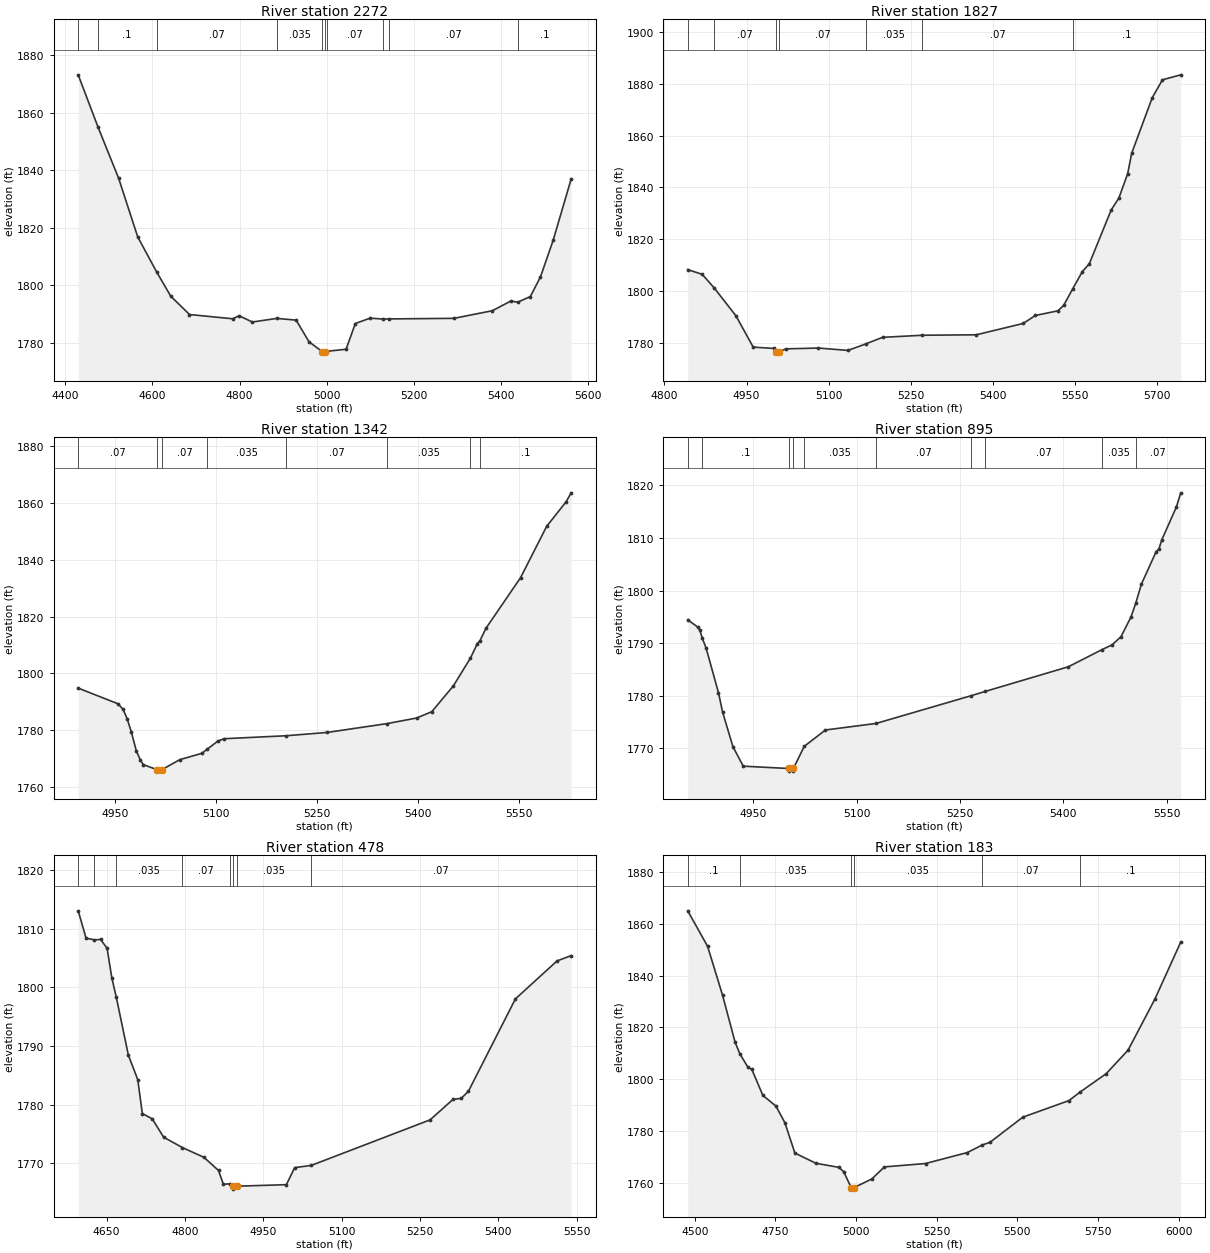
Type RM Length L Ch R = 1,2272,445,445,445
BEGIN DESCRIPTION:
Stream0455 5.0
END DESCRIPTION:
XS GIS Cut Line= 3
      1889475.03     13925525.03      1889875.00     13925925.00
      1890274.98     13926324.98
#Sta/Elev= 30
  4429.6 1873.17  4474.7 1855.16  4522.5 1837.16  4566.2 1816.83  4609.6 1804.66
  4641.9 1796.24  4685.0 1789.85  4784.0 1788.37  4798.9 1789.41  4829.2 1787.25
  4885.3 1788.50  4929.7 1787.90  4959.4 1780.34  4990.0 1776.93  4990.5 1776.43
  4996.7 1776.93  4999.5 1777.06  5044.3 1777.77  5065.5 1786.72  5099.4 1788.59
  5128.4 1788.28  5143.2 1788.32  5291.7 1788.52  5380.1 1791.18  5422.5 1794.56
  5438.0 1794.13  5467.1 1796.10  5490.4 1802.94  5519.5 1815.68  5560.9 1837.03
#Mann=10,-1,0
  4429.6    0.07       0  4474.7     0.1       0  4609.6    0.07       0
  4885.3   0.035       0  4990.0    0.05       0  4996.7   0.035       0
  4999.5    0.07       0  5128.4   0.035       0  5143.2    0.07       0
  5438.0     0.1       0
Bank Sta=4990,4996.7
Exp/Cntr=0.3,0.1

Type RM Length L Ch R = 1,1827,485,485,485
BEGIN DESCRIPTION:
Stream0455 4.0
END DESCRIPTION:
XS GIS Cut Line= 3
      1889425.04     13926175.01      1889575.00     13926225.00
      1890275.03     13926475.01
#Sta/Elev= 30
  4842.5 1808.29  4868.8 1806.49  4890.7 1801.27  4930.6 1790.47  4962.2 1778.35
  5000.2 1777.85  5003.1 1776.54  5003.6 1776.04  5009.9 1776.54  5021.9 1777.69
  5081.4 1778.00  5135.4 1777.09  5167.6 1779.57  5198.8 1782.14  5271.2 1782.94
  5370.1 1783.12  5455.7 1787.49  5478.3 1790.59  5519.4 1792.38  5529.7 1794.45
  5546.5 1800.92  5564.0 1807.54  5576.7 1810.55  5616.6 1831.28  5630.7 1835.90
  5646.8 1845.30  5654.1 1853.17  5691.7 1874.66  5710.5 1881.59  5743.9 1883.51
#Mann=7,-1,0
  4842.5   0.035       0  4890.7    0.07       0  5003.1    0.05       0
  5009.9    0.07       0  5167.6   0.035       0  5271.2    0.07       0
  5546.5     0.1       0
Bank Sta=5003.1,5009.9
Exp/Cntr=0.3,0.1

Type RM Length L Ch R = 1,1342,447,447,447
BEGIN DESCRIPTION:
Stream0455 3.0
END DESCRIPTION:
XS GIS Cut Line= 4
      1889474.95     13926675.00      1889575.00     13926675.00
      1889925.00     13926675.00      1890187.70     13926573.70
#Sta/Elev= 30
  4895.3 1794.85  4954.3 1789.34  4962.0 1787.35  4968.0 1784.01  4974.0 1779.55
  4981.6 1772.70  4987.6 1769.52  4992.0 1767.91  5012.5 1766.13  5013.0 1765.63
  5019.4 1766.13  5046.0 1769.66  5079.0 1771.91  5086.4 1773.29  5103.0 1776.27
  5112.0 1777.04  5203.7 1778.08  5265.0 1779.25  5353.4 1782.35  5397.4 1784.32
  5420.0 1786.55  5452.1 1795.66  5477.4 1805.45  5487.5 1810.45  5491.6 1811.58
  5500.3 1815.88  5551.8 1833.76  5590.4 1851.76  5619.3 1860.45  5626.9 1863.59
#Mann=8,-1,0
  4895.3    0.07       0  5012.5    0.05       0  5019.4    0.07       0
  5086.4   0.035       0  5203.7    0.07       0  5353.4   0.035       0
  5477.4    0.07       0  5491.6     0.1       0
Bank Sta=5012.5,5019.4
Exp/Cntr=0.3,0.1

Type RM Length L Ch R = 1,895,417,417,417
BEGIN DESCRIPTION:
Stream0455 2.0
END DESCRIPTION:
XS GIS Cut Line= 3
      1889575.05     13927075.00      1889725.00     13927075.00
      1890124.97     13926675.03
#Sta/Elev= 30
  4854.7 1794.43  4869.3 1793.05  4872.3 1792.45  4875.9 1790.90  4881.3 1789.09
  4899.3 1780.59  4905.3 1776.89  4920.3 1770.32  4935.3 1766.61  5001.2 1766.17
  5001.7 1765.67  5007.6 1765.67  5008.1 1766.17  5023.8 1770.38  5054.6 1773.49
  5128.0 1774.73  5265.6 1779.99  5286.7 1780.83  5407.2 1785.51  5455.9 1788.76
  5470.4 1789.66  5483.5 1791.21  5498.2 1795.01  5504.9 1797.57  5513.2 1801.23
  5534.4 1807.34  5538.7 1807.94  5542.9 1809.68  5563.9 1815.86  5570.3 1818.57
#Mann=10,-1,0
  4854.7    0.07       0  4875.9     0.1       0  5001.2    0.05       0
  5008.1     0.1       0  5023.8   0.035       0  5128.0    0.07       0
  5265.6   0.035       0  5286.7    0.07       0  5455.9   0.035       0
  5504.9    0.07       0
Bank Sta=5001.2,5008.1
Exp/Cntr=0.3,0.1

Type RM Length L Ch R = 1,478,295,295,295
BEGIN DESCRIPTION:
Stream0455 1.0
END DESCRIPTION:
XS GIS Cut Line= 3
      1889425.00     13927525.00      1889825.00     13927425.00
      1890224.98     13927075.01
#Sta/Elev= 30
  4595.6 1813.07  4610.7 1808.41  4626.7 1808.12  4638.5 1808.19  4650.9 1806.68
  4660.1 1801.57  4668.3 1798.44  4691.7 1788.45  4709.6 1784.29  4718.4 1778.51
  4737.4 1777.60  4759.1 1774.48  4795.0 1772.71  4836.4 1771.04  4864.2 1768.80
  4873.5 1766.46  4885.5 1766.52  4891.6 1766.12  4892.1 1765.62  4898.7 1766.12
  4994.1 1766.38  5010.1 1769.29  5041.7 1769.66  5269.2 1777.43  5313.0 1780.91
  5329.0 1781.11  5342.5 1782.29  5432.6 1798.06  5512.3 1804.53  5539.4 1805.44
#Mann=8,-1,0
  4595.6   0.035       0  4626.7     0.1       0  4668.3   0.035       0
  4795.0    0.07       0  4885.5   0.035       0  4891.6   0.035       0
  4898.7   0.035       0  5041.7    0.07       0
Bank Sta=4891.6,4898.7
Exp/Cntr=0.3,0.1

Type RM Length L Ch R = 1,183,151,151,151
BEGIN DESCRIPTION:
Stream0455 0.0
END DESCRIPTION:
XS GIS Cut Line= 4
      1889268.36     13927595.69      1889712.09     13927712.78
      1889944.08     13927696.60      1890759.93     13927509.96
#Sta/Elev= 30
  4478.3 1864.92  4539.8 1851.26  4586.3 1832.39  4625.0 1814.35  4639.5 1809.95
  4664.7 1804.69  4677.1 1803.80  4711.3 1793.81  4751.6 1789.71  4779.5 1783.29
  4810.5 1771.59  4875.7 1767.67  4946.8 1766.10  4961.8 1764.42  4985.3 1758.21
  4985.8 1757.71  4992.4 1758.21  5049.0 1761.63  5088.1 1766.27  5215.5 1767.58
  5344.8 1771.79  5391.0 1774.69  5415.5 1775.77  5517.0 1785.43  5660.1 1791.82
  5694.8 1795.12  5775.6 1802.20  5843.3 1811.24  5926.4 1830.89  6006.7 1852.90
#Mann=6,-1,0
  4478.3     0.1       0  4639.5   0.035       0  4985.3   0.035       0
  4992.4   0.035       0  5391.0    0.07       0  5694.8     0.1       0
Bank Sta=4985.3,4992.4
Exp/Cntr=0.3,0.1

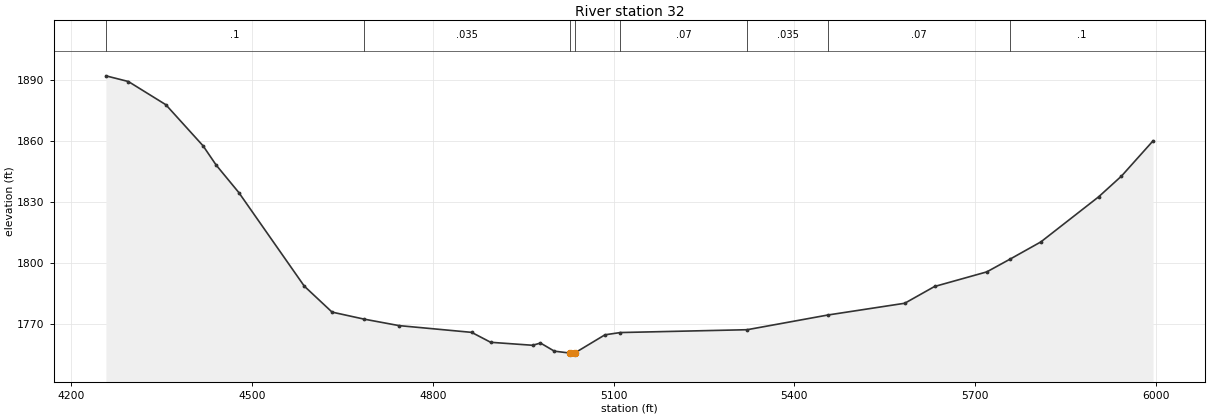
Type RM Length L Ch R = 1,32,0,0,0
BEGIN DESCRIPTION:
Stream0455 0.1
END DESCRIPTION:
XS GIS Cut Line= 4
      1889102.24     13927677.62      1889762.01     13927840.82
      1889925.20     13927847.77      1890793.27     13927629.01
#Sta/Elev= 30
  4257.4 1891.90  4294.7 1889.10  4356.9 1877.70  4418.7 1857.49  4440.4 1848.04
  4478.0 1834.53  4586.7 1788.51  4632.8 1775.74  4685.9 1772.29  4744.0 1769.10
  4864.5 1765.78  4896.1 1760.90  4965.7 1759.43  4978.8 1760.53  5001.8 1756.54
  5028.2 1755.58  5028.7 1755.08  5035.3 1755.58  5085.8 1764.58  5111.3 1765.69
  5321.8 1767.08  5455.8 1774.31  5583.4 1780.09  5632.9 1788.33  5719.6 1795.51
  5758.1 1801.76  5809.3 1810.24  5905.2 1832.40  5943.2 1842.61  5995.6 1859.94
#Mann=8,-1,0
  4257.4     0.1       0  4685.9   0.035       0  5028.2   0.035       0
  5035.3   0.035       0  5111.3    0.07       0  5321.8   0.035       0
  5455.8    0.07       0  5758.1     0.1       0
Bank Sta=5028.2,5035.3
Exp/Cntr=0.3,0.1

Chan Stop Cuts=-1