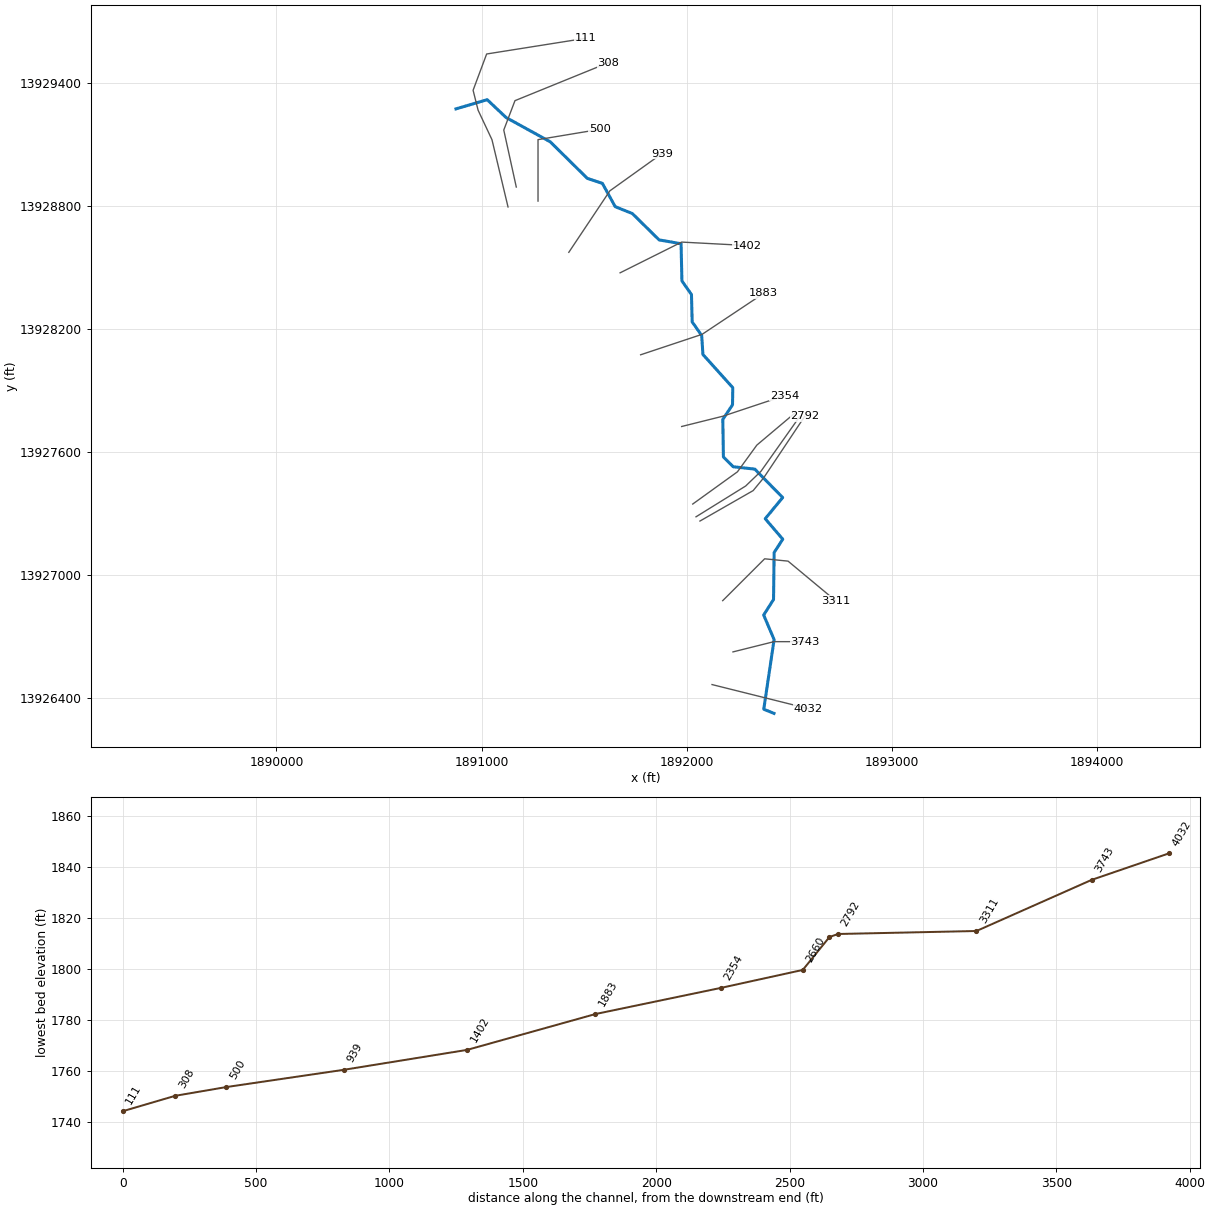
--- Stream0456.prj (project) ---

Proj Title=Stream0456 Base Level Engineering
Current Plan=p01
Default Exp/Contr=0.3,0.1
English Units
Geom File=g01
Flow File=f01
Plan File=p01
Y Axis Title=Elevation
X Axis Title(PF)=Main Channel Distance
X Axis Title(XS)=Station
BEGIN DESCRIPTION:
Stream0456
END DESCRIPTION:
DSS Export Rating Curves= 0
DSS Export Rating Curve Sorted= 0
DSS Export Volume Flow Curves= 0
DXF OffsetX= 0
DXF OffsetY= 0
DXF ScaleX= 1
DXF ScaleY= 10

--- Stream0456.p01 (plan) ---

Plan Title=Multiple Run
Short Identifier=Multiple
Geom File=g01
Flow File=f01
Subcritical Flow
K Sum by GR= 0
Std Step Tol= 0.01
Critical Tol= 0.01
Num of Std Step Trials= 20
Max Error Tol= 0.3
Flow Tol Ratio= 0.001
Split Flow NTrial= 30
Split Flow Tol= 0.02
Split Flow Ratio= 0.02
Log Output Level= 0
Friction Slope Method= 1
Unsteady Friction Slope Method= 2
Unsteady Bridges Friction Slope Method= 1
Parabolic Critical Depth
Global Vel Dist=  1 , 1 , 1
Global Log Level= 0
CheckData=True
Encroach Param= -1, 0, 0, 0
BEGIN DESCRIPTION:
Multiple Run
END DESCRIPTION:

--- Stream0456.f01 (steady flow) ---

Flow Title=Multiple
Number of Profiles=7
Profile Names=10-year,25-year,50-year,1pct_min,100-year,1pct_plu,500-year
River Rch & RM= Stream0456,Reach-1,4032
     724    1211    1668    1114    2222    4434    3889
Boundary for River Rch & Prof#=Stream0456,Reach-1,1
Up Type=0
Dn Type=3
Dn Slope=0.005
Boundary for River Rch & Prof#=Stream0456,Reach-1,2
Up Type=0
Dn Type=3
Dn Slope=0.005
Boundary for River Rch & Prof#=Stream0456,Reach-1,3
Up Type=0
Dn Type=3
Dn Slope=0.005
Boundary for River Rch & Prof#=Stream0456,Reach-1,4
Up Type=0
Dn Type=3
Dn Slope=0.005
Boundary for River Rch & Prof#=Stream0456,Reach-1,5
Up Type=0
Dn Type=3
Dn Slope=0.005
Boundary for River Rch & Prof#=Stream0456,Reach-1,6
Up Type=0
Dn Type=3
Dn Slope=0.005
Boundary for River Rch & Prof#=Stream0456,Reach-1,7
Up Type=0
Dn Type=3
Dn Slope=0.005

--- Stream0456.g01 (geometry) ---

Geom Title=Existing Conditions
Program Version=4.10

River Reach=Stream0456      ,Reach-1
Reach XY= 30
        1892425.       13926325.      1892375.08     13926345.12
      1892425.45     13926685.19      1892374.72     13926804.82
      1892422.71     13926880.93      1892425.66     13927109.84
      1892467.66      13927175.1      1892382.12       13927275.
      1892467.39     13927378.33      1892331.17     13927517.14
      1892226.25     13927528.51      1892178.43     13927576.22
      1892175.52     13927759.78      1892222.84     13927830.98
      1892224.07     13927914.52      1892078.61      13928076.5
      1892072.64     13928169.02      1892026.23     13928235.51
      1892022.73     13928369.06      1891976.22     13928435.51
      1891972.07     13928617.03      1891865.26     13928635.54
      1891734.66     13928764.21      1891651.17     13928797.87
      1891588.56     13928911.51      1891515.34     13928935.79
      1891334.68     13929114.22      1891118.96     13929233.18
       1891027.3     13929319.91        1890875.       13929275.

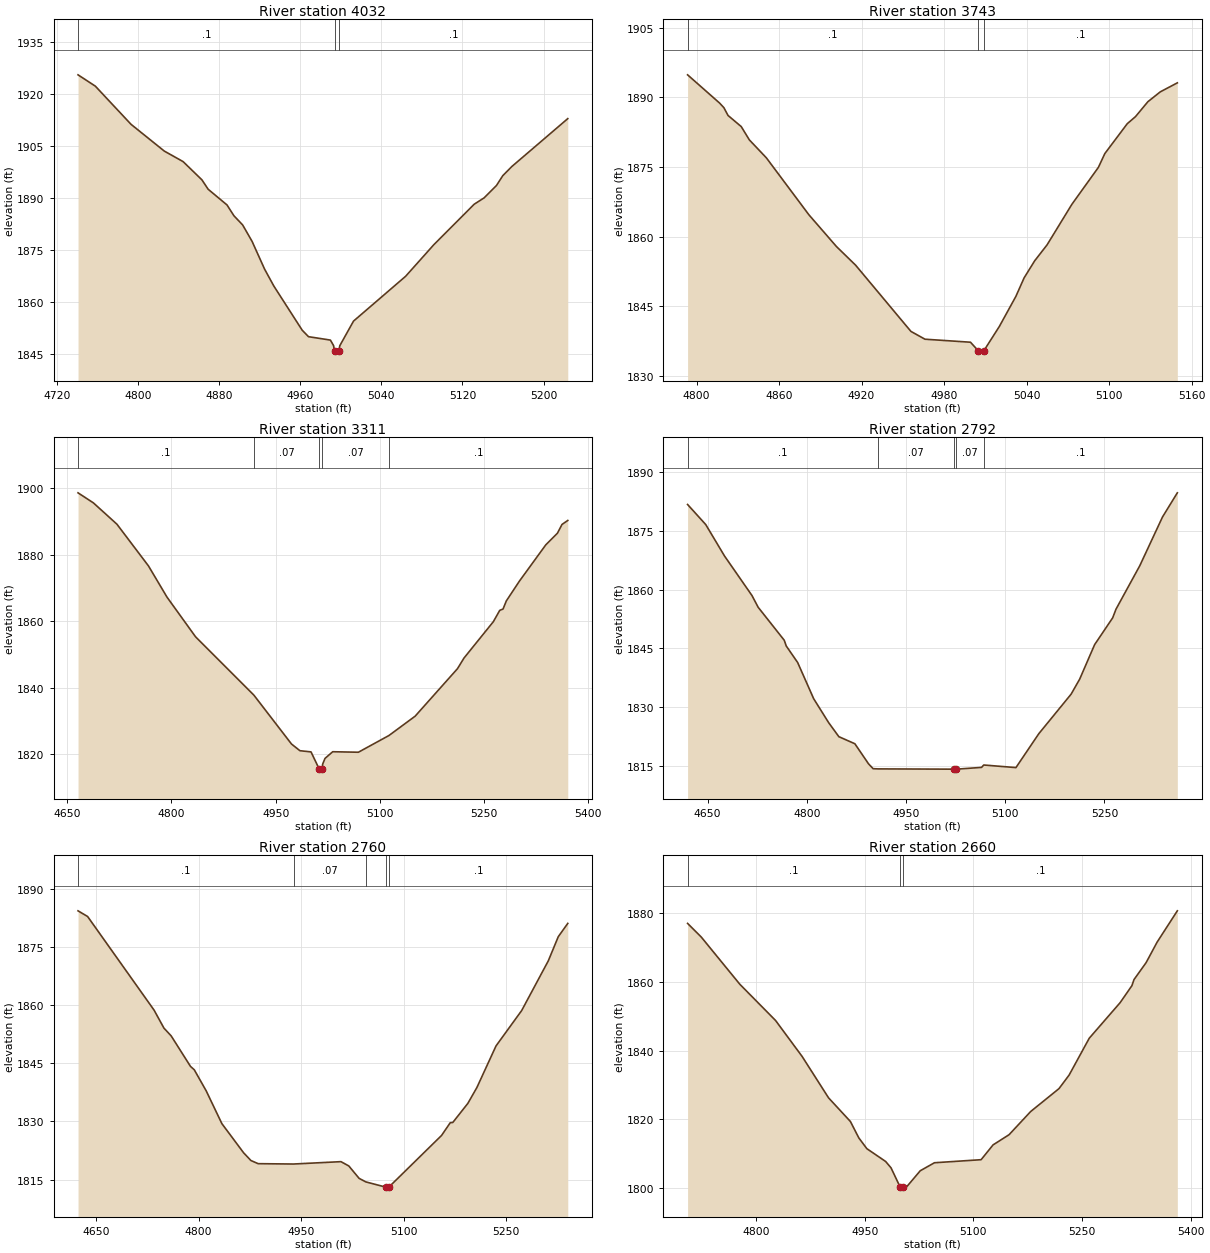
Type RM Length L Ch R = 1 ,4032    ,289,289,289
BEGIN DESCRIPTION:
Stream0456 9.0
END DESCRIPTION:
XS GIS Cut Line= 2
      1892123.03      13926465.6      1892591.78     13926348.29
#Sta/Elev= 30
  4740.7  1925.5  4757.8 1922.23    4793 1911.23  4825.8 1903.52  4844.4 1900.47
  4862.9 1895.23  4869.1 1892.51  4887.7 1887.98  4894.5 1884.87  4903.1 1882.23
  4912.4  1877.5  4924.8 1869.46  4933.9  1864.6  4961.9 1851.86  4968.1    1850
  4989.7 1849.02  4992.8 1847.45  4993.9 1845.76  4994.2 1845.26  4997.9 1845.76
    4999 1847.41  5012.5 1854.49  5063.9 1867.41  5091.8 1876.54  5131.6  1888.2
  5141.3 1890.01  5153.6 1893.61  5159.8 1896.43  5168.7 1899.06  5223.9 1912.87
#Mann= 3 ,-1 , 0
  4740.7      .1       0  4993.9     .05       0  4997.9      .1       0
Bank Sta=4993.9,4997.9
XS Rating Curve= 0 ,0
Exp/Cntr=0.3,0.1

Type RM Length L Ch R = 1 ,3743    ,432,432,432
BEGIN DESCRIPTION:
Stream0456 8.0
END DESCRIPTION:
XS GIS Cut Line= 3
      1892225.04     13926625.01        1892425.       13926675.
      1892574.99       13926675.
#Sta/Elev= 30
  4793.5 1894.87  4816.8 1888.78  4819.9 1887.79  4822.9 1886.12  4832.5 1883.72
  4838.4 1880.86  4850.8 1876.98  4881.7 1864.72  4901.7 1857.89  4915.7 1853.85
  4955.9 1839.59  4966.1 1837.91  4999.2 1837.26  5004.9 1835.41  5005.2 1834.91
  5008.7 1834.91  5008.9 1835.41  5020.2 1840.66  5032.2 1847.13  5038.2 1851.13
  5045.9 1854.81  5054.9 1858.24  5072.9 1866.96  5092.2 1874.93  5096.9 1877.91
  5113.2 1884.34  5119.2 1885.87  5128.2 1889.08  5137.2  1891.2  5149.6 1893.14
#Mann= 3 ,-1 , 0
  4793.5      .1       0  5004.9     .05       0  5008.9      .1       0
Bank Sta=5004.9,5008.9
XS Rating Curve= 0 ,0
Exp/Cntr=0.3,0.1

Type RM Length L Ch R = 1 ,3311    ,519,519,519
BEGIN DESCRIPTION:
Stream0456 7.0
END DESCRIPTION:
XS GIS Cut Line= 4
      1892175.01     13926875.01      1892379.33     13927079.33
      1892493.37     13927068.02      1892724.95     13926875.04
#Sta/Elev= 30
  4665.5 1898.55  4687.6 1895.53  4721.5 1889.12  4766.9 1876.58  4793.6 1867.19
  4834.7 1855.27  4918.7 1837.72  4972.8 1823.04  4984.9 1821.03  5000.9 1820.67
    5013 1815.39  5013.3 1814.89    5017 1815.39  5017.6 1816.96    5021  1818.7
  5032.1 1820.72  5069.1 1820.57  5113.1  1825.6  5150.8 1831.41  5211.7 1845.68
  5221.1 1848.88  5263.3  1859.8  5272.6 1863.23  5277.3 1863.61    5282 1866.04
  5300.8 1871.98  5338.8  1882.9  5355.6 1886.41  5362.2 1889.05  5370.5 1890.24
#Mann= 5 ,-1 , 0
  4665.5      .1       0  4918.7     .07       0    5013     .05       0
    5017     .07       0  5113.1      .1       0
Bank Sta=5013,5017
XS Rating Curve= 0 ,0
Exp/Cntr=0.3,0.1

Type RM Length L Ch R = 1 ,2792    ,32,32,32
BEGIN DESCRIPTION:
Stream0456 6.0
END DESCRIPTION:
XS GIS Cut Line= 4
      1892064.14     13927263.59      1892323.45     13927412.25
        1892375.       13927475.      1892575.02     13927775.03
#Sta/Elev= 30
  4619.6 1881.69  4647.1 1876.56  4675.5 1868.55    4717 1858.48  4726.3  1855.5
  4765.8 1847.08  4768.8 1845.63  4786.1  1841.4  4810.3 1832.18  4832.9 1826.09
  4848.4  1822.5  4872.6  1820.7  4893.2  1815.6  4900.2 1814.34  4907.8 1814.29
  5022.2 1814.22  5022.5 1813.72  5026.2 1814.22  5064.2 1814.67  5067.5 1815.28
  5116.2 1814.62  5150.8 1823.26  5199.7 1833.35  5212.7  1837.2  5235.2 1845.96
  5262.5 1852.79  5267.6 1855.02  5303.5 1866.07  5337.9 1878.51  5360.3 1884.66
#Mann= 5 ,-1 , 0
  4619.6      .1       0  4907.8     .07       0  5022.2     .05       0
  5026.2     .07       0  5067.5      .1       0
Bank Sta=5022.2,5026.2
XS Rating Curve= 0 ,0
Exp/Cntr=0.3,0.1

Type RM Length L Ch R = 1 ,2760    ,100,100,100
BEGIN DESCRIPTION:
Stream0456 5.1
END DESCRIPTION:
XS GIS Cut Line= 4
      1892044.93     13927284.28      1892286.93     13927434.61
      1892361.13     13927506.07       1892550.5       13927774.
#Sta/Elev= 30
  4623.8 1884.25  4637.8 1882.79    4735 1858.65  4749.4 1854.02    4760 1852.01
  4788.2 1844.16  4793.8 1843.27  4811.2 1837.84  4834.1  1829.4  4865.9 1821.88
  4876.5  1819.9  4887.1 1819.08  4938.9 1818.99  5008.2  1819.6  5019.7 1818.49
  5034.7  1815.3  5044.6 1814.38  5074.1 1813.02  5074.4 1812.52  5078.1 1813.02
  5155.3 1826.36    5168 1829.64  5171.7  1829.7  5193.7 1834.62  5206.9  1838.7
  5234.9 1849.43  5272.4 1858.55  5311.3 1871.35  5325.9 1877.58  5339.8 1881.01
#Mann= 5 ,-1 , 0
  4623.8      .1       0  4938.9     .07       0  5044.6      .1       0
  5074.1     .05       0  5078.1      .1       0
Bank Sta=5074.1,5078.1
XS Rating Curve= 0 ,0
Exp/Cntr=0.3,0.1

Type RM Length L Ch R = 1 ,2660    ,306,306,306
BEGIN DESCRIPTION:
Mapping XS 41e85bb2
END DESCRIPTION:
XS GIS Cut Line= 4
        1892029.     13927346.62      1892246.71     13927503.77
      1892341.42     13927634.28      1892529.58     13927792.97
#Sta/Elev= 30
  4705.5 1877.03  4724.4 1873.05  4777.6 1859.31    4827 1848.74  4863.6 1838.28
  4900.1 1826.22  4930.2 1819.35  4941.8 1814.58  4952.9 1811.43  4978.8 1807.71
  4986.3 1805.84  4999.1 1800.15  4999.3 1799.65  5003.1 1800.15  5008.5 1800.48
  5026.6    1805  5046.2 1807.33  5110.6 1808.22  5127.1 1812.53  5149.2  1815.5
    5179 1822.25  5218.1 1828.92  5232.1 1832.88  5259.8 1843.58  5302.5 1853.96
  5318.7 1858.89  5321.6 1860.67  5338.3  1865.6  5353.5 1871.57  5381.4 1880.69
#Mann= 3 ,-1 , 0
  4705.5      .1       0  4999.1     .05       0  5003.1      .1       0
#XS Ineff= 2 , 0
                         5056.59         1807.46
Permanent Ineff=
       F       F
Bank Sta=4999.1,5003.1
XS Rating Curve= 0 ,0
Exp/Cntr=0.3,0.1

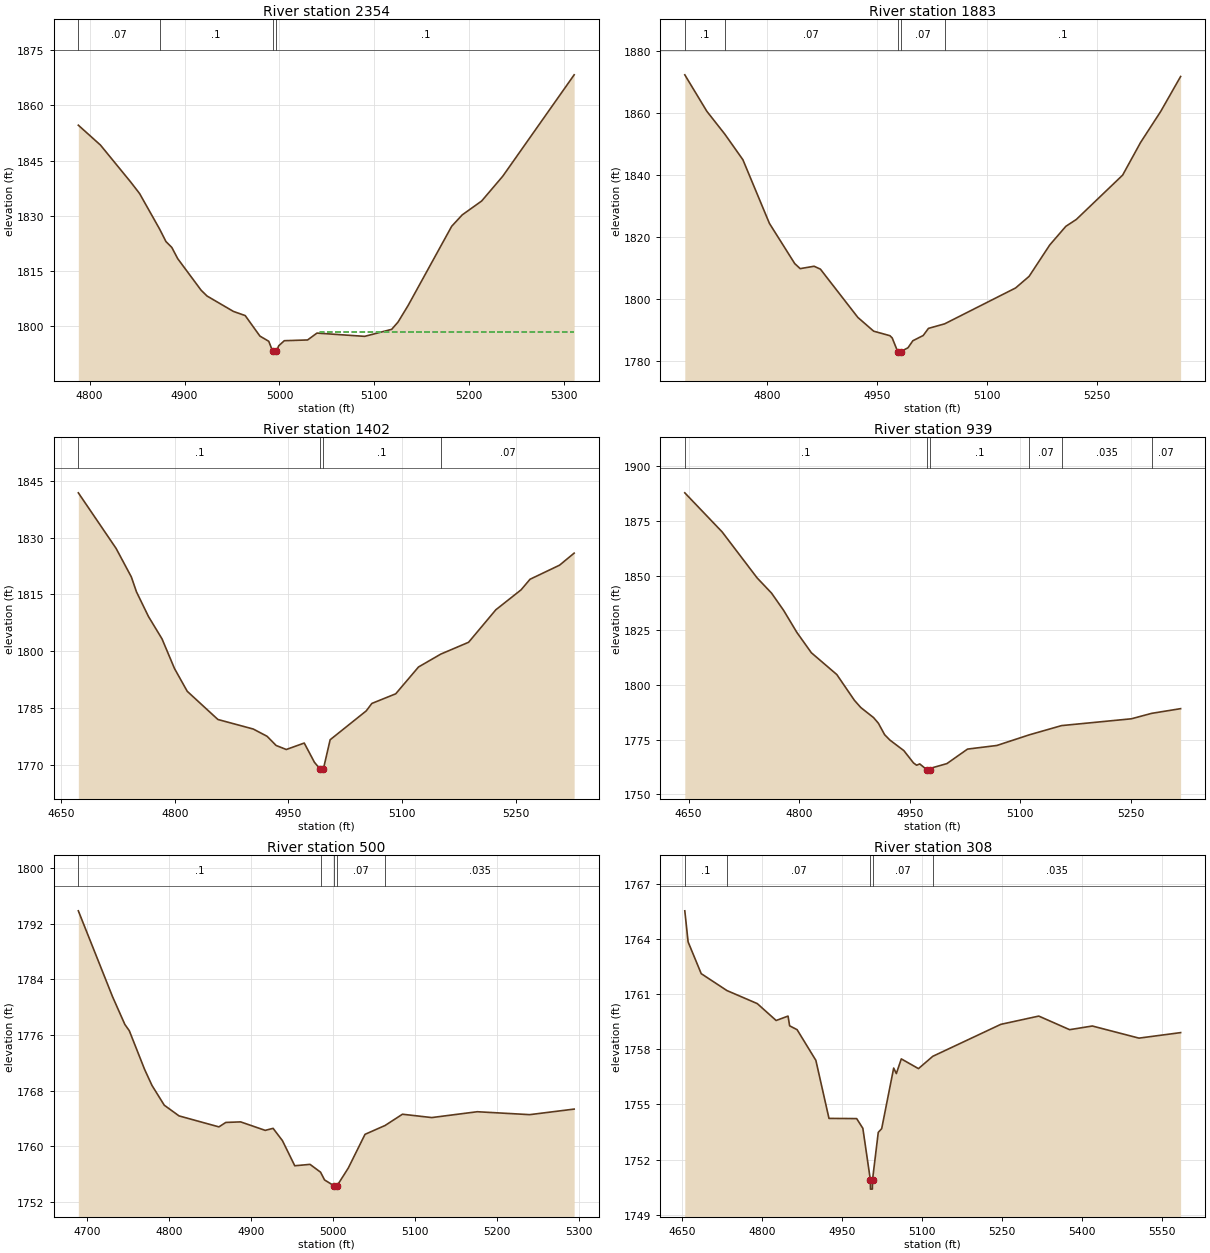
Type RM Length L Ch R = 1 ,2354    ,471,471,471
BEGIN DESCRIPTION:
Stream0456 5.0
END DESCRIPTION:
XS GIS Cut Line= 3
      1891975.05     13927725.01        1892175.       13927775.
      1892474.97     13927874.99
#Sta/Elev= 30
  4788.1 1854.63  4811.4 1849.23  4843.3 1839.16  4852.6 1836.05  4873.7 1826.39
  4880.4 1822.99  4886.6 1821.37  4892.8 1818.33  4917.5 1809.73  4923.7 1808.17
  4951.5 1803.98  4963.9 1802.85  4979.4 1797.27  4988.7 1795.86  4992.8 1793.14
  4993.1 1792.64  4996.8 1793.14  4999.2 1794.64  5005.1 1796.02  5029.6 1796.22
  5039.5 1798.09  5089.7  1797.2  5118.2 1799.11  5124.9  1801.1  5135.5  1805.6
  5181.4 1827.14  5192.4 1830.22    5213 1834.02  5235.2 1840.76  5310.4 1868.33
#Mann= 4 ,-1 , 0
  4788.1     .07       0  4873.7      .1       0  4992.8     .05       0
  4996.8      .1       0
#XS Ineff= 2 , 0
                         5042.45          1798.3
Permanent Ineff=
       F       F
Bank Sta=4992.8,4996.8
XS Rating Curve= 0 ,0
Exp/Cntr=0.3,0.1

Type RM Length L Ch R = 1 ,1883    ,481,481,481
BEGIN DESCRIPTION:
Stream0456 4.0
END DESCRIPTION:
XS GIS Cut Line= 3
      1891775.02     13928075.01        1892075.       13928175.
      1892375.03     13928375.02
#Sta/Elev= 30
    4688 1872.28  4718.1  1860.5  4742.7  1853.1  4767.3 1844.86  4803.5  1824.3
  4838.1  1811.3  4845.5 1809.68  4864.5 1810.45  4873.1 1809.52  4924.2 1793.93
  4945.8 1789.48    4968 1788.02  4971.1  1787.3  4978.6 1782.89  4978.9 1782.39
  4982.6 1782.89  4992.6 1784.11  4999.3 1786.39  5013.4 1788.08  5020.6 1790.38
  5042.7 1791.85  5139.5 1803.43    5158 1807.19  5186.1 1817.31  5208.1 1823.34
  5222.5 1825.58  5285.7  1839.9  5310.1 1850.42  5337.6 1860.45  5364.8 1871.74
#Mann= 5 ,-1 , 0
    4688      .1       0  4742.7     .07       0  4978.6     .05       0
  4982.6     .07       0  5042.7      .1       0
Bank Sta=4978.6,4982.6
XS Rating Curve= 0 ,0
Exp/Cntr=0.3,0.1

Type RM Length L Ch R = 1 ,1402    ,463,463,463
BEGIN DESCRIPTION:
Stream0456 3.0
END DESCRIPTION:
XS GIS Cut Line= 3
      1891675.02     13928475.01        1891975.       13928625.
      1892293.87     13928608.21
#Sta/Elev= 30
  4672.6 1841.82  4722.5 1827.14  4742.6 1819.62  4749.3 1815.72  4765.2 1809.18
  4783.1 1803.27  4799.6 1795.44  4816.4 1789.43  4856.9 1781.99  4903.6 1779.47
  4921.8 1777.56  4933.8 1775.13  4947.2 1774.07  4970.9 1775.77  4984.4 1770.68
  4992.1 1768.86  4992.4 1768.36  4996.1 1768.86  5005.1 1776.64  5052.7 1784.25
  5060.2 1786.23  5091.7 1788.77  5121.8 1795.85  5151.2 1799.25  5187.9 1802.37
  5223.9 1810.95  5257.2 1816.21    5269    1819    5308 1822.72  5327.3  1825.9
#Mann= 4 ,-1 , 0
  4672.6      .1       0  4992.1     .05       0  4996.1      .1       0
  5151.2     .07       0
Bank Sta=4992.1,4996.1
XS Rating Curve= 0 ,0
Exp/Cntr=0.3,0.1

Type RM Length L Ch R = 1 ,939     ,439,439,439
BEGIN DESCRIPTION:
Stream0456 2.0
END DESCRIPTION:
XS GIS Cut Line= 3
      1891425.02     13928575.03        1891625.       13928875.
      1891878.93     13929056.94
#Sta/Elev= 30
  4644.8 1887.86  4695.5 1869.97    4743 1848.92  4762.5    1842    4779 1834.05
    4797 1823.95  4816.6 1814.69  4851.1 1804.73    4875 1792.94  4883.7 1789.63
    4901 1785.03  4907.5 1782.47    4916 1777.22  4923.2 1774.74  4942.1 1769.93
  4955.1 1764.33  4959.4 1763.25  4963.7 1763.84  4973.8 1761.05    4974 1760.55
  4977.8 1761.05    4981 1762.12  5000.5 1763.99  5028.5 1770.63  5068.3 1772.28
  5112.3 1777.15  5156.2 1781.38  5250.9 1784.49  5278.4 1786.98  5317.7 1789.13
#Mann= 6 ,-1 , 0
  4644.8      .1       0  4973.8     .05       0  4977.8      .1       0
  5112.3     .07       0  5156.2    .035       0  5278.4     .07       0
Bank Sta=4973.8,4977.8
XS Rating Curve= 0 ,0
Exp/Cntr=0.3,0.1

Type RM Length L Ch R = 1 ,500     ,192,192,192
BEGIN DESCRIPTION:
Stream0456 1.0
END DESCRIPTION:
XS GIS Cut Line= 3
        1891275.     13928825.01        1891275.       13929125.
      1891574.97       13929175.
#Sta/Elev= 30
  4689.8 1793.84  4731.5 1781.49  4746.5  1777.5  4751.9  1776.6  4770.5 1771.05
  4779.5 1768.74  4794.5 1765.89  4812.5 1764.35  4861.1 1762.77  4869.5 1763.41
  4887.5 1763.49  4917.5 1762.27  4927.1 1762.56  4938.5 1760.79  4953.5 1757.18
  4972.1 1757.38  4984.9 1756.26  4989.8 1755.14  5001.1 1754.32  5001.3 1753.82
  5004.8 1753.82  5005.1 1754.32  5018.7 1756.85  5039.1  1761.7  5063.5 1762.97
  5084.7 1764.59  5120.4 1764.11  5175.9 1764.95  5239.8 1764.53  5293.9 1765.33
#Mann= 5 ,-1 , 0
  4689.8      .1       0  4984.9     .07       0  5001.1     .05       0
  5005.1     .07       0  5063.5    .035       0
Bank Sta=5001.1,5005.1
XS Rating Curve= 0 ,0
Exp/Cntr=0.3,0.1

Type RM Length L Ch R = 1 ,308     ,197,197,197
BEGIN DESCRIPTION:
Stream0456 0.0
END DESCRIPTION:
XS GIS Cut Line= 4
      1891169.07      13928893.6      1891108.07     13929171.83
      1891162.63     13929315.15      1891617.93     13929500.57
#Sta/Elev= 30
    4655 1765.54  4661.2 1763.85  4685.8 1762.12    4734  1761.2  4790.9 1760.49
  4826.3 1759.57  4848.6 1759.81  4851.6 1759.28  4865.6 1759.07  4900.8  1757.4
  4925.4 1754.24  4977.3 1754.23  4988.9  1753.7    5003 1750.89  5003.2 1750.39
  5006.7 1750.39    5007 1750.89  5017.8 1753.48  5024.2 1753.68  5046.7 1756.98
  5051.7 1756.68    5061 1757.48  5093.2 1756.95    5120 1757.62  5247.6 1759.36
  5318.8 1759.81  5376.7 1759.07  5419.2 1759.27  5506.7 1758.61  5584.8 1758.91
#Mann= 5 ,-1 , 0
    4655      .1       0    4734     .07       0    5003     .05       0
    5007     .07       0    5120    .035       0
#XS Ineff= 2 , 0
                         5063.54         1757.12
Permanent Ineff=
       F       F
Bank Sta=5003,5007
XS Rating Curve= 0 ,0
Exp/Cntr=0.3,0.1

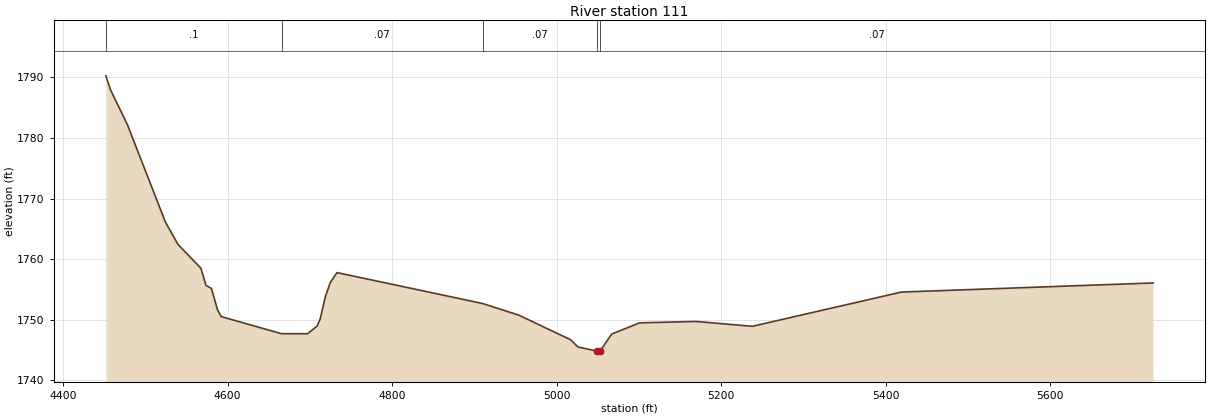
Type RM Length L Ch R = 1 ,111     ,0,0,0
BEGIN DESCRIPTION:
Stream0456 0.1
END DESCRIPTION:
XS GIS Cut Line= 6
      1891128.77     13928796.37      1891050.64     13929124.53
      1890982.93     13929268.63      1890958.62     13929365.85
      1891024.59     13929542.93      1891505.53     13929619.33
#Sta/Elev= 30
  4452.1 1790.26  4457.7 1787.95  4478.1 1782.25  4524.4 1766.15  4539.8 1762.43
  4567.6 1758.52  4573.7  1755.7  4580.4 1755.18  4587.8 1751.65  4592.2 1750.54
  4665.6 1747.72  4697.1 1747.71  4708.7 1748.96  4712.5 1750.12  4718.7 1753.76
  4724.8 1756.16    4733  1757.8  4910.3 1752.69  4954.1 1750.77  5016.7 1746.74
    5026 1745.52  5048.8 1744.85  5049.1 1744.35  5052.8 1744.85  5066.8 1747.66
  5100.8 1749.51  5169.3 1749.74  5237.8 1748.94  5419.1 1754.59  5724.8 1756.09
#Mann= 5 ,-1 , 0
  4452.1      .1       0  4665.6     .07       0  4910.3     .07       0
  5048.8     .05       0  5052.8     .07       0
#XS Ineff= 2 , 0
         4735.66 1756.29
Permanent Ineff=
       F       F
Bank Sta=5048.8,5052.8
XS Rating Curve= 0 ,0
Exp/Cntr=0.3,0.1

Chan Stop Cuts=-1
Use User Specified Reach Order=0
Composite Channel Slope=5