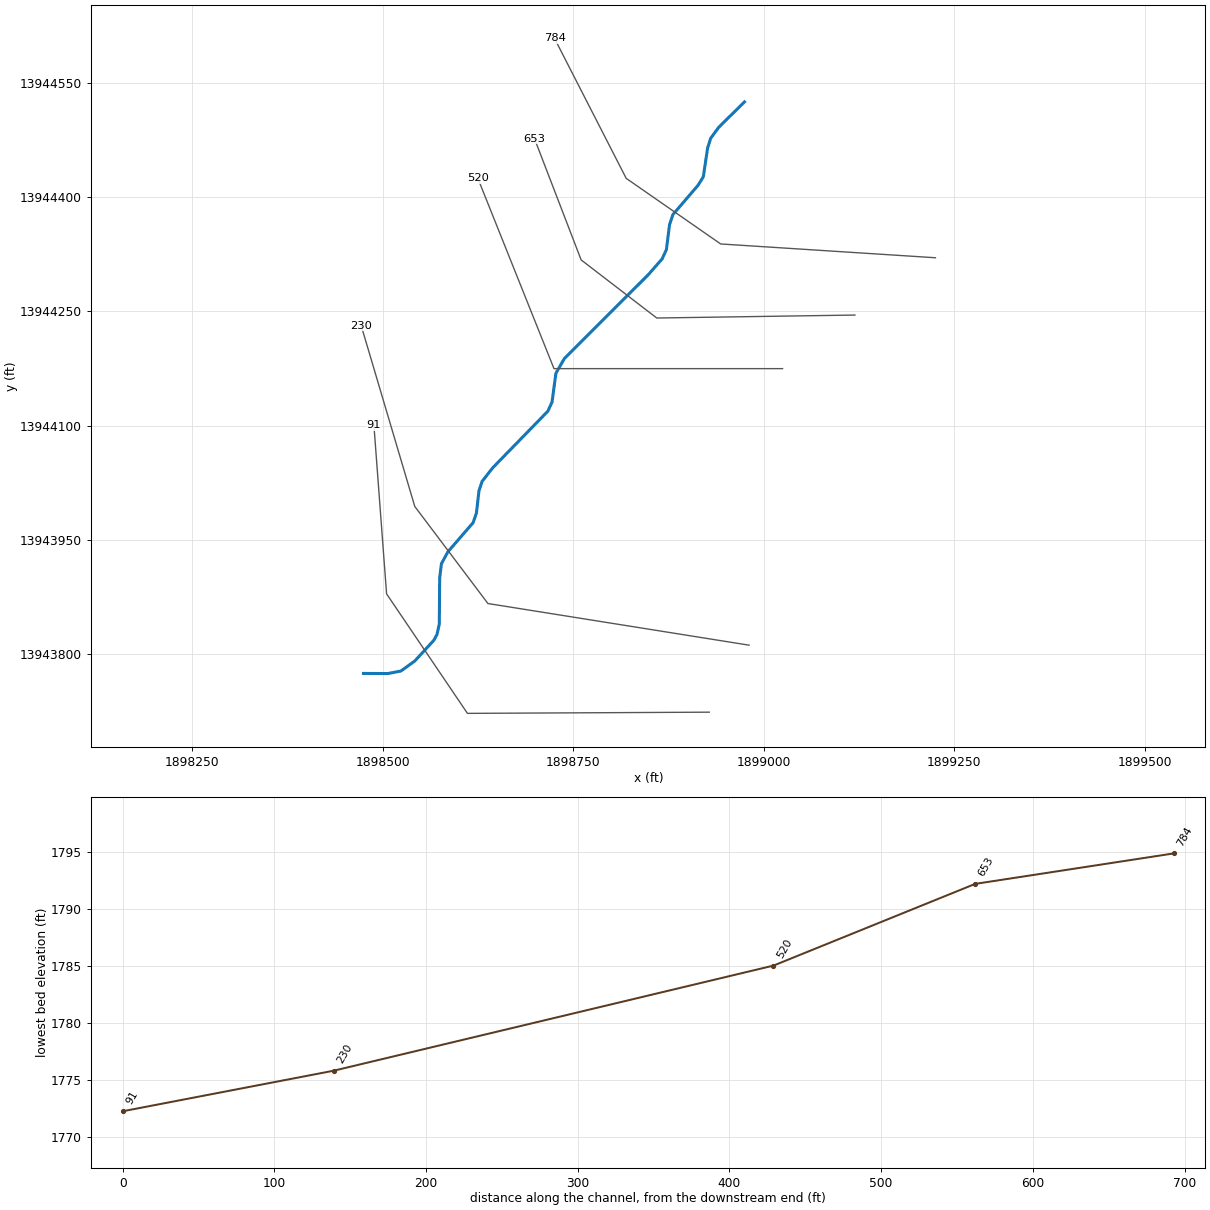
--- Stream0459.prj (project) ---

Proj Title=Stream0459 Base Level Engineering
Current Plan=p01
Default Exp/Contr=0.3,0.1
English Units
Geom File=g01
Flow File=f01
Plan File=p01
Y Axis Title=Elevation
X Axis Title(PF)=Main Channel Distance
X Axis Title(XS)=Station
BEGIN DESCRIPTION:
Stream0459
END DESCRIPTION:
DSS Export Rating Curves= 0
DSS Export Rating Curve Sorted= 0
DSS Export Volume Flow Curves= 0
DXF OffsetX= 0
DXF OffsetY= 0
DXF ScaleX= 1
DXF ScaleY= 10

--- Stream0459.p01 (plan) ---

Plan Title=Multiple Run
Short Identifier=Multiple
Geom File=g01
Flow File=f01
Subcritical Flow
K Sum by GR= 0
Std Step Tol= 0.01
Critical Tol= 0.01
Num of Std Step Trials= 20
Max Error Tol= 0.3
Flow Tol Ratio= 0.001
Split Flow NTrial= 30
Split Flow Tol= 0.02
Split Flow Ratio= 0.02
Log Output Level= 0
Friction Slope Method= 1
Unsteady Friction Slope Method= 2
Unsteady Bridges Friction Slope Method= 1
Parabolic Critical Depth
Global Vel Dist=  1 , 1 , 1
Global Log Level= 0
CheckData=True
Encroach Param= -1, 0, 0, 0
BEGIN DESCRIPTION:
Multiple Run
END DESCRIPTION:

--- Stream0459.f01 (steady flow) ---

Flow Title=Multiple
Program Version=4.10
Number of Profiles= 7
Profile Names=10-year,25-year,50-year,1pct_min,100-year,1pct_plu,500-year
River Rch & RM=Stream0459,Reach-1         ,784
     401     645     866     565    1128    2250    1881
Boundary for River Rch & Prof#=Stream0459,Reach-1         , 1
Up Type= 0
Dn Type= 3
Dn Slope=0.01
Boundary for River Rch & Prof#=Stream0459,Reach-1         , 2
Up Type= 0
Dn Type= 3
Dn Slope=0.01
Boundary for River Rch & Prof#=Stream0459,Reach-1         , 3
Up Type= 0
Dn Type= 3
Dn Slope=0.01
Boundary for River Rch & Prof#=Stream0459,Reach-1         , 4
Up Type= 0
Dn Type= 3
Dn Slope=0.01
Boundary for River Rch & Prof#=Stream0459,Reach-1         , 5
Up Type= 0
Dn Type= 3
Dn Slope=0.01
Boundary for River Rch & Prof#=Stream0459,Reach-1         , 6
Up Type= 0
Dn Type= 3
Dn Slope=0.01
Boundary for River Rch & Prof#=Stream0459,Reach-1         , 7
Up Type= 0
Dn Type= 3
Dn Slope=0.01
DSS Import GetInterval= 0
DSS Import GetPeak= 0
DSS Import FillOption= 0

--- Stream0459.g01 (geometry) ---

Geom Title=Existing Conditions
Program Version=4.10

River Reach=Stream0459      ,Reach-1
Reach XY= 30
        1898975.       13944525.      1898941.41     13944491.93
      1898930.67     13944477.36       1898926.6     13944464.34
      1898920.96     13944426.67      1898913.96     13944415.43
       1898881.1     13944377.19       1898876.7      13944364.3
       1898872.5     13944331.03      1898866.86     13944318.94
      1898848.71     13944298.18      1898738.63     13944188.21
      1898727.53     13944168.95      1898722.46     13944131.05
      1898716.82     13944118.96      1898644.82     13944045.07
      1898630.84     13944027.29      1898626.51     13944014.38
      1898623.28     13943985.71      1898618.86     13943972.83
      1898585.84     13943934.65      1898577.33     13943919.03
      1898574.99       13943900.      1898574.54     13943840.11
      1898571.54      13943826.3      1898567.36     13943818.55
      1898542.34     13943791.31      1898524.01     13943778.12
      1898507.07     13943774.85        1898475.       13943775.

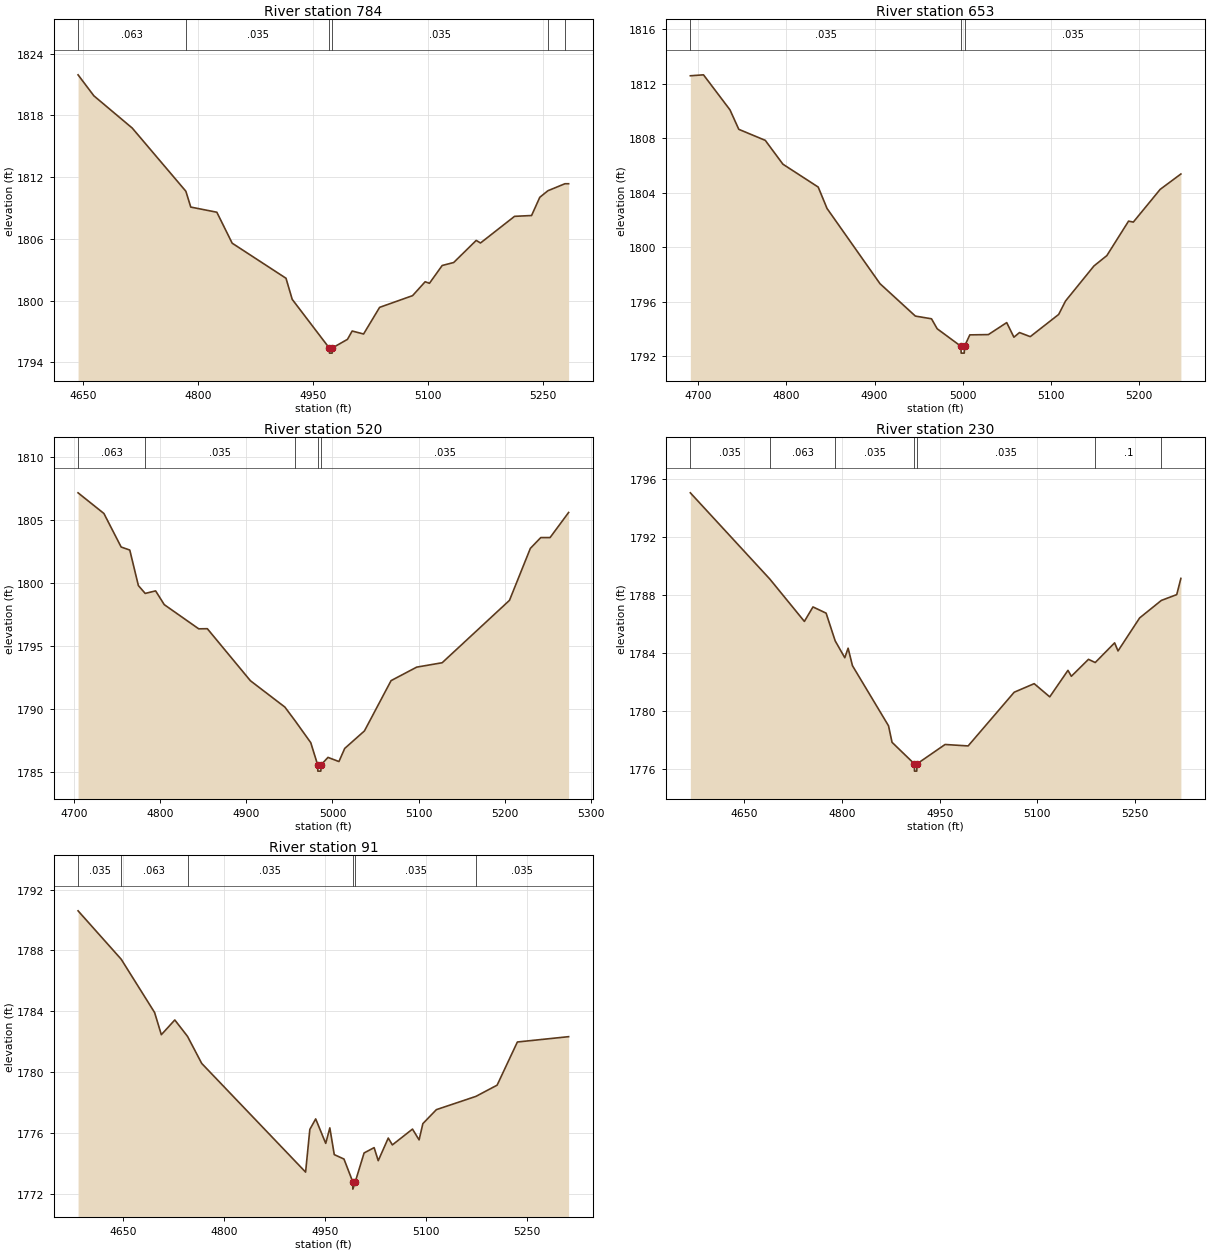
Type RM Length L Ch R = 1 ,784     ,131,131,131
BEGIN DESCRIPTION:
Stream0459 2.0
END DESCRIPTION:
XS GIS Cut Line= 4
       1899225.6      13944320.5      1898943.77      13944338.6
      1898819.79     13944424.69      1898725.68     13944608.44
#Sta/Elev= 30
  4643.9 1821.95  4664.5 1819.91  4714.6 1816.77  4784.5 1810.63  4790.9 1809.09
  4824.9 1808.59  4844.9 1805.58  4915.1 1802.17  4923.2 1800.12  4971.5 1795.39
  4971.8 1794.89  4975.3 1794.89  4975.5 1795.39  4995.3 1796.23  5001.4 1797.04
  5016.3 1796.75  5037.2 1799.34  5080.2 1800.48  5096.6 1801.83  5102.2 1801.68
  5118.8 1803.41  5133.8  1803.7  5163.2 1805.85  5168.8  1805.6  5213.2 1808.19
  5235.4 1808.27  5246.1 1810.04  5256.7 1810.68  5278.9 1811.36  5283.7 1811.36
#Mann= 6 ,-1 , 0
  4643.9    .063       0  4784.5    .035       0  4971.5    .035       0
  4975.5    .035       0  5256.7    .063       0  5278.9     .07       0
Bank Sta=4971.5,4975.5
XS Rating Curve= 0 ,0
Exp/Cntr=0.3,0.1

Type RM Length L Ch R = 1 ,653     ,133,133,133
BEGIN DESCRIPTION:
Mapping XS 30412b60
END DESCRIPTION:
XS GIS Cut Line= 4
      1899119.93     13944245.31      1898859.87     13944241.42
      1898760.65     13944317.66      1898699.36     13944476.96
#Sta/Elev= 30
  4691.3 1812.58  4706.2 1812.65  4736.2 1810.08  4746.2 1808.65  4776.2 1807.84
  4796.2 1806.09  4836.2 1804.41  4846.2 1802.84  4906.2 1797.32  4946.3 1794.94
  4964.6 1794.74    4971 1794.01    4998 1792.72  4998.2 1792.22  5001.7 1792.22
    5002 1792.72    5008 1793.56    5029 1793.58  5049.8 1794.46    5058 1793.39
  5064.3 1793.73  5076.5 1793.43  5108.7 1795.06  5116.5 1796.05  5148.7 1798.62
  5163.3 1799.38  5187.9 1801.91  5193.3 1801.84  5223.7 1804.24  5247.2 1805.37
#Mann= 3 ,-1 , 0
  4691.3    .035       0    4998    .035       0    5002    .035       0
Bank Sta=4998,5002
XS Rating Curve= 0 ,0
Exp/Cntr=0.3,0.1

Type RM Length L Ch R = 1 ,520     ,290,290,290
BEGIN DESCRIPTION:
Stream0459 1.0
END DESCRIPTION:
XS GIS Cut Line= 3
      1899024.96       13944175.        1898725.       13944175.
      1898625.01     13944424.98
#Sta/Elev= 30
  4704.8 1807.14  4734.8  1805.5  4754.8 1802.84  4764.8  1802.6  4774.8 1799.78
  4782.7 1799.16  4794.8 1799.36  4804.8 1798.27  4844.8 1796.35  4854.8 1796.36
  4904.8 1792.23  4944.8 1790.14  4956.8 1789.04  4974.8 1787.32  4982.8 1785.56
    4983 1785.06  4986.5 1785.06  4986.8 1785.56  4994.8 1786.15  5007.5 1785.82
  5014.2 1786.86  5037.1 1788.25    5068 1792.24  5097.7 1793.31  5127.3 1793.66
  5205.4 1798.61  5229.6 1802.73  5241.7 1803.59  5252.5 1803.59    5274 1805.58
#Mann= 5 ,-1 , 0
  4704.8    .063       0  4782.7    .035       0  4956.8    .035       0
  4982.8    .035       0  4986.8    .035       0
Bank Sta=4982.8,4986.8
XS Rating Curve= 0 ,0
Exp/Cntr=0.3,0.1

Type RM Length L Ch R = 1 ,230     ,139,139,139
BEGIN DESCRIPTION:
Stream0459 0.0
END DESCRIPTION:
XS GIS Cut Line= 4
      1898981.03      13943812.1      1898638.33     13943866.74
      1898542.33     13943994.15      1898472.11     13944231.11
#Sta/Elev= 30
  4566.9 1795.07  4689.1 1789.11  4742.1 1786.19  4755.3 1787.19  4775.5 1786.76
  4789.4 1784.85  4804.2 1783.68  4809.3 1784.34    4816 1783.13  4871.4 1778.98
  4876.8 1777.84  4911.1 1776.35  4911.3 1775.85  4914.8 1775.85  4915.1 1776.35
  4958.3 1777.69  4993.7 1777.59  5064.5  1781.3  5095.2 1781.89  5119.1 1780.98
  5147.1 1782.81  5152.3  1782.4  5178.6 1783.57    5189 1783.35  5218.8 1784.71
    5224 1784.15  5257.2 1786.43  5290.6 1787.64  5314.2 1788.04  5320.6 1789.16
#Mann= 7 ,-1 , 0
  4566.9    .035       0  4689.1    .063       0  4789.4    .035       0
  4911.1    .035       0  4915.1    .035       0    5189      .1       0
  5290.6    .035       0
Bank Sta=4911.1,4915.1
XS Rating Curve= 0 ,0
Exp/Cntr=0.3,0.1

Type RM Length L Ch R = 1 ,91      ,0,0,0
BEGIN DESCRIPTION:
Stream0459 0.1
END DESCRIPTION:
XS GIS Cut Line= 4
      1898928.73     13943724.17      1898611.46     13943722.59
      1898505.34     13943879.42      1898488.69     13944100.86
#Sta/Elev= 30
  4583.6 1790.61  4647.6 1787.43  4697.3 1783.92  4707.3 1782.46  4727.3 1783.43
  4746.2 1782.35  4767.3 1780.57  4921.6 1773.42  4927.9 1776.23  4936.6 1776.92
  4951.5 1775.31  4957.6 1776.33  4964.2 1774.57  4978.6 1774.28  4991.5  1772.8
  4991.8  1772.3  4995.5  1772.8  5008.5 1774.68  5023.4 1775.03  5029.5 1774.17
  5044.4 1775.66  5050.5 1775.21  5080.4 1776.25  5090.2 1775.54  5095.8 1776.61
  5115.9 1777.53  5174.5  1778.4  5206.1 1779.14  5236.2 1781.98  5312.3 1782.33
#Mann= 6 ,-1 , 0
  4583.6    .035       0  4647.6    .063       0  4746.2    .035       0
  4991.5    .035       0  4995.5    .035       0  5174.5    .035       0
Bank Sta=4991.5,4995.5
XS Rating Curve= 0 ,0
Exp/Cntr=0.3,0.1

Chan Stop Cuts=-1
Use User Specified Reach Order=0
Composite Channel Slope=5