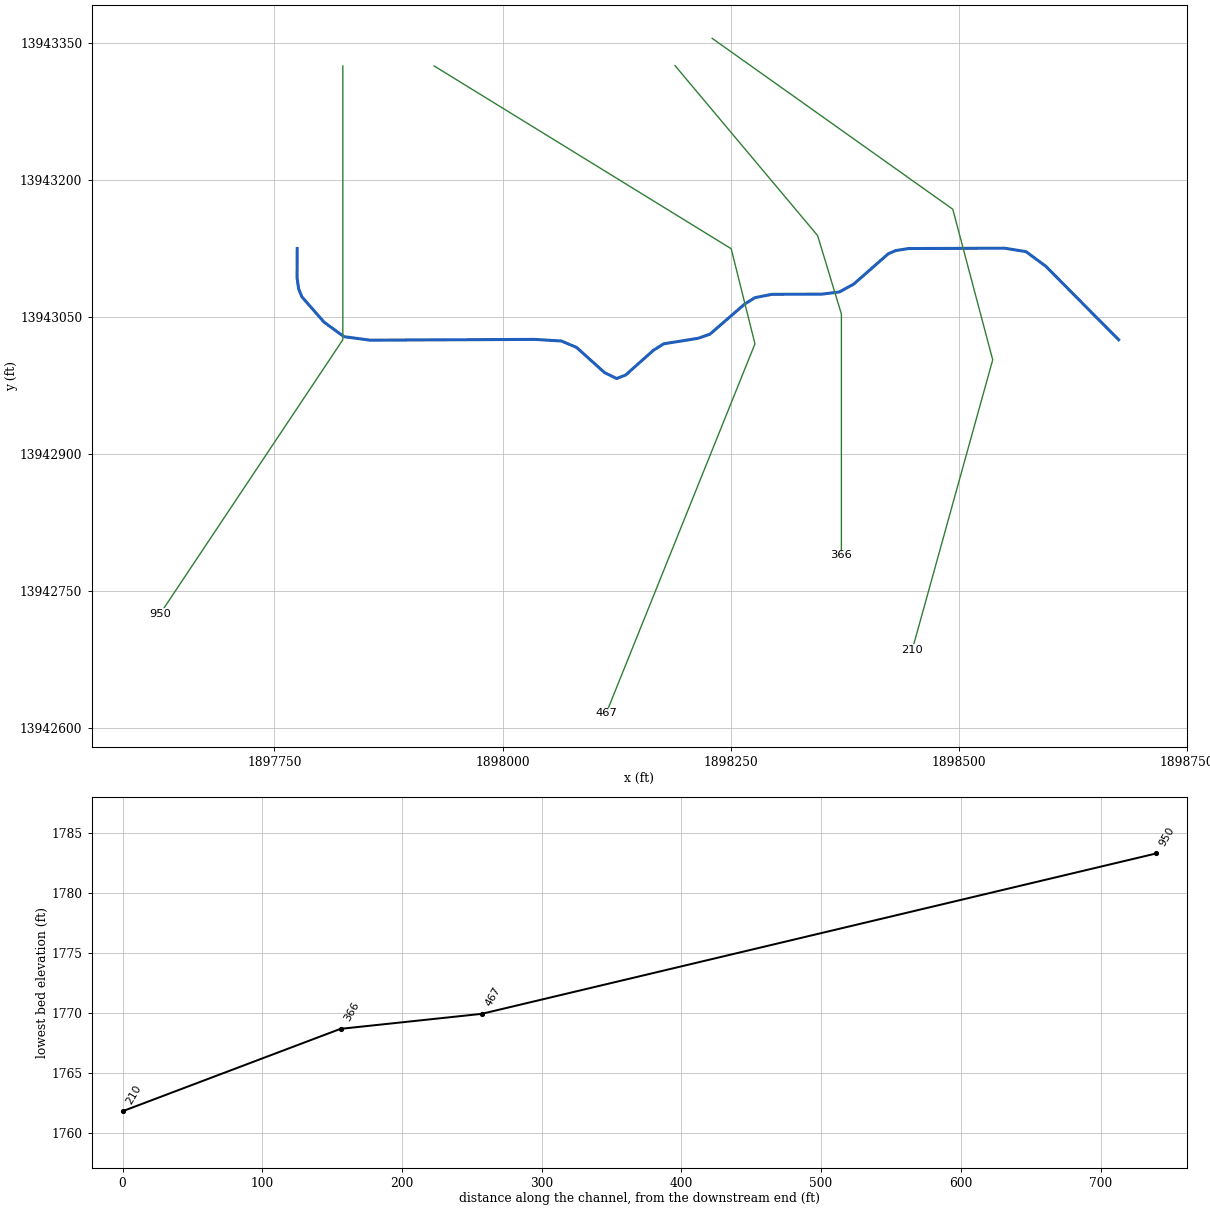
--- Stream0460.prj (project) ---

Proj Title=Stream0460 Base Level Engineering
Current Plan=p01
Default Exp/Contr=0.3,0.1
English Units
Geom File=g01
Flow File=f01
Plan File=p01
Y Axis Title=Elevation
X Axis Title(PF)=Main Channel Distance
X Axis Title(XS)=Station
BEGIN DESCRIPTION:
Stream0460
END DESCRIPTION:
DSS Export Rating Curves= 0
DSS Export Rating Curve Sorted= 0
DSS Export Volume Flow Curves= 0
DXF OffsetX= 0
DXF OffsetY= 0
DXF ScaleX= 1
DXF ScaleY= 10

--- Stream0460.p01 (plan) ---

Plan Title=Multiple Run
Short Identifier=Multiple
Geom File=g01
Flow File=f01
Subcritical Flow
K Sum by GR= 0
Std Step Tol= 0.01
Critical Tol= 0.01
Num of Std Step Trials= 20
Max Error Tol= 0.3
Flow Tol Ratio= 0.001
Split Flow NTrial= 30
Split Flow Tol= 0.02
Split Flow Ratio= 0.02
Log Output Level= 0
Friction Slope Method= 1
Unsteady Friction Slope Method= 2
Unsteady Bridges Friction Slope Method= 1
Parabolic Critical Depth
Global Vel Dist=  1 , 1 , 1
Global Log Level= 0
CheckData=True
Encroach Param= -1, 0, 0, 0
BEGIN DESCRIPTION:
Multiple Run
END DESCRIPTION:

--- Stream0460.f01 (steady flow) ---

Flow Title=Multiple
Program Version=4.10
Number of Profiles= 7
Profile Names=10-year,25-year,50-year,1pct_min,100-year,1pct_plu,500-year
River Rch & RM=Stream0460,Reach-1         ,950
     495     808    1096     723    1442    2878    2455
Boundary for River Rch & Prof#=Stream0460,Reach-1         , 1
Up Type= 0
Dn Type= 3
Dn Slope=0.01
Boundary for River Rch & Prof#=Stream0460,Reach-1         , 2
Up Type= 0
Dn Type= 3
Dn Slope=0.01
Boundary for River Rch & Prof#=Stream0460,Reach-1         , 3
Up Type= 0
Dn Type= 3
Dn Slope=0.01
Boundary for River Rch & Prof#=Stream0460,Reach-1         , 4
Up Type= 0
Dn Type= 3
Dn Slope=0.01
Boundary for River Rch & Prof#=Stream0460,Reach-1         , 5
Up Type= 0
Dn Type= 3
Dn Slope=0.01
Boundary for River Rch & Prof#=Stream0460,Reach-1         , 6
Up Type= 0
Dn Type= 3
Dn Slope=0.01
Boundary for River Rch & Prof#=Stream0460,Reach-1         , 7
Up Type= 0
Dn Type= 3
Dn Slope=0.01
DSS Import GetInterval= 0
DSS Import GetPeak= 0
DSS Import FillOption= 0

--- Stream0460.g01 (geometry) ---

Geom Title=Existing Conditions

River Reach=Stream0460,Reach-1
Reach XY= 30
      1897775.00     13943125.00      1897774.84     13943092.92
      1897776.55     13943080.83      1897780.13     13943072.05
      1897804.44     13943044.28      1897826.26     13943028.37
      1897854.77     13943024.55      1898035.21     13943025.40
      1898064.56     13943023.62      1898081.19     13943016.54
      1898111.80     13942988.94      1898125.01     13942982.53
      1898134.93     13942986.42      1898165.33     13943013.50
      1898176.64     13943020.58      1898214.29     13943026.62
      1898227.17     13943031.09      1898265.35     13943064.16
      1898276.58     13943071.17      1898295.09     13943074.77
      1898350.00     13943075.00      1898369.02     13943077.36
      1898384.63     13943085.90      1898422.67     13943119.26
      1898430.94     13943122.75      1898445.04     13943124.95
      1898550.11     13943125.33      1898573.55     13943121.52
      1898595.21     13943105.51      1898675.00     13943025.00

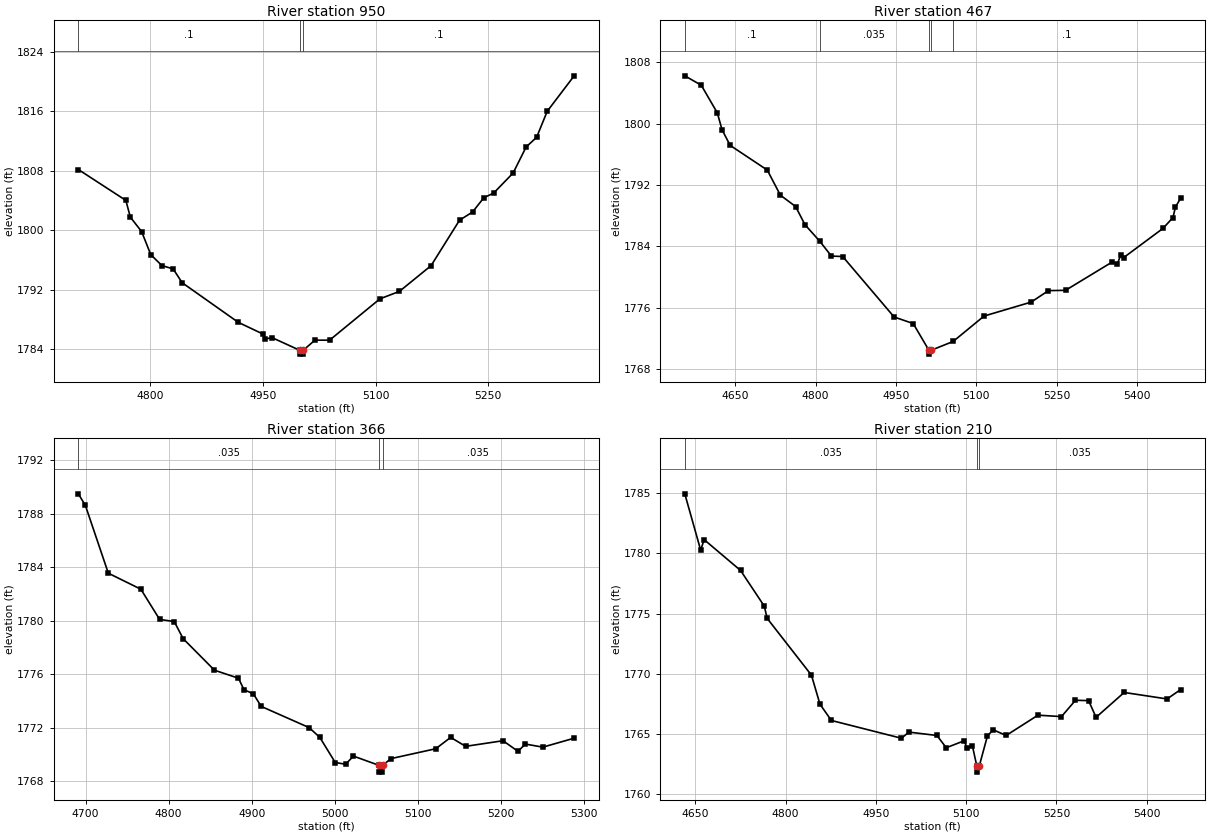
Type RM Length L Ch R = 1,950,483,483,483
BEGIN DESCRIPTION:
Stream0460 2.0
END DESCRIPTION:
XS GIS Cut Line= 3
      1897825.00     13943324.98      1897825.00     13943025.00
      1897625.02     13942725.03
#Sta/Elev= 30
  4704.0 1808.17  4767.3 1804.01  4773.3 1801.75  4788.3 1799.81  4800.5 1796.70
  4815.3 1795.23  4830.3 1794.78  4842.3 1792.92  4917.1 1787.58  4950.3 1785.99
  4953.3 1785.35  4962.1 1785.52  4999.3 1783.80  4999.6 1783.30  5003.1 1783.30
  5003.3 1783.80  5019.2 1785.18  5038.7 1785.18  5105.8 1790.75  5131.7 1791.75
  5173.9 1795.22  5211.8 1801.34  5229.1 1802.44  5244.2 1804.37  5257.2 1804.99
  5283.2 1807.70  5300.5 1811.20  5314.5 1812.51  5328.6 1816.01  5364.5 1820.79
#Mann=3,-1,0
  4704.0     0.1       0  4999.3    0.05       0  5003.3     0.1       0
Bank Sta=4999.3,5003.3
Exp/Cntr=0.3,0.1

Type RM Length L Ch R = 1,467,101,101,101
BEGIN DESCRIPTION:
Stream0460 1.0
END DESCRIPTION:
XS GIS Cut Line= 4
      1897925.02     13943324.99      1898250.51     13943124.72
      1898276.52     13943020.50      1898113.52     13942615.66
#Sta/Elev= 30
  4555.6 1806.25  4586.3 1805.03  4616.3 1801.42  4625.1 1799.22  4640.3 1797.17
  4709.6 1793.95  4734.1 1790.67  4762.5 1789.19  4780.1 1786.81  4807.4 1784.68
  4829.4 1782.72  4850.5 1782.66  4946.5 1774.77  4982.2 1773.91  5011.5 1770.42
  5011.7 1769.92  5015.5 1770.42  5056.7 1771.57  5114.5 1774.89  5202.4 1776.71
  5234.8 1778.21  5266.7 1778.25  5353.9 1781.95  5363.5 1781.70  5370.0 1782.92
  5375.0 1782.51  5448.8 1786.34  5467.3 1787.75  5471.9 1789.11  5481.6 1790.27
#Mann=5,-1,0
  4555.6     0.1       0  4807.4   0.035       0  5011.5   0.035       0
  5015.5   0.035       0  5056.7     0.1       0
Bank Sta=5011.5,5015.5
Exp/Cntr=0.3,0.1

Type RM Length L Ch R = 1,366,156,156,156
BEGIN DESCRIPTION:
Stream0460 0.1
END DESCRIPTION:
XS GIS Cut Line= 4
      1898188.97     13943325.32      1898345.18     13943139.16
      1898371.23     13943053.22      1898371.23     13942788.94
#Sta/Elev= 30
  4691.3 1789.50  4699.8 1788.63  4727.4 1783.56  4766.6 1782.36  4789.2 1780.10
  4806.8 1779.94  4817.5 1778.66  4855.2 1776.30  4884.1 1775.70  4890.8 1774.84
  4902.1 1774.53  4911.5 1773.59  4969.3 1772.00  4982.1 1771.27  5000.7 1769.39
  5013.2 1769.26  5022.6 1769.87  5053.7 1769.17  5053.9 1768.67  5057.4 1768.67
  5057.7 1769.17  5067.7 1769.68  5121.7 1770.42  5139.7 1771.27  5157.7 1770.60
  5202.7 1771.02  5220.7 1770.23  5229.7 1770.77  5250.7 1770.54  5288.4 1771.21
#Mann=3,-1,0
  4691.3   0.035       0  5053.7   0.035       0  5057.7   0.035       0
Bank Sta=5053.7,5057.7
Exp/Cntr=0.3,0.1

Type RM Length L Ch R = 1,210,0,0,0
BEGIN DESCRIPTION:
Stream0460 0.0
END DESCRIPTION:
XS GIS Cut Line= 4
      1898229.64     13943355.25      1898493.27     13943168.00
      1898537.01     13943003.05      1898448.84     13942685.26
#Sta/Elev= 30
  4632.6 1784.96  4659.0 1780.27  4664.7 1781.15  4725.3 1778.58  4764.7 1775.61
  4769.4 1774.60  4843.0 1769.87  4857.2 1767.45  4876.1 1766.10  4992.5 1764.62
  5005.0 1765.13  5051.5 1764.85  5067.0 1763.83  5097.3 1764.42  5100.9 1763.81
  5110.5 1763.97  5117.8 1762.30  5118.0 1761.80  5121.8 1762.30  5135.3 1764.79
  5144.7 1765.33  5166.5 1764.85  5219.4 1766.54  5258.4 1766.42  5281.7 1767.78
  5303.5 1767.75  5315.9 1766.36  5362.6 1768.43  5433.9 1767.89  5456.4 1768.67
#Mann=3,-1,0
  4632.6   0.035       0  5117.8   0.035       0  5121.8   0.035       0
Bank Sta=5117.8,5121.8
Exp/Cntr=0.3,0.1

Chan Stop Cuts=-1