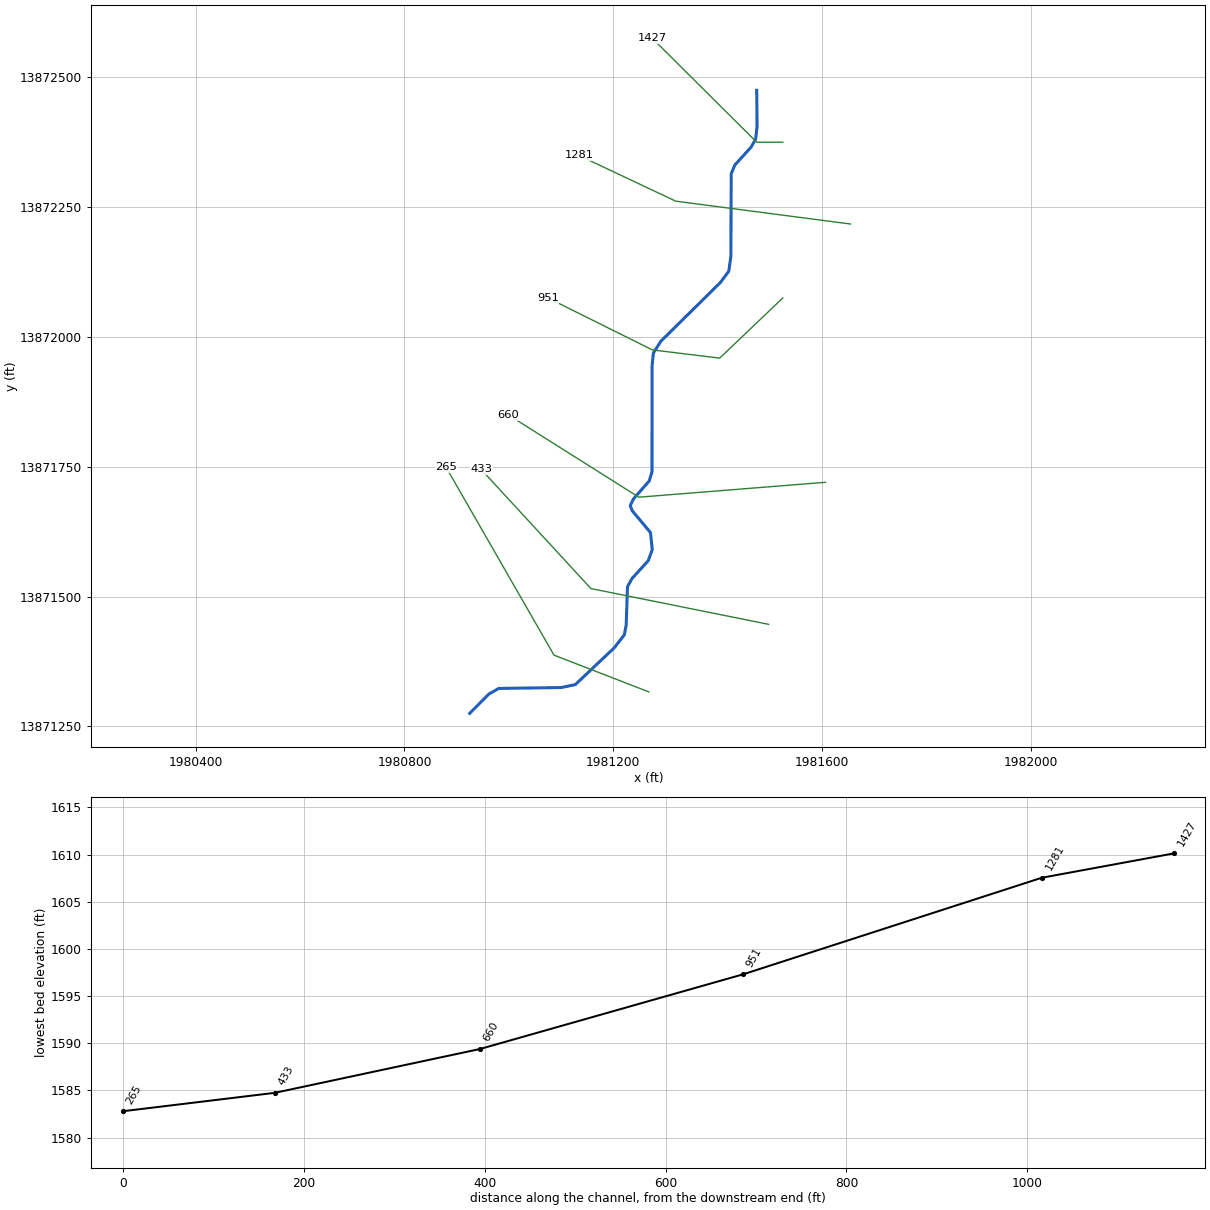
--- Stream0461.prj (project) ---

Proj Title=Stream0461 Base Level Engineering
Current Plan=p01
Default Exp/Contr=0.3,0.1
English Units
Geom File=g01
Flow File=f01
Plan File=p01
Y Axis Title=Elevation
X Axis Title(PF)=Main Channel Distance
X Axis Title(XS)=Station
BEGIN DESCRIPTION:
Stream0461
END DESCRIPTION:
DSS Export Rating Curves= 0
DSS Export Rating Curve Sorted= 0
DSS Export Volume Flow Curves= 0
DXF OffsetX= 0
DXF OffsetY= 0
DXF ScaleX= 1
DXF ScaleY= 10

--- Stream0461.p01 (plan) ---

Plan Title=Multiple Run
Short Identifier=Multiple
Geom File=g01
Flow File=f01
Subcritical Flow
K Sum by GR= 0
Std Step Tol= 0.01
Critical Tol= 0.01
Num of Std Step Trials= 20
Max Error Tol= 0.3
Flow Tol Ratio= 0.001
Split Flow NTrial= 30
Split Flow Tol= 0.02
Split Flow Ratio= 0.02
Log Output Level= 0
Friction Slope Method= 1
Unsteady Friction Slope Method= 2
Unsteady Bridges Friction Slope Method= 1
Parabolic Critical Depth
Global Vel Dist=  1 , 1 , 1
Global Log Level= 0
CheckData=True
Encroach Param= -1, 0, 0, 0
BEGIN DESCRIPTION:
Multiple Run
END DESCRIPTION:

--- Stream0461.f01 (steady flow) ---

Flow Title=Multiple
Program Version=4.10
Number of Profiles= 7
Profile Names=10-year,25-year,50-year,1pct_min,100-year,1pct_plu,500-year
River Rch & RM=Stream0461,Reach-1         ,1427
     622    1030    1411     939    1875    3740    3270
Boundary for River Rch & Prof#=Stream0461,Reach-1         , 1
Up Type= 0
Dn Type= 3
Dn Slope=0.008
Boundary for River Rch & Prof#=Stream0461,Reach-1         , 2
Up Type= 0
Dn Type= 3
Dn Slope=0.008
Boundary for River Rch & Prof#=Stream0461,Reach-1         , 3
Up Type= 0
Dn Type= 3
Dn Slope=0.008
Boundary for River Rch & Prof#=Stream0461,Reach-1         , 4
Up Type= 0
Dn Type= 3
Dn Slope=0.008
Boundary for River Rch & Prof#=Stream0461,Reach-1         , 5
Up Type= 0
Dn Type= 3
Dn Slope=0.008
Boundary for River Rch & Prof#=Stream0461,Reach-1         , 6
Up Type= 0
Dn Type= 3
Dn Slope=0.008
Boundary for River Rch & Prof#=Stream0461,Reach-1         , 7
Up Type= 0
Dn Type= 3
Dn Slope=0.008
DSS Import GetInterval= 0
DSS Import GetPeak= 0
DSS Import FillOption= 0

--- Stream0461.g01 (geometry) ---

Geom Title=Existing Conditions
Program Version=4.10

River Reach=Stream0461      ,Reach-1
Reach XY= 30
        1981475.       13872475.      1981475.63     13872404.74
       1981472.9     13872380.87      1981464.14     13872365.36
       1981433.1     13872331.07       1981426.2      13872314.5
      1981425.43     13872154.82      1981421.46     13872126.46
      1981405.39     13872104.84      1981291.43     13871991.76
      1981277.06     13871969.15      1981274.57     13871945.18
      1981274.34     13871740.16      1981268.98     13871722.55
      1981238.96      13871688.2      1981232.59     13871674.99
      1981236.53     13871665.07      1981271.39     13871623.36
      1981274.85     13871590.42      1981267.17     13871569.09
      1981235.95     13871534.65      1981227.38     13871519.03
      1981224.88     13871445.05      1981221.39     13871426.48
      1981202.15     13871401.42      1981127.47     13871330.46
      1981100.12     13871324.72      1980980.79     13871323.09
       1980961.5     13871312.08        1980925.       13871275.

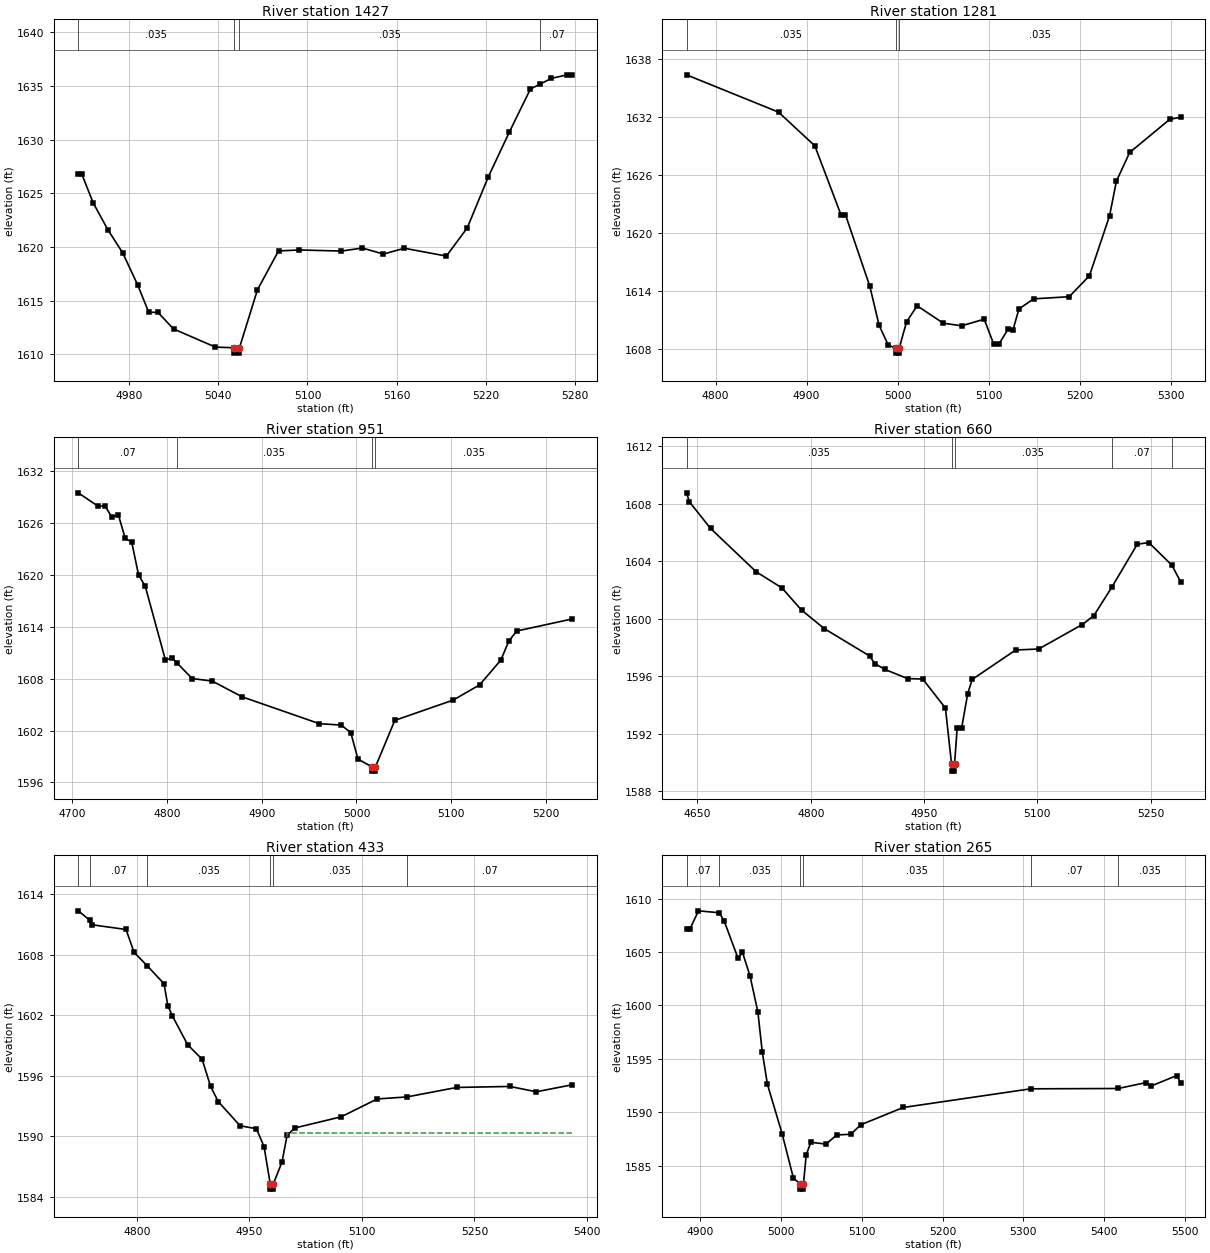
Type RM Length L Ch R = 1 ,1427    ,146,146,146
BEGIN DESCRIPTION:
Stream0461 3.0
END DESCRIPTION:
XS GIS Cut Line= 3
      1981525.02       13872375.        1981475.       13872375.
      1981274.97     13872575.03
#Sta/Elev= 30
  4945.6 1626.75  4948.1 1626.75  4955.6 1624.12  4965.6 1621.59  4975.6 1619.44
  4985.6 1616.47  4993.1 1613.92  4999.2 1613.92  5009.8 1612.37    5038 1610.68
  5050.2 1610.62  5050.4 1610.12  5053.9 1610.12  5054.2 1610.62  5066.3 1616.01
  5080.5 1619.63  5094.6 1619.72  5122.9 1619.62    5137  1619.9  5151.2 1619.34
  5165.3 1619.88  5193.6 1619.15  5207.7 1621.79  5221.9 1626.55    5236 1630.69
  5250.2  1634.7  5256.9 1635.17  5264.3 1635.69  5274.9 1636.02  5278.5 1636.02
#Mann= 4 ,-1 , 0
  4945.6    .035       0  5050.2    .035       0  5054.2    .035       0
  5256.9     .07       0
Bank Sta=5050.2,5054.2
XS Rating Curve= 0 ,0
Exp/Cntr=0.3,0.1

Type RM Length L Ch R = 1 ,1281    ,330,330,330
BEGIN DESCRIPTION:
Stream0461 4.0
END DESCRIPTION:
XS GIS Cut Line= 3
      1981654.75     13872217.43      1981319.92     13872261.43
      1981134.34     13872349.44
#Sta/Elev= 30
  4768.1 1636.35  4869.2 1632.49  4909.1    1629  4937.8 1621.87  4942.8 1621.86
  4969.6 1614.44  4979.7 1610.43  4989.7 1608.39  4997.8 1608.04  4998.1 1607.54
  5001.6 1607.54  5001.8 1608.04  5009.9 1610.77  5021.5 1612.44  5050.3 1610.64
  5070.4 1610.37  5095.2 1611.05  5105.8 1608.46  5111.3 1608.46  5121.3 1609.99
  5126.8 1609.91  5133.4 1612.11  5149.6 1613.16  5188.7 1613.38  5210.9 1615.55
    5233 1621.75  5240.5 1625.33  5255.1 1628.31  5299.4 1631.76  5311.2 1631.95
#Mann= 3 ,-1 , 0
  4768.1    .035       0  4997.8    .035       0  5001.8    .035       0
Bank Sta=4997.8,5001.8
XS Rating Curve= 0 ,0
Exp/Cntr=0.3,0.1

Type RM Length L Ch R = 1 ,951     ,291,291,291
BEGIN DESCRIPTION:
Stream0461 2.0
END DESCRIPTION:
XS GIS Cut Line= 4
      1981524.96     13872074.97      1981404.09     13871959.17
        1981275.       13871975.      1981074.96     13872075.02
#Sta/Elev= 30
  4706.6 1629.45  4727.8 1627.88  4734.7 1627.96  4741.9 1626.66  4748.9  1626.9
  4756.1  1624.2    4763 1623.75  4770.2 1619.96  4777.2 1618.67  4798.5 1610.15
  4805.5 1610.36  4810.6 1609.81  4826.8    1608  4847.9 1607.71  4879.4 1605.89
  4960.8 1602.79  4983.9 1602.63    4994 1601.75  5001.5 1598.71    5016 1597.81
  5016.3 1597.31  5019.8 1597.31    5020 1597.81  5040.4 1603.17  5101.9 1605.51
  5129.8 1607.27  5152.2 1610.13  5160.6 1612.33    5169 1613.49  5227.7 1614.89
#Mann= 4 ,-1 , 0
  4706.6     .07       0  4810.6    .035       0    5016    .035       0
    5020    .035       0
Bank Sta=5016,5020
XS Rating Curve= 0 ,0
Exp/Cntr=0.3,0.1

Type RM Length L Ch R = 1 ,660     ,227,227,227
BEGIN DESCRIPTION:
Stream0461 1.0
END DESCRIPTION:
XS GIS Cut Line= 3
      1981606.85     13871720.04      1981249.14     13871691.35
       1980999.4     13871849.58
#Sta/Elev= 30
  4635.5 1608.76  4639.2 1608.14  4667.4 1606.28  4727.6 1603.27  4761.9 1602.14
  4787.8  1600.6  4817.9 1599.31  4878.1  1597.4  4884.6 1596.88  4898.2 1596.47
  4928.3 1595.83  4948.3  1595.8  4978.4 1593.78  4986.5 1589.89  4986.7 1589.39
  4990.2 1589.39  4990.5 1589.89  4993.9 1592.37  4999.8 1592.37  5007.9 1594.78
  5013.8 1595.77  5071.4 1597.82  5101.9 1597.89  5159.5 1599.59  5174.8  1600.2
    5199 1602.21  5232.4 1605.18  5247.7  1605.3  5278.2 1603.73    5290 1602.56
#Mann= 5 ,-1 , 0
  4635.5    .035       0  4986.5    .035       0  4990.5    .035       0
    5199     .07       0  5278.2    .035       0
Bank Sta=4986.5,4990.5
XS Rating Curve= 0 ,0
Exp/Cntr=0.3,0.1

Type RM Length L Ch R = 1 ,433     ,168,168,168
BEGIN DESCRIPTION:
Stream0461 0.0
END DESCRIPTION:
XS GIS Cut Line= 3
      1981497.88     13871446.47      1981157.31     13871515.35
      1980946.86     13871744.93
#Sta/Elev= 30
  4721.7 1612.33  4736.9 1611.41  4739.7 1610.95  4785.4 1610.48  4796.1 1608.22
  4813.9 1606.86  4836.1  1605.1  4841.2  1602.9  4847.1 1601.93  4867.5 1599.06
  4886.8 1597.62  4898.1 1594.94  4908.3 1593.42  4937.5 1591.02  4959.3 1590.73
  4969.5 1588.93  4977.7 1585.24  4977.9 1584.74  4981.4 1584.74  4981.7 1585.24
  4993.4 1587.43  5000.1 1590.06  5010.3  1590.8  5072.3 1591.91  5120.3 1593.68
  5159.8 1593.88  5226.3 1594.82  5297.2 1594.92  5332.4 1594.39  5380.6 1595.09
#Mann= 6 ,-1 , 0
  4721.7    .035       0  4736.9     .07       0  4813.9    .035       0
  4977.7    .035       0  4981.7    .035       0  5159.8     .07       0
#XS Ineff= 2 , 0
                         4999.78         1590.29
Permanent Ineff=
       F       F
Bank Sta=4977.7,4981.7
XS Rating Curve= 0 ,0
Exp/Cntr=0.3,0.1

Type RM Length L Ch R = 1 ,265     ,0,0,0
BEGIN DESCRIPTION:
Stream0461 5.0
END DESCRIPTION:
XS GIS Cut Line= 3
      1981268.27     13871316.39      1981086.53     13871387.17
      1980879.96     13871748.67
#Sta/Elev= 30
  4883.3  1607.2  4887.7  1607.2  4898.1 1608.87  4923.7 1608.69  4929.7 1607.95
  4947.1 1604.41  4952.5 1604.98  4961.9 1602.76  4971.6 1599.38    4977 1595.65
  4983.4 1592.61  5001.5    1588  5015.6 1583.81    5024 1583.29  5024.2 1582.79
  5027.7 1582.79    5028 1583.29  5031.4 1586.01  5037.1 1587.18  5055.9 1587.01
  5069.2 1587.87  5086.5 1587.93  5098.9 1588.82  5151.3 1590.44  5309.1 1592.19
  5417.4 1592.22  5452.2 1592.78    5458 1592.45  5489.7 1593.43  5494.7 1592.75
#Mann= 6 ,-1 , 0
  4883.3     .07       0  4923.7    .035       0    5024    .035       0
    5028    .035       0  5309.1     .07       0  5417.4    .035       0
Bank Sta=5024,5028
XS Rating Curve= 0 ,0
Exp/Cntr=0.3,0.1

Chan Stop Cuts=-1
Use User Specified Reach Order=0
Composite Channel Slope=5