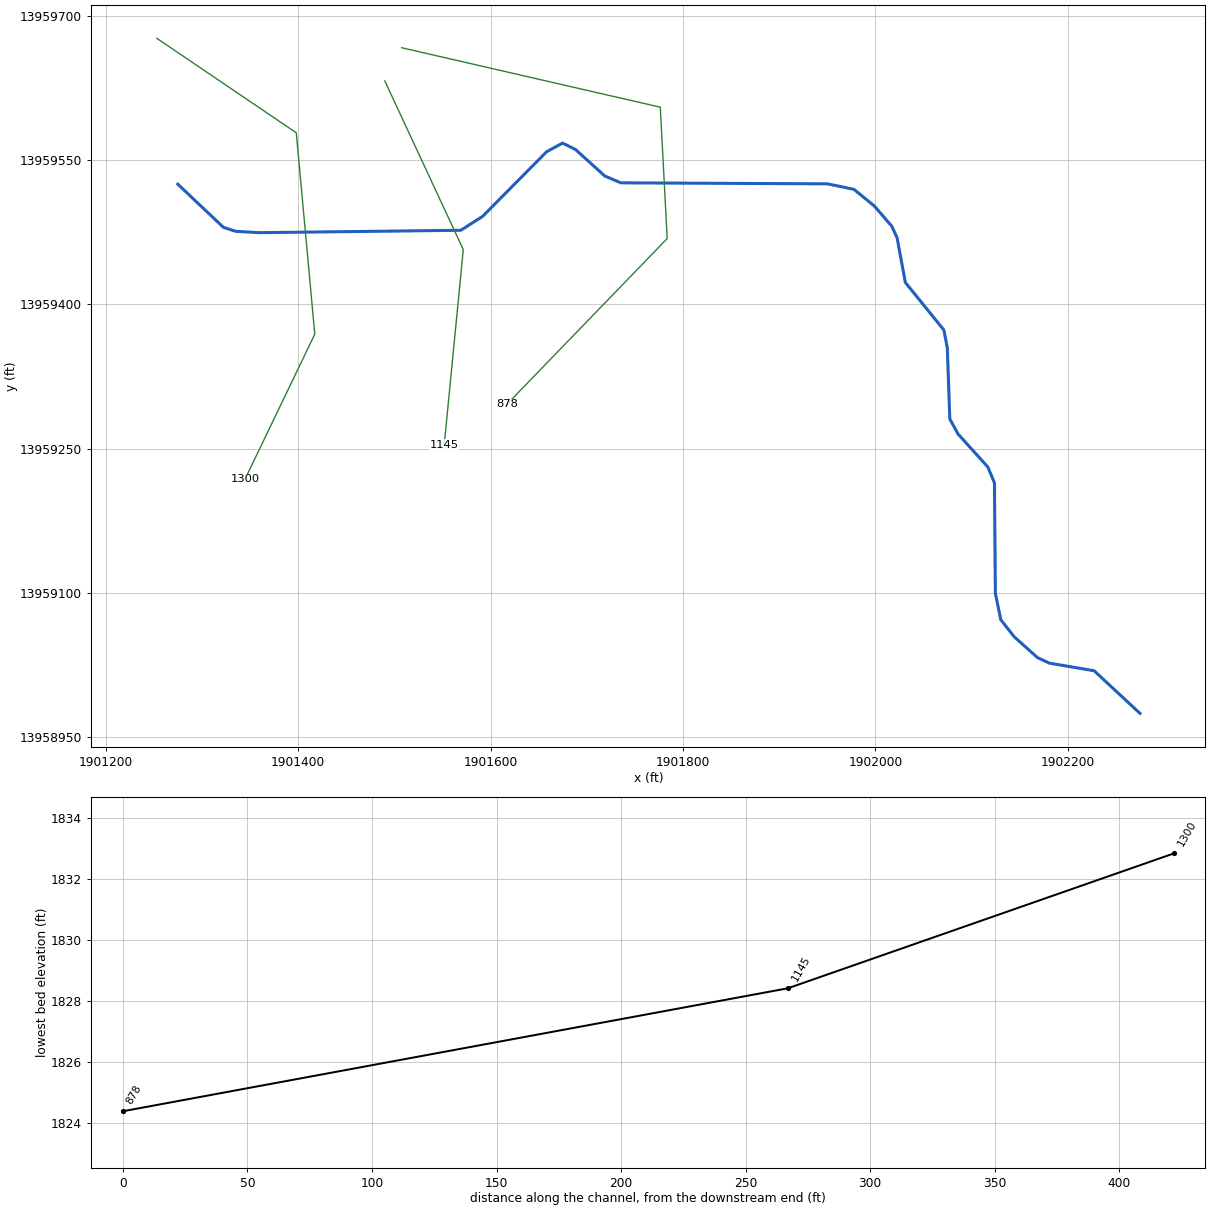
--- Stream0462.prj (project) ---

Proj Title=Stream0462 Base Level Engineering
Current Plan=p01
Default Exp/Contr=0.3,0.1
English Units
Geom File=g01
Flow File=f01
Plan File=p01
BEGIN DESCRIPTION:
Stream0462
END DESCRIPTION:

--- Stream0462.p01 (plan) ---

Plan Title=Multiple Run
Short Identifier=Multiple
Geom File=g01
Flow File=f01
Subcritical Flow
K Sum by GR= 0
Std Step Tol= 0.01
Critical Tol= 0.01
Num of Std Step Trials= 20
Max Error Tol= 0.3
Flow Tol Ratio= 0.001
Split Flow NTrial= 30
Split Flow Tol= 0.02
Split Flow Ratio= 0.02
Log Output Level= 0
Friction Slope Method= 1
Unsteady Friction Slope Method= 2
Unsteady Bridges Friction Slope Method= 1
Parabolic Critical Depth
Global Vel Dist=  1 , 1 , 1
Global Log Level= 0
CheckData=True
Encroach Param= -1, 0, 0, 0
BEGIN DESCRIPTION:
Multiple Run
END DESCRIPTION:

--- Stream0462.f01 (steady flow) ---

Flow Title=Multiple
Number of Profiles=7
Profile Names=10-year,25-year,50-year,1pct_min,100-year,1pct_plu,500-year
River Rch & RM= Stream0462,Reach-1,1300
     623    1031    1409     934    1864    3718    3212
Boundary for River Rch & Prof#=Stream0462,Reach-1,1
Up Type=0
Dn Type=3
Dn Slope=0.005
Boundary for River Rch & Prof#=Stream0462,Reach-1,2
Up Type=0
Dn Type=3
Dn Slope=0.005
Boundary for River Rch & Prof#=Stream0462,Reach-1,3
Up Type=0
Dn Type=3
Dn Slope=0.005
Boundary for River Rch & Prof#=Stream0462,Reach-1,4
Up Type=0
Dn Type=3
Dn Slope=0.005
Boundary for River Rch & Prof#=Stream0462,Reach-1,5
Up Type=0
Dn Type=3
Dn Slope=0.005
Boundary for River Rch & Prof#=Stream0462,Reach-1,6
Up Type=0
Dn Type=3
Dn Slope=0.005
Boundary for River Rch & Prof#=Stream0462,Reach-1,7
Up Type=0
Dn Type=3
Dn Slope=0.005

--- Stream0462.g01 (geometry) ---

Geom Title=Existing Conditions

River Reach=Stream0462,Reach-1
Reach XY= 30
      1901275.00     13959525.00      1901322.41     13959480.14
      1901335.40     13959475.96      1901359.83     13959474.59
      1901569.15     13959477.07      1901591.76     13959491.50
      1901658.31     13959558.67      1901674.90     13959567.67
      1901688.16     13959561.16      1901718.81     13959533.47
      1901735.43     13959526.39      1901950.21     13959525.33
      1901977.70     13959519.64      1901998.91     13959502.30
      1902017.00     13959481.39      1902022.59     13959469.17
      1902031.15     13959422.85      1902071.18     13959373.42
      1902074.77     13959354.91      1902077.36     13959280.98
      1902085.89     13959265.37      1902116.86     13959231.06
      1902123.77     13959214.49      1902124.69     13959099.80
      1902130.35     13959072.30      1902144.42     13959054.44
      1902168.55     13959032.91      1902180.74     13959027.24
      1902227.32     13959019.28      1902275.00     13958975.00

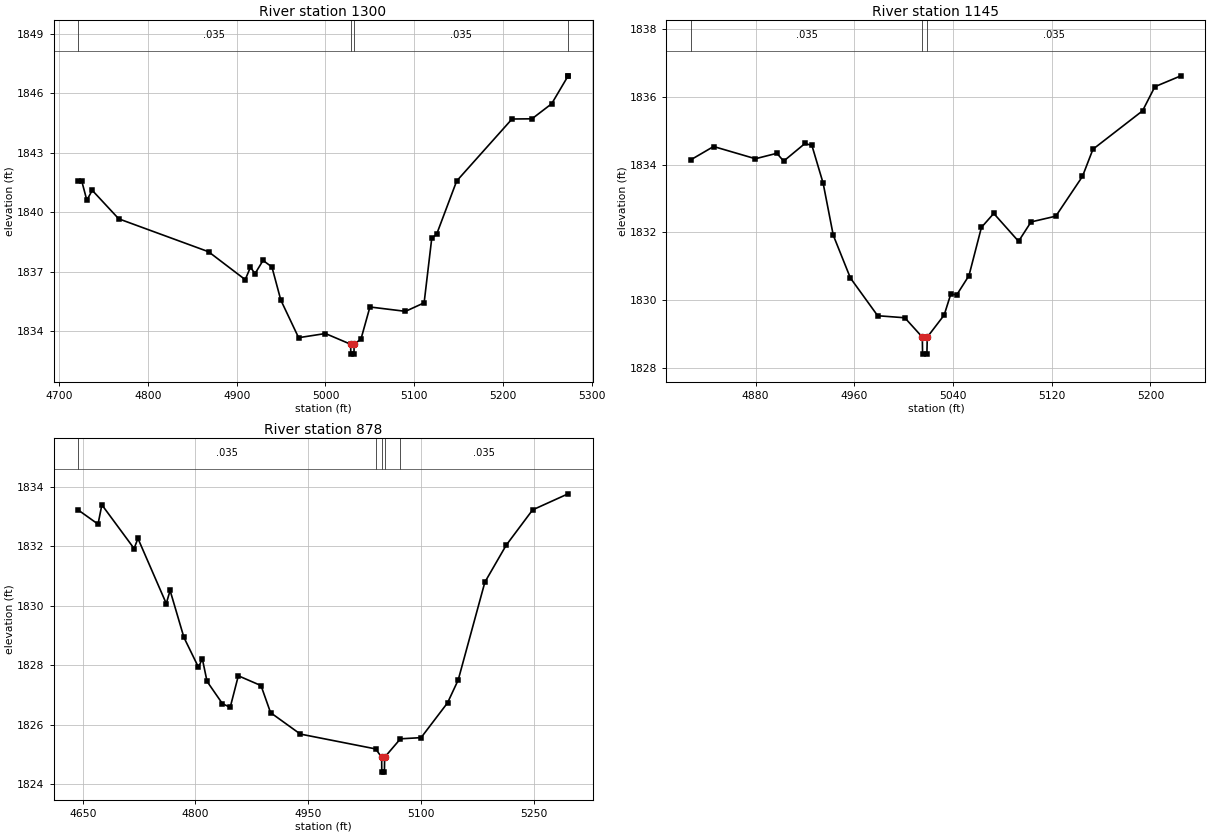
Type RM Length L Ch R = 1,1300,155,155,155
BEGIN DESCRIPTION:
Stream0462 2.0
END DESCRIPTION:
XS GIS Cut Line= 4
      1901253.24     13959676.56      1901398.13     13959578.41
      1901417.38     13959369.12      1901344.85     13959218.34
#Sta/Elev= 30
  4721.0 1841.58  4725.1 1841.58  4730.9 1840.60  4737.0 1841.10  4766.9 1839.66
  4868.1 1838.00  4909.5 1836.59  4915.4 1837.22  4920.5 1836.89  4929.6 1837.56
  4939.6 1837.23  4949.6 1835.56  4969.7 1833.66  4999.9 1833.87  5028.3 1833.33
  5028.6 1832.83  5032.1 1832.83  5032.3 1833.33  5040.0 1833.59  5050.1 1835.21
  5090.2 1834.99  5111.2 1835.42  5119.8 1838.68  5125.3 1838.88  5147.9 1841.57
  5210.3 1844.70  5232.8 1844.71  5255.0 1845.47  5273.2 1846.85  5273.5 1846.88
#Mann=4,-1,0
  4721.0   0.035       0  5028.3   0.035       0  5032.3   0.035       0
  5273.2    0.07       0
Bank Sta=5028.3,5032.3
Exp/Cntr=0.3,0.1

Type RM Length L Ch R = 1,1145,267,267,267
BEGIN DESCRIPTION:
Stream0462 1.0
END DESCRIPTION:
XS GIS Cut Line= 3
      1901490.19     13959632.23      1901571.71     13959457.02
      1901551.91     13959254.03
#Sta/Elev= 30
  4827.5 1834.14  4845.9 1834.53  4879.8 1834.17  4897.2 1834.33  4902.7 1834.10
  4920.0 1834.62  4925.6 1834.56  4934.7 1833.45  4942.9 1831.92  4956.8 1830.66
  4978.9 1829.55  5000.9 1829.49  5015.1 1828.92  5015.3 1828.42  5018.8 1828.42
  5019.1 1828.92  5032.8 1829.57  5038.1 1830.18  5043.1 1830.17  5052.9 1830.73
  5063.0 1832.15  5073.0 1832.56  5093.1 1831.74  5103.2 1832.31  5123.3 1832.48
  5144.9 1833.65  5153.4 1834.45  5193.6 1835.58  5203.6 1836.29  5224.7 1836.61
#Mann=3,-1,0
  4827.5   0.035       0  5015.1   0.035       0  5019.1   0.035       0
Bank Sta=5015.1,5019.1
Exp/Cntr=0.3,0.1

Type RM Length L Ch R = 1,878,0,0,0
BEGIN DESCRIPTION:
Stream0462 0.0
END DESCRIPTION:
XS GIS Cut Line= 4
      1901507.69     13959666.79      1901776.46     13959605.00
      1901783.64     13959468.48      1901617.07     13959296.24
#Sta/Elev= 30
  4643.8 1833.22  4670.4 1832.74  4675.5 1833.39  4718.4 1831.92  4723.5 1832.26
  4761.2 1830.07  4766.3 1830.51  4784.7 1828.93  4804.0 1827.93  4809.2 1828.21
  4815.5 1827.45  4836.0 1826.70  4846.3 1826.58  4857.1 1827.64  4887.3 1827.31
  4900.0 1826.40  4939.6 1825.68  5039.9 1825.18  5047.8 1824.90  5048.0 1824.40
  5051.5 1824.40  5051.8 1824.90  5072.8 1825.52  5100.3 1825.56  5135.5 1826.73
  5149.7 1827.50  5185.2 1830.79  5213.5 1832.03  5248.7 1833.22  5295.9 1833.76
#Mann=5,-1,0
  4643.8   0.035       0  5039.9    0.07       0  5047.8   0.035       0
  5051.8    0.07       0  5072.8   0.035       0
Bank Sta=5047.8,5051.8
Exp/Cntr=0.3,0.1

Chan Stop Cuts=-1