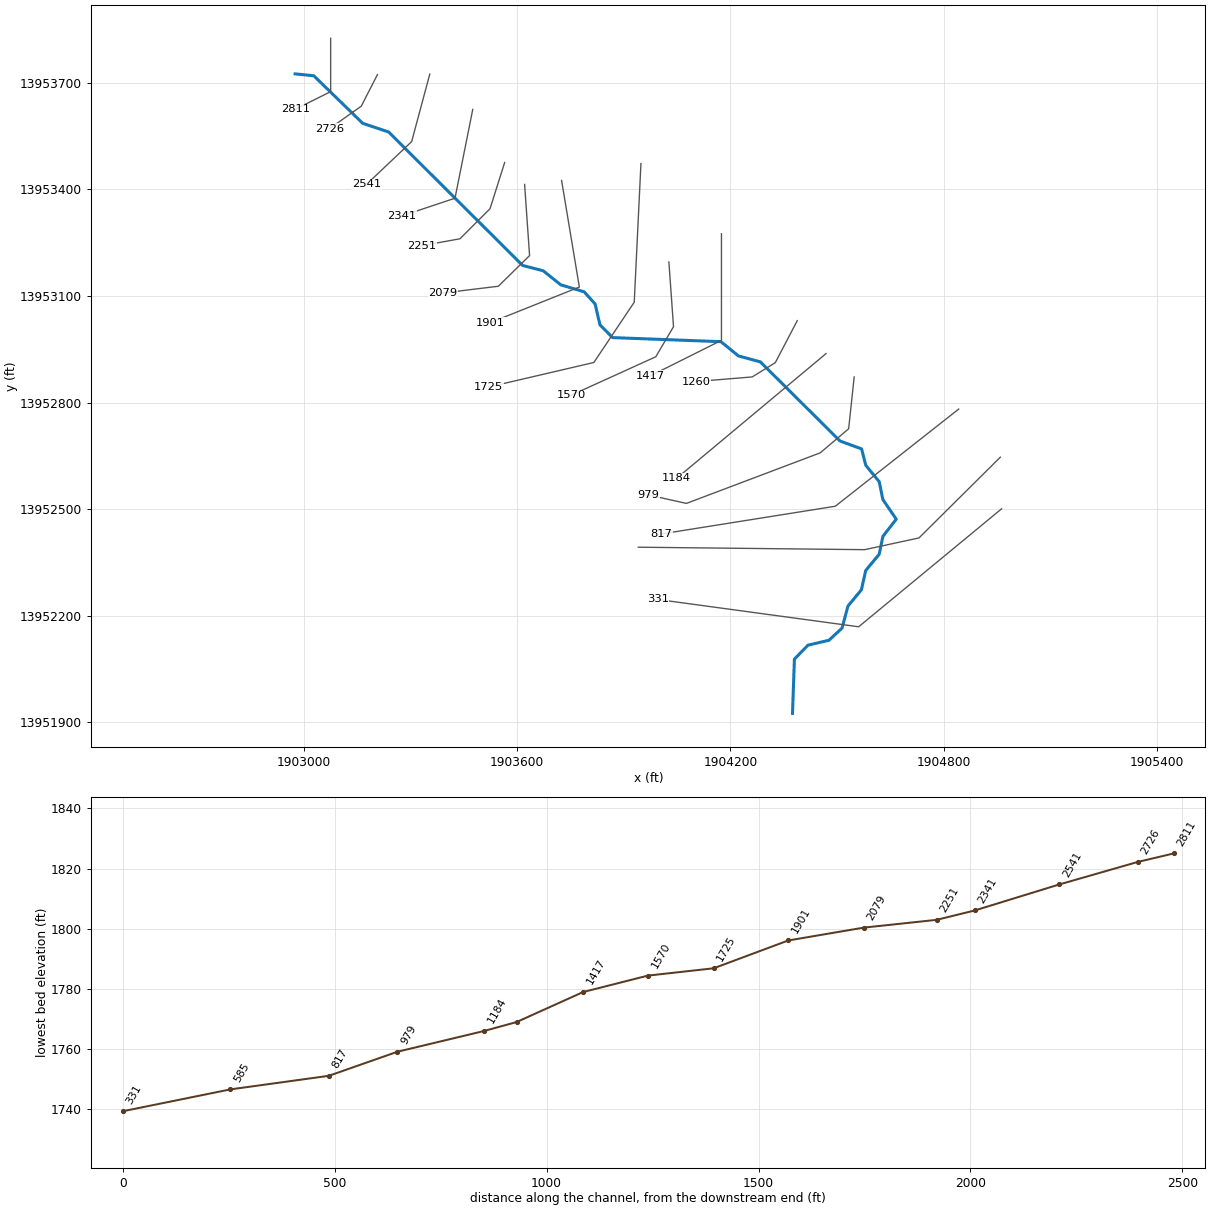
--- Stream0468.prj (project) ---

Proj Title=Stream0468 Base Level Engineering
Current Plan=p01
Default Exp/Contr=0.3,0.1
English Units
Geom File=g01
Flow File=f01
Plan File=p01
BEGIN DESCRIPTION:
Stream0468
END DESCRIPTION:

--- Stream0468.p01 (plan) ---

Plan Title=Multiple Run
Short Identifier=Multiple
Geom File=g01
Flow File=f01
Subcritical Flow
K Sum by GR= 0
Std Step Tol= 0.01
Critical Tol= 0.01
Num of Std Step Trials= 20
Max Error Tol= 0.3
Flow Tol Ratio= 0.001
Split Flow NTrial= 30
Split Flow Tol= 0.02
Split Flow Ratio= 0.02
Log Output Level= 0
Friction Slope Method= 1
Unsteady Friction Slope Method= 2
Unsteady Bridges Friction Slope Method= 1
Parabolic Critical Depth
Global Vel Dist=  1 , 1 , 1
Global Log Level= 0
CheckData=True
Encroach Param= -1, 0, 0, 0
BEGIN DESCRIPTION:
Multiple Run
END DESCRIPTION:

--- Stream0468.f01 (steady flow) ---

Flow Title=Multiple
Number of Profiles=7
Profile Names=10-year,25-year,50-year,1pct_min,100-year,1pct_plu,500-year
River Rch & RM= Stream0468,Reach-1,2811
     336     532     706     457     911    1818    1488
Boundary for River Rch & Prof#=Stream0468,Reach-1,1
Up Type=0
Dn Type=3
Dn Slope=0.005
Boundary for River Rch & Prof#=Stream0468,Reach-1,2
Up Type=0
Dn Type=3
Dn Slope=0.005
Boundary for River Rch & Prof#=Stream0468,Reach-1,3
Up Type=0
Dn Type=3
Dn Slope=0.005
Boundary for River Rch & Prof#=Stream0468,Reach-1,4
Up Type=0
Dn Type=3
Dn Slope=0.005
Boundary for River Rch & Prof#=Stream0468,Reach-1,5
Up Type=0
Dn Type=3
Dn Slope=0.005
Boundary for River Rch & Prof#=Stream0468,Reach-1,6
Up Type=0
Dn Type=3
Dn Slope=0.005
Boundary for River Rch & Prof#=Stream0468,Reach-1,7
Up Type=0
Dn Type=3
Dn Slope=0.005

--- Stream0468.g01 (geometry) ---

Geom Title=Existing Conditions

River Reach=Stream0468,Reach-1
Reach XY= 30
      1902975.00     13953725.00      1903027.52     13953719.69
      1903165.32     13953585.78      1903238.21     13953561.37
      1903615.32     13953185.76      1903673.27     13953170.81
      1903722.84     13953131.11      1903788.56     13953111.52
      1903819.24     13953077.51      1903833.03     13953018.64
      1903868.52     13952982.69      1904173.45     13952971.25
      1904222.83     13952931.14      1904284.68     13952914.24
      1904508.52     13952691.73      1904569.41     13952669.39
      1904581.24     13952623.15      1904618.96     13952577.22
      1904629.43     13952526.64      1904666.98     13952471.69
      1904629.43     13952423.36      1904618.95     13952372.81
      1904581.08     13952327.20      1904568.92     13952272.80
      1904531.11     13952227.16      1904514.37     13952165.00
      1904477.51     13952130.76      1904418.64     13952116.97
      1904380.33     13952077.72      1904375.00     13951925.00

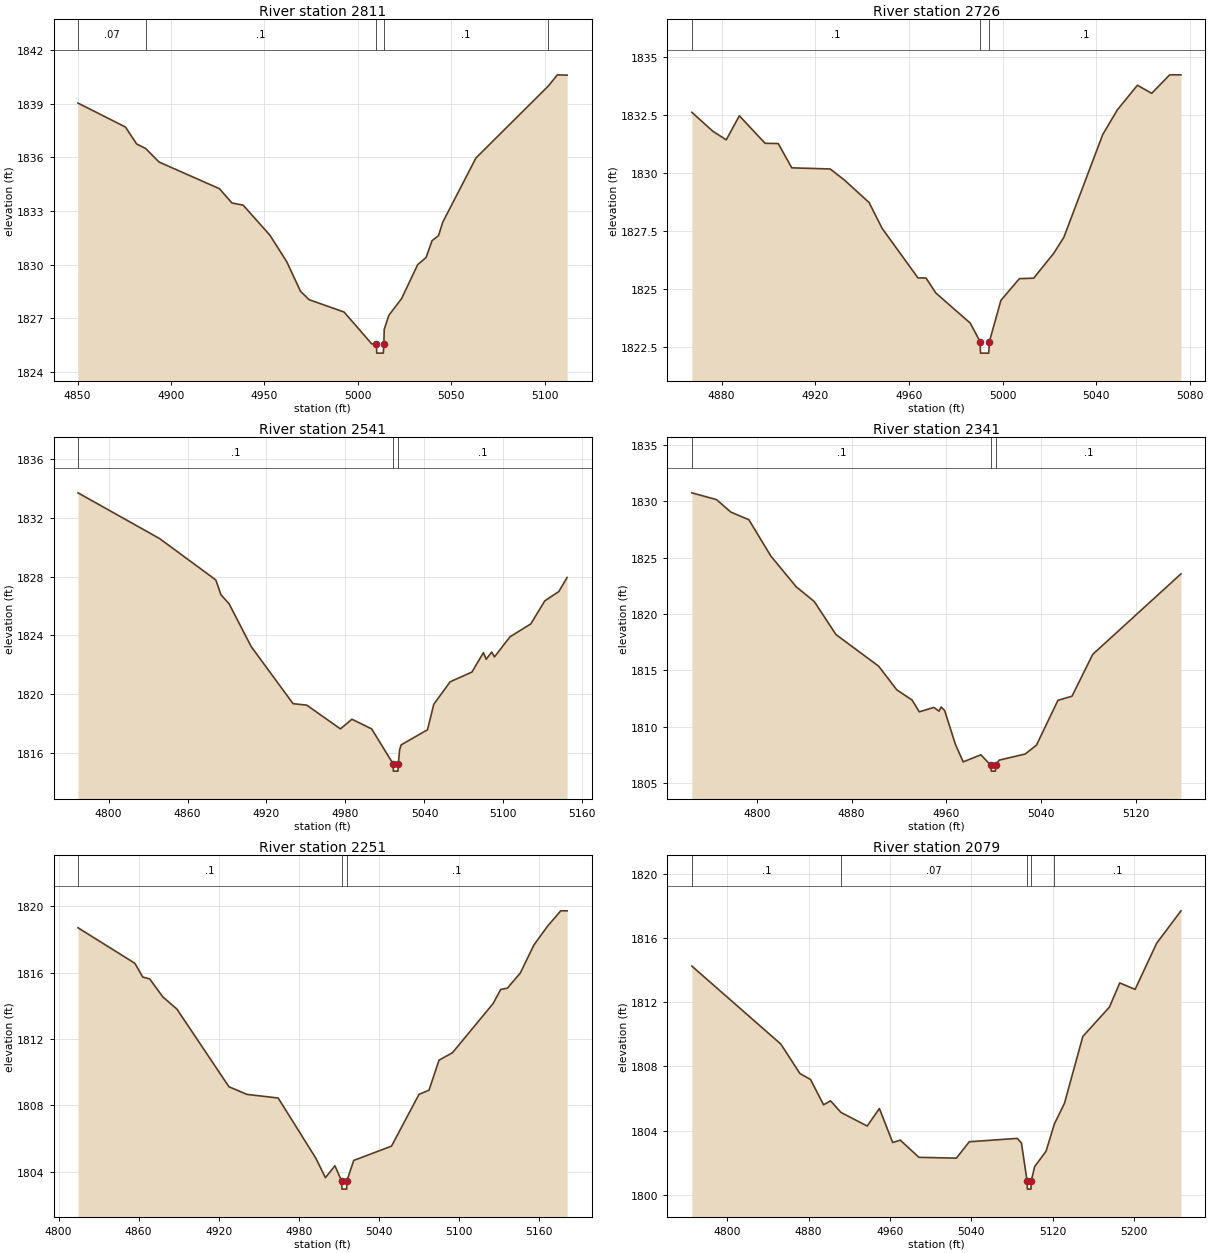
Type RM Length L Ch R = 1,2811,85,85,85
BEGIN DESCRIPTION:
Stream0468 4.0
END DESCRIPTION:
XS GIS Cut Line= 3
      1903075.00     13953825.03      1903075.00     13953675.00
      1902975.03     13953625.02
#Sta/Elev= 30
  4850.2 1839.04  4875.6 1837.70  4881.6 1836.75  4886.4 1836.50  4893.6 1835.74
  4925.9 1834.25  4932.6 1833.45  4938.6 1833.33  4952.9 1831.65  4961.9 1830.17
  4969.3 1828.51  4973.9 1828.04  4992.6 1827.35  5007.4 1825.57  5009.9 1825.55
  5010.1 1825.05  5013.6 1825.05  5013.9 1825.55  5014.1 1826.38  5016.6 1827.17
  5023.4 1828.10  5032.0 1830.00  5036.5 1830.40  5039.7 1831.34  5043.2 1831.63
  5045.4 1832.37  5063.2 1835.97  5101.9 1839.99  5106.8 1840.62  5112.0 1840.60
#Mann=5,-1,0
  4850.2    0.07       0  4886.4     0.1       0  5009.9    0.05       0
  5013.9     0.1       0  5101.9    0.07       0
Bank Sta=5009.9,5013.9
Exp/Cntr=0.3,0.1

Type RM Length L Ch R = 1,2726,185,185,185
BEGIN DESCRIPTION:
Stream0468 L
END DESCRIPTION:
XS GIS Cut Line= 3
      1903206.72     13953723.01      1903161.16     13953634.04
      1903072.21     13953571.13
#Sta/Elev= 30
  4867.3 1832.63  4876.3 1831.81  4882.0 1831.44  4887.6 1832.48  4898.6 1831.29
  4904.2 1831.28  4910.0 1830.23  4926.4 1830.18  4932.5 1829.70  4943.0 1828.73
  4948.6 1827.61  4963.9 1825.47  4967.3 1825.47  4971.5 1824.82  4986.2 1823.52
  4990.4 1822.72  4990.6 1822.22  4994.1 1822.22  4994.4 1822.72  4999.3 1824.50
  5007.2 1825.44  5013.3 1825.46  5021.9 1826.54  5026.2 1827.23  5042.8 1831.67
  5049.0 1832.73  5057.6 1833.80  5063.7 1833.45  5071.4 1834.25  5076.2 1834.25
#Mann=3,-1,0
  4867.3     0.1       0  4990.4    0.05       0  4994.4     0.1       0
Bank Sta=4990.4,4994.4
Exp/Cntr=0.3,0.1

Type RM Length L Ch R = 1,2541,200,200,200
BEGIN DESCRIPTION:
Mapping XS d5f56489
END DESCRIPTION:
XS GIS Cut Line= 3
      1903354.09     13953724.54      1903303.00     13953534.38
      1903176.23     13953414.18
#Sta/Elev= 30
  4776.8 1833.72  4838.8 1830.60  4881.5 1827.78  4885.4 1826.77  4891.6 1826.15
  4908.4 1823.23  4940.2 1819.34  4950.6 1819.24  4976.2 1817.62  4984.9 1818.28
  4999.9 1817.62  5016.2 1815.24  5016.4 1814.74  5019.9 1814.74  5020.2 1815.24
  5021.1 1816.18  5022.3 1816.53  5042.3 1817.56  5047.1 1819.30  5059.5 1820.83
  5076.1 1821.50  5084.8 1822.82  5086.9 1822.37  5091.1 1822.86  5093.2 1822.53
  5105.0 1823.90  5120.8 1824.78  5131.4 1826.35  5142.1 1826.99  5148.4 1827.95
#Mann=3,-1,0
  4776.8     0.1       0  5016.2    0.05       0  5020.2     0.1       0
Bank Sta=5016.2,5020.2
Exp/Cntr=0.3,0.1

Type RM Length L Ch R = 1,2341,90,90,90
BEGIN DESCRIPTION:
Stream0468 3.0
END DESCRIPTION:
XS GIS Cut Line= 3
      1903475.01     13953625.04      1903425.00     13953375.00
      1903275.01     13953325.00
#Sta/Elev= 30
  4745.0 1830.76  4765.8 1830.16  4778.0 1829.05  4793.2 1828.37  4811.7 1825.16
  4833.1 1822.43  4848.4 1821.12  4866.7 1818.19  4902.8 1815.38  4918.1 1813.28
  4931.0 1812.38  4937.1 1811.33  4949.4 1811.72  4953.8 1811.39  4955.5 1811.76
  4958.5 1811.45  4967.7 1808.42  4974.2 1806.89  4989.1 1807.52  4997.7 1806.57
  4997.9 1806.07  5001.4 1806.07  5001.7 1806.57  5004.4 1807.04  5026.6 1807.59
  5036.1 1808.38  5054.2 1812.35  5066.1 1812.72  5083.6 1816.43  5158.1 1823.57
#Mann=3,-1,0
  4745.0     0.1       0  4997.7    0.05       0  5001.7     0.1       0
Bank Sta=4997.7,5001.7
Exp/Cntr=0.3,0.1

Type RM Length L Ch R = 1,2251,172,172,172
BEGIN DESCRIPTION:
Stream0468 K
END DESCRIPTION:
XS GIS Cut Line= 4
      1903564.81     13953475.64      1903523.57     13953345.41
      1903438.93     13953260.78      1903330.47     13953241.26
#Sta/Elev= 30
  4814.6 1818.70  4857.2 1816.56  4863.1 1815.73  4868.3 1815.62  4878.2 1814.53
  4888.7 1813.80  4927.7 1809.12  4941.1 1808.66  4964.6 1808.44  4992.9 1804.80
  5000.0 1803.64  5007.1 1804.36  5012.1 1803.45  5012.4 1802.95  5015.9 1802.95
  5016.1 1803.45  5021.2 1804.68  5049.5 1805.54  5070.1 1808.66  5077.6 1808.91
  5085.1 1810.72  5095.2 1811.17  5125.7 1814.14  5131.3 1814.98  5136.3 1815.06
  5146.0 1815.97  5156.2 1817.66  5166.3 1818.78  5176.3 1819.72  5181.1 1819.72
#Mann=3,-1,0
  4814.6     0.1       0  5012.1    0.05       0  5016.1     0.1       0
Bank Sta=5012.1,5016.1
Exp/Cntr=0.3,0.1

Type RM Length L Ch R = 1,2079,178,178,178
BEGIN DESCRIPTION:
Mapping XS 1c591f07
END DESCRIPTION:
XS GIS Cut Line= 4
      1903620.93     13953413.74      1903634.93     13953213.50
      1903546.92     13953127.23      1903390.95     13953108.24
#Sta/Elev= 30
  4765.2 1814.25  4852.8 1809.39  4871.5 1807.56  4881.9 1807.19  4894.8 1805.61
  4901.6 1805.86  4912.0 1805.13  4937.7 1804.29  4949.7 1805.38  4962.8 1803.26
  4970.2 1803.41  4988.6 1802.34  5025.4 1802.29  5038.1 1803.31  5085.3 1803.52
  5089.4 1803.23  5095.0 1800.86  5095.3 1800.36  5098.8 1800.36  5099.0 1800.86
  5102.4 1801.76  5113.6 1802.72  5121.8 1804.42  5131.7 1805.70  5149.8 1809.87
  5175.9 1811.69  5186.1 1813.20  5201.2 1812.80  5222.4 1815.67  5246.3 1817.69
#Mann=5,-1,0
  4765.2     0.1       0  4912.0    0.07       0  5095.0    0.05       0
  5099.0    0.07       0  5121.8     0.1       0
Bank Sta=5095,5099
Exp/Cntr=0.3,0.1

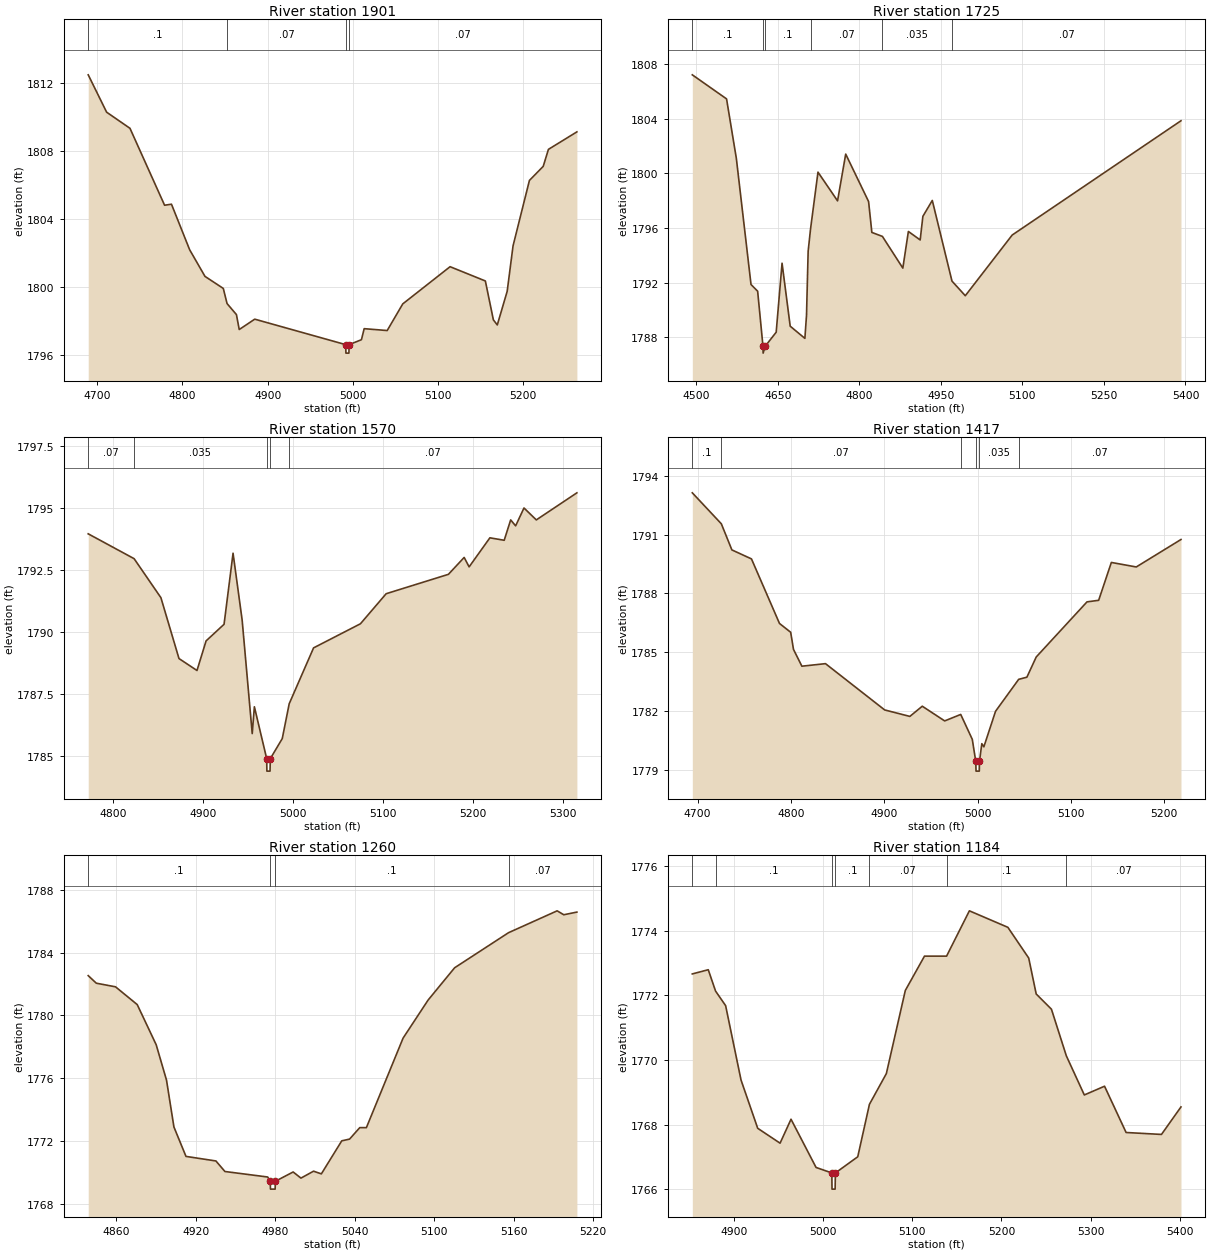
Type RM Length L Ch R = 1,1901,176,176,176
BEGIN DESCRIPTION:
Stream0468 2.0
END DESCRIPTION:
XS GIS Cut Line= 3
      1903725.00     13953425.01      1903775.00     13953125.00
      1903525.01     13953025.00
#Sta/Elev= 30
  4689.4 1812.48  4711.0 1810.28  4738.4 1809.33  4779.0 1804.80  4787.1 1804.86
  4808.4 1802.18  4826.4 1800.61  4847.9 1799.90  4852.3 1799.01  4863.3 1798.36
  4866.6 1797.48  4884.8 1798.09  4991.5 1796.59  4991.8 1796.09  4995.3 1796.09
  4995.5 1796.59  5010.0 1796.88  5013.2 1797.53  5040.2 1797.42  5058.5 1798.99
  5114.0 1801.18  5155.4 1800.34  5164.8 1798.05  5169.4 1797.75  5181.0 1799.73
  5187.9 1802.41  5207.1 1806.26  5223.3 1807.09  5229.4 1808.09  5262.8 1809.12
#Mann=4,-1,0
  4689.4     0.1       0  4852.3    0.07       0  4991.5    0.05       0
  4995.5    0.07       0
Bank Sta=4991.5,4995.5
Exp/Cntr=0.3,0.1

Type RM Length L Ch R = 1,1725,155,155,155
BEGIN DESCRIPTION:
Mapping XS abdf49bf
END DESCRIPTION:
XS GIS Cut Line= 4
      1903948.37     13953472.56      1903929.50     13953082.30
      1903815.89     13952912.67      1903519.71     13952843.58
#Sta/Elev= 30
  4492.8 1807.20  4555.8 1805.44  4573.8 1801.09  4600.8 1791.86  4613.0 1791.37
  4622.8 1787.34  4623.1 1786.84  4626.8 1787.34  4647.1 1788.37  4657.9 1793.42
  4672.9 1788.81  4699.9 1787.92  4702.9 1789.61  4705.9 1794.29  4710.3 1795.92
  4724.0 1800.08  4760.0 1797.98  4775.0 1801.40  4817.1 1797.93  4823.1 1795.67
  4842.5 1795.38  4880.1 1793.06  4890.3 1795.74  4912.0 1795.12  4917.0 1796.85
  4934.3 1798.01  4970.5 1792.11  4995.0 1791.04  5081.3 1795.48  5391.8 1803.84
#Mann=6,-1,0
  4492.8     0.1       0  4622.8    0.05       0  4626.8     0.1       0
  4710.3    0.07       0  4842.5   0.035       0  4970.5    0.07       0
Bank Sta=4622.8,4626.8
Exp/Cntr=0.3,0.1

Type RM Length L Ch R = 1,1570,153,153,153
BEGIN DESCRIPTION:
Stream0468 J
END DESCRIPTION:
XS GIS Cut Line= 4
      1904027.04     13953195.64      1904040.06     13953013.38
      1903990.15     13952928.75      1903751.43     13952820.24
#Sta/Elev= 30
  4772.7 1793.96  4823.7 1792.96  4853.5 1791.39  4873.6 1788.94  4893.6 1788.46
  4903.7 1789.65  4923.7 1790.32  4933.7 1793.18  4943.8 1790.49  4955.0 1785.92
  4957.4 1787.00  4971.1 1784.91  4971.3 1784.41  4974.8 1784.41  4975.1 1784.91
  4988.4 1785.72  4996.1 1787.12  5023.2 1789.37  5075.3 1790.34  5103.9 1791.55
  5173.1 1792.33  5190.6 1793.01  5196.1 1792.63  5219.2 1793.80  5235.1 1793.70
  5242.3 1794.52  5247.8 1794.28  5257.1 1795.00  5270.8 1794.52  5315.9 1795.61
#Mann=5,-1,0
  4772.7    0.07       0  4823.7   0.035       0  4971.1    0.05       0
  4975.1   0.035       0  4996.1    0.07       0
Bank Sta=4971.1,4975.1
Exp/Cntr=0.3,0.1

Type RM Length L Ch R = 1,1417,157,157,157
BEGIN DESCRIPTION:
Stream0468 1.0
END DESCRIPTION:
XS GIS Cut Line= 3
      1904175.00     13953275.03      1904175.00     13952975.00
      1903975.04     13952875.02
#Sta/Elev= 30
  4694.3 1793.13  4725.4 1791.55  4736.7 1790.22  4757.7 1789.76  4787.7 1786.47
  4799.7 1786.02  4802.7 1785.15  4811.7 1784.29  4837.0 1784.42  4900.4 1782.06
  4927.4 1781.73  4940.7 1782.25  4964.7 1781.50  4981.9 1781.83  4994.3 1780.56
  4998.0 1779.44  4998.3 1778.94  5001.8 1778.94  5002.0 1779.44  5004.5 1780.34
  5006.7 1780.18  5019.2 1781.99  5044.0 1783.62  5052.8 1783.73  5062.8 1784.76
  5117.2 1787.57  5129.7 1787.65  5143.3 1789.58  5170.0 1789.35  5217.9 1790.75
#Mann=6,-1,0
  4694.3     0.1       0  4725.4    0.07       0  4981.9   0.035       0
  4998.0   0.035       0  5002.0   0.035       0  5044.0    0.07       0
Bank Sta=4998,5002
Exp/Cntr=0.3,0.1

Type RM Length L Ch R = 1,1260,76,76,76
BEGIN DESCRIPTION:
Stream0468 M
END DESCRIPTION:
XS GIS Cut Line= 4
      1904388.39     13953030.42      1904326.52     13952912.11
      1904261.42     13952871.96      1904103.04     13952858.95
#Sta/Elev= 30
  4838.8 1782.53  4844.9 1782.05  4859.4 1781.82  4875.8 1780.69  4890.1 1778.14
  4897.9 1775.89  4903.5 1772.91  4912.6 1771.04  4935.2 1770.75  4942.0 1770.08
  4974.3 1769.73  4976.1 1769.46  4976.4 1768.96  4979.9 1768.96  4980.1 1769.46
  4993.5 1770.05  4999.4 1769.66  5008.9 1770.10  5014.8 1769.93  5030.2 1772.03
  5036.1 1772.14  5043.8 1772.87  5048.8 1772.87  5076.5 1778.56  5095.4 1780.98
  5115.4 1783.03  5156.1 1785.26  5192.8 1786.65  5197.8 1786.40  5207.7 1786.57
#Mann=4,-1,0
  4838.8     0.1       0  4976.1    0.05       0  4980.1     0.1       0
  5156.1    0.07       0
Bank Sta=4976.1,4980.1
Exp/Cntr=0.3,0.1

Type RM Length L Ch R = 1,1184,205,205,205
BEGIN DESCRIPTION:
Stream0468 0.1
END DESCRIPTION:
XS GIS Cut Line= 2
      1904469.43     13952937.70      1904048.41     13952586.14
#Sta/Elev= 30
  4853.0 1772.66  4870.9 1772.79  4879.1 1772.13  4890.4 1771.68  4907.7 1769.38
  4926.4 1767.89  4951.5 1767.43  4963.8 1768.17  4991.9 1766.68  5009.6 1766.51
  5009.8 1766.01  5013.3 1766.01  5013.6 1766.51  5038.7 1767.01  5051.8 1768.63
  5070.8 1769.58  5092.1 1772.15  5113.6 1773.21  5138.4 1773.21  5164.0 1774.61
  5207.2 1774.10  5230.6 1773.15  5239.0 1772.04  5256.1 1771.57  5272.8 1770.13
  5293.0 1768.92  5315.7 1769.19  5339.9 1767.76  5379.6 1767.70  5401.5 1768.55
#Mann=7,-1,0
  4853.0    0.07       0  4879.1     0.1       0  5009.6    0.05       0
  5013.6     0.1       0  5051.8    0.07       0  5138.4     0.1       0
  5272.8    0.07       0
Bank Sta=5009.6,5013.6
Exp/Cntr=0.3,0.1

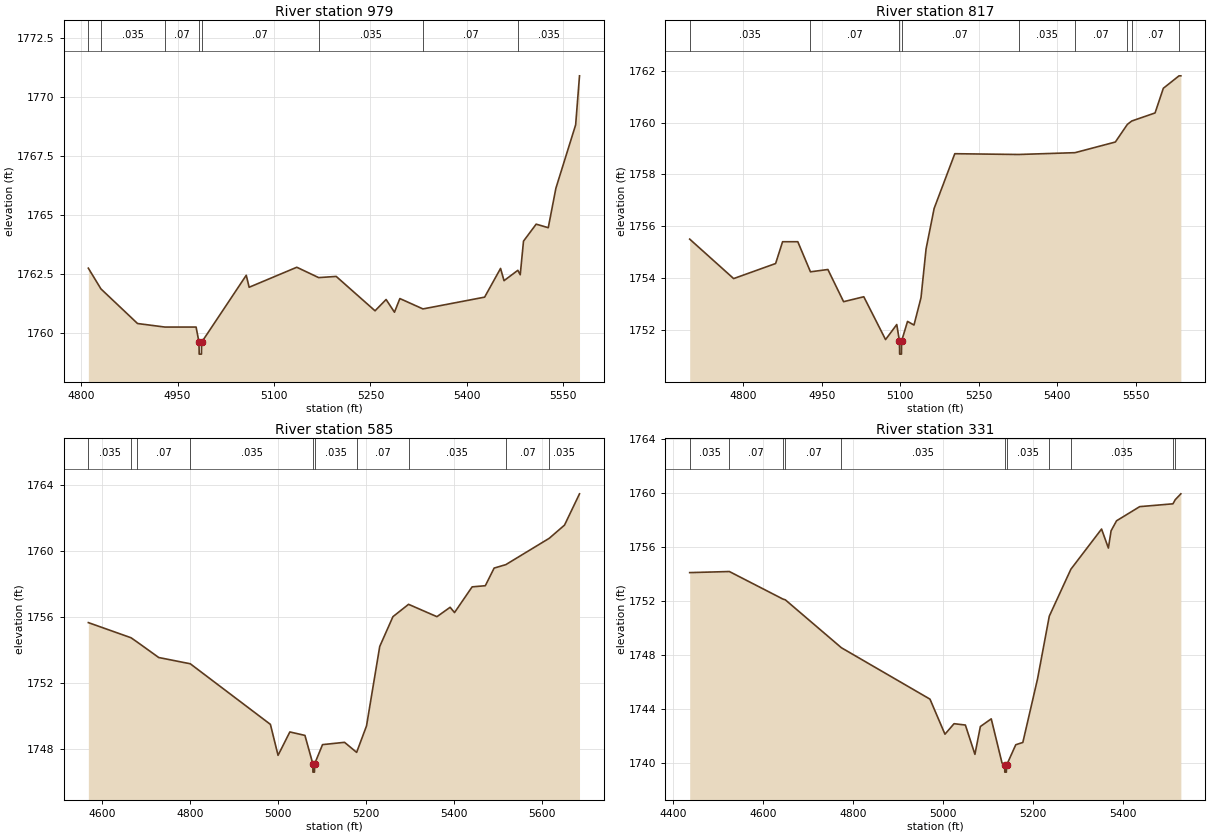
Type RM Length L Ch R = 1,979,162,162,162
BEGIN DESCRIPTION:
Stream0468 N
END DESCRIPTION:
XS GIS Cut Line= 5
      1904548.60     13952871.87      1904532.97     13952726.06
      1904453.11     13952658.35      1904076.38     13952515.99
      1903969.17     13952539.81
#Sta/Elev= 30
  4811.3 1762.74  4830.9 1761.86  4887.8 1760.39  4930.2 1760.24  4978.9 1760.24
  4983.4 1759.59  4983.7 1759.09  4987.2 1759.09  4987.4 1759.59  5056.9 1762.44
  5061.4 1761.93  5135.5 1762.78  5169.5 1762.34  5196.8 1762.39  5257.2 1760.93
  5274.4 1761.41  5287.4 1760.87  5295.8 1761.45  5331.7 1761.01  5427.6 1761.51
  5452.4 1762.73  5457.8 1762.21  5479.3 1762.65  5483.0 1762.46  5488.1 1763.89
  5507.8 1764.61  5526.6 1764.46  5538.5 1766.14  5569.2 1768.83  5575.2 1770.91
#Mann=8,-1,0
  4811.3    0.07       0  4830.9   0.035       0  4930.2    0.07       0
  4983.4    0.05       0  4987.4    0.07       0  5169.5   0.035       0
  5331.7    0.07       0  5479.3   0.035       0
Bank Sta=4983.4,4987.4
Exp/Cntr=0.3,0.1

Type RM Length L Ch R = 1,817,232,232,232
BEGIN DESCRIPTION:
Stream0468 0.0
END DESCRIPTION:
XS GIS Cut Line= 3
      1904842.75     13952781.50      1904495.50     13952508.04
      1904005.08     13952429.92
#Sta/Elev= 30
  4697.8 1755.51  4781.8 1753.99  4862.0 1754.57  4875.3 1755.41  4904.4 1755.41
  4928.6 1754.25  4961.9 1754.34  4991.9 1753.10  5030.5 1753.29  5072.1 1751.64
  5093.5 1752.22  5098.7 1751.58  5099.0 1751.08  5102.5 1751.08  5102.7 1751.58
  5114.1 1752.34  5126.4 1752.20  5139.8 1753.25  5149.5 1755.13  5164.9 1756.69
  5204.4 1758.80  5326.4 1758.77  5434.2 1758.84  5511.2 1759.25  5534.2 1759.93
  5542.6 1760.06  5587.1 1760.37  5602.9 1761.32  5632.9 1761.80  5636.4 1761.80
#Mann=9,-1,0
  4697.8   0.035       0  4928.6    0.07       0  5098.7    0.05       0
  5102.7    0.07       0  5326.4   0.035       0  5434.2    0.07       0
  5534.2   0.035       0  5542.6    0.07       0  5632.9   0.035       0
Bank Sta=5098.7,5102.7
Exp/Cntr=0.3,0.1

Type RM Length L Ch R = 1,585,254,254,254
BEGIN DESCRIPTION:
Stream0468 O
END DESCRIPTION:
XS GIS Cut Line= 4
      1904960.07     13952646.21      1904730.89     13952418.76
      1904578.11     13952385.78      1903940.93     13952392.72
#Sta/Elev= 30
  4568.5 1755.65  4665.5 1754.73  4679.5 1754.47  4728.5 1753.53  4800.2 1753.15
  4982.3 1749.47  4999.7 1747.59  5026.5 1749.01  5060.8 1748.80  5078.8 1747.07
  5079.0 1746.57  5082.5 1746.57  5082.8 1747.07  5100.8 1748.24  5150.8 1748.38
  5178.3 1747.77  5200.8 1749.38  5230.8 1754.20  5260.8 1756.01  5296.3 1756.76
  5360.8 1756.01  5390.8 1756.58  5400.8 1756.26  5440.8 1757.82  5470.8 1757.89
  5490.8 1758.96  5517.4 1759.17  5616.1 1760.77  5650.8 1761.57  5684.9 1763.47
#Mann=10,-1,0
  4568.5   0.035       0  4665.5   0.063       0  4679.5    0.07       0
  4800.2   0.035       0  5078.8   0.035       0  5082.8   0.035       0
  5178.3    0.07       0  5296.3   0.035       0  5517.4    0.07       0
  5616.1   0.035       0
Bank Sta=5078.8,5082.8
Exp/Cntr=0.3,0.1

Type RM Length L Ch R = 1,331,0,0,0
BEGIN DESCRIPTION:
Stream0468 0.3
END DESCRIPTION:
XS GIS Cut Line= 3
      1904963.47     13952500.75      1904561.16     13952168.75
      1903996.07     13952245.57
#Sta/Elev= 30
  4437.0 1754.09  4525.2 1754.17  4644.2 1752.13  4649.7 1752.07  4774.3 1748.52
  4971.2 1744.71  5004.5 1742.11  5024.7 1742.89  5049.9 1742.79  5071.1 1740.62
  5083.2 1742.68  5107.4 1743.25  5131.3 1739.98  5137.3 1739.80  5137.5 1739.30
  5141.0 1739.30  5141.3 1739.80  5161.9 1741.33  5177.6 1741.50  5210.3 1746.21
  5236.4 1750.86  5284.4 1754.34  5352.6 1757.32  5367.8 1755.91  5373.8 1757.19
  5385.9 1757.93  5437.4 1758.98  5511.4 1759.19  5516.3 1759.49  5528.9 1759.93
#Mann=11,-1,0
  4437.0   0.035       0  4525.2    0.07       0  4644.2   0.035       0
  4649.7    0.07       0  4774.3   0.035       0  5137.3   0.035       0
  5141.3   0.035       0  5236.4    0.07       0  5284.4   0.035       0
  5511.4    0.07       0  5516.3   0.035       0
Bank Sta=5137.3,5141.3
Exp/Cntr=0.3,0.1

Chan Stop Cuts=-1