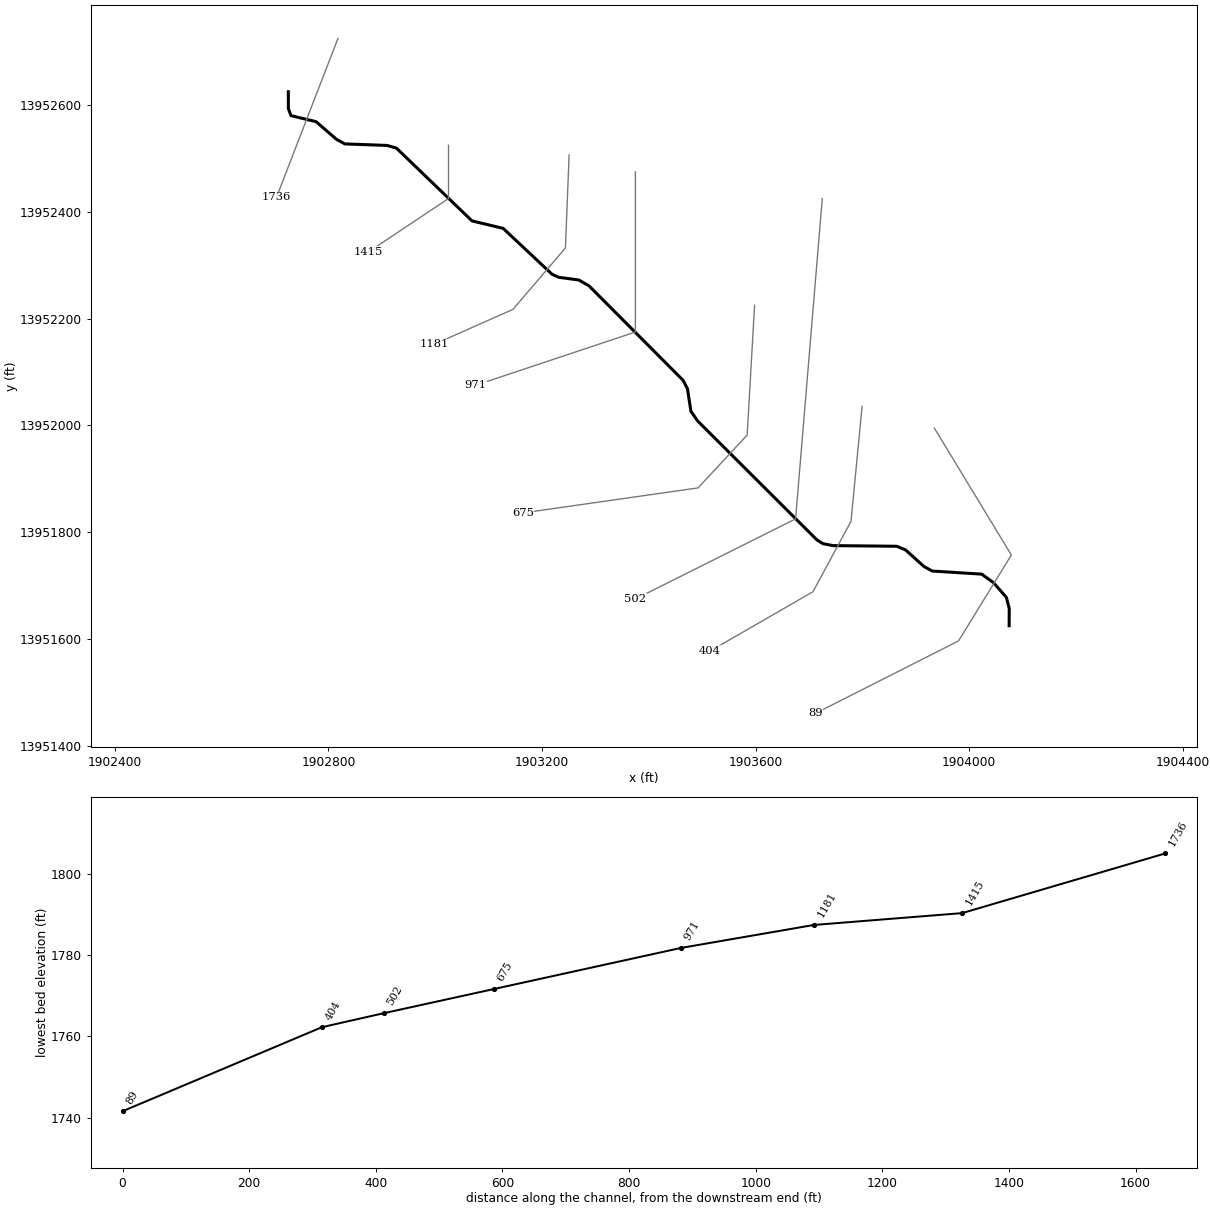
--- Stream0469.prj (project) ---

Proj Title=Stream0469 Base Level Engineering
Current Plan=p01
Default Exp/Contr=0.3,0.1
English Units
Geom File=g01
Flow File=f01
Plan File=p01
Y Axis Title=Elevation
X Axis Title(PF)=Main Channel Distance
X Axis Title(XS)=Station
BEGIN DESCRIPTION:
Stream0469
END DESCRIPTION:
DSS Export Rating Curves= 0
DSS Export Rating Curve Sorted= 0
DSS Export Volume Flow Curves= 0
DXF OffsetX= 0
DXF OffsetY= 0
DXF ScaleX= 1
DXF ScaleY= 10

--- Stream0469.p01 (plan) ---

Plan Title=Multiple Run
Short Identifier=Multiple
Geom File=g01
Flow File=f01
Subcritical Flow
K Sum by GR= 0
Std Step Tol= 0.01
Critical Tol= 0.01
Num of Std Step Trials= 20
Max Error Tol= 0.3
Flow Tol Ratio= 0.001
Split Flow NTrial= 30
Split Flow Tol= 0.02
Split Flow Ratio= 0.02
Log Output Level= 0
Friction Slope Method= 1
Unsteady Friction Slope Method= 2
Unsteady Bridges Friction Slope Method= 1
Parabolic Critical Depth
Global Vel Dist=  1 , 1 , 1
Global Log Level= 0
CheckData=True
Encroach Param= -1, 0, 0, 0
BEGIN DESCRIPTION:
Multiple Run
END DESCRIPTION:

--- Stream0469.f01 (steady flow) ---

Flow Title=Multiple
Program Version=4.10
Number of Profiles= 7
Profile Names=10-year,25-year,50-year,1pct_min,100-year,1pct_plu,500-year
River Rch & RM=Stream0469,Reach-1         ,1736
     395     636     854     558    1113    2220    1859
Boundary for River Rch & Prof#=Stream0469,Reach-1         , 1
Up Type= 0
Dn Type= 3
Dn Slope=0.015
Boundary for River Rch & Prof#=Stream0469,Reach-1         , 2
Up Type= 0
Dn Type= 3
Dn Slope=0.015
Boundary for River Rch & Prof#=Stream0469,Reach-1         , 3
Up Type= 0
Dn Type= 3
Dn Slope=0.015
Boundary for River Rch & Prof#=Stream0469,Reach-1         , 4
Up Type= 0
Dn Type= 3
Dn Slope=0.015
Boundary for River Rch & Prof#=Stream0469,Reach-1         , 5
Up Type= 0
Dn Type= 3
Dn Slope=0.015
Boundary for River Rch & Prof#=Stream0469,Reach-1         , 6
Up Type= 0
Dn Type= 3
Dn Slope=0.015
Boundary for River Rch & Prof#=Stream0469,Reach-1         , 7
Up Type= 0
Dn Type= 3
Dn Slope=0.015
DSS Import GetInterval= 0
DSS Import GetPeak= 0
DSS Import FillOption= 0

--- Stream0469.g01 (geometry) ---

Geom Title=Existing Conditions
Program Version=4.10

River Reach=Stream0469      ,Reach-1
Reach XY= 30
        1902725.       13952625.      1902725.06     13952593.44
       1902729.9     13952580.28        1902777.     13952568.96
      1902815.29     13952535.79      1902830.94     13952527.31
      1902909.78     13952524.48      1902927.43     13952519.48
      1903068.95     13952383.16      1903127.28     13952369.13
      1903218.96     13952283.18      1903231.05     13952277.54
      1903268.95     13952272.47      1903288.21     13952261.37
      1903464.22     13952084.68      1903472.47     13952068.95
      1903478.98     13952026.65      1903491.65     13952008.33
       1903715.2     13951785.48      1903726.47     13951778.54
      1903744.99     13951774.98      1903864.49     13951773.77
      1903881.06     13951766.86      1903915.37     13951735.89
      1903930.98     13951727.36       1904023.7     13951721.54
      1904045.55     13951705.69      1904069.87     13951677.94
      1904075.15     13951657.07        1904075.       13951625.

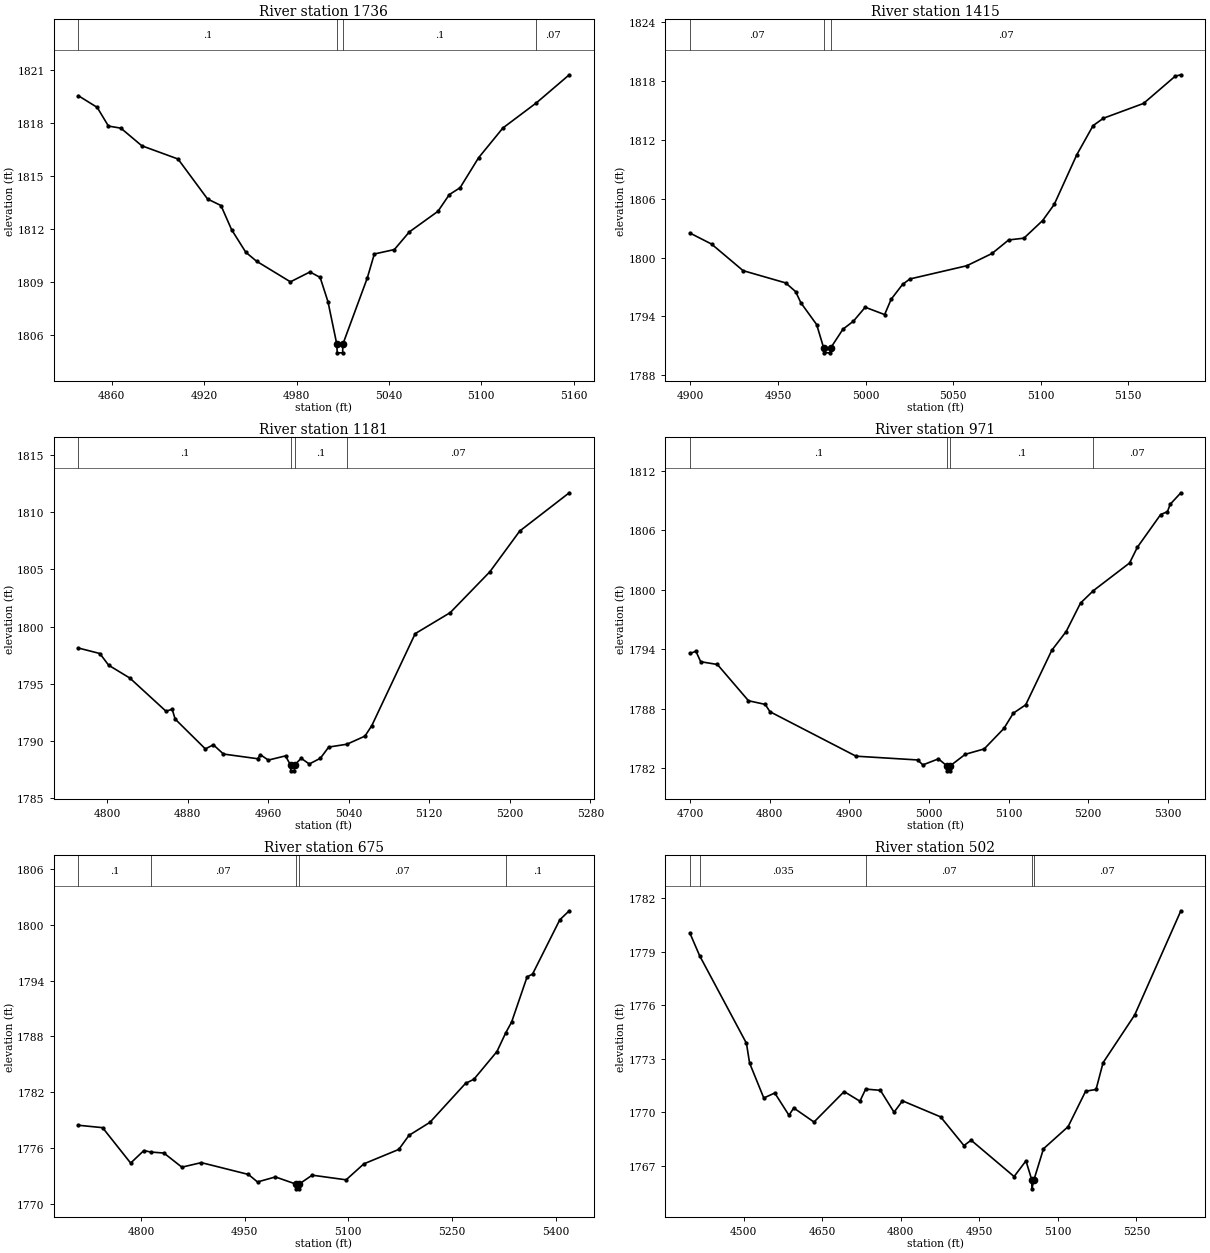
Type RM Length L Ch R = 1 ,1736    ,321,321,321
BEGIN DESCRIPTION:
Stream0469 4.0
END DESCRIPTION:
XS GIS Cut Line= 2
      1902817.98     13952725.05      1902702.96     13952427.73
#Sta/Elev= 30
  4838.3 1819.55  4850.5 1818.89  4857.8 1817.83  4865.9 1817.71  4879.5 1816.71
    4903 1815.96  4922.2 1813.69  4930.9 1813.32  4937.8 1811.95    4947 1810.67
    4954 1810.16    4976 1808.99  4988.7 1809.55  4995.3 1809.24  5000.4 1807.86
  5006.1 1805.46  5006.4 1804.96  5009.9 1804.96  5010.1 1805.46  5025.9  1809.2
  5030.5 1810.57  5043.5 1810.82  5053.2 1811.82  5071.8 1812.99  5079.2 1813.94
  5086.2 1814.33  5098.2 1816.03    5114 1817.72  5135.8 1819.15  5157.1 1820.74
#Mann= 4 ,-1 , 0
  4838.3      .1       0  5006.1     .05       0  5010.1      .1       0
  5135.8     .07       0
Bank Sta=5006.1,5010.1
XS Rating Curve= 0 ,0
Exp/Cntr=0.3,0.1

Type RM Length L Ch R = 1 ,1415    ,234,234,234
BEGIN DESCRIPTION:
Stream0469 3.0
END DESCRIPTION:
XS GIS Cut Line= 3
        1903025.     13952524.97        1903025.       13952425.
      1902875.04     13952325.03
#Sta/Elev= 30
  4899.8 1802.49  4912.1 1801.37  4930.1 1798.66  4954.4 1797.41  4960.1 1796.52
  4963.1 1795.38  4972.1 1793.16  4976.1 1790.78  4976.4 1790.28  4979.9 1790.28
  4980.1 1790.78  4987.1 1792.69  4993.1 1793.51  4999.8 1794.93  5010.9 1794.18
  5014.6 1795.74  5021.1 1797.25  5025.3 1797.81  5057.8 1799.16  5072.2 1800.41
  5081.7 1801.79  5090.4 1801.97  5101.1 1803.77  5107.7 1805.41  5120.6 1810.48
  5129.9 1813.45  5135.8  1814.2  5158.7 1815.71  5176.8 1818.49    5180 1818.63
#Mann= 3 ,-1 , 0
  4899.8     .07       0  4976.1     .05       0  4980.1     .07       0
Bank Sta=4976.1,4980.1
XS Rating Curve= 0 ,0
Exp/Cntr=0.3,0.1

Type RM Length L Ch R = 1 ,1181    ,210,210,210
BEGIN DESCRIPTION:
Mapping XS 4848cf75
END DESCRIPTION:
XS GIS Cut Line= 4
      1903250.87     13952506.68      1903243.94      13952332.4
      1903145.67     13952217.47      1902997.75     13952151.72
#Sta/Elev= 30
  4771.5 1798.12  4792.8 1797.64  4801.5 1796.62  4822.6 1795.49  4858.6 1792.58
  4864.6 1792.77  4867.6  1791.9  4897.6 1789.29  4905.5 1789.65  4915.6 1788.84
  4949.5 1788.43  4952.3 1788.78  4960.1 1788.31  4977.2 1788.68  4982.2 1787.87
  4982.4 1787.37  4985.9 1787.37  4986.2 1787.87  4992.7 1788.47  5000.8 1787.97
  5011.8 1788.47  5020.1 1789.45  5038.2  1789.7  5056.1 1790.41  5062.9 1791.33
    5106 1799.38  5140.8 1801.22  5180.2  1804.8  5209.8 1808.36    5259 1811.71
#Mann= 4 ,-1 , 0
  4771.5      .1       0  4982.2     .05       0  4986.2      .1       0
  5038.2     .07       0
Bank Sta=4982.2,4986.2
XS Rating Curve= 0 ,0
Exp/Cntr=0.3,0.1

Type RM Length L Ch R = 1 ,971     ,296,296,296
BEGIN DESCRIPTION:
Stream0469 2.0
END DESCRIPTION:
XS GIS Cut Line= 3
        1903375.     13952475.03        1903375.       13952175.
      1903074.96     13952074.99
#Sta/Elev= 30
    4700 1793.57  4707.4  1793.8  4713.4 1792.74  4734.4 1792.46  4773.4  1788.8
  4794.4 1788.43  4800.4 1787.69  4908.4  1783.2  4985.7 1782.82  4992.4 1782.32
  5011.9 1782.93  5022.6 1782.22  5022.8 1781.72  5026.3 1781.72  5026.6 1782.22
  5045.6 1783.39  5069.3 1783.93  5094.1    1786  5105.9 1787.54  5121.5 1788.39
  5154.2 1793.89  5172.3 1795.79  5190.3 1798.66  5206.5 1799.92  5251.9 1802.71
  5261.7  1804.3  5290.9  1807.6  5299.4 1807.89  5302.9 1808.64  5316.3  1809.8
#Mann= 4 ,-1 , 0
    4700      .1       0  5022.6     .05       0  5026.6      .1       0
  5206.5     .07       0
Bank Sta=5022.6,5026.6
XS Rating Curve= 0 ,0
Exp/Cntr=0.3,0.1

Type RM Length L Ch R = 1 ,675     ,173,173,173
BEGIN DESCRIPTION:
Stream0469 1.1
END DESCRIPTION:
XS GIS Cut Line= 4
      1903598.23     13952225.13      1903584.33     13951982.03
      1903492.32     13951883.07      1903164.17     13951836.19
#Sta/Elev= 30
  4709.5 1778.44  4744.5 1778.18  4785.1 1774.37  4804.2 1775.72    4814 1775.56
  4833.2 1775.45  4859.2 1773.93  4887.3 1774.42  4955.4 1773.15  4968.6 1772.34
  4994.5 1772.88  5024.6  1772.1  5024.8  1771.6  5028.3  1771.6  5028.6  1772.1
  5047.7 1773.07  5096.8 1772.57  5122.5 1774.29    5173 1775.84  5187.7 1777.35
    5218 1778.75  5269.5 1782.94  5281.7 1783.39    5315 1786.37  5327.5 1788.35
  5336.2 1789.54  5358.6  1794.4  5366.5  1794.7  5405.9 1800.54  5419.6 1801.51
#Mann= 5 ,-1 , 0
  4709.5      .1       0    4814     .07       0  5024.6     .05       0
  5028.6     .07       0  5327.5      .1       0
Bank Sta=5024.6,5028.6
XS Rating Curve= 0 ,0
Exp/Cntr=0.3,0.1

Type RM Length L Ch R = 1 ,502     ,98,98,98
BEGIN DESCRIPTION:
Stream0469 1.0
END DESCRIPTION:
XS GIS Cut Line= 3
        1903725.     13952425.05        1903675.       13951825.
      1903375.03     13951675.02
#Sta/Elev= 30
  4397.6 1780.03  4416.1 1778.77  4505.4 1773.86  4511.4 1772.75  4538.5 1770.79
  4559.5 1771.07  4586.6 1769.82  4595.7 1770.23  4634.4 1769.44    4692 1771.15
  4722.1 1770.61  4733.1 1771.29  4761.2 1771.22  4787.3 1769.99  4803.4 1770.63
  4876.2 1769.73  4920.8 1768.12  4934.5 1768.42  5016.6 1766.38  5039.2 1767.26
  5050.4 1766.19  5050.6 1765.69  5054.4 1766.19  5072.7 1767.94  5119.7 1769.18
  5153.2 1771.17  5173.1 1771.27  5186.5 1772.77  5246.9 1775.45  5335.1  1781.3
#Mann= 5 ,-1 , 0
  4397.6      .1       0  4416.1    .035       0  4733.1     .07       0
  5050.4     .05       0  5054.4     .07       0
Bank Sta=5050.4,5054.4
XS Rating Curve= 0 ,0
Exp/Cntr=0.3,0.1

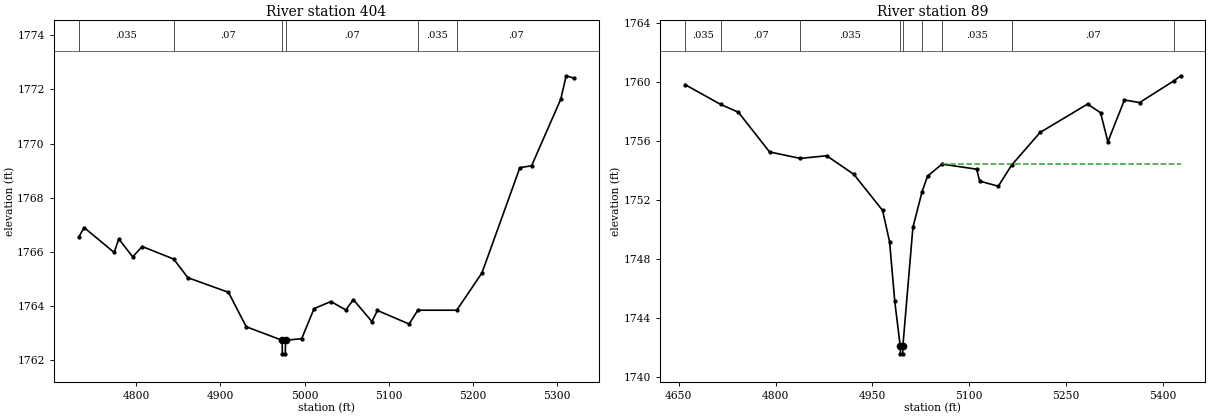
Type RM Length L Ch R = 1 ,404     ,315,315,315
BEGIN DESCRIPTION:
Stream0469 0.1
END DESCRIPTION:
XS GIS Cut Line= 4
      1903799.61     13952035.86      1903778.78     13951820.57
       1903707.6     13951688.62      1903514.85     13951577.49
#Sta/Elev= 30
  4731.5 1766.54    4738  1766.9  4773.7 1765.98  4779.2 1766.48  4795.7 1765.82
    4807  1766.2  4844.3 1765.74  4861.3 1765.05  4909.5 1764.51  4930.6 1763.24
  4973.3 1762.74  4973.5 1762.24    4977 1762.24  4977.3 1762.74  4996.5  1762.8
  5011.2 1763.91  5031.2 1764.17  5048.9 1763.86  5057.9 1764.24  5079.9 1763.43
  5086.5 1763.84  5124.1 1763.34  5134.5 1763.85  5180.7 1763.85  5210.7 1765.23
  5255.7 1769.11  5269.6 1769.18  5304.2 1771.63  5310.7  1772.5  5320.2 1772.41
#Mann= 6 ,-1 , 0
  4731.5    .035       0  4844.3     .07       0  4973.3     .05       0
  4977.3     .07       0  5134.5    .035       0  5180.7     .07       0
Bank Sta=4973.3,4977.3
XS Rating Curve= 0 ,0
Exp/Cntr=0.3,0.1

Type RM Length L Ch R = 1 ,89      ,0,0,0
BEGIN DESCRIPTION:
Stream0469 0.0
END DESCRIPTION:
XS GIS Cut Line= 4
      1903934.89     13951995.09      1904079.12     13951757.38
      1903980.21     13951596.49      1903712.11     13951460.78
#Sta/Elev= 30
    4660 1759.85  4715.3  1758.5  4742.4 1757.98  4790.8 1755.28  4838.3 1754.84
  4879.2 1755.02  4921.3 1753.76  4965.8 1751.31  4976.7 1749.17  4984.7 1745.13
  4993.2 1742.07  4993.5 1741.57    4997 1741.57  4997.2 1742.07  5012.8 1750.16
    5027 1752.58  5035.5 1753.64  5057.8 1754.45  5111.5 1754.11  5116.2  1753.3
    5145 1752.95  5165.6 1754.38  5209.7  1756.6  5283.3 1758.53  5303.4 1757.94
  5314.7 1755.97  5340.4 1758.81  5363.8 1758.63  5416.7  1760.1  5427.4 1760.45
#Mann= 9 ,-1 , 0
    4660    .035       0  4715.3     .07       0  4838.3    .035       0
  4993.2    .035       0  4997.2    .035       0    5027     .07       0
  5057.8    .035       0  5165.6     .07       0  5416.7    .035       0
#XS Ineff= 2 , 0
                         5058.01         1754.47
Permanent Ineff=
       F       F
Bank Sta=4993.2,4997.2
XS Rating Curve= 0 ,0
Exp/Cntr=0.3,0.1

Chan Stop Cuts=-1
Use User Specified Reach Order=0
Composite Channel Slope=5