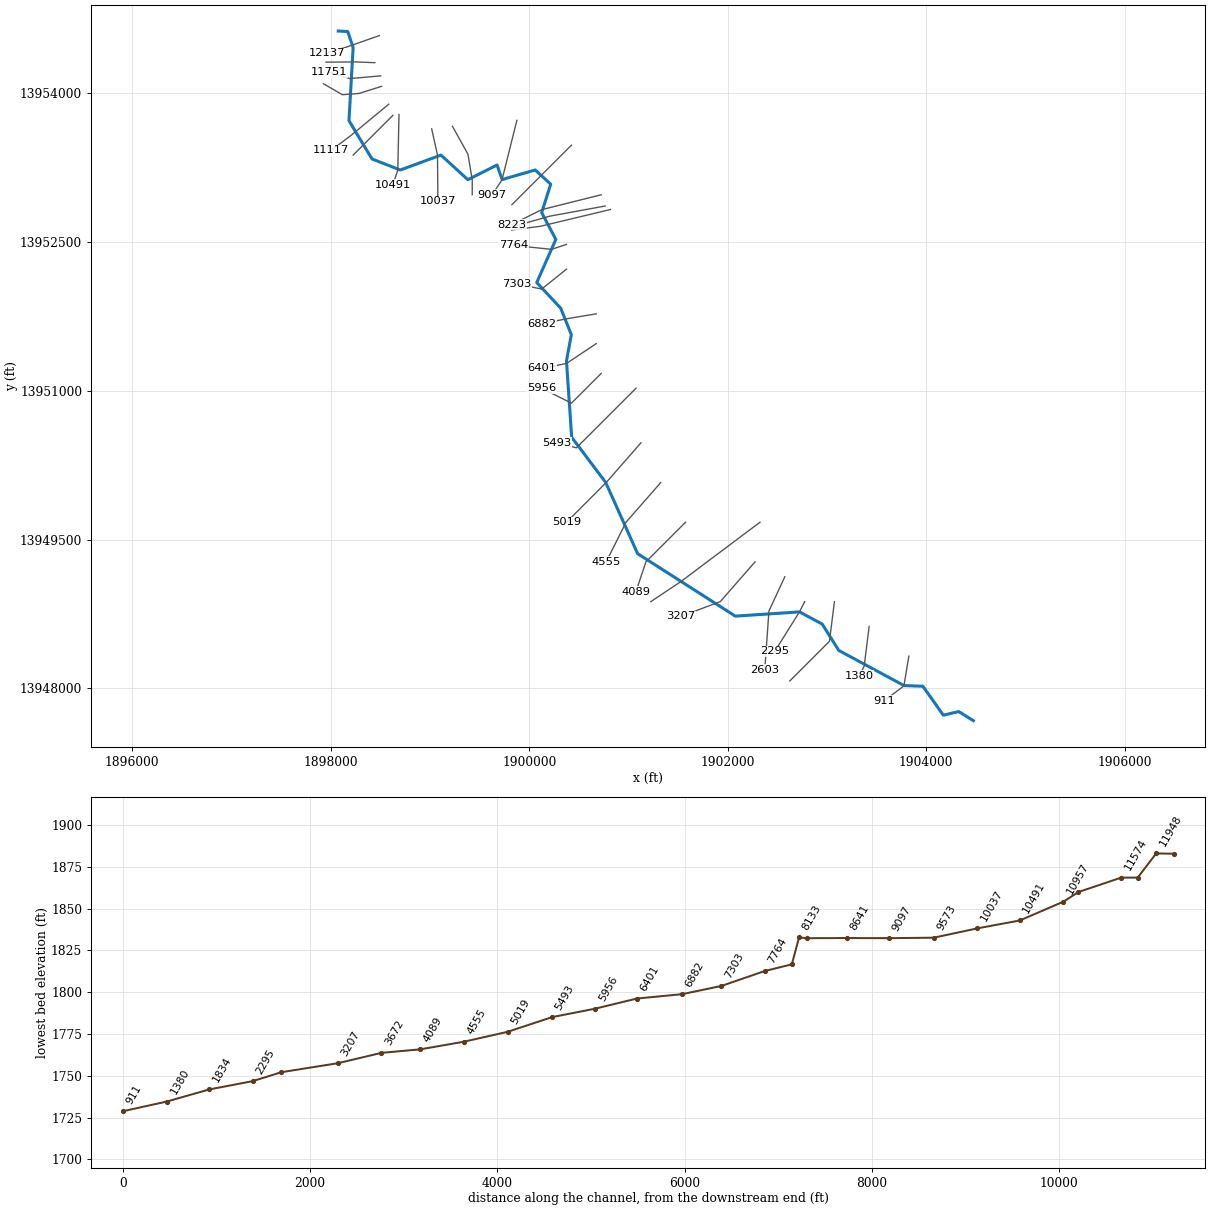
--- Stream0470.prj (project) ---

Proj Title=Stream0470 Base Level Engineering
Current Plan=p01
Default Exp/Contr=0.3,0.1
English Units
Geom File=g01
Flow File=f01
Plan File=p01
BEGIN DESCRIPTION:
Stream0470
END DESCRIPTION:

--- Stream0470.p01 (plan) ---

Plan Title=Multiple Run
Short Identifier=Multiple
Geom File=g01
Flow File=f01
Subcritical Flow
K Sum by GR= 0
Std Step Tol= 0.01
Critical Tol= 0.01
Num of Std Step Trials= 20
Max Error Tol= 0.3
Flow Tol Ratio= 0.001
Split Flow NTrial= 30
Split Flow Tol= 0.02
Split Flow Ratio= 0.02
Log Output Level= 0
Friction Slope Method= 1
Unsteady Friction Slope Method= 2
Unsteady Bridges Friction Slope Method= 1
Parabolic Critical Depth
Global Vel Dist=  1 , 1 , 1
Global Log Level= 0
CheckData=True
Encroach Param= -1, 0, 0, 0
BEGIN DESCRIPTION:
Multiple Run
END DESCRIPTION:

--- Stream0470.f01 (steady flow) ---

Flow Title=Multiple
Number of Profiles=7
Profile Names=10-year,25-year,50-year,1pct_min,100-year,1pct_plu,500-year
River Rch & RM= Stream0470,Reach-1,12137
     485     788    1065     698    1393    2780    2349
River Rch & RM= Stream0470,Reach-1,11117
     830    1399    1935    1297    2588    5163    4564
River Rch & RM= Stream0470,Reach-1,9097
    2236    3991    5734    3975    7930   15823   15000
River Rch & RM= Stream0470,Reach-1,5019
    2344    4184    6012    4165    8311   16582   15709
River Rch & RM= Stream0470,Reach-1,2603
    2570    4605    6632    4604    9187   18330   17433
Boundary for River Rch & Prof#=Stream0470,Reach-1,1
Up Type=0
Dn Type=3
Dn Slope=0.005
Boundary for River Rch & Prof#=Stream0470,Reach-1,2
Up Type=0
Dn Type=3
Dn Slope=0.005
Boundary for River Rch & Prof#=Stream0470,Reach-1,3
Up Type=0
Dn Type=3
Dn Slope=0.005
Boundary for River Rch & Prof#=Stream0470,Reach-1,4
Up Type=0
Dn Type=3
Dn Slope=0.005
Boundary for River Rch & Prof#=Stream0470,Reach-1,5
Up Type=0
Dn Type=3
Dn Slope=0.005
Boundary for River Rch & Prof#=Stream0470,Reach-1,6
Up Type=0
Dn Type=3
Dn Slope=0.005
Boundary for River Rch & Prof#=Stream0470,Reach-1,7
Up Type=0
Dn Type=3
Dn Slope=0.005

--- Stream0470.g01 (geometry) ---

Geom Title=Existing Conditions

River Reach=Stream0470,Reach-1
Reach XY= 30
      1898075.00     13954625.00      1898170.13     13954620.18
      1898224.91     13954459.61      1898182.80     13953721.66
      1898415.00     13953335.63      1898700.00     13953224.60
      1899109.78     13953374.76      1899380.88     13953126.96
      1899675.00     13953275.00      1899726.23     13953128.41
      1900059.78     13953224.76      1900215.87     13953081.74
      1900124.89     13952795.09      1900267.50     13952525.00
      1900075.07     13952090.39      1900316.98     13951831.34
      1900423.78     13951564.50      1900374.60     13951300.00
      1900427.24     13950530.93      1900769.17     13950077.30
      1901091.63     13949358.29      1902076.50     13948728.46
      1902723.45     13948771.25      1902951.89     13948648.74
      1903118.81     13948382.86      1903776.55     13948028.75
      1903966.72     13948021.94      1904172.57     13947730.40
      1904328.32     13947766.98      1904475.00     13947675.00

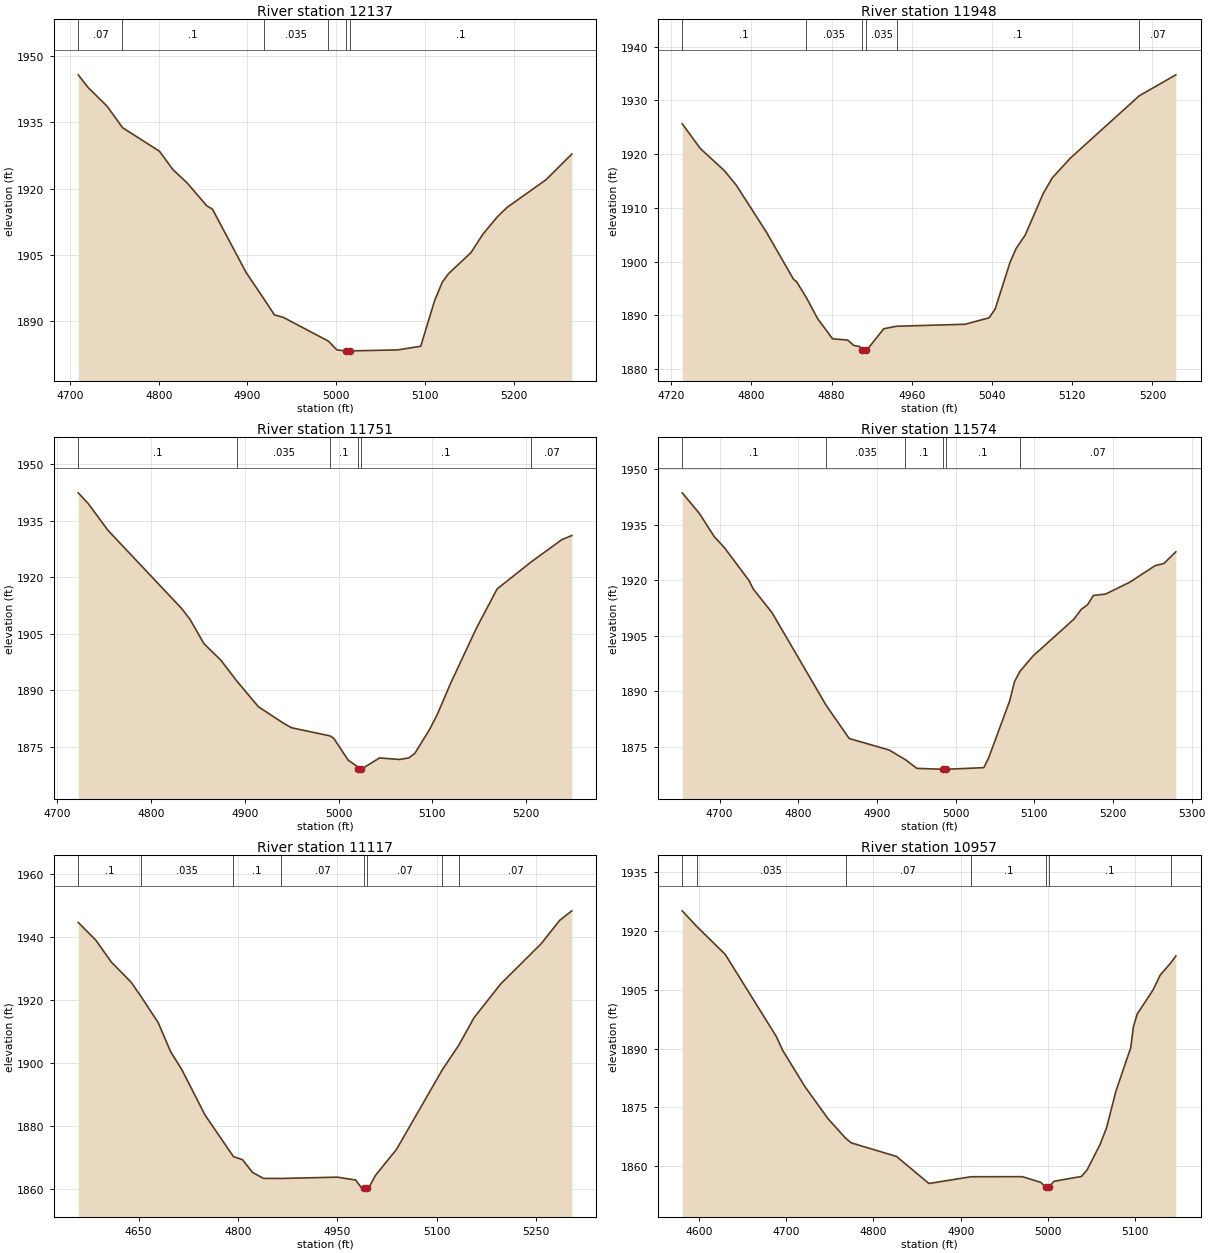
Type RM Length L Ch R = 1,12137,189,189,189
BEGIN DESCRIPTION:
Stream0470 29.0
END DESCRIPTION:
XS GIS Cut Line= 3
      1898489.83     13954579.41      1898174.77     13954468.75
      1897962.55     13954402.34
#Sta/Elev= 30
  4709.3 1945.70  4720.7 1942.77  4741.9 1938.60  4759.2 1933.76  4800.8 1928.44
  4816.1 1924.26  4832.0 1921.27  4854.2 1916.09  4860.6 1915.32  4898.7 1900.95
  4918.4 1895.10  4930.5 1891.42  4940.1 1890.90  4991.3 1885.49  5000.8 1883.51
  5011.2 1883.28  5011.5 1882.78  5015.0 1882.78  5015.2 1883.28  5069.5 1883.51
  5095.3 1884.34  5111.0 1894.66  5119.7 1898.86  5126.7 1900.76  5151.9 1905.49
  5165.2 1909.63  5182.0 1913.67  5192.7 1915.73  5236.7 1922.01  5265.6 1927.79
#Mann=6,-1,0
  4709.3    0.07       0  4759.2     0.1       0  4918.4   0.035       0
  4991.3     0.1       0  5011.2    0.05       0  5015.2     0.1       0
Bank Sta=5011.2,5015.2
Exp/Cntr=0.3,0.1

Type RM Length L Ch R = 1,11948,197,197,197
BEGIN DESCRIPTION:
Stream0470 28.0
END DESCRIPTION:
XS GIS Cut Line= 3
      1898443.02     13954305.98      1898247.69     13954313.80
      1897950.79     13954311.19
#Sta/Elev= 30
  4731.0 1925.65  4748.9 1921.07  4773.0 1916.93  4785.0 1914.20  4815.0 1905.48
  4842.0 1896.72  4845.0 1896.28  4854.7 1893.35  4866.0 1889.41  4881.0 1885.64
  4896.1 1885.41  4902.1 1884.41  4908.1 1884.19  4910.8 1883.48  4911.0 1882.98
  4914.5 1882.98  4914.8 1883.48  4932.1 1887.52  4944.9 1887.98  5013.1 1888.35
  5037.1 1889.55  5043.1 1891.15  5058.1 1899.91  5064.1 1902.45  5073.1 1904.92
  5091.1 1912.67  5100.1 1915.57  5118.1 1919.24  5186.9 1930.85  5223.4 1934.75
#Mann=6,-1,0
  4731.0     0.1       0  4854.7   0.035       0  4910.8    0.05       0
  4914.8   0.035       0  4944.9     0.1       0  5186.9    0.07       0
Bank Sta=4910.8,4914.8
Exp/Cntr=0.3,0.1

Type RM Length L Ch R = 1,11751,177,177,177
BEGIN DESCRIPTION:
Stream0470 26.0
END DESCRIPTION:
XS GIS Cut Line= 3
      1898501.59     13954173.17      1898191.70     13954145.83
      1897985.98     13954208.33
#Sta/Elev= 30
  4722.5 1942.34  4733.0 1939.55  4754.1 1932.42  4832.4 1911.75  4841.5 1908.85
  4856.5 1902.33  4874.6 1897.93  4891.9 1892.32  4914.5 1885.62  4940.8 1881.31
  4949.9 1880.03  4990.6 1877.89  4994.8 1877.26  5010.1 1871.48  5019.7 1869.80
  5020.2 1869.03  5020.4 1868.53  5024.2 1869.03  5043.6 1872.03  5065.0 1871.62
  5075.0 1872.05  5081.3 1873.25  5096.9 1879.53  5105.5 1883.72  5119.0 1891.60
  5147.1 1906.54  5169.0 1916.85  5205.3 1924.02  5238.0 1929.93  5248.6 1931.01
#Mann=6,-1,0
  4722.5     0.1       0  4891.9   0.035       0  4990.6     0.1       0
  5020.2    0.05       0  5024.2     0.1       0  5205.3    0.07       0
Bank Sta=5020.2,5024.2
Exp/Cntr=0.3,0.1

Type RM Length L Ch R = 1,11574,457,457,457
BEGIN DESCRIPTION:
Stream0470 25.0
END DESCRIPTION:
XS GIS Cut Line= 4
      1898512.00     13954067.70      1898284.15     13953996.09
      1898116.18     13953983.07      1897926.06     13954093.75
#Sta/Elev= 30
  4652.6 1943.56  4674.5 1937.97  4693.4 1931.71  4706.0 1928.83  4737.4 1919.92
  4742.8 1917.63  4766.7 1911.24  4835.5 1886.24  4864.8 1877.29  4915.6 1874.18
  4936.2 1871.58  4950.7 1869.24  4984.0 1868.99  4984.3 1868.49  4988.0 1868.99
  5035.9 1869.43  5041.9 1872.00  5068.8 1887.47  5074.8 1892.61  5081.8 1895.40
  5098.2 1899.51  5150.3 1909.47  5159.8 1912.15  5167.6 1913.34  5175.1 1915.88
  5190.5 1916.24  5221.2 1919.43  5253.6 1923.91  5264.8 1924.51  5279.9 1927.65
#Mann=6,-1,0
  4652.6     0.1       0  4835.5   0.035       0  4936.2     0.1       0
  4984.0    0.05       0  4988.0     0.1       0  5081.8    0.07       0
Bank Sta=4984,4988
Exp/Cntr=0.3,0.1

Type RM Length L Ch R = 1,11117,160,160,160
BEGIN DESCRIPTION:
Stream0470 23.1
END DESCRIPTION:
XS GIS Cut Line= 3
      1898583.56     13953887.45      1898207.10     13953576.06
      1898002.40     13953421.59
#Sta/Elev= 30
  4559.0 1944.70  4585.5 1939.06  4609.1 1932.06  4638.8 1925.69  4653.7 1921.16
  4679.7 1912.84  4698.5 1903.56  4715.5 1897.83  4750.3 1883.47  4793.3 1870.21
  4807.1 1869.21  4822.1 1865.19  4838.6 1863.29  4864.9 1863.26  4949.9 1863.68
  4977.6 1862.78  4986.1 1860.43  4990.5 1860.37  4990.8 1859.87  4994.5 1860.37
  4998.9 1860.80  5007.4 1864.18  5039.4 1872.51  5108.5 1897.81  5133.8 1905.78
  5156.3 1914.35  5196.2 1925.02  5257.8 1937.94  5285.8 1945.37  5304.0 1948.38
#Mann=8,-1,0
  4559.0     0.1       0  4653.7   0.035       0  4793.3     0.1       0
  4864.9    0.07       0  4990.5    0.05       0  4994.5    0.07       0
  5108.5     0.1       0  5133.8    0.07       0
Bank Sta=4990.5,4994.5
Exp/Cntr=0.3,0.1

Type RM Length L Ch R = 1,10957,466,466,466
BEGIN DESCRIPTION:
Stream0470 23.0
END DESCRIPTION:
XS GIS Cut Line= 3
      1898624.98     13953774.98      1898325.00     13953475.00
      1898224.97     13953374.97
#Sta/Elev= 30
  4580.8 1925.16  4597.2 1921.23  4630.1 1914.03  4688.5 1893.13  4696.0 1889.50
  4721.4 1880.29  4747.9 1872.08  4768.0 1867.12  4774.4 1865.93  4826.4 1862.45
  4863.5 1855.55  4911.7 1857.27  4970.6 1857.29  4991.9 1855.83  4997.2 1854.61
  4997.5 1854.11  5001.2 1854.61  5006.7 1856.10  5038.5 1857.36  5044.9 1859.06
  5059.7 1865.53  5067.1 1869.77  5077.8 1879.09  5094.8 1890.21  5097.9 1895.56
  5102.2 1898.81  5120.2 1904.89  5128.7 1908.79  5140.4 1911.78  5146.5 1913.62
#Mann=7,-1,0
  4580.8     0.1       0  4597.2   0.035       0  4768.0    0.07       0
  4911.7     0.1       0  4997.2    0.05       0  5001.2     0.1       0
  5140.4    0.07       0
Bank Sta=4997.2,5001.2
Exp/Cntr=0.3,0.1

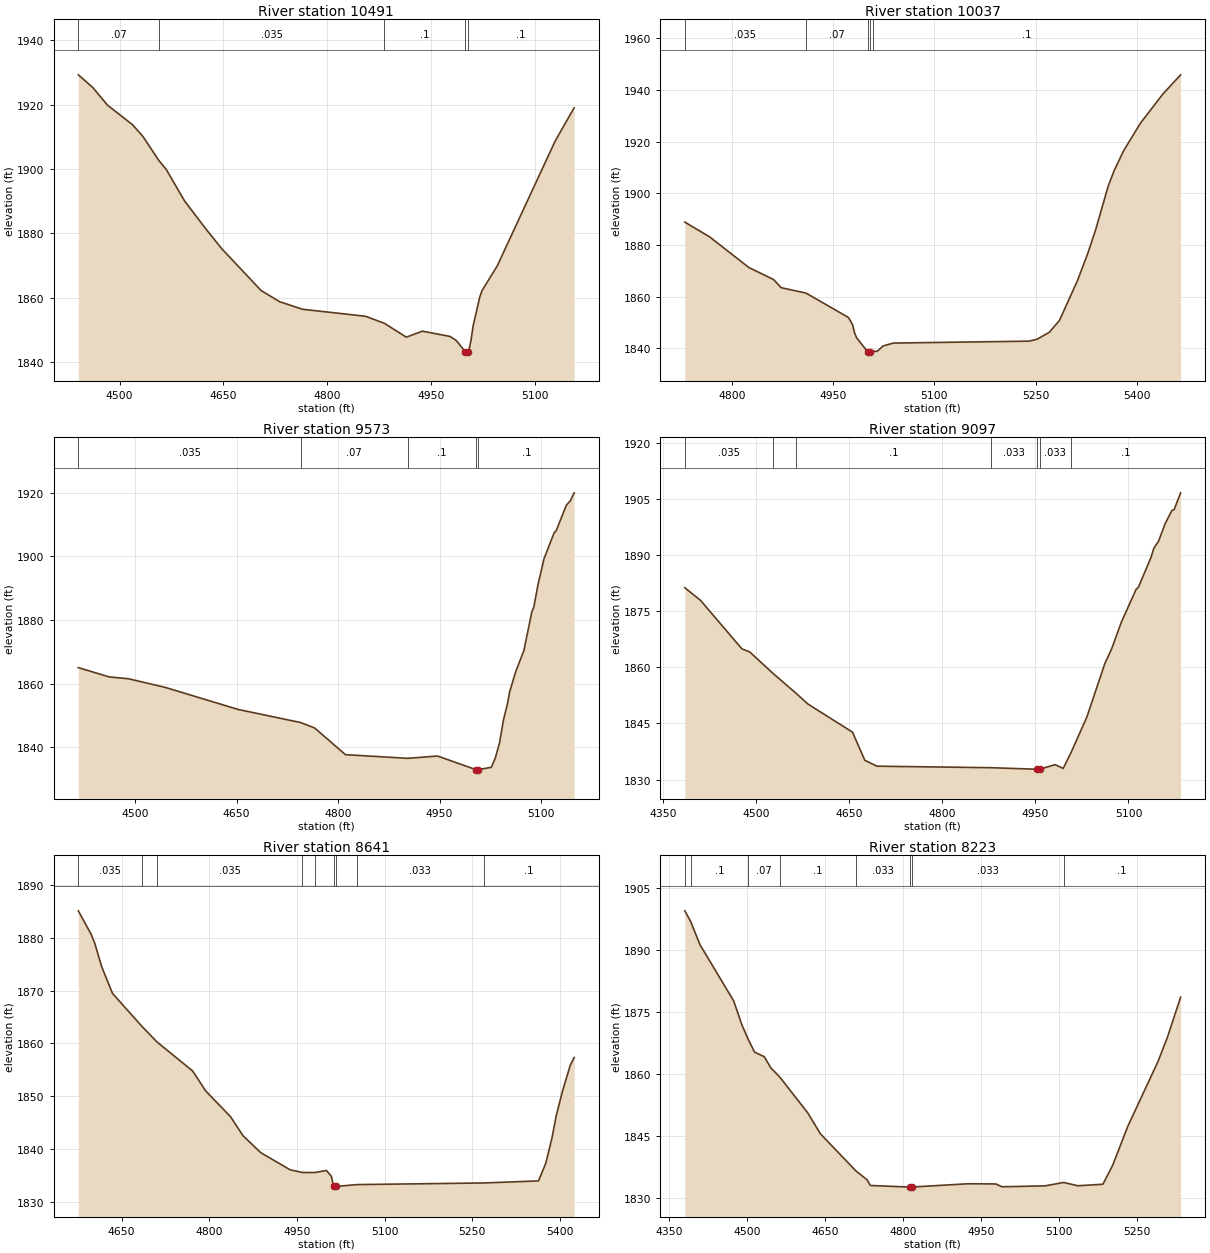
Type RM Length L Ch R = 1,10491,454,454,454
BEGIN DESCRIPTION:
Stream0470 22.0
END DESCRIPTION:
XS GIS Cut Line= 3
      1898686.87     13953783.71      1898675.00     13953225.00
      1898624.98     13953074.95
#Sta/Elev= 30
  4440.3 1929.24  4461.5 1925.23  4482.5 1919.82  4518.5 1913.78  4533.5 1910.18
  4556.7 1902.67  4567.6 1899.82  4594.0 1890.07  4623.5 1881.76  4647.5 1875.32
  4704.5 1862.31  4731.5 1858.81  4764.4 1856.48  4855.5 1854.30  4882.8 1852.13
  4914.6 1847.81  4937.8 1849.68  4977.6 1848.05  4986.6 1846.83  4999.7 1843.36
  5000.0 1842.86  5003.7 1843.36  5004.9 1843.54  5008.1 1846.76  5011.2 1851.29
  5020.7 1860.19  5023.9 1862.20  5046.0 1869.90  5129.9 1908.71  5157.3 1919.01
#Mann=5,-1,0
  4440.3    0.07       0  4556.7   0.035       0  4882.8     0.1       0
  4999.7    0.05       0  5003.7     0.1       0
Bank Sta=4999.7,5003.7
Exp/Cntr=0.3,0.1

Type RM Length L Ch R = 1,10037,464,464,464
BEGIN DESCRIPTION:
Stream0470 21.0
END DESCRIPTION:
XS GIS Cut Line= 3
      1899016.36     13953639.05      1899075.00     13953375.00
      1899078.94     13952911.10
#Sta/Elev= 30
  4730.4 1888.84  4766.8 1883.21  4825.2 1871.30  4862.0 1866.60  4873.1 1863.47
  4909.8 1861.40  4972.7 1851.97  4978.8 1849.23  4981.9 1845.95  4985.0 1844.06
  5001.3 1838.65  5001.6 1838.15  5005.3 1838.65  5009.7 1838.88  5015.3 1838.85
  5024.3 1840.95  5039.3 1842.04  5240.4 1842.78  5252.4 1843.54  5270.4 1846.25
  5285.4 1850.82  5312.4 1866.47  5327.4 1876.83  5339.4 1886.28  5357.4 1902.66
  5366.4 1908.83  5380.5 1916.51  5405.4 1927.16  5438.4 1938.36  5464.8 1945.83
#Mann=5,-1,0
  4730.4   0.035       0  4909.8    0.07       0  5001.3    0.05       0
  5005.3    0.07       0  5009.7     0.1       0
Bank Sta=5001.3,5005.3
Exp/Cntr=0.3,0.1

Type RM Length L Ch R = 1,9573,476,476,476
BEGIN DESCRIPTION:
Stream0470 20.0
END DESCRIPTION:
XS GIS Cut Line= 4
      1899225.89     13953664.18      1899381.80     13953384.22
      1899425.00     13953125.00      1899425.00     13952975.04
#Sta/Elev= 30
  4415.9 1865.07  4461.3 1862.16  4490.3 1861.56  4544.4 1858.86  4652.1 1851.94
  4744.7 1847.82  4765.3 1846.13  4810.9 1837.74  4902.7 1836.59  4947.1 1837.31
  5003.5 1833.07  5003.7 1832.57  5007.5 1833.07  5026.5 1833.75  5032.5 1836.69
  5038.5 1841.25  5044.5 1848.53  5050.8 1854.05  5053.5 1857.28  5062.5 1863.70
  5074.8 1870.47  5086.5 1882.56  5089.5 1884.14  5095.5 1890.98  5104.5 1899.23
  5119.5 1907.38  5122.5 1908.03  5137.5 1916.03  5143.5 1917.46  5149.1 1919.94
#Mann=5,-1,0
  4415.9   0.035       0  4744.7    0.07       0  4902.7     0.1       0
  5003.5    0.05       0  5007.5     0.1       0
Bank Sta=5003.5,5007.5
Exp/Cntr=0.3,0.1

Type RM Length L Ch R = 1,9097,456,456,456
BEGIN DESCRIPTION:
Stream0470 19.0
END DESCRIPTION:
XS GIS Cut Line= 3
      1899875.00     13953725.02      1899725.00     13953125.00
      1899624.98     13952974.97
#Sta/Elev= 30
  4385.2 1881.25  4410.5 1877.88  4477.3 1864.91  4489.6 1864.13  4527.2 1858.39
  4565.1 1852.96  4583.6 1850.19  4655.4 1842.68  4675.2 1835.17  4694.8 1833.59
  4878.1 1833.19  4952.7 1832.77  4953.0 1832.27  4956.7 1832.77  4981.9 1834.01
  4994.8 1832.98  5007.7 1837.32  5032.9 1846.70  5061.8 1860.94  5073.4 1865.16
  5088.5 1872.04  5112.3 1880.82  5115.9 1881.35  5136.1 1889.26  5141.1 1891.89
  5148.3 1893.62  5159.1 1898.38  5169.9 1901.85  5173.6 1902.13  5184.0 1906.59
#Mann=7,-1,0
  4385.2   0.035       0  4527.2    0.07       0  4565.1     0.1       0
  4878.1   0.033       0  4952.7   0.033       0  4956.7   0.033       0
  5007.7     0.1       0
Bank Sta=4952.7,4956.7
Exp/Cntr=0.3,0.1

Type RM Length L Ch R = 1,8641,418,418,418
BEGIN DESCRIPTION:
Stream0470 18.0
END DESCRIPTION:
XS GIS Cut Line= 3
      1900425.01     13953475.01      1900125.00     13953175.00
      1899825.03     13952875.03
#Sta/Elev= 30
  4576.0 1885.17  4597.7 1880.77  4604.0 1879.05  4616.0 1874.56  4634.5 1869.50
  4685.4 1863.18  4710.6 1860.29  4771.6 1854.78  4794.2 1850.96  4836.6 1846.09
  4857.8 1842.50  4888.3 1839.27  4938.4 1836.03  4959.4 1835.52  4980.8 1835.51
  5000.7 1835.90  5009.2 1834.75  5012.8 1832.86  5013.1 1832.36  5016.6 1832.36
  5016.8 1832.86  5052.3 1833.22  5270.2 1833.53  5363.5 1833.92  5376.2 1837.35
  5386.8 1842.20  5393.9 1846.33  5405.1 1851.18  5417.9 1855.88  5424.5 1857.33
#Mann=9,-1,0
  4576.0   0.035       0  4685.4    0.07       0  4710.6   0.035       0
  4959.4     0.1       0  4980.8    0.07       0  5012.8    0.05       0
  5016.8    0.07       0  5052.3   0.033       0  5270.2     0.1       0
Bank Sta=5012.8,5016.8
Exp/Cntr=0.3,0.1

Type RM Length L Ch R = 1,8223,90,90,90
BEGIN DESCRIPTION:
Stream0470 17.0
END DESCRIPTION:
XS GIS Cut Line= 3
      1900725.04     13952975.01      1900125.00     13952825.00
      1899825.02     13952675.01
#Sta/Elev= 30
  4380.6 1899.46  4391.9 1896.88  4409.8 1891.29  4474.7 1877.70  4490.2 1872.01
  4502.9 1868.36  4514.9 1865.32  4533.5 1864.25  4545.9 1861.57  4563.2 1859.34
  4617.0 1850.70  4641.7 1845.59  4710.3 1836.60  4731.4 1834.51  4737.6 1833.14
  4813.0 1832.76  4813.2 1832.26  4817.0 1832.76  4926.2 1833.56  4978.8 1833.51
  4991.1 1832.83  5073.7 1833.05  5109.6 1833.87  5136.7 1833.07  5185.0 1833.44
  5203.8 1838.03  5232.9 1847.44  5291.0 1863.08  5309.1 1868.94  5334.5 1878.60
#Mann=8,-1,0
  4380.6    0.07       0  4391.9     0.1       0  4502.9    0.07       0
  4563.2     0.1       0  4710.3   0.033       0  4813.0   0.033       0
  4817.0   0.033       0  5109.6     0.1       0
Bank Sta=4813,4817
Exp/Cntr=0.3,0.1

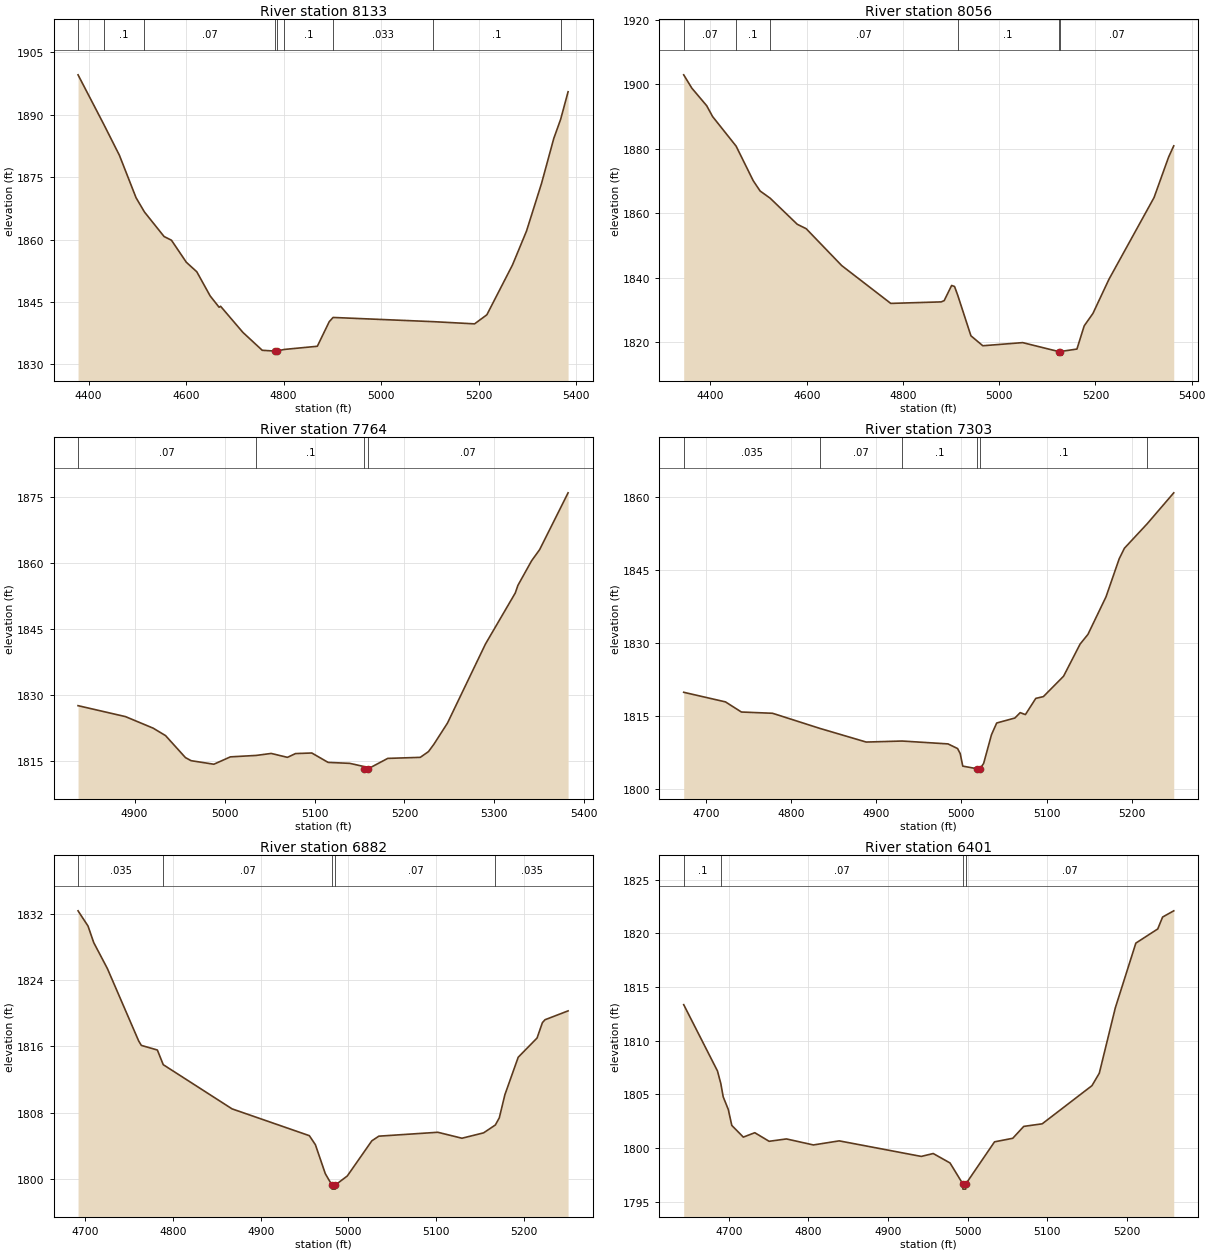
Type RM Length L Ch R = 1,8133,77,77,77
BEGIN DESCRIPTION:
Mapping XS a3f61fd4
END DESCRIPTION:
XS GIS Cut Line= 3
      1900765.12     13952861.69      1900206.41     13952759.21
      1899786.52     13952640.07
#Sta/Elev= 30
  4378.5 1899.62  4431.7 1887.61  4463.3 1880.27  4497.4 1870.07  4514.6 1866.64
  4554.8 1860.74  4570.0 1859.84  4600.5 1854.54  4621.9 1852.26  4649.3 1846.45
  4667.6 1843.73  4670.7 1843.96  4716.4 1837.68  4756.1 1833.37  4781.3 1833.19
  4781.5 1832.69  4785.3 1833.19  4801.6 1833.58  4869.0 1834.34  4893.4 1840.25
  4901.3 1841.27  5106.3 1840.26  5191.3 1839.73  5216.5 1841.91  5269.0 1853.89
  5297.6 1861.99  5328.7 1873.56  5353.7 1884.33  5367.8 1888.94  5383.0 1895.55
#Mann=9,-1,0
  4378.5    0.07       0  4431.7     0.1       0  4514.6    0.07       0
  4781.3   0.033       0  4785.3    0.07       0  4801.6     0.1       0
  4901.3   0.033       0  5106.3     0.1       0  5367.8    0.07       0
Bank Sta=4781.3,4785.3
Exp/Cntr=0.3,0.1

Type RM Length L Ch R = 1,8056,292,292,292
BEGIN DESCRIPTION:
Mapping XS 8f471973
END DESCRIPTION:
XS GIS Cut Line= 3
      1900818.19     13952826.40      1900108.08     13952656.41
      1899822.13     13952620.30
#Sta/Elev= 30
  4344.4 1902.99  4361.3 1898.86  4392.2 1893.40  4404.5 1890.03  4453.3 1880.87
  4488.9 1870.13  4503.2 1866.94  4524.2 1864.69  4580.4 1856.61  4598.9 1855.25
  4672.9 1843.78  4774.7 1832.06  4879.6 1832.53  4885.7 1832.92  4901.2 1837.63
  4907.3 1837.30  4914.0 1834.54  4941.3 1822.01  4966.0 1818.92  5048.9 1819.89
  5123.3 1817.13  5123.6 1816.63  5127.3 1817.13  5161.6 1817.89  5176.7 1825.09
  5194.9 1828.96  5228.1 1839.53  5321.9 1864.92  5352.1 1877.46  5362.8 1880.95
#Mann=6,-1,0
  4344.4    0.07       0  4453.3     0.1       0  4524.2    0.07       0
  4914.0     0.1       0  5123.3    0.05       0  5127.3    0.07       0
Bank Sta=5123.3,5127.3
Exp/Cntr=0.3,0.1

Type RM Length L Ch R = 1,7764,461,461,461
BEGIN DESCRIPTION:
Stream0470 16.0
END DESCRIPTION:
XS GIS Cut Line= 3
      1900374.99     13952475.00      1900225.00     13952425.00
      1899840.30     13952464.33
#Sta/Elev= 30
  4837.1 1827.49  4889.8 1825.00  4920.6 1822.37  4934.4 1820.67  4956.5 1815.66
  4962.8 1814.96  4988.1 1814.15  5006.5 1815.83  5035.4 1816.16  5051.8 1816.61
  5069.9 1815.72  5078.9 1816.58  5097.0 1816.71  5115.1 1814.57  5139.2 1814.35
  5154.3 1813.66  5155.3 1813.08  5155.6 1812.58  5159.3 1813.08  5181.4 1815.48
  5217.6 1815.72  5226.7 1817.03  5232.7 1818.70  5247.8 1823.52  5290.0 1841.52
  5323.2 1853.17  5326.1 1854.89  5341.3 1860.49  5350.3 1863.05  5381.9 1875.98
#Mann=4,-1,0
  4837.1    0.07       0  5035.4     0.1       0  5155.3    0.05       0
  5159.3    0.07       0
Bank Sta=5155.3,5159.3
Exp/Cntr=0.3,0.1

Type RM Length L Ch R = 1,7303,421,421,421
BEGIN DESCRIPTION:
Stream0470 15.0
END DESCRIPTION:
XS GIS Cut Line= 3
      1900374.98     13952224.98      1900125.00     13952025.00
      1899874.98     13952075.00
#Sta/Elev= 30
  4674.1 1819.87  4723.1 1817.90  4741.8 1815.82  4778.4 1815.56  4833.8 1812.46
  4888.3 1809.65  4930.4 1809.86  4984.3 1809.27  4995.5 1808.32  4998.6 1807.29
  5001.6 1804.71  5018.0 1804.18  5018.3 1803.68  5022.0 1804.18  5026.1 1805.27
  5035.3 1811.16  5041.4 1813.56  5062.8 1814.59  5069.0 1815.69  5075.1 1815.29
  5087.3 1818.62  5096.2 1818.98  5119.9 1823.17  5139.3 1829.77  5148.5 1831.76
  5169.7 1839.47  5185.2 1847.29  5191.3 1849.45  5218.2 1854.51  5249.2 1860.83
#Mann=6,-1,0
  4674.1   0.035       0  4833.8    0.07       0  4930.4     0.1       0
  5018.0    0.05       0  5022.0     0.1       0  5218.2    0.07       0
Bank Sta=5018,5022
Exp/Cntr=0.3,0.1

Type RM Length L Ch R = 1,6882,481,481,481
BEGIN DESCRIPTION:
Stream0470 14.0
END DESCRIPTION:
XS GIS Cut Line= 3
      1900674.98     13951775.00      1900375.00     13951725.00
      1900124.97     13951674.99
#Sta/Elev= 30
  4691.6 1832.39  4703.0 1830.55  4709.5 1828.55  4725.1 1825.41  4760.8 1816.66
  4763.8 1816.13  4782.1 1815.57  4788.8 1813.80  4867.3 1808.46  4955.5 1805.22
  4962.4 1804.13  4973.7 1800.63  4981.2 1799.26  4981.5 1798.76  4985.0 1798.76
  4985.2 1799.26  4998.8 1800.35  5026.8 1804.60  5034.8 1805.16  5102.1 1805.63
  5129.6 1804.91  5154.3 1805.56  5167.7 1806.51  5172.2 1807.37  5178.6 1810.17
  5193.8 1814.70  5215.3 1817.02  5221.4 1818.88  5224.4 1819.23  5250.7 1820.30
#Mann=5,-1,0
  4691.6   0.035       0  4788.8    0.07       0  4981.2    0.05       0
  4985.2    0.07       0  5167.7   0.035       0
Bank Sta=4981.2,4985.2
Exp/Cntr=0.3,0.1

Type RM Length L Ch R = 1,6401,445,445,445
BEGIN DESCRIPTION:
Stream0470 13.0
END DESCRIPTION:
XS GIS Cut Line= 3
      1900675.02     13951475.01      1900375.00     13951275.00
      1900125.02     13951225.00
#Sta/Elev= 30
  4643.3 1813.36  4685.7 1807.18  4689.9 1806.01  4692.9 1804.77  4699.3 1803.59
  4703.7 1802.10  4718.2 1801.01  4732.6 1801.42  4750.6 1800.62  4772.3 1800.84
  4806.2 1800.28  4838.6 1800.66  4941.7 1799.21  4956.7 1799.48  4977.8 1798.60
  4993.8 1796.66  4994.0 1796.16  4997.5 1796.16  4997.8 1796.66  5033.7 1800.57
  5056.6 1800.90  5070.4 1802.01  5093.6 1802.25  5156.1 1805.81  5165.3 1806.97
  5185.4 1813.06  5211.2 1819.10  5238.7 1820.42  5244.8 1821.53  5258.8 1822.11
#Mann=4,-1,0
  4643.3     0.1       0  4689.9    0.07       0  4993.8    0.05       0
  4997.8    0.07       0
Bank Sta=4993.8,4997.8
Exp/Cntr=0.3,0.1

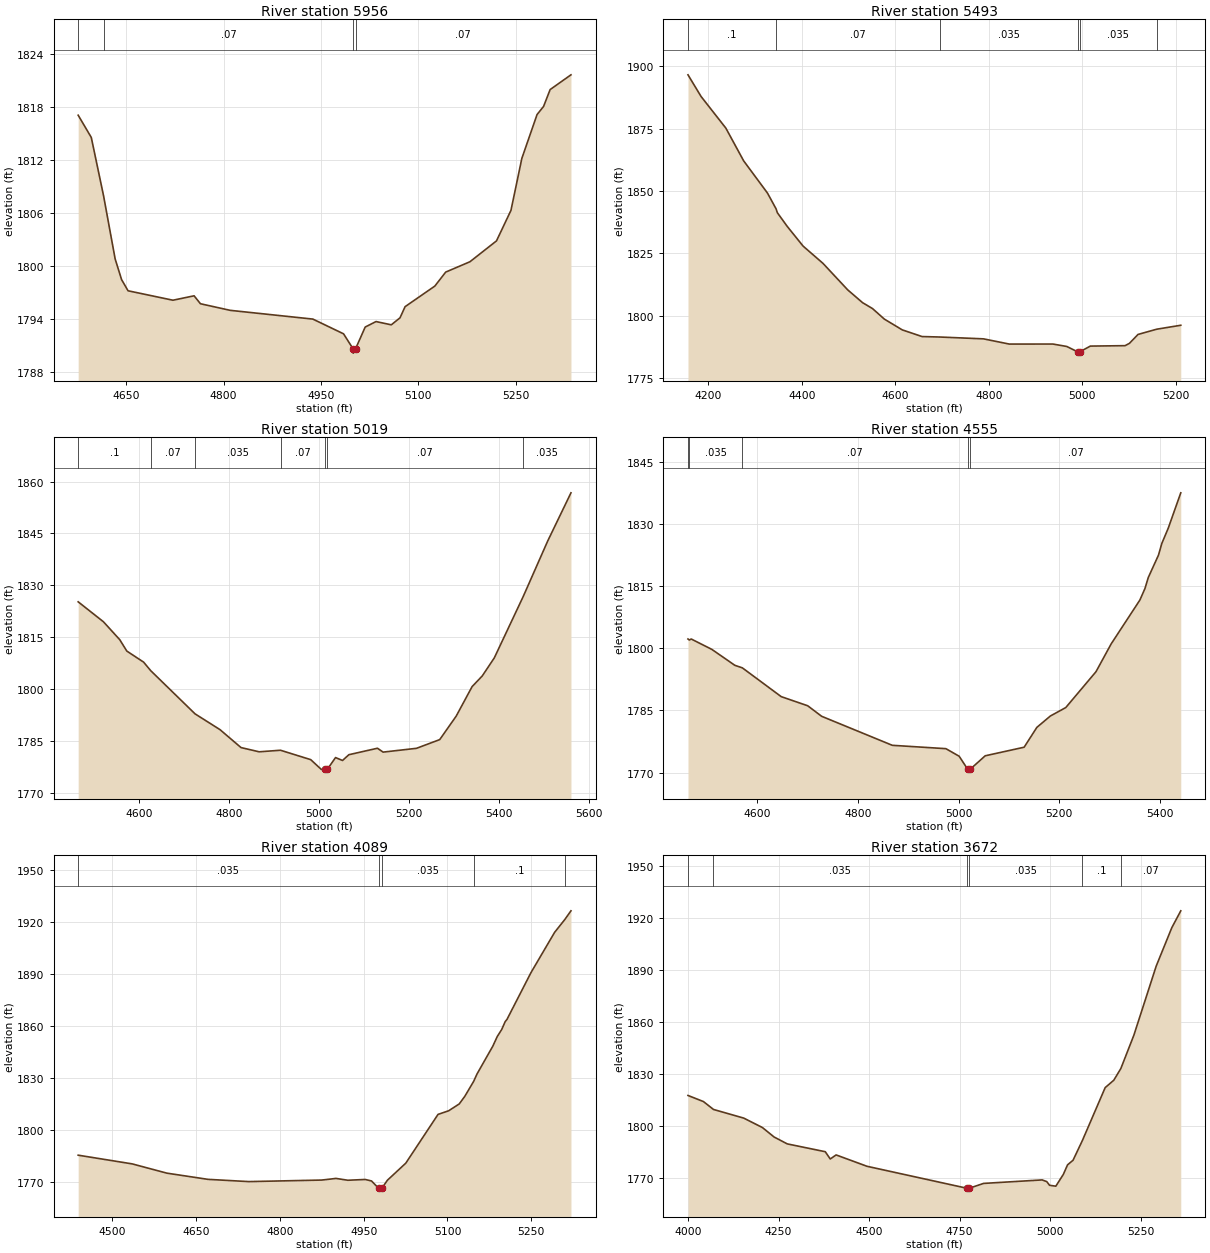
Type RM Length L Ch R = 1,5956,463,463,463
BEGIN DESCRIPTION:
Stream0470 12.0
END DESCRIPTION:
XS GIS Cut Line= 3
      1900725.00     13951175.00      1900425.00     13950875.00
      1900124.98     13951025.01
#Sta/Elev= 30
  4575.7 1817.09  4595.9 1814.57  4614.9 1807.93  4632.7 1800.79  4642.6 1798.45
  4652.6 1797.18  4721.8 1796.11  4754.4 1796.61  4764.2 1795.71  4810.2 1794.96
  4937.5 1793.97  4984.8 1792.30  4999.4 1790.61  4999.7 1790.11  5003.4 1790.61
  5018.2 1793.07  5034.9 1793.69  5058.4 1793.32  5071.8 1794.11  5079.7 1795.38
  5125.5 1797.71  5142.3 1799.30  5179.6 1800.47  5220.6 1802.84  5242.9 1806.30
  5259.7 1812.20  5283.1 1817.16  5293.2 1818.09  5303.3 1820.00  5335.4 1821.67
#Mann=4,-1,0
  4575.7     0.1       0  4614.9    0.07       0  4999.4    0.05       0
  5003.4    0.07       0
Bank Sta=4999.4,5003.4
Exp/Cntr=0.3,0.1

Type RM Length L Ch R = 1,5493,474,474,474
BEGIN DESCRIPTION:
Stream0470 11.0
END DESCRIPTION:
XS GIS Cut Line= 3
      1901074.98     13951024.98      1900475.00     13950425.00
      1900274.96     13950475.01
#Sta/Elev= 30
  4156.4 1896.58  4184.4 1887.90  4237.4 1875.23  4275.6 1862.08  4326.5 1849.19
  4344.9 1842.87  4347.7 1841.30  4368.9 1835.80  4402.8 1827.92  4445.3 1821.01
  4498.3 1810.37  4530.1 1805.24  4551.3 1802.89  4576.8 1798.64  4615.0 1794.34
  4657.4 1791.66  4694.9 1791.48  4788.9 1790.74  4844.1 1788.65  4937.4 1788.66
  4967.1 1787.69  4990.6 1785.52  4990.8 1785.02  4994.6 1785.52  5017.6 1787.84
  5091.8 1788.01  5101.1 1788.92  5119.6 1792.51  5159.6 1794.61  5211.1 1796.19
#Mann=6,-1,0
  4156.4     0.1       0  4344.9    0.07       0  4694.9   0.035       0
  4990.6   0.035       0  4994.6   0.035       0  5159.6    0.07       0
Bank Sta=4990.6,4994.6
Exp/Cntr=0.3,0.1

Type RM Length L Ch R = 1,5019,464,464,464
BEGIN DESCRIPTION:
Stream0470 10.0
END DESCRIPTION:
XS GIS Cut Line= 3
      1901125.01     13950475.02      1900775.00     13950075.00
      1900375.01     13949675.01
#Sta/Elev= 30
  4463.7 1825.22  4520.1 1819.43  4556.3 1814.26  4572.0 1810.97  4609.4 1807.77
  4625.3 1805.29  4723.9 1792.81  4779.5 1788.24  4826.3 1783.05  4866.7 1781.83
  4914.2 1782.28  4981.5 1779.56  5004.9 1776.75  5012.6 1776.74  5013.1 1776.24
  5018.3 1776.74  5036.7 1780.16  5052.3 1779.32  5066.4 1780.99  5130.0 1782.86
  5142.7 1781.74  5217.0 1782.84  5268.7 1785.36  5305.3 1792.14  5340.8 1800.69
  5363.4 1803.78  5390.2 1809.00  5454.4 1826.70  5509.0 1842.78  5560.9 1856.75
#Mann=7,-1,0
  4463.7     0.1       0  4625.3    0.07       0  4723.9   0.035       0
  4914.2    0.07       0  5012.6    0.05       0  5018.3    0.07       0
  5454.4   0.035       0
Bank Sta=5012.6,5018.3
Exp/Cntr=0.3,0.1

Type RM Length L Ch R = 1,4555,466,466,466
BEGIN DESCRIPTION:
Stream0470 9.0
END DESCRIPTION:
XS GIS Cut Line= 3
      1901324.99     13950074.99      1900975.00     13949675.00
      1900775.00     13949275.01
#Sta/Elev= 30
  4462.7 1802.25  4465.2 1802.01  4469.2 1802.24  4510.2 1799.73  4555.7 1795.90
  4570.7 1795.28  4647.8 1788.34  4700.5 1786.13  4728.2 1783.59  4868.5 1776.59
  4974.9 1775.78  5001.3 1773.95  5017.9 1770.86  5018.3 1770.36  5023.1 1770.36
  5023.6 1770.86  5053.0 1774.06  5130.3 1776.13  5155.6 1780.92  5182.4 1783.66
  5213.0 1785.70  5273.0 1794.35  5303.2 1801.07  5360.2 1811.65  5370.2 1814.41
  5376.9 1817.09  5397.1 1822.48  5403.8 1825.32  5416.5 1828.98  5441.4 1837.52
#Mann=5,-1,0
  4462.7    0.07       0  4465.2   0.035       0  4570.7    0.07       0
  5017.9    0.05       0  5023.6    0.07       0
Bank Sta=5017.9,5023.6
Exp/Cntr=0.3,0.1

Type RM Length L Ch R = 1,4089,417,417,417
BEGIN DESCRIPTION:
Stream0470 8.0
END DESCRIPTION:
XS GIS Cut Line= 3
      1901574.98     13949674.98      1901175.00     13949275.00
      1901075.00     13948974.99
#Sta/Elev= 30
  4439.1 1785.42  4535.6 1780.40  4597.9 1775.03  4671.4 1771.45  4744.3 1770.15
  4875.1 1771.04  4900.5 1771.99  4921.7 1770.93  4952.9 1771.38  4964.1 1770.50
  4976.8 1766.30  4977.3 1765.80  4982.6 1766.30  4992.5 1770.94  5025.4 1780.81
  5083.1 1809.00  5102.1 1811.08  5121.1 1815.06  5131.0 1819.43  5146.9 1828.12
  5152.7 1832.25  5181.2 1848.48  5189.1 1854.01  5197.0 1858.04  5203.3 1862.64
  5206.5 1863.91  5249.5 1890.99  5291.8 1914.25  5310.0 1921.64  5321.0 1926.66
#Mann=5,-1,0
  4439.1   0.035       0  4976.8   0.035       0  4982.6   0.035       0
  5146.9     0.1       0  5310.0   0.035       0
Bank Sta=4976.8,4982.6
Exp/Cntr=0.3,0.1

Type RM Length L Ch R = 1,3672,465,465,465
BEGIN DESCRIPTION:
Stream0470 7.0
END DESCRIPTION:
XS GIS Cut Line= 3
      1902325.00     13949675.00      1901525.00     13949075.00
      1901224.96     13948874.98
#Sta/Elev= 30
  4000.0 1817.76  4042.6 1814.24  4070.4 1809.68  4154.0 1804.68  4205.6 1799.22
  4237.6 1793.79  4274.0 1789.80  4379.0 1785.28  4392.8 1781.08  4409.0 1783.42
  4494.1 1776.87  4770.4 1764.17  4770.8 1763.67  4776.2 1764.17  4816.2 1766.97
  4977.8 1768.99  4990.6 1768.01  4998.3 1765.89  5015.6 1765.37  5036.4 1772.19
  5048.0 1777.69  5063.2 1780.36  5089.0 1791.76  5151.9 1822.29  5175.7 1826.57
  5195.2 1833.34  5231.1 1852.56  5292.7 1892.43  5335.8 1914.62  5360.6 1924.38
#Mann=6,-1,0
  4000.0    0.07       0  4070.4   0.035       0  4770.4   0.035       0
  4776.2   0.035       0  5089.0     0.1       0  5195.2    0.07       0
Bank Sta=4770.4,4776.2
Exp/Cntr=0.3,0.1

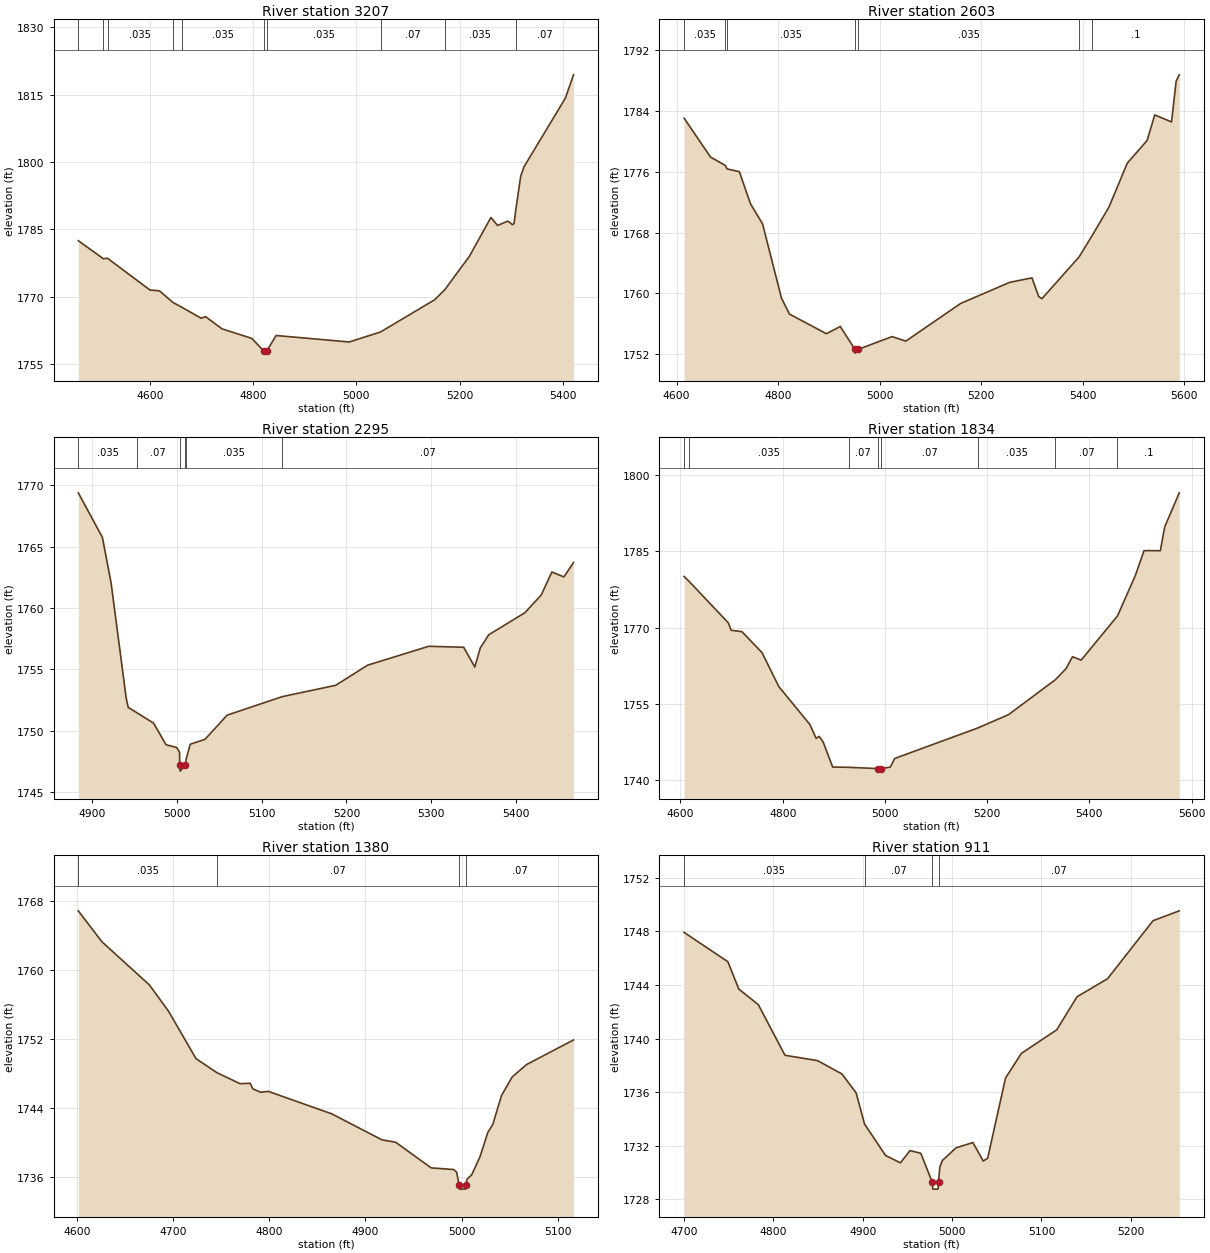
Type RM Length L Ch R = 1,3207,604,604,604
BEGIN DESCRIPTION:
Stream0470 6.0
END DESCRIPTION:
XS GIS Cut Line= 3
      1902275.02     13949275.02      1901925.00     13948875.00
      1901525.03     13948725.01
#Sta/Elev= 30
  4461.6 1782.49  4510.1 1778.48  4518.2 1778.58  4600.3 1771.52  4618.7 1771.34
  4644.5 1768.78  4662.7 1767.64  4699.5 1765.24  4708.1 1765.59  4739.8 1762.88
  4797.3 1760.77  4820.6 1757.98  4821.1 1757.48  4826.4 1757.98  4844.7 1761.40
  4986.0 1759.96  5046.7 1762.18  5151.5 1769.35  5171.3 1771.61  5218.8 1779.02
  5260.4 1787.65  5273.3 1785.88  5293.4 1786.85  5302.1 1786.04  5305.3 1786.32
  5308.2 1789.01  5318.1 1796.83  5324.5 1798.93  5404.6 1814.20  5420.3 1819.38
#Mann=10,-1,0
  4461.6   0.035       0  4510.1    0.07       0  4518.2   0.035       0
  4644.5    0.07       0  4662.7   0.035       0  4820.6   0.035       0
  4826.4   0.035       0  5046.7    0.07       0  5171.3   0.035       0
  5308.2    0.07       0
Bank Sta=4820.6,4826.4
Exp/Cntr=0.3,0.1

Type RM Length L Ch R = 1,2603,308,308,308
BEGIN DESCRIPTION:
Stream0470 5.0
END DESCRIPTION:
XS GIS Cut Line= 3
      1902574.99     13949124.98      1902415.08     13948779.76
      1902372.94     13948186.51
#Sta/Elev= 30
  4614.9 1783.08  4667.1 1777.94  4696.0 1776.86  4699.5 1776.39  4723.8 1776.02
  4745.7 1771.79  4769.5 1769.14  4806.7 1759.36  4822.4 1757.25  4895.2 1754.66
  4922.5 1755.61  4951.4 1752.60  4951.9 1752.10  4958.0 1752.60  5024.5 1754.28
  5051.6 1753.68  5159.6 1758.65  5256.1 1761.43  5300.0 1762.02  5313.3 1759.56
  5319.7 1759.28  5392.9 1764.79  5418.2 1767.56  5451.6 1771.35  5487.7 1777.14
  5526.8 1780.14  5541.8 1783.50  5574.9 1782.58  5583.9 1787.94  5590.1 1788.79
#Mann=7,-1,0
  4614.9   0.035       0  4696.0    0.07       0  4699.5   0.035       0
  4951.4   0.035       0  4958.0   0.035       0  5392.9    0.07       0
  5418.2     0.1       0
Bank Sta=4951.4,4958
Exp/Cntr=0.3,0.1

Type RM Length L Ch R = 1,2295,461,461,461
BEGIN DESCRIPTION:
Stream0470 4.0
END DESCRIPTION:
XS GIS Cut Line= 3
      1902775.02     13948875.04      1902725.00     13948775.00
      1902475.02     13948375.04
#Sta/Elev= 30
  4884.0 1769.39  4912.4 1765.76  4922.7 1762.02  4940.4 1752.68  4942.8 1751.91
  4953.0 1751.48  4972.7 1750.63  4987.4 1748.87  4999.8 1748.65  5003.3 1748.27
  5003.5 1747.22  5004.0 1746.72  5010.2 1747.22  5011.2 1747.72  5015.9 1748.91
  5033.3 1749.31  5059.4 1751.28  5124.4 1752.79  5187.3 1753.71  5224.9 1755.35
  5297.0 1756.89  5338.1 1756.81  5351.2 1755.20  5357.7 1756.76  5367.7 1757.83
  5410.2 1759.62  5429.5 1761.07  5442.0 1762.94  5456.2 1762.54  5467.5 1763.71
#Mann=6,-1,0
  4884.0   0.035       0  4953.0    0.07       0  5003.5    0.05       0
  5010.2    0.07       0  5011.2   0.035       0  5124.4    0.07       0
Bank Sta=5003.5,5010.2
Exp/Cntr=0.3,0.1

Type RM Length L Ch R = 1,1834,454,454,454
BEGIN DESCRIPTION:
Stream0470 3.0
END DESCRIPTION:
XS GIS Cut Line= 3
      1903075.00     13948875.01      1903025.00     13948475.00
      1902625.01     13948075.01
#Sta/Elev= 30
  4607.0 1780.07  4616.0 1779.19  4693.6 1770.95  4699.1 1769.49  4720.2 1769.22
  4759.5 1765.10  4792.5 1758.40  4853.3 1750.95  4865.3 1748.25  4871.4 1748.63
  4879.0 1747.54  4897.8 1742.60  4928.8 1742.55  4985.8 1742.30  4986.3 1741.80
  4992.6 1742.30  5010.5 1742.59  5019.0 1744.28  5182.1 1750.30  5241.8 1752.91
  5333.3 1759.76  5354.2 1761.94  5366.9 1764.29  5383.9 1763.63  5454.9 1772.30
  5489.9 1780.27  5506.9 1785.15  5538.8 1785.13  5547.3 1789.80  5575.8 1796.51
#Mann=8,-1,0
  4607.0    0.07       0  4616.0   0.035       0  4928.8    0.07       0
  4985.8    0.05       0  4992.6    0.07       0  5182.1   0.035       0
  5333.3    0.07       0  5454.9     0.1       0
Bank Sta=4985.8,4992.6
Exp/Cntr=0.3,0.1

Type RM Length L Ch R = 1,1380,469,469,469
BEGIN DESCRIPTION:
Stream0470 2.0
END DESCRIPTION:
XS GIS Cut Line= 3
      1903425.00     13948624.98      1903375.00     13948225.00
      1903325.00     13948125.00
#Sta/Elev= 30
  4601.4 1766.91  4625.9 1763.32  4675.4 1758.29  4695.4 1755.21  4723.8 1749.73
  4745.5 1748.10  4769.5 1746.82  4780.1 1746.86  4782.9 1746.22  4791.0 1745.82
  4799.0 1745.92  4864.8 1743.32  4917.3 1740.28  4931.3 1740.02  4968.3 1737.03
  4991.7 1736.84  4994.8 1736.53  4997.4 1735.06  4997.9 1734.56  5003.7 1734.56
  5004.2 1735.06  5005.7 1735.73  5010.5 1736.23  5019.1 1738.33  5027.2 1741.14
  5032.4 1742.09  5041.5 1745.45  5052.7 1747.62  5067.5 1749.04  5116.3 1751.90
#Mann=4,-1,0
  4601.4   0.035       0  4745.5    0.07       0  4997.4    0.05       0
  5004.2    0.07       0
Bank Sta=4997.4,5004.2
Exp/Cntr=0.3,0.1

Type RM Length L Ch R = 1,911,446,446,446
BEGIN DESCRIPTION:
Stream0470 1.0
END DESCRIPTION:
XS GIS Cut Line= 3
      1903825.00     13948325.00      1903775.00     13948025.00
      1903575.03     13947875.02
#Sta/Elev= 30
  4700.1 1747.93  4749.1 1745.74  4761.3 1743.70  4783.2 1742.53  4813.0 1738.75
  4849.5 1738.35  4876.8 1737.35  4892.7 1735.93  4902.0 1733.62  4925.5 1731.27
  4942.2 1730.71  4952.9 1731.63  4965.0 1731.43  4977.9 1729.25  4978.4 1728.75
  4984.3 1728.75  4984.8 1729.25  4986.3 1730.41  4989.1 1730.89  5004.6 1731.84
  5023.3 1732.23  5034.8 1730.85  5039.8 1731.06  5059.8 1737.05  5077.5 1738.89
  5117.1 1740.65  5139.8 1743.12  5174.0 1744.47  5224.8 1748.80  5254.2 1749.54
#Mann=4,-1,0
  4700.1   0.035       0  4902.0    0.07       0  4977.9    0.05       0
  4984.8    0.07       0
Bank Sta=4977.9,4984.8
Exp/Cntr=0.3,0.1