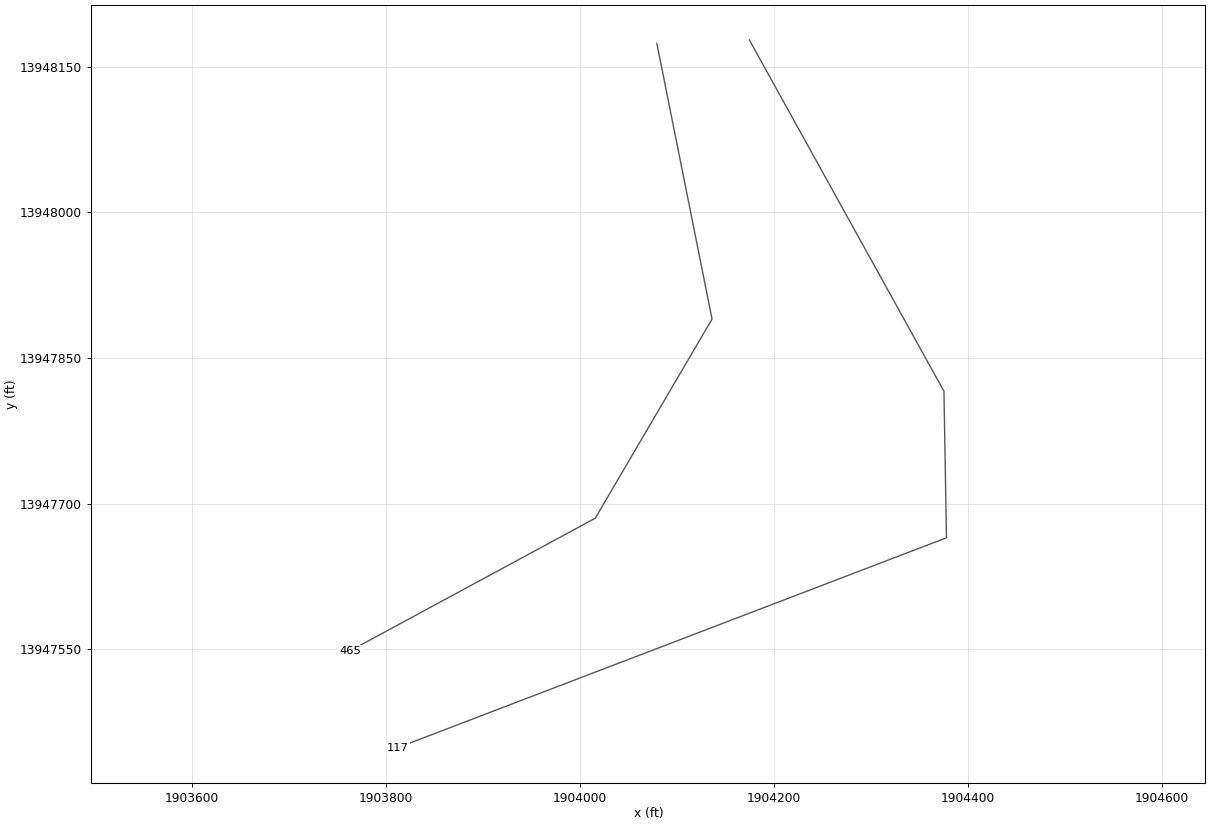
HEC-RAS study Stream0470.prj: Stream0470 Base Level Engineering

--- Stream0470.g01 (geometry) --- (continued)

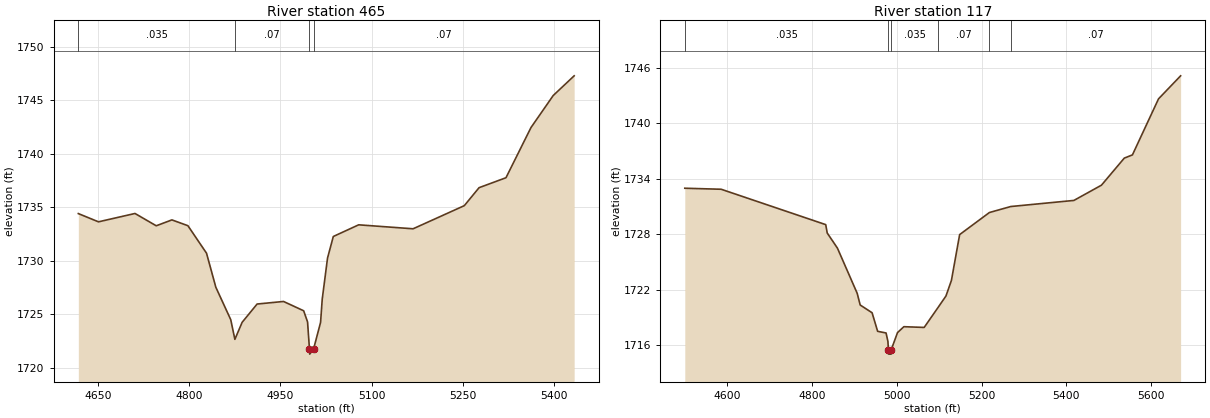
Type RM Length L Ch R = 1,465,348,348,348
BEGIN DESCRIPTION:
Stream0470 0.0
END DESCRIPTION:
XS GIS Cut Line= 4
      1904079.27     13948174.14      1904136.16     13947890.08
      1904015.80     13947684.87      1903763.34     13947548.38
#Sta/Elev= 30
  4617.9 1734.41  4651.0 1733.64  4711.0 1734.42  4745.9 1733.27  4771.6 1733.82
  4797.9 1733.28  4828.5 1730.71  4843.8 1727.53  4868.3 1724.50  4875.1 1722.66
  4887.0 1724.25  4911.6 1725.96  4955.0 1726.20  4988.1 1725.33  4994.5 1724.29
  4997.6 1721.78  4998.1 1721.28  5004.5 1721.78  5015.9 1724.25  5018.6 1726.41
  5027.3 1730.25  5036.8 1732.27  5078.5 1733.36  5167.9 1732.99  5252.0 1735.15
  5276.3 1736.83  5320.5 1737.76  5361.6 1742.45  5398.1 1745.44  5432.5 1747.28
#Mann=4,-1,0
  4617.9   0.035       0  4875.1    0.07       0  4997.6    0.05       0
  5004.5    0.07       0
Bank Sta=4997.6,5004.5
Exp/Cntr=0.3,0.1

Type RM Length L Ch R = 1,117,0,0,0
BEGIN DESCRIPTION:
Stream0470 0.1
END DESCRIPTION:
XS GIS Cut Line= 4
      1904174.61     13948177.69      1904375.11     13947815.75
      1904377.72     13947664.71      1903812.57     13947448.55
#Sta/Elev= 30
  4499.8 1732.99  4585.6 1732.88  4832.3 1729.05  4835.9 1728.14  4859.9 1726.51
  4906.6 1721.61  4913.6 1720.35  4941.7 1719.51  4954.8 1717.50  4974.7 1717.32
  4979.1 1716.40  4980.2 1715.53  4980.7 1715.03  4986.6 1715.03  4987.1 1715.53
  5001.7 1717.36  5016.7 1718.00  5064.6 1717.92  5096.6 1720.03  5116.0 1721.32
  5128.9 1723.01  5148.3 1727.97  5218.5 1730.36  5268.9 1731.01  5417.9 1731.67
  5482.9 1733.32  5536.8 1736.25  5556.0 1736.60  5617.6 1742.67  5669.7 1745.16
#Mann=6,-1,0
  4499.8   0.035       0  4980.2   0.035       0  4987.1   0.035       0
  5096.6    0.07       0  5218.5   0.035       0  5268.9    0.07       0
Bank Sta=4980.2,4987.1
Exp/Cntr=0.3,0.1

Chan Stop Cuts=-1