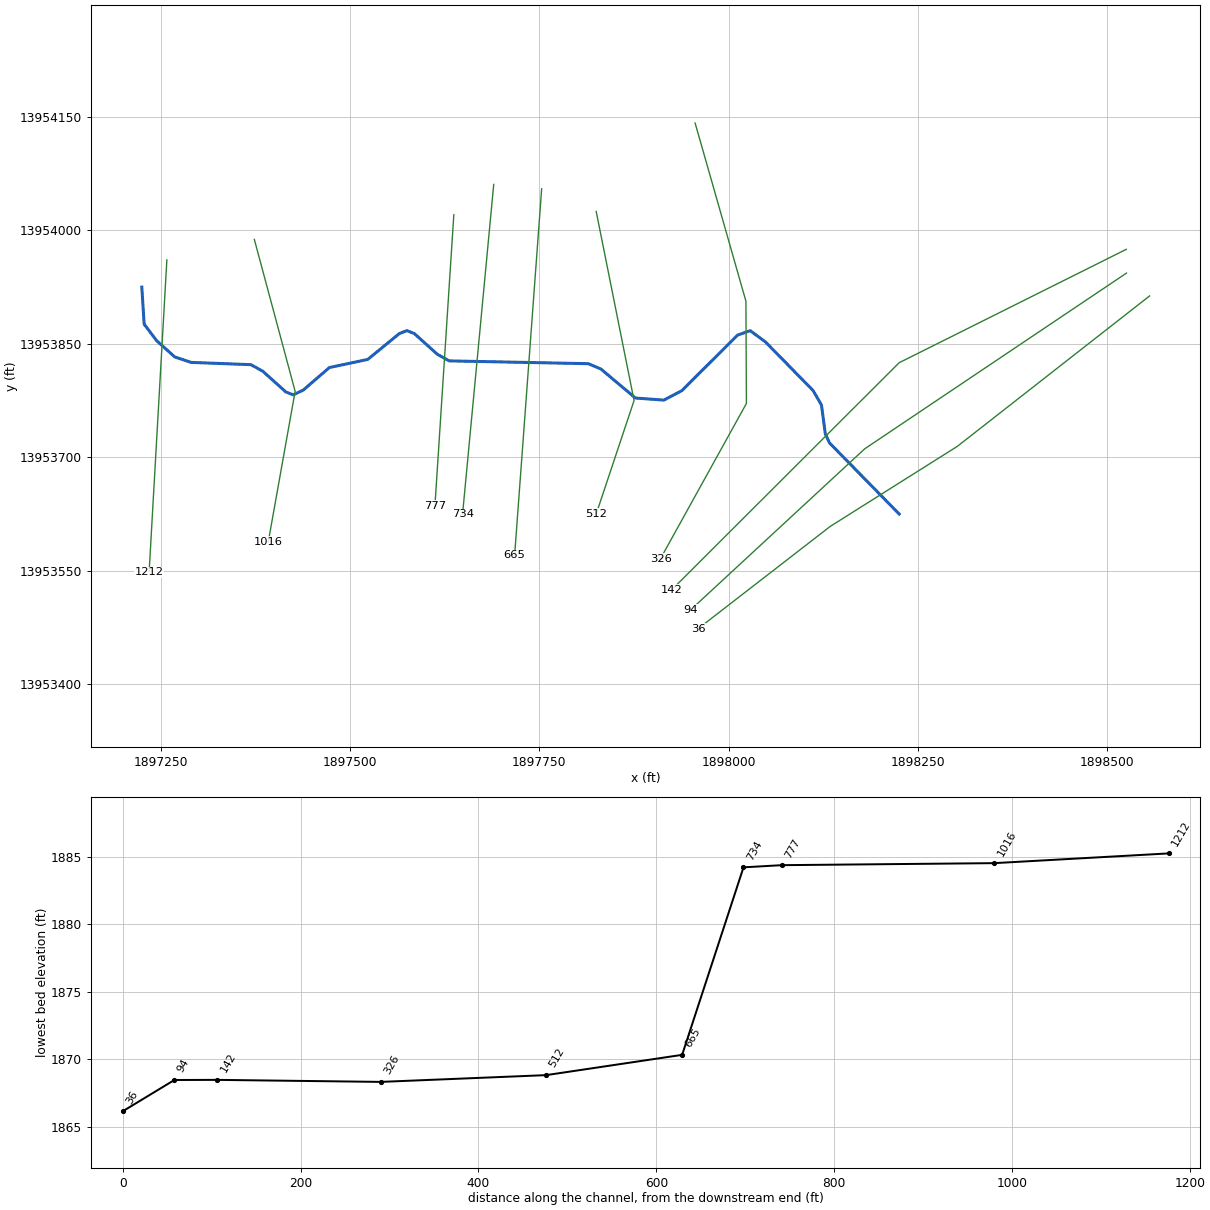
--- Stream0471.prj (project) ---

Proj Title=Stream0471 Base Level Engineering
Current Plan=p01
Default Exp/Contr=0.3,0.1
English Units
Geom File=g01
Flow File=f01
Plan File=p01
BEGIN DESCRIPTION:
Stream0471
END DESCRIPTION:

--- Stream0471.p01 (plan) ---

Plan Title=Multiple Run
Short Identifier=Multiple
Geom File=g01
Flow File=f01
Subcritical Flow
K Sum by GR= 0
Std Step Tol= 0.01
Critical Tol= 0.01
Num of Std Step Trials= 20
Max Error Tol= 0.3
Flow Tol Ratio= 0.001
Split Flow NTrial= 30
Split Flow Tol= 0.02
Split Flow Ratio= 0.02
Log Output Level= 0
Friction Slope Method= 1
Unsteady Friction Slope Method= 2
Unsteady Bridges Friction Slope Method= 1
Parabolic Critical Depth
Global Vel Dist=  1 , 1 , 1
Global Log Level= 0
CheckData=True
Encroach Param= -1, 0, 0, 0
BEGIN DESCRIPTION:
Multiple Run
END DESCRIPTION:

--- Stream0471.f01 (steady flow) ---

Flow Title=Multiple
Number of Profiles=7
Profile Names=10-year,25-year,50-year,1pct_min,100-year,1pct_plu,500-year
River Rch & RM= Stream0471,Reach-1,1212
     432     697     936     611    1219    2433    2036
River Rch & RM= Stream0471,Reach-1,142
     830    1399    1935    1297    2588    5163    4564
Boundary for River Rch & Prof#=Stream0471,Reach-1,1
Up Type=0
Dn Type=3
Dn Slope=0.005
Boundary for River Rch & Prof#=Stream0471,Reach-1,2
Up Type=0
Dn Type=3
Dn Slope=0.005
Boundary for River Rch & Prof#=Stream0471,Reach-1,3
Up Type=0
Dn Type=3
Dn Slope=0.005
Boundary for River Rch & Prof#=Stream0471,Reach-1,4
Up Type=0
Dn Type=3
Dn Slope=0.005
Boundary for River Rch & Prof#=Stream0471,Reach-1,5
Up Type=0
Dn Type=3
Dn Slope=0.005
Boundary for River Rch & Prof#=Stream0471,Reach-1,6
Up Type=0
Dn Type=3
Dn Slope=0.005
Boundary for River Rch & Prof#=Stream0471,Reach-1,7
Up Type=0
Dn Type=3
Dn Slope=0.005

--- Stream0471.g01 (geometry) ---

Geom Title=Existing Conditions

River Reach=Stream0471,Reach-1
Reach XY= 30
      1897225.00     13953925.00      1897228.12     13953875.99
      1897244.50     13953854.24      1897268.56     13953832.64
      1897290.12     13953825.46      1897369.10     13953822.45
      1897384.78     13953813.75      1897415.10     13953786.45
      1897425.01     13953782.53      1897438.24     13953788.88
      1897472.72     13953818.64      1897523.35     13953829.39
      1897565.07     13953863.58      1897574.99     13953867.47
      1897584.90     13953863.54      1897615.21     13953836.21
      1897630.86     13953827.46      1897814.50     13953823.76
      1897831.08     13953816.81      1897876.75     13953778.34
      1897914.38     13953775.61      1897938.22     13953788.18
      1898011.68     13953861.56      1898028.35     13953867.41
      1898048.38     13953852.63      1898111.37     13953788.27
      1898122.48     13953768.98      1898127.52     13953731.05
      1898133.11     13953718.93      1898225.00     13953625.00

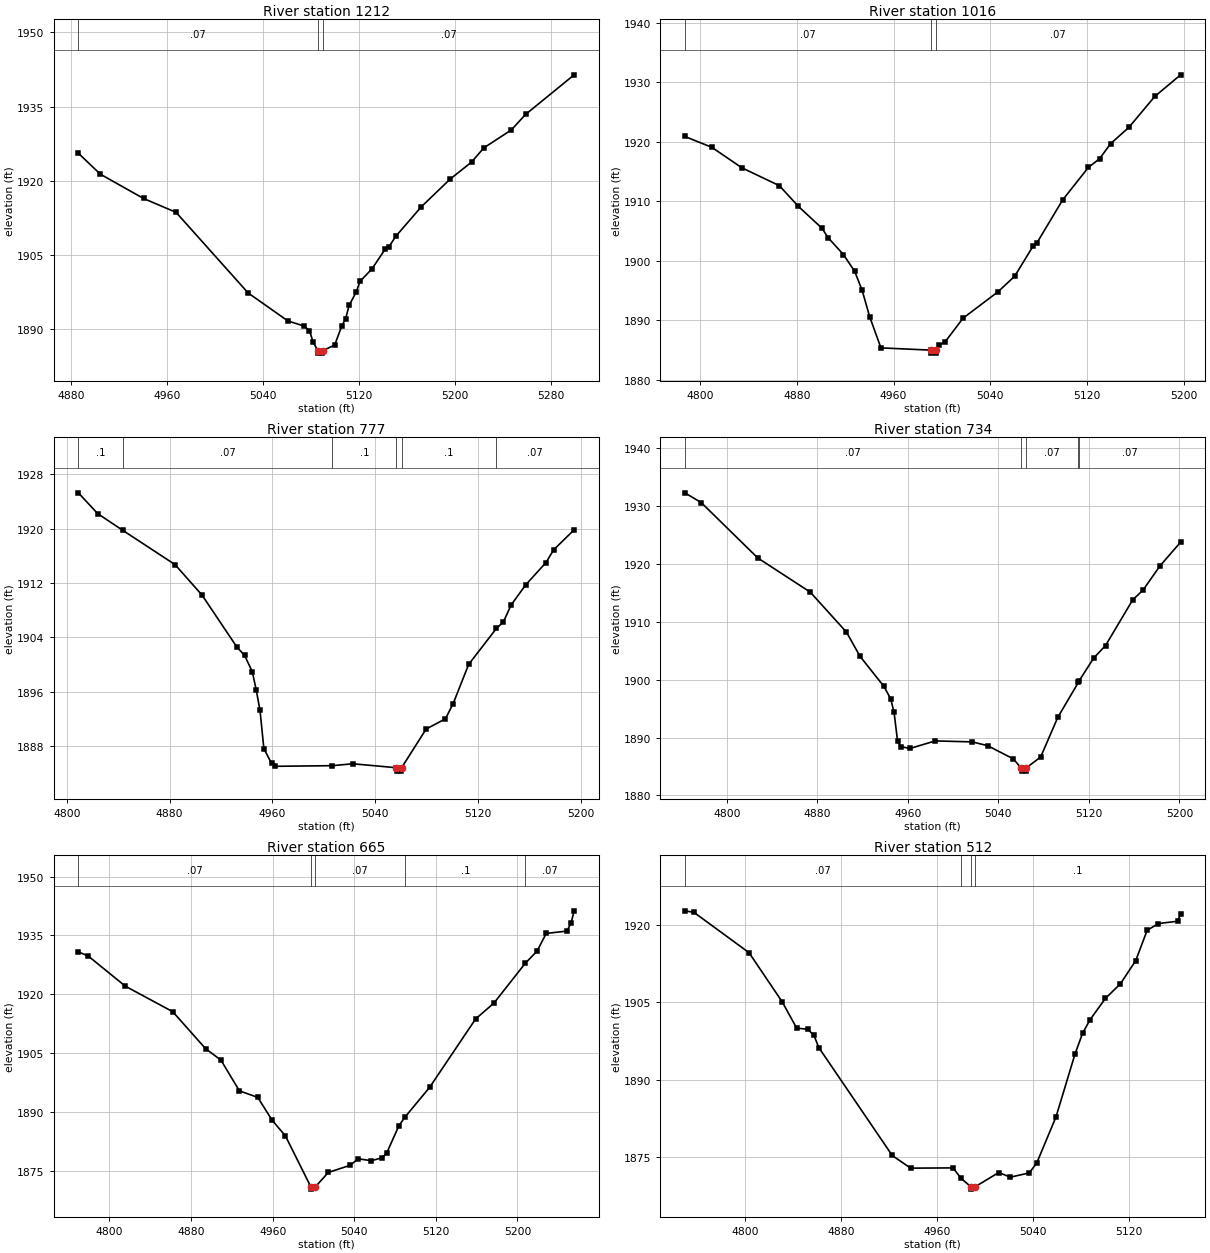
Type RM Length L Ch R = 1,1212,196,196,196
BEGIN DESCRIPTION:
Stream0471 3.0
END DESCRIPTION:
XS GIS Cut Line= 2
      1897258.10     13953960.94      1897234.67     13953548.20
#Sta/Elev= 30
  4885.9 1925.58  4904.3 1921.34  4940.3 1916.44  4967.4 1913.64  5027.5 1897.37
  5060.6 1891.73  5073.9 1890.71  5078.6 1889.79  5081.6 1887.50  5085.6 1885.73
  5085.9 1885.23  5089.4 1885.23  5089.6 1885.73  5099.6 1886.85  5105.7 1890.80
  5108.7 1892.13  5111.7 1894.88  5117.7 1897.62  5120.7 1899.69  5130.8 1902.26
  5141.7 1906.21  5144.7 1906.64  5150.7 1908.84  5171.8 1914.75  5195.8 1920.33
  5213.8 1923.80  5224.0 1926.66  5246.9 1930.27  5258.8 1933.41  5299.3 1941.40
#Mann=3,-1,0
  4885.9    0.07       0  5085.6    0.05       0  5089.6    0.07       0
Bank Sta=5085.6,5089.6
Exp/Cntr=0.3,0.1

Type RM Length L Ch R = 1,1016,239,239,239
BEGIN DESCRIPTION:
Stream0471 2.0
END DESCRIPTION:
XS GIS Cut Line= 3
      1897373.57     13953988.11      1897427.47     13953787.20
      1897392.06     13953588.55
#Sta/Elev= 30
  4787.5 1920.90  4809.8 1919.08  4834.7 1915.63  4865.7 1912.63  4881.3 1909.17
  4900.8 1905.50  4906.1 1903.86  4918.6 1901.07  4927.9 1898.25  4934.1 1895.04
  4940.3 1890.62  4949.6 1885.39  4991.1 1885.01  4991.3 1884.51  4994.8 1884.51
  4995.1 1885.01  4997.3 1885.84  5002.3 1886.31  5017.5 1890.38  5046.4 1894.82
  5060.2 1897.44  5075.4 1902.50  5078.5 1903.02  5099.8 1910.24  5121.1 1915.71
  5130.3 1917.15  5139.4 1919.68  5154.6 1922.44  5176.0 1927.63  5197.3 1931.25
#Mann=3,-1,0
  4787.5    0.07       0  4991.1    0.05       0  4995.1    0.07       0
Bank Sta=4991.1,4995.1
Exp/Cntr=0.3,0.1

Type RM Length L Ch R = 1,777,43,43,43
BEGIN DESCRIPTION:
Stream0471 1.1
END DESCRIPTION:
XS GIS Cut Line= 2
      1897637.00     13954020.65      1897612.03     13953635.56
#Sta/Elev= 30
  4808.9 1925.25  4824.0 1922.19  4843.3 1919.76  4884.2 1914.70  4905.2 1910.22
  4932.3 1902.59  4938.3 1901.36  4944.3 1898.97  4947.3 1896.34  4950.3 1893.29
  4953.3 1887.67  4959.3 1885.49  4962.3 1885.07  5006.5 1885.16  5022.5 1885.44
  5056.5 1884.86  5056.8 1884.36  5060.3 1884.36  5060.5 1884.86  5079.6 1890.54
  5094.6 1892.05  5100.6 1894.27  5112.7 1900.04  5134.3 1905.33  5139.7 1906.27
  5145.7 1908.76  5157.1 1911.73  5172.8 1914.99  5178.8 1916.87  5194.8 1919.82
#Mann=6,-1,0
  4808.9     0.1       0  4843.3    0.07       0  5006.5     0.1       0
  5056.5    0.05       0  5060.5     0.1       0  5134.3    0.07       0
Bank Sta=5056.5,5060.5
Exp/Cntr=0.3,0.1

Type RM Length L Ch R = 1,734,69,69,69
BEGIN DESCRIPTION:
Mapping XS 6bc1010a
END DESCRIPTION:
XS GIS Cut Line= 2
      1897689.68     13954060.76      1897648.50     13953624.40
#Sta/Elev= 30
  4762.8 1932.27  4777.3 1930.59  4827.3 1921.02  4873.7 1915.12  4905.7 1908.21
  4917.7 1904.03  4938.8 1898.84  4944.8 1896.69  4947.8 1894.34  4950.9 1889.35
  4953.9 1888.43  4961.8 1888.11  4984.2 1889.42  5016.9 1889.25  5030.6 1888.59
  5053.3 1886.30  5060.3 1884.70  5060.6 1884.20  5064.1 1884.20  5064.3 1884.70
  5077.4 1886.65  5092.5 1893.48  5110.8 1899.56  5111.5 1899.83  5124.2 1903.72
  5134.7 1905.89  5158.8 1913.80  5167.8 1915.45  5182.9 1919.66  5201.1 1923.75
#Mann=5,-1,0
  4762.8    0.07       0  5060.3    0.05       0  5064.3    0.07       0
  5110.8     0.1       0  5111.5    0.07       0
Bank Sta=5060.3,5064.3
Exp/Cntr=0.3,0.1

Type RM Length L Ch R = 1,665,153,153,153
BEGIN DESCRIPTION:
Mapping XS 545eb923
END DESCRIPTION:
XS GIS Cut Line= 2
      1897753.00     13954054.98      1897717.27     13953570.19
#Sta/Elev= 30
  4769.5 1930.81  4779.2 1929.75  4815.6 1922.06  4862.1 1915.55  4894.3 1906.12
  4909.3 1903.22  4927.4 1895.38  4945.4 1893.72  4959.5 1887.89  4972.5 1883.91
  4997.6 1870.83  4997.8 1870.33  5001.6 1870.83  5014.6 1874.59  5035.7 1876.38
  5044.0 1878.06  5056.7 1877.57  5067.7 1878.35  5071.8 1879.52  5083.8 1886.50
  5090.0 1888.78  5113.9 1896.27  5159.0 1913.71  5177.0 1917.77  5207.7 1927.91
  5219.2 1931.00  5228.2 1935.51  5248.5 1936.11  5252.6 1938.20  5255.6 1941.27
#Mann=5,-1,0
  4769.5    0.07       0  4997.6    0.05       0  5001.6    0.07       0
  5090.0     0.1       0  5207.7    0.07       0
Bank Sta=4997.6,5001.6
Exp/Cntr=0.3,0.1

Type RM Length L Ch R = 1,512,186,186,186
BEGIN DESCRIPTION:
Stream0471 1.0
END DESCRIPTION:
XS GIS Cut Line= 3
      1897825.01     13954024.97      1897875.00     13953775.00
      1897825.01     13953625.03
#Sta/Elev= 30
  4749.9 1922.70  4757.5 1922.41  4803.4 1914.60  4830.9 1905.13  4843.1 1900.00
  4852.3 1899.77  4857.5 1898.59  4861.5 1896.24  4922.7 1875.34  4938.0 1872.89
  4973.4 1872.94  4979.8 1870.96  4988.0 1869.33  4988.2 1868.83  4992.0 1869.33
  5011.4 1872.04  5021.1 1871.15  5036.9 1871.97  5043.2 1873.96  5059.1 1882.82
  5074.9 1894.96  5081.2 1898.98  5087.5 1901.64  5100.2 1905.73  5112.8 1908.59
  5125.5 1913.06  5135.0 1918.92  5144.4 1920.24  5160.3 1920.68  5162.9 1922.10
#Mann=4,-1,0
  4749.9    0.07       0  4979.8     0.1       0  4988.0    0.05       0
  4992.0     0.1       0
Bank Sta=4988,4992
Exp/Cntr=0.3,0.1

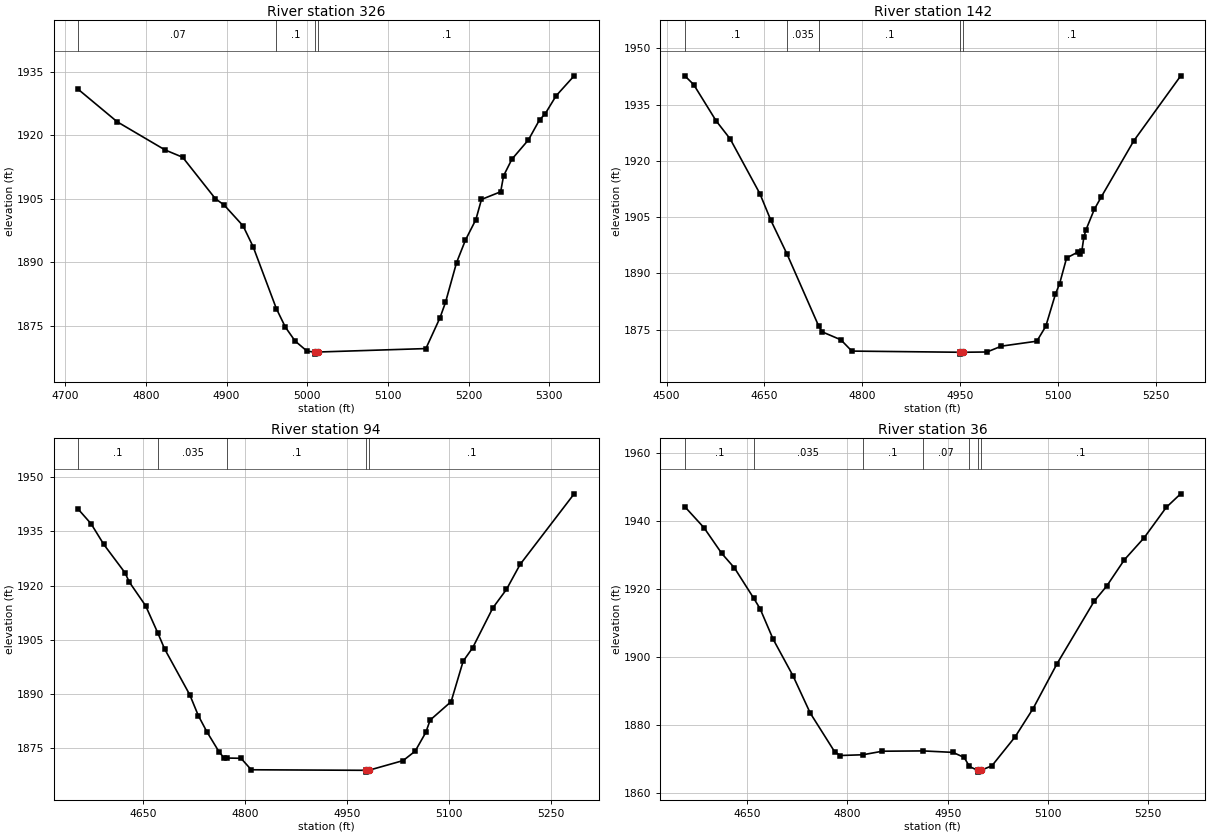
Type RM Length L Ch R = 1,326,184,184,184
BEGIN DESCRIPTION:
Mapping XS 39666433
END DESCRIPTION:
XS GIS Cut Line= 4
      1897955.62     13954141.92      1898022.69     13953906.40
      1898023.36     13953771.15      1897909.93     13953565.96
#Sta/Elev= 30
  4716.3 1930.79  4764.5 1923.15  4823.8 1916.51  4845.6 1914.79  4886.2 1905.00
  4897.0 1903.52  4920.5 1898.60  4933.0 1893.66  4961.8 1879.05  4973.0 1874.68
  4985.0 1871.42  5000.0 1869.00  5009.9 1868.83  5010.1 1868.33  5013.9 1868.83
  5147.1 1869.64  5164.6 1876.91  5171.4 1880.53  5185.1 1889.91  5196.2 1895.26
  5209.1 1900.09  5216.0 1904.83  5239.8 1906.64  5243.4 1910.40  5253.7 1914.32
  5274.2 1918.88  5288.0 1923.62  5294.8 1924.98  5308.5 1929.28  5330.9 1934.00
#Mann=4,-1,0
  4716.3    0.07       0  4961.8     0.1       0  5009.9    0.05       0
  5013.9     0.1       0
Bank Sta=5009.9,5013.9
Exp/Cntr=0.3,0.1

Type RM Length L Ch R = 1,142,48,48,48
BEGIN DESCRIPTION:
Stream0470 24.0
END DESCRIPTION:
XS GIS Cut Line= 3
      1898524.96     13953974.98      1898225.00     13953825.00
      1897925.02     13953525.02
#Sta/Elev= 30
  4528.0 1942.67  4541.6 1940.34  4575.9 1930.69  4597.5 1925.85  4643.0 1911.27
  4659.8 1904.16  4684.5 1895.19  4732.9 1876.05  4738.4 1874.42  4767.1 1872.30
  4783.9 1869.29  4949.7 1868.98  4949.9 1868.48  4953.7 1868.98  4990.9 1869.05
  5013.1 1870.61  5067.3 1871.93  5081.0 1875.89  5095.9 1884.52  5102.2 1887.26
  5112.9 1894.11  5129.9 1895.66  5134.1 1895.26  5136.2 1895.91  5139.4 1899.71
  5142.6 1901.62  5155.3 1907.05  5165.9 1910.35  5215.8 1925.33  5287.6 1942.63
#Mann=5,-1,0
  4528.0     0.1       0  4684.5   0.035       0  4732.9     0.1       0
  4949.7    0.05       0  4953.7     0.1       0
Bank Sta=4949.7,4953.7
Exp/Cntr=0.3,0.1

Type RM Length L Ch R = 1,94,58,58,58
BEGIN DESCRIPTION:
Stream0470 23.3
END DESCRIPTION:
XS GIS Cut Line= 3
      1898525.24     13953943.55      1898179.55     13953711.18
      1897950.04     13953498.54
#Sta/Elev= 30
  4554.2 1941.06  4573.0 1937.06  4591.7 1931.35  4622.8 1923.55  4629.2 1920.97
  4653.2 1914.42  4671.3 1906.83  4681.1 1902.51  4718.2 1889.81  4730.8 1884.04
  4743.5 1879.55  4761.6 1873.96  4768.8 1872.37  4773.0 1872.36  4793.5 1872.29
  4808.6 1869.12  4977.3 1868.97  4977.5 1868.47  4981.3 1868.97  5032.0 1871.66
  5049.7 1874.26  5065.4 1879.45  5071.7 1882.84  5102.6 1887.94  5120.3 1899.11
  5134.3 1902.82  5164.0 1913.84  5184.0 1918.93  5204.1 1925.84  5283.6 1945.34
#Mann=5,-1,0
  4554.2     0.1       0  4671.3   0.035       0  4773.0     0.1       0
  4977.3    0.05       0  4981.3     0.1       0
Bank Sta=4977.3,4981.3
Exp/Cntr=0.3,0.1

Type RM Length L Ch R = 1,36,0,0,0
BEGIN DESCRIPTION:
Stream0470 23.2
END DESCRIPTION:
XS GIS Cut Line= 4
      1898555.66     13953913.30      1898301.79     13953714.39
      1898134.11     13953608.64      1897959.65     13953473.40
#Sta/Elev= 30
  4556.9 1944.10  4585.6 1937.93  4612.2 1930.37  4631.2 1926.11  4660.2 1917.15
  4669.4 1914.19  4688.9 1905.23  4718.7 1894.45  4744.5 1883.50  4780.8 1872.20
  4789.3 1871.04  4823.3 1871.26  4852.3 1872.30  4913.1 1872.39  4957.9 1871.96
  4974.7 1870.47  4982.6 1867.82  4995.2 1866.66  4995.5 1866.16  4999.2 1866.66
  5016.1 1868.00  5050.9 1876.52  5077.7 1884.80  5113.4 1897.93  5169.2 1916.37
  5187.8 1920.78  5214.3 1928.52  5243.8 1934.97  5276.9 1943.90  5298.4 1947.88
#Mann=7,-1,0
  4556.9     0.1       0  4660.2   0.035       0  4823.3     0.1       0
  4913.1    0.07       0  4982.6     0.1       0  4995.2    0.05       0
  4999.2     0.1       0
Bank Sta=4995.2,4999.2
Exp/Cntr=0.3,0.1

Chan Stop Cuts=-1