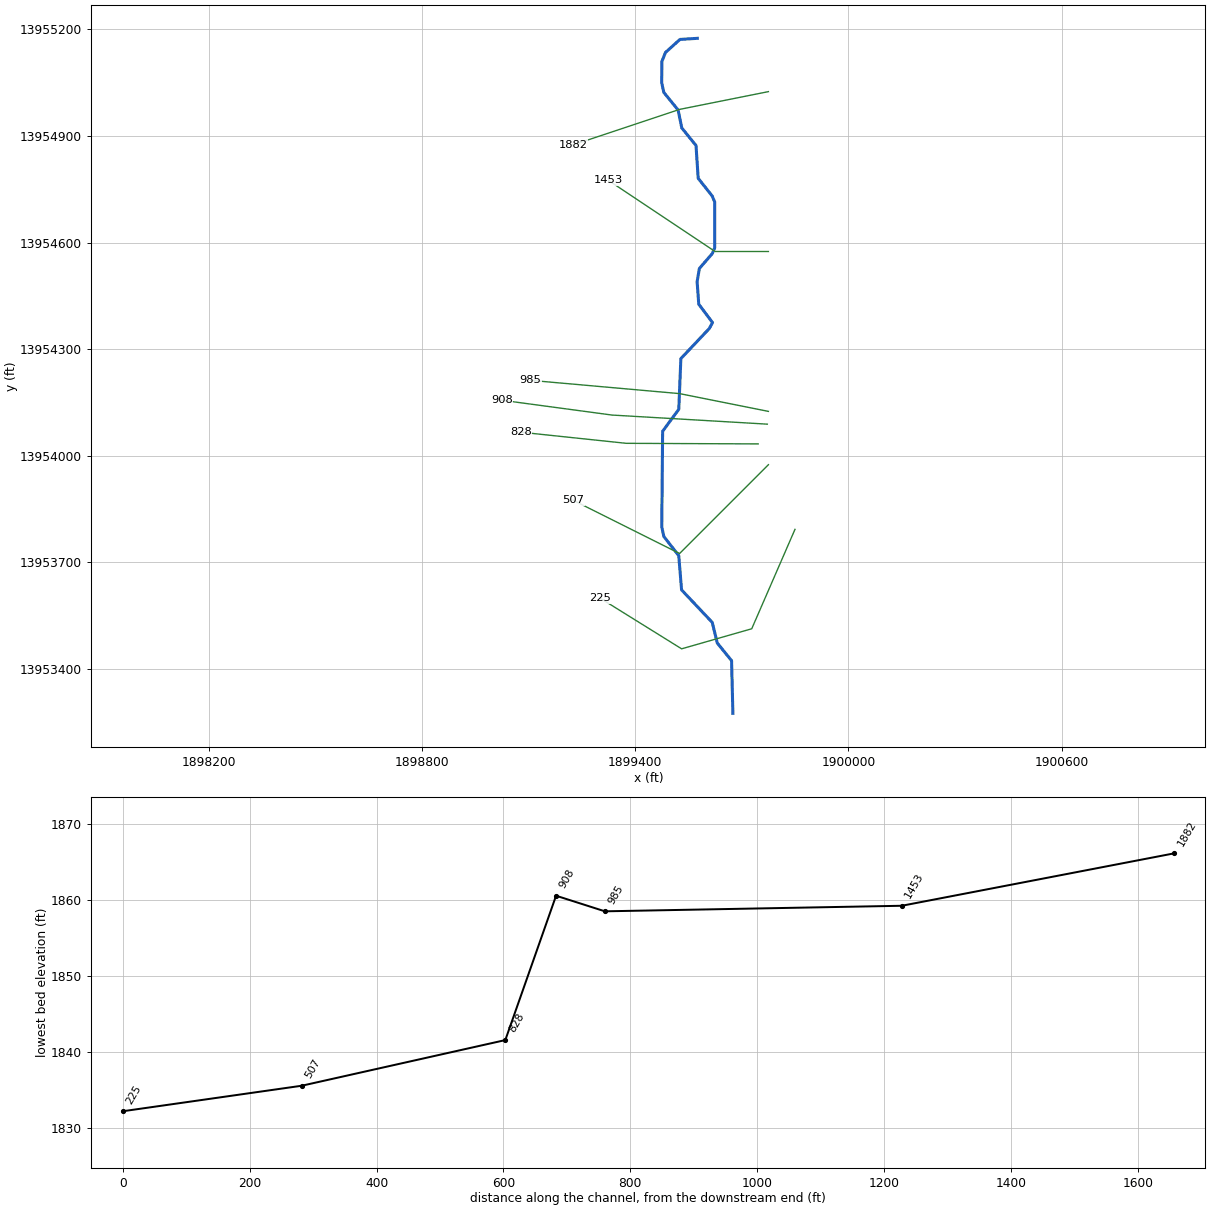
--- Stream0472.prj (project) ---

Proj Title=Stream0472 Base Level Engineering
Current Plan=p01
Default Exp/Contr=0.3,0.1
English Units
Geom File=g01
Flow File=f01
Plan File=p01
BEGIN DESCRIPTION:
Stream0472
END DESCRIPTION:

--- Stream0472.p01 (plan) ---

Plan Title=Multiple Run
Short Identifier=Multiple
Geom File=g01
Flow File=f01
Subcritical Flow
K Sum by GR= 0
Std Step Tol= 0.01
Critical Tol= 0.01
Num of Std Step Trials= 20
Max Error Tol= 0.3
Flow Tol Ratio= 0.001
Split Flow NTrial= 30
Split Flow Tol= 0.02
Split Flow Ratio= 0.02
Log Output Level= 0
Friction Slope Method= 1
Unsteady Friction Slope Method= 2
Unsteady Bridges Friction Slope Method= 1
Parabolic Critical Depth
Global Vel Dist=  1 , 1 , 1
Global Log Level= 0
CheckData=True
Encroach Param= -1, 0, 0, 0
BEGIN DESCRIPTION:
Multiple Run
END DESCRIPTION:

--- Stream0472.f01 (steady flow) ---

Flow Title=Multiple
Number of Profiles=7
Profile Names=10-year,25-year,50-year,1pct_min,100-year,1pct_plu,500-year
River Rch & RM= Stream0472,Reach-1,1882
     545     894    1215     802    1600    3192    2731
Boundary for River Rch & Prof#=Stream0472,Reach-1,1
Up Type=0
Dn Type=3
Dn Slope=0.005
Boundary for River Rch & Prof#=Stream0472,Reach-1,2
Up Type=0
Dn Type=3
Dn Slope=0.005
Boundary for River Rch & Prof#=Stream0472,Reach-1,3
Up Type=0
Dn Type=3
Dn Slope=0.005
Boundary for River Rch & Prof#=Stream0472,Reach-1,4
Up Type=0
Dn Type=3
Dn Slope=0.005
Boundary for River Rch & Prof#=Stream0472,Reach-1,5
Up Type=0
Dn Type=3
Dn Slope=0.005
Boundary for River Rch & Prof#=Stream0472,Reach-1,6
Up Type=0
Dn Type=3
Dn Slope=0.005
Boundary for River Rch & Prof#=Stream0472,Reach-1,7
Up Type=0
Dn Type=3
Dn Slope=0.005

--- Stream0472.g01 (geometry) ---

Geom Title=Existing Conditions

River Reach=Stream0472,Reach-1
Reach XY= 30
      1899575.00     13955175.00      1899525.98     13955171.88
      1899485.17     13955135.10      1899475.17     13955109.89
      1899474.57     13955050.00      1899480.64     13955022.68
      1899520.81     13954973.27      1899531.11     13954922.82
      1899571.17     13954873.42      1899577.36     13954780.98
      1899616.87     13954731.06      1899623.80     13954714.49
      1899623.79     13954585.51      1899616.86     13954568.94
      1899580.69     13954527.31      1899574.31     13954490.06
      1899578.95     13954426.50      1899617.67     13954374.90
      1899608.67     13954358.31      1899528.57     13954273.53
      1899522.73     13954130.94      1899477.26     13954069.06
      1899474.80     13953799.92      1899480.74     13953772.66
      1899522.64     13953719.02      1899530.54     13953622.58
      1899616.84     13953531.05      1899631.14     13953472.83
      1899671.28     13953423.46      1899675.00     13953275.00

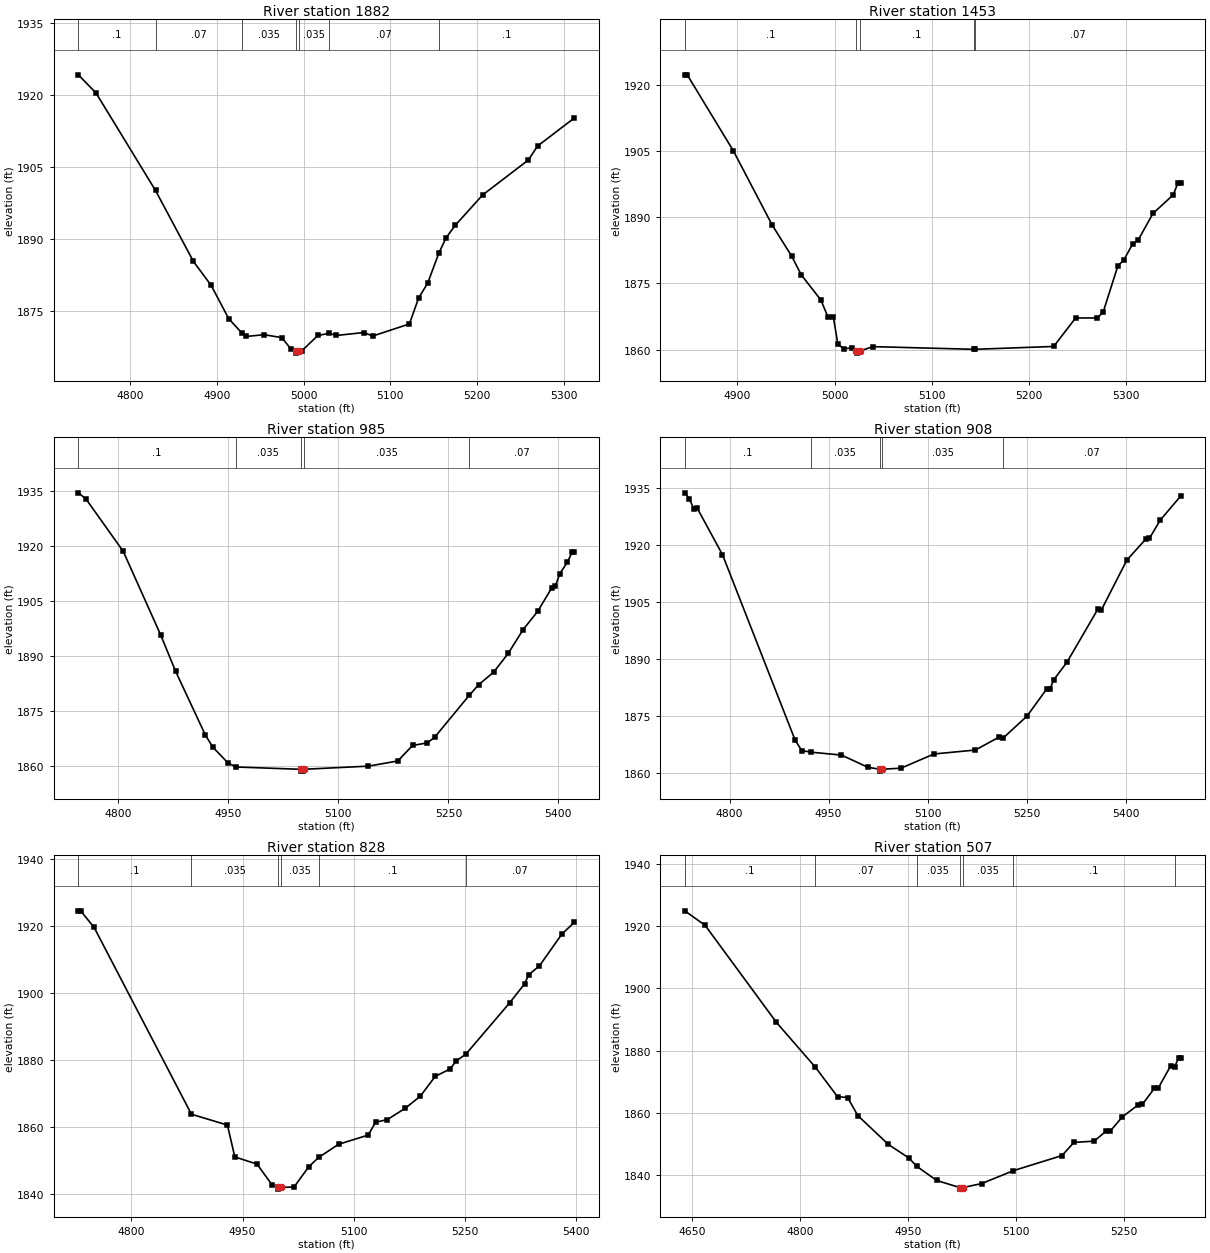
Type RM Length L Ch R = 1,1882,429,429,429
BEGIN DESCRIPTION:
Stream0472 4.0
END DESCRIPTION:
XS GIS Cut Line= 3
      1899774.98     13955025.00      1899525.00     13954975.00
      1899224.96     13954874.99
#Sta/Elev= 30
  4740.5 1924.26  4760.9 1920.46  4829.4 1900.10  4873.1 1885.26  4893.5 1880.27
  4913.8 1873.29  4928.9 1870.31  4934.2 1869.60  4954.6 1869.96  4975.0 1869.34
  4985.2 1867.01  4990.9 1866.61  4991.1 1866.11  4994.9 1866.61  4998.1 1866.61
  5016.5 1869.81  5029.8 1870.25  5037.6 1869.80  5069.2 1870.41  5079.8 1869.69
  5121.9 1872.21  5132.5 1877.62  5143.0 1880.74  5155.7 1886.96  5164.1 1890.19
  5174.6 1892.79  5206.2 1899.15  5259.0 1906.47  5269.5 1909.37  5311.7 1915.22
#Mann=7,-1,0
  4740.5     0.1       0  4829.4    0.07       0  4928.9   0.035       0
  4990.9   0.035       0  4994.9   0.035       0  5029.8    0.07       0
  5155.7     0.1       0
Bank Sta=4990.9,4994.9
Exp/Cntr=0.3,0.1

Type RM Length L Ch R = 1,1453,468,468,468
BEGIN DESCRIPTION:
Stream0472 3.0
END DESCRIPTION:
XS GIS Cut Line= 3
      1899774.98     13954575.00      1899625.00     13954575.00
      1899325.03     13954774.98
#Sta/Elev= 30
  4845.8 1922.20  4848.3 1922.20  4895.8 1905.00  4935.8 1888.20  4955.8 1881.19
  4965.8 1876.91  4985.8 1871.29  4993.3 1867.37  4998.8 1867.37  5003.3 1861.33
  5009.3 1860.20  5018.3 1860.43  5022.3 1859.73  5022.6 1859.23  5026.3 1859.73
  5039.4 1860.70  5143.8 1860.09  5144.1 1860.09  5225.6 1860.74  5248.2 1867.19
  5270.7 1867.18  5276.7 1868.61  5291.7 1878.98  5297.7 1880.26  5306.8 1883.89
  5312.8 1884.90  5327.8 1890.83  5348.8 1895.07  5353.3 1897.63  5356.3 1897.63
#Mann=5,-1,0
  4845.8     0.1       0  5022.3    0.05       0  5026.3     0.1       0
  5143.8   0.035       0  5144.1    0.07       0
Bank Sta=5022.3,5026.3
Exp/Cntr=0.3,0.1

Type RM Length L Ch R = 1,985,77,77,77
BEGIN DESCRIPTION:
Stream0472 2.0
END DESCRIPTION:
XS GIS Cut Line= 3
      1899774.98     13954125.00      1899525.00     13954175.00
      1899105.50     13954212.36
#Sta/Elev= 30
  4745.4 1934.48  4755.6 1932.86  4806.6 1918.51  4857.6 1895.72  4878.0 1885.77
  4918.8 1868.28  4928.9 1865.03  4949.3 1860.77  4960.2 1859.63  5048.5 1859.00
  5048.8 1858.50  5052.3 1858.50  5052.5 1859.00  5140.9 1859.86  5181.0 1861.27
  5201.1 1865.50  5221.2 1866.21  5231.2 1867.73  5278.7 1879.26  5291.5 1882.13
  5311.6 1885.50  5331.6 1890.63  5351.7 1897.08  5371.8 1902.13  5390.9 1908.51
  5395.9 1909.00  5401.9 1912.40  5412.0 1915.46  5419.2 1918.44  5421.5 1918.44
#Mann=5,-1,0
  4745.4     0.1       0  4960.2   0.035       0  5048.5   0.035       0
  5052.5   0.035       0  5278.7    0.07       0
Bank Sta=5048.5,5052.5
Exp/Cntr=0.3,0.1

Type RM Length L Ch R = 1,908,80,80,80
BEGIN DESCRIPTION:
Mapping XS 5225a3c0
END DESCRIPTION:
XS GIS Cut Line= 3
      1899771.99     13954089.08      1899334.90     13954114.65
      1899024.34     13954156.46
#Sta/Elev= 30
  4732.1 1933.86  4739.1 1932.33  4745.9 1929.51  4751.0 1929.79  4789.2 1917.57
  4899.4 1868.64  4909.4 1865.96  4923.3 1865.54  4969.5 1864.78  5009.6 1861.55
  5027.6 1861.05  5027.8 1860.55  5031.6 1861.05  5059.6 1861.33  5109.7 1865.07
  5172.4 1866.11  5207.6 1869.46  5214.3 1869.24  5250.6 1875.05  5280.4 1882.19
  5285.4 1882.16  5290.9 1884.58  5311.1 1889.23  5358.2 1903.31  5363.3 1903.03
  5401.9 1916.16  5431.0 1921.75  5436.1 1921.88  5452.4 1926.66  5483.3 1933.00
#Mann=5,-1,0
  4732.1     0.1       0  4923.3   0.035       0  5027.6   0.035       0
  5031.6   0.035       0  5214.3    0.07       0
Bank Sta=5027.6,5031.6
Exp/Cntr=0.3,0.1

Type RM Length L Ch R = 1,828,321,321,321
BEGIN DESCRIPTION:
Mapping XS 352b298f
END DESCRIPTION:
XS GIS Cut Line= 3
      1899746.26     13954033.47      1899375.18     13954035.09
      1899078.41     13954066.38
#Sta/Elev= 30
  4728.3 1924.51  4731.4 1924.51  4749.6 1919.57  4881.0 1863.90  4929.6 1860.67
  4939.6 1851.18  4969.6 1849.03  4989.6 1842.94  4997.6 1842.08  4997.8 1841.58
  5001.6 1842.08  5019.6 1842.22  5039.6 1848.29  5053.0 1851.05  5079.6 1854.93
  5119.7 1857.69  5129.7 1861.53  5145.5 1862.29  5170.0 1865.72  5190.1 1869.28
  5210.2 1875.17  5230.3 1877.39  5238.5 1879.77  5251.5 1881.78  5310.7 1897.09
  5330.8 1902.74  5336.4 1905.45  5351.0 1908.13  5381.1 1917.55  5397.8 1921.04
#Mann=6,-1,0
  4728.3     0.1       0  4881.0   0.035       0  4997.6   0.035       0
  5001.6   0.035       0  5053.0     0.1       0  5251.5    0.07       0
Bank Sta=4997.6,5001.6
Exp/Cntr=0.3,0.1

Type RM Length L Ch R = 1,507,282,282,282
BEGIN DESCRIPTION:
Stream0472 1.0
END DESCRIPTION:
XS GIS Cut Line= 3
      1899775.01     13953975.01      1899525.00     13953725.00
      1899224.99     13953875.01
#Sta/Elev= 30
  4639.3 1924.89  4667.6 1920.22  4766.6 1889.09  4820.8 1874.69  4851.5 1865.25
  4865.6 1864.97  4879.7 1859.18  4922.2 1849.92  4950.4 1845.62  4961.7 1842.89
  4989.3 1838.36  5021.6 1836.08  5021.9 1835.58  5025.6 1836.08  5051.6 1837.35
  5096.0 1841.51  5163.4 1846.35  5180.1 1850.58  5208.1 1850.97  5224.9 1854.21
  5230.5 1854.19  5247.2 1858.74  5269.6 1862.69  5275.2 1862.79  5291.9 1867.94
  5297.5 1868.15  5314.3 1875.06  5320.1 1874.89  5325.5 1877.70  5328.3 1877.70
#Mann=7,-1,0
  4639.3     0.1       0  4820.8    0.07       0  4961.7   0.035       0
  5021.6   0.035       0  5025.6   0.035       0  5096.0     0.1       0
  5320.1    0.07       0
Bank Sta=5021.6,5025.6
Exp/Cntr=0.3,0.1

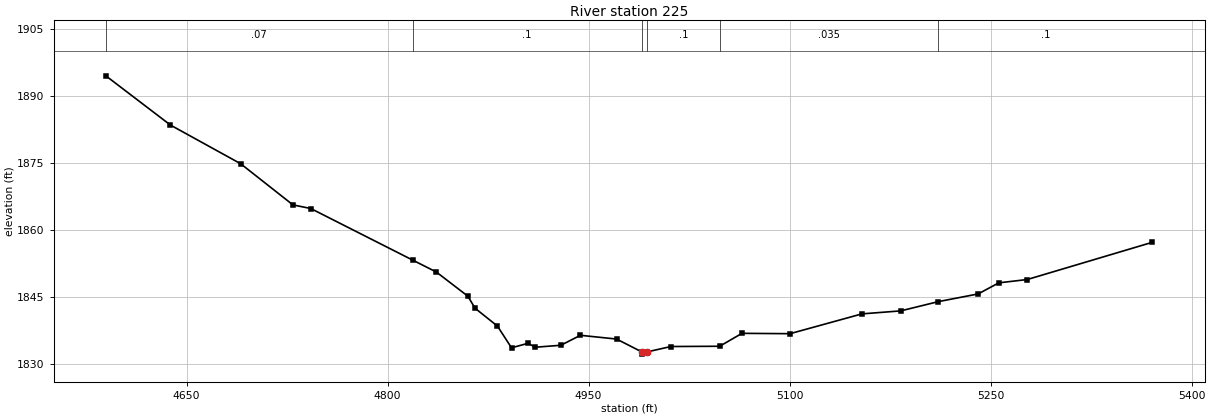
Type RM Length L Ch R = 1,225,0,0,0
BEGIN DESCRIPTION:
Stream0472 0.0
END DESCRIPTION:
XS GIS Cut Line= 4
      1899849.78     13953792.97      1899728.05     13953513.16
      1899530.65     13953456.69      1899301.08     13953599.46
#Sta/Elev= 30
  4589.8 1894.46  4638.0 1883.45  4690.4 1874.80  4729.4 1865.60  4742.7 1864.79
  4818.7 1853.26  4836.4 1850.59  4859.9 1845.19  4865.3 1842.49  4882.0 1838.50
  4892.5 1833.64  4904.9 1834.66  4910.1 1833.77  4929.3 1834.21  4943.9 1836.44
  4970.9 1835.60  4989.7 1832.73  4990.0 1832.23  4993.7 1832.73  5011.4 1833.93
  5047.8 1833.99  5064.5 1836.88  5100.3 1836.80  5154.0 1841.23  5182.9 1841.90
  5211.0 1843.97  5240.7 1845.69  5256.1 1848.17  5277.3 1848.91  5370.6 1857.23
#Mann=6,-1,0
  4589.8    0.07       0  4818.7     0.1       0  4989.7    0.05       0
  4993.7     0.1       0  5047.8   0.035       0  5211.0     0.1       0
Bank Sta=4989.7,4993.7
Exp/Cntr=0.3,0.1

Chan Stop Cuts=-1