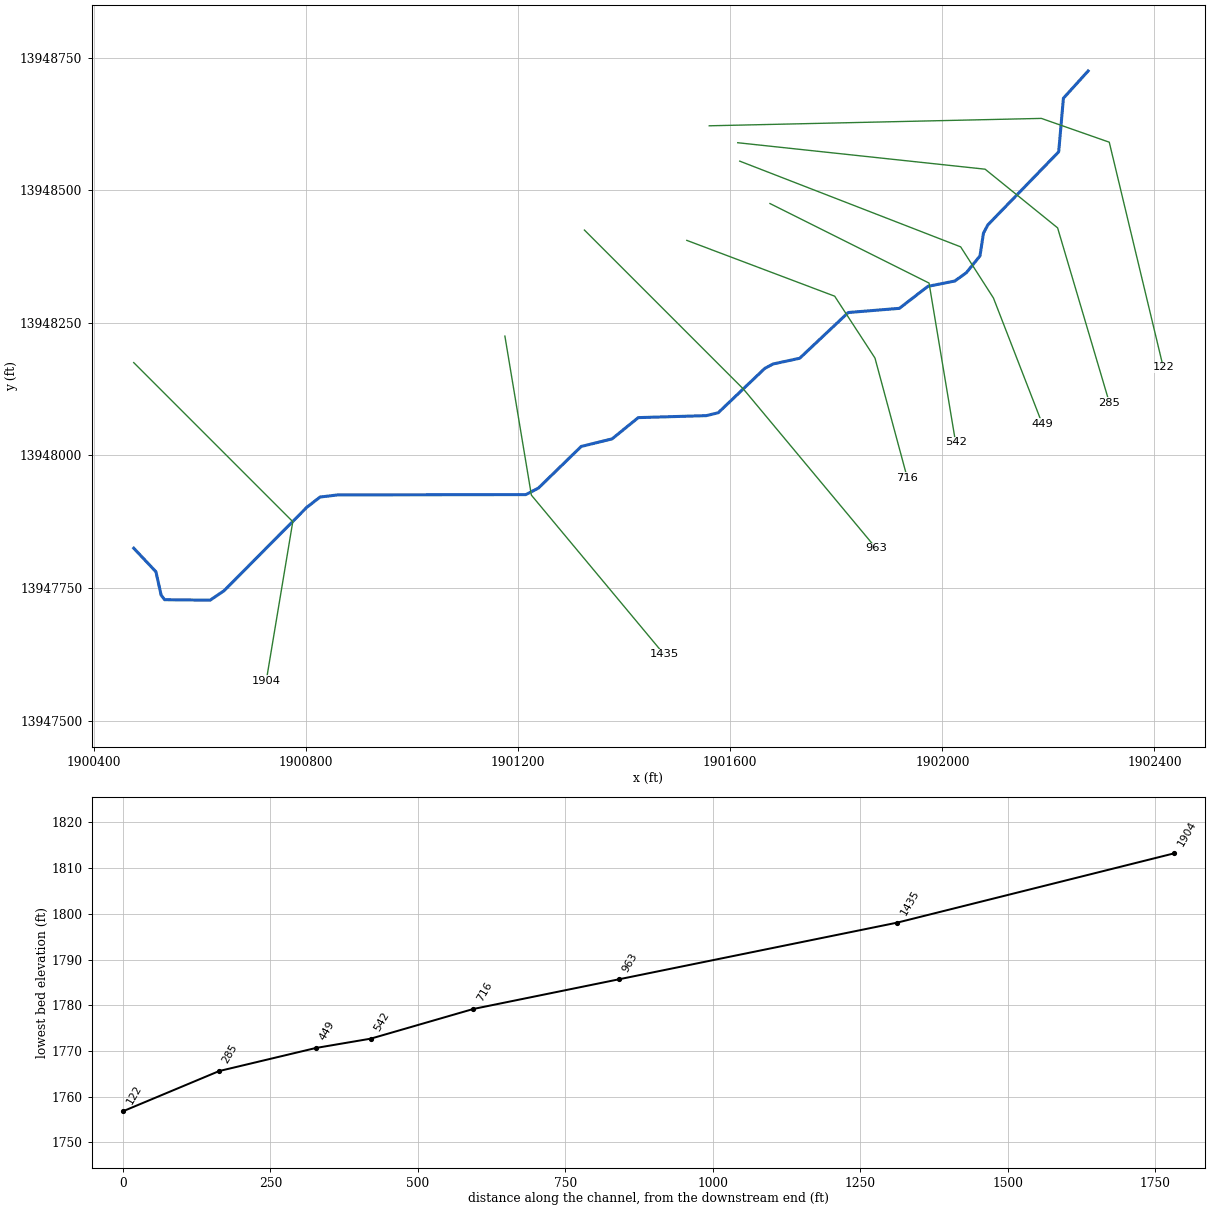
--- Stream0474.prj (project) ---

Proj Title=Stream0474 Base Level Engineering
Current Plan=p01
Default Exp/Contr=0.3,0.1
English Units
Geom File=g01
Flow File=f01
Plan File=p01
Y Axis Title=Elevation
X Axis Title(PF)=Main Channel Distance
X Axis Title(XS)=Station
BEGIN DESCRIPTION:
Stream0474
END DESCRIPTION:
DSS Export Rating Curves= 0
DSS Export Rating Curve Sorted= 0
DSS Export Volume Flow Curves= 0
DXF OffsetX= 0
DXF OffsetY= 0
DXF ScaleX= 1
DXF ScaleY= 10

--- Stream0474.p01 (plan) ---

Plan Title=Multiple Run
Short Identifier=Multiple
Geom File=g01
Flow File=f01
Subcritical Flow
K Sum by GR= 0
Std Step Tol= 0.01
Critical Tol= 0.01
Num of Std Step Trials= 20
Max Error Tol= 0.3
Flow Tol Ratio= 0.001
Split Flow NTrial= 30
Split Flow Tol= 0.02
Split Flow Ratio= 0.02
Log Output Level= 0
Friction Slope Method= 1
Unsteady Friction Slope Method= 2
Unsteady Bridges Friction Slope Method= 1
Parabolic Critical Depth
Global Vel Dist=  1 , 1 , 1
Global Log Level= 0
CheckData=True
Encroach Param= -1, 0, 0, 0
BEGIN DESCRIPTION:
Multiple Run
END DESCRIPTION:

--- Stream0474.f01 (steady flow) ---

Flow Title=Multiple
Program Version=4.10
Number of Profiles= 7
Profile Names=10-year,25-year,50-year,1pct_min,100-year,1pct_plu,500-year
River Rch & RM=Stream0474,Reach-1         ,1904
     547     901    1226     811    1619    3230    2776
Boundary for River Rch & Prof#=Stream0474,Reach-1         , 1
Up Type= 0
Dn Type= 3
Dn Slope=0.01
Boundary for River Rch & Prof#=Stream0474,Reach-1         , 2
Up Type= 0
Dn Type= 3
Dn Slope=0.01
Boundary for River Rch & Prof#=Stream0474,Reach-1         , 3
Up Type= 0
Dn Type= 3
Dn Slope=0.01
Boundary for River Rch & Prof#=Stream0474,Reach-1         , 4
Up Type= 0
Dn Type= 3
Dn Slope=0.01
Boundary for River Rch & Prof#=Stream0474,Reach-1         , 5
Up Type= 0
Dn Type= 3
Dn Slope=0.01
Boundary for River Rch & Prof#=Stream0474,Reach-1         , 6
Up Type= 0
Dn Type= 3
Dn Slope=0.01
Boundary for River Rch & Prof#=Stream0474,Reach-1         , 7
Up Type= 0
Dn Type= 3
Dn Slope=0.01
DSS Import GetInterval= 0
DSS Import GetPeak= 0
DSS Import FillOption= 0

--- Stream0474.g01 (geometry) ---

Geom Title=Existing Conditions
Program Version=4.10

River Reach=Stream0474      ,Reach-1
Reach XY= 30
        1900475.       13947825.      1900516.85     13947780.62
      1900526.72      13947736.4      1900533.18     13947727.84
      1900619.02     13947726.92      1900645.13     13947744.57
      1900801.47     13947902.14      1900826.46     13947921.46
       1900859.8     13947925.49      1901214.56     13947926.05
      1901238.31      13947938.4      1901318.95     13948016.84
      1901377.17     13948031.14      1901426.56     13948071.24
      1901555.01     13948074.98      1901577.44     13948080.48
      1901665.33      13948164.2      1901681.05     13948172.46
      1901731.04     13948183.18      1901822.58     13948269.46
      1901919.03     13948277.33      1901972.85     13948318.85
      1902023.58     13948328.86      1902045.47     13948344.62
      1902071.11     13948376.43      1902077.55     13948418.91
      1902085.79     13948434.66       1902219.5     13948572.56
      1902228.39     13948673.59        1902275.       13948725.

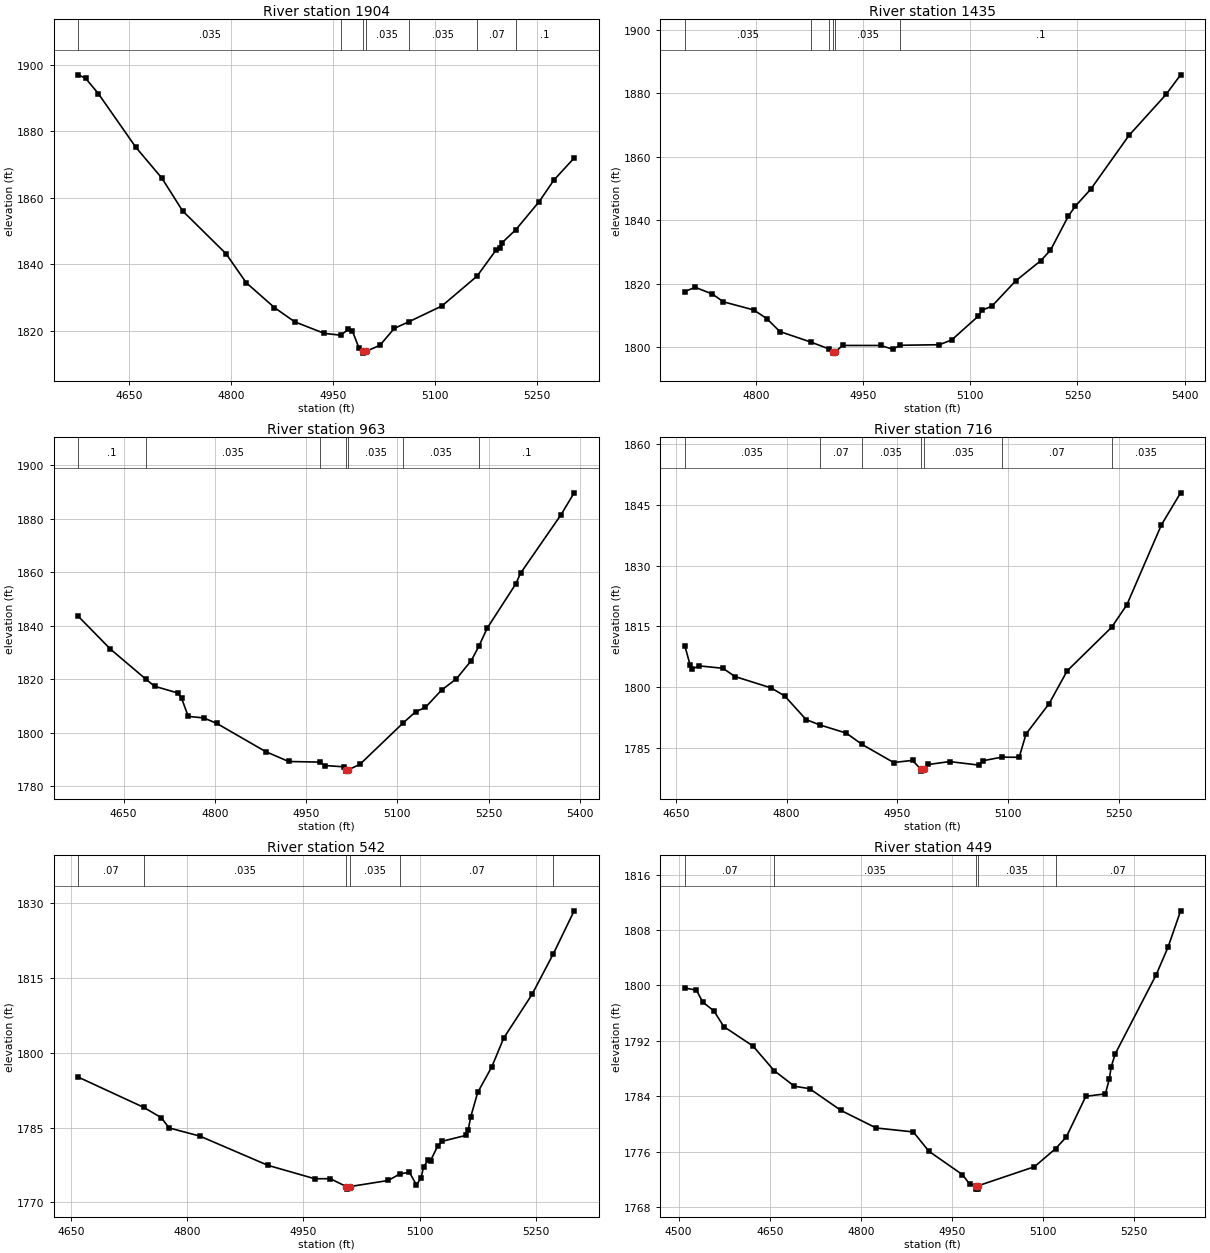
Type RM Length L Ch R = 1 ,1904    ,469,469,469
BEGIN DESCRIPTION:
Stream0474 4.0
END DESCRIPTION:
XS GIS Cut Line= 3
      1900474.98     13948175.02        1900775.       13947875.
        1900725.     13947575.02
#Sta/Elev= 30
    4576 1897.04  4586.7 1895.99  4605.3 1891.41  4660.5 1875.21  4698.7 1865.94
  4729.2 1856.06  4792.9 1843.18  4822.6 1834.45  4864.1 1826.94  4893.8 1822.67
  4937.1 1819.19  4961.6 1818.62  4972.8 1820.43  4978.7 1819.85    4988 1814.92
  4994.1 1813.73  4994.3 1813.23  4998.1 1813.73  5018.9 1815.56  5040.2 1820.68
  5061.6 1822.68  5110.1 1827.43  5161.8 1836.43  5189.2 1844.15  5195.3 1844.96
  5198.3 1846.43  5218.9 1850.45  5253.1 1858.88  5274.5 1865.32  5304.4 1871.99
#Mann= 7 ,-1 , 0
    4576    .035       0  4961.6    .035       0  4994.1    .035       0
  4998.1    .035       0  5061.6    .035       0  5161.8     .07       0
  5218.9      .1       0
Bank Sta=4994.1,4998.1
XS Rating Curve= 0 ,0
Exp/Cntr=0.3,0.1

Type RM Length L Ch R = 1 ,1435    ,472,472,472
BEGIN DESCRIPTION:
Stream0474 3.0
END DESCRIPTION:
XS GIS Cut Line= 3
      1901175.01     13948224.96        1901225.       13947925.
      1901474.99     13947625.01
#Sta/Elev= 30
  4699.9 1817.49  4714.4 1818.82  4738.7 1816.68  4753.9 1814.25  4796.5 1811.68
  4814.8 1808.95    4833 1804.88  4876.4 1801.57  4902.2 1799.37    4907 1798.58
  4907.3 1798.08    4911 1798.58  4921.2  1800.5  4974.3 1800.49  4991.2 1799.31
  5001.4 1800.55  5056.6 1800.73  5073.9 1802.25  5111.3 1809.79  5116.4 1811.61
  5130.1 1812.86  5163.3 1820.81  5198.4 1827.17  5212.1 1830.47  5237.4 1841.32
  5247.2 1844.43  5268.7 1849.76  5322.2 1866.68  5374.1 1879.58  5394.5 1885.76
#Mann= 6 ,-1 , 0
  4699.9    .035       0  4876.4     .07       0  4902.2    .035       0
    4907    .035       0    4911    .035       0  5001.4      .1       0
Bank Sta=4907,4911
XS Rating Curve= 0 ,0
Exp/Cntr=0.3,0.1

Type RM Length L Ch R = 1 ,963     ,247,247,247
BEGIN DESCRIPTION:
Stream0474 2.0
END DESCRIPTION:
XS GIS Cut Line= 3
        1901325.       13948425.        1901625.       13948125.
      1901875.01     13947824.99
#Sta/Elev= 30
  4575.7 1843.52  4628.5 1831.26  4686.8 1820.02  4700.9  1817.4  4739.4 1814.86
  4745.5 1812.83  4756.3 1806.14  4781.8 1805.55    4803 1803.53  4883.6 1792.96
  4921.3 1789.27  4972.9 1789.04  4981.2 1787.75    5012 1787.29  5015.3 1786.17
  5015.6 1785.67  5019.3 1786.17  5038.4  1788.2  5109.4 1803.67  5129.9 1807.83
  5146.2 1809.52  5172.5 1815.95    5197 1820.17  5221.5    1827  5234.1 1832.46
  5247.7 1839.14  5294.6 1855.66  5302.4 1859.64  5368.8 1881.46  5390.5 1889.69
#Mann= 7 ,-1 , 0
  4575.7      .1       0  4686.8    .035       0  4972.9    .035       0
  5015.3    .035       0  5019.3    .035       0  5109.4    .035       0
  5234.1      .1       0
Bank Sta=5015.3,5019.3
XS Rating Curve= 0 ,0
Exp/Cntr=0.3,0.1

Type RM Length L Ch R = 1 ,716     ,174,174,174
BEGIN DESCRIPTION:
Mapping XS 57adf288
END DESCRIPTION:
XS GIS Cut Line= 4
      1901518.11     13948405.54      1901796.98     13948300.27
      1901872.99      13948183.6      1901933.94      13947957.6
#Sta/Elev= 30
  4662.2 1810.21  4669.3 1805.47  4672.5 1804.49  4682.1  1805.2  4713.8 1804.61
  4730.2 1802.57    4779 1799.76  4797.5 1797.77  4826.4 1791.93  4844.6 1790.63
  4880.9 1788.57  4902.3 1785.77    4945  1781.3  4970.6 1781.83  4981.6 1779.67
  4981.9 1779.17  4985.6 1779.67    4992 1780.81  5020.7 1781.53  5060.1 1780.67
  5066.1 1781.75  5091.6 1782.63    5115 1782.59  5124.3 1788.37  5155.4 1795.83
    5180 1803.98  5240.2 1814.76  5260.8 1820.32  5307.6  1840.1  5333.6 1848.02
#Mann= 7 ,-1 , 0
  4662.2    .035       0  4844.6     .07       0  4902.3    .035       0
  4981.6    .035       0  4985.6    .035       0  5091.6     .07       0
  5240.2    .035       0
Bank Sta=4981.6,4985.6
XS Rating Curve= 0 ,0
Exp/Cntr=0.3,0.1

Type RM Length L Ch R = 1 ,542     ,93,93,93
BEGIN DESCRIPTION:
Stream0474 1.0
END DESCRIPTION:
XS GIS Cut Line= 3
      1901674.99       13948475.        1901975.       13948325.
      1902025.01     13948024.96
#Sta/Elev= 30
  4659.8  1795.1  4744.4 1789.03  4766.8 1786.98  4776.9 1784.93  4816.4  1783.3
  4904.3 1777.44  4964.7 1774.75  4984.8 1774.76  5005.7 1773.17    5006 1772.67
  5009.7 1773.17  5059.4  1774.4  5074.3 1775.68  5086.8 1776.08  5095.9 1773.52
    5102 1774.94  5105.1 1777.12  5111.1  1778.5  5114.2 1778.38  5123.3 1781.27
  5129.4 1782.26  5159.8 1783.44  5162.8 1784.59  5165.9  1787.1    5175 1792.05
  5193.3 1797.21  5208.5 1802.92    5245 1811.66  5272.7 1819.86  5299.4 1828.42
#Mann= 6 ,-1 , 0
  4659.8     .07       0  4744.4    .035       0  5005.7    .035       0
  5009.7    .035       0  5074.3     .07       0  5272.7    .035       0
Bank Sta=5005.7,5009.7
XS Rating Curve= 0 ,0
Exp/Cntr=0.3,0.1

Type RM Length L Ch R = 1 ,449     ,164,164,164
BEGIN DESCRIPTION:
Stream0474 1.1
END DESCRIPTION:
XS GIS Cut Line= 4
      1901617.92     13948554.99      1902034.62      13948393.3
      1902096.47     13948296.73      1902188.68     13948059.14
#Sta/Elev= 30
  4510.1 1799.64  4529.2 1799.33  4539.6 1797.61  4558.1 1796.33  4574.2 1794.08
  4622.5 1791.26  4657.2 1787.72  4690.7 1785.47  4715.6 1785.12  4767.3 1781.98
  4825.2 1779.45  4886.4 1778.88  4912.1 1776.09  4967.3 1772.72  4979.5 1771.32
  4989.6 1771.13  4989.9 1770.63  4993.4 1770.63  4993.6 1771.13  5085.9 1773.86
  5120.8 1776.48  5138.3 1778.14  5170.5 1784.02  5202.7 1784.37  5209.1 1786.49
  5212.3 1788.28  5218.8 1790.12  5286.4 1801.56  5305.7 1805.49  5326.6 1810.77
#Mann= 5 ,-1 , 0
  4510.1     .07       0  4657.2    .035       0  4989.6    .035       0
  4993.6    .035       0  5120.8     .07       0
Bank Sta=4989.6,4993.6
XS Rating Curve= 0 ,0
Exp/Cntr=0.3,0.1

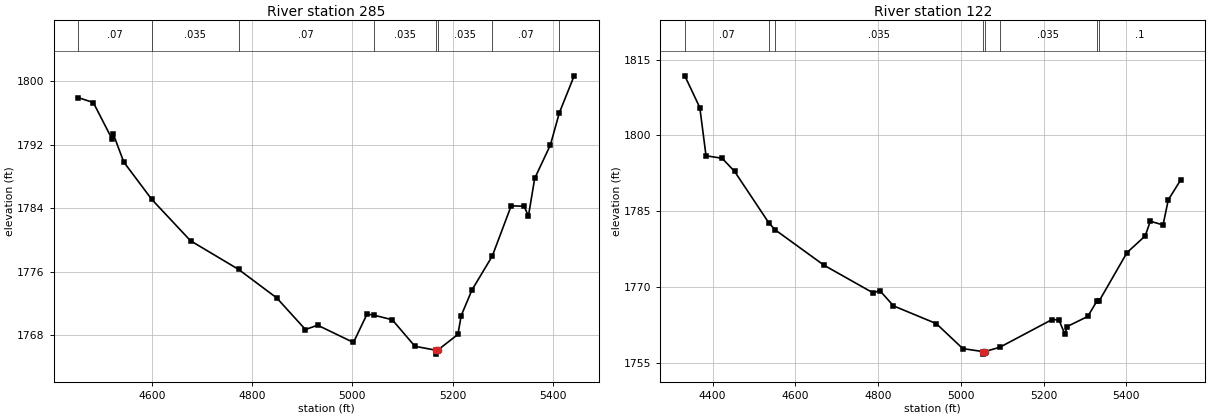
Type RM Length L Ch R = 1 ,285     ,163,163,163
BEGIN DESCRIPTION:
Stream0474 1.2
END DESCRIPTION:
XS GIS Cut Line= 4
      1901614.15     13948589.69      1902080.73     13948539.78
      1902217.45      13948429.1      1902315.12      13948099.2
#Sta/Elev= 30
  4453.3 1797.93  4483.2 1797.31  4520.2 1792.75  4523.3 1793.29    4544  1789.8
  4599.9 1785.09  4677.1 1779.88  4773.1 1776.26  4849.1 1772.67  4906.4 1768.68
  4930.7 1769.23  5002.2 1767.05  5029.3 1770.63  5042.5  1770.5  5079.5 1769.92
  5124.8 1766.57  5166.2 1766.08  5166.5 1765.58  5170.2 1766.08  5210.5 1768.06
  5217.2 1770.45  5238.7 1773.68  5279.1 1777.94  5316.9 1784.29  5342.5 1784.23
  5351.3 1783.01  5363.8 1787.75  5395.1 1791.96  5412.8 1795.99  5442.5 1800.68
#Mann= 8 ,-1 , 0
  4453.3     .07       0  4599.9    .035       0  4773.1     .07       0
  5042.5    .035       0  5166.2    .035       0  5170.2    .035       0
  5279.1     .07       0  5412.8      .1       0
Bank Sta=5166.2,5170.2
XS Rating Curve= 0 ,0
Exp/Cntr=0.3,0.1

Type RM Length L Ch R = 1 ,122     ,0,0,0
BEGIN DESCRIPTION:
Stream0474 0.0
END DESCRIPTION:
XS GIS Cut Line= 4
      1901560.41     13948621.62      1902186.77     13948635.57
      1902314.87     13948590.69      1902416.68     13948166.38
#Sta/Elev= 30
  4332.8 1811.79  4369.1 1805.51  4384.1 1795.99  4423.1 1795.49  4453.1  1792.9
  4535.9 1782.73    4551 1781.36  4669.2 1774.36  4788.1 1768.88  4804.2 1769.35
  4837.2 1766.32  4940.8 1762.81  5004.8 1757.87  5053.8 1757.28  5054.1 1756.78
  5057.8 1757.28  5094.4 1758.14  5220.5 1763.61  5237.4 1763.53  5251.4 1760.75
  5257.3 1762.24  5306.9 1764.23    5329 1767.26  5334.8 1767.33  5401.8 1776.85
  5445.8 1780.15  5458.1 1783.05  5488.9 1782.31  5501.6 1787.28  5531.4 1791.19
#Mann= 8 ,-1 , 0
  4332.8     .07       0  4535.9    .035       0    4551    .035       0
  5053.8    .035       0  5057.8    .035       0  5094.4    .035       0
    5329     .07       0  5334.8      .1       0
Bank Sta=5053.8,5057.8
XS Rating Curve= 0 ,0
Exp/Cntr=0.3,0.1

Chan Stop Cuts=-1
Use User Specified Reach Order=0
Composite Channel Slope=5