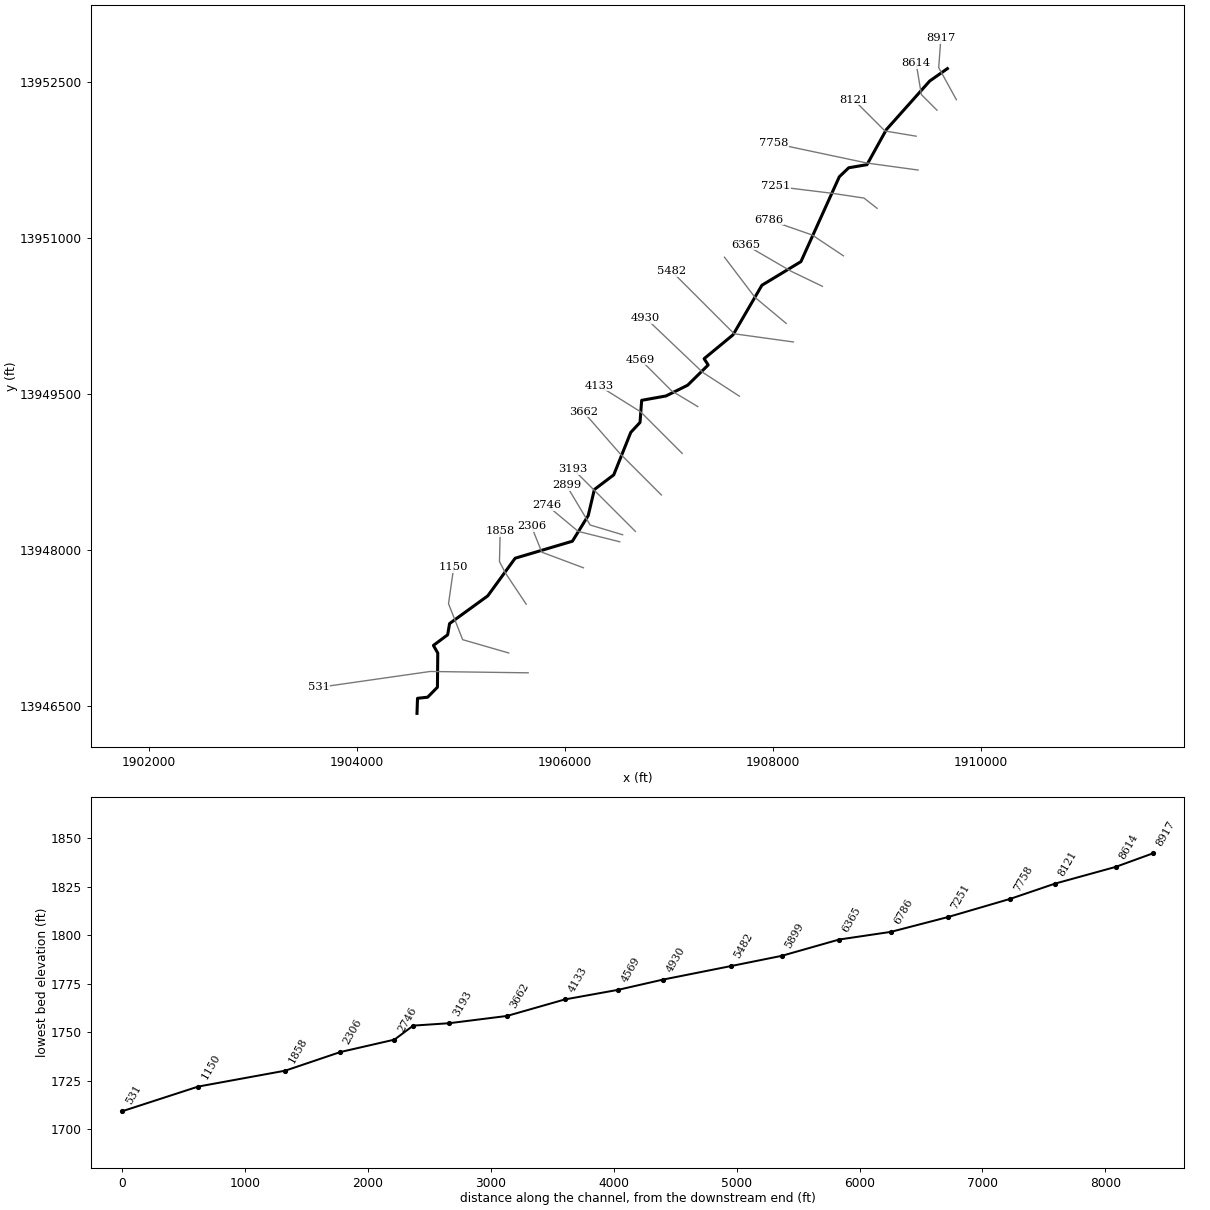
--- Stream0476.prj (project) ---

Proj Title=Stream0476 Base Level Engineering
Current Plan=p01
Default Exp/Contr=0.3,0.1
English Units
Geom File=g01
Flow File=f01
Plan File=p01
BEGIN DESCRIPTION:
Stream0476
END DESCRIPTION:

--- Stream0476.p01 (plan) ---

Plan Title=Multiple Run
Short Identifier=Multiple
Geom File=g01
Flow File=f01
Subcritical Flow
K Sum by GR= 0
Std Step Tol= 0.01
Critical Tol= 0.01
Num of Std Step Trials= 20
Max Error Tol= 0.3
Flow Tol Ratio= 0.001
Split Flow NTrial= 30
Split Flow Tol= 0.02
Split Flow Ratio= 0.02
Log Output Level= 0
Friction Slope Method= 1
Unsteady Friction Slope Method= 2
Unsteady Bridges Friction Slope Method= 1
Parabolic Critical Depth
Global Vel Dist=  1 , 1 , 1
Global Log Level= 0
CheckData=True
Encroach Param= -1, 0, 0, 0
BEGIN DESCRIPTION:
Multiple Run
END DESCRIPTION:

--- Stream0476.f01 (steady flow) ---

Flow Title=Multiple
Number of Profiles=7
Profile Names=10-year,25-year,50-year,1pct_min,100-year,1pct_plu,500-year
River Rch & RM= Stream0476,Reach-1,8917
    1226    2105    2948    1996    3983    7948    7179
River Rch & RM= Stream0476,Reach-1,4930
    1810    3171    4500    3082    6150   12270   11350
Boundary for River Rch & Prof#=Stream0476,Reach-1,1
Up Type=0
Dn Type=3
Dn Slope=0.005
Boundary for River Rch & Prof#=Stream0476,Reach-1,2
Up Type=0
Dn Type=3
Dn Slope=0.005
Boundary for River Rch & Prof#=Stream0476,Reach-1,3
Up Type=0
Dn Type=3
Dn Slope=0.005
Boundary for River Rch & Prof#=Stream0476,Reach-1,4
Up Type=0
Dn Type=3
Dn Slope=0.005
Boundary for River Rch & Prof#=Stream0476,Reach-1,5
Up Type=0
Dn Type=3
Dn Slope=0.005
Boundary for River Rch & Prof#=Stream0476,Reach-1,6
Up Type=0
Dn Type=3
Dn Slope=0.005
Boundary for River Rch & Prof#=Stream0476,Reach-1,7
Up Type=0
Dn Type=3
Dn Slope=0.005

--- Stream0476.g01 (geometry) ---

Geom Title=Existing Conditions

River Reach=Stream0476,Reach-1
Reach XY= 30
      1909675.00     13952625.00      1909504.61     13952505.16
      1909088.30     13952038.35      1908901.93     13951701.14
      1908726.46     13951671.46      1908635.75     13951584.71
      1908266.87     13950768.93      1907891.64     13950541.71
      1907614.24     13950065.32      1907335.72     13949835.41
      1907375.00     13949775.00      1907177.43     13949580.52
      1906969.14     13949477.07      1906735.32     13949435.18
      1906719.53     13949222.55      1906630.85     13949127.29
      1906466.98     13948718.66      1906280.52     13948577.44
      1906221.38     13948326.50      1906069.42     13948080.58
      1905518.93     13947916.87      1905255.16     13947554.61
      1904888.34     13947288.60      1904869.74     13947180.48
      1904732.79     13947078.43      1904774.81     13947005.02
      1904771.47     13946676.45      1904677.38     13946580.54
      1904579.98     13946569.97      1904575.00     13946425.00

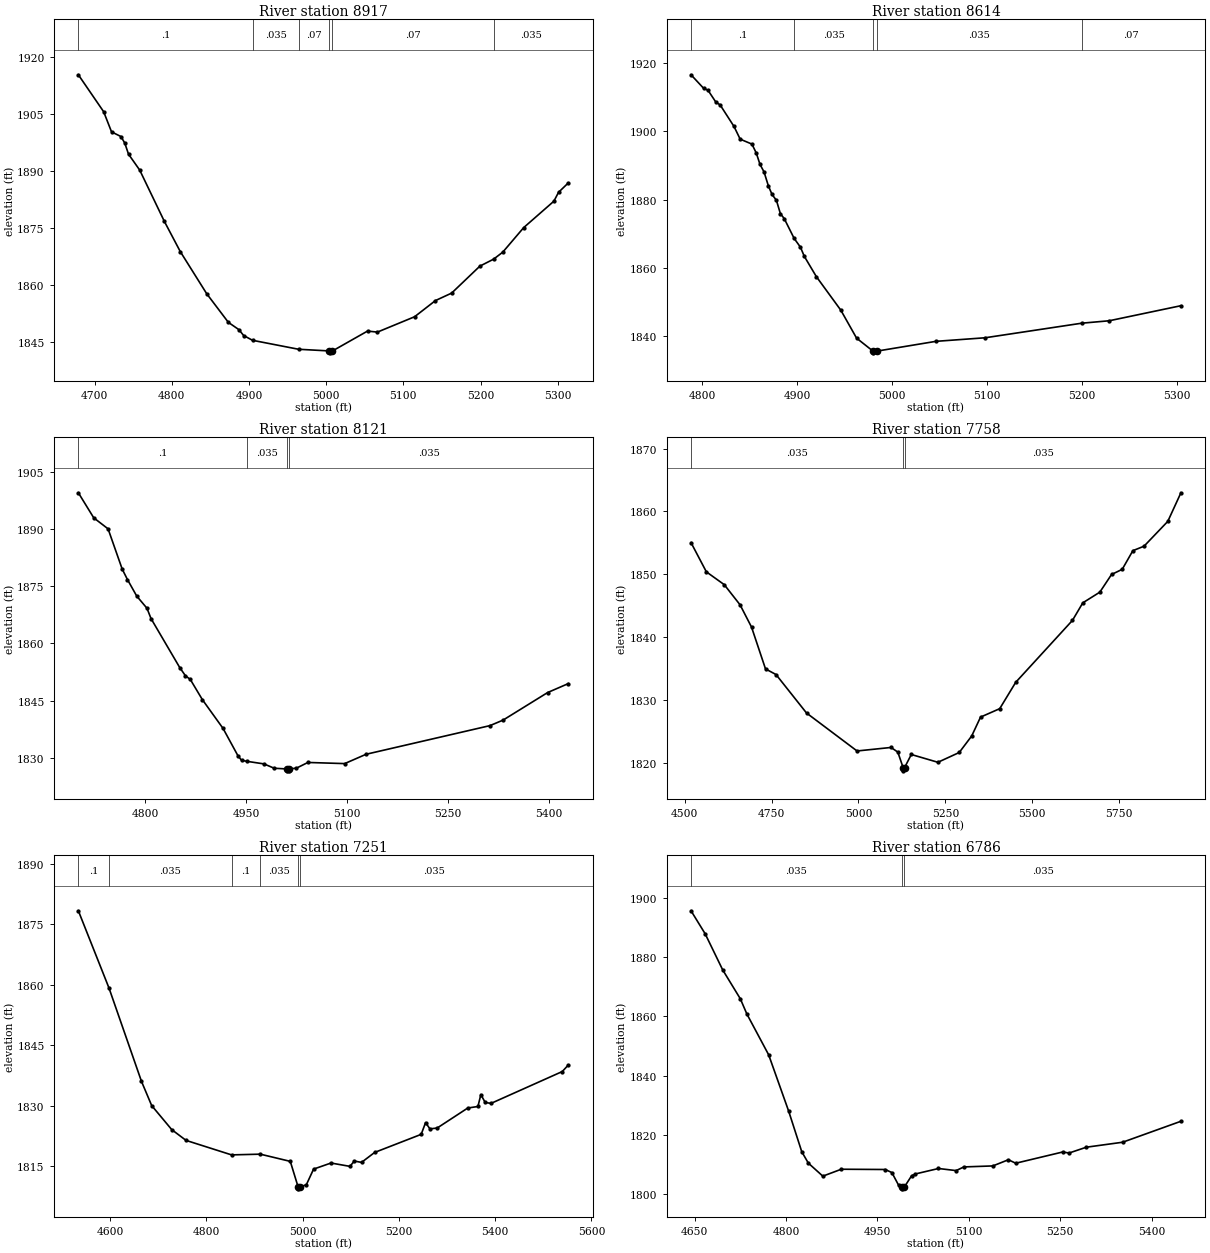
Type RM Length L Ch R = 1,8917,303,303,303
BEGIN DESCRIPTION:
Stream0476 16.1
END DESCRIPTION:
XS GIS Cut Line= 3
      1909761.69     13952325.73      1909591.55     13952634.76
      1909612.38     13952916.02
#Sta/Elev= 30
  4678.9 1915.32  4711.7 1905.59  4721.9 1900.29  4734.1 1899.06  4739.1 1897.32
  4743.9 1894.42  4758.4 1890.23  4790.4 1876.70  4811.0 1868.76  4845.2 1857.68
  4873.3 1850.13  4886.9 1848.22  4893.1 1846.67  4904.6 1845.41  4964.3 1843.05
  5004.2 1842.61  5004.4 1842.11  5008.2 1842.61  5053.6 1847.84  5066.4 1847.57
  5114.6 1851.61  5141.6 1855.87  5162.6 1857.84  5199.2 1864.94  5217.0 1866.78
  5228.9 1868.63  5256.0 1875.09  5295.1 1882.04  5301.1 1884.37  5313.7 1886.84
#Mann=6,-1,0
  4678.9     0.1       0  4904.6   0.035       0  4964.3    0.07       0
  5004.2    0.05       0  5008.2    0.07       0  5217.0   0.035       0
Bank Sta=5004.2,5008.2
Exp/Cntr=0.3,0.1

Type RM Length L Ch R = 1,8614,493,493,493
BEGIN DESCRIPTION:
Stream0476 16.0
END DESCRIPTION:
XS GIS Cut Line= 3
      1909574.99     13952225.01      1909425.00     13952375.00
      1909374.99     13952675.04
#Sta/Elev= 30
  4788.1 1916.56  4801.4 1912.59  4806.0 1912.03  4814.4 1908.50  4818.7 1907.77
  4833.4 1901.43  4839.9 1897.71  4852.3 1896.26  4856.9 1893.63  4860.8 1890.32
  4865.1 1888.09  4869.6 1884.05  4873.5 1881.51  4878.1 1879.80  4882.3 1875.88
  4886.3 1874.47  4896.8 1868.64  4903.4 1866.09  4907.5 1863.39  4920.2 1857.45
  4946.0 1847.62  4962.6 1839.44  4979.9 1835.64  4980.1 1835.14  4983.9 1835.64
  5046.3 1838.51  5098.0 1839.55  5199.9 1843.82  5228.8 1844.53  5304.4 1848.94
#Mann=5,-1,0
  4788.1     0.1       0  4896.8   0.035       0  4979.9   0.035       0
  4983.9   0.035       0  5199.9    0.07       0
Bank Sta=4979.9,4983.9
Exp/Cntr=0.3,0.1

Type RM Length L Ch R = 1,8121,363,363,363
BEGIN DESCRIPTION:
Stream0476 15.0
END DESCRIPTION:
XS GIS Cut Line= 3
      1909375.00     13951975.00      1909075.00     13952025.00
      1908775.00     13952325.00
#Sta/Elev= 30
  4700.2 1899.54  4723.1 1892.96  4744.4 1890.07  4765.4 1879.50  4773.2 1876.76
  4787.0 1872.42  4802.2 1869.23  4808.3 1866.50  4850.9 1853.67  4859.3 1851.53
  4866.7 1850.52  4884.6 1845.23  4915.4 1837.66  4937.4 1830.53  4942.8 1829.31
  4950.4 1829.05  4976.2 1828.36  4991.4 1827.22  5009.8 1827.04  5010.1 1826.54
  5013.6 1826.54  5013.8 1827.04  5024.5 1827.25  5041.5 1828.74  5096.2 1828.44
  5128.0 1830.89  5312.2 1838.41  5331.7 1839.86  5397.9 1847.09  5428.6 1849.44
#Mann=4,-1,0
  4700.2     0.1       0  4950.4   0.035       0  5009.8   0.035       0
  5013.8   0.035       0
Bank Sta=5009.8,5013.8
Exp/Cntr=0.3,0.1

Type RM Length L Ch R = 1,7758,507,507,507
BEGIN DESCRIPTION:
Stream0476 14.0
END DESCRIPTION:
XS GIS Cut Line= 3
      1909393.20     13951649.60      1908903.92     13951716.54
      1908007.39     13951906.15
#Sta/Elev= 30
  4518.0 1855.03  4562.2 1850.38  4613.7 1848.34  4659.1 1845.14  4692.2 1841.59
  4732.4 1834.94  4762.7 1834.04  4850.5 1827.92  4995.9 1821.88  5093.8 1822.44
  5113.3 1821.70  5128.6 1819.22  5128.9 1818.72  5132.6 1819.22  5152.1 1821.32
  5228.7 1820.08  5290.1 1821.64  5326.0 1824.27  5351.4 1827.27  5406.6 1828.61
  5452.6 1832.80  5616.0 1842.66  5645.8 1845.45  5694.8 1847.15  5728.5 1849.96
  5759.2 1850.78  5789.9 1853.75  5822.0 1854.46  5890.4 1858.41  5928.2 1862.96
#Mann=3,-1,0
  4518.0   0.035       0  5128.6   0.035       0  5132.6   0.035       0
Bank Sta=5128.6,5132.6
Exp/Cntr=0.3,0.1

Type RM Length L Ch R = 1,7251,465,465,465
BEGIN DESCRIPTION:
Stream0476 13.0
END DESCRIPTION:
XS GIS Cut Line= 4
      1908998.93     13951281.57      1908873.58     13951379.96
      1908575.00     13951425.00      1908022.44     13951492.66
#Sta/Elev= 30
  4533.9 1878.40  4597.6 1859.21  4665.1 1836.03  4686.3 1830.02  4728.0 1824.05
  4757.7 1821.38  4852.3 1817.78  4912.0 1817.96  4974.3 1816.17  4990.5 1809.85
  4990.7 1809.35  4994.5 1809.85  5007.6 1810.35  5022.7 1814.25  5058.9 1815.76
  5098.3 1814.93  5107.3 1816.25  5122.4 1815.92  5149.6 1818.39  5246.3 1822.88
  5255.4 1825.79  5264.5 1824.24  5279.5 1824.45  5343.1 1829.42  5364.2 1829.80
  5370.3 1832.75  5379.3 1830.80  5391.4 1830.57  5539.5 1838.48  5551.9 1840.09
#Mann=6,-1,0
  4533.9     0.1       0  4597.6   0.035       0  4852.3     0.1       0
  4912.0   0.035       0  4990.5   0.035       0  4994.5   0.035       0
Bank Sta=4990.5,4994.5
Exp/Cntr=0.3,0.1

Type RM Length L Ch R = 1,6786,421,421,421
BEGIN DESCRIPTION:
Stream0476 12.0
END DESCRIPTION:
XS GIS Cut Line= 3
      1908675.00     13950825.00      1908375.00     13951025.00
      1907956.33     13951170.85
#Sta/Elev= 30
  4644.1 1895.75  4667.3 1887.97  4696.1 1875.75  4725.0 1865.99  4735.8 1860.82
  4771.5 1847.04  4804.3 1828.01  4825.8 1814.27  4836.6 1810.41  4860.4 1806.00
  4890.7 1808.34  4962.9 1808.25  4973.7 1807.21  4984.6 1802.99  4989.8 1802.21
  4990.0 1801.71  4993.8 1802.21  5006.0 1806.11  5012.4 1806.75  5050.2 1808.59
  5079.1 1807.88  5091.8 1809.12  5139.4 1809.46  5164.9 1811.55  5176.9 1810.37
  5253.8 1814.16  5264.6 1813.83  5292.8 1815.79  5352.3 1817.47  5448.0 1824.56
#Mann=3,-1,0
  4644.1   0.035       0  4989.8   0.035       0  4993.8   0.035       0
Bank Sta=4989.8,4993.8
Exp/Cntr=0.3,0.1

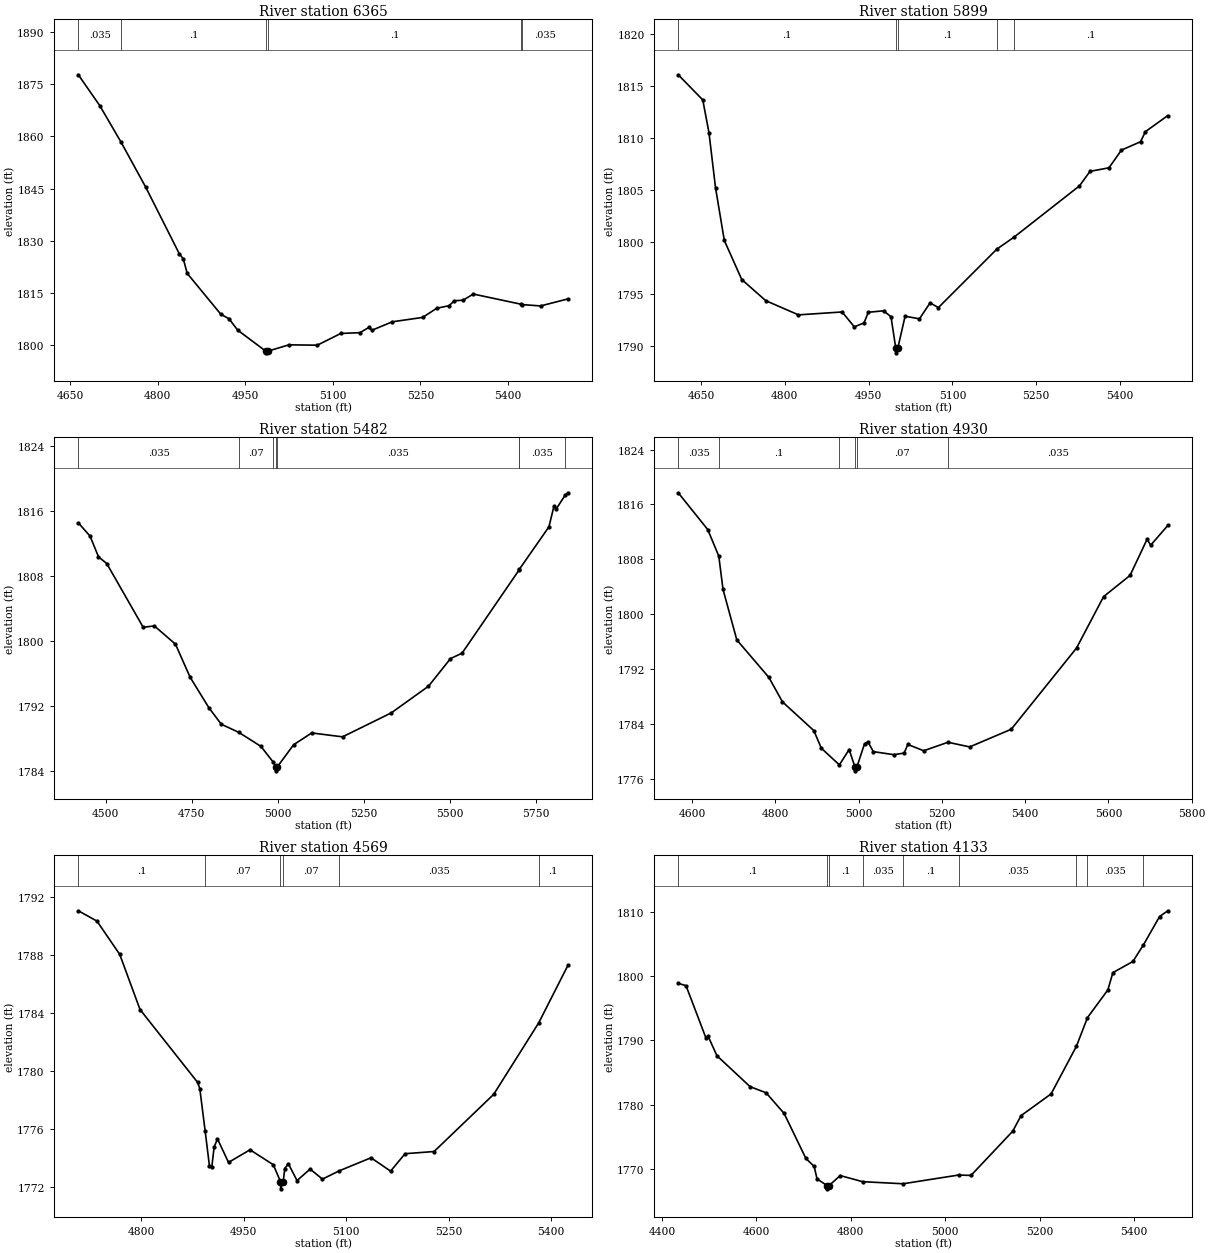
Type RM Length L Ch R = 1,6365,466,466,466
BEGIN DESCRIPTION:
Stream0476 11.0
END DESCRIPTION:
XS GIS Cut Line= 3
      1908472.78     13950531.81      1908175.00     13950675.00
      1907735.58     13950930.47
#Sta/Elev= 30
  4663.9 1877.69  4700.6 1868.83  4737.2 1858.29  4779.2 1845.43  4837.1 1826.17
  4843.7 1824.79  4850.4 1820.61  4908.1 1808.84  4922.0 1807.58  4936.9 1804.29
  4984.9 1798.27  4985.1 1797.77  4988.9 1798.27  5024.7 1800.07  5073.3 1799.97
  5113.5 1803.34  5146.4 1803.57  5161.8 1805.09  5167.0 1804.27  5201.7 1806.69
  5253.7 1807.95  5278.0 1810.59  5298.9 1811.31  5308.0 1812.73  5323.1 1812.91
  5340.5 1814.67  5422.7 1811.73  5424.1 1811.64  5455.8 1811.25  5502.6 1813.27
#Mann=6,-1,0
  4663.9   0.035       0  4737.2     0.1       0  4984.9   0.035       0
  4988.9     0.1       0  5422.7    0.07       0  5424.1   0.035       0
Bank Sta=4984.9,4988.9
Exp/Cntr=0.3,0.1

Type RM Length L Ch R = 1,5899,417,417,417
BEGIN DESCRIPTION:
Stream0476 10.0
END DESCRIPTION:
XS GIS Cut Line= 3
      1908124.99     13950175.01      1907825.00     13950425.00
      1907531.57     13950811.54
#Sta/Elev= 30
  4609.5 1816.05  4653.4 1813.64  4664.5 1810.49  4676.2 1805.22  4691.9 1800.17
  4723.1 1796.42  4766.1 1794.39  4824.6 1793.03  4902.7 1793.31  4924.5 1791.88
  4941.8 1792.26  4949.6 1793.28  4976.9 1793.42  4990.1 1792.85  4998.5 1789.89
  4998.7 1789.39  5002.5 1789.89  5015.3 1792.90  5041.0 1792.65  5060.0 1794.18
  5074.9 1793.73  5179.6 1799.34  5210.4 1800.49  5327.3 1805.40  5346.1 1806.79
  5380.0 1807.13  5402.4 1808.83  5436.5 1809.63  5445.3 1810.60  5485.3 1812.14
#Mann=5,-1,0
  4609.5     0.1       0  4998.5    0.05       0  5002.5     0.1       0
  5179.6    0.07       0  5210.4     0.1       0
Bank Sta=4998.5,5002.5
Exp/Cntr=0.3,0.1

Type RM Length L Ch R = 1,5482,552,552,552
BEGIN DESCRIPTION:
Stream0476 9.0
END DESCRIPTION:
XS GIS Cut Line= 3
      1908194.52     13949996.35      1907625.00     13950075.00
      1907024.97     13950675.03
#Sta/Elev= 30
  4420.3 1814.56  4454.4 1812.93  4478.9 1810.39  4502.9 1809.56  4608.9 1801.72
  4641.3 1801.89  4702.8 1799.64  4745.2 1795.59  4799.7 1791.84  4836.0 1789.80
  4886.5 1788.81  4951.1 1787.08  4986.5 1785.17  4995.0 1784.57  4995.3 1784.07
  4999.0 1784.57  5046.1 1787.27  5098.9 1788.73  5188.5 1788.25  5330.4 1791.20
  5438.3 1794.47  5502.4 1797.87  5536.1 1798.54  5701.4 1808.74  5702.9 1808.87
  5788.6 1814.07  5803.1 1816.59  5809.8 1816.27  5836.2 1817.99  5843.8 1818.26
#Mann=8,-1,0
  4420.3   0.035       0  4886.5    0.07       0  4986.5   0.035       0
  4995.0   0.035       0  4999.0   0.035       0  5701.4     0.1       0
  5702.9   0.035       0  5836.2   0.063       0
Bank Sta=4995,4999
Exp/Cntr=0.3,0.1

Type RM Length L Ch R = 1,4930,361,361,361
BEGIN DESCRIPTION:
Stream0476 8.0
END DESCRIPTION:
XS GIS Cut Line= 3
      1907674.96     13949475.02      1907322.04     13949704.19
      1906775.01     13950224.99
#Sta/Elev= 30
  4566.6 1817.70  4637.4 1812.34  4664.0 1808.46  4674.2 1803.59  4707.3 1796.23
  4784.4 1790.75  4816.9 1787.19  4892.4 1782.99  4910.3 1780.42  4953.7 1777.99
  4977.2 1780.23  4991.4 1777.62  4991.6 1777.12  4995.4 1777.62  5014.2 1781.08
  5022.4 1781.34  5035.3 1779.92  5084.5 1779.48  5109.3 1779.71  5118.1 1780.97
  5156.3 1780.05  5214.6 1781.29  5266.7 1780.61  5366.6 1783.19  5523.4 1795.04
  5588.5 1802.55  5652.0 1805.64  5692.9 1810.91  5701.6 1810.05  5742.7 1812.93
#Mann=6,-1,0
  4566.6   0.035       0  4664.0     0.1       0  4953.7    0.07       0
  4991.4    0.05       0  4995.4    0.07       0  5214.6   0.035       0
Bank Sta=4991.4,4995.4
Exp/Cntr=0.3,0.1

Type RM Length L Ch R = 1,4569,436,436,436
BEGIN DESCRIPTION:
Stream0476 7.0
END DESCRIPTION:
XS GIS Cut Line= 3
      1907275.04     13949374.98      1907025.00     13949525.00
      1906724.97     13949825.03
#Sta/Elev= 30
  4708.4 1791.05  4735.6 1790.34  4768.9 1788.05  4798.6 1784.25  4882.7 1779.24
  4886.0 1778.81  4893.8 1775.90  4900.2 1773.45  4903.5 1773.38  4907.0 1774.78
  4911.9 1775.34  4928.0 1773.72  4959.5 1774.59  4993.5 1773.56  5004.0 1772.40
  5004.3 1771.90  5008.0 1772.40  5010.3 1773.30  5015.5 1773.63  5028.2 1772.47
  5047.3 1773.26  5065.4 1772.57  5089.9 1773.14  5136.4 1774.04  5165.0 1773.12
  5186.2 1774.32  5228.6 1774.47  5315.8 1778.41  5381.6 1783.33  5424.3 1787.29
#Mann=6,-1,0
  4708.4     0.1       0  4893.8    0.07       0  5004.0    0.05       0
  5008.0    0.07       0  5089.9   0.035       0  5381.6     0.1       0
Bank Sta=5004,5008
Exp/Cntr=0.3,0.1

Type RM Length L Ch R = 1,4133,471,471,471
BEGIN DESCRIPTION:
Stream0476 6.0
END DESCRIPTION:
XS GIS Cut Line= 3
      1907125.01     13948924.99      1906725.00     13949325.00
      1906325.00     13949575.00
#Sta/Elev= 30
  4434.3 1798.85  4450.8 1798.48  4492.7 1790.42  4497.5 1790.65  4516.3 1787.60
  4586.6 1782.79  4620.5 1781.84  4658.7 1778.63  4704.8 1771.64  4722.3 1770.41
  4728.4 1768.47  4749.8 1767.42  4750.0 1766.92  4753.8 1767.42  4777.5 1768.98
  4825.1 1768.03  4910.8 1767.71  5028.8 1769.07  5054.6 1769.00  5143.0 1775.87
  5160.7 1778.29  5224.4 1781.67  5277.9 1789.05  5301.5 1793.52  5344.7 1797.83
  5355.3 1800.51  5397.7 1802.24  5420.1 1804.83  5454.3 1809.23  5471.7 1810.12
#Mann=9,-1,0
  4434.3     0.1       0  4749.8    0.05       0  4753.8     0.1       0
  4825.1   0.035       0  4910.8     0.1       0  5028.8   0.035       0
  5277.9     0.1       0  5301.5   0.035       0  5420.1    0.07       0
Bank Sta=4749.8,4753.8
Exp/Cntr=0.3,0.1

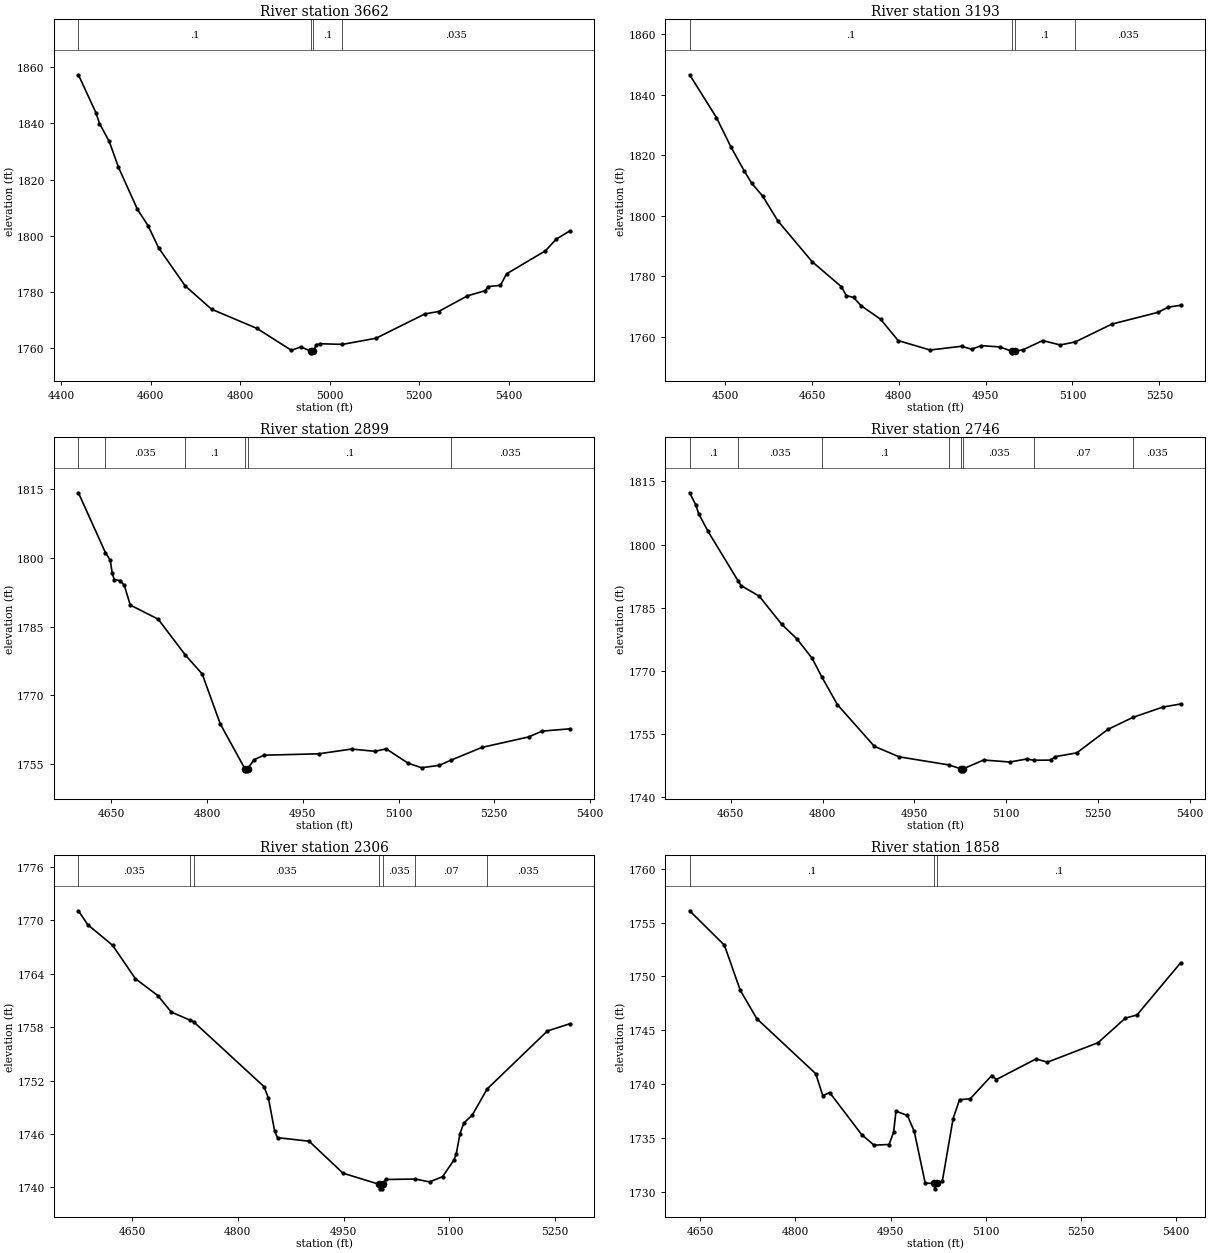
Type RM Length L Ch R = 1,3662,469,469,469
BEGIN DESCRIPTION:
Stream0476 5.0
END DESCRIPTION:
XS GIS Cut Line= 3
      1906925.01     13948524.99      1906525.00     13948925.00
      1906175.01     13949324.99
#Sta/Elev= 30
  4438.9 1857.26  4477.8 1843.83  4486.0 1839.94  4507.7 1833.58  4528.4 1824.38
  4570.8 1809.39  4594.4 1803.66  4618.0 1795.76  4677.4 1782.23  4736.3 1773.92
  4838.1 1767.08  4914.5 1759.32  4936.2 1760.54  4959.0 1758.92  4959.3 1758.42
  4963.3 1758.92  4970.2 1761.25  4978.7 1761.66  5028.4 1761.42  5103.7 1763.61
  5213.1 1772.27  5243.3 1773.10  5307.9 1778.68  5347.0 1780.49  5354.9 1781.98
  5381.6 1782.41  5395.3 1786.51  5482.2 1794.70  5506.4 1798.86  5536.1 1801.72
#Mann=4,-1,0
  4438.9     0.1       0  4959.0    0.05       0  4963.3     0.1       0
  5028.4   0.035       0
Bank Sta=4959,4963.3
Exp/Cntr=0.3,0.1

Type RM Length L Ch R = 1,3193,294,294,294
BEGIN DESCRIPTION:
Stream0476 4.0
END DESCRIPTION:
XS GIS Cut Line= 3
      1906674.98     13948175.02      1906275.00     13948575.00
      1906075.00     13948775.00
#Sta/Elev= 30
  4438.7 1846.64  4484.9 1832.51  4510.3 1822.65  4533.4 1814.70  4546.1 1810.72
  4564.9 1806.49  4590.9 1798.36  4650.0 1784.89  4700.7 1776.57  4709.4 1773.62
  4721.9 1773.00  4734.6 1770.31  4768.6 1765.79  4798.8 1758.75  4854.0 1755.62
  4908.6 1756.87  4925.6 1755.89  4942.5 1757.06  4974.6 1756.65  4995.5 1755.19
  4995.8 1754.69  4999.9 1755.19  5015.2 1755.74  5048.6 1758.76  5078.8 1757.29
  5104.8 1758.30  5167.9 1764.19  5248.0 1768.09  5265.0 1769.78  5287.2 1770.43
#Mann=4,-1,0
  4438.7     0.1       0  4995.5    0.05       0  4999.9     0.1       0
  5104.8   0.035       0
Bank Sta=4995.5,4999.9
Exp/Cntr=0.3,0.1

Type RM Length L Ch R = 1,2899,153,153,153
BEGIN DESCRIPTION:
Mapping XS 6bf160d4
END DESCRIPTION:
XS GIS Cut Line= 3
      1906552.46     13948142.56      1906239.92     13948236.37
      1906012.63     13948616.72
#Sta/Elev= 30
  4598.6 1814.28  4640.9 1801.19  4648.4 1799.57  4651.6 1796.68  4654.7 1795.27
  4664.1 1795.06  4670.4 1794.04  4679.8 1789.72  4723.6 1786.62  4766.2 1778.76
  4792.5 1774.64  4820.7 1763.74  4859.2 1753.94  4859.5 1753.44  4863.3 1753.44
  4863.6 1753.94  4874.0 1755.88  4889.2 1756.86  4975.3 1757.17  5026.5 1758.21
  5063.1 1757.71  5080.6 1758.25  5115.1 1755.11  5136.1 1754.12  5164.1 1754.65
  5182.3 1755.78  5230.5 1758.56  5303.9 1760.86  5324.8 1762.13  5368.0 1762.63
#Mann=6,-1,0
  4598.6     0.1       0  4640.9   0.035       0  4766.2     0.1       0
  4859.2    0.05       0  4863.6     0.1       0  5182.3   0.035       0
Bank Sta=4859.2,4863.6
Exp/Cntr=0.3,0.1

Type RM Length L Ch R = 1,2746,440,440,440
BEGIN DESCRIPTION:
Stream0476 3.0
END DESCRIPTION:
XS GIS Cut Line= 3
      1906524.96     13948075.01      1906125.00     13948175.00
      1905825.06     13948424.95
#Sta/Elev= 30
  4582.9 1812.30  4592.7 1809.48  4597.6 1807.34  4613.0 1803.11  4662.0 1791.38
  4666.9 1790.24  4696.5 1787.74  4733.6 1781.00  4758.3 1777.56  4783.1 1772.95
  4798.7 1768.58  4824.2 1761.98  4884.6 1752.06  4925.4 1749.54  5006.0 1747.64
  5025.9 1746.72  5026.2 1746.22  5030.0 1746.22  5030.3 1746.72  5063.2 1748.79
  5106.2 1748.32  5133.5 1749.03  5145.3 1748.74  5172.6 1748.77  5180.4 1749.60
  5215.5 1750.49  5266.4 1756.07  5307.3 1758.93  5356.1 1761.37  5385.6 1762.12
#Mann=8,-1,0
  4582.9     0.1       0  4662.0   0.035       0  4798.7     0.1       0
  5006.0   0.035       0  5025.9    0.05       0  5030.3   0.035       0
  5145.3    0.07       0  5307.3   0.035       0
Bank Sta=5025.9,5030.3
Exp/Cntr=0.3,0.1

Type RM Length L Ch R = 1,2306,448,448,448
BEGIN DESCRIPTION:
Stream0476 2.0
END DESCRIPTION:
XS GIS Cut Line= 3
      1906175.04     13947824.99      1905775.00     13947975.00
      1905675.00     13948225.00
#Sta/Elev= 30
  4573.9 1771.08  4587.2 1769.51  4622.3 1767.21  4654.7 1763.45  4686.4 1761.56
  4705.6 1759.70  4732.2 1758.79  4737.2 1758.61  4837.0 1751.33  4843.3 1750.05
  4852.1 1746.35  4856.2 1745.59  4901.0 1745.19  4949.1 1741.60  5000.7 1740.34
  5001.0 1739.84  5004.8 1739.84  5005.1 1740.34  5009.4 1740.89  5051.6 1740.94
  5071.9 1740.62  5090.2 1741.20  5106.3 1743.07  5109.6 1743.73  5115.0 1746.05
  5120.4 1747.24  5132.2 1748.11  5153.5 1751.06  5238.8 1757.57  5270.4 1758.38
#Mann=7,-1,0
  4573.9   0.035       0  4732.2     0.1       0  4737.2   0.035       0
  5000.7   0.035       0  5005.1   0.035       0  5051.6    0.07       0
  5153.5   0.035       0
Bank Sta=5000.7,5005.1
Exp/Cntr=0.3,0.1

Type RM Length L Ch R = 1,1858,708,708,708
BEGIN DESCRIPTION:
Stream0476 1.0
END DESCRIPTION:
XS GIS Cut Line= 4
      1905624.98     13947475.03      1905425.00     13947775.00
      1905368.15     13947884.21      1905375.00     13948174.99
#Sta/Elev= 30
  4633.2 1756.09  4688.0 1752.89  4713.0 1748.70  4739.1 1746.06  4832.0 1740.95
  4843.1 1738.91  4853.9 1739.20  4904.4 1735.29  4923.9 1734.31  4947.6 1734.37
  4954.8 1735.51  4958.5 1737.47  4976.5 1737.07  4987.3 1735.59  5004.6 1730.78
  5019.2 1730.75  5019.5 1730.25  5023.8 1730.75  5031.7 1730.99  5048.6 1736.78
  5058.7 1738.53  5075.6 1738.62  5109.5 1740.78  5116.8 1740.41  5179.3 1742.32
  5197.3 1742.02  5277.1 1743.83  5320.3 1746.12  5338.4 1746.40  5407.7 1751.28
#Mann=3,-1,0
  4633.2     0.1       0  5019.2    0.05       0  5023.8     0.1       0
Bank Sta=5019.2,5023.8
Exp/Cntr=0.3,0.1

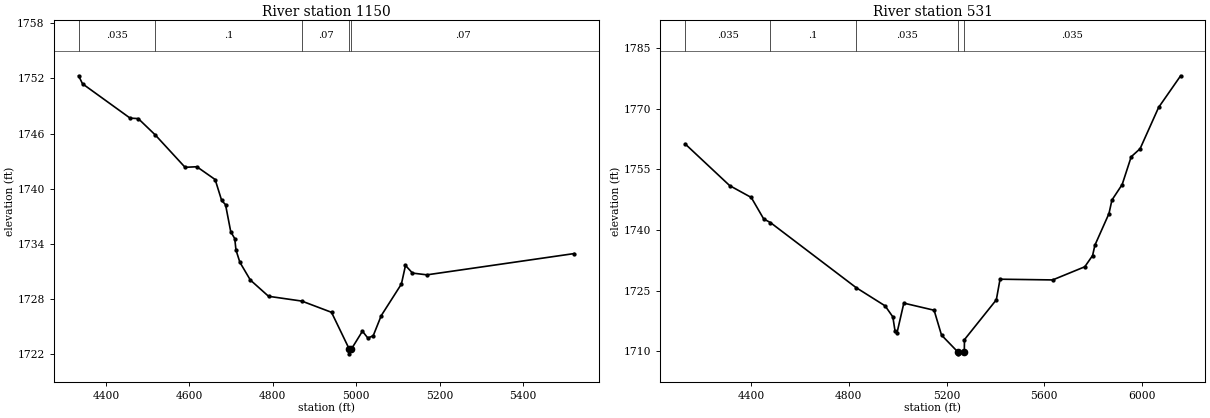
Type RM Length L Ch R = 1,1150,619,619,619
BEGIN DESCRIPTION:
Stream0476 0.0
END DESCRIPTION:
XS GIS Cut Line= 4
      1905457.03     13947005.69      1905014.24     13947133.55
      1904878.14     13947479.67      1904928.41     13947830.99
#Sta/Elev= 30
  4334.6 1752.27  4343.9 1751.40  4458.0 1747.67  4477.5 1747.62  4518.6 1745.83
  4589.7 1742.33  4618.0 1742.39  4661.8 1741.00  4677.4 1738.73  4686.7 1738.27
  4699.2 1735.33  4708.8 1734.58  4711.7 1733.35  4721.1 1732.01  4746.1 1730.09
  4789.8 1728.32  4869.5 1727.80  4940.7 1726.58  4983.4 1722.57  4983.8 1722.07
  4988.1 1722.57  5014.8 1724.53  5027.7 1723.79  5040.6 1724.03  5059.9 1726.22
  5108.2 1729.65  5118.0 1731.67  5134.8 1730.84  5169.4 1730.65  5522.3 1732.96
#Mann=5,-1,0
  4334.6   0.035       0  4518.6     0.1       0  4869.5    0.07       0
  4983.4    0.05       0  4988.1    0.07       0
Bank Sta=4983.4,4988.1
Exp/Cntr=0.3,0.1

Type RM Length L Ch R = 1,531,0,0,0
BEGIN DESCRIPTION:
Stream0476 0.1
END DESCRIPTION:
XS GIS Cut Line= 3
      1905644.23     13946814.90      1904701.52     13946827.92
      1903628.56     13946674.27
#Sta/Elev= 30
  4130.7 1761.32  4313.0 1750.99  4401.2 1748.06  4452.2 1742.74  4479.6 1741.85
  4830.1 1725.75  4948.8 1721.23  4980.3 1718.51  4989.3 1715.02  4997.5 1714.59
  5025.3 1721.91  5149.1 1720.15  5179.4 1714.00  5245.6 1709.86  5246.1 1709.36
  5272.6 1709.86  5273.3 1712.88  5403.6 1722.73  5418.8 1727.83  5634.0 1727.65
  5765.5 1730.91  5797.3 1733.69  5806.7 1736.24  5864.3 1744.07  5876.4 1747.42
  5918.3 1751.26  5955.2 1758.13  5991.6 1760.12  6067.3 1770.34  6157.4 1778.17
#Mann=5,-1,0
  4130.7   0.035       0  4479.6     0.1       0  4830.1   0.035       0
  5245.6   0.035       0  5272.6   0.035       0
Bank Sta=5245.6,5272.6
Exp/Cntr=0.3,0.1

Chan Stop Cuts=-1