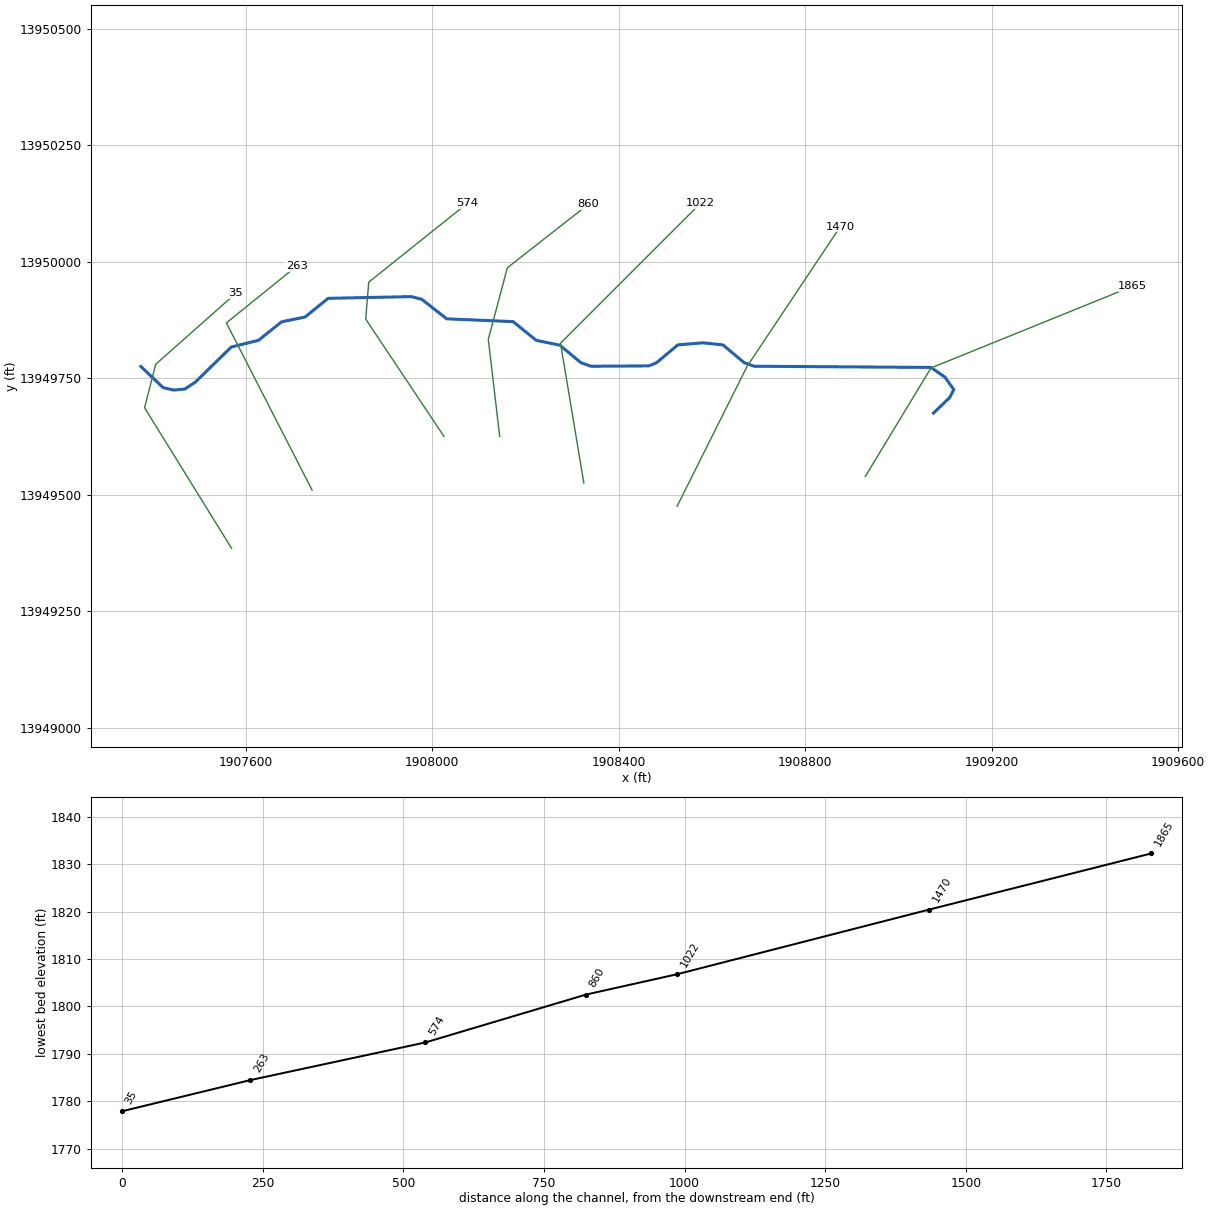
--- Stream0478.prj (project) ---

Proj Title=Stream0478 Base Level Engineering
Current Plan=p01
Default Exp/Contr=0.3,0.1
English Units
Geom File=g01
Flow File=f01
Plan File=p01
Y Axis Title=Elevation
X Axis Title(PF)=Main Channel Distance
X Axis Title(XS)=Station
BEGIN DESCRIPTION:
Stream0478
END DESCRIPTION:
DSS Export Rating Curves= 0
DSS Export Rating Curve Sorted= 0
DSS Export Volume Flow Curves= 0
DXF OffsetX= 0
DXF OffsetY= 0
DXF ScaleX= 1
DXF ScaleY= 10

--- Stream0478.p01 (plan) ---

Plan Title=Multiple Run
Short Identifier=Multiple
Geom File=g01
Flow File=f01
Subcritical Flow
K Sum by GR= 0
Std Step Tol= 0.01
Critical Tol= 0.01
Num of Std Step Trials= 20
Max Error Tol= 0.3
Flow Tol Ratio= 0.001
Split Flow NTrial= 30
Split Flow Tol= 0.02
Split Flow Ratio= 0.02
Log Output Level= 0
Friction Slope Method= 1
Unsteady Friction Slope Method= 2
Unsteady Bridges Friction Slope Method= 1
Parabolic Critical Depth
Global Vel Dist=  1 , 1 , 1
Global Log Level= 0
CheckData=True
Encroach Param= -1, 0, 0, 0
BEGIN DESCRIPTION:
Multiple Run
END DESCRIPTION:

--- Stream0478.f01 (steady flow) ---

Flow Title=Multiple
Program Version=4.10
Number of Profiles= 7
Profile Names=10-year,25-year,50-year,1pct_min,100-year,1pct_plu,500-year
River Rch & RM=Stream0478,Reach-1         ,1865
     402     642     856     555    1108    2211    1825
Boundary for River Rch & Prof#=Stream0478,Reach-1         , 1
Up Type= 0
Dn Type= 3
Dn Slope=0.005
Boundary for River Rch & Prof#=Stream0478,Reach-1         , 2
Up Type= 0
Dn Type= 3
Dn Slope=0.005
Boundary for River Rch & Prof#=Stream0478,Reach-1         , 3
Up Type= 0
Dn Type= 3
Dn Slope=0.005
Boundary for River Rch & Prof#=Stream0478,Reach-1         , 4
Up Type= 0
Dn Type= 3
Dn Slope=0.005
Boundary for River Rch & Prof#=Stream0478,Reach-1         , 5
Up Type= 0
Dn Type= 3
Dn Slope=0.005
Boundary for River Rch & Prof#=Stream0478,Reach-1         , 6
Up Type= 0
Dn Type= 3
Dn Slope=0.005
Boundary for River Rch & Prof#=Stream0478,Reach-1         , 7
Up Type= 0
Dn Type= 3
Dn Slope=0.005
DSS Import GetInterval= 0
DSS Import GetPeak= 0
DSS Import FillOption= 0

--- Stream0478.g01 (geometry) ---

Geom Title=Existing Conditions
Program Version=4.10

River Reach=Stream0478      ,Reach-1
Reach XY= 30
        1909075.       13949675.      1909109.67     13949708.38
      1909118.56     13949725.33      1909099.41     13949752.25
      1909069.51     13949772.98      1908690.22     13949775.52
      1908668.94     13949783.15       1908623.4      13949821.3
      1908580.03     13949825.81       1908526.6     13949821.29
      1908481.06     13949783.14      1908464.49     13949776.21
      1908340.22     13949775.49      1908318.93     13949783.09
      1908273.26     13949820.81      1908222.82     13949831.12
      1908173.44     13949871.24      1908030.94     13949877.27
      1907977.33     13949919.25      1907954.97     13949924.93
      1907776.55     13949921.25      1907727.18     13949881.12
      1907676.72     13949870.84      1907627.19      13949831.1
      1907568.95     13949816.84      1907491.68     13949741.27
      1907469.03     13949726.55      1907445.25     13949724.36
      1907422.65     13949729.57        1907375.       13949775.

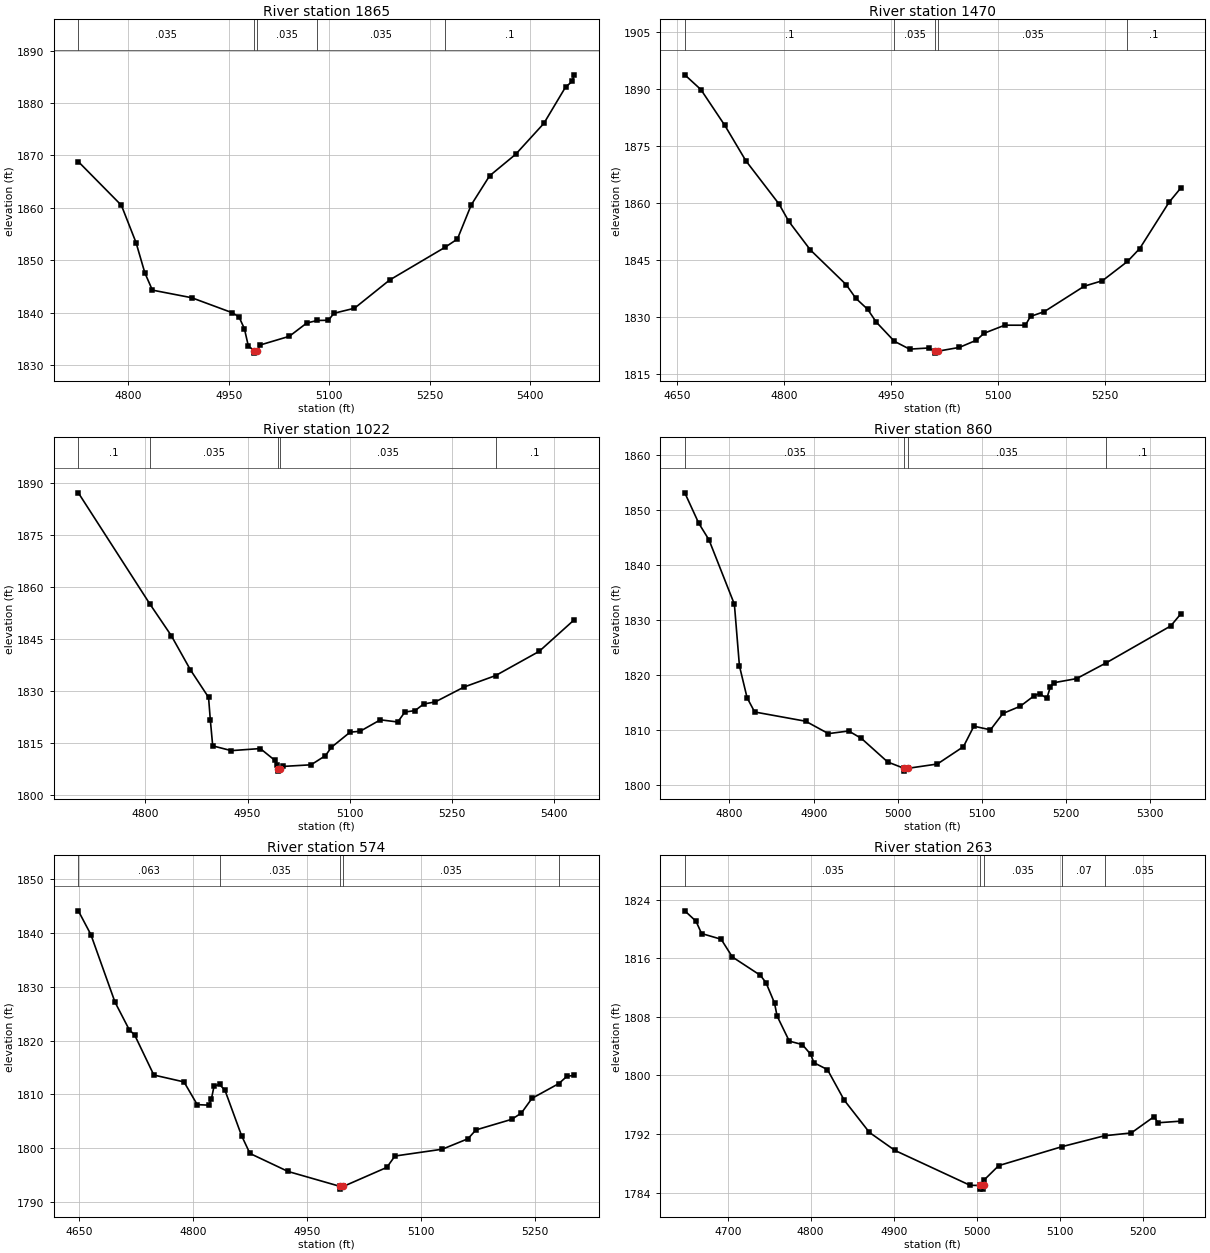
Type RM Length L Ch R = 1 ,1865    ,395,395,395
BEGIN DESCRIPTION:
Stream0478 4.0
END DESCRIPTION:
XS GIS Cut Line= 3
      1908928.56     13949538.75      1909069.59     13949771.79
      1909502.25     13949947.34
#Sta/Elev= 30
  4725.9  1868.8  4790.1 1860.47  4811.9 1853.37  4825.1 1847.57  4836.3 1844.29
  4894.9 1842.84  4954.9    1840  4965.4 1839.19  4973.5 1836.94  4979.4 1833.62
    4988 1832.77  4988.2 1832.27    4992 1832.77    4997 1833.82  5040.5 1835.48
  5066.6 1838.02  5082.3  1838.5  5098.8 1838.54    5107 1839.87  5137.6 1840.83
  5190.1 1846.22  5272.3 1852.43  5291.1 1854.03  5311.8 1860.56  5339.1 1866.09
  5377.9 1870.19    5420 1876.09  5452.3 1883.01  5462.1 1884.09  5465.2 1885.36
#Mann= 5 ,-1 , 0
  4725.9    .035       0    4988    .035       0    4992    .035       0
  5082.3    .035       0  5272.3      .1       0
Bank Sta=4988,4992
XS Rating Curve= 0 ,0
Exp/Cntr=0.3,0.1

Type RM Length L Ch R = 1 ,1470    ,448,448,448
BEGIN DESCRIPTION:
Stream0478 3.0
END DESCRIPTION:
XS GIS Cut Line= 3
      1908525.01     13949475.03        1908675.       13949775.
      1908874.98     13950074.97
#Sta/Elev= 30
  4660.4 1893.74    4683 1889.85  4716.6 1880.41  4746.1  1871.1  4792.6 1859.72
  4806.4 1855.13  4836.6 1847.62  4886.9 1838.47  4900.4 1834.88  4917.1 1831.96
    4929 1828.63  4954.5 1823.55  4975.9 1821.48  5002.5 1821.78  5011.4 1820.93
  5011.6 1820.43  5015.4 1820.93  5045.8 1821.94  5069.6 1823.83  5080.4 1825.66
  5109.5 1827.79  5138.4 1827.78  5145.6  1830.1  5164.8 1831.34    5221 1838.06
  5246.6 1839.51  5281.7 1844.58  5298.9 1847.98    5340 1860.16  5356.3 1863.87
#Mann= 5 ,-1 , 0
  4660.4      .1       0  4954.5    .035       0  5011.4    .035       0
  5015.4    .035       0  5281.7      .1       0
Bank Sta=5011.4,5015.4
XS Rating Curve= 0 ,0
Exp/Cntr=0.3,0.1

Type RM Length L Ch R = 1 ,1022    ,162,162,162
BEGIN DESCRIPTION:
Stream0478 2.0
END DESCRIPTION:
XS GIS Cut Line= 3
      1908325.01     13949524.97        1908275.       13949825.
      1908574.98     13950124.98
#Sta/Elev= 30
  4701.4  1887.2  4806.5 1855.08  4837.9 1845.96  4866.1 1836.05  4892.7 1828.11
  4895.3 1821.59  4898.8  1814.1  4926.1 1812.72  4968.7 1813.32    4990 1809.93
  4993.9 1808.57  4994.1  1807.3  4994.4  1806.8  4998.1  1807.3  5002.2 1808.16
  5043.3 1808.63  5064.5 1811.28    5073 1813.65  5100.6 1818.05  5115.4 1818.32
  5145.1 1821.62  5170.6    1821  5181.2 1823.88    5196 1824.28  5208.7 1826.19
  5225.7 1826.79  5268.1  1831.1  5314.4  1834.4  5378.4  1841.4  5429.8  1850.5
#Mann= 5 ,-1 , 0
  4701.4      .1       0  4806.5    .035       0  4994.1    .035       0
  4998.1    .035       0  5314.4      .1       0
Bank Sta=4994.1,4998.1
XS Rating Curve= 0 ,0
Exp/Cntr=0.3,0.1

Type RM Length L Ch R = 1 ,860     ,286,286,286
BEGIN DESCRIPTION:
Mapping XS a74d8310
END DESCRIPTION:
XS GIS Cut Line= 4
      1908144.58     13949625.18      1908120.14     13949833.16
        1908161.     13949986.83      1908334.59     13950122.93
#Sta/Elev= 30
  4746.9 1853.05  4763.5 1847.52  4775.6 1844.52  4805.8 1832.82  4811.8 1821.62
  4820.9 1815.83  4829.9 1813.25  4890.5 1811.57  4917.5 1809.32  4941.6  1809.8
  4956.8 1808.44  4987.9 1804.17  5007.5 1803.01  5007.8 1802.51  5011.5 1803.01
  5046.9  1803.8  5077.9 1806.95  5090.3 1810.67    5110 1810.01  5124.8 1812.98
  5145.5  1814.3    5162 1816.21  5168.3 1816.58    5177 1815.75  5181.2 1817.83
  5185.5 1818.57  5212.3 1819.31  5247.1 1822.14  5324.1 1828.87  5335.9 1831.02
#Mann= 4 ,-1 , 0
  4746.9    .035       0  5007.5    .035       0  5011.5    .035       0
  5247.1      .1       0
Bank Sta=5007.5,5011.5
XS Rating Curve= 0 ,0
Exp/Cntr=0.3,0.1

Type RM Length L Ch R = 1 ,574     ,311,311,311
BEGIN DESCRIPTION:
Stream0478 1.0
END DESCRIPTION:
XS GIS Cut Line= 4
      1908025.03     13949624.96      1907857.21     13949876.68
      1907863.71     13949955.97      1908075.03     13950125.02
#Sta/Elev= 30
  4648.8 1844.11  4665.3  1839.7  4697.1 1827.13  4715.7 1822.05    4723 1821.02
  4748.2  1813.6  4787.9 1812.32  4805.3  1808.1  4820.6    1808  4823.9 1809.11
  4827.5 1811.55  4834.7 1811.85  4841.9 1810.74  4863.6 1802.36  4874.7 1799.03
  4924.9 1795.68  4993.6  1792.9  4993.8  1792.4  4997.6  1792.9  5054.9 1796.44
  5065.6 1798.55    5128 1799.82  5161.7 1801.76  5172.2  1803.4  5219.3 1805.37
    5232 1806.53    5246 1809.27  5281.3 1812.01  5292.1 1813.38  5301.5 1813.52
#Mann= 5 ,-1 , 0
  4648.8    .063       0  4834.7    .035       0  4993.6    .035       0
  4997.6    .035       0  5281.3      .1       0
Bank Sta=4993.6,4997.6
XS Rating Curve= 0 ,0
Exp/Cntr=0.3,0.1

Type RM Length L Ch R = 1 ,263     ,228,228,228
BEGIN DESCRIPTION:
Stream0478 0.0
END DESCRIPTION:
XS GIS Cut Line= 3
       1907742.2     13949509.65      1907558.36     13949868.53
      1907709.46     13949990.64
#Sta/Elev= 30
  4648.3 1822.47  4661.8 1821.05  4668.5 1819.37  4692.1 1818.59  4705.6 1816.17
  4739.3 1813.67  4746.1 1812.67  4756.4 1809.89  4759.5 1808.11  4774.2 1804.68
  4789.9 1804.21    4800 1802.88  4803.9 1801.73  4820.2 1800.79  4840.4 1796.62
  4870.8 1792.21  4901.6 1789.75  4992.1 1784.99  5004.3 1784.97  5004.5 1784.47
    5008 1784.47  5008.3 1784.97    5009 1785.72  5026.6 1787.68  5103.2 1790.28
  5154.1 1791.76  5186.3 1792.14    5214 1794.38  5218.3 1793.53  5245.8 1793.75
#Mann= 5 ,-1 , 0
  4648.3    .035       0  5004.3    .035       0  5008.3    .035       0
  5103.2     .07       0  5154.1    .035       0
Bank Sta=5004.3,5008.3
XS Rating Curve= 0 ,0
Exp/Cntr=0.3,0.1

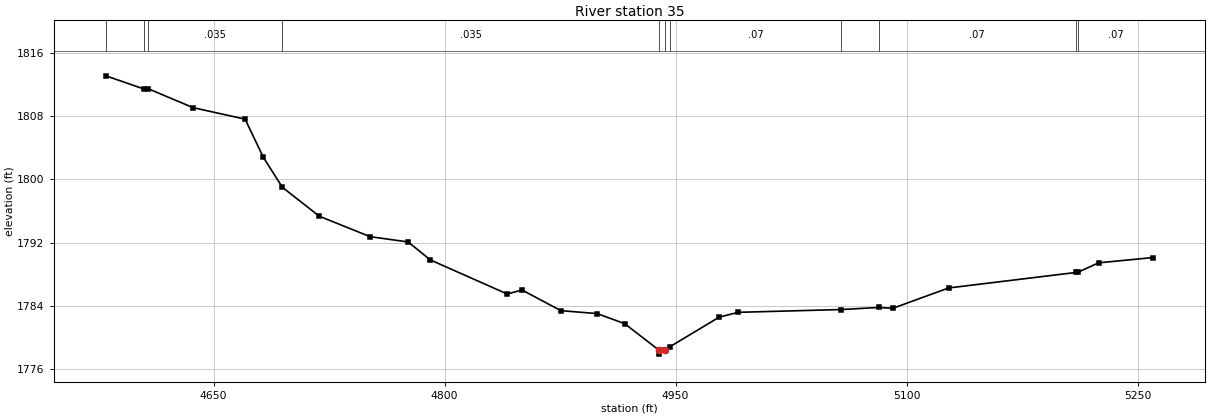
Type RM Length L Ch R = 1 ,35      ,0,0,0
BEGIN DESCRIPTION:
Stream0478 0.1
END DESCRIPTION:
XS GIS Cut Line= 4
      1907569.55     13949384.76      1907382.92     13949686.41
      1907406.79     13949779.73      1907578.24     13949931.64
#Sta/Elev= 30
    4580 1813.11  4604.9 1811.43  4607.3 1811.49  4636.7 1809.08  4670.4 1807.63
  4682.3 1802.78  4694.6 1799.01  4718.6 1795.35  4751.6 1792.76  4776.3 1792.09
  4790.7 1789.82  4840.6 1785.51  4850.3 1786.01  4875.5  1783.4    4899 1783.03
  4916.9 1781.76  4939.2  1778.4  4939.4  1777.9  4943.2  1778.4  4946.2 1778.82
  4978.3 1782.58  4990.7 1783.19  5057.4 1783.54  5081.8  1783.8  5091.1  1783.7
  5127.3 1786.27  5209.9 1788.23  5211.2 1788.25  5224.7 1789.45  5260.1 1790.12
#Mann= 11 ,-1 , 0
    4580    .035       0  4604.9      .1       0  4607.3    .035       0
  4694.6    .035       0  4939.2    .035       0  4943.2    .035       0
  4946.2     .07       0  5057.4      .1       0  5081.8     .07       0
  5209.9    .035       0  5211.2     .07       0
Bank Sta=4939.2,4943.2
XS Rating Curve= 0 ,0
Exp/Cntr=0.3,0.1

Chan Stop Cuts=-1
Use User Specified Reach Order=0
Composite Channel Slope=5