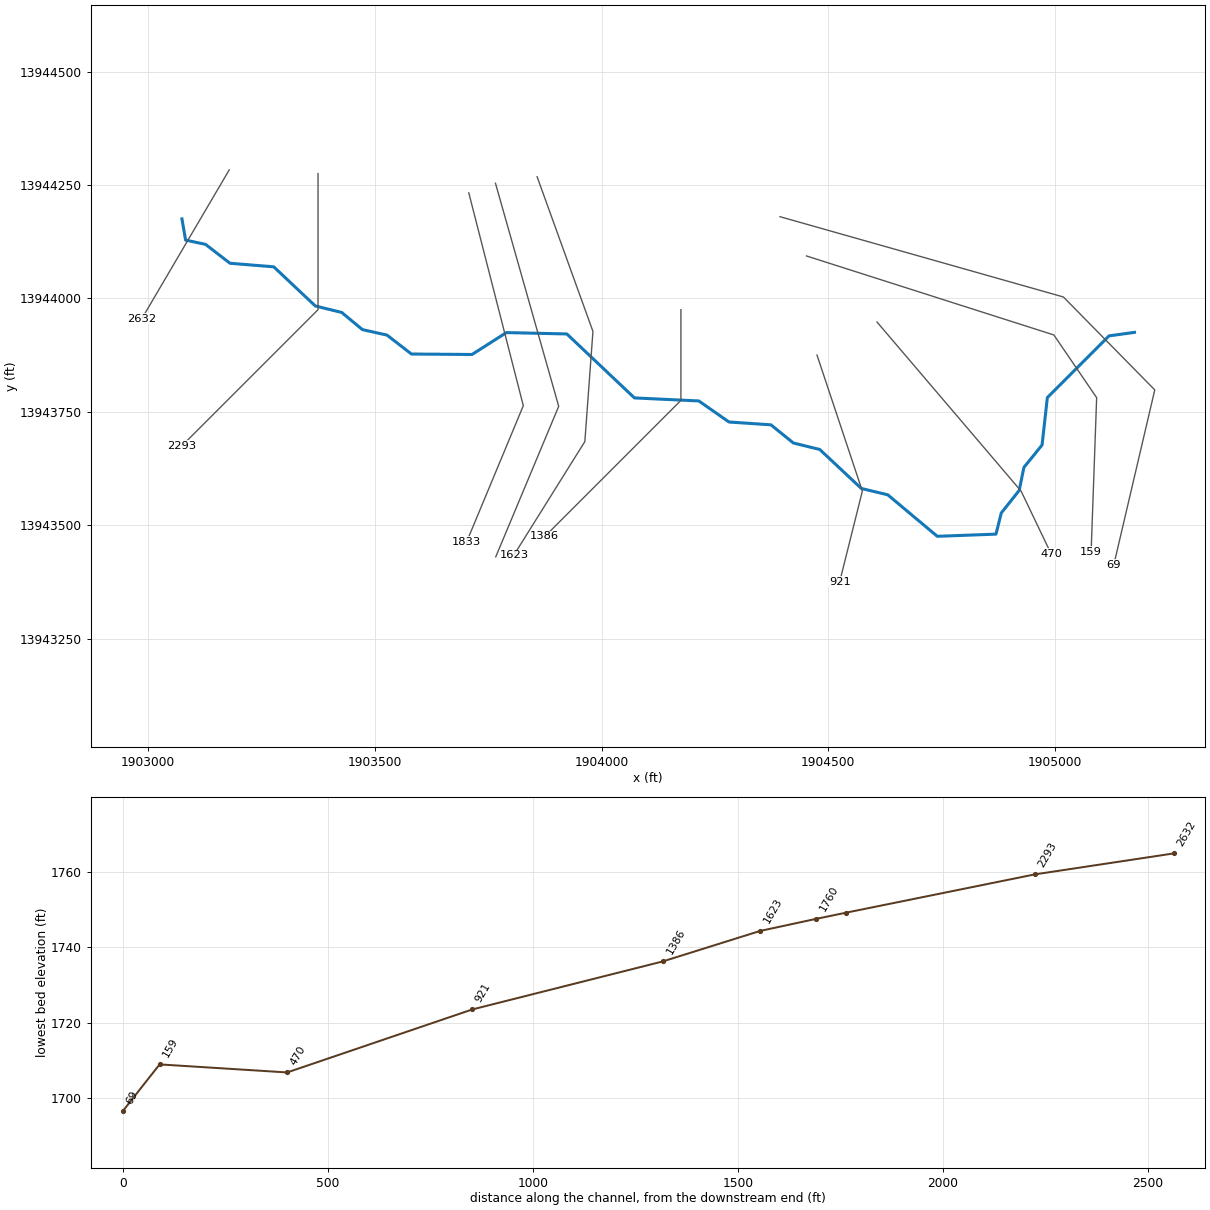
--- Stream0479.prj (project) ---

Proj Title=Stream0479 Base Level Engineering
Current Plan=p01
Default Exp/Contr=0.3,0.1
English Units
Geom File=g01
Flow File=f01
Plan File=p01
Y Axis Title=Elevation
X Axis Title(PF)=Main Channel Distance
X Axis Title(XS)=Station
BEGIN DESCRIPTION:
Stream0479
END DESCRIPTION:
DSS Export Rating Curves= 0
DSS Export Rating Curve Sorted= 0
DSS Export Volume Flow Curves= 0
DXF OffsetX= 0
DXF OffsetY= 0
DXF ScaleX= 1
DXF ScaleY= 10

--- Stream0479.p01 (plan) ---

Plan Title=Multiple Run
Short Identifier=Multiple
Geom File=g01
Flow File=f01
Subcritical Flow
K Sum by GR= 0
Std Step Tol= 0.01
Critical Tol= 0.01
Num of Std Step Trials= 20
Max Error Tol= 0.3
Flow Tol Ratio= 0.001
Split Flow NTrial= 30
Split Flow Tol= 0.02
Split Flow Ratio= 0.02
Log Output Level= 0
Friction Slope Method= 1
Unsteady Friction Slope Method= 2
Unsteady Bridges Friction Slope Method= 1
Parabolic Critical Depth
Global Vel Dist=  1 , 1 , 1
Global Log Level= 0
CheckData=True
Encroach Param= -1, 0, 0, 0
BEGIN DESCRIPTION:
Multiple Run
END DESCRIPTION:

--- Stream0479.f01 (steady flow) ---

Flow Title=Multiple
Program Version=4.10
Number of Profiles= 7
Profile Names=10-year,25-year,50-year,1pct_min,100-year,1pct_plu,500-year
River Rch & RM=Stream0479,Reach-1         ,2632
     853    1438    1990    1335    2664    5316    4706
Boundary for River Rch & Prof#=Stream0479,Reach-1         , 1
Up Type= 0
Dn Type= 3
Dn Slope=0.005
Boundary for River Rch & Prof#=Stream0479,Reach-1         , 2
Up Type= 0
Dn Type= 3
Dn Slope=0.005
Boundary for River Rch & Prof#=Stream0479,Reach-1         , 3
Up Type= 0
Dn Type= 3
Dn Slope=0.005
Boundary for River Rch & Prof#=Stream0479,Reach-1         , 4
Up Type= 0
Dn Type= 3
Dn Slope=0.005
Boundary for River Rch & Prof#=Stream0479,Reach-1         , 5
Up Type= 0
Dn Type= 3
Dn Slope=0.005
Boundary for River Rch & Prof#=Stream0479,Reach-1         , 6
Up Type= 0
Dn Type= 3
Dn Slope=0.005
Boundary for River Rch & Prof#=Stream0479,Reach-1         , 7
Up Type= 0
Dn Type= 3
Dn Slope=0.005
DSS Import GetInterval= 0
DSS Import GetPeak= 0
DSS Import FillOption= 0

--- Stream0479.g01 (geometry) ---

Geom Title=Existing Conditions

River Reach=Stream0479,Reach-1
Reach XY= 30
      1903075.00     13944175.00      1903082.99     13944128.40
      1903127.00     13944118.96      1903180.94     13944077.31
      1903277.42     13944069.46      1903368.95     13943983.16
      1903427.19     13943968.90      1903472.80     13943931.08
      1903527.18     13943918.88      1903580.93     13943877.23
      1903714.49     13943876.21      1903790.22     13943924.49
      1903923.53     13943921.47      1904072.55     13943780.47
      1904214.49     13943773.77      1904280.98     13943727.36
      1904373.42     13943721.17      1904422.83     13943681.14
      1904481.05     13943666.84      1904572.72     13943580.87
      1904631.04     13943566.82      1904740.18     13943475.36
      1904869.59     13943480.16      1904881.27     13943526.79
      1904920.86     13943576.69      1904931.12     13943627.18
      1904971.17     13943676.59      1904982.86     13943781.17
      1905118.79     13943917.24      1905175.00     13943925.00

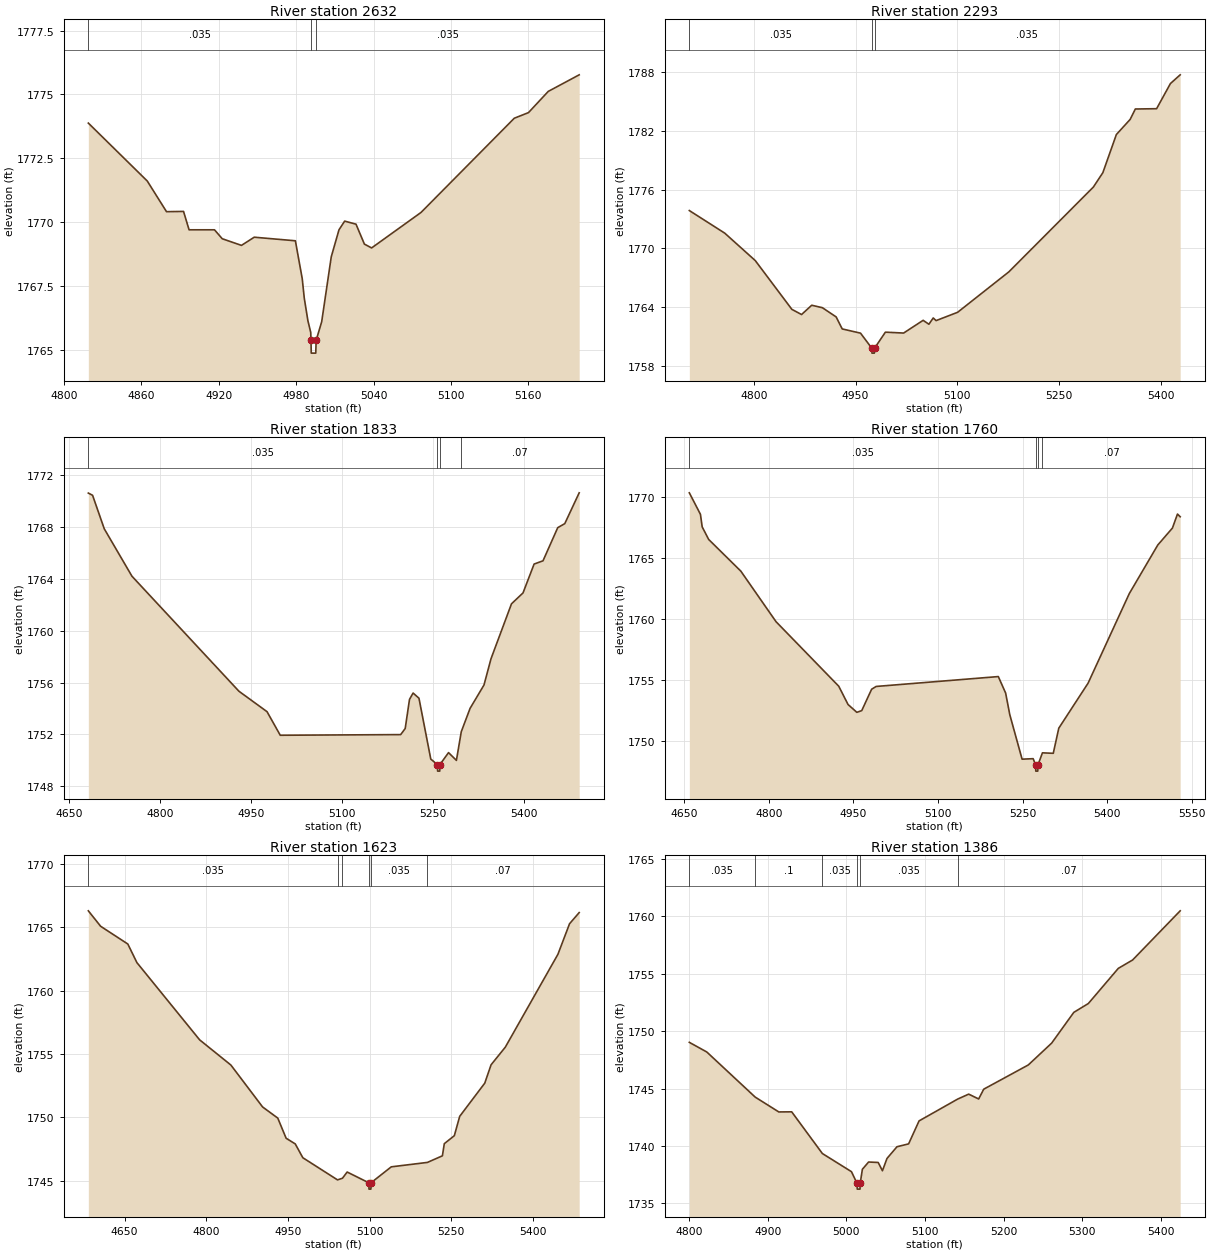
Type RM Length L Ch R = 1,2632,339,339,339
BEGIN DESCRIPTION:
Stream0479 6.0
END DESCRIPTION:
XS GIS Cut Line= 2
      1903179.20     13944283.16      1902986.51     13943955.06
#Sta/Elev= 30
  4818.9 1773.88  4864.6 1771.61  4879.5 1770.41  4892.7 1770.42  4897.0 1769.70
  4916.7 1769.70  4922.7 1769.35  4937.6 1769.09  4947.5 1769.41  4979.4 1769.27
  4984.7 1767.79  4986.3 1767.02  4989.1 1766.14  4991.3 1765.68  4991.5 1765.37
  4991.7 1764.87  4995.2 1764.87  4995.5 1765.37  4999.8 1766.10  5007.2 1768.64
  5013.2 1769.70  5017.6 1770.04  5026.4 1769.92  5032.9 1769.14  5038.5 1768.99
  5076.8 1770.38  5149.1 1774.07  5160.1 1774.29  5175.4 1775.12  5199.4 1775.77
#Mann=3,-1,0
  4818.9   0.035       0  4991.5   0.035       0  4995.5   0.035       0
Bank Sta=4991.5,4995.5
Exp/Cntr=0.3,0.1

Type RM Length L Ch R = 1,2293,460,460,460
BEGIN DESCRIPTION:
Stream0479 5.0
END DESCRIPTION:
XS GIS Cut Line= 3
      1903375.00     13944275.05      1903375.00     13943975.00
      1903075.01     13943675.01
#Sta/Elev= 30
  4704.7 1773.87  4757.0 1771.56  4802.0 1768.76  4856.0 1763.78  4870.3 1763.25
  4885.3 1764.20  4901.0 1763.95  4921.3 1763.01  4930.3 1761.78  4957.3 1761.35
  4974.0 1759.81  4974.2 1759.31  4977.7 1759.31  4978.0 1759.81  4994.0 1761.45
  5020.9 1761.36  5049.7 1762.66  5058.2 1762.26  5064.6 1762.90  5068.8 1762.63
  5100.6 1763.48  5176.2 1767.61  5300.9 1776.27  5314.9 1777.74  5334.8 1781.63
  5355.2 1783.18  5362.8 1784.24  5394.2 1784.27  5414.6 1786.84  5429.0 1787.73
#Mann=3,-1,0
  4704.7   0.035       0  4974.0   0.035       0  4978.0   0.035       0
Bank Sta=4974,4978
Exp/Cntr=0.3,0.1

Type RM Length L Ch R = 1,1833,73,73,73
BEGIN DESCRIPTION:
Stream0479 4.0
END DESCRIPTION:
XS GIS Cut Line= 3
      1903707.33     13944232.56      1903827.55     13943763.29
      1903702.47     13943462.70
#Sta/Elev= 30
  4681.4 1770.64  4688.4 1770.47  4707.7 1767.88  4753.4 1764.22  4929.9 1755.34
  4976.3 1753.76  4998.1 1751.94  5196.8 1751.99  5204.3 1752.46  5211.4 1754.71
  5217.3 1755.20  5227.0 1754.80  5246.5 1750.10  5257.5 1749.67  5257.8 1749.17
  5261.3 1749.17  5261.5 1749.67  5275.8 1750.60  5288.8 1750.00  5296.8 1752.21
  5311.4 1754.02  5334.3 1755.82  5345.9 1757.85  5379.7 1762.09  5398.7 1762.93
  5417.0 1765.16  5431.7 1765.41  5456.0 1767.97  5467.6 1768.28  5491.4 1770.66
#Mann=4,-1,0
  4681.4   0.035       0  5257.5   0.035       0  5261.5   0.035       0
  5296.8    0.07       0
Bank Sta=5257.5,5261.5
Exp/Cntr=0.3,0.1

Type RM Length L Ch R = 1,1760,137,137,137
BEGIN DESCRIPTION:
Mapping XS 2b2e348c
END DESCRIPTION:
XS GIS Cut Line= 3
      1903766.16     13944253.71      1903905.59     13943761.94
      1903766.78     13943430.05
#Sta/Elev= 30
  4658.8 1770.34  4678.5 1768.58  4681.6 1767.55  4693.1 1766.52  4750.2 1763.92
  4812.6 1759.78  4923.9 1754.49  4940.4 1752.99  4956.0 1752.35  4964.7 1752.49
  4982.2 1754.24  4990.3 1754.47  5207.0 1755.28  5220.0 1753.93  5227.4 1752.15
  5249.2 1748.51  5268.8 1748.55  5273.3 1748.03  5273.5 1747.53  5277.0 1747.53
  5277.3 1748.03  5285.3 1749.03  5304.5 1748.99  5314.3 1751.05  5366.3 1754.74
  5439.4 1762.08  5489.9 1766.06  5515.9 1767.45  5524.9 1768.60  5529.7 1768.38
#Mann=4,-1,0
  4658.8   0.035       0  5273.3   0.035       0  5277.3   0.035       0
  5285.3    0.07       0
Bank Sta=5273.3,5277.3
Exp/Cntr=0.3,0.1

Type RM Length L Ch R = 1,1623,237,237,237
BEGIN DESCRIPTION:
Mapping XS 5dd26b28
END DESCRIPTION:
XS GIS Cut Line= 4
      1903857.98     13944268.07      1903981.07     13943927.04
      1903963.20     13943684.20      1903806.66     13943433.75
#Sta/Elev= 30
  4583.5 1766.30  4606.1 1765.08  4656.0 1763.68  4672.7 1762.21  4787.9 1756.11
  4845.3 1754.12  4903.5 1750.81  4931.4 1749.93  4946.7 1748.34  4963.5 1747.89
  4977.4 1746.80  5041.1 1745.05  5050.2 1745.18  5058.8 1745.67  5098.6 1744.82
  5098.9 1744.32  5102.4 1744.32  5102.6 1744.82  5139.8 1746.08  5206.2 1746.43
  5233.7 1746.95  5237.2 1747.91  5255.6 1748.54  5265.5 1750.07  5311.5 1752.69
  5323.1 1754.14  5349.2 1755.53  5445.9 1762.87  5467.2 1765.28  5484.9 1766.16
#Mann=6,-1,0
  4583.5   0.035       0  5041.1     0.1       0  5050.2   0.035       0
  5098.6   0.035       0  5102.6   0.035       0  5206.2    0.07       0
Bank Sta=5098.6,5102.6
Exp/Cntr=0.3,0.1

Type RM Length L Ch R = 1,1386,465,465,465
BEGIN DESCRIPTION:
Stream0479 3.0
END DESCRIPTION:
XS GIS Cut Line= 3
      1904175.00     13943975.03      1904175.00     13943775.00
      1903874.99     13943474.99
#Sta/Elev= 30
  4800.3 1749.03  4822.5 1748.19  4884.1 1744.26  4914.1 1742.97  4930.5 1742.98
  4969.5 1739.35  5006.5 1737.77  5013.6 1736.75  5013.9 1736.25  5017.4 1736.25
  5017.6 1736.75  5020.4 1737.98  5028.3 1738.61  5040.5 1738.57  5045.9 1737.85
  5051.7 1738.92  5064.4 1739.94  5079.2 1740.19  5092.5 1742.19  5141.6 1744.09
  5155.6 1744.52  5168.3 1744.10  5174.7 1744.95  5231.4 1747.06  5261.1 1748.96
  5289.3 1751.64  5307.8 1752.41  5345.9 1755.47  5364.1 1756.20  5424.6 1760.48
#Mann=6,-1,0
  4800.3   0.035       0  4884.1     0.1       0  4969.5   0.035       0
  5013.6   0.035       0  5017.6   0.035       0  5141.6    0.07       0
Bank Sta=5013.6,5017.6
Exp/Cntr=0.3,0.1

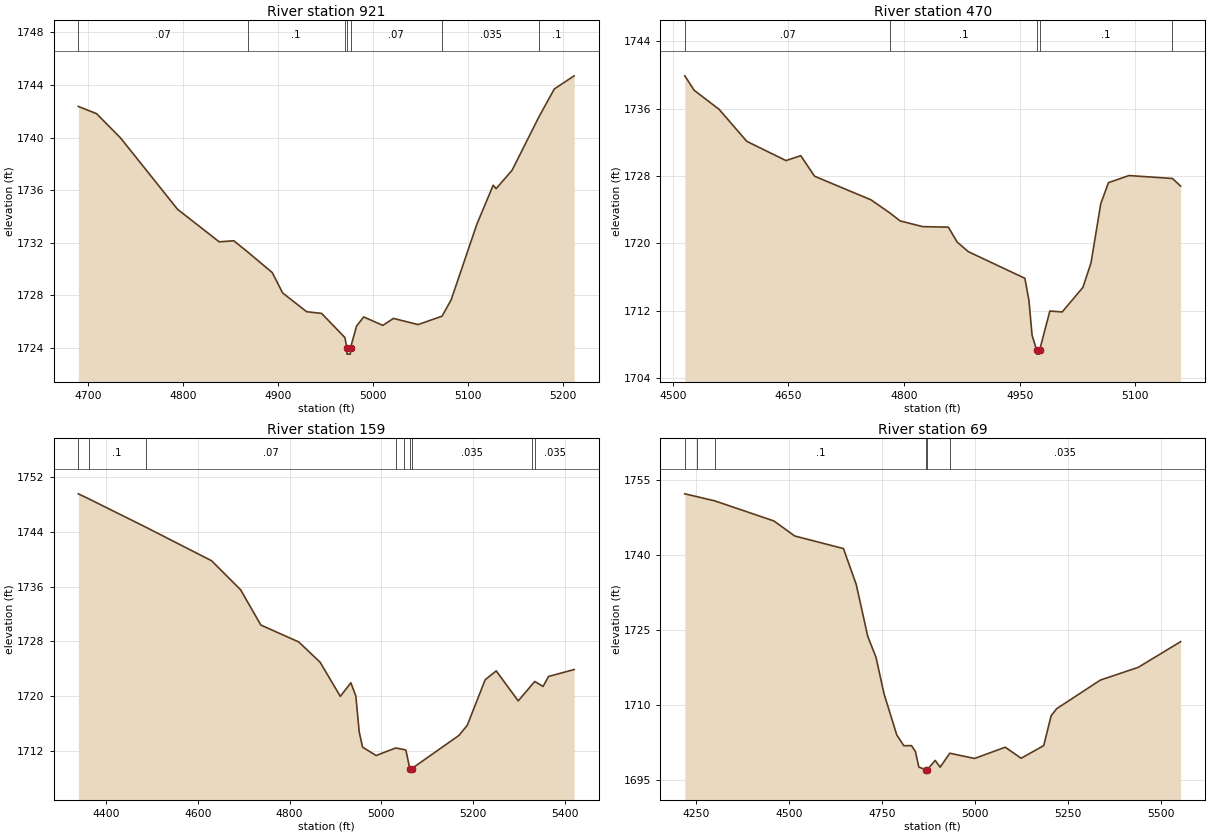
Type RM Length L Ch R = 1,921,451,451,451
BEGIN DESCRIPTION:
Stream0479 2.0
END DESCRIPTION:
XS GIS Cut Line= 3
      1904475.01     13943874.96      1904575.00     13943575.00
      1904525.01     13943375.04
#Sta/Elev= 30
  4689.8 1742.37  4709.0 1741.82  4734.3 1739.97  4794.3 1734.54  4838.2 1732.06
  4853.6 1732.14  4868.0 1731.30  4894.1 1729.72  4905.0 1728.17  4930.3 1726.74
  4946.1 1726.61  4970.6 1724.77  4972.6 1724.01  4972.8 1723.51  4976.3 1723.51
  4976.6 1724.01  4982.9 1725.65  4990.4 1726.34  5010.6 1725.70  5021.7 1726.23
  5047.7 1725.76  5072.9 1726.40  5082.4 1727.62  5109.6 1733.40  5126.8 1736.37
  5129.9 1736.11  5146.7 1737.51  5175.1 1741.59  5191.2 1743.70  5212.1 1744.70
#Mann=7,-1,0
  4689.8    0.07       0  4868.0     0.1       0  4970.6    0.07       0
  4972.6    0.05       0  4976.6    0.07       0  5072.9   0.035       0
  5175.1     0.1       0
Bank Sta=4972.6,4976.6
Exp/Cntr=0.3,0.1

Type RM Length L Ch R = 1,470,311,311,311
BEGIN DESCRIPTION:
Stream0479 1.0
END DESCRIPTION:
XS GIS Cut Line= 3
      1904607.37     13943947.72      1904925.00     13943575.00
      1904991.36     13943436.38
#Sta/Elev= 30
  4515.5 1739.90  4527.7 1738.18  4560.1 1735.91  4596.0 1732.11  4646.8 1729.83
  4666.0 1730.41  4683.9 1727.97  4757.2 1725.16  4781.7 1723.60  4794.9 1722.66
  4824.2 1721.98  4857.5 1721.92  4868.9 1720.15  4883.3 1719.01  4956.8 1715.84
  4962.1 1713.21  4966.1 1709.10  4972.0 1707.33  4972.2 1706.83  4975.7 1706.83
  4976.0 1707.33  4989.2 1711.95  5005.2 1711.84  5032.1 1714.76  5042.6 1717.67
  5055.3 1724.71  5065.3 1727.21  5091.9 1728.05  5148.3 1727.70  5158.9 1726.80
#Mann=5,-1,0
  4515.5    0.07       0  4781.7     0.1       0  4972.0    0.05       0
  4976.0     0.1       0  5148.3   0.035       0
Bank Sta=4972,4976
Exp/Cntr=0.3,0.1

Type RM Length L Ch R = 1,159,90,90,90
BEGIN DESCRIPTION:
Stream0479 0.0
END DESCRIPTION:
XS GIS Cut Line= 4
      1904451.85     13944093.42      1904997.22     13943919.25
      1905091.54     13943781.00      1905079.35     13943441.08
#Sta/Elev= 30
  4339.8 1749.51  4362.3 1748.79  4486.6 1744.66  4630.3 1739.75  4693.3 1735.53
  4737.4 1730.39  4819.9 1727.93  4866.5 1724.97  4910.5 1720.00  4933.4 1721.98
  4944.3 1720.05  4951.6 1714.81  4958.9 1712.60  4988.5 1711.38  5031.0 1712.48
  5048.2 1712.26  5053.3 1712.17  5061.8 1709.46  5062.1 1708.96  5065.8 1709.46
  5168.9 1714.31  5186.9 1715.78  5226.0 1722.42  5250.0 1723.71  5298.0 1719.34
  5328.7 1721.76  5334.1 1722.17  5352.0 1721.44  5364.1 1722.90  5419.8 1723.91
#Mann=9,-1,0
  4339.8    0.07       0  4362.3     0.1       0  4486.6    0.07       0
  5031.0     0.1       0  5048.2   0.035       0  5061.8    0.05       0
  5065.8   0.035       0  5328.7     0.1       0  5334.1   0.035       0
Bank Sta=5061.8,5065.8
Exp/Cntr=0.3,0.1

Type RM Length L Ch R = 1,69,0,0,0
BEGIN DESCRIPTION:
Stream0479 0.1
END DESCRIPTION:
XS GIS Cut Line= 4
      1904393.30     13944180.05      1905018.27     13944002.98
      1905219.66     13943798.12      1905129.40     13943412.79
#Sta/Elev= 30
  4219.8 1752.18  4252.6 1751.61  4300.5 1750.77  4459.2 1746.76  4515.3 1743.75
  4646.2 1741.24  4680.6 1734.05  4711.5 1723.70  4733.6 1719.53  4755.4 1712.17
  4789.6 1703.98  4808.4 1701.83  4829.0 1701.85  4839.6 1700.68  4848.9 1697.55
  4867.7 1697.05  4868.0 1696.55  4871.7 1697.05  4892.7 1698.89  4906.1 1697.54
  4932.0 1700.33  4998.6 1699.28  5081.0 1701.53  5123.8 1699.32  5184.4 1701.85
  5204.4 1707.82  5219.4 1709.24  5336.7 1714.95  5438.4 1717.49  5552.4 1722.63
#Mann=6,-1,0
  4219.8   0.035       0  4252.6    0.07       0  4300.5     0.1       0
  4867.7   0.035       0  4871.7     0.1       0  4932.0   0.035       0
Bank Sta=4867.7,4871.7
Exp/Cntr=0.3,0.1

Chan Stop Cuts=-1