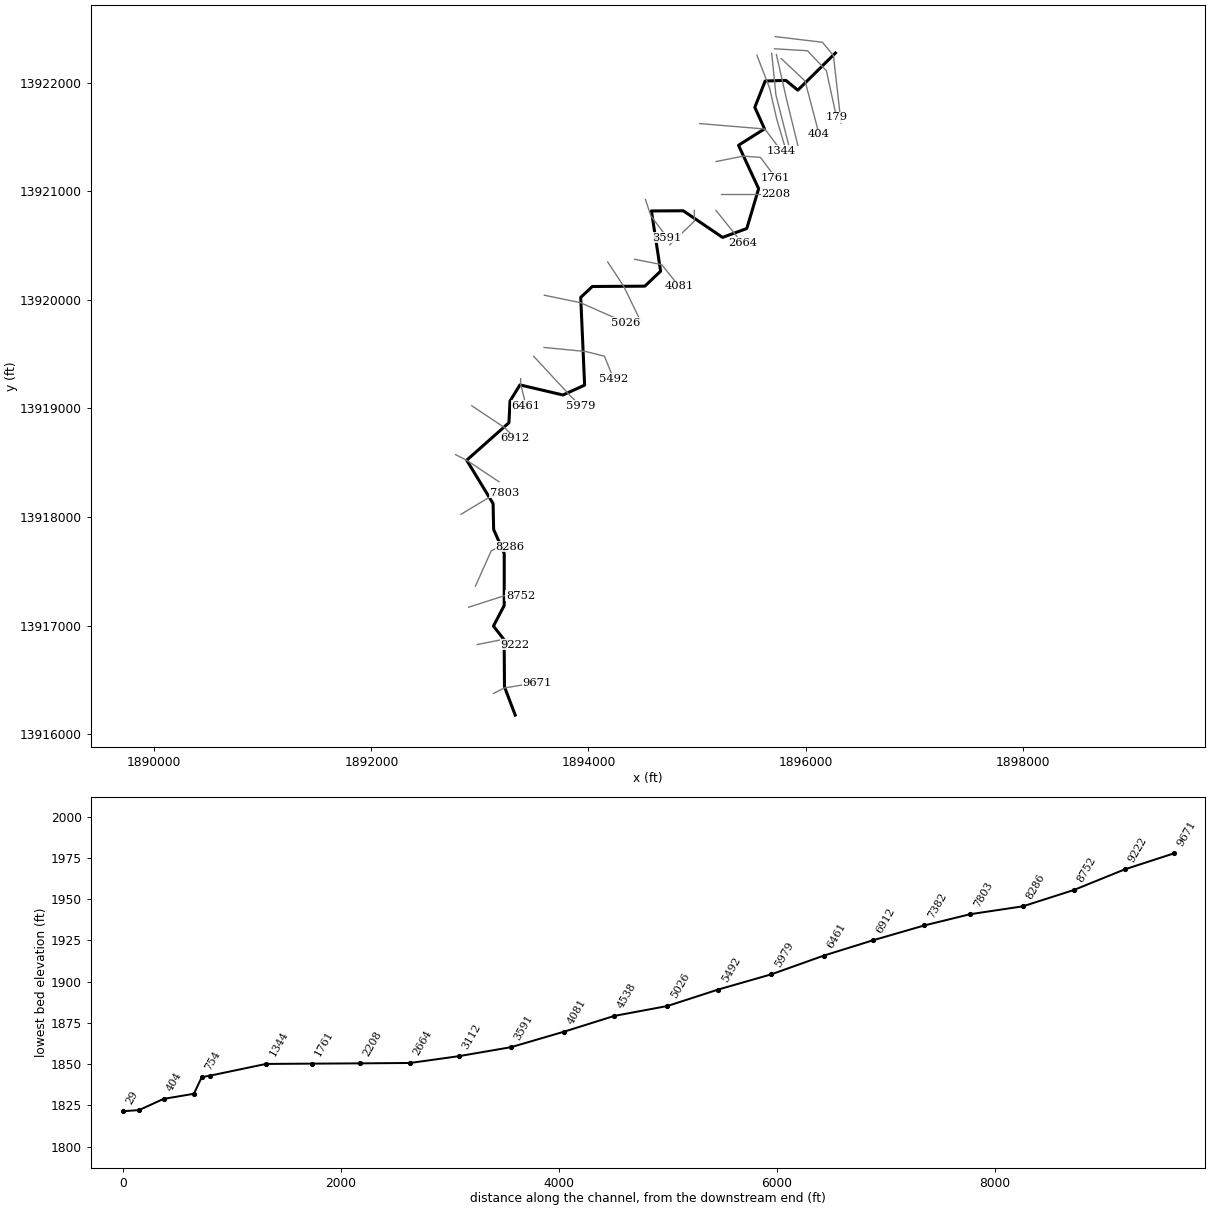
--- Stream0480.prj (project) ---

Proj Title=Stream0480 Base Level Engineering
Current Plan=p01
Default Exp/Contr=0.3,0.1
English Units
Geom File=g01
Flow File=f01
Plan File=p01
Y Axis Title=Elevation
X Axis Title(PF)=Main Channel Distance
X Axis Title(XS)=Station
BEGIN DESCRIPTION:
Stream0480
END DESCRIPTION:
DSS Export Rating Curves= 0
DSS Export Rating Curve Sorted= 0
DSS Export Volume Flow Curves= 0
DXF OffsetX= 0
DXF OffsetY= 0
DXF ScaleX= 1
DXF ScaleY= 10

--- Stream0480.p01 (plan) ---

Plan Title=Multiple Run
Short Identifier=Multiple
Geom File=g01
Flow File=f01
Subcritical Flow
K Sum by GR= 0
Std Step Tol= 0.01
Critical Tol= 0.01
Num of Std Step Trials= 20
Max Error Tol= 0.3
Flow Tol Ratio= 0.001
Split Flow NTrial= 30
Split Flow Tol= 0.02
Split Flow Ratio= 0.02
Log Output Level= 0
Friction Slope Method= 1
Unsteady Friction Slope Method= 2
Unsteady Bridges Friction Slope Method= 1
Parabolic Critical Depth
Global Vel Dist=  1 , 1 , 1
Global Log Level= 0
CheckData=True
Encroach Param= -1, 0, 0, 0
BEGIN DESCRIPTION:
Multiple Run
END DESCRIPTION:

--- Stream0480.f01 (steady flow) ---

Flow Title=Multiple
Program Version=4.10
Number of Profiles= 7
Profile Names=10-year,25-year,50-year,1pct_min,100-year,1pct_plu,500-year
River Rch & RM=Stream0480,Reach-1         ,9671
     807    1348    1854    1235    2465    4917    4293
River Rch & RM=Stream0480,Reach-1         ,7803
    1437    2479    3480    2360    4709    9396    8516
Boundary for River Rch & Prof#=Stream0480,Reach-1         , 1
Up Type= 0
Dn Type= 3
Dn Slope=0.005
Boundary for River Rch & Prof#=Stream0480,Reach-1         , 2
Up Type= 0
Dn Type= 3
Dn Slope=0.005
Boundary for River Rch & Prof#=Stream0480,Reach-1         , 3
Up Type= 0
Dn Type= 3
Dn Slope=0.005
Boundary for River Rch & Prof#=Stream0480,Reach-1         , 4
Up Type= 0
Dn Type= 3
Dn Slope=0.005
Boundary for River Rch & Prof#=Stream0480,Reach-1         , 5
Up Type= 0
Dn Type= 3
Dn Slope=0.005
Boundary for River Rch & Prof#=Stream0480,Reach-1         , 6
Up Type= 0
Dn Type= 3
Dn Slope=0.005
Boundary for River Rch & Prof#=Stream0480,Reach-1         , 7
Up Type= 0
Dn Type= 3
Dn Slope=0.005
DSS Import GetInterval= 0
DSS Import GetPeak= 0
DSS Import FillOption= 0

--- Stream0480.g01 (geometry) ---

Geom Title=Existing Conditions
Program Version=4.10

River Reach=Stream0480      ,Reach-1
Reach XY= 30
        1893325.       13916175.       1893226.2      13916435.5
      1893222.93     13916869.14       1893124.6     13916995.13
       1893223.8      13917185.5      1893223.78      13917664.5
      1893126.22      13917885.5      1893121.25     13918123.45
      1892878.01     13918523.57      1893267.19     13918868.81
      1893277.24     13919069.07      1893368.52     13919217.31
      1893764.83      13919124.5      1893964.53     13919215.17
      1893928.52     13920023.54      1894035.43     13920123.96
      1894519.15     13920127.06      1894664.52      13920265.2
        1894580.       13920820.      1894873.54     13920821.46
       1895235.5     13920576.19      1895458.58      13920658.2
      1895567.67      13921025.1      1895382.28      13921425.1
      1895621.98     13921576.39       1895532.5       13921775.
        1895628.     13922017.05      1895819.15     13922022.93
      1895928.34      13921932.6        1896275.       13922275.

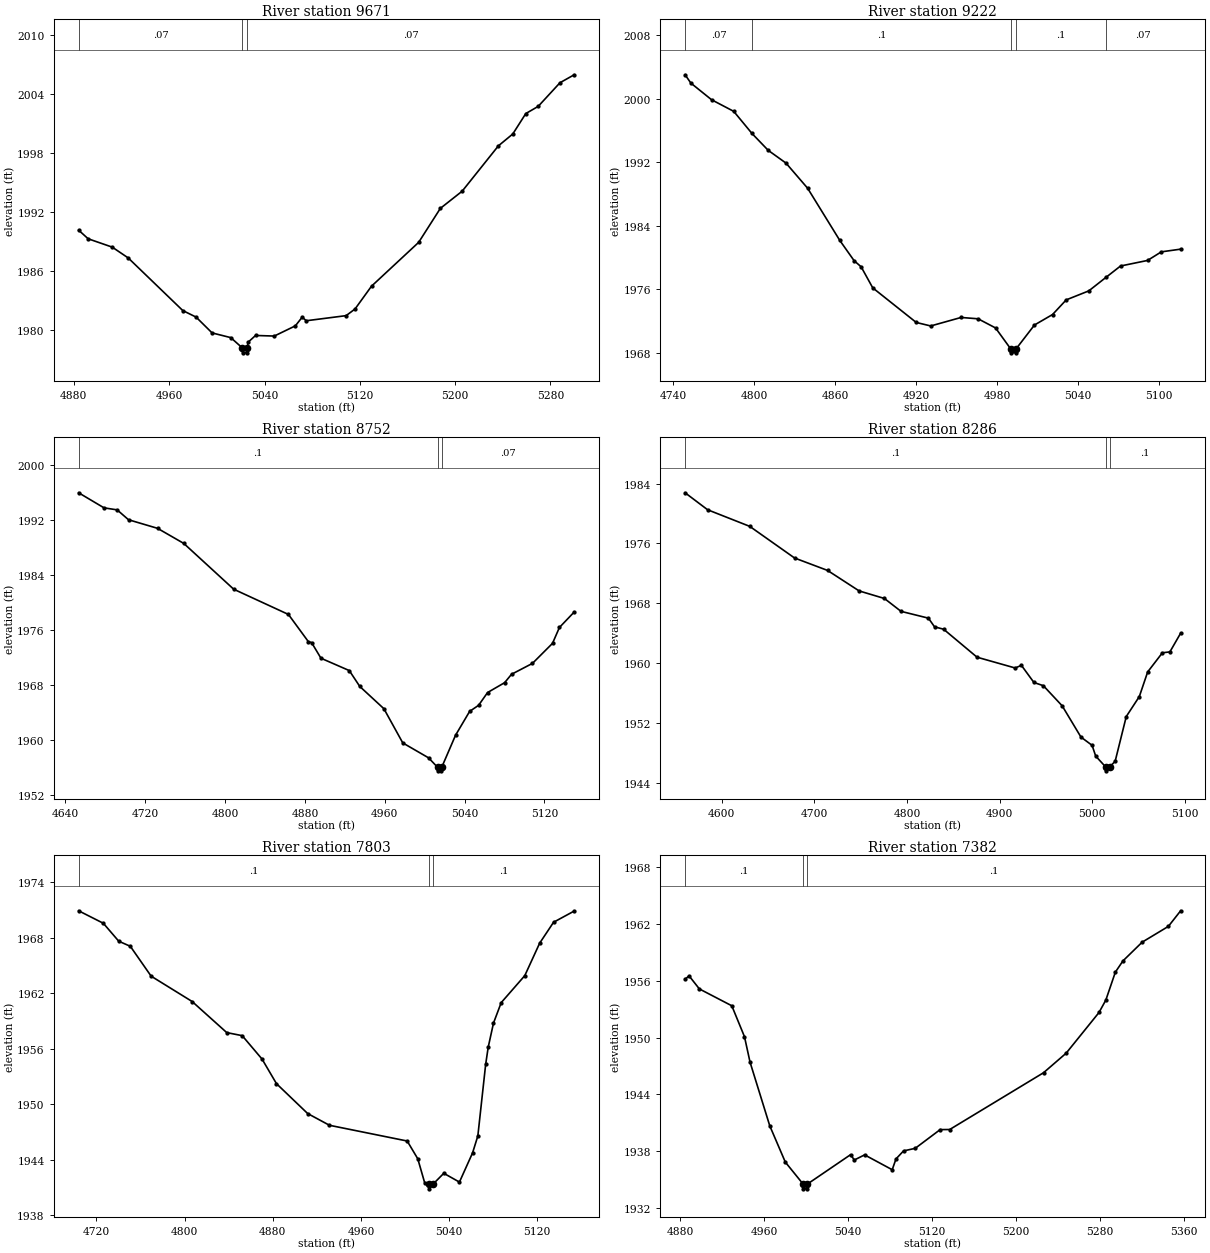
Type RM Length L Ch R = 1 ,9671    ,449,449,449
BEGIN DESCRIPTION:
Stream0480 21.0
END DESCRIPTION:
XS GIS Cut Line= 3
      1893125.04     13916375.02        1893225.       13916425.
        1893525.       13916475.
#Sta/Elev= 30
    4884 1990.16    4892 1989.28  4912.2 1988.43  4925.6 1987.33  4971.4 1981.97
  4982.6  1981.3    4996 1979.69  5011.7 1979.21  5021.4 1978.16  5021.6 1977.66
  5025.1 1977.66  5025.4 1978.16  5026.4 1978.76  5032.5 1979.43  5048.2 1979.37
  5065.9 1980.41  5071.6 1981.29  5075.1 1980.93  5108.5 1981.45    5116 1982.13
  5129.8 1984.45  5169.4 1988.92  5187.6 1992.38  5205.9 1994.13  5236.3 1998.75
  5248.4 1999.96  5259.3 2002.04  5269.7 2002.77    5288 2005.18  5299.9 2005.99
#Mann= 3 ,-1 , 0
    4884     .07       0  5021.4     .05       0  5025.4     .07       0
Bank Sta=5021.4,5025.4
XS Rating Curve= 0 ,0
Exp/Cntr=0.3,0.1

Type RM Length L Ch R = 1 ,9222    ,470,470,470
BEGIN DESCRIPTION:
Stream0480 20.0
END DESCRIPTION:
XS GIS Cut Line= 3
      1892974.99       13916825.        1893225.       13916875.
      1893325.03     13916824.99
#Sta/Elev= 30
    4749    2003  4753.3 2001.95  4768.6 1999.86    4785  1998.4  4798.5 1995.62
  4810.5  1993.5  4823.7 1991.89  4839.7 1988.73  4863.5 1982.17  4874.1 1979.62
  4879.3 1978.85  4887.9  1976.2  4920.1 1971.85  4930.8 1971.41  4953.3 1972.48
  4965.9 1972.31  4978.8 1971.16    4990 1968.53  4990.2 1968.03  4993.7 1968.03
    4994 1968.53  5007.6 1971.53    5021 1972.85  5031.1 1974.69  5047.8 1975.82
  5060.6 1977.53  5071.3 1978.95  5091.3 1979.65  5101.5 1980.73  5115.8 1981.07
#Mann= 5 ,-1 , 0
    4749     .07       0  4798.5      .1       0    4990     .05       0
    4994      .1       0  5060.6     .07       0
Bank Sta=4990,4994
XS Rating Curve= 0 ,0
Exp/Cntr=0.3,0.1

Type RM Length L Ch R = 1 ,8752    ,466,466,466
BEGIN DESCRIPTION:
Stream0480 19.0
END DESCRIPTION:
XS GIS Cut Line= 3
      1892894.97     13917168.77        1893225.       13917275.
      1893374.99       13917275.
#Sta/Elev= 30
  4653.2 1995.97  4678.7 1993.77  4691.8 1993.48  4703.2 1992.04  4732.3 1990.79
  4758.6 1988.59  4808.6 1981.92  4863.5 1978.24  4883.5 1974.27  4886.7 1974.14
  4896.1 1971.86  4924.5 1970.06    4935 1967.75  4959.2  1964.5  4978.1 1959.52
    5004 1957.34  5013.1 1955.95  5013.4 1955.45  5016.9 1955.45  5017.1 1955.95
    5031 1960.64  5045.1 1964.11  5054.1    1965  5063.1 1966.86  5080.2  1968.3
  5087.1 1969.52  5108.1 1971.11  5128.2 1974.03  5135.1 1976.34  5149.9 1978.59
#Mann= 3 ,-1 , 0
  4653.2      .1       0  5013.1     .05       0  5017.1     .07       0
Bank Sta=5013.1,5017.1
XS Rating Curve= 0 ,0
Exp/Cntr=0.3,0.1

Type RM Length L Ch R = 1 ,8286    ,483,483,483
BEGIN DESCRIPTION:
Stream0480 18.0
END DESCRIPTION:
XS GIS Cut Line= 4
      1892959.03     13917364.15      1893103.06     13917687.37
        1893175.       13917725.      1893274.96       13917725.
#Sta/Elev= 30
  4560.3 1982.77  4584.6  1980.5  4630.1 1978.28  4678.5 1974.05  4714.1 1972.39
  4748.2 1969.65  4775.5 1968.64  4793.4 1966.92    4823 1966.01  4829.6 1964.85
  4839.4 1964.53  4875.5 1960.79  4916.6 1959.35  4923.4  1959.7  4936.9 1957.41
  4947.1 1956.98  4967.4 1954.29  4987.7 1950.11  4999.7 1949.01  5003.6 1947.57
  5014.5  1946.1  5014.7  1945.6  5018.5  1946.1  5024.6 1946.88  5036.6 1952.86
  5050.7 1955.53  5059.7 1958.82  5075.6 1961.38  5083.7  1961.5  5095.3    1964
#Mann= 3 ,-1 , 0
  4560.3      .1       0  5014.5     .05       0  5018.5      .1       0
Bank Sta=5014.5,5018.5
XS Rating Curve= 0 ,0
Exp/Cntr=0.3,0.1

Type RM Length L Ch R = 1 ,7803    ,421,421,421
BEGIN DESCRIPTION:
Stream0480 17.0
END DESCRIPTION:
XS GIS Cut Line= 3
      1892825.02     13918025.01        1893075.       13918175.
      1893224.96     13918224.99
#Sta/Elev= 30
  4703.9 1970.89  4726.3 1969.54  4740.3  1967.6  4750.8 1967.05  4769.7 1963.82
  4806.9 1961.08  4838.3 1957.72  4852.3 1957.39  4870.3 1954.86  4883.4  1952.2
  4911.7 1948.97  4931.5  1947.7    5002    1946  5011.6 1944.08  5017.8 1941.51
  5021.4 1941.33  5021.6 1940.83  5025.4 1941.33  5035.2 1942.51  5049.4 1941.56
  5061.3 1944.71  5066.1 1946.55  5073.2 1954.29  5075.5 1956.14  5080.3 1958.75
  5087.3 1960.96  5108.7 1963.88  5122.2 1967.39  5134.8 1969.65  5153.5 1970.86
#Mann= 3 ,-1 , 0
  4703.9      .1       0  5021.4     .05       0  5025.4      .1       0
Bank Sta=5021.4,5025.4
XS Rating Curve= 0 ,0
Exp/Cntr=0.3,0.1

Type RM Length L Ch R = 1 ,7382    ,470,470,470
BEGIN DESCRIPTION:
Stream0480 16.0
END DESCRIPTION:
XS GIS Cut Line= 3
      1892775.02     13918574.99        1892875.       13918525.
      1893174.97     13918325.02
#Sta/Elev= 30
  4884.8 1956.17  4888.6 1956.52  4898.4 1955.14  4929.3 1953.36  4941.4 1950.09
  4946.7  1947.4  4965.5 1940.67  4980.3 1936.84  4997.3 1934.51  4997.5 1934.01
    5001 1934.01  5001.3 1934.51  5042.5 1937.62  5046.1 1937.06  5055.9  1937.6
  5082.2 1936.03  5085.8 1937.17    5093 1938.02  5104.1 1938.29  5127.9 1940.27
    5137 1940.28  5226.4 1946.28    5248 1948.35  5279.3 1952.65  5285.8 1953.96
  5294.9 1956.92  5302.1  1958.1  5320.4 1960.08  5345.4 1961.75  5357.1  1963.4
#Mann= 3 ,-1 , 0
  4884.8      .1       0  4997.3     .05       0  5001.3      .1       0
Bank Sta=4997.3,5001.3
XS Rating Curve= 0 ,0
Exp/Cntr=0.3,0.1

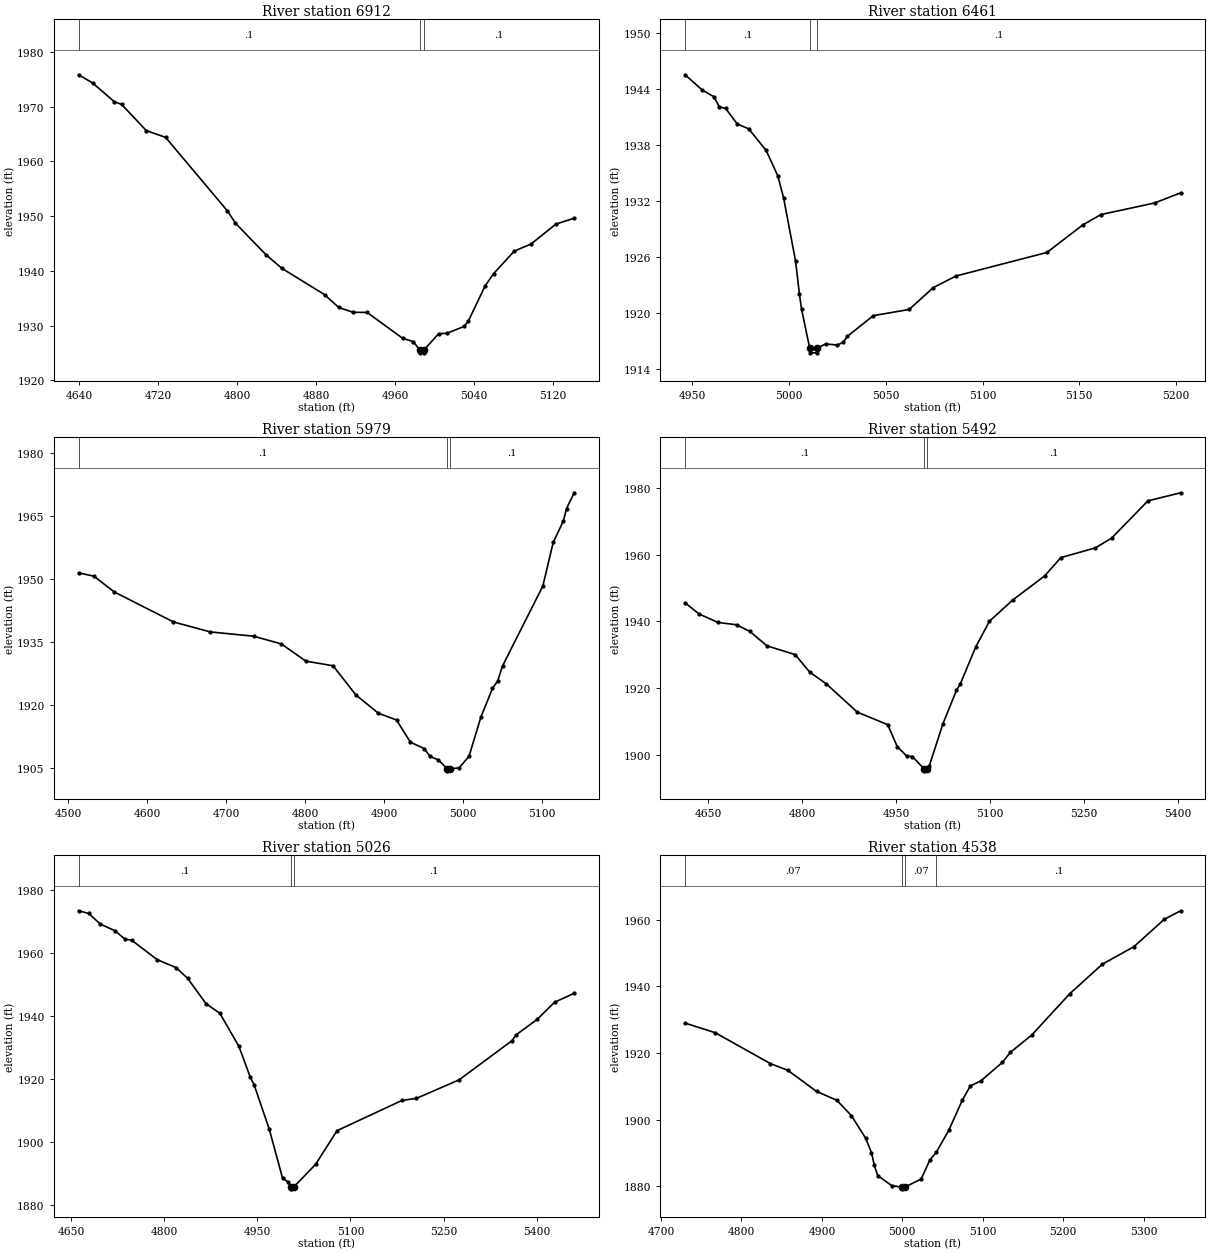
Type RM Length L Ch R = 1 ,6912    ,451,451,451
BEGIN DESCRIPTION:
Stream0480 15.0
END DESCRIPTION:
XS GIS Cut Line= 3
      1892925.01       13919025.        1893225.       13918825.
      1893325.02     13918724.98
#Sta/Elev= 30
  4639.2  1975.8  4653.4  1974.3  4675.5 1970.86  4682.7  1970.4  4707.8  1965.6
  4727.3 1964.37    4790 1950.93  4798.1  1948.7  4828.9 1942.96    4845 1940.47
  4888.3 1935.66  4902.7 1933.31  4917.1 1932.44  4931.5  1932.4  4967.4 1927.69
  4978.2 1927.08  4984.9 1925.53  4985.1 1925.03  4988.6 1925.03  4988.9 1925.53
  5003.8  1928.5  5012.3  1928.6  5029.8 1929.86    5034 1930.84    5051 1937.26
  5059.5 1939.48  5080.5  1943.6  5097.7 1944.92  5122.6 1948.53  5141.2 1949.61
#Mann= 3 ,-1 , 0
  4639.2      .1       0  4984.9     .05       0  4988.9      .1       0
Bank Sta=4984.9,4988.9
XS Rating Curve= 0 ,0
Exp/Cntr=0.3,0.1

Type RM Length L Ch R = 1 ,6461    ,482,482,482
BEGIN DESCRIPTION:
Stream0480 14.0
END DESCRIPTION:
XS GIS Cut Line= 3
        1893375.     13919274.98        1893375.       13919225.
      1893424.99     13919025.03
#Sta/Elev= 30
  4946.3 1945.51  4955.2 1943.87  4961.2 1943.16    4964 1942.07  4967.2 1941.92
  4973.2 1940.26  4979.2 1939.72  4988.2 1937.41  4994.2  1934.7  4997.2 1932.35
  5003.4 1925.56  5005.4 1922.01  5006.5 1920.42  5010.7 1916.26  5010.9 1915.76
  5014.4 1915.76  5014.7 1916.26  5018.9 1916.72    5025 1916.59  5028.1 1916.91
  5030.2 1917.53  5043.6 1919.74  5062.1  1920.4  5074.5 1922.73  5086.3 1923.98
  5133.3  1926.5  5151.8 1929.44  5161.1 1930.55  5188.9 1931.79  5202.4 1932.88
#Mann= 3 ,-1 , 0
  4946.3      .1       0  5010.7     .05       0  5014.7      .1       0
Bank Sta=5010.7,5014.7
XS Rating Curve= 0 ,0
Exp/Cntr=0.3,0.1

Type RM Length L Ch R = 1 ,5979    ,487,487,487
BEGIN DESCRIPTION:
Stream0480 13.0
END DESCRIPTION:
XS GIS Cut Line= 3
      1893494.62     13919481.27        1893825.       13919125.
        1893925.       13919025.
#Sta/Elev= 30
  4513.4 1951.54  4532.7 1950.75  4558.4 1947.01  4633.4 1939.86    4680 1937.48
  4734.9 1936.46    4770 1934.62  4801.1 1930.52  4835.5 1929.42  4864.1 1922.53
  4892.8 1918.12  4915.8 1916.51  4933.4 1911.22  4951.1 1909.69  4958.2 1907.82
  4968.7 1907.02    4980  1904.9  4980.2  1904.4    4984  1904.9    4995  1905.1
  5007.6 1907.87  5022.7 1917.24  5037.3 1924.02  5043.9 1925.81    5050 1929.38
    5101 1948.38  5114.2 1958.81  5126.9 1963.85  5131.1 1966.86  5140.7 1970.61
#Mann= 3 ,-1 , 0
  4513.4      .1       0    4980     .05       0    4984      .1       0
Bank Sta=4980,4984
XS Rating Curve= 0 ,0
Exp/Cntr=0.3,0.1

Type RM Length L Ch R = 1 ,5492    ,466,466,466
BEGIN DESCRIPTION:
Stream0480 12.0
END DESCRIPTION:
XS GIS Cut Line= 4
      1893590.43     13919562.36        1893975.       13919525.
      1894147.42     13919481.91      1894231.69     13919271.68
#Sta/Elev= 30
  4613.6 1945.59  4635.6 1942.27  4665.9 1939.71  4695.8 1938.99  4716.9 1937.01
    4744  1932.7  4789.2 1930.06  4812.3 1924.82    4839 1921.26  4888.4 1912.78
  4936.9 1909.04    4952 1902.47  4967.1 1899.63  4976.3 1899.48  4995.2 1895.69
  4995.5 1895.19  4999.2 1895.69  5003.3 1896.73    5025 1909.32  5046.6 1919.36
  5052.7 1921.26  5077.5 1932.44  5099.2 1940.06  5136.3 1946.43  5187.2 1953.64
  5213.1 1959.14    5268 1962.06  5293.9 1964.95    5352 1976.17  5404.2 1978.59
#Mann= 3 ,-1 , 0
  4613.6      .1       0  4995.2     .05       0  4999.2      .1       0
Bank Sta=4995.2,4999.2
XS Rating Curve= 0 ,0
Exp/Cntr=0.3,0.1

Type RM Length L Ch R = 1 ,5026    ,488,488,488
BEGIN DESCRIPTION:
Stream0480 11.0
END DESCRIPTION:
XS GIS Cut Line= 3
      1893593.28     13920043.51        1893925.       13919975.
      1894346.15     13919789.79
#Sta/Elev= 30
  4661.8 1973.37  4678.1 1972.53  4696.5 1969.18    4721 1966.97  4736.3 1964.39
  4747.4 1964.03  4788.4 1957.88    4819 1955.34  4837.4 1951.98  4867.1 1943.92
  4889.5 1940.85  4920.1 1930.41  4938.5 1920.58  4944.6 1918.23  4969.1 1904.11
  4990.5 1888.59  4999.7 1887.31  5004.2  1885.7  5004.5  1885.2  5008.2  1885.7
  5043.9 1892.99  5078.3 1903.64  5183.2 1913.25  5206.1 1913.87    5275 1919.75
  5360.2 1932.15  5367.1 1934.04  5400.9 1938.92    5429 1944.36  5460.6 1947.21
#Mann= 3 ,-1 , 0
  4661.8      .1       0  5004.2     .05       0  5008.2      .1       0
Bank Sta=5004.2,5008.2
XS Rating Curve= 0 ,0
Exp/Cntr=0.3,0.1

Type RM Length L Ch R = 1 ,4538    ,457,457,457
BEGIN DESCRIPTION:
Stream0480 10.0
END DESCRIPTION:
XS GIS Cut Line= 3
      1894176.89     13920350.74        1894325.       13920125.
      1894476.08     13919813.83
#Sta/Elev= 30
    4730 1928.99  4767.5  1926.1    4836 1916.82  4857.5 1914.83  4893.4 1908.46
  4918.5 1905.82  4936.6 1901.22  4954.4 1894.39  4961.6  1890.1  4965.2 1886.24
  4969.4 1883.18  4986.7 1880.18    4999 1879.69  4999.2 1879.19    5003 1879.69
  5023.4 1882.14  5034.3  1887.9  5042.1 1890.12  5057.8 1896.81  5074.4 1905.76
  5084.4 1910.07  5097.7 1911.66  5124.4  1917.2  5134.4 1920.23  5160.8 1925.39
  5207.8 1937.74  5248.5 1946.67  5287.8 1951.95  5325.6 1960.18  5345.9 1962.74
#Mann= 4 ,-1 , 0
    4730     .07       0    4999     .05       0    5003     .07       0
  5042.1      .1       0
Bank Sta=4999,5003
XS Rating Curve= 0 ,0
Exp/Cntr=0.3,0.1

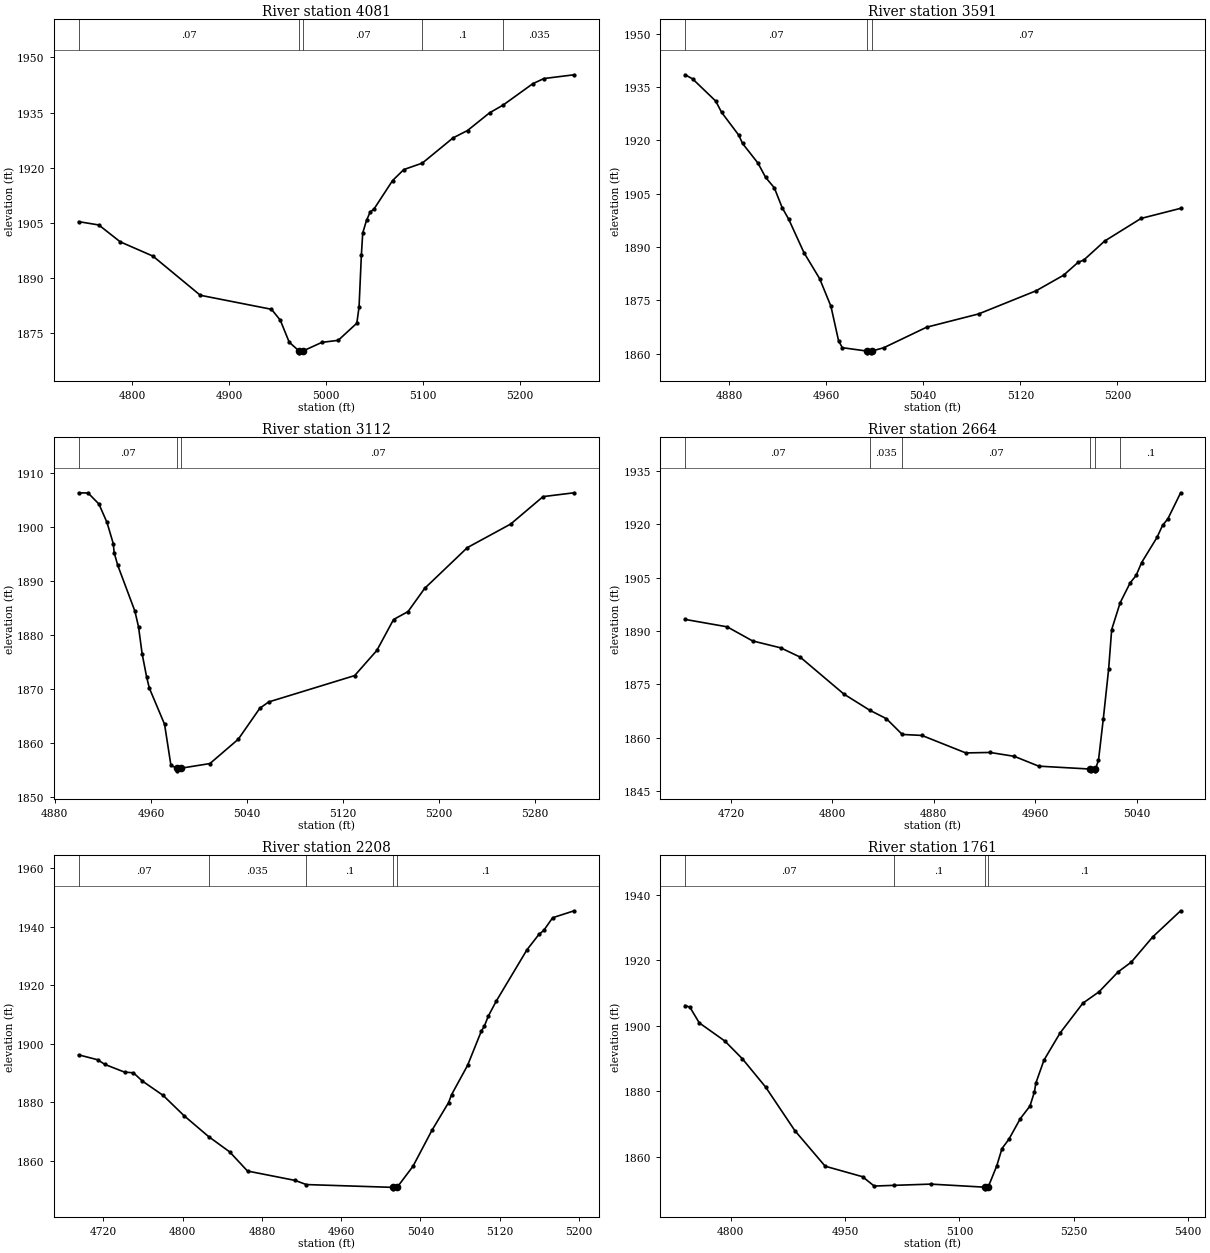
Type RM Length L Ch R = 1 ,4081    ,490,490,490
BEGIN DESCRIPTION:
Stream0480 9.0
END DESCRIPTION:
XS GIS Cut Line= 3
      1894425.04     13920374.99        1894675.       13920325.
      1894836.05     13920125.11
#Sta/Elev= 30
  4744.4 1905.35  4765.2 1904.45  4787.4 1899.86  4821.1 1895.99    4870 1885.35
  4943.5 1881.54  4952.6 1878.58  4961.8  1872.6    4972 1870.21  4972.3 1869.71
    4976 1870.21  4995.5 1872.55  5012.4 1873.11  5031.6 1877.76  5033.9 1882.13
  5036.3 1896.22  5037.7 1902.27  5041.6 1905.69  5045.4 1907.98  5049.3 1908.76
  5068.5 1916.51  5080.1  1919.5  5099.2 1921.25    5131 1928.11  5145.9 1930.11
  5168.7 1934.92  5182.7 1937.03  5213.3 1942.83  5224.8 1944.23    5256 1945.25
#Mann= 5 ,-1 , 0
  4744.4     .07       0    4972     .05       0    4976     .07       0
  5099.2      .1       0  5182.7    .035       0
Bank Sta=4972,4976
XS Rating Curve= 0 ,0
Exp/Cntr=0.3,0.1

Type RM Length L Ch R = 1 ,3591    ,479,479,479
BEGIN DESCRIPTION:
Stream0480 8.0
END DESCRIPTION:
XS GIS Cut Line= 3
        1894525.     13920924.99        1894575.       13920775.
        1894725.       13920575.
#Sta/Elev= 30
  4843.9 1938.47  4850.1 1937.31  4869.1 1931.08    4874 1927.88  4888.1 1921.48
  4891.2 1919.15  4903.9 1913.63  4910.2 1909.61  4917.4 1906.66  4923.8 1901.12
  4929.2 1897.85  4941.8 1888.43  4954.7 1881.12    4964 1873.35  4970.3 1863.63
  4973.4  1861.7  4993.6 1860.75  4993.8 1860.25  4997.3 1860.25  4997.6 1860.75
  5007.4 1861.67  5042.8 1867.46  5085.7  1871.2  5133.1 1877.73  5155.6 1882.09
  5167.4 1885.67  5172.4  1886.4  5189.4 1891.69  5219.4 1898.06    5252  1900.9
#Mann= 3 ,-1 , 0
  4843.9     .07       0  4993.6     .05       0  4997.6     .07       0
Bank Sta=4993.6,4997.6
XS Rating Curve= 0 ,0
Exp/Cntr=0.3,0.1

Type RM Length L Ch R = 1 ,3112    ,448,448,448
BEGIN DESCRIPTION:
Stream0480 7.0
END DESCRIPTION:
XS GIS Cut Line= 3
        1894975.     13920824.97        1894975.       13920725.
      1894749.37     13920508.17
#Sta/Elev= 30
  4899.8 1906.37  4907.7 1906.32  4916.7 1904.29  4923.4 1900.88  4928.7 1896.91
  4929.4 1895.26  4932.4 1892.91  4946.7  1884.4  4949.7  1881.5  4952.7 1876.52
  4956.4 1872.26  4958.7 1870.14  4971.4 1863.43  4976.7 1855.82  4981.4 1855.29
  4981.7 1854.79  4985.4 1855.29  5009.2 1856.14  5032.8 1860.65  5050.8 1866.41
  5058.2 1867.57  5129.8 1872.46  5148.3 1877.13  5162.2 1882.86  5174.3 1884.34
  5188.1 1888.63  5223.7  1896.2  5259.8 1900.57  5286.8 1905.66  5312.7 1906.37
#Mann= 3 ,-1 , 0
  4899.8     .07       0  4981.4     .05       0  4985.4     .07       0
Bank Sta=4981.4,4985.4
XS Rating Curve= 0 ,0
Exp/Cntr=0.3,0.1

Type RM Length L Ch R = 1 ,2664    ,456,456,456
BEGIN DESCRIPTION:
Stream0480 6.0
END DESCRIPTION:
XS GIS Cut Line= 3
      1895175.01     13920824.99        1895375.       13920575.
      1895425.03     13920524.97
#Sta/Elev= 30
  4683.9 1893.27  4717.1 1891.18  4737.1 1887.22  4759.3 1885.27  4774.7 1882.66
  4809.1 1872.28  4829.6 1867.71  4842.7 1865.34  4855.2 1860.91  4870.7 1860.63
  4905.3 1855.71  4924.5 1855.84  4943.6 1854.75  4962.8 1851.99  5003.6 1851.17
  5003.8 1850.67  5007.3 1850.67  5007.6 1851.17    5010 1853.65  5013.8 1865.32
    5018 1879.26  5020.4 1890.41  5027.1 1897.97    5035 1903.56  5039.7 1905.64
    5044 1909.25  5056.2 1916.36  5060.5  1919.7  5064.7 1921.54  5074.8 1928.89
#Mann= 6 ,-1 , 0
  4683.9     .07       0  4829.6    .035       0  4855.2     .07       0
  5003.6     .05       0  5007.6     .07       0  5027.1      .1       0
Bank Sta=5003.6,5007.6
XS Rating Curve= 0 ,0
Exp/Cntr=0.3,0.1

Type RM Length L Ch R = 1 ,2208    ,447,447,447
BEGIN DESCRIPTION:
Stream0480 5.0
END DESCRIPTION:
XS GIS Cut Line= 3
      1895224.96       13920975.        1895525.       13920975.
      1895724.96       13920975.
#Sta/Elev= 30
  4695.1 1896.22  4714.4 1894.53  4721.5 1892.96  4741.4 1890.32  4750.4 1890.08
  4759.4 1887.27  4780.4 1882.35  4801.4 1875.45  4826.2 1868.31  4847.5 1863.06
  4865.5 1856.52  4913.5 1853.32  4924.8  1851.9  5012.4 1850.94  5012.6 1850.44
  5016.4 1850.94  5032.4 1858.12  5051.5 1870.38  5068.4 1879.93  5071.4 1882.62
  5087.5 1892.59  5101.4  1904.3  5104.4 1905.98  5108.5 1909.48  5116.4 1914.53
  5147.5 1932.13  5159.5 1937.35  5164.4 1938.73  5173.4 1943.07  5195.1 1945.44
#Mann= 5 ,-1 , 0
  4695.1     .07       0  4826.2    .035       0  4924.8      .1       0
  5012.4     .05       0  5016.4      .1       0
Bank Sta=5012.4,5016.4
XS Rating Curve= 0 ,0
Exp/Cntr=0.3,0.1

Type RM Length L Ch R = 1 ,1761    ,417,417,417
BEGIN DESCRIPTION:
Stream0480 4.0
END DESCRIPTION:
XS GIS Cut Line= 4
      1895174.97     13921274.99        1895425.       13921325.
      1895585.39     13921313.35      1895724.97     13921125.04
#Sta/Elev= 30
  4740.1 1906.15  4746.4 1905.65  4758.7 1900.87  4792.3 1895.33  4815.2 1889.94
  4845.8 1881.29    4884 1868.05  4923.9 1857.17  4972.9 1853.97  4988.2 1851.12
  5013.6 1851.33  5062.5 1851.71  5133.7 1850.77  5133.9 1850.27  5137.7 1850.77
    5149 1857.26  5155.9 1862.56  5164.9 1865.37  5179.9 1871.67  5192.6 1875.51
  5198.5 1879.88  5200.3  1882.5    5211 1889.52  5232.1 1897.78    5262 1906.87
  5283.3 1910.36  5308.4 1916.45  5325.5 1919.38  5353.8 1927.11  5390.3 1935.05
#Mann= 4 ,-1 , 0
  4740.1     .07       0  5013.6      .1       0  5133.7     .05       0
  5137.7      .1       0
Bank Sta=5133.7,5137.7
XS Rating Curve= 0 ,0
Exp/Cntr=0.3,0.1

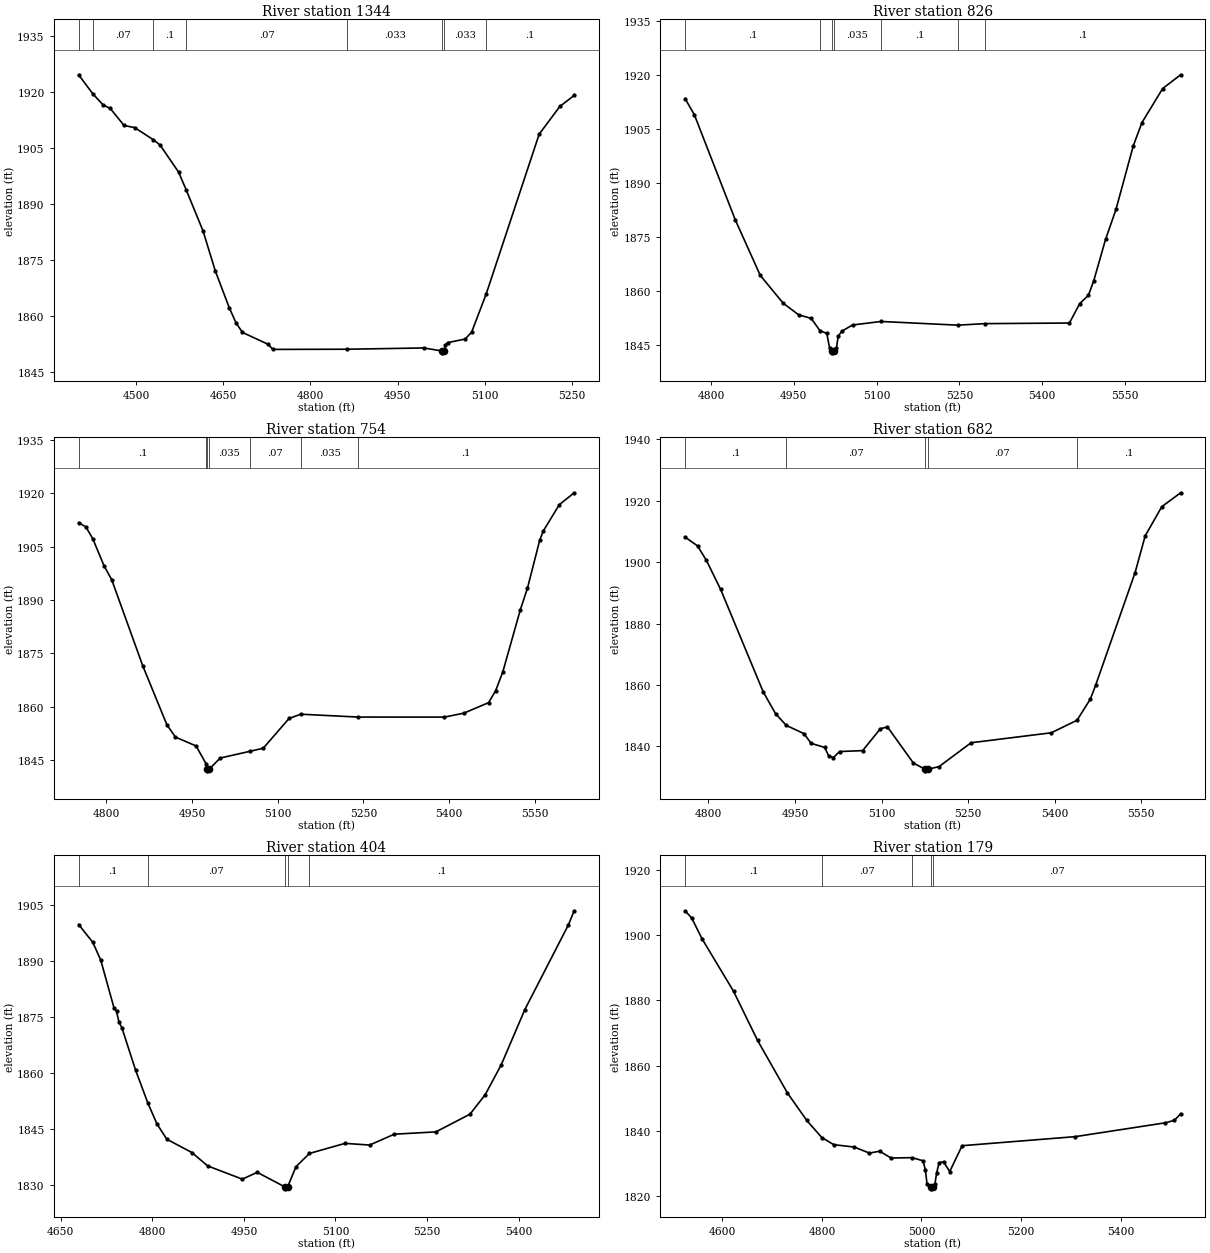
Type RM Length L Ch R = 1 ,1344    ,518,518,518
BEGIN DESCRIPTION:
Stream0480 3.0
END DESCRIPTION:
XS GIS Cut Line= 3
      1895025.01       13921625.        1895625.       13921575.
      1895775.02     13921374.98
#Sta/Elev= 30
  4401.5 1924.72    4426 1919.59  4443.5 1916.65  4455.9 1915.68  4479.6 1911.12
  4498.1 1910.53    4530 1907.28  4541.5 1905.88  4573.3 1898.62  4586.3  1893.9
  4615.5 1882.79  4636.5 1872.08  4660.6 1862.17  4672.1 1858.16  4683.2 1855.58
  4726.8 1852.43  4735.9 1851.02  4863.4 1851.07  4994.8 1851.41  5026.4  1850.6
  5026.7  1850.1  5030.4  1850.6  5032.2 1852.22  5035.9 1852.84  5065.9 1853.79
  5077.2 1855.62  5102.4 1865.93  5193.4 1908.78    5229 1916.23  5253.6 1919.18
#Mann= 8 ,-1 , 0
  4401.5      .1       0    4426     .07       0    4530      .1       0
  4586.3     .07       0  4863.4    .033       0  5026.4    .033       0
  5030.4    .033       0  5102.4      .1       0
Bank Sta=5026.4,5030.4
XS Rating Curve= 0 ,0
Exp/Cntr=0.3,0.1

Type RM Length L Ch R = 1 ,826     ,72,72,72
BEGIN DESCRIPTION:
Mapping XS 172e3648
END DESCRIPTION:
XS GIS Cut Line= 4
      1895551.77     13922254.75      1895668.12     13921954.11
      1895734.58     13921666.18      1895813.94     13921397.83
#Sta/Elev= 30
  4753.1 1913.54  4769.9 1909.05  4843.9 1879.91  4889.2 1864.47  4930.7 1856.73
  4958.8  1853.5  4981.6  1852.5  4997.3 1849.12  5009.8 1848.33  5014.8 1844.35
  5018.7 1843.44    5019 1842.94  5022.8 1843.44  5027.2 1844.16  5030.4 1847.54
  5036.9 1848.94  5056.4 1850.67    5108 1851.65  5247.3 1850.63  5296.1 1851.05
  5449.3 1851.22    5468 1856.61  5483.7 1858.91  5493.2 1862.86  5514.8 1874.44
  5533.7 1882.79    5565 1900.43  5580.7 1906.88  5618.2 1916.34  5650.8 1920.16
#Mann= 7 ,-1 , 0
  4753.1      .1       0  4997.3    .035       0  5018.7    .035       0
  5022.8    .035       0    5108      .1       0  5247.3    .033       0
  5296.1      .1       0
Bank Sta=5018.7,5022.8
XS Rating Curve= 0 ,0
Exp/Cntr=0.3,0.1

Type RM Length L Ch R = 1 ,754     ,72,72,72
BEGIN DESCRIPTION:
Mapping XS ebb23806
END DESCRIPTION:
XS GIS Cut Line= 3
      1895688.21     13922272.79      1895726.96     13921889.38
      1895846.33     13921421.84
#Sta/Elev= 30
  4751.2 1911.72    4764  1910.5    4776 1907.21  4795.6 1899.64  4809.2 1895.68
  4863.5 1871.55  4905.7 1855.02  4920.8 1851.53  4956.9 1849.06  4974.4 1844.06
    4976 1842.57  4976.2 1842.07  4980.1 1842.57  4999.1 1845.66  5050.7 1847.53
  5074.5 1848.41  5119.8 1856.78  5140.3 1857.96    5241 1857.16  5391.8 1857.15
  5425.8 1858.25  5469.2  1861.2  5481.6 1864.58    5494 1869.78  5524.9 1887.32
  5537.3 1893.34    5559 1906.93  5565.2 1909.43    5593 1916.75  5619.1  1920.1
#Mann= 7 ,-1 , 0
  4751.2      .1       0  4974.4    .035       0    4976    .035       0
  4980.1    .035       0  5050.7     .07       0  5140.3    .035       0
    5241      .1       0
Bank Sta=4976,4980.1
XS Rating Curve= 0 ,0
Exp/Cntr=0.3,0.1

Type RM Length L Ch R = 1 ,682     ,278,278,278
BEGIN DESCRIPTION:
Mapping XS 1fdae5fd
END DESCRIPTION:
XS GIS Cut Line= 3
      1895731.61     13922260.04      1895822.47     13921859.51
      1895928.68     13921424.39
#Sta/Elev= 30
  4759.5 1908.17    4781 1905.31  4796.4 1900.59  4821.1 1891.12  4894.8 1857.75
  4916.3 1850.62  4934.8 1846.82  4965.5 1844.12  4977.9 1840.97  5001.5 1839.62
  5008.6 1836.74  5016.6 1836.35  5027.1 1838.29  5067.1  1838.6  5097.8 1845.72
  5110.1 1846.32  5155.2 1834.51  5175.8 1832.51    5176 1832.01  5179.9 1832.51
  5199.5 1833.39    5255 1841.16    5394 1844.41  5438.6 1848.49  5461.9 1855.49
  5471.2  1860.1  5539.1 1896.56  5556.7 1908.58  5585.5 1918.09  5618.1 1922.61
#Mann= 5 ,-1 , 0
  4759.5      .1       0  4934.8     .07       0  5175.8    .035       0
  5179.9     .07       0  5438.6      .1       0
Bank Sta=5175.8,5179.9
XS Rating Curve= 0 ,0
Exp/Cntr=0.3,0.1

Type RM Length L Ch R = 1 ,404     ,225,225,225
BEGIN DESCRIPTION:
Stream0480 1.0
END DESCRIPTION:
XS GIS Cut Line= 3
      1895775.03     13922224.97      1895995.41     13922017.61
      1896125.01     13921524.97
#Sta/Elev= 30
  4679.1 1899.78  4702.3    1895  4715.4  1890.2    4737 1877.46  4741.2 1876.46
  4745.3 1873.54  4749.9 1872.14  4772.3 1860.79  4792.3 1852.02  4807.3 1846.36
  4823.6 1842.21  4864.7 1838.64  4890.5 1835.06  4947.3 1831.51  4971.8 1833.33
  5017.3 1829.41  5017.6 1828.91  5021.5 1829.41  5035.2 1834.83  5057.3  1838.4
  5115.6  1841.1  5155.9 1840.65  5196.3 1843.56  5264.5 1844.18  5320.4 1848.93
  5345.2 1854.12  5371.7 1862.21  5410.3 1876.98  5481.7 1899.71  5491.1 1903.46
#Mann= 5 ,-1 , 0
  4679.1      .1       0  4792.3     .07       0  5017.3     .05       0
  5021.5     .07       0  5057.3      .1       0
Bank Sta=5017.3,5021.5
XS Rating Curve= 0 ,0
Exp/Cntr=0.3,0.1

Type RM Length L Ch R = 1 ,179     ,150,150,150
BEGIN DESCRIPTION:
Stream0480 0.0
END DESCRIPTION:
XS GIS Cut Line= 4
      1895714.02     13922314.11      1896017.53     13922296.12
      1896191.83     13922112.76      1896284.99     13921684.09
#Sta/Elev= 30
    4525 1907.53  4538.2 1905.32  4559.3 1898.86  4622.4 1882.79  4670.5 1867.74
  4730.7 1851.56  4769.6 1843.12  4799.7 1837.88  4823.7  1835.7  4864.9 1834.96
  4895.3 1833.11    4916 1833.69  4938.9 1831.59  4981.1 1831.71  5002.9 1830.75
  5007.8    1828  5011.2 1823.53  5018.4 1822.63  5018.7 1822.13  5022.6 1822.63
  5026.9 1823.54  5030.4    1827  5035.4 1830.16  5044.3 1830.45  5056.7 1827.43
  5081.6 1835.38  5308.9 1838.16    5490 1842.41  5508.3 1843.18  5520.7 1845.18
#Mann= 5 ,-1 , 0
    4525      .1       0  4799.7     .07       0  4981.1     .07       0
  5018.4     .05       0  5022.6     .07       0
Bank Sta=5018.4,5022.6
XS Rating Curve= 0 ,0
Exp/Cntr=0.3,0.1

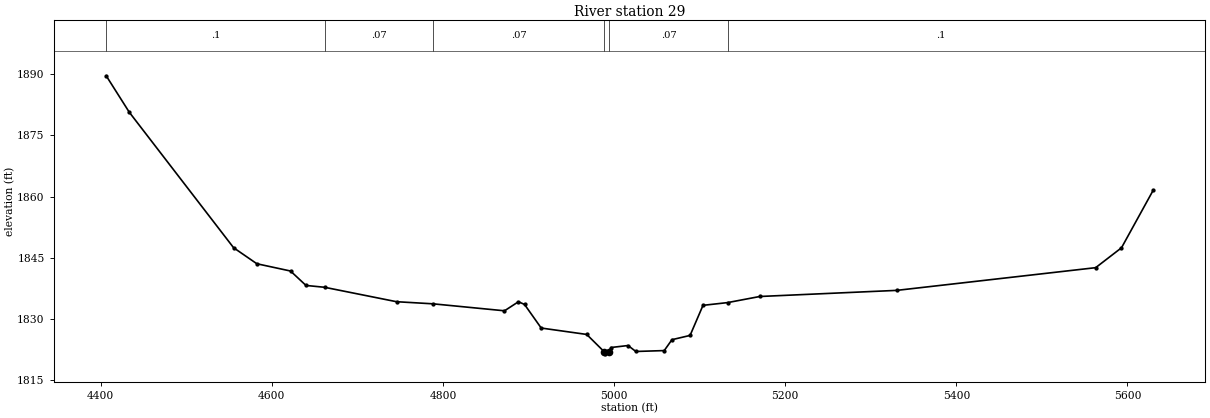
Type RM Length L Ch R = 1 ,29      ,0,0,0
BEGIN DESCRIPTION:
Stream0480 0.1
END DESCRIPTION:
XS GIS Cut Line= 4
      1895720.37     13922426.33      1896155.31     13922374.24
      1896256.87     13922251.84      1896327.19      13921629.4
#Sta/Elev= 30
  4406.4 1889.65  4433.4  1880.7  4555.3 1847.46  4582.5 1843.53  4621.8 1841.75
  4639.9 1838.21  4661.6 1837.76  4745.7 1834.22  4788.4  1833.7  4871.9 1831.99
  4888.2 1834.21  4895.3 1833.55  4914.8 1827.76    4968 1826.19  4988.5 1821.93
    4989 1821.43  4994.6 1821.93  4996.2 1822.98  5016.3 1823.47  5025.4 1822.01
  5058.6 1822.23  5067.6  1824.9  5088.8 1825.95  5103.9 1833.33  5132.6    1834
  5170.3  1835.5  5330.3    1837  5562.8 1842.57    5593 1847.45  5629.9 1861.51
#Mann= 6 ,-1 , 0
  4406.4      .1       0  4661.6     .07       0  4788.4     .07       0
  4988.5     .05       0  4994.6     .07       0  5132.6      .1       0
Bank Sta=4988.5,4994.6
XS Rating Curve= 0 ,0
Exp/Cntr=0.3,0.1

Chan Stop Cuts=-1
Use User Specified Reach Order=0
Composite Channel Slope=5