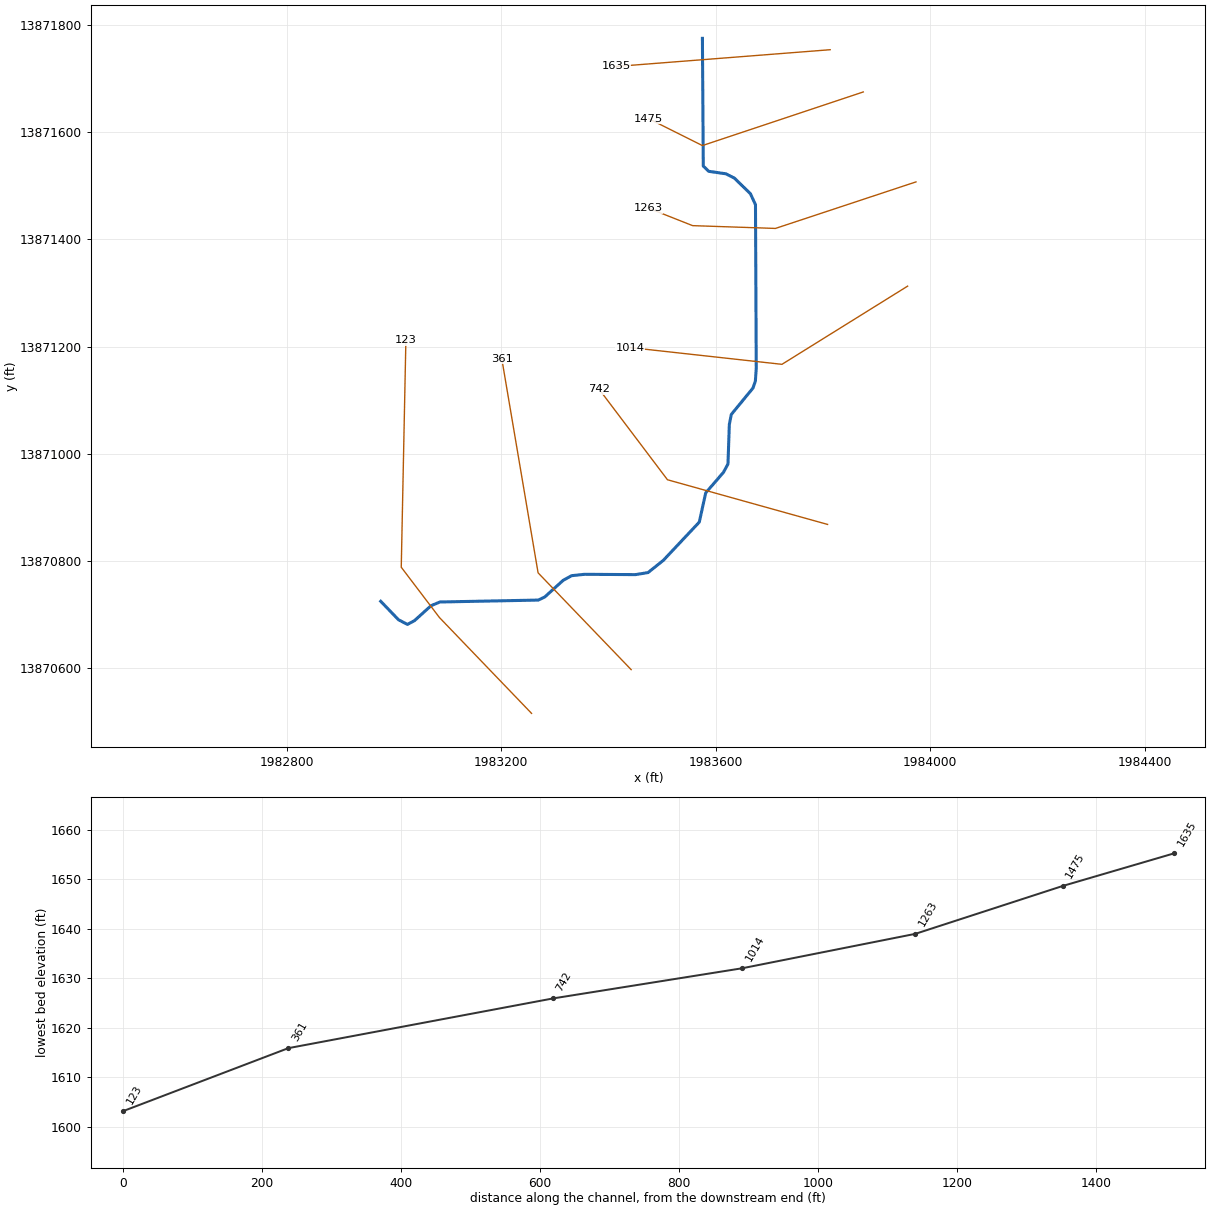
--- Stream0481.prj (project) ---

Proj Title=Stream0481 Base Level Engineering
Current Plan=p01
Default Exp/Contr=0.3,0.1
English Units
Geom File=g01
Flow File=f01
Plan File=p01
Y Axis Title=Elevation
X Axis Title(PF)=Main Channel Distance
X Axis Title(XS)=Station
BEGIN DESCRIPTION:
Stream0481
END DESCRIPTION:
DSS Export Rating Curves= 0
DSS Export Rating Curve Sorted= 0
DSS Export Volume Flow Curves= 0
DXF OffsetX= 0
DXF OffsetY= 0
DXF ScaleX= 1
DXF ScaleY= 10

--- Stream0481.p01 (plan) ---

Plan Title=Multiple Run
Short Identifier=Multiple
Geom File=g01
Flow File=f01
Subcritical Flow
K Sum by GR= 0
Std Step Tol= 0.01
Critical Tol= 0.01
Num of Std Step Trials= 20
Max Error Tol= 0.3
Flow Tol Ratio= 0.001
Split Flow NTrial= 30
Split Flow Tol= 0.02
Split Flow Ratio= 0.02
Log Output Level= 0
Friction Slope Method= 1
Unsteady Friction Slope Method= 2
Unsteady Bridges Friction Slope Method= 1
Parabolic Critical Depth
Global Vel Dist=  1 , 1 , 1
Global Log Level= 0
CheckData=True
Encroach Param= -1, 0, 0, 0
BEGIN DESCRIPTION:
Multiple Run
END DESCRIPTION:

--- Stream0481.f01 (steady flow) ---

Flow Title=Multiple
Number of Profiles=7
Profile Names=10-year,25-year,50-year,1pct_min,100-year,1pct_plu,500-year
River Rch & RM= Stream0481,Reach-1,1635
     368     588     787     514    1025    2046    1713
Boundary for River Rch & Prof#=Stream0481,Reach-1,1
Up Type=0
Dn Type=3
Dn Slope=0.005
Boundary for River Rch & Prof#=Stream0481,Reach-1,2
Up Type=0
Dn Type=3
Dn Slope=0.005
Boundary for River Rch & Prof#=Stream0481,Reach-1,3
Up Type=0
Dn Type=3
Dn Slope=0.005
Boundary for River Rch & Prof#=Stream0481,Reach-1,4
Up Type=0
Dn Type=3
Dn Slope=0.005
Boundary for River Rch & Prof#=Stream0481,Reach-1,5
Up Type=0
Dn Type=3
Dn Slope=0.005
Boundary for River Rch & Prof#=Stream0481,Reach-1,6
Up Type=0
Dn Type=3
Dn Slope=0.005
Boundary for River Rch & Prof#=Stream0481,Reach-1,7
Up Type=0
Dn Type=3
Dn Slope=0.005

--- Stream0481.g01 (geometry) ---

Geom Title=Existing Conditions
Program Version=4.10

River Reach=Stream0481      ,Reach-1
Reach XY= 30
        1983575.       13871775.      1983576.64     13871536.83
      1983586.74       13871527.      1983618.68     13871522.35
      1983634.75     13871514.25       1983664.6      13871485.1
      1983673.99     13871464.71      1983675.43     13871159.82
      1983673.78      13871135.5      1983669.26     13871122.66
      1983628.86      13871073.4      1983625.24      13871054.9
      1983622.67     13870980.97      1983614.16     13870965.35
      1983581.14     13870927.17      1983569.18     13870872.69
      1983501.93     13870801.14      1983473.54     13870778.54
      1983450.12     13870774.73      1983354.87     13870775.32
      1983330.94     13870772.73      1983315.36     13870764.14
      1983281.06     13870733.14      1983269.06     13870727.26
      1983085.42     13870723.69      1983068.78     13870716.71
      1983038.11     13870688.97      1983024.86     13870681.91
      1983008.16     13870690.54        1982975.       13870725.

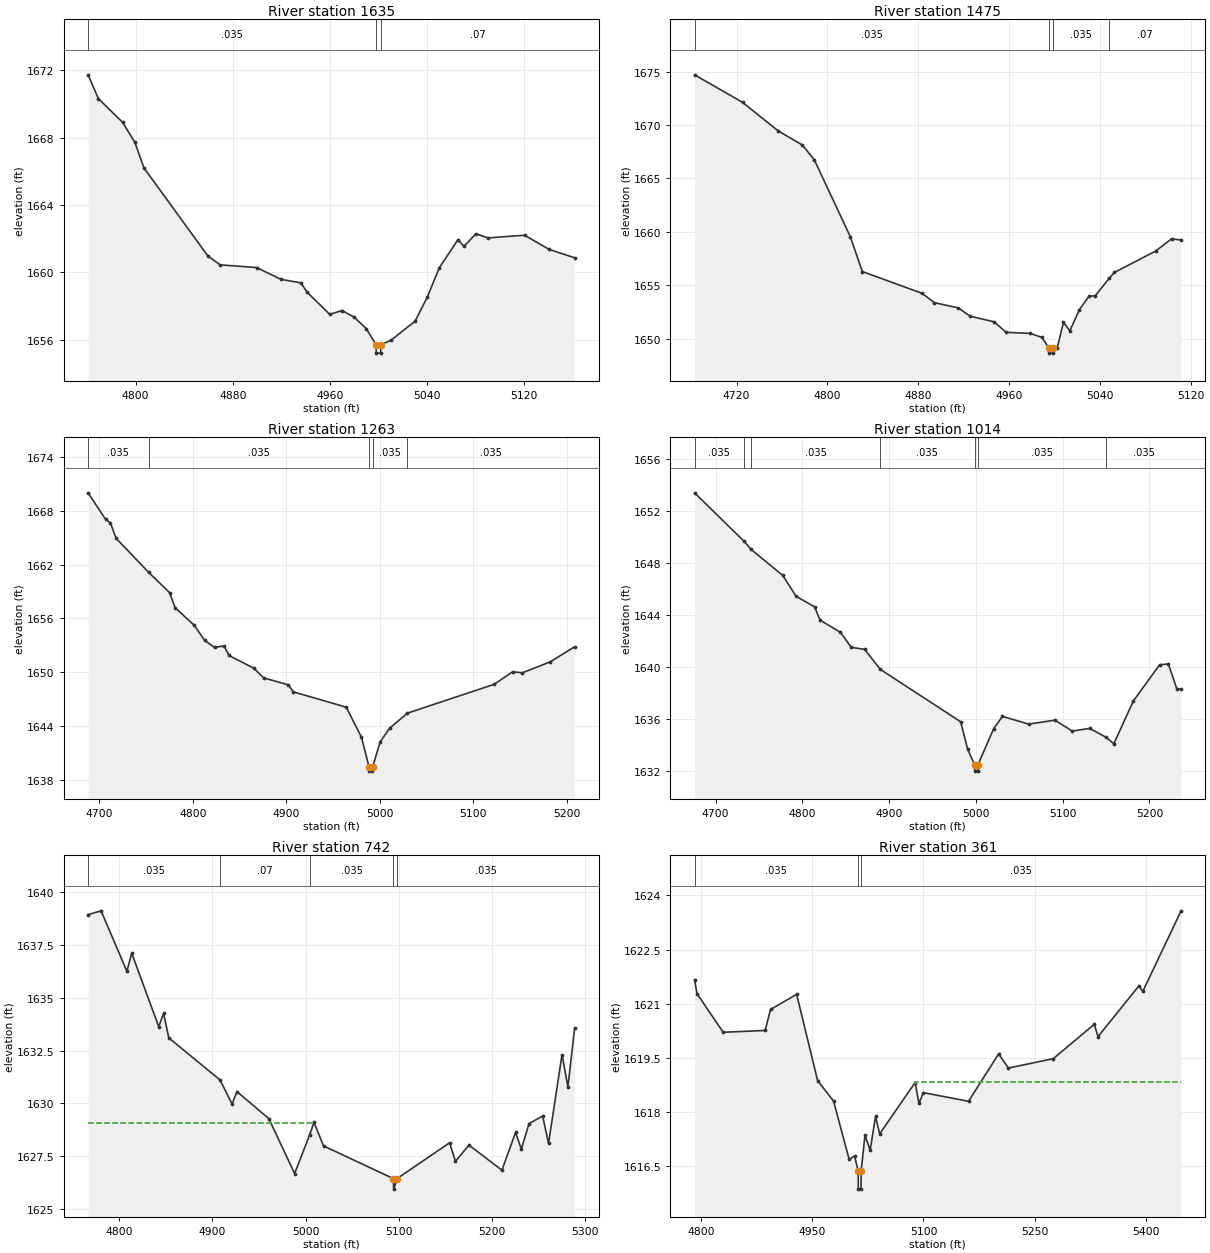
Type RM Length L Ch R = 1 ,1635    ,160,160,160
BEGIN DESCRIPTION:
Stream0481 2.0
END DESCRIPTION:
XS GIS Cut Line= 2
      1983813.35     13871753.78      1983413.97     13871722.52
#Sta/Elev= 30
  4760.9 1671.73  4769.3 1670.32  4789.3 1668.91  4799.4 1667.72  4806.9  1666.2
  4859.6 1660.97  4869.6 1660.45  4899.7 1660.29  4919.7 1659.59  4936.1 1659.38
  4941.2 1658.83  4959.9 1657.51  4969.9 1657.74  4979.9 1657.35  4989.9 1656.67
    4998 1655.71  4998.2 1655.21  5001.7 1655.21    5002 1655.71    5010 1655.96
  5030.1  1657.1  5040.1 1658.52  5050.1 1660.28  5065.4 1661.94  5070.4 1661.55
  5080.2 1662.29  5090.3 1662.05  5120.3 1662.21  5140.4 1661.37  5161.5 1660.87
#Mann= 3 ,-1 , 0
  4760.9    .035       0    4998    .035       0    5002     .07       0
Bank Sta=4998,5002
XS Rating Curve= 0 ,0
Exp/Cntr=0.3,0.1

Type RM Length L Ch R = 1 ,1475    ,212,212,212
BEGIN DESCRIPTION:
Stream0481 1.0
END DESCRIPTION:
XS GIS Cut Line= 3
      1983875.03     13871675.01        1983575.       13871575.
      1983474.97     13871625.02
#Sta/Elev= 30
  4683.1  1674.7  4725.3 1672.12  4756.9 1669.43    4778 1668.12  4788.5 1666.73
  4820.2 1659.52  4830.7 1656.27  4883.4 1654.23    4894 1653.36    4915 1652.87
  4925.6 1652.09  4946.7 1651.56  4957.2 1650.58  4978.3 1650.48  4988.8  1650.1
  4994.7 1649.13    4995 1648.63  4998.5 1648.63  4998.7 1649.13  5002.2 1649.13
  5007.7 1651.51  5013.3 1650.72  5021.7  1652.7  5030.1 1653.95  5035.7 1654.01
    5048 1655.64  5052.5 1656.19  5088.8 1658.19  5102.8 1659.34  5111.2 1659.22
#Mann= 4 ,-1 , 0
  4683.1    .035       0  4994.7    .035       0  4998.7    .035       0
    5048     .07       0
Bank Sta=4994.7,4998.7
XS Rating Curve= 0 ,0
Exp/Cntr=0.3,0.1

Type RM Length L Ch R = 1 ,1263    ,249,249,249
BEGIN DESCRIPTION:
Stream0481 3.0
END DESCRIPTION:
XS GIS Cut Line= 4
      1983973.36     13871507.24      1983711.22     13871420.44
      1983556.71     13871425.65      1983473.34     13871458.65
#Sta/Elev= 30
    4688 1670.03  4706.6 1667.08  4711.8 1666.68  4717.9 1664.96  4752.7 1661.16
  4775.2 1658.88  4781.1  1657.2  4801.7 1655.22  4812.7 1653.55  4823.2 1652.77
  4833.4 1652.94  4838.7 1651.87  4865.1 1650.46  4875.9 1649.36  4902.1  1648.6
  4907.5 1647.81  4964.1  1646.1  4980.4 1642.75  4988.4 1639.46  4988.6 1638.96
  4992.1 1638.96  4992.4 1639.46  5000.4 1642.22  5010.4 1643.74  5029.5 1645.43
  5122.3 1648.65  5142.1 1650.05  5152.6 1649.94  5182.3 1651.16  5208.4 1652.84
#Mann= 5 ,-1 , 0
    4688    .035       0  4752.7    .035       0  4988.4    .035       0
  4992.4    .035       0  5029.5    .035       0
Bank Sta=4988.4,4992.4
XS Rating Curve= 0 ,0
Exp/Cntr=0.3,0.1

Type RM Length L Ch R = 1 ,1014    ,272,272,272
BEGIN DESCRIPTION:
Stream0481 4.0
END DESCRIPTION:
XS GIS Cut Line= 3
      1983957.76     13871312.81      1983723.37     13871166.97
      1983440.35     13871198.22
#Sta/Elev= 30
  4675.7 1653.42  4732.7 1649.69  4740.8 1649.07  4777.4 1647.06  4792.7 1645.46
    4814 1644.65  4820.3 1643.63  4843.8 1642.69  4856.4 1641.53  4871.8 1641.38
  4889.7 1639.84  4982.4 1635.81  4990.4 1633.71  4998.4 1632.51  4998.7 1632.01
  5002.2 1632.01  5002.4 1632.51  5020.5 1635.28  5030.6 1636.22  5060.8 1635.63
    5091 1635.93  5111.1 1635.09  5131.2  1635.3  5149.8 1634.62    5159 1634.12
  5181.5 1637.41  5211.7 1640.19  5221.8 1640.26  5231.6 1638.34  5236.5 1638.34
#Mann= 7 ,-1 , 0
  4675.7    .035       0  4732.7     .07       0  4740.8    .035       0
  4889.7    .035       0  4998.4    .035       0  5002.4    .035       0
  5149.8    .035       0
Bank Sta=4998.4,5002.4
XS Rating Curve= 0 ,0
Exp/Cntr=0.3,0.1

Type RM Length L Ch R = 1 ,742     ,381,381,381
BEGIN DESCRIPTION:
Stream0481 5.0
END DESCRIPTION:
XS GIS Cut Line= 3
      1983808.43     13870868.36      1983509.83     13870951.69
      1983382.03     13871120.95
#Sta/Elev= 30
  4766.6 1638.95  4780.5 1639.13  4808.2 1636.26  4813.4 1637.12  4842.4 1633.63
  4847.6 1634.26  4853.2  1633.1  4908.2  1631.1  4921.1 1629.96  4926.3 1630.55
  4960.5 1629.27  4988.2 1626.66  5004.4  1628.5    5009 1629.09  5019.3 1627.97
  5094.2 1626.42  5094.5 1625.92  5098.2 1626.42  5154.5 1628.12  5160.8 1627.24
  5175.3 1628.01  5210.7 1626.82  5225.3 1628.61  5231.5 1627.82  5239.8 1629.03
  5254.4 1629.39  5260.7 1628.09  5275.2 1632.31  5281.5 1630.77  5288.7 1633.56
#Mann= 5 ,-1 , 0
  4766.6    .035       0  4908.2     .07       0  5004.4    .035       0
  5094.2    .035       0  5098.2    .035       0
#XS Ineff= 2 , 0
         5008.07 1629.04 5154.71         1628.07
Permanent Ineff=
       F       F
Bank Sta=5094.2,5098.2
XS Rating Curve= 0 ,0
Exp/Cntr=0.3,0.1

Type RM Length L Ch R = 1 ,361     ,238,238,238
BEGIN DESCRIPTION:
Stream0481 6.0
END DESCRIPTION:
XS GIS Cut Line= 3
      1983442.11     13870597.53      1983268.51     13870778.08
       1983200.8     13871177.41
#Sta/Elev= 30
  4791.6 1621.66  4794.8 1621.28  4830.1 1620.21  4886.7 1620.26  4893.9 1620.84
  4929.1 1621.26  4957.4 1618.87  4978.8 1618.31  4999.9 1616.69  5007.1 1616.79
    5012 1616.37  5012.3 1615.87  5015.8 1615.87    5016 1616.37  5021.2 1617.36
  5028.2 1616.95  5035.4 1617.88    5041  1617.4  5088.8 1618.82  5093.9 1618.24
  5099.8 1618.54  5160.7  1618.3  5201.2 1619.61  5214.5 1619.22  5274.9 1619.48
  5330.1 1620.43  5335.2 1620.09  5390.5  1621.5  5395.5 1621.34  5447.1 1623.57
#Mann= 3 ,-1 , 0
  4791.6    .035       0    5012    .035       0    5016    .035       0
#XS Ineff= 2 , 0
                         5089.24         1618.83
Permanent Ineff=
       F       F
Bank Sta=5012,5016
XS Rating Curve= 0 ,0
Exp/Cntr=0.3,0.1

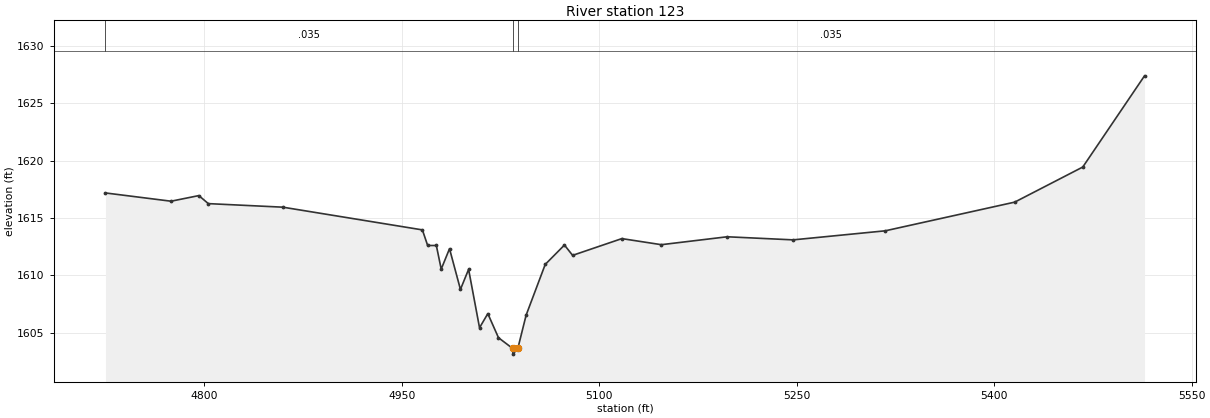
Type RM Length L Ch R = 1 ,123     ,0,0,0
BEGIN DESCRIPTION:
Stream0481 7.0
END DESCRIPTION:
XS GIS Cut Line= 4
      1983256.34     13870515.94      1983084.48     13870694.75
       1983013.3      13870788.5      1983021.94     13871211.89
#Sta/Elev= 30
    4725 1617.18  4774.8 1616.46  4795.9 1616.95  4803.1 1616.25  4859.7 1615.94
  4965.7 1613.96  4969.7  1612.6  4976.3  1612.6    4980 1610.54  4986.3 1612.32
  4994.6 1608.77  5000.8 1610.52  5009.1 1605.43  5015.4 1606.66  5023.5 1604.56
  5034.2 1603.63  5034.5 1603.13  5038.2 1603.63  5044.5 1606.53    5059 1610.95
  5073.6 1612.64  5079.8 1611.74  5117.2  1613.2  5147.2 1612.67  5197.2 1613.36
  5247.3 1613.09  5317.3 1613.88  5415.6 1616.38  5467.3 1619.44  5514.2 1627.39
#Mann= 3 ,-1 , 0
    4725    .035       0  5034.2    .035       0  5038.2    .035       0
Bank Sta=5034.2,5038.2
XS Rating Curve= 0 ,0
Exp/Cntr=0.3,0.1

Chan Stop Cuts=-1
Use User Specified Reach Order=0
Composite Channel Slope=5