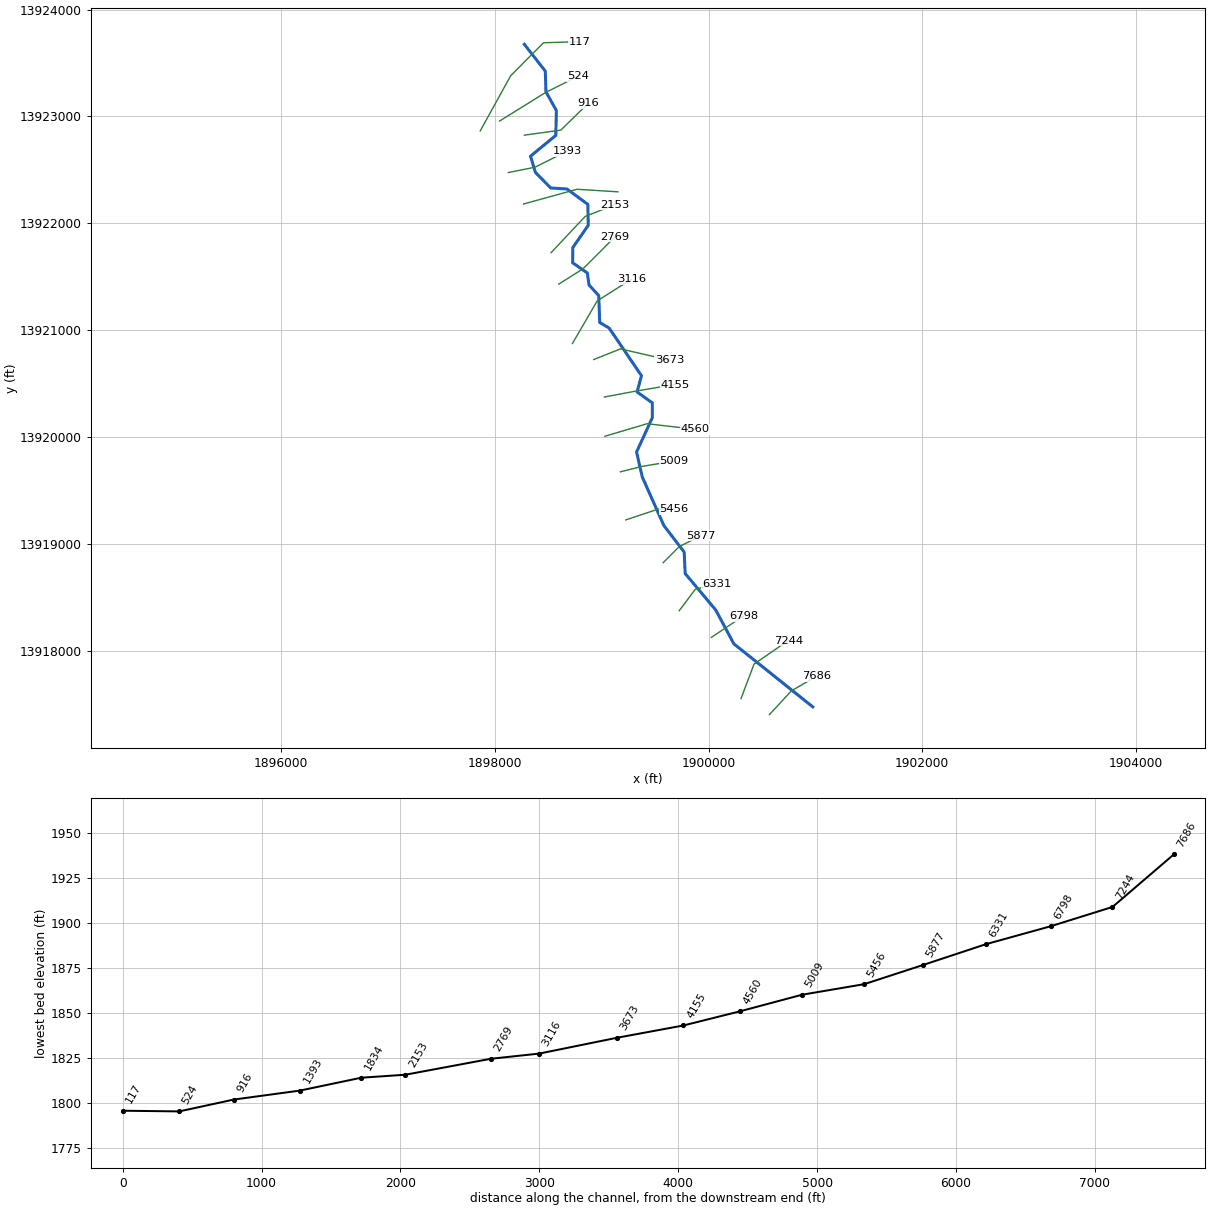
--- Stream0482.prj (project) ---

Proj Title=Stream0482 Base Level Engineering
Current Plan=p01
Default Exp/Contr=0.3,0.1
English Units
Geom File=g01
Flow File=f01
Plan File=p01
BEGIN DESCRIPTION:
Stream0482
END DESCRIPTION:

--- Stream0482.p01 (plan) ---

Plan Title=Multiple Run
Short Identifier=Multiple
Geom File=g01
Flow File=f01
Subcritical Flow
K Sum by GR= 0
Std Step Tol= 0.01
Critical Tol= 0.01
Num of Std Step Trials= 20
Max Error Tol= 0.3
Flow Tol Ratio= 0.001
Split Flow NTrial= 30
Split Flow Tol= 0.02
Split Flow Ratio= 0.02
Log Output Level= 0
Friction Slope Method= 1
Unsteady Friction Slope Method= 2
Unsteady Bridges Friction Slope Method= 1
Parabolic Critical Depth
Global Vel Dist=  1 , 1 , 1
Global Log Level= 0
CheckData=True
Encroach Param= -1, 0, 0, 0
BEGIN DESCRIPTION:
Multiple Run
END DESCRIPTION:

--- Stream0482.f01 (steady flow) ---

Flow Title=Multiple
Number of Profiles=7
Profile Names=10-year,25-year,50-year,1pct_min,100-year,1pct_plu,500-year
River Rch & RM= Stream0482,Reach-1,7686
     501     812    1094     716    1429    2852    2399
River Rch & RM= Stream0482,Reach-1,6331
     873    1465    2021    1350    2694    5376    4722
River Rch & RM= Stream0482,Reach-1,3116
    1323    2275    3188    2159    4308    8595    7766
Boundary for River Rch & Prof#=Stream0482,Reach-1,1
Up Type=0
Dn Type=3
Dn Slope=0.005
Boundary for River Rch & Prof#=Stream0482,Reach-1,2
Up Type=0
Dn Type=3
Dn Slope=0.005
Boundary for River Rch & Prof#=Stream0482,Reach-1,3
Up Type=0
Dn Type=3
Dn Slope=0.005
Boundary for River Rch & Prof#=Stream0482,Reach-1,4
Up Type=0
Dn Type=3
Dn Slope=0.005
Boundary for River Rch & Prof#=Stream0482,Reach-1,5
Up Type=0
Dn Type=3
Dn Slope=0.005
Boundary for River Rch & Prof#=Stream0482,Reach-1,6
Up Type=0
Dn Type=3
Dn Slope=0.005
Boundary for River Rch & Prof#=Stream0482,Reach-1,7
Up Type=0
Dn Type=3
Dn Slope=0.005

--- Stream0482.g01 (geometry) ---

Geom Title=Existing Conditions

River Reach=Stream0482,Reach-1
Reach XY= 30
      1900975.00     13917475.00      1900235.76     13918065.32
      1900066.84     13918381.05      1899780.47     13918722.55
      1899771.25     13918923.45      1899580.52     13919172.57
      1899378.83     13919626.58      1899325.37     13919859.73
      1899472.75     13920180.94      1899473.03     13920319.32
      1899329.99     13920422.45      1899371.66     13920573.28
      1899069.35     13921019.37      1898980.36     13921072.30
      1898971.61     13921323.59      1898880.54     13921422.58
      1898864.61     13921535.10      1898726.97     13921630.68
      1898728.74     13921773.44      1898872.94     13921980.86
      1898869.55     13922177.47      1898673.44     13922321.24
      1898522.55     13922330.47      1898378.61     13922476.50
      1898332.79     13922628.43      1898569.55     13922822.53
      1898574.94     13923054.97      1898477.24     13923230.93
      1898471.25     13923423.45      1898275.00     13923675.00

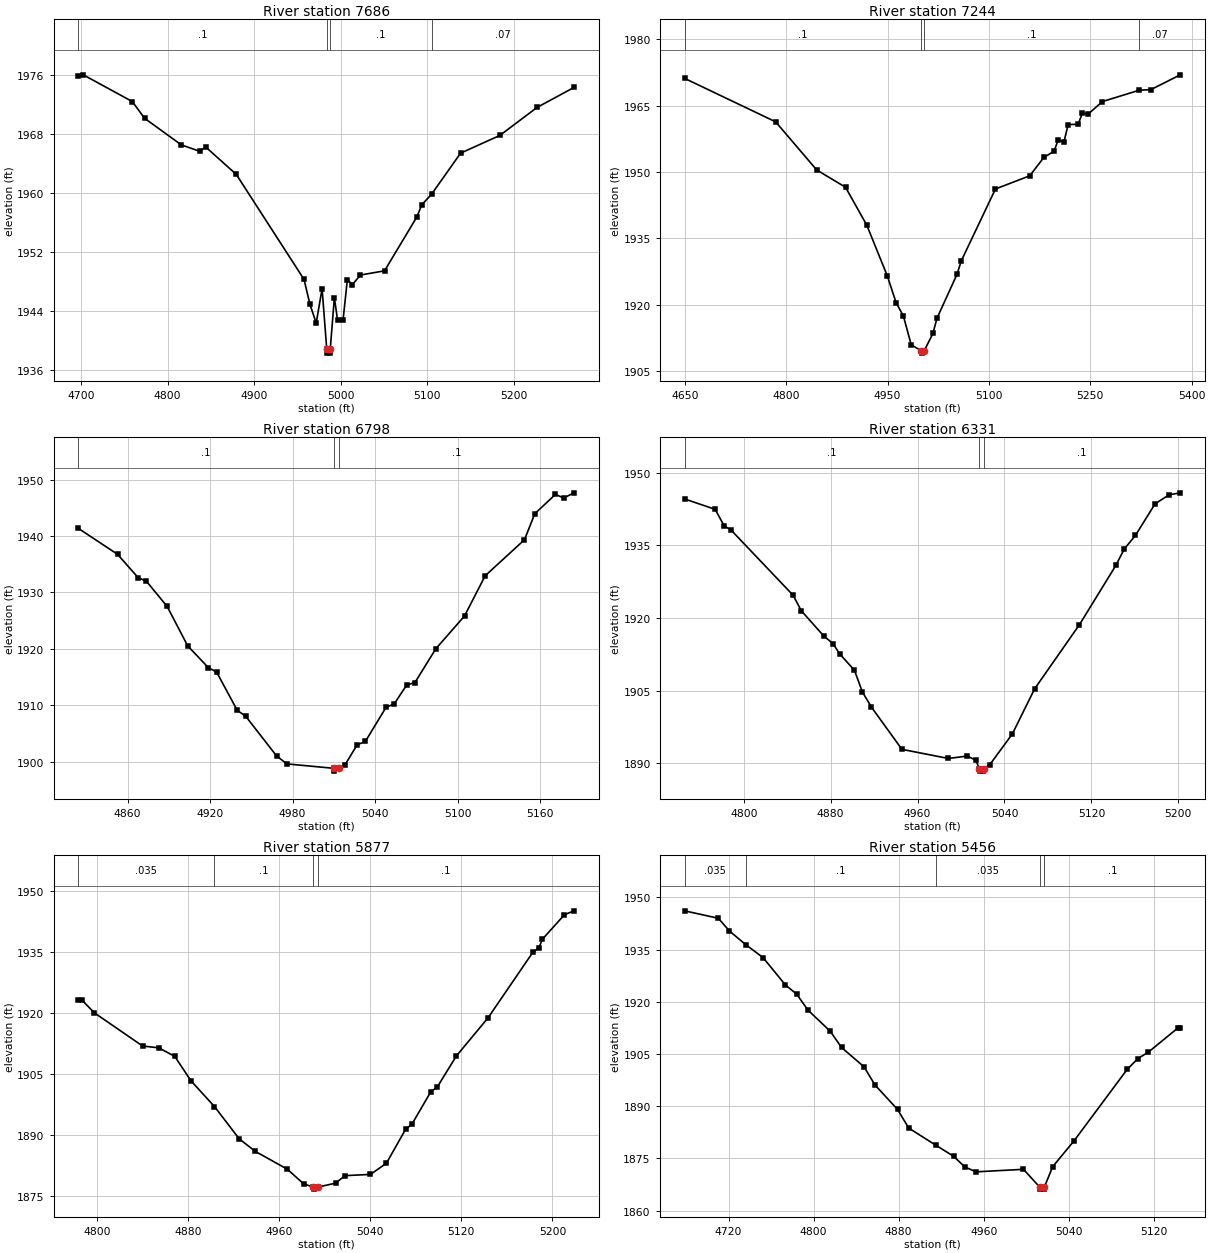
Type RM Length L Ch R = 1,7686,442,442,442
BEGIN DESCRIPTION:
Stream0482 17.0
END DESCRIPTION:
XS GIS Cut Line= 3
      1900569.04     13917402.62      1900775.00     13917625.00
      1901008.40     13917760.54
#Sta/Elev= 30
  4696.9 1975.87  4702.6 1976.00  4759.3 1972.38  4773.5 1970.11  4816.0 1966.51
  4837.0 1965.65  4844.4 1966.20  4879.5 1962.51  4957.8 1948.29  4964.6 1944.93
  4971.9 1942.37  4978.7 1947.03  4984.1 1938.80  4984.3 1938.30  4987.8 1938.30
  4988.1 1938.80  4992.9 1945.83  4996.6 1942.74  5002.9 1942.74  5007.9 1948.26
  5013.7 1947.59  5023.1 1948.88  5050.9 1949.45  5088.2 1956.74  5094.0 1958.40
  5105.3 1959.83  5138.8 1965.39  5184.2 1967.79  5227.3 1971.59  5269.9 1974.29
#Mann=4,-1,0
  4696.9     0.1       0  4984.1    0.05       0  4988.1     0.1       0
  5105.3    0.07       0
Bank Sta=4984.1,4988.1
Exp/Cntr=0.3,0.1

Type RM Length L Ch R = 1,7244,446,446,446
BEGIN DESCRIPTION:
Stream0482 16.0
END DESCRIPTION:
XS GIS Cut Line= 3
      1900303.00     13917552.13      1900425.00     13917875.00
      1900745.06     13918095.30
#Sta/Elev= 30
  4649.5 1971.13  4784.3 1961.31  4845.0 1950.45  4887.7 1946.54  4919.2 1937.96
  4949.4 1926.58  4962.6 1920.46  4973.3 1917.48  4984.9 1910.97  5000.1 1909.58
  5000.3 1909.08  5004.1 1909.58  5017.0 1913.52  5023.1 1916.97  5052.8 1926.90
  5058.9 1929.88  5109.6 1946.15  5160.4 1949.13  5181.3 1953.28  5196.2 1954.66
  5202.3 1957.14  5211.1 1956.85  5217.2 1960.69  5232.1 1960.77  5238.1 1963.25
  5247.0 1963.08  5267.9 1965.89  5322.8 1968.47  5339.6 1968.58  5383.2 1971.93
#Mann=4,-1,0
  4649.5     0.1       0  5000.1    0.05       0  5004.1     0.1       0
  5322.8    0.07       0
Bank Sta=5000.1,5004.1
Exp/Cntr=0.3,0.1

Type RM Length L Ch R = 1,6798,467,467,467
BEGIN DESCRIPTION:
Stream0482 15.0
END DESCRIPTION:
XS GIS Cut Line= 3
      1900025.04     13918125.03      1900175.00     13918225.00
      1900324.99     13918324.99
#Sta/Elev= 30
  4824.2 1941.36  4852.7 1936.77  4867.7 1932.63  4873.7 1932.00  4888.8 1927.52
  4903.8 1920.52  4918.8 1916.67  4924.8 1915.89  4939.8 1909.10  4945.8 1908.11
  4968.4 1901.03  4975.9 1899.62  5009.9 1898.84  5010.2 1898.34  5013.9 1898.84
  5018.0 1899.39  5027.0 1903.00  5033.0 1903.61  5048.0 1909.65  5054.0 1910.26
  5063.0 1913.60  5069.0 1914.03  5084.1 1919.99  5105.1 1925.84  5120.1 1932.96
  5148.7 1939.35  5156.2 1943.96  5171.2 1947.38  5177.2 1946.74  5184.7 1947.66
#Mann=3,-1,0
  4824.2     0.1       0  5009.9    0.05       0  5013.9     0.1       0
Bank Sta=5009.9,5013.9
Exp/Cntr=0.3,0.1

Type RM Length L Ch R = 1,6331,454,454,454
BEGIN DESCRIPTION:
Stream0482 14.0
END DESCRIPTION:
XS GIS Cut Line= 3
      1899724.99     13918374.99      1899875.00     13918575.00
      1900075.03     13918625.01
#Sta/Elev= 30
  4745.6 1944.59  4773.7 1942.45  4782.1 1939.00  4788.3 1938.18  4845.6 1924.66
  4852.9 1921.52  4873.7 1916.27  4882.1 1914.72  4888.3 1912.59  4901.9 1909.20
  4909.2 1904.73  4917.5 1901.60  4945.6 1892.86  4988.3 1890.98  5005.9 1891.47
  5013.7 1890.60  5016.8 1888.86  5017.1 1888.36  5020.6 1888.36  5020.8 1888.86
  5026.5 1889.70  5047.2 1896.03  5067.8 1905.38  5109.0 1918.62  5142.5 1930.86
  5150.2 1934.24  5160.5 1937.05  5178.6 1943.59  5191.5 1945.45  5201.8 1945.86
#Mann=3,-1,0
  4745.6     0.1       0  5016.8    0.05       0  5020.8     0.1       0
Bank Sta=5016.8,5020.8
Exp/Cntr=0.3,0.1

Type RM Length L Ch R = 1,5877,421,421,421
BEGIN DESCRIPTION:
Stream0482 13.0
END DESCRIPTION:
XS GIS Cut Line= 3
      1899575.02     13918825.02      1899725.00     13918975.00
      1899925.00     13919075.00
#Sta/Elev= 30
  4783.3 1923.04  4786.8 1923.04  4797.4 1920.01  4839.8 1911.87  4854.0 1911.43
  4868.1 1909.32  4882.3 1903.34  4903.0 1897.02  4924.7 1889.11  4938.8 1886.04
  4967.1 1881.64  4981.3 1878.07  4989.9 1877.27  4990.1 1876.77  4993.9 1877.27
  5009.4 1878.23  5017.8 1880.08  5040.1 1880.38  5054.1 1883.11  5070.9 1891.40
  5076.5 1892.68  5093.2 1900.67  5098.8 1901.80  5115.6 1909.42  5143.5 1918.80
  5182.7 1934.81  5188.3 1936.01  5191.1 1938.02  5210.6 1944.07  5219.0 1945.03
#Mann=4,-1,0
  4783.3   0.035       0  4903.0     0.1       0  4989.9    0.05       0
  4993.9     0.1       0
Bank Sta=4989.9,4993.9
Exp/Cntr=0.3,0.1

Type RM Length L Ch R = 1,5456,447,447,447
BEGIN DESCRIPTION:
Stream0482 12.0
END DESCRIPTION:
XS GIS Cut Line= 3
      1899224.97     13919224.99      1899525.00     13919325.00
      1899675.04     13919325.00
#Sta/Elev= 30
  4678.7 1946.13  4710.4 1943.99  4720.9 1940.33  4736.3 1936.39  4752.5 1932.69
  4773.6 1924.81  4784.1 1922.21  4794.7 1917.62  4815.8 1911.51  4826.3 1906.87
  4847.4 1901.35  4857.9 1896.06  4879.0 1889.08  4889.5 1883.73  4915.2 1878.76
  4931.7 1875.63  4942.3 1872.56  4952.8 1871.15  4997.5 1871.87  5013.0 1866.68
  5013.2 1866.18  5016.7 1866.18  5017.0 1866.68  5025.0 1872.64  5045.0 1880.03
  5095.0 1900.56  5105.0 1903.66  5115.0 1905.54  5142.5 1912.41  5145.0 1912.41
#Mann=5,-1,0
  4678.7   0.035       0  4736.3     0.1       0  4915.2   0.035       0
  5013.0   0.035       0  5017.0     0.1       0
Bank Sta=5013,5017
Exp/Cntr=0.3,0.1

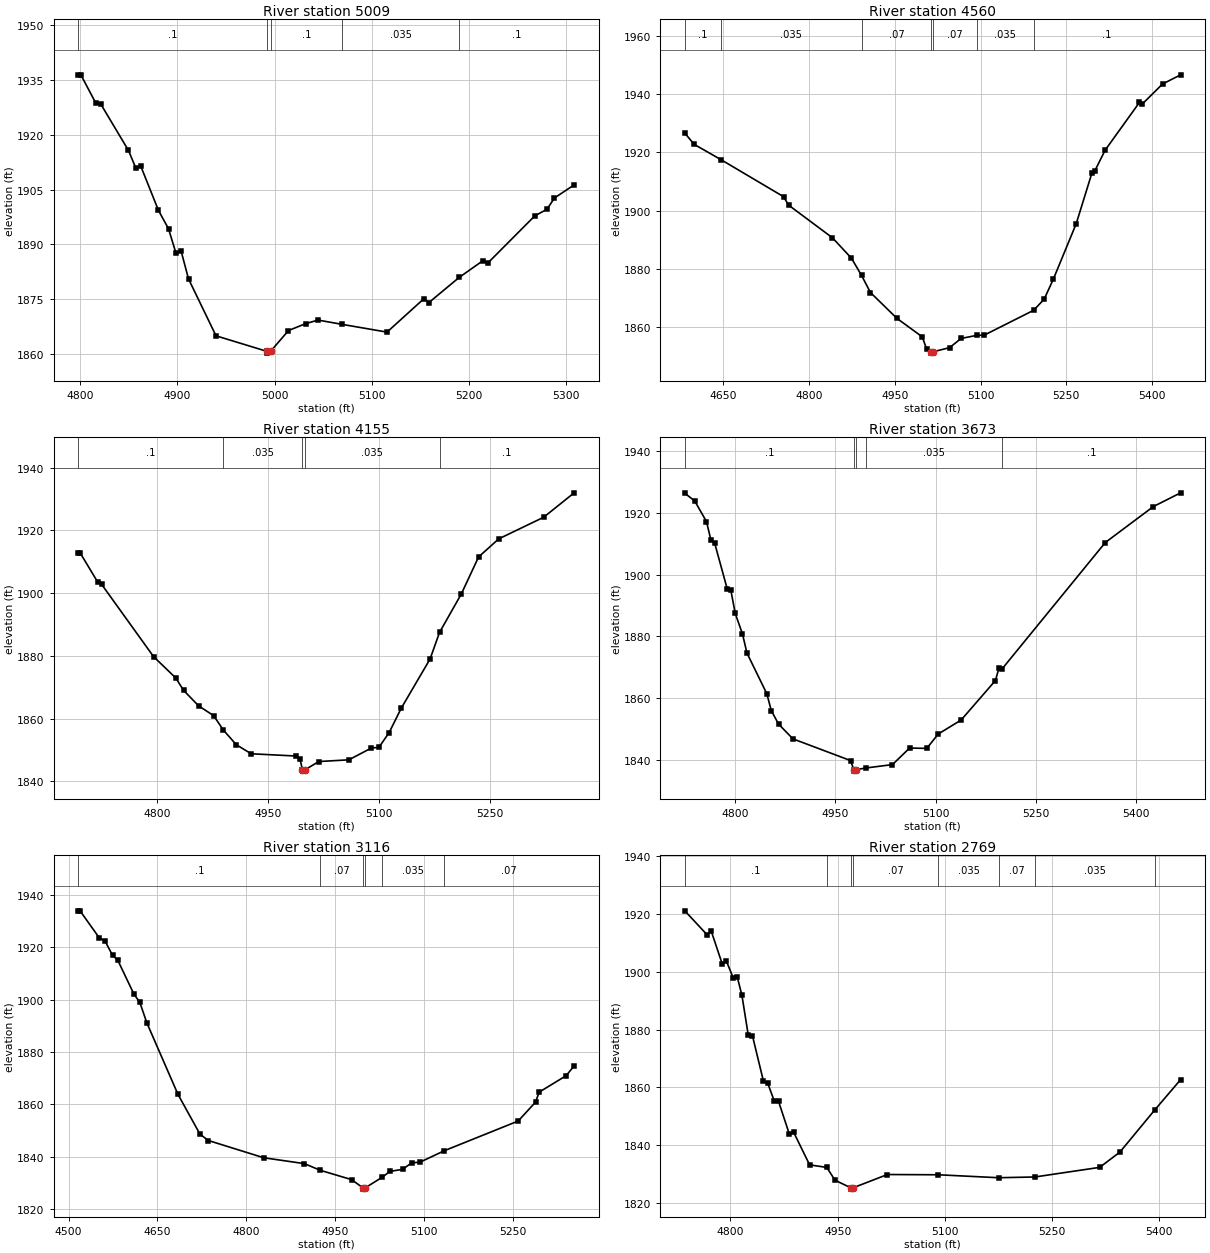
Type RM Length L Ch R = 1,5009,449,449,449
BEGIN DESCRIPTION:
Stream0482 11.0
END DESCRIPTION:
XS GIS Cut Line= 3
      1899174.99     13919675.00      1899375.00     13919725.00
      1899674.99     13919775.00
#Sta/Elev= 30
  4798.1 1936.35  4800.7 1936.35  4816.2 1928.55  4821.3 1928.31  4849.7 1915.69
  4857.4 1910.80  4862.5 1911.31  4880.6 1899.29  4890.9 1894.30  4898.6 1887.62
  4903.8 1888.29  4911.5 1880.60  4939.8 1865.05  4992.0 1860.82  4992.2 1860.32
  4996.0 1860.82  5014.4 1866.49  5032.1 1868.38  5044.8 1869.35  5069.8 1868.17
  5115.8 1866.06  5153.8 1875.20  5158.9 1874.13  5190.1 1881.01  5214.6 1885.59
  5219.7 1884.97  5267.9 1897.82  5280.5 1899.63  5288.1 1902.70  5308.4 1906.28
#Mann=5,-1,0
  4798.1     0.1       0  4992.0    0.05       0  4996.0     0.1       0
  5069.8   0.035       0  5190.1     0.1       0
Bank Sta=4992,4996
Exp/Cntr=0.3,0.1

Type RM Length L Ch R = 1,4560,405,405,405
BEGIN DESCRIPTION:
Stream0482 10.0
END DESCRIPTION:
XS GIS Cut Line= 3
      1899029.27     13920007.28      1899425.00     13920125.00
      1899876.35     13920072.16
#Sta/Elev= 30
  4582.7 1926.63  4599.1 1922.77  4646.5 1917.46  4755.6 1904.78  4764.2 1901.91
  4841.0 1890.68  4874.2 1883.67  4891.8 1877.79  4907.4 1871.89  4953.8 1863.00
  4998.1 1856.66  5005.6 1852.50  5013.7 1851.57  5014.0 1851.07  5017.7 1851.57
  5045.9 1852.95  5066.0 1856.11  5093.3 1857.17  5106.3 1857.23  5192.9 1865.78
  5211.3 1869.60  5227.1 1876.36  5267.4 1895.54  5294.6 1912.79  5299.6 1913.53
  5317.8 1920.73  5377.9 1937.15  5382.9 1936.62  5418.4 1943.50  5450.0 1946.65
#Mann=7,-1,0
  4582.7     0.1       0  4646.5   0.035       0  4891.8    0.07       0
  5013.7    0.05       0  5017.7    0.07       0  5093.3   0.035       0
  5192.9     0.1       0
Bank Sta=5013.7,5017.7
Exp/Cntr=0.3,0.1

Type RM Length L Ch R = 1,4155,482,482,482
BEGIN DESCRIPTION:
Stream0482 9.0
END DESCRIPTION:
XS GIS Cut Line= 3
      1899024.96     13920374.99      1899339.21     13920433.60
      1899685.71     13920491.68
#Sta/Elev= 30
  4693.3 1912.75  4695.9 1912.75  4719.7 1903.42  4724.8 1902.78  4795.1 1879.74
  4825.1 1872.95  4835.7 1869.00  4856.1 1864.04  4876.4 1860.93  4889.5 1856.35
  4907.0 1851.67  4927.3 1848.77  4988.3 1848.05  4993.4 1847.02  4996.5 1843.74
  4996.8 1843.24  5000.5 1843.74  5018.8 1846.30  5059.4 1846.84  5089.8 1850.60
  5100.0 1850.82  5113.7 1855.43  5130.4 1863.34  5169.3 1878.98  5182.1 1887.45
  5211.5 1899.67  5235.0 1911.52  5262.2 1917.27  5323.0 1924.16  5364.3 1931.95
#Mann=5,-1,0
  4693.3     0.1       0  4889.5   0.035       0  4996.5   0.035       0
  5000.5   0.035       0  5182.1     0.1       0
Bank Sta=4996.5,5000.5
Exp/Cntr=0.3,0.1

Type RM Length L Ch R = 1,3673,557,557,557
BEGIN DESCRIPTION:
Stream0482 8.0
END DESCRIPTION:
XS GIS Cut Line= 3
      1898924.95     13920724.98      1899175.00     13920825.00
      1899634.73     13920718.99
#Sta/Elev= 30
  4725.2 1926.44  4740.1 1923.91  4757.6 1917.24  4764.3 1911.22  4769.7 1910.37
  4788.5 1895.51  4793.9 1895.14  4800.6 1887.46  4811.4 1880.84  4818.1 1874.64
  4847.8 1861.44  4854.5 1855.96  4865.3 1851.62  4886.8 1846.82  4973.0 1839.78
  4977.7 1836.86  4977.9 1836.36  4981.7 1836.86  4996.6 1837.40  5035.6 1838.48
  5061.2 1843.84  5086.9 1843.73  5104.0 1848.39  5138.2 1852.92  5189.5 1865.73
  5194.7 1869.71  5199.3 1869.46  5353.7 1910.46  5425.5 1922.11  5466.3 1926.57
#Mann=5,-1,0
  4725.2     0.1       0  4977.7   0.035       0  4981.7     0.1       0
  4996.6   0.035       0  5199.3     0.1       0
Bank Sta=4977.7,4981.7
Exp/Cntr=0.3,0.1

Type RM Length L Ch R = 1,3116,347,347,347
BEGIN DESCRIPTION:
Stream0482 7.0
END DESCRIPTION:
XS GIS Cut Line= 3
      1898725.00     13920875.00      1898957.16     13921274.06
      1899274.99     13921475.00
#Sta/Elev= 30
  4516.3 1933.95  4519.2 1933.95  4551.5 1923.68  4561.4 1922.41  4574.1 1916.96
  4582.9 1915.09  4610.2 1902.14  4620.2 1898.97  4632.0 1891.17  4684.7 1863.78
  4721.9 1848.58  4736.1 1846.18  4829.5 1839.60  4898.1 1837.36  4925.1 1834.80
  4978.0 1831.24  4997.1 1828.11  4997.3 1827.61  5001.1 1828.11  5029.3 1832.10
  5042.9 1834.40  5064.1 1835.15  5079.3 1837.64  5093.7 1837.92  5134.4 1842.26
  5259.4 1853.63  5288.7 1860.84  5294.9 1864.68  5340.5 1870.96  5354.0 1874.73
#Mann=6,-1,0
  4516.3     0.1       0  4925.1    0.07       0  4997.1    0.05       0
  5001.1    0.07       0  5029.3   0.035       0  5134.4    0.07       0
Bank Sta=4997.1,5001.1
Exp/Cntr=0.3,0.1

Type RM Length L Ch R = 1,2769,616,616,616
BEGIN DESCRIPTION:
Stream0482 6.0
END DESCRIPTION:
XS GIS Cut Line= 3
      1898597.48     13921430.93      1898825.00     13921575.00
      1899125.02     13921875.02
#Sta/Elev= 30
  4736.1 1921.16  4767.3 1912.86  4773.2 1914.05  4788.4 1902.80  4794.4 1903.66
  4803.7 1898.01  4809.6 1898.12  4816.0 1891.91  4824.9 1878.03  4830.8 1877.83
  4846.1 1862.16  4852.0 1861.52  4861.3 1855.24  4867.2 1855.17  4882.5 1843.69
  4888.4 1844.44  4910.7 1833.16  4934.7 1832.27  4946.2 1827.85  4967.9 1825.25
  4968.1 1824.75  4971.9 1825.25  5019.5 1829.81  5090.8 1829.72  5175.0 1828.70
  5225.9 1828.96  5316.5 1832.29  5344.8 1837.59  5393.2 1852.09  5429.7 1862.69
#Mann=8,-1,0
  4736.1     0.1       0  4934.7    0.07       0  4967.9    0.05       0
  4971.9    0.07       0  5090.8   0.035       0  5175.0    0.07       0
  5225.9   0.035       0  5393.2     0.1       0
Bank Sta=4967.9,4971.9
Exp/Cntr=0.3,0.1

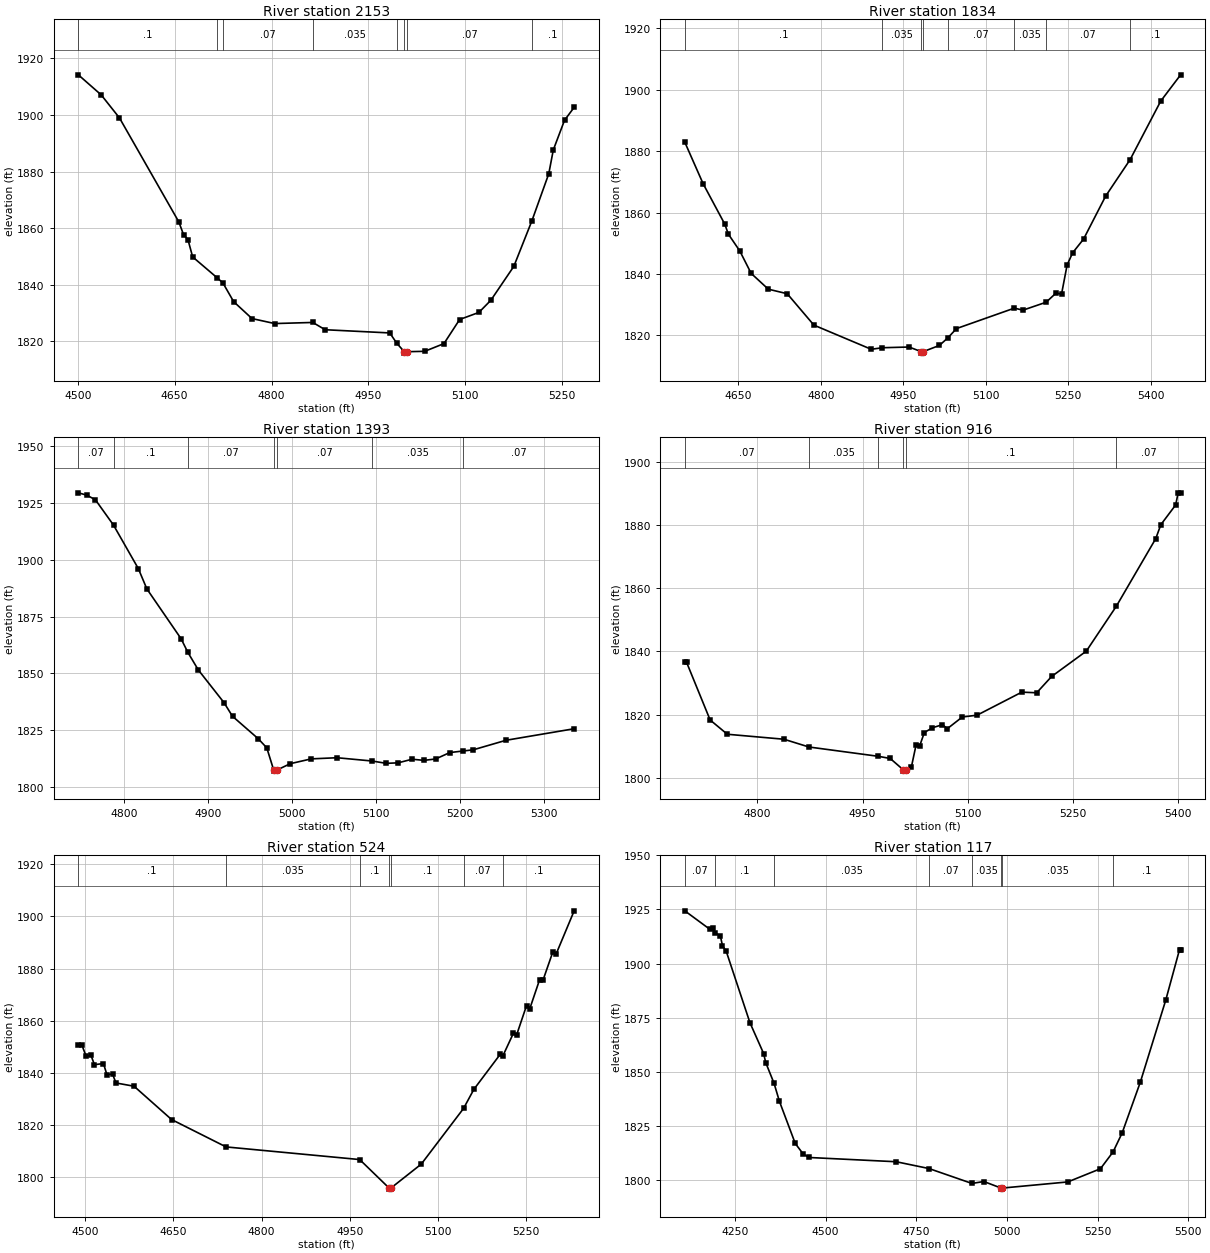
Type RM Length L Ch R = 1,2153,319,319,319
BEGIN DESCRIPTION:
Stream0482 5.0
END DESCRIPTION:
XS GIS Cut Line= 3
      1898524.99     13921724.99      1898843.99     13922064.14
      1899125.02     13922175.01
#Sta/Elev= 30
  4500.9 1914.14  4536.3 1907.06  4564.6 1898.92  4656.5 1862.21  4663.8 1857.71
  4670.6 1855.98  4677.9 1849.85  4715.4 1842.56  4724.7 1840.69  4741.4 1834.05
  4769.8 1828.08  4805.0 1826.32  4863.9 1826.71  4883.1 1824.14  4983.1 1823.01
  4993.9 1819.39  5005.5 1816.38  5005.7 1815.88  5009.5 1816.38  5037.2 1816.52
  5067.0 1819.24  5091.3 1827.75  5121.1 1830.25  5139.6 1834.54  5175.2 1846.52
  5203.2 1862.61  5229.3 1879.22  5236.3 1887.62  5253.7 1898.11  5268.6 1902.66
#Mann=8,-1,0
  4500.9     0.1       0  4715.4   0.035       0  4724.7    0.07       0
  4863.9   0.035       0  4993.9    0.07       0  5005.5    0.05       0
  5009.5    0.07       0  5203.2     0.1       0
Bank Sta=5005.5,5009.5
Exp/Cntr=0.3,0.1

Type RM Length L Ch R = 1,1834,441,441,441
BEGIN DESCRIPTION:
Stream0482 4.0
END DESCRIPTION:
XS GIS Cut Line= 3
      1898268.66     13922180.92      1898767.30     13922318.63
      1899151.14     13922294.62
#Sta/Elev= 30
  4552.4 1882.95  4585.7 1869.42  4625.2 1856.21  4631.6 1852.99  4652.4 1847.51
  4673.1 1840.19  4704.3 1835.04  4738.7 1833.56  4787.2 1823.33  4891.6 1815.45
  4911.7 1815.96  4960.3 1816.19  4982.3 1814.70  4982.6 1814.20  4986.3 1814.70
  5015.5 1816.71  5030.9 1819.18  5046.6 1822.20  5151.8 1828.86  5167.6 1828.21
  5209.7 1830.79  5227.7 1833.78  5237.7 1833.44  5247.8 1842.90  5257.8 1846.88
  5277.8 1851.38  5317.9 1865.37  5362.4 1877.26  5418.1 1896.34  5454.3 1904.90
#Mann=8,-1,0
  4552.4     0.1       0  4911.7   0.035       0  4982.3   0.035       0
  4986.3   0.035       0  5030.9    0.07       0  5151.8   0.035       0
  5209.7    0.07       0  5362.4     0.1       0
Bank Sta=4982.3,4986.3
Exp/Cntr=0.3,0.1

Type RM Length L Ch R = 1,1393,477,477,477
BEGIN DESCRIPTION:
Stream0482 3.0
END DESCRIPTION:
XS GIS Cut Line= 3
      1898124.96     13922474.99      1898375.00     13922525.00
      1898675.00     13922675.00
#Sta/Elev= 30
  4745.1 1929.44  4755.3 1928.41  4765.5 1926.35  4787.0 1915.24  4816.5 1896.14
  4826.7 1887.19  4867.5 1865.25  4875.4 1859.36  4887.9 1851.59  4918.5 1837.21
  4928.7 1831.17  4959.3 1821.31  4969.5 1817.30  4977.7 1807.56  4977.9 1807.06
  4981.7 1807.56  4997.5 1810.34  5022.5 1812.45  5053.2 1812.95  5094.8 1811.51
  5111.9 1810.48  5125.9 1810.71  5142.6 1812.30  5156.6 1811.79  5170.6 1812.41
  5187.4 1815.22  5203.2 1815.91  5215.3 1816.43  5254.4 1820.63  5335.5 1825.70
#Mann=7,-1,0
  4745.1    0.07       0  4787.0     0.1       0  4875.4    0.07       0
  4977.7    0.05       0  4981.7    0.07       0  5094.8   0.035       0
  5203.2    0.07       0
Bank Sta=4977.7,4981.7
Exp/Cntr=0.3,0.1

Type RM Length L Ch R = 1,916,392,392,392
BEGIN DESCRIPTION:
Stream0482 2.0
END DESCRIPTION:
XS GIS Cut Line= 3
      1898274.99     13922825.00      1898616.31     13922871.85
      1898875.02     13923125.02
#Sta/Elev= 30
  4696.7 1836.58  4699.2 1836.58  4732.8 1818.27  4757.3 1813.75  4838.0 1812.17
  4873.6 1809.71  4972.7 1806.75  4989.4 1806.07  5007.6 1802.56  5007.9 1802.06
  5011.6 1802.56  5019.7 1803.51  5026.2 1810.33  5031.2 1809.94  5038.0 1814.29
  5049.6 1815.81  5063.8 1816.79  5070.8 1815.52  5092.1 1819.22  5113.2 1819.80
  5176.9 1827.10  5198.1 1826.90  5219.4 1832.07  5268.8 1840.10  5311.6 1854.34
  5367.8 1875.79  5375.0 1880.19  5396.1 1886.44  5399.7 1890.29  5403.2 1890.29
#Mann=6,-1,0
  4696.7    0.07       0  4873.6   0.035       0  4972.7     0.1       0
  5007.6    0.05       0  5011.6     0.1       0  5311.6    0.07       0
Bank Sta=5007.6,5011.6
Exp/Cntr=0.3,0.1

Type RM Length L Ch R = 1,524,407,407,407
BEGIN DESCRIPTION:
Stream0482 1.0
END DESCRIPTION:
XS GIS Cut Line= 3
      1898043.74     13922957.45      1898475.00     13923225.00
      1898774.98     13923374.99
#Sta/Elev= 30
  4488.4 1850.87  4494.5 1850.66  4501.7 1846.37  4509.9 1846.75  4515.8 1843.17
  4531.1 1843.62  4537.0 1839.34  4546.5 1839.59  4552.4 1836.17  4583.1 1834.92
  4646.9 1822.16  4739.6 1811.66  4966.7 1806.82  5016.3 1795.99  5016.5 1795.49
  5020.3 1795.99  5071.4 1805.08  5143.3 1826.42  5160.8 1833.72  5205.5 1847.12
  5210.0 1846.50  5227.9 1855.17  5233.5 1854.58  5250.3 1865.80  5255.9 1864.65
  5272.6 1875.77  5278.2 1875.46  5295.0 1886.35  5300.6 1885.56  5331.3 1902.13
#Mann=7,-1,0
  4488.4     0.1       0  4739.6   0.035       0  4966.7     0.1       0
  5016.3    0.05       0  5020.3     0.1       0  5143.3    0.07       0
  5210.0     0.1       0
Bank Sta=5016.3,5020.3
Exp/Cntr=0.3,0.1

Type RM Length L Ch R = 1,117,0,0,0
BEGIN DESCRIPTION:
Stream0482 0.0
END DESCRIPTION:
XS GIS Cut Line= 4
      1897862.08     13922864.78      1898147.34     13923381.16
      1898454.43     13923689.59      1898796.00     13923699.96
#Sta/Elev= 30
  4111.9 1924.33  4180.7 1915.84  4188.4 1916.34  4196.3 1914.18  4210.1 1912.57
  4215.8 1908.22  4226.2 1905.61  4291.5 1872.68  4329.2 1858.47  4335.0 1854.27
  4358.0 1844.70  4372.8 1836.38  4416.4 1816.95  4438.1 1812.13  4454.2 1810.48
  4694.8 1808.51  4785.1 1805.37  4903.6 1798.49  4936.2 1799.39  4983.7 1796.37
  4984.0 1795.87  4987.7 1796.37  5167.7 1799.19  5257.7 1805.28  5292.6 1813.05
  5317.7 1821.85  5367.7 1845.25  5437.8 1883.12  5475.8 1906.46  5478.8 1906.46
#Mann=8,-1,0
  4111.9    0.07       0  4196.3     0.1       0  4358.0   0.035       0
  4785.1    0.07       0  4903.6   0.035       0  4983.7   0.035       0
  4987.7   0.035       0  5292.6     0.1       0
Bank Sta=4983.7,4987.7
Exp/Cntr=0.3,0.1

Chan Stop Cuts=-1