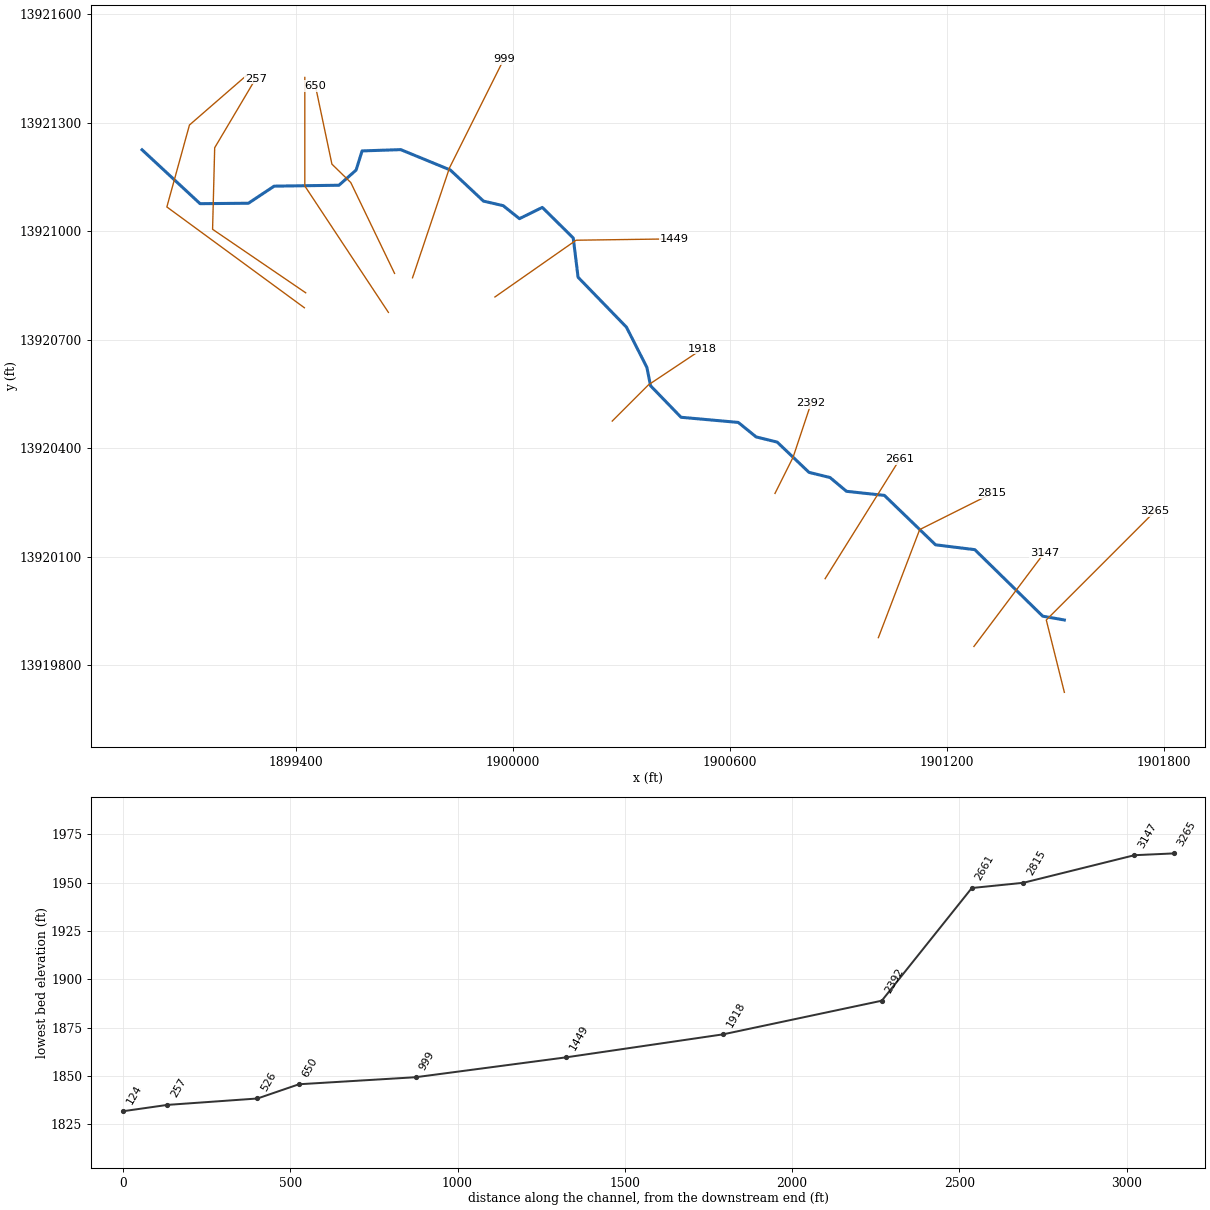
--- Stream0483.prj (project) ---

Proj Title=Stream0483 Base Level Engineering
Current Plan=p01
Default Exp/Contr=0.3,0.1
English Units
Geom File=g01
Flow File=f01
Plan File=p01
BEGIN DESCRIPTION:
Stream0483
END DESCRIPTION:

--- Stream0483.p01 (plan) ---

Plan Title=Multiple Run
Short Identifier=Multiple
Geom File=g01
Flow File=f01
Subcritical Flow
K Sum by GR= 0
Std Step Tol= 0.01
Critical Tol= 0.01
Num of Std Step Trials= 20
Max Error Tol= 0.3
Flow Tol Ratio= 0.001
Split Flow NTrial= 30
Split Flow Tol= 0.02
Split Flow Ratio= 0.02
Log Output Level= 0
Friction Slope Method= 1
Unsteady Friction Slope Method= 2
Unsteady Bridges Friction Slope Method= 1
Parabolic Critical Depth
Global Vel Dist=  1 , 1 , 1
Global Log Level= 0
CheckData=True
Encroach Param= -1, 0, 0, 0
BEGIN DESCRIPTION:
Multiple Run
END DESCRIPTION:

--- Stream0483.f01 (steady flow) ---

Flow Title=Multiple
Number of Profiles=7
Profile Names=10-year,25-year,50-year,1pct_min,100-year,1pct_plu,500-year
River Rch & RM= Stream0483,Reach-1,3265
     597     981    1335     882    1761    3513    3014
Boundary for River Rch & Prof#=Stream0483,Reach-1,1
Up Type=0
Dn Type=3
Dn Slope=0.005
Boundary for River Rch & Prof#=Stream0483,Reach-1,2
Up Type=0
Dn Type=3
Dn Slope=0.005
Boundary for River Rch & Prof#=Stream0483,Reach-1,3
Up Type=0
Dn Type=3
Dn Slope=0.005
Boundary for River Rch & Prof#=Stream0483,Reach-1,4
Up Type=0
Dn Type=3
Dn Slope=0.005
Boundary for River Rch & Prof#=Stream0483,Reach-1,5
Up Type=0
Dn Type=3
Dn Slope=0.005
Boundary for River Rch & Prof#=Stream0483,Reach-1,6
Up Type=0
Dn Type=3
Dn Slope=0.005
Boundary for River Rch & Prof#=Stream0483,Reach-1,7
Up Type=0
Dn Type=3
Dn Slope=0.005

--- Stream0483.g01 (geometry) ---

Geom Title=Existing Conditions

River Reach=Stream0483,Reach-1
Reach XY= 30
      1901525.00     13919925.00      1901465.21     13919935.52
      1901277.43     13920119.48      1901168.83     13920132.86
      1901027.43     13920269.48      1900922.68     13920280.77
      1900877.17     13920318.86      1900818.95     13920333.16
      1900731.05     13920416.84      1900672.83     13920431.14
      1900623.44     13920471.24      1900465.18     13920485.47
      1900380.83     13920572.69      1900370.81     13920623.26
      1900314.23     13920734.68      1900180.52     13920872.57
      1900167.14     13920981.21      1900081.69     13921065.71
      1900018.45     13921034.59      1899973.35     13921070.56
      1899918.96     13921083.14      1899827.29     13921169.16
      1899690.13     13921225.49      1899583.32     13921221.91
      1899566.83     13921168.97      1899519.32     13921127.01
      1899340.22     13921124.48      1899269.06     13921077.25
      1899135.44     13921076.03      1898975.00     13921225.00

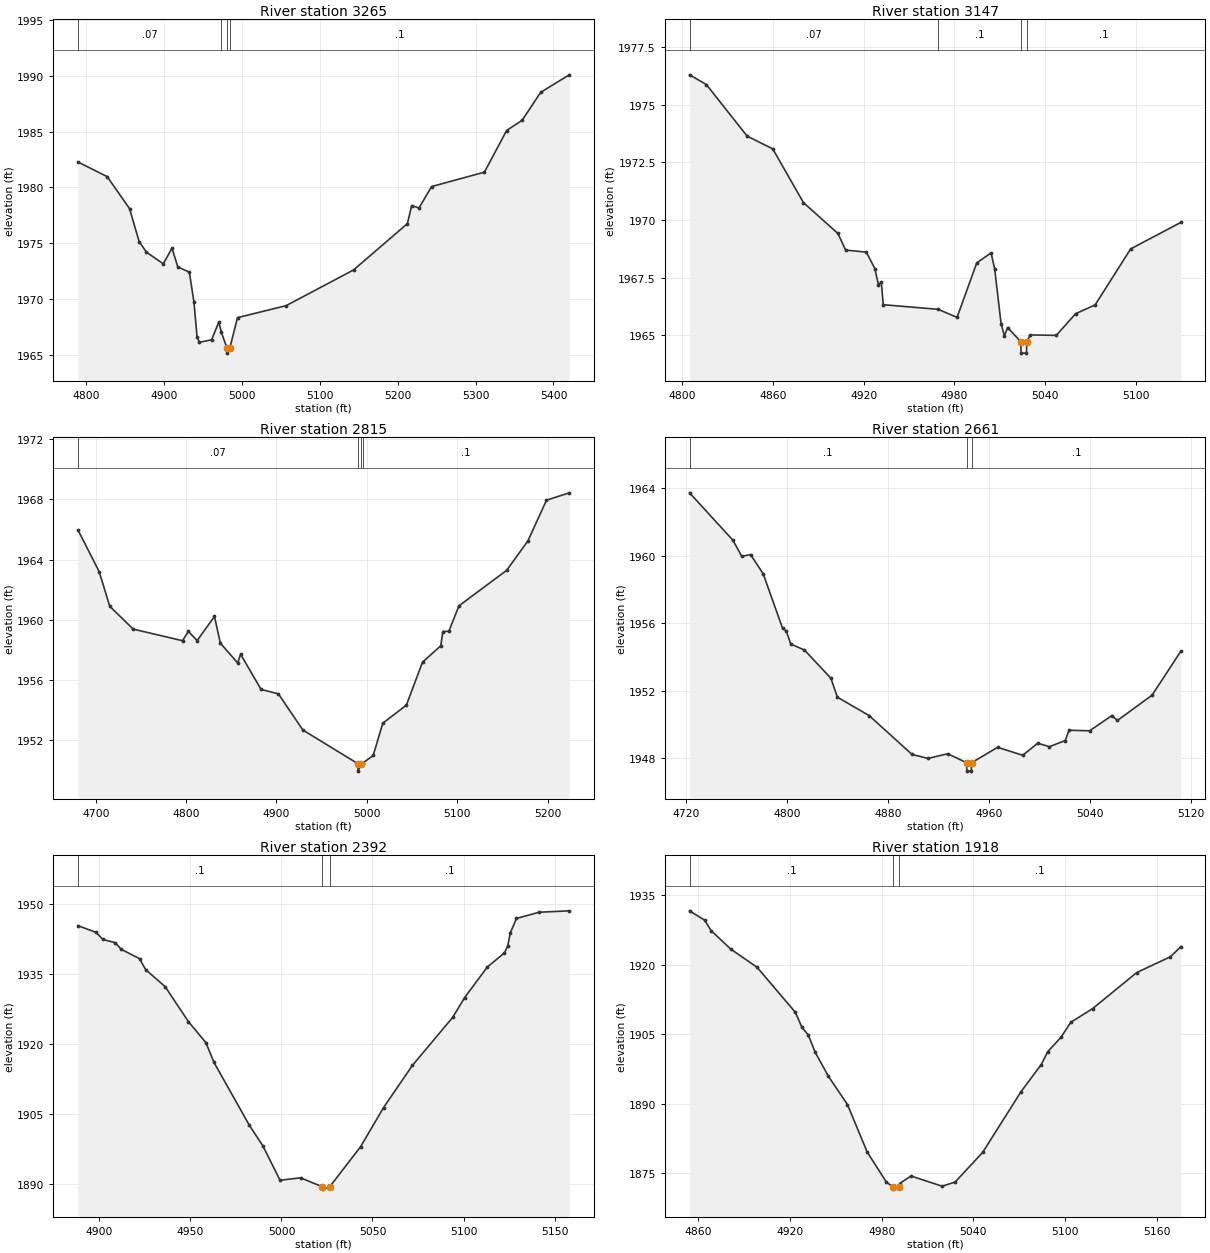
Type RM Length L Ch R = 1,3265,118,118,118
BEGIN DESCRIPTION:
Stream0483 7.0
END DESCRIPTION:
XS GIS Cut Line= 3
      1901525.00     13919725.01      1901475.00     13919925.00
      1901774.99     13920224.99
#Sta/Elev= 30
  4789.9 1982.27  4827.4 1980.96  4856.1 1978.09  4868.4 1975.14  4877.8 1974.19
  4899.4 1973.15  4910.5 1974.55  4918.0 1972.87  4932.8 1972.41  4938.7 1969.73
  4942.7 1966.61  4945.8 1966.12  4961.3 1966.34  4970.6 1967.93  4973.9 1967.01
  4980.9 1965.65  4981.2 1965.15  4984.9 1965.65  4994.6 1968.33  5056.9 1969.40
  5143.5 1972.60  5212.6 1976.75  5218.1 1978.37  5227.5 1978.15  5243.6 1980.07
  5311.4 1981.36  5339.9 1985.09  5359.9 1986.01  5383.6 1988.51  5420.3 1990.08
#Mann=4,-1,0
  4789.9    0.07       0  4973.9     0.1       0  4980.9    0.05       0
  4984.9     0.1       0
Bank Sta=4980.9,4984.9
Exp/Cntr=0.3,0.1

Type RM Length L Ch R = 1,3147,332,332,332
BEGIN DESCRIPTION:
Stream0483 6.1
END DESCRIPTION:
XS GIS Cut Line= 2
      1901274.99     13919851.80      1901470.10     13920111.60
#Sta/Elev= 30
  4804.9 1976.29  4816.0 1975.87  4843.0 1973.63  4859.9 1973.08  4880.2 1970.75
  4903.0 1969.41  4908.1 1968.69  4921.8 1968.60  4927.4 1967.89  4929.8 1967.19
  4931.7 1967.30  4933.0 1966.32  4969.3 1966.12  4981.8 1965.77  4994.8 1968.13
  5004.3 1968.57  5006.7 1967.86  5010.9 1965.50  5013.1 1964.96  5015.2 1965.33
  5023.9 1964.72  5024.2 1964.22  5027.7 1964.22  5027.9 1964.72  5030.2 1965.01
  5047.4 1964.99  5060.2 1965.93  5073.1 1966.31  5096.6 1968.74  5129.8 1969.89
#Mann=4,-1,0
  4804.9    0.07       0  4969.3     0.1       0  5023.9    0.05       0
  5027.9     0.1       0
Bank Sta=5023.9,5027.9
Exp/Cntr=0.3,0.1

Type RM Length L Ch R = 1,2815,154,154,154
BEGIN DESCRIPTION:
Stream0483 6.0
END DESCRIPTION:
XS GIS Cut Line= 3
      1901010.80     13919876.19      1901125.00     13920175.00
      1901325.01     13920275.00
#Sta/Elev= 30
  4680.4 1965.96  4703.9 1963.19  4715.5 1960.90  4741.5 1959.38  4796.1 1958.61
  4802.5 1959.23  4812.2 1958.62  4831.4 1960.22  4837.9 1958.45  4857.1 1957.13
  4860.3 1957.71  4882.9 1955.38  4902.1 1955.08  4929.2 1952.68  4989.9 1950.45
  4990.2 1949.95  4993.9 1950.45  4995.3 1950.48  5007.0 1950.99  5017.6 1953.13
  5043.7 1954.33  5061.6 1957.19  5081.7 1958.27  5084.1 1959.22  5090.7 1959.24
  5101.9 1960.93  5154.6 1963.28  5178.1 1965.23  5198.7 1967.94  5223.9 1968.43
#Mann=4,-1,0
  4680.4    0.07       0  4989.9    0.05       0  4993.9    0.07       0
  4995.3     0.1       0
Bank Sta=4989.9,4993.9
Exp/Cntr=0.3,0.1

Type RM Length L Ch R = 1,2661,269,269,269
BEGIN DESCRIPTION:
Mapping XS 02841323
END DESCRIPTION:
XS GIS Cut Line= 2
      1900863.58     13920039.20      1901069.98     13920369.63
#Sta/Elev= 30
  4722.7 1963.73  4757.0 1960.93  4764.1 1959.97  4771.1 1960.07  4781.1 1958.93
  4796.4 1955.72  4799.4 1955.55  4802.9 1954.78  4813.8 1954.42  4834.8 1952.75
  4839.9 1951.63  4865.1 1950.54  4899.1 1948.24  4911.8 1948.00  4927.4 1948.28
  4942.4 1947.75  4942.6 1947.25  4946.1 1947.25  4946.4 1947.75  4967.0 1948.66
  4986.9 1948.19  4998.8 1948.90  5008.1 1948.70  5020.6 1949.06  5023.6 1949.67
  5040.0 1949.64  5057.6 1950.54  5062.0 1950.25  5089.5 1951.75  5112.3 1954.35
#Mann=3,-1,0
  4722.7     0.1       0  4942.4    0.05       0  4946.4     0.1       0
Bank Sta=4942.4,4946.4
Exp/Cntr=0.3,0.1

Type RM Length L Ch R = 1,2392,474,474,474
BEGIN DESCRIPTION:
Stream0483 5.0
END DESCRIPTION:
XS GIS Cut Line= 3
      1900725.01     13920275.02      1900775.00     13920375.00
      1900825.00     13920525.00
#Sta/Elev= 30
  4888.2 1945.37  4898.1 1943.96  4901.9 1942.42  4908.6 1941.75  4912.0 1940.31
  4922.0 1938.32  4925.4 1935.96  4936.1 1932.32  4948.9 1924.82  4958.5 1920.32
  4962.9 1916.11  4982.4 1902.60  4989.8 1898.21  4999.2 1890.86  5010.5 1891.38
  5022.5 1889.46  5022.8 1888.96  5026.5 1889.46  5043.5 1898.07  5056.1 1906.44
  5071.9 1915.44  5094.1 1925.76  5100.6 1929.98  5113.1 1936.53  5122.5 1939.56
  5124.3 1941.04  5125.7 1943.82  5129.1 1946.92  5141.5 1948.26  5158.1 1948.56
#Mann=3,-1,0
  4888.2     0.1       0  5022.5    0.05       0  5026.5     0.1       0
Bank Sta=5022.5,5026.5
Exp/Cntr=0.3,0.1

Type RM Length L Ch R = 1,1918,469,469,469
BEGIN DESCRIPTION:
Stream0483 4.0
END DESCRIPTION:
XS GIS Cut Line= 3
      1900275.02     13920475.02      1900375.00     13920575.00
      1900525.03     13920675.02
#Sta/Elev= 30
  4854.2 1931.62  4864.1 1929.60  4868.3 1927.35  4881.2 1923.35  4898.4 1919.44
  4923.5 1909.71  4927.7 1906.53  4932.0 1904.79  4936.4 1901.14  4945.1 1895.93
  4957.6 1889.81  4970.5 1879.58  4983.1 1873.07  4987.4 1872.07  4987.7 1871.57
  4991.4 1872.07  4991.7 1872.76  4999.2 1874.40  5019.6 1872.20  5028.1 1873.10
  5046.1 1879.49  5071.3 1892.63  5084.5 1898.45  5088.8 1901.25  5097.5 1904.37
  5103.8 1907.56  5118.2 1910.54  5147.0 1918.30  5169.1 1921.71  5175.9 1923.90
#Mann=3,-1,0
  4854.2     0.1       0  4987.4    0.05       0  4991.4     0.1       0
Bank Sta=4987.4,4991.4
Exp/Cntr=0.3,0.1

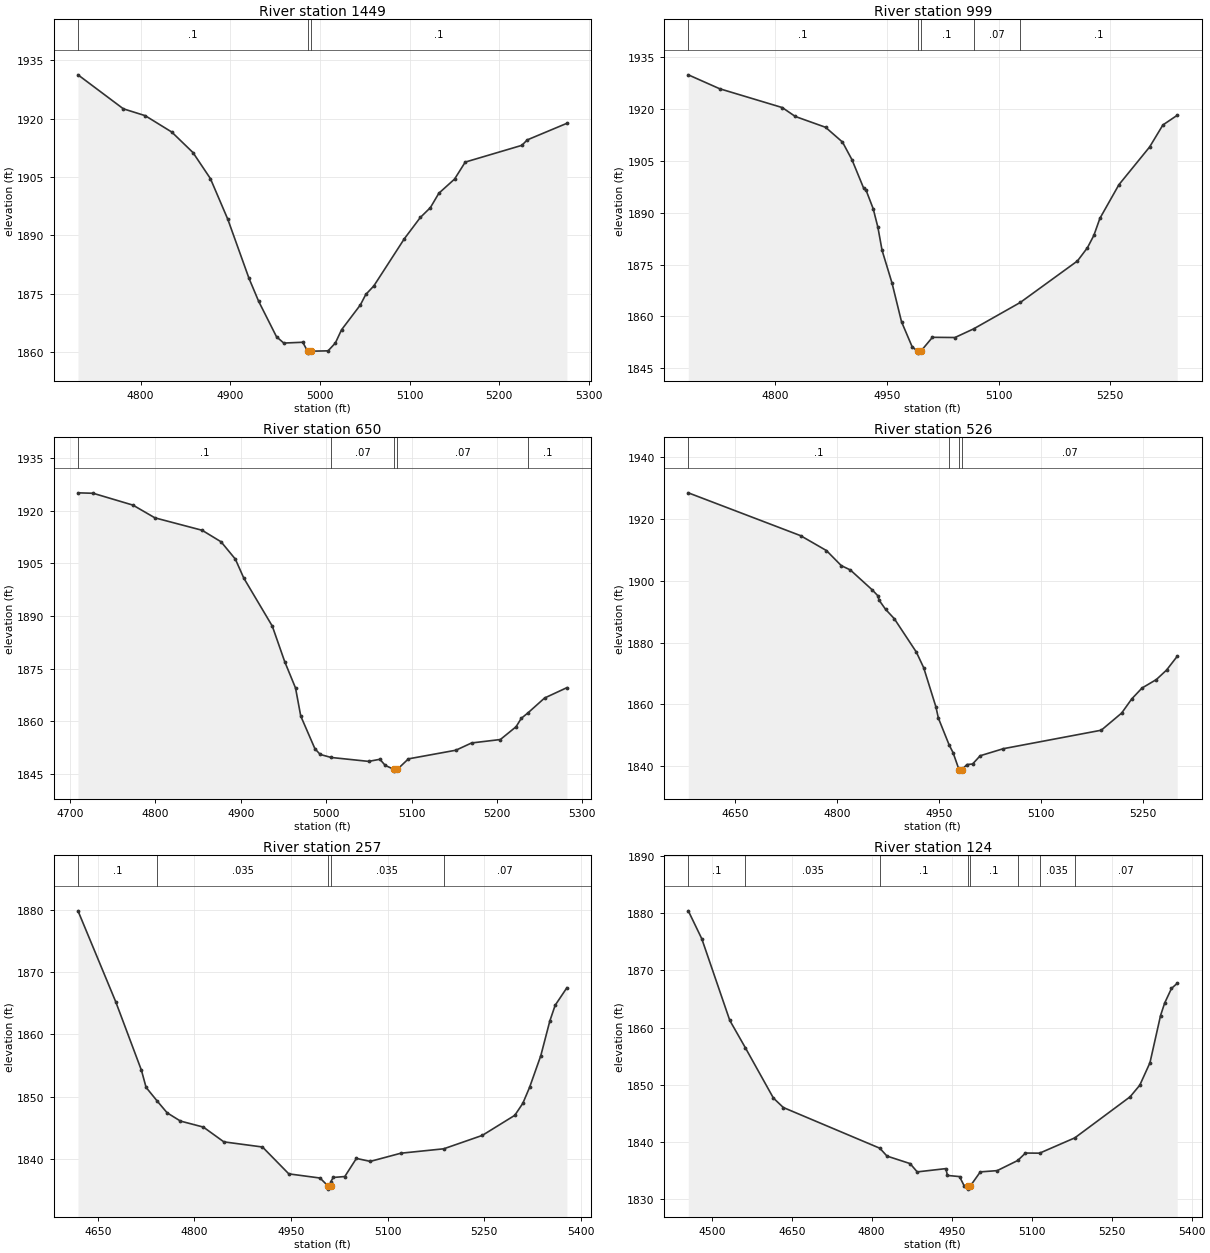
Type RM Length L Ch R = 1,1449,450,450,450
BEGIN DESCRIPTION:
Stream0483 3.0
END DESCRIPTION:
XS GIS Cut Line= 3
      1899950.66     13920818.10      1900175.00     13920975.00
      1900446.21     13920978.77
#Sta/Elev= 30
  4730.3 1931.31  4780.9 1922.56  4805.2 1920.80  4834.8 1916.59  4858.5 1911.30
  4877.9 1904.61  4897.3 1894.14  4921.0 1878.89  4931.7 1873.02  4951.6 1863.90
  4959.7 1862.27  4980.9 1862.48  4986.2 1860.18  4986.5 1859.68  4990.2 1860.18
  5009.1 1860.27  5017.2 1862.28  5024.1 1865.69  5045.1 1872.09  5051.1 1874.77
  5060.1 1876.98  5094.1 1889.12  5111.9 1894.59  5123.1 1897.12  5132.6 1900.84
  5150.1 1904.48  5162.0 1908.85  5225.1 1913.16  5231.1 1914.56  5275.3 1918.83
#Mann=3,-1,0
  4730.3     0.1       0  4986.2    0.05       0  4990.2     0.1       0
Bank Sta=4986.2,4990.2
Exp/Cntr=0.3,0.1

Type RM Length L Ch R = 1,999,349,349,349
BEGIN DESCRIPTION:
Stream0483 2.0
END DESCRIPTION:
XS GIS Cut Line= 3
      1899722.81     13920871.12      1899825.00     13921175.00
      1899974.99     13921474.98
#Sta/Elev= 30
  4683.7 1929.97  4725.8 1925.94  4809.8 1920.49  4827.3 1917.91  4867.9 1914.78
  4890.6 1910.50  4903.3 1905.40  4919.1 1897.10  4922.3 1896.52  4931.8 1891.20
  4938.1 1885.83  4943.7 1879.16  4957.1 1869.65  4969.8 1858.48  4984.0 1851.26
  4991.5 1849.89  4991.7 1849.39  4995.5 1849.89  5011.3 1853.97  5041.5 1853.91
  5066.5 1856.41  5129.1 1864.05  5205.9 1876.08  5219.3 1879.92  5227.9 1883.48
  5236.0 1888.42  5261.5 1898.16  5302.7 1909.08  5320.5 1915.45  5339.7 1918.25
#Mann=5,-1,0
  4683.7     0.1       0  4991.5    0.05       0  4995.5     0.1       0
  5066.5    0.07       0  5129.1     0.1       0
Bank Sta=4991.5,4995.5
Exp/Cntr=0.3,0.1

Type RM Length L Ch R = 1,650,124,124,124
BEGIN DESCRIPTION:
Stream0483 1.1
END DESCRIPTION:
XS GIS Cut Line= 4
      1899673.12     13920883.28      1899552.03     13921134.55
      1899499.95     13921185.33      1899454.37     13921401.51
#Sta/Elev= 30
  4709.3 1925.17  4727.1 1925.04  4773.7 1921.66  4799.4 1918.03  4854.7 1914.48
  4876.9 1911.19  4893.6 1906.25  4903.5 1900.83  4936.9 1887.12  4951.4 1877.00
  4964.1 1869.46  4970.2 1861.46  4986.8 1852.13  4993.0 1850.50  5005.8 1849.64
  5049.7 1848.52  5062.9 1849.12  5069.1 1847.39  5079.3 1846.24  5079.6 1845.74
  5083.3 1846.24  5096.3 1849.24  5151.9 1851.71  5170.3 1853.78  5204.0 1854.76
  5222.4 1858.41  5228.5 1860.81  5236.3 1862.36  5255.8 1866.61  5281.9 1869.56
#Mann=5,-1,0
  4709.3     0.1       0  5005.8    0.07       0  5079.3    0.05       0
  5083.3    0.07       0  5236.3     0.1       0
Bank Sta=5079.3,5083.3
Exp/Cntr=0.3,0.1

Type RM Length L Ch R = 1,526,269,269,269
BEGIN DESCRIPTION:
Stream0483 1.0
END DESCRIPTION:
XS GIS Cut Line= 3
      1899656.08     13920775.48      1899425.00     13921125.00
      1899425.00     13921425.00
#Sta/Elev= 30
  4581.0 1928.45  4746.1 1914.59  4784.2 1909.76  4806.0 1904.89  4819.3 1903.49
  4851.7 1897.00  4859.5 1895.20  4861.6 1893.70  4871.2 1890.73  4884.0 1887.70
  4916.4 1876.90  4927.2 1871.84  4945.2 1859.15  4948.8 1855.53  4964.6 1846.87
  4970.4 1844.36  4979.1 1838.88  4979.4 1838.38  4983.1 1838.88  4990.9 1840.51
  4999.1 1840.69  5010.3 1843.36  5044.3 1845.64  5188.3 1851.62  5218.3 1857.17
  5233.3 1861.79  5248.3 1865.28  5269.3 1868.01  5284.3 1871.07  5300.0 1875.53
#Mann=4,-1,0
  4581.0     0.1       0  4964.6    0.07       0  4979.1    0.05       0
  4983.1    0.07       0
Bank Sta=4979.1,4983.1
Exp/Cntr=0.3,0.1

Type RM Length L Ch R = 1,257,133,133,133
BEGIN DESCRIPTION:
Stream0483 0.0
END DESCRIPTION:
XS GIS Cut Line= 4
      1899427.46     13920829.66      1899170.00     13921005.22
      1899175.82     13921230.65      1899289.28     13921421.90
#Sta/Elev= 30
  4619.1 1879.93  4677.7 1865.28  4717.7 1854.22  4724.9 1851.47  4742.3 1849.25
  4757.6 1847.37  4778.3 1846.04  4813.9 1845.07  4845.7 1842.69  4905.7 1841.86
  4946.6 1837.53  4995.1 1836.86  5007.6 1835.57  5007.9 1835.07  5011.6 1835.57
  5011.8 1836.25  5015.6 1836.95  5033.6 1837.10  5051.6 1840.02  5073.2 1839.54
  5120.7 1840.86  5187.3 1841.57  5247.2 1843.73  5297.7 1846.97  5310.2 1848.91
  5320.7 1851.49  5338.1 1856.59  5352.1 1862.17  5360.4 1864.71  5378.6 1867.53
#Mann=5,-1,0
  4619.1     0.1       0  4742.3   0.035       0  5007.6   0.035       0
  5011.6   0.035       0  5187.3    0.07       0
Bank Sta=5007.6,5011.6
Exp/Cntr=0.3,0.1

Type RM Length L Ch R = 1,124,0,0,0
BEGIN DESCRIPTION:
Stream0483 0.1
END DESCRIPTION:
XS GIS Cut Line= 4
      1899423.77     13920788.33      1899043.57     13921066.97
      1899106.07     13921293.54      1899264.89     13921431.53
#Sta/Elev= 30
  4456.1 1880.38  4481.4 1875.50  4533.9 1861.25  4563.0 1856.49  4615.7 1847.69
  4634.3 1846.04  4815.3 1838.93  4828.7 1837.56  4872.0 1836.25  4885.4 1834.80
  4939.0 1835.37  4942.1 1834.18  4964.7 1833.98  4973.2 1832.41  4980.6 1832.29
  4980.8 1831.79  4984.6 1832.29  5003.7 1834.80  5035.4 1835.02  5073.9 1836.79
  5088.4 1838.09  5114.9 1838.07  5180.9 1840.74  5284.6 1847.91  5302.7 1849.93
  5321.8 1853.85  5341.7 1862.10  5349.4 1864.28  5362.2 1866.83  5372.9 1867.72
#Mann=8,-1,0
  4456.1     0.1       0  4563.0   0.035       0  4815.3     0.1       0
  4980.6    0.05       0  4984.6     0.1       0  5073.9    0.07       0
  5114.9   0.035       0  5180.9    0.07       0
Bank Sta=4980.6,4984.6
Exp/Cntr=0.3,0.1

Chan Stop Cuts=-1