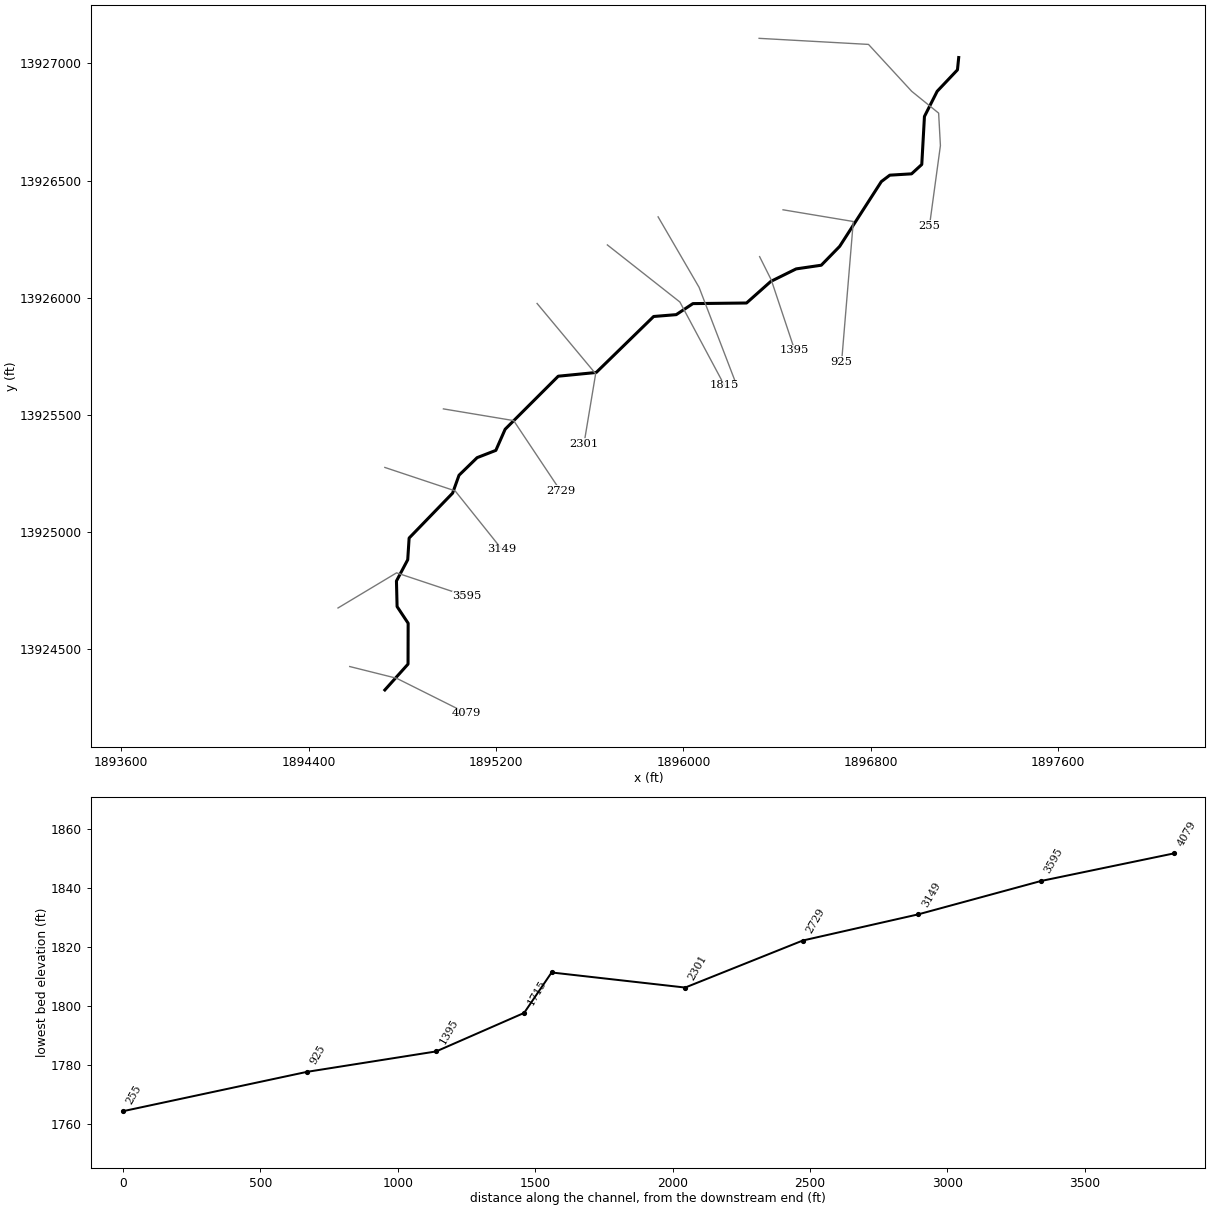
--- Stream0484.prj (project) ---

Proj Title=Stream0484 Base Level Engineering
Current Plan=p01
Default Exp/Contr=0.3,0.1
English Units
Geom File=g01
Flow File=f01
Plan File=p01
Y Axis Title=Elevation
X Axis Title(PF)=Main Channel Distance
X Axis Title(XS)=Station
BEGIN DESCRIPTION:
Stream0484
END DESCRIPTION:
DSS Export Rating Curves= 0
DSS Export Rating Curve Sorted= 0
DSS Export Volume Flow Curves= 0
DXF OffsetX= 0
DXF OffsetY= 0
DXF ScaleX= 1
DXF ScaleY= 10

--- Stream0484.p01 (plan) ---

Plan Title=Multiple Run
Short Identifier=Multiple
Geom File=g01
Flow File=f01
Subcritical Flow
K Sum by GR= 0
Std Step Tol= 0.01
Critical Tol= 0.01
Num of Std Step Trials= 20
Max Error Tol= 0.3
Flow Tol Ratio= 0.001
Split Flow NTrial= 30
Split Flow Tol= 0.02
Split Flow Ratio= 0.02
Log Output Level= 0
Friction Slope Method= 1
Unsteady Friction Slope Method= 2
Unsteady Bridges Friction Slope Method= 1
Parabolic Critical Depth
Global Vel Dist=  1 , 1 , 1
Global Log Level= 0
CheckData=True
Encroach Param= -1, 0, 0, 0
BEGIN DESCRIPTION:
Multiple Run
END DESCRIPTION:

--- Stream0484.f01 (steady flow) ---

Flow Title=Multiple
Program Version=4.10
Number of Profiles= 7
Profile Names=10-year,25-year,50-year,1pct_min,100-year,1pct_plu,500-year
River Rch & RM=Stream0484,Reach-1         ,4079
     803    1348    1862    1247    2489    4966    4380
Boundary for River Rch & Prof#=Stream0484,Reach-1         , 1
Up Type= 0
Dn Type= 3
Dn Slope=0.01
Boundary for River Rch & Prof#=Stream0484,Reach-1         , 2
Up Type= 0
Dn Type= 3
Dn Slope=0.01
Boundary for River Rch & Prof#=Stream0484,Reach-1         , 3
Up Type= 0
Dn Type= 3
Dn Slope=0.01
Boundary for River Rch & Prof#=Stream0484,Reach-1         , 4
Up Type= 0
Dn Type= 3
Dn Slope=0.01
Boundary for River Rch & Prof#=Stream0484,Reach-1         , 5
Up Type= 0
Dn Type= 3
Dn Slope=0.01
Boundary for River Rch & Prof#=Stream0484,Reach-1         , 6
Up Type= 0
Dn Type= 3
Dn Slope=0.01
Boundary for River Rch & Prof#=Stream0484,Reach-1         , 7
Up Type= 0
Dn Type= 3
Dn Slope=0.01
DSS Import GetInterval= 0
DSS Import GetPeak= 0
DSS Import FillOption= 0

--- Stream0484.g01 (geometry) ---

Geom Title=Existing Conditions
Program Version=4.10

River Reach=Stream0484      ,Reach-1
Reach XY= 30
        1894725.       13924325.      1894823.98     13924435.42
      1894824.48     13924609.78      1894777.25     13924680.94
      1894774.53     13924790.16      1894822.64     13924880.98
      1894828.61      13924973.5      1895014.22     13925165.32
      1895041.64     13925241.71      1895118.95     13925316.84
      1895198.84     13925347.86      1895238.64      13925438.2
       1895465.2     13925664.52      1895627.45     13925680.47
      1895872.57     13925919.48      1895969.02     13925927.36
      1896040.22     13925974.48      1896269.14     13925977.06
      1896372.71     13926069.15      1896480.97     13926122.67
      1896588.33     13926138.39      1896666.85     13926218.93
      1896844.73     13926495.51      1896880.89     13926522.85
      1896973.75     13926528.51      1897017.32     13926568.48
      1897028.75     13926773.45      1897083.14     13926881.06
      1897169.67     13926972.49        1897175.       13927025.

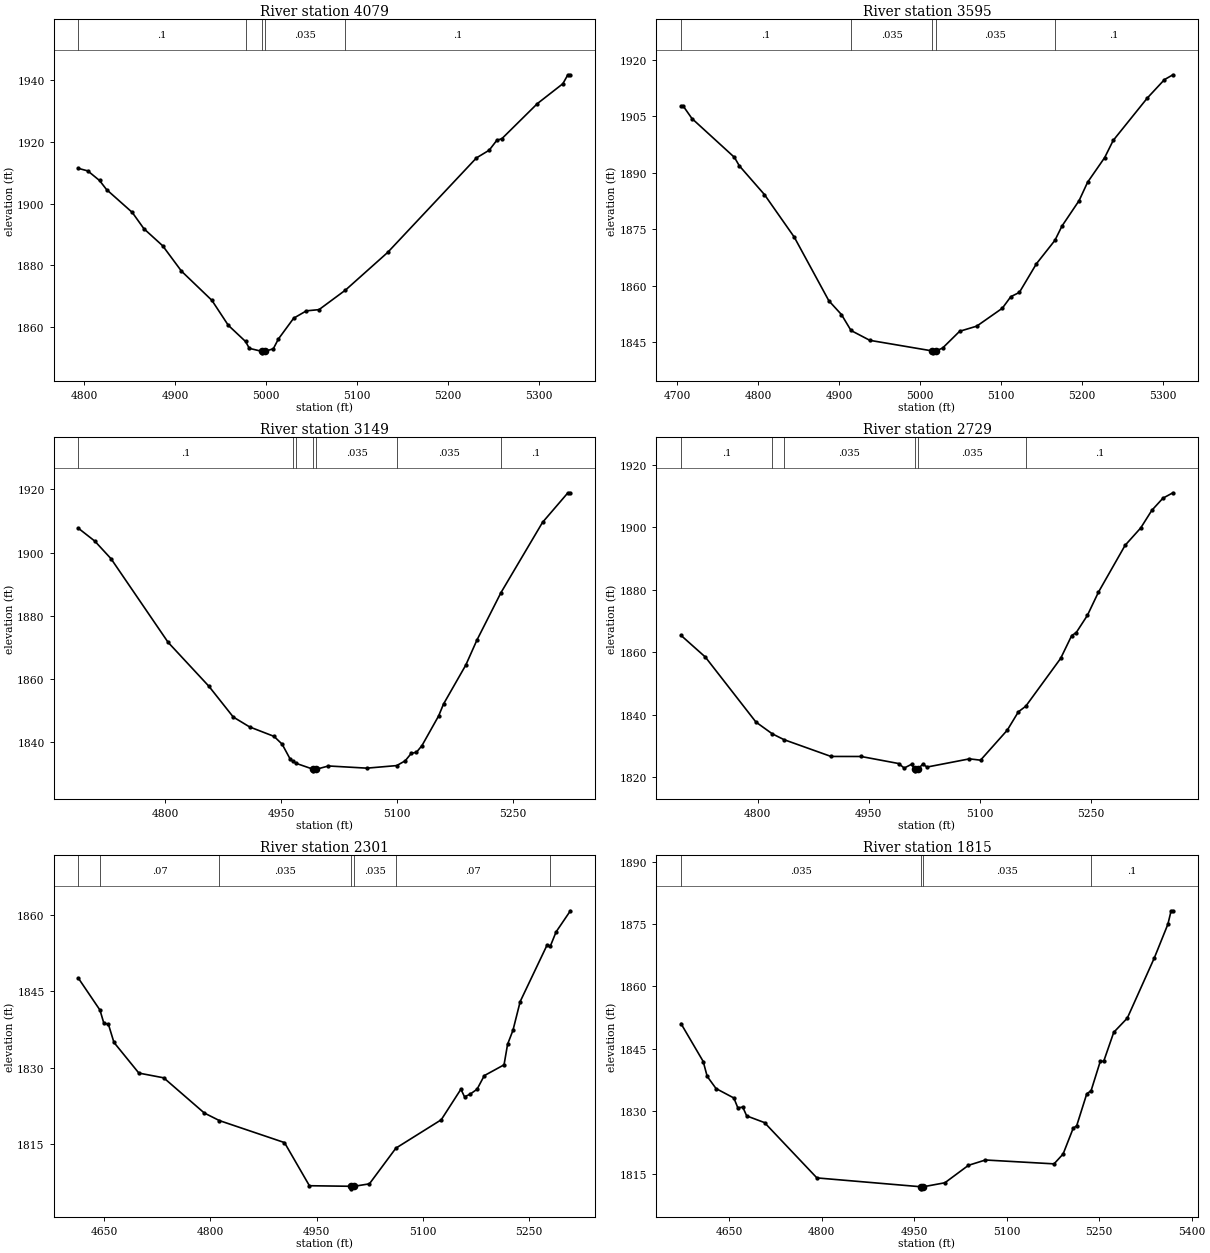
Type RM Length L Ch R = 1 ,4079    ,484,484,484
BEGIN DESCRIPTION:
Stream0484 8.0
END DESCRIPTION:
XS GIS Cut Line= 3
      1894575.02     13924424.99        1894775.       13924375.
      1895074.96     13924225.02
#Sta/Elev= 30
  4793.5 1911.44  4803.8 1910.62  4816.7 1907.51  4824.4 1904.58  4852.7 1897.16
  4865.6 1891.84  4886.2 1886.33  4906.9 1878.09  4940.4 1868.61  4958.4 1860.53
  4977.4 1855.27  4981.6 1853.04  4995.1 1852.08  4995.3 1851.58  4999.1 1852.08
    5008 1852.91  5013.6 1856.08  5030.4 1862.82  5044.4 1865.21  5058.3  1865.6
  5087.4 1871.94  5133.8 1884.15  5231.6 1914.85  5245.6 1917.34    5254 1920.55
  5259.6 1921.09  5298.7 1932.48  5326.7 1938.92  5332.2 1941.82    5335 1941.82
#Mann= 5 ,-1 , 0
  4793.5      .1       0  4977.4    .035       0  4995.1    .035       0
  4999.1    .035       0  5087.4      .1       0
Bank Sta=4995.1,4999.1
XS Rating Curve= 0 ,0
Exp/Cntr=0.3,0.1

Type RM Length L Ch R = 1 ,3595    ,446,446,446
BEGIN DESCRIPTION:
Stream0484 7.0
END DESCRIPTION:
XS GIS Cut Line= 3
      1894524.97     13924674.98        1894775.       13924825.
      1895074.99       13924725.
#Sta/Elev= 30
  4704.3 1907.66  4707.3 1907.66  4717.9 1904.41  4770.4 1894.11  4776.3  1891.9
  4807.4 1884.25  4844.3 1872.94    4887 1856.06  4902.6 1852.39  4914.4 1848.17
  4937.6 1845.56    5015 1842.74  5015.2 1842.24    5019 1842.74  5027.5  1843.5
  5048.6 1847.96  5069.7 1849.32  5101.3 1854.07  5111.8 1857.14  5122.4 1858.28
  5143.5 1865.89  5166.3 1872.09  5175.1 1875.91  5196.2 1882.64  5206.7 1887.52
  5227.8 1894.06  5238.3  1898.6  5280.5 1909.87  5301.6 1914.74  5312.1 1916.03
#Mann= 5 ,-1 , 0
  4704.3      .1       0  4914.4    .035       0    5015    .035       0
    5019    .035       0  5166.3      .1       0
Bank Sta=5015,5019
XS Rating Curve= 0 ,0
Exp/Cntr=0.3,0.1

Type RM Length L Ch R = 1 ,3149    ,420,420,420
BEGIN DESCRIPTION:
Stream0484 6.0
END DESCRIPTION:
XS GIS Cut Line= 3
        1894725.       13925275.        1895025.       13925175.
      1895225.01     13924924.99
#Sta/Elev= 30
  4688.1 1907.66  4709.2 1903.63  4730.3 1898.03  4804.1  1871.6  4856.8 1857.73
  4888.4 1847.98  4909.5 1844.86  4941.1 1841.87  4951.6  1839.4  4962.2 1834.59
    4966 1833.96  4969.9 1833.32  4991.8 1831.47    4992 1830.97  4995.8 1831.47
  5011.5 1832.51  5061.2 1831.82  5099.8 1832.63  5110.8 1834.14  5118.8 1836.54
  5125.2 1836.81  5132.4 1838.92    5154 1848.32  5160.4 1852.11  5189.2 1864.43
  5203.6 1872.33  5234.7 1887.33  5288.5 1909.56  5321.3  1918.9  5324.5  1918.9
#Mann= 7 ,-1 , 0
  4688.1      .1       0    4966     .07       0  4969.9    .035       0
  4991.8    .035       0  4995.8    .035       0  5099.8    .035       0
  5234.7      .1       0
Bank Sta=4991.8,4995.8
XS Rating Curve= 0 ,0
Exp/Cntr=0.3,0.1

Type RM Length L Ch R = 1 ,2729    ,428,428,428
BEGIN DESCRIPTION:
Stream0484 5.0
END DESCRIPTION:
XS GIS Cut Line= 3
      1894975.04     13925524.99        1895275.       13925475.
      1895474.97     13925175.04
#Sta/Elev= 30
  4696.2 1865.44  4729.1 1858.51  4797.5 1837.71  4819.6 1833.95  4835.5 1832.08
  4898.9 1826.72  4939.5 1826.71  4990.2 1824.46  4997.8 1823.01  5007.8 1824.23
  5011.8 1822.62  5012.1 1822.12  5015.8 1822.62  5022.8 1824.22  5028.8 1823.34
  5085.9 1825.95  5100.9 1825.53    5137 1835.12    5152 1840.98    5162 1842.78
  5209.1 1858.06  5224.1 1865.39  5230.1 1866.29  5245.2  1871.8  5260.2 1879.25
  5296.2 1894.22  5317.3 1899.78  5332.3 1905.41  5347.3 1909.29  5360.8 1911.02
#Mann= 6 ,-1 , 0
  4696.2      .1       0  4819.6     .07       0  4835.5    .035       0
  5011.8    .035       0  5015.8    .035       0    5162      .1       0
Bank Sta=5011.8,5015.8
XS Rating Curve= 0 ,0
Exp/Cntr=0.3,0.1

Type RM Length L Ch R = 1 ,2301    ,486,486,486
BEGIN DESCRIPTION:
Stream0484 4.0
END DESCRIPTION:
XS GIS Cut Line= 3
      1895375.01     13925974.99        1895625.       13925675.
      1895575.01     13925375.04
#Sta/Elev= 30
  4613.6  1847.5    4644 1841.26  4649.4 1838.71  4655.9 1838.48  4663.7 1834.93
  4698.9 1828.91    4734 1827.98  4791.3 1821.08  4812.7 1819.59  4904.5 1815.28
  4939.7 1806.82  4998.9 1806.71  4999.1 1806.21  5002.9 1806.71  5024.4 1807.19
  5061.8 1814.19  5125.8 1819.75  5153.6 1825.75  5158.7 1824.26  5166.3 1824.75
  5176.4 1825.74  5186.6 1828.41  5214.5 1830.53  5219.5 1834.56  5227.1  1837.3
  5237.3 1842.94  5275.3 1854.03  5279.9 1853.82    5288  1856.6  5308.2 1860.74
#Mann= 7 ,-1 , 0
  4613.6    .035       0    4644     .07       0  4812.7    .035       0
  4998.9    .035       0  5002.9    .035       0  5061.8     .07       0
  5279.9      .1       0
Bank Sta=4998.9,5002.9
XS Rating Curve= 0 ,0
Exp/Cntr=0.3,0.1

Type RM Length L Ch R = 1 ,1815    ,100,100,100
BEGIN DESCRIPTION:
Stream0484 3.0
END DESCRIPTION:
XS GIS Cut Line= 3
      1895675.01     13926224.99       1895984.6     13925981.28
      1896175.01     13925624.97
#Sta/Elev= 30
  4571.5 1851.08  4607.6 1841.95    4614 1838.38  4628.4 1835.44  4657.3 1833.17
  4663.7 1830.82  4671.8 1830.97  4678.1 1828.86    4707 1827.25    4792 1813.94
  4960.6 1811.81  4960.8 1811.31  4964.6 1811.81  4999.6 1812.77  5037.8 1816.97
  5065.4 1818.25  5176.7 1817.32  5191.4  1819.7  5207.7 1825.88  5213.4 1826.49
  5229.7 1834.16  5236.8 1834.94  5251.6 1841.96  5257.3 1842.03  5273.5 1848.97
  5295.5 1852.39  5339.4  1866.9  5361.3 1874.97  5366.6 1878.22  5369.5 1878.22
#Mann= 4 ,-1 , 0
  4571.5    .035       0  4960.6    .035       0  4964.6    .035       0
  5236.8      .1       0
Bank Sta=4960.6,4964.6
XS Rating Curve= 0 ,0
Exp/Cntr=0.3,0.1

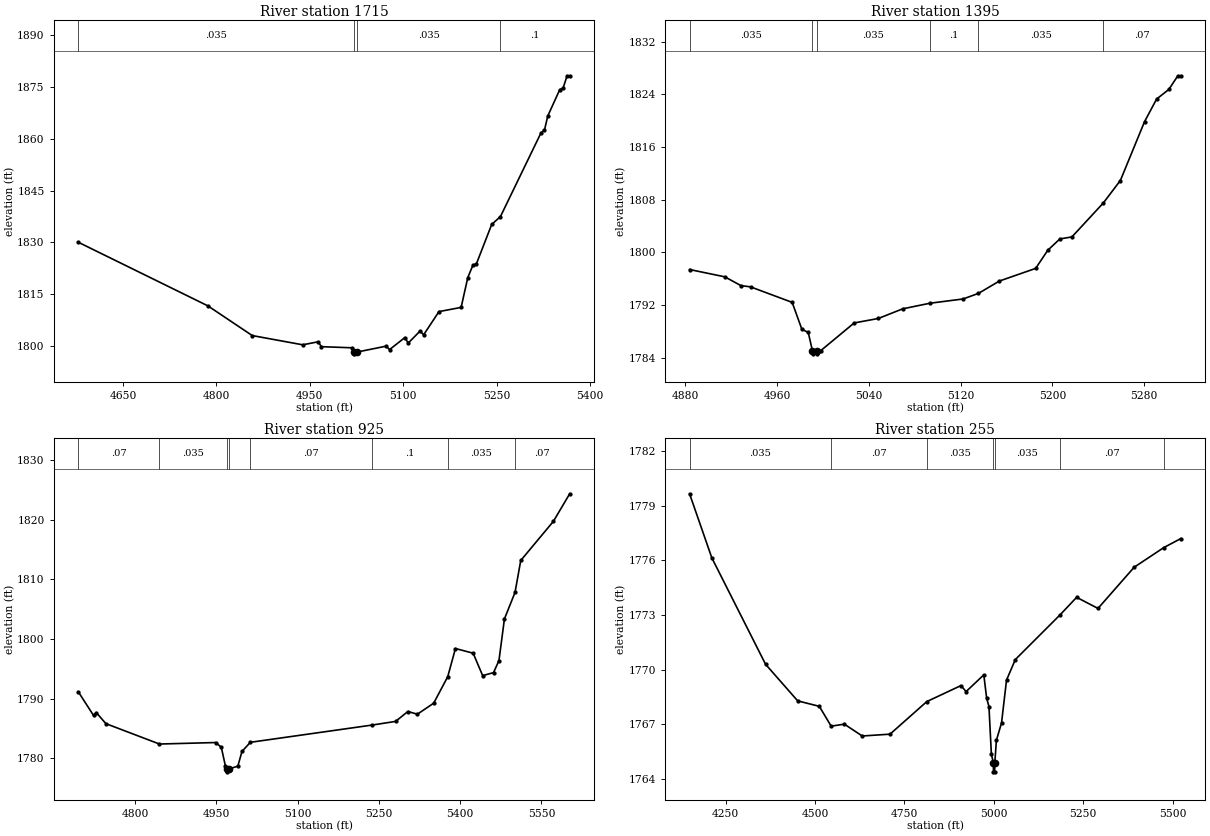
Type RM Length L Ch R = 1 ,1715    ,320,320,320
BEGIN DESCRIPTION:
Mapping XS 723ab1a1
END DESCRIPTION:
XS GIS Cut Line= 3
      1895891.64     13926344.83      1896066.52     13926044.02
      1896224.61     13925632.17
#Sta/Elev= 30
  4578.4 1829.98  4786.4 1811.54  4857.6 1802.93  4938.7 1800.25  4963.4 1801.12
  4968.7 1799.71  5018.1 1799.38  5021.4 1798.13  5021.7 1797.63  5025.4 1798.13
  5072.7 1799.86  5078.1 1798.85  5102.8 1802.36  5108.1 1800.75  5127.4 1804.28
  5132.8 1803.13  5157.5 1809.88  5193.1  1811.1  5203.8 1819.75  5212.1 1823.37
  5217.5 1823.67  5242.2 1835.15  5256.3 1837.46  5321.5 1861.76  5326.9 1862.47
  5332.3 1866.63  5351.5 1874.25  5356.9 1874.72  5363.3 1878.28  5367.5 1878.28
#Mann= 4 ,-1 , 0
  4578.4    .035       0  5021.4    .035       0  5025.4    .035       0
  5256.3      .1       0
Bank Sta=5021.4,5025.4
XS Rating Curve= 0 ,0
Exp/Cntr=0.3,0.1

Type RM Length L Ch R = 1 ,1395    ,470,470,470
BEGIN DESCRIPTION:
Stream0484 2.0
END DESCRIPTION:
XS GIS Cut Line= 3
      1896325.01     13926174.99        1896375.       13926075.
      1896474.99     13925775.02
#Sta/Elev= 30
  4883.9 1797.41  4914.6  1796.3  4928.6 1794.97    4937 1794.78  4973.3 1792.42
  4981.7 1788.35  4987.3 1787.85  4990.9 1785.11  4991.1 1784.61  4994.6 1784.61
  4994.9 1785.11  4998.3 1785.11  5027.3  1789.3  5048.4 1789.98  5069.5 1791.44
  5093.2 1792.29  5122.2 1792.94  5135.6 1793.79  5153.8 1795.66  5185.4 1797.58
    5196 1800.34  5206.5 1802.05    5217 1802.36  5244.3  1807.5  5259.2 1810.92
  5280.3 1819.87  5290.8 1823.29  5301.4 1824.74  5309.3 1826.82  5311.9 1826.82
#Mann= 6 ,-1 , 0
  4883.9    .035       0  4990.9    .035       0  4994.9    .035       0
  5093.2      .1       0  5135.6    .035       0  5244.3     .07       0
Bank Sta=4990.9,4994.9
XS Rating Curve= 0 ,0
Exp/Cntr=0.3,0.1

Type RM Length L Ch R = 1 ,925     ,670,670,670
BEGIN DESCRIPTION:
Stream0484 1.0
END DESCRIPTION:
XS GIS Cut Line= 3
      1896424.95     13926375.01        1896725.       13926325.
        1896675.     13925724.97
#Sta/Elev= 30
  4695.8 1791.11  4723.7 1787.17  4728.8 1787.65  4746.5 1785.79  4845.3 1782.37
  4949.3 1782.62  4959.4 1781.81    4967 1778.67  4970.1  1778.2  4970.4  1777.7
  4974.1  1778.2  4989.9 1778.66  4997.5 1781.12    5013 1782.66    5238 1785.56
    5281 1786.17  5303.5 1787.83  5321.1 1787.38  5351.2 1789.23  5377.1 1793.68
  5391.3 1798.41    5424 1797.62  5441.5 1793.86  5461.6 1794.36  5471.6 1796.39
  5481.7 1803.38  5501.2 1807.82  5511.8 1813.19    5572 1819.76  5602.1 1824.39
#Mann= 8 ,-1 , 0
  4695.8     .07       0  4845.3    .035       0  4970.1    .035       0
  4974.1    .035       0    5013     .07       0    5238      .1       0
  5377.1    .035       0  5501.2     .07       0
Bank Sta=4970.1,4974.1
XS Rating Curve= 0 ,0
Exp/Cntr=0.3,0.1

Type RM Length L Ch R = 1 ,255     ,0,0,0
BEGIN DESCRIPTION:
Stream0484 0.0
END DESCRIPTION:
XS GIS Cut Line= 6
      1896322.86     13927107.03      1896789.87     13927081.09
      1896974.38     13926880.81      1897089.28     13926787.75
       1897096.9     13926649.08      1897050.06     13926305.54
#Sta/Elev= 30
  4149.4 1779.66  4211.6 1776.14  4361.9 1770.29  4451.7 1768.28  4512.1 1767.98
  4545.3 1766.89  4582.2    1767  4632.1 1766.35  4709.8 1766.45  4812.6 1768.24
  4908.1 1769.12  4922.5 1768.79    4972 1769.71    4980 1768.42  4986.4 1767.97
  4993.2 1765.34  4998.8 1764.88    4999 1764.38  5002.5 1764.38  5002.8 1764.88
  5007.2 1766.11  5021.6 1767.07  5035.5 1769.42  5060.1 1770.55  5185.4 1773.01
  5231.5 1773.97  5291.3 1773.36  5392.2 1775.62  5474.9  1776.7  5522.9  1777.2
#Mann= 7 ,-1 , 0
  4149.4    .035       0  4545.3     .07       0  4812.6    .035       0
  4998.8    .035       0  5002.8    .035       0  5185.4     .07       0
  5474.9      .1       0
#Block Obstruct= 2 , 0
         4968.61 1769.56
Bank Sta=4998.8,5002.8
XS Rating Curve= 0 ,0
Exp/Cntr=0.3,0.1

Chan Stop Cuts=-1
Use User Specified Reach Order=0
Composite Channel Slope=5