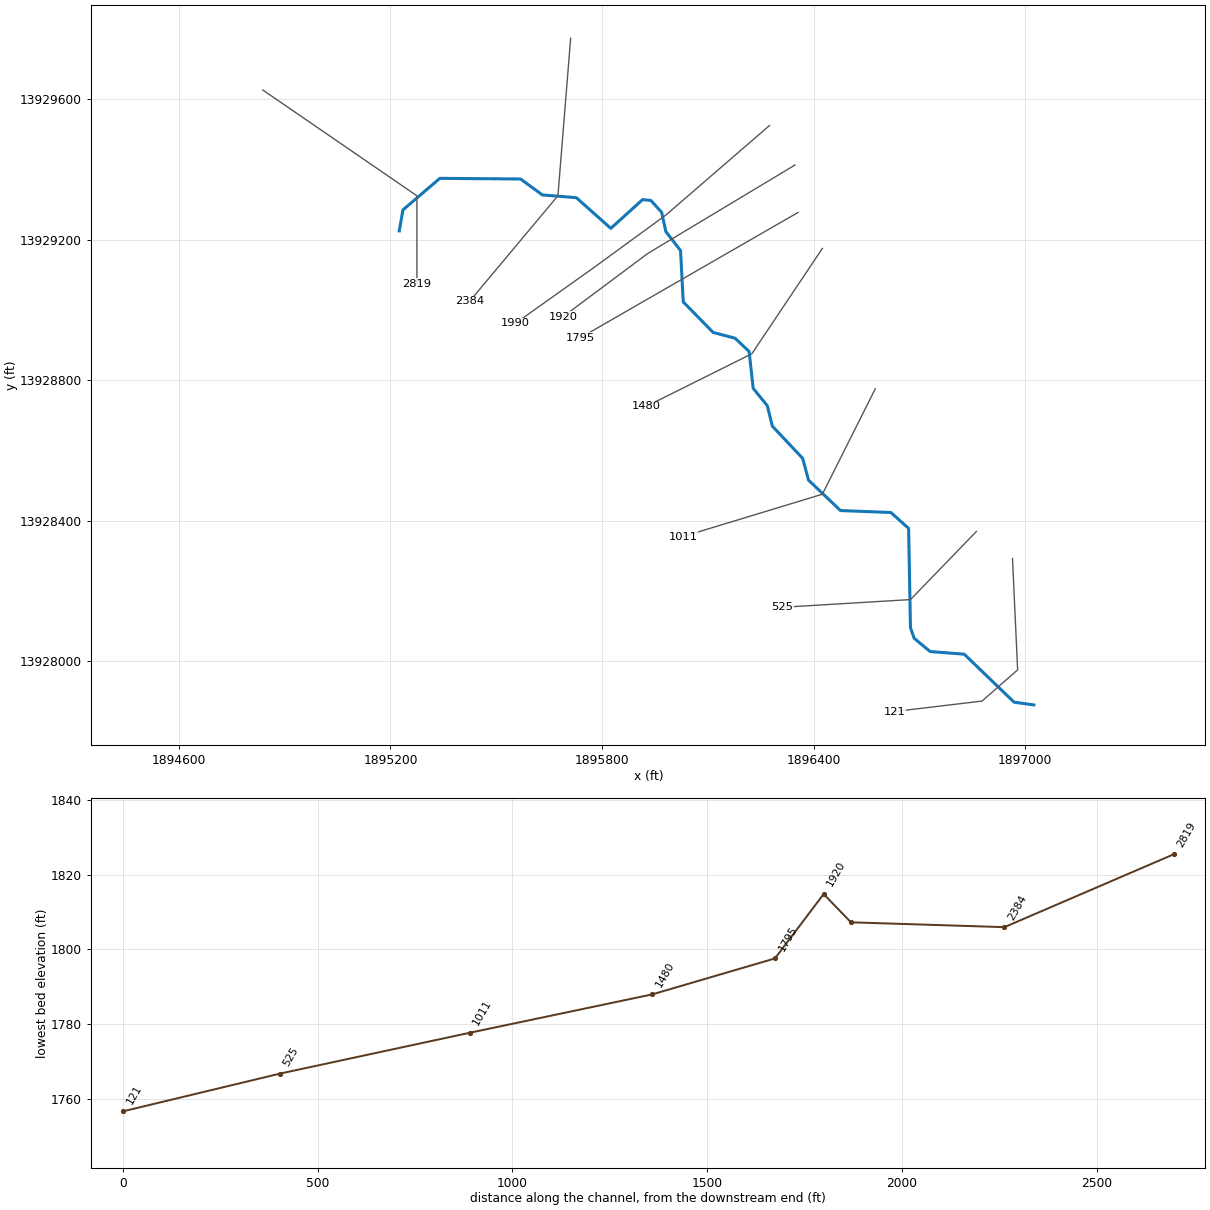
--- Stream0485.prj (project) ---

Proj Title=Stream0485 Base Level Engineering
Current Plan=p01
Default Exp/Contr=0.3,0.1
English Units
Geom File=g01
Flow File=f01
Plan File=p01
BEGIN DESCRIPTION:
Stream0485
END DESCRIPTION:

--- Stream0485.p01 (plan) ---

Plan Title=Multiple Run
Short Identifier=Multiple
Geom File=g01
Flow File=f01
Subcritical Flow
K Sum by GR= 0
Std Step Tol= 0.01
Critical Tol= 0.01
Num of Std Step Trials= 20
Max Error Tol= 0.3
Flow Tol Ratio= 0.001
Split Flow NTrial= 30
Split Flow Tol= 0.02
Split Flow Ratio= 0.02
Log Output Level= 0
Friction Slope Method= 1
Unsteady Friction Slope Method= 2
Unsteady Bridges Friction Slope Method= 1
Parabolic Critical Depth
Global Vel Dist=  1 , 1 , 1
Global Log Level= 0
CheckData=True
Encroach Param= -1, 0, 0, 0
BEGIN DESCRIPTION:
Multiple Run
END DESCRIPTION:

--- Stream0485.f01 (steady flow) ---

Flow Title=Multiple
Number of Profiles=7
Profile Names=10-year,25-year,50-year,1pct_min,100-year,1pct_plu,500-year
River Rch & RM= Stream0485,Reach-1,2819
     544     893    1215     802    1600    3193    2735
Boundary for River Rch & Prof#=Stream0485,Reach-1,1
Up Type=0
Dn Type=3
Dn Slope=0.005
Boundary for River Rch & Prof#=Stream0485,Reach-1,2
Up Type=0
Dn Type=3
Dn Slope=0.005
Boundary for River Rch & Prof#=Stream0485,Reach-1,3
Up Type=0
Dn Type=3
Dn Slope=0.005
Boundary for River Rch & Prof#=Stream0485,Reach-1,4
Up Type=0
Dn Type=3
Dn Slope=0.005
Boundary for River Rch & Prof#=Stream0485,Reach-1,5
Up Type=0
Dn Type=3
Dn Slope=0.005
Boundary for River Rch & Prof#=Stream0485,Reach-1,6
Up Type=0
Dn Type=3
Dn Slope=0.005
Boundary for River Rch & Prof#=Stream0485,Reach-1,7
Up Type=0
Dn Type=3
Dn Slope=0.005

--- Stream0485.g01 (geometry) ---

Geom Title=Existing Conditions

River Reach=Stream0485,Reach-1
Reach XY= 30
      1895225.00     13929225.00      1895235.50     13929284.82
      1895340.15     13929374.62      1895569.06     13929372.74
      1895630.98     13929327.36      1895727.43     13929319.45
      1895825.01     13929232.11      1895915.13     13929314.06
      1895938.69     13929311.73      1895969.17     13929277.87
      1895981.14     13929222.88      1896022.75     13929169.07
      1896030.46     13929022.54      1896115.32     13928935.78
      1896177.57     13928919.26      1896217.26     13928881.45
      1896228.83     13928776.59      1896268.86     13928727.17
      1896283.16     13928668.95      1896369.13     13928577.28
      1896385.77     13928515.30      1896476.46     13928428.54
      1896619.35     13928423.02      1896669.66     13928377.74
      1896674.91     13928094.87      1896685.32     13928064.83
      1896730.69     13928027.07      1896827.42     13928019.47
      1896968.79     13927882.76      1897025.00     13927875.00

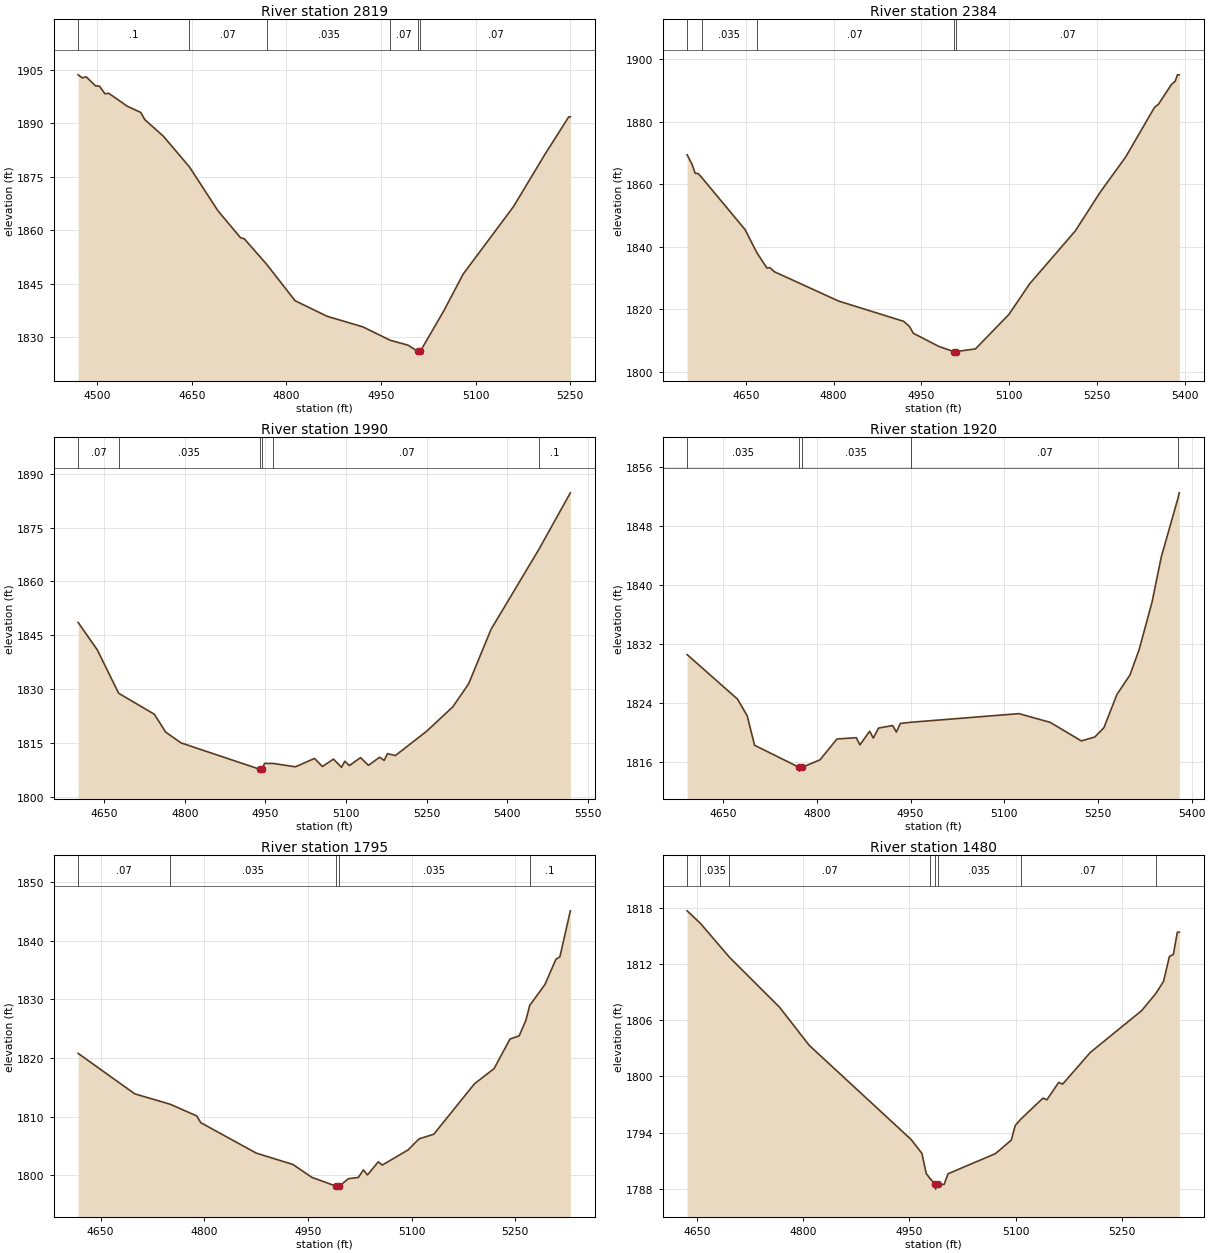
Type RM Length L Ch R = 1,2819,435,435,435
BEGIN DESCRIPTION:
Stream0485 6.0
END DESCRIPTION:
XS GIS Cut Line= 3
      1894837.97     13929626.15      1895275.00     13929325.00
      1895275.00     13929075.04
#Sta/Elev= 30
  4469.7 1903.65  4476.3 1902.79  4482.4 1903.10  4497.3 1900.54  4503.4 1900.48
  4512.2 1898.34  4518.3 1898.46  4548.0 1894.79  4569.0 1893.09  4575.4 1891.07
  4604.8 1886.41  4646.2 1877.78  4691.4 1865.46  4727.2 1857.88  4733.3 1857.56
  4768.7 1850.40  4813.8 1840.17  4864.5 1835.80  4921.3 1832.82  4965.1 1829.03
  4993.0 1827.68  5008.4 1825.94  5008.7 1825.44  5012.4 1825.94  5050.4 1837.55
  5080.4 1847.65  5160.4 1866.66  5210.4 1881.39  5247.9 1891.84  5250.4 1891.84
#Mann=6,-1,0
  4469.7     0.1       0  4646.2    0.07       0  4768.7   0.035       0
  4965.1    0.07       0  5008.4    0.05       0  5012.4    0.07       0
Bank Sta=5008.4,5012.4
Exp/Cntr=0.3,0.1

Type RM Length L Ch R = 1,2384,394,394,394
BEGIN DESCRIPTION:
Stream0485 5.0
END DESCRIPTION:
XS GIS Cut Line= 3
      1895711.10     13929773.59      1895675.00     13929325.00
      1895425.03     13929025.04
#Sta/Elev= 30
  4550.0 1869.39  4558.6 1866.27  4563.7 1863.45  4568.7 1863.41  4575.0 1862.11
  4648.9 1845.47  4669.0 1838.10  4686.2 1833.18  4691.2 1833.29  4699.1 1831.97
  4808.7 1822.60  4919.8 1816.12  4929.8 1814.46  4936.3 1812.30  4980.0 1808.08
  5005.2 1806.45  5005.4 1805.95  5009.2 1806.45  5042.3 1807.30  5099.6 1818.34
  5134.8 1828.09  5212.9 1845.04  5255.8 1857.54  5298.8 1868.65  5348.2 1884.57
  5354.8 1885.53  5376.9 1891.84  5383.4 1892.89  5387.3 1894.96  5390.5 1894.96
#Mann=5,-1,0
  4550.0    0.07       0  4575.0   0.035       0  4669.0    0.07       0
  5005.2    0.05       0  5009.2    0.07       0
Bank Sta=5005.2,5009.2
Exp/Cntr=0.3,0.1

Type RM Length L Ch R = 1,1990,70,70,70
BEGIN DESCRIPTION:
Stream0485 4.0
END DESCRIPTION:
XS GIS Cut Line= 4
      1896274.96     13929524.97      1895981.49     13929270.35
      1895774.18     13929118.47      1895553.91     13928961.33
#Sta/Elev= 30
  4601.6 1848.60  4637.2 1840.98  4677.0 1828.90  4743.5 1823.06  4764.4 1818.11
  4792.9 1815.11  4940.0 1807.74  4940.3 1807.24  4944.0 1807.74  4948.6 1809.40
  4965.1 1809.37  5006.0 1808.44  5041.5 1810.77  5056.2 1808.53  5077.0 1810.58
  5091.7 1808.29  5097.9 1810.00  5106.4 1808.79  5127.2 1811.00  5141.9 1808.85
  5162.7 1811.11  5171.2 1810.22  5177.4 1812.10  5192.0 1811.57  5249.7 1818.26
  5298.8 1825.09  5328.3 1831.49  5370.1 1846.67  5459.9 1869.11  5517.7 1884.65
#Mann=6,-1,0
  4601.6    0.07       0  4677.0   0.035       0  4940.0    0.05       0
  4944.0   0.035       0  4965.1    0.07       0  5459.9     0.1       0
Bank Sta=4940,4944
Exp/Cntr=0.3,0.1

Type RM Length L Ch R = 1,1920,125,125,125
BEGIN DESCRIPTION:
Mapping XS 1b6f4b8b
END DESCRIPTION:
XS GIS Cut Line= 3
      1896347.48     13929412.61      1895930.02     13929160.86
      1895689.50     13928980.54
#Sta/Elev= 30
  4592.2 1830.61  4672.9 1824.57  4688.4 1822.30  4700.2 1818.31  4771.8 1815.30
  4772.1 1814.80  4775.8 1815.30  4804.9 1816.33  4832.1 1819.16  4863.1 1819.34
  4868.9 1818.36  4884.5 1820.22  4890.3 1819.29  4898.7 1820.64  4921.3 1820.99
  4927.2 1820.11  4933.7 1821.27  4950.5 1821.43  5123.5 1822.60  5173.5 1821.42
  5223.4 1818.90  5245.0 1819.43  5259.6 1820.70  5280.4 1825.20  5301.3 1827.85
  5315.9 1831.27  5336.7 1837.76  5351.3 1843.82  5378.0 1851.78  5380.3 1852.56
#Mann=5,-1,0
  4592.2   0.035       0  4771.8    0.05       0  4775.8   0.035       0
  4950.5    0.07       0  5378.0     0.1       0
Bank Sta=4771.8,4775.8
Exp/Cntr=0.3,0.1

Type RM Length L Ch R = 1,1795,315,315,315
BEGIN DESCRIPTION:
Mapping XS 4967cbb0
END DESCRIPTION:
XS GIS Cut Line= 2
      1896355.98     13929277.42      1895739.38     13928920.99
#Sta/Elev= 30
  4617.5 1820.79  4699.5 1813.87  4750.6 1812.10  4789.1 1810.10  4794.9 1808.95
  4875.3 1803.74  4928.4 1801.80  4955.7 1799.60  4991.0 1798.09  4991.3 1797.59
  4995.0 1798.09  5008.8 1799.38  5022.9 1799.58  5030.3 1800.87  5036.1 1800.01
  5051.9 1802.26  5057.6 1801.70  5094.9 1804.29  5110.7 1806.17  5132.2 1806.98
  5191.1 1815.61  5219.3 1818.18  5242.4 1823.24  5255.7 1823.79  5265.5 1826.47
  5270.9 1828.98  5293.0 1832.57  5308.8 1836.86  5314.6 1837.29  5329.7 1845.15
#Mann=5,-1,0
  4617.5    0.07       0  4750.6   0.035       0  4991.0   0.035       0
  4995.0   0.035       0  5270.9     0.1       0
Bank Sta=4991,4995
Exp/Cntr=0.3,0.1

Type RM Length L Ch R = 1,1480,469,469,469
BEGIN DESCRIPTION:
Stream0485 3.0
END DESCRIPTION:
XS GIS Cut Line= 3
      1896424.98     13929174.96      1896225.00     13928875.00
      1895925.02     13928725.01
#Sta/Elev= 30
  4635.7 1817.68  4654.4 1816.35  4695.5 1812.73  4766.4 1807.39  4808.4 1803.32
  4952.6 1793.26  4967.7 1791.79  4973.7 1789.66  4978.5 1789.17  4986.7 1788.48
  4986.9 1787.98  4990.7 1788.48  4999.0 1788.48  5004.6 1789.62  5071.7 1791.77
  5094.0 1793.21  5099.6 1794.77  5107.1 1795.42  5138.8 1797.69  5144.4 1797.52
  5161.1 1799.37  5166.7 1799.19  5205.8 1802.57  5278.5 1807.04  5298.3 1808.85
  5309.3 1810.15  5317.6 1812.81  5323.2 1813.03  5328.8 1815.40  5331.6 1815.40
#Mann=8,-1,0
  4635.7    0.07       0  4654.4   0.035       0  4695.5    0.07       0
  4978.5   0.035       0  4986.7   0.035       0  4990.7   0.035       0
  5107.1    0.07       0  5298.3   0.035       0
Bank Sta=4986.7,4990.7
Exp/Cntr=0.3,0.1

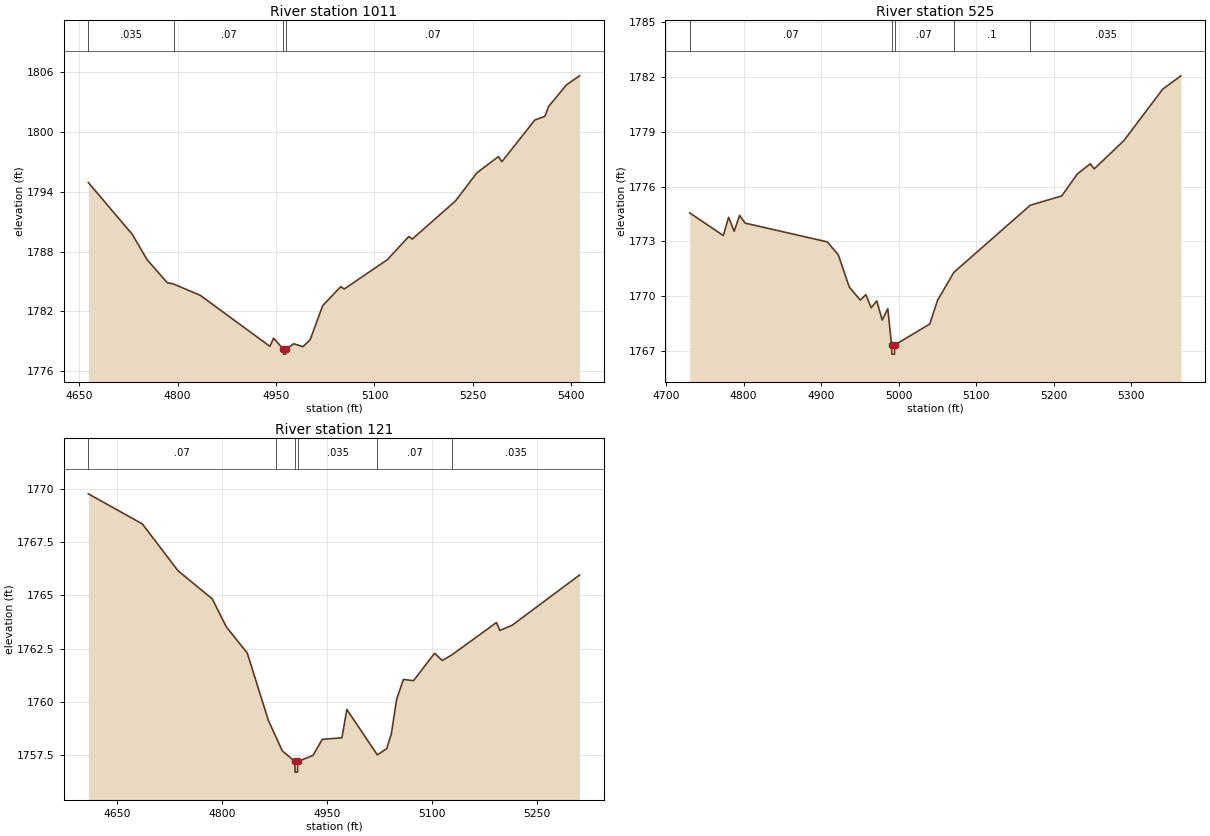
Type RM Length L Ch R = 1,1011,486,486,486
BEGIN DESCRIPTION:
Stream0485 2.0
END DESCRIPTION:
XS GIS Cut Line= 3
      1896575.01     13928775.01      1896425.00     13928475.00
      1896029.88     13928354.56
#Sta/Elev= 30
  4664.0 1794.92  4731.1 1789.71  4753.5 1787.18  4784.2 1784.88  4793.9 1784.74
  4834.5 1783.61  4940.7 1778.49  4946.3 1779.32  4961.1 1778.21  4961.3 1777.71
  4964.8 1777.71  4965.1 1778.21  4977.1 1778.75  4991.0 1778.46  5002.0 1779.15
  5021.1 1782.57  5048.7 1784.48  5053.9 1784.24  5119.6 1787.18  5152.4 1789.51
  5157.6 1789.25  5223.3 1793.06  5256.1 1795.89  5288.9 1797.52  5294.2 1797.01
  5344.4 1801.19  5359.8 1801.56  5365.3 1802.54  5392.7 1804.72  5412.5 1805.62
#Mann=4,-1,0
  4664.0   0.035       0  4793.9    0.07       0  4961.1    0.05       0
  4965.1    0.07       0
Bank Sta=4961.1,4965.1
Exp/Cntr=0.3,0.1

Type RM Length L Ch R = 1,525,404,404,404
BEGIN DESCRIPTION:
Stream0485 1.0
END DESCRIPTION:
XS GIS Cut Line= 3
      1896862.00     13928369.08      1896675.00     13928175.00
      1896311.67     13928153.07
#Sta/Elev= 30
  4730.4 1774.56  4773.7 1773.32  4780.6 1774.32  4787.8 1773.55  4794.7 1774.42
  4801.9 1774.00  4907.9 1772.97  4922.1 1772.26  4936.2 1770.50  4950.4 1769.78
  4957.6 1770.08  4964.5 1769.36  4971.7 1769.74  4978.7 1768.69  4985.9 1769.31
  4990.8 1767.32  4991.1 1766.82  4994.6 1766.82  4994.8 1767.32  5040.0 1768.47
  5050.0 1769.76  5071.1 1771.30  5169.7 1774.98  5210.3 1775.49  5230.3 1776.69
  5247.1 1777.25  5252.1 1776.97  5290.4 1778.52  5340.5 1781.34  5363.9 1782.07
#Mann=5,-1,0
  4730.4    0.07       0  4990.8    0.05       0  4994.8    0.07       0
  5071.1     0.1       0  5169.7   0.035       0
Bank Sta=4990.8,4994.8
Exp/Cntr=0.3,0.1

Type RM Length L Ch R = 1,121,0,0,0
BEGIN DESCRIPTION:
Stream0485 0.0
END DESCRIPTION:
XS GIS Cut Line= 4
      1896964.29     13928292.10      1896978.87     13927974.89
      1896877.88     13927885.96      1896629.16     13927856.20
#Sta/Elev= 30
  4608.8 1769.77  4686.0 1768.36  4737.1 1766.16  4786.1 1764.84  4806.1 1763.53
  4836.1 1762.30  4866.2 1759.15  4877.3 1758.35  4886.2 1757.71  4904.2 1757.21
  4904.5 1756.71  4908.0 1756.71  4908.2 1757.21  4930.0 1757.49  4943.5 1758.25
  4971.5 1758.32  4978.6 1759.65  5022.2 1757.52  5035.5 1757.81  5042.2 1758.50
  5049.8 1760.13  5059.5 1761.06  5073.9 1761.00  5104.1 1762.29  5115.1 1761.95
  5128.7 1762.21  5192.5 1763.73  5197.5 1763.36  5214.9 1763.60  5311.4 1765.96
#Mann=6,-1,0
  4608.8    0.07       0  4877.3   0.035       0  4904.2   0.035       0
  4908.2   0.035       0  5022.2    0.07       0  5128.7   0.035       0
Bank Sta=4904.2,4908.2
Exp/Cntr=0.3,0.1

Chan Stop Cuts=-1