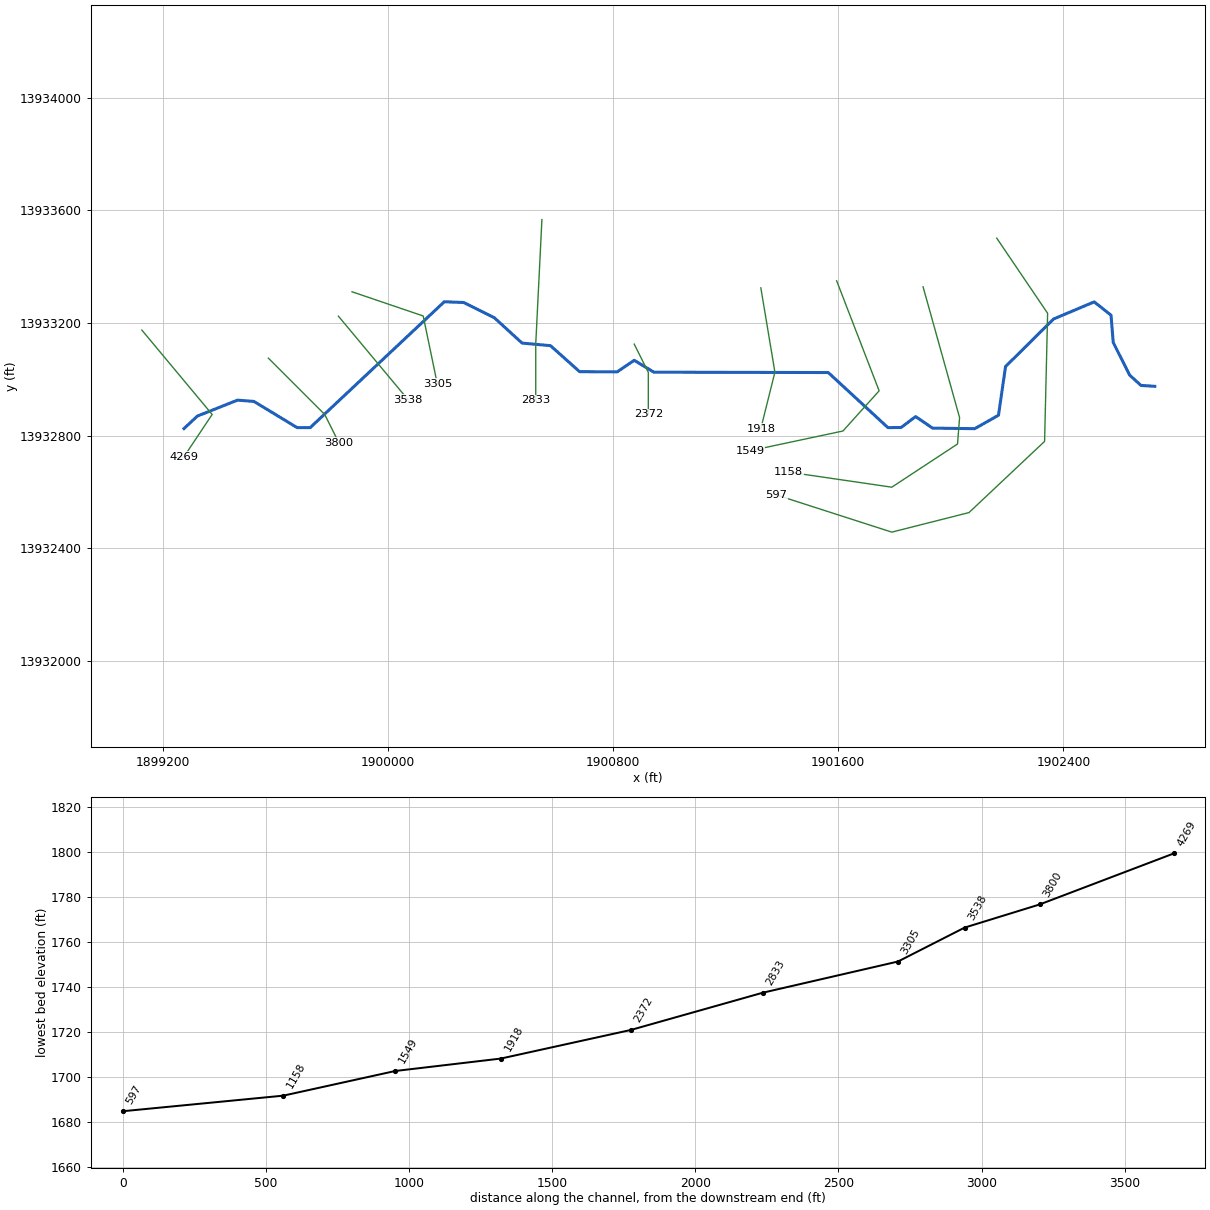
--- Stream0486.prj (project) ---

Proj Title=Stream0486 Base Level Engineering
Current Plan=p01
Default Exp/Contr=0.3,0.1
English Units
Geom File=g01
Flow File=f01
Plan File=p01
BEGIN DESCRIPTION:
Stream0486
END DESCRIPTION:

--- Stream0486.p01 (plan) ---

Plan Title=Multiple Run
Short Identifier=Multiple
Geom File=g01
Flow File=f01
Subcritical Flow
K Sum by GR= 0
Std Step Tol= 0.01
Critical Tol= 0.01
Num of Std Step Trials= 20
Max Error Tol= 0.3
Flow Tol Ratio= 0.001
Split Flow NTrial= 30
Split Flow Tol= 0.02
Split Flow Ratio= 0.02
Log Output Level= 0
Friction Slope Method= 1
Unsteady Friction Slope Method= 2
Unsteady Bridges Friction Slope Method= 1
Parabolic Critical Depth
Global Vel Dist=  1 , 1 , 1
Global Log Level= 0
CheckData=True
Encroach Param= -1, 0, 0, 0
BEGIN DESCRIPTION:
Multiple Run
END DESCRIPTION:

--- Stream0486.f01 (steady flow) ---

Flow Title=Multiple
Number of Profiles=7
Profile Names=10-year,25-year,50-year,1pct_min,100-year,1pct_plu,500-year
River Rch & RM= Stream0486,Reach-1,4269
     749    1253    1724    1151    2296    4581    4013
Boundary for River Rch & Prof#=Stream0486,Reach-1,1
Up Type=0
Dn Type=3
Dn Slope=0.005
Boundary for River Rch & Prof#=Stream0486,Reach-1,2
Up Type=0
Dn Type=3
Dn Slope=0.005
Boundary for River Rch & Prof#=Stream0486,Reach-1,3
Up Type=0
Dn Type=3
Dn Slope=0.005
Boundary for River Rch & Prof#=Stream0486,Reach-1,4
Up Type=0
Dn Type=3
Dn Slope=0.005
Boundary for River Rch & Prof#=Stream0486,Reach-1,5
Up Type=0
Dn Type=3
Dn Slope=0.005
Boundary for River Rch & Prof#=Stream0486,Reach-1,6
Up Type=0
Dn Type=3
Dn Slope=0.005
Boundary for River Rch & Prof#=Stream0486,Reach-1,7
Up Type=0
Dn Type=3
Dn Slope=0.005

--- Stream0486.g01 (geometry) ---

Geom Title=Existing Conditions

River Reach=Stream0486,Reach-1
Reach XY= 30
      1899275.00     13932825.00      1899322.63     13932869.33
      1899464.95     13932925.78      1899523.42     13932921.33
      1899676.74     13932828.31      1899723.37     13932828.12
      1900199.96     13933275.50      1900269.03     13933272.86
      1900377.29     13933219.15      1900476.50     13933128.63
      1900577.42     13933119.46      1900680.86     13933027.06
      1900814.56     13933026.37      1900875.00     13933067.44
      1900944.98     13933025.18      1901564.57     13933023.95
      1901776.65     13932828.16      1901823.35     13932828.57
      1901874.99     13932867.41      1901935.44     13932826.38
      1902085.25     13932824.47      1902169.65     13932872.26
      1902194.61     13933045.16      1902365.32     13933214.24
      1902509.80     13933275.11      1902569.58     13933227.75
      1902577.33     13933130.97      1902635.55     13933015.02
      1902676.03     13932978.14      1902725.00     13932975.00

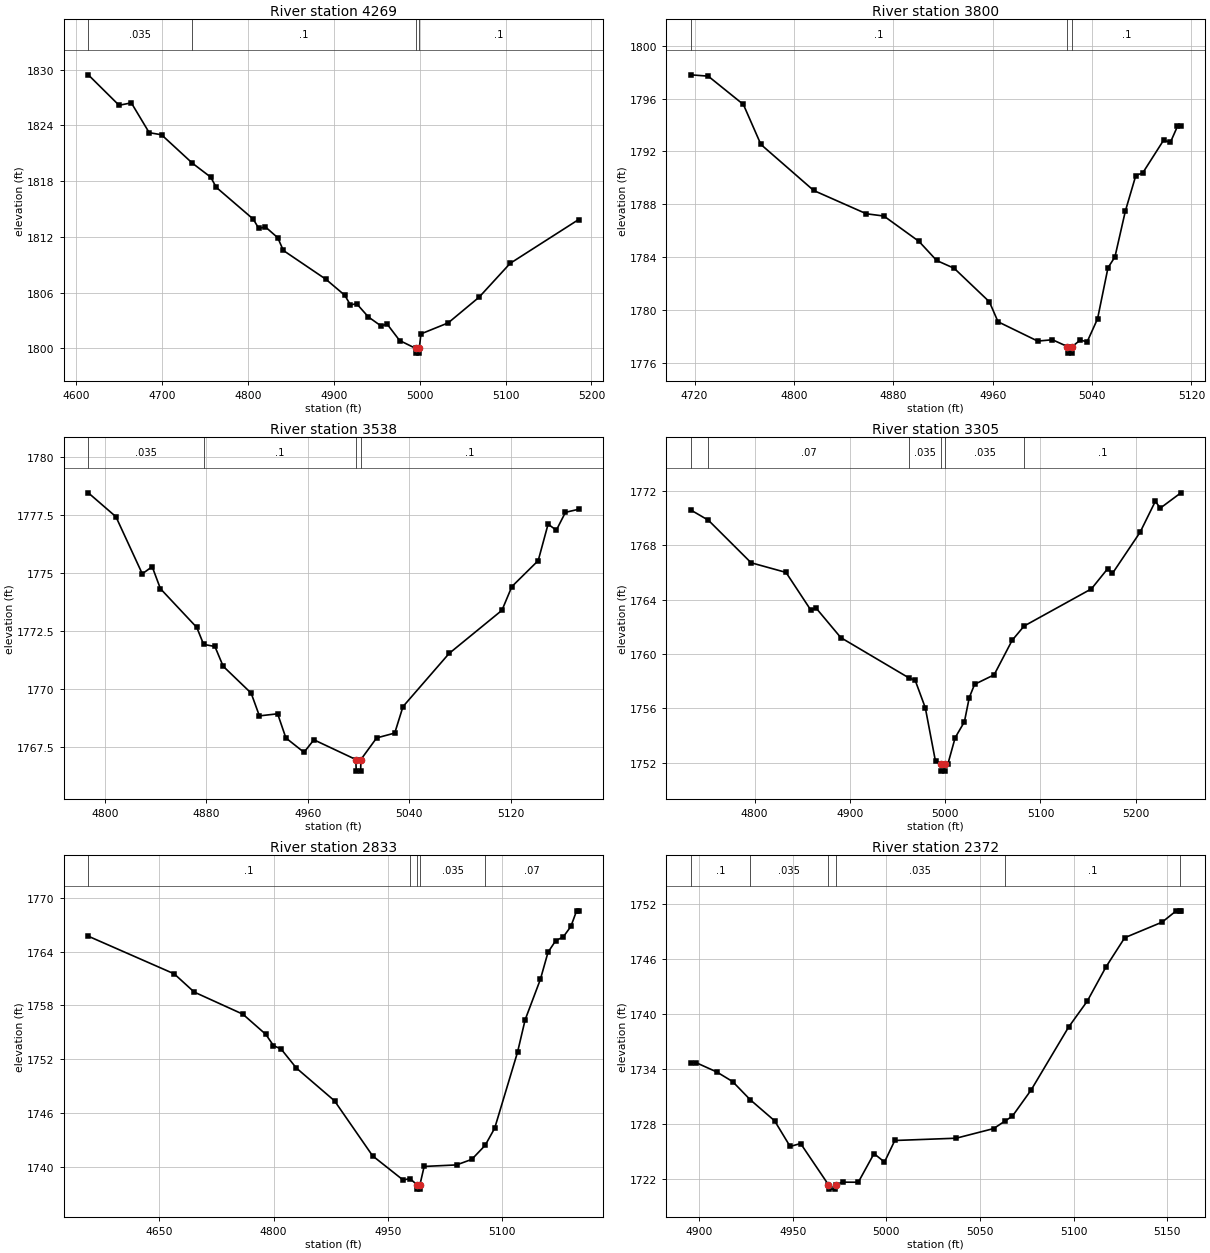
Type RM Length L Ch R = 1,4269,469,469,469
BEGIN DESCRIPTION:
Stream0486 7.0
END DESCRIPTION:
XS GIS Cut Line= 3
      1899125.00     13933175.00      1899375.00     13932875.00
      1899274.99     13932724.99
#Sta/Elev= 30
  4614.2 1829.45  4650.0 1826.17  4664.3 1826.43  4685.1 1823.22  4699.5 1822.99
  4735.4 1819.93  4756.7 1818.43  4763.2 1817.33  4806.2 1813.91  4812.7 1812.91
  4820.5 1813.06  4834.8 1811.90  4841.3 1810.53  4890.8 1807.43  4912.9 1805.70
  4919.4 1804.66  4926.6 1804.80  4940.3 1803.37  4954.6 1802.43  4962.4 1802.57
  4976.7 1800.83  4995.6 1799.97  4995.8 1799.47  4999.3 1799.47  4999.6 1799.97
  5001.5 1801.54  5033.3 1802.73  5069.3 1805.50  5105.4 1809.14  5185.0 1813.85
#Mann=4,-1,0
  4614.2   0.035       0  4735.4     0.1       0  4995.6    0.05       0
  4999.6     0.1       0
Bank Sta=4995.6,4999.6
Exp/Cntr=0.3,0.1

Type RM Length L Ch R = 1,3800,262,262,262
BEGIN DESCRIPTION:
Stream0486 6.0
END DESCRIPTION:
XS GIS Cut Line= 3
      1899575.03     13933074.97      1899775.00     13932875.00
      1899825.00     13932775.01
#Sta/Elev= 30
  4716.9 1797.79  4731.0 1797.69  4759.3 1795.55  4773.4 1792.53  4815.9 1789.05
  4858.3 1787.29  4872.4 1787.12  4900.7 1785.20  4914.9 1783.76  4929.0 1783.17
  4957.3 1780.64  4964.3 1779.13  4996.2 1777.67  5008.1 1777.77  5020.1 1777.26
  5020.3 1776.76  5023.8 1776.76  5024.1 1777.26  5030.5 1777.75  5036.0 1777.61
  5044.4 1779.35  5052.8 1783.21  5058.4 1784.03  5066.8 1787.50  5075.2 1790.18
  5080.8 1790.38  5097.5 1792.84  5103.1 1792.70  5108.7 1793.89  5111.5 1793.89
#Mann=3,-1,0
  4716.9     0.1       0  5020.1    0.05       0  5024.1     0.1       0
Bank Sta=5020.1,5024.1
Exp/Cntr=0.3,0.1

Type RM Length L Ch R = 1,3538,233,233,233
BEGIN DESCRIPTION:
Mapping XS aa873e67
END DESCRIPTION:
XS GIS Cut Line= 2
      1899823.84     13933224.12      1900071.58     13932927.06
#Sta/Elev= 30
  4786.8 1778.46  4808.6 1777.43  4829.4 1774.97  4837.2 1775.28  4843.7 1774.33
  4872.4 1772.66  4877.8 1771.93  4886.7 1771.84  4893.2 1770.99  4915.3 1769.83
  4921.8 1768.85  4936.2 1768.94  4942.7 1767.90  4957.0 1767.28  4964.8 1767.82
  4997.9 1766.97  4998.2 1766.47  5001.7 1766.47  5001.9 1766.97  5014.3 1767.90
  5028.6 1768.11  5035.1 1769.25  5071.5 1771.54  5113.2 1773.40  5121.0 1774.42
  5141.8 1775.54  5149.6 1777.11  5156.1 1776.85  5163.3 1777.62  5173.6 1777.75
#Mann=4,-1,0
  4786.8   0.035       0  4877.8     0.1       0  4997.9    0.05       0
  5001.9     0.1       0
Bank Sta=4997.9,5001.9
Exp/Cntr=0.3,0.1

Type RM Length L Ch R = 1,3305,472,472,472
BEGIN DESCRIPTION:
Stream0486 5.0
END DESCRIPTION:
XS GIS Cut Line= 3
      1899871.94     13933311.04      1900125.00     13933225.00
      1900175.32     13932983.07
#Sta/Elev= 30
  4733.0 1770.60  4751.6 1769.84  4796.4 1766.71  4833.0 1766.00  4859.1 1763.22
  4864.4 1763.39  4890.5 1761.20  4961.6 1758.25  4968.6 1758.05  4979.2 1756.03
  4989.9 1752.08  4995.7 1751.87  4995.9 1751.37  4999.4 1751.37  4999.7 1751.87
  5002.8 1751.87  5010.5 1753.83  5020.2 1755.00  5025.3 1756.78  5030.9 1757.76
  5051.4 1758.46  5070.3 1761.00  5082.8 1762.05  5153.5 1764.79  5170.5 1766.27
  5175.6 1765.93  5204.6 1768.96  5220.6 1771.24  5225.7 1770.73  5247.4 1771.86
#Mann=6,-1,0
  4733.0     0.1       0  4751.6    0.07       0  4961.6   0.035       0
  4995.7   0.035       0  4999.7   0.035       0  5082.8     0.1       0
Bank Sta=4995.7,4999.7
Exp/Cntr=0.3,0.1

Type RM Length L Ch R = 1,2833,461,461,461
BEGIN DESCRIPTION:
Stream0486 4.0
END DESCRIPTION:
XS GIS Cut Line= 3
      1900546.94     13933567.57      1900525.00     13933125.00
      1900525.00     13932925.02
#Sta/Elev= 30
  4556.9 1765.72  4669.6 1761.52  4695.8 1759.49  4759.7 1757.02  4789.8 1754.77
  4799.8 1753.52  4809.8 1753.14  4829.8 1751.02  4879.9 1747.36  4929.9 1741.22
  4970.0 1738.52  4978.7 1738.69  4988.0 1738.01  4988.3 1737.51  4991.8 1737.51
  4992.0 1738.01  4997.5 1740.04  5040.0 1740.21  5060.0 1740.83  5077.5 1742.39
  5090.0 1744.30  5120.0 1752.78  5130.0 1756.40  5150.0 1760.91  5160.0 1763.93
  5170.0 1765.21  5180.0 1765.64  5190.0 1766.81  5197.5 1768.55  5200.0 1768.55
#Mann=5,-1,0
  4556.9     0.1       0  4978.7   0.035       0  4988.0   0.035       0
  4992.0   0.035       0  5077.5    0.07       0
Bank Sta=4988,4992
Exp/Cntr=0.3,0.1

Type RM Length L Ch R = 1,2372,454,454,454
BEGIN DESCRIPTION:
Stream0486 3.0
END DESCRIPTION:
XS GIS Cut Line= 3
      1900874.99     13933125.03      1900925.00     13933025.00
      1900925.00     13932875.04
#Sta/Elev= 30
  4895.5 1734.73  4898.3 1734.73  4909.5 1733.70  4917.9 1732.66  4927.3 1730.68
  4940.3 1728.39  4948.6 1725.59  4954.2 1725.91  4969.0 1721.44  4969.3 1720.94
  4972.8 1720.94  4973.0 1721.44  4976.6 1721.70  4985.0 1721.69  4993.4 1724.81
  4999.0 1723.89  5004.5 1726.24  5037.3 1726.49  5057.3 1727.54  5063.2 1728.34
  5067.3 1728.89  5077.3 1731.74  5097.3 1738.59  5107.3 1741.43  5117.3 1745.16
  5127.3 1748.34  5147.3 1750.04  5154.8 1751.27  5157.0 1751.27  5157.3 1751.27
#Mann=6,-1,0
  4895.5     0.1       0  4927.3   0.035       0  4969.0   0.035       0
  4973.0   0.035       0  5063.2     0.1       0  5157.0    0.07       0
Bank Sta=4969,4973
Exp/Cntr=0.3,0.1

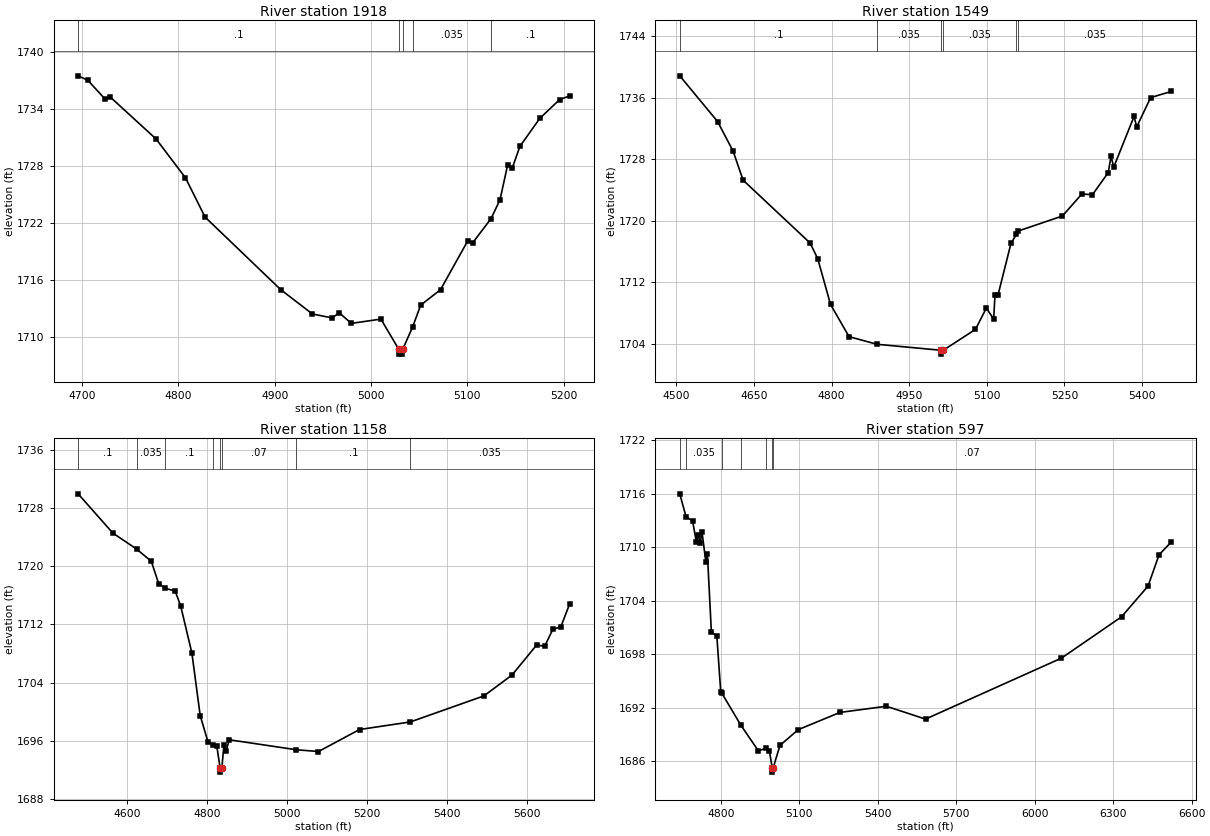
Type RM Length L Ch R = 1,1918,369,369,369
BEGIN DESCRIPTION:
Stream0486 2.0
END DESCRIPTION:
XS GIS Cut Line= 3
      1901325.00     13933324.98      1901375.00     13933025.00
      1901324.99     13932824.98
#Sta/Elev= 30
  4695.9 1737.54  4706.0 1737.07  4723.8 1735.10  4728.8 1735.35  4777.0 1730.87
  4807.4 1726.79  4827.7 1722.66  4906.2 1715.02  4939.2 1712.45  4959.5 1712.04
  4967.1 1712.56  4979.7 1711.46  5010.3 1711.91  5028.9 1708.72  5029.2 1708.22
  5032.7 1708.22  5032.9 1708.72  5043.2 1711.07  5051.6 1713.38  5072.2 1715.01
  5100.5 1720.16  5105.7 1719.96  5124.7 1722.50  5134.0 1724.49  5141.8 1728.11
  5146.9 1727.88  5154.6 1730.10  5175.3 1733.06  5195.9 1735.04  5206.2 1735.42
#Mann=5,-1,0
  4695.9     0.1       0  5028.9    0.05       0  5032.9     0.1       0
  5043.2   0.035       0  5124.7     0.1       0
Bank Sta=5028.9,5032.9
Exp/Cntr=0.3,0.1

Type RM Length L Ch R = 1,1549,391,391,391
BEGIN DESCRIPTION:
Stream0486 1.0
END DESCRIPTION:
XS GIS Cut Line= 4
      1901594.39     13933350.09      1901745.47     13932958.93
      1901616.77     13932816.17      1901286.08     13932745.87
#Sta/Elev= 30
  4506.7 1738.84  4579.8 1732.90  4609.8 1729.05  4629.0 1725.29  4758.7 1717.11
  4773.4 1715.06  4798.0 1709.14  4833.8 1704.96  4887.6 1703.97  5011.8 1703.19
  5012.1 1702.69  5015.8 1703.19  5078.1 1705.91  5099.0 1708.67  5113.2 1707.25
  5115.8 1710.39  5121.7 1710.39  5146.7 1717.09  5157.2 1718.24  5160.2 1718.67
  5246.0 1720.63  5283.6 1723.49  5304.1 1723.40  5334.7 1726.28  5340.0 1728.41
  5345.2 1726.98  5384.5 1733.57  5389.6 1732.21  5416.5 1736.01  5456.3 1736.81
#Mann=6,-1,0
  4506.7     0.1       0  4887.6   0.035       0  5011.8   0.035       0
  5015.8   0.035       0  5157.2    0.07       0  5160.2   0.035       0
Bank Sta=5011.8,5015.8
Exp/Cntr=0.3,0.1

Type RM Length L Ch R = 1,1158,561,561,561
BEGIN DESCRIPTION:
Stream0486 0.0
END DESCRIPTION:
XS GIS Cut Line= 5
      1901901.58     13933328.56      1902031.33     13932863.67
      1902023.99     13932770.00      1901790.38     13932616.52
      1901423.51     13932670.16
#Sta/Elev= 30
  4478.4 1729.93  4565.1 1724.54  4624.3 1722.35  4661.1 1720.67  4679.4 1717.61
  4695.8 1716.97  4720.9 1716.57  4734.7 1714.48  4762.4 1708.08  4783.2 1699.48
  4803.0 1695.80  4816.2 1695.47  4824.7 1695.27  4833.1 1692.22  4833.3 1691.72
  4837.1 1692.22  4842.4 1695.40  4847.6 1694.61  4855.8 1696.16  5023.4 1694.79
  5078.5 1694.55  5181.0 1697.57  5307.8 1698.61  5491.6 1702.19  5561.6 1705.05
  5622.9 1709.16  5643.2 1709.01  5663.4 1711.31  5683.6 1711.69  5705.3 1714.78
#Mann=8,-1,0
  4478.4     0.1       0  4624.3   0.035       0  4695.8     0.1       0
  4816.2    0.07       0  4833.1    0.05       0  4837.1    0.07       0
  5023.4     0.1       0  5307.8   0.035       0
Bank Sta=4833.1,4837.1
Exp/Cntr=0.3,0.1

Type RM Length L Ch R = 1,597,0,0,0
BEGIN DESCRIPTION:
Stream0486 0.1
END DESCRIPTION:
XS GIS Cut Line= 6
      1902163.43     13933501.51      1902344.20     13933234.55
      1902333.45     13932779.34      1902064.68     13932526.24
      1901790.38     13932456.80      1901380.68     13932588.73
#Sta/Elev= 30
  4643.6 1715.97  4667.8 1713.37  4692.4 1712.96  4707.3 1710.52  4713.4 1711.41
  4722.3 1710.46  4728.3 1711.74  4743.3 1708.36  4749.3 1709.19  4764.3 1700.51
  4785.3 1700.02  4800.2 1693.79  4804.4 1693.63  4877.5 1690.03  4944.0 1687.18
  4972.0 1687.45  4985.9 1687.21  4996.7 1685.29  4996.9 1684.79  5000.7 1685.29
  5026.7 1687.79  5096.5 1689.55  5256.0 1691.48  5433.3 1692.17  5582.8 1690.73
  6102.2 1697.56  6331.9 1702.19  6433.4 1705.64  6475.3 1709.14  6521.9 1710.57
#Mann=7,-1,0
  4643.6     0.1       0  4667.8   0.035       0  4804.4     0.1       0
  4877.5   0.035       0  4972.0    0.07       0  4996.7    0.05       0
  5000.7    0.07       0
Bank Sta=4996.7,5000.7
Exp/Cntr=0.3,0.1

Chan Stop Cuts=-1