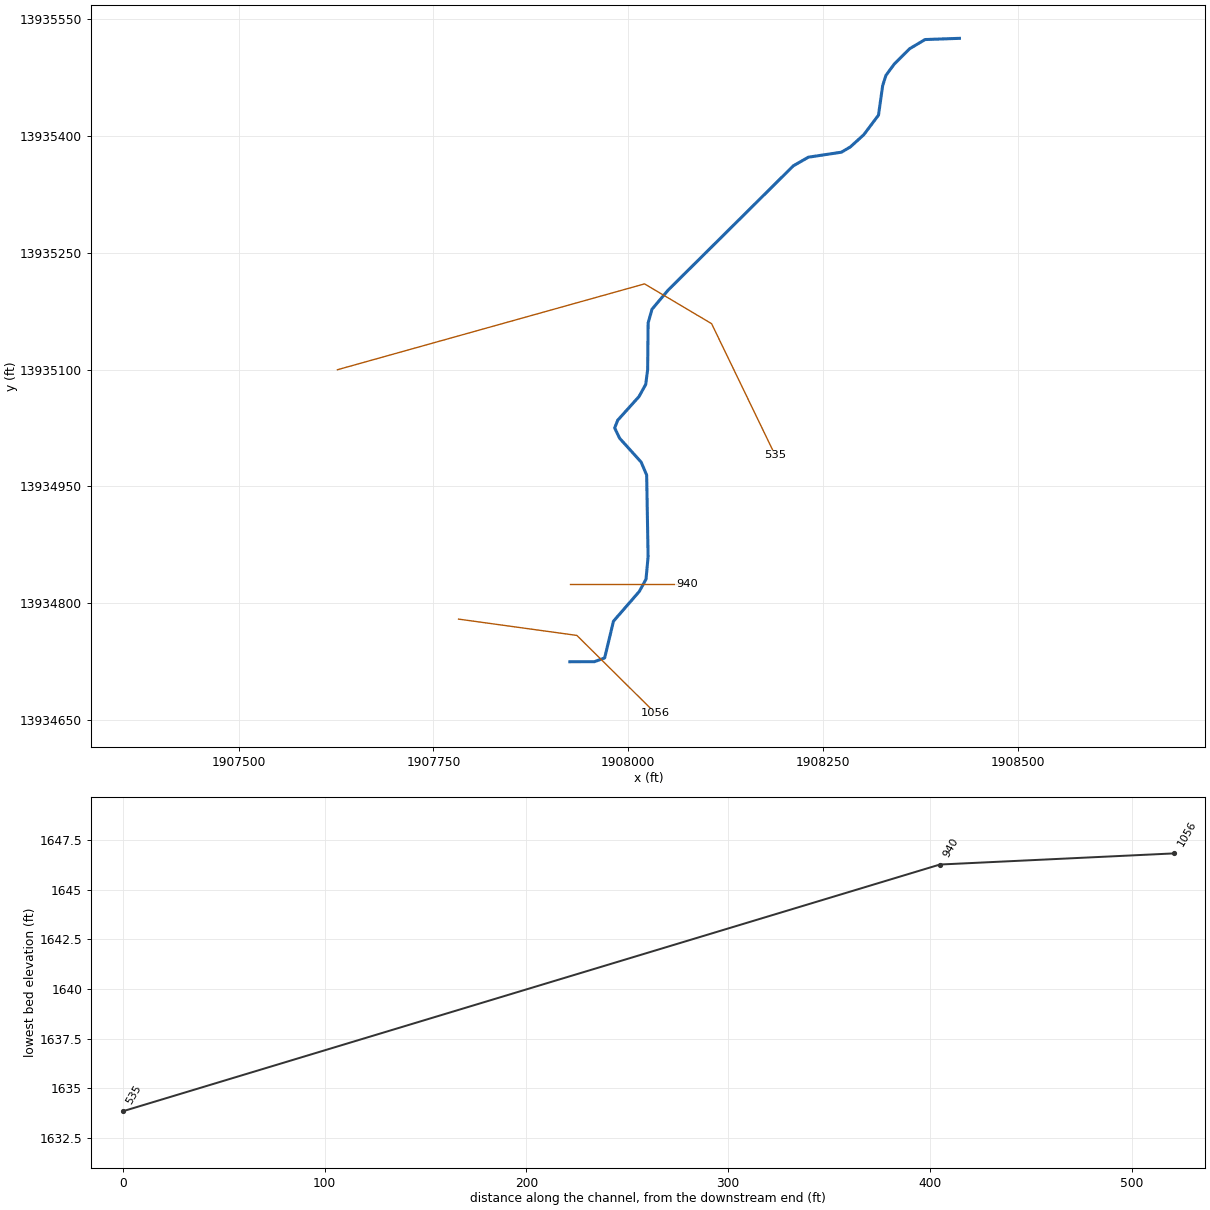
--- Stream0487.prj (project) ---

Proj Title=Stream0487 Base Level Engineering
Current Plan=p01
Default Exp/Contr=0.3,0.1
English Units
Geom File=g01
Flow File=f01
Plan File=p01
BEGIN DESCRIPTION:
Stream0487
END DESCRIPTION:

--- Stream0487.p01 (plan) ---

Plan Title=Multiple Run
Short Identifier=Multiple
Geom File=g01
Flow File=f01
Subcritical Flow
K Sum by GR= 0
Std Step Tol= 0.01
Critical Tol= 0.01
Num of Std Step Trials= 20
Max Error Tol= 0.3
Flow Tol Ratio= 0.001
Split Flow NTrial= 30
Split Flow Tol= 0.02
Split Flow Ratio= 0.02
Log Output Level= 0
Friction Slope Method= 1
Unsteady Friction Slope Method= 2
Unsteady Bridges Friction Slope Method= 1
Parabolic Critical Depth
Global Vel Dist=  1 , 1 , 1
Global Log Level= 0
CheckData=True
Encroach Param= -1, 0, 0, 0
BEGIN DESCRIPTION:
Multiple Run
END DESCRIPTION:

--- Stream0487.f01 (steady flow) ---

Flow Title=Multiple
Number of Profiles=7
Profile Names=10-year,25-year,50-year,1pct_min,100-year,1pct_plu,500-year
River Rch & RM= Stream0487,Reach-1,1056
     527     861    1168     771    1538    3068    2620
Boundary for River Rch & Prof#=Stream0487,Reach-1,1
Up Type=0
Dn Type=3
Dn Slope=0.005
Boundary for River Rch & Prof#=Stream0487,Reach-1,2
Up Type=0
Dn Type=3
Dn Slope=0.005
Boundary for River Rch & Prof#=Stream0487,Reach-1,3
Up Type=0
Dn Type=3
Dn Slope=0.005
Boundary for River Rch & Prof#=Stream0487,Reach-1,4
Up Type=0
Dn Type=3
Dn Slope=0.005
Boundary for River Rch & Prof#=Stream0487,Reach-1,5
Up Type=0
Dn Type=3
Dn Slope=0.005
Boundary for River Rch & Prof#=Stream0487,Reach-1,6
Up Type=0
Dn Type=3
Dn Slope=0.005
Boundary for River Rch & Prof#=Stream0487,Reach-1,7
Up Type=0
Dn Type=3
Dn Slope=0.005

--- Stream0487.g01 (geometry) ---

Geom Title=Existing Conditions

River Reach=Stream0487,Reach-1
Reach XY= 30
      1907925.00     13934725.00      1907956.56     13934725.06
      1907969.72     13934729.90      1907981.04     13934777.00
      1908014.26     13934815.28      1908022.80     13934830.91
      1908025.48     13934859.83      1908023.63     13934964.56
      1908016.55     13934981.18      1907988.95     13935011.79
      1907982.56     13935025.00      1907986.47     13935034.91
      1908013.75     13935065.22      1908022.44     13935080.90
      1908024.90     13935099.97      1908025.51     13935159.78
      1908030.52     13935177.43      1908051.18     13935201.87
      1908211.80     13935361.36      1908231.09     13935372.45
      1908273.57     13935378.89      1908285.00     13935385.65
      1908302.14     13935401.16      1908321.13     13935426.44
      1908326.52     13935464.42      1908330.72     13935477.48
      1908341.39     13935492.02      1908361.22     13935511.73
      1908380.87     13935523.44      1908425.00     13935525.00

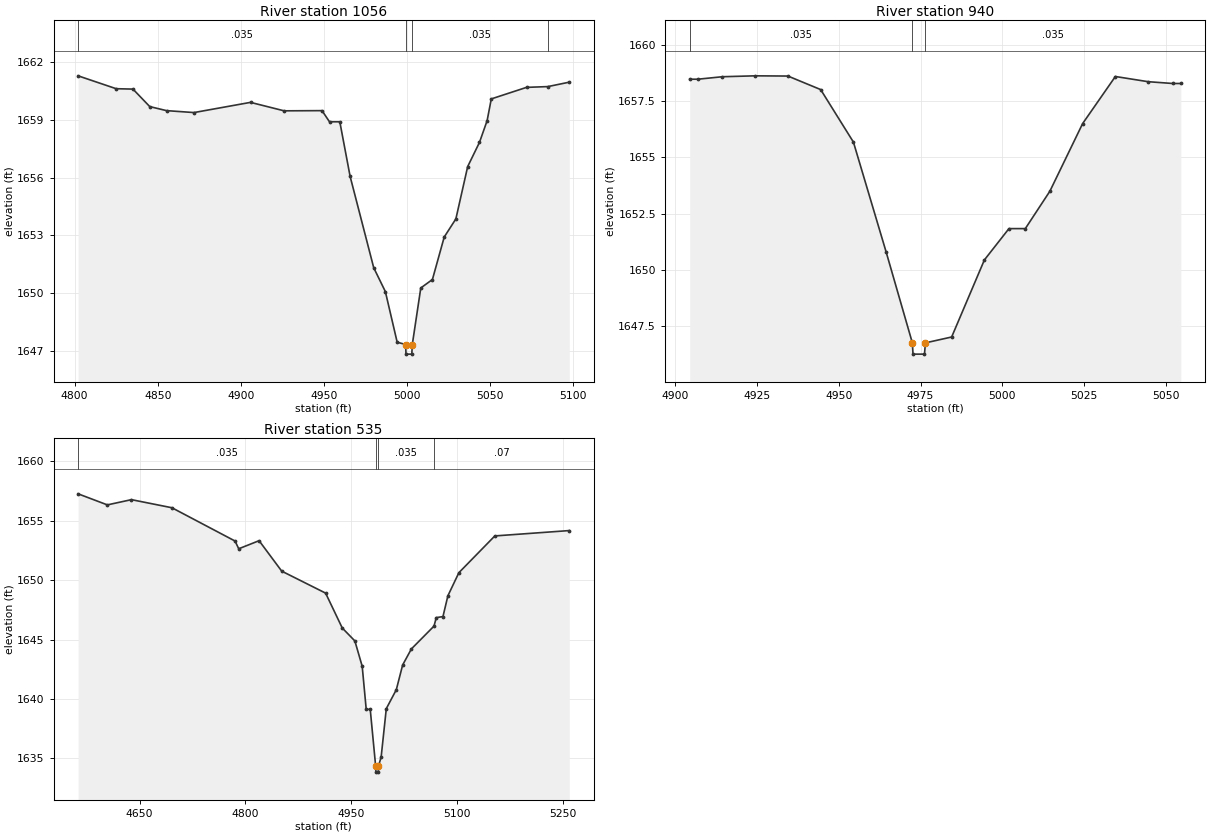
Type RM Length L Ch R = 1,1056,116,116,116
BEGIN DESCRIPTION:
Stream0487 3.0
END DESCRIPTION:
XS GIS Cut Line= 3
      1907782.27     13934779.69      1907934.05     13934758.78
      1908035.09     13934658.73
#Sta/Elev= 30
  4802.1 1661.30  4825.0 1660.63  4835.1 1660.61  4845.2 1659.70  4855.3 1659.49
  4871.8 1659.39  4905.8 1659.92  4926.0 1659.48  4948.8 1659.49  4953.3 1658.91
  4959.5 1658.91  4965.7 1656.07  4979.9 1651.32  4986.9 1650.08  4994.0 1647.45
  4999.1 1647.33  4999.3 1646.83  5002.8 1646.83  5003.1 1647.33  5008.2 1650.27
  5015.2 1650.71  5022.3 1652.92  5029.3 1653.86  5036.4 1656.58  5043.5 1657.84
  5048.1 1658.97  5050.6 1660.10  5071.8 1660.70  5084.6 1660.74  5097.5 1660.97
#Mann=4,-1,0
  4802.1   0.035       0  4999.1   0.035       0  5003.1   0.035       0
  5084.6    0.07       0
Bank Sta=4999.1,5003.1
Exp/Cntr=0.3,0.1

Type RM Length L Ch R = 1,940,405,405,405
BEGIN DESCRIPTION:
Stream0487 2.0
END DESCRIPTION:
XS GIS Cut Line= 3
      1907925.03     13934825.00      1908025.00     13934825.00
      1908075.03     13934825.00
#Sta/Elev= 22
  4904.5 1658.47  4907.0 1658.47  4914.5 1658.58  4924.5 1658.62  4934.5 1658.61
  4944.5 1658.01  4954.5 1655.68  4964.5 1650.80  4972.5 1646.77  4972.7 1646.27
  4976.2 1646.27  4976.5 1646.77  4984.5 1647.03  4994.5 1650.45  5002.0 1651.84
  5007.0 1651.84  5014.5 1653.50  5024.5 1656.50  5034.5 1658.59  5044.5 1658.36
  5052.0 1658.28  5054.5 1658.28
#Mann=3,-1,0
  4904.5   0.035       0  4972.5   0.035       0  4976.5   0.035       0
Bank Sta=4972.5,4976.5
Exp/Cntr=0.3,0.1

Type RM Length L Ch R = 1,535,0,0,0
BEGIN DESCRIPTION:
Stream0487 1.0
END DESCRIPTION:
XS GIS Cut Line= 4
      1907626.77     13935099.71      1908020.93     13935209.89
      1908106.97     13935158.83      1908188.59     13934989.93
#Sta/Elev= 30
  4562.7 1657.25  4604.2 1656.32  4638.4 1656.76  4695.8 1656.08  4785.4 1653.28
  4790.6 1652.63  4819.5 1653.31  4851.6 1650.75  4913.9 1648.90  4937.5 1645.97
  4955.4 1644.88  4965.8 1642.75  4971.5 1639.13  4977.2 1639.13  4984.9 1634.35
  4985.2 1633.85  4988.7 1633.85  4988.9 1634.35  4992.7 1635.13  5000.0 1639.19
  5014.2 1640.78  5023.2 1642.86  5035.6 1644.21  5067.7 1646.13  5070.9 1646.84
  5080.4 1646.93  5087.4 1648.68  5103.0 1650.62  5154.0 1653.71  5259.6 1654.16
#Mann=4,-1,0
  4562.7   0.035       0  4984.9   0.035       0  4988.9   0.035       0
  5067.7    0.07       0
Bank Sta=4984.9,4988.9
Exp/Cntr=0.3,0.1

Chan Stop Cuts=-1