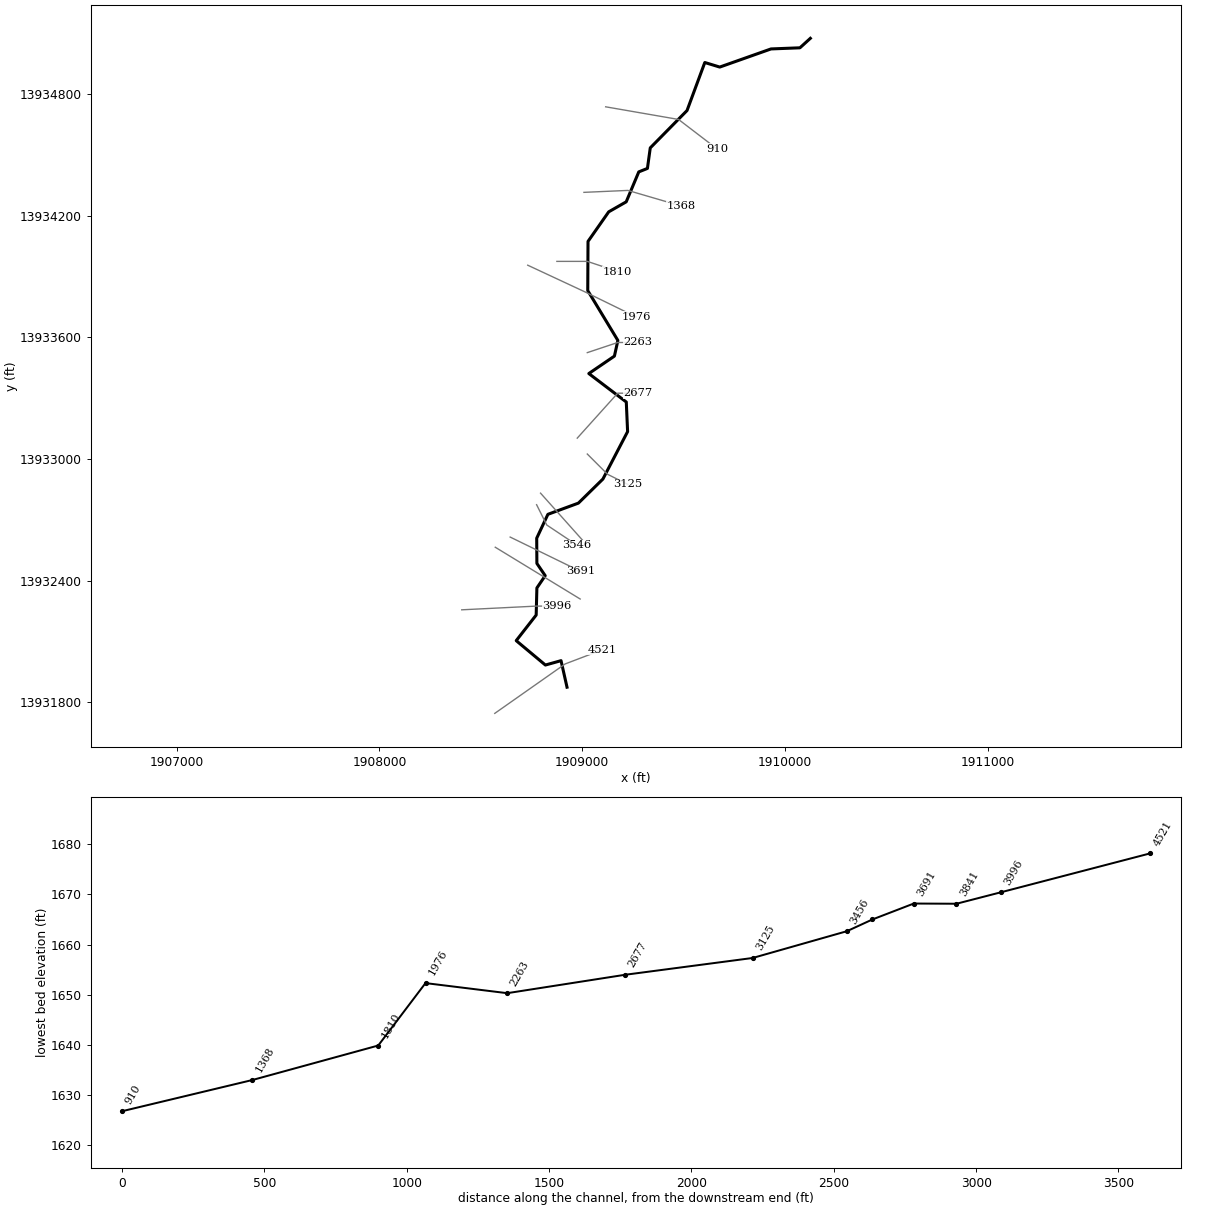
--- Stream0488.prj (project) ---

Proj Title=Stream0488 Base Level Engineering
Current Plan=p01
Default Exp/Contr=0.3,0.1
English Units
Geom File=g01
Flow File=f01
Plan File=p01
Y Axis Title=Elevation
X Axis Title(PF)=Main Channel Distance
X Axis Title(XS)=Station
BEGIN DESCRIPTION:
Stream0488
END DESCRIPTION:
DSS Export Rating Curves= 0
DSS Export Rating Curve Sorted= 0
DSS Export Volume Flow Curves= 0
DXF OffsetX= 0
DXF OffsetY= 0
DXF ScaleX= 1
DXF ScaleY= 10

--- Stream0488.p01 (plan) ---

Plan Title=Multiple Run
Short Identifier=Multiple
Geom File=g01
Flow File=f01
Subcritical Flow
K Sum by GR= 0
Std Step Tol= 0.01
Critical Tol= 0.01
Num of Std Step Trials= 20
Max Error Tol= 0.3
Flow Tol Ratio= 0.001
Split Flow NTrial= 30
Split Flow Tol= 0.02
Split Flow Ratio= 0.02
Log Output Level= 0
Friction Slope Method= 1
Unsteady Friction Slope Method= 2
Unsteady Bridges Friction Slope Method= 1
Parabolic Critical Depth
Global Vel Dist=  1 , 1 , 1
Global Log Level= 0
CheckData=True
Encroach Param= -1, 0, 0, 0
BEGIN DESCRIPTION:
Multiple Run
END DESCRIPTION:

--- Stream0488.f01 (steady flow) ---

Flow Title=Multiple
Program Version=4.10
Number of Profiles= 7
Profile Names=10-year,25-year,50-year,1pct_min,100-year,1pct_plu,500-year
River Rch & RM=Stream0488,Reach-1         ,4521
    1902    3358    4793    3303    6590   13149   12311
Boundary for River Rch & Prof#=Stream0488,Reach-1         , 1
Up Type= 0
Dn Type= 3
Dn Slope=0.01
Boundary for River Rch & Prof#=Stream0488,Reach-1         , 2
Up Type= 0
Dn Type= 3
Dn Slope=0.01
Boundary for River Rch & Prof#=Stream0488,Reach-1         , 3
Up Type= 0
Dn Type= 3
Dn Slope=0.01
Boundary for River Rch & Prof#=Stream0488,Reach-1         , 4
Up Type= 0
Dn Type= 3
Dn Slope=0.01
Boundary for River Rch & Prof#=Stream0488,Reach-1         , 5
Up Type= 0
Dn Type= 3
Dn Slope=0.01
Boundary for River Rch & Prof#=Stream0488,Reach-1         , 6
Up Type= 0
Dn Type= 3
Dn Slope=0.01
Boundary for River Rch & Prof#=Stream0488,Reach-1         , 7
Up Type= 0
Dn Type= 3
Dn Slope=0.01
DSS Import GetInterval= 0
DSS Import GetPeak= 0
DSS Import FillOption= 0

--- Stream0488.g01 (geometry) ---

Geom Title=Existing Conditions
Program Version=4.10

River Reach=Stream0488      ,Reach-1
Reach XY= 30
        1908925.       13931875.      1908895.47      13932005.9
      1908818.35     13931984.32      1908674.42     13932104.58
      1908772.92     13932230.86       1908776.4     13932364.56
      1908817.44       13932425.      1908776.37     13932485.44
      1908775.49     13932609.78      1908830.71     13932727.58
      1908981.17     13932782.86      1909101.99     13932901.53
      1909223.81      13933135.5      1909217.31     13933281.47
      1909032.51     13933421.83      1909158.75     13933507.87
      1909175.85     13933585.05      1909027.24     13933830.93
      1909028.55     13934073.53      1909130.65     13934219.37
      1909216.93     13934268.68       1909278.9     13934416.36
       1909321.5     13934433.48      1909335.53     13934534.75
      1909516.86     13934718.94      1909604.52     13934955.83
      1909678.21     13934933.29      1909930.94     13935022.73
      1910073.63      13935028.3        1910125.       13935075.

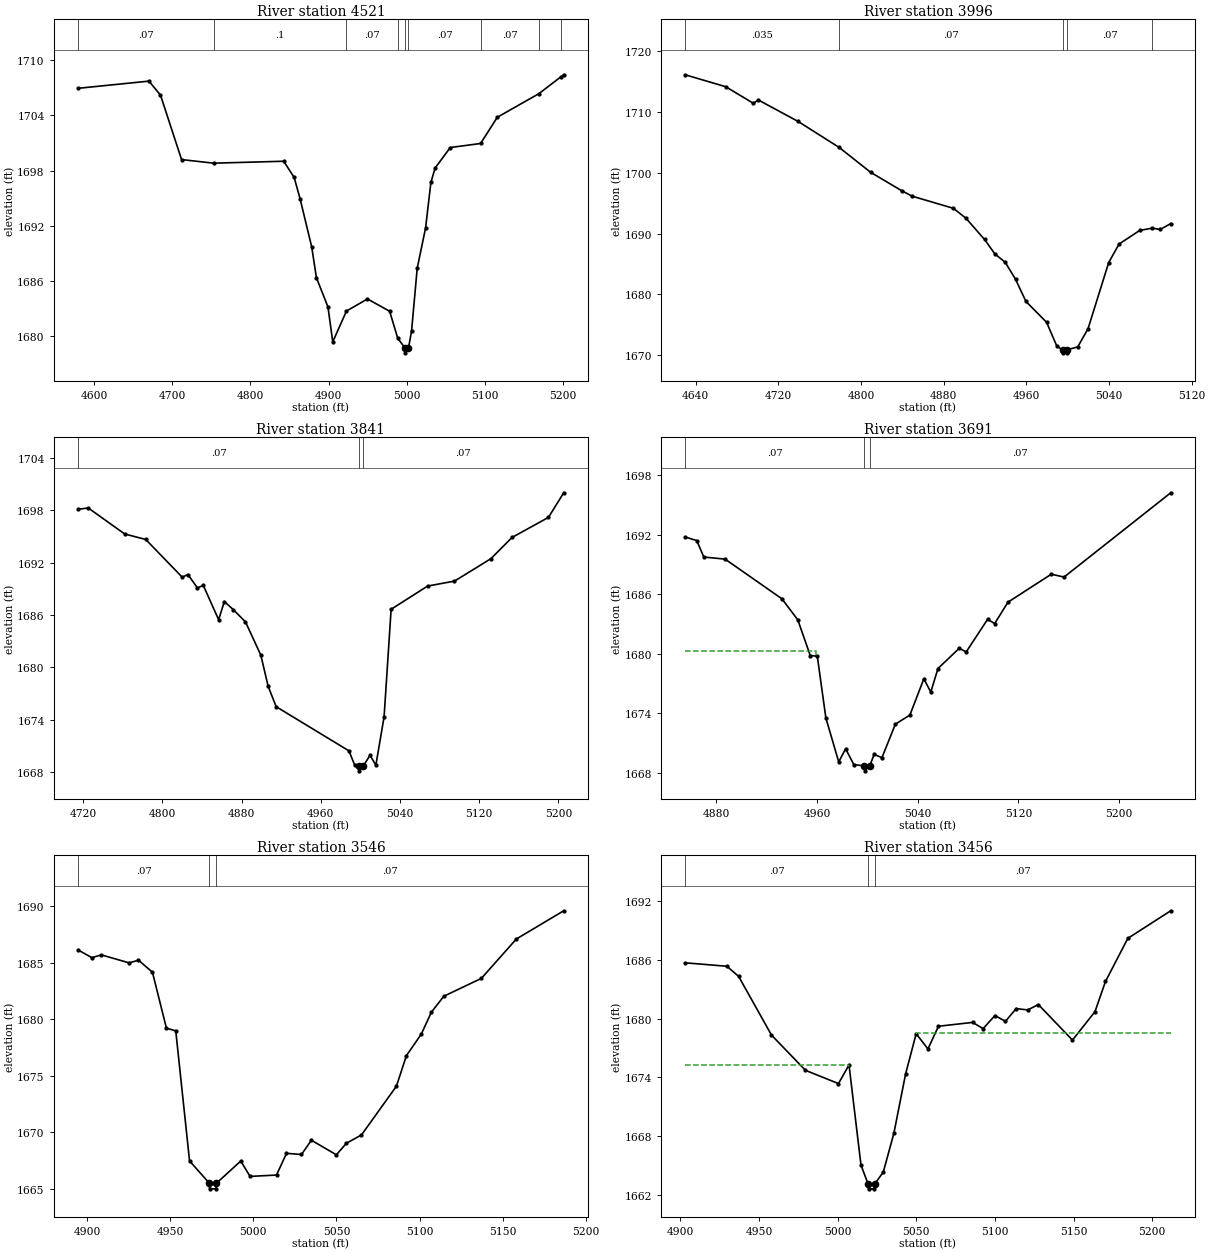
Type RM Length L Ch R = 1 ,4521    ,525,525,525
BEGIN DESCRIPTION:
Stream0488 9.0
END DESCRIPTION:
XS GIS Cut Line= 3
      1908568.71     13931745.93      1908915.88     13931989.78
      1909100.22     13932059.95
#Sta/Elev= 30
  4579.4 1706.94    4670 1707.72  4684.8  1706.2  4711.8 1699.19  4752.9  1698.8
  4842.5 1699.01  4855.9 1697.25  4863.5 1694.92  4878.3 1689.72  4884.4 1686.35
  4899.2 1683.16  4905.3 1679.37  4922.8 1682.72  4949.7 1684.04  4978.1  1682.7
  4988.5 1679.76    4998 1678.68  4998.3 1678.18  5002.2 1678.68  5006.2 1680.59
  5013.4 1687.38  5024.1 1691.75  5030.9  1696.7  5036.3 1698.27  5055.7  1700.5
  5094.5 1700.94  5115.9 1703.79  5169.2 1706.36  5197.8 1708.22  5200.9 1708.41
#Mann= 9 ,-1 , 0
  4579.4     .07       0  4752.9      .1       0  4922.8     .07       0
  4988.5     .07       0    4998     .05       0  5002.2     .07       0
  5094.5     .07       0  5169.2    .035       0  5197.8     .07       0
Bank Sta=4998,5002.2
XS Rating Curve= 0 ,0
Exp/Cntr=0.3,0.1

Type RM Length L Ch R = 1 ,3996    ,155,155,155
BEGIN DESCRIPTION:
Stream0488 8.0
END DESCRIPTION:
XS GIS Cut Line= 3
      1908405.81     13932256.65        1908775.       13932275.
      1908875.05       13932275.
#Sta/Elev= 30
    4630 1716.09  4669.2 1714.13  4695.9 1711.41  4700.9 1711.94  4739.3 1708.42
    4779 1704.15  4809.4 1700.07  4839.5 1697.04  4849.5 1696.15  4889.5 1694.15
  4901.7 1692.51  4919.6 1689.03  4929.6 1686.66  4939.6 1685.28  4949.6 1682.49
  4959.6 1678.86  4979.6 1675.43  4989.6 1671.48    4995 1670.91  4995.3 1670.41
    4999 1670.41  4999.3 1670.91  5009.7 1671.38  5019.7 1674.37  5039.7 1685.25
  5049.7 1688.28  5069.7 1690.52  5081.6 1690.89  5089.7 1690.69  5099.7 1691.65
#Mann= 5 ,-1 , 0
    4630    .035       0    4779     .07       0    4995     .05       0
  4999.3     .07       0  5081.6    .035       0
Bank Sta=4995,4999.3
XS Rating Curve= 0 ,0
Exp/Cntr=0.3,0.1

Type RM Length L Ch R = 1 ,3841    ,150,150,150
BEGIN DESCRIPTION:
Stream0488 7.2
END DESCRIPTION:
XS GIS Cut Line= 2
      1908571.16     13932565.25      1908989.86     13932309.94
#Sta/Elev= 30
  4714.9 1698.11  4725.1 1698.26  4761.9 1695.28  4783.2 1694.65    4820 1690.33
  4825.8 1690.63  4835.4  1689.1  4841.3 1689.39  4856.8 1685.46  4862.6 1687.54
  4871.7  1686.6  4883.9 1685.21  4899.4  1681.4  4906.8 1677.83  4914.9 1675.49
  4988.4 1670.43  4994.3 1668.77  4998.3 1668.64  4998.6 1668.14  5002.6 1668.64
  5009.7 1669.92  5015.6 1668.79  5023.9 1674.33    5031 1686.65  5067.8 1689.31
    5095 1689.88  5131.8 1692.45  5153.1 1694.88  5189.9 1697.18  5205.3    1700
#Mann= 3 ,-1 , 0
  4714.9     .07       0  4998.3     .05       0  5002.6     .07       0
Bank Sta=4998.3,5002.6
XS Rating Curve= 0 ,0
Exp/Cntr=0.3,0.1

Type RM Length L Ch R = 1 ,3691    ,145,145,145
BEGIN DESCRIPTION:
Stream0488 7.1
END DESCRIPTION:
XS GIS Cut Line= 2
      1908644.63     13932615.45      1908991.13     13932446.49
#Sta/Elev= 30
  4855.4 1691.76  4864.6  1691.4  4870.2 1689.74  4887.1 1689.53  4932.2 1685.53
  4944.8 1683.41  4954.7 1679.81  4960.3 1679.74  4967.1 1673.52  4977.3 1669.08
  4982.8  1670.4  4989.3 1668.81  4997.7 1668.68    4998 1668.18    5002 1668.68
  5005.4 1669.85  5011.6  1669.5  5022.3 1672.89  5033.8  1673.8  5044.9 1677.46
  5050.4 1676.12  5056.1  1678.5    5073 1680.54  5078.5 1680.17  5095.5 1683.46
  5101.1 1683.03  5111.7 1685.19  5146.1 1688.01  5156.2 1687.72  5240.9 1696.22
#Mann= 3 ,-1 , 0
  4855.4     .07       0  4997.7     .05       0    5002     .07       0
#XS Ineff= 2 , 0
         4959.34 1680.23
Permanent Ineff=
       F       F
Bank Sta=4997.7,5002
XS Rating Curve= 0 ,0
Exp/Cntr=0.3,0.1

Type RM Length L Ch R = 1 ,3546    ,90,90,90
BEGIN DESCRIPTION:
Stream0488 7.0
END DESCRIPTION:
XS GIS Cut Line= 3
      1908775.02     13932774.96        1908825.       13932675.
      1908974.97     13932575.02
#Sta/Elev= 30
  4894.7 1686.14    4903 1685.46  4908.6 1685.71  4925.4    1685    4931 1685.24
  4939.4 1684.17  4947.8 1679.22  4953.4 1678.99  4961.7 1667.48  4973.6 1665.51
  4973.8 1665.01  4977.6 1665.01  4977.9 1665.51  4992.5 1667.47  4998.1 1666.11
    5014 1666.23    5020 1668.15    5029 1668.05    5035 1669.31    5050 1668.02
    5056 1669.04  5065.1 1669.78  5086.1 1674.09  5092.1 1676.79  5101.1 1678.71
  5107.1 1680.63  5114.6 1682.05  5137.2 1683.63  5158.2 1687.11  5186.7 1689.61
#Mann= 3 ,-1 , 0
  4894.7     .07       0  4973.6     .05       0  4977.9     .07       0
Bank Sta=4973.6,4977.9
XS Rating Curve= 0 ,0
Exp/Cntr=0.3,0.1

Type RM Length L Ch R = 1 ,3456    ,331,331,331
BEGIN DESCRIPTION:
Mapping XS af1e1c5c
END DESCRIPTION:
XS GIS Cut Line= 2
      1908794.42     13932832.06      1909000.07      13932601.7
#Sta/Elev= 30
    4903 1685.68  4929.5 1685.33    4937  1684.3  4957.9 1678.32  4979.5 1674.73
  5000.5 1673.38  5007.2 1675.28  5014.8 1665.09  5019.3 1663.16  5019.6 1662.66
  5023.4 1662.66  5023.6 1663.16    5029 1664.37  5035.7  1668.3  5043.2 1674.37
  5049.9 1678.46  5057.4 1676.91  5064.1 1679.22  5085.8 1679.61  5092.5 1678.98
    5100 1680.31  5106.7 1679.72  5113.5 1681.02  5120.9 1680.88  5127.6 1681.43
  5149.3 1677.81  5163.6  1680.7  5170.3 1683.78  5184.5 1688.17  5211.8 1690.98
#Mann= 3 ,-1 , 0
    4903     .07       0  5019.3     .05       0  5023.6     .07       0
#XS Ineff= 2 , 0
         5007.34  1675.3    5050         1678.51
Permanent Ineff=
       F       F
Bank Sta=5019.3,5023.6
XS Rating Curve= 0 ,0
Exp/Cntr=0.3,0.1

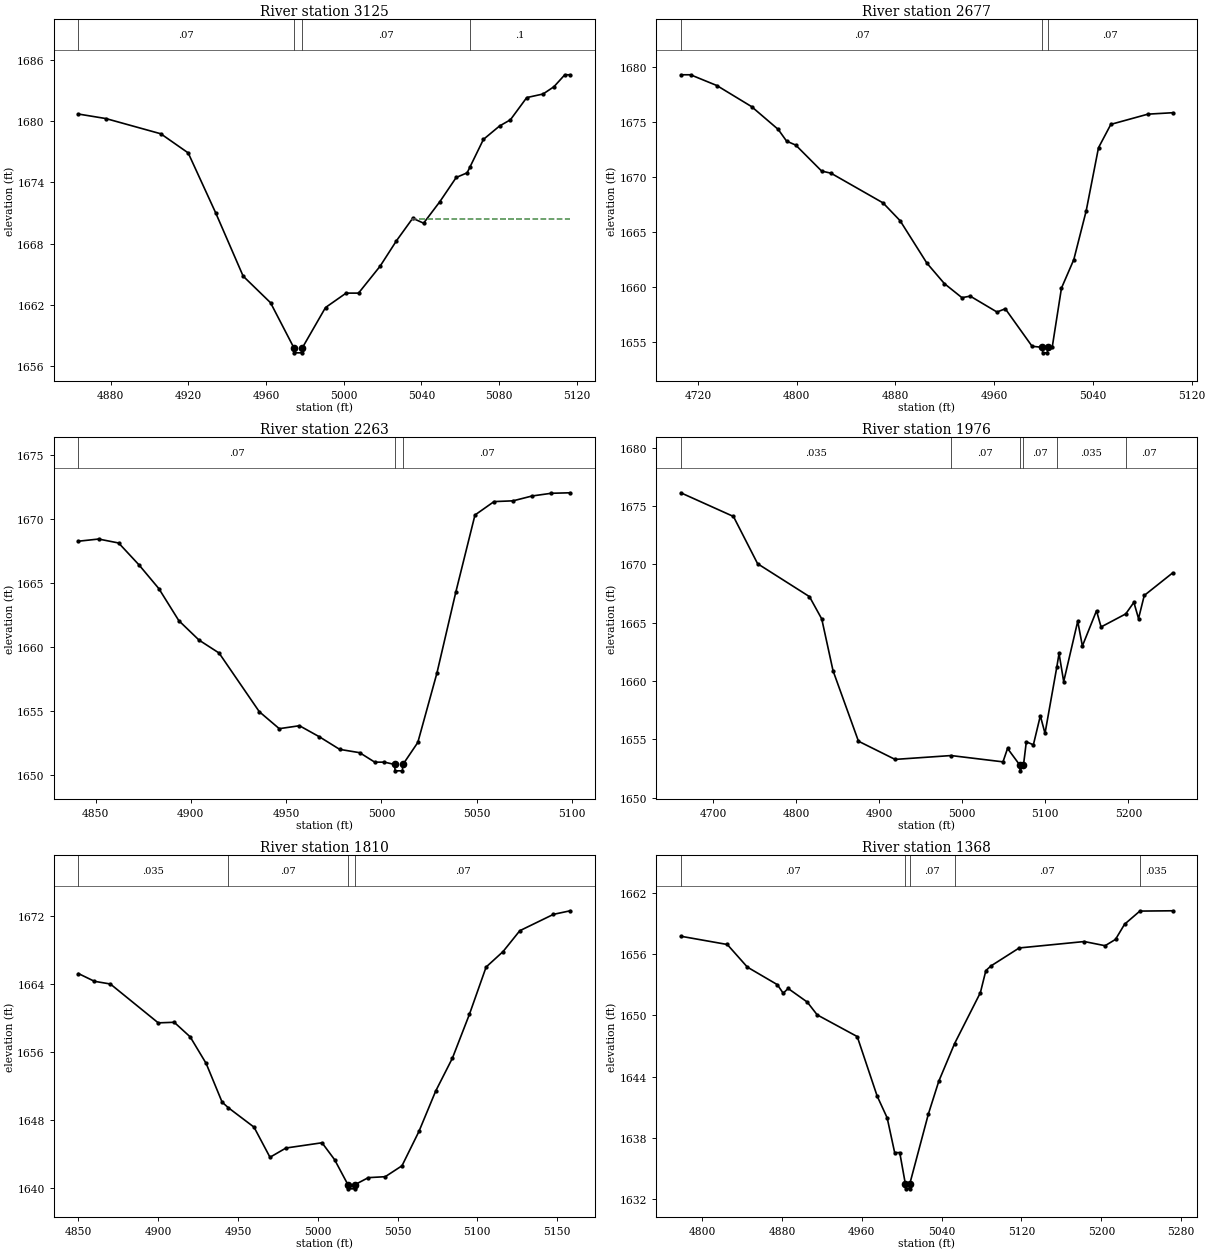
Type RM Length L Ch R = 1 ,3125    ,448,448,448
BEGIN DESCRIPTION:
Stream0488 6.0
END DESCRIPTION:
XS GIS Cut Line= 3
      1909025.04     13933024.96        1909125.       13932925.
      1909225.02     13932874.99
#Sta/Elev= 30
  4863.4 1680.67  4877.5 1680.23  4905.8 1678.74  4919.9 1676.87  4934.1 1670.99
  4948.2 1664.82  4962.3 1662.22  4974.3 1657.82  4974.6 1657.32  4978.4 1657.32
  4978.7 1657.82  4990.6 1661.75  5001.2 1663.16  5007.6 1663.16  5018.7 1665.79
  5027.1 1668.27  5035.5 1670.48  5041.1    1670  5049.5 1672.11  5057.9 1674.47
  5063.5 1674.92    5065  1675.5  5071.9 1678.19  5080.2  1679.5  5085.8 1680.11
  5094.2 1682.28  5102.6 1682.63  5108.2 1683.34  5113.8 1684.51  5116.6 1684.51
#Mann= 4 ,-1 , 0
  4863.4     .07       0  4974.3     .05       0  4978.7     .07       0
    5065      .1       0
#XS Ineff= 2 , 0
                         5034.92         1670.45
Permanent Ineff=
       F       F
Bank Sta=4974.3,4978.7
XS Rating Curve= 0 ,0
Exp/Cntr=0.3,0.1

Type RM Length L Ch R = 1 ,2677    ,414,414,414
BEGIN DESCRIPTION:
Stream0488 5.0
END DESCRIPTION:
XS GIS Cut Line= 3
      1908975.42     13933103.28        1909175.       13933325.
      1909274.99       13933325.
#Sta/Elev= 30
  4706.2 1679.32  4714.1 1679.32  4735.4 1678.34  4763.5 1676.42  4785.1 1674.34
  4791.9 1673.27  4799.3 1672.91  4820.3 1670.54  4827.8 1670.35    4870 1667.64
  4883.8 1666.02  4905.5 1662.15  4919.7 1660.28  4933.9    1659  4940.6 1659.14
  4962.3 1657.69    4969 1657.99  4990.7 1654.57    4999 1654.47  4999.3 1653.97
  5003.1 1653.97  5003.4 1654.47    5007 1654.47  5014.5 1659.87  5024.5 1662.47
  5034.5  1666.9  5044.5 1672.67  5054.5  1674.8  5084.5 1675.73  5104.5 1675.86
#Mann= 3 ,-1 , 0
  4706.2     .07       0    4999     .05       0  5003.4     .07       0
Bank Sta=4999,5003.4
XS Rating Curve= 0 ,0
Exp/Cntr=0.3,0.1

Type RM Length L Ch R = 1 ,2263    ,287,287,287
BEGIN DESCRIPTION:
Stream0488 4.0
END DESCRIPTION:
XS GIS Cut Line= 3
      1909024.97     13933524.99        1909175.       13933575.
      1909274.96       13933575.
#Sta/Elev= 29
    4841 1668.27  4851.6 1668.44  4862.1 1668.13  4872.7 1666.43  4883.2 1664.56
  4893.7 1662.05  4904.3 1660.53  4914.8 1659.52  4935.9 1654.93  4946.4  1653.6
    4957 1653.83  4967.5 1652.96  4978.1 1651.98  4988.6 1651.72  4996.5 1650.98
  5001.6 1650.98  5006.9  1650.8  5007.2  1650.3    5011  1650.3  5011.3  1650.8
  5019.1 1652.52  5029.1 1657.93  5039.1 1664.32  5049.1 1670.32  5059.1 1671.37
  5069.1 1671.43  5079.1 1671.81  5089.1 1672.02  5099.1 1672.06
#Mann= 3 ,-1 , 0
    4841     .07       0  5006.9     .05       0  5011.3     .07       0
Bank Sta=5006.9,5011.3
XS Rating Curve= 0 ,0
Exp/Cntr=0.3,0.1

Type RM Length L Ch R = 1 ,1976    ,166,166,166
BEGIN DESCRIPTION:
Mapping XS 4a3ac447
END DESCRIPTION:
XS GIS Cut Line= 3
      1908731.19     13933956.21      1909015.36     13933823.66
      1909265.62     13933701.37
#Sta/Elev= 30
  4661.1 1676.14  4724.5 1674.11  4753.6 1670.06    4816 1667.24  4830.8 1665.33
  4844.4 1660.89    4875 1654.85  4919.1 1653.29  4986.5 1653.62    5049 1653.08
  5054.5 1654.23  5069.2 1652.81  5069.6 1652.31  5073.7 1652.81  5077.1  1654.8
  5085.6 1654.54    5094 1657.03  5099.6 1655.52  5113.9 1661.24  5116.5 1662.37
  5122.1 1659.96    5139 1665.13  5144.6 1663.01  5161.6 1666.03  5167.1 1664.64
  5196.8 1665.76  5206.6 1666.75  5212.2 1665.36  5219.1 1667.34  5253.2 1669.27
#Mann= 6 ,-1 , 0
  4661.1    .035       0  4986.5     .07       0  5069.2     .05       0
  5073.7     .07       0  5113.9    .035       0  5196.8     .07       0
Bank Sta=5069.2,5073.7
XS Rating Curve= 0 ,0
Exp/Cntr=0.3,0.1

Type RM Length L Ch R = 1 ,1810    ,442,442,442
BEGIN DESCRIPTION:
Stream0488 3.0
END DESCRIPTION:
XS GIS Cut Line= 3
      1908874.99       13933975.        1909025.       13933975.
      1909174.98     13933925.01
#Sta/Elev= 30
  4850.1 1665.23  4860.1 1664.32  4870.1    1664  4900.1 1659.42  4910.1 1659.49
  4920.1 1657.77  4930.1 1654.64  4940.1 1650.08    4944 1649.42  4960.1 1647.13
  4970.1 1643.58  4980.1 1644.67  5002.7 1645.29  5010.6 1643.29  5018.9 1640.36
  5019.2 1639.86  5023.1 1639.86  5023.4 1640.36  5031.7 1641.18  5042.3 1641.29
  5052.8 1642.58  5063.4 1646.62  5073.9 1651.38  5084.4 1655.27    5095 1660.41
  5105.5    1666  5116.1 1667.82  5126.6 1670.28  5147.7 1672.21  5158.2 1672.63
#Mann= 4 ,-1 , 0
  4850.1    .035       0    4944     .07       0  5018.9     .05       0
  5023.4     .07       0
Bank Sta=5018.9,5023.4
XS Rating Curve= 0 ,0
Exp/Cntr=0.3,0.1

Type RM Length L Ch R = 1 ,1368    ,458,458,458
BEGIN DESCRIPTION:
Stream0488 2.0
END DESCRIPTION:
XS GIS Cut Line= 3
       1909008.4     13934315.43        1909225.       13934325.
      1909489.91     13934247.59
#Sta/Elev= 30
  4778.6 1657.78  4825.2 1656.97  4845.3 1654.75  4875.3 1653.03  4881.2 1652.19
  4886.2 1652.65  4905.3 1651.32  4915.3 1650.06  4955.4 1647.93  4975.4 1642.08
  4985.4 1639.95  4992.9 1636.54    4998 1636.54  5003.6 1633.48  5003.9 1632.98
  5007.8 1632.98  5008.1 1633.48  5026.7 1640.33  5037.1 1643.54  5052.9 1647.23
  5078.8 1652.24  5084.3 1654.41  5089.5 1654.87  5117.7 1656.63  5182.9 1657.26
  5203.8 1656.85  5214.2 1657.47  5223.3 1658.96  5238.6 1660.25  5271.4 1660.28
#Mann= 5 ,-1 , 0
  4778.6     .07       0  5003.6     .05       0  5008.1     .07       0
  5052.9     .07       0  5238.6    .035       0
Bank Sta=5003.6,5008.1
XS Rating Curve= 0 ,0
Exp/Cntr=0.3,0.1

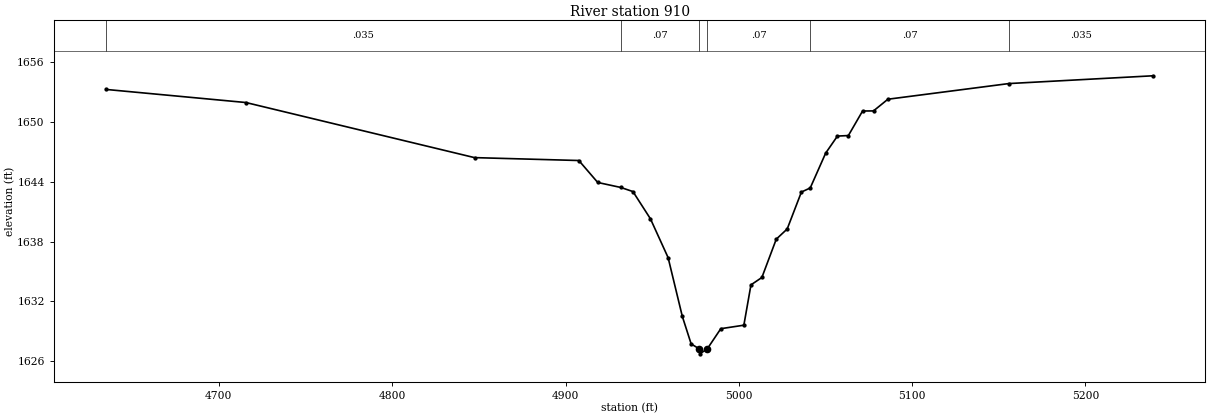
Type RM Length L Ch R = 1 ,910     ,0,0,0
BEGIN DESCRIPTION:
Stream0488 1.0
END DESCRIPTION:
XS GIS Cut Line= 3
      1909115.57     13934737.31        1909475.       13934675.
      1909664.99     13934529.65
#Sta/Elev= 30
    4635 1653.24  4715.6 1651.93  4847.5 1646.41  4907.7 1646.12  4918.6 1643.92
  4931.9 1643.42  4938.9 1643.01    4949 1640.28  4959.2 1636.39  4967.4  1630.5
  4972.5 1627.74  4977.2 1627.25  4977.5 1626.75  4981.8 1627.25  4989.6 1629.27
  5002.9 1629.62    5007 1633.66  5013.3  1634.4  5021.6 1638.24  5027.9 1639.26
  5036.1 1642.96  5041.2 1643.37  5050.1 1646.86  5056.9 1648.57  5063.2 1648.62
  5071.4 1651.08  5077.7 1651.09    5086 1652.26  5155.8 1653.83    5239 1654.61
#Mann= 6 ,-1 , 0
    4635    .035       0  4931.9     .07       0  4977.2     .05       0
  4981.8     .07       0  5041.2     .07       0  5155.8    .035       0
Bank Sta=4977.2,4981.8
XS Rating Curve= 0 ,0
Exp/Cntr=0.3,0.1

Chan Stop Cuts=-1
Use User Specified Reach Order=0
Composite Channel Slope=5