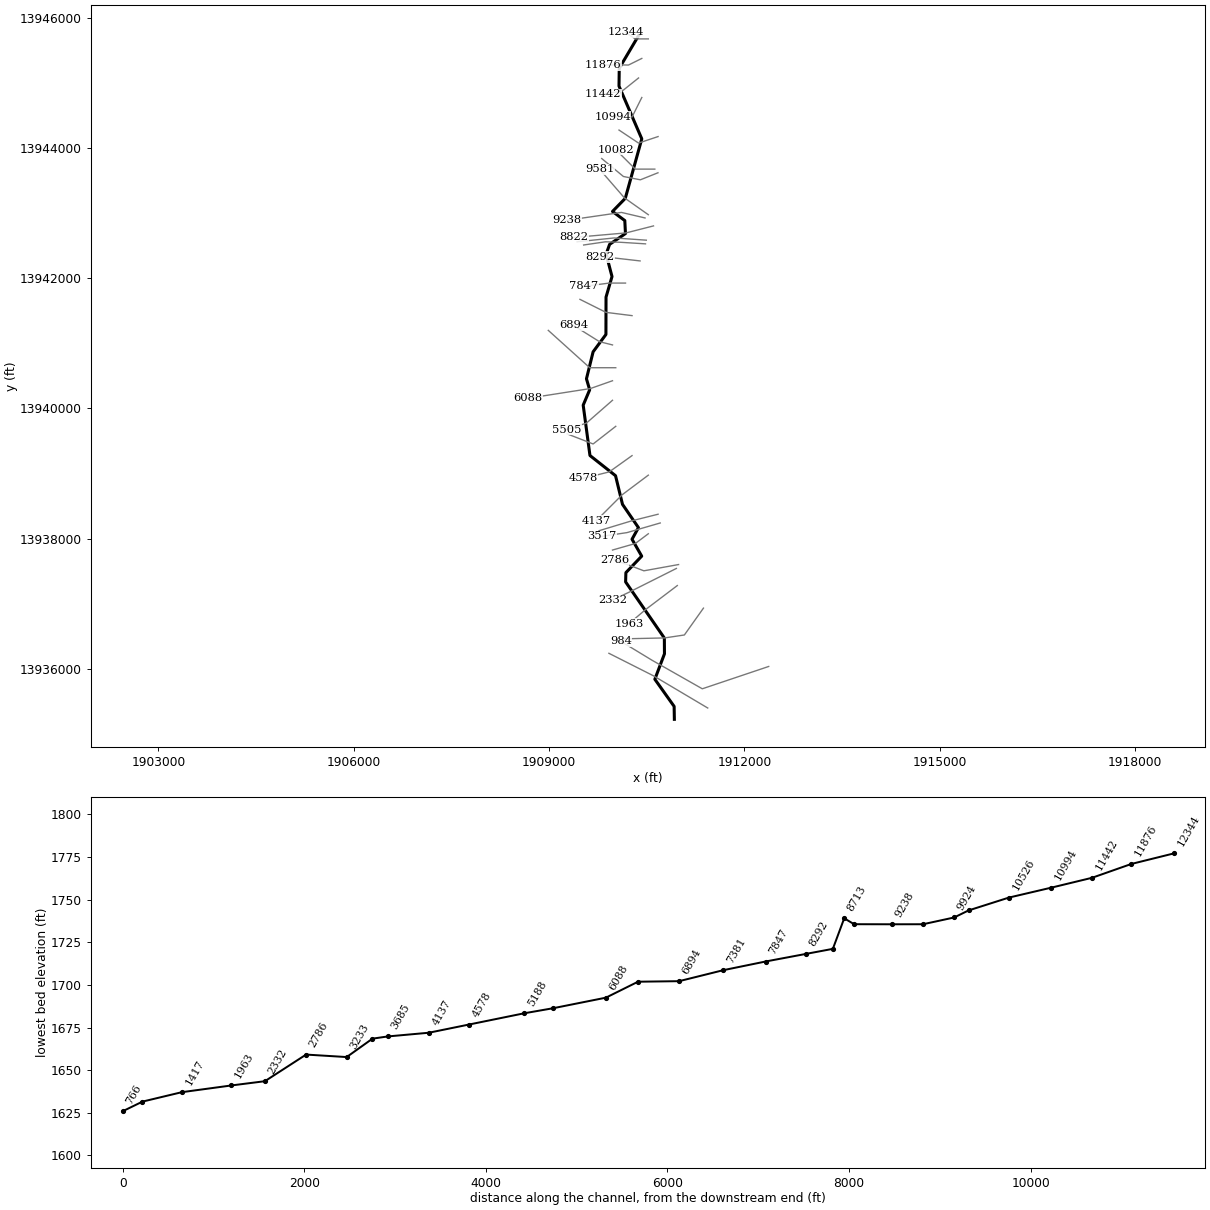
--- Stream0489.prj (project) ---

Proj Title=Stream0489 Base Level Engineering
Current Plan=p01
Default Exp/Contr=0.3,0.1
English Units
Geom File=g01
Flow File=f01
Plan File=p01
BEGIN DESCRIPTION:
Stream0489
END DESCRIPTION:

--- Stream0489.p01 (plan) ---

Plan Title=Multiple Run
Short Identifier=Multiple
Geom File=g01
Flow File=f01
Subcritical Flow
K Sum by GR= 0
Std Step Tol= 0.01
Critical Tol= 0.01
Num of Std Step Trials= 20
Max Error Tol= 0.3
Flow Tol Ratio= 0.001
Split Flow NTrial= 30
Split Flow Tol= 0.02
Split Flow Ratio= 0.02
Log Output Level= 0
Friction Slope Method= 1
Unsteady Friction Slope Method= 2
Unsteady Bridges Friction Slope Method= 1
Parabolic Critical Depth
Global Vel Dist=  1 , 1 , 1
Global Log Level= 0
CheckData=True
Encroach Param= -1, 0, 0, 0
BEGIN DESCRIPTION:
Multiple Run
END DESCRIPTION:

--- Stream0489.f01 (steady flow) ---

Flow Title=Multiple
Number of Profiles=7
Profile Names=10-year,25-year,50-year,1pct_min,100-year,1pct_plu,500-year
River Rch & RM= Stream0489,Reach-1,12344
     931    1573    2180    1463    2920    5825    5163
River Rch & RM= Stream0489,Reach-1,10526
    1395    2416    3405    2320    4629    9236    8445
River Rch & RM= Stream0489,Reach-1,9581
    1775    3119    4437    3049    6083   12137   11293
River Rch & RM= Stream0489,Reach-1,9238
    2435    4328    6202    4285    8549   17058   16059
River Rch & RM= Stream0489,Reach-1,766
    3048    5481    7915    5507   10987   21922   20933
Boundary for River Rch & Prof#=Stream0489,Reach-1,1
Up Type=0
Dn Type=3
Dn Slope=0.005
Boundary for River Rch & Prof#=Stream0489,Reach-1,2
Up Type=0
Dn Type=3
Dn Slope=0.005
Boundary for River Rch & Prof#=Stream0489,Reach-1,3
Up Type=0
Dn Type=3
Dn Slope=0.005
Boundary for River Rch & Prof#=Stream0489,Reach-1,4
Up Type=0
Dn Type=3
Dn Slope=0.005
Boundary for River Rch & Prof#=Stream0489,Reach-1,5
Up Type=0
Dn Type=3
Dn Slope=0.005
Boundary for River Rch & Prof#=Stream0489,Reach-1,6
Up Type=0
Dn Type=3
Dn Slope=0.005
Boundary for River Rch & Prof#=Stream0489,Reach-1,7
Up Type=0
Dn Type=3
Dn Slope=0.005

--- Stream0489.g01 (geometry) ---

Geom Title=Existing Conditions

River Reach=Stream0489,Reach-1
Reach XY= 30
      1910375.00     13945725.00      1910078.55     13945223.53
      1910074.79     13944949.91      1910424.71     13944140.12
      1910171.40     13943226.49      1909975.00     13943025.00
      1910163.77     13942885.02      1910174.06     13942685.48
      1909930.25     13942519.56      1909877.25     13942369.06
      1909967.44     13942025.00      1909875.52     13941709.78
      1909873.95     13941135.44      1909677.07     13940869.14
      1909574.90     13940454.90      1909624.39     13940285.62
      1909524.77     13940049.93      1909628.74     13939276.52
      1910021.49     13938966.52      1910128.55     13938526.47
      1910373.38     13938168.96      1910275.00     13937990.71
      1910423.42     13937731.05      1910180.45     13937477.45
      1910176.20     13937335.51      1910771.25     13936473.45
      1910772.94     13936230.86      1910625.36     13935840.16
      1910921.46     13935423.53      1910925.00     13935225.00

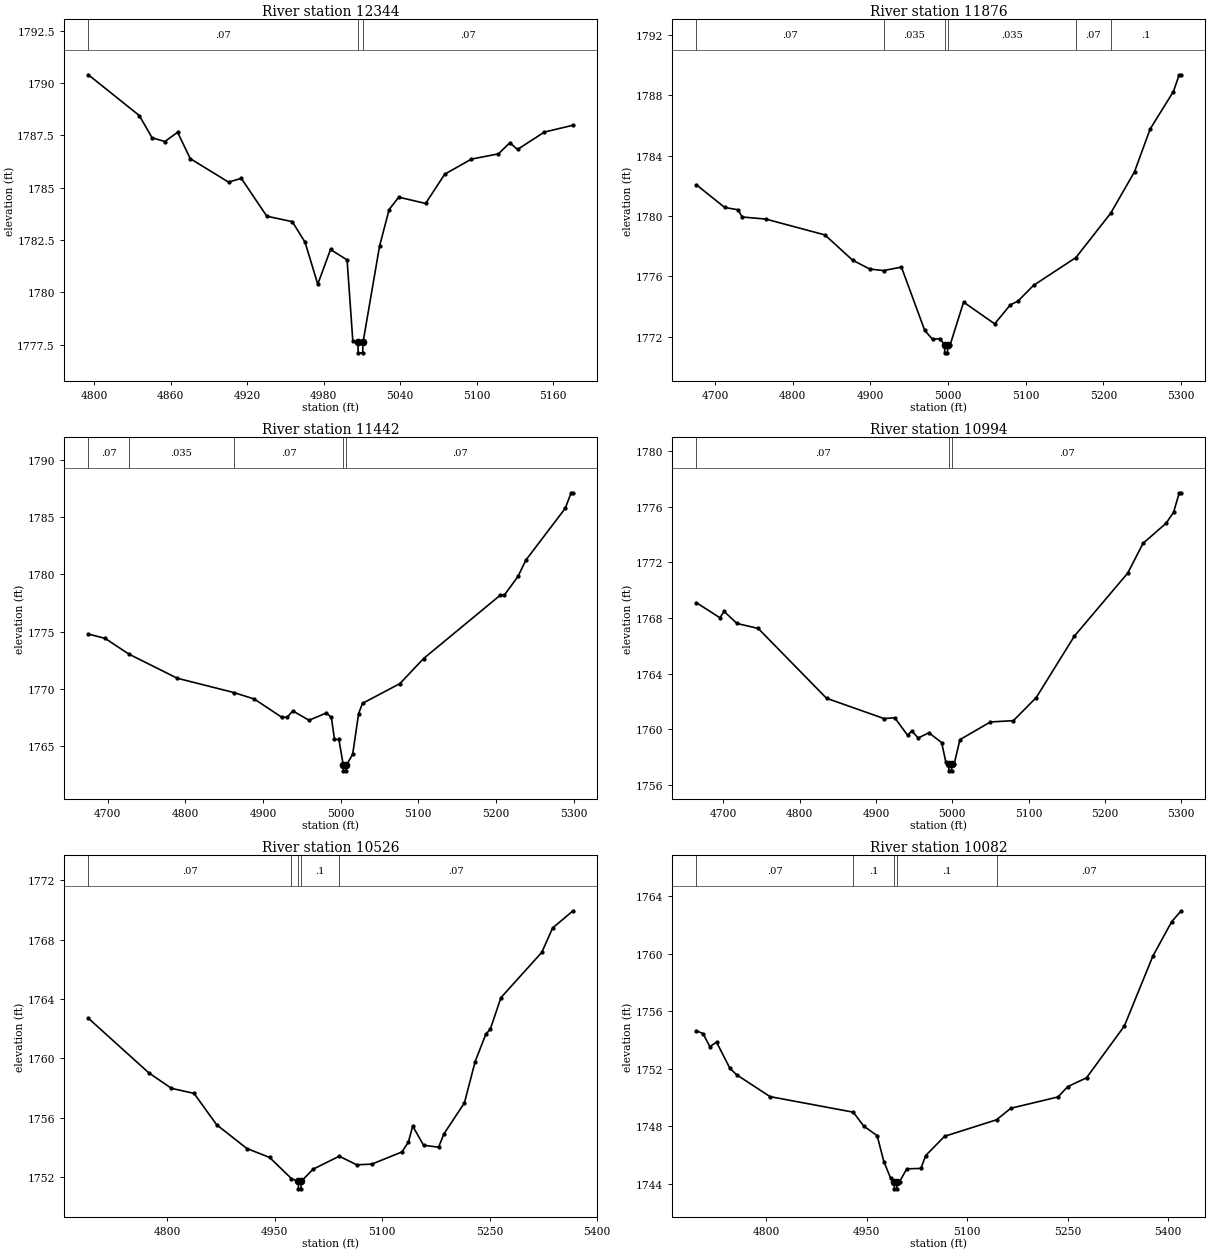
Type RM Length L Ch R = 1,12344,468,468,468
BEGIN DESCRIPTION:
Stream0489 26.0
END DESCRIPTION:
XS GIS Cut Line= 3
      1910524.98     13945675.00      1910325.00     13945675.00
      1910174.96     13945775.03
#Sta/Elev= 30
  4795.4 1790.40  4835.4 1788.45  4845.4 1787.39  4855.4 1787.21  4865.4 1787.65
  4875.4 1786.39  4905.4 1785.27  4915.4 1785.45  4935.4 1783.64  4955.4 1783.38
  4965.4 1782.40  4975.4 1780.39  4985.4 1782.05  4998.4 1781.55  5002.9 1777.68
  5006.9 1777.61  5007.1 1777.11  5010.6 1777.11  5010.9 1777.61  5023.9 1782.22
  5031.4 1783.96  5038.9 1784.55  5060.0 1784.25  5075.0 1785.65  5096.0 1786.37
  5117.1 1786.62  5126.1 1787.15  5132.1 1786.83  5153.1 1787.66  5175.7 1787.99
#Mann=3,-1,0
  4795.4    0.07       0  5006.9    0.05       0  5010.9    0.07       0
Bank Sta=5006.9,5010.9
Exp/Cntr=0.3,0.1

Type RM Length L Ch R = 1,11876,434,434,434
BEGIN DESCRIPTION:
Stream0489 25.0
END DESCRIPTION:
XS GIS Cut Line= 4
      1910425.00     13945375.00      1910220.10     13945273.53
      1910125.00     13945275.00      1909824.96     13945275.00
#Sta/Elev= 30
  4676.2 1782.06  4712.6 1780.56  4729.5 1780.41  4735.1 1779.93  4765.5 1779.79
  4841.6 1778.74  4877.1 1777.07  4899.3 1776.48  4917.1 1776.38  4940.0 1776.61
  4970.0 1772.41  4980.0 1771.83  4990.0 1771.87  4995.5 1771.43  4995.7 1770.93
  4999.2 1770.93  4999.5 1771.43  5002.5 1771.43  5020.0 1774.29  5060.0 1772.85
  5080.0 1774.10  5090.0 1774.36  5110.0 1775.40  5164.5 1777.24  5209.3 1780.18
  5240.0 1782.93  5260.0 1785.75  5290.0 1788.24  5297.5 1789.35  5300.0 1789.35
#Mann=6,-1,0
  4676.2    0.07       0  4917.1   0.035       0  4995.5   0.035       0
  4999.5   0.035       0  5164.5    0.07       0  5209.3     0.1       0
Bank Sta=4995.5,4999.5
Exp/Cntr=0.3,0.1

Type RM Length L Ch R = 1,11442,448,448,448
BEGIN DESCRIPTION:
Stream0489 24.0
END DESCRIPTION:
XS GIS Cut Line= 3
      1910375.01     13945075.01      1910125.00     13944875.00
      1909825.01     13944825.00
#Sta/Elev= 30
  4675.1 1774.78  4696.7 1774.40  4727.1 1773.03  4789.6 1770.91  4862.3 1769.66
  4888.8 1769.09  4924.0 1767.50  4931.2 1767.49  4938.4 1768.05  4959.3 1767.23
  4981.7 1767.87  4988.1 1767.48  4992.1 1765.55  4997.8 1765.55  5003.4 1763.30
  5003.7 1762.80  5007.2 1762.80  5007.4 1763.30  5015.5 1764.24  5023.2 1767.82
  5028.2 1768.71  5076.4 1770.44  5106.8 1772.63  5205.6 1778.18  5210.7 1778.17
  5228.4 1779.82  5238.6 1781.25  5289.3 1785.79  5296.9 1787.15  5299.4 1787.15
#Mann=5,-1,0
  4675.1    0.07       0  4727.1   0.035       0  4862.3    0.07       0
  5003.4    0.05       0  5007.4    0.07       0
Bank Sta=5003.4,5007.4
Exp/Cntr=0.3,0.1

Type RM Length L Ch R = 1,10994,468,468,468
BEGIN DESCRIPTION:
Stream0489 23.0
END DESCRIPTION:
XS GIS Cut Line= 3
      1910424.99     13944774.99      1910275.00     13944475.00
      1909975.00     13944475.00
#Sta/Elev= 30
  4664.6 1769.10  4695.3 1768.02  4700.9 1768.47  4717.7 1767.61  4745.6 1767.25
  4835.1 1762.24  4910.6 1760.78  4924.5 1760.84  4941.3 1759.59  4946.9 1759.89
  4955.3 1759.39  4969.3 1759.76  4986.0 1759.06  4991.6 1757.64  4995.2 1757.53
  4995.5 1757.03  4999.0 1757.03  4999.2 1757.53  5002.5 1757.53  5010.0 1759.27
  5050.0 1760.54  5080.0 1760.63  5110.0 1762.29  5160.0 1766.70  5230.0 1771.23
  5250.0 1773.36  5280.0 1774.79  5290.0 1775.58  5297.5 1776.99  5300.0 1776.99
#Mann=3,-1,0
  4664.6    0.07       0  4995.2    0.05       0  4999.2    0.07       0
Bank Sta=4995.2,4999.2
Exp/Cntr=0.3,0.1

Type RM Length L Ch R = 1,10526,444,444,444
BEGIN DESCRIPTION:
Stream0489 22.0
END DESCRIPTION:
XS GIS Cut Line= 3
      1910675.00     13944175.00      1910375.00     13944075.00
      1910074.99     13944275.01
#Sta/Elev= 30
  4689.6 1762.70  4773.9 1759.02  4805.6 1757.97  4837.2 1757.63  4868.8 1755.51
  4911.0 1753.91  4942.6 1753.31  4973.2 1751.88  4982.7 1751.69  4983.0 1751.19
  4986.5 1751.19  4986.7 1751.69  5003.2 1752.51  5039.9 1753.39  5064.4 1752.81
  5085.5 1752.86  5127.5 1753.68  5136.5 1754.35  5142.5 1755.43  5157.6 1754.13
  5178.6 1754.00  5186.1 1754.90  5214.7 1756.99  5229.7 1759.78  5244.7 1761.64
  5250.7 1761.95  5265.7 1764.09  5322.8 1767.15  5337.8 1768.79  5366.4 1769.95
#Mann=5,-1,0
  4689.6    0.07       0  4973.2     0.1       0  4982.7    0.05       0
  4986.7     0.1       0  5039.9    0.07       0
Bank Sta=4982.7,4986.7
Exp/Cntr=0.3,0.1

Type RM Length L Ch R = 1,10082,158,158,158
BEGIN DESCRIPTION:
Stream0489 21.0
END DESCRIPTION:
XS GIS Cut Line= 3
      1910625.03     13943675.00      1910325.00     13943675.00
      1910025.00     13943975.00
#Sta/Elev= 30
  4695.5 1754.65  4705.5 1754.45  4715.5 1753.54  4725.5 1753.86  4745.5 1752.04
  4755.5 1751.59  4805.5 1750.07  4929.8 1748.99  4945.5 1748.02  4965.5 1747.36
  4975.5 1745.56  4985.5 1744.42  4991.0 1744.16  4991.3 1743.66  4994.8 1743.66
  4995.0 1744.16  4999.1 1744.16  5009.7 1745.05  5030.9 1745.08  5038.0 1745.97
  5066.2 1747.31  5143.9 1748.46  5165.2 1749.26  5235.9 1750.05  5250.1 1750.76
  5278.4 1751.38  5334.9 1754.98  5377.4 1759.83  5405.7 1762.24  5419.8 1762.99
#Mann=5,-1,0
  4695.5    0.07       0  4929.8     0.1       0  4991.0    0.05       0
  4995.0     0.1       0  5143.9    0.07       0
Bank Sta=4991,4995
Exp/Cntr=0.3,0.1

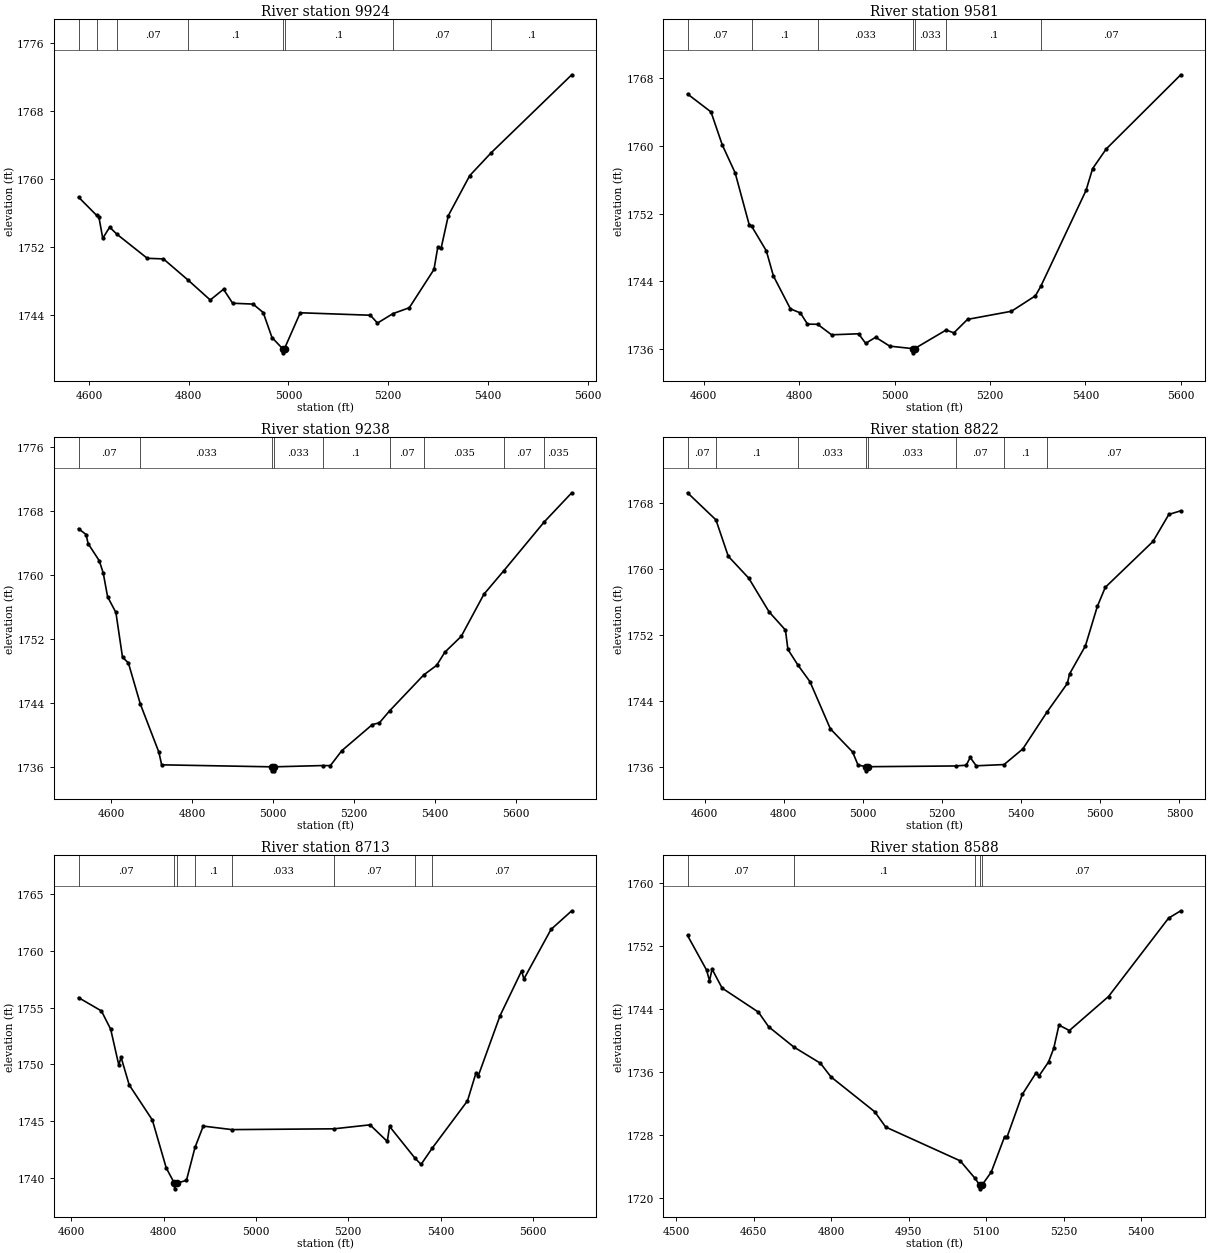
Type RM Length L Ch R = 1,9924,343,343,343
BEGIN DESCRIPTION:
Stream0489 20.1
END DESCRIPTION:
XS GIS Cut Line= 4
      1910673.00     13943618.93      1910403.07     13943510.97
      1910142.72     13943561.71      1909809.19     13943837.73
#Sta/Elev= 30
  4579.0 1757.84  4615.3 1755.70  4619.9 1755.49  4627.6 1753.00  4641.5 1754.31
  4655.6 1753.50  4716.9 1750.65  4749.2 1750.58  4799.1 1748.07  4843.1 1745.75
  4869.7 1747.01  4888.1 1745.37  4928.9 1745.27  4949.3 1744.28  4966.9 1741.34
  4988.0 1740.04  4988.3 1739.54  4992.0 1740.04  5023.6 1744.25  5164.1 1743.96
  5178.4 1743.04  5209.5 1744.15  5242.2 1744.84  5291.7 1749.34  5299.5 1752.01
  5306.0 1751.83  5320.4 1755.66  5363.4 1760.37  5406.3 1763.05  5567.9 1772.22
#Mann=8,-1,0
  4579.0    0.07       0  4615.3     0.1       0  4655.6    0.07       0
  4799.1     0.1       0  4988.0    0.05       0  4992.0     0.1       0
  5209.5    0.07       0  5406.3     0.1       0
Bank Sta=4988,4992
Exp/Cntr=0.3,0.1

Type RM Length L Ch R = 1,9581,343,343,343
BEGIN DESCRIPTION:
Stream0489 20.0
END DESCRIPTION:
XS GIS Cut Line= 3
      1910525.02     13942974.99      1910157.35     13943234.06
      1909775.00     13943675.00
#Sta/Elev= 30
  4566.3 1766.13  4615.5 1764.01  4639.0 1760.13  4666.1 1756.81  4695.6 1750.67
  4700.5 1750.53  4731.4 1747.61  4746.2 1744.65  4781.9 1740.76  4802.8 1740.28
  4817.6 1738.96  4838.9 1738.94  4868.1 1737.70  4924.7 1737.82  4939.5 1736.69
  4960.4 1737.41  4990.0 1736.36  5037.7 1736.07  5038.0 1735.57  5042.1 1736.07
  5108.0 1738.26  5124.4 1737.93  5152.9 1739.52  5245.0 1740.48  5295.3 1742.31
  5306.5 1743.43  5401.2 1754.74  5415.0 1757.32  5443.5 1759.64  5599.7 1768.40
#Mann=7,-1,0
  4566.3    0.07       0  4700.5     0.1       0  4838.9   0.033       0
  5037.7   0.033       0  5042.1   0.033       0  5108.0     0.1       0
  5306.5    0.07       0
Bank Sta=5037.7,5042.1
Exp/Cntr=0.3,0.1

Type RM Length L Ch R = 1,9238,416,416,416
BEGIN DESCRIPTION:
Stream0489 19.0
END DESCRIPTION:
XS GIS Cut Line= 3
      1910474.96     13942925.01      1910111.64     13943010.15
      1909274.73     13942888.97
#Sta/Elev= 30
  4518.7 1765.77  4537.3 1765.04  4542.5 1763.90  4570.0 1761.77  4579.8 1760.23
  4590.6 1757.27  4611.1 1755.31  4627.4 1749.73  4641.9 1749.02  4671.5 1743.88
  4717.4 1737.86  4724.1 1736.30  4997.3 1736.05  4997.6 1735.55  5001.7 1735.55
  5002.0 1736.05  5122.0 1736.21  5141.1 1736.20  5169.2 1738.06  5244.5 1741.31
  5262.3 1741.55  5287.5 1743.04  5371.8 1747.52  5403.8 1748.72  5424.0 1750.36
  5464.4 1752.33  5520.5 1757.59  5570.1 1760.55  5669.3 1766.60  5737.5 1770.25
#Mann=9,-1,0
  4518.7    0.07       0  4671.5   0.033       0  4997.3   0.033       0
  5002.0   0.033       0  5122.0     0.1       0  5287.5    0.07       0
  5371.8   0.035       0  5570.1    0.07       0  5669.3   0.035       0
Bank Sta=4997.3,5002
Exp/Cntr=0.3,0.1

Type RM Length L Ch R = 1,8822,109,109,109
BEGIN DESCRIPTION:
Stream0489 18.0
END DESCRIPTION:
XS GIS Cut Line= 3
      1910604.70     13942802.99      1910184.76     13942695.80
      1909375.05     13942625.00
#Sta/Elev= 30
  4557.0 1769.23  4628.8 1765.95  4659.9 1761.55  4711.5 1758.91  4763.1 1754.82
  4804.4 1752.62  4810.6 1750.28  4836.4 1748.35  4866.3 1746.38  4917.9 1740.67
  4974.0 1737.88  4987.7 1736.30  5007.8 1736.09  5008.2 1735.59  5012.6 1736.09
  5234.6 1736.18  5261.2 1736.27  5271.2 1737.21  5286.4 1736.20  5356.8 1736.35
  5404.1 1738.24  5465.5 1742.72  5516.7 1746.17  5522.2 1747.31  5562.3 1750.71
  5592.4 1755.48  5612.5 1757.79  5733.0 1763.34  5773.1 1766.61  5803.2 1767.05
#Mann=8,-1,0
  4557.0    0.07       0  4628.8     0.1       0  4836.4   0.033       0
  5007.8   0.033       0  5012.6   0.033       0  5234.6    0.07       0
  5356.8     0.1       0  5465.5    0.07       0
Bank Sta=5007.8,5012.6
Exp/Cntr=0.3,0.1

Type RM Length L Ch R = 1,8713,125,125,125
BEGIN DESCRIPTION:
Stream0489 17.2
END DESCRIPTION:
XS GIS Cut Line= 4
      1910494.52     13942583.72      1910206.16     13942603.97
      1910000.18     13942618.12      1909430.38     13942558.95
#Sta/Elev= 30
  4615.7 1755.88  4665.3 1754.71  4685.4 1753.10  4702.9 1749.96  4707.9 1750.63
  4725.5 1748.20  4775.6 1745.12  4805.7 1740.90  4823.3 1739.56  4823.7 1739.06
  4828.1 1739.56  4849.5 1739.80  4868.0 1742.70  4885.9 1744.58  4948.0 1744.27
  5169.1 1744.34  5247.1 1744.69  5284.5 1743.23  5289.5 1744.55  5344.3 1741.77
  5357.7 1741.21  5382.1 1742.65  5458.3 1746.80  5476.8 1749.27  5481.8 1749.02
  5528.7 1754.28  5575.5 1758.23  5580.5 1757.52  5639.2 1761.88  5684.1 1763.52
#Mann=8,-1,0
  4615.7    0.07       0  4823.3   0.033       0  4828.1    0.07       0
  4868.0     0.1       0  4948.0   0.033       0  5169.1    0.07       0
  5344.3     0.1       0  5382.1    0.07       0
Bank Sta=4823.3,4828.1
Exp/Cntr=0.3,0.1

Type RM Length L Ch R = 1,8588,296,296,296
BEGIN DESCRIPTION:
Stream0489 17.1
END DESCRIPTION:
XS GIS Cut Line= 4
      1910481.81     13942527.30      1910098.05     13942551.41
      1909868.26     13942558.95      1909531.76     13942509.80
#Sta/Elev= 30
  4522.0 1753.32  4558.9 1748.92  4564.5 1747.57  4569.5 1749.05  4588.9 1746.64
  4659.1 1743.59  4679.1 1741.72  4727.6 1739.16  4779.3 1737.09  4799.4 1735.37
  4884.3 1730.93  4905.5 1728.99  5049.6 1724.70  5077.8 1722.52  5087.3 1721.64
  5087.6 1721.14  5092.1 1721.64  5109.7 1723.26  5135.6 1727.77  5140.6 1727.77
  5170.0 1733.15  5196.8 1735.90  5201.9 1735.46  5220.6 1737.25  5230.7 1738.99
  5240.8 1741.94  5261.0 1741.25  5336.7 1745.57  5453.0 1755.53  5476.5 1756.46
#Mann=5,-1,0
  4522.0    0.07       0  4727.6     0.1       0  5077.8    0.07       0
  5087.3    0.05       0  5092.1    0.07       0
Bank Sta=5087.3,5092.1
Exp/Cntr=0.3,0.1

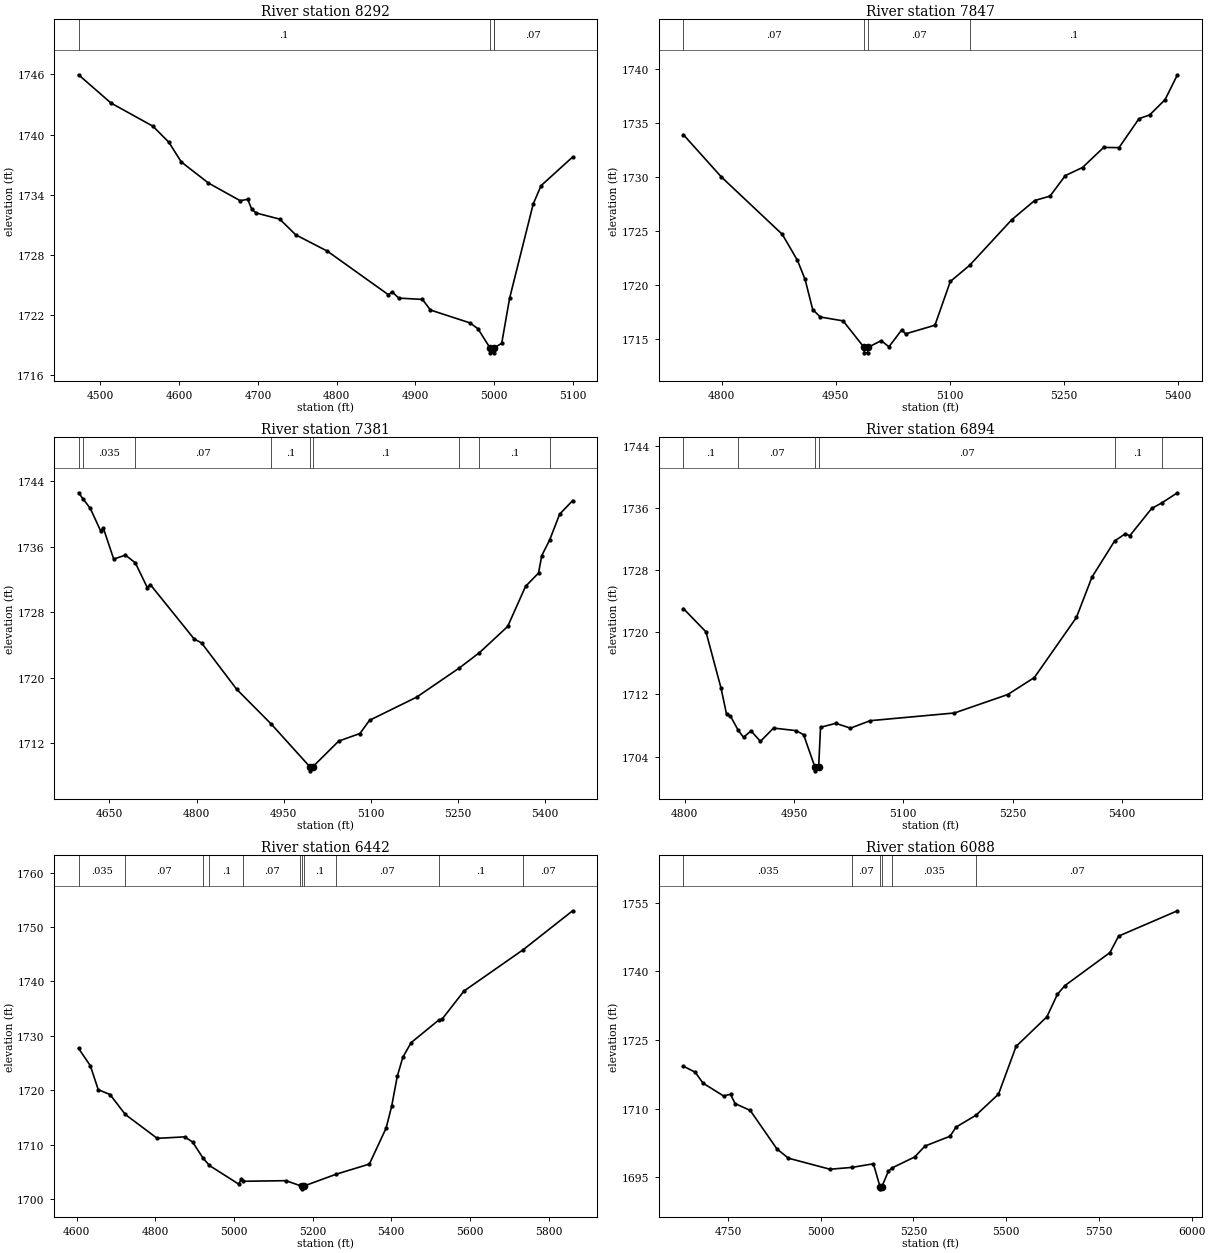
Type RM Length L Ch R = 1,8292,445,445,445
BEGIN DESCRIPTION:
Stream0489 17.0
END DESCRIPTION:
XS GIS Cut Line= 3
      1910398.81     13942265.09      1909875.00     13942325.00
      1909775.03     13942325.00
#Sta/Elev= 30
  4472.3 1745.97  4513.4 1743.15  4566.7 1740.83  4586.9 1739.23  4602.7 1737.26
  4637.2 1735.15  4677.4 1733.39  4687.0 1733.52  4692.0 1732.57  4697.6 1732.16
  4727.8 1731.54  4747.9 1729.98  4788.2 1728.34  4865.6 1723.99  4870.6 1724.27
  4878.7 1723.65  4908.9 1723.52  4919.0 1722.46  4969.3 1721.17  4979.4 1720.58
  4994.6 1718.68  4994.9 1718.18  4999.1 1718.18  4999.5 1718.68  4999.9 1718.68
  5009.5 1719.13  5019.5 1723.63  5049.5 1733.06  5059.5 1734.89  5099.5 1737.75
#Mann=4,-1,0
  4472.3     0.1       0  4994.6    0.05       0  4999.5     0.1       0
  4999.9    0.07       0
Bank Sta=4994.6,4999.5
Exp/Cntr=0.3,0.1

Type RM Length L Ch R = 1,7847,466,466,466
BEGIN DESCRIPTION:
Stream0489 16.0
END DESCRIPTION:
XS GIS Cut Line= 3
      1910175.03     13941925.00      1909925.00     13941925.00
      1909528.85     13941873.62
#Sta/Elev= 30
  4749.6 1733.93  4799.6 1730.01  4879.6 1724.70  4899.6 1722.28  4909.6 1720.52
  4919.6 1717.73  4929.6 1717.04  4959.6 1716.68  4987.2 1714.22  4987.5 1713.72
  4991.7 1713.72  4992.1 1714.22  5009.7 1714.85  5019.8 1714.28  5036.7 1715.85
  5041.8 1715.48  5080.3 1716.28  5100.5 1720.33  5125.8 1721.82  5181.1 1726.04
  5211.4 1727.83  5231.6 1728.24  5251.7 1730.14  5274.3 1730.89  5302.1 1732.75
  5322.3 1732.73  5348.5 1735.41  5362.6 1735.76  5382.8 1737.17  5399.1 1739.48
#Mann=4,-1,0
  4749.6    0.07       0  4987.2    0.05       0  4992.1    0.07       0
  5125.8     0.1       0
Bank Sta=4987.2,4992.1
Exp/Cntr=0.3,0.1

Type RM Length L Ch R = 1,7381,487,487,487
BEGIN DESCRIPTION:
Stream0489 15.0
END DESCRIPTION:
XS GIS Cut Line= 3
      1910274.98     13941425.00      1909875.00     13941475.00
      1909475.01     13941675.00
#Sta/Elev= 30
  4596.9 1742.61  4604.1 1741.91  4617.0 1740.72  4634.7 1737.98  4639.7 1738.27
  4657.4 1734.51  4677.5 1734.99  4694.6 1734.05  4715.3 1731.01  4720.3 1731.40
  4795.9 1724.74  4808.5 1724.27  4869.0 1718.60  4928.9 1714.32  4994.9 1709.13
  4995.3 1708.63  5000.1 1709.13  5044.7 1712.27  5081.1 1713.19  5097.8 1714.81
  5178.9 1717.64  5252.4 1721.21  5286.7 1723.06  5335.4 1726.27  5366.2 1731.17
  5388.5 1732.80  5394.1 1734.93  5407.8 1736.86  5424.9 1740.00  5447.2 1741.65
#Mann=9,-1,0
  4596.9    0.07       0  4604.1   0.035       0  4694.6    0.07       0
  4928.9     0.1       0  4994.9    0.05       0  5000.1     0.1       0
  5252.4    0.07       0  5286.7     0.1       0  5407.8    0.07       0
Bank Sta=4994.9,5000.1
Exp/Cntr=0.3,0.1

Type RM Length L Ch R = 1,6894,452,452,452
BEGIN DESCRIPTION:
Stream0489 14.0
END DESCRIPTION:
XS GIS Cut Line= 3
      1909975.04     13940974.99      1909775.00     13941025.00
      1909375.00     13941275.00
#Sta/Elev= 30
  4798.2 1723.05  4829.2 1720.05  4849.8 1712.84  4857.5 1709.43  4862.7 1709.24
  4873.5 1707.38  4880.7 1706.49  4891.0 1707.32  4903.9 1705.97  4921.9 1707.68
  4952.9 1707.35  4963.2 1706.82  4978.6 1702.68  4979.0 1702.18  4983.8 1702.68
  4986.4 1707.78  5007.3 1708.29  5027.4 1707.67  5054.5 1708.63  5170.1 1709.62
  5243.2 1711.99  5279.8 1714.18  5337.5 1721.91  5358.8 1727.09  5389.9 1731.74
  5404.8 1732.68  5410.6 1732.40  5440.7 1735.92  5454.7 1736.64  5476.1 1737.94
#Mann=6,-1,0
  4798.2     0.1       0  4873.5    0.07       0  4978.6    0.05       0
  4983.8    0.07       0  5389.9     0.1       0  5454.7    0.07       0
Bank Sta=4978.6,4983.8
Exp/Cntr=0.3,0.1

Type RM Length L Ch R = 1,6442,354,354,354
BEGIN DESCRIPTION:
Stream0489 13.0
END DESCRIPTION:
XS GIS Cut Line= 3
      1910024.96     13940625.00      1909625.00     13940625.00
      1908988.69     13941198.55
#Sta/Elev= 30
  4604.7 1727.69  4634.7 1724.49  4654.7 1720.10  4684.7 1719.20  4723.6 1715.54
  4804.7 1711.15  4874.7 1711.42  4894.7 1710.48  4920.8 1707.58  4937.3 1706.17
  5011.8 1702.75  5018.5 1703.61  5024.2 1703.26  5132.1 1703.37  5167.1 1702.49
  5172.0 1702.37  5172.4 1701.87  5177.3 1702.37  5259.5 1704.55  5344.3 1706.42
  5386.9 1713.02  5401.1 1717.05  5415.3 1722.54  5429.5 1726.06  5450.5 1728.73
  5520.2 1732.85  5528.9 1733.02  5585.0 1738.22  5736.3 1745.85  5861.3 1752.97
#Mann=11,-1,0
  4604.7   0.035       0  4723.6    0.07       0  4920.8   0.035       0
  4937.3     0.1       0  5024.2    0.07       0  5167.1     0.1       0
  5172.0    0.05       0  5177.3     0.1       0  5259.5    0.07       0
  5520.2     0.1       0  5736.3    0.07       0
Bank Sta=5172,5177.3
Exp/Cntr=0.3,0.1

Type RM Length L Ch R = 1,6088,583,583,583
BEGIN DESCRIPTION:
Stream0489 12.0
END DESCRIPTION:
XS GIS Cut Line= 3
      1909974.98     13940424.99      1909636.01     13940305.40
      1908675.22     13940155.23
#Sta/Elev= 30
  4629.8 1719.29  4661.6 1717.98  4682.8 1715.59  4738.0 1712.80  4757.0 1713.16
  4769.0 1711.14  4810.0 1709.63  4882.1 1701.21  4913.1 1699.20  5025.0 1696.79
  5083.9 1697.19  5142.1 1697.98  5159.7 1693.01  5160.1 1692.51  5165.0 1693.01
  5182.6 1696.38  5192.7 1697.09  5253.4 1699.47  5281.0 1701.85  5348.8 1704.00
  5364.8 1705.99  5418.4 1708.58  5479.3 1713.19  5526.7 1723.61  5609.9 1730.09
  5638.0 1734.98  5658.3 1736.89  5779.7 1744.10  5803.2 1747.70  5961.7 1753.23
#Mann=6,-1,0
  4629.8   0.035       0  5083.9    0.07       0  5159.7   0.035       0
  5165.0    0.07       0  5192.7   0.035       0  5418.4    0.07       0
Bank Sta=5159.7,5165
Exp/Cntr=0.3,0.1

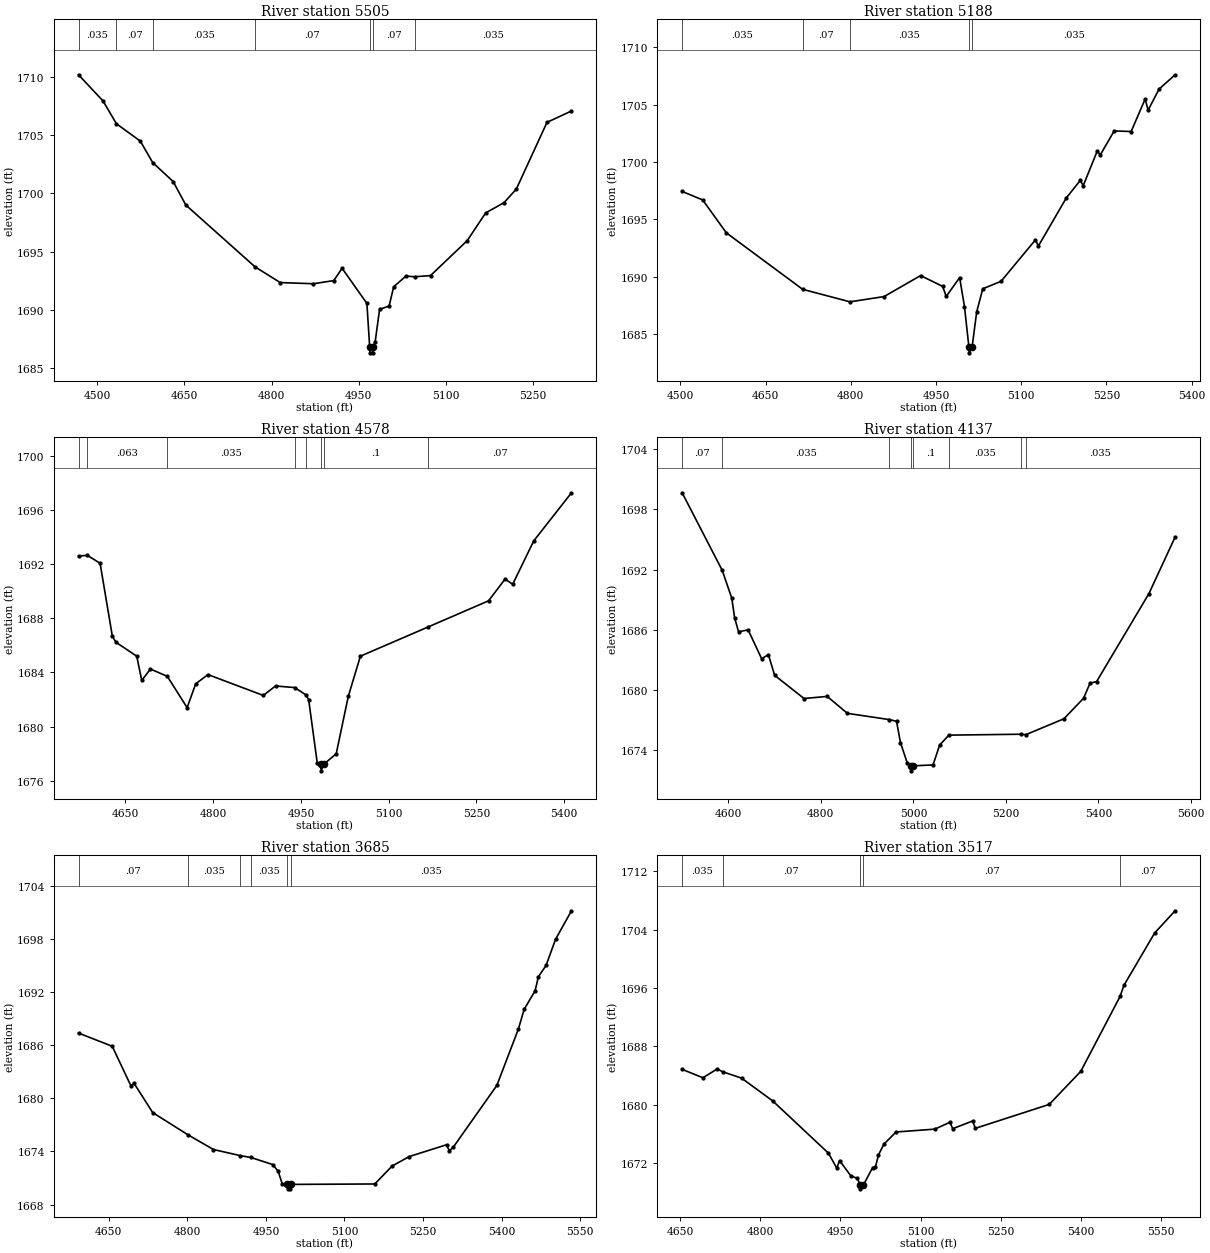
Type RM Length L Ch R = 1,5505,317,317,317
BEGIN DESCRIPTION:
Stream0489 11.0
END DESCRIPTION:
XS GIS Cut Line= 3
      1909974.99     13940124.99      1909575.00     13939775.00
      1909275.02     13939675.01
#Sta/Elev= 30
  4468.1 1710.20  4510.3 1707.95  4533.3 1705.99  4574.4 1704.50  4595.6 1702.66
  4630.9 1701.02  4652.7 1699.00  4771.7 1693.69  4815.0 1692.34  4871.9 1692.24
  4907.1 1692.51  4921.3 1693.57  4964.0 1690.55  4968.8 1686.80  4969.2 1686.30
  4973.9 1686.30  4974.4 1686.80  4978.2 1687.23  4985.8 1690.04  5002.2 1690.32
  5010.1 1691.98  5031.2 1692.90  5046.1 1692.84  5073.4 1692.94  5136.6 1695.95
  5168.3 1698.33  5199.9 1699.21  5221.0 1700.38  5273.7 1706.11  5315.8 1707.09
#Mann=7,-1,0
  4468.1   0.035       0  4533.3    0.07       0  4595.6   0.035       0
  4771.7    0.07       0  4968.8    0.05       0  4974.4    0.07       0
  5046.1   0.035       0
Bank Sta=4968.8,4974.4
Exp/Cntr=0.3,0.1

Type RM Length L Ch R = 1,5188,610,610,610
BEGIN DESCRIPTION:
Stream0489 10.0
END DESCRIPTION:
XS GIS Cut Line= 3
      1910024.99     13939725.00      1909677.31     13939453.90
      1909279.42     13939608.63
#Sta/Elev= 30
  4503.0 1697.43  4539.2 1696.69  4580.8 1693.82  4715.2 1688.89  4798.5 1687.80
  4858.5 1688.26  4922.7 1690.09  4961.6 1689.15  4967.8 1688.27  4991.5 1689.91
  5000.0 1687.39  5007.8 1683.85  5008.3 1683.35  5013.4 1683.85  5021.5 1686.92
  5032.2 1688.94  5064.4 1689.59  5124.8 1693.20  5130.2 1692.68  5179.2 1696.86
  5203.8 1698.39  5209.1 1697.94  5233.7 1700.96  5239.0 1700.61  5263.5 1702.71
  5293.4 1702.66  5318.0 1705.49  5323.3 1704.52  5342.5 1706.36  5370.8 1707.61
#Mann=5,-1,0
  4503.0   0.035       0  4715.2    0.07       0  4798.5   0.035       0
  5007.8   0.035       0  5013.4   0.035       0
Bank Sta=5007.8,5013.4
Exp/Cntr=0.3,0.1

Type RM Length L Ch R = 1,4578,441,441,441
BEGIN DESCRIPTION:
Stream0489 9.0
END DESCRIPTION:
XS GIS Cut Line= 3
      1910275.00     13939275.00      1909925.00     13939025.00
      1909525.03     13938925.01
#Sta/Elev= 30
  4569.9 1692.59  4585.0 1692.65  4606.8 1692.06  4627.7 1686.68  4633.8 1686.23
  4669.4 1685.20  4678.0 1683.41  4692.8 1684.25  4721.7 1683.71  4755.5 1681.40
  4770.2 1683.16  4791.1 1683.84  4885.7 1682.30  4906.6 1683.00  4939.3 1682.88
  4958.6 1682.34  4963.2 1681.99  4977.9 1677.30  4983.7 1677.23  4984.2 1676.73
  4989.4 1677.23  5010.3 1677.99  5030.9 1682.23  5051.6 1685.20  5166.4 1687.34
  5270.6 1689.29  5298.9 1690.90  5311.8 1690.51  5347.9 1693.72  5412.3 1697.27
#Mann=8,-1,0
  4569.9    0.07       0  4585.0   0.063       0  4721.7   0.035       0
  4939.3    0.07       0  4958.6     0.1       0  4983.7    0.05       0
  4989.4     0.1       0  5166.4    0.07       0
Bank Sta=4983.7,4989.4
Exp/Cntr=0.3,0.1

Type RM Length L Ch R = 1,4137,452,452,452
BEGIN DESCRIPTION:
Stream0489 8.0
END DESCRIPTION:
XS GIS Cut Line= 3
      1910524.99     13938974.99      1910125.00     13938675.00
      1909724.98     13938274.98
#Sta/Elev= 30
  4500.1 1699.66  4586.8 1691.92  4607.4 1689.15  4613.6 1687.18  4622.0 1685.81
  4642.8 1685.99  4672.0 1683.11  4686.5 1683.53  4700.1 1681.46  4763.6 1679.15
  4813.6 1679.36  4857.4 1677.67  4947.9 1677.05  4963.6 1676.88  4972.0 1674.76
  4986.5 1672.76  4994.1 1672.44  4994.6 1671.94  4999.9 1672.44  5042.5 1672.53
  5056.7 1674.50  5076.6 1675.50  5232.5 1675.59  5242.7 1675.54  5325.4 1677.13
  5367.8 1679.17  5381.9 1680.68  5396.1 1680.84  5509.2 1689.61  5565.8 1695.25
#Mann=8,-1,0
  4500.1    0.07       0  4586.8   0.035       0  4947.9     0.1       0
  4994.1    0.05       0  4999.9     0.1       0  5076.6   0.035       0
  5232.5    0.07       0  5242.7   0.035       0
Bank Sta=4994.1,4999.9
Exp/Cntr=0.3,0.1

Type RM Length L Ch R = 1,3685,168,168,168
BEGIN DESCRIPTION:
Stream0489 7.0
END DESCRIPTION:
XS GIS Cut Line= 3
      1910674.96     13938374.99      1910275.00     13938275.00
      1909768.61     13938121.90
#Sta/Elev= 30
  4592.1 1687.36  4656.5 1685.87  4692.6 1681.35  4697.7 1681.73  4733.8 1678.38
  4800.3 1675.90  4849.8 1674.21  4901.1 1673.52  4921.3 1673.31  4963.1 1672.51
  4973.4 1671.75  4981.2 1670.31  4991.1 1670.27  4991.6 1669.77  4996.5 1669.77
  4997.0 1670.27  5157.9 1670.32  5190.8 1672.34  5223.8 1673.42  5294.9 1674.75
  5300.1 1674.07  5307.3 1674.44  5390.9 1681.45  5431.9 1687.79  5443.1 1690.05
  5464.0 1692.14  5470.1 1693.71  5484.9 1695.00  5503.0 1697.95  5533.4 1701.17
#Mann=6,-1,0
  4592.1    0.07       0  4800.3   0.035       0  4901.1    0.07       0
  4921.3   0.035       0  4991.1   0.035       0  4997.0   0.035       0
Bank Sta=4991.1,4997
Exp/Cntr=0.3,0.1

Type RM Length L Ch R = 1,3517,284,284,284
BEGIN DESCRIPTION:
Stream0489 6.1
END DESCRIPTION:
XS GIS Cut Line= 3
      1910708.21     13938240.58      1910196.54     13938092.39
      1909810.13     13938034.63
#Sta/Elev= 30
  4653.4 1684.84  4692.3 1683.69  4719.2 1684.90  4729.0 1684.52  4764.7 1683.64
  4823.3 1680.50  4927.4 1673.36  4943.1 1671.30  4948.3 1672.35  4969.1 1670.27
  4981.8 1669.89  4986.9 1668.97  4987.4 1668.47  4992.8 1668.97  5010.2 1671.39
  5015.4 1671.44  5021.1 1673.11  5031.5 1674.61  5054.2 1676.26  5126.6 1676.65
  5155.0 1677.59  5160.2 1676.71  5197.5 1677.77  5202.6 1676.76  5341.0 1680.04
  5400.0 1684.56  5473.7 1694.83  5480.9 1696.35  5538.5 1703.53  5576.8 1706.57
#Mann=5,-1,0
  4653.4   0.035       0  4729.0    0.07       0  4986.9   0.035       0
  4992.8    0.07       0  5473.7    0.07       0
Bank Sta=4986.9,4992.8
Exp/Cntr=0.3,0.1

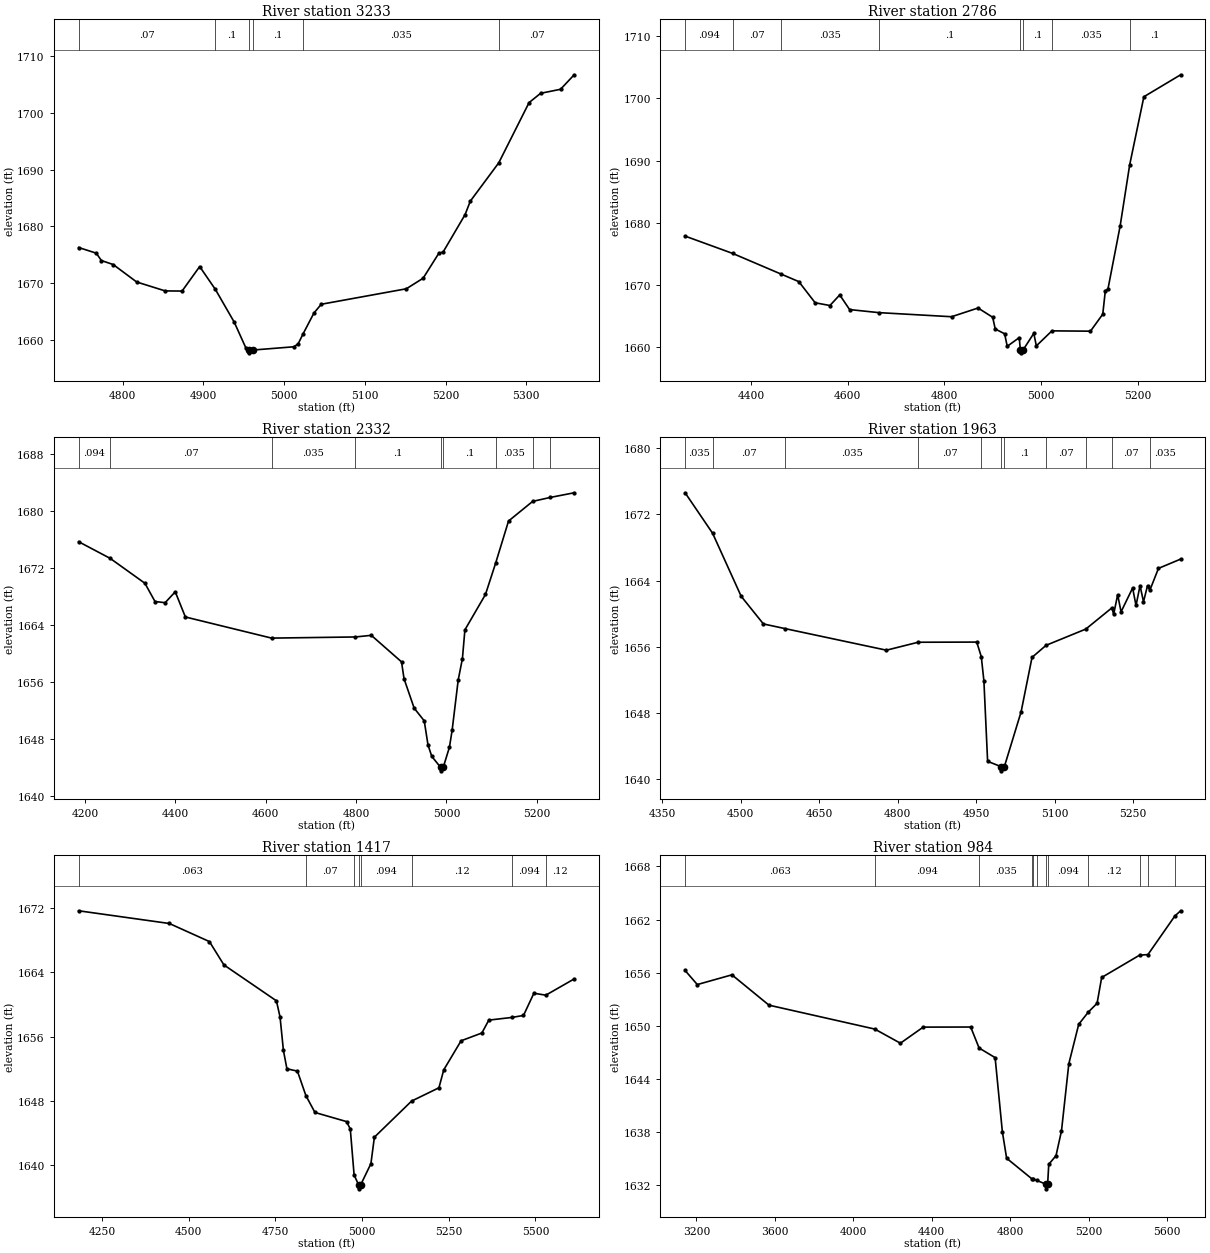
Type RM Length L Ch R = 1,3233,447,447,447
BEGIN DESCRIPTION:
Stream0489 6.0
END DESCRIPTION:
XS GIS Cut Line= 3
      1910525.04     13938075.03      1910325.00     13937925.00
      1909974.96     13937824.99
#Sta/Elev= 30
  4745.3 1676.26  4767.2 1675.26  4773.5 1673.96  4788.1 1673.26  4817.2 1670.18
  4852.6 1668.60  4873.5 1668.58  4895.3 1672.90  4914.8 1668.86  4938.1 1663.10
  4952.6 1658.53  4955.9 1658.18  4956.4 1657.68  4961.8 1658.18  5012.2 1658.75
  5017.4 1659.29  5023.5 1661.04  5036.9 1664.70  5046.0 1666.25  5151.4 1668.98
  5172.2 1670.84  5191.7 1675.25  5196.9 1675.44  5224.2 1682.06  5230.7 1684.44
  5266.0 1691.21  5303.5 1701.82  5317.8 1703.46  5342.5 1704.17  5359.4 1706.73
#Mann=6,-1,0
  4745.3    0.07       0  4914.8     0.1       0  4955.9    0.05       0
  4961.8     0.1       0  5023.5   0.035       0  5266.0    0.07       0
Bank Sta=4955.9,4961.8
Exp/Cntr=0.3,0.1

Type RM Length L Ch R = 1,2786,454,454,454
BEGIN DESCRIPTION:
Stream0489 5.0
END DESCRIPTION:
XS GIS Cut Line= 4
      1910989.64     13937602.13      1910456.93     13937505.87
      1910275.00     13937575.00      1910003.50     13937672.71
#Sta/Elev= 30
  4264.0 1677.89  4362.2 1675.11  4461.8 1671.81  4499.1 1670.58  4532.9 1667.18
  4563.4 1666.74  4583.7 1668.44  4604.1 1666.09  4664.2 1665.60  4814.9 1664.94
  4869.7 1666.34  4899.9 1664.85  4905.2 1662.97  4924.6 1662.20  4930.0 1660.19
  4954.8 1661.58  4957.1 1659.64  4957.6 1659.14  4963.1 1659.64  4984.9 1662.27
  4990.2 1660.26  5022.4 1662.67  5102.1 1662.62  5127.5 1665.35  5132.8 1669.12
  5138.1 1669.34  5163.5 1679.55  5183.2 1689.36  5212.5 1700.27  5288.5 1703.80
#Mann=8,-1,0
  4264.0   0.094       0  4362.2    0.07       0  4461.8   0.035       0
  4664.2     0.1       0  4957.1    0.05       0  4963.1     0.1       0
  5022.4   0.035       0  5183.2     0.1       0
Bank Sta=4957.1,4963.1
Exp/Cntr=0.3,0.1

Type RM Length L Ch R = 1,2332,369,369,369
BEGIN DESCRIPTION:
Stream0489 4.0
END DESCRIPTION:
XS GIS Cut Line= 3
      1910956.13     13937542.15      1910225.00     13937175.00
      1909972.75     13937056.11
#Sta/Elev= 30
  4185.8 1675.73  4255.6 1673.39  4332.5 1669.89  4354.9 1667.32  4377.3 1667.16
  4399.7 1668.69  4422.1 1665.15  4612.9 1662.18  4798.5 1662.34  4833.7 1662.57
  4900.6 1658.84  4906.2 1656.46  4928.6 1652.33  4950.9 1650.55  4959.2 1647.16
  4967.6 1645.55  4987.0 1644.02  4987.5 1643.52  4993.0 1644.02  5006.7 1646.85
  5012.6 1649.21  5026.1 1656.30  5035.4 1659.30  5040.9 1663.34  5086.4 1668.31
  5108.9 1672.71  5137.5 1678.64  5190.9 1681.40  5230.3 1681.96  5282.8 1682.61
#Mann=9,-1,0
  4185.8   0.094       0  4255.6    0.07       0  4612.9   0.035       0
  4798.5     0.1       0  4987.0    0.05       0  4993.0     0.1       0
  5108.9   0.035       0  5190.9     0.1       0  5230.3   0.035       0
Bank Sta=4987,4993
Exp/Cntr=0.3,0.1

Type RM Length L Ch R = 1,1963,546,546,546
BEGIN DESCRIPTION:
Stream0489 3.0
END DESCRIPTION:
XS GIS Cut Line= 3
      1910970.46     13937279.55      1910482.48     13936910.16
      1910226.84     13936693.23
#Sta/Elev= 30
  4393.6 1674.61  4446.1 1669.73  4500.8 1662.11  4543.3 1658.77  4585.2 1658.20
  4778.5 1655.60  4839.1 1656.56  4951.1 1656.58  4959.8 1654.82  4964.8 1651.90
  4971.9 1642.18  4997.9 1641.53  4998.4 1641.03  5003.9 1641.53  5035.9 1648.15
  5056.8 1654.73  5083.7 1656.19  5159.6 1658.15  5209.6 1660.72  5212.8 1659.92
  5220.5 1662.30  5227.0 1660.23  5249.1 1663.11  5255.6 1661.00  5263.3 1663.40
  5269.9 1661.45  5277.6 1663.40  5282.0 1662.83  5298.5 1665.48  5340.9 1666.60
#Mann=11,-1,0
  4393.6   0.035       0  4446.1    0.07       0  4585.2   0.035       0
  4839.1    0.07       0  4959.8     0.1       0  4997.9    0.05       0
  5003.9     0.1       0  5083.7    0.07       0  5159.6   0.035       0
  5209.6    0.07       0  5282.0   0.035       0
Bank Sta=4997.9,5003.9
Exp/Cntr=0.3,0.1

Type RM Length L Ch R = 1,1417,433,433,433
BEGIN DESCRIPTION:
Stream0489 2.0
END DESCRIPTION:
XS GIS Cut Line= 4
      1911371.88     13936932.80      1911078.88     13936520.43
      1910775.00     13936475.00      1910158.87     13936461.45
#Sta/Elev= 30
  4182.4 1671.64  4444.0 1670.06  4559.7 1667.81  4601.5 1664.91  4752.9 1660.45
  4763.4 1658.44  4773.1 1654.29  4783.2 1652.00  4813.5 1651.71  4838.0 1648.66
  4864.1 1646.57  4955.1 1645.44  4966.0 1644.52  4977.0 1638.81  4989.9 1637.58
  4990.4 1637.08  4996.0 1637.58  5025.5 1640.21  5035.5 1643.50  5142.9 1647.99
  5221.7 1649.64  5235.6 1651.87  5285.6 1655.48  5345.6 1656.45  5365.6 1658.05
  5431.4 1658.38  5465.6 1658.63  5495.6 1661.39  5530.0 1661.15  5611.8 1663.17
#Mann=8,-1,0
  4182.4   0.063       0  4838.0    0.07       0  4977.0   0.094       0
  4989.9    0.05       0  4996.0   0.094       0  5142.9    0.12       0
  5431.4   0.094       0  5530.0    0.12       0
Bank Sta=4989.9,4996
Exp/Cntr=0.3,0.1

Type RM Length L Ch R = 1,984,218,218,218
BEGIN DESCRIPTION:
Stream0489 1.1
END DESCRIPTION:
XS GIS Cut Line= 4
      1912373.96     13936036.84      1911354.04     13935693.98
      1910580.75     13936133.20      1910100.77     13936424.71
#Sta/Elev= 30
  3142.2 1656.24  3204.4 1654.65  3380.9 1655.75  3570.0 1652.32  4109.3 1649.62
  4240.1 1648.02  4356.4 1649.84  4598.6 1649.85  4641.3 1647.48  4723.1 1646.39
  4760.1 1638.00  4781.7 1635.02  4912.8 1632.65  4916.7 1632.65  4935.2 1632.52
  4984.5 1632.06  4985.0 1631.56  4990.8 1632.06  4996.6 1634.33  5033.6 1635.31
  5061.5 1638.11  5099.0 1645.71  5149.4 1650.16  5198.4 1651.54  5243.0 1652.53
  5266.4 1655.45  5459.6 1657.97  5502.4 1658.04  5639.6 1662.40  5669.1 1662.99
#Mann=12,-1,0
  3142.2   0.063       0  4109.3   0.094       0  4641.3   0.035       0
  4912.8   0.094       0  4916.7   0.035       0  4935.2   0.094       0
  4984.5    0.05       0  4990.8   0.094       0  5198.4    0.12       0
  5459.6   0.094       0  5502.4    0.12       0  5639.6   0.035       0
Bank Sta=4984.5,4990.8
Exp/Cntr=0.3,0.1

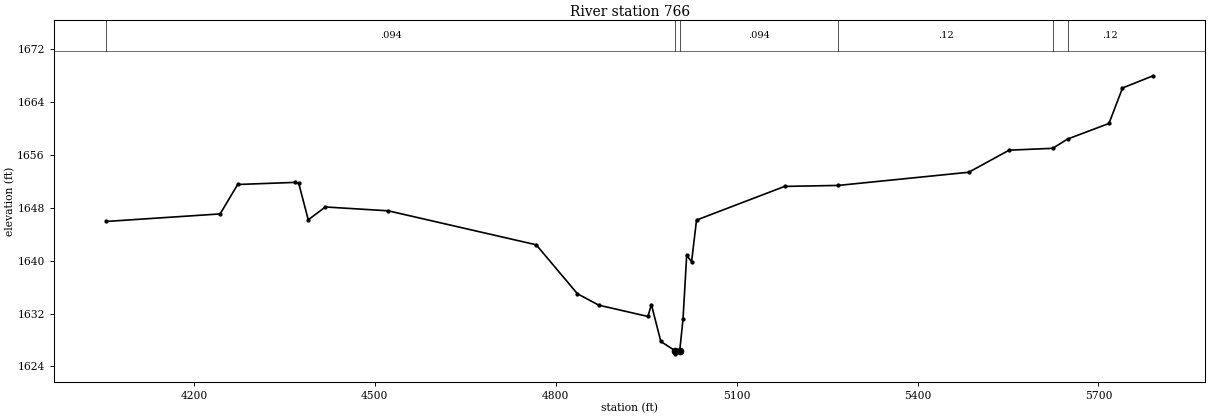
Type RM Length L Ch R = 1,766,0,0,0
BEGIN DESCRIPTION:
Stream0489 1.0
END DESCRIPTION:
XS GIS Cut Line= 3
      1911437.50     13935398.75      1910602.74     13935894.02
      1909919.78     13936239.07
#Sta/Elev= 30
  4054.7 1645.93  4243.6 1647.07  4272.7 1651.52  4368.2 1651.84  4374.0 1651.68
  4389.7 1646.18  4418.1 1648.12  4522.2 1647.54  4767.7 1642.40  4836.0 1635.00
  4871.5 1633.27  4952.9 1631.56  4958.7 1633.36  4974.3 1627.78  4997.5 1626.41
  4998.0 1625.91  5005.7 1626.41  5011.1 1631.15  5017.2 1640.82  5025.3 1639.83
  5033.5 1646.14  5179.6 1651.23  5268.6 1651.38  5484.9 1653.37  5551.8 1656.71
  5624.0 1656.99  5649.0 1658.40  5717.4 1660.75  5739.8 1666.11  5790.5 1667.96
#Mann=6,-1,0
  4054.7   0.094       0  4997.5    0.05       0  5005.7   0.094       0
  5268.6    0.12       0  5624.0   0.035       0  5649.0    0.12       0
Bank Sta=4997.5,5005.7
Exp/Cntr=0.3,0.1

Chan Stop Cuts=-1