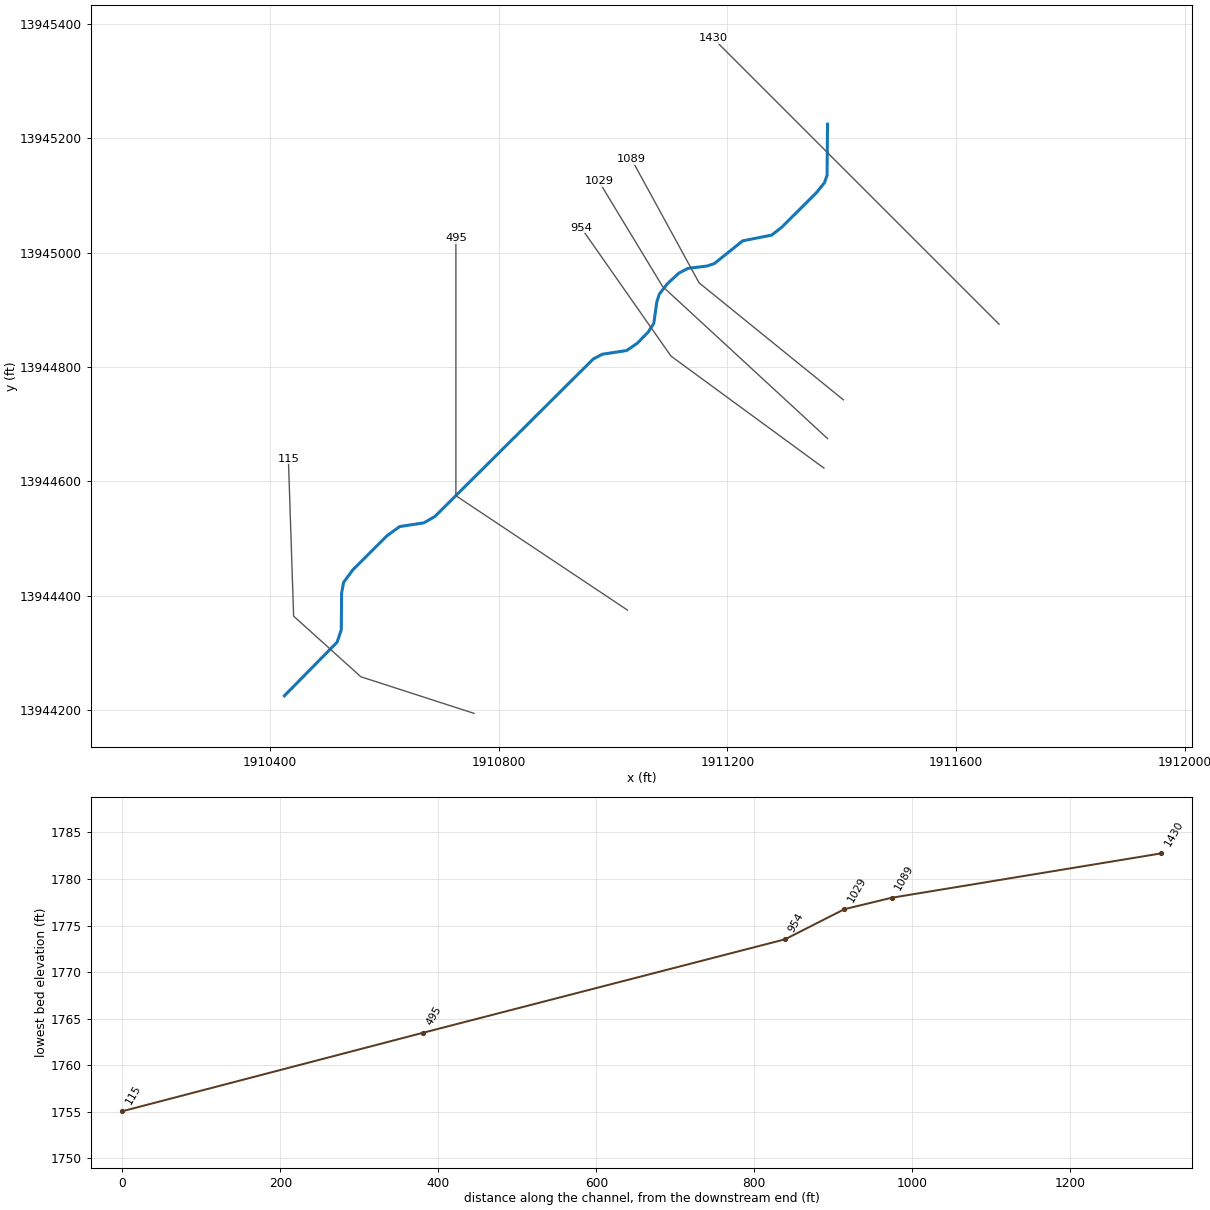
--- Stream0490.prj (project) ---

Proj Title=Stream0490 Base Level Engineering
Current Plan=p01
Default Exp/Contr=0.3,0.1
English Units
Geom File=g01
Flow File=f01
Plan File=p01
Y Axis Title=Elevation
X Axis Title(PF)=Main Channel Distance
X Axis Title(XS)=Station
BEGIN DESCRIPTION:
Stream0490
END DESCRIPTION:
DSS Export Rating Curves= 0
DSS Export Rating Curve Sorted= 0
DSS Export Volume Flow Curves= 0
DXF OffsetX= 0
DXF OffsetY= 0
DXF ScaleX= 1
DXF ScaleY= 10

--- Stream0490.p01 (plan) ---

Plan Title=Multiple Run
Short Identifier=Multiple
Geom File=g01
Flow File=f01
Subcritical Flow
K Sum by GR= 0
Std Step Tol= 0.01
Critical Tol= 0.01
Num of Std Step Trials= 20
Max Error Tol= 0.3
Flow Tol Ratio= 0.001
Split Flow NTrial= 30
Split Flow Tol= 0.02
Split Flow Ratio= 0.02
Log Output Level= 0
Friction Slope Method= 1
Unsteady Friction Slope Method= 2
Unsteady Bridges Friction Slope Method= 1
Parabolic Critical Depth
Global Vel Dist=  1 , 1 , 1
Global Log Level= 0
CheckData=True
Encroach Param= -1, 0, 0, 0
BEGIN DESCRIPTION:
Multiple Run
END DESCRIPTION:

--- Stream0490.f01 (steady flow) ---

Flow Title=Multiple
Program Version=4.10
Number of Profiles= 7
Profile Names=10-year,25-year,50-year,1pct_min,100-year,1pct_plu,500-year
River Rch & RM=Stream0490,Reach-1         ,1430
     633    1043    1421     939    1873    3737    3207
Boundary for River Rch & Prof#=Stream0490,Reach-1         , 1
Up Type= 0
Dn Type= 3
Dn Slope=0.005
Boundary for River Rch & Prof#=Stream0490,Reach-1         , 2
Up Type= 0
Dn Type= 3
Dn Slope=0.005
Boundary for River Rch & Prof#=Stream0490,Reach-1         , 3
Up Type= 0
Dn Type= 3
Dn Slope=0.005
Boundary for River Rch & Prof#=Stream0490,Reach-1         , 4
Up Type= 0
Dn Type= 3
Dn Slope=0.005
Boundary for River Rch & Prof#=Stream0490,Reach-1         , 5
Up Type= 0
Dn Type= 3
Dn Slope=0.005
Boundary for River Rch & Prof#=Stream0490,Reach-1         , 6
Up Type= 0
Dn Type= 3
Dn Slope=0.005
Boundary for River Rch & Prof#=Stream0490,Reach-1         , 7
Up Type= 0
Dn Type= 3
Dn Slope=0.005
DSS Import GetInterval= 0
DSS Import GetPeak= 0
DSS Import FillOption= 0

--- Stream0490.g01 (geometry) ---

Geom Title=Existing Conditions
Program Version=4.10

River Reach=Stream0490      ,Reach-1
Reach XY= 30
        1911375.       13945225.      1911374.19     13945135.33
      1911369.66     13945122.49       1911355.4      13945104.8
      1911295.13     13945044.76      1911277.31     13945030.83
      1911226.74     13945020.81      1911177.16     13944981.11
      1911164.25     13944976.72      1911130.85     13944972.58
        1911115.     13944964.37      1911094.63     13944945.47
      1911080.76     13944927.51       1911076.5     13944914.47
       1911071.1     13944876.46      1911061.51     13944861.45
      1911042.05      13944841.5      1911023.57     13944828.89
      1910981.09     13944822.45      1910965.34     13944814.21
      1910688.21     13944538.63      1910668.95     13944527.54
      1910626.63     13944521.03      1910604.87     13944505.23
      1910544.61      13944445.2      1910528.61     13944423.51
      1910525.13     13944404.95      1910524.49     13944340.21
      1910517.21      13944318.8        1910425.       13944225.

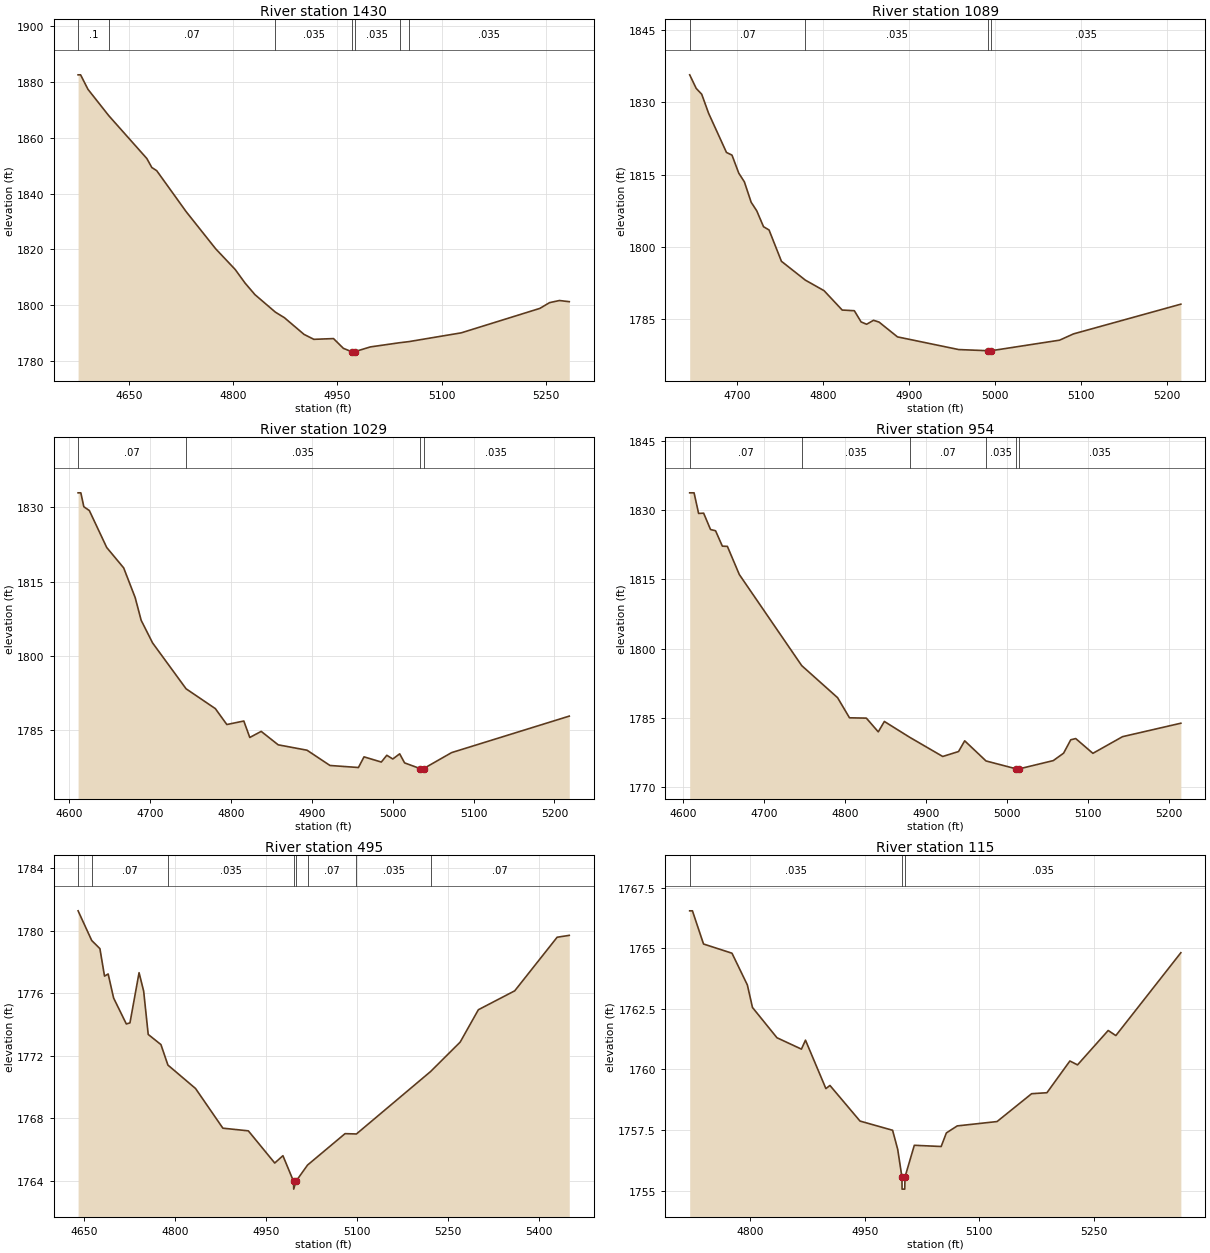
Type RM Length L Ch R = 1 ,1430    ,341,341,341
BEGIN DESCRIPTION:
Stream0490 3.0
END DESCRIPTION:
XS GIS Cut Line= 3
      1911675.02     13944874.98        1911375.       13945175.
      1911175.02     13945374.98
#Sta/Elev= 30
  4576.7 1882.62  4580.3 1882.62  4590.9 1877.42  4620.8 1867.98  4675.7 1852.57
  4682.8 1849.37  4689.9 1848.21  4732.3  1833.5  4774.7  1820.2    4803 1812.72
  4817.1 1807.87  4831.3 1803.73  4860.8 1797.43  4873.7 1795.46    4902 1789.46
  4916.1 1787.69  4944.4 1787.96  4958.6 1784.46  4970.7 1783.24    4971 1782.74
  4974.5 1782.74  4974.7 1783.24  4997.5 1784.97  5039.5 1786.47  5052.9 1786.87
  5128.3 1790.02  5241.4 1798.79  5255.5 1800.87  5269.7 1801.62  5283.8  1801.2
#Mann= 7 ,-1 , 0
  4576.7      .1       0  4620.8     .07       0  4860.8    .035       0
  4970.7    .035       0  4974.7    .035       0  5039.5     .07       0
  5052.9    .035       0
Bank Sta=4970.7,4974.7
XS Rating Curve= 0 ,0
Exp/Cntr=0.3,0.1

Type RM Length L Ch R = 1 ,1089    ,60,60,60
BEGIN DESCRIPTION:
Stream0490 2.1
END DESCRIPTION:
XS GIS Cut Line= 3
      1911402.78     13944742.71      1911150.35     13944947.37
      1911032.24     13945163.54
#Sta/Elev= 30
  4645.1 1835.73  4652.7 1832.91  4659.1  1831.7  4667.1 1827.75  4687.9 1819.62
  4694.3 1819.07  4702.2 1815.32  4708.7 1813.53  4716.6 1809.29  4723.1 1807.51
    4731 1804.21  4737.4 1803.54  4751.8 1797.04  4779.6 1793.13  4801.4 1790.94
  4822.5 1786.92  4836.6 1786.78  4844.5 1784.45  4850.9 1783.97  4858.9 1784.79
  4865.3 1784.43  4886.8 1781.35    4958 1778.72  4991.8 1778.48    4992 1777.98
  4995.5 1777.98  4995.8 1778.48  5075.4 1780.67  5091.5 1781.97  5216.4 1788.14
#Mann= 4 ,-1 , 0
  4645.1     .07       0  4779.6    .035       0  4991.8    .035       0
  4995.8    .035       0
Bank Sta=4991.8,4995.8
XS Rating Curve= 0 ,0
Exp/Cntr=0.3,0.1

Type RM Length L Ch R = 1 ,1029    ,75,75,75
BEGIN DESCRIPTION:
Stream0490 2.0
END DESCRIPTION:
XS GIS Cut Line= 3
        1911375.       13944675.       1911086.4     13944941.11
      1910974.98     13945125.04
#Sta/Elev= 30
  4610.7  1832.9  4614.1  1832.9  4617.8 1830.09  4624.6 1829.33  4646.1 1821.87
  4667.1 1817.75  4681.3 1811.77  4688.7 1807.19  4702.8 1802.63  4744.3 1793.36
  4780.5 1789.36  4794.7 1786.15  4815.7 1786.86  4823.1 1783.54  4837.2 1784.77
  4858.2 1782.06  4893.9 1780.97  4922.3 1777.89  4957.5 1777.48  4964.4 1779.63
  4985.8 1778.58  4992.6 1779.95    5000  1779.2  5008.5 1780.24  5014.6 1778.41
    5034 1777.25  5034.2 1776.75    5038 1777.25  5072.8 1780.49  5218.3 1787.85
#Mann= 4 ,-1 , 0
  4610.7     .07       0  4744.3    .035       0    5034    .035       0
    5038    .035       0
Bank Sta=5034,5038
XS Rating Curve= 0 ,0
Exp/Cntr=0.3,0.1

Type RM Length L Ch R = 1 ,954     ,459,459,459
BEGIN DESCRIPTION:
Stream0490 1.1
END DESCRIPTION:
XS GIS Cut Line= 3
      1911368.69     13944623.33      1911101.13     13944819.25
      1910943.95     13945043.91
#Sta/Elev= 30
  4608.4 1833.75  4613.8 1833.75  4619.4 1829.29  4625.6 1829.35  4634.1 1825.81
  4640.3 1825.54  4648.7 1822.21  4654.9 1822.16  4669.6 1816.07  4746.6 1796.35
  4790.8 1789.42  4805.5 1785.06  4826.3 1784.99    4841 1782.02  4848.5 1784.27
  4879.8 1780.84  4920.5 1776.69    4940 1777.76  4947.6 1780.08  4973.9 1775.72
    5011 1774.02  5011.2 1773.52    5015 1774.02  5056.9  1775.8  5069.6 1777.41
  5078.4  1780.3  5084.5 1780.57  5105.7 1777.37  5142.3 1780.98  5214.2 1783.89
#Mann= 6 ,-1 , 0
  4608.4     .07       0  4746.6    .035       0  4879.8     .07       0
  4973.9    .035       0    5011    .035       0    5015    .035       0
Bank Sta=5011,5015
XS Rating Curve= 0 ,0
Exp/Cntr=0.3,0.1

Type RM Length L Ch R = 1 ,495     ,380,380,380
BEGIN DESCRIPTION:
Stream0490 1.0
END DESCRIPTION:
XS GIS Cut Line= 3
      1911024.99     13944375.01        1910725.       13944575.
        1910725.     13945024.95
#Sta/Elev= 30
  4639.7 1781.28  4662.2 1779.38  4675.7 1778.86  4683.3  1777.1  4689.3 1777.24
  4698.3  1775.7  4719.3 1774.04  4725.3 1774.11  4740.3 1777.32  4747.9 1776.14
  4755.4 1773.37  4776.4 1772.72  4787.9 1771.41  4833.5 1769.91  4878.6 1767.37
  4920.6  1767.2  4964.2 1765.14  4977.7 1765.61  4995.2 1763.97  4995.5 1763.47
  4999.2 1763.97  5018.3 1765.01  5080.2 1767.02    5099    1767  5221.5    1771
  5270.2 1772.88  5300.2 1774.95  5360.2 1776.16  5430.2 1779.59  5450.2 1779.71
#Mann= 8 ,-1 , 0
  4639.7    .035       0  4662.2     .07       0  4787.9    .035       0
  4995.2    .035       0  4999.2    .035       0  5018.3     .07       0
    5099    .035       0  5221.5     .07       0
Bank Sta=4995.2,4999.2
XS Rating Curve= 0 ,0
Exp/Cntr=0.3,0.1

Type RM Length L Ch R = 1 ,115     ,0,0,0
BEGIN DESCRIPTION:
Stream0490 0.0
END DESCRIPTION:
XS GIS Cut Line= 4
      1910756.76      13944194.3      1910558.74     13944258.35
      1910441.17     13944364.41      1910432.01       13944640.
#Sta/Elev= 30
  4721.2 1766.55  4724.8 1766.55  4739.3 1765.18  4776.5  1764.8  4796.6 1763.49
  4803.3 1762.56  4835.3 1761.31  4867.3 1760.84  4872.6 1761.21  4899.3 1759.21
  4904.6 1759.34  4943.9 1757.87  4986.5 1757.49  4993.2  1756.7  4998.7 1755.56
  4998.9 1755.06  5002.4 1755.06  5002.7 1755.56  5014.9 1756.87    5050 1756.82
  5056.8 1757.38    5071 1757.67  5123.1 1757.85  5168.3    1759  5188.3 1759.04
  5218.3 1760.35  5228.3 1760.19  5268.4 1761.61  5278.4  1761.4  5363.4 1764.82
#Mann= 3 ,-1 , 0
  4721.2    .035       0  4998.7    .035       0  5002.7    .035       0
Bank Sta=4998.7,5002.7
XS Rating Curve= 0 ,0
Exp/Cntr=0.3,0.1

Chan Stop Cuts=-1
Use User Specified Reach Order=0
Composite Channel Slope=5