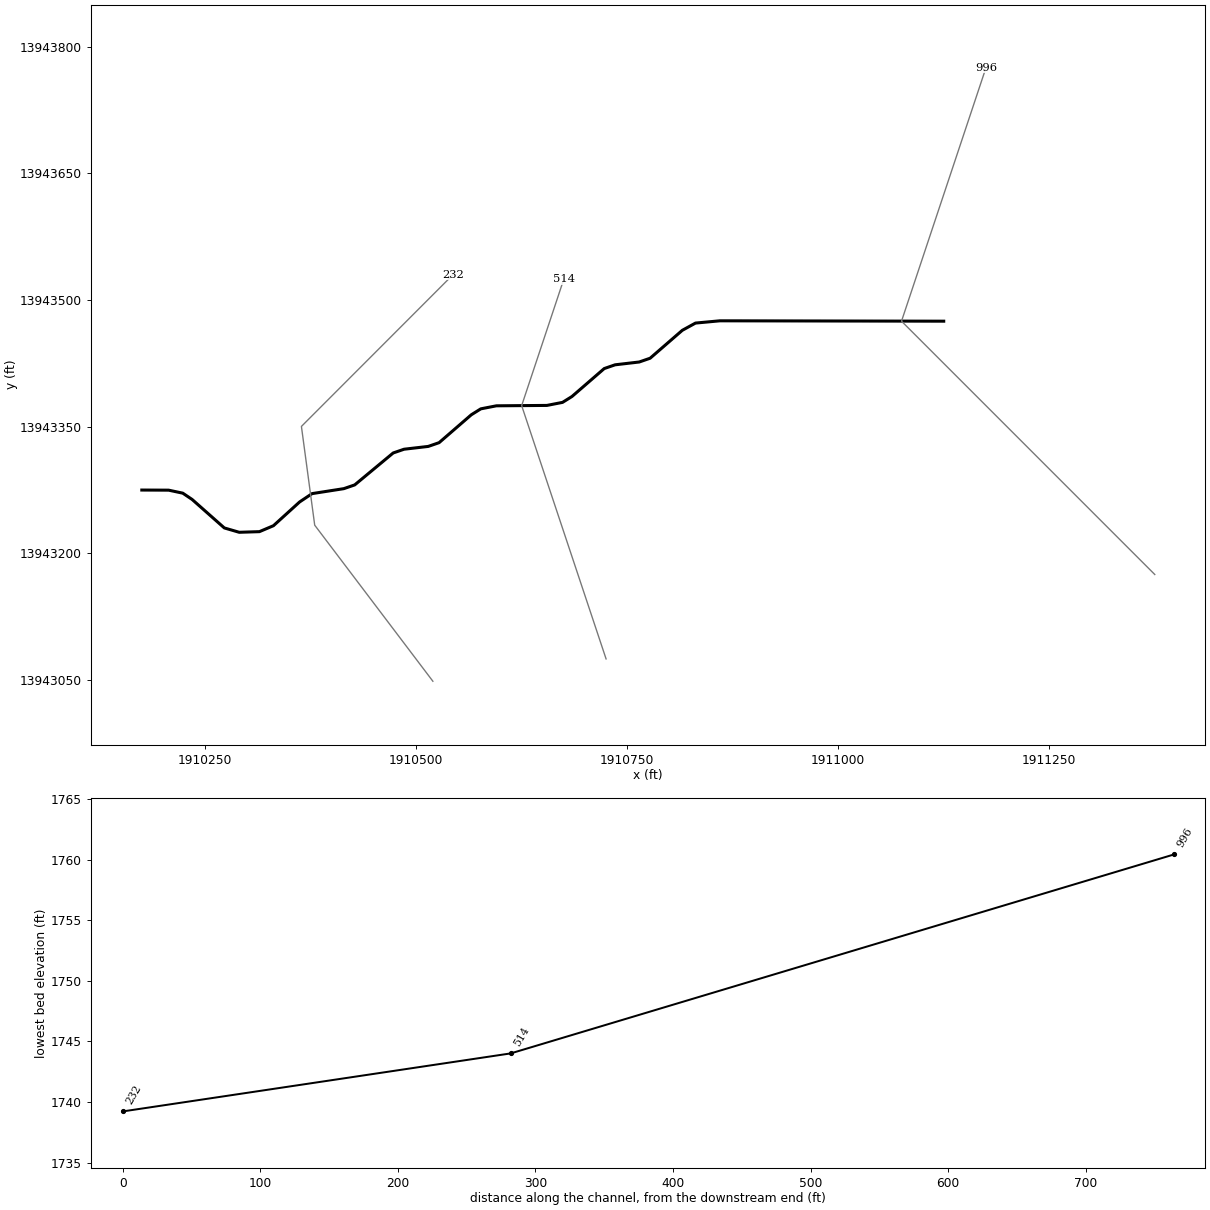
--- Stream0491.prj (project) ---

Proj Title=Stream0491 Base Level Engineering
Current Plan=p01
Default Exp/Contr=0.3,0.1
English Units
Geom File=g01
Flow File=f01
Plan File=p01
BEGIN DESCRIPTION:
Stream0491
END DESCRIPTION:

--- Stream0491.p01 (plan) ---

Plan Title=Multiple Run
Short Identifier=Multiple
Geom File=g01
Flow File=f01
Subcritical Flow
K Sum by GR= 0
Std Step Tol= 0.01
Critical Tol= 0.01
Num of Std Step Trials= 20
Max Error Tol= 0.3
Flow Tol Ratio= 0.001
Split Flow NTrial= 30
Split Flow Tol= 0.02
Split Flow Ratio= 0.02
Log Output Level= 0
Friction Slope Method= 1
Unsteady Friction Slope Method= 2
Unsteady Bridges Friction Slope Method= 1
Parabolic Critical Depth
Global Vel Dist=  1 , 1 , 1
Global Log Level= 0
CheckData=True
Encroach Param= -1, 0, 0, 0
BEGIN DESCRIPTION:
Multiple Run
END DESCRIPTION:

--- Stream0491.f01 (steady flow) ---

Flow Title=Multiple
Number of Profiles=7
Profile Names=10-year,25-year,50-year,1pct_min,100-year,1pct_plu,500-year
River Rch & RM= Stream0491,Reach-1,996
     691    1146    1569    1042    2079    4149    3596
Boundary for River Rch & Prof#=Stream0491,Reach-1,1
Up Type=0
Dn Type=3
Dn Slope=0.005
Boundary for River Rch & Prof#=Stream0491,Reach-1,2
Up Type=0
Dn Type=3
Dn Slope=0.005
Boundary for River Rch & Prof#=Stream0491,Reach-1,3
Up Type=0
Dn Type=3
Dn Slope=0.005
Boundary for River Rch & Prof#=Stream0491,Reach-1,4
Up Type=0
Dn Type=3
Dn Slope=0.005
Boundary for River Rch & Prof#=Stream0491,Reach-1,5
Up Type=0
Dn Type=3
Dn Slope=0.005
Boundary for River Rch & Prof#=Stream0491,Reach-1,6
Up Type=0
Dn Type=3
Dn Slope=0.005
Boundary for River Rch & Prof#=Stream0491,Reach-1,7
Up Type=0
Dn Type=3
Dn Slope=0.005

--- Stream0491.g01 (geometry) ---

Geom Title=Existing Conditions

River Reach=Stream0491,Reach-1
Reach XY= 30
      1911125.00     13943475.00      1910859.82     13943475.44
      1910830.93     13943472.76      1910815.33     13943464.20
      1910777.18     13943431.12      1910764.31     13943426.67
      1910735.69     13943423.33      1910722.82     13943418.89
      1910684.65     13943385.84      1910673.42     13943378.83
      1910654.90     13943375.23      1910595.10     13943374.77
      1910576.58     13943371.17      1910565.35     13943364.16
      1910527.18     13943331.12      1910514.31     13943326.67
      1910485.68     13943323.35      1910472.80     13943318.92
      1910427.20     13943281.08      1910414.31     13943276.65
      1910376.72     13943270.78      1910361.93     13943260.89
      1910330.94     13943232.76      1910314.32     13943225.72
      1910290.38     13943224.97      1910272.75     13943230.12
      1910234.59     13943263.86      1910223.51     13943271.31
      1910206.81     13943274.86      1910175.00     13943275.00

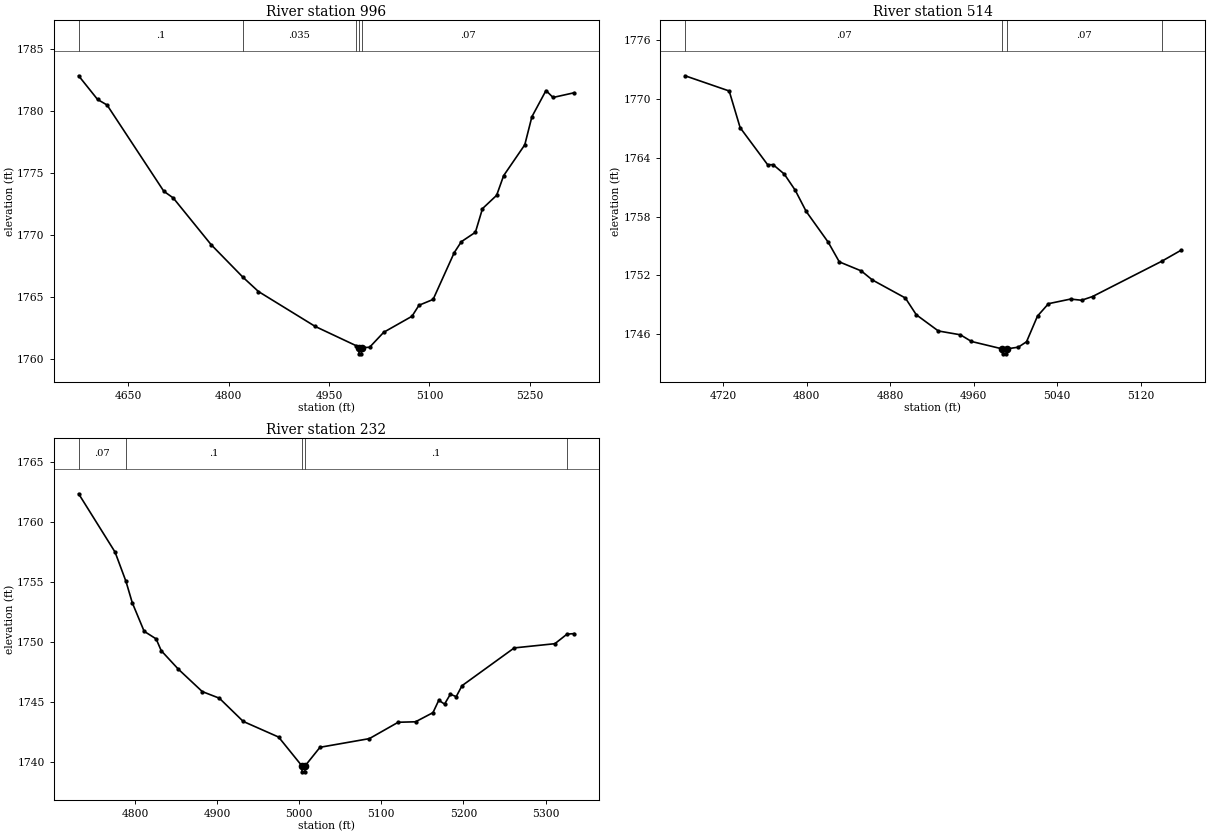
Type RM Length L Ch R = 1,996,482,482,482
BEGIN DESCRIPTION:
Stream0491 2.0
END DESCRIPTION:
XS GIS Cut Line= 3
      1911375.02     13943174.98      1911075.00     13943475.00
      1911174.99     13943774.98
#Sta/Elev= 30
  4575.7 1782.87  4604.0 1780.96  4618.2 1780.51  4703.0 1773.55  4717.1 1773.01
  4773.7 1769.24  4821.3 1766.61  4844.4 1765.46  4929.3 1762.64  4989.9 1761.10
  4994.5 1760.93  4994.7 1760.43  4998.2 1760.43  4998.5 1760.93  5010.5 1760.96
  5031.6 1762.17  5073.8 1763.46  5084.3 1764.35  5105.4 1764.82  5137.0 1768.60
  5147.6 1769.48  5168.6 1770.24  5179.2 1772.15  5200.3 1773.22  5210.8 1774.81
  5242.4 1777.30  5253.0 1779.56  5274.1 1781.68  5284.6 1781.12  5316.2 1781.50
#Mann=5,-1,0
  4575.7     0.1       0  4821.3   0.035       0  4989.9    0.07       0
  4994.5    0.05       0  4998.5    0.07       0
Bank Sta=4994.5,4998.5
Exp/Cntr=0.3,0.1

Type RM Length L Ch R = 1,514,282,282,282
BEGIN DESCRIPTION:
Stream0491 1.0
END DESCRIPTION:
XS GIS Cut Line= 3
      1910725.00     13943075.01      1910625.00     13943375.00
      1910674.99     13943524.97
#Sta/Elev= 30
  4683.8 1772.34  4726.0 1770.79  4736.5 1767.05  4762.8 1763.28  4768.1 1763.28
  4778.7 1762.33  4789.2 1760.68  4799.7 1758.52  4820.8 1755.38  4831.4 1753.38
  4852.4 1752.46  4863.0 1751.54  4894.6 1749.70  4905.1 1747.99  4926.2 1746.34
  4947.3 1745.95  4957.9 1745.27  4987.5 1744.51  4987.7 1744.01  4991.2 1744.01
  4991.5 1744.51  5002.7 1744.69  5010.6 1745.24  5021.1 1747.86  5031.6 1749.12
  5052.7 1749.59  5063.3 1749.47  5073.8 1749.85  5140.3 1753.46  5158.1 1754.54
#Mann=4,-1,0
  4683.8    0.07       0  4987.5    0.05       0  4991.5    0.07       0
  5140.3     0.1       0
Bank Sta=4987.5,4991.5
Exp/Cntr=0.3,0.1

Type RM Length L Ch R = 1,232,0,0,0
BEGIN DESCRIPTION:
Stream0491 0.0
END DESCRIPTION:
XS GIS Cut Line= 4
      1910519.82     13943048.54      1910379.83     13943233.39
      1910364.08     13943350.36      1910543.40     13943529.84
#Sta/Elev= 30
  4731.3 1762.33  4775.7 1757.48  4789.0 1755.04  4796.6 1753.28  4811.1 1750.90
  4825.7 1750.27  4831.9 1749.29  4852.8 1747.75  4881.9 1745.89  4902.7 1745.34
  4931.8 1743.41  4974.9 1742.11  5003.2 1739.72  5003.4 1739.22  5006.9 1739.22
  5007.2 1739.72  5025.3 1741.26  5085.4 1741.98  5120.5 1743.34  5141.7 1743.38
  5162.9 1744.14  5170.0 1745.17  5177.0 1744.85  5184.1 1745.67  5191.2 1745.47
  5198.3 1746.38  5261.9 1749.52  5311.4 1749.87  5326.1 1750.66  5334.9 1750.71
#Mann=5,-1,0
  4731.3    0.07       0  4789.0     0.1       0  5003.2    0.05       0
  5007.2     0.1       0  5326.1    0.07       0
Bank Sta=5003.2,5007.2
Exp/Cntr=0.3,0.1

Chan Stop Cuts=-1