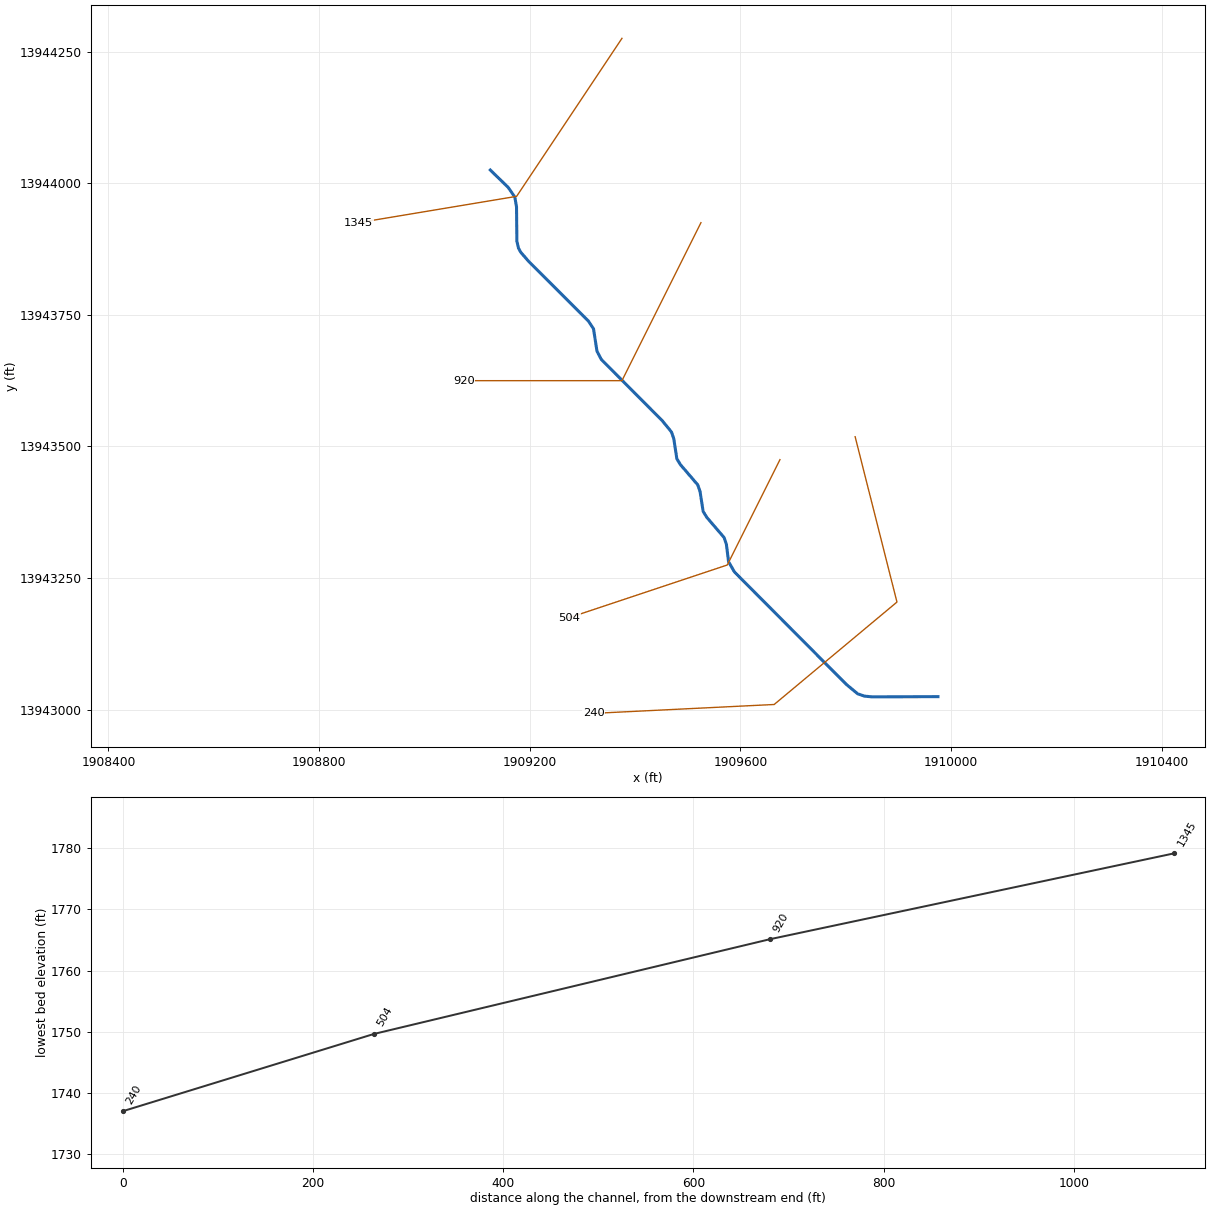
--- Stream0492.prj (project) ---

Proj Title=Stream0492 Base Level Engineering
Current Plan=p01
Default Exp/Contr=0.3,0.1
English Units
Geom File=g01
Flow File=f01
Plan File=p01
BEGIN DESCRIPTION:
Stream0492
END DESCRIPTION:

--- Stream0492.p01 (plan) ---

Plan Title=Multiple Run
Short Identifier=Multiple
Geom File=g01
Flow File=f01
Subcritical Flow
K Sum by GR= 0
Std Step Tol= 0.01
Critical Tol= 0.01
Num of Std Step Trials= 20
Max Error Tol= 0.3
Flow Tol Ratio= 0.001
Split Flow NTrial= 30
Split Flow Tol= 0.02
Split Flow Ratio= 0.02
Log Output Level= 0
Friction Slope Method= 1
Unsteady Friction Slope Method= 2
Unsteady Bridges Friction Slope Method= 1
Parabolic Critical Depth
Global Vel Dist=  1 , 1 , 1
Global Log Level= 0
CheckData=True
Encroach Param= -1, 0, 0, 0
BEGIN DESCRIPTION:
Multiple Run
END DESCRIPTION:

--- Stream0492.f01 (steady flow) ---

Flow Title=Multiple
Number of Profiles=7
Profile Names=10-year,25-year,50-year,1pct_min,100-year,1pct_plu,500-year
River Rch & RM= Stream0492,Reach-1,1345
     441     709     953     622    1242    2477    2073
Boundary for River Rch & Prof#=Stream0492,Reach-1,1
Up Type=0
Dn Type=3
Dn Slope=0.005
Boundary for River Rch & Prof#=Stream0492,Reach-1,2
Up Type=0
Dn Type=3
Dn Slope=0.005
Boundary for River Rch & Prof#=Stream0492,Reach-1,3
Up Type=0
Dn Type=3
Dn Slope=0.005
Boundary for River Rch & Prof#=Stream0492,Reach-1,4
Up Type=0
Dn Type=3
Dn Slope=0.005
Boundary for River Rch & Prof#=Stream0492,Reach-1,5
Up Type=0
Dn Type=3
Dn Slope=0.005
Boundary for River Rch & Prof#=Stream0492,Reach-1,6
Up Type=0
Dn Type=3
Dn Slope=0.005
Boundary for River Rch & Prof#=Stream0492,Reach-1,7
Up Type=0
Dn Type=3
Dn Slope=0.005

--- Stream0492.g01 (geometry) ---

Geom Title=Existing Conditions

River Reach=Stream0492,Reach-1
Reach XY= 30
      1909125.00     13944025.00      1909158.87     13943992.05
      1909171.61     13943973.59      1909174.80     13943954.92
      1909175.47     13943890.19      1909178.58     13943876.48
      1909182.85     13943868.82      1909197.88     13943851.48
      1909311.37     13943738.21      1909321.02     13943723.35
      1909327.54     13943681.05      1909335.78     13943665.32
      1909451.99     13943548.47      1909469.17     13943527.30
      1909473.50     13943514.38      1909479.19     13943476.74
      1909486.10     13943465.46      1909518.92     13943427.20
      1909523.35     13943414.31      1909529.16     13943376.72
      1909536.08     13943365.45      1909568.90     13943327.19
      1909573.30     13943314.30      1909577.50     13943281.03
      1909588.62     13943261.79      1909801.47     13943047.86
      1909822.54     13943030.43      1909835.41     13943025.99
      1909849.84     13943024.62      1909975.00     13943025.00

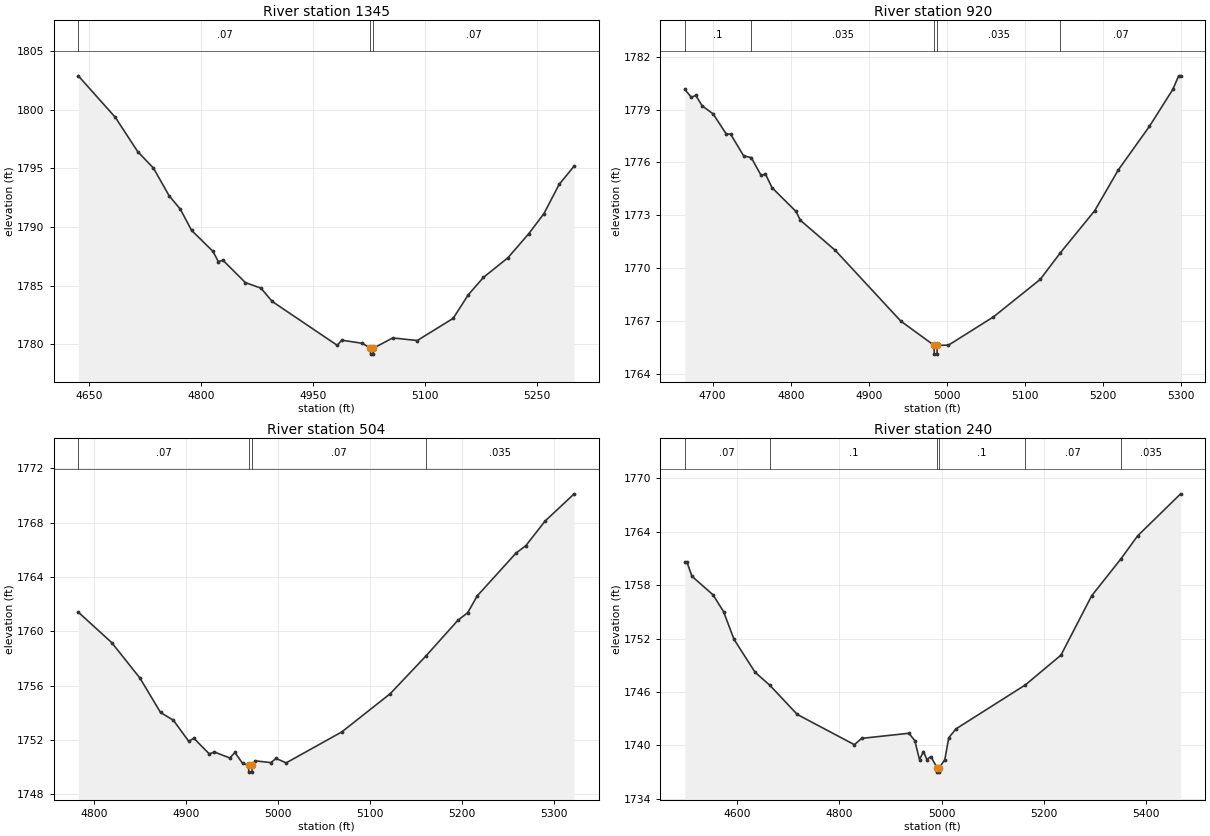
Type RM Length L Ch R = 1,1345,425,425,425
BEGIN DESCRIPTION:
Stream0492 3.0
END DESCRIPTION:
XS GIS Cut Line= 3
      1909375.02     13944275.03      1909175.00     13943975.00
      1908875.03     13943925.01
#Sta/Elev= 30
  4635.6 1802.88  4685.2 1799.34  4715.3 1796.41  4736.3 1795.02  4757.3 1792.66
  4772.3 1791.52  4787.4 1789.71  4815.9 1787.93  4823.4 1787.04  4829.4 1787.17
  4859.5 1785.26  4880.5 1784.78  4895.5 1783.65  4982.7 1779.91  4988.7 1780.35
  5016.5 1780.08  5027.1 1779.66  5027.4 1779.16  5030.9 1779.16  5031.1 1779.66
  5057.0 1780.54  5090.0 1780.32  5138.1 1782.21  5158.4 1784.22  5178.7 1785.70
  5211.6 1787.38  5239.5 1789.43  5259.8 1791.14  5280.1 1793.62  5300.3 1795.19
#Mann=3,-1,0
  4635.6    0.07       0  5027.1    0.05       0  5031.1    0.07       0
Bank Sta=5027.1,5031.1
Exp/Cntr=0.3,0.1

Type RM Length L Ch R = 1,920,416,416,416
BEGIN DESCRIPTION:
Stream0492 2.0
END DESCRIPTION:
XS GIS Cut Line= 3
      1909525.00     13943925.00      1909375.00     13943625.00
      1909075.01     13943625.00
#Sta/Elev= 30
  4664.3 1780.15  4672.7 1779.70  4678.3 1779.81  4686.7 1779.21  4700.6 1778.76
  4717.4 1777.62  4723.0 1777.61  4739.8 1776.37  4749.4 1776.28  4762.1 1775.27
  4767.7 1775.34  4776.1 1774.57  4806.8 1773.22  4812.4 1772.72  4857.2 1771.01
  4941.0 1767.00  4983.7 1765.62  4984.0 1765.12  4987.5 1765.12  4987.7 1765.62
  5002.2 1765.63  5059.7 1767.23  5119.7 1769.36  5145.7 1770.88  5189.7 1773.27
  5219.7 1775.57  5259.7 1778.05  5289.7 1780.15  5297.2 1780.92  5299.7 1780.92
#Mann=5,-1,0
  4664.3     0.1       0  4749.4   0.035       0  4983.7    0.05       0
  4987.7   0.035       0  5145.7    0.07       0
Bank Sta=4983.7,4987.7
Exp/Cntr=0.3,0.1

Type RM Length L Ch R = 1,504,264,264,264
BEGIN DESCRIPTION:
Stream0492 1.0
END DESCRIPTION:
XS GIS Cut Line= 3
      1909675.02     13943475.04      1909575.00     13943275.00
      1909274.98     13943174.99
#Sta/Elev= 30
  4782.4 1761.41  4818.8 1759.17  4849.5 1756.56  4871.9 1754.03  4885.9 1753.46
  4902.6 1751.91  4908.2 1752.13  4925.0 1750.98  4930.6 1751.12  4947.4 1750.68
  4952.9 1751.09  4961.3 1750.28  4967.7 1750.14  4968.0 1749.64  4971.5 1749.64
  4971.7 1750.14  4975.3 1750.47  4992.1 1750.34  4997.7 1750.65  5008.7 1750.32
  5069.3 1752.60  5122.0 1755.41  5160.8 1758.18  5195.8 1760.82  5206.3 1761.37
  5216.9 1762.62  5259.0 1765.76  5269.6 1766.30  5290.7 1768.12  5322.3 1770.12
#Mann=4,-1,0
  4782.4    0.07       0  4967.7    0.05       0  4971.7    0.07       0
  5160.8   0.035       0
Bank Sta=4967.7,4971.7
Exp/Cntr=0.3,0.1

Type RM Length L Ch R = 1,240,0,0,0
BEGIN DESCRIPTION:
Stream0492 0.0
END DESCRIPTION:
XS GIS Cut Line= 4
      1909817.80     13943518.53      1909897.19     13943204.61
      1909664.07     13943010.12      1909320.99     13942993.24
#Sta/Elev= 30
  4497.3 1760.54  4501.7 1760.54  4511.3 1758.99  4552.5 1756.91  4573.1 1755.03
  4593.8 1751.90  4635.0 1748.21  4663.6 1746.77  4717.6 1743.48  4829.4 1740.09
  4843.7 1740.80  4936.1 1741.37  4947.7 1740.54  4956.9 1738.42  4964.7 1739.32
  4971.3 1738.42  4979.1 1738.75  4991.3 1737.51  4991.5 1737.01  4995.0 1737.01
  4995.3 1737.51  5006.4 1738.39  5014.2 1740.87  5028.5 1741.87  5164.2 1746.80
  5233.9 1750.14  5294.0 1756.80  5351.0 1760.92  5384.1 1763.53  5468.2 1768.24
#Mann=6,-1,0
  4497.3    0.07       0  4663.6     0.1       0  4991.3    0.05       0
  4995.3     0.1       0  5164.2    0.07       0  5351.0   0.035       0
Bank Sta=4991.3,4995.3
Exp/Cntr=0.3,0.1

Chan Stop Cuts=-1