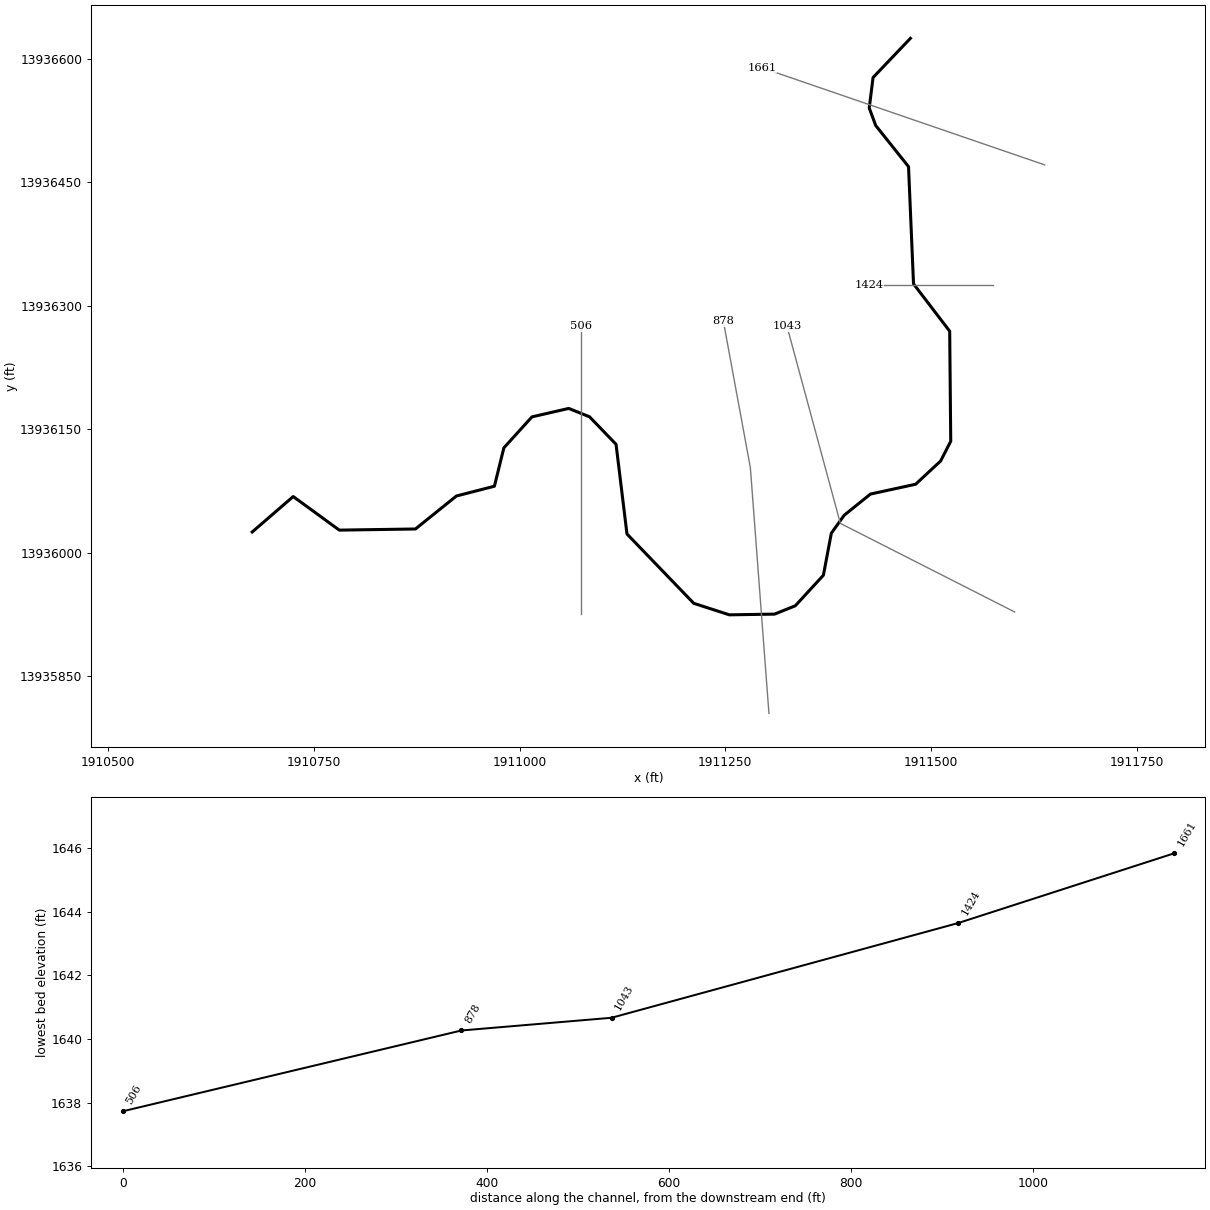
--- Stream0493.prj (project) ---

Proj Title=Stream0493 Base Level Engineering
Current Plan=p01
Default Exp/Contr=0.3,0.1
English Units
Geom File=g01
Flow File=f01
Plan File=p01
BEGIN DESCRIPTION:
Stream0493
END DESCRIPTION:

--- Stream0493.p01 (plan) ---

Plan Title=Multiple Run
Short Identifier=Multiple
Geom File=g01
Flow File=f01
Subcritical Flow
K Sum by GR= 0
Std Step Tol= 0.01
Critical Tol= 0.01
Num of Std Step Trials= 20
Max Error Tol= 0.3
Flow Tol Ratio= 0.001
Split Flow NTrial= 30
Split Flow Tol= 0.02
Split Flow Ratio= 0.02
Log Output Level= 0
Friction Slope Method= 1
Unsteady Friction Slope Method= 2
Unsteady Bridges Friction Slope Method= 1
Parabolic Critical Depth
Global Vel Dist=  1 , 1 , 1
Global Log Level= 0
CheckData=True
Encroach Param= -1, 0, 0, 0
BEGIN DESCRIPTION:
Multiple Run
END DESCRIPTION:

--- Stream0493.f01 (steady flow) ---

Flow Title=Multiple
Number of Profiles=7
Profile Names=10-year,25-year,50-year,1pct_min,100-year,1pct_plu,500-year
River Rch & RM= Stream0493,Reach-1,1661
    1184    2030    2839    1921    3833    7647    6894
Boundary for River Rch & Prof#=Stream0493,Reach-1,1
Up Type=0
Dn Type=3
Dn Slope=0.005
Boundary for River Rch & Prof#=Stream0493,Reach-1,2
Up Type=0
Dn Type=3
Dn Slope=0.005
Boundary for River Rch & Prof#=Stream0493,Reach-1,3
Up Type=0
Dn Type=3
Dn Slope=0.005
Boundary for River Rch & Prof#=Stream0493,Reach-1,4
Up Type=0
Dn Type=3
Dn Slope=0.005
Boundary for River Rch & Prof#=Stream0493,Reach-1,5
Up Type=0
Dn Type=3
Dn Slope=0.005
Boundary for River Rch & Prof#=Stream0493,Reach-1,6
Up Type=0
Dn Type=3
Dn Slope=0.005
Boundary for River Rch & Prof#=Stream0493,Reach-1,7
Up Type=0
Dn Type=3
Dn Slope=0.005

--- Stream0493.g01 (geometry) ---

Geom Title=Existing Conditions

River Reach=Stream0493,Reach-1
Reach XY= 30
      1911475.00     13936625.00      1911429.61     13936577.37
      1911424.97     13936540.33      1911432.83     13936519.06
      1911472.72     13936469.07      1911478.79     13936326.57
      1911522.75     13936269.06      1911524.03     13936135.29
      1911511.78     13936111.33      1911481.36     13936083.03
      1911426.47     13936071.10      1911394.64     13936045.46
      1911378.90     13936023.53      1911369.25     13935972.44
      1911335.10     13935935.30      1911309.91     13935925.18
      1911254.93     13935924.31      1911211.67     13935938.32
      1911130.52     13936022.56      1911117.25     13936131.55
      1911085.03     13936164.99      1911059.73     13936175.19
      1911015.04     13936164.91      1910980.89     13936127.28
      1910969.38     13936080.63      1910923.16     13936068.72
      1910873.44     13936028.66      1910780.88     13936027.27
      1910724.86     13936068.09      1910675.00     13936025.00

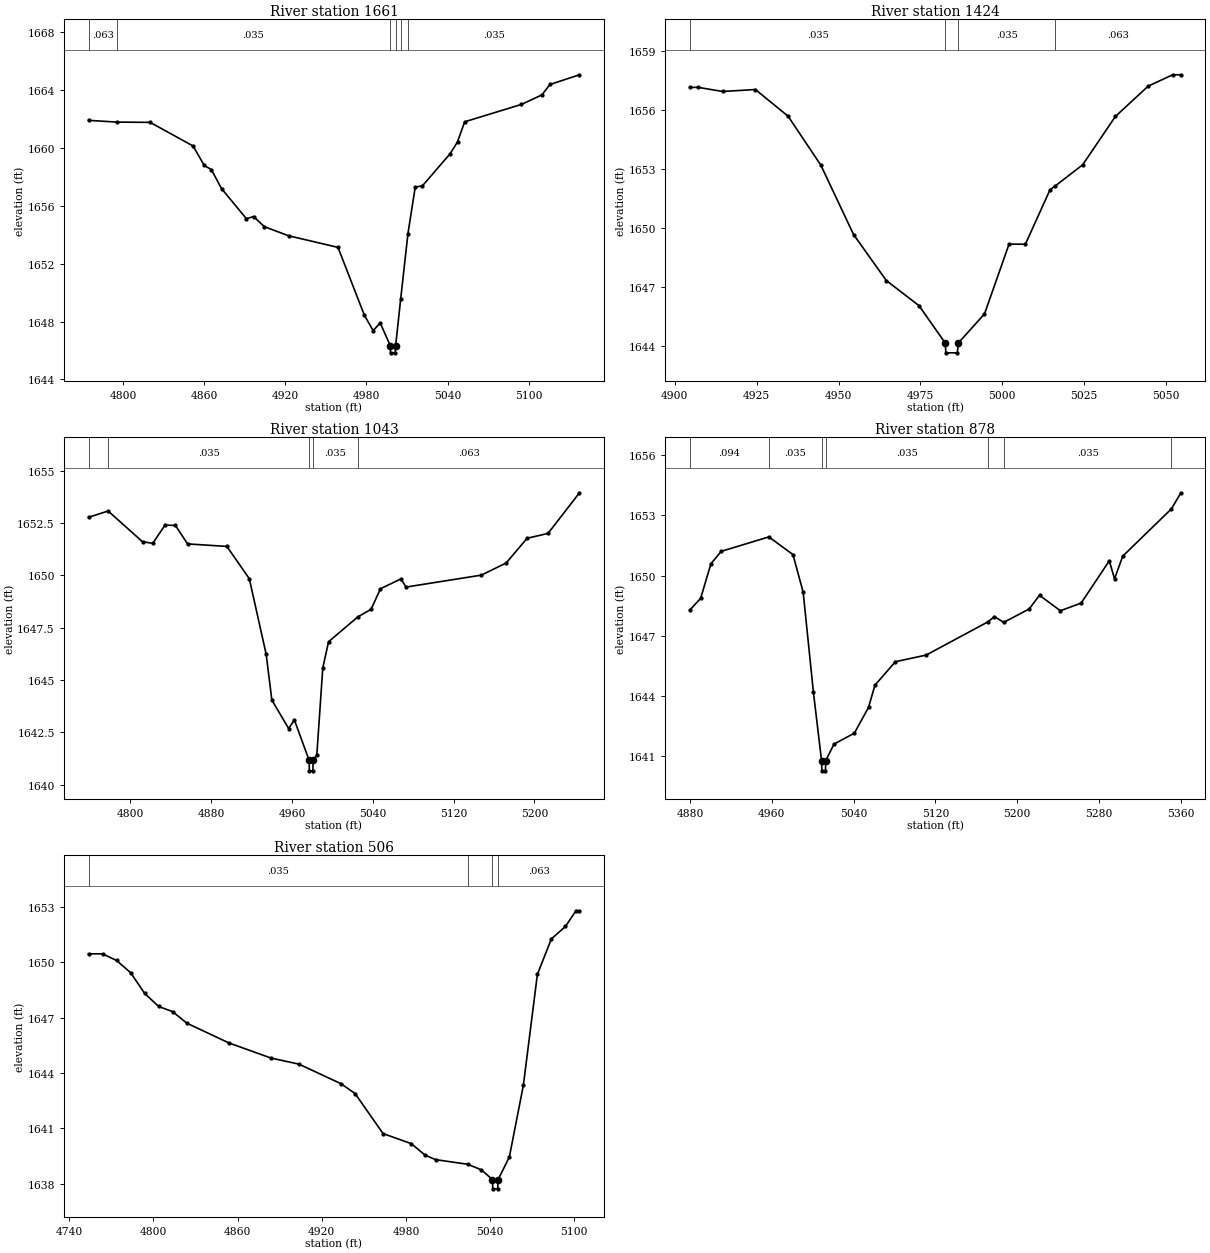
Type RM Length L Ch R = 1,1661,237,237,237
BEGIN DESCRIPTION:
Stream0493 5.0
END DESCRIPTION:
XS GIS Cut Line= 2
      1911638.16     13936471.20      1911294.37     13936589.27
#Sta/Elev= 30
  4774.2 1661.91  4795.0 1661.79  4819.8 1661.77  4851.6 1660.14  4859.9 1658.79
  4865.1 1658.51  4872.7 1657.19  4891.1 1655.11  4896.4 1655.26  4904.4 1654.56
  4922.4 1653.93  4958.9 1653.13  4978.4 1648.45  4984.9 1647.38  4990.2 1647.90
  4997.6 1646.34  4997.8 1645.84  5001.3 1645.84  5001.6 1646.34  5005.3 1649.54
  5010.7 1654.08  5016.1 1657.30  5021.4 1657.38  5041.9 1659.60  5047.4 1660.42
  5052.7 1661.81  5094.7 1663.01  5109.9 1663.67  5115.9 1664.39  5137.7 1665.06
#Mann=6,-1,0
  4774.2   0.063       0  4795.0   0.035       0  4997.6   0.035       0
  5001.6   0.035       0  5005.3   0.063       0  5010.7   0.035       0
Bank Sta=4997.6,5001.6
Exp/Cntr=0.3,0.1

Type RM Length L Ch R = 1,1424,381,381,381
BEGIN DESCRIPTION:
Stream0493 3.0
END DESCRIPTION:
XS GIS Cut Line= 3
      1911574.98     13936325.00      1911475.00     13936325.00
      1911424.98     13936325.00
#Sta/Elev= 23
  4904.6 1657.16  4907.1 1657.16  4914.6 1656.95  4924.6 1657.05  4934.6 1655.69
  4944.6 1653.20  4954.6 1649.67  4964.6 1647.33  4974.6 1646.05  4982.6 1644.15
  4982.8 1643.65  4986.3 1643.65  4986.6 1644.15  4994.6 1645.63  5002.1 1649.18
  5007.1 1649.18  5014.6 1651.94  5016.2 1652.14  5024.6 1653.22  5034.6 1655.68
  5044.6 1657.22  5052.1 1657.80  5054.6 1657.80
#Mann=4,-1,0
  4904.6   0.035       0  4982.6   0.035       0  4986.6   0.035       0
  5016.2   0.063       0
Bank Sta=4982.6,4986.6
Exp/Cntr=0.3,0.1

Type RM Length L Ch R = 1,1043,165,165,165
BEGIN DESCRIPTION:
Stream0493 2.0
END DESCRIPTION:
XS GIS Cut Line= 3
      1911601.69     13935927.80      1911389.88     13936035.45
      1911324.99     13936275.02
#Sta/Elev= 30
  4758.7 1652.77  4778.1 1653.07  4812.2 1651.60  4822.3 1651.53  4834.4 1652.40
  4844.7 1652.38  4856.7 1651.50  4895.6 1651.38  4917.8 1649.84  4934.5 1646.23
  4940.1 1644.05  4956.7 1642.69  4962.4 1643.10  4977.0 1641.17  4977.2 1640.67
  4980.7 1640.67  4981.0 1641.17  4984.6 1641.43  4990.5 1645.58  4996.2 1646.83
  5025.0 1648.01  5038.3 1648.38  5047.6 1649.36  5067.8 1649.83  5072.9 1649.44
  5147.4 1650.01  5172.0 1650.59  5192.7 1651.77  5213.4 1652.00  5244.5 1653.94
#Mann=5,-1,0
  4758.7   0.094       0  4778.1   0.035       0  4977.0   0.035       0
  4981.0   0.035       0  5025.0   0.063       0
Bank Sta=4977,4981
Exp/Cntr=0.3,0.1

Type RM Length L Ch R = 1,878,372,372,372
BEGIN DESCRIPTION:
Stream0493 4.0
END DESCRIPTION:
XS GIS Cut Line= 3
      1911303.07     13935804.54      1911280.50     13936103.15
      1911247.70     13936280.98
#Sta/Elev= 30
  4879.9 1648.29  4890.4 1648.87  4900.4 1650.59  4910.5 1651.21  4957.1 1651.93
  4980.7 1651.05  4990.7 1649.17  5000.7 1644.19  5008.7 1640.77  5009.0 1640.27
  5012.5 1640.27  5012.7 1640.77  5020.8 1641.60  5040.8 1642.15  5054.6 1643.43
  5060.9 1644.54  5080.9 1645.71  5111.0 1646.04  5171.6 1647.70  5177.8 1647.96
  5186.9 1647.67  5211.8 1648.34  5221.9 1649.02  5242.3 1648.25  5262.6 1648.63
  5290.2 1650.74  5295.3 1649.84  5303.3 1650.97  5351.0 1653.33  5360.2 1654.13
#Mann=7,-1,0
  4879.9   0.094       0  4957.1   0.035       0  5008.7   0.035       0
  5012.7   0.035       0  5171.6   0.063       0  5186.9   0.035       0
  5351.0   0.063       0
Bank Sta=5008.7,5012.7
Exp/Cntr=0.3,0.1

Type RM Length L Ch R = 1,506,0,0,0
BEGIN DESCRIPTION:
Stream0493 1.0
END DESCRIPTION:
XS GIS Cut Line= 3
      1911075.00     13935925.01      1911075.00     13936175.00
      1911075.00     13936275.01
#Sta/Elev= 30
  4753.7 1650.45  4763.7 1650.45  4773.7 1650.09  4783.7 1649.43  4793.7 1648.31
  4803.7 1647.60  4813.7 1647.32  4823.7 1646.70  4853.7 1645.63  4883.7 1644.81
  4903.7 1644.48  4933.7 1643.42  4943.7 1642.89  4963.7 1640.72  4983.7 1640.18
  4993.7 1639.55  5001.2 1639.31  5024.0 1639.06  5033.7 1638.76  5041.7 1638.23
  5041.9 1637.73  5045.4 1637.73  5045.7 1638.23  5053.7 1639.45  5063.7 1643.33
  5073.7 1649.34  5083.7 1651.26  5093.7 1651.93  5101.2 1652.78  5103.7 1652.78
#Mann=4,-1,0
  4753.7   0.035       0  5024.0   0.063       0  5041.7   0.035       0
  5045.7   0.063       0
Bank Sta=5041.7,5045.7
Exp/Cntr=0.3,0.1

Chan Stop Cuts=-1