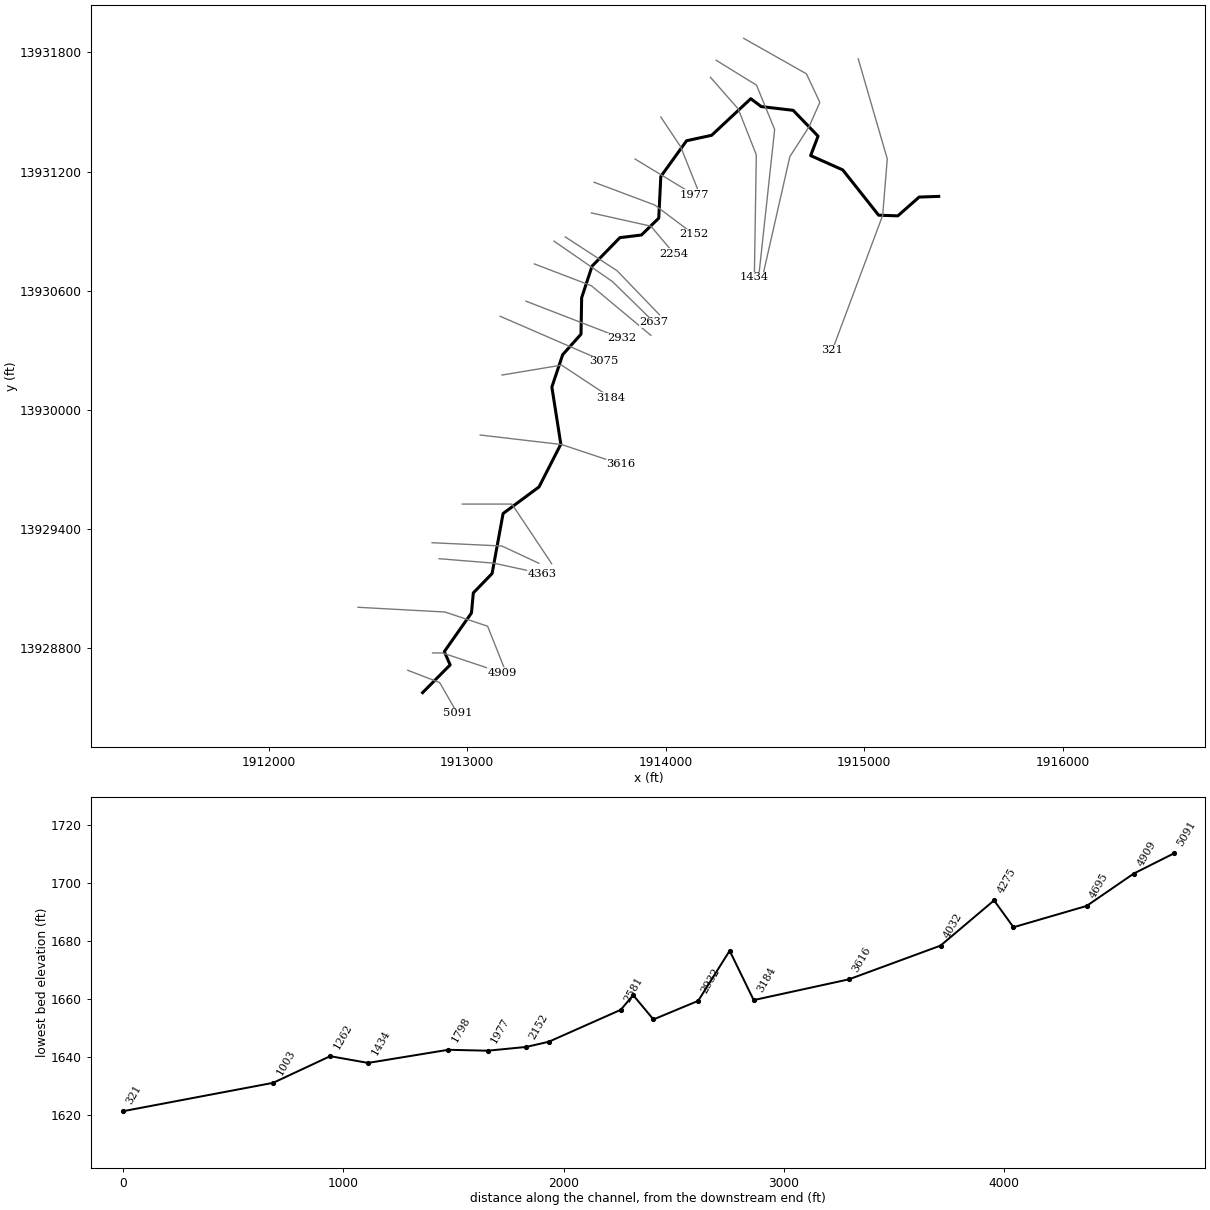
--- Stream0495.prj (project) ---

Proj Title=Stream0495 Base Level Engineering
Current Plan=p01
Default Exp/Contr=0.3,0.1
English Units
Geom File=g01
Flow File=f01
Plan File=p01
Y Axis Title=Elevation
X Axis Title(PF)=Main Channel Distance
X Axis Title(XS)=Station
BEGIN DESCRIPTION:
Stream0495
END DESCRIPTION:
DSS Export Rating Curves= 0
DSS Export Rating Curve Sorted= 0
DSS Export Volume Flow Curves= 0
DXF OffsetX= 0
DXF OffsetY= 0
DXF ScaleX= 1
DXF ScaleY= 10

--- Stream0495.p01 (plan) ---

Plan Title=Multiple Run
Short Identifier=Multiple
Geom File=g01
Flow File=f01
Subcritical Flow
K Sum by GR= 0
Std Step Tol= 0.01
Critical Tol= 0.01
Num of Std Step Trials= 20
Max Error Tol= 0.3
Flow Tol Ratio= 0.001
Split Flow NTrial= 30
Split Flow Tol= 0.02
Split Flow Ratio= 0.02
Log Output Level= 0
Friction Slope Method= 1
Unsteady Friction Slope Method= 2
Unsteady Bridges Friction Slope Method= 1
Parabolic Critical Depth
Global Vel Dist=  1 , 1 , 1
Global Log Level= 0
CheckData=True
Encroach Param= -1, 0, 0, 0
BEGIN DESCRIPTION:
Multiple Run
END DESCRIPTION:

--- Stream0495.f01 (steady flow) ---

Flow Title=Multiple
Number of Profiles=7
Profile Names=10-year,25-year,50-year,1pct_min,100-year,1pct_plu,500-year
River Rch & RM= Stream0495,Reach-1,5091
     757    1270    1754    1175    2345    4678    4128
River Rch & RM= Stream0495,Reach-1,4363
    1244    2153    3033    2068    4127    8235    7538
River Rch & RM= Stream0495,Reach-1,1977
    1450    2527    3575    2447    4882    9741    8988
Boundary for River Rch & Prof#=Stream0495,Reach-1,1
Up Type=0
Dn Type=3
Dn Slope=0.005
Boundary for River Rch & Prof#=Stream0495,Reach-1,2
Up Type=0
Dn Type=3
Dn Slope=0.005
Boundary for River Rch & Prof#=Stream0495,Reach-1,3
Up Type=0
Dn Type=3
Dn Slope=0.005
Boundary for River Rch & Prof#=Stream0495,Reach-1,4
Up Type=0
Dn Type=3
Dn Slope=0.005
Boundary for River Rch & Prof#=Stream0495,Reach-1,5
Up Type=0
Dn Type=3
Dn Slope=0.005
Boundary for River Rch & Prof#=Stream0495,Reach-1,6
Up Type=0
Dn Type=3
Dn Slope=0.005
Boundary for River Rch & Prof#=Stream0495,Reach-1,7
Up Type=0
Dn Type=3
Dn Slope=0.005

--- Stream0495.g01 (geometry) ---

Geom Title=Existing Conditions
Program Version=4.10

River Reach=Stream0495      ,Reach-1
Reach XY= 30
        1912775.       13928575.      1912913.77       13928715.
      1912884.32     13928781.66      1913021.17     13928976.58
      1913030.46     13929077.45        1913125.       13929175.
      1913180.52     13929477.44      1913361.53     13929611.43
      1913471.33     13929826.58       1913426.2     13930114.49
      1913480.54     13930277.42      1913572.93     13930380.86
      1913576.22      13930564.5      1913628.61      13930723.5
      1913768.83     13930867.14      1913877.44     13930880.52
      1913964.54     13930965.17        1913975.       13931175.
       1914104.8     13931355.39      1914231.17     13931382.86
      1914428.21     13931567.13      1914480.86     13931527.48
      1914641.77     13931508.57      1914767.17     13931378.39
      1914729.79     13931280.59      1914891.68     13931208.36
      1915072.33     13930980.29       1915169.1     13930976.97
      1915276.41     13931071.61        1915375.       13931075.

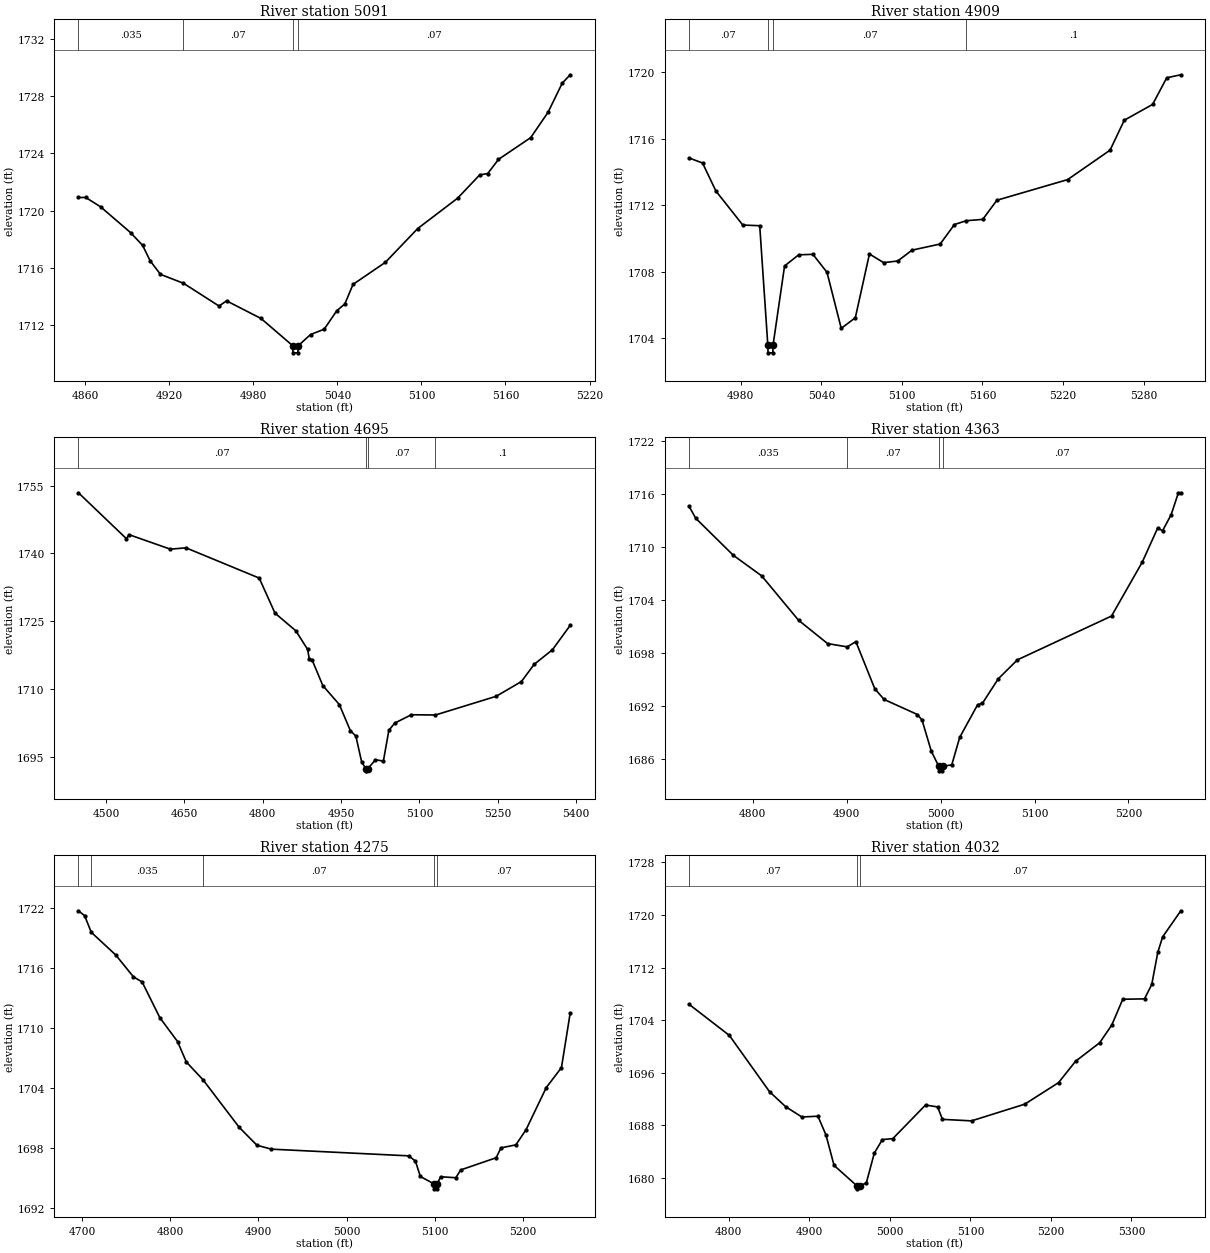
Type RM Length L Ch R = 1 ,5091    ,182,182,182
BEGIN DESCRIPTION:
Stream0495 12.0
END DESCRIPTION:
XS GIS Cut Line= 3
      1912700.29      13928687.7      1912861.03     13928625.62
      1912950.32      13928470.6
#Sta/Elev= 30
    4855 1720.91  4860.2 1720.91  4870.8 1720.26  4892.2 1718.46  4900.8 1717.57
  4906.2 1716.49  4913.6 1715.54    4930 1714.92  4955.4 1713.33  4960.8 1713.69
  4985.4 1712.46    5008 1710.56  5008.2 1710.06  5011.7 1710.06    5012 1710.56
  5020.8 1711.34  5030.5 1711.71  5039.5    1713  5045.3 1713.48  5051.1 1714.84
  5074.2 1716.38  5097.3 1718.74  5125.8 1720.86  5141.6 1722.49  5147.3 1722.58
    5155 1723.57    5178 1725.09  5190.4 1726.86  5200.5 1728.89  5206.2 1729.48
#Mann= 4 ,-1 , 0
    4855    .035       0    4930     .07       0    5008     .05       0
    5012     .07       0
Bank Sta=5008,5012
XS Rating Curve= 0 ,0
Exp/Cntr=0.3,0.1

Type RM Length L Ch R = 1 ,4909    ,214,214,214
BEGIN DESCRIPTION:
Stream0495 11.0
END DESCRIPTION:
XS GIS Cut Line= 3
      1912824.99       13928775.        1912875.       13928775.
      1913174.96     13928675.01
#Sta/Elev= 30
  4941.5 1714.84  4951.5 1714.54  4961.5 1712.85  4981.5 1710.81  4994.1 1710.77
  5000.1 1703.63  5000.3 1703.13  5003.8 1703.13  5004.1 1703.63  5012.6 1708.35
  5023.1 1709.02  5033.7 1709.05  5044.2 1707.97  5054.8  1704.6  5065.3 1705.24
  5075.8 1709.07  5086.4 1708.55  5096.9 1708.65  5107.5  1709.3  5128.5 1709.67
  5139.1 1710.84  5147.9 1711.07  5160.2 1711.15  5170.7  1712.3  5223.4 1713.54
    5255 1715.31  5265.6 1717.11  5286.7 1718.06  5297.2 1719.66  5307.7 1719.84
#Mann= 4 ,-1 , 0
  4941.5     .07       0  5000.1     .05       0  5004.1     .07       0
  5147.9      .1       0
#XS Ineff= 2 , 0
                         5025.87         1708.97
Permanent Ineff=
       F       F
Bank Sta=5000.1,5004.1
XS Rating Curve= 0 ,0
Exp/Cntr=0.3,0.1

Type RM Length L Ch R = 1 ,4695    ,332,332,332
BEGIN DESCRIPTION:
Stream0495 10.1
END DESCRIPTION:
XS GIS Cut Line= 4
      1912449.48     13929005.05      1912887.45      13928981.2
      1913102.46     13928909.71       1913204.5     13928653.38
#Sta/Elev= 30
  4447.4  1753.4  4539.2 1743.26  4544.2 1744.15  4623.2 1740.95  4653.2 1741.24
  4793.4 1734.56  4823.5 1726.83  4863.5 1722.91    4886 1718.81  4889.3  1716.6
  4894.5 1716.51  4915.1 1710.82  4946.7 1706.63  4967.7 1700.89  4978.3 1699.67
  4989.5 1693.92  4997.4 1692.49  4997.6 1691.99  5001.4 1692.49  5015.9 1694.44
    5031 1694.14  5041.5 1700.94  5052.8 1702.54  5084.5 1704.38  5130.6 1704.32
  5246.8 1708.45  5295.2 1711.71  5319.5  1715.5  5354.6 1718.74  5388.5 1724.11
#Mann= 4 ,-1 , 0
  4447.4     .07       0  4997.4     .05       0  5001.4     .07       0
  5130.6      .1       0
Bank Sta=4997.4,5001.4
XS Rating Curve= 0 ,0
Exp/Cntr=0.3,0.1

Type RM Length L Ch R = 1 ,4363    ,88,88,88
BEGIN DESCRIPTION:
Stream0495 10.0
END DESCRIPTION:
XS GIS Cut Line= 3
      1912857.95     13929249.81      1913133.32     13929227.32
      1913375.04     13929174.99
#Sta/Elev= 30
  4732.2 1714.61  4739.3 1713.26  4779.4 1709.06  4809.5 1706.74  4848.7 1701.72
  4879.7 1699.07  4900.6  1698.7  4909.8 1699.29  4929.9 1693.96  4939.9 1692.74
  4975.3 1691.04  4980.3 1690.39  4990.1 1686.89  4998.1 1685.16  4998.4 1684.66
  5001.9 1684.66  5002.1 1685.16  5011.9 1685.34  5020.4 1688.46  5039.4 1692.14
  5044.6 1692.32  5061.4 1695.08  5081.8 1697.23    5182 1702.19  5214.8 1708.31
  5231.2 1712.17  5236.3 1711.84  5245.5 1713.67  5253.2 1716.15  5255.8 1716.15
#Mann= 4 ,-1 , 0
  4732.2    .035       0  4900.6     .07       0  4998.1     .05       0
  5002.1     .07       0
Bank Sta=4998.1,5002.1
XS Rating Curve= 0 ,0
Exp/Cntr=0.3,0.1

Type RM Length L Ch R = 1 ,4275    ,243,243,243
BEGIN DESCRIPTION:
Mapping XS 6c2e7216
END DESCRIPTION:
XS GIS Cut Line= 3
      1912822.76     13929330.32      1913173.94     13929313.85
      1913360.86     13929226.71
#Sta/Elev= 30
  4695.9 1721.72    4703 1721.22  4710.4 1719.57  4738.2  1717.3  4758.2 1715.12
  4768.2 1714.59  4788.2 1711.03  4808.3 1708.64  4818.3 1706.59  4837.2 1704.81
  4878.3 1700.05  4898.4 1698.26  4914.8 1697.87  5070.7  1697.2  5078.2 1696.67
  5083.7 1695.14  5099.1  1694.4  5099.3  1693.9  5102.8  1693.9  5103.1  1694.4
  5106.6 1695.11    5124 1695.01  5129.5 1695.79  5169.7 1697.01  5175.2    1698
  5192.1  1698.3  5203.6 1699.81  5226.5 1704.02  5243.8 1706.03  5253.7 1711.48
#Mann= 5 ,-1 , 0
  4695.9     .07       0  4710.4    .035       0  4837.2     .07       0
  5099.1     .05       0  5103.1     .07       0
Bank Sta=5099.1,5103.1
XS Rating Curve= 0 ,0
Exp/Cntr=0.3,0.1

Type RM Length L Ch R = 1 ,4032    ,416,416,416
BEGIN DESCRIPTION:
Stream0495 9.0
END DESCRIPTION:
XS GIS Cut Line= 3
      1912974.99       13929525.        1913225.       13929525.
      1913425.02     13929224.97
#Sta/Elev= 30
  4750.7 1706.41  4800.7 1701.68  4850.7  1693.1  4870.7 1690.83  4890.7 1689.27
  4910.7 1689.39  4920.7 1686.52  4930.7 1681.91  4958.7 1678.84    4959 1678.34
  4962.7 1678.84  4970.7 1679.21  4980.7 1683.78  4990.7 1685.83  5003.7 1685.98
  5044.3 1691.09  5059.3  1690.8  5065.3 1688.91  5101.4 1688.68  5167.5 1691.22
  5209.5  1694.5  5230.6 1697.75  5260.6 1700.57  5275.6 1703.27  5289.2 1707.18
  5316.2 1707.24  5325.2 1709.43  5332.7 1714.32  5338.7 1716.67  5361.3 1720.64
#Mann= 3 ,-1 , 0
  4750.7     .07       0  4958.7     .05       0  4962.7     .07       0
#XS Ineff= 2 , 0
                         5044.06         1690.72
Permanent Ineff=
       F       F
Bank Sta=4958.7,4962.7
XS Rating Curve= 0 ,0
Exp/Cntr=0.3,0.1

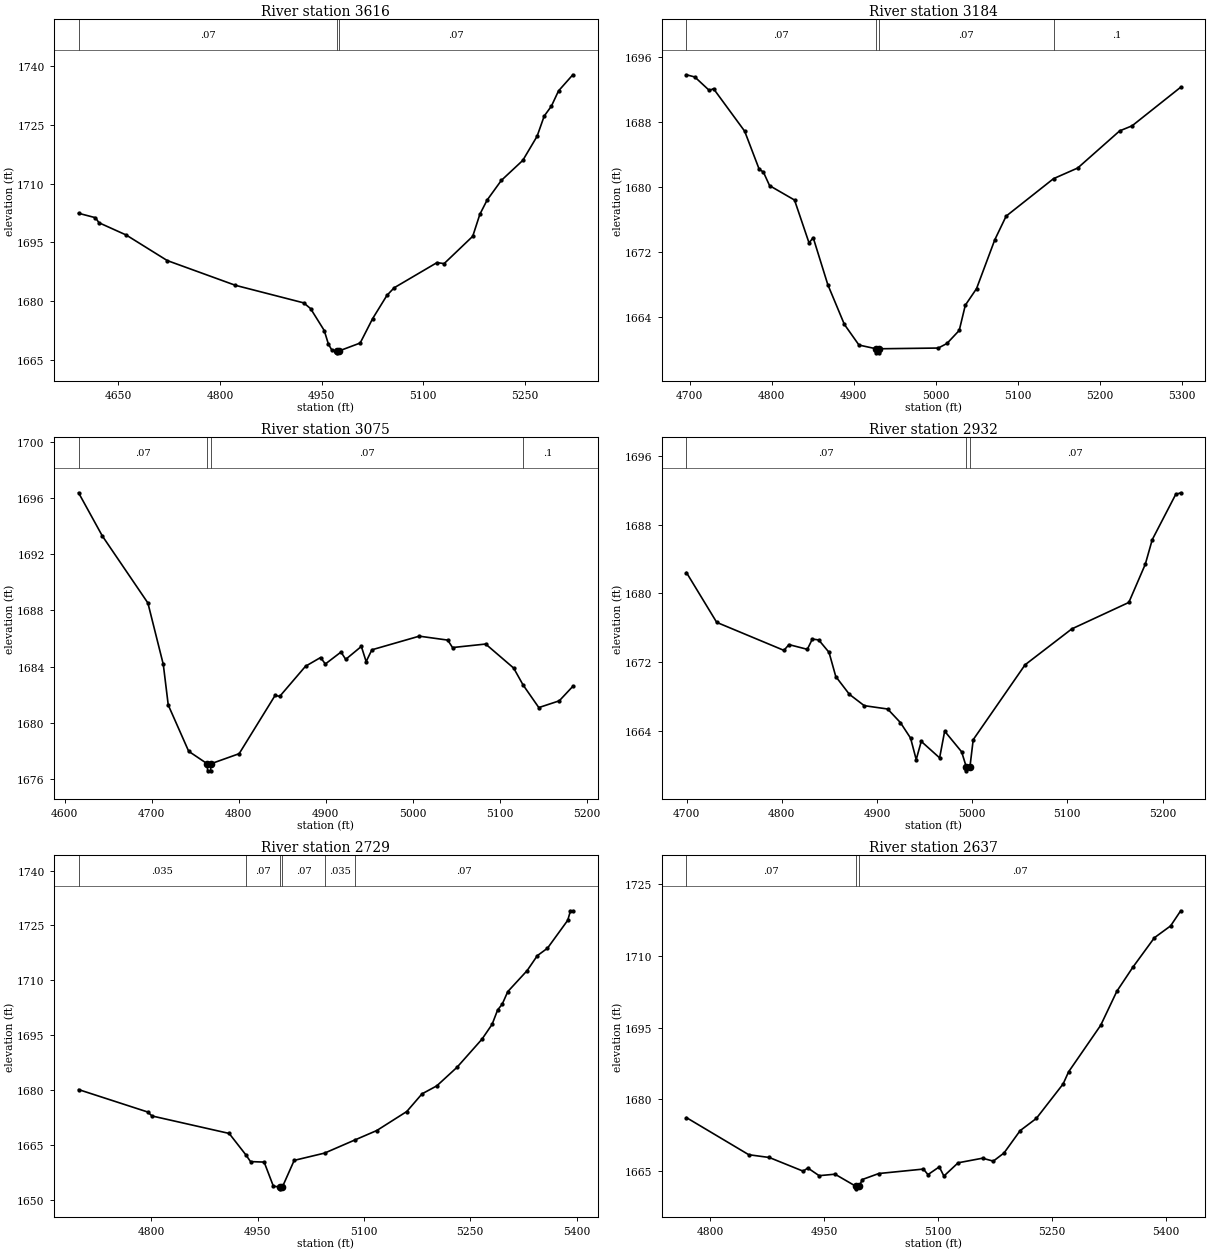
Type RM Length L Ch R = 1 ,3616    ,432,432,432
BEGIN DESCRIPTION:
Stream0495 8.0
END DESCRIPTION:
XS GIS Cut Line= 3
      1913065.13     13929872.87        1913475.       13929825.
      1913775.02     13929724.99
#Sta/Elev= 30
  4591.6 1702.42  4616.5 1701.29  4621.7    1700  4661.9 1696.86  4722.4 1690.33
    4823    1684  4923.7 1679.51  4933.8 1678.04  4953.9 1672.45    4960    1669
  4965.1 1667.44    4972 1667.24  4972.3 1666.74    4976 1667.24  5006.9 1669.25
  5025.3  1675.5  5046.4 1681.44    5057 1683.37  5120.2 1689.81  5130.7 1689.55
  5172.9 1696.54  5183.4 1702.16    5194 1705.77  5215.1 1710.83  5246.7 1715.94
  5267.8 1722.11  5278.3 1727.28  5288.9 1729.81  5299.4 1733.71  5320.5 1737.83
#Mann= 3 ,-1 , 0
  4591.6     .07       0    4972     .05       0    4976     .07       0
Bank Sta=4972,4976
XS Rating Curve= 0 ,0
Exp/Cntr=0.3,0.1

Type RM Length L Ch R = 1 ,3184    ,109,109,109
BEGIN DESCRIPTION:
Stream0495 7.0
END DESCRIPTION:
XS GIS Cut Line= 3
      1913174.99       13930175.        1913475.       13930225.
      1913724.21     13930060.43
#Sta/Elev= 30
  4695.9 1693.81  4706.1 1693.54  4723.8 1691.88  4728.9  1692.1  4766.9 1686.87
  4784.6 1682.19  4789.7 1681.85  4797.3 1680.17  4827.7  1678.4  4845.4 1673.13
  4850.5 1673.77  4868.3 1667.99  4888.5  1663.1  4906.3 1660.56  4927.1  1660.1
  4927.3  1659.6  4930.8  1659.6  4931.1  1660.1    5003 1660.19  5013.6 1660.75
  5028.6 1662.36    5036 1665.46  5049.7  1667.5    5072 1673.52  5085.8 1676.42
  5143.6 1681.03  5173.1 1682.34  5224.3 1686.91  5239.4 1687.53  5298.7 1692.28
#Mann= 4 ,-1 , 0
  4695.9     .07       0  4927.1     .05       0  4931.1     .07       0
  5143.6      .1       0
Bank Sta=4927.1,4931.1
XS Rating Curve= 0 ,0
Exp/Cntr=0.3,0.1

Type RM Length L Ch R = 1 ,3075    ,143,143,143
BEGIN DESCRIPTION:
Mapping XS 753bc27f
END DESCRIPTION:
XS GIS Cut Line= 2
      1913165.67     13930471.17      1913686.88      13930244.9
#Sta/Elev= 30
  4615.9 1696.36  4643.2 1693.29  4695.6 1688.52  4713.3 1684.15    4719 1681.26
  4742.5 1677.97  4763.9 1677.08  4764.2 1676.58  4767.7 1676.58  4767.9 1677.08
  4800.5  1677.8  4841.8 1681.94  4847.2 1681.88  4876.8 1684.02  4894.1 1684.64
  4899.6 1684.18  4917.6 1685.03    4923 1684.51    4941 1685.43  4946.5 1684.35
  4953.1 1685.19  5007.6 1686.16  5040.3 1685.88  5045.8 1685.35  5083.9  1685.6
  5116.1 1683.89  5126.9 1682.69    5145 1681.08  5168.5 1681.56  5184.1 1682.59
#Mann= 4 ,-1 , 0
  4615.9     .07       0  4763.9     .05       0  4767.9     .07       0
  5126.9      .1       0
#Block Obstruct= 2 , 0
                         5083.72         1685.28
Bank Sta=4763.9,4767.9
XS Rating Curve= 0 ,0
Exp/Cntr=0.3,0.1

Type RM Length L Ch R = 1 ,2932    ,203,203,203
BEGIN DESCRIPTION:
Mapping XS 5f0b66bf
END DESCRIPTION:
XS GIS Cut Line= 2
      1913295.33     13930547.25      1913779.66     13930359.91
#Sta/Elev= 30
  4699.8 1682.43  4731.6 1676.63  4802.2 1673.37  4807.5 1674.04  4826.8 1673.49
  4832.1 1674.69  4838.8 1674.58  4849.6 1673.14  4856.7 1670.32    4871 1668.25
  4886.6 1666.93  4911.2 1666.54  4924.6 1664.96  4935.3 1663.15  4941.2 1660.65
  4946.5 1662.77  4965.8 1660.85  4971.1 1663.96  4988.9 1661.56  4993.7 1659.84
  4993.9 1659.34  4997.7 1659.84  5001.1 1662.97  5055.6 1671.69  5104.7 1675.87
  5164.6 1678.95  5181.9  1683.4  5189.2 1686.26  5213.8 1691.52  5219.1 1691.72
#Mann= 3 ,-1 , 0
  4699.8     .07       0  4993.7     .05       0  4997.7     .07       0
Bank Sta=4993.7,4997.7
XS Rating Curve= 0 ,0
Exp/Cntr=0.3,0.1

Type RM Length L Ch R = 1 ,2729    ,92,92,92
BEGIN DESCRIPTION:
Stream0495 6.0
END DESCRIPTION:
XS GIS Cut Line= 3
      1913338.27     13930734.68        1913625.       13930625.
        1913925.       13930375.
#Sta/Elev= 30
  4697.2  1680.1  4794.8 1673.96  4800.8 1672.88  4909.7  1668.1    4933 1662.31
  4939.9 1660.39  4959.1 1660.26  4972.1 1653.67  4980.8 1653.44    4981 1652.94
  4984.8 1653.44  5001.5 1660.73  5044.4 1662.72    5087  1666.3  5118.1  1668.9
  5160.4  1674.1  5181.9 1678.93  5202.7 1681.11  5231.3  1686.2  5266.5 1693.89
  5280.8 1697.95  5288.6 1701.89  5295.1 1703.48  5302.9  1706.9  5330.3 1712.67
  5344.6 1716.74  5358.9 1718.77  5387.5 1726.41  5391.4 1729.02  5394.7 1729.02
#Mann= 6 ,-1 , 0
  4697.2    .035       0    4933     .07       0  4980.8     .05       0
  4984.8     .07       0  5044.4    .035       0    5087     .07       0
Bank Sta=4980.8,4984.8
XS Rating Curve= 0 ,0
Exp/Cntr=0.3,0.1

Type RM Length L Ch R = 1 ,2637    ,56,56,56
BEGIN DESCRIPTION:
Mapping XS d97e69c5
END DESCRIPTION:
XS GIS Cut Line= 3
      1913436.89     13930849.63      1913731.76     13930645.64
      1913940.43      13930441.6
#Sta/Elev= 30
  4768.9 1676.21  4850.9 1668.46  4877.9 1667.88  4922.5 1665.02  4928.6 1665.69
  4943.5 1664.08  4964.4 1664.39  4992.2 1661.83  4992.4 1661.33  4996.2 1661.83
  5000.2 1663.27    5022 1664.53  5080.7 1665.46  5086.7  1664.3  5101.6 1665.92
  5107.7    1664  5126.4 1666.77  5158.5 1667.73  5172.7 1667.12  5186.8 1668.82
    5208 1673.49  5229.3 1676.04  5264.6 1683.25  5271.7 1685.76    5314  1695.5
  5335.3 1702.62  5356.4 1707.65  5384.7  1713.8    5406 1716.27  5419.3 1719.43
#Mann= 3 ,-1 , 0
  4768.9     .07       0  4992.2     .05       0  4996.2     .07       0
Bank Sta=4992.2,4996.2
XS Rating Curve= 0 ,0
Exp/Cntr=0.3,0.1

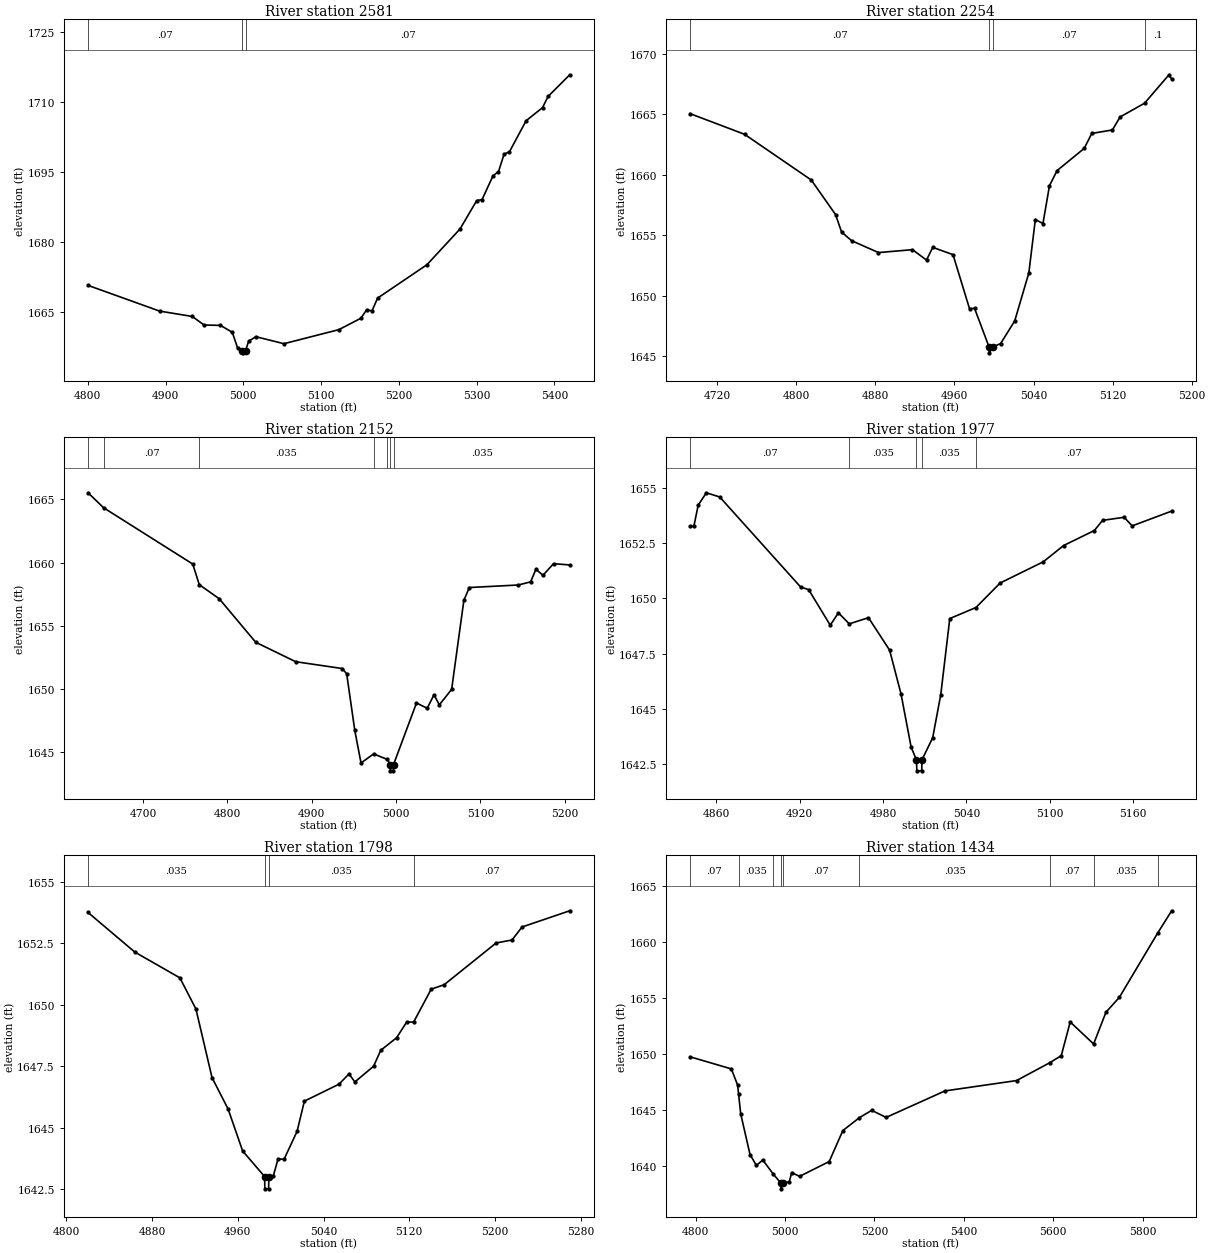
Type RM Length L Ch R = 1 ,2581    ,327,327,327
BEGIN DESCRIPTION:
Mapping XS f007ce69
END DESCRIPTION:
XS GIS Cut Line= 3
      1913493.93     13930870.77       1913754.9     13930700.37
      1913968.21     13930478.85
#Sta/Elev= 30
  4800.4 1670.74  4892.3 1665.23  4934.4 1664.07  4949.5 1662.24  4970.6 1662.16
  4985.8 1660.68  4992.8 1657.25  4998.9 1656.77  4999.1 1656.27  5002.9 1656.77
  5006.8 1658.75    5016 1659.74  5052.2 1658.23  5122.9 1661.25  5151.2  1663.7
  5158.5 1665.51  5165.4 1665.26  5172.6 1668.01  5236.1 1675.18  5278.6 1682.85
    5300 1688.93  5306.9 1689.15    5321 1694.27    5328 1695.13  5335.2  1698.9
  5342.1  1699.4  5363.5 1706.06  5384.6 1708.87  5391.8 1711.28  5419.6 1715.92
#Mann= 3 ,-1 , 0
  4800.4     .07       0  4998.9     .05       0  5002.9     .07       0
Bank Sta=4998.9,5002.9
XS Rating Curve= 0 ,0
Exp/Cntr=0.3,0.1

Type RM Length L Ch R = 1 ,2254    ,102,102,102
BEGIN DESCRIPTION:
Stream0495 5.0
END DESCRIPTION:
XS GIS Cut Line= 3
      1913625.28     13930991.84        1913925.       13930925.
      1914041.23     13930787.26
#Sta/Elev= 30
  4692.4 1665.05  4747.6 1663.34  4815.1 1659.56  4839.7  1656.7  4845.8 1655.25
    4856 1654.54  4883.1 1653.56  4917.5  1653.8  4931.7 1652.94    4938 1653.99
  4958.5 1653.39  4975.2 1648.92  4980.3 1648.95  4994.9 1645.77  4995.2 1645.27
  4998.9 1645.77  5006.6 1646.03  5020.9  1647.9  5035.2 1651.87  5041.8 1656.29
  5049.5 1655.96  5056.1 1659.09  5063.8 1660.34  5091.2 1662.17  5098.9 1663.41
  5119.8  1663.7  5127.5 1664.77  5152.3 1665.91    5177 1668.26  5179.7 1667.91
#Mann= 4 ,-1 , 0
  4692.4     .07       0  4994.9     .05       0  4998.9     .07       0
  5152.3      .1       0
Bank Sta=4994.9,4998.9
XS Rating Curve= 0 ,0
Exp/Cntr=0.3,0.1

Type RM Length L Ch R = 1 ,2152    ,175,175,175
BEGIN DESCRIPTION:
Mapping XS cd458287
END DESCRIPTION:
XS GIS Cut Line= 3
      1913638.73     13931146.28      1913943.84     13931031.82
      1914140.34      13930884.6
#Sta/Elev= 30
  4634.6 1665.53  4653.1 1664.34  4758.8 1659.88  4766.5 1658.25  4790.2 1657.13
  4833.5 1653.68  4880.9 1652.14  4936.1  1651.6  4941.4 1651.18    4951  1646.7
  4958.4 1644.11  4973.3 1644.83  4989.8 1644.39    4993 1643.99  4993.3 1643.49
  4996.8 1643.49    4997 1643.99  5024.2 1648.87  5036.9 1648.45    5045 1649.52
  5051.3 1648.72  5065.9 1649.95  5080.4    1657  5086.9 1658.02    5145 1658.22
  5159.6 1658.47  5165.9 1659.47  5174.2 1658.99  5186.8 1659.91    5206 1659.81
#Mann= 7 ,-1 , 0
  4634.6    .035       0  4653.1     .07       0  4766.5    .035       0
  4973.3     .07       0  4989.8    .035       0    4993    .035       0
    4997    .035       0
Bank Sta=4993,4997
XS Rating Curve= 0 ,0
Exp/Cntr=0.3,0.1

Type RM Length L Ch R = 1 ,1977    ,179,179,179
BEGIN DESCRIPTION:
Mapping XS 2a5f2dc4
END DESCRIPTION:
XS GIS Cut Line= 2
      1913845.18     13931263.23      1914141.47     13931083.57
#Sta/Elev= 30
  4841.1 1653.27  4843.9 1653.27    4847 1654.23  4852.9 1654.79  4862.5  1654.6
  4920.7 1650.52  4926.5  1650.4    4942 1648.79  4947.9 1649.35  4955.7 1648.85
  4969.5 1649.13  4984.7 1647.66  4992.9 1645.68  5000.2 1643.26    5004 1642.69
  5004.3 1642.19  5007.8 1642.19    5008 1642.69  5015.7 1643.69  5021.5 1645.64
    5028 1649.09  5046.8 1649.59  5064.2  1650.7  5095.2 1651.66  5109.9  1652.4
    5132 1653.08  5137.9 1653.54  5153.4 1653.68  5159.2 1653.29  5187.6 1653.96
#Mann= 5 ,-1 , 0
  4841.1     .07       0  4955.7    .035       0    5004    .035       0
    5008    .035       0  5046.8     .07       0
Bank Sta=5004,5008
XS Rating Curve= 0 ,0
Exp/Cntr=0.3,0.1

Type RM Length L Ch R = 1 ,1798    ,364,364,364
BEGIN DESCRIPTION:
Stream0495 4.0
END DESCRIPTION:
XS GIS Cut Line= 3
      1913974.98     13931475.03        1914075.       13931325.
      1914175.01     13931074.97
#Sta/Elev= 30
  4820.2 1653.76  4863.8 1652.15  4905.9  1651.1  4920.9 1649.83  4935.9 1647.04
  4950.9 1645.76  4964.5 1644.05    4985 1643.01  4985.2 1642.51  4988.7 1642.51
    4989 1643.01    4993 1643.02  4997.5 1643.72  5003.2 1643.72  5015.3 1644.85
  5022.1 1646.08  5054.4 1646.77  5063.8 1647.19  5069.2 1646.86  5086.7  1647.5
  5093.4 1648.15  5108.2 1648.66  5117.6  1649.3  5124.1  1649.3  5140.5 1650.64
  5152.6 1650.82  5201.1 1652.52  5215.9 1652.64  5225.3 1653.17  5269.8 1653.83
#Mann= 4 ,-1 , 0
  4820.2    .035       0    4985    .035       0    4989    .035       0
  5124.1     .07       0
Bank Sta=4985,4989
XS Rating Curve= 0 ,0
Exp/Cntr=0.3,0.1

Type RM Length L Ch R = 1 ,1434    ,172,172,172
BEGIN DESCRIPTION:
Stream0495 3.0
END DESCRIPTION:
XS GIS Cut Line= 4
      1914224.99     13931675.01      1914364.92     13931515.67
      1914456.13     13931284.19       1914446.2     13930668.23
#Sta/Elev= 30
  4787.6 1649.75  4880.1 1648.67  4894.1 1647.23  4896.2 1646.45    4901 1644.67
  4921.9 1641.04  4936.1 1640.07  4950.4 1640.56  4973.9  1639.3  4991.1 1638.49
  4991.3 1637.99  4995.1 1638.49  5009.6 1638.62    5015 1639.44  5032.6  1639.1
  5098.9 1640.42  5129.4 1643.18  5166.5 1644.33  5193.9 1644.98  5226.1 1644.35
  5357.7 1646.71  5517.7 1647.63  5591.6 1649.21  5617.7 1649.85  5637.7 1652.85
    5690 1650.89  5717.7 1653.72  5747.7 1655.05    5833 1660.75  5864.5 1662.75
#Mann= 9 ,-1 , 0
  4787.6     .07       0  4896.2    .035       0  4973.9     .07       0
  4991.1     .05       0  4995.1     .07       0  5166.5    .035       0
  5591.6     .07       0    5690    .035       0    5833     .07       0
Bank Sta=4991.1,4995.1
XS Rating Curve= 0 ,0
Exp/Cntr=0.3,0.1

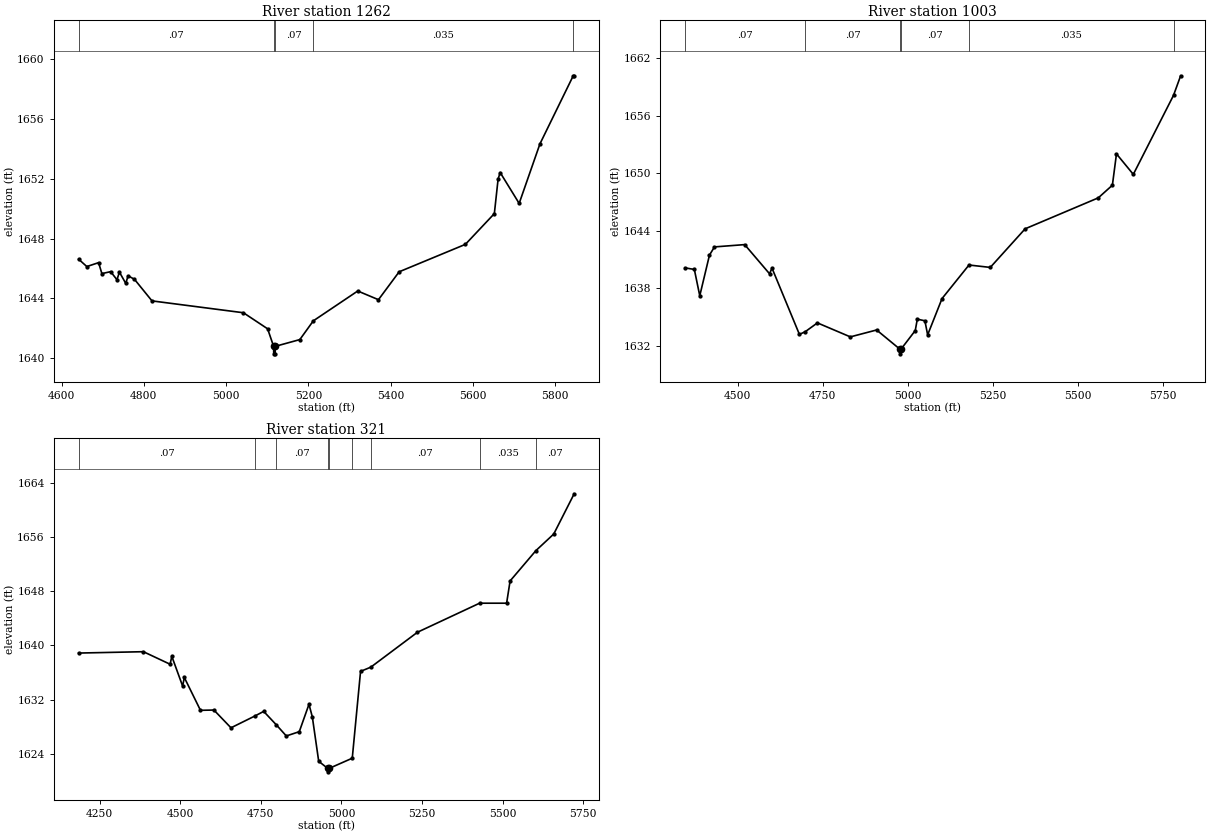
Type RM Length L Ch R = 1 ,1262    ,259,259,259
BEGIN DESCRIPTION:
Mapping XS 06ab8d39
END DESCRIPTION:
XS GIS Cut Line= 4
      1914253.76     13931760.84      1914457.21     13931635.29
      1914548.48     13931412.07      1914470.53      13930692.1
#Sta/Elev= 30
  4641.6 1646.62  4661.5 1646.13  4690.1 1646.39  4698.1 1645.66  4719.4 1645.79
  4734.8 1645.25  4740.7 1645.76  4756.1 1645.01  4761.9 1645.51  4777.3 1645.28
  4819.9 1643.84  5042.1 1643.05  5100.9 1641.98  5115.5 1640.81  5115.8 1640.31
  5119.3 1640.31  5119.5 1640.81  5179.2 1641.26    5212 1642.51    5320  1644.5
  5370.3 1643.92  5420.6 1645.78  5581.6 1647.61    5652 1649.66  5661.1 1651.96
  5666.1  1652.4  5712.3 1650.34  5762.8 1654.31  5843.7 1658.85    5846 1658.85
#Mann= 5 ,-1 , 0
  4641.6     .07       0  5115.5     .05       0  5119.5     .07       0
    5212    .035       0  5843.7     .07       0
Bank Sta=5115.5,5119.5
XS Rating Curve= 0 ,0
Exp/Cntr=0.3,0.1

Type RM Length L Ch R = 1 ,1003    ,682,682,682
BEGIN DESCRIPTION:
Stream0495 2.0
END DESCRIPTION:
XS GIS Cut Line= 6
      1914392.55     13931871.24      1914708.65      13931692.5
      1914776.03      13931548.8      1914722.02     13931426.38
        1914625.       13931275.      1914487.46     13930669.37
#Sta/Elev= 30
  4345.9 1640.11  4373.1 1639.95    4389  1637.2  4417.6 1641.45  4432.3  1642.3
    4521 1642.54    4594  1639.5  4601.4 1640.08  4681.9 1633.17    4699 1633.45
  4734.8 1634.37  4831.6 1632.91  4908.8 1633.63  4976.8 1631.64    4977 1631.14
  4980.8 1631.64  5022.4 1633.57  5028.4 1634.76  5050.7 1634.59  5058.8 1633.12
  5101.1 1636.91  5180.3 1640.41  5242.9 1640.16  5345.4 1644.19  5560.4 1647.42
  5601.8 1648.74  5613.8 1652.01  5663.3 1649.87  5781.5 1658.12  5802.4 1660.16
#Mann= 6 ,-1 , 0
  4345.9     .07       0    4699     .07       0  4976.8     .05       0
  4980.8     .07       0  5180.3    .035       0  5781.5     .07       0
Bank Sta=4976.8,4980.8
XS Rating Curve= 0 ,0
Exp/Cntr=0.3,0.1

Type RM Length L Ch R = 1 ,321     ,0,0,0
BEGIN DESCRIPTION:
Stream0495 1.0
END DESCRIPTION:
XS GIS Cut Line= 4
      1914969.59     13931767.87      1915115.86     13931263.72
      1915092.68     13930979.56      1914838.54     13930298.89
#Sta/Elev= 30
  4185.2 1638.88    4386 1639.08  4468.9 1637.23  4474.1  1638.4  4507.7 1634.01
  4512.9 1635.28    4563 1630.44  4604.7 1630.48  4657.6 1627.86  4731.7  1629.6
    4759 1630.28  4797.8 1628.32  4829.2 1626.66  4869.4 1627.29  4899.5 1631.33
  4909.9 1629.46  4929.6 1622.93  4957.7 1621.87  4957.9 1621.37  4961.7 1621.87
  5033.7 1623.38  5059.4 1636.18  5091.2  1636.8  5235.9 1641.95  5428.5 1646.23
  5512.3 1646.23  5523.1 1649.51  5603.1 1653.98  5658.5 1656.43  5721.8 1662.36
#Mann= 9 ,-1 , 0
  4185.2     .07       0  4731.7    .035       0  4797.8     .07       0
  4957.7     .05       0  4961.7     .07       0  5033.7      .1       0
  5091.2     .07       0  5428.5    .035       0  5603.1     .07       0
Bank Sta=4957.7,4961.7
XS Rating Curve= 0 ,0
Exp/Cntr=0.3,0.1

Chan Stop Cuts=-1
Use User Specified Reach Order=0
Composite Channel Slope=5