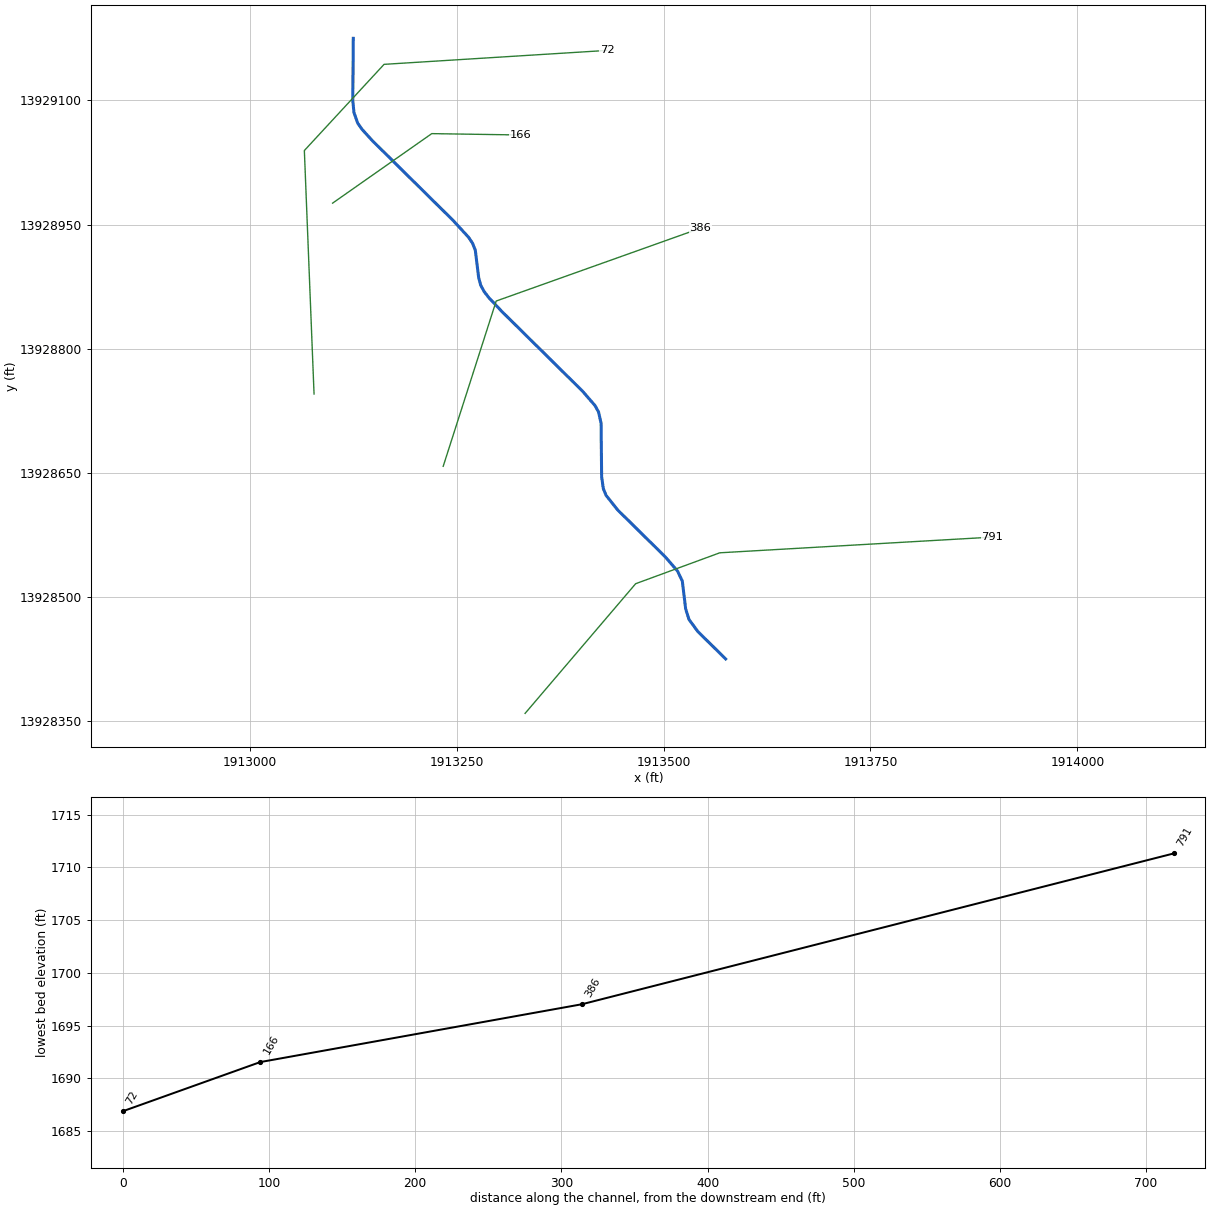
--- Stream0496.prj (project) ---

Proj Title=Stream0496 Base Level Engineering
Current Plan=p01
Default Exp/Contr=0.3,0.1
English Units
Geom File=g01
Flow File=f01
Plan File=p01
BEGIN DESCRIPTION:
Stream0496
END DESCRIPTION:

--- Stream0496.p01 (plan) ---

Plan Title=Multiple Run
Short Identifier=Multiple
Geom File=g01
Flow File=f01
Subcritical Flow
K Sum by GR= 0
Std Step Tol= 0.01
Critical Tol= 0.01
Num of Std Step Trials= 20
Max Error Tol= 0.3
Flow Tol Ratio= 0.001
Split Flow NTrial= 30
Split Flow Tol= 0.02
Split Flow Ratio= 0.02
Log Output Level= 0
Friction Slope Method= 1
Unsteady Friction Slope Method= 2
Unsteady Bridges Friction Slope Method= 1
Parabolic Critical Depth
Global Vel Dist=  1 , 1 , 1
Global Log Level= 0
CheckData=True
Encroach Param= -1, 0, 0, 0
BEGIN DESCRIPTION:
Multiple Run
END DESCRIPTION:

--- Stream0496.f01 (steady flow) ---

Flow Title=Multiple
Number of Profiles=7
Profile Names=10-year,25-year,50-year,1pct_min,100-year,1pct_plu,500-year
River Rch & RM= Stream0496,Reach-1,791
     486     791    1070     704    1405    2803    2380
Boundary for River Rch & Prof#=Stream0496,Reach-1,1
Up Type=0
Dn Type=3
Dn Slope=0.005
Boundary for River Rch & Prof#=Stream0496,Reach-1,2
Up Type=0
Dn Type=3
Dn Slope=0.005
Boundary for River Rch & Prof#=Stream0496,Reach-1,3
Up Type=0
Dn Type=3
Dn Slope=0.005
Boundary for River Rch & Prof#=Stream0496,Reach-1,4
Up Type=0
Dn Type=3
Dn Slope=0.005
Boundary for River Rch & Prof#=Stream0496,Reach-1,5
Up Type=0
Dn Type=3
Dn Slope=0.005
Boundary for River Rch & Prof#=Stream0496,Reach-1,6
Up Type=0
Dn Type=3
Dn Slope=0.005
Boundary for River Rch & Prof#=Stream0496,Reach-1,7
Up Type=0
Dn Type=3
Dn Slope=0.005

--- Stream0496.g01 (geometry) ---

Geom Title=Existing Conditions

River Reach=Stream0496,Reach-1
Reach XY= 30
      1913575.00     13928425.00      1913541.42     13928458.08
      1913530.70     13928472.65      1913526.65     13928485.68
      1913522.65     13928519.03      1913516.93     13928531.08
      1913501.95     13928548.45      1913444.67     13928604.86
      1913430.54     13928622.58      1913427.16     13928630.90
      1913425.14     13928645.06      1913424.47     13928709.78
      1913421.39     13928723.50      1913417.14     13928731.17
      1913402.12     13928748.52      1913304.62     13928844.84
      1913288.63     13928861.79      1913283.16     13928868.95
      1913278.98     13928876.65      1913276.55     13928885.64
      1913272.46     13928918.95      1913269.14     13928927.29
      1913264.22     13928934.68      1913245.38     13928955.16
      1913147.88     13929051.48      1913135.43     13929065.18
      1913130.35     13929072.50      1913125.81     13929085.34
      1913124.41     13929099.75      1913125.00     13929175.00

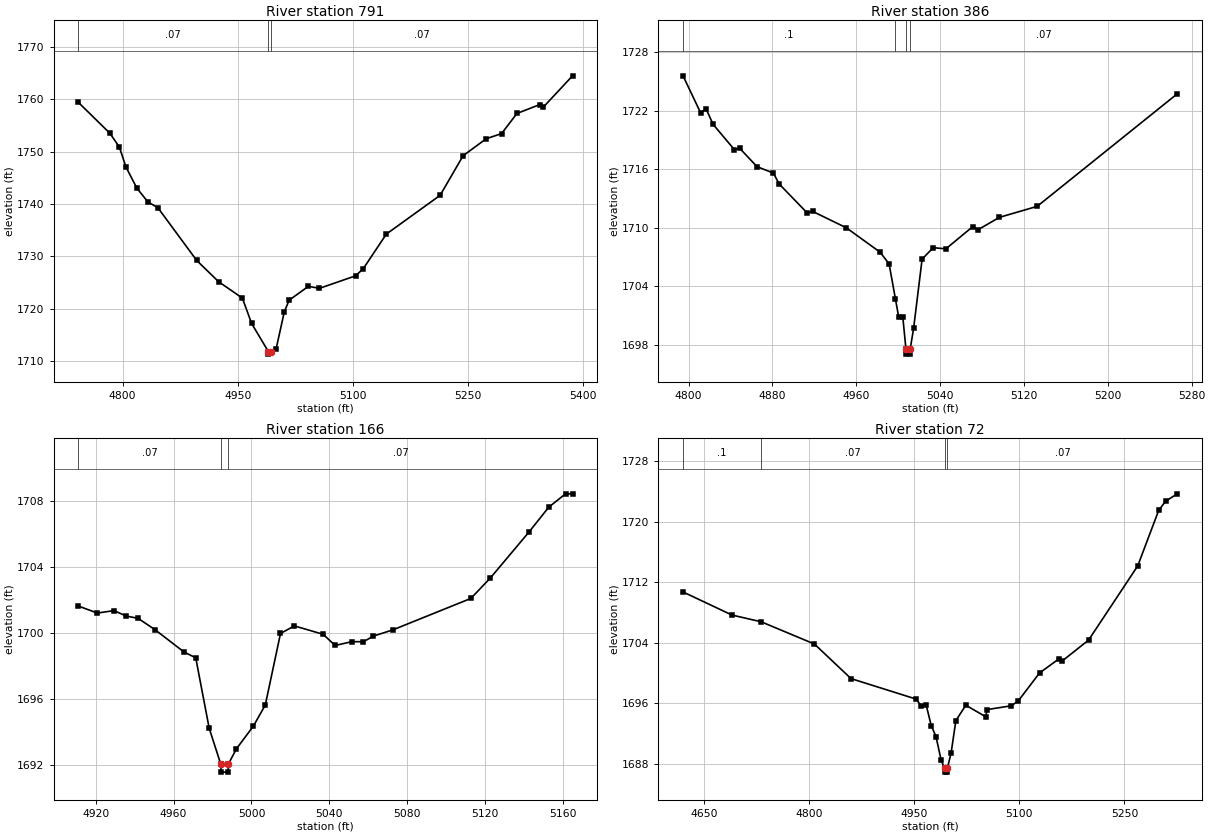
Type RM Length L Ch R = 1,791,405,405,405
BEGIN DESCRIPTION:
Stream0496 2.0
END DESCRIPTION:
XS GIS Cut Line= 4
      1913332.66     13928359.18      1913466.27     13928515.90
      1913567.95     13928553.24      1913897.34     13928572.21
#Sta/Elev= 30
  4742.2 1759.41  4783.5 1753.48  4795.8 1750.85  4804.4 1747.04  4818.6 1743.01
  4832.9 1740.39  4846.0 1739.27  4896.6 1729.20  4925.2 1725.14  4956.1 1722.02
  4968.1 1717.18  4989.9 1711.82  4990.1 1711.32  4993.9 1711.82  5000.1 1712.35
  5010.7 1719.37  5017.0 1721.62  5042.2 1724.27  5056.5 1723.88  5103.6 1726.27
  5113.6 1727.62  5143.7 1734.24  5213.8 1741.64  5243.8 1749.21  5273.9 1752.45
  5293.9 1753.43  5313.9 1757.27  5343.5 1758.96  5348.5 1758.51  5386.4 1764.46
#Mann=3,-1,0
  4742.2    0.07       0  4989.9    0.05       0  4993.9    0.07       0
Bank Sta=4989.9,4993.9
Exp/Cntr=0.3,0.1

Type RM Length L Ch R = 1,386,220,220,220
BEGIN DESCRIPTION:
Stream0496 1.0
END DESCRIPTION:
XS GIS Cut Line= 3
      1913233.66     13928657.79      1913297.70     13928857.51
      1913544.36     13928945.43
#Sta/Elev= 30
  4794.7 1725.57  4811.5 1721.77  4816.7 1722.19  4823.3 1720.60  4843.6 1718.01
  4848.9 1718.12  4865.3 1716.25  4881.0 1715.59  4886.3 1714.49  4913.1 1711.51
  4918.4 1711.66  4950.5 1709.98  4982.6 1707.49  4991.3 1706.28  4997.3 1702.71
  5000.5 1700.80  5004.4 1700.80  5007.4 1697.52  5007.6 1697.02  5011.1 1697.02
  5011.4 1697.52  5014.7 1699.67  5022.8 1706.77  5033.4 1707.94  5045.5 1707.82
  5071.0 1710.09  5076.3 1709.79  5096.5 1711.05  5132.6 1712.18  5266.3 1723.73
#Mann=4,-1,0
  4794.7     0.1       0  4997.3    0.07       0  5007.4    0.05       0
  5011.4    0.07       0
Bank Sta=5007.4,5011.4
Exp/Cntr=0.3,0.1

Type RM Length L Ch R = 1,166,94,94,94
BEGIN DESCRIPTION:
Stream0496 0.0
END DESCRIPTION:
XS GIS Cut Line= 3
      1913099.99     13928975.82      1913219.84     13929059.84
      1913327.16     13929058.20
#Sta/Elev= 30
  4911.1 1701.64  4920.9 1701.21  4929.4 1701.36  4935.7 1701.03  4941.8 1700.89
  4950.5 1700.20  4965.3 1698.85  4971.4 1698.49  4978.3 1694.21  4984.2 1692.04
  4984.5 1691.54  4988.0 1691.54  4988.2 1692.04  4992.3 1692.96  5001.0 1694.34
  5007.1 1695.62  5014.9 1699.97  5022.0 1700.43  5036.8 1699.92  5042.9 1699.24
  5051.5 1699.47  5057.5 1699.47  5062.6 1699.81  5072.6 1700.19  5112.6 1702.10
  5122.6 1703.34  5142.6 1706.16  5152.6 1707.65  5161.2 1708.46  5164.8 1708.46
#Mann=3,-1,0
  4911.1    0.07       0  4984.2    0.05       0  4988.2    0.07       0
Bank Sta=4984.2,4988.2
Exp/Cntr=0.3,0.1

Type RM Length L Ch R = 1,72,0,0,0
BEGIN DESCRIPTION:
Stream0496 0.1
END DESCRIPTION:
XS GIS Cut Line= 4
      1913077.58     13928745.16      1913065.86     13929039.40
      1913162.22     13929143.57      1913431.52     13929160.40
#Sta/Elev= 30
  4619.4 1710.69  4689.3 1707.64  4731.0 1706.75  4807.1 1703.81  4859.4 1699.24
  4952.5 1696.53  4959.8 1695.61  4966.7 1695.78  4974.0 1693.03  4980.8 1691.58
  4988.2 1688.46  4993.0 1687.38  4993.3 1686.88  4996.8 1686.88  4997.0 1687.38
  5002.4 1689.41  5009.2 1693.69  5023.4 1695.72  5051.7 1694.21  5054.1 1695.15
  5088.6 1695.65  5098.6 1696.32  5128.7 1699.98  5156.3 1701.84  5161.3 1701.58
  5198.8 1704.33  5269.0 1714.13  5299.0 1721.48  5309.0 1722.70  5325.6 1723.66
#Mann=4,-1,0
  4619.4     0.1       0  4731.0    0.07       0  4993.0    0.05       0
  4997.0    0.07       0
Bank Sta=4993,4997
Exp/Cntr=0.3,0.1

Chan Stop Cuts=-1