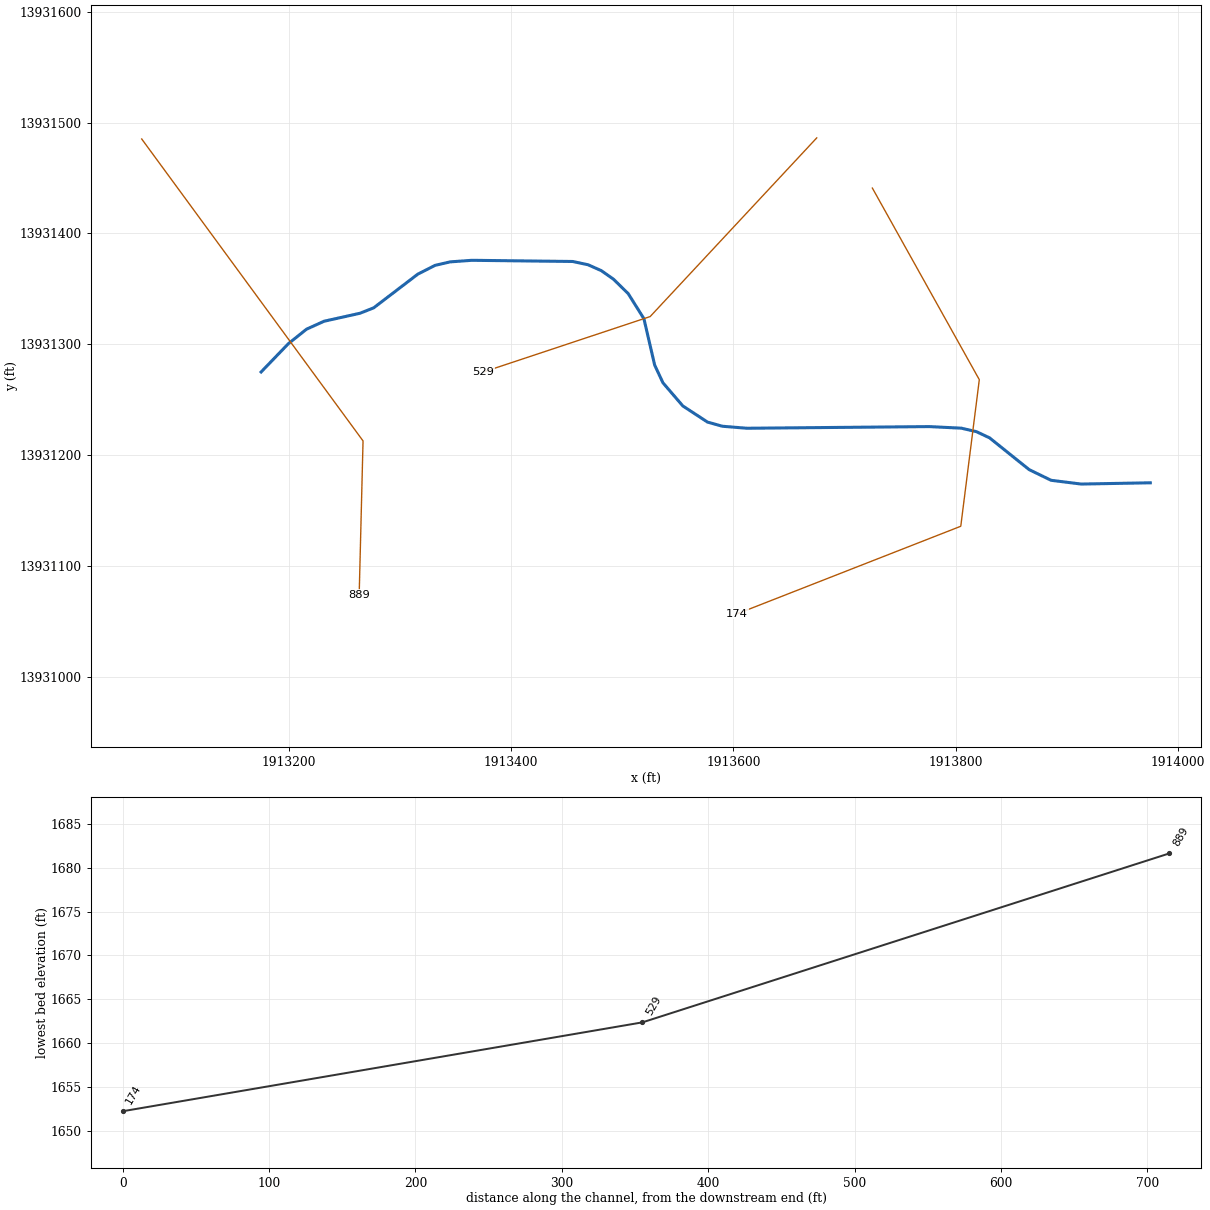
--- Stream0497.prj (project) ---

Proj Title=Stream0497 Base Level Engineering
Current Plan=p01
Default Exp/Contr=0.3,0.1
English Units
Geom File=g01
Flow File=f01
Plan File=p01
BEGIN DESCRIPTION:
Stream0497
END DESCRIPTION:

--- Stream0497.p01 (plan) ---

Plan Title=Multiple Run
Short Identifier=Multiple
Geom File=g01
Flow File=f01
Subcritical Flow
K Sum by GR= 0
Std Step Tol= 0.01
Critical Tol= 0.01
Num of Std Step Trials= 20
Max Error Tol= 0.3
Flow Tol Ratio= 0.001
Split Flow NTrial= 30
Split Flow Tol= 0.02
Split Flow Ratio= 0.02
Log Output Level= 0
Friction Slope Method= 1
Unsteady Friction Slope Method= 2
Unsteady Bridges Friction Slope Method= 1
Parabolic Critical Depth
Global Vel Dist=  1 , 1 , 1
Global Log Level= 0
CheckData=True
Encroach Param= -1, 0, 0, 0
BEGIN DESCRIPTION:
Multiple Run
END DESCRIPTION:

--- Stream0497.f01 (steady flow) ---

Flow Title=Multiple
Number of Profiles=7
Profile Names=10-year,25-year,50-year,1pct_min,100-year,1pct_plu,500-year
River Rch & RM= Stream0497,Reach-1,889
     444     718     968     635    1267    2529    2134
Boundary for River Rch & Prof#=Stream0497,Reach-1,1
Up Type=0
Dn Type=3
Dn Slope=0.005
Boundary for River Rch & Prof#=Stream0497,Reach-1,2
Up Type=0
Dn Type=3
Dn Slope=0.005
Boundary for River Rch & Prof#=Stream0497,Reach-1,3
Up Type=0
Dn Type=3
Dn Slope=0.005
Boundary for River Rch & Prof#=Stream0497,Reach-1,4
Up Type=0
Dn Type=3
Dn Slope=0.005
Boundary for River Rch & Prof#=Stream0497,Reach-1,5
Up Type=0
Dn Type=3
Dn Slope=0.005
Boundary for River Rch & Prof#=Stream0497,Reach-1,6
Up Type=0
Dn Type=3
Dn Slope=0.005
Boundary for River Rch & Prof#=Stream0497,Reach-1,7
Up Type=0
Dn Type=3
Dn Slope=0.005

--- Stream0497.g01 (geometry) ---

Geom Title=Existing Conditions

River Reach=Stream0497,Reach-1
Reach XY= 30
      1913175.00     13931275.00      1913199.55     13931300.57
      1913215.80     13931313.59      1913231.62     13931320.79
      1913263.91     13931327.99      1913276.30     13931332.90
      1913315.99     13931363.30      1913331.50     13931371.22
      1913345.09     13931374.37      1913364.71     13931375.79
      1913455.27     13931374.73      1913469.09     13931371.79
      1913481.11     13931366.44      1913492.11     13931358.67
      1913505.30     13931345.68      1913519.41     13931323.08
      1913529.07     13931281.27      1913536.52     13931265.25
      1913554.41     13931244.36      1913576.62     13931229.78
      1913589.97     13931226.03      1913612.02     13931224.22
      1913776.21     13931225.72      1913804.92     13931224.30
      1913818.50     13931221.16      1913830.29     13931215.61
      1913866.04     13931186.87      1913885.75     13931177.25
      1913912.81     13931173.86      1913975.00     13931175.00

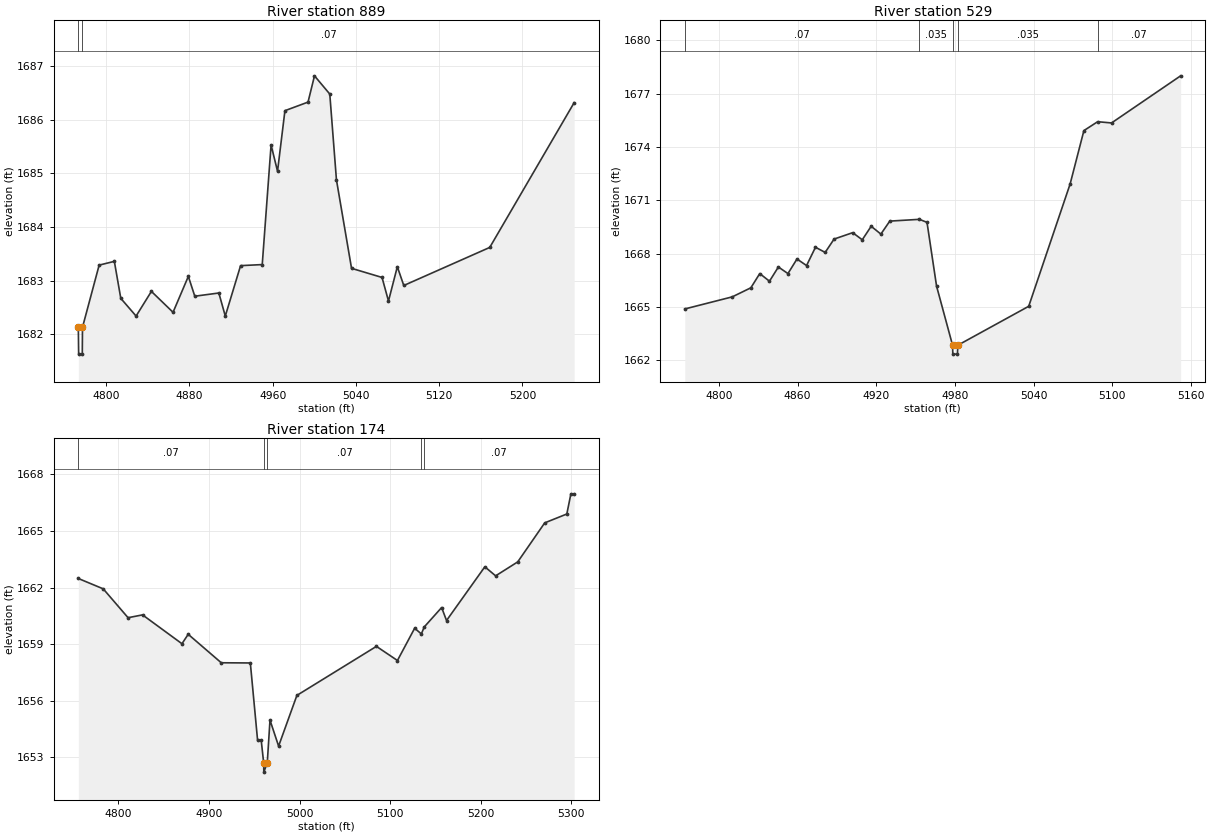
Type RM Length L Ch R = 1,889,360,360,360
BEGIN DESCRIPTION:
Stream0497 2.0
END DESCRIPTION:
XS GIS Cut Line= 3
      1913067.59     13931485.27      1913266.71     13931212.79
      1913263.24     13931073.91
#Sta/Elev= 30
  4773.3 1682.13  4773.6 1681.63  4777.1 1681.63  4777.3 1682.13  4793.3 1683.29
  4807.9 1683.36  4814.1 1682.67  4828.8 1682.34  4843.5 1682.80  4864.3 1682.41
  4879.0 1683.08  4885.2 1682.71  4908.3 1682.77  4914.5 1682.34  4929.2 1683.28
  4950.0 1683.30  4958.5 1685.53  4964.7 1685.04  4971.8 1686.17  4994.0 1686.33
  5000.2 1686.82  5014.9 1686.48  5021.3 1684.88  5035.8 1683.23  5065.1 1683.06
  5071.3 1682.62  5079.8 1683.26  5086.0 1682.91  5168.6 1683.62  5249.7 1686.32
#Mann=2,-1,0
  4773.3    0.05       0  4777.3    0.07       0
Bank Sta=4773.3,4777.3
Exp/Cntr=0.3,0.1

Type RM Length L Ch R = 1,529,355,355,355
BEGIN DESCRIPTION:
Stream0497 1.0
END DESCRIPTION:
XS GIS Cut Line= 3
      1913674.90     13931486.28      1913525.00     13931325.00
      1913375.00     13931275.00
#Sta/Elev= 30
  4773.9 1664.89  4810.1 1665.57  4824.3 1666.08  4831.1 1666.88  4838.5 1666.45
  4845.3 1667.25  4852.6 1666.88  4859.5 1667.70  4866.8 1667.33  4873.6 1668.36
  4881.0 1668.07  4887.8 1668.82  4902.0 1669.18  4909.3 1668.78  4916.1 1669.54
  4923.5 1669.10  4930.3 1669.83  4952.9 1669.93  4958.7 1669.76  4966.0 1666.17
  4978.2 1662.85  4978.4 1662.35  4981.9 1662.35  4982.2 1662.85  5036.3 1665.04
  5067.9 1671.92  5078.4 1674.92  5088.9 1675.42  5099.5 1675.35  5152.2 1678.00
#Mann=5,-1,0
  4773.9    0.07       0  4952.9   0.035       0  4978.2   0.035       0
  4982.2   0.035       0  5088.9    0.07       0
Bank Sta=4978.2,4982.2
Exp/Cntr=0.3,0.1

Type RM Length L Ch R = 1,174,0,0,0
BEGIN DESCRIPTION:
Stream0497 0.0
END DESCRIPTION:
XS GIS Cut Line= 4
      1913724.94     13931440.98      1913821.16     13931268.06
      1913804.47     13931135.77      1913603.27     13931056.74
#Sta/Elev= 30
  4755.8 1662.48  4783.3 1661.93  4810.7 1660.40  4826.7 1660.55  4870.2 1659.02
  4877.1 1659.52  4913.6 1658.01  4945.7 1658.00  4953.7 1653.90  4957.7 1653.90
  4960.4 1652.71  4960.6 1652.21  4964.4 1652.71  4967.4 1654.97  4976.9 1653.59
  4997.1 1656.28  5084.9 1658.88  5108.1 1658.13  5127.1 1659.84  5134.5 1659.54
  5137.7 1659.91  5156.9 1660.94  5162.3 1660.25  5204.6 1663.10  5216.5 1662.62
  5240.9 1663.36  5270.7 1665.43  5295.1 1665.90  5299.6 1666.97  5303.2 1666.97
#Mann=5,-1,0
  4755.8    0.07       0  4960.4    0.05       0  4964.4    0.07       0
  5134.5   0.035       0  5137.7    0.07       0
Bank Sta=4960.4,4964.4
Exp/Cntr=0.3,0.1

Chan Stop Cuts=-1