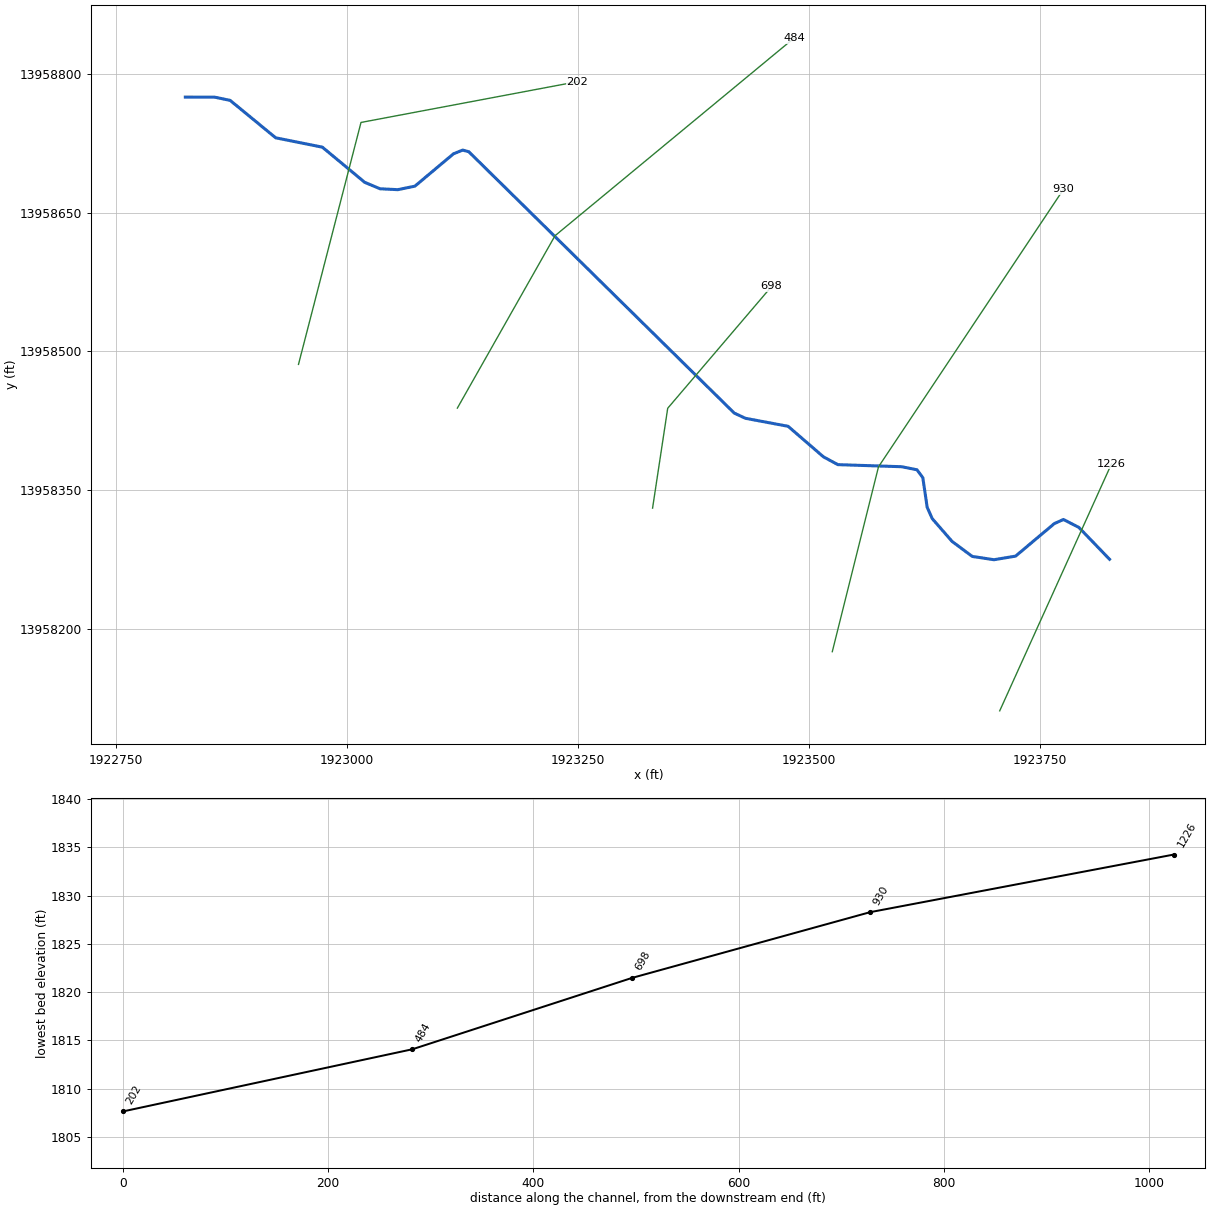
--- Stream0500.prj (project) ---

Proj Title=Stream0500 Base Level Engineering
Current Plan=p01
Default Exp/Contr=0.3,0.1
English Units
Geom File=g01
Flow File=f01
Plan File=p01
BEGIN DESCRIPTION:
Stream0500
END DESCRIPTION:

--- Stream0500.p01 (plan) ---

Plan Title=Multiple Run
Short Identifier=Multiple
Geom File=g01
Flow File=f01
Subcritical Flow
K Sum by GR= 0
Std Step Tol= 0.01
Critical Tol= 0.01
Num of Std Step Trials= 20
Max Error Tol= 0.3
Flow Tol Ratio= 0.001
Split Flow NTrial= 30
Split Flow Tol= 0.02
Split Flow Ratio= 0.02
Log Output Level= 0
Friction Slope Method= 1
Unsteady Friction Slope Method= 2
Unsteady Bridges Friction Slope Method= 1
Parabolic Critical Depth
Global Vel Dist=  1 , 1 , 1
Global Log Level= 0
CheckData=True
Encroach Param= -1, 0, 0, 0
BEGIN DESCRIPTION:
Multiple Run
END DESCRIPTION:

--- Stream0500.f01 (steady flow) ---

Flow Title=Multiple
Number of Profiles=7
Profile Names=10-year,25-year,50-year,1pct_min,100-year,1pct_plu,500-year
River Rch & RM= Stream0500,Reach-1,1226
     488     791    1066     699    1394    2781    2342
Boundary for River Rch & Prof#=Stream0500,Reach-1,1
Up Type=0
Dn Type=3
Dn Slope=0.005
Boundary for River Rch & Prof#=Stream0500,Reach-1,2
Up Type=0
Dn Type=3
Dn Slope=0.005
Boundary for River Rch & Prof#=Stream0500,Reach-1,3
Up Type=0
Dn Type=3
Dn Slope=0.005
Boundary for River Rch & Prof#=Stream0500,Reach-1,4
Up Type=0
Dn Type=3
Dn Slope=0.005
Boundary for River Rch & Prof#=Stream0500,Reach-1,5
Up Type=0
Dn Type=3
Dn Slope=0.005
Boundary for River Rch & Prof#=Stream0500,Reach-1,6
Up Type=0
Dn Type=3
Dn Slope=0.005
Boundary for River Rch & Prof#=Stream0500,Reach-1,7
Up Type=0
Dn Type=3
Dn Slope=0.005

--- Stream0500.g01 (geometry) ---

Geom Title=Existing Conditions

River Reach=Stream0500,Reach-1
Reach XY= 30
      1923825.00     13958275.00      1923791.83     13958309.44
      1923775.12     13958318.05      1923765.17     13958313.55
      1923723.34     13958278.42      1923699.91     13958274.52
      1923676.44     13958278.09      1923654.57     13958294.38
      1923633.18     13958318.92      1923627.65     13958331.29
      1923622.98     13958363.21      1923616.65     13958371.81
      1923600.12     13958375.12      1923531.05     13958377.37
      1923515.39     13958385.85      1923477.17     13958418.86
      1923431.03     13958427.50      1923418.94     13958433.14
      1923131.73     13958715.85      1923125.09     13958717.65
      1923115.13     13958713.61      1923073.37     13958678.61
      1923054.87     13958674.83      1923035.70     13958675.80
      1923019.07     13958682.78      1922973.28     13958720.80
      1922922.75     13958730.94      1922873.51     13958771.40
      1922856.81     13958774.90      1922825.00     13958775.00

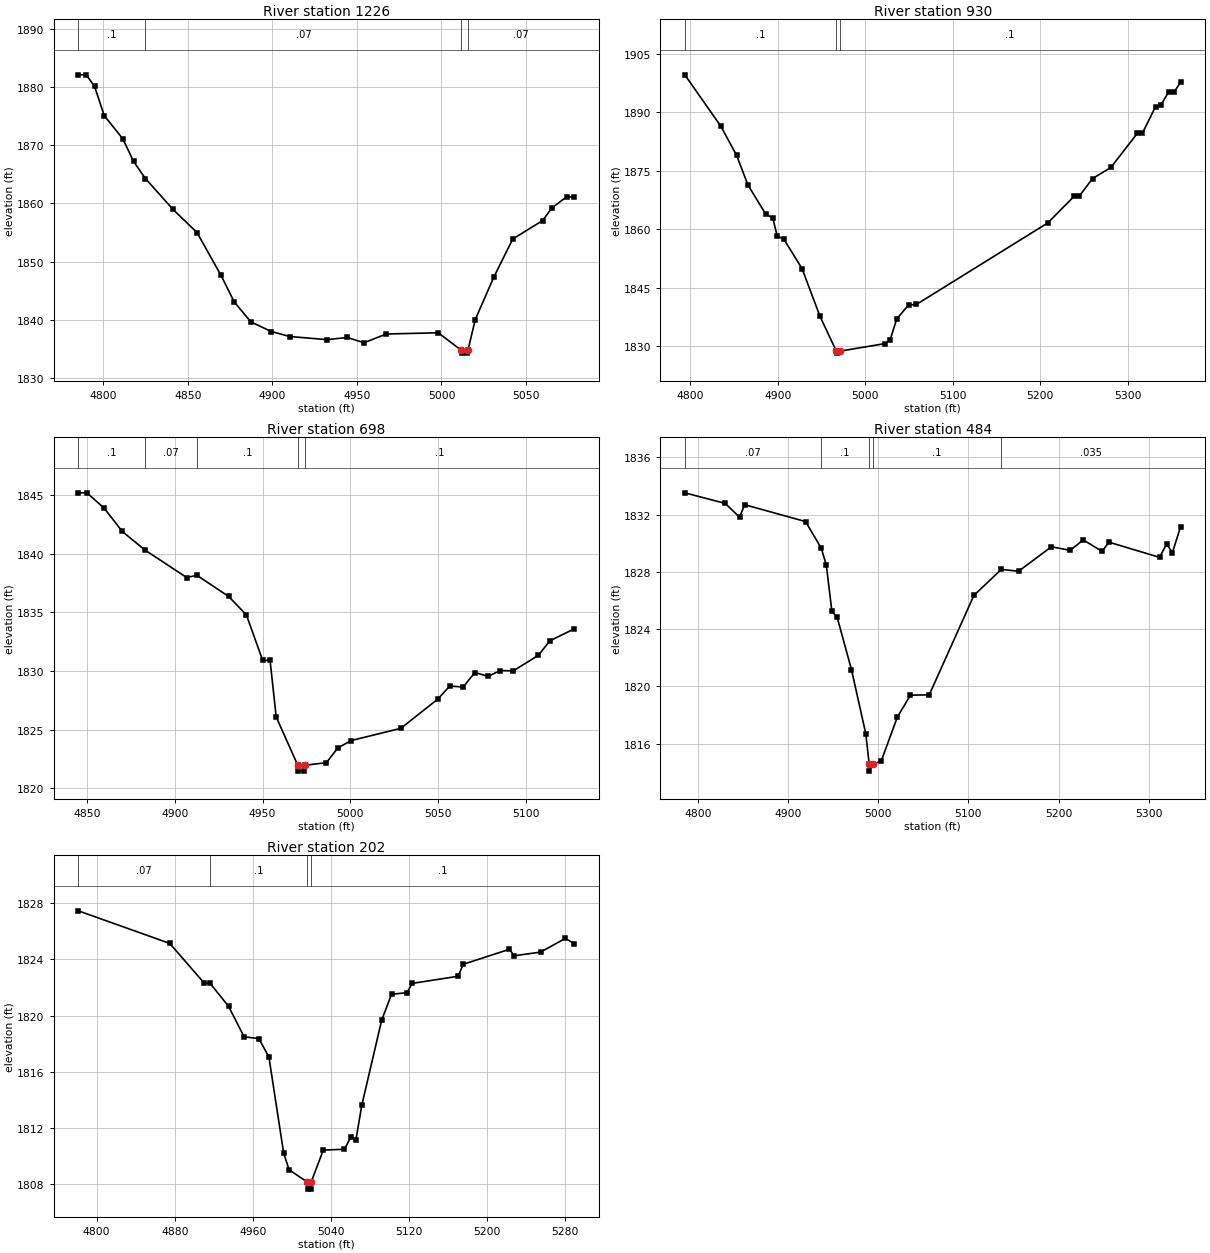
Type RM Length L Ch R = 1,1226,296,296,296
BEGIN DESCRIPTION:
Stream0500 3.0
END DESCRIPTION:
XS GIS Cut Line= 2
      1923706.17     13958111.05      1923827.11     13958378.25
#Sta/Elev= 30
  4785.2 1882.13  4789.9 1882.13  4794.8 1880.14  4800.5 1875.12  4811.5 1871.13
  4817.9 1867.22  4824.9 1864.28  4841.0 1859.04  4855.4 1854.99  4869.6 1847.63
  4877.4 1843.07  4887.2 1839.64  4899.3 1837.97  4910.3 1837.11  4932.2 1836.57
  4944.3 1836.94  4954.2 1836.04  4967.4 1837.54  4998.1 1837.75  5011.7 1834.75
  5011.9 1834.25  5015.4 1834.25  5015.7 1834.75  5020.0 1840.03  5031.0 1847.35
  5042.2 1853.89  5059.9 1857.06  5065.3 1859.23  5074.0 1861.13  5078.5 1861.13
#Mann=4,-1,0
  4785.2     0.1       0  4824.9    0.07       0  5011.7    0.05       0
  5015.7    0.07       0
Bank Sta=5011.7,5015.7
Exp/Cntr=0.3,0.1

Type RM Length L Ch R = 1,930,232,232,232
BEGIN DESCRIPTION:
Stream0500 2.0
END DESCRIPTION:
XS GIS Cut Line= 3
      1923525.01     13958175.04      1923575.00     13958375.00
      1923775.02     13958675.02
#Sta/Elev= 30
  4793.7 1899.62  4834.9 1886.44  4852.9 1878.98  4865.8 1871.42  4886.4 1863.83
  4894.2 1862.99  4899.3 1858.31  4907.0 1857.45  4927.7 1849.95  4948.3 1837.67
  4966.9 1828.78  4967.1 1828.28  4970.9 1828.78  5022.4 1830.72  5028.4 1831.68
  5035.9 1837.03  5049.4 1840.61  5058.4 1840.76  5208.6 1861.66  5238.7 1868.49
  5244.7 1868.57  5259.7 1873.03  5280.7 1875.87  5310.8 1884.59  5316.8 1884.71
  5331.8 1891.49  5337.8 1891.87  5346.9 1895.29  5352.9 1895.20  5360.4 1897.73
#Mann=3,-1,0
  4793.7     0.1       0  4966.9    0.05       0  4970.9     0.1       0
Bank Sta=4966.9,4970.9
Exp/Cntr=0.3,0.1

Type RM Length L Ch R = 1,698,214,214,214
BEGIN DESCRIPTION:
Stream0500 1.1
END DESCRIPTION:
XS GIS Cut Line= 3
      1923330.55     13958330.33      1923346.93     13958438.35
      1923459.29     13958570.09
#Sta/Elev= 30
  4845.1 1845.19  4850.0 1845.19  4859.9 1843.87  4870.1 1841.90  4882.9 1840.33
  4906.8 1837.97  4912.6 1838.16  4930.7 1836.36  4940.8 1834.79  4950.1 1830.91
  4954.3 1830.91  4957.8 1826.08  4970.1 1821.97  4970.3 1821.47  4973.8 1821.47
  4974.1 1821.97  4986.4 1822.19  4992.9 1823.45  5000.6 1824.08  5028.8 1825.12
  5050.0 1827.63  5056.6 1828.72  5064.3 1828.64  5070.9 1829.87  5078.6 1829.55
  5085.2 1830.04  5092.9 1830.02  5107.1 1831.34  5113.7 1832.58  5127.5 1833.59
#Mann=5,-1,0
  4845.1     0.1       0  4882.9    0.07       0  4912.6     0.1       0
  4970.1    0.05       0  4974.1     0.1       0
Bank Sta=4970.1,4974.1
Exp/Cntr=0.3,0.1

Type RM Length L Ch R = 1,484,282,282,282
BEGIN DESCRIPTION:
Stream0500 1.0
END DESCRIPTION:
XS GIS Cut Line= 3
      1923119.32     13958438.52      1923225.00     13958625.00
      1923483.47     13958838.67
#Sta/Elev= 30
  4785.6 1833.53  4830.4 1832.79  4846.3 1831.83  4852.0 1832.70  4919.5 1831.52
  4936.9 1829.66  4942.5 1828.47  4948.7 1825.24  4954.5 1824.84  4970.4 1821.17
  4986.3 1816.68  4990.0 1814.58  4990.2 1814.08  4994.0 1814.58  5003.2 1814.76
  5021.4 1817.88  5035.8 1819.39  5056.6 1819.41  5106.1 1826.36  5136.5 1828.18
  5155.6 1828.05  5192.1 1829.76  5212.9 1829.51  5227.3 1830.24  5248.1 1829.44
  5255.9 1830.08  5311.9 1829.02  5319.8 1829.95  5326.2 1829.35  5335.3 1831.17
#Mann=5,-1,0
  4785.6    0.07       0  4936.9     0.1       0  4990.0    0.05       0
  4994.0     0.1       0  5136.5   0.035       0
Bank Sta=4990,4994
Exp/Cntr=0.3,0.1

Type RM Length L Ch R = 1,202,0,0,0
BEGIN DESCRIPTION:
Stream0500 0.0
END DESCRIPTION:
XS GIS Cut Line= 3
      1922947.43     13958485.82      1923015.07     13958747.55
      1923248.93     13958791.61
#Sta/Elev= 30
  4781.2 1827.46  4874.9 1825.14  4910.4 1822.30  4916.0 1822.32  4935.3 1820.65
  4951.1 1818.49  4966.3 1818.36  4976.6 1817.04  4991.7 1810.20  4997.3 1809.02
  5015.9 1808.14  5016.2 1807.64  5019.7 1807.64  5019.9 1808.14  5032.3 1810.42
  5054.0 1810.48  5060.6 1811.35  5065.7 1811.12  5071.8 1813.62  5092.2 1819.68
  5102.3 1821.52  5118.2 1821.63  5123.3 1822.29  5170.6 1822.80  5175.7 1823.65
  5223.1 1824.72  5228.2 1824.26  5255.0 1824.52  5280.6 1825.50  5289.5 1825.11
#Mann=4,-1,0
  4781.2    0.07       0  4916.0     0.1       0  5015.9    0.05       0
  5019.9     0.1       0
Bank Sta=5015.9,5019.9
Exp/Cntr=0.3,0.1

Chan Stop Cuts=-1