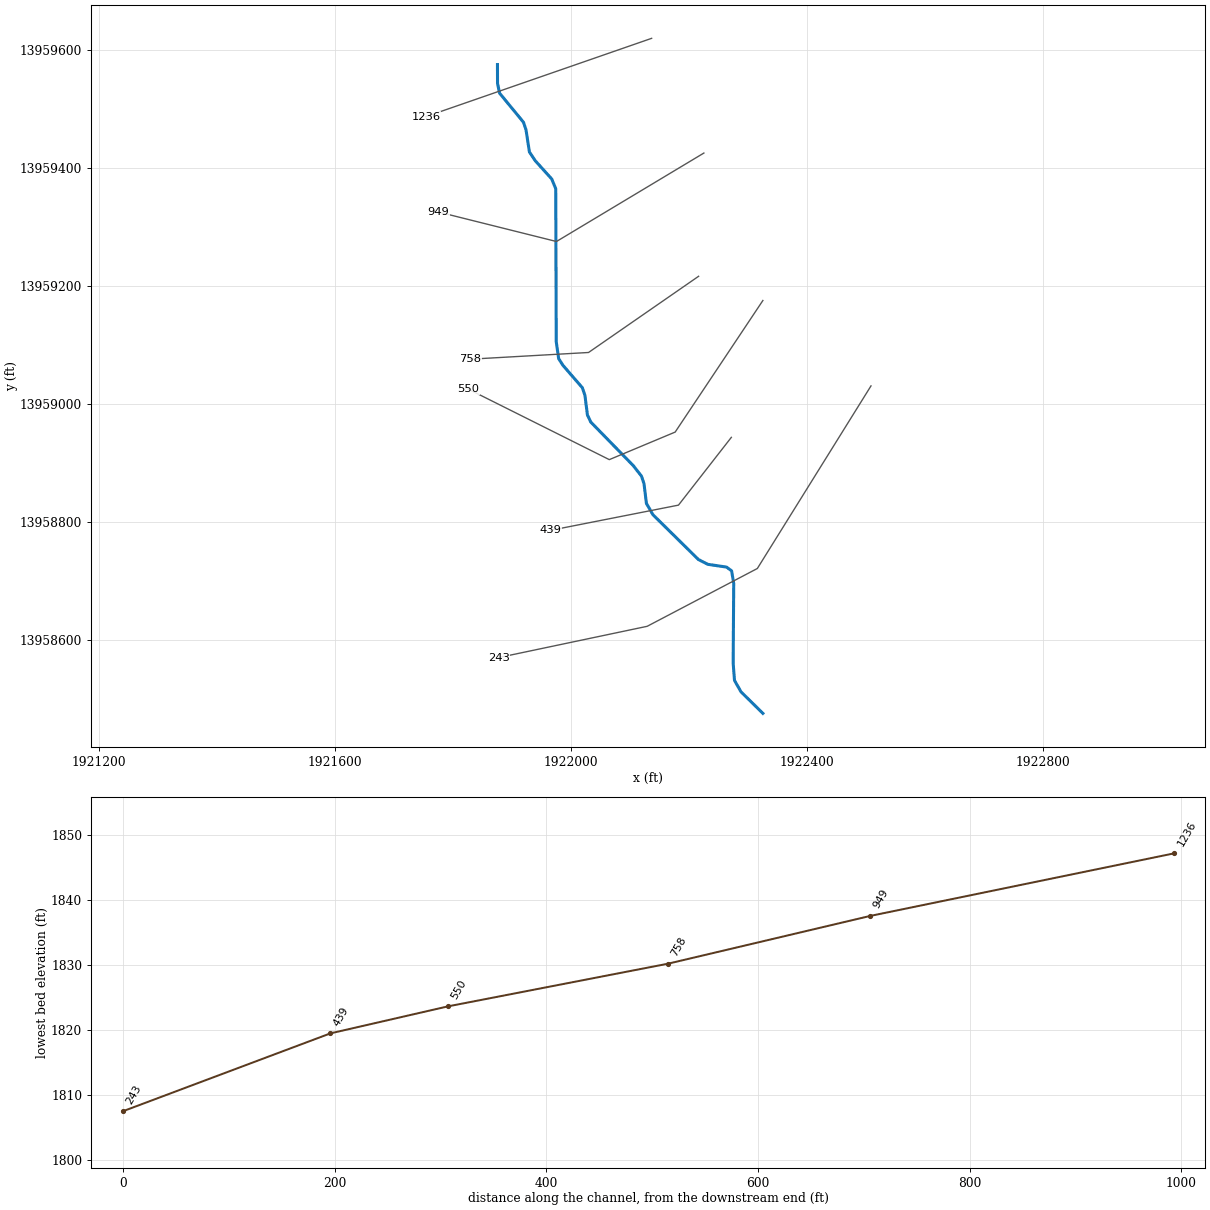
--- Stream0501.prj (project) ---

Proj Title=Stream0501 Base Level Engineering
Current Plan=p01
Default Exp/Contr=0.3,0.1
English Units
Geom File=g01
Flow File=f01
Plan File=p01
BEGIN DESCRIPTION:
Stream0501
END DESCRIPTION:

--- Stream0501.p01 (plan) ---

Plan Title=Multiple Run
Short Identifier=Multiple
Geom File=g01
Flow File=f01
Subcritical Flow
K Sum by GR= 0
Std Step Tol= 0.01
Critical Tol= 0.01
Num of Std Step Trials= 20
Max Error Tol= 0.3
Flow Tol Ratio= 0.001
Split Flow NTrial= 30
Split Flow Tol= 0.02
Split Flow Ratio= 0.02
Log Output Level= 0
Friction Slope Method= 1
Unsteady Friction Slope Method= 2
Unsteady Bridges Friction Slope Method= 1
Parabolic Critical Depth
Global Vel Dist=  1 , 1 , 1
Global Log Level= 0
CheckData=True
Encroach Param= -1, 0, 0, 0
BEGIN DESCRIPTION:
Multiple Run
END DESCRIPTION:

--- Stream0501.f01 (steady flow) ---

Flow Title=Multiple
Number of Profiles=7
Profile Names=10-year,25-year,50-year,1pct_min,100-year,1pct_plu,500-year
River Rch & RM= Stream0501,Reach-1,1236
     283     441     581     372     743    1483    1194
Boundary for River Rch & Prof#=Stream0501,Reach-1,1
Up Type=0
Dn Type=3
Dn Slope=0.005
Boundary for River Rch & Prof#=Stream0501,Reach-1,2
Up Type=0
Dn Type=3
Dn Slope=0.005
Boundary for River Rch & Prof#=Stream0501,Reach-1,3
Up Type=0
Dn Type=3
Dn Slope=0.005
Boundary for River Rch & Prof#=Stream0501,Reach-1,4
Up Type=0
Dn Type=3
Dn Slope=0.005
Boundary for River Rch & Prof#=Stream0501,Reach-1,5
Up Type=0
Dn Type=3
Dn Slope=0.005
Boundary for River Rch & Prof#=Stream0501,Reach-1,6
Up Type=0
Dn Type=3
Dn Slope=0.005
Boundary for River Rch & Prof#=Stream0501,Reach-1,7
Up Type=0
Dn Type=3
Dn Slope=0.005

--- Stream0501.g01 (geometry) ---

Geom Title=Existing Conditions

River Reach=Stream0501,Reach-1
Reach XY= 30
      1921875.00     13959575.00      1921875.10     13959543.19
      1921878.60     13959526.49      1921919.05     13959477.25
      1921923.39     13959464.33      1921929.17     13959426.73
      1921939.04     13959411.96      1921966.91     13959381.08
      1921973.80     13959364.50      1921974.64     13959104.85
      1921978.75     13959076.55      1921985.79     13959065.33
      1922018.86     13959027.17      1922023.28     13959014.29
      1922027.50     13958981.04      1922033.16     13958968.95
      1922105.17     13958895.07      1922119.13     13958877.28
      1922123.44     13958864.35      1922127.53     13958831.04
      1922138.62     13958811.76      1922215.61     13958735.90
      1922231.52     13958727.73      1922263.31     13958723.02
      1922271.93     13958716.70      1922275.54     13958695.44
      1922274.60     13958559.84      1922276.89     13958530.79
      1922287.92     13958511.50      1922325.00     13958475.00

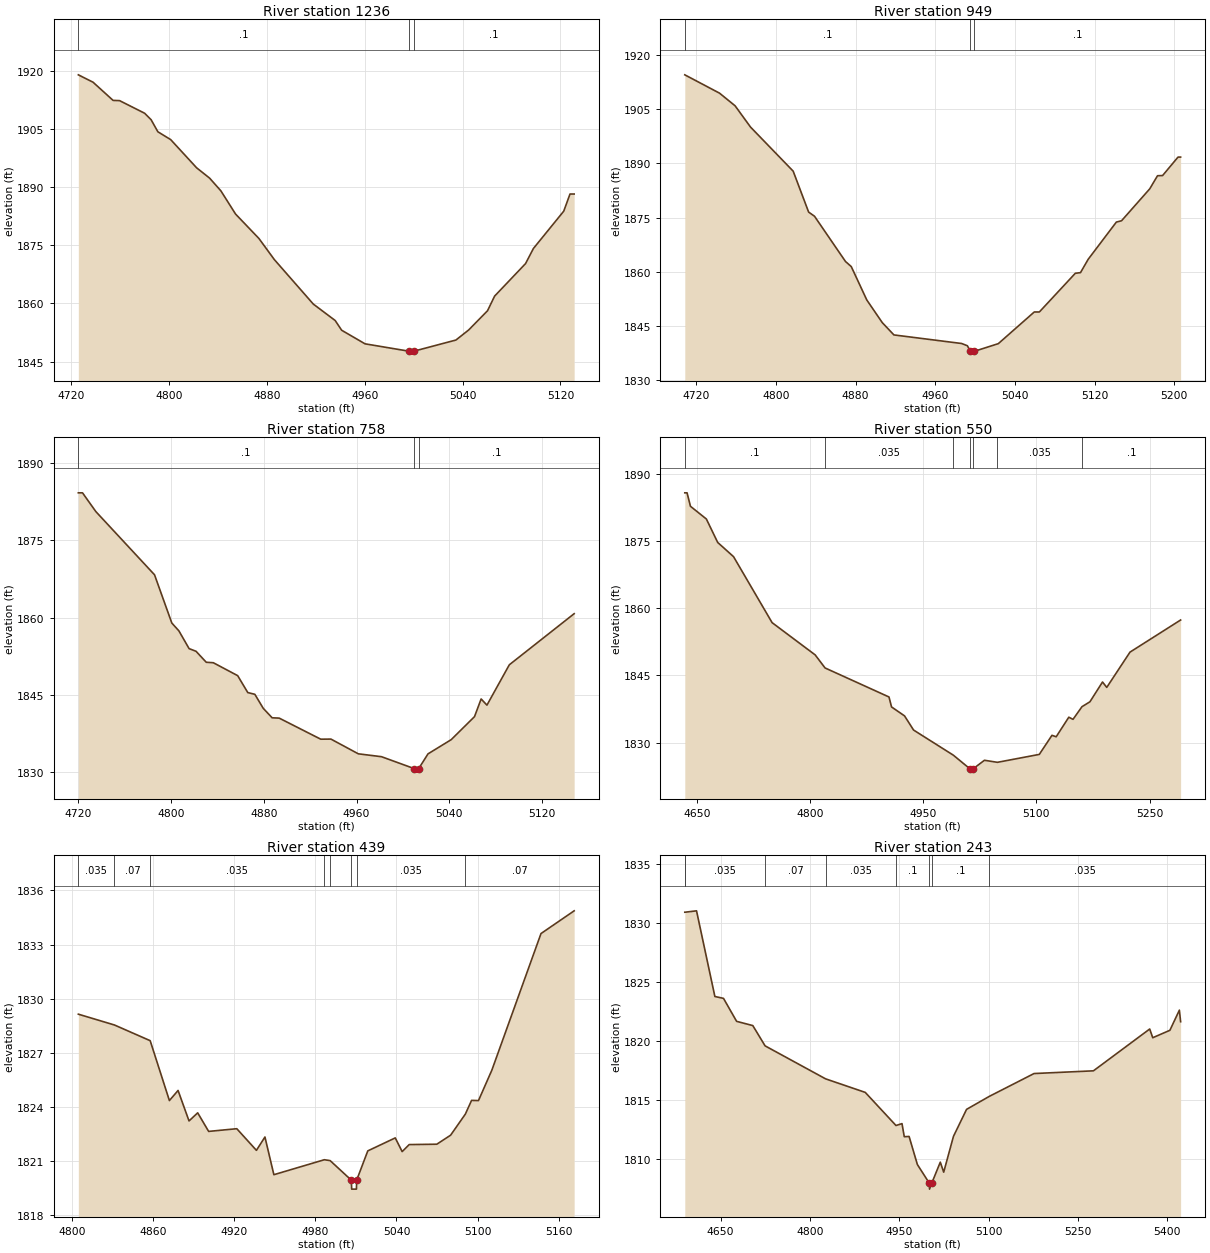
Type RM Length L Ch R = 1,1236,287,287,287
BEGIN DESCRIPTION:
Stream0501 3.0
END DESCRIPTION:
XS GIS Cut Line= 2
      1922136.37     13959619.46      1921753.55     13959486.65
#Sta/Elev= 30
  4726.0 1919.02  4738.0 1917.12  4754.4 1912.42  4759.7 1912.36  4780.2 1909.10
  4785.5 1907.42  4791.0 1904.32  4801.5 1902.29  4822.7 1895.01  4833.3 1892.35
  4842.5 1889.07  4854.5 1883.08  4873.6 1876.77  4886.2 1871.32  4918.0 1859.85
  4935.9 1855.60  4941.2 1853.09  4960.3 1849.58  4996.2 1847.68  4996.4 1847.18
  5000.2 1847.68  5034.6 1850.56  5045.0 1853.16  5060.4 1858.12  5066.2 1861.90
  5091.5 1870.30  5097.9 1874.19  5122.7 1883.83  5127.8 1888.25  5131.2 1888.25
#Mann=3,-1,0
  4726.0     0.1       0  4996.2    0.05       0  5000.2     0.1       0
Bank Sta=4996.2,5000.2
Exp/Cntr=0.3,0.1

Type RM Length L Ch R = 1,949,191,191,191
BEGIN DESCRIPTION:
Stream0501 2.0
END DESCRIPTION:
XS GIS Cut Line= 3
      1922224.96     13959424.98      1921975.00     13959275.00
      1921774.96     13959325.01
#Sta/Elev= 30
  4708.6 1914.43  4743.5 1909.36  4759.1 1905.87  4774.6 1899.99  4817.4 1887.81
  4832.9 1876.51  4838.8 1875.36  4869.9 1862.86  4875.7 1861.45  4891.3 1852.22
  4906.8 1845.98  4918.5 1842.57  4986.5 1840.20  4992.3 1839.57  4995.2 1838.04
  4995.4 1837.54  4999.2 1838.04  5023.3 1840.16  5059.4 1848.91  5064.5 1848.91
  5100.6 1859.60  5105.8 1859.78  5113.5 1863.46  5141.8 1873.75  5147.0 1874.11
  5175.3 1882.93  5183.1 1886.55  5188.2 1886.60  5203.7 1891.70  5206.3 1891.70
#Mann=3,-1,0
  4708.6     0.1       0  4995.2    0.05       0  4999.2     0.1       0
Bank Sta=4995.2,4999.2
Exp/Cntr=0.3,0.1

Type RM Length L Ch R = 1,758,208,208,208
BEGIN DESCRIPTION:
Mapping XS c7ac642b
END DESCRIPTION:
XS GIS Cut Line= 3
      1922216.02     13959216.05      1922029.42     13959086.85
      1921829.21     13959075.51
#Sta/Elev= 30
  4720.1 1884.20  4723.7 1884.20  4735.2 1880.56  4785.8 1868.29  4800.7 1858.93
  4806.8 1857.41  4815.6 1853.96  4821.6 1853.44  4830.4 1851.31  4836.5 1851.22
  4857.5 1848.71  4866.2 1845.43  4872.3 1845.09  4879.5 1842.38  4887.2 1840.53
  4893.3 1840.47  4929.1 1836.38  4937.9 1836.40  4961.5 1833.54  4981.5 1832.98
  5009.6 1830.68  5009.8 1830.18  5013.6 1830.68  5021.6 1833.53  5041.6 1836.29
  5061.7 1840.76  5067.4 1844.19  5072.4 1842.99  5091.7 1850.82  5147.6 1860.74
#Mann=3,-1,0
  4720.1     0.1       0  5009.6    0.05       0  5013.6     0.1       0
Bank Sta=5009.6,5013.6
Exp/Cntr=0.3,0.1

Type RM Length L Ch R = 1,550,111,111,111
BEGIN DESCRIPTION:
Stream0501 1.0
END DESCRIPTION:
XS GIS Cut Line= 4
      1922325.01     13959175.01      1922176.27     13958951.91
      1922064.61     13958905.20      1921824.97     13959025.01
#Sta/Elev= 30
  4634.1 1885.86  4637.1 1885.86  4641.6 1882.85  4662.7 1880.00  4677.7 1874.76
  4698.7 1871.58  4749.8 1856.82  4806.9 1849.60  4820.0 1846.68  4904.7 1840.19
  4908.1 1837.96  4925.3 1835.96  4937.3 1832.79  4990.0 1827.17  5012.1 1824.10
  5012.4 1823.60  5016.1 1824.10  5031.2 1826.03  5048.4 1825.57  5103.9 1827.34
  5120.7 1831.61  5126.3 1831.29  5143.0 1835.66  5148.6 1835.19  5160.5 1838.02
  5171.0 1839.11  5187.7 1843.54  5193.3 1842.33  5224.1 1850.22  5291.2 1857.41
#Mann=7,-1,0
  4634.1     0.1       0  4820.0   0.035       0  4990.0    0.07       0
  5012.1    0.05       0  5016.1    0.07       0  5048.4   0.035       0
  5160.5     0.1       0
Bank Sta=5012.1,5016.1
Exp/Cntr=0.3,0.1

Type RM Length L Ch R = 1,439,196,196,196
BEGIN DESCRIPTION:
Mapping XS 673d6b98
END DESCRIPTION:
XS GIS Cut Line= 3
      1922271.52     13958942.97      1922181.89     13958828.06
      1921965.39     13958785.39
#Sta/Elev= 30
  4804.9 1829.14  4831.6 1828.54  4858.0 1827.67  4872.2 1824.35  4878.6 1824.91
  4886.7 1823.22  4893.1 1823.67  4901.2 1822.64  4922.0 1822.79  4936.5 1821.59
  4942.8 1822.33  4949.4 1820.24  4986.7 1821.07  4991.0 1821.02  5006.6 1819.94
  5006.9 1819.44  5010.4 1819.44  5010.6 1819.94  5018.8 1821.56  5039.1 1822.28
  5044.2 1821.52  5049.4 1821.91  5069.8 1821.93  5080.0 1822.43  5090.9 1823.60
  5095.5 1824.36  5100.6 1824.35  5110.5 1826.04  5146.8 1833.61  5171.3 1834.87
#Mann=8,-1,0
  4804.9   0.035       0  4831.6    0.07       0  4858.0   0.035       0
  4986.7    0.07       0  4991.0   0.035       0  5006.6   0.035       0
  5010.6   0.035       0  5090.9    0.07       0
Bank Sta=5006.6,5010.6
Exp/Cntr=0.3,0.1

Type RM Length L Ch R = 1,243,0,0,0
BEGIN DESCRIPTION:
Stream0501 0.0
END DESCRIPTION:
XS GIS Cut Line= 4
      1922508.29     13959030.22      1922315.60     13958720.63
      1922128.80     13958622.61      1921877.43     13958569.67
#Sta/Elev= 30
  4589.9 1830.94  4590.0 1830.94  4609.6 1831.06  4640.4 1823.79  4654.9 1823.63
  4676.9 1821.68  4704.1 1821.32  4724.7 1819.60  4826.3 1816.80  4892.9 1815.65
  4944.5 1812.84  4954.6 1813.00  4958.4 1811.89  4966.5 1811.91  4980.4 1809.53
  5000.5 1807.94  5000.8 1807.44  5004.5 1807.94  5018.9 1809.73  5024.6 1808.88
  5041.0 1811.92  5063.0 1814.21  5101.1 1815.31  5176.3 1817.25  5276.0 1817.48
  5370.5 1821.03  5375.6 1820.29  5404.4 1820.92  5420.3 1822.63  5422.4 1821.65
#Mann=8,-1,0
  4589.9     0.1       0  4590.0   0.035       0  4724.7    0.07       0
  4826.3   0.035       0  4944.5     0.1       0  5000.5    0.05       0
  5004.5     0.1       0  5101.1   0.035       0
Bank Sta=5000.5,5004.5
Exp/Cntr=0.3,0.1

Chan Stop Cuts=-1