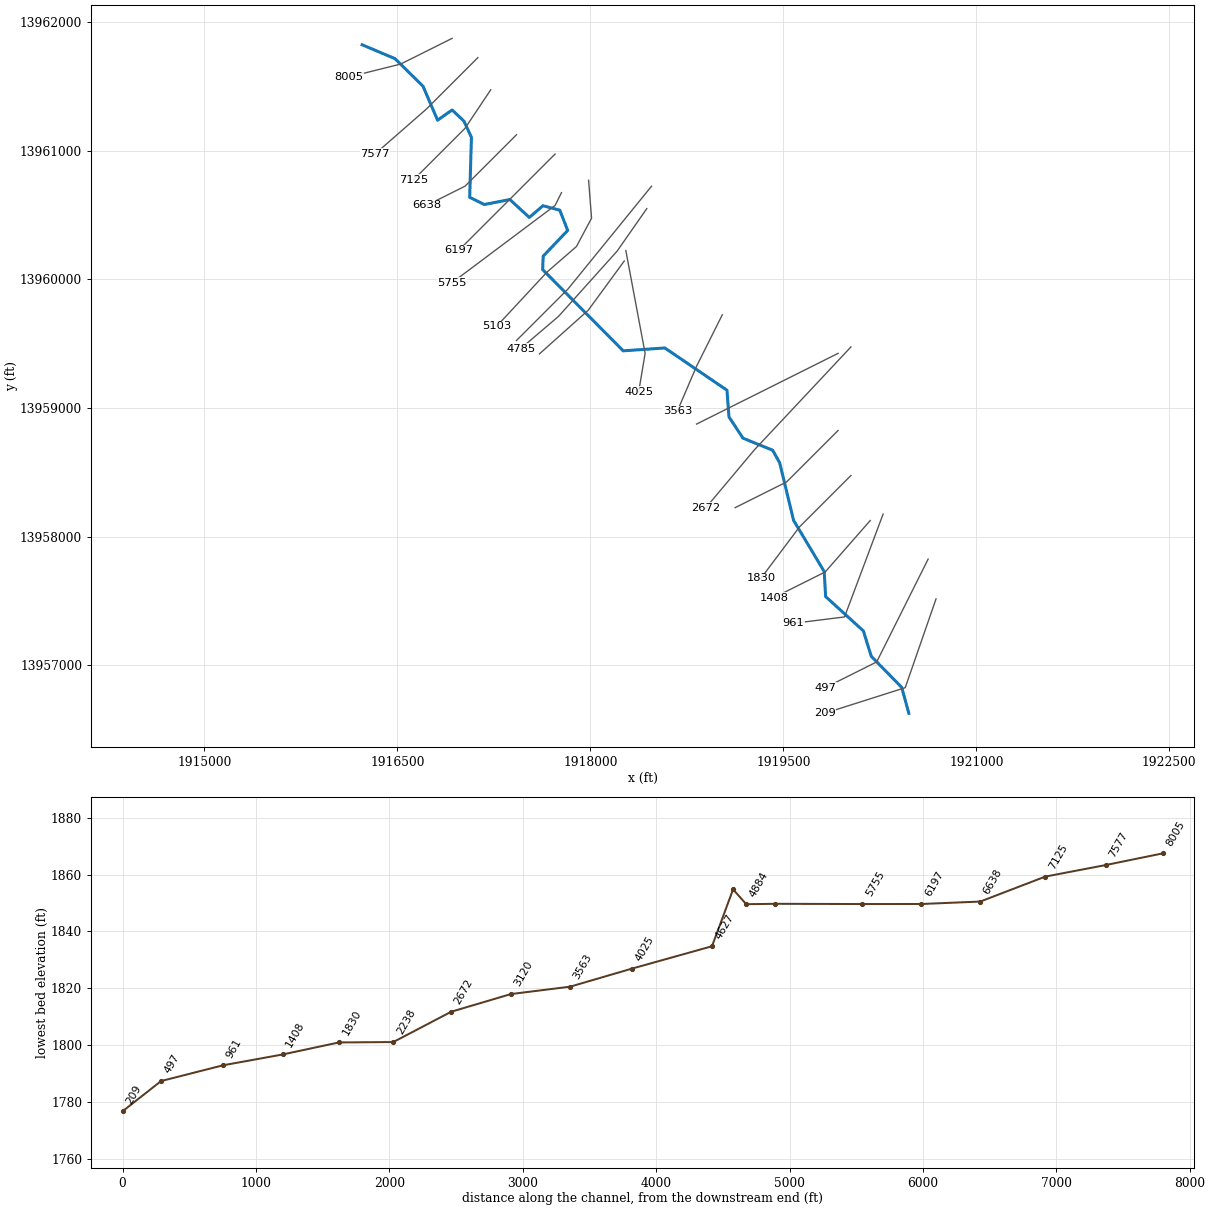
--- Stream0502.prj (project) ---

Proj Title=Stream0502 Base Level Engineering
Current Plan=p01
Default Exp/Contr=0.3,0.1
English Units
Geom File=g01
Flow File=f01
Plan File=p01
Y Axis Title=Elevation
X Axis Title(PF)=Main Channel Distance
X Axis Title(XS)=Station
BEGIN DESCRIPTION:
Stream0502
END DESCRIPTION:
DSS Export Rating Curves= 0
DSS Export Rating Curve Sorted= 0
DSS Export Volume Flow Curves= 0
DXF OffsetX= 0
DXF OffsetY= 0
DXF ScaleX= 1
DXF ScaleY= 10

--- Stream0502.p01 (plan) ---

Plan Title=Multiple Run
Short Identifier=Multiple
Geom File=g01
Flow File=f01
Subcritical Flow
K Sum by GR= 0
Std Step Tol= 0.01
Critical Tol= 0.01
Num of Std Step Trials= 20
Max Error Tol= 0.3
Flow Tol Ratio= 0.001
Split Flow NTrial= 30
Split Flow Tol= 0.02
Split Flow Ratio= 0.02
Log Output Level= 0
Friction Slope Method= 1
Unsteady Friction Slope Method= 2
Unsteady Bridges Friction Slope Method= 1
Parabolic Critical Depth
Global Vel Dist=  1 , 1 , 1
Global Log Level= 0
CheckData=True
Encroach Param= -1, 0, 0, 0
BEGIN DESCRIPTION:
Multiple Run
END DESCRIPTION:

--- Stream0502.f01 (steady flow) ---

Flow Title=Multiple
Program Version=4.10
Number of Profiles= 7
Profile Names=10-year,25-year,50-year,1pct_min,100-year,1pct_plu,500-year
River Rch & RM=Stream0502,Reach-1         ,8005
    2348    4178    5989    4139    8259   16478   15531
Boundary for River Rch & Prof#=Stream0502,Reach-1         , 1
Up Type= 0
Dn Type= 3
Dn Slope=0.008
Boundary for River Rch & Prof#=Stream0502,Reach-1         , 2
Up Type= 0
Dn Type= 3
Dn Slope=0.008
Boundary for River Rch & Prof#=Stream0502,Reach-1         , 3
Up Type= 0
Dn Type= 3
Dn Slope=0.008
Boundary for River Rch & Prof#=Stream0502,Reach-1         , 4
Up Type= 0
Dn Type= 3
Dn Slope=0.008
Boundary for River Rch & Prof#=Stream0502,Reach-1         , 5
Up Type= 0
Dn Type= 3
Dn Slope=0.008
Boundary for River Rch & Prof#=Stream0502,Reach-1         , 6
Up Type= 0
Dn Type= 3
Dn Slope=0.008
Boundary for River Rch & Prof#=Stream0502,Reach-1         , 7
Up Type= 0
Dn Type= 3
Dn Slope=0.008
DSS Import GetInterval= 0
DSS Import GetPeak= 0
DSS Import FillOption= 0

--- Stream0502.g01 (geometry) ---

Geom Title=Existing Conditions
Program Version=4.10

River Reach=Stream0502      ,Reach-1
Reach XY= 30
        1916225.       13961825.      1916481.06     13961716.86
      1916698.83     13961501.87      1916811.64      13961238.4
      1916925.01     13961317.91      1917016.86     13961231.09
      1917074.94     13961104.97      1917061.37     13960638.43
      1917174.99     13960582.53      1917373.53     13960621.47
        1917525.     13960482.08       1917630.9     13960573.02
      1917761.56     13960538.65      1917823.39     13960381.04
      1917632.76     13960181.17      1917628.45     13960076.49
      1918254.84      13959444.6      1918578.32     13959466.96
       1919061.4     13959138.21      1919076.66     13958931.05
      1919185.78     13958765.28      1919416.53     13958671.54
      1919471.19     13958573.44      1919578.82     13958126.59
      1919816.99     13957728.33      1919828.18     13957533.35
      1920121.49     13957266.52      1920182.86     13957068.83
      1920419.48     13956827.43        1920475.       13956625.

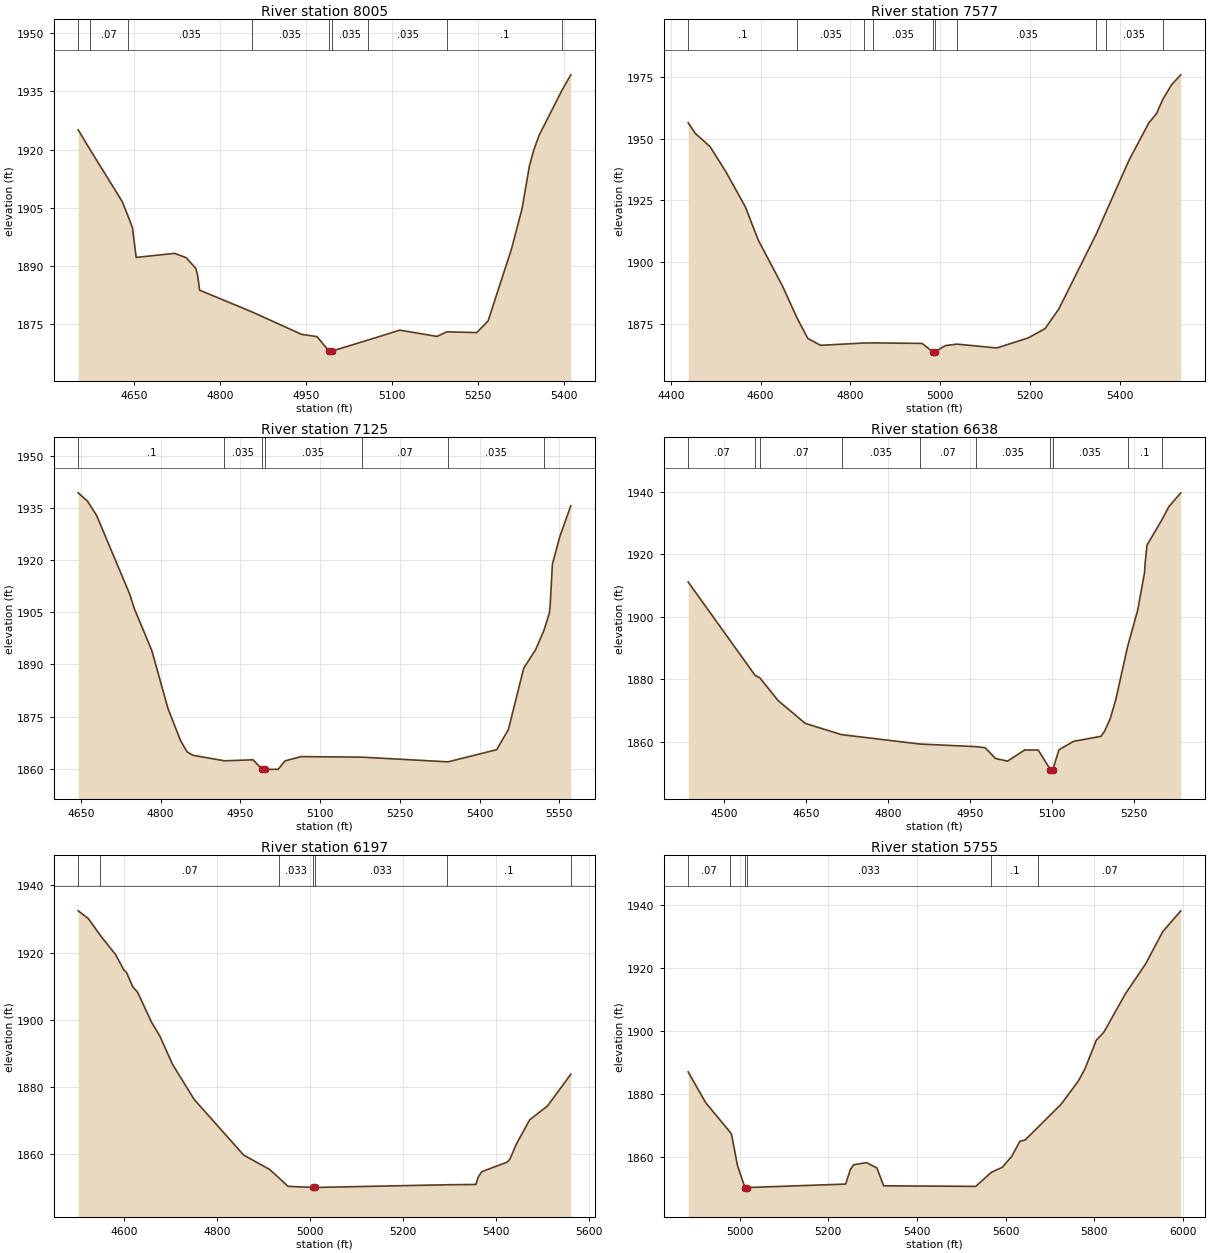
Type RM Length L Ch R = 1 ,8005    ,428,428,428
BEGIN DESCRIPTION:
Stream0502 18.0
END DESCRIPTION:
XS GIS Cut Line= 3
      1916925.02     13961875.01        1916525.       13961675.
      1916125.04     13961575.01
#Sta/Elev= 30
    4553 1925.09  4574.1  1919.9  4629.8 1906.59  4640.4 1902.68  4647.7 1899.81
  4654.2 1892.16  4721.3  1893.2  4741.4 1892.09  4758.2 1889.35  4761.5 1887.45
  4764.9 1883.71  4855.8 1878.13  4942.8  1872.3  4969.7 1871.72  4990.8 1867.96
  4991.1 1867.46  4995.1 1867.96  5059.5 1870.87  5114.1 1873.39  5179.1 1871.77
    5196 1872.95  5248.4 1872.76  5268.2 1875.77  5308.9 1894.26  5327.5 1904.76
  5340.3 1915.77    5348  1919.9  5357.3  1923.7  5397.7 1935.46  5412.5 1939.28
#Mann= 9 ,-1 , 0
    4553      .1       0  4574.1     .07       0  4640.4    .035       0
  4855.8    .035       0  4990.8    .035       0  4995.1    .035       0
  5059.5    .035       0    5196      .1       0  5397.7     .07       0
Bank Sta=4990.8,4995.1
XS Rating Curve= 0 ,0
Exp/Cntr=0.3,0.1

Type RM Length L Ch R = 1 ,7577    ,452,452,452
BEGIN DESCRIPTION:
Stream0502 17.0
END DESCRIPTION:
XS GIS Cut Line= 3
      1917124.98     13961724.98        1916725.       13961325.
      1916324.98     13960974.98
#Sta/Elev= 30
  4438.6 1956.37  4454.8 1951.99  4487.4 1946.74  4523.4 1936.32  4565.8 1922.47
  4594.8 1908.96  4648.6 1890.46  4682.1 1877.19  4705.1 1869.29  4733.4 1866.51
  4830.7 1867.43  4851.3 1867.49  4959.7 1867.26  4983.7 1863.85    4984 1863.35
    4988 1863.85  5011.3 1866.38  5037.2 1866.99  5125.8 1865.43  5196.3 1869.51
  5233.5 1873.24  5264.3 1881.22  5347.1 1911.28  5368.3 1919.95  5420.8 1941.35
  5464.7 1956.33  5481.8 1960.07  5495.8 1965.81  5515.2 1971.68  5535.8 1975.71
#Mann= 10 ,-1 , 0
  4438.6      .1       0  4682.1    .035       0  4830.7     .07       0
  4851.3    .035       0  4983.7    .035       0    4988    .035       0
  5037.2    .035       0  5347.1     .07       0  5368.3    .035       0
  5495.8     .07       0
Bank Sta=4983.7,4988
XS Rating Curve= 0 ,0
Exp/Cntr=0.3,0.1

Type RM Length L Ch R = 1 ,7125    ,487,487,487
BEGIN DESCRIPTION:
Stream0502 16.0
END DESCRIPTION:
XS GIS Cut Line= 3
        1917225.       13961475.        1917025.       13961175.
      1916625.03     13960775.03
#Sta/Elev= 30
  4645.2 1939.36  4662.6 1936.99  4679.8 1932.87  4741.9 1910.29  4751.2 1905.88
  4783.6 1894.02  4814.1  1877.3  4837.7 1868.07  4850.1 1864.81  4860.9 1863.85
  4920.2 1862.26    4974 1862.55  4991.3 1859.79  4991.6 1859.29  4995.6 1859.79
  5021.3 1859.82    5034 1862.23  5064.4 1863.47  5178.8 1863.31  5340.7 1861.96
  5432.1 1865.46  5454.1 1871.26    5483 1888.95    5505 1894.14  5521.4 1899.97
  5531.1  1904.8  5532.5 1906.68  5536.8  1918.8  5550.9 1926.84  5571.4 1935.64
#Mann= 7 ,-1 , 0
  4645.2      .1       0  4920.2    .035       0  4991.3    .035       0
  4995.6    .035       0  5178.8     .07       0  5340.7    .035       0
  5521.4     .07       0
Bank Sta=4991.3,4995.6
XS Rating Curve= 0 ,0
Exp/Cntr=0.3,0.1

Type RM Length L Ch R = 1 ,6638    ,441,441,441
BEGIN DESCRIPTION:
Stream0502 15.0
END DESCRIPTION:
XS GIS Cut Line= 3
      1917425.02     13961125.02        1917025.       13960725.
      1916725.03     13960575.01
#Sta/Elev= 30
  4433.8 1911.15  4556.4 1881.16  4564.9 1880.42  4598.6 1873.09  4648.1 1865.81
  4714.3 1862.21  4857.9 1859.19  4959.6 1858.37  4976.9 1858.02    4996 1854.57
    5018 1853.72  5049.4 1857.29    5074 1857.29  5096.4 1851.01  5096.7 1850.51
  5100.8 1851.01  5112.1 1857.36  5138.7 1860.05    5189 1861.68  5195.7 1863.37
  5205.8 1867.32  5215.8 1873.28  5237.6 1890.41  5256.1 1902.15  5268.6  1914.1
  5269.5 1916.86  5273.1 1922.96  5300.4 1931.09  5313.1  1935.3  5334.9 1939.73
#Mann= 10 ,-1 , 0
  4433.8     .07       0  4556.4      .1       0  4564.9     .07       0
  4714.3    .035       0  4857.9     .07       0  4959.6    .035       0
  5096.4    .035       0  5100.8    .035       0  5237.6      .1       0
  5300.4     .07       0
Bank Sta=5096.4,5100.8
XS Rating Curve= 0 ,0
Exp/Cntr=0.3,0.1

Type RM Length L Ch R = 1 ,6197    ,442,442,442
BEGIN DESCRIPTION:
Stream0502 14.0
END DESCRIPTION:
XS GIS Cut Line= 3
      1917724.98     13960974.98        1917375.       13960625.
      1916975.02     13960225.02
#Sta/Elev= 30
  4500.8 1932.45  4522.7 1930.15  4548.2  1925.2  4581.4 1919.41    4599  1914.9
  4604.7 1914.15  4618.8 1909.73  4628.7 1908.25  4658.4 1899.41  4676.8 1895.16
  4703.7 1886.84  4750.4 1876.37  4857.1 1859.78    4913  1855.5  4932.6 1853.05
  4952.6 1850.48  5006.9 1850.15  5007.2 1849.65  5011.5 1850.15  5295.9 1850.95
  5357.1 1851.04    5362 1853.21  5369.8 1854.85  5424.9 1857.71  5430.6 1858.65
  5444.7 1863.19    5473 1870.28  5511.2 1874.38  5561.1 1883.76  5561.4 1883.85
#Mann= 7 ,-1 , 0
  4500.8    .035       0  4548.2     .07       0  4932.6    .033       0
  5006.9    .033       0  5011.5    .033       0  5295.9      .1       0
  5561.1     .07       0
Bank Sta=5006.9,5011.5
XS Rating Curve= 0 ,0
Exp/Cntr=0.3,0.1

Type RM Length L Ch R = 1 ,5755    ,652,652,652
BEGIN DESCRIPTION:
Stream0502 13.0
END DESCRIPTION:
XS GIS Cut Line= 3
      1917775.01     13960675.02        1917725.       13960575.
      1916925.02     13959975.02
#Sta/Elev= 30
  4883.8 1886.97  4923.3 1877.17  4978.3 1867.81  4981.6 1867.14  4995.1 1857.15
  5011.9 1850.13  5012.2 1849.63  5016.5 1850.13  5239.2 1851.24  5249.9 1855.88
  5257.5  1857.4  5286.3 1858.07  5309.8 1856.37    5325 1850.69  5532.8  1850.5
  5567.9 1854.97  5592.8 1856.59  5613.7 1860.01  5632.5 1864.84  5644.2 1865.27
    5673 1869.29  5725.6 1876.68  5764.2 1884.02  5779.2 1887.87  5804.9 1897.06
    5822 1899.61  5871.3    1912  5916.3 1921.37  5954.9 1931.63  5995.6 1938.26
#Mann= 6 ,-1 , 0
  4883.8     .07       0  4978.3    .033       0  5011.9    .033       0
  5016.5    .033       0  5567.9      .1       0    5673     .07       0
Bank Sta=5011.9,5016.5
XS Rating Curve= 0 ,0
Exp/Cntr=0.3,0.1

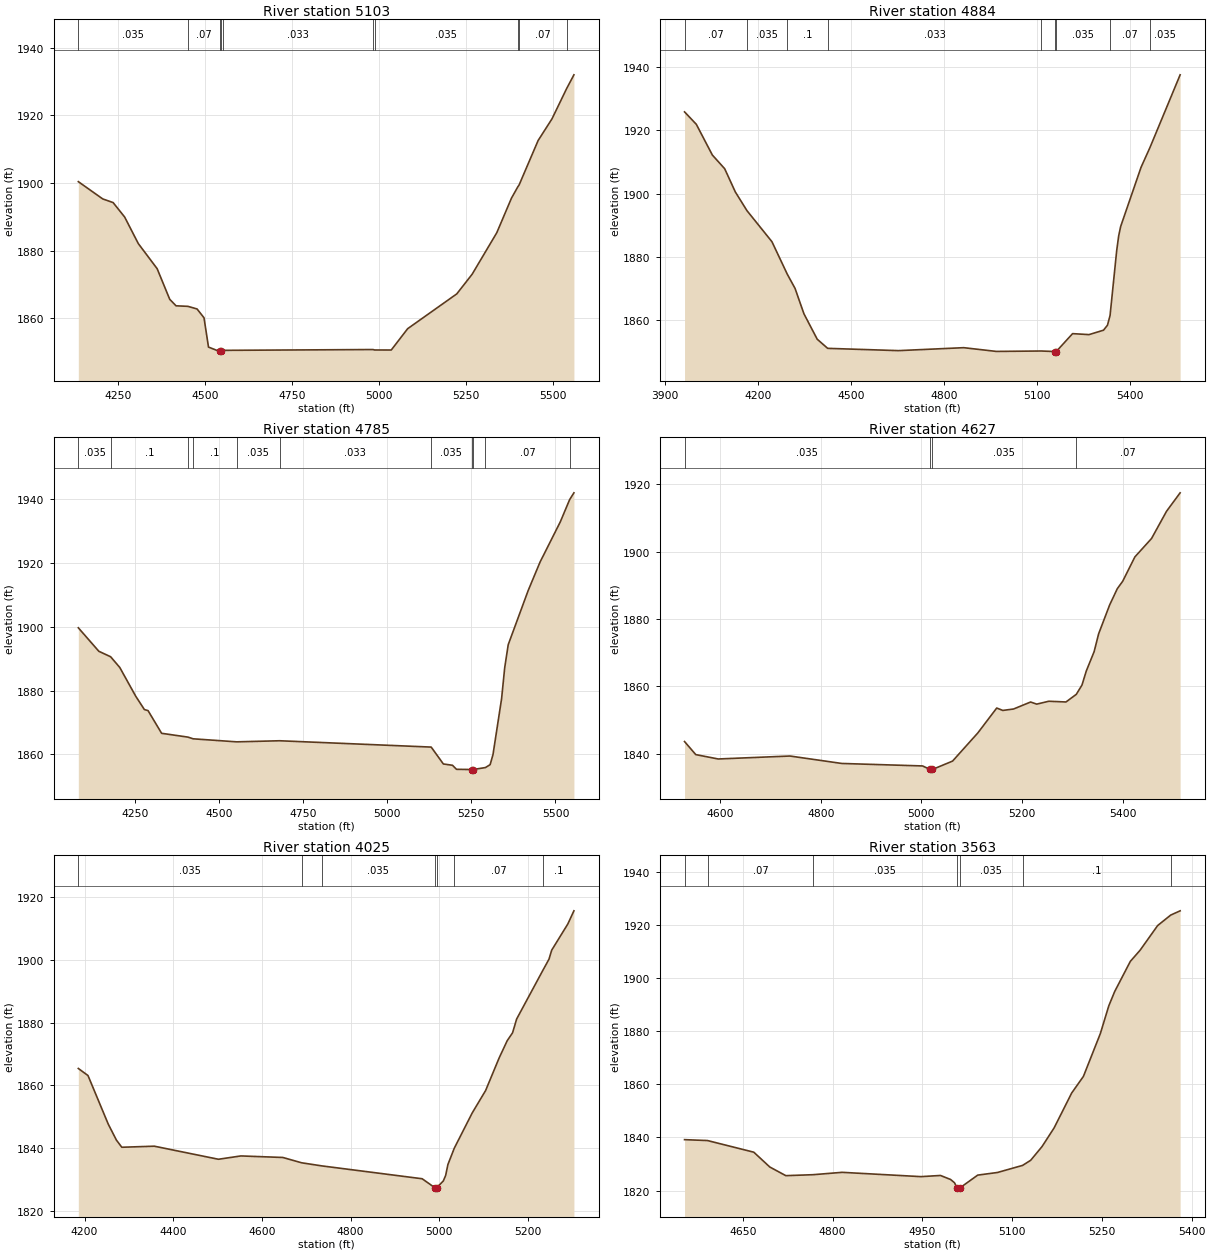
Type RM Length L Ch R = 1 ,5103    ,219,219,219
BEGIN DESCRIPTION:
Stream0502 12.0
END DESCRIPTION:
XS GIS Cut Line= 5
      1917985.65     13960771.23      1918008.77      13960476.5
      1917891.31     13960255.87      1917664.01     13960058.63
       1917271.6      13959636.2
#Sta/Elev= 30
  4136.9 1900.38  4206.8 1895.29  4236.9 1894.19    4270 1889.92  4309.1 1882.09
  4363.3 1874.66  4399.4 1865.62  4417.5  1863.7  4451.7 1863.54  4477.8 1862.77
  4497.8 1860.17  4510.7 1851.51  4542.3 1850.22  4542.6 1849.72    4547 1850.22
  4551.4 1850.54  4982.9 1850.78  4987.7 1850.65  5035.5 1850.64  5082.6 1856.94
  5223.7 1867.23  5267.7 1873.02  5338.5 1885.29  5380.8 1895.53  5399.2  1898.9
  5402.6  1899.4  5457.2 1912.53    5497 1918.93  5539.3 1927.92    5560 1931.94
#Mann= 10 ,-1 , 0
  4136.9    .035       0  4451.7     .07       0  4542.3    .035       0
    4547     .07       0  4551.4    .033       0  4982.9     .07       0
  4987.7    .035       0  5399.2      .1       0  5402.6     .07       0
  5539.3      .1       0
Bank Sta=4542.3,4547
XS Rating Curve= 0 ,0
Exp/Cntr=0.3,0.1

Type RM Length L Ch R = 1 ,4884    ,99,99,99
BEGIN DESCRIPTION:
Stream0502 11.0
END DESCRIPTION:
XS GIS Cut Line= 3
      1918475.03     13960725.04        1917825.       13959925.
      1917425.01     13959525.01
#Sta/Elev= 30
  3964.5 1925.83  4002.5 1921.89  4054.1 1912.19  4093.9 1907.85    4128 1900.54
  4165.5 1894.62  4246.1 1884.79  4295.6  1874.5  4320.5 1870.03  4349.1 1862.01
  4391.9 1853.97  4425.6 1851.08  4653.6 1850.36  4863.8 1851.29  4968.9 1850.11
  5113.8 1850.24    5157 1850.07  5157.3 1849.57  5161.8 1850.07  5214.5 1855.73
  5267.5 1855.42  5314.2 1856.82  5326.9 1858.39  5335.3 1861.49  5356.6 1881.95
    5363 1886.62  5369.4  1889.6  5435.1 1908.31  5464.1 1914.63    5561 1937.54
#Mann= 9 ,-1 , 0
  3964.5     .07       0  4165.5    .035       0  4295.6      .1       0
  4425.6    .033       0  5113.8    .035       0    5157    .033       0
  5161.8    .035       0  5335.3     .07       0  5464.1    .035       0
Bank Sta=5157,5161.8
XS Rating Curve= 0 ,0
Exp/Cntr=0.3,0.1

Type RM Length L Ch R = 1 ,4785    ,158,158,158
BEGIN DESCRIPTION:
Stream0502 10.1
END DESCRIPTION:
XS GIS Cut Line= 4
      1918437.89     13960550.52      1918207.85     13960220.65
      1917752.12     13959712.84      1917456.97      13959461.1
#Sta/Elev= 30
  4082.4 1899.62  4143.4 1892.27  4178.4 1890.56  4205.5 1887.22  4253.1 1878.19
  4278.7 1874.04  4289.5 1873.72  4329.9 1866.61  4408.2 1865.42  4423.6 1864.89
  4552.9 1863.94  4680.5 1864.28  5130.8  1862.3  5166.9 1857.02    5194 1856.61
  5205.9 1855.35  5250.7 1855.28  5251.1 1854.78  5255.5 1855.28  5292.1  1855.9
  5305.9 1856.81  5314.4 1859.97  5339.9 1877.43  5349.2 1887.15  5359.6 1894.33
  5418.7 1911.22  5454.2 1920.18  5514.4 1932.77  5542.1 1939.72  5554.8 1941.84
#Mann= 11 ,-1 , 0
  4082.4    .035       0  4178.4      .1       0  4408.2    .033       0
  4423.6      .1       0  4552.9    .035       0  4680.5    .033       0
  5130.8    .035       0  5250.7    .033       0  5255.5    .035       0
  5292.1     .07       0  5542.1    .035       0
Bank Sta=5250.7,5255.5
XS Rating Curve= 0 ,0
Exp/Cntr=0.3,0.1

Type RM Length L Ch R = 1 ,4627    ,602,602,602
BEGIN DESCRIPTION:
Stream0502 10.0
END DESCRIPTION:
XS GIS Cut Line= 3
      1918263.04     13960143.49      1917983.13     13959760.61
      1917603.28     13959420.58
#Sta/Elev= 30
  4529.6 1843.56  4551.9 1839.68  4596.5 1838.38  4738.9 1839.26  4841.7 1837.05
  5002.3 1836.31  5017.1 1835.27  5017.4 1834.77  5021.9 1835.27  5061.8 1837.75
  5112.1 1846.14  5149.5 1853.52  5161.6 1852.81  5182.9 1853.23  5216.8 1855.31
  5228.9 1854.68  5252.9 1855.54    5287 1855.32  5307.5 1857.59  5318.8 1860.35
  5327.3 1864.51  5342.9 1870.27  5351.9  1875.6  5373.8 1884.18  5388.9 1888.98
  5399.6 1891.19  5423.8 1898.43  5456.9  1903.9  5486.7    1912  5513.7 1917.48
#Mann= 4 ,-1 , 0
  4529.6    .035       0  5017.1    .035       0  5021.9    .035       0
  5307.5     .07       0
Bank Sta=5017.1,5021.9
XS Rating Curve= 0 ,0
Exp/Cntr=0.3,0.1

Type RM Length L Ch R = 1 ,4025    ,462,462,462
BEGIN DESCRIPTION:
Stream0502 9.0
END DESCRIPTION:
XS GIS Cut Line= 3
      1918275.01     13960224.96        1918425.       13959425.
      1918375.01     13959125.04
#Sta/Elev= 30
    4186 1865.37  4207.8 1863.12  4253.6 1847.59  4271.9 1842.53  4284.1 1840.23
  4357.4 1840.57  4502.1  1836.4  4552.7 1837.46  4647.4 1836.97  4689.8 1835.27
  4735.5 1834.28  4961.7 1830.18  4989.8 1827.37  4990.1 1826.87  4994.8 1827.37
  5009.4 1829.48  5014.7 1831.26  5019.7  1834.7  5034.1 1839.92  5074.6 1851.19
  5104.8 1858.33  5135.2 1868.69  5153.5 1874.23  5165.6 1876.75  5174.8 1881.15
  5234.6 1896.85  5247.8 1900.25  5253.8  1903.1  5290.3 1911.48    5304 1915.67
#Mann= 7 ,-1 , 0
    4186    .035       0  4689.8     .07       0  4735.5    .035       0
  4989.8    .035       0  4994.8    .035       0  5034.1     .07       0
  5234.6      .1       0
Bank Sta=4989.8,4994.8
XS Rating Curve= 0 ,0
Exp/Cntr=0.3,0.1

Type RM Length L Ch R = 1 ,3563    ,443,443,443
BEGIN DESCRIPTION:
Stream0502 8.0
END DESCRIPTION:
XS GIS Cut Line= 3
      1919024.99     13959724.99        1918825.       13959325.
        1918675.     13958974.99
#Sta/Elev= 30
  4552.8 1839.15  4591.2 1838.81  4668.5 1834.43  4695.3 1828.85    4722  1825.6
  4767.6 1825.96  4816.1 1826.85  4947.8 1825.23  4980.4 1825.67  4997.2 1824.17
  5003.8 1822.94  5008.1 1821.03  5008.5 1820.53  5013.1 1821.03  5042.6  1825.8
  5075.6 1826.79  5117.6 1829.46  5131.1 1831.38    5150 1836.52  5170.3 1843.59
  5199.6  1856.7  5219.2 1862.95  5247.5 1879.07  5261.6  1889.5  5271.4 1894.87
  5297.6 1906.24  5313.9 1910.43  5343.2 1919.71    5365 1923.65  5380.8 1925.26
#Mann= 7 ,-1 , 0
  4552.8    .035       0  4591.2     .07       0  4767.6    .035       0
  5008.1    .035       0  5013.1    .035       0  5117.6      .1       0
    5365     .07       0
Bank Sta=5008.1,5013.1
XS Rating Curve= 0 ,0
Exp/Cntr=0.3,0.1

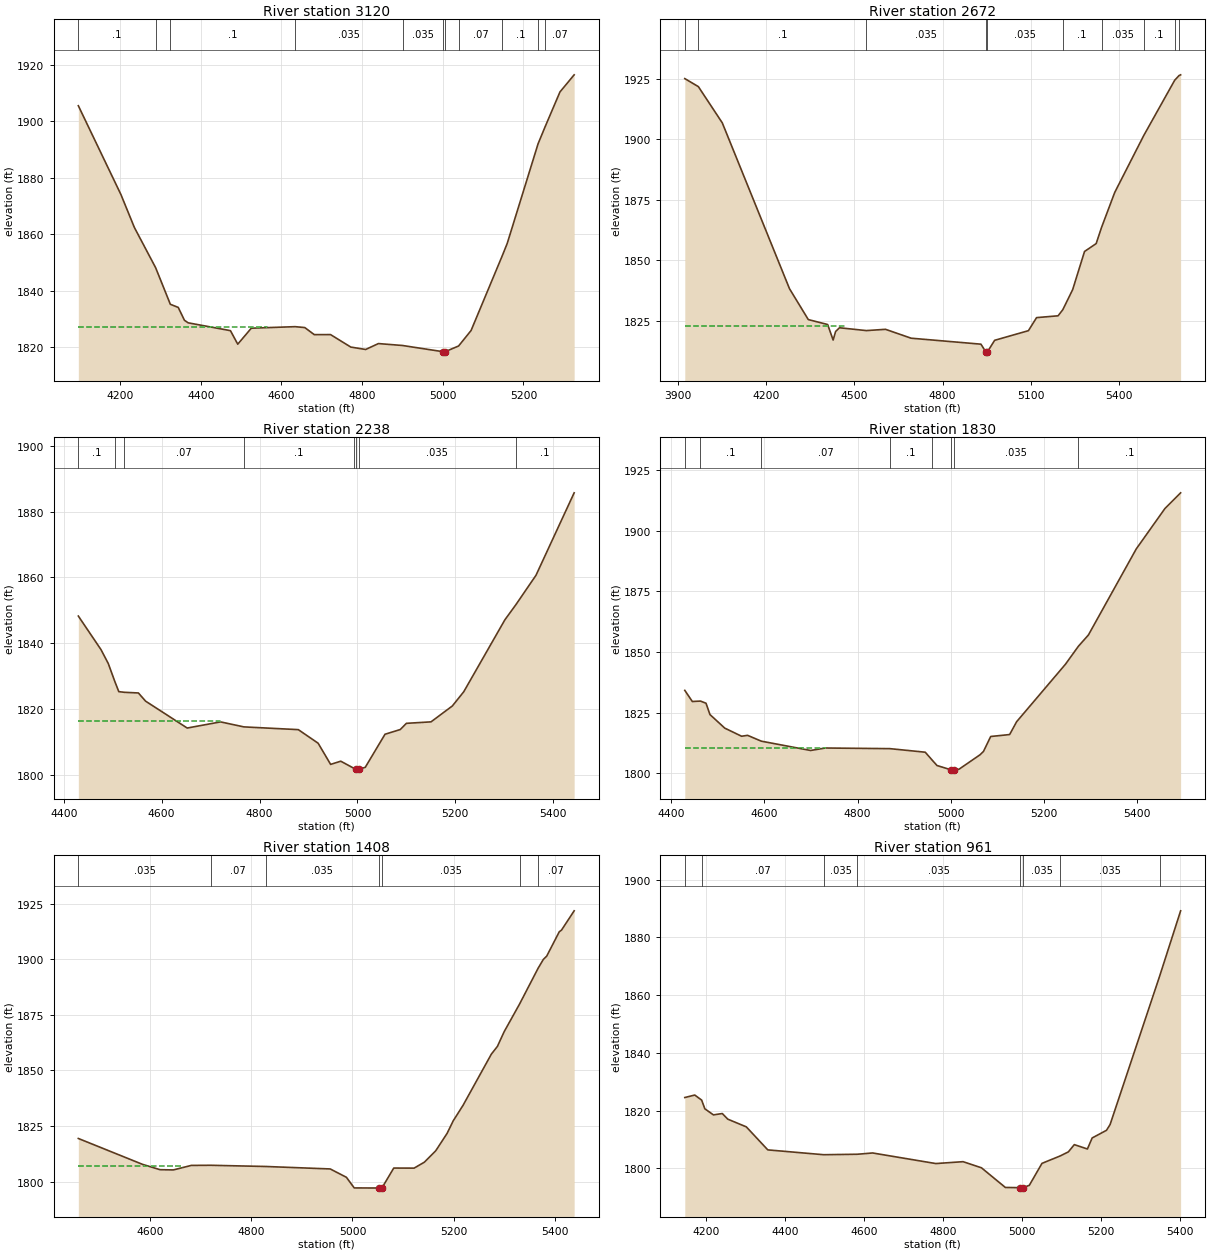
Type RM Length L Ch R = 1 ,3120    ,448,448,448
BEGIN DESCRIPTION:
Stream0502 7.0
END DESCRIPTION:
XS GIS Cut Line= 3
      1919924.98     13959424.99        1919125.       13959025.
      1918825.02     13958875.01
#Sta/Elev= 30
  4096.1 1905.45  4201.7 1874.05  4235.2 1862.36  4287.9 1848.14  4324.3 1835.22
  4343.9 1834.11  4359.3 1829.56  4368.5 1828.66  4473.4 1825.89  4491.5  1821.1
  4525.1 1826.76  4633.9  1827.3  4657.8 1826.98  4681.3 1824.48  4721.6  1824.5
  4771.9 1820.08  4808.8 1819.23  4840.4 1821.32  4900.2 1820.64  5000.8 1818.44
  5001.2 1817.94  5005.9 1818.44  5039.3 1820.47  5070.2 1825.93  5147.9 1852.49
  5159.9 1856.75  5236.5 1892.03  5254.3 1898.15  5290.7 1910.33  5325.9 1916.38
#Mann= 11 ,-1 , 0
  4096.1      .1       0  4287.9    .035       0  4324.3      .1       0
  4633.9    .035       0  4900.2    .035       0  5000.8    .035       0
  5005.9    .035       0  5039.3     .07       0  5147.9      .1       0
  5236.5    .035       0  5254.3     .07       0
#XS Ineff= 2 , 0
         4565.04 1827.31
Permanent Ineff=
       F       F
Bank Sta=5000.8,5005.9
XS Rating Curve= 0 ,0
Exp/Cntr=0.3,0.1

Type RM Length L Ch R = 1 ,2672    ,434,434,434
BEGIN DESCRIPTION:
Stream0502 6.0
END DESCRIPTION:
XS GIS Cut Line= 3
      1920025.01     13959475.01        1919275.       13958675.
      1918895.58     13958222.27
#Sta/Elev= 30
    3923 1925.14  3969.2 1921.82  4050.6 1906.85  4279.3 1838.33  4343.3 1825.57
  4409.1 1823.53  4427.8 1817.12  4436.3 1820.66  4449.5 1822.19  4540.9 1821.02
  4606.1 1821.55  4693.1 1817.88  4930.8 1815.41  4947.4 1812.21  4947.8 1811.71
  4952.6 1812.21  4977.5 1817.01  5092.4 1820.99  5120.1 1826.38  5193.3 1827.13
  5209.4 1829.66  5242.9 1837.94  5283.3 1853.71  5322.9 1856.97  5341.2 1863.65
  5386.2 1878.15  5484.9 1901.64  5590.1 1924.46  5604.9 1926.39  5610.3  1926.7
#Mann= 10 ,-1 , 0
    3923    .035       0  3969.2      .1       0  4540.9    .035       0
  4947.4    .035       0  4952.6    .035       0  5209.4      .1       0
  5341.2    .035       0  5484.9      .1       0  5590.1    .035       0
  5604.9      .1       0
#XS Ineff= 2 , 0
         4467.33 1822.91
Permanent Ineff=
       F       F
Bank Sta=4947.4,4952.6
XS Rating Curve= 0 ,0
Exp/Cntr=0.3,0.1

Type RM Length L Ch R = 1 ,2238    ,408,408,408
BEGIN DESCRIPTION:
Stream0502 5.0
END DESCRIPTION:
XS GIS Cut Line= 3
      1919924.98     13958824.98        1919525.       13958425.
      1919124.98     13958224.99
#Sta/Elev= 30
  4429.8 1848.22  4476.1 1838.01    4491 1833.77  4504.6 1828.21  4512.5 1825.22
    4524 1825.02  4552.5 1824.82  4567.3 1822.32  4652.2 1814.15  4720.3 1816.02
  4767.9  1814.5  4879.2 1813.66  4919.7 1809.53  4945.2 1803.09  4965.9 1804.06
  4993.9 1801.81  4996.2 1801.54  4996.7 1801.04  5002.4 1801.54    5016 1802.21
  5056.3 1812.26  5087.5  1813.7    5100 1815.58  5150.3 1816.03  5193.9 1820.87
  5217.2  1825.2  5301.2 1847.08  5323.8 1851.71  5364.8 1860.64  5442.7 1885.71
#Mann= 8 ,-1 , 0
  4429.8      .1       0  4504.6    .035       0    4524     .07       0
  4767.9      .1       0  4993.9    .035       0  4996.2    .035       0
  5002.4    .035       0  5323.8      .1       0
#XS Ineff= 2 , 0
         4720.08 1816.37
Permanent Ineff=
       F       F
Bank Sta=4996.2,5002.4
XS Rating Curve= 0 ,0
Exp/Cntr=0.3,0.1

Type RM Length L Ch R = 1 ,1830    ,422,422,422
BEGIN DESCRIPTION:
Stream0502 4.0
END DESCRIPTION:
XS GIS Cut Line= 3
      1920024.99     13958474.99        1919625.       13958075.
      1919324.98     13957674.98
#Sta/Elev= 30
  4428.8  1834.2    4445  1829.6  4462.5 1829.78  4474.4 1828.89  4482.9 1824.22
  4514.7 1818.63  4550.8 1815.29  4563.8 1815.65  4593.3 1813.25  4699.3 1809.41
  4731.1 1810.43  4869.6 1810.17  4945.6  1808.7  4960.5 1805.44  4970.8 1803.22
  5001.7  1801.4  5002.2  1800.9    5008  1801.4  5018.3  1801.7  5063.3 1807.63
  5070.8 1809.03  5086.3 1815.18    5127 1815.98    5142 1821.26    5247 1844.98
  5274.7 1852.36  5296.3 1857.03  5399.2 1892.53  5460.8 1909.17  5494.5 1915.64
#Mann= 8 ,-1 , 0
  4428.8    .035       0  4462.5      .1       0  4593.3     .07       0
  4869.6      .1       0  4960.5    .035       0  5001.7    .035       0
    5008    .035       0  5274.7      .1       0
#XS Ineff= 2 , 0
         4733.27 1810.54
Permanent Ineff=
       F       F
Bank Sta=5001.7,5008
XS Rating Curve= 0 ,0
Exp/Cntr=0.3,0.1

Type RM Length L Ch R = 1 ,1408    ,447,447,447
BEGIN DESCRIPTION:
Stream0502 3.0
END DESCRIPTION:
XS GIS Cut Line= 3
      1920175.01     13958125.01        1919825.       13957725.
      1919425.03     13957525.01
#Sta/Elev= 30
  4458.9 1819.43  4585.7 1807.79  4620.2  1805.4  4646.4 1805.29  4681.8 1807.32
  4719.9 1807.38  4828.5 1806.84  4956.1 1805.73    4988 1801.99  5003.5  1797.2
  5051.8 1797.16  5052.3 1796.66  5058.1 1797.16  5081.5 1806.13  5121.7  1806.1
  5142.1  1808.8  5164.5 1813.94  5186.9 1821.76  5198.9 1827.37  5218.2  1834.3
  5274.1 1857.32  5286.1 1860.81  5299.5 1867.46  5329.8 1879.84  5366.5 1895.97
  5376.9 1899.95  5383.4 1901.39  5408.2 1912.34  5412.7 1913.12  5437.6 1921.76
#Mann= 7 ,-1 , 0
  4458.9    .035       0  4719.9     .07       0  4828.5    .035       0
  5051.8    .035       0  5058.1    .035       0  5329.8      .1       0
  5366.5     .07       0
#XS Ineff= 2 , 0
         4663.74 1807.15
Permanent Ineff=
       F       F
Bank Sta=5051.8,5058.1
XS Rating Curve= 0 ,0
Exp/Cntr=0.3,0.1

Type RM Length L Ch R = 1 ,961     ,464,464,464
BEGIN DESCRIPTION:
Stream0502 2.0
END DESCRIPTION:
XS GIS Cut Line= 3
      1920274.99     13958174.98        1919975.       13957375.
      1919574.99       13957325.
#Sta/Elev= 30
  4145.3 1824.55  4170.6 1825.41    4188 1823.66  4196.2 1820.64    4218 1818.54
  4240.4 1819.01  4254.4 1817.06  4301.3  1814.4  4355.8 1806.43  4497.4 1804.76
    4583 1804.92  4621.7 1805.36  4781.9  1801.7    4851 1802.35  4897.6 1800.24
  4958.3 1793.43  4996.5 1793.35    4997 1792.85  5002.8 1793.35    5019 1794.16
  5051.2 1801.77  5097.1 1804.32  5118.1 1805.74  5133.2 1808.25  5166.4 1806.74
  5178.5 1810.56  5214.8 1813.21  5223.9 1815.19  5349.6 1866.56  5402.8 1889.16
#Mann= 8 ,-1 , 0
  4145.3    .035       0    4188     .07       0  4497.4    .035       0
    4583    .035       0  4996.5    .035       0  5002.8    .035       0
  5097.1    .035       0  5349.6      .1       0
Bank Sta=4996.5,5002.8
XS Rating Curve= 0 ,0
Exp/Cntr=0.3,0.1

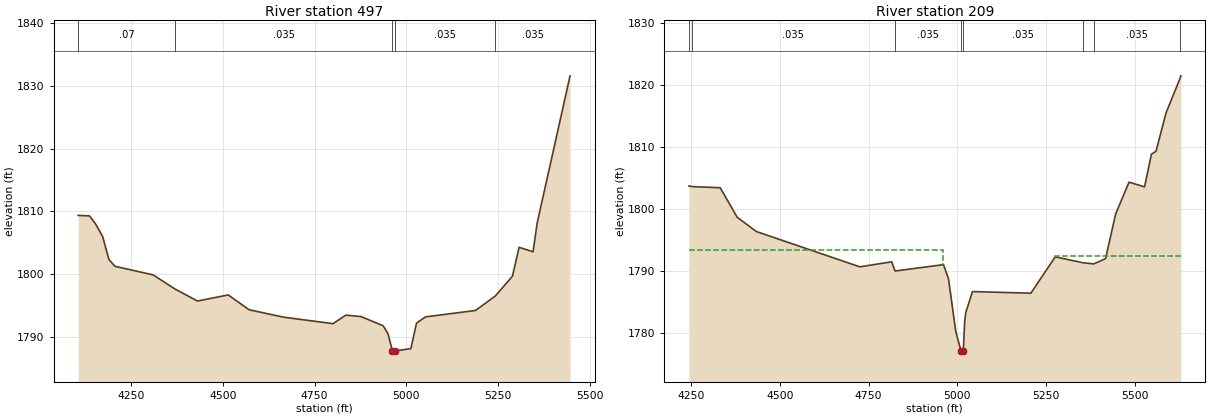
Type RM Length L Ch R = 1 ,497     ,288,288,288
BEGIN DESCRIPTION:
Stream0502 1.0
END DESCRIPTION:
XS GIS Cut Line= 3
        1920625.     13957824.99        1920225.       13957025.
      1919825.03     13956825.01
#Sta/Elev= 30
  4105.3 1809.38  4136.3  1809.3  4152.3 1808.07    4172 1806.05  4189.2 1802.37
  4205.6 1801.28    4310 1799.91    4369 1797.68  4430.7 1795.75  4514.6 1796.72
  4571.6 1794.36  4665.5 1793.18  4800.4 1792.15  4835.3  1793.5  4876.8 1793.28
  4937.2 1791.81  4950.2 1790.58  4962.6  1787.8  4963.1  1787.3    4969  1787.8
  5012.8 1788.18  5028.2 1792.24    5053 1793.23  5189.2 1794.25  5243.1 1796.55
  5289.8 1799.69    5308  1804.3    5346 1803.59  5357.2 1808.14  5446.9 1831.59
#Mann= 5 ,-1 , 0
  4105.3     .07       0    4369    .035       0  4962.6    .035       0
    4969    .035       0  5243.1    .035       0
Bank Sta=4962.6,4969
XS Rating Curve= 0 ,0
Exp/Cntr=0.3,0.1

Type RM Length L Ch R = 1 ,209     ,0,0,0
BEGIN DESCRIPTION:
Stream0502 0.0
END DESCRIPTION:
XS GIS Cut Line= 3
      1920686.29     13957515.26      1920446.91     13956824.81
      1919823.62     13956626.67
#Sta/Elev= 30
  4244.4 1803.73  4252.2 1803.63  4332.6 1803.44  4380.2  1798.7  4434.2  1796.4
  4725.5 1790.72  4815.2 1791.53  4824.8 1790.05  4961.2 1791.07  4975.2 1788.81
  4995.5 1780.38  5010.4 1777.18  5010.9 1776.68  5016.9 1777.18  5020.7 1781.95
  5023.8 1783.36  5042.7 1786.74  5207.1 1786.48  5275.7 1792.33  5354.4 1791.37
  5384.2 1791.19  5417.3 1792.04  5445.7 1799.21  5483.4 1804.34  5527.2 1803.58
  5546.4 1808.84  5559.3 1809.29  5587.8 1815.51  5627.3 1821.07  5629.2 1821.44
#Mann= 8 ,-1 , 0
  4244.4     .07       0  4252.2    .035       0  4824.8    .035       0
  5010.4     .05       0  5016.9    .035       0  5354.4     .07       0
  5384.2    .035       0  5627.3      .1       0
#XS Ineff= 2 , 0
         4958.74 1793.37 5276.23         1792.42
Permanent Ineff=
       F       F
Bank Sta=5010.4,5016.9
XS Rating Curve= 0 ,0
Exp/Cntr=0.3,0.1

Chan Stop Cuts=-1
Use User Specified Reach Order=0
Composite Channel Slope=5