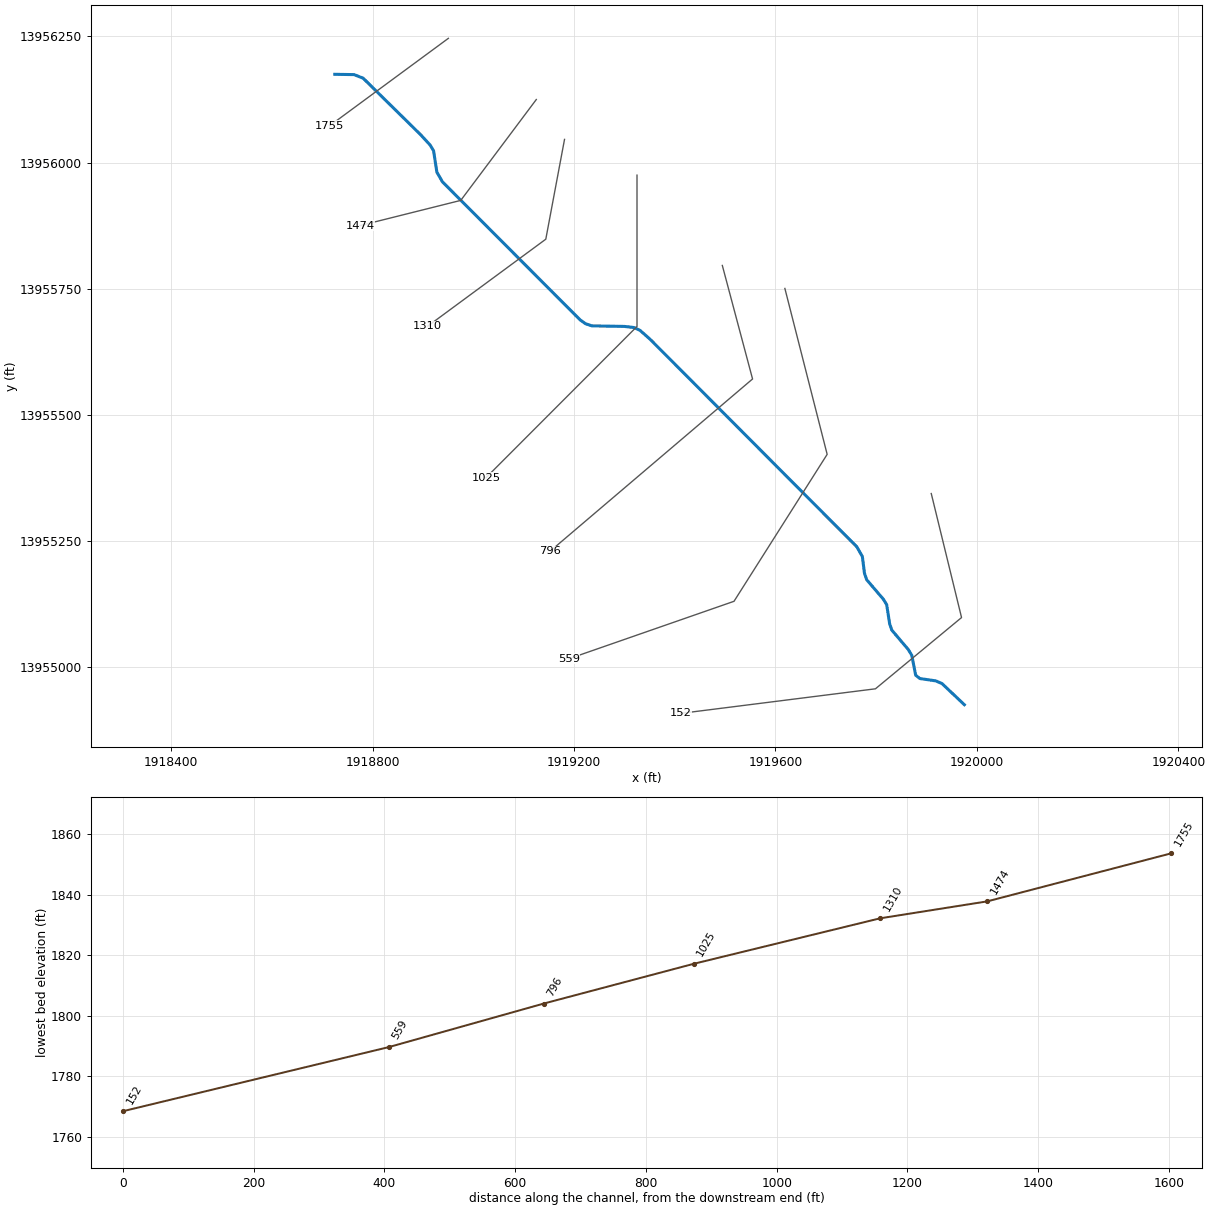
--- Stream0503.prj (project) ---

Proj Title=Stream0503 Base Level Engineering
Current Plan=p01
Default Exp/Contr=0.3,0.1
English Units
Geom File=g01
Flow File=f01
Plan File=p01
Y Axis Title=Elevation
X Axis Title(PF)=Main Channel Distance
X Axis Title(XS)=Station
BEGIN DESCRIPTION:
Stream0503
END DESCRIPTION:
DSS Export Rating Curves= 0
DSS Export Rating Curve Sorted= 0
DSS Export Volume Flow Curves= 0
DXF OffsetX= 0
DXF OffsetY= 0
DXF ScaleX= 1
DXF ScaleY= 10

--- Stream0503.p01 (plan) ---

Plan Title=Multiple Run
Short Identifier=Multiple
Geom File=g01
Flow File=f01
Subcritical Flow
K Sum by GR= 0
Std Step Tol= 0.01
Critical Tol= 0.01
Num of Std Step Trials= 20
Max Error Tol= 0.3
Flow Tol Ratio= 0.001
Split Flow NTrial= 30
Split Flow Tol= 0.02
Split Flow Ratio= 0.02
Log Output Level= 0
Friction Slope Method= 1
Unsteady Friction Slope Method= 2
Unsteady Bridges Friction Slope Method= 1
Parabolic Critical Depth
Global Vel Dist=  1 , 1 , 1
Global Log Level= 0
CheckData=True
Encroach Param= -1, 0, 0, 0
BEGIN DESCRIPTION:
Multiple Run
END DESCRIPTION:

--- Stream0503.f01 (steady flow) ---

Flow Title=Multiple
Number of Profiles=7
Profile Names=10-year,25-year,50-year,1pct_min,100-year,1pct_plu,500-year
River Rch & RM= Stream0503,Reach-1,1755
     179     268     344     215     429     857     655
Boundary for River Rch & Prof#=Stream0503,Reach-1,1
Up Type=0
Dn Type=3
Dn Slope=0.005
Boundary for River Rch & Prof#=Stream0503,Reach-1,2
Up Type=0
Dn Type=3
Dn Slope=0.005
Boundary for River Rch & Prof#=Stream0503,Reach-1,3
Up Type=0
Dn Type=3
Dn Slope=0.005
Boundary for River Rch & Prof#=Stream0503,Reach-1,4
Up Type=0
Dn Type=3
Dn Slope=0.005
Boundary for River Rch & Prof#=Stream0503,Reach-1,5
Up Type=0
Dn Type=3
Dn Slope=0.005
Boundary for River Rch & Prof#=Stream0503,Reach-1,6
Up Type=0
Dn Type=3
Dn Slope=0.005
Boundary for River Rch & Prof#=Stream0503,Reach-1,7
Up Type=0
Dn Type=3
Dn Slope=0.005

--- Stream0503.g01 (geometry) ---

Geom Title=Existing Conditions
Program Version=4.10

River Reach=Stream0503      ,Reach-1
Reach XY= 30
        1918725.       13956175.      1918763.16     13956174.41
      1918781.21     13956167.24      1918895.39     13956055.16
      1918914.22     13956034.68      1918921.02     13956023.35
      1918927.53     13955981.05      1918938.63     13955961.79
       1919211.7      13955688.4      1919222.57     13955680.52
      1919235.48     13955676.17      1919300.04     13955675.08
      1919319.11     13955672.85      1919331.17     13955667.14
      1919351.87     13955648.82      1919761.38     13955238.21
       1919772.5     13955218.97       1919776.7      13955185.7
       1919781.1     13955172.81      1919813.92     13955134.55
      1919820.84     13955123.27      1919826.65     13955085.67
      1919831.06     13955072.77       1919863.8     13955034.29
      1919870.68     13955022.91      1919878.43     13954983.34
      1919886.82     13954976.85       1919918.4     13954972.21
       1919930.7     13954966.88        1919975.       13954925.

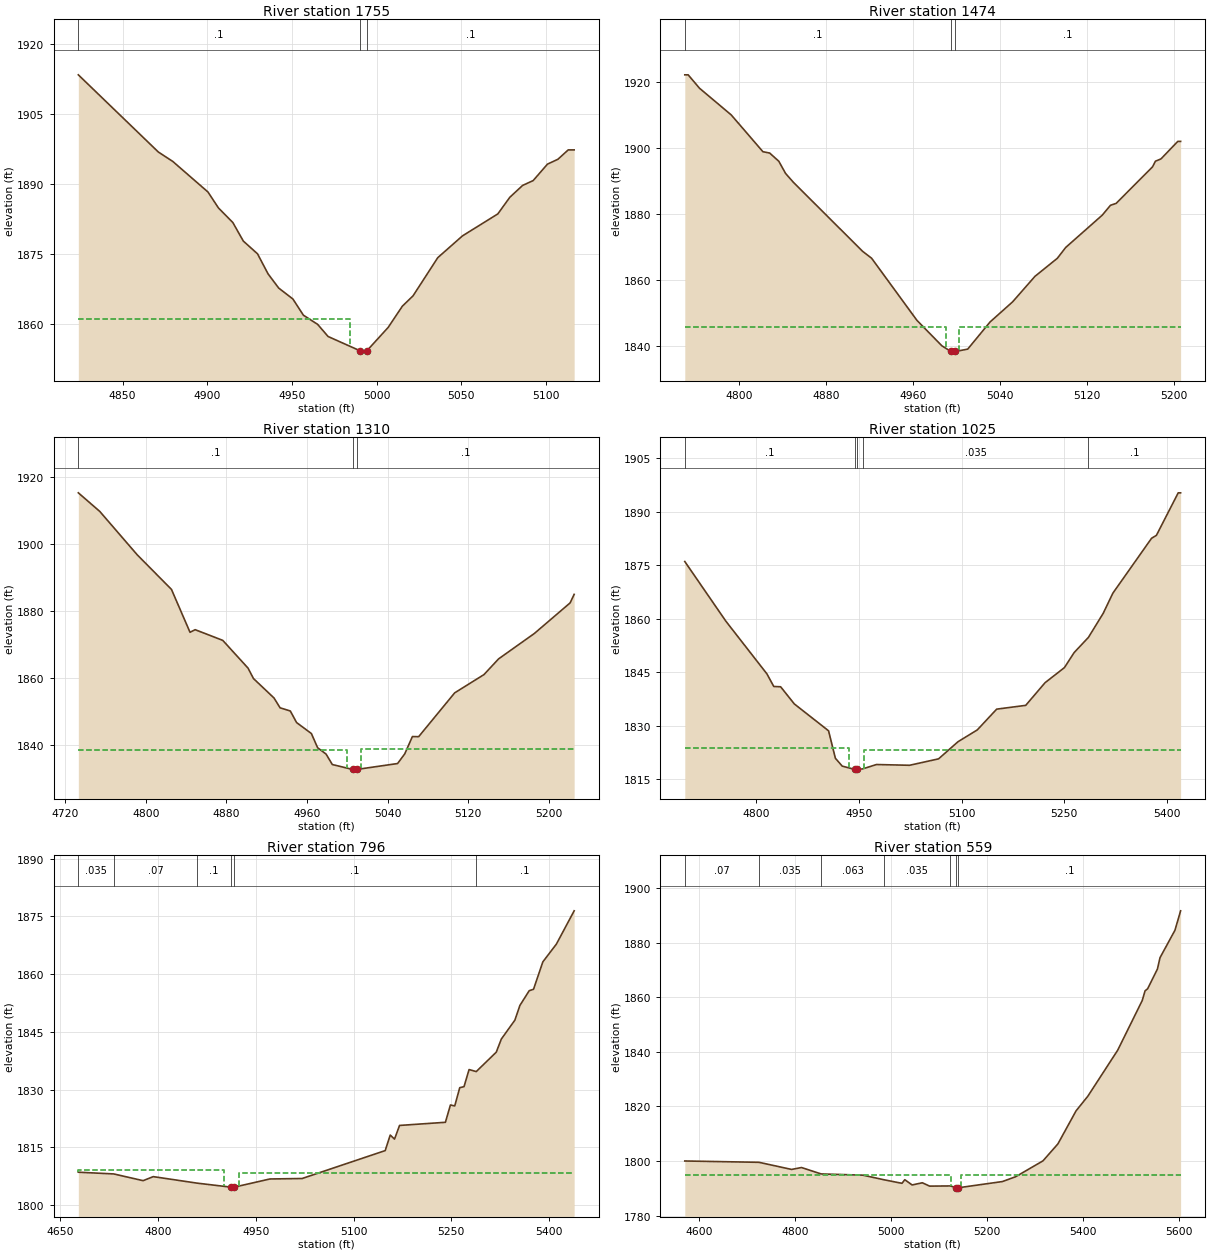
Type RM Length L Ch R = 1 ,1755    ,281,281,281
BEGIN DESCRIPTION:
Stream0503 3.0
END DESCRIPTION:
XS GIS Cut Line= 2
      1918950.42     13956246.34      1918714.36     13956072.77
#Sta/Elev= 30
  4823.8 1913.38  4871.1 1896.83  4879.6 1894.82  4900.4 1888.27  4906.6 1884.85
  4915.1 1881.72  4921.3 1877.75  4929.7 1875.01  4935.9 1870.73  4942.2 1867.68
  4950.6 1865.33  4956.8 1861.86  4965.2  1859.9  4971.4 1857.29  4990.3 1854.23
  4990.5 1853.73  4994.3 1854.23  5006.9 1859.24  5015.3  1863.8  5021.6 1866.01
  5036.2 1874.19  5050.8 1878.86  5071.7 1883.57  5078.8 1887.14  5086.3 1889.66
  5092.6 1890.72    5101 1894.23  5107.2 1895.28  5113.3 1897.29  5116.8 1897.29
#Mann= 3 ,-1 , 0
  4823.8      .1       0  4990.3     .05       0  4994.3      .1       0
#XS Ineff= 2 , 0
         4984.47 1860.95
Permanent Ineff=
       F       F
Bank Sta=4990.3,4994.3
XS Rating Curve= 0 ,0
Exp/Cntr=0.3,0.1

Type RM Length L Ch R = 1 ,1474    ,164,164,164
BEGIN DESCRIPTION:
Stream0503 2.0
END DESCRIPTION:
XS GIS Cut Line= 3
      1919125.01     13956125.01        1918975.       13955925.
      1918774.97     13955874.99
#Sta/Elev= 30
  4749.7 1922.12  4752.8 1922.12  4763.3 1918.04  4792.4 1909.99  4821.6 1898.84
  4827.8 1898.44  4836.2 1895.96  4842.4 1892.28  4849.7 1889.55  4913.3 1868.69
  4921.6 1866.59  4963.3 1847.79  4986.2  1840.1  4994.6 1838.37  4994.8 1837.87
  4998.6 1838.37    5010 1839.08  5030.6 1847.31  5051.3 1853.39  5071.9 1861.12
  5092.5 1866.59  5100.2 1869.87  5133.7 1879.61  5141.4 1882.63  5146.6 1883.21
  5180.1 1894.28  5182.7 1895.97  5187.8 1896.66  5203.3 1901.97  5205.9 1901.97
#Mann= 3 ,-1 , 0
  4749.7      .1       0  4994.6     .05       0  4998.6      .1       0
#XS Ineff= 2 , 0
         4990.21 1845.82 5002.41         1845.82
Permanent Ineff=
       F       F
Bank Sta=4994.6,4998.6
XS Rating Curve= 0 ,0
Exp/Cntr=0.3,0.1

Type RM Length L Ch R = 1 ,1310    ,285,285,285
BEGIN DESCRIPTION:
Mapping XS b7301af7
END DESCRIPTION:
XS GIS Cut Line= 3
      1919181.06     13956045.91      1919143.88     13955848.04
      1918909.49     13955675.65
#Sta/Elev= 30
  4732.9 1915.33  4754.2 1909.78  4791.3 1896.85  4825.4 1886.49  4843.8  1873.7
  4848.9 1874.48  4876.3 1871.29  4901.4 1863.01  4906.8 1859.89  4927.2 1854.09
  4933.2 1851.16  4943.4 1850.21  4949.6 1846.76  4964.3 1843.48  4970.5 1839.24
  4978.9 1837.34  4985.1 1834.23  5005.3 1832.76  5005.6 1832.26  5009.3 1832.76
  5049.9 1834.53    5057 1837.42  5064.6 1842.58  5070.8 1842.54  5106.6 1855.63
  5135.6 1861.06  5150.2 1865.77  5185.7 1873.35  5221.2 1882.48  5225.2 1885.02
#Mann= 3 ,-1 , 0
  4732.9      .1       0  5005.3     .05       0  5009.3      .1       0
#XS Ineff= 2 , 0
         5000.11  1838.7 5014.01         1838.81
Permanent Ineff=
       F       F
Bank Sta=5005.3,5009.3
XS Rating Curve= 0 ,0
Exp/Cntr=0.3,0.1

Type RM Length L Ch R = 1 ,1025    ,229,229,229
BEGIN DESCRIPTION:
Stream0503 1.0
END DESCRIPTION:
XS GIS Cut Line= 3
        1919325.     13955975.04        1919325.       13955675.
        1919025.       13955375.
#Sta/Elev= 30
  4695.6 1875.99  4755.6 1859.26  4815.6 1844.48  4825.6 1840.95  4835.6 1840.87
  4855.6 1836.06  4905.6 1828.53  4915.6 1820.82  4925.6 1818.62  4943.6 1817.72
  4943.9 1817.22  4947.6 1817.72  4955.3 1817.84  4975.6 1819.07  5023.9 1818.86
  5066.3 1820.66  5094.6 1825.45  5122.9 1828.78  5151.2  1834.6  5193.6 1835.66
  5221.9 1842.02  5250.2 1846.25  5264.3 1850.45  5285.3 1854.74  5306.8 1861.46
  5320.9 1867.11  5377.5 1882.52  5384.5 1883.32  5416.4 1895.25  5419.9 1895.25
#Mann= 5 ,-1 , 0
  4695.6      .1       0  4943.6     .05       0  4947.6      .1       0
  4955.3    .035       0  5285.3      .1       0
#XS Ineff= 2 , 0
         4935.68 1823.68 4957.07         1823.22
Permanent Ineff=
       F       F
Bank Sta=4943.6,4947.6
XS Rating Curve= 0 ,0
Exp/Cntr=0.3,0.1

Type RM Length L Ch R = 1 ,796     ,237,237,237
BEGIN DESCRIPTION:
Mapping XS 19244544
END DESCRIPTION:
XS GIS Cut Line= 3
      1919494.43     13955795.98      1919554.48     13955570.87
      1919152.69     13955229.51
#Sta/Elev= 30
  4678.1  1808.5  4732.4 1808.05  4777.4  1806.3    4793 1807.35  4860.1 1805.66
  4912.7  1804.6  4912.9  1804.1  4916.7  1804.6  4971.8 1806.74  5021.2 1806.86
  5148.6 1814.12  5156.3 1818.16  5162.9 1817.11  5170.6 1820.66  5240.9 1821.48
  5248.6 1825.98  5255.2 1825.73  5262.9 1830.48  5269.4 1830.74  5277.2 1835.19
  5288.2 1834.67  5318.9 1839.72  5326.6 1843.11  5347.4 1848.04  5355.1 1851.86
  5369.4  1855.7    5376 1856.07  5390.3  1863.2  5411.1 1867.83  5438.3 1876.47
#Mann= 6 ,-1 , 0
  4678.1    .035       0  4732.4     .07       0  4860.1      .1       0
  4912.7     .05       0  4916.7      .1       0  5288.2      .1       0
#XS Ineff= 2 , 0
         4900.72 1809.18 4924.43         1808.35
Permanent Ineff=
       F       F
Bank Sta=4912.7,4916.7
XS Rating Curve= 0 ,0
Exp/Cntr=0.3,0.1

Type RM Length L Ch R = 1 ,559     ,407,407,407
BEGIN DESCRIPTION:
Stream0503 0.0
END DESCRIPTION:
XS GIS Cut Line= 4
      1919618.66      13955750.4      1919702.63     13955421.37
      1919517.65     13955130.01      1919189.41     13955015.92
#Sta/Elev= 30
  4570.6 1800.02  4725.2 1799.53  4792.9 1796.92  4813.5 1797.62  4854.5 1795.27
  4941.4 1794.82  4985.6 1793.12  5022.7 1791.83  5028.6 1793.15  5043.9 1791.23
  5065.1 1792.03  5080.3  1790.8  5123.5 1790.87  5135.9  1790.2  5136.2  1789.7
  5139.9  1790.2  5231.9 1792.48  5259.4 1794.25  5316.3 1800.07  5347.4  1806.3
  5385.1  1818.4  5409.6 1823.76  5471.8 1840.64  5522.8 1858.83  5528.8 1862.41
  5534.1 1863.17  5554.5 1870.39  5559.9 1874.57    5591 1884.63  5602.8 1891.75
#Mann= 7 ,-1 , 0
  4570.6     .07       0  4725.2    .035       0  4854.5    .063       0
  4985.6    .035       0  5123.5      .1       0  5135.9     .05       0
  5139.9      .1       0
#XS Ineff= 2 , 0
         5124.33  1794.7 5145.71         1795.01
Permanent Ineff=
       F       F
Bank Sta=5135.9,5139.9
XS Rating Curve= 0 ,0
Exp/Cntr=0.3,0.1

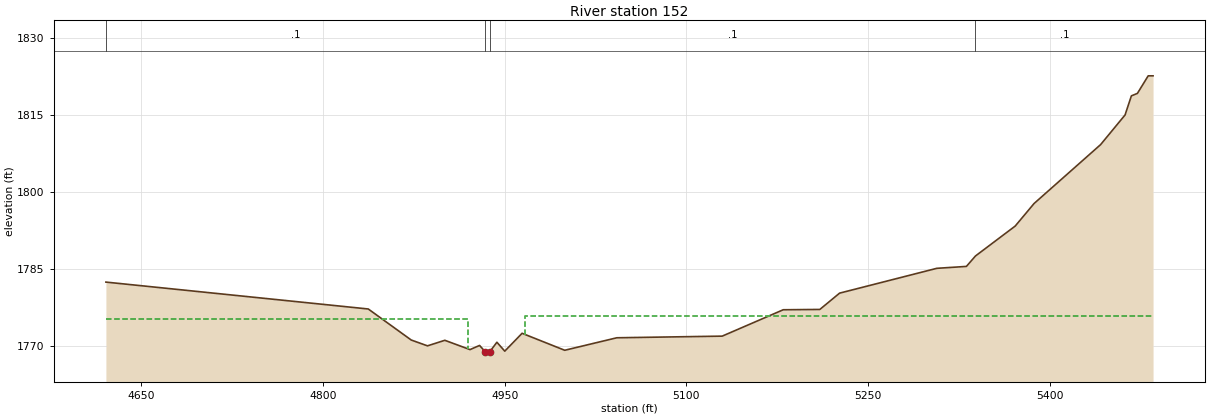
Type RM Length L Ch R = 1 ,152     ,0,0,0
BEGIN DESCRIPTION:
Stream0503 0.1
END DESCRIPTION:
XS GIS Cut Line= 4
      1919909.34     13955343.72      1919969.51     13955097.78
      1919798.53     13954956.49      1919412.08     13954907.77
#Sta/Elev= 30
  4620.8 1782.49  4837.4 1777.26  4872.9 1771.22  4886.3 1770.09  4900.6 1771.17
  4921.4 1769.36  4929.3 1770.17  4933.8 1768.98    4934 1768.48  4937.8 1768.98
  4943.6 1770.79  4950.1 1769.06  4964.4 1772.53  4999.6 1769.23  5042.6 1771.66
  5129.6 1771.98    5180 1777.11  5210.2 1777.17  5226.5 1780.34  5306.8 1785.17
  5331.2 1785.54  5338.7 1787.57  5371.5 1793.39  5387.1 1797.78    5442 1809.23
  5462.2    1815  5467.4 1818.71  5472.4  1819.2  5481.3 1822.61  5485.3 1822.61
#Mann= 4 ,-1 , 0
  4620.8      .1       0  4933.8     .05       0  4937.8      .1       0
  5338.7      .1       0
#XS Ineff= 2 , 0
         4919.54 1775.39 4967.16         1775.98
Permanent Ineff=
       F       F
Bank Sta=4933.8,4937.8
XS Rating Curve= 0 ,0
Exp/Cntr=0.3,0.1

Chan Stop Cuts=-1
Use User Specified Reach Order=0
Composite Channel Slope=5