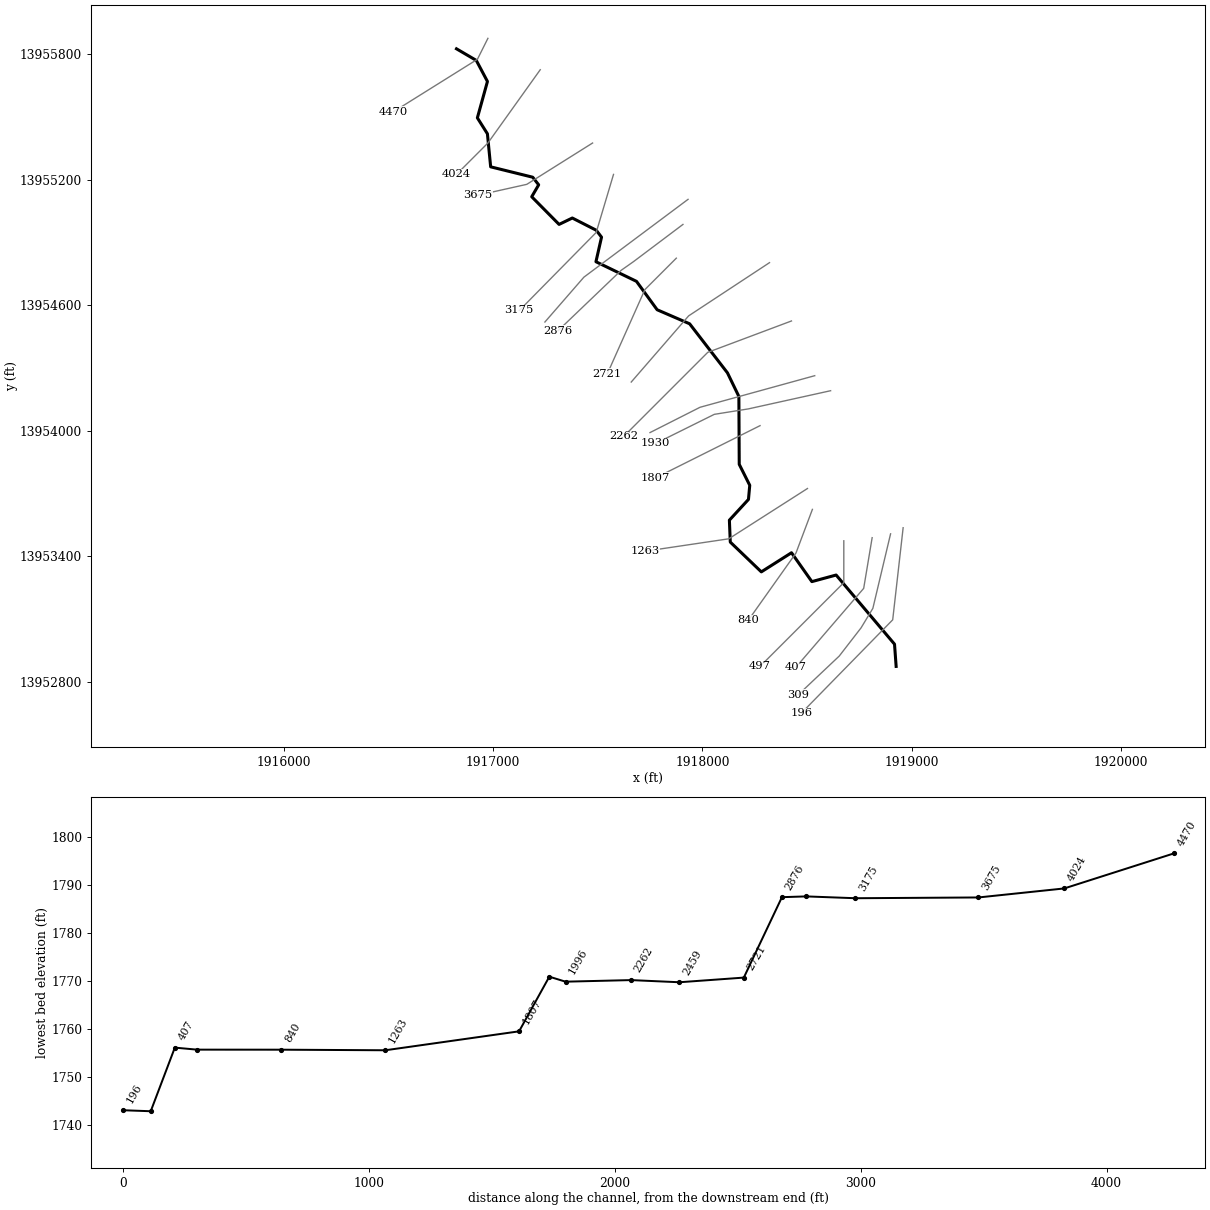
--- Stream0504.prj (project) ---

Proj Title=Stream0504 Base Level Engineering
Current Plan=p01
Default Exp/Contr=0.3,0.1
English Units
Geom File=g01
Flow File=f01
Plan File=p01
Y Axis Title=Elevation
X Axis Title(PF)=Main Channel Distance
X Axis Title(XS)=Station
BEGIN DESCRIPTION:
Stream0504
END DESCRIPTION:
DSS Export Rating Curves= 0
DSS Export Rating Curve Sorted= 0
DSS Export Volume Flow Curves= 0
DXF OffsetX= 0
DXF OffsetY= 0
DXF ScaleX= 1
DXF ScaleY= 10

--- Stream0504.p01 (plan) ---

Plan Title=Multiple Run
Short Identifier=Multiple
Geom File=g01
Flow File=f01
Subcritical Flow
K Sum by GR= 0
Std Step Tol= 0.01
Critical Tol= 0.01
Num of Std Step Trials= 20
Max Error Tol= 0.3
Flow Tol Ratio= 0.001
Split Flow NTrial= 30
Split Flow Tol= 0.02
Split Flow Ratio= 0.02
Log Output Level= 0
Friction Slope Method= 1
Unsteady Friction Slope Method= 2
Unsteady Bridges Friction Slope Method= 1
Parabolic Critical Depth
Global Vel Dist=  1 , 1 , 1
Global Log Level= 0
CheckData=True
Encroach Param= -1, 0, 0, 0
BEGIN DESCRIPTION:
Multiple Run
END DESCRIPTION:

--- Stream0504.f01 (steady flow) ---

Flow Title=Multiple
Program Version=4.10
Number of Profiles= 7
Profile Names=10-year,25-year,50-year,1pct_min,100-year,1pct_plu,500-year
River Rch & RM=Stream0504,Reach-1         ,4470
    2329    4140    5932    4101    8182   16326   15385
Boundary for River Rch & Prof#=Stream0504,Reach-1         , 1
Up Type= 0
Dn Type= 3
Dn Slope=0.007
Boundary for River Rch & Prof#=Stream0504,Reach-1         , 2
Up Type= 0
Dn Type= 3
Dn Slope=0.007
Boundary for River Rch & Prof#=Stream0504,Reach-1         , 3
Up Type= 0
Dn Type= 3
Dn Slope=0.007
Boundary for River Rch & Prof#=Stream0504,Reach-1         , 4
Up Type= 0
Dn Type= 3
Dn Slope=0.007
Boundary for River Rch & Prof#=Stream0504,Reach-1         , 5
Up Type= 0
Dn Type= 3
Dn Slope=0.007
Boundary for River Rch & Prof#=Stream0504,Reach-1         , 6
Up Type= 0
Dn Type= 3
Dn Slope=0.007
Boundary for River Rch & Prof#=Stream0504,Reach-1         , 7
Up Type= 0
Dn Type= 3
Dn Slope=0.007
DSS Import GetInterval= 0
DSS Import GetPeak= 0
DSS Import FillOption= 0

--- Stream0504.g01 (geometry) ---

Geom Title=Existing Conditions
Program Version=4.10

River Reach=Stream0504      ,Reach-1
Reach XY= 30
        1916825.       13955825.      1916919.53     13955769.58
      1916972.87     13955669.06      1916924.72     13955495.18
       1916972.7     13955419.07       1916988.2     13955261.26
       1917189.1     13955211.63      1917217.54     13955175.25
      1917184.31     13955118.34        1917315.     13954986.24
      1917378.23     13955016.75      1917492.56     13954958.38
      1917517.74      13954925.3      1917491.07     13954807.95
       1917684.7     13954714.24      1917783.48     13954578.51
      1917938.56     13954511.53      1918119.17      13954277.3
       1918173.8      13954164.5      1918175.52     13953840.22
      1918225.73     13953740.06      1918219.59     13953672.58
      1918128.47      13953573.5      1918132.76     13953468.83
      1918281.05     13953326.58      1918425.22       13953418.
      1918522.46     13953280.02      1918638.38     13953311.46
      1918917.24     13952981.22        1918925.       13952875.

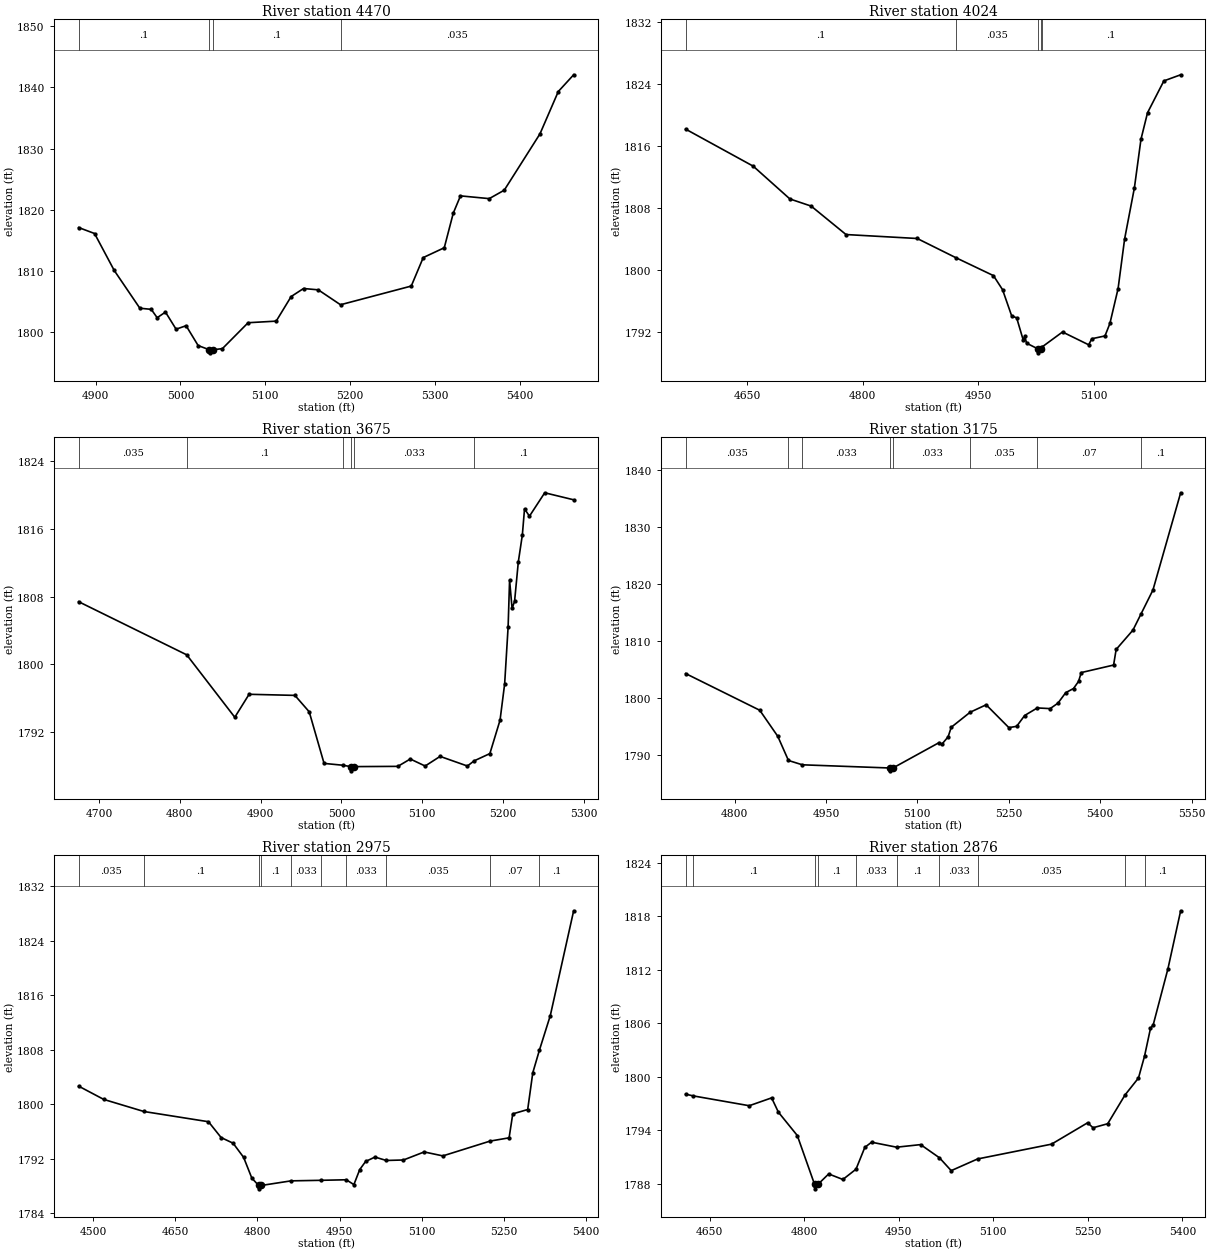
Type RM Length L Ch R = 1 ,4470    ,446,446,446
BEGIN DESCRIPTION:
Stream0504 10.0
END DESCRIPTION:
XS GIS Cut Line= 3
      1916975.01     13955875.01        1916925.       13955775.
      1916525.02     13955525.01
#Sta/Elev= 30
    4880 1817.08  4898.8  1816.1    4922 1810.05  4952.2 1803.87  4965.6 1803.69
  4972.6 1802.32  4982.4 1803.24  4994.9 1800.44  5006.7 1801.01  5020.9 1797.76
  5034.2 1797.07  5034.5 1796.57  5038.2 1797.07  5049.5 1797.26  5079.8  1801.5
  5112.9 1801.76  5130.5 1805.78  5145.1  1807.1  5162.5 1806.88  5188.7 1804.44
  5272.1  1807.5  5286.2 1812.16    5311 1813.77  5321.6 1819.43  5330.1 1822.26
    5364 1821.81  5381.7 1823.19  5423.8 1832.41  5445.4 1839.34  5463.5 1842.08
#Mann= 4 ,-1 , 0
    4880      .1       0  5034.2     .05       0  5038.2      .1       0
  5188.7    .035       0
Bank Sta=5034.2,5038.2
XS Rating Curve= 0 ,0
Exp/Cntr=0.3,0.1

Type RM Length L Ch R = 1 ,4024    ,349,349,349
BEGIN DESCRIPTION:
Stream0504 9.0
END DESCRIPTION:
XS GIS Cut Line= 3
      1917225.03     13955725.04        1916975.       13955375.
        1916825.       13955225.
#Sta/Elev= 30
  4570.4 1818.12  4658.1 1813.34  4705.7 1809.11  4733.3 1808.19  4778.5 1804.52
  4870.9 1804.01  4920.7 1801.55  4969.8 1799.22  4981.6 1797.41  4993.5 1794.01
  4999.9 1793.78  5008.4 1790.92  5010.6  1791.4  5012.7 1790.51  5027.7 1789.76
  5027.9 1789.26  5031.7 1789.76  5032.5 1789.99  5059.4 1791.95  5093.3  1790.3
  5097.5 1791.08  5114.5 1791.44  5120.9 1793.05  5131.5 1797.54    5140 1803.96
  5152.7 1810.56  5161.2 1816.81  5169.7 1820.23  5190.9 1824.34  5212.7 1825.13
#Mann= 5 ,-1 , 0
  4570.4      .1       0  4920.7    .035       0  5027.7    .035       0
  5031.7    .035       0  5032.5      .1       0
Bank Sta=5027.7,5031.7
XS Rating Curve= 0 ,0
Exp/Cntr=0.3,0.1

Type RM Length L Ch R = 1 ,3675    ,500,500,500
BEGIN DESCRIPTION:
Stream0504 8.0
END DESCRIPTION:
XS GIS Cut Line= 3
      1917475.04     13955375.02      1917160.83     13955177.62
        1916925.       13955125.
#Sta/Elev= 30
  4674.7  1807.4  4808.5 1801.11    4868 1793.72  4885.7 1796.44  4942.4 1796.31
  4960.1 1794.37  4978.5 1788.26  5002.1 1788.04  5011.3 1787.88  5011.5 1787.38
  5015.3 1787.88  5069.8 1787.91  5085.2 1788.78  5103.6 1787.95  5122.1 1789.09
  5155.9 1787.95  5164.2 1788.56  5183.7 1789.42  5196.3 1793.38    5202 1797.67
  5206.3 1804.43  5208.1 1809.95  5211.2  1806.6  5214.3 1807.45  5218.9  1812.1
  5223.9 1815.29  5226.6 1818.39  5232.7 1817.52  5251.6 1820.29  5287.4 1819.46
#Mann= 6 ,-1 , 0
  4674.7    .035       0  4808.5      .1       0  5002.1    .033       0
  5011.3     .05       0  5015.3    .033       0  5164.2      .1       0
Bank Sta=5011.3,5015.3
XS Rating Curve= 0 ,0
Exp/Cntr=0.3,0.1

Type RM Length L Ch R = 1 ,3175    ,200,200,200
BEGIN DESCRIPTION:
Stream0504 7.0
END DESCRIPTION:
XS GIS Cut Line= 3
        1917575.     13955225.01       1917492.3     13954947.76
      1917125.02     13954575.02
#Sta/Elev= 30
  4719.6 1804.31  4841.3 1797.86  4870.9 1793.28  4888.4 1789.04  4911.2 1788.28
  5054.6 1787.72    5055 1787.22  5059.9 1787.72  5135.7 1792.18  5139.9 1791.85
  5150.5  1793.2  5155.6 1794.87  5186.6 1797.51  5212.9 1798.82  5250.2 1794.81
    5263 1795.04  5276.1 1796.94  5296.9 1798.27    5318 1798.15  5330.8 1799.11
  5343.5 1800.95  5356.3 1801.68  5364.6 1802.93    5369 1804.48  5422.1  1805.8
  5426.3 1808.54  5453.9 1811.94    5467 1814.75  5486.7 1818.98  5532.2 1836.06
#Mann= 8 ,-1 , 0
  4719.6    .035       0  4888.4      .1       0  4911.2    .033       0
  5054.6    .033       0  5059.9    .033       0  5186.6    .035       0
  5296.9     .07       0    5467      .1       0
Bank Sta=5054.6,5059.9
XS Rating Curve= 0 ,0
Exp/Cntr=0.3,0.1

Type RM Length L Ch R = 1 ,2975    ,99,99,99
BEGIN DESCRIPTION:
Stream0504 6.1
END DESCRIPTION:
XS GIS Cut Line= 3
      1917931.07     13955105.96      1917433.52     13954734.18
      1917247.33     13954520.02
#Sta/Elev= 30
    4473 1802.66    4519 1800.71  4592.3 1798.94  4710.4 1797.44  4733.5 1795.12
  4755.4 1794.29  4774.6 1792.22  4789.6 1789.18    4802  1788.1  4802.4  1787.6
  4807.3  1788.1  4861.3 1788.77    4916 1788.85  4962.3 1788.93  4976.2 1788.22
  4986.9 1790.43  4997.6 1791.61  5014.7 1792.26  5035.4 1791.76  5066.8 1791.83
  5104.7 1793.01  5138.8 1792.43  5225.1  1794.6  5259.9 1795.08  5266.6 1798.59
  5293.9 1799.23  5303.2 1804.62  5315.3 1807.93  5335.2    1813  5377.9 1828.37
#Mann= 10 ,-1 , 0
    4473    .035       0  4592.3      .1       0    4802    .033       0
  4807.3      .1       0  4861.3    .033       0    4916      .1       0
  4962.3    .033       0  5035.4    .035       0  5225.1     .07       0
  5315.3      .1       0
Bank Sta=4802,4807.3
XS Rating Curve= 0 ,0
Exp/Cntr=0.3,0.1

Type RM Length L Ch R = 1 ,2876    ,155,155,155
BEGIN DESCRIPTION:
Stream0504 6.2
END DESCRIPTION:
XS GIS Cut Line= 4
      1917906.69     13954986.11      1917670.14     13954808.16
      1917611.55     13954766.93      1917309.93     13954478.33
#Sta/Elev= 30
  4612.1 1798.06  4623.6 1797.87    4713 1796.76  4748.5 1797.64  4759.2 1796.04
  4789.2 1793.42  4816.6 1787.94    4817 1787.44  4821.9 1787.94    4839 1789.11
  4861.5 1788.49  4882.3 1789.64  4896.3 1792.09    4907 1792.67  4946.7 1792.11
  4984.8  1792.4  5014.7 1790.92  5033.3 1789.48  5075.1 1790.79  5192.4 1792.45
  5249.7 1794.85  5258.2 1794.29  5281.5 1794.74    5309 1797.97  5330.3 1799.87
  5339.9 1802.32  5349.3 1805.42  5353.7 1805.84    5377 1812.11  5397.2 1818.62
#Mann= 10 ,-1 , 0
  4612.1    .035       0  4623.6      .1       0  4816.6     .05       0
  4821.9      .1       0  4882.3    .033       0  4946.7      .1       0
  5014.7    .033       0  5075.1    .035       0    5309     .07       0
  5339.9      .1       0
Bank Sta=4816.6,4821.9
XS Rating Curve= 0 ,0
Exp/Cntr=0.3,0.1

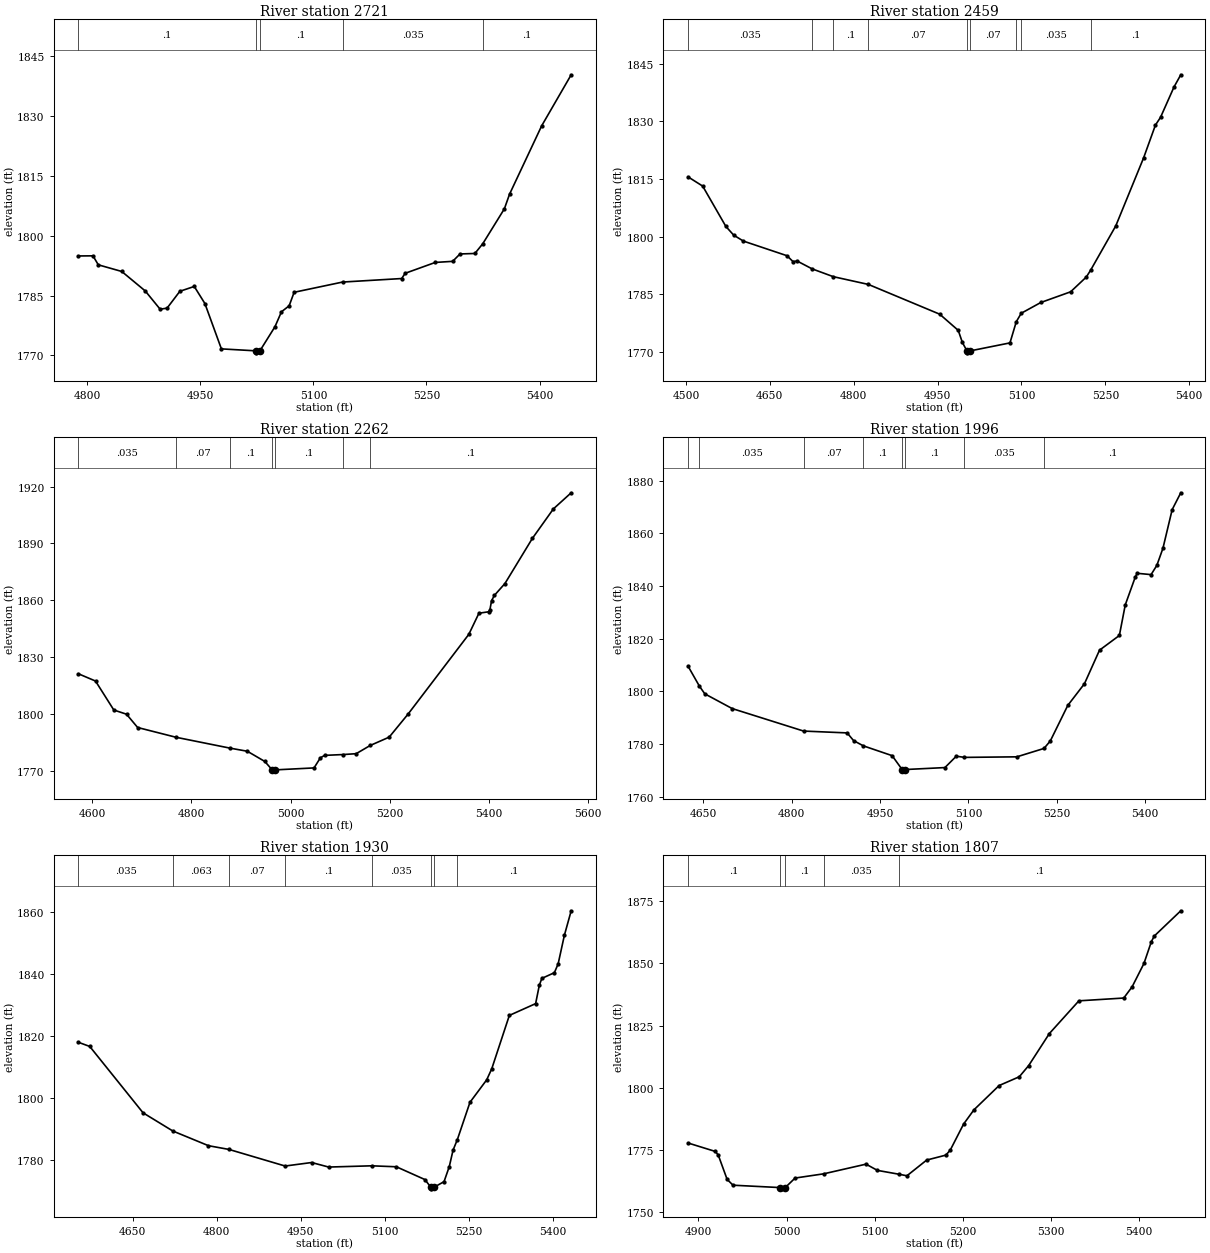
Type RM Length L Ch R = 1 ,2721    ,262,262,262
BEGIN DESCRIPTION:
Stream0504 6.0
END DESCRIPTION:
XS GIS Cut Line= 3
      1917874.99     13954824.99        1917725.       13954675.
      1917545.04     13954271.75
#Sta/Elev= 30
  4788.3  1794.9  4807.5 1794.93  4814.6 1792.68  4845.7 1791.02  4876.9 1786.14
  4896.6 1781.58  4905.8 1781.84  4922.8 1786.06  4941.9 1787.27    4956    1783
  4977.9 1771.65  5023.7 1771.16  5024.1 1770.66    5029 1771.16    5049  1777.2
  5057.6 1780.93  5067.8 1782.43  5074.4 1785.81  5138.7 1788.37  5217.1 1789.25
  5221.7 1790.56  5261.7 1793.28  5284.7 1793.55  5294.5  1795.4  5314.2 1795.52
  5324.7 1797.96  5353.4 1806.71  5360.2 1810.35  5402.9 1827.48    5442 1840.23
#Mann= 5 ,-1 , 0
  4788.3      .1       0  5023.7     .05       0    5029      .1       0
  5138.7    .035       0  5324.7      .1       0
Bank Sta=5023.7,5029
XS Rating Curve= 0 ,0
Exp/Cntr=0.3,0.1

Type RM Length L Ch R = 1 ,2459    ,197,197,197
BEGIN DESCRIPTION:
Stream0504 5.1
END DESCRIPTION:
XS GIS Cut Line= 3
      1918320.15     13954803.57      1917933.83     13954549.37
      1917659.65     13954233.26
#Sta/Elev= 30
  4503.9 1815.54    4530 1813.14  4571.5 1802.62  4585.4 1800.37  4602.8 1798.81
  4680.7    1795  4691.5 1793.47  4698.8 1793.62  4725.7 1791.57  4763.5 1789.54
  4826.2 1787.52  4953.8 1779.76  4986.9 1775.55  4994.3  1772.4  5002.5 1770.19
  5002.9 1769.69  5007.9 1770.19  5079.4 1772.28  5090.7  1777.8  5099.6 1780.01
  5134.6 1782.81  5187.8 1785.59  5215.8 1789.43  5223.5  1791.2  5268.6 1802.78
  5318.4 1820.52  5339.5 1829.05  5348.6 1831.06  5372.8    1839  5384.8 1842.15
#Mann= 9 ,-1 , 0
  4503.9    .035       0  4725.7     .07       0  4763.5      .1       0
  4826.2     .07       0  5002.5     .05       0  5007.9     .07       0
  5090.7      .1       0  5099.6    .035       0  5223.5      .1       0
Bank Sta=5002.5,5007.9
XS Rating Curve= 0 ,0
Exp/Cntr=0.3,0.1

Type RM Length L Ch R = 1 ,2262    ,266,266,266
BEGIN DESCRIPTION:
Stream0504 5.0
END DESCRIPTION:
XS GIS Cut Line= 3
        1918425.       13954525.        1918025.       13954375.
      1917624.99     13953974.99
#Sta/Elev= 30
  4572.6 1821.28  4606.9 1817.47  4643.8  1802.2  4669.4 1799.99  4691.8 1792.98
  4769.4 1787.82  4877.7 1782.12  4912.9 1780.46  4948.1 1775.08    4963 1770.64
  4963.5 1770.14  4968.5 1770.64  5047.3 1771.68    5060 1776.98  5068.5 1778.29
    5106 1778.73  5132.2 1779.18  5160.4  1783.5  5198.7  1787.9  5236.9 1800.09
  5359.2 1842.08  5379.6 1853.22  5399.5 1853.99  5401.6 1854.91  5405.1 1859.86
  5410.8 1862.64    5432 1868.87  5487.2 1892.63  5529.6  1908.2  5565.5  1916.7
#Mann= 7 ,-1 , 0
  4572.6    .035       0  4769.4     .07       0  4877.7      .1       0
    4963     .05       0  4968.5      .1       0    5106    .035       0
  5160.4      .1       0
Bank Sta=4963,4968.5
XS Rating Curve= 0 ,0
Exp/Cntr=0.3,0.1

Type RM Length L Ch R = 1 ,1996    ,66,66,66
BEGIN DESCRIPTION:
Mapping XS 52fa3f6d
END DESCRIPTION:
XS GIS Cut Line= 3
      1918536.11     13954263.61        1917988.     13954112.65
      1917749.35     13953991.86
#Sta/Elev= 30
  4624.3 1809.55  4643.6 1801.95  4652.7 1799.06  4699.1 1793.47  4820.3 1784.92
  4894.2 1784.22  4905.1  1781.3  4921.7  1779.3  4970.5 1775.58  4987.5 1770.31
    4988 1769.81    4993 1770.31  5060.1 1771.05  5079.4 1775.38  5093.3 1774.92
  5182.1 1775.13  5228.2 1778.32  5238.9 1781.16  5268.6 1794.68  5296.9 1802.92
  5322.4 1815.65  5356.1 1821.24  5366.1 1832.86    5383 1843.38  5386.3 1844.86
  5409.9 1844.36  5419.7 1847.87    5430 1854.34  5445.7 1869.06  5460.3 1875.45
#Mann= 8 ,-1 , 0
  4624.3      .1       0  4643.6    .035       0  4820.3     .07       0
  4921.7      .1       0  4987.5     .05       0    4993      .1       0
  5093.3    .035       0  5228.2      .1       0
Bank Sta=4987.5,4993
XS Rating Curve= 0 ,0
Exp/Cntr=0.3,0.1

Type RM Length L Ch R = 1 ,1930    ,123,123,123
BEGIN DESCRIPTION:
Stream0504 4.1
END DESCRIPTION:
XS GIS Cut Line= 4
      1918611.96     13954191.84      1918219.19     13954105.04
      1918056.43       13954079.      1917776.46      13953940.1
#Sta/Elev= 30
  4553.2    1818  4573.3 1816.67  4668.5 1795.31  4721.6 1789.46  4785.3 1784.73
  4821.9 1783.53  4922.1 1778.19  4969.4 1779.32  4999.8 1777.86  5076.7 1778.26
  5120.7 1777.95  5171.7 1773.83  5182.3 1771.35  5182.8 1770.85  5187.8 1771.35
  5205.8 1773.16  5215.2 1778.03  5221.9  1783.3  5229.6 1786.71  5252.1  1798.7
  5281.9 1805.91  5290.9 1809.44  5322.4 1826.66  5369.3 1830.45  5375.9 1836.35
  5380.4 1838.57  5402.8 1840.41  5409.5 1843.23  5420.7 1852.48  5432.8 1860.33
#Mann= 8 ,-1 , 0
  4553.2    .035       0  4721.6    .063       0  4821.9     .07       0
  4922.1      .1       0  5076.7    .035       0  5182.3     .05       0
  5187.8    .035       0  5229.6      .1       0
Bank Sta=5182.3,5187.8
XS Rating Curve= 0 ,0
Exp/Cntr=0.3,0.1

Type RM Length L Ch R = 1 ,1807    ,544,544,544
BEGIN DESCRIPTION:
Stream0504 4.0
END DESCRIPTION:
XS GIS Cut Line= 3
      1918274.97     13954024.98        1918175.       13953975.
      1917774.98     13953774.99
#Sta/Elev= 30
  4888.2 1777.85  4919.1 1774.46  4922.4 1773.04  4932.5 1763.24  4939.2 1760.91
  4992.9 1759.95  4993.3 1759.45  4998.4 1759.95  5009.6 1763.78  5042.1 1765.48
  5090.1 1769.36    5103 1766.86  5127.7  1765.3  5136.5 1764.69  5158.9    1771
  5180.7 1772.99  5185.7 1775.03  5200.8 1785.46  5212.5 1791.16  5241.1 1800.92
    5264 1804.45  5274.6 1808.92  5298.1 1821.79  5331.6 1834.93  5382.5 1836.05
    5392 1840.56  5405.4 1849.92  5413.8 1858.66  5417.1 1860.93  5447.2 1871.08
#Mann= 5 ,-1 , 0
  4888.2      .1       0  4992.9     .05       0  4998.4      .1       0
  5042.1    .035       0  5127.7      .1       0
Bank Sta=4992.9,4998.4
XS Rating Curve= 0 ,0
Exp/Cntr=0.3,0.1

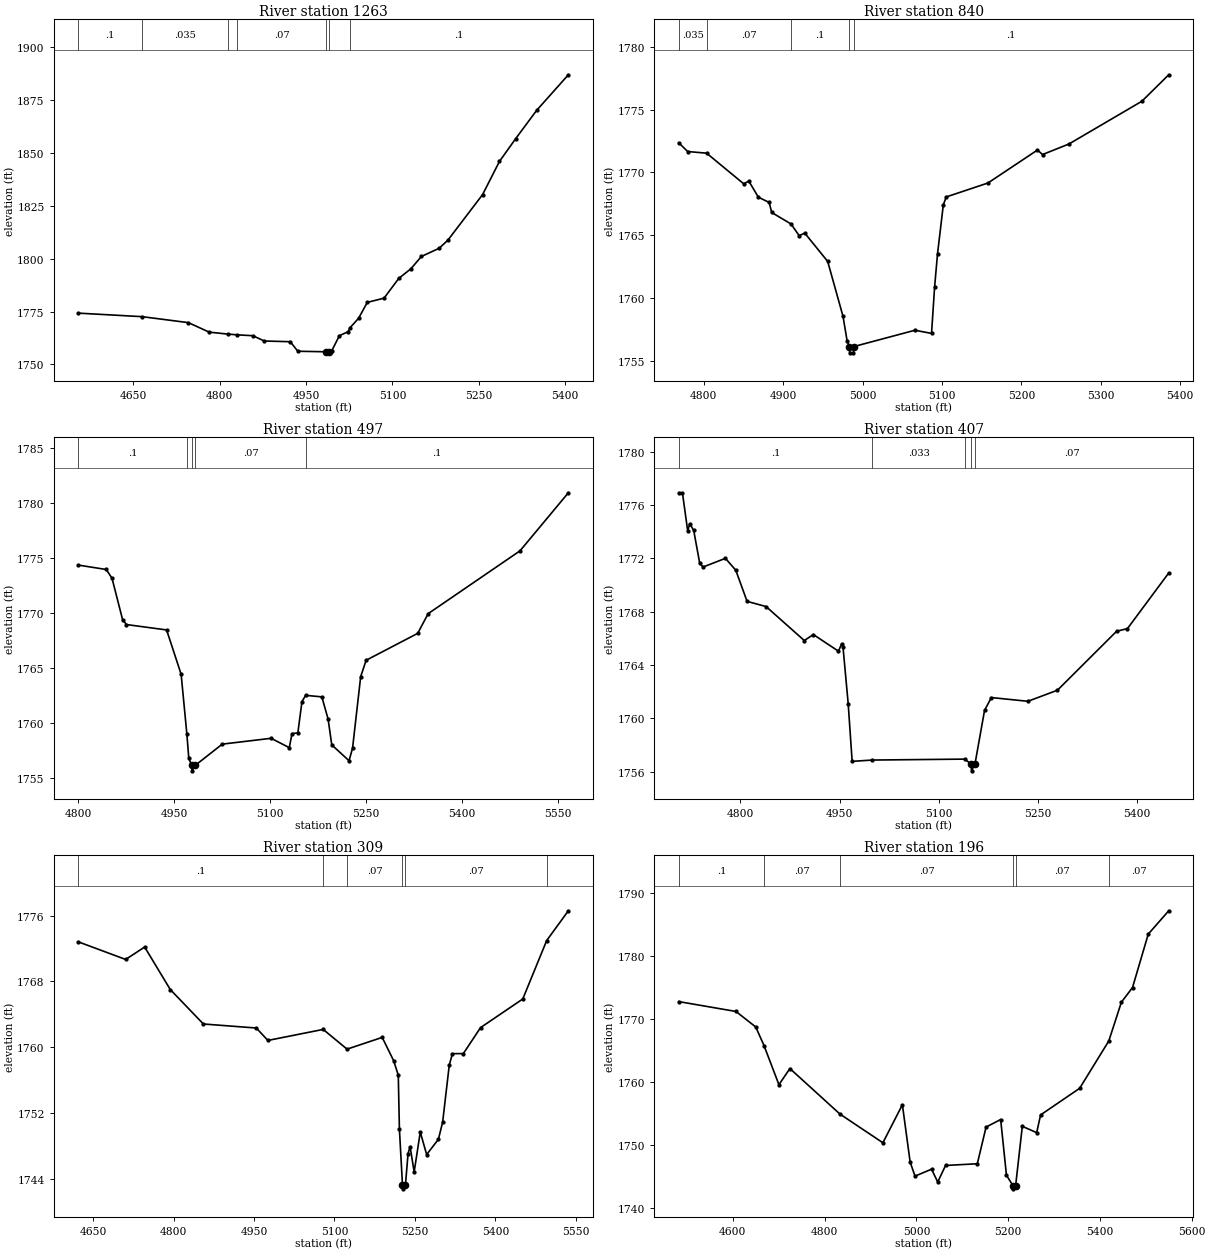
Type RM Length L Ch R = 1 ,1263    ,423,423,423
BEGIN DESCRIPTION:
Stream0504 3.0
END DESCRIPTION:
XS GIS Cut Line= 3
      1918501.45     13953724.77       1918125.5     13953484.51
      1917724.97       13953425.
#Sta/Elev= 30
  4554.5 1774.24  4665.4 1772.57  4745.7 1769.75  4781.7 1765.27  4814.4 1764.34
  4830.6 1763.99  4857.5 1763.59  4877.4 1761.09  4922.6 1760.75  4935.7 1756.25
    4985    1756  4985.4  1755.5  4990.6    1756  4994.9  1756.6  5007.9 1763.59
  5023.1 1765.48  5026.7 1767.44  5041.3 1771.83  5056.4 1779.33  5085.4 1781.29
    5111 1790.61  5132.2 1795.21  5150.4    1801  5181.2 1804.85  5196.3 1808.66
  5256.6 1830.18    5286 1845.88  5314.2 1856.63  5350.6 1869.97  5405.6 1886.74
#Mann= 7 ,-1 , 0
  4554.5      .1       0  4665.4    .035       0  4814.4      .1       0
  4830.6     .07       0    4985     .05       0  4990.6     .07       0
  5026.7      .1       0
Bank Sta=4985,4990.6
XS Rating Curve= 0 ,0
Exp/Cntr=0.3,0.1

Type RM Length L Ch R = 1 ,840     ,343,343,343
BEGIN DESCRIPTION:
Stream0504 2.0
END DESCRIPTION:
XS GIS Cut Line= 3
      1918525.01     13953625.03      1918446.63     13953416.72
      1918218.48     13953094.85
#Sta/Elev= 30
  4768.5 1772.37  4779.8 1771.67  4803.6 1771.54  4850.3  1769.1  4856.8 1769.31
  4868.8 1768.03  4882.4 1767.61  4885.6 1766.81    4910 1765.89  4920.1 1764.97
  4927.3 1765.16  4956.1 1762.91  4975.4 1758.53  4980.6 1756.56  4983.4 1756.12
  4983.8 1755.62  4988.5 1755.62    4989 1756.12  5065.9 1757.42  5086.9 1757.17
  5090.7 1760.83  5094.4  1763.5  5101.7 1767.41  5105.4 1768.05  5157.9 1769.16
  5220.3 1771.79  5226.7 1771.43  5259.9 1772.27  5351.8 1775.68  5385.6 1777.79
#Mann= 5 ,-1 , 0
  4768.5    .035       0  4803.6     .07       0    4910      .1       0
  4983.4     .05       0    4989      .1       0
Bank Sta=4983.4,4989
XS Rating Curve= 0 ,0
Exp/Cntr=0.3,0.1

Type RM Length L Ch R = 1 ,497     ,90,90,90
BEGIN DESCRIPTION:
Stream0504 1.0
END DESCRIPTION:
XS GIS Cut Line= 3
        1918675.     13953475.02        1918675.       13953275.
        1918275.       13952875.
#Sta/Elev= 30
  4800.5 1774.35  4844.1 1773.95  4853.1 1773.15  4869.7 1769.37  4875.7 1768.94
  4938.4 1768.45  4961.1 1764.42    4970 1759.01  4973.1 1756.77  4977.6 1756.13
  4978.1 1755.63  4983.2 1756.13  5025.4 1758.06  5101.7 1758.59  5130.1 1757.74
  5134.4 1759.02  5143.5 1759.08  5149.9 1761.93  5155.7  1762.5    5181 1762.36
  5190.8 1760.33  5196.5 1757.99  5223.5 1756.55    5229  1757.7  5241.7 1764.21
  5250.2 1765.69  5330.8 1768.14  5347.1 1769.93  5490.7 1775.65  5566.2 1780.93
#Mann= 5 ,-1 , 0
  4800.5      .1       0    4970     .07       0  4977.6     .05       0
  4983.2     .07       0  5155.7      .1       0
Bank Sta=4977.6,4983.2
XS Rating Curve= 0 ,0
Exp/Cntr=0.3,0.1

Type RM Length L Ch R = 1 ,407     ,98,98,98
BEGIN DESCRIPTION:
Mapping XS 962db9f1
END DESCRIPTION:
XS GIS Cut Line= 3
      1918810.39     13953489.84      1918769.96     13953247.74
      1918446.69     13952871.62
#Sta/Elev= 30
  4706.6 1776.92  4712.2 1776.92  4720.2 1774.05  4723.2  1774.6  4729.3 1774.09
  4738.4 1771.62  4743.5 1771.35  4777.3    1772    4793  1771.1    4810 1768.77
  4838.8 1768.38  4896.6 1765.83  4910.3 1766.28  4948.3 1765.03    4953 1765.57
  4955.1 1765.38    4963  1761.1    4969 1756.76  4999.5 1756.86  5139.3 1756.93
  5149.2 1756.55  5149.6 1756.05  5154.8 1756.55  5169.3 1760.58  5179.6 1761.55
  5234.9 1761.27  5279.6  1762.1    5369 1766.52  5385.6 1766.73    5448  1770.9
#Mann= 5 ,-1 , 0
  4706.6      .1       0  4999.5    .033       0  5139.3     .07       0
  5149.2     .05       0  5154.8     .07       0
Bank Sta=5149.2,5154.8
XS Rating Curve= 0 ,0
Exp/Cntr=0.3,0.1

Type RM Length L Ch R = 1 ,309     ,113,113,113
BEGIN DESCRIPTION:
Stream0504 0.1
END DESCRIPTION:
XS GIS Cut Line= 5
      1918898.43     13953508.21      1918813.81     13953152.35
      1918757.38     13953059.03      1918653.22     13952924.48
      1918457.94     13952740.05
#Sta/Elev= 30
  4622.5 1772.82  4710.7 1770.68  4746.1 1772.19  4793.9 1767.02  4855.6 1762.83
  4954.3 1762.34  4975.9 1760.83    5079 1762.17  5123.5 1759.77    5189  1761.2
  5210.4 1758.36    5219  1756.6  5221.1 1750.06  5226.8 1743.28  5227.3 1742.78
  5232.4 1743.28  5237.2 1747.06    5241 1747.92  5248.6 1744.84    5260 1749.68
  5271.9 1746.95  5293.8  1748.8  5301.7 1750.89  5314.1 1757.85    5320 1759.22
  5340.3 1759.23  5372.4 1762.39  5451.1 1765.87  5495.7 1772.98  5536.1  1776.6
#Mann= 6 ,-1 , 0
  4622.5      .1       0    5079    .033       0  5123.5     .07       0
  5226.8     .05       0  5232.4     .07       0  5495.7     .07       0
Bank Sta=5226.8,5232.4
XS Rating Curve= 0 ,0
Exp/Cntr=0.3,0.1

Type RM Length L Ch R = 1 ,196     ,0,0,0
BEGIN DESCRIPTION:
Stream0504 0.0
END DESCRIPTION:
XS GIS Cut Line= 3
      1918958.42     13953537.42      1918908.56     13953097.56
      1918471.19     13952650.65
#Sta/Elev= 30
    4482 1772.78  4606.8 1771.21  4649.9 1768.74  4667.9 1765.78  4700.4 1759.56
  4724.3 1762.13  4833.5 1754.88    4927 1750.32  4969.5 1756.37  4986.4 1747.25
    4997 1745.01  5033.1 1746.12  5046.5 1744.07  5063.6 1746.71  5132.8 1746.98
  5151.9 1752.82  5183.7 1754.02  5196.3 1745.17  5210.5 1743.49    5211 1742.99
  5216.3 1743.49  5230.9 1752.94  5262.2 1751.93  5270.7 1754.75  5355.8 1758.98
  5419.4 1766.52  5446.8 1772.68  5471.1 1775.02  5505.4 1783.52    5550 1787.23
#Mann= 6 ,-1 , 0
    4482      .1       0  4667.9     .07       0  4833.5     .07       0
  5210.5     .05       0  5216.3     .07       0  5419.4     .07       0
Bank Sta=5210.5,5216.3
XS Rating Curve= 0 ,0
Exp/Cntr=0.3,0.1

Chan Stop Cuts=-1
Use User Specified Reach Order=0
Composite Channel Slope=5