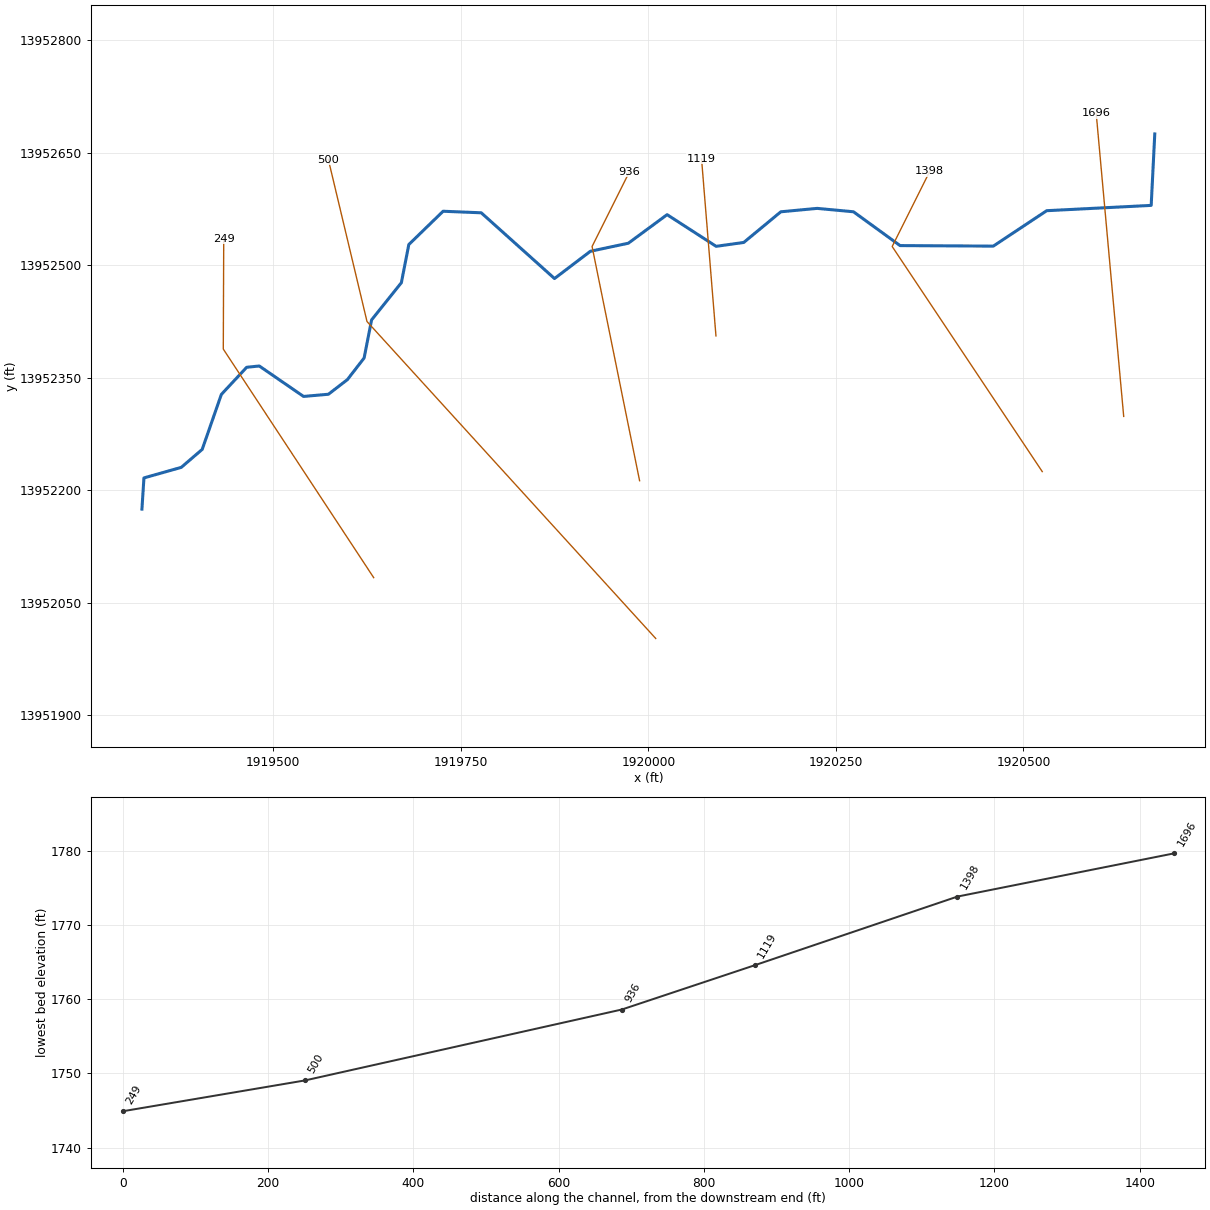
--- Stream0505.prj (project) ---

Proj Title=Stream0505 Base Level Engineering
Current Plan=p01
Default Exp/Contr=0.3,0.1
English Units
Geom File=g01
Flow File=f01
Plan File=p01
BEGIN DESCRIPTION:
Stream0505
END DESCRIPTION:

--- Stream0505.p01 (plan) ---

Plan Title=Multiple Run
Short Identifier=Multiple
Geom File=g01
Flow File=f01
Subcritical Flow
K Sum by GR= 0
Std Step Tol= 0.01
Critical Tol= 0.01
Num of Std Step Trials= 20
Max Error Tol= 0.3
Flow Tol Ratio= 0.001
Split Flow NTrial= 30
Split Flow Tol= 0.02
Split Flow Ratio= 0.02
Log Output Level= 0
Friction Slope Method= 1
Unsteady Friction Slope Method= 2
Unsteady Bridges Friction Slope Method= 1
Parabolic Critical Depth
Global Vel Dist=  1 , 1 , 1
Global Log Level= 0
CheckData=True
Encroach Param= -1, 0, 0, 0
BEGIN DESCRIPTION:
Multiple Run
END DESCRIPTION:

--- Stream0505.f01 (steady flow) ---

Flow Title=Multiple
Number of Profiles=7
Profile Names=10-year,25-year,50-year,1pct_min,100-year,1pct_plu,500-year
River Rch & RM= Stream0505,Reach-1,1696
     542     886    1200     790    1577    3146    2678
Boundary for River Rch & Prof#=Stream0505,Reach-1,1
Up Type=0
Dn Type=3
Dn Slope=0.005
Boundary for River Rch & Prof#=Stream0505,Reach-1,2
Up Type=0
Dn Type=3
Dn Slope=0.005
Boundary for River Rch & Prof#=Stream0505,Reach-1,3
Up Type=0
Dn Type=3
Dn Slope=0.005
Boundary for River Rch & Prof#=Stream0505,Reach-1,4
Up Type=0
Dn Type=3
Dn Slope=0.005
Boundary for River Rch & Prof#=Stream0505,Reach-1,5
Up Type=0
Dn Type=3
Dn Slope=0.005
Boundary for River Rch & Prof#=Stream0505,Reach-1,6
Up Type=0
Dn Type=3
Dn Slope=0.005
Boundary for River Rch & Prof#=Stream0505,Reach-1,7
Up Type=0
Dn Type=3
Dn Slope=0.005

--- Stream0505.g01 (geometry) ---

Geom Title=Existing Conditions

River Reach=Stream0505,Reach-1
Reach XY= 30
      1920675.00     13952675.00      1920670.22     13952579.79
      1920530.95     13952572.72      1920459.78     13952525.51
      1920335.51     13952526.21      1920273.40     13952571.29
      1920225.00     13952575.81      1920176.58     13952571.27
      1920127.17     13952530.40      1920090.34     13952525.23
      1920025.00     13952567.44      1919973.35     13952529.39
      1919922.71     13952518.62      1919874.92     13952482.30
      1919777.26     13952569.92      1919726.43     13952571.99
      1919680.73     13952527.62      1919670.80     13952476.77
      1919631.11     13952427.16      1919621.14     13952376.36
      1919598.84     13952347.56      1919573.57     13952328.07
      1919540.41     13952325.15      1919481.40     13952365.73
      1919464.63     13952364.02      1919430.86     13952327.83
      1919405.33     13952254.55      1919377.42     13952230.60
      1919327.66     13952216.55      1919325.00     13952175.00

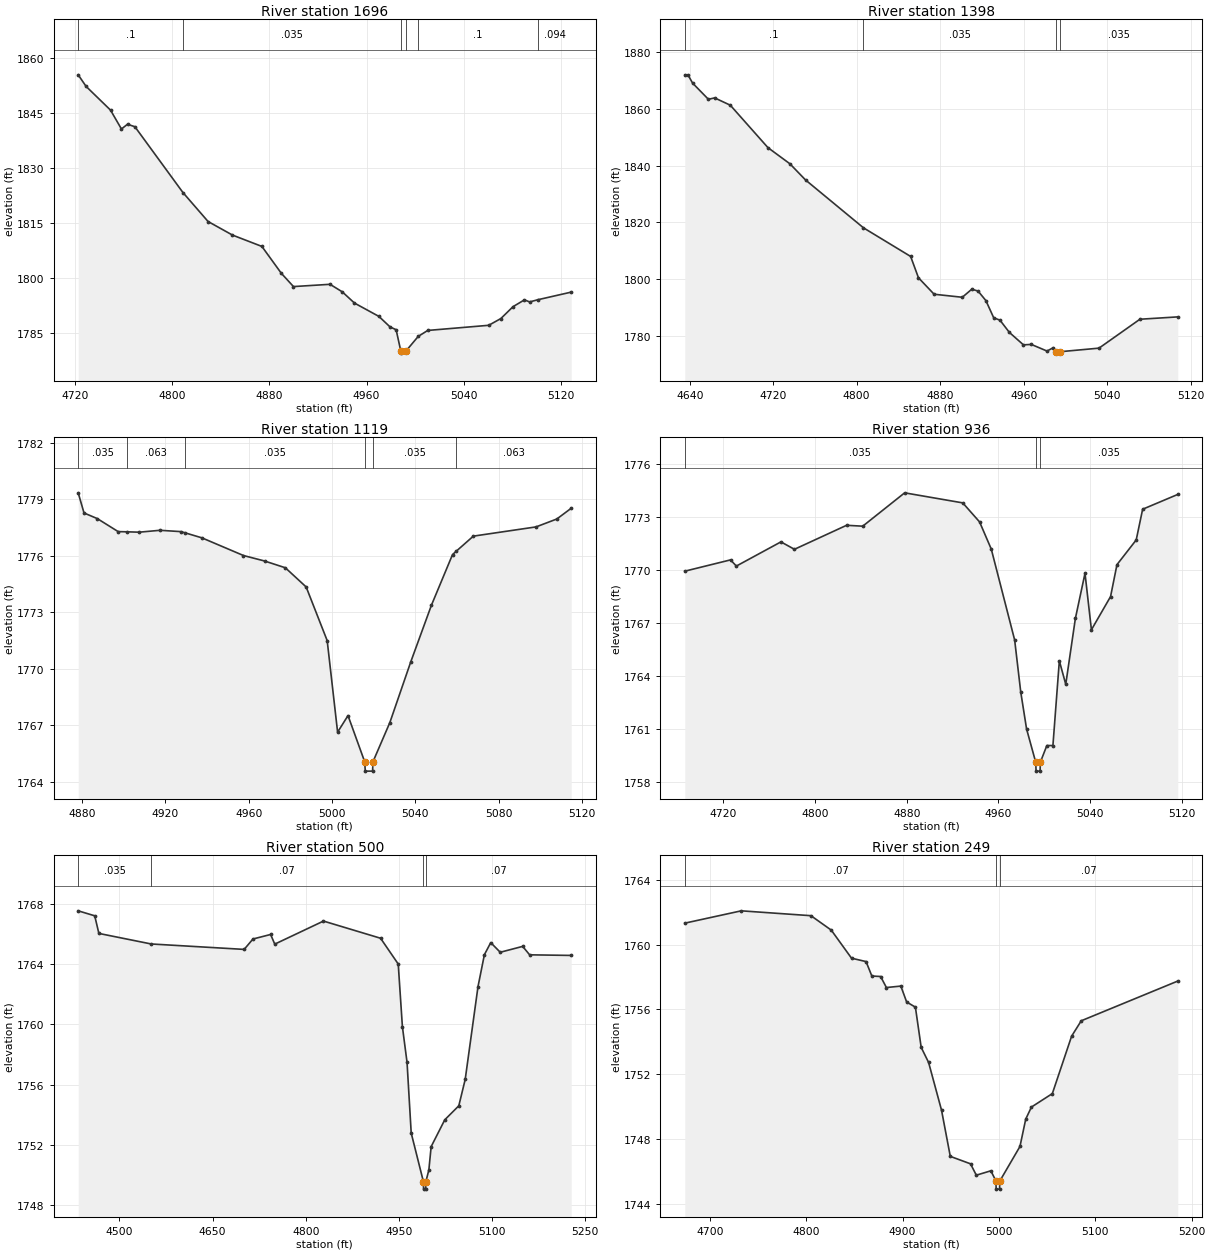
Type RM Length L Ch R = 1,1696,298,298,298
BEGIN DESCRIPTION:
Stream0505 4.0
END DESCRIPTION:
XS GIS Cut Line= 2
      1920633.58     13952298.53      1920596.91     13952702.67
#Sta/Elev= 30
  4722.6 1855.44  4729.1 1852.29  4749.2 1845.83  4758.2 1840.68  4763.2 1841.98
  4769.3 1841.29  4808.8 1823.38  4829.5 1815.48  4849.6 1811.78  4873.8 1808.69
  4889.8 1801.37  4899.8 1797.75  4929.9 1798.37  4940.0 1796.31  4950.0 1793.26
  4970.1 1789.63  4979.3 1786.76  4984.3 1785.99  4988.2 1780.12  4988.4 1779.62
  4992.2 1780.12  5002.5 1784.18  5010.3 1785.80  5060.5 1787.20  5070.5 1789.04
  5080.5 1792.27  5089.9 1794.13  5094.2 1793.57  5101.0 1794.17  5128.4 1796.24
#Mann=6,-1,0
  4722.6     0.1       0  4808.8   0.035       0  4988.2   0.035       0
  4992.2   0.035       0  5002.5     0.1       0  5101.0   0.094       0
Bank Sta=4988.2,4992.2
Exp/Cntr=0.3,0.1

Type RM Length L Ch R = 1,1398,279,279,279
BEGIN DESCRIPTION:
Stream0505 3.0
END DESCRIPTION:
XS GIS Cut Line= 3
      1920525.02     13952224.98      1920325.00     13952525.00
      1920375.01     13952625.01
#Sta/Elev= 30
  4635.3 1872.11  4638.3 1872.11  4642.8 1869.17  4657.9 1863.47  4663.9 1863.96
  4678.9 1861.38  4715.0 1846.38  4736.0 1840.69  4751.0 1834.97  4806.5 1818.07
  4851.7 1807.96  4859.2 1800.42  4874.2 1794.61  4901.2 1793.54  4910.3 1796.39
  4916.3 1795.73  4923.8 1792.37  4931.3 1786.29  4937.3 1785.45  4946.3 1781.13
  4959.8 1776.73  4967.3 1776.89  4982.4 1774.54  4988.4 1775.74  4990.9 1774.31
  4991.1 1773.81  4994.9 1774.31  5032.2 1775.57  5071.4 1785.78  5107.7 1786.61
#Mann=4,-1,0
  4635.3     0.1       0  4806.5   0.035       0  4990.9   0.035       0
  4994.9   0.035       0
Bank Sta=4990.9,4994.9
Exp/Cntr=0.3,0.1

Type RM Length L Ch R = 1,1119,183,183,183
BEGIN DESCRIPTION:
Mapping XS c90e59b7
END DESCRIPTION:
XS GIS Cut Line= 2
      1920090.12     13952405.82      1920070.89     13952641.84
#Sta/Elev= 30
  4878.1 1779.35  4880.9 1778.28  4887.3 1777.98  4897.3 1777.29  4901.4 1777.28
  4907.4 1777.26  4917.4 1777.36  4927.4 1777.29  4929.3 1777.23  4937.5 1776.96
  4957.5 1776.02  4967.6 1775.73  4977.6 1775.37  4987.6 1774.35  4997.7 1771.50
  5002.7 1766.64  5007.7 1767.52  5015.7 1765.07  5016.0 1764.57  5019.5 1764.57
  5019.7 1765.07  5027.8 1767.15  5037.8 1770.36  5047.8 1773.39  5057.9 1776.07
  5059.7 1776.25  5067.9 1777.05  5098.0 1777.54  5108.0 1777.96  5114.9 1778.53
#Mann=6,-1,0
  4878.1   0.035       0  4901.4   0.063       0  4929.3   0.035       0
  5015.7   0.035       0  5019.7   0.035       0  5059.7   0.063       0
Bank Sta=5015.7,5019.7
Exp/Cntr=0.3,0.1

Type RM Length L Ch R = 1,936,436,436,436
BEGIN DESCRIPTION:
Stream0505 2.0
END DESCRIPTION:
XS GIS Cut Line= 3
      1919988.32     13952212.81      1919925.00     13952525.00
      1919974.98     13952624.96
#Sta/Elev= 30
  4686.3 1769.94  4726.2 1770.58  4731.3 1770.23  4770.2 1771.60  4782.0 1771.18
  4827.5 1772.54  4841.6 1772.49  4878.2 1774.38  4928.9 1773.81  4943.6 1772.73
  4953.8 1771.19  4974.2 1766.04  4979.5 1763.10  4984.6 1761.00  4992.6 1759.11
  4992.9 1758.61  4996.4 1758.61  4996.6 1759.11  5002.3 1760.06  5007.6 1760.06
  5013.2 1764.86  5018.8 1763.53  5027.2 1767.26  5035.6 1769.82  5041.2 1766.62
  5057.9 1768.50  5063.5 1770.31  5080.3 1771.71  5085.9 1773.45  5116.6 1774.29
#Mann=3,-1,0
  4686.3   0.035       0  4992.6   0.035       0  4996.6   0.035       0
Bank Sta=4992.6,4996.6
Exp/Cntr=0.3,0.1

Type RM Length L Ch R = 1,500,251,251,251
BEGIN DESCRIPTION:
Stream0505 1.0
END DESCRIPTION:
XS GIS Cut Line= 3
      1920009.86     13952002.50      1919625.00     13952425.00
      1919573.46     13952640.93
#Sta/Elev= 30
  4433.7 1767.54  4460.3 1767.21  4467.0 1766.04  4551.2 1765.34  4700.8 1764.98
  4715.0 1765.67  4743.4 1765.97  4750.1 1765.33  4828.5 1766.86  4920.4 1765.72
  4948.8 1764.01  4955.5 1759.86  4963.0 1757.48  4969.7 1752.79  4989.3 1749.57
  4989.6 1749.07  4993.1 1749.07  4993.3 1749.57  4998.1 1750.34  5001.8 1751.89
  5023.7 1753.67  5046.3 1754.60  5056.6 1756.35  5077.2 1762.51  5087.5 1764.63
  5097.7 1765.43  5113.0 1764.79  5149.1 1765.18  5160.3 1764.62  5227.2 1764.58
#Mann=4,-1,0
  4433.7   0.035       0  4551.2    0.07       0  4989.3    0.05       0
  4993.3    0.07       0
Bank Sta=4989.3,4993.3
Exp/Cntr=0.3,0.1

Type RM Length L Ch R = 1,249,0,0,0
BEGIN DESCRIPTION:
Stream0505 0.0
END DESCRIPTION:
XS GIS Cut Line= 3
      1919633.91     13952083.63      1919433.44     13952388.26
      1919434.02     13952535.19
#Sta/Elev= 30
  4674.0 1761.32  4732.6 1762.08  4804.9 1761.78  4826.0 1760.89  4847.0 1759.16
  4862.1 1758.95  4868.1 1758.06  4877.2 1758.03  4883.2 1757.35  4898.2 1757.44
  4904.2 1756.46  4913.3 1756.14  4919.3 1753.66  4927.0 1752.73  4940.4 1749.79
  4949.5 1746.94  4970.5 1746.48  4976.5 1745.78  4991.6 1746.05  4996.9 1745.42
  4997.1 1744.92  5000.6 1744.92  5000.9 1745.42  5021.8 1747.55  5027.8 1749.24
  5033.7 1749.98  5055.4 1750.81  5075.4 1754.35  5085.4 1755.30  5185.6 1757.75
#Mann=3,-1,0
  4674.0    0.07       0  4996.9    0.05       0  5000.9    0.07       0
Bank Sta=4996.9,5000.9
Exp/Cntr=0.3,0.1

Chan Stop Cuts=-1