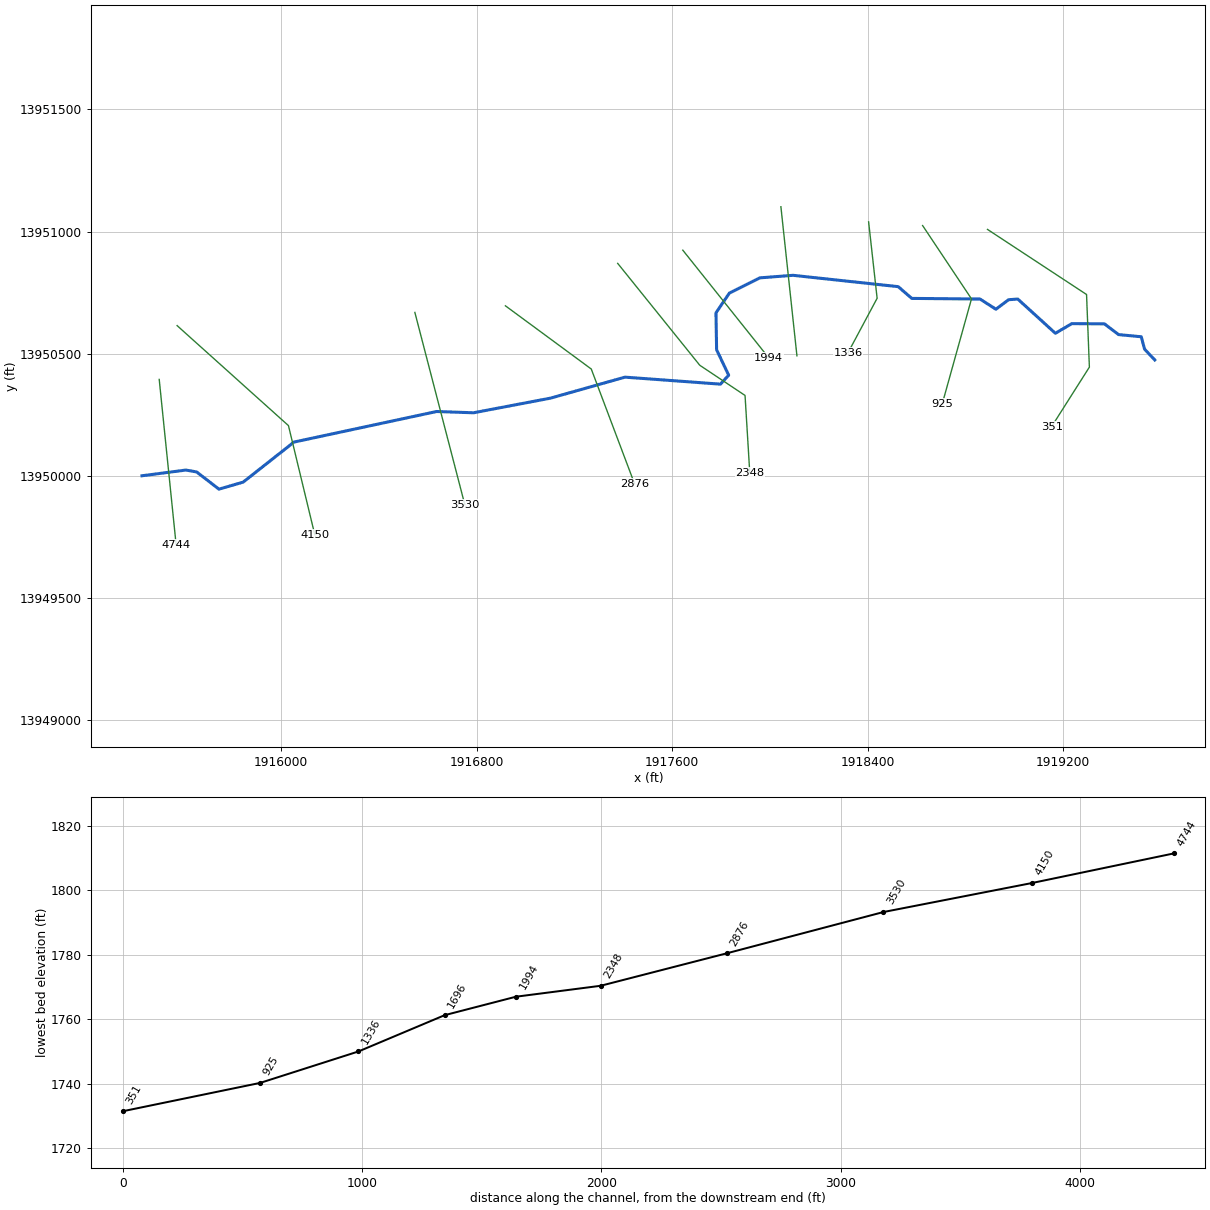
--- Stream0506.prj (project) ---

Proj Title=Stream0506 Base Level Engineering
Current Plan=p01
Default Exp/Contr=0.3,0.1
English Units
Geom File=g01
Flow File=f01
Plan File=p01
Y Axis Title=Elevation
X Axis Title(PF)=Main Channel Distance
X Axis Title(XS)=Station
BEGIN DESCRIPTION:
Stream0506
END DESCRIPTION:
DSS Export Rating Curves= 0
DSS Export Rating Curve Sorted= 0
DSS Export Volume Flow Curves= 0
DXF OffsetX= 0
DXF OffsetY= 0
DXF ScaleX= 1
DXF ScaleY= 10

--- Stream0506.p01 (plan) ---

Plan Title=Multiple Run
Short Identifier=Multiple
Geom File=g01
Flow File=f01
Subcritical Flow
K Sum by GR= 0
Std Step Tol= 0.01
Critical Tol= 0.01
Num of Std Step Trials= 20
Max Error Tol= 0.3
Flow Tol Ratio= 0.001
Split Flow NTrial= 30
Split Flow Tol= 0.02
Split Flow Ratio= 0.02
Log Output Level= 0
Friction Slope Method= 1
Unsteady Friction Slope Method= 2
Unsteady Bridges Friction Slope Method= 1
Parabolic Critical Depth
Global Vel Dist=  1 , 1 , 1
Global Log Level= 0
CheckData=True
Encroach Param= -1, 0, 0, 0
BEGIN DESCRIPTION:
Multiple Run
END DESCRIPTION:

--- Stream0506.f01 (steady flow) ---

Flow Title=Multiple
Program Version=4.10
Number of Profiles= 7
Profile Names=10-year,25-year,50-year,1pct_min,100-year,1pct_plu,500-year
River Rch & RM=Stream0506,Reach-1         ,4744
    1303    2243    3148    2136    4261    8502    7709
Boundary for River Rch & Prof#=Stream0506,Reach-1         , 1
Up Type= 0
Dn Type= 3
Dn Slope=0.007
Boundary for River Rch & Prof#=Stream0506,Reach-1         , 2
Up Type= 0
Dn Type= 3
Dn Slope=0.007
Boundary for River Rch & Prof#=Stream0506,Reach-1         , 3
Up Type= 0
Dn Type= 3
Dn Slope=0.007
Boundary for River Rch & Prof#=Stream0506,Reach-1         , 4
Up Type= 0
Dn Type= 3
Dn Slope=0.007
Boundary for River Rch & Prof#=Stream0506,Reach-1         , 5
Up Type= 0
Dn Type= 3
Dn Slope=0.007
Boundary for River Rch & Prof#=Stream0506,Reach-1         , 6
Up Type= 0
Dn Type= 3
Dn Slope=0.007
Boundary for River Rch & Prof#=Stream0506,Reach-1         , 7
Up Type= 0
Dn Type= 3
Dn Slope=0.007
DSS Import GetInterval= 0
DSS Import GetPeak= 0
DSS Import FillOption= 0

--- Stream0506.g01 (geometry) ---

Geom Title=Existing Conditions
Program Version=4.10

River Reach=Stream0506      ,Reach-1
Reach XY= 30
      1915430.47     13950001.06      1915610.16     13950024.49
      1915654.43     13950016.68      1915745.58     13949946.37
      1915844.54     13949975.01      1916052.87     13950139.08
       1916636.2     13950264.08      1916787.24     13950258.87
      1917102.35     13950318.76      1917407.04      13950404.7
      1917797.66     13950376.06      1917831.51     13950412.51
      1917782.04     13950516.68      1917779.43     13950667.72
      1917834.12     13950748.45      1917959.12     13950810.95
      1918094.54     13950821.37        1918525.       13950775.
      1918580.78     13950726.89      1918859.84     13950724.34
      1918925.01     13950682.59      1918976.65     13950721.43
      1919014.36     13950724.35      1919168.26     13950584.13
      1919235.44     13950623.62      1919369.06     13950622.75
      1919426.67     13950578.89      1919519.73      13950569.9
      1919533.15     13950519.36        1919575.       13950475.

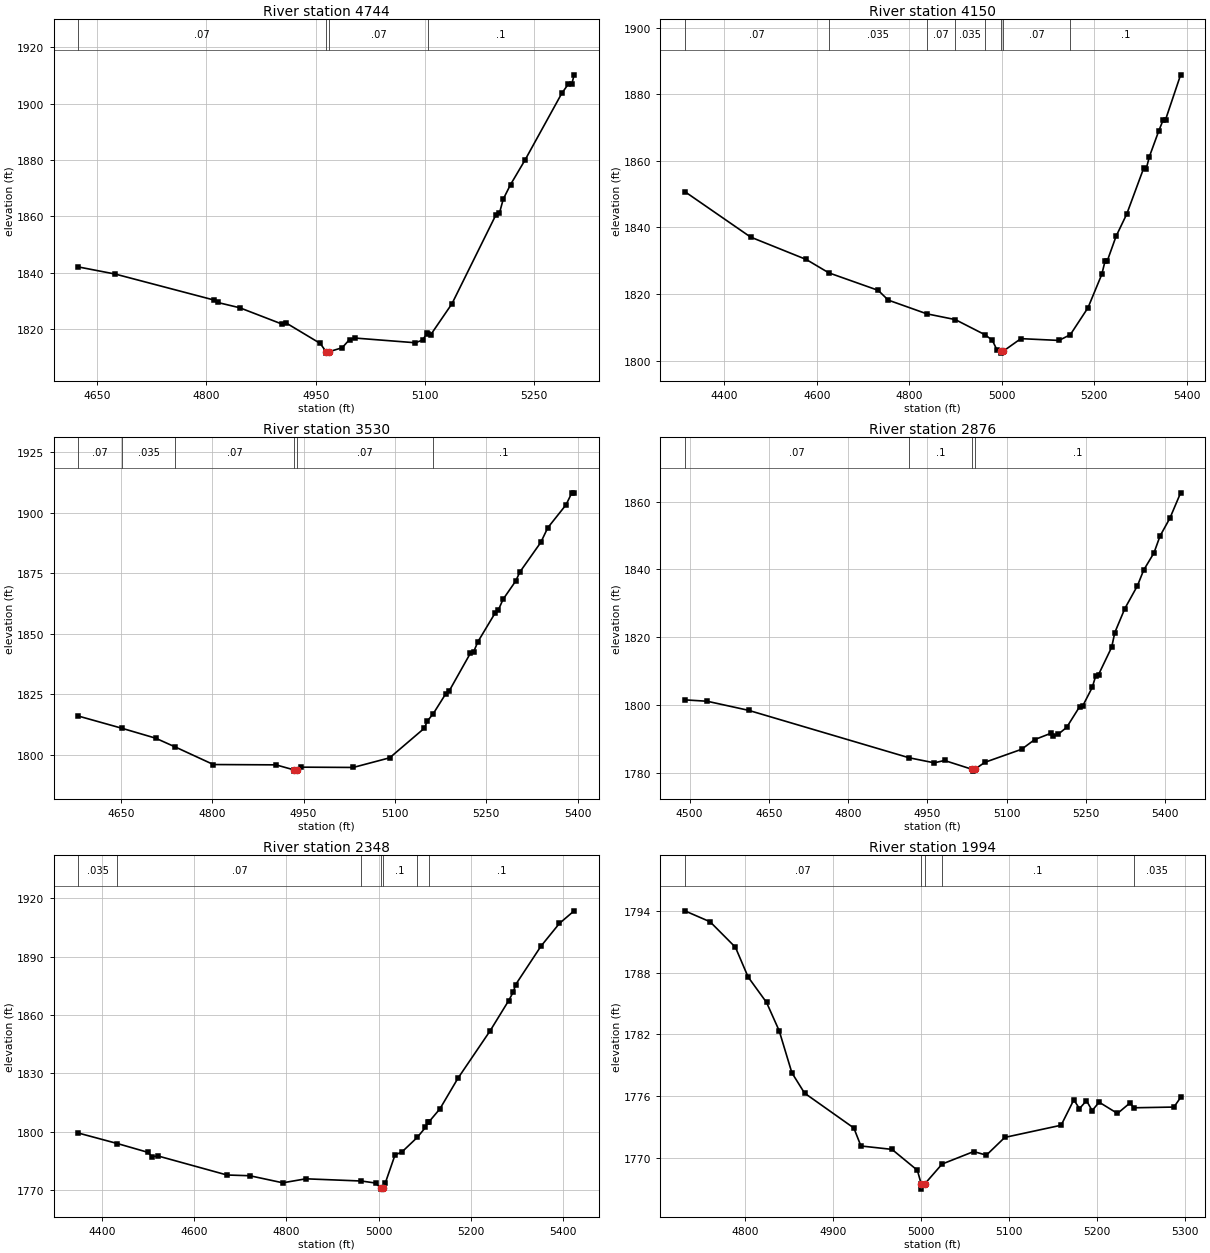
Type RM Length L Ch R = 1 ,4744    ,594,594,594
BEGIN DESCRIPTION:
Stream0506 9.0
END DESCRIPTION:
XS GIS Cut Line= 2
      1915501.19     13950395.43      1915570.46     13949718.07
#Sta/Elev= 30
  4624.1 1842.06  4674.8 1839.53  4809.8 1830.36  4815.5 1829.45  4845.7 1827.58
  4904.1 1821.76  4909.2 1822.22  4956.3 1814.92  4964.3 1811.98  4964.6 1811.48
  4968.1 1811.48  4968.3 1811.98  4986.4 1813.39  4996.5 1816.29  5003.5 1816.84
  5086.9 1815.16    5097 1816.12  5102.9  1818.6  5104.7 1818.38    5108 1817.99
  5137.2 1829.01  5197.3 1860.41  5202.3 1861.05  5207.6 1866.11  5217.6 1871.26
  5237.7 1880.07    5288 1903.65  5296.7 1906.84  5301.7 1906.92    5305 1910.22
#Mann= 4 ,-1 , 0
  4624.1     .07       0  4964.3     .05       0  4968.3     .07       0
  5104.7      .1       0
Bank Sta=4964.3,4968.3
XS Rating Curve= 0 ,0
Exp/Cntr=0.3,0.1

Type RM Length L Ch R = 1 ,4150    ,620,620,620
BEGIN DESCRIPTION:
Stream0506 7.0
END DESCRIPTION:
XS GIS Cut Line= 3
      1915574.52      13950615.5      1916030.04      13950206.3
      1916137.95     13949759.26
#Sta/Elev= 30
  4314.7 1850.77    4457 1837.12  4577.4 1830.39    4626 1826.39  4732.9 1821.13
  4754.6  1818.2    4838 1814.08  4899.6 1812.35  4964.5 1807.75  4979.8 1806.11
  4990.1 1803.13  4998.4 1802.78  4998.6 1802.28  5002.4 1802.78  5041.5 1806.63
  5123.8 1806.09  5148.4 1807.82  5186.6 1815.91  5216.4 1825.92  5223.4 1829.86
  5228.5 1830.05  5247.3 1837.35  5270.4 1844.04  5307.1 1857.84  5312.3 1857.49
  5319.3 1861.25  5339.8 1869.06    5349 1872.24  5354.2 1872.32  5386.9 1885.83
#Mann= 8 ,-1 , 0
  4314.7     .07       0    4626    .035       0    4838     .07       0
  4899.6    .035       0  4964.5     .07       0  4998.4     .05       0
  5002.4     .07       0  5148.4      .1       0
Bank Sta=4998.4,5002.4
XS Rating Curve= 0 ,0
Exp/Cntr=0.3,0.1

Type RM Length L Ch R = 1 ,3530    ,654,654,654
BEGIN DESCRIPTION:
Stream0506 6.0
END DESCRIPTION:
XS GIS Cut Line= 2
      1916547.32     13950669.52      1916751.91     13949882.07
#Sta/Elev= 30
  4580.5 1816.03  4651.7 1811.01  4707.2 1806.91  4739.5 1803.27  4802.1 1796.01
  4904.8 1795.88  4934.5 1793.79  4934.7 1793.29  4938.5 1793.79  4945.3 1794.93
  5031.6 1794.81  5091.4 1798.79  5148.1 1810.97  5153.4 1814.04  5162.8 1816.97
  5183.5 1825.26  5188.6 1826.19    5224 1842.06  5229.2 1842.59  5236.1  1846.7
  5264.6 1858.66  5269.7 1859.81  5277.4 1864.22  5298.1 1871.75  5305.1 1875.54
  5339.4 1887.77  5350.8 1893.78  5380.7 1903.24  5390.3 1908.21  5394.1 1908.21
#Mann= 6 ,-1 , 0
  4580.5     .07       0  4651.7    .035       0  4739.5     .07       0
  4934.5     .05       0  4938.5     .07       0  5162.8      .1       0
Bank Sta=4934.5,4938.5
XS Rating Curve= 0 ,0
Exp/Cntr=0.3,0.1

Type RM Length L Ch R = 1 ,2876    ,528,528,528
BEGIN DESCRIPTION:
Stream0506 5.0
END DESCRIPTION:
XS GIS Cut Line= 3
      1916917.89     13950696.56      1917269.19     13950437.91
      1917446.18     13949968.52
#Sta/Elev= 30
  4491.1 1801.53  4533.4 1801.12  4611.7 1798.44  4915.4 1784.44  4962.9 1782.95
  4982.4 1783.64  5035.3    1781  5035.6  1780.5  5039.3    1781  5058.7  1783.1
  5128.1 1786.94    5153 1789.81  5183.2 1791.64  5188.5 1790.76  5197.6 1791.41
  5213.4 1793.41  5238.2 1799.57  5243.6 1799.67  5261.8  1805.2  5268.4  1808.6
  5273.8    1809  5298.6 1817.07  5304.5 1821.39  5323.5 1828.48  5347.3  1835.2
  5359.1 1839.82  5378.6  1844.9    5390 1849.86  5408.8 1855.17    5429 1862.62
#Mann= 4 ,-1 , 0
  4491.1     .07       0  4915.4      .1       0  5035.3     .05       0
  5039.3      .1       0
Bank Sta=5035.3,5039.3
XS Rating Curve= 0 ,0
Exp/Cntr=0.3,0.1

Type RM Length L Ch R = 1 ,2348    ,354,354,354
BEGIN DESCRIPTION:
Stream0506 8.0
END DESCRIPTION:
XS GIS Cut Line= 4
      1917377.27     13950870.27      1917713.12     13950453.35
      1917898.41     13950329.82      1917917.72     13950013.27
#Sta/Elev= 30
  4348.6 1799.27  4433.5 1793.85  4499.7 1789.33  4507.7 1787.17  4522.1 1787.42
  4670.9 1777.68  4720.5  1777.3    4792 1773.66    4842 1775.72  4962.5 1774.58
  4993.3 1773.54  5004.4 1770.91  5004.7 1770.41  5008.4 1770.91  5014.3 1773.59
  5035.3 1787.98  5050.4 1789.55  5083.6 1797.04  5101.4 1802.16  5106.5 1805.11
  5109.2 1805.11  5132.7 1811.72  5171.6 1827.39  5241.7 1851.92  5281.8 1867.41
  5291.8 1871.87  5296.9 1875.64  5351.9 1895.46    5392 1907.18  5423.8 1913.62
#Mann= 7 ,-1 , 0
  4348.6    .035       0  4433.5     .07       0  4962.5      .1       0
  5004.4     .05       0  5008.4      .1       0  5083.6     .07       0
  5109.2      .1       0
Bank Sta=5004.4,5008.4
XS Rating Curve= 0 ,0
Exp/Cntr=0.3,0.1

Type RM Length L Ch R = 1 ,1994    ,298,298,298
BEGIN DESCRIPTION:
Stream0506 4.0
END DESCRIPTION:
XS GIS Cut Line= 2
      1917643.61     13950924.34      1917994.91     13950484.25
#Sta/Elev= 30
  4731.5 1793.98  4760.2 1792.92    4789 1790.45  4803.4 1787.57  4824.3 1785.11
  4838.7 1782.36  4853.1 1778.29  4867.5 1776.32  4923.5 1772.94  4931.5  1771.2
  4966.8 1770.87  4995.6 1768.85    5000 1767.52  5000.2 1767.02    5004 1767.52
  5023.7 1769.45  5059.6 1770.66    5074 1770.31  5094.9 1772.03  5158.9 1773.21
  5173.3 1775.67  5179.7 1774.82  5187.7 1775.59  5194.1 1774.63  5202.1 1775.44
  5222.9 1774.35  5237.4 1775.39  5241.2  1774.9    5287 1774.97  5294.6  1775.9
#Mann= 5 ,-1 , 0
  4731.5     .07       0    5000     .05       0    5004     .07       0
  5023.7      .1       0  5241.2    .035       0
Bank Sta=5000,5004
XS Rating Curve= 0 ,0
Exp/Cntr=0.3,0.1

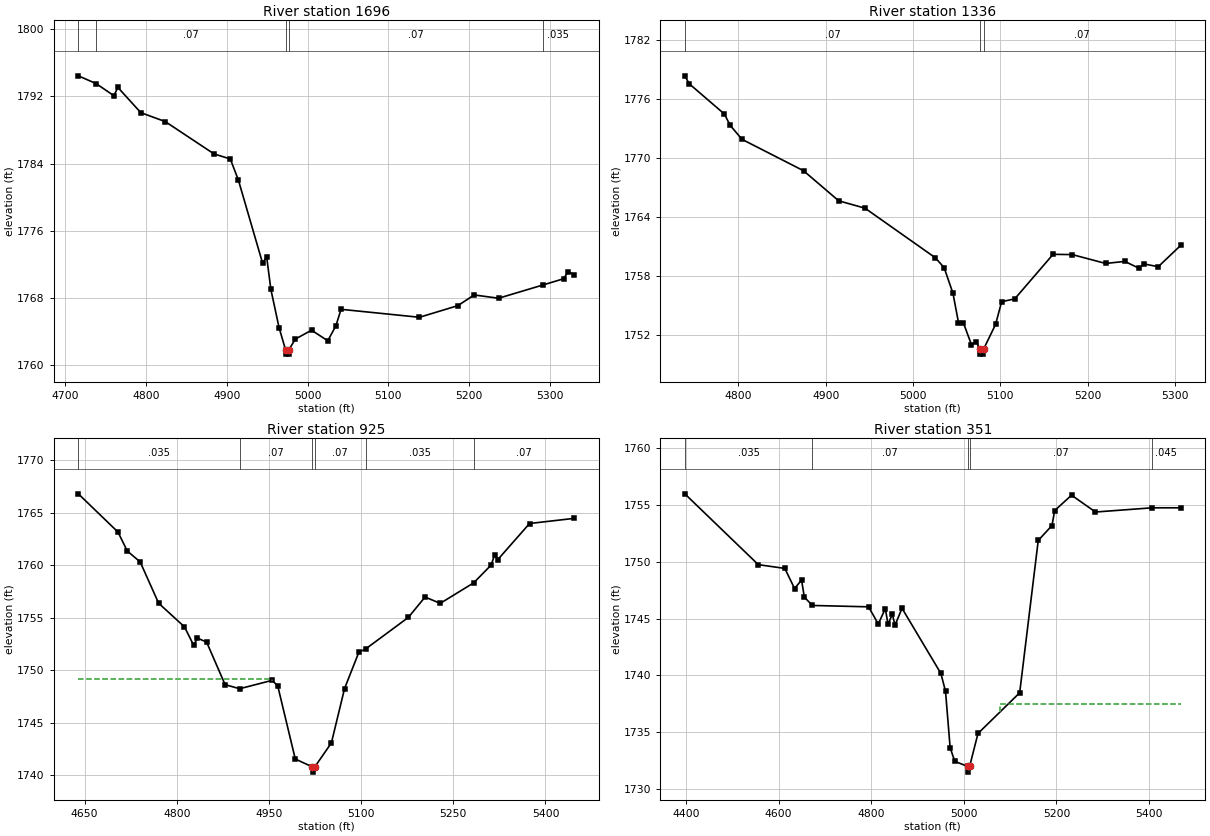
Type RM Length L Ch R = 1 ,1696    ,360,360,360
BEGIN DESCRIPTION:
Stream0506 3.0
END DESCRIPTION:
XS GIS Cut Line= 2
      1918045.11     13951101.87      1918110.73     13950491.99
#Sta/Elev= 30
  4716.4 1794.45  4738.3 1793.53  4760.3 1792.09  4765.4 1793.06  4793.7 1790.06
  4823.9    1789  4884.2 1785.15  4904.4 1784.54  4914.4 1782.03  4944.3 1772.14
  4949.4 1772.87  4954.6    1769  4964.7 1764.46  4972.8 1761.79    4973 1761.29
  4976.5 1761.29  4976.8 1761.79  4984.8 1763.08  5004.9 1764.14    5025 1762.88
  5035.1 1764.68  5041.4 1766.63  5138.4 1765.68    5186 1767.07  5206.1 1768.34
  5236.3 1767.95  5290.9 1769.52  5316.7 1770.27  5322.4 1771.12  5329.8 1770.76
#Mann= 5 ,-1 , 0
  4716.4    .035       0  4738.3     .07       0  4972.8     .05       0
  4976.8     .07       0  5290.9    .035       0
Bank Sta=4972.8,4976.8
XS Rating Curve= 0 ,0
Exp/Cntr=0.3,0.1

Type RM Length L Ch R = 1 ,1336    ,411,411,411
BEGIN DESCRIPTION:
Stream0506 2.0
END DESCRIPTION:
XS GIS Cut Line= 3
      1918404.11     13951040.08      1918438.85     13950727.43
      1918319.58     13950504.27
#Sta/Elev= 30
  4738.7 1778.34  4743.8 1777.53  4784.1 1774.45  4790.5 1773.32  4804.2 1771.88
  4874.6 1768.69  4914.9 1765.63    4945 1764.88  5025.5 1759.84  5035.6 1758.83
  5045.7 1756.22    5052 1753.25  5057.5 1753.25  5066.9 1750.99  5072.5 1751.25
  5076.7 1750.54    5077 1750.04  5080.5 1750.04  5080.7 1750.54  5094.5 1753.07
  5101.4 1755.37  5116.4 1755.66  5160.3 1760.19  5182.3 1760.16  5220.5 1759.26
  5242.4 1759.47  5258.7 1758.77  5264.4 1759.21  5280.7 1758.93  5306.3 1761.09
#Mann= 3 ,-1 , 0
  4738.7     .07       0  5076.7     .05       0  5080.7     .07       0
Bank Sta=5076.7,5080.7
XS Rating Curve= 0 ,0
Exp/Cntr=0.3,0.1

Type RM Length L Ch R = 1 ,925     ,574,574,574
BEGIN DESCRIPTION:
Stream0506 1.0
END DESCRIPTION:
XS GIS Cut Line= 3
      1918625.02     13951024.96        1918825.       13950725.
      1918705.21     13950295.09
#Sta/Elev= 30
  4639.9 1766.81  4704.5 1763.16  4719.5 1761.36  4740.5 1760.32  4770.6 1756.38
  4812.6 1754.13  4827.6 1752.37  4833.7 1753.06  4848.7 1752.67  4878.7 1748.62
  4902.4 1748.23  4955.3 1749.03  4964.4 1748.49  4992.9 1741.53  5020.7 1740.78
    5021 1740.28  5024.7 1740.78  5051.7 1743.07  5073.1 1748.25  5096.3  1751.7
  5107.6 1752.03  5176.9 1755.03  5204.1 1756.97  5228.8 1756.37  5283.1 1758.32
  5311.8 1760.03  5317.1 1760.98  5322.3 1760.53  5374.1 1763.98  5446.7 1764.47
#Mann= 6 ,-1 , 0
  4639.9    .035       0  4902.4     .07       0  5020.7     .05       0
  5024.7     .07       0  5107.6    .035       0  5283.1     .07       0
#XS Ineff= 2 , 0
         4954.26 1749.16
Permanent Ineff=
       F       F
Bank Sta=5020.7,5024.7
XS Rating Curve= 0 ,0
Exp/Cntr=0.3,0.1

Type RM Length L Ch R = 1 ,351     ,0,0,0
BEGIN DESCRIPTION:
Stream0506 0.0
END DESCRIPTION:
XS GIS Cut Line= 4
      1918890.53     13951009.21      1919295.83     13950742.87
      1919307.41     13950445.63      1919153.01     13950202.45
#Sta/Elev= 30
  4397.5 1755.97  4556.2 1749.74  4613.4 1749.41  4634.5 1747.64  4649.6 1748.39
  4655.6 1746.88    4673 1746.15  4794.2 1746.03  4815.3 1744.52  4830.4 1745.88
  4836.3 1744.48  4845.4 1745.38  4851.4 1744.42  4866.5  1745.9  4950.4 1740.17
  4960.4  1738.6  4970.4 1733.63  4980.4 1732.44  5008.4 1731.99  5008.7 1731.49
  5012.4 1731.99  5030.5 1734.89  5120.5 1738.47  5160.6 1751.87  5190.2 1753.18
  5196.1  1754.5  5232.5 1755.85  5284.2 1754.37  5406.1 1754.74    5468 1754.74
#Mann= 5 ,-1 , 0
  4397.5    .035       0    4673     .07       0  5008.4     .05       0
  5012.4     .07       0  5406.1    .045       0
#XS Ineff= 2 , 0
                         5078.92          1737.5
Permanent Ineff=
       F       F
Bank Sta=5008.4,5012.4
XS Rating Curve= 0 ,0
Exp/Cntr=0.3,0.1

Chan Stop Cuts=-1
Use User Specified Reach Order=0
Composite Channel Slope=5