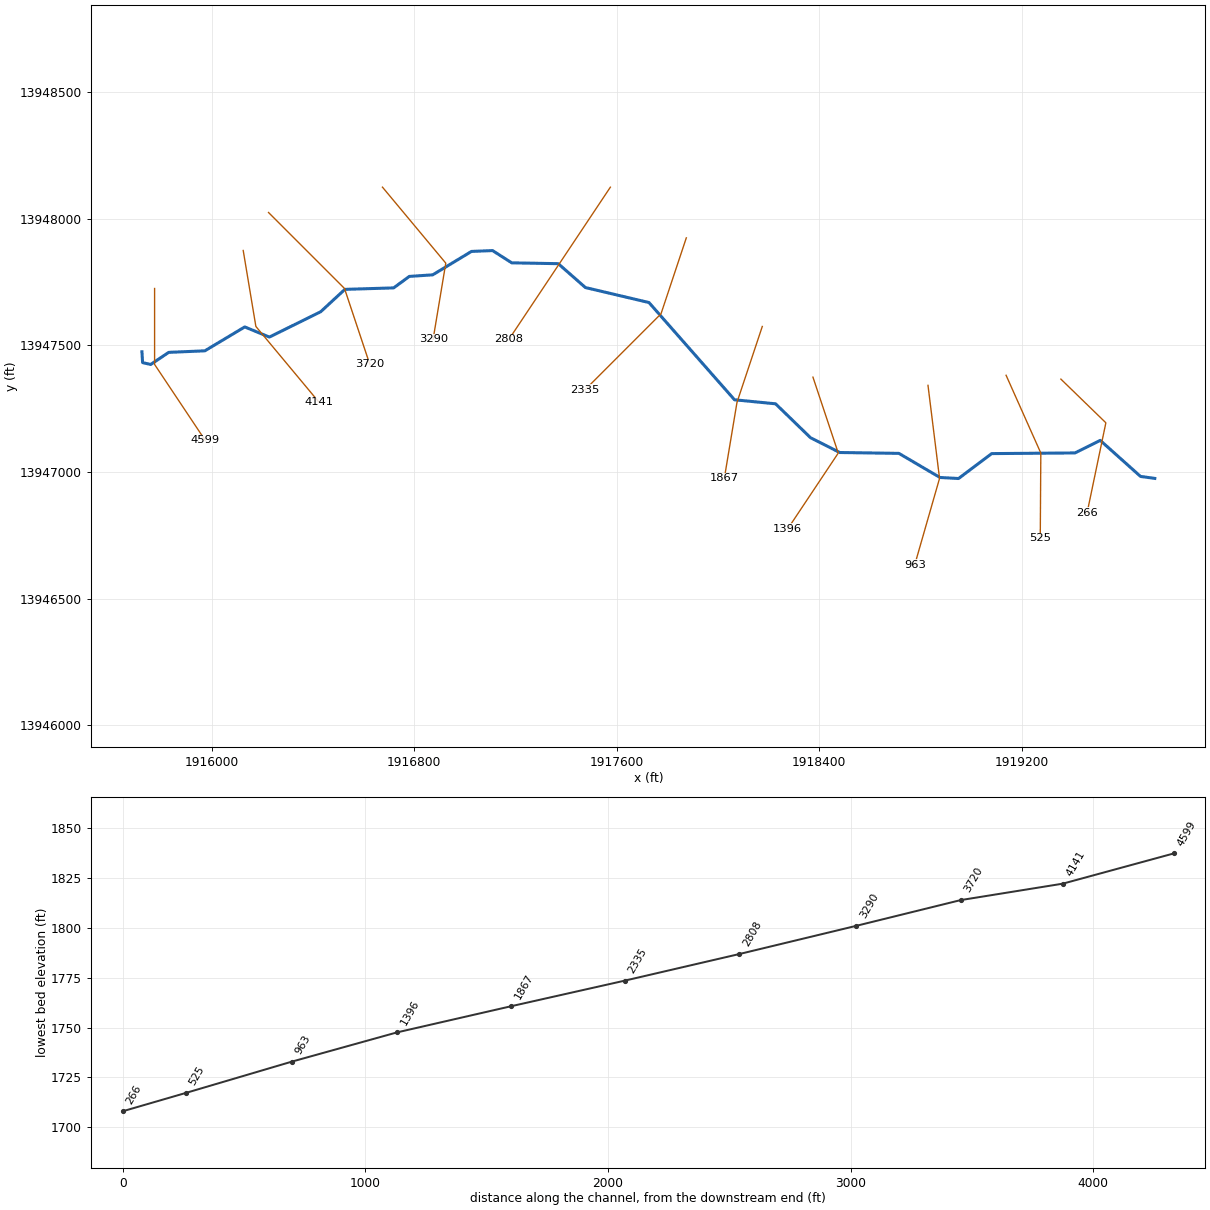
--- Stream0508.prj (project) ---

Proj Title=Stream0508 Base Level Engineering
Current Plan=p01
Default Exp/Contr=0.3,0.1
English Units
Geom File=g01
Flow File=f01
Plan File=p01
BEGIN DESCRIPTION:
Stream0508
END DESCRIPTION:

--- Stream0508.p01 (plan) ---

Plan Title=Multiple Run
Short Identifier=Multiple
Geom File=g01
Flow File=f01
Subcritical Flow
K Sum by GR= 0
Std Step Tol= 0.01
Critical Tol= 0.01
Num of Std Step Trials= 20
Max Error Tol= 0.3
Flow Tol Ratio= 0.001
Split Flow NTrial= 30
Split Flow Tol= 0.02
Split Flow Ratio= 0.02
Log Output Level= 0
Friction Slope Method= 1
Unsteady Friction Slope Method= 2
Unsteady Bridges Friction Slope Method= 1
Parabolic Critical Depth
Global Vel Dist=  1 , 1 , 1
Global Log Level= 0
CheckData=True
Encroach Param= -1, 0, 0, 0
BEGIN DESCRIPTION:
Multiple Run
END DESCRIPTION:

--- Stream0508.f01 (steady flow) ---

Flow Title=Multiple
Number of Profiles=7
Profile Names=10-year,25-year,50-year,1pct_min,100-year,1pct_plu,500-year
River Rch & RM= Stream0508,Reach-1,4599
     856    1445    2001    1343    2681    5348    4742
Boundary for River Rch & Prof#=Stream0508,Reach-1,1
Up Type=0
Dn Type=3
Dn Slope=0.005
Boundary for River Rch & Prof#=Stream0508,Reach-1,2
Up Type=0
Dn Type=3
Dn Slope=0.005
Boundary for River Rch & Prof#=Stream0508,Reach-1,3
Up Type=0
Dn Type=3
Dn Slope=0.005
Boundary for River Rch & Prof#=Stream0508,Reach-1,4
Up Type=0
Dn Type=3
Dn Slope=0.005
Boundary for River Rch & Prof#=Stream0508,Reach-1,5
Up Type=0
Dn Type=3
Dn Slope=0.005
Boundary for River Rch & Prof#=Stream0508,Reach-1,6
Up Type=0
Dn Type=3
Dn Slope=0.005
Boundary for River Rch & Prof#=Stream0508,Reach-1,7
Up Type=0
Dn Type=3
Dn Slope=0.005

--- Stream0508.g01 (geometry) ---

Geom Title=Existing Conditions

River Reach=Stream0508,Reach-1
Reach XY= 30
      1915725.00     13947475.00      1915727.61     13947432.24
      1915759.45     13947424.86      1915830.91     13947472.73
      1915973.44     13947478.76      1916131.12     13947573.16
      1916228.31     13947533.07      1916431.05     13947633.16
      1916526.47     13947721.45      1916719.06     13947727.26
      1916780.98     13947772.64      1916873.42     13947778.83
      1917026.58     13947871.33      1917109.73     13947874.62
      1917185.50     13947826.22      1917369.14     13947822.93
      1917476.50     13947728.62      1917727.43     13947669.48
      1918065.20     13947285.48      1918227.45     13947269.53
      1918365.32     13947135.76      1918480.93     13947077.24
      1918714.50     13947073.80      1918876.59     13946978.67
      1918950.04     13946974.51      1919080.86     13947072.93
      1919409.79     13947075.54      1919509.66     13947125.05
      1919668.79     13946982.76      1919725.00     13946975.00

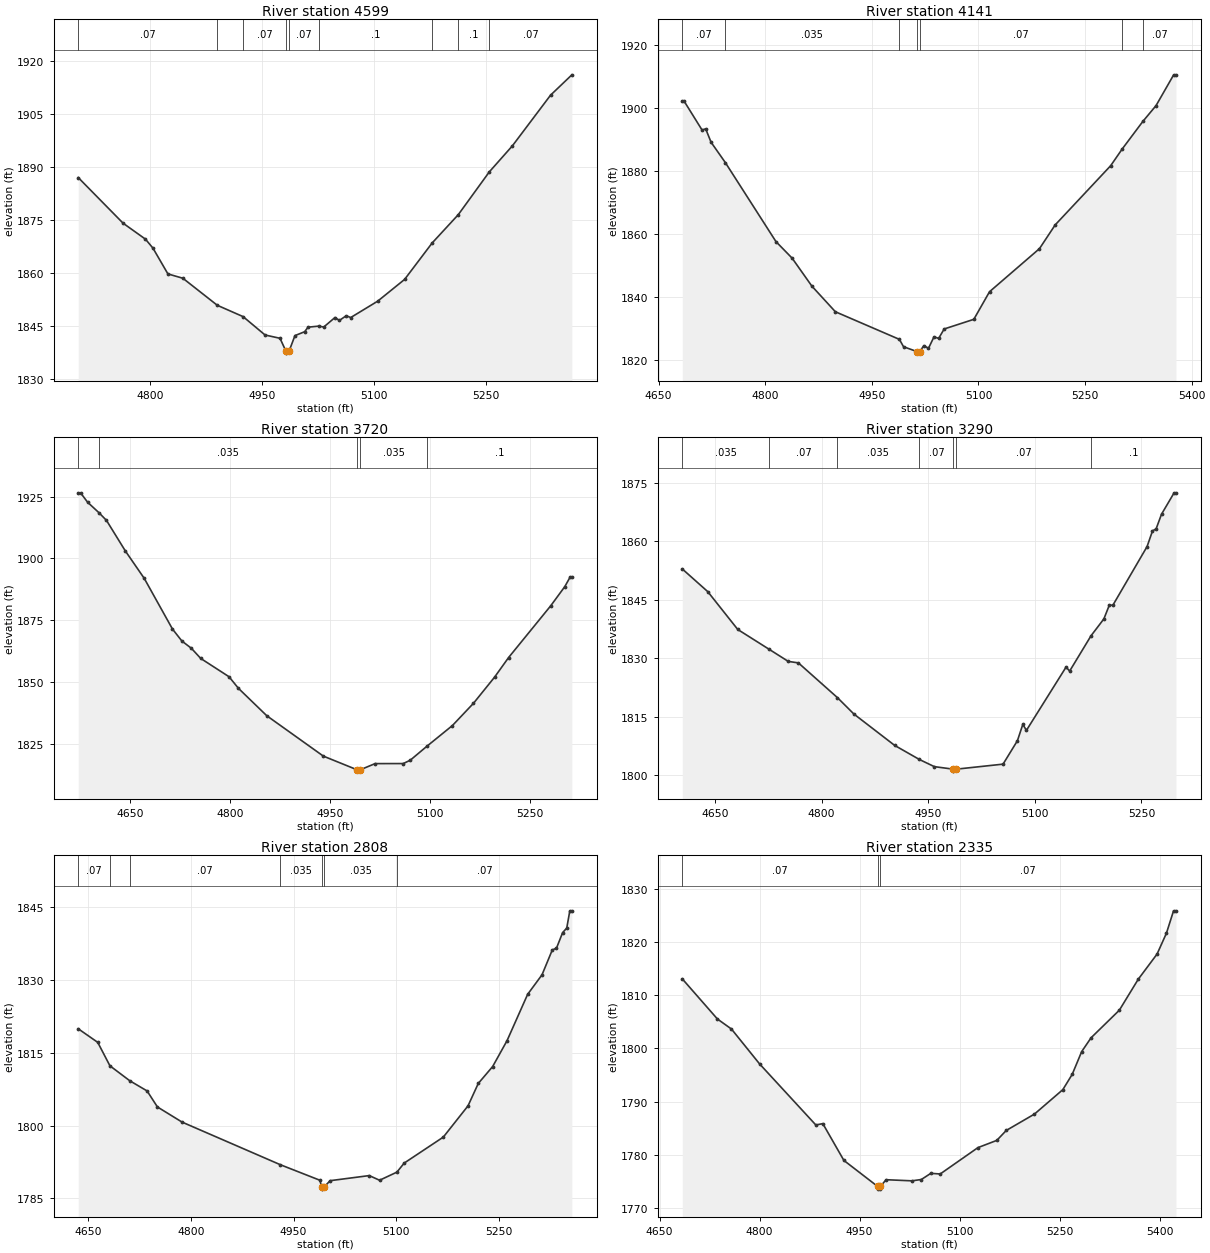
Type RM Length L Ch R = 1,4599,458,458,458
BEGIN DESCRIPTION:
Stream0508 10.0
END DESCRIPTION:
XS GIS Cut Line= 3
      1915775.00     13947724.97      1915775.00     13947425.00
      1915974.99     13947125.02
#Sta/Elev= 30
  4704.3 1886.99  4764.3 1874.10  4794.3 1869.58  4804.3 1867.05  4824.3 1859.77
  4844.3 1858.55  4890.4 1850.91  4924.9 1847.71  4954.3 1842.52  4974.3 1841.59
  4982.3 1837.90  4982.5 1837.40  4986.3 1837.90  4994.3 1842.35  5007.3 1843.45
  5011.8 1844.73  5026.2 1845.03  5032.8 1844.77  5047.8 1847.45  5053.8 1846.64
  5062.9 1847.96  5068.9 1847.45  5104.9 1852.06  5141.0 1858.22  5177.9 1868.52
  5212.8 1876.50  5254.3 1888.58  5285.2 1895.94  5336.3 1910.26  5364.8 1916.00
#Mann=9,-1,0
  4704.3    0.07       0  4890.4   0.035       0  4924.9    0.07       0
  4982.3    0.05       0  4986.3    0.07       0  5026.2     0.1       0
  5177.9    0.07       0  5212.8     0.1       0  5254.3    0.07       0
Bank Sta=4982.3,4986.3
Exp/Cntr=0.3,0.1

Type RM Length L Ch R = 1,4141,421,421,421
BEGIN DESCRIPTION:
Stream0508 9.0
END DESCRIPTION:
XS GIS Cut Line= 3
      1916125.01     13947874.96      1916175.00     13947575.00
      1916424.99     13947275.01
#Sta/Elev= 30
  4683.3 1902.14  4685.8 1902.14  4711.1 1892.97  4716.2 1893.34  4723.8 1889.09
  4743.9 1882.63  4815.1 1857.58  4837.9 1852.31  4865.7 1843.44  4898.7 1835.33
  4988.8 1826.57  4994.6 1824.24  5013.4 1822.71  5013.6 1822.21  5017.4 1822.71
  5023.2 1824.59  5029.7 1823.74  5037.5 1827.39  5044.0 1826.88  5051.8 1829.87
  5093.5 1832.93  5115.6 1841.68  5185.9 1855.35  5208.0 1862.88  5286.1 1881.66
  5302.3 1886.96  5331.3 1895.68  5349.9 1900.71  5374.7 1910.47  5377.9 1910.47
#Mann=7,-1,0
  4683.3    0.07       0  4743.9   0.035       0  4988.8    0.07       0
  5013.4    0.05       0  5017.4    0.07       0  5302.3     0.1       0
  5331.3    0.07       0
Bank Sta=5013.4,5017.4
Exp/Cntr=0.3,0.1

Type RM Length L Ch R = 1,3720,430,430,430
BEGIN DESCRIPTION:
Stream0508 8.0
END DESCRIPTION:
XS GIS Cut Line= 3
      1916225.02     13948024.98      1916525.00     13947725.00
      1916625.01     13947424.96
#Sta/Elev= 30
  4571.9 1926.49  4575.4 1926.49  4586.0 1922.68  4603.0 1918.45  4614.3 1915.34
  4642.6 1902.98  4670.9 1891.91  4713.3 1871.40  4727.4 1866.57  4741.6 1863.64
  4755.7 1859.52  4798.1 1852.13  4812.3 1847.42  4854.7 1836.37  4939.6 1820.03
  4990.6 1814.46  4990.8 1813.96  4994.6 1814.46  5017.2 1817.00  5059.4 1817.02
  5069.9 1818.36  5095.3 1824.10  5133.2 1832.39  5164.8 1841.39  5196.4 1851.94
  5217.5 1859.90  5280.7 1880.82  5301.8 1888.57  5309.7 1892.39  5312.4 1892.39
#Mann=5,-1,0
  4571.9    0.07       0  4603.0   0.035       0  4990.6   0.035       0
  4994.6   0.035       0  5095.3     0.1       0
Bank Sta=4990.6,4994.6
Exp/Cntr=0.3,0.1

Type RM Length L Ch R = 1,3290,482,482,482
BEGIN DESCRIPTION:
Stream0508 7.0
END DESCRIPTION:
XS GIS Cut Line= 3
      1916674.99     13948125.02      1916925.00     13947825.00
      1916875.00     13947524.97
#Sta/Elev= 30
  4603.9 1852.85  4639.7 1847.05  4682.0 1837.34  4726.2 1832.26  4753.0 1829.17
  4767.3 1828.78  4822.3 1819.87  4845.4 1815.68  4902.7 1807.65  4937.5 1804.04
  4958.6 1802.20  4985.3 1801.55  4985.5 1801.05  4989.3 1801.55  5055.3 1802.84
  5075.5 1808.84  5083.1 1813.02  5088.2 1811.50  5144.0 1827.72  5149.0 1826.68
  5179.2 1835.76  5197.2 1840.06  5204.8 1843.56  5209.9 1843.58  5258.0 1858.60
  5265.6 1862.60  5270.7 1863.13  5278.3 1866.88  5296.0 1872.36  5298.6 1872.36
#Mann=7,-1,0
  4603.9   0.035       0  4726.2    0.07       0  4822.3   0.035       0
  4937.5    0.07       0  4985.3    0.05       0  4989.3    0.07       0
  5179.2     0.1       0
Bank Sta=4985.3,4989.3
Exp/Cntr=0.3,0.1

Type RM Length L Ch R = 1,2808,473,473,473
BEGIN DESCRIPTION:
Stream0508 6.0
END DESCRIPTION:
XS GIS Cut Line= 3
      1917574.99     13948124.98      1917375.00     13947825.00
      1917174.99     13947524.99
#Sta/Elev= 30
  4635.5 1819.94  4664.0 1817.14  4681.8 1812.31  4710.8 1809.23  4736.1 1807.13
  4751.2 1803.83  4787.2 1800.71  4930.9 1791.92  4988.5 1788.73  4991.0 1787.40
  4991.3 1786.90  4995.0 1787.40  5003.5 1788.64  5060.6 1789.69  5075.7 1788.73
  5101.0 1790.40  5111.7 1792.27  5168.8 1797.62  5204.9 1804.06  5219.9 1808.68
  5240.9 1812.16  5261.9 1817.49  5292.0 1827.04  5313.0 1831.06  5328.0 1836.18
  5334.1 1836.54  5343.1 1839.75  5349.1 1840.68  5353.6 1844.24  5356.6 1844.24
#Mann=7,-1,0
  4635.5    0.07       0  4681.8   0.035       0  4710.8    0.07       0
  4930.9   0.035       0  4991.0   0.035       0  4995.0   0.035       0
  5101.0    0.07       0
Bank Sta=4991,4995
Exp/Cntr=0.3,0.1

Type RM Length L Ch R = 1,2335,468,468,468
BEGIN DESCRIPTION:
Stream0508 5.0
END DESCRIPTION:
XS GIS Cut Line= 3
      1917874.99     13947924.98      1917775.00     13947625.00
      1917474.98     13947324.98
#Sta/Elev= 30
  4684.1 1813.07  4736.8 1805.52  4757.9 1803.63  4800.0 1797.08  4884.4 1785.59
  4894.9 1785.84  4926.5 1778.92  4977.2 1774.02  4977.5 1773.52  4981.0 1773.52
  4981.2 1774.02  4989.8 1775.29  5028.6 1775.08  5042.7 1775.33  5056.9 1776.49
  5071.0 1776.37  5127.6 1781.33  5155.9 1782.69  5170.0 1784.55  5212.4 1787.64
  5254.9 1792.23  5269.0 1795.11  5283.2 1799.39  5297.3 1801.99  5339.7 1807.18
  5368.0 1812.99  5396.3 1817.74  5410.4 1821.68  5421.0 1825.87  5424.6 1825.87
#Mann=3,-1,0
  4684.1    0.07       0  4977.2    0.05       0  4981.2    0.07       0
Bank Sta=4977.2,4981.2
Exp/Cntr=0.3,0.1

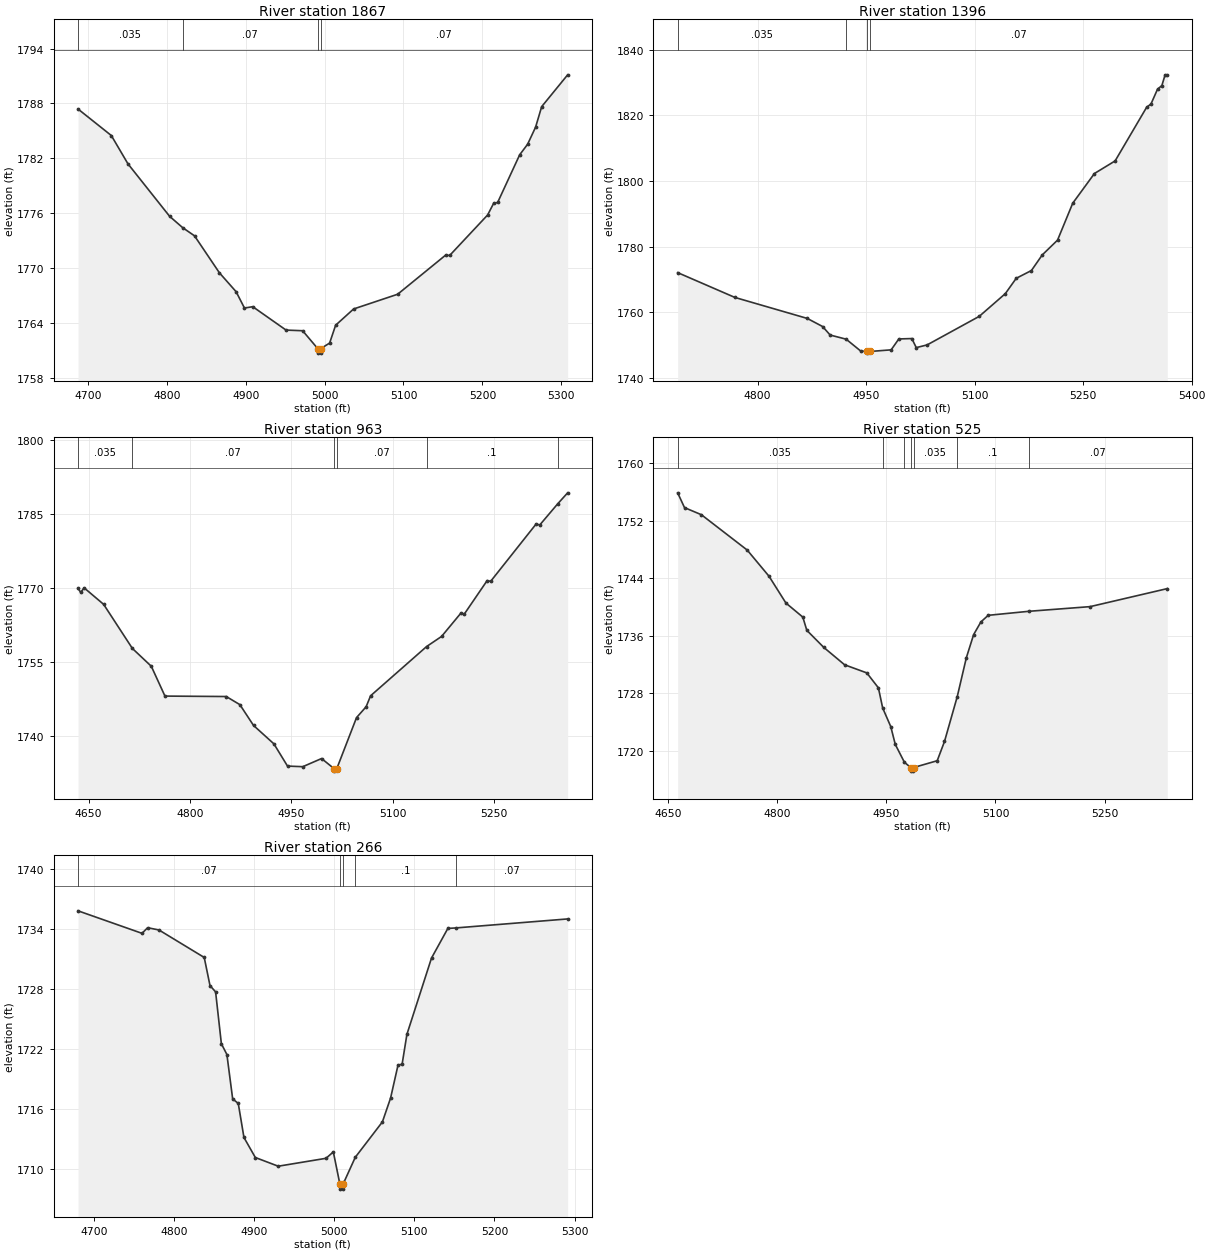
Type RM Length L Ch R = 1,1867,471,471,471
BEGIN DESCRIPTION:
Stream0508 4.0
END DESCRIPTION:
XS GIS Cut Line= 3
      1918175.01     13947575.03      1918075.00     13947275.00
      1918025.00     13946975.00
#Sta/Elev= 30
  4687.6 1787.39  4729.8 1784.49  4750.9 1781.39  4803.6 1775.66  4820.1 1774.42
  4835.2 1773.52  4866.8 1769.47  4887.9 1767.41  4898.5 1765.62  4909.0 1765.77
  4951.2 1763.21  4972.2 1763.14  4991.3 1761.19  4991.6 1760.69  4995.1 1760.69
  4995.3 1761.19  5006.4 1761.79  5014.0 1763.74  5036.8 1765.52  5092.6 1767.13
  5153.4 1771.41  5158.5 1771.37  5206.6 1775.80  5214.2 1777.07  5219.3 1777.17
  5247.2 1782.38  5257.3 1783.54  5267.4 1785.41  5275.1 1787.65  5308.0 1791.13
#Mann=4,-1,0
  4687.6   0.035       0  4820.1    0.07       0  4991.3    0.05       0
  4995.3    0.07       0
Bank Sta=4991.3,4995.3
Exp/Cntr=0.3,0.1

Type RM Length L Ch R = 1,1396,433,433,433
BEGIN DESCRIPTION:
Stream0508 3.0
END DESCRIPTION:
XS GIS Cut Line= 3
      1918375.00     13947375.00      1918475.00     13947075.00
      1918274.99     13946774.99
#Sta/Elev= 30
  4689.5 1772.07  4768.6 1764.51  4868.7 1758.11  4889.8 1755.65  4900.3 1753.05
  4922.4 1751.79  4942.5 1748.18  4951.0 1748.04  4951.3 1747.54  4955.0 1748.04
  4984.6 1748.54  4995.2 1751.86  5013.2 1751.98  5019.3 1749.22  5034.3 1750.04
  5106.4 1758.75  5142.4 1765.66  5157.5 1770.34  5178.5 1772.71  5193.5 1777.47
  5214.6 1781.97  5235.6 1793.22  5265.6 1802.27  5294.2 1806.11  5337.7 1822.43
  5343.8 1823.47  5352.8 1827.96  5358.8 1829.07  5363.3 1832.34  5366.3 1832.34
#Mann=4,-1,0
  4689.5   0.035       0  4922.4    0.07       0  4951.0    0.05       0
  4955.0    0.07       0
Bank Sta=4951,4955
Exp/Cntr=0.3,0.1

Type RM Length L Ch R = 1,963,438,438,438
BEGIN DESCRIPTION:
Stream0508 2.0
END DESCRIPTION:
XS GIS Cut Line= 3
      1918829.34     13947342.58      1918875.00     13946975.00
      1918777.32     13946634.85
#Sta/Elev= 30
  4634.4 1769.90  4638.4 1769.08  4643.4 1770.01  4672.3 1766.66  4714.8 1757.73
  4742.8 1754.12  4763.0 1748.08  4853.7 1747.99  4873.8 1746.35  4894.0 1742.14
  4924.2 1738.40  4944.3 1733.90  4966.9 1733.78  4994.7 1735.43  5013.2 1733.38
  5013.5 1732.88  5017.2 1733.38  5046.4 1743.72  5060.6 1745.92  5067.2 1748.14
  5150.1 1758.12  5172.2 1760.16  5200.7 1764.87  5205.9 1764.71  5239.6 1771.47
  5244.8 1771.32  5312.2 1782.96  5317.4 1782.73  5344.1 1787.04  5358.7 1789.25
#Mann=6,-1,0
  4634.4   0.035       0  4714.8    0.07       0  5013.2    0.05       0
  5017.2    0.07       0  5150.1     0.1       0  5344.1    0.07       0
Bank Sta=5013.2,5017.2
Exp/Cntr=0.3,0.1

Type RM Length L Ch R = 1,525,259,259,259
BEGIN DESCRIPTION:
Stream0508 1.0
END DESCRIPTION:
XS GIS Cut Line= 3
      1919137.81     13947382.24      1919275.00     13947075.00
      1919272.75     13946738.99
#Sta/Elev= 30
  4663.5 1755.89  4672.9 1753.83  4696.1 1752.84  4759.0 1747.92  4789.0 1744.27
  4812.2 1740.54  4835.4 1738.58  4840.9 1736.74  4864.1 1734.37  4892.8 1731.94
  4923.3 1730.81  4939.2 1728.73  4945.1 1725.92  4956.2 1723.33  4962.4 1720.85
  4974.9 1718.37  4983.6 1717.63  4983.9 1717.13  4987.4 1717.13  4987.6 1717.63
  5020.0 1718.58  5030.0 1721.26  5047.5 1727.50  5060.0 1732.92  5070.0 1736.14
  5080.0 1737.91  5090.0 1738.83  5145.9 1739.39  5230.0 1740.04  5336.0 1742.55
#Mann=7,-1,0
  4663.5   0.035       0  4945.1    0.07       0  4974.9   0.035       0
  4983.6   0.035       0  4987.6   0.035       0  5047.5     0.1       0
  5145.9    0.07       0
Bank Sta=4983.6,4987.6
Exp/Cntr=0.3,0.1

Type RM Length L Ch R = 1,266,0,0,0
BEGIN DESCRIPTION:
Stream0508 0.0
END DESCRIPTION:
XS GIS Cut Line= 3
      1919354.14     13947367.12      1919531.85     13947194.59
      1919457.63     13946838.53
#Sta/Elev= 30
  4680.0 1735.78  4759.9 1733.53  4766.9 1734.09  4781.0 1733.87  4837.6 1731.12
  4844.8 1728.31  4851.8 1727.68  4859.0 1722.50  4865.9 1721.42  4873.1 1716.99
  4880.1 1716.53  4887.2 1713.13  4901.4 1711.13  4930.0 1710.26  4989.7 1711.05
  4998.8 1711.69  5007.0 1708.47  5007.2 1707.97  5010.7 1707.97  5011.0 1708.47
  5026.2 1711.15  5060.1 1714.69  5070.3 1717.07  5079.6 1720.37  5084.7 1720.45
  5090.7 1723.44  5121.4 1731.06  5141.8 1734.02  5151.6 1734.07  5291.4 1734.97
#Mann=5,-1,0
  4680.0    0.07       0  5007.0    0.05       0  5011.0    0.07       0
  5026.2     0.1       0  5151.6    0.07       0
Bank Sta=5007,5011
Exp/Cntr=0.3,0.1

Chan Stop Cuts=-1