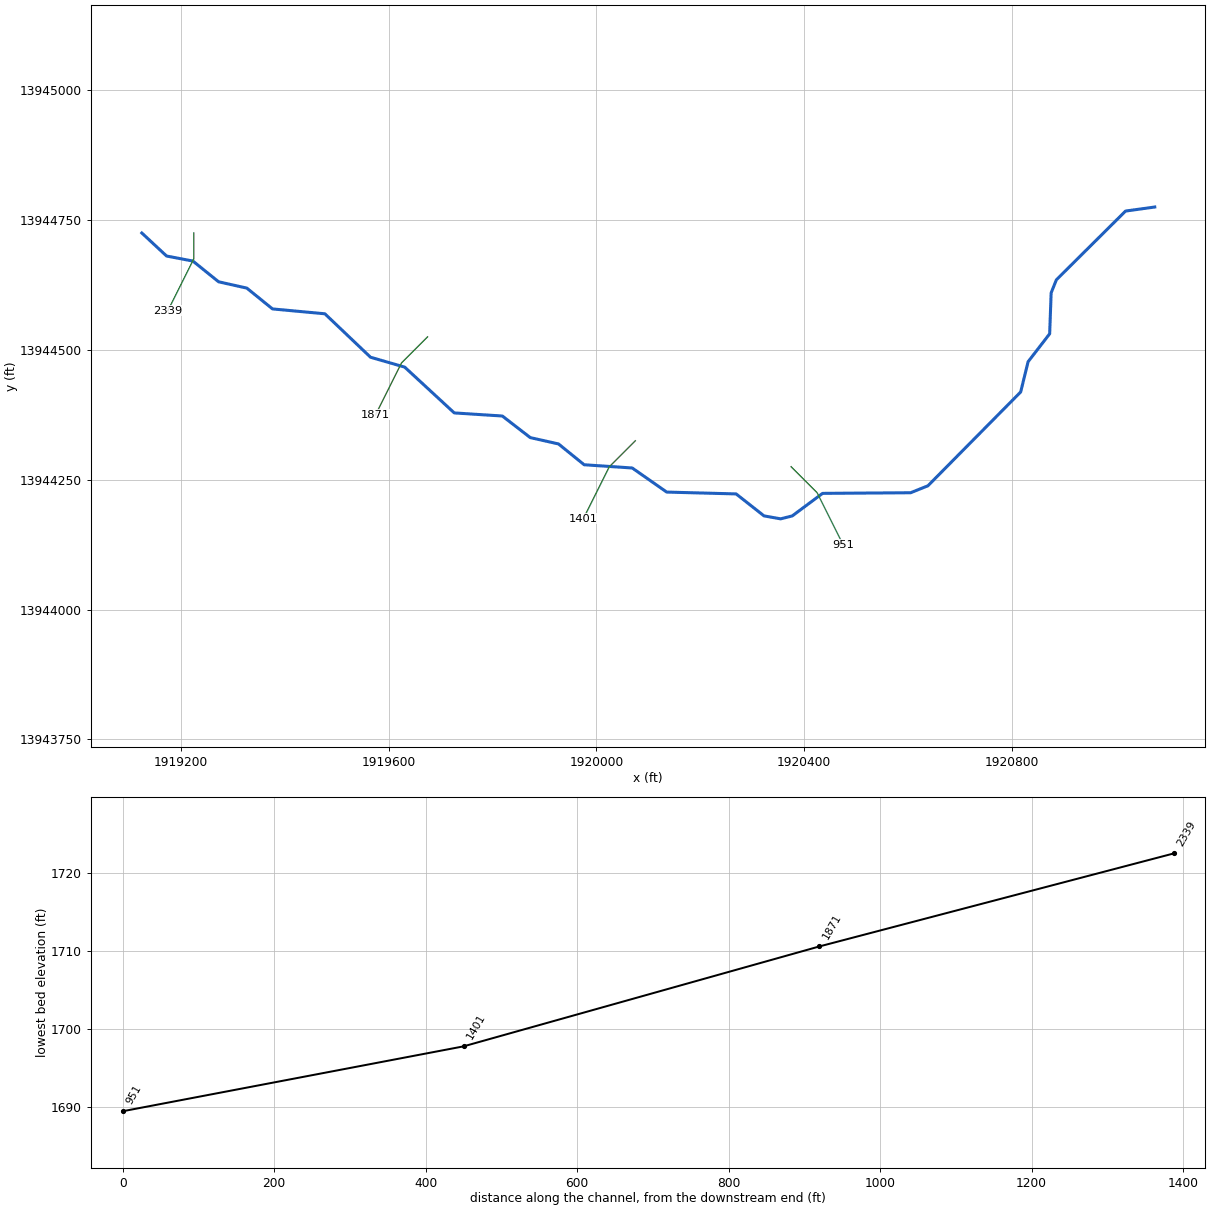
--- Stream0509.prj (project) ---

Proj Title=Stream0509 Base Level Engineering
Current Plan=p01
Default Exp/Contr=0.3,0.1
English Units
Geom File=g01
Flow File=f01
Plan File=p01
BEGIN DESCRIPTION:
Stream0509
END DESCRIPTION:

--- Stream0509.p01 (plan) ---

Plan Title=Multiple Run
Short Identifier=Multiple
Geom File=g01
Flow File=f01
Subcritical Flow
K Sum by GR= 0
Std Step Tol= 0.01
Critical Tol= 0.01
Num of Std Step Trials= 20
Max Error Tol= 0.3
Flow Tol Ratio= 0.001
Split Flow NTrial= 30
Split Flow Tol= 0.02
Split Flow Ratio= 0.02
Log Output Level= 0
Friction Slope Method= 1
Unsteady Friction Slope Method= 2
Unsteady Bridges Friction Slope Method= 1
Parabolic Critical Depth
Global Vel Dist=  1 , 1 , 1
Global Log Level= 0
CheckData=True
Encroach Param= -1, 0, 0, 0
BEGIN DESCRIPTION:
Multiple Run
END DESCRIPTION:

--- Stream0509.f01 (steady flow) ---

Flow Title=Multiple
Number of Profiles=7
Profile Names=10-year,25-year,50-year,1pct_min,100-year,1pct_plu,500-year
River Rch & RM= Stream0509,Reach-1,2339
     403     644     861     559    1116    2226    1843
Boundary for River Rch & Prof#=Stream0509,Reach-1,1
Up Type=0
Dn Type=3
Dn Slope=0.005
Boundary for River Rch & Prof#=Stream0509,Reach-1,2
Up Type=0
Dn Type=3
Dn Slope=0.005
Boundary for River Rch & Prof#=Stream0509,Reach-1,3
Up Type=0
Dn Type=3
Dn Slope=0.005
Boundary for River Rch & Prof#=Stream0509,Reach-1,4
Up Type=0
Dn Type=3
Dn Slope=0.005
Boundary for River Rch & Prof#=Stream0509,Reach-1,5
Up Type=0
Dn Type=3
Dn Slope=0.005
Boundary for River Rch & Prof#=Stream0509,Reach-1,6
Up Type=0
Dn Type=3
Dn Slope=0.005
Boundary for River Rch & Prof#=Stream0509,Reach-1,7
Up Type=0
Dn Type=3
Dn Slope=0.005

--- Stream0509.g01 (geometry) ---

Geom Title=Existing Conditions

River Reach=Stream0509,Reach-1
Reach XY= 30
      1919125.00     13944725.00      1919172.64     13944680.67
      1919223.33     13944670.96      1919272.80     13944631.07
      1919327.18     13944618.89      1919376.59     13944578.83
      1919477.42     13944569.46      1919565.33     13944485.80
      1919631.04     13944466.82      1919726.50     13944378.62
      1919819.03     13944372.67      1919872.82     13944331.11
      1919927.18     13944318.89      1919976.58     13944278.83
      1920069.02     13944272.64      1920135.51     13944226.23
      1920269.07     13944222.70      1920322.82     13944180.38
      1920354.82     13944174.72      1920377.18     13944180.38
      1920435.50     13944223.76      1920605.02     13944224.96
      1920638.32     13944238.37      1920816.86     13944418.94
      1920831.14     13944477.17      1920872.67     13944530.97
      1920875.52     13944609.78      1920885.52     13944634.79
      1921018.79     13944767.24      1921075.00     13944775.00

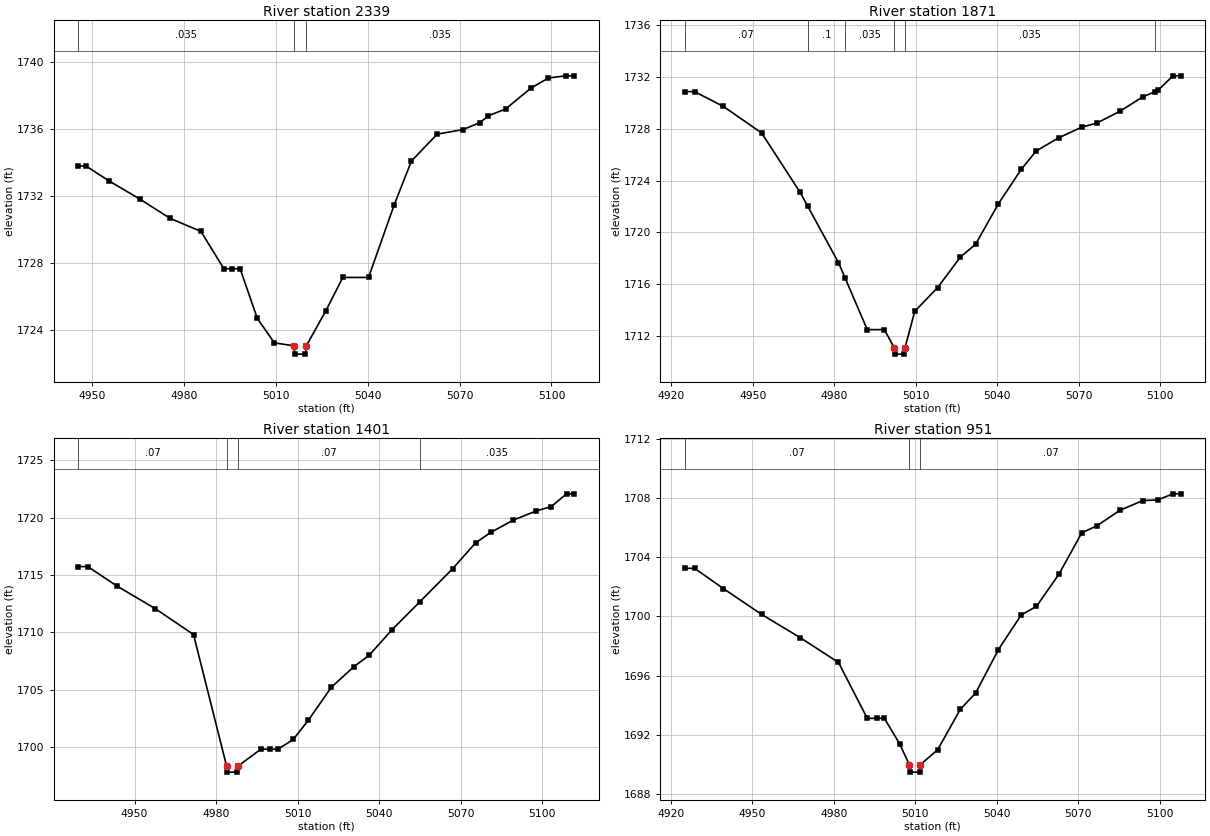
Type RM Length L Ch R = 1,2339,468,468,468
BEGIN DESCRIPTION:
Stream0509 4.0
END DESCRIPTION:
XS GIS Cut Line= 3
      1919225.00     13944724.99      1919225.00     13944675.00
      1919175.00     13944575.00
#Sta/Elev= 29
  4945.6 1733.80  4948.1 1733.80  4955.6 1732.91  4965.6 1731.83  4975.6 1730.66
  4985.6 1729.89  4993.1 1727.65  4995.6 1727.65  4998.4 1727.65  5004.0 1724.68
  5009.6 1723.21  5016.0 1723.04  5016.2 1722.54  5019.7 1722.54  5020.0 1723.04
  5026.3 1725.11  5031.9 1727.13  5040.3 1727.13  5048.7 1731.49  5054.3 1734.10
  5062.7 1735.71  5071.1 1735.98  5076.7 1736.40  5079.4 1736.81  5085.0 1737.21
  5093.4 1738.48  5099.0 1739.07  5104.6 1739.20  5107.4 1739.20
#Mann=3,-1,0
  4945.6   0.035       0  5016.0   0.035       0  5020.0   0.035       0
Bank Sta=5016,5020
Exp/Cntr=0.3,0.1

Type RM Length L Ch R = 1,1871,470,470,470
BEGIN DESCRIPTION:
Stream0509 3.0
END DESCRIPTION:
XS GIS Cut Line= 3
      1919675.03     13944525.03      1919625.00     13944475.00
      1919574.98     13944374.96
#Sta/Elev= 30
  4924.9 1730.86  4928.5 1730.86  4939.1 1729.72  4953.2 1727.67  4967.4 1723.08
  4970.2 1722.01  4981.5 1717.67  4984.0 1716.45  4992.1 1712.50  4998.4 1712.50
  5002.0 1711.11  5002.3 1710.61  5005.8 1710.61  5006.0 1711.11  5009.6 1713.92
  5018.0 1715.74  5026.4 1718.10  5032.0 1719.09  5040.4 1722.21  5048.8 1724.86
  5054.3 1726.28  5062.7 1727.31  5071.1 1728.12  5076.7 1728.44  5085.1 1729.34
  5093.5 1730.45  5097.9 1730.84  5099.1 1730.95  5104.7 1732.08  5107.5 1732.08
#Mann=6,-1,0
  4924.9    0.07       0  4970.2     0.1       0  4984.0   0.035       0
  5002.0   0.035       0  5006.0   0.035       0  5097.9   0.063       0
Bank Sta=5002,5006
Exp/Cntr=0.3,0.1

Type RM Length L Ch R = 1,1401,450,450,450
BEGIN DESCRIPTION:
Stream0509 2.0
END DESCRIPTION:
XS GIS Cut Line= 3
      1920074.99     13944324.99      1920025.00     13944275.00
      1919975.00     13944175.00
#Sta/Elev= 27
  4929.3 1715.73  4932.8 1715.73  4943.4 1714.05  4957.6 1712.06  4971.7 1709.80
  4983.9 1698.29  4984.1 1697.79  4987.6 1697.79  4987.9 1698.29  4996.5 1699.79
  5000.0 1699.79  5002.8 1699.79  5008.4 1700.64  5014.0 1702.33  5022.4 1705.19
  5030.7 1706.99  5036.3 1707.98  5044.7 1710.20  5055.1 1712.68  5067.1 1715.55
  5075.5 1717.80  5081.1 1718.71  5089.4 1719.79  5097.8 1720.58  5103.4 1720.97
  5109.0 1722.08  5111.8 1722.08
#Mann=4,-1,0
  4929.3    0.07       0  4983.9    0.05       0  4987.9    0.07       0
  5055.1   0.035       0
Bank Sta=4983.9,4987.9
Exp/Cntr=0.3,0.1

Type RM Length L Ch R = 1,951,0,0,0
BEGIN DESCRIPTION:
Stream0509 1.0
END DESCRIPTION:
XS GIS Cut Line= 3
      1920374.97     13944275.03      1920425.00     13944225.00
      1920475.02     13944124.96
#Sta/Elev= 28
  4925.1 1703.26  4928.7 1703.26  4939.3 1701.89  4953.4 1700.14  4967.6 1698.57
  4981.7 1696.89  4992.3 1693.11  4995.9 1693.11  4998.6 1693.11  5004.2 1691.39
  5007.8 1689.97  5008.1 1689.47  5011.6 1689.47  5011.8 1689.97  5018.2 1690.98
  5026.6 1693.73  5032.2 1694.82  5040.6 1697.76  5049.0 1700.11  5054.6 1700.68
  5062.9 1702.87  5071.3 1705.66  5076.9 1706.14  5085.3 1707.18  5093.7 1707.84
  5099.3 1707.89  5104.9 1708.30  5107.7 1708.30
#Mann=3,-1,0
  4925.1    0.07       0  5007.8    0.05       0  5011.8    0.07       0
Bank Sta=5007.8,5011.8
Exp/Cntr=0.3,0.1

Chan Stop Cuts=-1