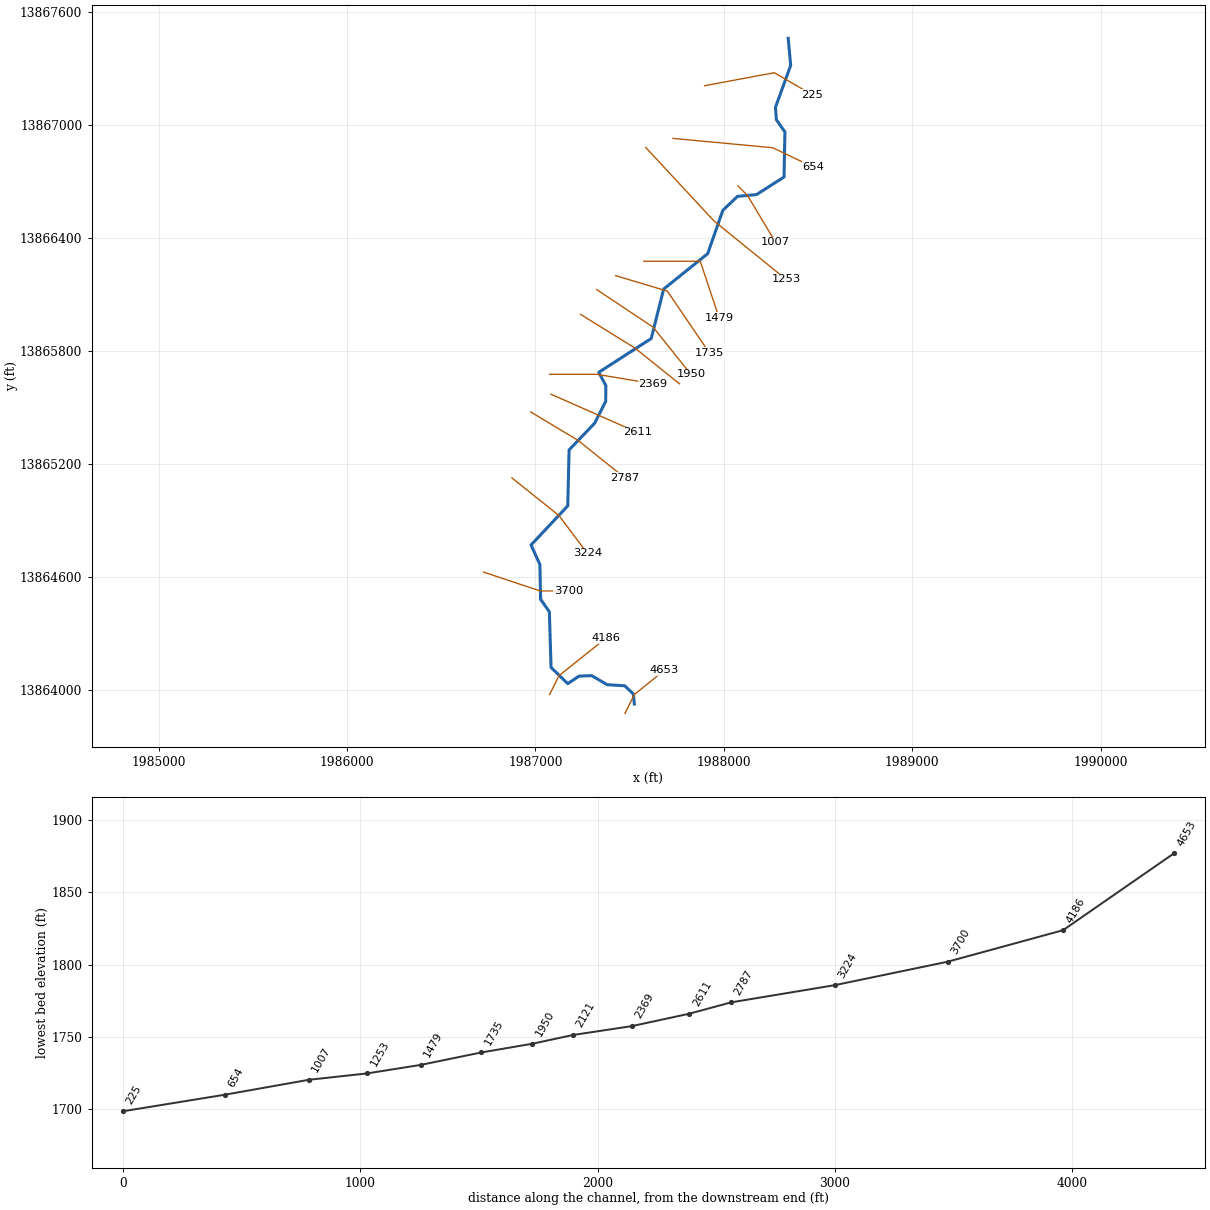
--- Stream0510.prj (project) ---

Proj Title=Stream0510 Base Level Engineering
Current Plan=p01
Default Exp/Contr=0.3,0.1
English Units
Geom File=g01
Flow File=f01
Plan File=p01
Y Axis Title=Elevation
X Axis Title(PF)=Main Channel Distance
X Axis Title(XS)=Station
BEGIN DESCRIPTION:
Stream0510
END DESCRIPTION:
DSS Export Rating Curves= 0
DSS Export Rating Curve Sorted= 0
DSS Export Volume Flow Curves= 0
DXF OffsetX= 0
DXF OffsetY= 0
DXF ScaleX= 1
DXF ScaleY= 10

--- Stream0510.p01 (plan) ---

Plan Title=Multiple Run
Short Identifier=Multiple
Geom File=g01
Flow File=f01
Subcritical Flow
K Sum by GR= 0
Std Step Tol= 0.01
Critical Tol= 0.01
Num of Std Step Trials= 20
Max Error Tol= 0.3
Flow Tol Ratio= 0.001
Split Flow NTrial= 30
Split Flow Tol= 0.02
Split Flow Ratio= 0.02
Log Output Level= 0
Friction Slope Method= 1
Unsteady Friction Slope Method= 2
Unsteady Bridges Friction Slope Method= 1
Parabolic Critical Depth
Global Vel Dist=  1 , 1 , 1
Global Log Level= 0
CheckData=True
Encroach Param= -1, 0, 0, 0
BEGIN DESCRIPTION:
Multiple Run
END DESCRIPTION:

--- Stream0510.f01 (steady flow) ---

Flow Title=Multiple
Program Version=4.10
Number of Profiles= 7
Profile Names=10-year,25-year,50-year,1pct_min,100-year,1pct_plu,500-year
River Rch & RM=Stream0510,Reach-1         ,4653
     569     938    1282     853    1701    3395    2957
Boundary for River Rch & Prof#=Stream0510,Reach-1         , 1
Up Type= 0
Dn Type= 3
Dn Slope=0.01
Boundary for River Rch & Prof#=Stream0510,Reach-1         , 2
Up Type= 0
Dn Type= 3
Dn Slope=0.01
Boundary for River Rch & Prof#=Stream0510,Reach-1         , 3
Up Type= 0
Dn Type= 3
Dn Slope=0.01
Boundary for River Rch & Prof#=Stream0510,Reach-1         , 4
Up Type= 0
Dn Type= 3
Dn Slope=0.01
Boundary for River Rch & Prof#=Stream0510,Reach-1         , 5
Up Type= 0
Dn Type= 3
Dn Slope=0.01
Boundary for River Rch & Prof#=Stream0510,Reach-1         , 6
Up Type= 0
Dn Type= 3
Dn Slope=0.01
Boundary for River Rch & Prof#=Stream0510,Reach-1         , 7
Up Type= 0
Dn Type= 3
Dn Slope=0.01
DSS Import GetInterval= 0
DSS Import GetPeak= 0
DSS Import FillOption= 0

--- Stream0510.g01 (geometry) ---

Geom Title=Existing Conditions
Program Version=4.10

River Reach=Stream0510      ,Reach-1
Reach XY= 30
        1987525.       13863925.      1987519.87     13863977.94
       1987473.7     13864021.54      1987380.98     13864027.36
      1987297.75     13864075.49      1987230.89     13864072.63
      1987171.57     13864032.79      1987082.81     13864118.77
      1987073.78      13864414.5      1987027.38     13864480.53
       1987023.6     13864665.35      1986976.62     13864768.97
      1987171.46     13864976.46      1987178.54     13865273.54
      1987314.24     13865415.32      1987372.85     13865530.97
      1987373.55     13865615.37      1987335.97     13865685.38
      1987614.61      13865864.9      1987680.52     13866127.44
      1987914.25     13866315.29      1987994.61      13866545.2
      1988072.56     13866619.48      1988173.42     13866628.83
      1988319.64      13866722.3      1988324.31     13866961.08
       1988278.7      13867026.6      1988274.36     13867093.24
      1988354.89     13867314.53      1988341.61     13867458.39

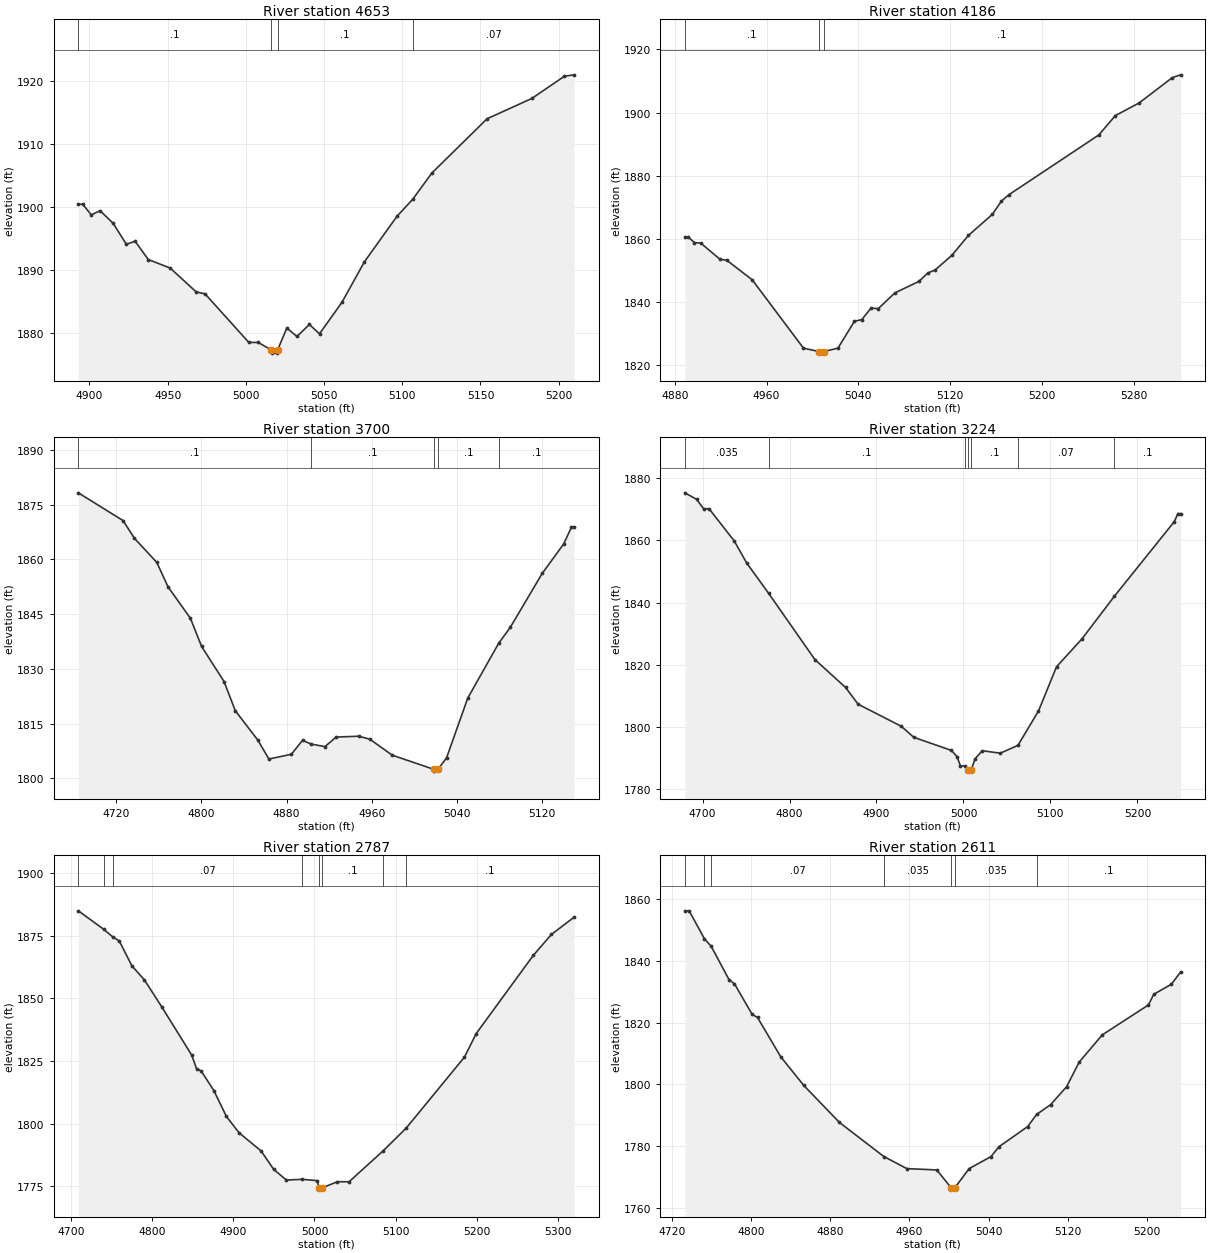
Type RM Length L Ch R = 1 ,4653    ,467,467,467
BEGIN DESCRIPTION:
Stream0510 10.0
END DESCRIPTION:
XS GIS Cut Line= 3
      1987475.02     13863875.04        1987525.       13863975.
      1987684.62     13864104.01
#Sta/Elev= 30
  4892.9 1900.45  4895.7 1900.45  4901.2 1898.76  4906.8 1899.43  4915.2 1897.41
  4923.6 1894.08  4929.2 1894.57  4937.6 1891.66  4951.6  1890.3  4968.3 1886.49
  4973.9  1886.2  5001.9 1878.46  5007.9 1878.46  5016.3 1877.26  5016.5 1876.76
    5020 1876.76  5020.3 1877.26  5026.2 1880.75  5032.7 1879.41  5040.6 1881.32
  5047.1 1879.84  5061.4 1884.83  5075.8 1891.29  5096.6 1898.53  5106.7 1901.25
    5119 1905.44  5154.2 1914.05  5182.9  1917.3  5203.7 1920.83  5209.9 1921.05
#Mann= 4 ,-1 , 0
  4892.9      .1       0  5016.3     .05       0  5020.3      .1       0
  5106.7     .07       0
Bank Sta=5016.3,5020.3
XS Rating Curve= 0 ,0
Exp/Cntr=0.3,0.1

Type RM Length L Ch R = 1 ,4186    ,486,486,486
BEGIN DESCRIPTION:
Stream0510 9.0
END DESCRIPTION:
XS GIS Cut Line= 3
      1987074.99     13863974.99        1987125.       13864075.
      1987375.02     13864275.02
#Sta/Elev= 30
  4888.8 1860.58  4891.6 1860.58  4897.2 1858.78  4902.8 1858.58  4919.6 1853.43
  4925.2 1853.21  4947.5 1846.98  4992.2 1825.29  5005.8 1824.22  5006.1 1823.72
  5009.8 1824.22  5022.2 1825.29  5036.6 1833.82    5043 1834.34    5051 1837.97
  5057.4 1837.85  5071.9 1842.83  5092.7 1846.44  5100.7 1849.15  5107.1 1850.13
  5121.5 1854.74  5135.9 1861.04  5156.7 1867.69  5164.7 1871.92  5171.1 1873.92
  5249.5 1892.88  5263.9 1899.01  5284.8 1903.07  5313.6 1911.08  5320.8 1911.95
#Mann= 3 ,-1 , 0
  4888.8      .1       0  5005.8     .05       0  5009.8      .1       0
Bank Sta=5005.8,5009.8
XS Rating Curve= 0 ,0
Exp/Cntr=0.3,0.1

Type RM Length L Ch R = 1 ,3700    ,476,476,476
BEGIN DESCRIPTION:
Stream0510 8.0
END DESCRIPTION:
XS GIS Cut Line= 3
      1986725.01       13864625.        1987025.       13864525.
      1987174.99       13864525.
#Sta/Elev= 30
  4684.2 1878.26  4726.3 1870.64  4736.9 1865.81    4758 1859.18  4768.5  1852.5
  4789.6 1843.86  4800.1 1836.14  4821.2 1826.53  4831.8 1818.51  4852.8 1810.53
  4863.4 1805.28  4884.5 1806.58    4895  1810.4  4903.3 1809.37  4916.1 1808.68
  4926.6  1811.3  4947.7 1811.53  4958.2 1810.73  4979.3 1806.34  5018.4 1802.46
  5018.7 1801.96  5022.4 1802.46  5030.4 1805.58  5050.4 1822.01  5079.4 1836.99
  5090.4  1841.4  5120.4 1856.18  5140.4 1864.18  5147.9 1868.84  5150.4 1868.84
#Mann= 5 ,-1 , 0
  4684.2      .1       0  4903.3      .1       0  5018.4     .05       0
  5022.4      .1       0  5079.4      .1       0
Bank Sta=5018.4,5022.4
XS Rating Curve= 0 ,0
Exp/Cntr=0.3,0.1

Type RM Length L Ch R = 1 ,3224    ,437,437,437
BEGIN DESCRIPTION:
Stream0510 7.0
END DESCRIPTION:
XS GIS Cut Line= 3
      1986875.03     13865124.97        1987125.       13864925.
      1987274.99     13864725.01
#Sta/Elev= 30
  4679.6  1875.3  4693.2 1873.22  4701.2 1870.17  4707.6 1870.16  4736.4 1859.83
  4750.8 1852.71    4776 1842.96  4829.2 1821.65  4864.4  1812.7  4878.9 1807.29
  4928.5 1800.19  4942.9 1796.64  4986.1 1792.43  4992.5 1790.46  4996.5 1787.44
  5002.2 1787.44    5005 1786.26  5005.3 1785.76    5009 1786.26  5013.3 1789.68
  5021.6 1792.33  5042.4 1791.53  5062.7 1794.07  5086.2 1805.07    5107 1819.33
  5136.2 1828.29  5173.6 1842.05  5242.4 1866.03  5246.6 1868.61  5249.7 1868.61
#Mann= 7 ,-1 , 0
  4679.6    .035       0    4776      .1       0  5002.2      .1       0
    5005     .05       0    5009      .1       0  5062.7     .07       0
  5173.6      .1       0
Bank Sta=5005,5009
XS Rating Curve= 0 ,0
Exp/Cntr=0.3,0.1

Type RM Length L Ch R = 1 ,2787    ,176,176,176
BEGIN DESCRIPTION:
Stream0510 6.0
END DESCRIPTION:
XS GIS Cut Line= 3
      1986974.99       13865475.        1987225.       13865325.
      1987474.99     13865125.01
#Sta/Elev= 30
  4708.7 1884.88  4740.3 1877.45    4751 1874.51  4759.2 1872.88  4774.8 1862.93
  4790.3 1857.29  4811.7 1846.52  4848.6 1827.32  4854.5 1821.95  4860.3 1820.98
  4875.9 1813.19  4891.4 1802.85    4907 1796.34  4934.2 1789.09  4949.7 1781.76
  4965.3 1777.51  4985.2 1777.78  5003.5 1777.24  5005.5 1774.37  5005.7 1773.87
  5009.5 1774.37  5028.3 1776.83  5042.7 1776.81  5084.8 1789.16  5113.1 1798.18
  5185.1 1826.55  5199.6 1835.94    5270 1867.13  5292.4 1875.47  5320.4 1882.35
#Mann= 8 ,-1 , 0
  4708.7     .07       0  4740.3    .035       0    4751     .07       0
  4985.2      .1       0  5005.5     .05       0  5009.5      .1       0
  5084.8    .035       0  5113.1      .1       0
Bank Sta=5005.5,5009.5
XS Rating Curve= 0 ,0
Exp/Cntr=0.3,0.1

Type RM Length L Ch R = 1 ,2611    ,242,242,242
BEGIN DESCRIPTION:
Mapping XS cb91b1df
END DESCRIPTION:
XS GIS Cut Line= 2
      1987082.03     13865569.39      1987540.38      13865367.1
#Sta/Elev= 30
    4733 1856.26  4737.4 1856.26  4752.9 1847.16  4759.7 1844.74  4777.8 1833.89
  4783.2 1832.61  4801.1 1822.67  4806.5 1821.68  4829.9 1808.96  4853.2 1799.67
  4889.3 1787.64  4934.2 1776.59  4957.4 1772.69  4987.6 1772.26    5002 1766.54
  5002.2 1766.04    5006 1766.54  5020.4 1772.71  5042.3 1776.57  5050.6 1779.82
  5079.4 1786.31  5088.5 1790.24  5102.7 1793.45  5118.8 1799.25  5131.5 1807.22
  5154.8 1816.04  5201.4 1825.73  5206.9 1829.21  5224.7 1832.47    5234 1836.44
#Mann= 7 ,-1 , 0
    4733     .07       0  4752.9    .035       0  4759.7     .07       0
  4934.2    .035       0    5002    .035       0    5006    .035       0
  5088.5      .1       0
#XS Ineff= 2 , 0
         4983.75  1772.2
Permanent Ineff=
       F       F
Bank Sta=5002,5006
XS Rating Curve= 0 ,0
Exp/Cntr=0.3,0.1

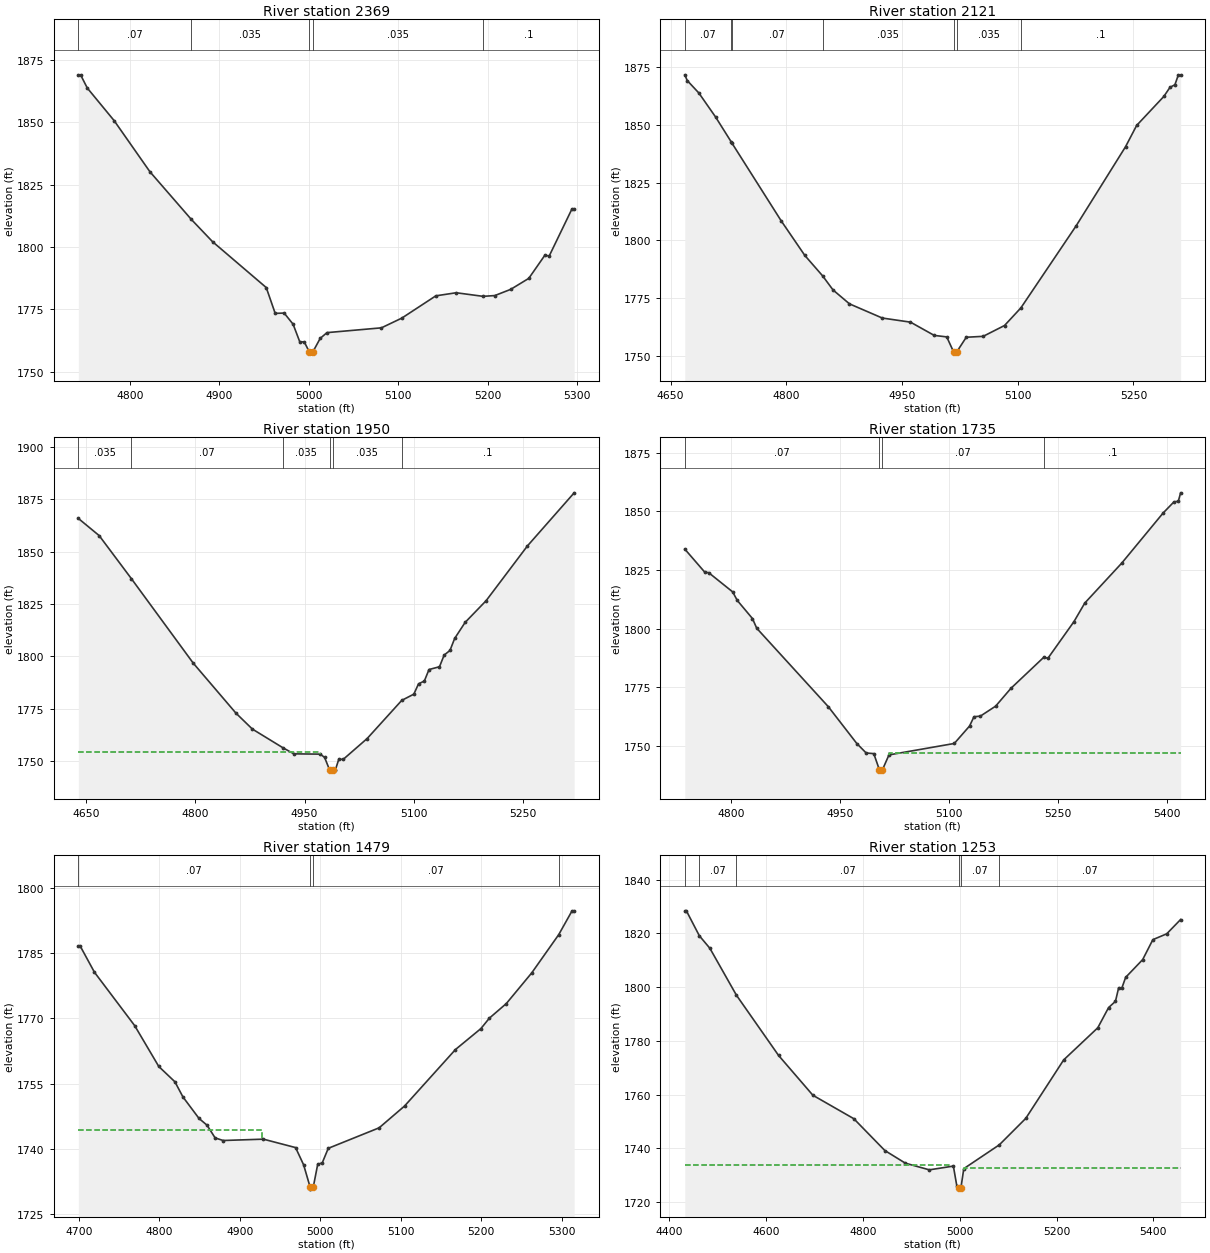
Type RM Length L Ch R = 1 ,2369    ,248,248,248
BEGIN DESCRIPTION:
Stream0510 5.0
END DESCRIPTION:
XS GIS Cut Line= 3
        1987075.       13865675.        1987325.       13865675.
      1987624.96     13865625.01
#Sta/Elev= 30
  4742.4 1869.06  4744.9 1869.06  4752.4 1863.77  4782.4  1850.7  4822.4  1830.2
  4868.7 1811.07  4892.4 1802.15  4952.4 1783.76  4962.4 1773.41  4972.4 1773.54
  4982.4 1769.07  4989.9 1761.98  4994.9 1761.98  5000.5 1757.97  5000.8 1757.47
  5004.5 1757.97  5012.7 1763.39  5020.3 1765.69  5081.1 1767.61  5103.9 1771.51
  5141.9 1780.44  5164.7 1781.68  5194.7 1780.24  5207.8 1780.55  5225.6 1783.04
  5245.8 1787.45  5263.6 1796.63  5268.7 1796.48    5294 1815.26  5296.5 1815.26
#Mann= 5 ,-1 , 0
  4742.4     .07       0  4868.7    .035       0  5000.5    .035       0
  5004.5    .035       0  5194.7      .1       0
#XS Ineff= 2 , 0
                         5020.52         1765.61
Permanent Ineff=
       F       F
Bank Sta=5000.5,5004.5
XS Rating Curve= 0 ,0
Exp/Cntr=0.3,0.1

Type RM Length L Ch R = 1 ,2121    ,171,171,171
BEGIN DESCRIPTION:
Mapping XS 49ad0037
END DESCRIPTION:
XS GIS Cut Line= 3
      1987239.55     13865993.12      1987528.17     13865814.17
      1987764.81     13865624.61
#Sta/Elev= 30
  4668.3 1871.55  4671.5 1869.07  4686.5 1863.71  4708.2 1853.34  4728.7 1842.47
  4729.4 1842.07  4793.2 1808.51  4823.9 1793.54  4846.9 1784.74  4860.5 1778.62
  4881.8 1772.62  4924.3  1766.5  4960.9 1764.72  4991.7 1758.99  5007.9 1758.35
  5016.8 1751.84  5017.1 1751.34  5020.8 1751.84  5033.2  1758.2  5055.1 1758.59
  5082.8 1763.27    5104 1770.88  5175.7 1806.35  5239.7  1840.5  5254.1 1849.69
  5289.3  1862.2  5297.3 1866.14  5303.7 1867.27    5308 1871.37  5311.1 1871.37
#Mann= 7 ,-1 , 0
  4668.3     .07       0  4728.7    .035       0  4729.4     .07       0
  4846.9    .035       0  5016.8    .035       0  5020.8    .035       0
    5104      .1       0
#XS Ineff= 2 , 0
                         5033.25         1758.15
Permanent Ineff=
       F       F
Bank Sta=5016.8,5020.8
XS Rating Curve= 0 ,0
Exp/Cntr=0.3,0.1

Type RM Length L Ch R = 1 ,1950    ,215,215,215
BEGIN DESCRIPTION:
Stream0510 4.0
END DESCRIPTION:
XS GIS Cut Line= 3
      1987324.96     13866125.03        1987625.       13865925.
      1987825.02     13865674.97
#Sta/Elev= 30
  4639.3 1865.87  4667.9 1857.68  4712.1 1837.15  4797.1 1796.82  4855.7 1772.98
  4878.2 1765.39    4920  1756.5  4935.3 1753.55  4971.4 1753.42  4977.4 1751.88
  4984.4 1745.81  4984.6 1745.31  4988.4 1745.81  4992.4 1746.07  4996.9 1750.95
  5003.1 1750.95  5035.9 1760.87  5083.4 1779.07    5100 1782.04  5106.4 1786.96
  5114.4 1788.29  5120.8 1793.78  5135.2 1795.11  5141.6 1800.67  5149.6 1802.89
    5156 1808.59  5170.4 1816.27  5199.2 1826.61    5256 1852.77  5320.1 1878.08
#Mann= 6 ,-1 , 0
  4639.3    .035       0  4712.1     .07       0    4920    .035       0
  4984.4    .035       0  4988.4    .035       0  5083.4      .1       0
#XS Ineff= 2 , 0
         4971.05 1754.27
Permanent Ineff=
       F       F
Bank Sta=4984.4,4988.4
XS Rating Curve= 0 ,0
Exp/Cntr=0.3,0.1

Type RM Length L Ch R = 1 ,1735    ,256,256,256
BEGIN DESCRIPTION:
Mapping XS a599fc12
END DESCRIPTION:
XS GIS Cut Line= 3
      1987425.79     13866198.55      1987700.11     13866116.62
      1987922.97     13865789.15
#Sta/Elev= 30
  4736.3 1833.91  4763.9 1824.03  4769.1 1823.88  4802.2 1815.67  4808.5 1812.04
  4829.4 1804.32  4835.3 1800.18  4933.8 1766.76  4973.1 1751.04  4985.9 1747.03
  4996.4 1746.74  5004.2 1739.79  5004.4 1739.29  5008.2 1739.79  5017.3  1746.2
  5107.2 1751.08  5128.2  1758.5  5134.3 1762.47  5143.1 1762.73  5164.1 1766.98
  5185.1 1774.56  5230.5 1787.85    5236 1787.36  5271.9    1803  5286.8 1810.92
  5337.7 1827.95  5394.6 1849.29  5409.5 1854.03  5415.5 1854.29  5418.7 1857.89
#Mann= 4 ,-1 , 0
  4736.3     .07       0  5004.2     .05       0  5008.2     .07       0
  5230.5      .1       0
#XS Ineff= 2 , 0
                         5017.37         1746.87
Permanent Ineff=
       F       F
Bank Sta=5004.2,5008.2
XS Rating Curve= 0 ,0
Exp/Cntr=0.3,0.1

Type RM Length L Ch R = 1 ,1479    ,226,226,226
BEGIN DESCRIPTION:
Stream0510 3.0
END DESCRIPTION:
XS GIS Cut Line= 3
      1987574.99       13866275.        1987875.       13866275.
      1987974.99     13865975.04
#Sta/Elev= 30
  4699.5  1786.6    4702  1786.6  4719.5 1780.64  4769.5 1768.34  4799.5 1758.92
  4819.5  1755.4  4829.5 1751.91  4849.5 1746.95  4859.5 1745.39  4869.5 1742.47
  4879.5 1741.87  4929.5 1742.18  4969.5 1740.24  4979.5 1736.26  4987.5 1731.17
  4987.8 1730.67  4991.5 1731.17    4997  1736.4  5002.6 1736.71  5010.1 1740.07
  5073.3 1744.79  5104.9 1749.81  5168.2 1762.83  5199.8 1767.65  5210.3 1770.05
  5231.4 1773.42    5263 1780.49  5296.5 1789.29  5313.1 1794.78  5315.7 1794.78
#Mann= 4 ,-1 , 0
  4699.5     .07       0  4987.5     .05       0  4991.5     .07       0
  5296.5      .1       0
#XS Ineff= 2 , 0
         4927.35 1744.27
Permanent Ineff=
       F       F
Bank Sta=4987.5,4991.5
XS Rating Curve= 0 ,0
Exp/Cntr=0.3,0.1

Type RM Length L Ch R = 1 ,1253    ,246,246,246
BEGIN DESCRIPTION:
Mapping XS f6068911
END DESCRIPTION:
XS GIS Cut Line= 3
      1987585.57     13866878.86      1987947.99     13866488.77
      1988329.49     13866179.62
#Sta/Elev= 30
  4432.7  1828.4    4436  1828.4  4462.7 1819.12  4484.5 1814.45  4539.2 1797.01
  4626.2 1774.58  4697.1 1759.74  4781.6 1751.01  4845.6 1739.17  4888.1 1734.44
  4937.5 1731.97  4987.1 1733.37  4994.2 1726.01  4998.7 1725.29  4998.9 1724.79
  5002.7 1725.29  5008.6 1732.41    5082 1741.29  5136.5 1751.12  5214.8  1772.9
  5285.2 1784.86  5307.5 1792.38  5321.7 1794.71  5328.3 1799.78  5334.8 1799.62
  5342.7 1803.62  5377.9 1810.25  5398.9 1817.67  5427.5 1819.84  5456.2 1825.17
#Mann= 6 ,-1 , 0
  4432.7    .035       0  4462.7     .07       0  4539.2     .07       0
  4998.7     .05       0  5002.7     .07       0    5082     .07       0
#XS Ineff= 2 , 0
         4978.43 1733.65 5008.21         1732.59
Permanent Ineff=
       F       F
Bank Sta=4998.7,5002.7
XS Rating Curve= 0 ,0
Exp/Cntr=0.3,0.1

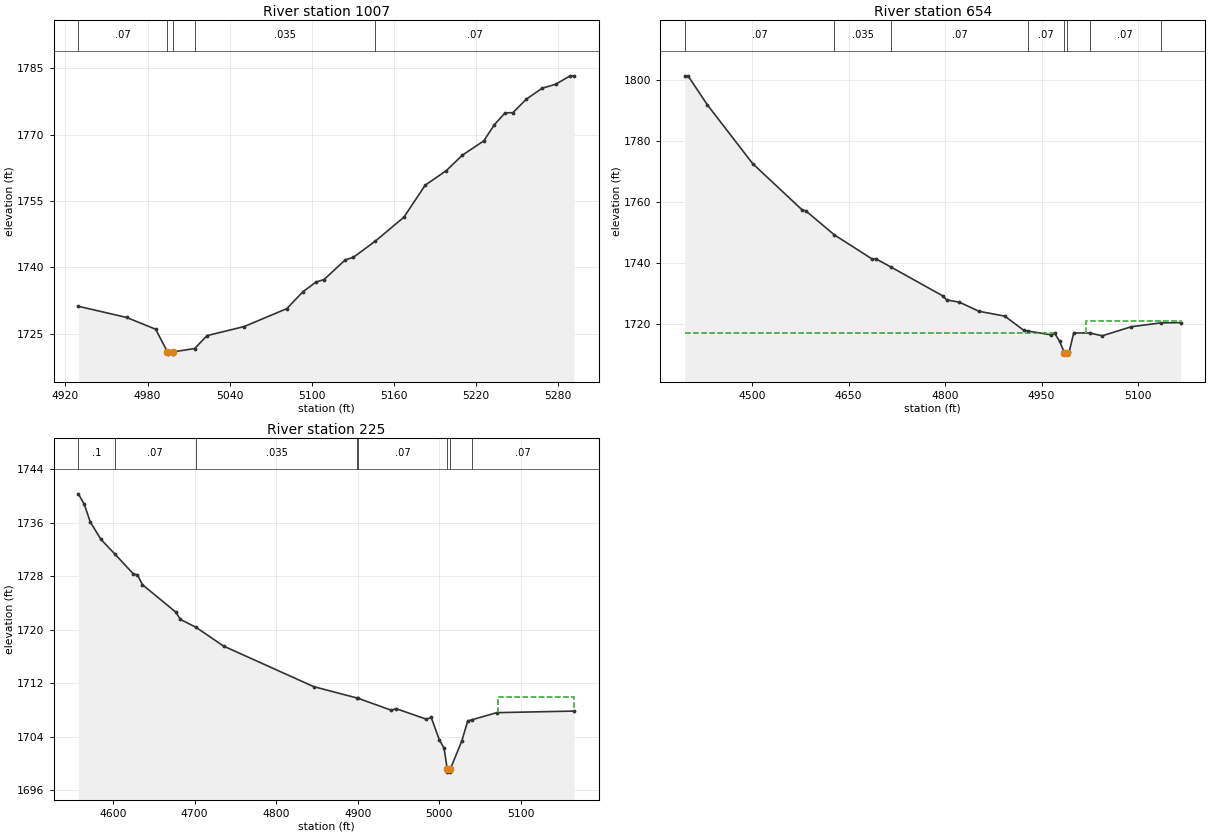
Type RM Length L Ch R = 1 ,1007    ,353,353,353
BEGIN DESCRIPTION:
Stream0510 2.0
END DESCRIPTION:
XS GIS Cut Line= 3
      1988075.03     13866674.97        1988125.       13866625.
      1988274.99     13866375.01
#Sta/Elev= 30
  4929.4  1731.2  4964.7 1728.67  4985.9 1726.01  4994.5 1720.88  4994.8 1720.38
  4998.3 1720.38  4998.5 1720.88  5014.4 1721.65  5023.4 1724.56  5050.6 1726.62
  5081.7 1730.67  5093.4 1734.47  5103.1 1736.68  5108.9 1737.25  5124.5 1741.72
  5130.3 1742.26  5146.4 1745.94  5167.2 1751.33  5182.8 1758.58  5198.3 1761.89
    5210 1765.38  5225.5 1768.57  5233.3 1772.24  5241.1 1774.92  5246.9 1774.98
  5256.6 1778.01  5268.3 1780.51    5278 1781.38  5288.7  1783.3  5291.6  1783.3
#Mann= 5 ,-1 , 0
  4929.4     .07       0  4994.5     .05       0  4998.5     .07       0
  5014.4    .035       0  5146.4     .07       0
Bank Sta=4994.5,4998.5
XS Rating Curve= 0 ,0
Exp/Cntr=0.3,0.1

Type RM Length L Ch R = 1 ,654     ,429,429,429
BEGIN DESCRIPTION:
Stream0510 1.0
END DESCRIPTION:
XS GIS Cut Line= 3
      1987730.06     13866927.21      1988259.07     13866877.69
      1988474.97     13866775.01
#Sta/Elev= 30
  4395.6 1801.43  4400.6 1801.43  4430.7  1791.9    4501 1772.63  4578.3 1757.35
  4583.3 1757.17  4628.2  1749.2  4687.2 1741.24  4692.2 1741.41  4715.4 1738.74
  4796.1 1729.25  4802.3  1727.9  4822.4 1727.13  4852.5 1724.16  4892.7 1722.57
  4922.4 1717.89    4929 1717.66  4964.6 1716.43  4970.2 1716.95  4977.8 1714.35
  4985.4 1710.59  4985.6 1710.09  4989.4 1710.59  4992.9  1710.9  4999.9 1717.03
  5024.6 1717.04  5044.2 1716.11  5089.3 1719.08  5135.4 1720.34    5166 1720.42
#Mann= 8 ,-1 , 0
  4395.6     .07       0  4628.2    .035       0  4715.4     .07       0
    4929     .07       0  4985.4     .05       0  4989.4     .07       0
  5024.6     .07       0  5135.4      .1       0
#XS Ineff= 2 , 0
         4970.28 1716.95  5019.5            1721
Permanent Ineff=
       F       F
Bank Sta=4985.4,4989.4
XS Rating Curve= 0 ,0
Exp/Cntr=0.3,0.1

Type RM Length L Ch R = 1 ,225     ,0,0,0
BEGIN DESCRIPTION:
Stream0510 0.0
END DESCRIPTION:
XS GIS Cut Line= 3
      1987897.79     13867206.95      1988268.04     13867275.87
       1988467.8     13867159.88
#Sta/Elev= 30
  4557.5 1740.33  4564.8 1738.77    4572 1736.15  4585.2 1733.51  4601.9 1731.37
  4624.8 1728.36  4629.9 1728.21    4636 1726.74  4676.7 1722.65  4682.6 1721.53
  4701.5 1720.37  4735.4 1717.55    4846 1711.47  4899.5 1709.76  4900.8 1709.71
  4941.1 1707.94  4946.9 1708.18  4984.1  1706.6  4989.9 1706.87  4999.9 1703.51
  5005.7 1702.25  5009.5 1699.18  5009.8 1698.68  5013.3 1698.68  5013.5 1699.18
  5027.2 1703.28  5034.7 1706.33  5039.9 1706.52  5070.2 1707.58  5165.1 1707.82
#Mann= 8 ,-1 , 0
  4557.5      .1       0  4601.9     .07       0  4701.5    .035       0
  4899.5     .07       0  4900.8     .07       0  5009.5     .05       0
  5013.5     .07       0  5039.9     .07       0
#XS Ineff= 2 , 0
                         5071.47         1709.94
Permanent Ineff=
       F       F
Bank Sta=5009.5,5013.5
XS Rating Curve= 0 ,0
Exp/Cntr=0.3,0.1

Chan Stop Cuts=-1
Use User Specified Reach Order=0
Composite Channel Slope=5