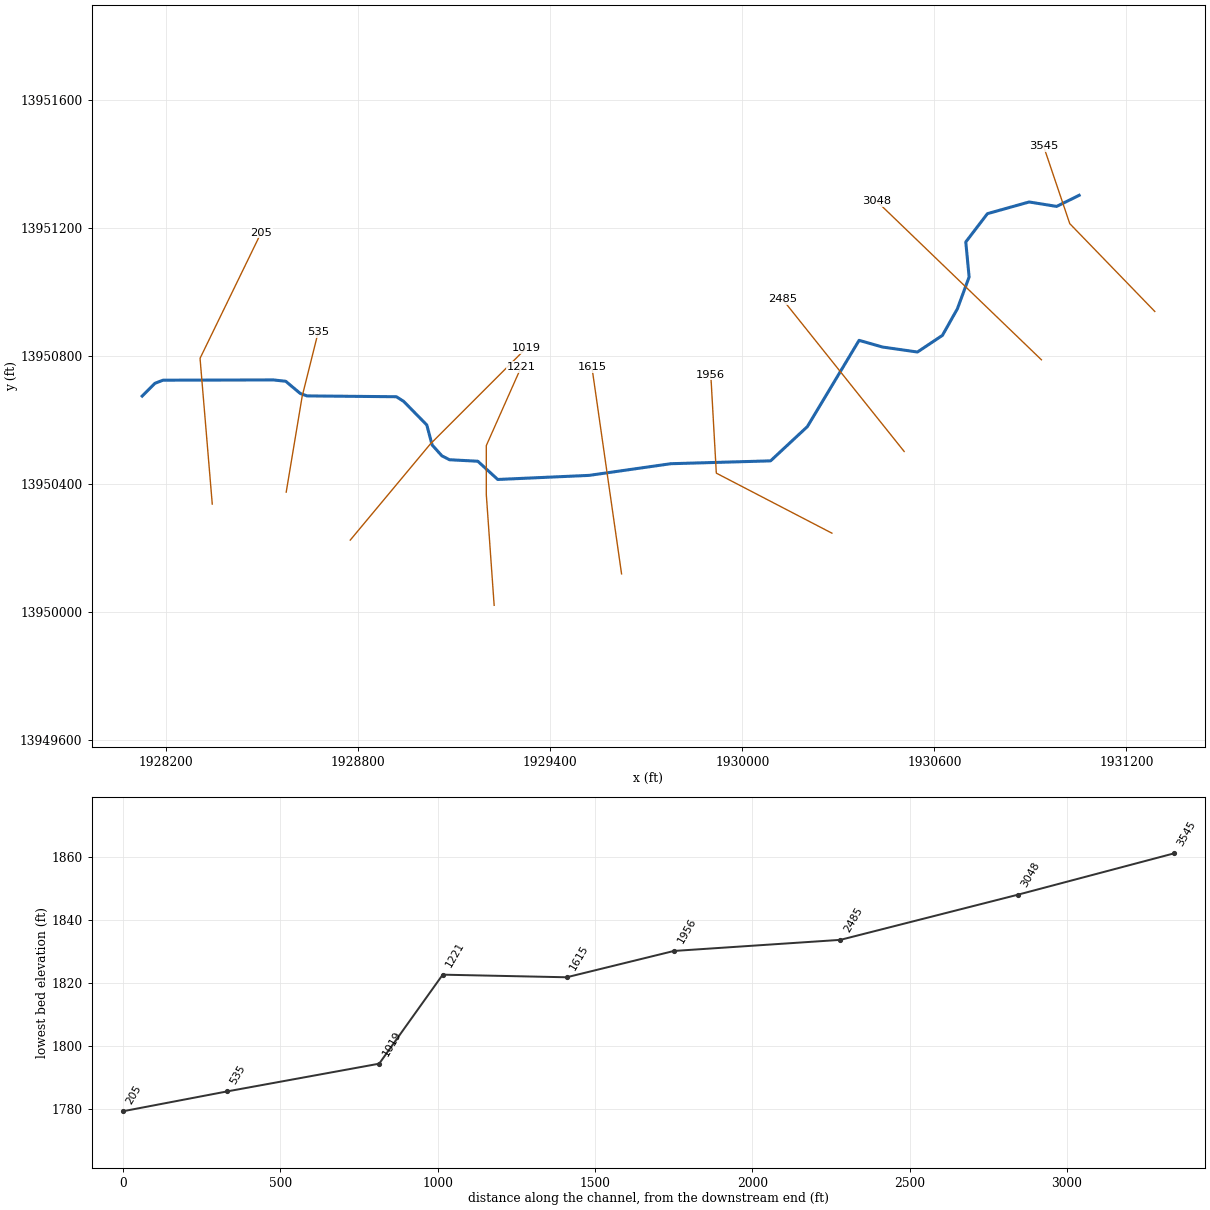
--- Stream0513.prj (project) ---

Proj Title=Stream0513 Base Level Engineering
Current Plan=p01
Default Exp/Contr=0.3,0.1
English Units
Geom File=g01
Flow File=f01
Plan File=p01
Y Axis Title=Elevation
X Axis Title(PF)=Main Channel Distance
X Axis Title(XS)=Station
BEGIN DESCRIPTION:
Stream0513
END DESCRIPTION:
DSS Export Rating Curves= 0
DSS Export Rating Curve Sorted= 0
DSS Export Volume Flow Curves= 0
DXF OffsetX= 0
DXF OffsetY= 0
DXF ScaleX= 1
DXF ScaleY= 10

--- Stream0513.p01 (plan) ---

Plan Title=Multiple Run
Short Identifier=Multiple
Geom File=g01
Flow File=f01
Subcritical Flow
K Sum by GR= 0
Std Step Tol= 0.01
Critical Tol= 0.01
Num of Std Step Trials= 20
Max Error Tol= 0.3
Flow Tol Ratio= 0.001
Split Flow NTrial= 30
Split Flow Tol= 0.02
Split Flow Ratio= 0.02
Log Output Level= 0
Friction Slope Method= 1
Unsteady Friction Slope Method= 2
Unsteady Bridges Friction Slope Method= 1
Parabolic Critical Depth
Global Vel Dist=  1 , 1 , 1
Global Log Level= 0
CheckData=True
Encroach Param= -1, 0, 0, 0
BEGIN DESCRIPTION:
Multiple Run
END DESCRIPTION:

--- Stream0513.f01 (steady flow) ---

Flow Title=Multiple
Program Version=4.10
Number of Profiles= 7
Profile Names=10-year,25-year,50-year,1pct_min,100-year,1pct_plu,500-year
River Rch & RM=Stream0513,Reach-1         ,3545
     949    1608    2233    1502    2996    5978    5321
Boundary for River Rch & Prof#=Stream0513,Reach-1         , 1
Up Type= 0
Dn Type= 3
Dn Slope=0.007
Boundary for River Rch & Prof#=Stream0513,Reach-1         , 2
Up Type= 0
Dn Type= 3
Dn Slope=0.007
Boundary for River Rch & Prof#=Stream0513,Reach-1         , 3
Up Type= 0
Dn Type= 3
Dn Slope=0.007
Boundary for River Rch & Prof#=Stream0513,Reach-1         , 4
Up Type= 0
Dn Type= 3
Dn Slope=0.007
Boundary for River Rch & Prof#=Stream0513,Reach-1         , 5
Up Type= 0
Dn Type= 3
Dn Slope=0.007
Boundary for River Rch & Prof#=Stream0513,Reach-1         , 6
Up Type= 0
Dn Type= 3
Dn Slope=0.007
Boundary for River Rch & Prof#=Stream0513,Reach-1         , 7
Up Type= 0
Dn Type= 3
Dn Slope=0.007
DSS Import GetInterval= 0
DSS Import GetPeak= 0
DSS Import FillOption= 0

--- Stream0513.g01 (geometry) ---

Geom Title=Existing Conditions
Program Version=4.10

River Reach=Stream0513      ,Reach-1
Reach XY= 30
      1931052.22     13951302.23      1930981.94     13951267.53
      1930895.97     13951281.39      1930765.76     13951244.94
      1930698.05     13951156.39      1930708.47     13951047.02
      1930672.01     13950948.06      1930625.13     13950864.73
      1930547.01     13950812.64      1930437.63     13950828.27
      1930364.72      13950849.1      1930203.04      13950579.5
      1930088.22      13950472.6      1929776.18     13950463.69
      1929520.97     13950427.23      1929235.86     13950414.46
      1929173.52     13950471.43      1929085.33      13950476.1
      1929061.35     13950488.26      1929030.74     13950522.43
      1929014.22     13950584.68       1928941.8     13950658.58
      1928919.16     13950672.95      1928640.22     13950675.52
      1928618.94     13950683.14      1928573.43     13950721.22
      1928535.19     13950725.45      1928190.15     13950724.64
      1928165.02     13950714.95        1928125.       13950675.

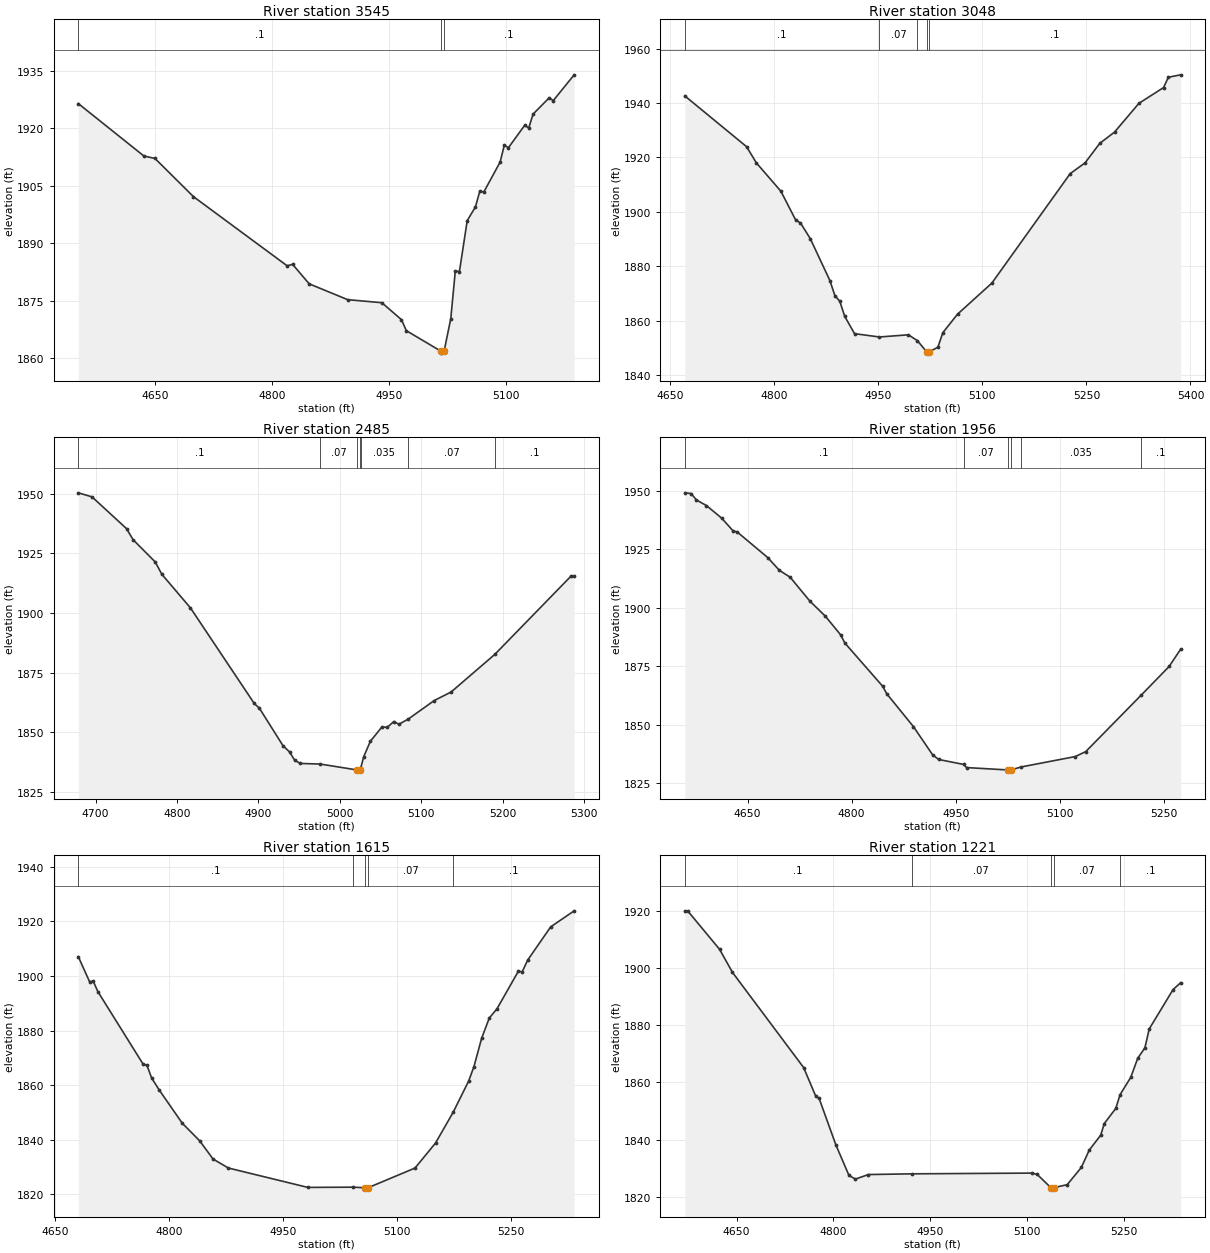
Type RM Length L Ch R = 1 ,3545    ,497,497,497
BEGIN DESCRIPTION:
Stream0513 8.0
END DESCRIPTION:
XS GIS Cut Line= 3
      1931288.52     13950939.42       1931022.9     13951213.72
      1930941.29     13951455.07
#Sta/Elev= 30
  4551.2 1926.42  4635.4 1912.73  4649.6  1912.1    4699 1902.13  4819.3 1884.07
  4826.3 1884.45  4847.6 1879.36    4897 1875.23  4940.9 1874.43  4966.1    1870
  4972.3 1867.14  5016.8 1861.77  5017.1 1861.27  5020.8 1861.77  5029.4 1870.28
  5035.2 1882.69  5040.5 1882.58  5050.5 1895.85  5061.1 1899.47  5066.6 1903.51
  5071.9 1903.37  5092.7 1911.14  5098.1 1915.51  5103.4 1914.91  5124.3 1920.75
  5129.5 1920.04    5135 1923.66  5155.7 1927.92    5161 1927.21  5187.8 1933.93
#Mann= 3 ,-1 , 0
  4551.2      .1       0  5016.8     .05       0  5020.8      .1       0
Bank Sta=5016.8,5020.8
XS Rating Curve= 0 ,0
Exp/Cntr=0.3,0.1

Type RM Length L Ch R = 1 ,3048    ,563,563,563
BEGIN DESCRIPTION:
Stream0513 7.0
END DESCRIPTION:
XS GIS Cut Line= 2
      1930934.34     13950788.39      1930419.39     13951284.27
#Sta/Elev= 30
  4670.9  1942.6    4760 1923.94  4774.1 1917.99  4809.4  1907.6  4830.7 1897.04
  4837.7 1895.93  4851.8 1890.18  4880.1 1874.77  4887.3 1869.25  4894.3  1867.2
  4901.5 1861.62  4915.6 1855.26  4951.6 1854.04  4993.3 1854.84  5006.3 1852.68
  5019.6 1848.61  5019.9 1848.11  5023.6 1848.61  5035.8 1850.29    5043 1855.64
  5064.1 1862.41  5113.7 1873.85  5226.6 1914.06    5248 1917.99  5269.1 1925.14
  5290.5  1929.3  5325.7 1939.88  5361.2 1945.66  5368.1 1949.45  5385.8 1950.34
#Mann= 5 ,-1 , 0
  4670.9      .1       0  4951.6     .07       0  5006.3      .1       0
  5019.6     .05       0  5023.6      .1       0
Bank Sta=5019.6,5023.6
XS Rating Curve= 0 ,0
Exp/Cntr=0.3,0.1

Type RM Length L Ch R = 1 ,2485    ,529,529,529
BEGIN DESCRIPTION:
Stream0513 6.0
END DESCRIPTION:
XS GIS Cut Line= 2
      1930505.54     13950501.91      1930125.31     13950977.63
#Sta/Elev= 30
  4678.9 1950.32  4695.7 1948.63  4738.1 1935.33  4746.2 1930.67  4773.4 1921.35
  4781.4 1916.24  4816.6 1902.14    4895  1862.1  4901.4 1860.07  4930.3 1844.43
  4938.3 1841.84  4944.7 1838.29  4951.7    1837    4976 1836.74  5021.1 1834.28
  5021.4 1833.78  5025.1 1834.28  5025.9 1835.29  5029.5 1839.85  5037.5 1846.23
  5051.9 1852.33  5058.3 1852.09  5066.3 1854.53  5072.7 1853.42  5083.8  1855.5
    5116 1863.33  5136.8 1866.92  5190.4 1882.65  5284.1 1915.46  5287.9 1915.46
#Mann= 7 ,-1 , 0
  4678.9      .1       0    4976     .07       0  5021.1     .05       0
  5025.1     .07       0  5025.9    .035       0  5083.8     .07       0
  5190.4      .1       0
Bank Sta=5021.1,5025.1
XS Rating Curve= 0 ,0
Exp/Cntr=0.3,0.1

Type RM Length L Ch R = 1 ,1956    ,341,341,341
BEGIN DESCRIPTION:
Stream0513 5.0
END DESCRIPTION:
XS GIS Cut Line= 3
      1930279.81     13950246.73      1929918.73     13950434.21
      1929901.46     13950741.57
#Sta/Elev= 30
  4559.6 1949.09  4568.7  1948.8  4576.3 1946.05  4590.8 1943.66  4612.9 1938.25
  4629.4 1932.77    4635 1932.41  4679.3 1921.41  4695.8 1916.02  4711.5 1913.05
    4740 1902.81  4762.1 1896.45  4784.2 1888.45  4790.4 1884.92  4844.9 1866.47
  4850.6 1863.32  4889.2 1849.24  4916.9 1837.18  4925.6 1835.22  4961.5 1833.11
  4965.7 1831.77  5025.3 1830.75  5025.6 1830.25  5029.3 1830.75  5044.8 1832.05
  5122.3 1836.46  5137.5 1838.58  5217.5 1862.71  5257.7 1874.93  5274.3  1882.3
#Mann= 6 ,-1 , 0
  4559.6      .1       0  4961.5     .07       0  5025.3     .05       0
  5029.3     .07       0  5044.8    .035       0  5217.5      .1       0
Bank Sta=5025.3,5029.3
XS Rating Curve= 0 ,0
Exp/Cntr=0.3,0.1

Type RM Length L Ch R = 1 ,1615    ,394,394,394
BEGIN DESCRIPTION:
Stream0513 4.0
END DESCRIPTION:
XS GIS Cut Line= 2
      1929622.68     13950119.52        1929530.      13950765.6
#Sta/Elev= 30
    4681 1907.08  4695.7 1897.98  4700.8 1898.01  4706.7 1894.29  4766.3 1867.68
  4771.4 1867.22  4777.5 1862.62  4787.6 1858.17  4817.9 1846.01  4840.7 1839.61
  4858.3 1832.92  4878.5 1829.62  4983.1 1822.51  5042.4  1822.6  5058.3 1822.38
  5058.6 1821.88  5062.3 1822.38  5124.2 1829.61  5151.2 1838.77  5174.4 1850.05
  5194.8 1861.49  5201.8 1866.81  5211.9 1877.18    5222 1884.62  5232.1 1887.98
  5260.3 1901.79  5265.3 1901.53  5272.5 1905.84  5302.8 1918.01  5333.7  1923.9
#Mann= 5 ,-1 , 0
    4681      .1       0  5042.4     .07       0  5058.3     .05       0
  5062.3     .07       0  5174.4      .1       0
Bank Sta=5058.3,5062.3
XS Rating Curve= 0 ,0
Exp/Cntr=0.3,0.1

Type RM Length L Ch R = 1 ,1221    ,202,202,202
BEGIN DESCRIPTION:
Stream0513 3.0
END DESCRIPTION:
XS GIS Cut Line= 4
      1929224.63     13950021.28      1929200.09     13950367.58
      1929200.09     13950520.26      1929309.16     13950765.66
#Sta/Elev= 30
  4569.7 1919.89  4574.1 1919.89  4623.6 1906.45  4643.6 1898.39  4753.9 1865.15
  4772.8 1855.08  4777.8 1854.43    4804 1838.06  4824.1 1827.51  4834.1 1826.21
  4854.1  1827.8  4921.2 1828.05  5107.6 1828.31  5115.8 1827.85  5137.1 1823.21
  5137.3 1822.71  5141.1 1823.21  5162.3 1824.26  5184.2 1830.27  5196.5 1836.35
  5214.3 1841.57  5219.8 1845.62  5237.6 1850.89  5244.3 1855.71  5260.8 1861.74
  5271.7 1868.44  5282.7 1872.03  5289.5 1878.68  5326.4  1892.4  5338.1 1894.79
#Mann= 5 ,-1 , 0
  4569.7      .1       0  4921.2     .07       0  5137.1     .05       0
  5141.1     .07       0  5244.3      .1       0
Bank Sta=5137.1,5141.1
XS Rating Curve= 0 ,0
Exp/Cntr=0.3,0.1

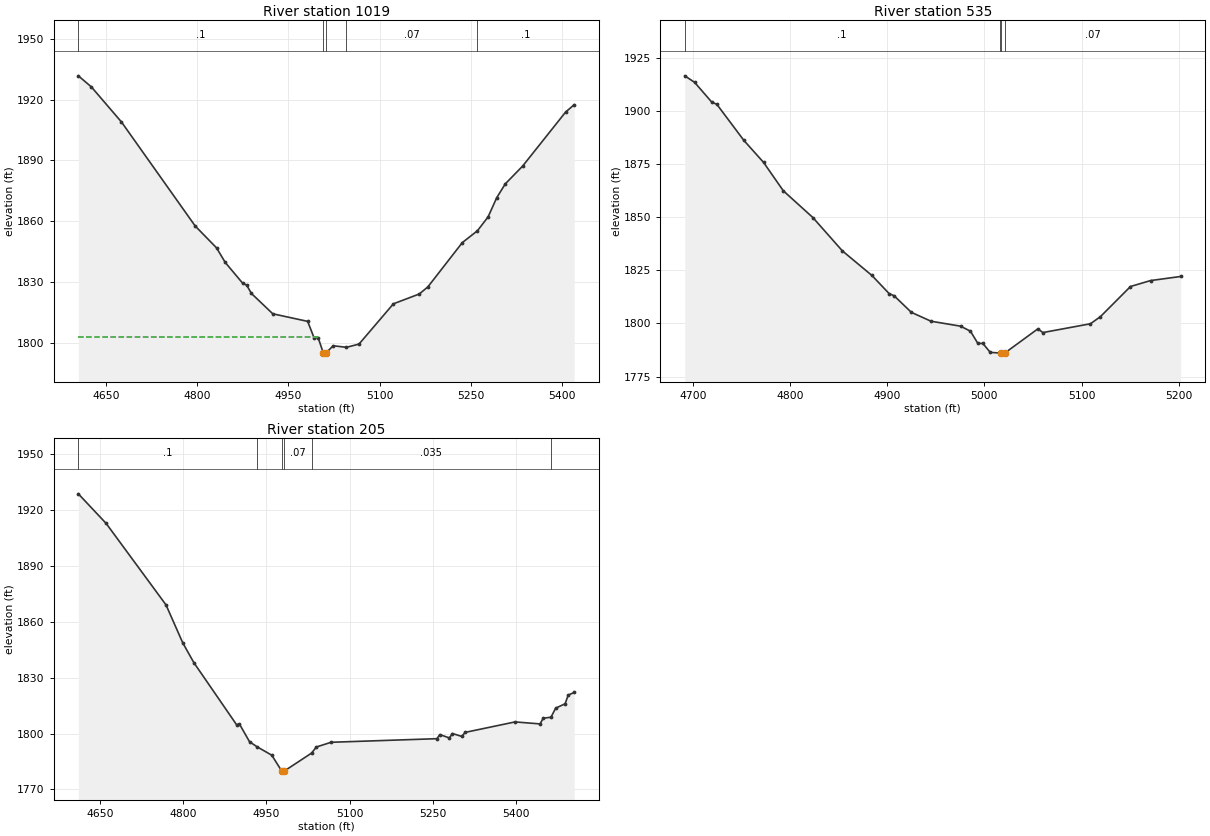
Type RM Length L Ch R = 1 ,1019    ,484,484,484
BEGIN DESCRIPTION:
Stream0513 2.0
END DESCRIPTION:
XS GIS Cut Line= 3
      1928775.03     13950225.03        1929025.       13950525.
      1929324.98     13950824.98
#Sta/Elev= 30
  4604.9 1931.77  4626.3 1926.31  4675.8 1908.98  4796.9 1857.65    4832 1846.86
  4846.3 1839.65    4875 1829.37  4881.5 1828.46  4889.3 1824.35  4924.4 1814.31
  4981.7 1810.57  4992.1 1802.56  4998.9 1802.56  5007.5  1794.9  5007.8  1794.4
  5011.5  1794.9  5023.7 1798.54  5045.5 1797.76  5066.1 1799.36  5122.6 1819.24
  5165.1 1824.08  5179.2 1827.58  5235.8 1849.44  5260.7  1855.3  5278.2 1862.14
  5292.4 1871.63  5306.5 1878.46  5334.8 1887.17  5405.5 1913.86  5419.6 1917.51
#Mann= 5 ,-1 , 0
  4604.9      .1       0  5007.5     .05       0  5011.5      .1       0
  5045.5     .07       0  5260.7      .1       0
#XS Ineff= 2 , 0
          4998.7 1802.79
Permanent Ineff=
       F       F
Bank Sta=5007.5,5011.5
XS Rating Curve= 0 ,0
Exp/Cntr=0.3,0.1

Type RM Length L Ch R = 1 ,535     ,330,330,330
BEGIN DESCRIPTION:
Stream0513 1.0
END DESCRIPTION:
XS GIS Cut Line= 3
        1928575.     13950375.02        1928625.       13950675.
      1928675.01     13950875.03
#Sta/Elev= 30
  4691.7 1916.57  4701.8  1913.5  4719.6 1904.11  4724.6  1903.2  4752.5 1886.18
  4772.8  1875.8  4793.1 1862.45  4823.5 1849.87  4853.9 1834.16  4884.3 1822.59
    4902 1814.06  4907.1 1813.05  4924.9 1805.23  4945.1 1801.06  4975.5 1798.73
  4985.7 1796.37  4993.3 1790.62  4998.4 1790.62  5006.1 1786.39  5015.7  1786.1
    5017 1786.07  5017.3 1785.57    5021 1786.07  5055.1 1797.48  5060.2 1795.72
  5109.2 1799.86  5119.5 1803.23  5150.4  1817.4    5171 1820.19    5202 1822.12
#Mann= 4 ,-1 , 0
  4691.7      .1       0  5015.7     .07       0    5017     .05       0
    5021     .07       0
Bank Sta=5017,5021
XS Rating Curve= 0 ,0
Exp/Cntr=0.3,0.1

Type RM Length L Ch R = 1 ,205     ,0,0,0
BEGIN DESCRIPTION:
Stream0513 0.0
END DESCRIPTION:
XS GIS Cut Line= 3
      1928343.98     13950337.59      1928305.81     13950792.91
      1928496.69     13951185.56
#Sta/Elev= 30
  4611.2 1928.83  4661.3 1912.94  4769.2 1869.15  4799.3 1848.79  4819.3 1838.15
  4896.4 1804.74  4901.5 1805.15  4919.7 1795.62  4933.1 1792.93  4959.8 1788.38
  4977.9 1779.78  4978.1 1779.28  4981.9 1779.78  5031.5 1789.51  5040.1 1792.77
  5066.7 1795.32  5257.3 1797.25  5262.8 1799.44  5279.8 1797.66  5285.4 1800.03
  5302.4 1798.44    5308 1800.62  5398.2 1806.26  5443.3 1805.19  5448.9 1808.24
  5462.9 1808.78  5471.4 1813.66  5488.4 1816.01    5494 1820.68  5504.7 1822.09
#Mann= 6 ,-1 , 0
  4611.2      .1       0  4933.1     .07       0  4977.9     .05       0
  4981.9     .07       0  5031.5    .035       0  5462.9      .1       0
Bank Sta=4977.9,4981.9
XS Rating Curve= 0 ,0
Exp/Cntr=0.3,0.1

Chan Stop Cuts=-1
Use User Specified Reach Order=0
Composite Channel Slope=5