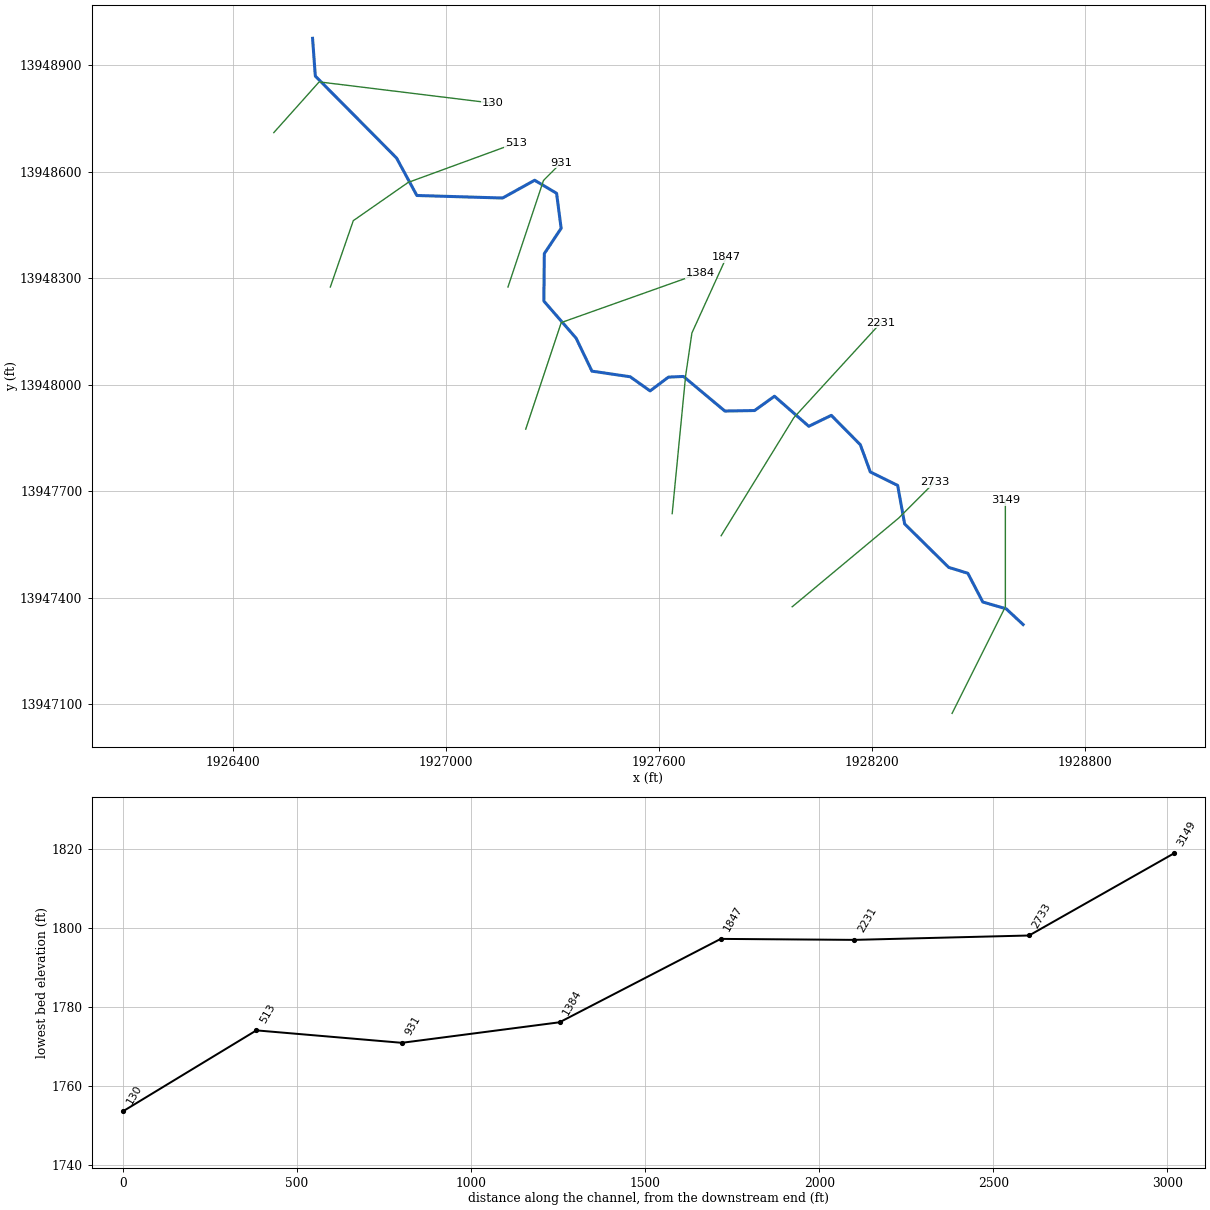
--- Stream0514.prj (project) ---

Proj Title=Stream0514 Base Level Engineering
Current Plan=p01
Default Exp/Contr=0.3,0.1
English Units
Geom File=g01
Flow File=f01
Plan File=p01
Y Axis Title=Elevation
X Axis Title(PF)=Main Channel Distance
X Axis Title(XS)=Station
BEGIN DESCRIPTION:
Stream0514
END DESCRIPTION:
DSS Export Rating Curves= 0
DSS Export Rating Curve Sorted= 0
DSS Export Volume Flow Curves= 0
DXF OffsetX= 0
DXF OffsetY= 0
DXF ScaleX= 1
DXF ScaleY= 10

--- Stream0514.p01 (plan) ---

Plan Title=Multiple Run
Short Identifier=Multiple
Geom File=g01
Flow File=f01
Subcritical Flow
K Sum by GR= 0
Std Step Tol= 0.01
Critical Tol= 0.01
Num of Std Step Trials= 20
Max Error Tol= 0.3
Flow Tol Ratio= 0.001
Split Flow NTrial= 30
Split Flow Tol= 0.02
Split Flow Ratio= 0.02
Log Output Level= 0
Friction Slope Method= 1
Unsteady Friction Slope Method= 2
Unsteady Bridges Friction Slope Method= 1
Parabolic Critical Depth
Global Vel Dist=  1 , 1 , 1
Global Log Level= 0
CheckData=True
Encroach Param= -1, 0, 0, 0
BEGIN DESCRIPTION:
Multiple Run
END DESCRIPTION:

--- Stream0514.f01 (steady flow) ---

Flow Title=Multiple
Program Version=4.10
Number of Profiles= 7
Profile Names=10-year,25-year,50-year,1pct_min,100-year,1pct_plu,500-year
River Rch & RM=Stream0514,Reach-1         ,3149
    1141    1954    2731    1847    3686    7355    6625
Boundary for River Rch & Prof#=Stream0514,Reach-1         , 1
Up Type= 0
Dn Type= 3
Dn Slope=0.005
Boundary for River Rch & Prof#=Stream0514,Reach-1         , 2
Up Type= 0
Dn Type= 3
Dn Slope=0.005
Boundary for River Rch & Prof#=Stream0514,Reach-1         , 3
Up Type= 0
Dn Type= 3
Dn Slope=0.005
Boundary for River Rch & Prof#=Stream0514,Reach-1         , 4
Up Type= 0
Dn Type= 3
Dn Slope=0.005
Boundary for River Rch & Prof#=Stream0514,Reach-1         , 5
Up Type= 0
Dn Type= 3
Dn Slope=0.005
Boundary for River Rch & Prof#=Stream0514,Reach-1         , 6
Up Type= 0
Dn Type= 3
Dn Slope=0.005
Boundary for River Rch & Prof#=Stream0514,Reach-1         , 7
Up Type= 0
Dn Type= 3
Dn Slope=0.005
DSS Import GetInterval= 0
DSS Import GetPeak= 0
DSS Import FillOption= 0

--- Stream0514.g01 (geometry) ---

Geom Title=Existing Conditions
Program Version=4.10

River Reach=Stream0514      ,Reach-1
Reach XY= 30
        1928625.       13947325.      1928577.32     13947369.28
      1928511.42     13947388.49      1928469.37     13947469.35
      1928415.58     13947485.89      1928291.47     13947608.27
      1928271.81     13947716.65      1928194.74     13947754.57
      1928166.83     13947831.07      1928085.02     13947913.77
      1928021.67     13947883.03       1927925.1     13947967.66
      1927869.11     13947927.37      1927785.49     13947925.95
      1927668.95     13948023.33      1927626.65     13948021.42
      1927575.01     13947982.59       1927519.1     13948022.44
      1927411.35     13948038.26      1927366.81     13948131.02
      1927276.04     13948235.44      1927277.25     13948369.06
      1927324.63     13948440.28      1927311.81      13948538.8
      1927250.13     13948575.54      1927159.79     13948525.54
      1926918.52     13948532.69      1926861.36      13948638.2
      1926632.74     13948868.78        1926625.       13948975.

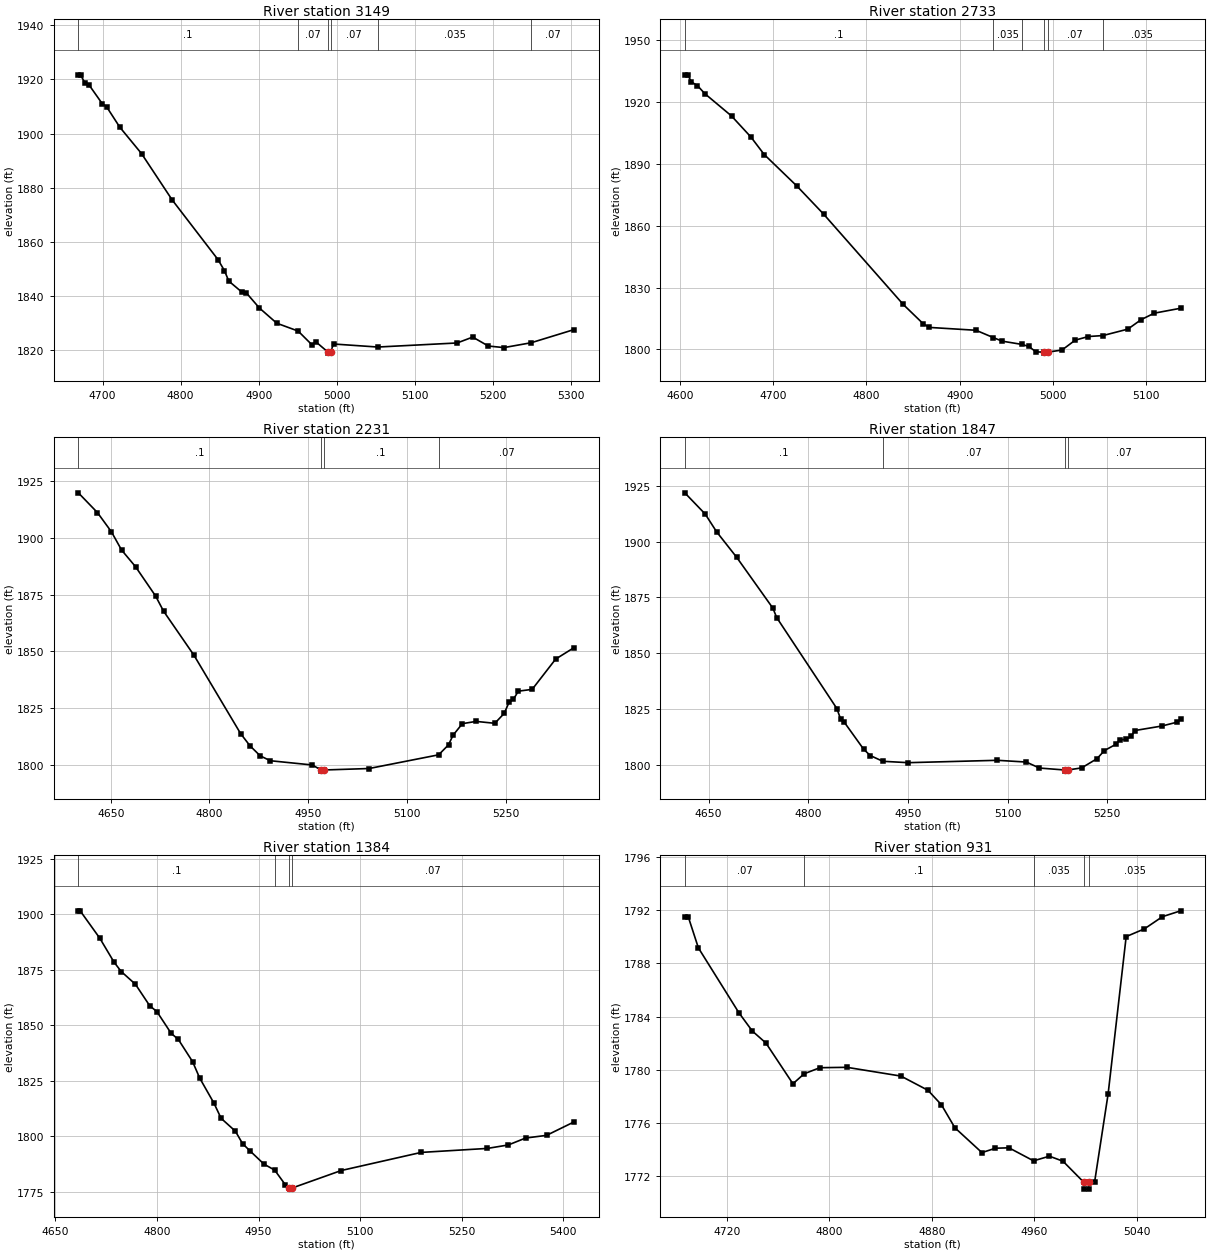
Type RM Length L Ch R = 1 ,3149    ,416,416,416
BEGIN DESCRIPTION:
Stream0514 7.0
END DESCRIPTION:
XS GIS Cut Line= 3
      1928425.01     13947075.01        1928575.       13947375.
        1928575.     13947675.01
#Sta/Elev= 30
  4668.9  1921.7  4671.7  1921.7  4677.3 1918.73  4682.9 1917.85  4699.6 1911.03
  4705.2 1909.87    4722 1902.39  4749.9 1892.62  4789.1 1875.55  4847.8 1853.53
  4856.2  1849.4  4861.7 1845.57  4878.5  1841.5  4884.1 1841.25  4900.9 1835.64
  4923.2 1830.02  4950.6 1827.12    4968 1822.13  4973.5 1823.11  4988.3 1819.48
  4988.6 1818.98  4992.3 1819.48  4995.9 1822.35  5052.6 1821.23  5154.3 1822.73
  5174.3  1824.9  5194.3  1821.6  5214.3 1821.02  5249.3 1822.82  5304.3 1827.68
#Mann= 6 ,-1 , 0
  4668.9      .1       0  4950.6     .07       0  4988.3     .05       0
  4992.3     .07       0  5052.6    .035       0  5249.3     .07       0
Bank Sta=4988.3,4992.3
XS Rating Curve= 0 ,0
Exp/Cntr=0.3,0.1

Type RM Length L Ch R = 1 ,2733    ,502,502,502
BEGIN DESCRIPTION:
Stream0514 6.0
END DESCRIPTION:
XS GIS Cut Line= 3
      1927975.03     13947375.02        1928275.       13947625.
        1928375.       13947725.
#Sta/Elev= 30
  4605.1 1933.13  4608.3 1933.13  4612.2 1929.66  4618.7 1927.89  4626.5 1924.03
  4655.2 1913.18    4676 1902.99  4690.3 1894.49  4725.5 1879.14  4754.1 1865.55
  4839.4  1821.8  4860.8 1812.45  4867.4 1810.66  4917.5 1809.27  4936.1 1805.72
  4945.5    1804  4966.7 1802.42  4974.1 1801.43  4981.9 1798.78  4990.3 1798.69
  4990.6 1798.19  4994.3 1798.69  5009.7 1799.67  5023.9 1804.48    5038 1806.24
  5053.6  1806.7  5080.4 1809.83  5094.6 1814.41  5108.7 1817.56    5137 1819.95
#Mann= 6 ,-1 , 0
  4605.1      .1       0  4936.1    .035       0  4966.7     .07       0
  4990.3     .05       0  4994.3     .07       0  5053.6    .035       0
Bank Sta=4990.3,4994.3
XS Rating Curve= 0 ,0
Exp/Cntr=0.3,0.1

Type RM Length L Ch R = 1 ,2231    ,384,384,384
BEGIN DESCRIPTION:
Stream0514 5.0
END DESCRIPTION:
XS GIS Cut Line= 3
        1927775.       13947575.      1927979.63     13947907.27
      1928225.01     13948175.01
#Sta/Elev= 30
  4600.8 1919.92  4629.8 1911.21  4651.1 1902.71  4666.5 1894.68  4687.7 1887.32
  4718.2 1874.37  4730.3  1867.7  4776.5 1848.23  4847.4 1813.64  4861.6 1808.27
  4877.1 1803.84  4892.5 1801.67  4956.3 1799.79  4969.7 1797.58    4970 1797.08
  4973.7 1797.58  5042.5 1798.23  5148.3 1804.28  5163.3 1808.69  5170.1 1812.89
  5184.3 1818.03  5205.3 1819.03  5233.6 1818.19  5247.8 1822.53  5255.2  1827.4
    5262 1828.84  5269.4 1832.37  5290.4 1833.17  5326.1 1846.54  5354.2 1851.62
#Mann= 4 ,-1 , 0
  4600.8      .1       0  4969.7     .05       0  4973.7      .1       0
  5148.3     .07       0
Bank Sta=4969.7,4973.7
XS Rating Curve= 0 ,0
Exp/Cntr=0.3,0.1

Type RM Length L Ch R = 1 ,1847    ,463,463,463
BEGIN DESCRIPTION:
Stream0514 4.0
END DESCRIPTION:
XS GIS Cut Line= 4
      1927637.23     13947637.21        1927675.       13948025.
      1927692.79     13948145.87        1927790.     13948359.38
#Sta/Elev= 30
  4614.2 1921.81  4644.9 1912.32  4662.2 1904.33  4692.4 1892.93  4746.8 1870.22
  4752.6 1865.98  4843.1 1825.33  4848.6 1820.77  4853.6 1819.48  4883.3 1807.18
  4893.3 1804.31  4912.3 1801.73  4950.4 1801.11  5084.7 1802.17  5128.3 1801.39
    5148 1798.71  5186.6 1797.83  5186.8 1797.33  5190.6 1797.83  5211.6 1798.78
  5234.7 1802.89  5245.9 1806.53  5263.2 1809.34  5268.7 1811.25  5278.9 1811.57
  5286.3 1812.99  5291.8 1815.49  5332.4 1817.51  5355.4 1819.24  5360.6 1820.46
#Mann= 4 ,-1 , 0
  4614.2      .1       0  4912.3     .07       0  5186.6     .05       0
  5190.6     .07       0
Bank Sta=5186.6,5190.6
XS Rating Curve= 0 ,0
Exp/Cntr=0.3,0.1

Type RM Length L Ch R = 1 ,1384    ,453,453,453
BEGIN DESCRIPTION:
Stream0514 3.0
END DESCRIPTION:
XS GIS Cut Line= 3
      1927224.99     13947874.98        1927325.       13948175.
      1927716.85     13948314.24
#Sta/Elev= 30
  4683.8 1901.65  4686.5 1901.65  4715.4 1889.35  4736.5 1878.53  4747.1  1874.3
  4768.1 1868.55  4789.2 1858.87  4799.8 1856.22  4820.9 1846.42  4831.4  1843.7
  4852.5 1833.67    4863 1826.26  4884.1 1814.93  4894.6 1808.13  4915.7 1802.32
  4926.3 1796.71  4936.8 1793.58  4957.9 1787.48  4973.7 1784.79  4989.5 1778.16
  4995.4 1776.71  4995.7 1776.21  4999.4 1776.71  5071.9 1784.59    5190 1792.76
  5287.8 1794.56  5318.7 1796.12  5344.2 1799.24  5375.1 1800.44  5415.9 1806.53
#Mann= 4 ,-1 , 0
  4683.8      .1       0  4973.7     .07       0  4995.4     .05       0
  4999.4     .07       0
Bank Sta=4995.4,4999.4
XS Rating Curve= 0 ,0
Exp/Cntr=0.3,0.1

Type RM Length L Ch R = 1 ,931     ,418,418,418
BEGIN DESCRIPTION:
Stream0514 2.0
END DESCRIPTION:
XS GIS Cut Line= 3
      1927174.99     13948274.97        1927275.       13948575.
      1927325.02     13948625.02
#Sta/Elev= 30
  4687.1 1791.51  4689.8 1791.51  4697.7 1789.17  4729.3 1784.29  4739.8 1782.91
  4750.4 1782.01  4771.5 1778.94  4780.2 1779.69  4792.5 1780.15  4813.6 1780.18
  4855.8 1779.52  4876.9 1778.45  4887.4 1777.36  4897.9 1775.63    4919 1773.76
  4929.6 1774.09  4940.1 1774.12  4959.3 1773.14  4971.7 1773.49  4982.3 1773.11
  4998.7 1771.51    4999 1771.01  5002.5 1771.01  5002.7 1771.51  5006.9 1771.51
  5017.5 1778.17  5031.6 1790.02  5045.8  1790.6  5059.9 1791.52  5074.1 1791.96
#Mann= 5 ,-1 , 0
  4687.1     .07       0  4780.2      .1       0  4959.3    .035       0
  4998.7    .035       0  5002.7    .035       0
Bank Sta=4998.7,5002.7
XS Rating Curve= 0 ,0
Exp/Cntr=0.3,0.1

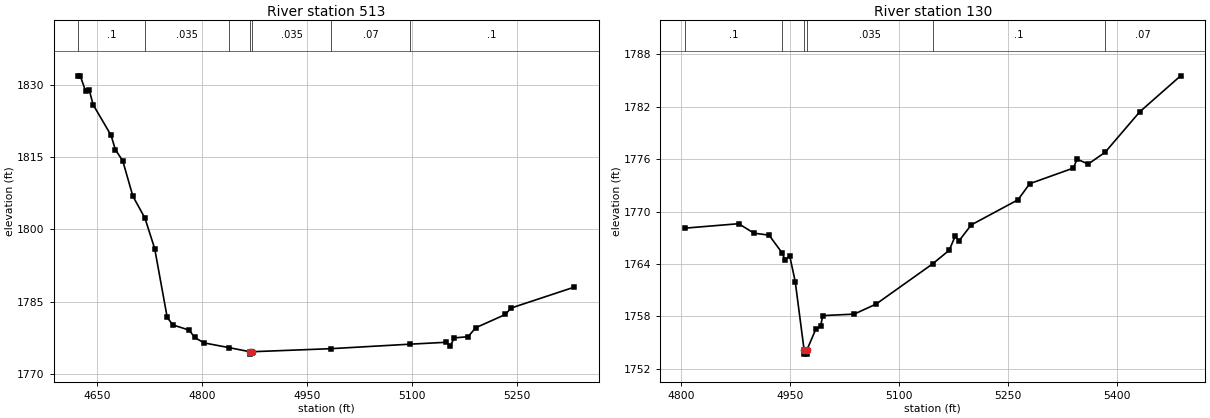
Type RM Length L Ch R = 1 ,513     ,383,383,383
BEGIN DESCRIPTION:
Stream0514 1.0
END DESCRIPTION:
XS GIS Cut Line= 4
        1926675.     13948274.99      1926739.66     13948461.84
      1926894.18     13948569.48      1927197.21     13948680.31
#Sta/Elev= 30
  4623.5 1831.81  4626.2 1831.81  4633.8 1828.69  4639.1 1828.85  4644.7 1825.81
  4670.3 1819.48  4676.4 1816.53    4687 1814.19  4701.4  1806.9  4718.7 1802.33
  4732.6 1796.04  4750.5 1781.79  4758.4 1780.22  4782.2 1779.12  4789.6 1777.61
  4803.4 1776.48  4839.5 1775.49  4868.4 1774.66  4868.7 1774.16  4872.4 1774.66
  4984.6 1775.29  5097.4 1776.22  5148.8 1776.61  5155.4 1775.88  5160.7 1777.52
  5180.6 1777.77  5191.4 1779.62    5234 1782.38  5241.7 1783.69  5332.2 1788.03
#Mann= 7 ,-1 , 0
  4623.5      .1       0  4718.7    .035       0  4839.5    .035       0
  4868.4    .035       0  4872.4    .035       0  4984.6     .07       0
  5097.4      .1       0
Bank Sta=4868.4,4872.4
XS Rating Curve= 0 ,0
Exp/Cntr=0.3,0.1

Type RM Length L Ch R = 1 ,130     ,0,0,0
BEGIN DESCRIPTION:
Stream0514 0.0
END DESCRIPTION:
XS GIS Cut Line= 3
      1926515.95     13948709.65      1926643.56     13948852.45
      1927131.39      13948792.6
#Sta/Elev= 30
  4804.6  1768.1  4878.8 1768.61  4899.8 1767.53  4920.7  1767.3  4938.6 1765.27
  4942.5 1764.51  4949.2 1764.89  4956.7 1761.99  4968.9 1754.18  4969.1 1753.68
  4972.6 1753.68  4972.9 1754.18  4985.1 1756.54  4991.8 1756.89  4994.5 1758.09
  5037.9 1758.26  5068.1 1759.41  5145.9 1764.01  5168.8 1765.57  5177.2 1767.21
  5182.2 1766.63  5199.1 1768.47  5263.6 1771.35  5279.7 1773.19  5339.9 1774.98
  5344.9    1776  5360.3 1775.44  5383.6 1776.79  5431.3 1781.42  5487.6 1785.54
#Mann= 6 ,-1 , 0
  4804.6      .1       0  4938.6    .035       0  4968.9    .035       0
  4972.9    .035       0  5145.9      .1       0  5383.6     .07       0
Bank Sta=4968.9,4972.9
XS Rating Curve= 0 ,0
Exp/Cntr=0.3,0.1

Chan Stop Cuts=-1
Use User Specified Reach Order=0
Composite Channel Slope=5