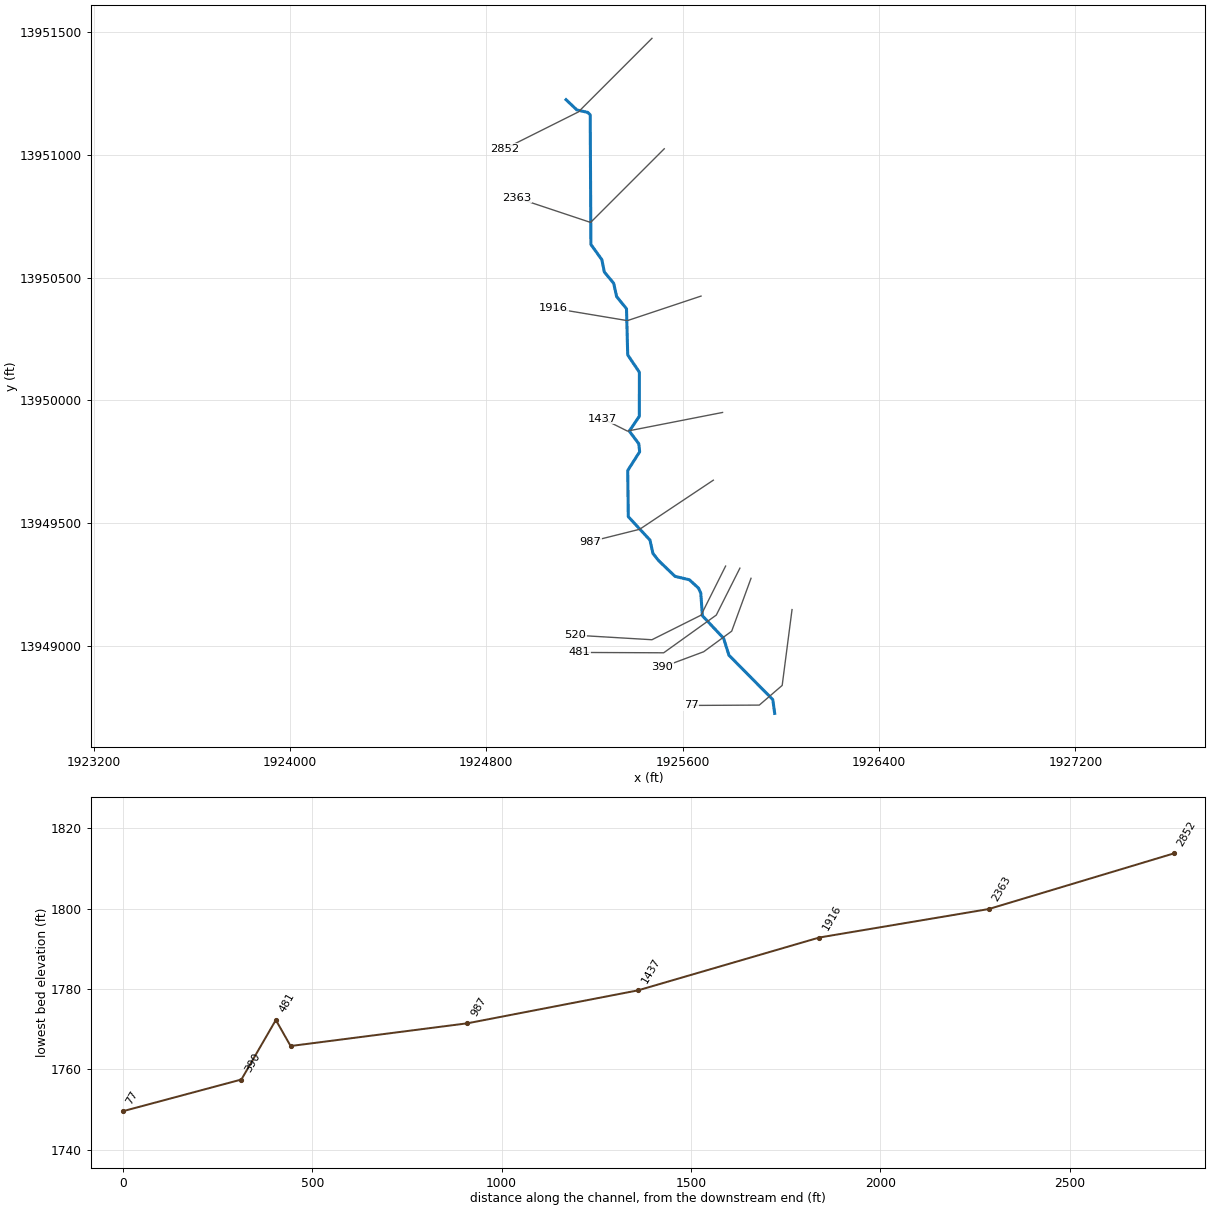
--- Stream0515.prj (project) ---

Proj Title=Stream0515 Base Level Engineering
Current Plan=p01
Default Exp/Contr=0.3,0.1
English Units
Geom File=g01
Flow File=f01
Plan File=p01
Y Axis Title=Elevation
X Axis Title(PF)=Main Channel Distance
X Axis Title(XS)=Station
BEGIN DESCRIPTION:
Stream0515
END DESCRIPTION:
DSS Export Rating Curves= 0
DSS Export Rating Curve Sorted= 0
DSS Export Volume Flow Curves= 0
DXF OffsetX= 0
DXF OffsetY= 0
DXF ScaleX= 1
DXF ScaleY= 10

--- Stream0515.p01 (plan) ---

Plan Title=Multiple Run
Short Identifier=Multiple
Geom File=g01
Flow File=f01
Subcritical Flow
K Sum by GR= 0
Std Step Tol= 0.01
Critical Tol= 0.01
Num of Std Step Trials= 20
Max Error Tol= 0.3
Flow Tol Ratio= 0.001
Split Flow NTrial= 30
Split Flow Tol= 0.02
Split Flow Ratio= 0.02
Log Output Level= 0
Friction Slope Method= 1
Unsteady Friction Slope Method= 2
Unsteady Bridges Friction Slope Method= 1
Parabolic Critical Depth
Global Vel Dist=  1 , 1 , 1
Global Log Level= 0
CheckData=True
Encroach Param= -1, 0, 0, 0
BEGIN DESCRIPTION:
Multiple Run
END DESCRIPTION:

--- Stream0515.f01 (steady flow) ---

Flow Title=Multiple
Program Version=4.10
Number of Profiles= 7
Profile Names=10-year,25-year,50-year,1pct_min,100-year,1pct_plu,500-year
River Rch & RM=Stream0515,Reach-1         ,2852
     923    1562    2167    1457    2907    5800    5158
Boundary for River Rch & Prof#=Stream0515,Reach-1         , 1
Up Type= 0
Dn Type= 3
Dn Slope=0.006
Boundary for River Rch & Prof#=Stream0515,Reach-1         , 2
Up Type= 0
Dn Type= 3
Dn Slope=0.006
Boundary for River Rch & Prof#=Stream0515,Reach-1         , 3
Up Type= 0
Dn Type= 3
Dn Slope=0.006
Boundary for River Rch & Prof#=Stream0515,Reach-1         , 4
Up Type= 0
Dn Type= 3
Dn Slope=0.006
Boundary for River Rch & Prof#=Stream0515,Reach-1         , 5
Up Type= 0
Dn Type= 3
Dn Slope=0.006
Boundary for River Rch & Prof#=Stream0515,Reach-1         , 6
Up Type= 0
Dn Type= 3
Dn Slope=0.006
Boundary for River Rch & Prof#=Stream0515,Reach-1         , 7
Up Type= 0
Dn Type= 3
Dn Slope=0.006
DSS Import GetInterval= 0
DSS Import GetPeak= 0
DSS Import FillOption= 0

--- Stream0515.g01 (geometry) ---

Geom Title=Existing Conditions
Program Version=4.10

River Reach=Stream0515      ,Reach-1
Reach XY= 30
        1925125.       13951225.      1925169.37     13951183.15
      1925213.54      13951173.3      1925223.46     13951163.29
       1925226.2      13950635.5      1925270.81     13950573.26
      1925281.08      13950522.8      1925318.92      13950477.2
      1925331.12     13950422.82      1925371.25     13950373.45
      1925376.22     13950185.51      1925423.78     13950114.49
      1925423.62     13949935.44      1925382.59     13949874.99
      1925421.39     13949823.36      1925424.85     13949790.42
      1925376.24      13949714.5      1925378.55     13949526.47
      1925466.82     13949431.04      1925478.97     13949376.64
      1925501.27     13949348.12      1925568.96     13949283.16
      1925627.57     13949269.26      1925664.61      13949235.1
       1925673.9     13949214.67      1925680.54     13949122.58
      1925766.82     13949031.04      1925788.63     13948961.79
      1925967.24     13948781.21        1925975.       13948725.

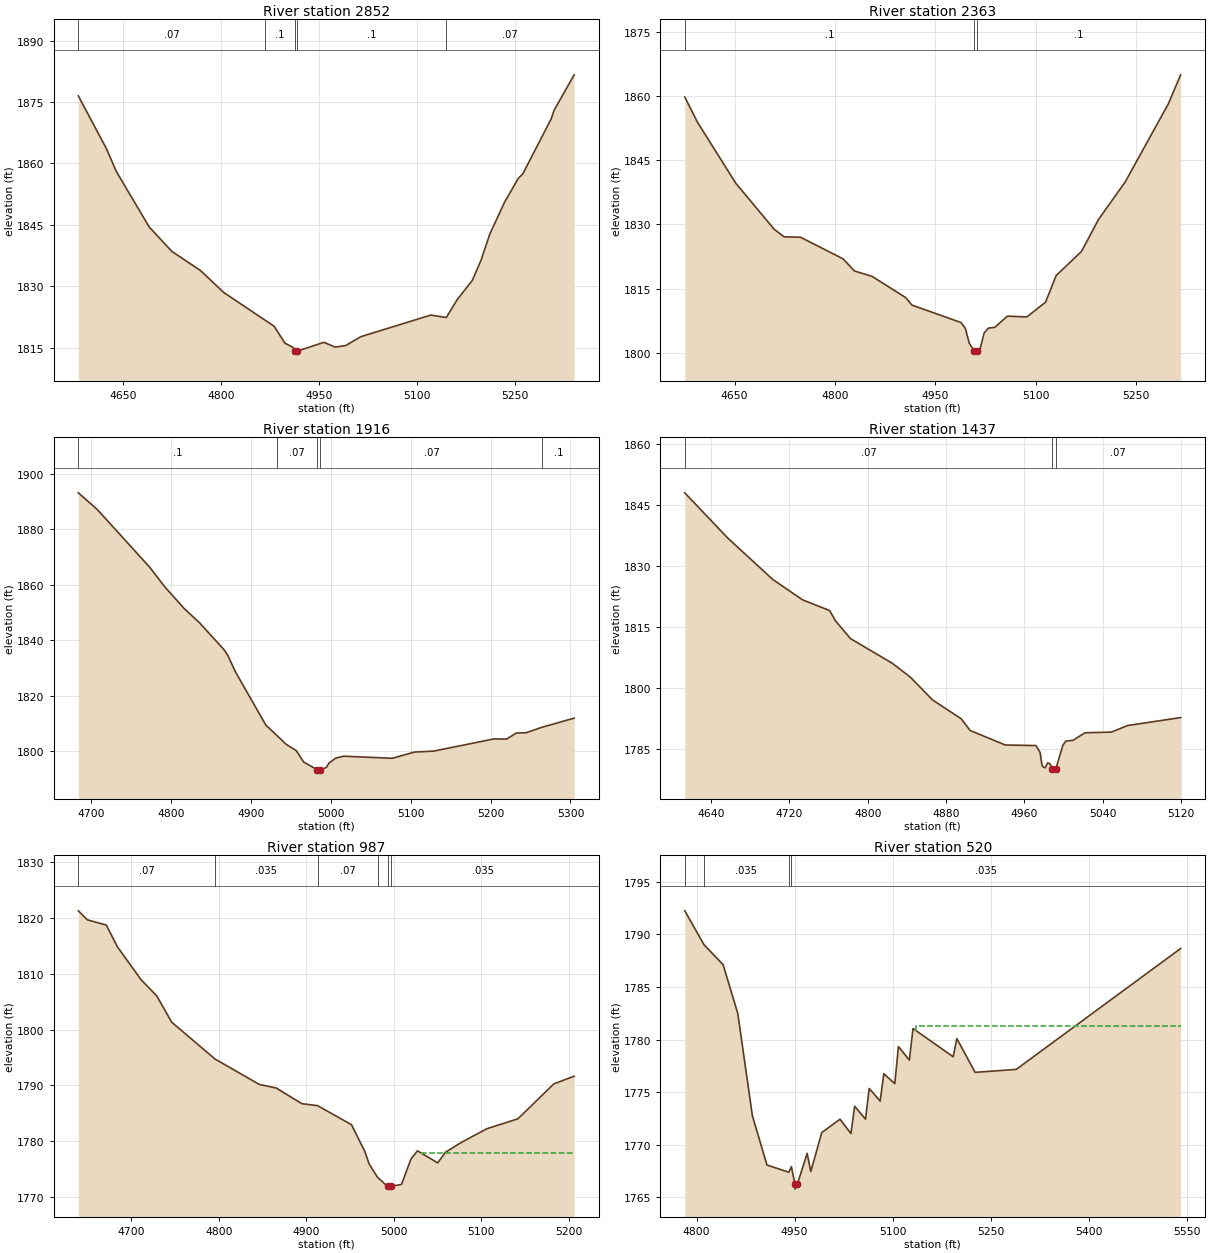
Type RM Length L Ch R = 1 ,2852    ,489,489,489
BEGIN DESCRIPTION:
Stream0515 6.0
END DESCRIPTION:
XS GIS Cut Line= 3
        1925475.       13951475.        1925175.       13951175.
      1924874.98     13951024.99
#Sta/Elev= 30
    4581  1876.5    4624 1863.63  4639.2 1858.06  4689.7 1844.48  4724.1 1838.58
  4768.2 1833.88  4803.9 1828.51  4866.7 1821.82    4881 1820.29  4897.6 1816.16
  4910.3 1815.08  4912.6 1814.23  4912.8 1813.73  4916.6 1814.23  4957.4 1816.37
  4974.4  1815.2  4990.5 1815.57  5013.8 1817.74  5121.1 1823.02  5144.8 1822.42
  5161.3 1826.73  5184.8 1831.52  5197.9 1836.34  5211.5 1842.78  5233.9  1850.5
  5255.2  1856.4    5262 1857.45  5305.5 1870.89  5309.9 1872.96  5340.7 1881.63
#Mann= 5 ,-1 , 0
    4581     .07       0  4866.7      .1       0  4912.6     .05       0
  4916.6      .1       0  5144.8     .07       0
Bank Sta=4912.6,4916.6
XS Rating Curve= 0 ,0
Exp/Cntr=0.3,0.1

Type RM Length L Ch R = 1 ,2363    ,447,447,447
BEGIN DESCRIPTION:
Stream0515 5.0
END DESCRIPTION:
XS GIS Cut Line= 3
      1925525.03     13951025.03        1925225.       13950725.
      1924925.03     13950824.99
#Sta/Elev= 30
  4575.6 1859.82  4594.6 1853.91  4651.8 1839.64  4709.1 1828.87    4724  1827.1
  4748.4 1827.01    4812 1821.95    4829 1819.11  4855.5 1817.83  4905.4 1812.89
  4914.9 1811.12    4988 1807.05  4994.5 1805.71  5000.5  1802.2    5008 1800.38
  5008.3 1799.88    5012 1800.38  5016.3 1800.68  5022.7 1804.62    5029 1805.73
  5038.5 1805.91  5057.4 1808.54  5086.4 1808.35  5114.4 1811.81  5130.2 1818.04
  5168.1 1823.69  5193.4 1831.14  5233.5 1839.99  5297.8 1858.24  5316.1 1865.02
#Mann= 3 ,-1 , 0
  4575.6      .1       0    5008     .05       0    5012      .1       0
Bank Sta=5008,5012
XS Rating Curve= 0 ,0
Exp/Cntr=0.3,0.1

Type RM Length L Ch R = 1 ,1916    ,479,479,479
BEGIN DESCRIPTION:
Stream0515 4.0
END DESCRIPTION:
XS GIS Cut Line= 3
      1925674.99       13950425.        1925375.       13950325.
      1925074.96     13950375.01
#Sta/Elev= 30
  4684.2 1893.17  4707.7 1887.22  4773.4 1866.38  4792.3  1859.3  4816.8 1851.39
  4835.8 1846.32  4866.6 1836.57  4871.3 1834.51  4880.9 1828.54  4918.8 1809.41
  4932.7 1805.65  4944.1 1802.51  4956.8 1800.23  4966.1  1796.1  4983.2  1793.3
  4983.5  1792.8  4987.2  1793.3  4994.6 1794.15  4997.9 1795.72  5006.2 1797.48
  5016.2 1798.19  5077.1 1797.43  5104.4 1799.66  5128.8 1800.02  5204.8 1804.44
    5220 1804.34  5232.2 1806.55  5244.3 1806.63  5264.8 1808.66  5304.6 1811.91
#Mann= 5 ,-1 , 0
  4684.2      .1       0  4932.7     .07       0  4983.2     .05       0
  4987.2     .07       0  5264.8      .1       0
Bank Sta=4983.2,4987.2
XS Rating Curve= 0 ,0
Exp/Cntr=0.3,0.1

Type RM Length L Ch R = 1 ,1437    ,450,450,450
BEGIN DESCRIPTION:
Stream0515 3.0
END DESCRIPTION:
XS GIS Cut Line= 3
      1925762.62     13949950.91        1925375.       13949875.
      1925274.99     13949925.01
#Sta/Elev= 30
    4613 1847.98    4657 1836.85  4702.9 1826.71  4733.4  1821.7    4761 1819.08
  4767.1 1816.53  4782.4 1812.18  4825.2 1806.11  4843.5 1802.73  4866.3 1797.11
  4895.5  1792.5  4904.6 1789.63  4940.5 1786.06  4971.9 1785.92  4976.2 1784.22
    4978 1781.22  4978.8 1780.76  4981.4 1780.46  4983.9 1781.68  4986.5 1781.39
  4988.2 1780.14  4988.5 1779.64  4992.2 1780.14  4999.4 1785.95  5002.5 1787.03
  5009.8  1787.2  5022.1 1789.06  5048.9 1789.22  5065.7 1790.84  5119.8 1792.79
#Mann= 3 ,-1 , 0
    4613     .07       0  4988.2     .05       0  4992.2     .07       0
#XS Ineff= 2 , 0
         4971.88 1785.89
Permanent Ineff=
       F       F
Bank Sta=4988.2,4992.2
XS Rating Curve= 0 ,0
Exp/Cntr=0.3,0.1

Type RM Length L Ch R = 1 ,987     ,467,467,467
BEGIN DESCRIPTION:
Stream0515 2.0
END DESCRIPTION:
XS GIS Cut Line= 3
      1925725.01     13949675.01        1925425.       13949475.
      1925225.02       13949425.
#Sta/Elev= 30
  4639.4 1821.26  4649.7 1819.65  4671.4 1818.71  4683.9 1814.86    4711 1808.95
  4729.1 1806.02  4746.1 1801.33  4795.8 1794.72  4846.2 1790.19  4865.7 1789.54
  4894.9 1786.74  4912.9 1786.39  4951.6 1782.98    4967 1778.14  4971.7 1775.98
  4981.4 1773.56  4992.8 1771.95  4993.1 1771.45  4996.6 1771.45  4996.8 1771.95
  5008.8  1772.3  5019.5 1776.82    5027 1778.31  5050.1 1776.15  5059.1 1778.05
  5076.4 1779.74  5106.1 1782.25  5141.8 1784.03  5182.8 1790.28  5206.1 1791.66
#Mann= 6 ,-1 , 0
  4639.4     .07       0  4795.8    .035       0  4912.9     .07       0
  4981.4    .035       0  4992.8    .035       0  4996.8    .035       0
#XS Ineff= 2 , 0
                         5031.26         1777.98
Permanent Ineff=
       F       F
Bank Sta=4992.8,4996.8
XS Rating Curve= 0 ,0
Exp/Cntr=0.3,0.1

Type RM Length L Ch R = 1 ,520     ,39,39,39
BEGIN DESCRIPTION:
Stream0515 1.0
END DESCRIPTION:
XS GIS Cut Line= 4
      1925775.01     13949325.03        1925675.       13949125.
        1925475.       13949025.       1925163.7      13949043.5
#Sta/Elev= 30
  4781.9 1792.22  4811.2 1789.01  4840.6  1787.1    4863 1782.48  4885.4 1772.75
  4907.7 1768.08  4941.11767.398  4945.11767.919  4950.4 1766.29  4950.7 1765.79
  4954.4 1766.29  4969.2 1769.19  4974.8 1767.46  4991.6 1771.16  5019.5 1772.43
  5036.3 1771.07  5041.9 1773.66  5058.6 1772.44  5064.2 1775.35    5081 1774.15
  5086.6 1776.75  5103.4 1775.81    5109 1779.33  5125.7 1778.04  5131.3 1781.04
  5192.8 1778.36  5198.4 1780.09  5226.4 1776.88  5289.3 1777.16    5541 1788.64
#Mann= 4 ,-1 , 0
  4781.9     .07       0  4811.2    .035       0  4941.1    .035       0
  4945.1    .035       0
#XS Ineff= 2 , 0
                          5135.8         1781.25
Permanent Ineff=
       F       F
Bank Sta=4950.4,4954.4
XS Rating Curve= 0 ,0
Exp/Cntr=0.3,0.1

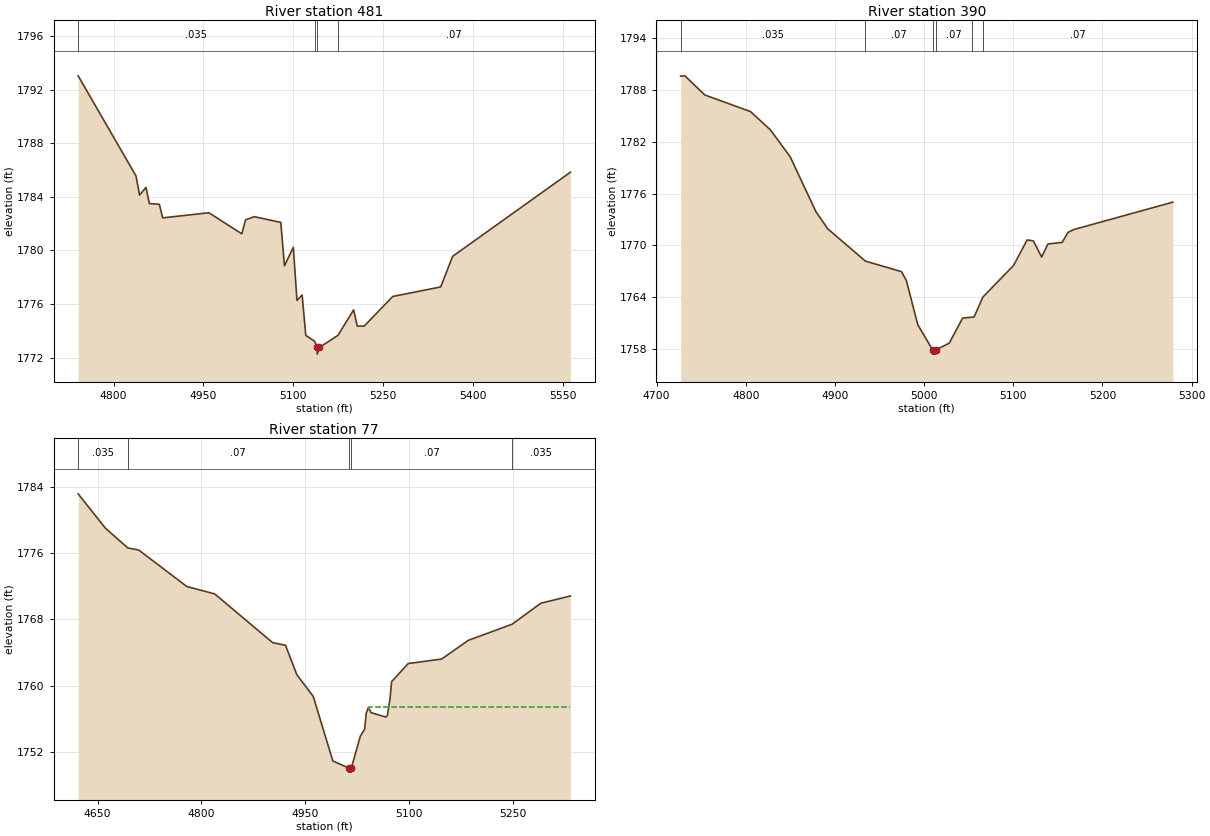
Type RM Length L Ch R = 1 ,481     ,91,91,91
BEGIN DESCRIPTION:
Stream0515 0.2
END DESCRIPTION:
XS GIS Cut Line= 4
      1925833.23     13949316.65      1925737.07     13949125.46
      1925522.81     13948971.82      1925178.37     13948973.19
#Sta/Elev= 30
  4740.8 1793.02  4837.4 1785.56  4843.4 1784.13  4854.1  1784.7  4859.7  1783.5
  4876.4 1783.44    4882 1782.43  4959.2 1782.81  5014.2 1781.24  5020.3 1782.28
  5035.1 1782.52  5079.3 1782.09  5085.4 1778.86  5100.2 1780.24  5106.3 1776.27
  5114.9 1776.68    5121 1773.67  5135.81773.228  5139.81772.781  5139.9 1772.77
  5140.2 1772.27  5143.9 1772.77  5174.7 1773.67  5200.9 1775.57    5207 1774.36
  5218.5 1774.36  5266.3 1776.57  5346.3 1777.28  5366.3 1779.56  5562.9 1785.83
#Mann= 4 ,-1 , 0
  4740.8    .035       0  5135.8    .035       0  5139.8    .035       0
  5174.7     .07       0
Bank Sta=5139.9,5143.9
XS Rating Curve= 0 ,0
Exp/Cntr=0.3,0.1

Type RM Length L Ch R = 1 ,390     ,313,313,313
BEGIN DESCRIPTION:
Stream 0515 0.1
END DESCRIPTION:
XS GIS Cut Line= 4
      1925878.54     13949275.31      1925799.82     13949059.88
      1925685.78     13948976.09      1925516.16     13948912.83
#Sta/Elev= 30
    4727 1789.55  4731.8 1789.59  4754.1 1787.38  4805.4 1785.46  4827.6 1783.36
  4849.9 1780.23  4878.7  1773.9    4892 1771.92  4934.2 1768.19  4974.6 1766.98
  4980.1 1765.96  4992.9 1760.85  5009.5 1757.95  5009.7 1757.45  5013.2 1757.45
  5013.5 1757.95  5028.2 1758.72  5043.2 1761.61  5053.3 1761.71  5056.1 1761.75
  5065.9 1764.04  5100.4  1767.7  5115.5 1770.64  5122.5 1770.53  5131.8 1768.66
  5138.8 1770.17  5154.8 1770.35  5161.2  1771.5  5167.6 1771.83  5278.9    1775
#Mann= 6 ,-1 , 0
    4727    .035       0  4934.2     .07       0  5009.5     .05       0
  5013.5     .07       0  5053.3    .035       0  5065.9     .07       0
Bank Sta=5009.5,5013.5
XS Rating Curve= 0 ,0
Exp/Cntr=0.3,0.1

Type RM Length L Ch R = 1 ,77      ,0,0,0
BEGIN DESCRIPTION:
Stream0515 0.0
END DESCRIPTION:
XS GIS Cut Line= 4
      1926045.62      13949147.8      1926005.51     13948838.93
      1925912.27     13948758.71      1925634.93     13948757.35
#Sta/Elev= 30
  4621.8 1783.13  4661.1    1779  4693.6  1776.6  4709.4 1776.35    4779 1771.95
  4819.2 1771.06  4903.1 1765.18  4921.7 1764.86    4938 1761.32  4961.8 1758.69
  4990.1 1750.91  5012.9 1750.06  5013.2 1749.56  5016.7 1749.56  5016.9 1750.06
  5029.8 1753.88  5036.2 1754.76  5038.3 1756.62  5041.6 1757.37  5045.5 1756.73
  5066.9  1756.2  5069.1 1756.43  5072.9 1758.46  5075.1 1760.47  5099.1 1762.66
  5147.5  1763.2  5186.1 1765.46  5249.4  1767.4  5290.8 1769.93  5333.6 1770.81
#Mann= 5 ,-1 , 0
  4621.8    .035       0  4693.6     .07       0  5012.9     .05       0
  5016.9     .07       0  5249.4    .035       0
#XS Ineff= 2 , 0
                         5043.06         1757.45
Permanent Ineff=
       F       F
Bank Sta=5012.9,5016.9
XS Rating Curve= 0 ,0
Exp/Cntr=0.3,0.1

Chan Stop Cuts=-1
Use User Specified Reach Order=0
Composite Channel Slope=5