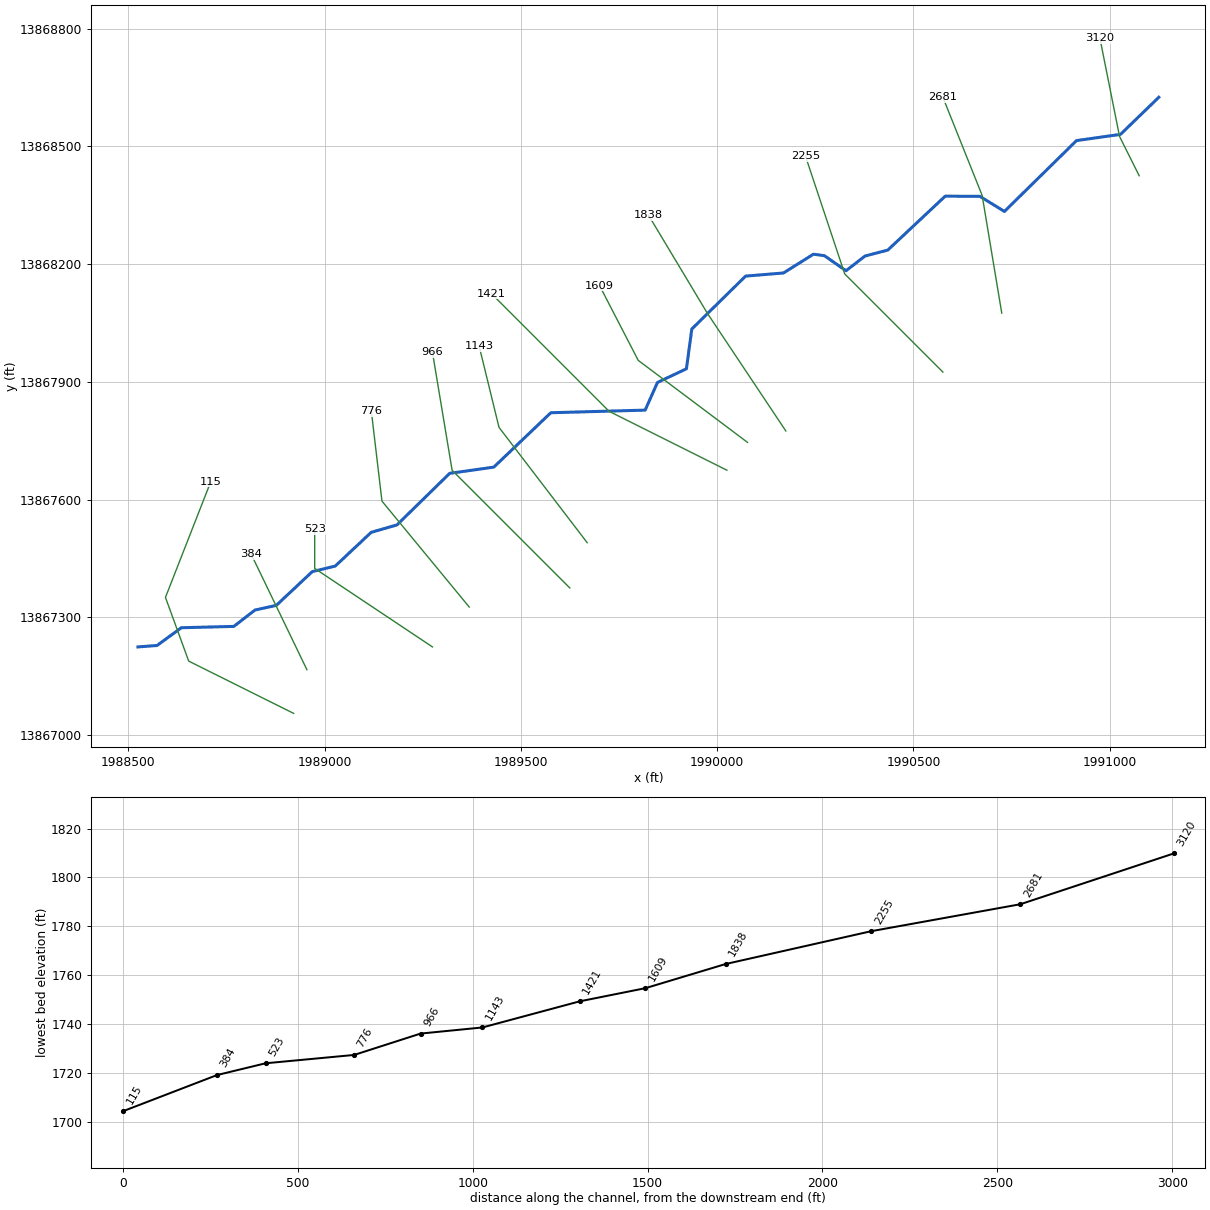
--- Stream0517.prj (project) ---

Proj Title=Stream0517 Base Level Engineering
Current Plan=p01
Default Exp/Contr=0.3,0.1
English Units
Geom File=g01
Flow File=f01
Plan File=p01
Y Axis Title=Elevation
X Axis Title(PF)=Main Channel Distance
X Axis Title(XS)=Station
BEGIN DESCRIPTION:
Stream0517
END DESCRIPTION:
DSS Export Rating Curves= 0
DSS Export Rating Curve Sorted= 0
DSS Export Volume Flow Curves= 0
DXF OffsetX= 0
DXF OffsetY= 0
DXF ScaleX= 1
DXF ScaleY= 10

--- Stream0517.p01 (plan) ---

Plan Title=Multiple Run
Short Identifier=Multiple
Geom File=g01
Flow File=f01
Subcritical Flow
K Sum by GR= 0
Std Step Tol= 0.01
Critical Tol= 0.01
Num of Std Step Trials= 20
Max Error Tol= 0.3
Flow Tol Ratio= 0.001
Split Flow NTrial= 30
Split Flow Tol= 0.02
Split Flow Ratio= 0.02
Log Output Level= 0
Friction Slope Method= 1
Unsteady Friction Slope Method= 2
Unsteady Bridges Friction Slope Method= 1
Parabolic Critical Depth
Global Vel Dist=  1 , 1 , 1
Global Log Level= 0
CheckData=True
Encroach Param= -1, 0, 0, 0
BEGIN DESCRIPTION:
Multiple Run
END DESCRIPTION:

--- Stream0517.f01 (steady flow) ---

Flow Title=Multiple
Number of Profiles=7
Profile Names=10-year,25-year,50-year,1pct_min,100-year,1pct_plu,500-year
River Rch & RM= Stream0517,Reach-1,3120
     375     601     805     525    1048    2091    1753
Boundary for River Rch & Prof#=Stream0517,Reach-1,1
Up Type=0
Dn Type=3
Dn Slope=0.005
Boundary for River Rch & Prof#=Stream0517,Reach-1,2
Up Type=0
Dn Type=3
Dn Slope=0.005
Boundary for River Rch & Prof#=Stream0517,Reach-1,3
Up Type=0
Dn Type=3
Dn Slope=0.005
Boundary for River Rch & Prof#=Stream0517,Reach-1,4
Up Type=0
Dn Type=3
Dn Slope=0.005
Boundary for River Rch & Prof#=Stream0517,Reach-1,5
Up Type=0
Dn Type=3
Dn Slope=0.005
Boundary for River Rch & Prof#=Stream0517,Reach-1,6
Up Type=0
Dn Type=3
Dn Slope=0.005
Boundary for River Rch & Prof#=Stream0517,Reach-1,7
Up Type=0
Dn Type=3
Dn Slope=0.005

--- Stream0517.g01 (geometry) ---

Geom Title=Existing Conditions
Program Version=4.10

River Reach=Stream0517      ,Reach-1
Reach XY= 30
        1991125.       13868625.      1991027.45     13868530.46
      1990915.21     13868514.48      1990731.74     13868334.13
      1990669.11     13868372.63      1990580.89     13868373.03
      1990434.68     13868235.75      1990376.65     13868220.55
      1990328.31     13868183.07      1990273.36     13868221.39
      1990245.21     13868225.21      1990169.03     13868177.38
      1990072.57     13868169.48      1989935.53     13868034.75
      1989921.81     13867933.35      1989848.06     13867898.63
      1989816.69     13867828.09      1989576.46     13867821.46
      1989431.17     13867682.86      1989318.83     13867667.14
      1989184.68     13867535.78      1989118.96     13867516.82
      1989027.28     13867430.87      1988968.96     13867416.82
      1988877.29     13867330.84      1988822.83     13867318.86
      1988769.07     13867277.25      1988635.47     13867273.87
      1988573.49     13867228.65        1988525.       13867225.

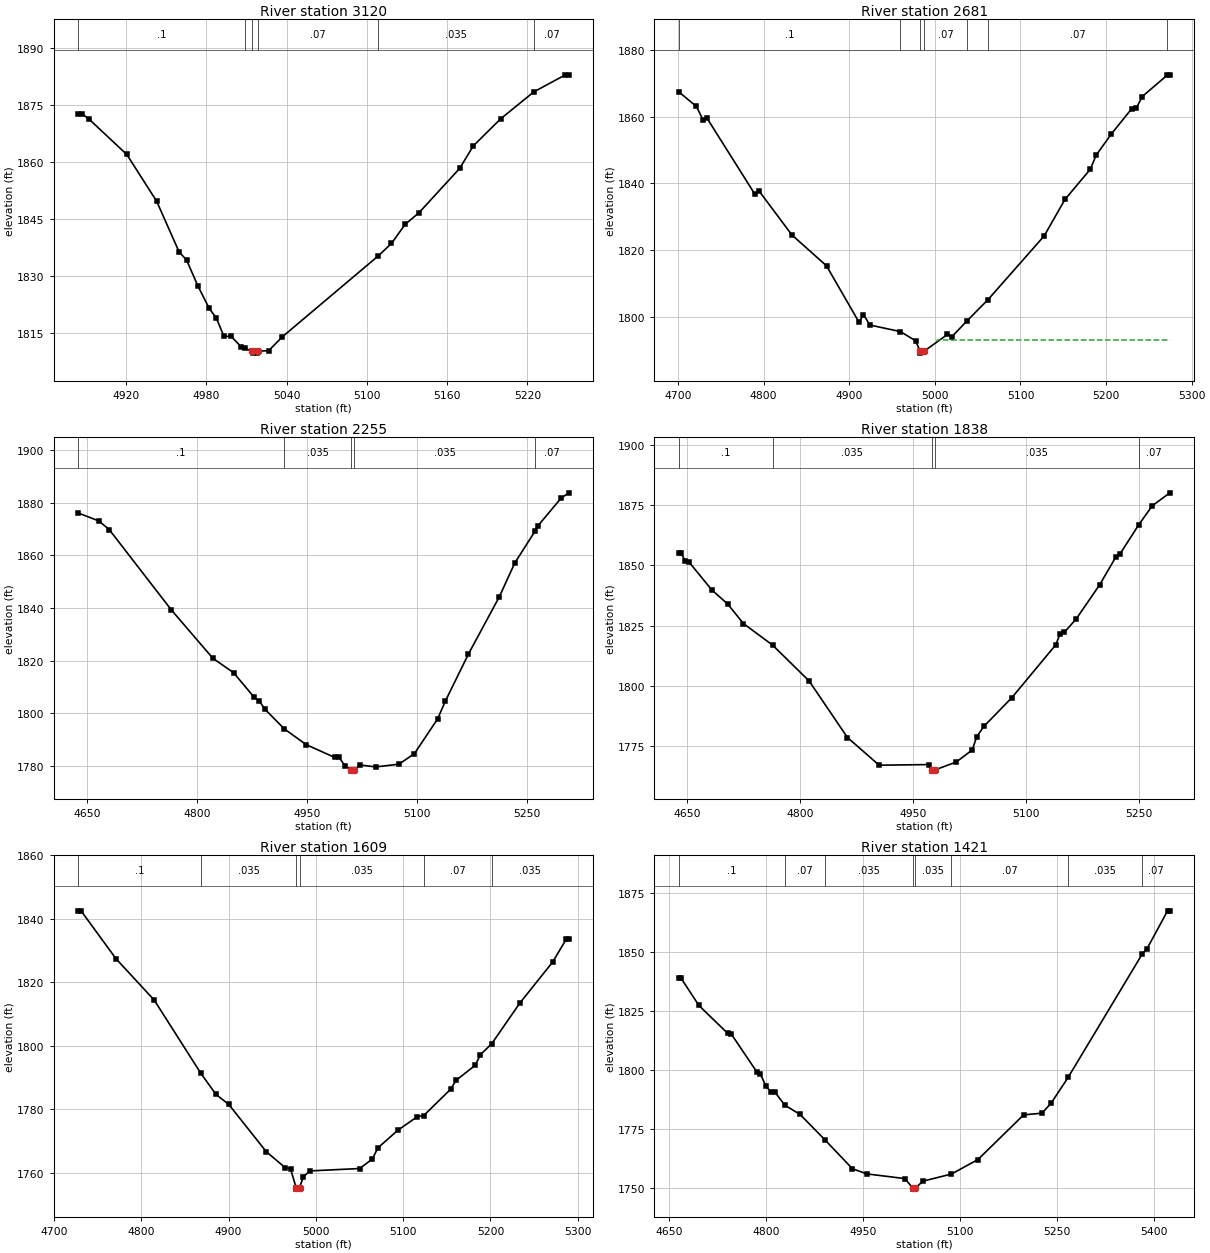
Type RM Length L Ch R = 1 ,3120    ,439,439,439
BEGIN DESCRIPTION:
Stream0517 7.0
END DESCRIPTION:
XS GIS Cut Line= 3
      1991075.01     13868424.99        1991025.       13868525.
      1990974.99     13868775.03
#Sta/Elev= 30
  4884.2  1872.7    4887  1872.7  4892.6 1871.17  4920.6 1861.96  4942.9 1849.71
  4959.7  1836.4  4965.3 1834.25  4973.7 1827.49    4982 1821.69  4987.6 1818.97
  4993.2 1814.24  4998.6 1814.24  5006.2 1811.43  5008.9 1811.07  5014.4 1810.33
  5014.7 1809.83  5018.2 1809.83  5018.4 1810.33  5026.6 1810.47  5036.8 1814.09
  5108.6 1835.37  5118.4 1838.61  5128.6 1843.62  5138.8 1846.61  5169.4 1858.32
  5179.6 1864.24    5200 1871.32  5224.8  1878.4  5248.4 1882.87    5251 1882.87
#Mann= 6 ,-1 , 0
  4884.2      .1       0  5008.9     .07       0  5014.4     .05       0
  5018.4     .07       0  5108.6    .035       0  5224.8     .07       0
Bank Sta=5014.4,5018.4
XS Rating Curve= 0 ,0
Exp/Cntr=0.3,0.1

Type RM Length L Ch R = 1 ,2681    ,426,426,426
BEGIN DESCRIPTION:
Stream0517 6.0
END DESCRIPTION:
XS GIS Cut Line= 3
        1990725.       13868075.        1990675.       13868375.
        1990575.     13868625.01
#Sta/Elev= 30
  4701.1 1867.43  4721.4 1863.11    4729 1859.16    4734  1859.5  4789.8 1836.73
  4794.9 1837.64  4832.9 1824.56  4873.4 1815.27  4911.5 1798.29  4916.5 1800.66
  4924.1  1797.5  4959.8 1795.53  4977.4 1792.78    4983 1789.57  4983.2 1789.07
    4987 1789.57  5014.7 1794.67    5020 1794.03  5037.7 1798.79    5062  1805.1
  5127.7 1824.25    5152  1835.2  5181.6 1844.26  5188.3 1848.42  5205.8 1854.73
  5230.1 1862.47  5235.4 1862.62  5242.2 1866.07  5271.3 1872.47  5274.5  1872.6
#Mann= 7 ,-1 , 0
  4701.1      .1       0  4959.8     .07       0    4983     .05       0
    4987     .07       0  5037.7    .035       0    5062     .07       0
  5271.3    .035       0
#XS Ineff= 2 , 0
                         5002.62         1792.97
Permanent Ineff=
       F       F
Bank Sta=4983,4987
XS Rating Curve= 0 ,0
Exp/Cntr=0.3,0.1

Type RM Length L Ch R = 1 ,2255    ,417,417,417
BEGIN DESCRIPTION:
Stream0517 5.0
END DESCRIPTION:
XS GIS Cut Line= 3
      1990575.02     13867924.98        1990325.       13868175.
        1990225.     13868474.99
#Sta/Elev= 30
    4638 1876.16  4666.3 1873.12  4680.5 1869.84  4765.3 1839.31  4821.9 1820.95
  4850.2 1815.47  4878.4 1806.09  4885.5 1804.64  4892.6 1801.71  4919.2 1794.17
  4949.2 1788.15    4988  1783.3  4994.2  1783.3  5002.1 1780.06  5010.7 1778.57
  5010.9 1778.07  5014.7 1778.57  5023.2 1780.38  5044.3 1779.67  5075.9 1780.71
    5097 1784.72  5128.6 1797.88  5139.2 1804.66  5170.8  1822.6  5212.9 1844.32
    5234 1857.18  5261.7 1869.26  5265.6 1871.28  5297.3 1881.83  5307.8  1883.8
#Mann= 5 ,-1 , 0
    4638      .1       0  4919.2    .035       0  5010.7    .035       0
  5014.7    .035       0  5261.7     .07       0
Bank Sta=5010.7,5014.7
XS Rating Curve= 0 ,0
Exp/Cntr=0.3,0.1

Type RM Length L Ch R = 1 ,1838    ,229,229,229
BEGIN DESCRIPTION:
Stream0517 4.0
END DESCRIPTION:
XS GIS Cut Line= 3
      1990174.99     13867775.01        1989975.       13868075.
      1989824.99     13868325.01
#Sta/Elev= 30
  4639.2 1855.16  4642.2 1855.16  4646.7 1851.99  4652.7  1851.3  4682.8 1839.77
  4703.8 1833.97  4724.8 1825.84  4763.6 1816.89    4812 1802.05    4863 1778.58
  4905.1  1767.1  4971.2 1767.36  4975.2 1765.14  4975.5 1764.64  4979.2 1765.14
  5007.5 1768.41  5028.9 1773.46  5034.7 1778.93  5044.4 1783.24  5081.4 1795.11
  5139.7 1817.02  5145.5 1821.53  5151.3 1822.27  5166.9 1827.78    5198 1841.89
  5219.4 1853.39  5225.2 1854.76  5249.9 1866.79    5268 1874.72  5291.3 1880.08
#Mann= 5 ,-1 , 0
  4639.2      .1       0  4763.6    .035       0  4975.2    .035       0
  4979.2    .035       0  5249.9     .07       0
Bank Sta=4975.2,4979.2
XS Rating Curve= 0 ,0
Exp/Cntr=0.3,0.1

Type RM Length L Ch R = 1 ,1609    ,188,188,188
BEGIN DESCRIPTION:
Mapping XS a1d92b2d
END DESCRIPTION:
XS GIS Cut Line= 3
       1990077.4     13867745.95      1989799.07     13867954.83
      1989700.65     13868145.08
#Sta/Elev= 30
  4727.6 1842.53    4731 1842.53    4771 1827.44  4814.8 1814.39  4868.2 1791.31
  4885.6 1784.63  4900.2  1781.5  4943.1 1766.62  4964.7 1761.58    4971 1761.17
  4977.3 1755.29  4977.6 1754.79  4981.3 1755.29  4985.6 1758.68  4993.2 1760.53
  5050.2 1761.29  5064.7  1764.3    5071 1767.79    5094 1773.38  5116.1 1777.62
  5123.5 1777.98  5154.6 1786.35  5160.4 1789.05  5182.6 1793.87  5188.4 1797.17
  5201.4 1800.62  5233.4 1813.37  5271.1 1826.35  5286.9 1833.62  5289.8 1833.62
#Mann= 6 ,-1 , 0
  4727.6      .1       0  4868.2    .035       0  4977.3    .035       0
  4981.3    .035       0  5123.5     .07       0  5201.4    .035       0
#XS Ineff= 2 , 0
                         4993.38         1760.48
Permanent Ineff=
       F       F
Bank Sta=4977.3,4981.3
XS Rating Curve= 0 ,0
Exp/Cntr=0.3,0.1

Type RM Length L Ch R = 1 ,1421    ,278,278,278
BEGIN DESCRIPTION:
Stream0517 3.0
END DESCRIPTION:
XS GIS Cut Line= 3
      1990025.03     13867674.99        1989725.       13867825.
        1989425.       13868125.
#Sta/Elev= 30
  4664.8 1838.88  4667.6 1838.88  4695.6 1827.17  4740.3 1815.34  4745.9    1815
    4785 1799.13  4790.6 1798.25    4799  1793.2  4807.4 1790.37    4813 1790.58
  4828.5 1784.97  4852.1 1781.05  4890.2 1770.42  4933.2 1758.04  4955.5 1755.86
  5014.4 1753.87  5026.5 1749.91  5026.8 1749.41  5030.5 1749.91  5042.7 1752.81
  5086.4 1755.79  5127.5 1761.94  5198.2 1780.86  5226.5 1781.57  5240.7 1785.78
  5267.4 1796.87    5382 1849.06  5389.2 1851.21    5421 1867.26  5424.5 1867.26
#Mann= 8 ,-1 , 0
  4664.8      .1       0  4828.5     .07       0  4890.2    .035       0
  5026.5    .035       0  5030.5    .035       0  5086.4     .07       0
  5267.4    .035       0    5382     .07       0
Bank Sta=5026.5,5030.5
XS Rating Curve= 0 ,0
Exp/Cntr=0.3,0.1

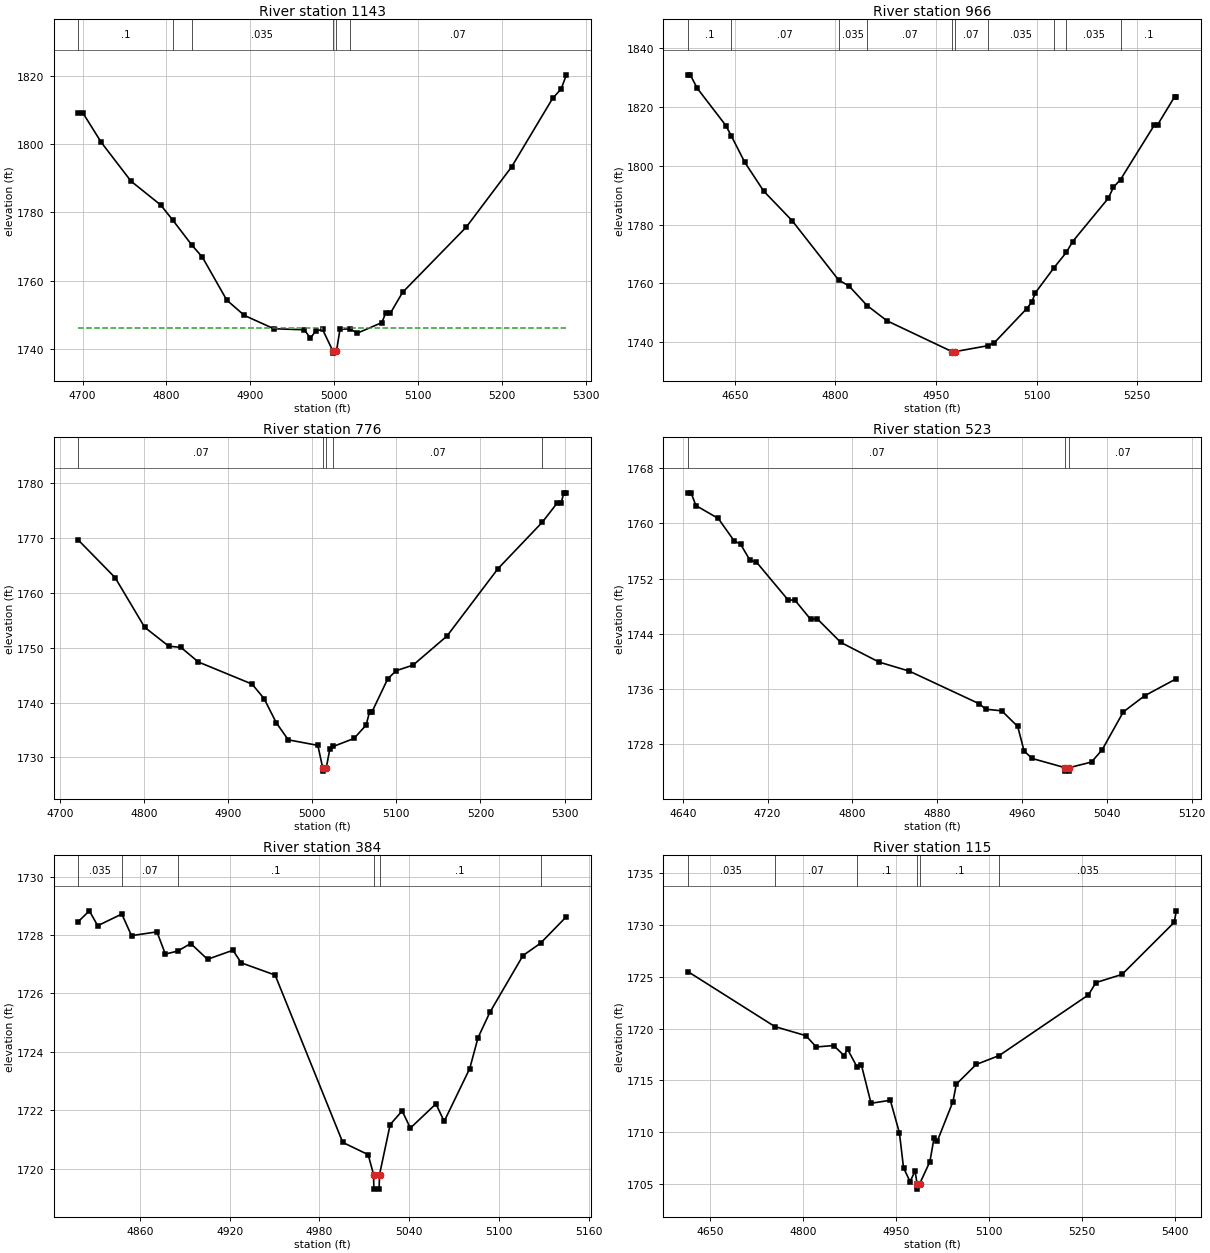
Type RM Length L Ch R = 1 ,1143    ,177,177,177
BEGIN DESCRIPTION:
Mapping XS 71941dcf
END DESCRIPTION:
XS GIS Cut Line= 3
      1989669.03     13867490.52      1989444.48     13867784.14
      1989393.89     13867991.01
#Sta/Elev= 30
  4694.5 1809.16  4700.4 1809.16  4722.4 1800.51  4757.8 1789.16  4793.1  1782.2
  4807.4 1777.81  4830.2 1770.47    4843 1766.84    4872 1754.29  4892.9 1749.81
  4928.2 1745.89  4964.5 1745.59  4971.8 1743.11  4978.1 1745.25  4986.3 1745.67
  4998.8 1739.24  4999.1 1738.74  5002.8 1739.24  5007.1  1745.8  5019.1  1745.8
  5027.9 1744.62    5057 1747.69  5061.5 1750.46  5067.2 1750.46  5081.7 1756.56
  5157.7  1775.7  5211.8 1793.37  5260.6 1813.41  5270.9 1816.23  5277.1 1820.35
#Mann= 6 ,-1 , 0
  4694.5      .1       0  4807.4     .07       0  4830.2    .035       0
  4998.8    .035       0  5002.8    .035       0  5019.1     .07       0
#XS Ineff= 2 , 0
         4985.61  1746.1 5011.06         1746.03
Permanent Ineff=
       F       F
Bank Sta=4998.8,5002.8
XS Rating Curve= 0 ,0
Exp/Cntr=0.3,0.1

Type RM Length L Ch R = 1 ,966     ,190,190,190
BEGIN DESCRIPTION:
Stream0517 2.0
END DESCRIPTION:
XS GIS Cut Line= 3
        1989625.       13867375.        1989325.       13867675.
        1989275.       13867975.
#Sta/Elev= 30
  4580.1 1830.95  4583.6 1830.95  4594.2 1826.32  4636.7 1813.69  4644.7 1810.21
    4665 1801.15  4693.2 1791.36  4735.7 1781.27  4804.7 1761.17  4820.5 1759.05
  4847.3 1752.43  4877.1 1747.23  4974.1 1736.74  4974.3 1736.24  4978.1 1736.74
  5026.9 1738.74  5037.3 1739.84  5085.5  1751.4  5093.1 1753.68  5098.1 1756.72
  5126.1 1765.32  5144.5 1770.54  5153.9 1774.22  5207.1 1788.97  5214.7 1792.69
  5225.3 1795.32  5275.6 1813.82  5280.6 1813.96    5306 1823.51  5308.5 1823.51
#Mann= 10 ,-1 , 0
  4580.1      .1       0  4644.7     .07       0  4804.7    .035       0
  4847.3     .07       0  4974.1     .05       0  4978.1     .07       0
  5026.9    .035       0  5126.1      .1       0  5144.5    .035       0
  5225.3      .1       0
Bank Sta=4974.1,4978.1
XS Rating Curve= 0 ,0
Exp/Cntr=0.3,0.1

Type RM Length L Ch R = 1 ,776     ,253,253,253
BEGIN DESCRIPTION:
Mapping XS 95bd9c55
END DESCRIPTION:
XS GIS Cut Line= 3
      1989368.61     13867326.57      1989146.32     13867596.38
      1989119.25     13867825.91
#Sta/Elev= 30
  4721.5 1769.73  4765.7 1762.81  4800.8 1753.76  4829.5  1750.3  4843.8  1750.1
  4864.7 1747.42  4928.5 1743.39  4942.8 1740.74  4957.2 1736.36  4971.5 1733.22
  5006.7 1732.21  5012.6 1728.01  5012.8 1727.51  5016.6 1728.01    5021 1731.58
    5025 1732.01  5049.7 1733.47  5064.1 1735.91  5068.2 1738.33  5071.1 1738.33
  5089.8 1744.35  5099.9 1745.84    5120 1746.86  5160.3 1752.17  5220.7 1764.42
  5273.7 1772.95    5291 1776.38    5296  1776.5  5299.2 1778.29  5302.2 1778.29
#Mann= 5 ,-1 , 0
  4721.5     .07       0  5012.6     .05       0  5016.6     .07       0
    5025     .07       0  5273.7    .035       0
Bank Sta=5012.6,5016.6
XS Rating Curve= 0 ,0
Exp/Cntr=0.3,0.1

Type RM Length L Ch R = 1 ,523     ,139,139,139
BEGIN DESCRIPTION:
Stream0517 1.0
END DESCRIPTION:
XS GIS Cut Line= 3
      1989275.01     13867224.99        1988975.       13867425.
        1988975.     13867525.03
#Sta/Elev= 30
  4644.9 1764.44  4647.9 1764.44  4652.4  1762.6  4673.5 1760.73  4688.5 1757.48
  4694.5 1757.01  4703.5 1754.65  4709.5 1754.41  4739.6 1748.87  4745.6 1748.93
  4760.6 1746.11  4766.6 1746.22  4789.1 1742.76  4825.2 1739.91  4853.7  1738.6
  4919.8 1733.86  4925.8 1733.08  4940.9 1732.85  4955.9 1730.58  4961.9 1727.04
  4969.4 1725.95  5000.5 1724.61  5000.7 1724.11  5004.2 1724.11  5004.5 1724.61
  5025.5 1725.43  5035.5 1727.19  5055.5 1732.69  5075.5 1735.02  5105.5  1737.5
#Mann= 3 ,-1 , 0
  4644.9     .07       0  5000.5     .05       0  5004.5     .07       0
Bank Sta=5000.5,5004.5
XS Rating Curve= 0 ,0
Exp/Cntr=0.3,0.1

Type RM Length L Ch R = 1 ,384     ,269,269,269
BEGIN DESCRIPTION:
Mapping XS 9d4f4d84
END DESCRIPTION:
XS GIS Cut Line= 2
      1988955.16       13867167.      1988813.31     13867461.08
#Sta/Elev= 30
  4818.6 1728.45  4826.2 1728.83  4831.8 1728.32  4847.9 1728.72  4854.4 1727.98
  4871.4 1728.11    4877 1727.35  4885.2 1727.45    4894 1727.71  4905.2 1727.17
  4922.2 1727.48  4927.7 1727.05  4950.4 1726.63  4995.6  1720.9  5012.6 1720.48
  5016.2  1719.8  5016.4  1719.3  5019.9  1719.3  5020.2  1719.8  5027.3 1721.51
  5035.3 1721.98  5040.8 1721.39  5057.9 1722.22  5063.4 1721.62  5080.5 1723.43
    5086 1724.48  5093.9 1725.35  5116.1  1727.3  5127.8 1727.72  5145.1 1728.63
#Mann= 6 ,-1 , 0
  4818.6    .035       0  4847.9     .07       0  4885.2      .1       0
  5016.2     .05       0  5020.2      .1       0  5127.8     .07       0
Bank Sta=5016.2,5020.2
XS Rating Curve= 0 ,0
Exp/Cntr=0.3,0.1

Type RM Length L Ch R = 1 ,115     ,0,0,0
BEGIN DESCRIPTION:
Stream0517 0.0
END DESCRIPTION:
XS GIS Cut Line= 4
      1988921.37     13867055.73      1988654.17     13867188.84
       1988594.9     13867351.09      1988710.26     13867645.65
#Sta/Elev= 30
  4614.7  1725.5  4754.8  1720.2  4804.9 1719.32  4821.7 1718.23  4849.7 1718.37
  4866.5  1717.4  4872.1 1718.01  4887.3 1716.32  4894.5 1716.48    4910  1712.8
  4941.1 1713.09  4955.8 1709.94  4962.4 1706.58    4973 1705.24    4981 1706.28
  4984.3 1705.02  4984.6 1704.52  4988.3 1705.02  5004.9 1707.17  5011.5 1709.42
  5016.9 1709.16  5042.1 1712.96  5047.5 1714.64  5079.5 1716.54  5116.6  1717.4
  5260.5 1723.25  5272.7 1724.44  5314.8 1725.23  5398.9 1730.25  5402.3 1731.36
#Mann= 6 ,-1 , 0
  4614.7    .035       0  4754.8     .07       0  4887.3      .1       0
  4984.3     .05       0  4988.3      .1       0  5116.6    .035       0
Bank Sta=4984.3,4988.3
XS Rating Curve= 0 ,0
Exp/Cntr=0.3,0.1

Chan Stop Cuts=-1
Use User Specified Reach Order=0
Composite Channel Slope=5