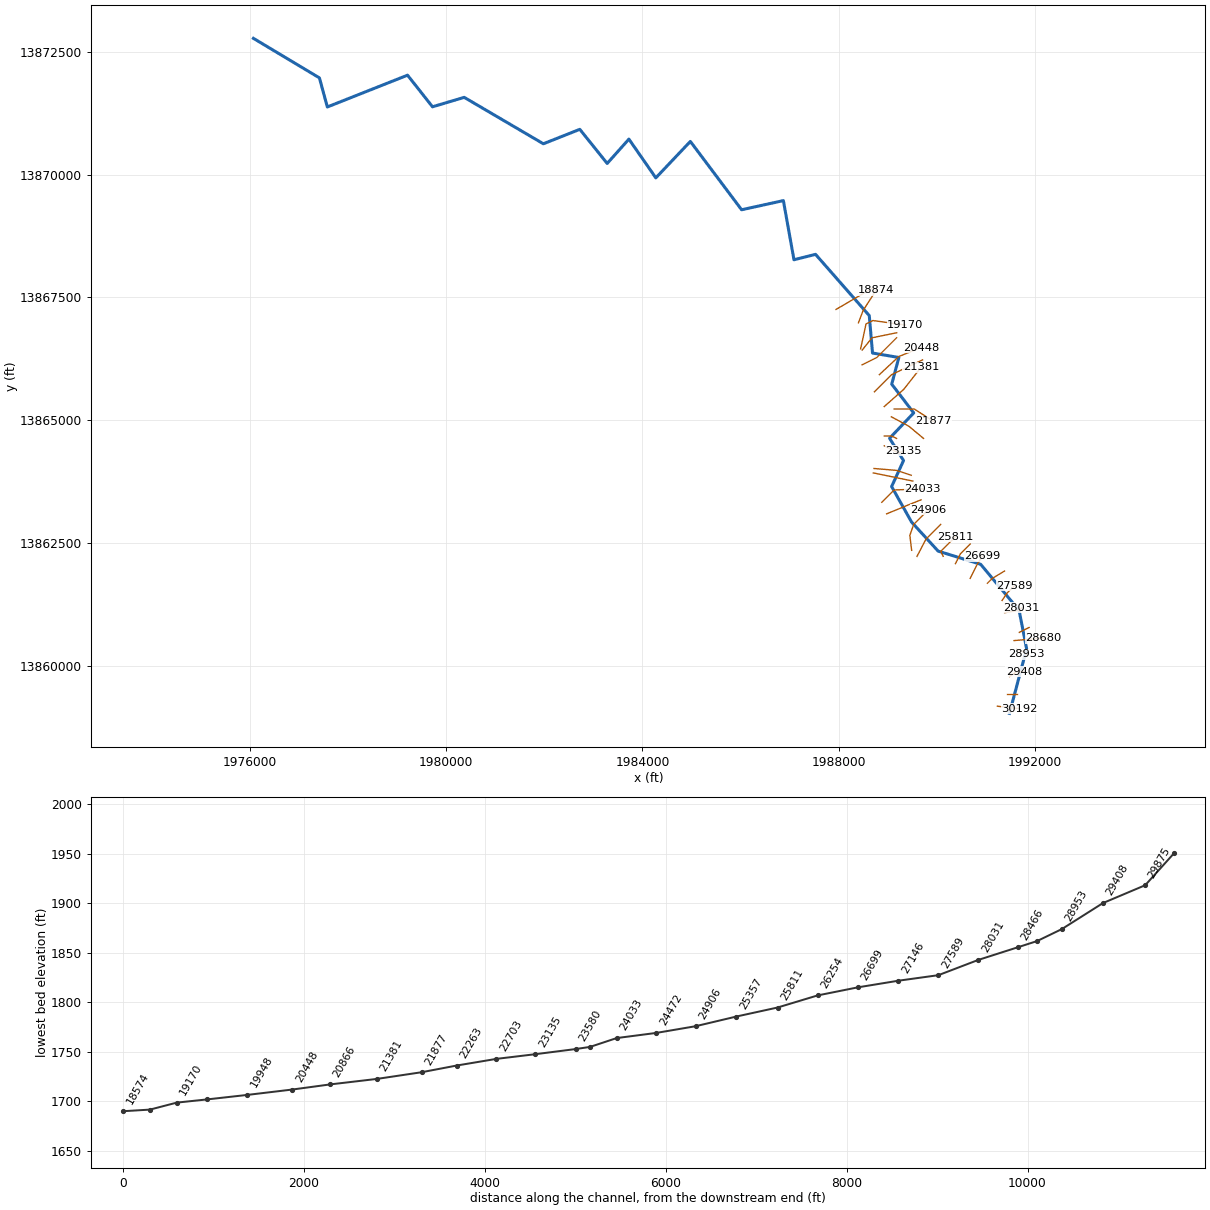
--- Stream0518.prj (project) ---

Proj Title=Stream0518 Base Level Engineering
Current Plan=p01
Default Exp/Contr=0.3,0.1
English Units
Geom File=g01
Flow File=f01
Plan File=p01
Y Axis Title=Elevation
X Axis Title(PF)=Main Channel Distance
X Axis Title(XS)=Station
BEGIN DESCRIPTION:
Stream0518
END DESCRIPTION:
DSS Export Rating Curves= 0
DSS Export Rating Curve Sorted= 0
DSS Export Volume Flow Curves= 0
DXF OffsetX= 0
DXF OffsetY= 0
DXF ScaleX= 1
DXF ScaleY= 10

--- Stream0518.p01 (plan) ---

Plan Title=Multiple Run
Short Identifier=Multiple
Geom File=g01
Flow File=f01
Subcritical Flow
K Sum by GR= 0
Std Step Tol= 0.01
Critical Tol= 0.01
Num of Std Step Trials= 20
Max Error Tol= 0.3
Flow Tol Ratio= 0.001
Split Flow NTrial= 30
Split Flow Tol= 0.02
Split Flow Ratio= 0.02
Log Output Level= 0
Friction Slope Method= 1
Unsteady Friction Slope Method= 2
Unsteady Bridges Friction Slope Method= 1
Parabolic Critical Depth
Global Vel Dist=  1 , 1 , 1
Global Log Level= 0
CheckData=True
Encroach Param= -1, 0, 0, 0
BEGIN DESCRIPTION:
Multiple Run
END DESCRIPTION:

--- Stream0518.f01 (steady flow) ---

Flow Title=Multiple
Number of Profiles=7
Profile Names=10-year,25-year,50-year,1pct_min,100-year,1pct_plu,500-year
River Rch & RM= Stream0518,Reach-1,30192
     316     499     664     431     860    1715    1419
River Rch & RM= Stream0518,Reach-1,28466
    1649    2894    4117    2837    5660   11294   10593
River Rch & RM= Stream0518,Reach-1,21381
    1617    2824    4005    2750    5486   10947   10195
River Rch & RM= Stream0518,Reach-1,18874
    1769    3106    4421    3045    6075   12122   11364
River Rch & RM= Stream0518,Reach-1,18574
    2193    3888    5567    3854    7691   15345   14541
River Rch & RM= Stream0518,Reach-1,15899
    2542    4518    6482    4491    8962   17881   16977
River Rch & RM= Stream0518,Reach-1,8663
    3000    5370    7738    5383   10741   21432   20511
River Rch & RM= Stream0518,Reach-1,6403
    3369    6047    8730    6081   12132   24207   23227
Boundary for River Rch & Prof#=Stream0518,Reach-1,1
Up Type=0
Dn Type=3
Dn Slope=0.005
Boundary for River Rch & Prof#=Stream0518,Reach-1,2
Up Type=0
Dn Type=3
Dn Slope=0.005
Boundary for River Rch & Prof#=Stream0518,Reach-1,3
Up Type=0
Dn Type=3
Dn Slope=0.005
Boundary for River Rch & Prof#=Stream0518,Reach-1,4
Up Type=0
Dn Type=3
Dn Slope=0.005
Boundary for River Rch & Prof#=Stream0518,Reach-1,5
Up Type=0
Dn Type=3
Dn Slope=0.005
Boundary for River Rch & Prof#=Stream0518,Reach-1,6
Up Type=0
Dn Type=3
Dn Slope=0.005
Boundary for River Rch & Prof#=Stream0518,Reach-1,7
Up Type=0
Dn Type=3
Dn Slope=0.005

--- Stream0518.g01 (geometry) ---

Geom Title=Existing Conditions
Program Version=4.10

River Reach=Stream0518      ,Reach-1
Reach XY= 30
        1991475.       13859025.      1991824.62     13860340.16
      1991671.18     13861123.42      1990888.32     13862061.63
      1990022.27     13862330.35      1989480.52     13862922.56
      1989074.94     13863644.99      1989317.51     13864174.97
      1989032.83     13864628.27      1989524.93     13865145.03
      1989077.05     13865730.84      1989221.91     13866273.83
      1988685.48      13866365.2      1988619.54     13867127.45
        1987525.       13868375.      1987085.63     13868264.94
      1986869.83     13869469.59      1986018.67     13869283.06
        1984975.       13870675.      1984271.68     13869933.04
      1983723.37     13870721.88      1983281.05     13870226.59
      1982723.42     13870921.33      1981980.92     13870627.23
      1980369.07     13871572.76      1979722.55     13871380.45
      1979214.45      13872024.5      1977580.84     13871377.05
      1977419.41     13871969.39        1976075.       13872775.

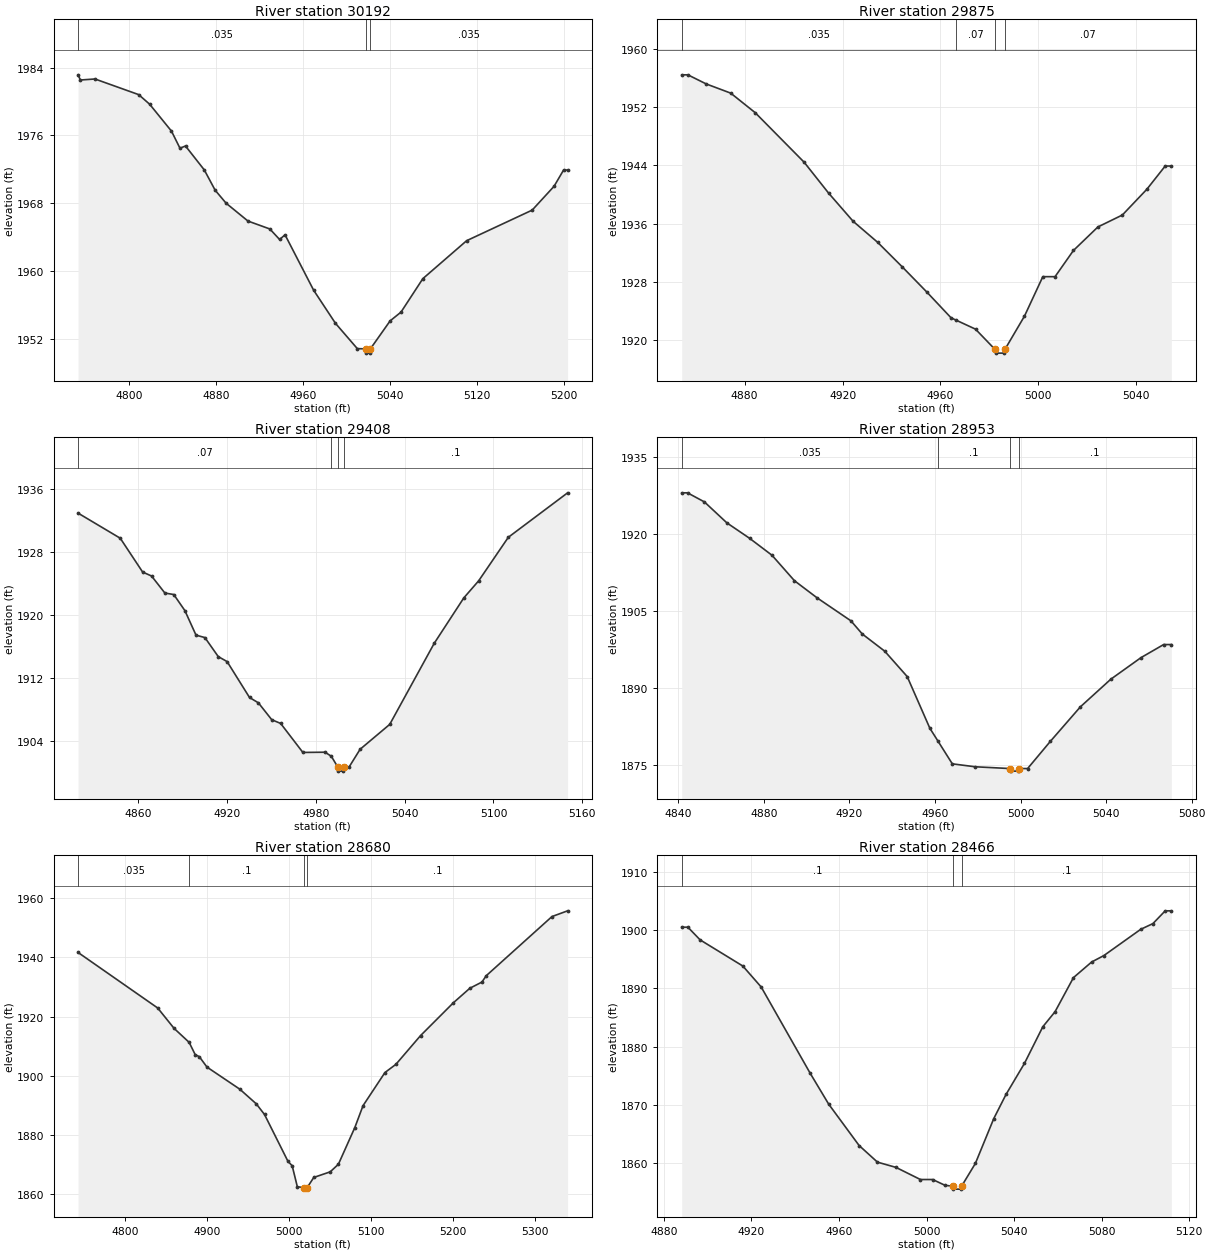
Type RM Length L Ch R = 1 ,30192   ,317,317,317
BEGIN DESCRIPTION:
Stream0518 62.0
END DESCRIPTION:
XS GIS Cut Line= 2
      1991229.51     13859170.43      1991677.38     13859121.82
#Sta/Elev= 30
  4753.1 1983.14  4755.3 1982.53  4768.7 1982.65  4808.9 1980.81    4819 1979.68
  4839.1 1976.51  4846.9  1974.5    4852 1974.76  4869.3 1971.94  4879.3 1969.55
  4889.4 1968.02  4909.5 1965.92  4929.6 1964.99  4938.6 1963.75  4943.6  1964.3
  4969.9 1957.78    4990 1953.88  5010.1  1950.9  5018.1 1950.87  5018.4 1950.37
  5021.9 1950.37  5022.1 1950.87  5040.3 1954.17  5050.3  1955.2  5070.4 1959.14
  5110.7 1963.61    5171 1967.21  5191.1 1970.01  5199.9 1971.93  5203.6 1971.93
#Mann= 3 ,-1 , 0
  4753.1    .035       0  5018.1    .035       0  5022.1    .035       0
Bank Sta=5018.1,5022.1
XS Rating Curve= 0 ,0
Exp/Cntr=0.3,0.1

Type RM Length L Ch R = 1 ,29875   ,467,467,467
BEGIN DESCRIPTION:
Stream0518 61.0
END DESCRIPTION:
XS GIS Cut Line= 3
      1991425.03       13859425.        1991575.       13859425.
      1991625.03       13859425.
#Sta/Elev= 27
  4854.3 1956.41  4856.8 1956.41  4864.3 1955.16  4874.3  1953.9  4884.3 1951.22
  4904.3 1944.42  4914.3 1940.18  4924.3 1936.32  4934.3 1933.44  4944.3 1930.09
  4954.3 1926.65  4964.3 1923.08  4966.2 1922.78  4974.3 1921.52  4982.3 1918.73
  4982.5 1918.23    4986 1918.23  4986.3 1918.73  4994.3  1923.3  5001.8 1928.72
  5006.8 1928.72  5014.3 1932.31  5024.3 1935.54  5034.3 1937.18  5044.3 1940.71
  5051.8  1943.9  5054.3  1943.9
#Mann= 4 ,-1 , 0
  4854.3    .035       0  4966.2     .07       0  4982.3     .05       0
  4986.3     .07       0
Bank Sta=4982.3,4986.3
XS Rating Curve= 0 ,0
Exp/Cntr=0.3,0.1

Type RM Length L Ch R = 1 ,29408   ,455,455,455
BEGIN DESCRIPTION:
Stream0518 60.0
END DESCRIPTION:
XS GIS Cut Line= 3
      1991475.01       13859775.        1991625.       13859875.
      1991775.03       13859875.
#Sta/Elev= 30
  4819.7 1932.93  4848.2 1929.74  4863.3 1925.45  4869.3 1924.95  4878.3 1922.79
  4884.3  1922.6  4891.8 1920.56  4899.3 1917.45  4905.3 1917.14  4914.3 1914.73
  4920.3 1914.09  4935.4 1909.54  4941.4 1908.86  4950.4 1906.72  4956.4 1906.25
  4971.4 1902.57  4986.4  1902.6  4990.6 1902.08    4995  1900.7  4995.2  1900.2
  4998.7  1900.2    4999  1900.7  5002.5  1900.7    5010 1902.97    5030 1906.13
    5060 1916.41    5080 1922.18    5090 1924.34    5110 1929.86    5150  1935.5
#Mann= 4 ,-1 , 0
  4819.7     .07       0  4990.6      .1       0    4995     .05       0
    4999      .1       0
Bank Sta=4995,4999
XS Rating Curve= 0 ,0
Exp/Cntr=0.3,0.1

Type RM Length L Ch R = 1 ,28953   ,273,273,273
BEGIN DESCRIPTION:
Stream0518 59.0
END DESCRIPTION:
XS GIS Cut Line= 3
      1991624.96     13860325.01        1991775.       13860275.
      1991825.02     13860224.98
#Sta/Elev= 28
  4841.6 1928.09  4844.3 1928.09  4852.2 1926.32  4862.7 1922.24  4873.3 1919.24
  4883.8 1915.93  4894.3 1910.97  4904.9 1907.63  4920.7 1903.16    4926  1900.6
  4936.5 1897.25    4947 1892.31  4957.6 1882.24  4961.3  1879.8  4968.1 1875.31
  4978.7 1874.74  4995.1 1874.39  4995.4 1873.89  4998.9 1873.89  4999.1 1874.39
  4999.8 1874.39  5003.3 1874.39  5013.9 1879.67    5028 1886.42  5042.2 1891.79
  5056.3 1895.99  5066.9 1898.54  5070.5 1898.54
#Mann= 4 ,-1 , 0
  4841.6    .035       0  4961.3      .1       0  4995.1     .05       0
  4999.1      .1       0
Bank Sta=4995.1,4999.1
XS Rating Curve= 0 ,0
Exp/Cntr=0.3,0.1

Type RM Length L Ch R = 1 ,28680   ,214,214,214
BEGIN DESCRIPTION:
Mapping XS 0c88fe7c
END DESCRIPTION:
XS GIS Cut Line= 2
      1991567.99     13860507.66      1992164.08       13860559.
#Sta/Elev= 30
    4742 1941.62  4839.4 1922.88  4859.4 1916.01  4877.8  1911.3  4885.2 1907.16
  4890.2 1906.48  4899.6 1902.96  4939.7 1895.51  4959.8 1890.58  4969.9 1886.98
  4998.6 1871.16  5003.7  1869.7    5010 1862.62    5018 1862.31  5018.3 1861.81
    5022 1862.31  5030.1 1865.75  5050.2 1867.64  5060.2  1870.2  5080.3 1882.59
  5090.3 1889.95  5117.1 1901.13  5130.4 1903.87  5160.6 1913.58  5200.7 1924.65
  5220.8 1929.54  5235.6 1931.63  5240.9 1933.78  5321.2 1953.72  5340.3 1955.65
#Mann= 4 ,-1 , 0
    4742    .035       0  4877.8      .1       0    5018     .05       0
    5022      .1       0
Bank Sta=5018,5022
XS Rating Curve= 0 ,0
Exp/Cntr=0.3,0.1

Type RM Length L Ch R = 1 ,28466   ,435,435,435
BEGIN DESCRIPTION:
Stream0518 58.0
END DESCRIPTION:
XS GIS Cut Line= 3
      1991675.02     13860675.01        1991775.       13860725.
      1991875.01     13860775.01
#Sta/Elev= 30
  4888.2 1900.49    4891 1900.49  4896.6 1898.31  4916.1 1893.82  4924.5 1890.21
  4946.9 1875.38  4955.3 1870.11  4969.2    1863  4977.6 1860.14    4986 1859.25
  4997.2 1857.16  5002.8 1857.16  5008.4 1856.17    5012 1856.01  5012.2 1855.51
  5015.7 1855.51    5016 1856.01  5022.3 1859.92  5030.7 1867.62  5036.3 1871.77
  5044.7 1877.09  5053.1 1883.39  5058.7 1885.98  5067.1 1891.83  5075.4 1894.51
    5081 1895.62  5097.8 1900.12  5103.4 1901.11    5109  1903.3  5111.8  1903.3
#Mann= 3 ,-1 , 0
  4888.2      .1       0    5012     .05       0    5016      .1       0
Bank Sta=5012,5016
XS Rating Curve= 0 ,0
Exp/Cntr=0.3,0.1

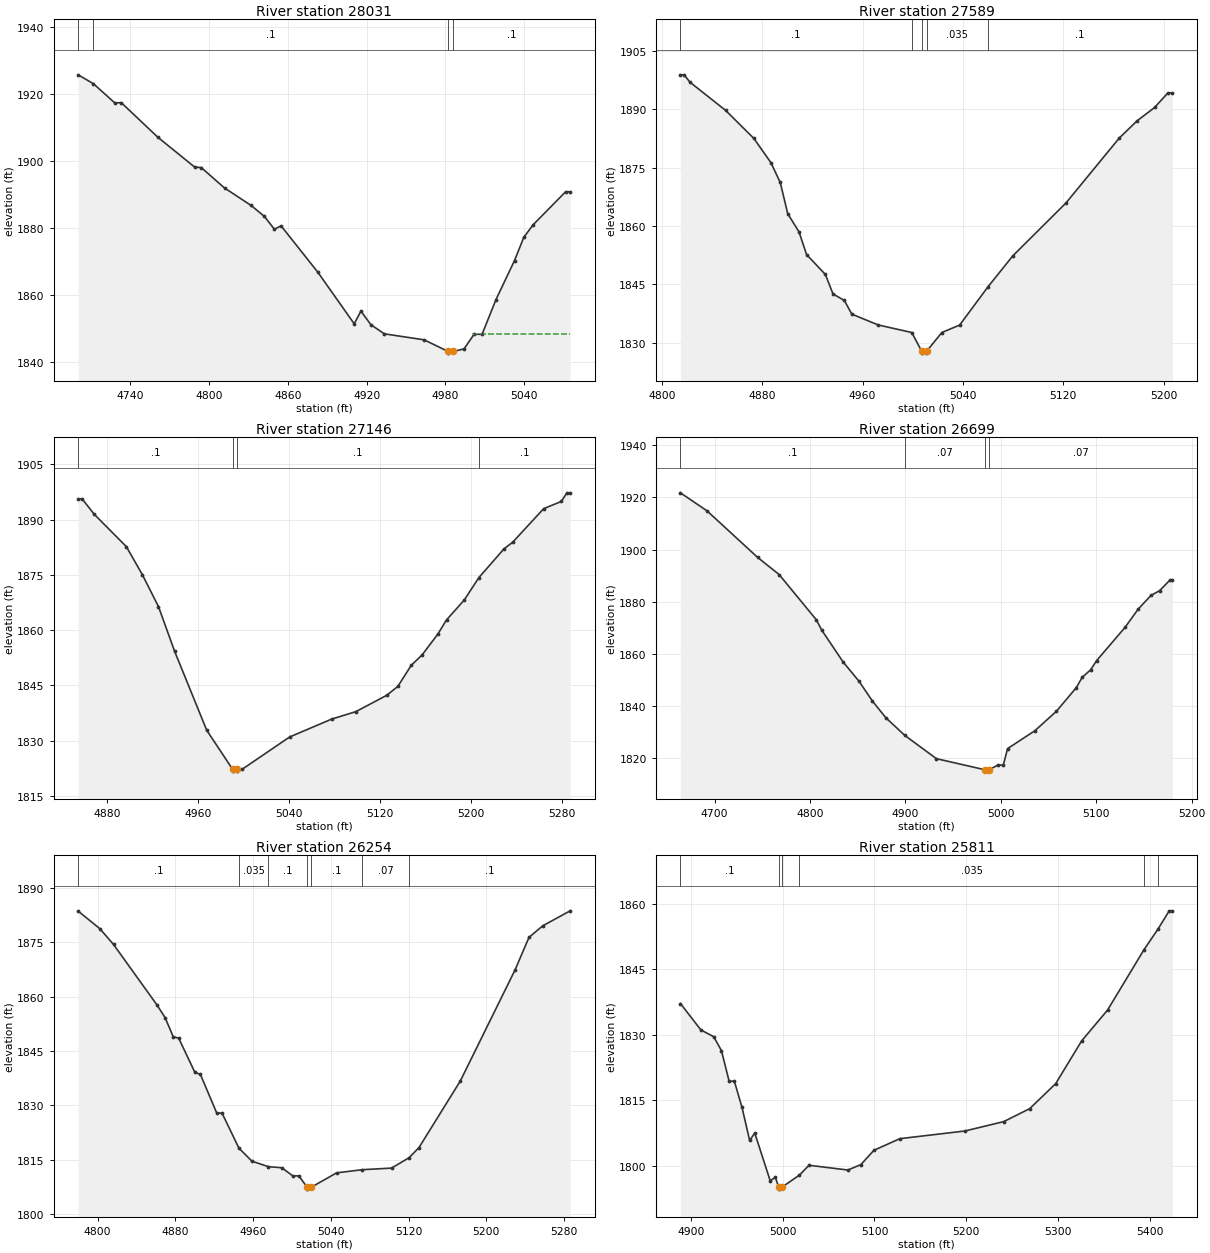
Type RM Length L Ch R = 1 ,28031   ,442,442,442
BEGIN DESCRIPTION:
Stream0518 57.0
END DESCRIPTION:
XS GIS Cut Line= 3
      1991375.02       13861075.        1991675.       13861125.
      1991724.98     13861174.98
#Sta/Elev= 30
  4700.2 1925.72  4711.8 1923.08  4728.1 1917.36  4733.1 1917.42    4761 1907.09
  4788.9 1898.25    4794 1898.08  4811.7    1892    4832 1886.79  4842.1 1883.52
  4849.7 1879.71  4854.8 1880.71  4882.7 1866.95  4910.5 1851.53  4915.6 1855.31
  4923.2 1851.27  4933.4 1848.54  4963.8 1846.75    4982 1843.29  4982.3 1842.79
    4986 1843.29  4994.2 1844.07  5001.8 1848.41  5007.9 1848.41  5018.5 1858.76
  5032.6 1870.37  5039.7 1877.31  5046.7    1881  5071.5 1890.87    5075 1890.87
#Mann= 4 ,-1 , 0
  4700.2     .07       0  4711.8      .1       0    4982     .05       0
    4986      .1       0
#XS Ineff= 2 , 0
                          5001.3         1848.58
Permanent Ineff=
       F       F
Bank Sta=4982,4986
XS Rating Curve= 0 ,0
Exp/Cntr=0.3,0.1

Type RM Length L Ch R = 1 ,27589   ,443,443,443
BEGIN DESCRIPTION:
Stream0518 56.0
END DESCRIPTION:
XS GIS Cut Line= 3
      1991325.02     13861325.03        1991425.       13861475.
      1991575.01     13861625.01
#Sta/Elev= 30
  4814.7 1898.86  4817.7 1898.86  4822.2    1897  4850.7 1889.73  4873.3 1882.51
  4886.8 1876.32  4894.3 1871.21  4900.3 1863.16  4909.3 1858.49  4915.3 1852.68
  4930.3 1847.56  4936.4 1842.55  4945.4 1840.89  4951.4 1837.37  4972.4 1834.59
  4999.2 1832.65  5007.1 1827.85  5007.3 1827.35  5010.8 1827.35  5011.1 1827.85
  5023.2 1832.65  5037.4 1834.56    5060  1844.4  5079.8 1852.35  5122.2 1865.94
  5164.7 1882.62  5178.8 1887.01  5192.9 1890.48  5203.5 1894.22  5207.1 1894.22
#Mann= 5 ,-1 , 0
  4814.7      .1       0  4999.2    .035       0  5007.1    .035       0
  5011.1    .035       0    5060      .1       0
Bank Sta=5007.1,5011.1
XS Rating Curve= 0 ,0
Exp/Cntr=0.3,0.1

Type RM Length L Ch R = 1 ,27146   ,447,447,447
BEGIN DESCRIPTION:
Stream0518 55.0
END DESCRIPTION:
XS GIS Cut Line= 3
      1991025.02     13861675.02        1991125.       13861775.
      1991374.96     13861924.98
#Sta/Elev= 30
  4854.2 1895.61  4857.7 1895.61  4868.3 1891.45  4896.6 1882.66  4910.7 1875.04
  4924.9 1866.37    4939 1854.32  4967.3 1832.85  4990.1 1822.24  4990.3 1821.74
  4993.8 1821.74  4994.1 1822.24  4998.5 1822.24  5040.3 1831.01  5077.2 1835.85
  5098.6 1837.89  5125.8 1842.33  5135.5 1844.74  5147.2 1850.41  5156.9  1853.3
  5170.5 1858.84  5178.3 1862.77  5193.9 1868.16  5206.8 1874.26  5228.8 1882.02
  5236.6 1883.87  5263.8 1892.96  5279.4 1894.92  5284.2 1897.25  5287.1 1897.25
#Mann= 4 ,-1 , 0
  4854.2      .1       0  4990.1    .035       0  4994.1      .1       0
  5206.8      .1       0
Bank Sta=4990.1,4994.1
XS Rating Curve= 0 ,0
Exp/Cntr=0.3,0.1

Type RM Length L Ch R = 1 ,26699   ,445,445,445
BEGIN DESCRIPTION:
Stream0518 54.0
END DESCRIPTION:
XS GIS Cut Line= 3
        1990675.     13861775.01        1990825.       13862075.
      1990925.01     13862225.02
#Sta/Elev= 30
  4664.1 1921.77    4692 1914.85  4745.1 1896.98  4767.5 1890.45  4806.6 1873.06
  4812.2 1869.12  4834.6 1856.92  4851.4 1849.46  4865.3 1841.94  4879.3 1835.56
  4899.2 1828.77  4932.4 1819.83  4983.5 1815.55  4983.8 1815.05  4987.5 1815.55
  4996.7 1817.35  5002.5 1817.35    5007 1823.69  5035.6 1830.54  5058.1 1837.97
  5079.1 1847.09  5085.1 1850.97  5094.1 1853.93  5100.2 1857.38  5130.2 1870.21
  5143.7  1877.1  5157.2  1882.4  5166.3 1884.25  5176.8 1888.18  5179.8 1888.18
#Mann= 4 ,-1 , 0
  4664.1      .1       0  4899.2     .07       0  4983.5     .05       0
  4987.5     .07       0
Bank Sta=4983.5,4987.5
XS Rating Curve= 0 ,0
Exp/Cntr=0.3,0.1

Type RM Length L Ch R = 1 ,26254   ,443,443,443
BEGIN DESCRIPTION:
Stream0518 53.0
END DESCRIPTION:
XS GIS Cut Line= 3
      1990374.98     13862074.96        1990475.       13862275.
        1990675.       13862475.
#Sta/Elev= 30
  4779.9 1883.57  4802.3 1878.69  4816.3 1874.36    4861  1857.7  4869.4 1854.18
  4877.8  1848.9  4883.4 1848.53  4900.1 1839.06  4905.7 1838.56  4922.5 1827.92
  4928.1 1827.82  4945.4 1818.19  4958.8  1814.6  4975.8 1813.08  4989.6 1812.79
  5000.8 1810.55  5007.1 1810.55  5015.7 1807.39  5015.9 1806.89  5019.7 1807.39
    5046 1811.38  5072.5 1812.25  5102.5 1812.69  5120.6 1815.55  5130.8 1818.36
  5173.3  1836.7  5229.8 1867.41    5244 1876.31  5258.1 1879.49  5286.4 1883.63
#Mann= 7 ,-1 , 0
  4779.9      .1       0  4945.4    .035       0  4975.8      .1       0
  5015.7     .05       0  5019.7      .1       0  5072.5     .07       0
  5120.6      .1       0
Bank Sta=5015.7,5019.7
XS Rating Curve= 0 ,0
Exp/Cntr=0.3,0.1

Type RM Length L Ch R = 1 ,25811   ,454,454,454
BEGIN DESCRIPTION:
Stream0518 52.0
END DESCRIPTION:
XS GIS Cut Line= 3
      1990124.99     13862225.03        1990075.       13862325.
      1990374.97     13862624.97
#Sta/Elev= 30
  4888.6 1837.14  4910.9 1831.09  4924.9 1829.53  4933.3 1826.35  4941.7 1819.31
  4947.3  1819.4  4955.7 1813.35    4964  1805.8  4969.6 1807.49  4986.4 1796.57
    4992 1797.36  4995.6 1795.16  4995.8 1794.66  4999.6 1795.16  5018.2 1797.87
  5028.7 1800.12  5071.1 1799.03  5085.2 1800.28  5099.4 1803.55  5127.7 1806.21
  5198.4 1807.96  5240.8 1810.11  5269.1 1813.08  5297.4  1818.8  5325.6 1828.56
  5353.9 1835.64  5393.5 1849.42  5408.9 1854.19  5421.1 1858.35  5424.6 1858.35
#Mann= 6 ,-1 , 0
  4888.6      .1       0  4995.6     .05       0  4999.6      .1       0
  5018.2    .035       0  5393.5      .1       0  5408.9    .035       0
Bank Sta=4995.6,4999.6
XS Rating Curve= 0 ,0
Exp/Cntr=0.3,0.1

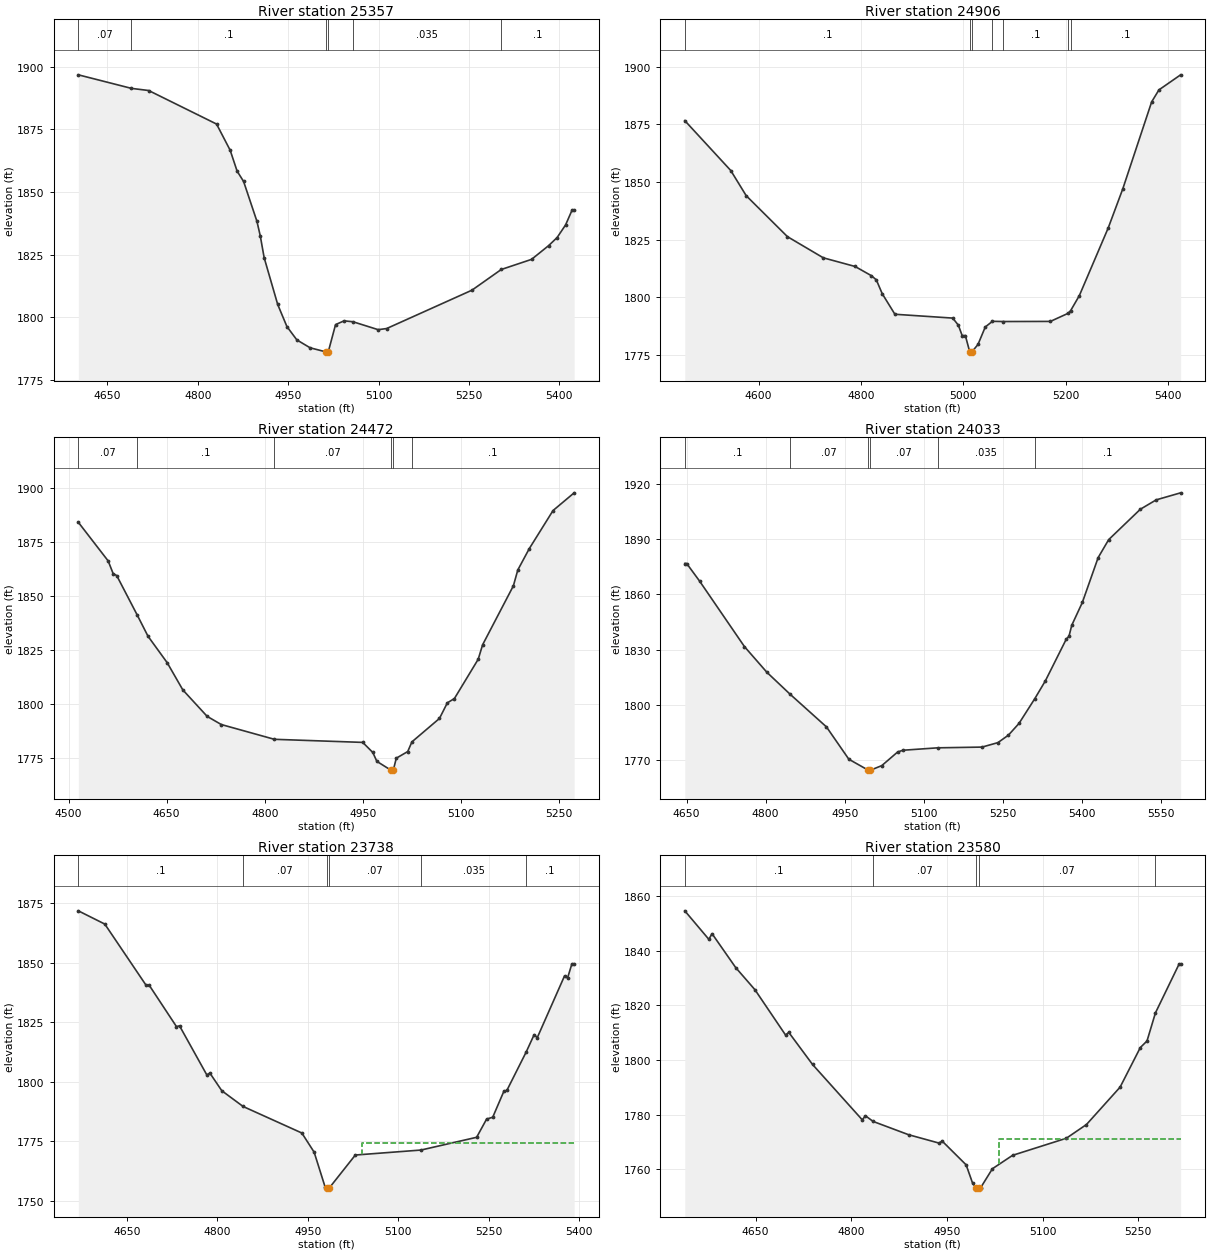
Type RM Length L Ch R = 1 ,25357   ,451,451,451
BEGIN DESCRIPTION:
Stream0518 51.0
END DESCRIPTION:
XS GIS Cut Line= 3
      1989590.67     13862221.57        1989775.       13862575.
      1990075.02     13862875.02
#Sta/Elev= 30
  4601.8 1896.86    4690 1891.44  4718.5 1890.59  4831.2 1877.18  4853.8  1866.7
  4865.3 1858.36  4876.1 1854.21  4898.2  1838.3  4903.8 1832.42  4910.2 1823.74
  4932.7 1805.03    4948 1796.19  4964.5 1790.86  4986.5 1787.71  5012.6 1786.08
  5012.8 1785.58  5016.6 1786.08  5028.7 1796.98  5042.8 1798.49  5057.7 1798.12
  5099.4 1794.96  5113.5 1795.41    5255 1810.74  5303.7 1819.02    5354 1823.07
  5382.2 1828.54  5396.4 1831.79  5410.5 1836.86  5421.1  1842.7  5424.7  1842.7
#Mann= 6 ,-1 , 0
  4601.8     .07       0    4690      .1       0  5012.6     .05       0
  5016.6      .1       0  5057.7    .035       0  5303.7      .1       0
Bank Sta=5012.6,5016.6
XS Rating Curve= 0 ,0
Exp/Cntr=0.3,0.1

Type RM Length L Ch R = 1 ,24906   ,434,434,434
BEGIN DESCRIPTION:
Stream0518 50.0
END DESCRIPTION:
XS GIS Cut Line= 4
      1989482.59     13862345.84      1989446.25     13862650.86
        1989525.       13862875.      1989824.99     13863174.99
#Sta/Elev= 30
  4455.8 1876.59  4545.6 1854.97  4575.8 1844.05  4656.4 1826.29  4726.5 1817.11
  4788.6 1813.36  4820.4 1809.37  4830.1 1807.56  4841.6 1801.57  4866.4 1792.64
  4979.4 1790.98  4990.4 1787.91  4997.9  1783.4  5004.1  1783.4  5012.7 1776.29
  5012.9 1775.79  5016.7 1776.29  5028.8 1779.55    5043 1787.12    5057 1789.58
  5078.4 1789.49  5170.3 1789.54    5205 1793.06  5209.9 1794.23  5226.8  1800.7
  5283.4 1830.12  5311.7 1846.97  5368.2 1884.73  5382.4 1889.92  5424.8 1896.45
#Mann= 7 ,-1 , 0
  4455.8      .1       0  5012.7     .05       0  5016.7      .1       0
    5057     .07       0  5078.4      .1       0    5205    .035       0
  5209.9      .1       0
Bank Sta=5012.7,5016.7
XS Rating Curve= 0 ,0
Exp/Cntr=0.3,0.1

Type RM Length L Ch R = 1 ,24472   ,439,439,439
BEGIN DESCRIPTION:
Stream0518 49.0
END DESCRIPTION:
XS GIS Cut Line= 3
      1988972.88     13863088.86        1989425.       13863275.
        1989675.       13863375.
#Sta/Elev= 30
  4514.9 1884.22  4560.5 1866.34  4568.1  1860.5  4573.6 1859.55  4605.3 1841.08
  4621.4 1831.49  4650.8 1819.21  4674.7 1806.62  4711.9 1794.37  4733.5 1790.59
  4814.7 1783.75  4949.8 1782.32  4965.2 1777.66  4971.4 1773.54  4992.6 1769.52
  4992.8 1769.02  4996.6 1769.52  5001.1 1775.01  5018.6 1778.08    5025 1782.56
  5067.1  1793.4  5079.2 1800.64    5090 1802.63  5126.4 1820.83  5133.1 1827.51
  5180.2 1854.83  5186.9 1862.13  5204.4 1871.99  5240.8 1889.66  5273.1 1897.86
#Mann= 6 ,-1 , 0
  4514.9     .07       0  4605.3      .1       0  4814.7     .07       0
  4992.6     .05       0  4996.6     .07       0    5025      .1       0
Bank Sta=4992.6,4996.6
XS Rating Curve= 0 ,0
Exp/Cntr=0.3,0.1

Type RM Length L Ch R = 1 ,24033   ,295,295,295
BEGIN DESCRIPTION:
Stream0518 48.0
END DESCRIPTION:
XS GIS Cut Line= 3
      1988874.99     13863324.99        1989125.       13863575.
      1989711.26     13863598.49
#Sta/Elev= 30
  4646.7 1876.86  4650.3 1876.86    4675 1867.18  4759.9 1831.58  4802.3 1817.65
  4846.3  1805.7  4915.4 1787.87  4957.8 1770.28  4994.7  1764.3    4995  1763.8
  4998.7  1764.3  5020.3 1766.81  5050.3 1774.21  5060.3 1775.17  5126.3 1776.49
  5210.4 1776.89  5240.5 1779.32  5260.5 1783.41  5280.5 1789.78  5310.6 1803.33
  5330.5 1812.96  5370.2 1835.71  5375.2 1837.17  5380.6 1843.26  5400.6 1855.64
  5430.6 1880.08  5450.6 1889.87  5510.7 1906.43  5540.7 1911.52    5587 1915.35
#Mann= 6 ,-1 , 0
  4646.7      .1       0  4846.3     .07       0  4994.7     .05       0
  4998.7     .07       0  5126.3    .035       0  5310.6      .1       0
Bank Sta=4994.7,4998.7
XS Rating Curve= 0 ,0
Exp/Cntr=0.3,0.1

Type RM Length L Ch R = 1 ,23738   ,158,158,158
BEGIN DESCRIPTION:
Mapping XS 3dd6bee1
END DESCRIPTION:
XS GIS Cut Line= 2
      1988702.03     13863923.17      1989507.17     13863757.06
#Sta/Elev= 30
  4569.4  1871.8  4613.3 1866.23  4681.9 1840.46    4687  1840.5  4732.1 1823.16
  4737.2 1823.47  4782.4 1802.87  4787.5 1803.62  4807.3  1796.2  4842.6 1789.59
    4940 1778.44  4960.4 1770.38  4978.4 1755.89  4981.5 1755.36  4981.7 1754.86
  4985.5 1755.36  5028.7 1769.19  5137.5 1771.28  5229.8 1776.64  5246.3 1784.28
  5256.5 1785.08  5274.9 1795.94    5280 1796.38  5311.9 1812.45  5325.2 1819.78
  5330.3 1818.49  5375.5 1844.43  5380.6  1843.6  5387.8 1849.55  5391.5 1849.55
#Mann= 6 ,-1 , 0
  4569.4      .1       0  4842.6     .07       0  4981.5     .05       0
  4985.5     .07       0  5137.5    .035       0  5311.9      .1       0
#XS Ineff= 2 , 0
                         5039.36         1774.09
Permanent Ineff=
       F       F
Bank Sta=4981.5,4985.5
XS Rating Curve= 0 ,0
Exp/Cntr=0.3,0.1

Type RM Length L Ch R = 1 ,23580   ,445,445,445
BEGIN DESCRIPTION:
Stream0518 47.0
END DESCRIPTION:
XS GIS Cut Line= 3
      1988715.42     13864013.38        1989175.       13863975.
      1989474.99       13863875.
#Sta/Elev= 30
  4538.9 1854.52  4576.6 1844.09  4581.6 1846.17  4618.8 1833.73  4648.9 1825.65
  4696.9 1809.08  4701.9 1810.06  4739.2 1798.31  4817.1 1778.07  4822.2 1779.54
  4834.2 1777.47  4889.7 1772.62  4937.4 1769.56  4942.5 1770.27    4980 1761.59
    4990 1754.98  4995.6 1753.21  4995.8 1752.71  4999.6 1753.21  5002.7 1753.21
  5021.2 1760.17  5052.8 1765.07  5137.1 1771.32  5168.7 1776.35  5221.4 1790.02
  5253.1  1804.5  5263.6 1806.91  5276.8 1817.18  5313.7 1834.95  5316.3 1834.95
#Mann= 5 ,-1 , 0
  4538.9      .1       0  4834.2     .07       0  4995.6     .05       0
  4999.6     .07       0  5276.8      .1       0
#XS Ineff= 2 , 0
                         5032.29         1771.04
Permanent Ineff=
       F       F
Bank Sta=4995.6,4999.6
XS Rating Curve= 0 ,0
Exp/Cntr=0.3,0.1

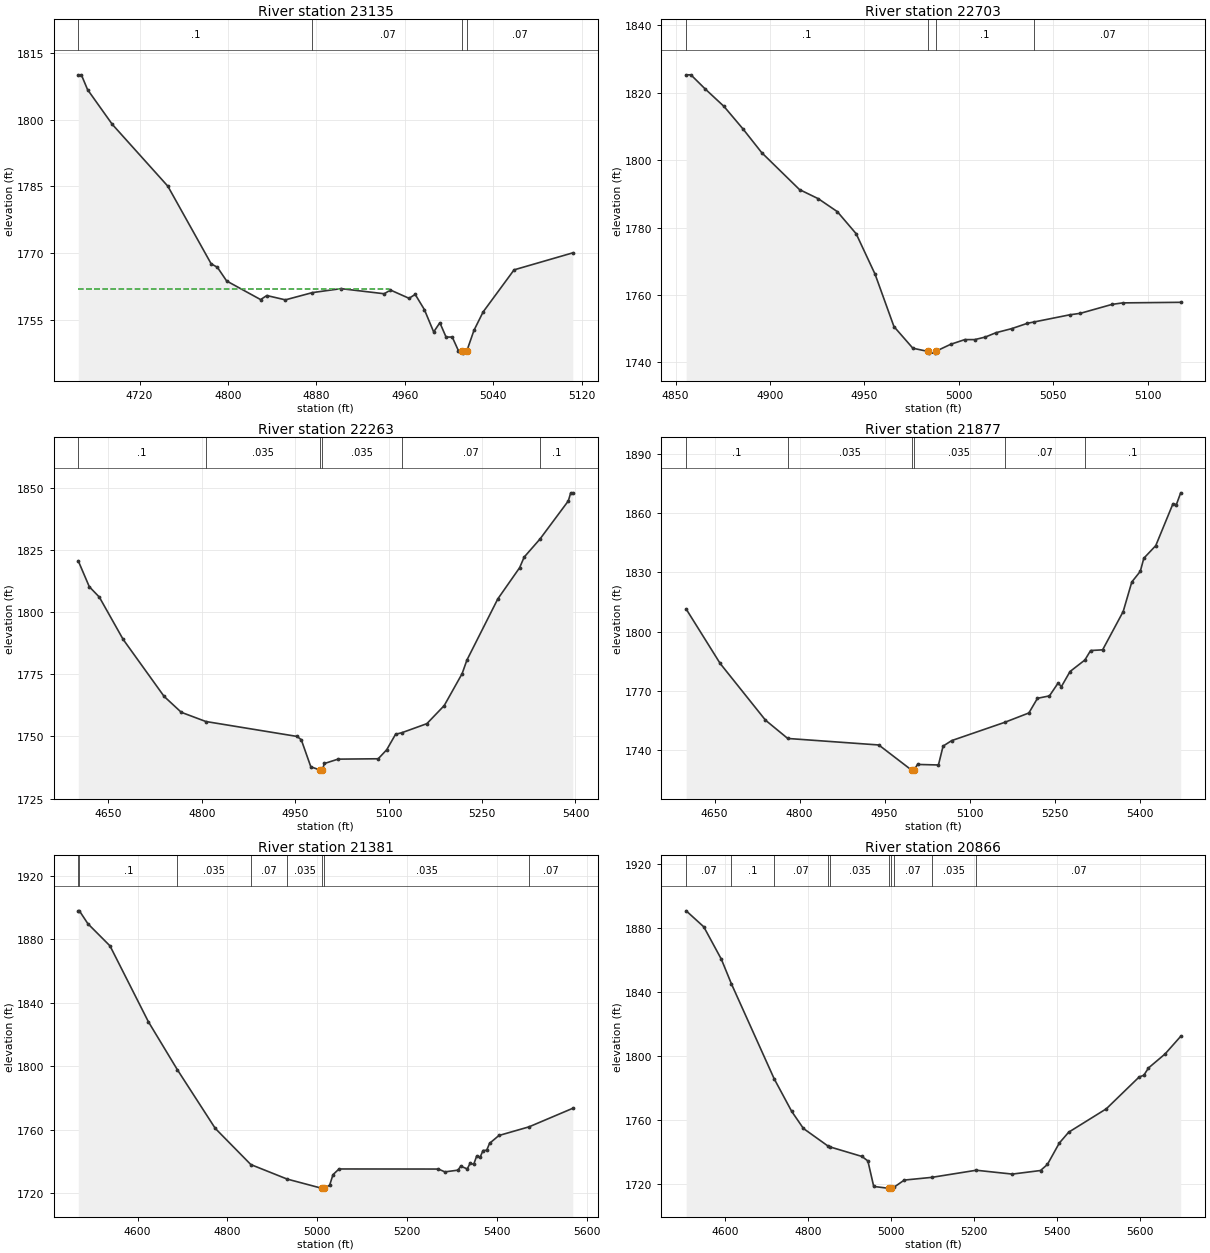
Type RM Length L Ch R = 1 ,23135   ,432,432,432
BEGIN DESCRIPTION:
Stream0518 46.0
END DESCRIPTION:
XS GIS Cut Line= 3
      1988925.01       13864475.        1989225.       13864325.
        1989325.       13864375.
#Sta/Elev= 30
  4664.6 1810.05  4667.4 1810.05    4673 1806.73  4695.3 1798.94  4745.6 1785.03
  4784.8 1767.58  4790.4 1766.81  4798.8 1763.73  4829.5 1759.55  4835.1 1760.46
  4851.9 1759.49  4876.4 1761.12  4902.2 1762.01  4941.3 1760.86  4946.9  1761.7
  4963.7 1759.84  4969.3 1760.71  4977.6  1757.3    4986 1752.28  4991.6 1754.35
  4997.2 1751.13  5002.8 1751.13  5008.4 1748.06    5012 1748.02  5012.2 1747.52
    5016 1748.02  5022.4 1752.62  5030.7 1756.77  5058.7 1766.23  5111.8 1770.05
#Mann= 4 ,-1 , 0
  4664.6      .1       0  4876.4     .07       0    5012     .05       0
    5016     .07       0
#XS Ineff= 2 , 0
         4945.85 1761.88
Permanent Ineff=
       F       F
Bank Sta=5012,5016
XS Rating Curve= 0 ,0
Exp/Cntr=0.3,0.1

Type RM Length L Ch R = 1 ,22703   ,440,440,440
BEGIN DESCRIPTION:
Stream0518 45.0
END DESCRIPTION:
XS GIS Cut Line= 3
        1988925.       13864675.        1989075.       13864675.
      1989174.99       13864625.
#Sta/Elev= 30
  4855.6 1825.25  4858.1 1825.25  4865.6  1821.1  4875.6  1815.9  4885.6 1809.27
  4895.6 1802.18  4915.6 1791.24  4925.6 1788.52  4935.6 1784.71  4945.6 1778.15
  4955.6 1766.17  4965.6 1750.64  4975.6 1744.23  4983.6 1743.27  4983.9 1742.77
  4987.4 1742.77  4987.6 1743.27  4995.6 1745.38  5003.1 1746.78  5008.4 1746.78
    5014 1747.54  5019.6 1748.82    5028 1750.04  5036.3 1751.62  5039.9 1752.02
  5058.7 1754.13  5064.3 1754.57  5081.1 1757.22  5086.7 1757.66  5117.4 1757.83
#Mann= 4 ,-1 , 0
  4855.6      .1       0  4983.6     .05       0  4987.6      .1       0
  5039.9     .07       0
#XS Ineff= 2 , 0
         4946.41 1761.49
Permanent Ineff=
       F       F
Bank Sta=4983.6,4987.6
XS Rating Curve= 0 ,0
Exp/Cntr=0.3,0.1

Type RM Length L Ch R = 1 ,22263   ,386,386,386
BEGIN DESCRIPTION:
Stream0518 44.0
END DESCRIPTION:
XS GIS Cut Line= 3
      1989069.39     13865065.57        1989425.       13864875.
      1989725.02     13864624.98
#Sta/Elev= 30
  4601.7 1820.55  4619.4 1810.17  4635.5    1806  4673.7 1789.01  4739.5 1766.08
  4767.1 1759.68  4806.5 1755.98  4953.2 1749.97  4959.8 1748.63  4975.1 1737.76
  4989.4 1736.53  4989.6 1736.03  4993.4 1736.53    4997  1739.1  5018.8 1740.85
  5083.3    1741  5096.9 1744.61  5111.2 1750.86    5121 1751.45  5161.4 1755.11
  5189.3 1762.39    5218 1775.21  5225.8 1780.72  5275.3 1805.26  5310.4 1817.83
  5317.6 1822.06  5343.1 1829.36  5388.5 1844.64  5392.4 1847.91  5395.7 1847.91
#Mann= 6 ,-1 , 0
  4601.7      .1       0  4806.5    .035       0  4989.4    .035       0
  4993.4    .035       0    5121     .07       0  5343.1      .1       0
Bank Sta=4989.4,4993.4
XS Rating Curve= 0 ,0
Exp/Cntr=0.3,0.1

Type RM Length L Ch R = 1 ,21877   ,496,496,496
BEGIN DESCRIPTION:
Stream0518 43.0
END DESCRIPTION:
XS GIS Cut Line= 3
      1989124.99       13865225.      1989536.68      13865223.8
      1989925.02     13864974.99
#Sta/Elev= 30
  4599.8 1811.46  4659.8 1783.87  4739.8 1755.12  4779.1 1745.85  4939.8 1742.55
  4997.8 1729.79  4998.1 1729.29  5001.8 1729.79  5008.2 1732.68  5045.1 1732.41
  5053.3 1741.98  5068.5 1744.77  5161.8    1754  5204.7 1758.77  5219.9 1766.21
    5241 1767.43  5256.2 1773.89  5262.2 1772.18  5277.4 1779.79  5303.6 1785.63
  5313.7 1790.43  5334.9 1790.78  5371.2  1810.2  5386.4 1825.18  5401.4 1830.58
  5407.6 1837.21  5428.7 1843.61  5459.1 1864.87  5465.1 1864.44  5472.7 1870.38
#Mann= 6 ,-1 , 0
  4599.8      .1       0  4779.1    .035       0  4997.8    .035       0
  5001.8    .035       0  5161.8     .07       0  5303.6      .1       0
Bank Sta=4997.8,5001.8
XS Rating Curve= 0 ,0
Exp/Cntr=0.3,0.1

Type RM Length L Ch R = 1 ,21381   ,515,515,515
BEGIN DESCRIPTION:
Stream0518 42.0
END DESCRIPTION:
XS GIS Cut Line= 3
      1988924.97     13865274.98      1989322.43     13865625.85
      1989675.02     13866075.02
#Sta/Elev= 30
    4468 1897.96  4470.5 1897.96  4489.4 1889.83  4538.7 1875.84  4624.1 1828.05
  4688.7 1797.78    4773 1760.82  4852.3 1737.99  4933.1 1728.85  5010.8 1723.01
  5011.2 1722.51  5015.7 1723.01  5027.8 1725.01  5035.2 1731.61  5048.6 1735.22
    5270 1735.17  5284.4 1733.38  5313.4 1734.47  5319.7 1736.99  5334.2 1735.24
  5340.5  1738.8  5348.6 1738.16    5355 1743.21  5363.1 1742.82  5369.4 1746.86
  5377.5 1747.02  5383.9 1751.39  5404.7 1756.32  5471.8 1761.78  5569.2 1773.47
#Mann= 8 ,-1 , 0
    4468     .07       0  4470.5      .1       0  4688.7    .035       0
  4852.3     .07       0  4933.1    .035       0  5010.8    .035       0
  5015.7    .035       0  5471.8     .07       0
Bank Sta=5010.8,5015.7
XS Rating Curve= 0 ,0
Exp/Cntr=0.3,0.1

Type RM Length L Ch R = 1 ,20866   ,418,418,418
BEGIN DESCRIPTION:
Stream0518 41.0
END DESCRIPTION:
XS GIS Cut Line= 3
      1988724.97     13865574.97        1989075.       13865925.
      1989705.32     13866225.72
#Sta/Elev= 30
  4505.1 1890.74  4547.6 1880.75    4590 1860.53  4614.4 1845.08  4717.3 1785.96
  4759.7 1765.55    4788 1754.86    4847 1743.95  4852.4 1743.32  4929.4 1737.37
  4943.6 1734.58  4957.7 1718.66  4994.1 1717.48  4994.5 1716.98    4999 1717.48
  5005.9 1718.04  5031.4 1722.63  5097.6 1724.32  5205.2 1728.77  5292.1 1726.37
  5360.2  1728.6  5376.8 1732.36  5405.5 1745.72  5428.2 1752.53    5519 1767.13
  5598.4 1787.04  5609.5 1788.05  5620.8 1792.64  5660.7 1801.35  5698.5 1812.37
#Mann= 10 ,-1 , 0
  4505.1     .07       0  4614.4      .1       0  4717.3     .07       0
    4847      .1       0  4852.4    .035       0  4994.1    .035       0
    4999    .035       0  5005.9     .07       0  5097.6    .035       0
  5205.2     .07       0
Bank Sta=4994.1,4999
XS Rating Curve= 0 ,0
Exp/Cntr=0.3,0.1

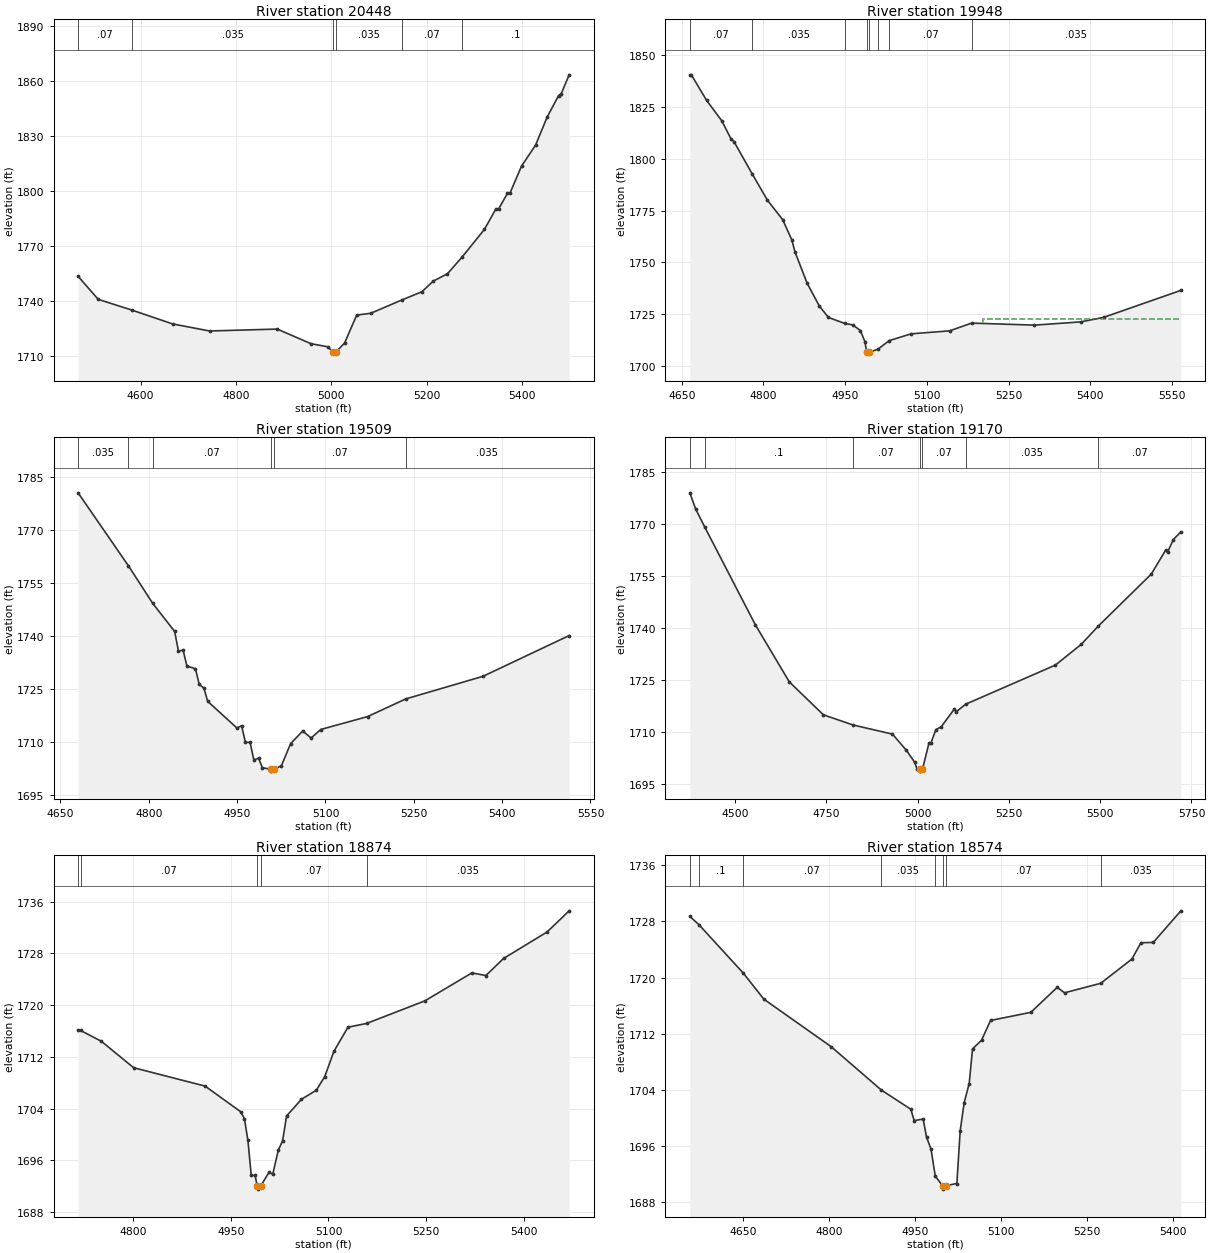
Type RM Length L Ch R = 1 ,20448   ,500,500,500
BEGIN DESCRIPTION:
Stream0518 40.0
END DESCRIPTION:
XS GIS Cut Line= 3
      1988824.97     13865924.97      1989219.62     13866292.79
      1989673.82     13866476.95
#Sta/Elev= 30
  4468.9 1753.69  4511.2 1741.11  4582.3 1735.23  4667.1 1727.73  4744.7 1723.88
  4886.4 1724.93  4957.3 1716.94  4992.4 1715.27  5003.8 1712.31  5004.2 1711.81
  5008.8 1712.31  5027.6 1717.28  5053.1 1732.55  5082.6 1733.54  5147.1 1740.72
  5189.7 1745.28  5213.8  1751.1  5243.3 1755.07  5273.4 1763.98    5321 1779.32
  5345.1  1790.5  5350.5 1790.41  5369.2 1798.93  5374.6 1799.14  5398.7 1813.78
  5428.2 1825.25  5452.3 1840.47  5476.4 1852.23  5481.8 1853.19  5498.5 1863.55
#Mann= 6 ,-1 , 0
  4468.9     .07       0  4582.3    .035       0  5003.8    .035       0
  5008.8    .035       0  5147.1     .07       0  5273.4      .1       0
#XS Ineff= 2 , 0
                         5202.02         1728.48
Permanent Ineff=
       F       F
Bank Sta=5003.8,5008.8
XS Rating Curve= 0 ,0
Exp/Cntr=0.3,0.1

Type RM Length L Ch R = 1 ,19948   ,439,439,439
BEGIN DESCRIPTION:
Stream0518 39.0
END DESCRIPTION:
XS GIS Cut Line= 3
      1988475.02     13866125.01        1988775.       13866275.
      1989175.02     13866675.02
#Sta/Elev= 30
  4664.9 1840.32  4667.7 1840.32  4695.6 1828.06  4723.6 1818.17  4740.3 1809.57
  4745.9  1808.2  4779.7 1792.47  4807.4 1779.93  4835.4 1770.57  4852.1 1760.85
  4857.7 1755.21  4880.1 1740.03  4902.5 1729.06  4919.2 1723.53  4948.9 1720.67
  4963.9 1719.94  4977.9 1717.23  4986.3 1711.78  4989.4 1706.85  4989.8 1706.35
  4994.4 1706.85  5009.7 1708.16  5030.7 1712.36    5071 1715.64  5141.7 1717.07
    5182  1720.8  5297.3 1719.83  5382.1 1721.38  5424.5 1723.58    5566 1736.55
#Mann= 8 ,-1 , 0
  4664.9     .07       0  4779.7    .035       0  4948.9     .07       0
  4989.4     .05       0  4994.4     .07       0  5009.7    .035       0
  5030.7     .07       0    5182    .035       0
#XS Ineff= 2 , 0
                         5202.02         1722.78
Permanent Ineff=
       F       F
Bank Sta=4989.4,4994.4
XS Rating Curve= 0 ,0
Exp/Cntr=0.3,0.1

Type RM Length L Ch R = 1 ,19509   ,339,339,339
BEGIN DESCRIPTION:
Stream0518 38.0
END DESCRIPTION:
XS GIS Cut Line= 3
      1988475.03     13866425.04        1988675.       13866675.
      1989178.36       13866778.
#Sta/Elev= 30
  4679.9 1780.56  4765.2 1759.97  4806.6 1749.31  4843.9 1741.35  4850.3 1735.82
  4858.3 1736.05  4864.7 1731.58  4879.2  1730.8  4885.6 1726.38  4893.6 1725.31
    4900  1721.6  4949.6 1714.06  4957.6  1714.7    4964 1710.03    4972 1709.99
  4978.4 1705.01  4986.4 1705.51  4992.8 1702.83  5007.7 1702.36  5008.1 1701.86
  5012.7 1702.36  5025.2  1703.4  5040.8 1709.63  5061.3 1713.19  5075.7 1711.23
  5091.9 1713.63  5171.5 1717.28  5236.2 1722.27  5367.5 1728.67  5513.8 1740.19
#Mann= 6 ,-1 , 0
  4679.9    .035       0  4765.2      .1       0  4806.6     .07       0
  5007.7     .05       0  5012.7     .07       0  5236.2    .035       0
Bank Sta=5007.7,5012.7
XS Rating Curve= 0 ,0
Exp/Cntr=0.3,0.1

Type RM Length L Ch R = 1 ,19170   ,296,296,296
BEGIN DESCRIPTION:
Stream0518 37.0
END DESCRIPTION:
XS GIS Cut Line= 4
       1988443.1     13866449.46      1988553.41     13866957.08
      1988691.76     13867027.08      1989355.26     13866934.85
#Sta/Elev= 30
  4376.6 1779.04  4392.5 1774.39  4417.3 1769.17  4556.2 1740.85    4649 1724.38
  4742.2 1714.87  4822.8 1711.94  4931.5 1709.28  4969.8 1704.56  4992.1 1701.16
  4998.7  1699.2  5006.3 1699.08  5006.7 1698.58  5011.4 1699.08  5014.4 1699.48
  5031.1 1706.59  5036.7 1706.69  5050.1 1710.56  5064.5 1711.36  5101.2 1716.57
  5106.2 1715.76  5132.1 1717.94  5377.5 1729.24  5448.1 1735.22  5495.1 1740.53
    5640 1755.55  5679.5  1762.5  5684.5 1761.89  5700.5 1765.54    5721 1767.76
#Mann= 7 ,-1 , 0
  4376.6     .07       0  4417.3      .1       0  4822.8     .07       0
  5006.3     .05       0  5011.4     .07       0  5132.1    .035       0
  5495.1     .07       0
Bank Sta=5006.3,5011.4
XS Rating Curve= 0 ,0
Exp/Cntr=0.3,0.1

Type RM Length L Ch R = 1 ,18874   ,300,300,300
BEGIN DESCRIPTION:
Mapping XS a161ac2e
END DESCRIPTION:
XS GIS Cut Line= 3
      1988399.21     13866981.68      1988493.59     13867230.11
      1988756.85      13867640.7
#Sta/Elev= 30
  4715.8 1716.13  4719.5 1716.09  4751.5 1714.41    4801 1710.32  4910.8 1707.47
  4965.4  1703.5  4971.1  1702.4  4976.4 1699.06  4981.5 1693.64  4987.4 1693.64
  4990.7 1692.03  4991.1 1691.53  4996.1 1692.03  5008.6 1694.12  5014.5 1693.84
    5023 1697.54  5029.7 1699.05  5035.7 1702.85  5058.6 1705.44  5081.3 1706.83
  5094.3 1708.95  5108.3 1712.85  5129.9 1716.59  5158.5 1717.17  5247.8 1720.66
    5320 1724.99  5341.6 1724.59  5368.7 1727.23  5435.5 1731.33  5469.3  1734.6
#Mann= 5 ,-1 , 0
  4715.8    .035       0  4719.5     .07       0  4990.7     .05       0
  4996.1     .07       0  5158.5    .035       0
Bank Sta=4990.7,4996.1
XS Rating Curve= 0 ,0
Exp/Cntr=0.3,0.1

Type RM Length L Ch R = 1 ,18574   ,182,182,182
BEGIN DESCRIPTION:
Mapping XS 9f60f0c3
END DESCRIPTION:
XS GIS Cut Line= 2
      1987942.26     13867252.89      1988680.93     13867684.65
#Sta/Elev= 30
  4557.5  1728.7  4573.1 1727.55  4650.5 1720.65  4686.4 1716.93  4803.8 1710.16
  4891.1 1703.99  4942.6 1701.25  4948.4 1699.63  4964.1 1699.86  4969.9 1697.29
  4977.7 1695.59  4985.2 1691.73  4997.8 1690.38  4998.3 1689.88  5003.9 1690.38
  5022.8 1690.68  5028.6 1698.19  5035.6 1702.21  5044.3 1704.91  5050.1 1709.85
  5065.8 1711.08  5081.5 1713.89  5151.7 1715.05  5197.7 1718.61  5210.4 1717.83
  5273.4 1719.18  5327.8 1722.63  5343.5 1724.96    5365    1725  5413.1  1729.5
#Mann= 8 ,-1 , 0
  4557.5     .07       0  4573.1      .1       0  4650.5     .07       0
  4891.1    .035       0  4985.2     .07       0  4997.8     .05       0
  5003.9     .07       0  5273.4    .035       0
Bank Sta=4997.8,5003.9
XS Rating Curve= 0 ,0
Exp/Cntr=0.3,0.1