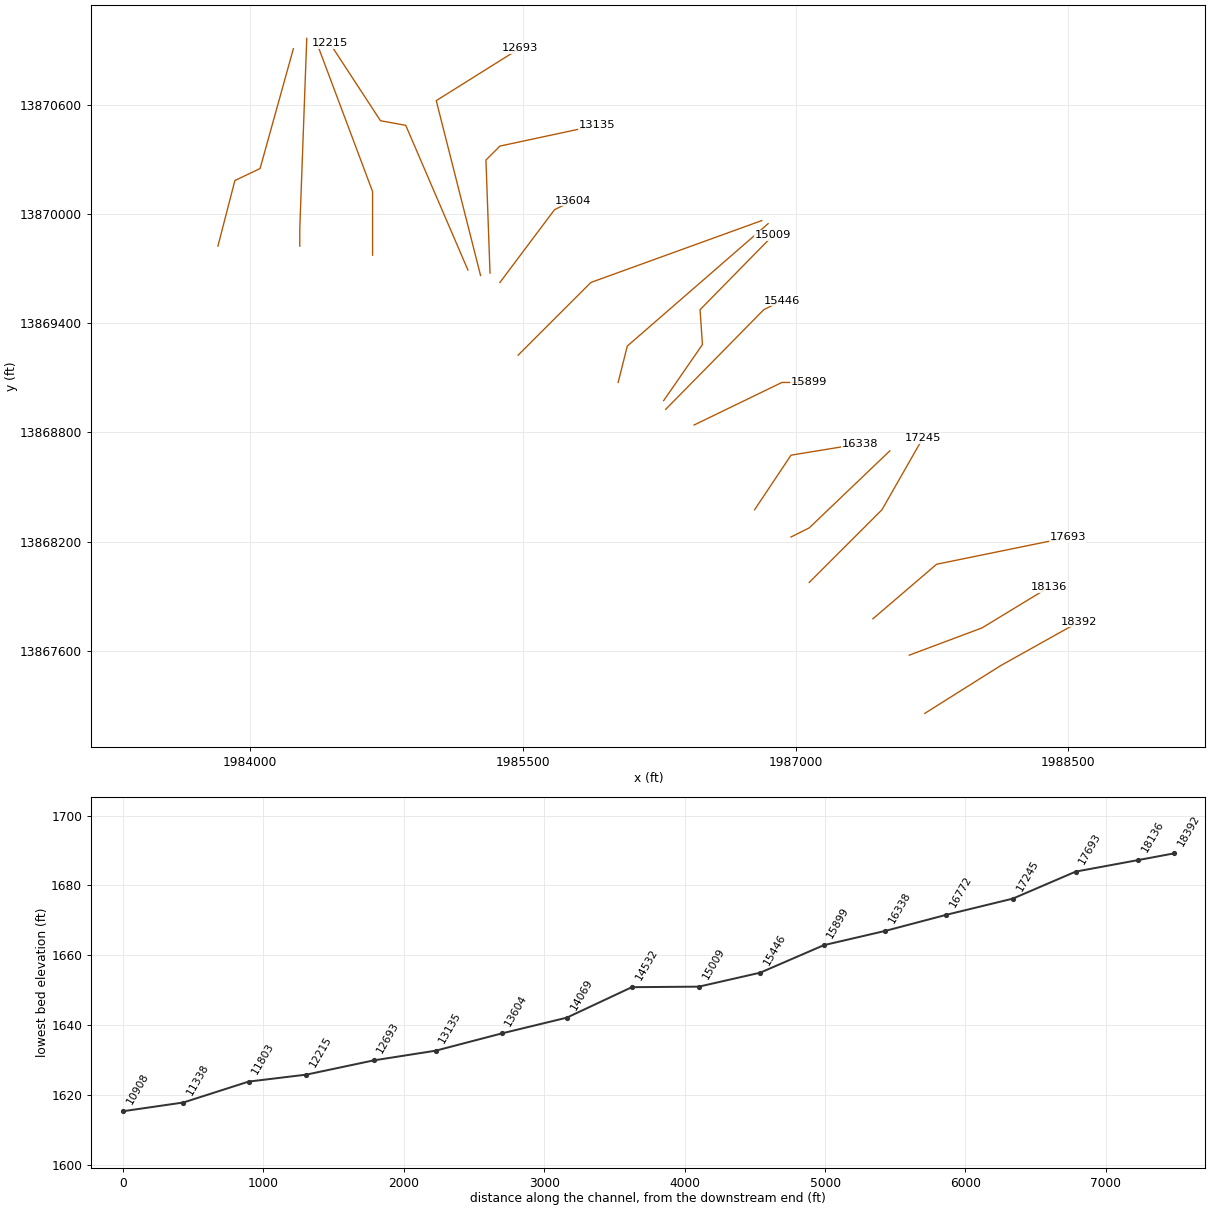
HEC-RAS study Stream0518.prj: Stream0518 Base Level Engineering

--- Stream0518.g01 (geometry) --- (continued)

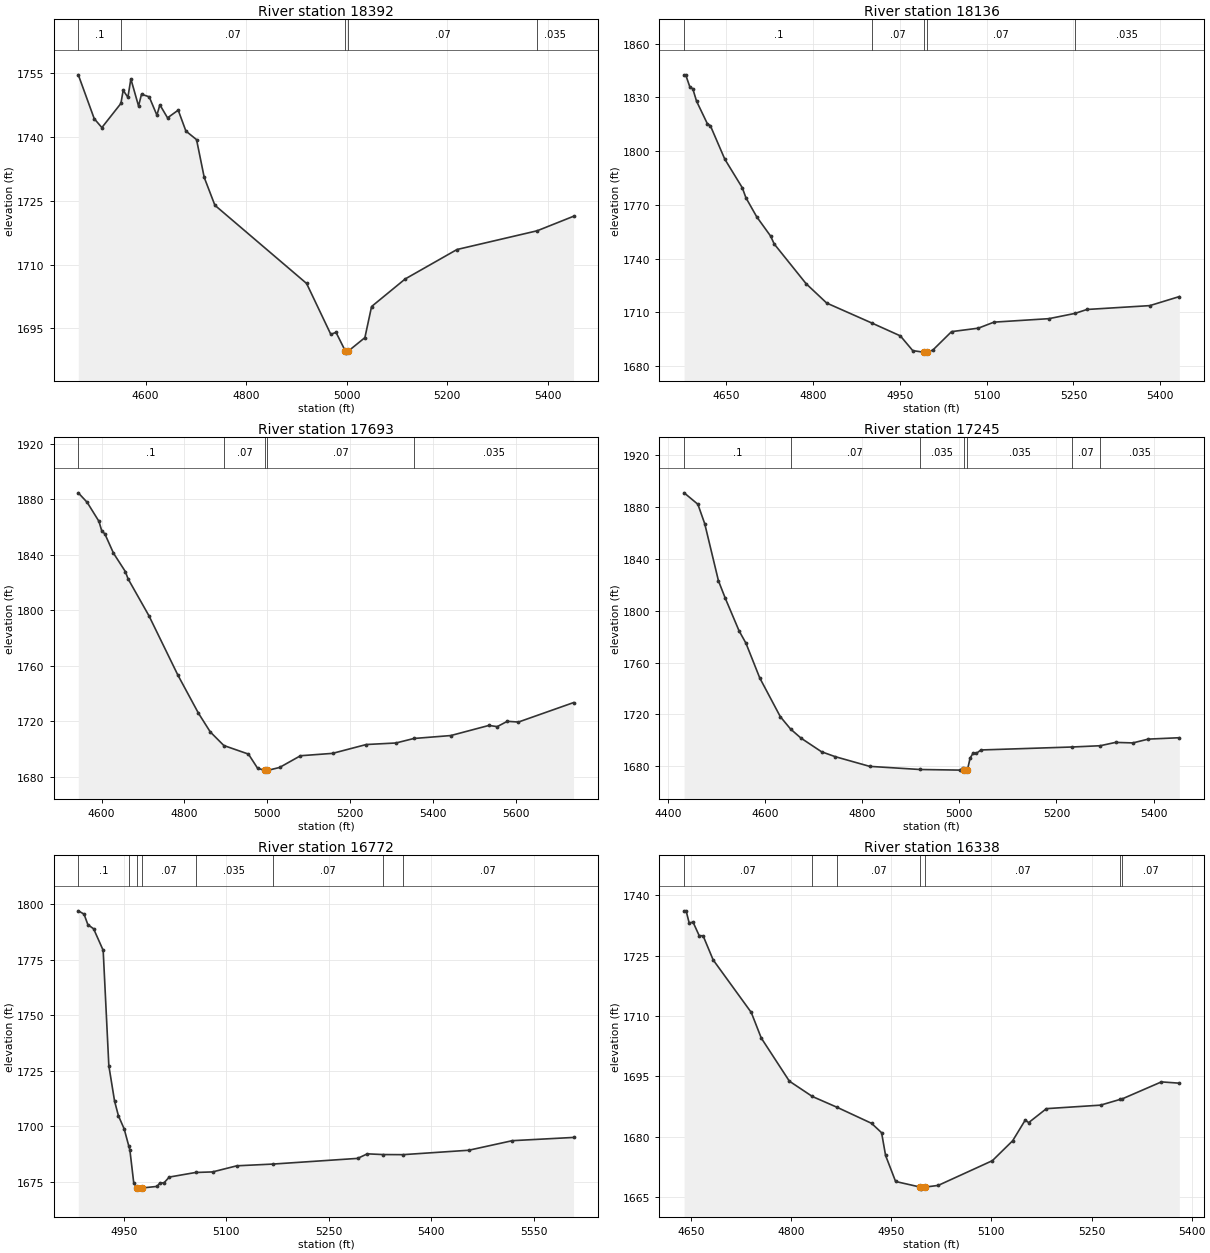
Type RM Length L Ch R = 1 ,18392   ,256,256,256
BEGIN DESCRIPTION:
Stream0518 36.0
END DESCRIPTION:
XS GIS Cut Line= 3
      1987710.42     13867254.89      1988128.17       13867518.
      1988557.42     13867758.01
#Sta/Elev= 30
  4466.2 1754.59  4497.9 1744.28  4513.1 1742.19    4551 1747.87  4555.5 1750.95
  4564.9 1749.31  4570.8 1753.62  4586.1 1747.26    4592 1750.03  4607.3 1749.42
  4622.6 1745.11  4628.5 1747.54  4643.8 1744.48    4665 1746.29  4680.3 1741.38
  4701.5 1739.36  4716.8 1730.47    4738 1723.94  4920.5 1705.56  4968.7  1693.6
    4979 1694.08  4997.6 1689.69  4998.1 1689.19  5003.7 1689.69  5036.5 1692.83
  5049.8 1700.14  5116.7 1706.62  5219.8 1713.54  5379.3 1717.94  5451.7 1721.35
#Mann= 5 ,-1 , 0
  4466.2      .1       0    4551     .07       0  4997.6     .05       0
  5003.7     .07       0  5379.3    .035       0
Bank Sta=4997.6,5003.7
XS Rating Curve= 0 ,0
Exp/Cntr=0.3,0.1

Type RM Length L Ch R = 1 ,18136   ,443,443,443
BEGIN DESCRIPTION:
Stream0518 35.0
END DESCRIPTION:
XS GIS Cut Line= 3
        1987625.       13867575.        1988025.       13867725.
      1988391.38     13867947.98
#Sta/Elev= 30
  4577.1 1842.63  4579.8 1842.63  4586.9 1835.98  4592.2 1834.76  4598.5 1827.99
  4617.1 1815.44  4622.5 1814.22  4647.4 1795.56  4677.7 1779.57  4683.9 1774.03
  4702.6 1763.37  4726.6 1752.62  4732.8 1748.23    4788 1726.02  4823.6 1715.22
  4902.6 1703.93  4950.9  1696.9  4972.3 1688.68  4991.4 1687.77  4991.9 1687.27
  4997.6 1687.77  5007.2 1689.02  5039.4 1699.27  5085.6  1701.2  5112.8 1704.57
  5207.7 1706.51  5252.8 1709.45  5273.5 1711.64  5382.1 1713.79  5433.2 1718.84
#Mann= 5 ,-1 , 0
  4577.1      .1       0  4902.6     .07       0  4991.4     .05       0
  4997.6     .07       0  5252.8    .035       0
Bank Sta=4991.4,4997.6
XS Rating Curve= 0 ,0
Exp/Cntr=0.3,0.1

Type RM Length L Ch R = 1 ,17693   ,448,448,448
BEGIN DESCRIPTION:
Stream0518 34.0
END DESCRIPTION:
XS GIS Cut Line= 3
      1987425.02     13867775.02        1987775.       13868075.
      1988495.44     13868222.32
#Sta/Elev= 30
  4543.7 1884.57  4565.1 1877.71  4593.6    1864  4600.2 1857.28  4607.9 1854.95
  4628.7 1841.08  4657.3 1827.85  4663.9 1822.58  4714.3 1795.99  4784.6 1752.98
    4834  1725.7  4862.5 1712.24  4895.3 1702.43  4954.7 1696.26  4976.7 1686.11
  4994.4 1684.48  4994.9 1683.98  5000.6 1684.48  5029.9 1686.62  5080.4 1695.07
  5157.8 1696.78  5239.4 1703.16  5310.9 1704.26  5354.4 1707.51  5443.5 1709.62
  5535.4  1716.9  5555.8 1716.07    5580 1719.89  5606.9 1719.36    5740 1733.37
#Mann= 5 ,-1 , 0
  4543.7      .1       0  4895.3     .07       0  4994.4     .05       0
  5000.6     .07       0  5354.4    .035       0
Bank Sta=4994.4,5000.6
XS Rating Curve= 0 ,0
Exp/Cntr=0.3,0.1

Type RM Length L Ch R = 1 ,17245   ,473,473,473
BEGIN DESCRIPTION:
Stream0518 33.0
END DESCRIPTION:
XS GIS Cut Line= 3
        1987075.       13867975.        1987475.       13868375.
      1987699.78     13868769.01
#Sta/Elev= 30
  4433.6 1890.86  4461.9 1882.05    4476 1867.06  4504.3 1822.98  4518.4 1809.49
  4546.7 1784.43  4560.9 1774.86  4589.2 1748.16  4631.6 1718.22  4652.7 1708.71
    4674 1701.74  4716.4 1691.18  4744.7 1687.38  4815.4 1679.92  4918.7  1677.5
  5002.2 1677.03  5007.2 1678.96  5009.5 1676.74    5010 1676.24  5016.4 1676.74
  5022.3 1686.35  5028.8 1690.33  5034.6 1689.85  5044.7 1692.56  5232.3 1694.85
  5290.1 1695.83  5321.6  1698.4  5357.2    1698  5388.9 1700.93  5452.9    1702
#Mann= 7 ,-1 , 0
  4433.6      .1       0  4652.7     .07       0  4918.7    .035       0
  5009.5    .035       0  5016.4    .035       0  5232.3     .07       0
  5290.1    .035       0
Bank Sta=5009.5,5016.4
XS Rating Curve= 0 ,0
Exp/Cntr=0.3,0.1

Type RM Length L Ch R = 1 ,16772   ,434,434,434
BEGIN DESCRIPTION:
Stream0518 32.0
END DESCRIPTION:
XS GIS Cut Line= 3
      1986974.98     13868224.99        1987075.       13868275.
      1987518.04     13868698.77
#Sta/Elev= 30
  4883.6    1797    4892 1795.51  4897.6 1790.77    4906 1788.91    4920  1779.2
  4928.3  1727.2  4936.7 1711.25  4942.3 1704.69  4950.7 1698.78  4957.3 1691.26
  4959.1 1689.21  4964.7 1674.56  4969.6 1672.11  4970.1 1671.61  4976.5 1672.11
  4998.9 1672.84  5002.5 1674.17  5009.4 1674.56  5016.7 1677.04  5055.3 1679.11
  5080.2 1679.37  5115.7 1682.12    5168 1682.89  5292.5 1685.46  5306.6 1687.51
  5329.2 1687.19  5358.8 1687.14  5455.1 1689.13  5518.9 1693.44  5608.5  1694.9
#Mann= 8 ,-1 , 0
  4883.6      .1       0  4957.3     .07       0  4969.6     .05       0
  4976.5     .07       0  5055.3    .035       0    5168     .07       0
  5329.2    .035       0  5358.8     .07       0
Bank Sta=4969.6,4976.5
XS Rating Curve= 0 ,0
Exp/Cntr=0.3,0.1

Type RM Length L Ch R = 1 ,16338   ,439,439,439
BEGIN DESCRIPTION:
Stream0518 31.0
END DESCRIPTION:
XS GIS Cut Line= 3
      1986775.02     13868375.03        1986975.       13868675.
      1987351.55     13868736.76
#Sta/Elev= 30
  4639.5 1736.17  4642.5 1736.17    4647 1733.19    4653 1733.32    4662 1730.03
    4668 1729.95    4683 1723.98  4740.1 1710.92  4755.1 1704.56  4797.2 1693.84
  4831.7 1690.03  4868.8 1687.34  4920.4 1683.36  4935.4 1681.03  4941.4 1675.37
  4956.4 1668.91  4993.5 1667.51    4994 1667.01  5000.5 1667.51  5020.3 1667.94
  5101.4 1674.08  5131.8 1679.03  5150.7 1684.18  5155.8 1683.54  5182.4 1687.01
  5263.5 1687.88  5292.5 1689.29  5295.6 1689.41  5354.7 1693.66  5381.6 1693.34
#Mann= 7 ,-1 , 0
  4639.5     .07       0  4831.7    .035       0  4868.8     .07       0
  4993.5     .05       0  5000.5     .07       0  5292.5    .035       0
  5295.6     .07       0
Bank Sta=4993.5,5000.5
XS Rating Curve= 0 ,0
Exp/Cntr=0.3,0.1

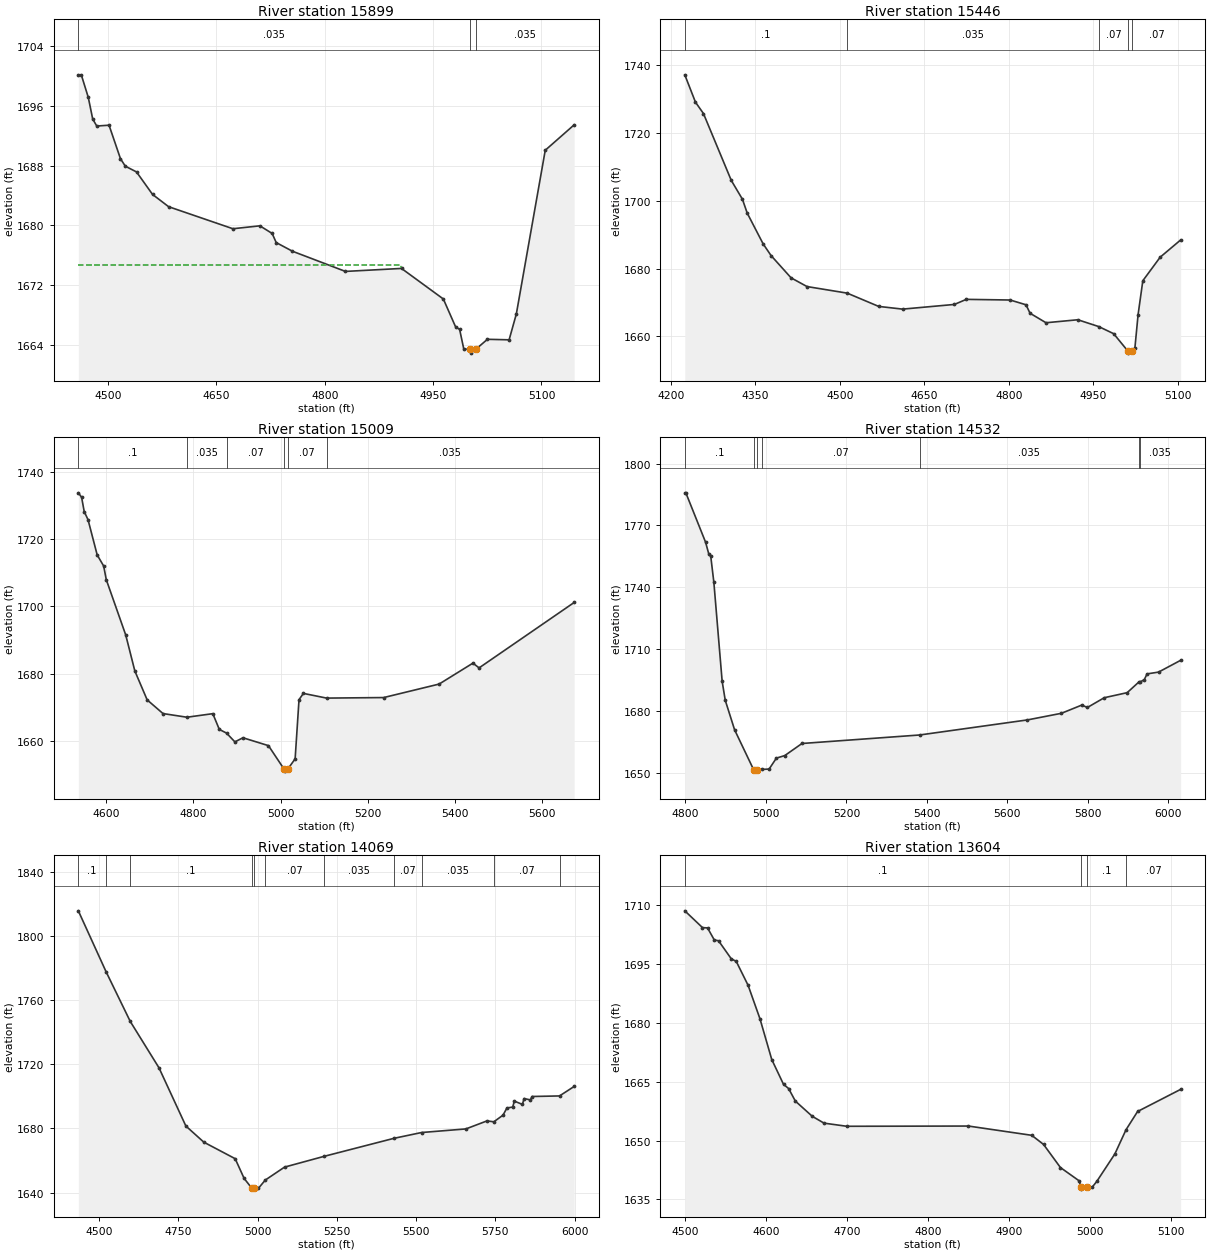
Type RM Length L Ch R = 1 ,15899   ,453,453,453
BEGIN DESCRIPTION:
Stream0518 30.0
END DESCRIPTION:
XS GIS Cut Line= 3
      1986442.58     13868841.09        1986925.       13869075.
      1987074.96       13869075.
#Sta/Elev= 30
  4459.1 1700.14  4463.2 1700.14  4472.9 1697.11    4479 1694.22  4484.6 1693.29
  4501.6  1693.4  4517.4 1688.92  4524.1 1687.92  4539.6 1687.15  4561.8 1684.14
    4584  1682.5    4673 1679.55  4710.3 1679.94  4727.3 1678.92  4732.9  1677.7
  4755.4 1676.54  4828.7 1673.84  4906.3 1674.24  4964.2 1670.15  4981.2 1666.41
  4986.7 1666.09  4992.5 1663.45  5001.6 1663.41  5002.1 1662.91  5008.9 1663.41
  5025.2 1664.76  5055.2 1664.69  5065.2 1668.15  5105.2 1690.05  5145.2 1693.45
#Mann= 3 ,-1 , 0
  4459.1    .035       0  5001.6    .035       0  5008.9    .035       0
#XS Ineff= 2 , 0
         4905.83 1674.64
Permanent Ineff=
       F       F
Bank Sta=5001.6,5008.9
XS Rating Curve= 0 ,0
Exp/Cntr=0.3,0.1

Type RM Length L Ch R = 1 ,15446   ,437,437,437
BEGIN DESCRIPTION:
Stream0518 29.0
END DESCRIPTION:
XS GIS Cut Line= 3
      1986286.17     13868927.05        1986825.       13869475.
        1986925.       13869525.
#Sta/Elev= 30
  4224.6 1737.18  4243.5 1729.12  4257.7 1725.76  4307.1 1706.02  4326.9 1700.46
  4335.4 1696.37  4363.7 1687.27  4377.8 1683.82  4413.3 1677.25  4441.6 1674.68
  4512.9 1672.74  4568.8 1668.82  4611.3 1668.02  4703.2  1669.4  4724.4  1670.9
  4802.2 1670.71  4830.4  1669.3  4837.6  1666.8  4865.9    1664  4922.4 1664.88
  4959.5 1662.87    4986 1660.77  5011.8 1655.53  5012.3 1655.03  5019.1 1655.53
  5023.8 1656.69  5029.4 1666.42  5037.8  1676.4  5068.6 1683.35  5104.9 1688.43
#Mann= 5 ,-1 , 0
  4224.6      .1       0  4512.9    .035       0  4959.5     .07       0
  5011.8     .05       0  5019.1     .07       0
Bank Sta=5011.8,5019.1
XS Rating Curve= 0 ,0
Exp/Cntr=0.3,0.1

Type RM Length L Ch R = 1 ,15009   ,477,477,477
BEGIN DESCRIPTION:
Stream0518 28.0
END DESCRIPTION:
XS GIS Cut Line= 4
      1986274.98     13868974.97      1986488.18     13869283.37
        1986475.       13869475.      1986875.44     13869883.32
#Sta/Elev= 30
  4535.6  1733.8  4543.1 1732.48  4549.1 1728.23  4557.9  1725.8  4578.9 1715.33
  4593.8 1712.03  4599.8 1707.97  4644.5 1691.51  4665.4 1680.82  4693.7 1672.22
  4730.1 1668.15    4785 1667.06  4844.5 1668.12  4859.4 1663.44    4876 1662.34
  4895.2 1659.73  4913.8 1660.95  4972.3 1658.61  5008.7 1651.53  5009.2 1651.03
  5016.1 1651.53  5033.6 1654.69  5042.5 1672.27  5052.5 1674.15  5105.9 1672.75
    5237 1672.91  5364.3 1676.92    5442 1683.15  5456.1 1681.73  5674.5 1701.19
#Mann= 6 ,-1 , 0
  4535.6      .1       0    4785    .035       0    4876     .07       0
  5008.7     .05       0  5016.1     .07       0  5105.9    .035       0
Bank Sta=5008.7,5016.1
XS Rating Curve= 0 ,0
Exp/Cntr=0.3,0.1

Type RM Length L Ch R = 1 ,14532   ,463,463,463
BEGIN DESCRIPTION:
Stream0518 27.0
END DESCRIPTION:
XS GIS Cut Line= 3
      1986024.99     13869074.97        1986075.       13869275.
      1986849.07     13869948.14
#Sta/Elev= 30
  4798.5 1785.81  4801.1 1785.81  4850.1 1761.88  4857.8 1756.39    4863 1755.02
  4870.7 1742.45  4891.3 1694.46    4899 1685.23  4922.2 1670.93    4970 1651.38
  4970.5 1650.88  4977.5 1651.38  4989.5 1651.71    5008 1651.88  5026.1 1657.19
  5046.9 1658.42  5089.7 1664.28  5381.9  1668.4  5649.9 1675.71  5734.4 1678.92
  5784.7 1682.89    5799 1681.75  5840.7 1686.47  5897.7 1688.92  5926.5 1694.05
  5929.8 1694.07  5940.4 1695.29  5947.1 1698.02  5975.6 1698.89  6030.5  1704.6
#Mann= 7 ,-1 , 0
  4798.5      .1       0    4970     .05       0  4977.5      .1       0
  4989.5     .07       0  5381.9    .035       0  5926.5     .07       0
  5929.8    .035       0
Bank Sta=4970,4977.5
XS Rating Curve= 0 ,0
Exp/Cntr=0.3,0.1

Type RM Length L Ch R = 1 ,14069   ,465,465,465
BEGIN DESCRIPTION:
Stream0518 26.0
END DESCRIPTION:
XS GIS Cut Line= 3
      1985475.02     13869225.02        1985875.       13869625.
      1986814.38     13869965.35
#Sta/Elev= 30
    4434 1815.57  4521.4 1777.68  4597.9 1746.63  4688.5 1717.76  4773.4 1681.47
    4830 1671.42    4929 1661.11  4957.2 1648.84  4981.8 1642.65  4982.3 1642.15
  4989.3 1642.65  5002.3 1642.66    5024  1647.8  5084.8 1655.87  5209.8 1662.59
  5429.9  1673.8  5517.4 1677.43    5657 1679.66  5723.6 1684.66  5745.4 1684.11
  5774.2 1688.24  5786.7 1692.73  5804.8 1693.28  5810.1 1696.99  5835.5 1694.94
  5840.8  1698.6  5860.8 1697.74  5866.1 1699.87  5952.6 1700.22  5998.8 1706.13
#Mann= 11 ,-1 , 0
    4434      .1       0  4521.4     .07       0  4597.9      .1       0
  4981.8     .05       0  4989.3      .1       0    5024     .07       0
  5209.8    .035       0  5429.9     .07       0  5517.4    .035       0
  5745.4     .07       0  5952.6    .035       0
Bank Sta=4981.8,4989.3
XS Rating Curve= 0 ,0
Exp/Cntr=0.3,0.1

Type RM Length L Ch R = 1 ,13604   ,469,469,469
BEGIN DESCRIPTION:
Stream0518 25.0
END DESCRIPTION:
XS GIS Cut Line= 3
      1985375.02     13869625.03        1985675.       13870025.
      1985775.03     13870075.02
#Sta/Elev= 30
  4499.8 1708.52  4521.6 1704.25  4527.9 1704.16  4536.2 1701.09  4541.4  1700.9
  4557.1 1696.31  4563.3 1695.63  4577.9 1689.55  4592.5 1681.05  4607.1 1670.64
  4621.6 1664.32  4627.9 1663.25  4636.2 1660.05  4657.1 1656.17  4671.6 1654.43
  4699.8 1653.63  4849.8 1653.69  4927.9 1651.33  4942.5    1649  4963.3 1643.12
  4986.2 1639.76  4988.7 1638.12  4989.2 1637.62  4996.3 1638.12  5002.6 1638.15
  5008.1 1639.57  5030.5  1646.6  5044.2 1652.74  5058.5  1657.4  5111.6 1663.03
#Mann= 4 ,-1 , 0
  4499.8      .1       0  4988.7     .05       0  4996.3      .1       0
  5044.2     .07       0
Bank Sta=4988.7,4996.3
XS Rating Curve= 0 ,0
Exp/Cntr=0.3,0.1

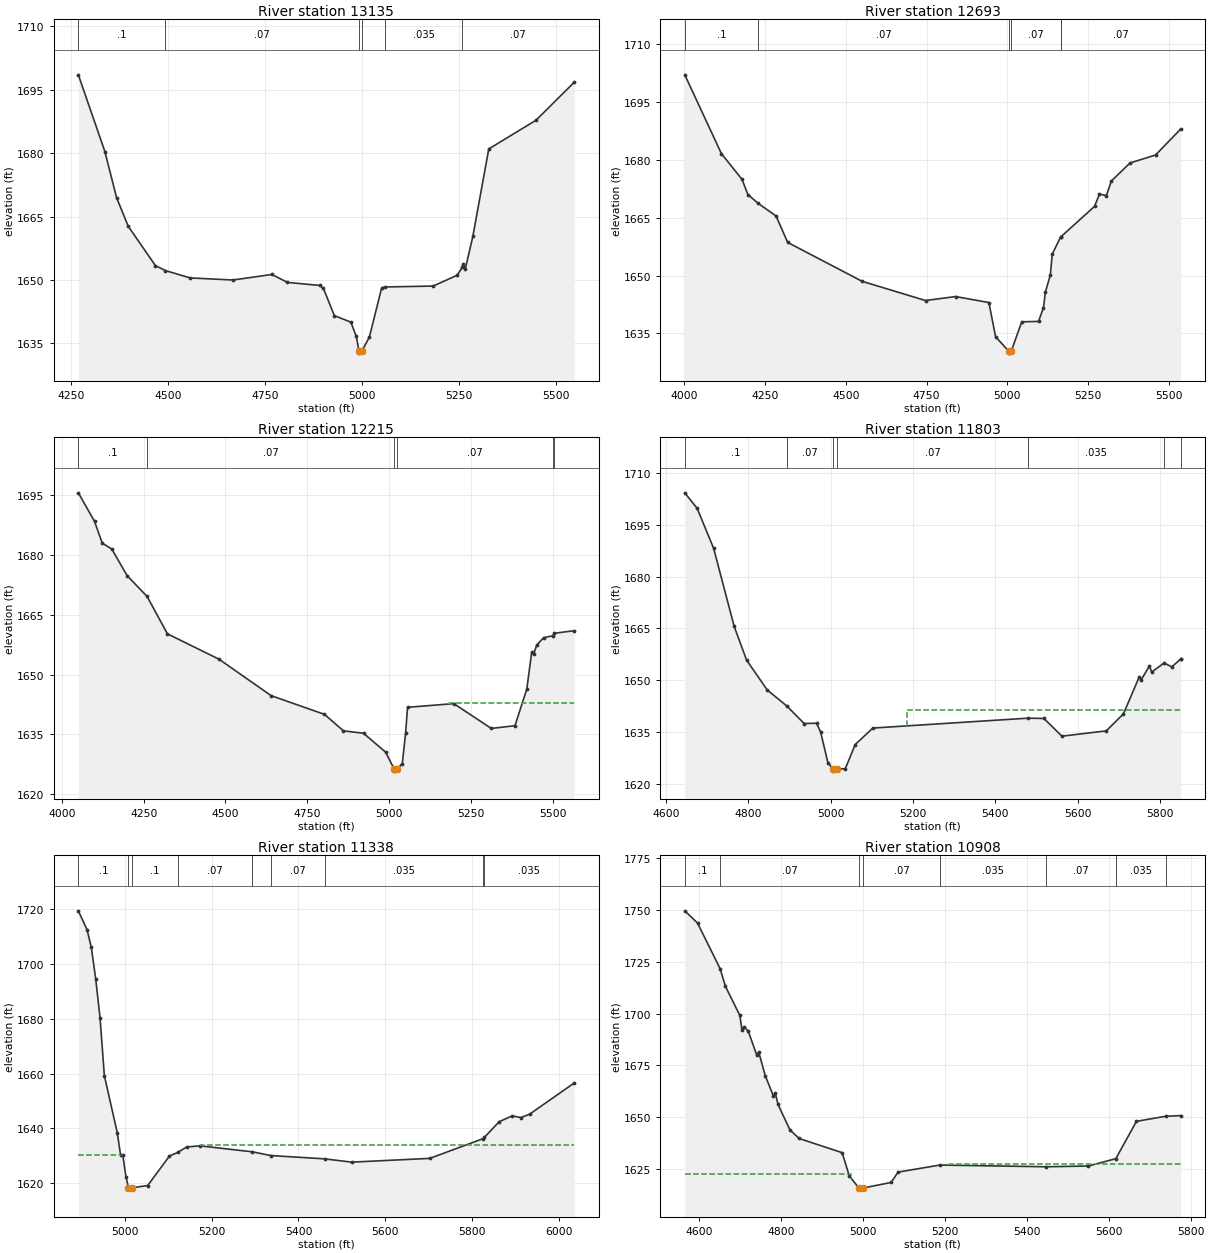
Type RM Length L Ch R = 1 ,13135   ,442,442,442
BEGIN DESCRIPTION:
Stream0518 24.0
END DESCRIPTION:
XS GIS Cut Line= 4
      1985320.49     13869676.55      1985298.21     13870298.21
        1985375.       13870375.      1985910.18     13870489.78
#Sta/Elev= 30
  4269.3 1698.53  4337.8 1680.36  4367.8  1669.5  4397.8 1662.71  4467.9 1653.41
  4493.4 1652.23  4557.5 1650.48    4668 1649.99  4768.1  1651.3  4808.1 1649.43
  4891.4  1648.7    4901 1648.01  4929.2 1641.56  4971.7 1640.02  4985.8 1636.63
  4992.6 1633.19  4993.1 1632.69  5000.3 1633.19  5019.5 1636.51  5051.1 1648.09
  5059.1 1648.34    5184 1648.56  5245.4  1651.1  5258.8 1652.95  5261.5 1653.79
  5266.6 1652.57  5286.3 1660.36  5327.2    1681  5448.9 1687.78  5547.3 1696.75
#Mann= 6 ,-1 , 0
  4269.3      .1       0  4493.4     .07       0  4992.6     .05       0
  5000.3     .07       0  5059.1    .035       0  5258.8     .07       0
Bank Sta=4992.6,5000.3
XS Rating Curve= 0 ,0
Exp/Cntr=0.3,0.1

Type RM Length L Ch R = 1 ,12693   ,478,478,478
BEGIN DESCRIPTION:
Stream0518 23.0
END DESCRIPTION:
XS GIS Cut Line= 3
      1985268.55     13869663.34        1985025.       13870625.
       1985483.7     13870912.56
#Sta/Elev= 30
  4002.4 1702.08  4115.6 1681.64  4179.5 1674.95  4197.5 1671.03  4228.6 1668.79
  4284.7 1665.47  4320.5 1658.62  4550.8 1648.53  4746.8 1643.55  4839.7 1644.58
  4942.8 1643.03  4963.5 1634.19  5004.1 1630.41  5004.6 1629.91  5011.9 1630.41
  5044.5 1638.03  5096.4 1638.14  5111.7 1641.73  5117.6 1645.75  5132.9 1650.16
  5138.8 1655.58  5164.5 1660.01  5165.2 1660.05  5269.6 1667.97  5284.9 1671.17
  5306.1 1670.75  5321.4 1674.51  5379.2 1679.22  5458.1 1681.28  5535.8    1688
#Mann= 6 ,-1 , 0
  4002.4      .1       0  4228.6     .07       0  5004.1     .05       0
  5011.9     .07       0  5164.5    .035       0  5165.2     .07       0
Bank Sta=5004.1,5011.9
XS Rating Curve= 0 ,0
Exp/Cntr=0.3,0.1

Type RM Length L Ch R = 1 ,12215   ,412,412,412
BEGIN DESCRIPTION:
Stream0518 22.0
END DESCRIPTION:
XS GIS Cut Line= 4
      1985199.06     13869693.37      1984857.26     13870489.21
      1984718.45     13870514.56      1984440.29     13870940.43
#Sta/Elev= 30
  4050.2 1695.43  4099.7 1688.29  4123.3 1682.85  4152.3 1681.39  4199.4 1674.72
  4260.4 1669.52  4322.6 1660.17  4480.2 1653.83  4639.7 1644.71  4802.8 1640.03
  4860.7 1635.91  4922.2 1635.31  4989.8 1630.58  5015.9 1626.34  5016.4 1625.84
  5024.6 1626.34  5040.6 1627.71  5050.8 1635.36  5056.7  1641.8  5198.1 1642.72
  5312.7 1636.52  5385.1  1637.2  5421.3 1646.34  5436.4 1655.66  5442.4 1655.05
  5451.5 1657.37  5472.6 1659.19    5501  1659.7  5505.8 1660.32  5566.1 1660.95
#Mann= 6 ,-1 , 0
  4050.2      .1       0  4260.4     .07       0  5015.9     .05       0
  5024.6     .07       0    5501    .035       0  5505.8     .07       0
#XS Ineff= 2 , 0
                         5182.06         1642.91
Permanent Ineff=
       F       F
Bank Sta=5015.9,5024.6
XS Rating Curve= 0 ,0
Exp/Cntr=0.3,0.1

Type RM Length L Ch R = 1 ,11803   ,465,465,465
BEGIN DESCRIPTION:
Stream0518 21.0
END DESCRIPTION:
XS GIS Cut Line= 3
        1984675.     13869775.04        1984675.       13870125.
      1984374.99     13870925.04
#Sta/Elev= 30
  4645.9 1704.15  4675.9 1699.67  4715.9 1688.14  4765.9 1665.59  4795.9  1655.9
  4845.9 1647.29  4893.7 1642.64  4935.9 1637.57  4965.9 1637.66  4975.9 1635.13
  4993.4 1626.32  5006.5 1624.34    5007 1623.84  5015.4 1624.34  5035.9 1624.59
  5059.9 1631.52  5102.7 1636.27  5480.3 1639.13  5518.3 1639.03  5561.9 1633.93
  5669.6 1635.45  5711.4 1640.37  5749.7    1651    5755 1650.28  5774.6 1654.22
  5779.9 1652.42    5810 1655.03  5828.9 1653.94    5850 1656.14  5850.3 1656.14
#Mann= 7 ,-1 , 0
  4645.9      .1       0  4893.7     .07       0  5006.5     .05       0
  5015.4     .07       0  5480.3    .035       0    5810     .07       0
    5850    .035       0
#XS Ineff= 2 , 0
                         5184.62         1641.56
Permanent Ineff=
       F       F
Bank Sta=5006.5,5015.4
XS Rating Curve= 0 ,0
Exp/Cntr=0.3,0.1

Type RM Length L Ch R = 1 ,11338   ,430,430,430
BEGIN DESCRIPTION:
Stream0518 20.0
END DESCRIPTION:
XS GIS Cut Line= 3
        1984275.     13869824.98        1984275.       13869925.
      1984313.26     13870967.68
#Sta/Elev= 30
  4892.4 1719.32  4912.4 1712.48  4922.4 1705.95  4932.4 1694.56  4942.4 1680.42
  4952.4 1659.25  4982.4 1638.26  4989.9 1630.15  4994.9 1630.15  5002.4 1622.25
    5008 1618.35  5008.5 1617.85  5016.9 1618.35  5052.5 1619.17  5102.5 1629.93
    5122 1631.26  5142.5 1633.23  5172.5 1633.64  5293.6 1631.45  5336.5 1630.09
  5460.1 1628.89  5522.8 1627.69  5702.9 1629.06    5825 1636.21    5829 1636.76
    5863 1642.44    5893 1644.56    5913 1643.94  5933.1 1645.17  6035.8 1656.53
#Mann= 9 ,-1 , 0
  4892.4      .1       0    5008     .05       0  5016.9      .1       0
    5122     .07       0  5293.6    .035       0  5336.5     .07       0
  5460.1    .035       0    5825     .07       0    5829    .035       0
#XS Ineff= 2 , 0
         4994.67 1630.25 5173.43         1634.01
Permanent Ineff=
       F       F
Bank Sta=5008,5016.9
XS Rating Curve= 0 ,0
Exp/Cntr=0.3,0.1

Type RM Length L Ch R = 1 ,10908   ,463,463,463
BEGIN DESCRIPTION:
Stream0518 19.0
END DESCRIPTION:
XS GIS Cut Line= 4
      1983824.99     13869824.96      1983918.22     13870185.74
      1984056.59      13870251.4      1984239.71     13870910.54
#Sta/Elev= 30
    4565 1749.62    4596 1743.74  4651.1 1721.76  4664.1 1713.18  4699.3 1699.17
  4704.7 1691.92  4709.9 1693.59    4720 1691.49  4740.2 1680.21  4745.4 1681.48
  4761.3 1670.07  4780.8 1660.47    4786 1661.59  4792.3 1656.27  4821.5 1643.93
  4843.9 1639.78  4949.1 1632.93  4966.3 1621.72  4990.1 1615.85  4990.6 1615.35
  4999.1 1615.85  5068.3 1618.56  5085.5 1623.57  5187.7 1626.97    5446 1626.14
  5548.9 1626.49  5616.7 1630.03  5667.2 1648.07  5738.2 1650.49  5774.9 1650.83
#Mann= 8 ,-1 , 0
    4565      .1       0  4651.1     .07       0  4990.1     .05       0
  4999.1     .07       0  5187.7    .035       0    5446     .07       0
  5616.7    .035       0  5738.2     .07       0
#XS Ineff= 2 , 0
         4971.51 1622.57 5209.87         1627.44
Permanent Ineff=
       F       F
Bank Sta=4990.1,4999.1
XS Rating Curve= 0 ,0
Exp/Cntr=0.3,0.1