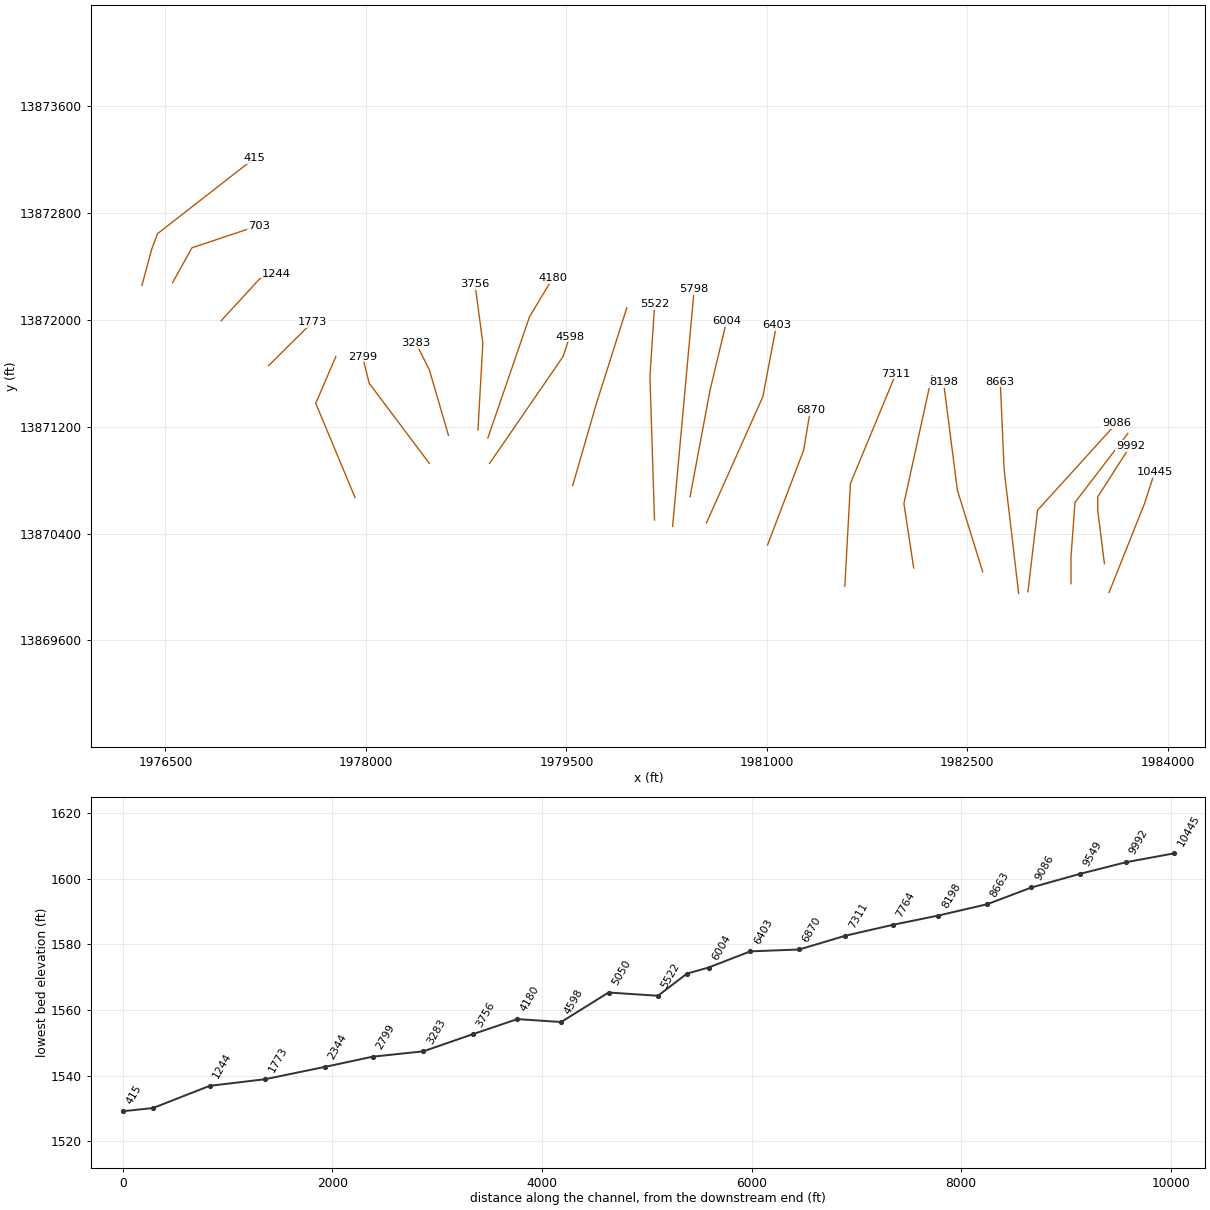
HEC-RAS study Stream0518.prj: Stream0518 Base Level Engineering

--- Stream0518.g01 (geometry) --- (continued)

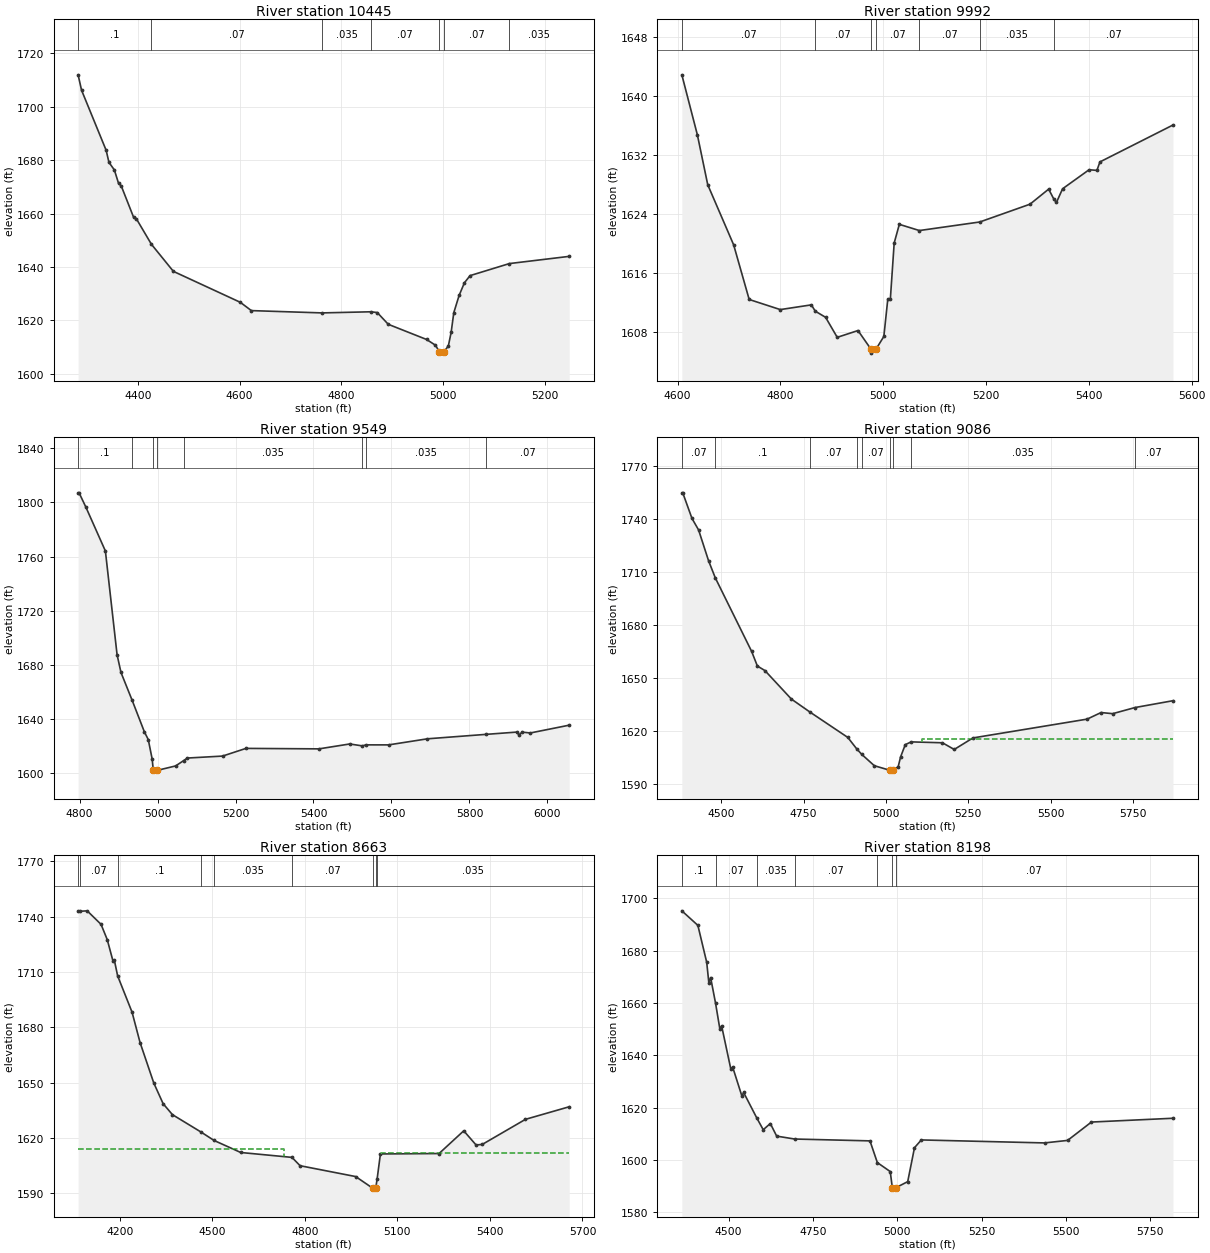
Type RM Length L Ch R = 1 ,10445   ,453,453,453
BEGIN DESCRIPTION:
Stream0518 18.0
END DESCRIPTION:
XS GIS Cut Line= 3
      1983559.58     13869958.72        1983825.       13870625.
      1983901.75     13870860.92
#Sta/Elev= 30
  4282.5 1711.96  4289.3  1706.2  4337.7 1683.67  4343.1  1679.2  4353.8 1676.34
    4362 1671.33  4367.3 1670.37  4391.6 1658.61    4397 1658.07  4426.7 1648.49
  4469.8 1638.37  4601.4 1626.78    4623 1623.68  4762.1 1622.82  4858.1 1623.24
  4870.5 1622.95  4892.1 1618.55  4967.4 1612.87  4984.9 1610.72  4992.5 1608.26
    4993 1607.76  5001.5 1608.26  5010.2 1610.45  5015.7 1615.54  5020.9  1622.9
  5031.3 1629.34  5041.8 1634.11  5052.9 1636.78  5130.1 1641.29  5247.8 1643.99
#Mann= 7 ,-1 , 0
  4282.5      .1       0  4426.7     .07       0  4762.1    .035       0
  4858.1     .07       0  4992.5     .05       0  5001.5     .07       0
  5130.1    .035       0
Bank Sta=4992.5,5001.5
XS Rating Curve= 0 ,0
Exp/Cntr=0.3,0.1

Type RM Length L Ch R = 1 ,9992    ,443,443,443
BEGIN DESCRIPTION:
Stream0518 17.0
END DESCRIPTION:
XS GIS Cut Line= 4
        1983525.     13870174.99        1983475.       13870575.
        1983475.       13870675.      1983719.06     13871055.89
#Sta/Elev= 30
  4608.2 1642.81  4638.4 1634.68  4658.6 1627.91    4709 1619.77  4739.2 1612.37
  4799.7    1611  4860.2 1611.64  4867.7 1610.79  4887.9 1609.95  4910.5 1607.24
  4950.9 1608.16  4976.5  1605.6    4977  1605.1  4985.6  1605.6  5001.2 1607.36
  5008.8 1612.37  5013.8 1612.37  5021.3 1620.02  5031.3 1622.55  5070.3 1621.71
  5187.8 1622.87  5285.5 1625.28  5321.8 1627.32  5332.2 1625.93    5337 1625.52
  5348.9 1627.37  5400.5 1629.95  5415.7 1629.86  5421.6 1631.01  5563.7 1636.01
#Mann= 7 ,-1 , 0
  4608.2     .07       0  4867.7     .07       0  4976.5     .05       0
  4985.6     .07       0  5070.3     .07       0  5187.8    .035       0
  5332.2     .07       0
Bank Sta=4976.5,4985.6
XS Rating Curve= 0 ,0
Exp/Cntr=0.3,0.1

Type RM Length L Ch R = 1 ,9549    ,463,463,463
BEGIN DESCRIPTION:
Stream0518 16.0
END DESCRIPTION:
XS GIS Cut Line= 4
        1983275.       13870025.        1983275.       13870225.
      1983305.01     13870633.58      1983700.22     13871149.79
#Sta/Elev= 30
  4796.2 1807.03  4798.7 1807.03  4816.2 1796.44  4866.2 1764.08  4896.2 1687.43
  4906.2 1674.37  4934.8 1653.86  4966.2 1630.53  4976.2 1624.82  4986.2 1610.45
  4989.1 1602.02  4989.6 1601.52  4998.2 1602.02  5046.3 1605.35  5066.6 1609.23
  5076.4 1611.18  5166.7 1612.63  5226.8 1618.31    5414 1617.96  5492.9 1621.57
  5525.4 1620.16  5534.5 1620.91  5592.7  1620.9  5692.4 1625.39  5841.3 1628.64
  5920.9 1630.34  5927.2 1628.32  5935.4 1630.31  5956.2  1629.7    6056 1635.46
#Mann= 8 ,-1 , 0
  4796.2      .1       0  4934.8     .07       0  4989.1     .05       0
  4998.2     .07       0  5066.6    .035       0  5525.4     .07       0
  5534.5    .035       0  5841.3     .07       0
Bank Sta=4989.1,4998.2
XS Rating Curve= 0 ,0
Exp/Cntr=0.3,0.1

Type RM Length L Ch R = 1 ,9086    ,423,423,423
BEGIN DESCRIPTION:
Stream0518 15.0
END DESCRIPTION:
XS GIS Cut Line= 3
      1982952.78     13869964.48        1983025.       13870575.
      1983614.25     13871224.44
#Sta/Elev= 30
  4380.1 1754.74  4382.9 1754.74  4410.8  1740.3    4431 1733.73  4461.2 1716.36
  4481.6  1706.7  4592.1 1665.06  4609.5 1656.79  4632.4 1654.24  4712.9  1638.1
    4770 1630.67  4884.1 1616.43  4910.8 1610.06  4926.6 1606.82  4964.7 1600.43
  5011.6 1597.87  5012.1 1597.37  5020.7 1597.87  5037.1 1599.83  5044.6 1605.45
  5058.7 1612.34  5076.7 1613.91  5171.6  1613.4  5207.4 1609.62  5264.2 1616.14
  5610.9 1626.77  5653.4  1630.5  5688.6 1629.86  5756.5 1633.33  5871.8 1637.19
#Mann= 9 ,-1 , 0
  4380.1     .07       0  4481.6      .1       0    4770     .07       0
  4910.8    .035       0  4926.6     .07       0  5011.6     .05       0
  5020.7     .07       0  5076.7    .035       0  5756.5     .07       0
#XS Ineff= 2 , 0
                         5108.07         1615.53
Permanent Ineff=
       F       F
Bank Sta=5011.6,5020.7
XS Rating Curve= 0 ,0
Exp/Cntr=0.3,0.1

Type RM Length L Ch R = 1 ,8663    ,465,465,465
BEGIN DESCRIPTION:
Stream0518 14.0
END DESCRIPTION:
XS GIS Cut Line= 3
       1982883.5     13869951.15        1982775.       13870875.
        1982746.     13871536.76
#Sta/Elev= 30
  4064.6 1742.86  4070.8 1742.96  4094.1 1743.21    4139 1735.88  4159.1 1727.59
  4177.3 1716.24  4182.3 1716.34  4192.8 1707.93  4239.6 1688.22  4265.5 1671.77
  4310.1 1649.79  4340.3  1638.6  4370.5 1632.65  4462.8 1623.26  4505.7 1618.63
  4592.1 1612.12  4758.1 1609.47  4784.4 1604.95  4964.6 1599.07    5020 1592.75
  5020.5 1592.25  5029.6 1592.75  5034.2 1597.66  5044.9 1611.33    5235 1611.55
  5315.1 1623.88  5355.1  1616.2  5375.2  1616.5  5515.3 1630.11  5657.2 1636.93
#Mann= 9 ,-1 , 0
  4064.6      .1       0  4070.8     .07       0  4192.8      .1       0
  4462.8     .07       0  4505.7    .035       0  4758.1     .07       0
    5020     .05       0  5029.6     .07       0  5034.2    .035       0
#XS Ineff= 2 , 0
         4732.51 1613.79 5047.31         1611.75
Permanent Ineff=
       F       F
Bank Sta=5020,5029.6
XS Rating Curve= 0 ,0
Exp/Cntr=0.3,0.1

Type RM Length L Ch R = 1 ,8198    ,434,434,434
BEGIN DESCRIPTION:
Stream0518 13.0
END DESCRIPTION:
XS GIS Cut Line= 3
      1982614.03     13870114.58        1982425.       13870725.
      1982321.28     13871534.76
#Sta/Elev= 30
  4361.5 1695.23    4409 1689.67  4435.2 1675.53  4441.6 1667.58  4446.8  1669.7
  4461.4 1659.91  4474.2 1650.01  4479.4 1651.22  4506.8 1634.63    4512 1635.52
  4539.4 1624.42  4544.6 1625.77  4583.9 1615.94  4602.7 1611.52  4623.7  1613.9
  4642.5 1609.08  4695.6 1607.97    4919 1607.26  4940.8 1598.96    4979 1595.53
  4985.3 1589.31  4985.8 1588.81  4994.9 1589.31  5030.8 1591.67  5050.9 1604.65
  5071.1 1607.62  5436.3 1606.48  5504.6 1607.44  5575.2 1614.46  5816.9 1615.91
#Mann= 7 ,-1 , 0
  4361.5      .1       0  4461.4     .07       0  4583.9    .035       0
  4695.6     .07       0  4940.8     .07       0  4985.3     .05       0
  4994.9     .07       0
Bank Sta=4985.3,4994.9
XS Rating Curve= 0 ,0
Exp/Cntr=0.3,0.1

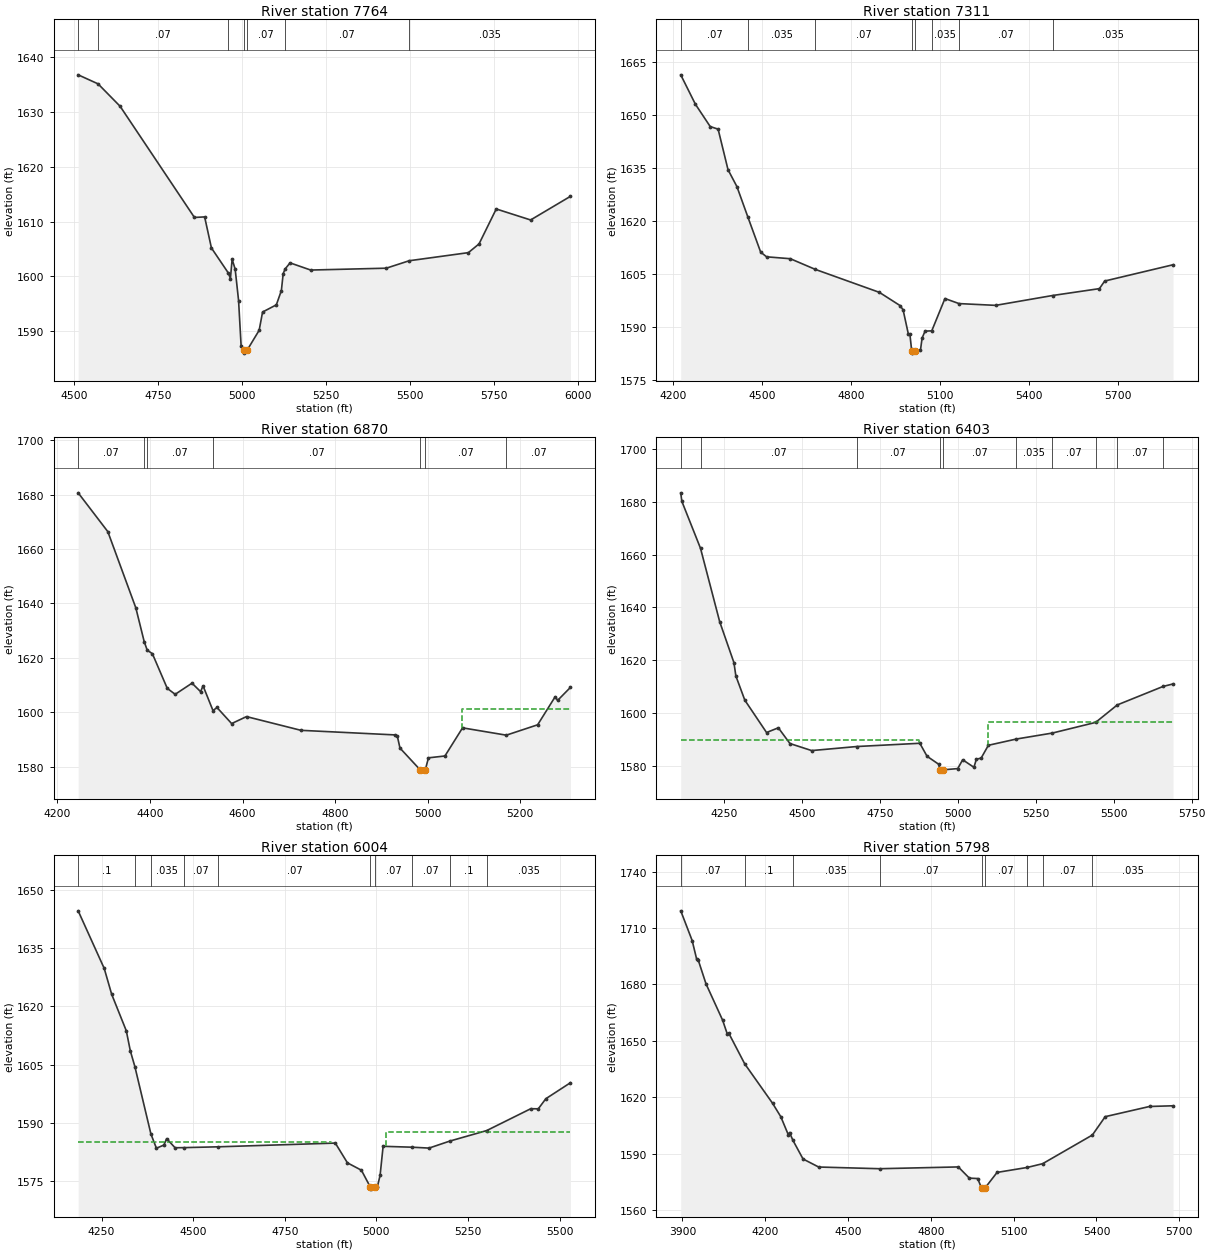
Type RM Length L Ch R = 1 ,7764    ,453,453,453
BEGIN DESCRIPTION:
Stream0518 12.0
END DESCRIPTION:
XS GIS Cut Line= 3
      1982098.15      13870142.5        1982025.       13870625.
      1982234.15     13871580.98
#Sta/Elev= 30
  4512.4 1636.83  4571.7 1635.18  4637.4 1631.08  4858.8 1610.77  4889.2 1610.87
  4909.4  1605.2  4959.7 1600.63    4966 1599.61  4971.1 1603.13  4980.2 1601.31
  4990.3 1595.59  4997.9 1587.29  5005.8 1586.48  5006.3 1585.98  5015.4 1586.48
  5051.6 1590.15  5061.8 1593.49  5102.8  1594.8  5117.8 1597.41  5123.2 1600.51
  5129.1 1601.37  5143.7 1602.47  5205.1 1601.16  5430.3  1601.5  5498.6 1602.86
  5674.9 1604.34  5706.7 1605.94  5757.9 1612.32  5860.3 1610.31    5979 1614.63
#Mann= 7 ,-1 , 0
  4512.4    .035       0  4571.7     .07       0  4959.7     .07       0
  5005.8     .05       0  5015.4     .07       0  5129.1     .07       0
  5498.6    .035       0
Bank Sta=5005.8,5015.4
XS Rating Curve= 0 ,0
Exp/Cntr=0.3,0.1

Type RM Length L Ch R = 1 ,7311    ,441,441,441
BEGIN DESCRIPTION:
Stream0518 11.0
END DESCRIPTION:
XS GIS Cut Line= 3
      1981583.05     13870005.71        1981625.       13870775.
      1981965.59     13871598.08
#Sta/Elev= 30
  4225.5 1661.48  4274.9 1653.16  4324.9 1646.83  4351.6 1646.09    4385 1634.61
  4415.1 1629.81  4452.5 1621.09  4495.2 1611.26  4515.2 1609.93  4595.3 1609.39
  4680.2 1606.35  4895.8 1599.86  4965.9  1596.1  4975.9 1594.88  4993.4  1588.1
  4998.6  1588.1    5005 1583.15  5005.5 1582.65  5016.1 1583.15  5034.5 1583.55
  5039.9 1586.93    5050 1588.89  5072.5 1588.96    5117 1598.11  5164.6 1596.68
  5288.1 1596.18    5480 1598.97  5638.3 1600.92  5656.1 1603.07  5886.7 1607.68
#Mann= 8 ,-1 , 0
  4225.5     .07       0  4452.5    .035       0  4680.2     .07       0
    5005     .05       0  5016.1     .07       0  5072.5    .035       0
  5164.6     .07       0    5480    .035       0
Bank Sta=5005,5016.1
XS Rating Curve= 0 ,0
Exp/Cntr=0.3,0.1

Type RM Length L Ch R = 1 ,6870    ,467,467,467
BEGIN DESCRIPTION:
Stream0518 10.0
END DESCRIPTION:
XS GIS Cut Line= 3
      1981005.18     13870315.05        1981275.       13871025.
      1981324.99     13871324.97
#Sta/Elev= 30
  4244.8 1680.62  4308.9 1666.37  4369.4 1638.39  4387.5 1625.98    4394 1622.86
  4405.2 1621.55  4437.3 1608.84  4454.4 1606.65  4490.8 1610.74  4509.3 1607.63
  4514.6 1609.77  4536.1 1600.67  4544.7 1601.81  4576.4 1595.91  4608.5 1598.47
  4726.1 1593.43    4929 1591.75  4934.3 1591.32  4940.1 1586.91  4983.6 1578.95
  4984.1 1578.45  4994.9 1578.95  5001.6 1583.33  5037.2 1584.01  5075.3 1594.34
  5169.8 1591.65  5237.5 1595.46  5275.5 1605.79  5280.6  1604.4  5308.4  1609.2
#Mann= 7 ,-1 , 0
  4244.8     .07       0  4387.5      .1       0    4394     .07       0
  4536.1     .07       0  4983.6     .05       0  4994.9     .07       0
  5169.8     .07       0
#XS Ineff= 2 , 0
                         5073.93         1601.36
Permanent Ineff=
       F       F
Bank Sta=4983.6,4994.9
XS Rating Curve= 0 ,0
Exp/Cntr=0.3,0.1

Type RM Length L Ch R = 1 ,6403    ,399,399,399
BEGIN DESCRIPTION:
Mapping XS bc509891
END DESCRIPTION:
XS GIS Cut Line= 3
      1980547.58     13870479.24       1980969.6     13871424.35
      1981071.09     13871958.75
#Sta/Elev= 30
  4111.3  1683.4  4114.7 1680.22  4174.7 1662.36  4236.2 1634.53  4281.9 1619.01
  4288.1 1613.95  4316.8 1604.78  4386.5 1592.51  4424.3  1594.3  4461.6 1588.33
  4531.2 1585.66    4676  1587.2  4878.1 1588.43  4901.4 1583.49    4939 1580.45
  4941.8 1578.37  4942.3 1577.87  4953.8 1578.37  4999.7 1578.83  5015.6 1582.18
  5051.6 1579.32  5059.5 1582.37  5074.8 1582.82    5098 1587.67  5187.7 1590.04
  5303.3 1592.31  5441.9 1596.34  5511.4 1602.97  5658.3 1609.98  5690.3 1610.93
#Mann= 10 ,-1 , 0
  4111.3      .1       0  4174.7     .07       0    4676     .07       0
  4941.8     .05       0  4953.8     .07       0  5187.7    .035       0
  5303.3     .07       0  5441.9    .035       0  5511.4     .07       0
  5658.3    .035       0
#XS Ineff= 2 , 0
         4875.57 1589.72  5096.9         1596.33
Permanent Ineff=
       F       F
Bank Sta=4941.8,4953.8
XS Rating Curve= 0 ,0
Exp/Cntr=0.3,0.1

Type RM Length L Ch R = 1 ,6004    ,206,206,206
BEGIN DESCRIPTION:
Stream0518 9.0
END DESCRIPTION:
XS GIS Cut Line= 3
      1980425.01     13870675.04        1980575.       13871475.
      1980698.11      13871990.4
#Sta/Elev= 30
  4186.1 1644.63  4257.3 1629.78  4277.6 1623.13  4317.5 1613.73  4328.5 1608.56
  4340.9 1604.51  4384.7 1587.14  4399.7 1583.48  4420.1 1584.29  4427.7 1585.95
  4450.6  1583.6  4474.3 1583.63  4568.6 1583.84  4888.1  1584.8  4921.1 1579.71
  4959.3 1577.81  4983.8 1573.44  4984.3 1572.94  4995.8 1573.44  5002.6 1573.46
  5010.3 1576.48  5018.5 1583.97    5098 1583.74  5143.9 1583.51  5200.7 1585.32
  5301.2 1588.02  5421.5 1593.65  5442.1 1593.63  5462.7 1596.23  5529.9 1600.35
#Mann= 10 ,-1 , 0
  4186.1      .1       0  4340.9     .07       0  4384.7    .035       0
  4474.3     .07       0  4568.6     .07       0  4983.8     .05       0
  4995.8     .07       0    5098     .07       0  5200.7      .1       0
  5301.2    .035       0
#XS Ineff= 2 , 0
         4877.52 1585.01 5026.17         1587.72
Permanent Ineff=
       F       F
Bank Sta=4983.8,4995.8
XS Rating Curve= 0 ,0
Exp/Cntr=0.3,0.1

Type RM Length L Ch R = 1 ,5798    ,276,276,276
BEGIN DESCRIPTION:
Mapping XS 430bd9e3
END DESCRIPTION:
XS GIS Cut Line= 2
      1980294.62     13870453.86      1980456.12     13872229.74
#Sta/Elev= 30
  3894.1 1719.14  3935.4 1703.35    3952 1693.27    3957 1693.15  3985.6  1680.3
  4045.9 1660.92  4062.4 1653.72  4067.4 1654.21  4125.8 1637.73  4226.6 1616.78
  4256.7 1609.55  4283.3 1600.14  4288.3 1601.19    4300 1597.16  4337.1 1587.11
  4393.7 1582.84  4614.6 1581.94  4899.4 1582.89  4939.5 1576.93  4969.7 1576.71
  4983.7 1571.58  4984.2 1571.08  4995.7 1571.58  5039.9 1579.97  5149.4 1582.62
  5204.9 1584.61  5385.1 1599.87  5431.6 1609.63  5592.2 1615.05  5677.3 1615.42
#Mann= 9 ,-1 , 0
  3894.1     .07       0  4125.8      .1       0    4300    .035       0
  4614.6     .07       0  4983.7     .05       0  4995.7     .07       0
  5149.4      .1       0  5204.9     .07       0  5385.1    .035       0
Bank Sta=4983.7,4995.7
XS Rating Curve= 0 ,0
Exp/Cntr=0.3,0.1

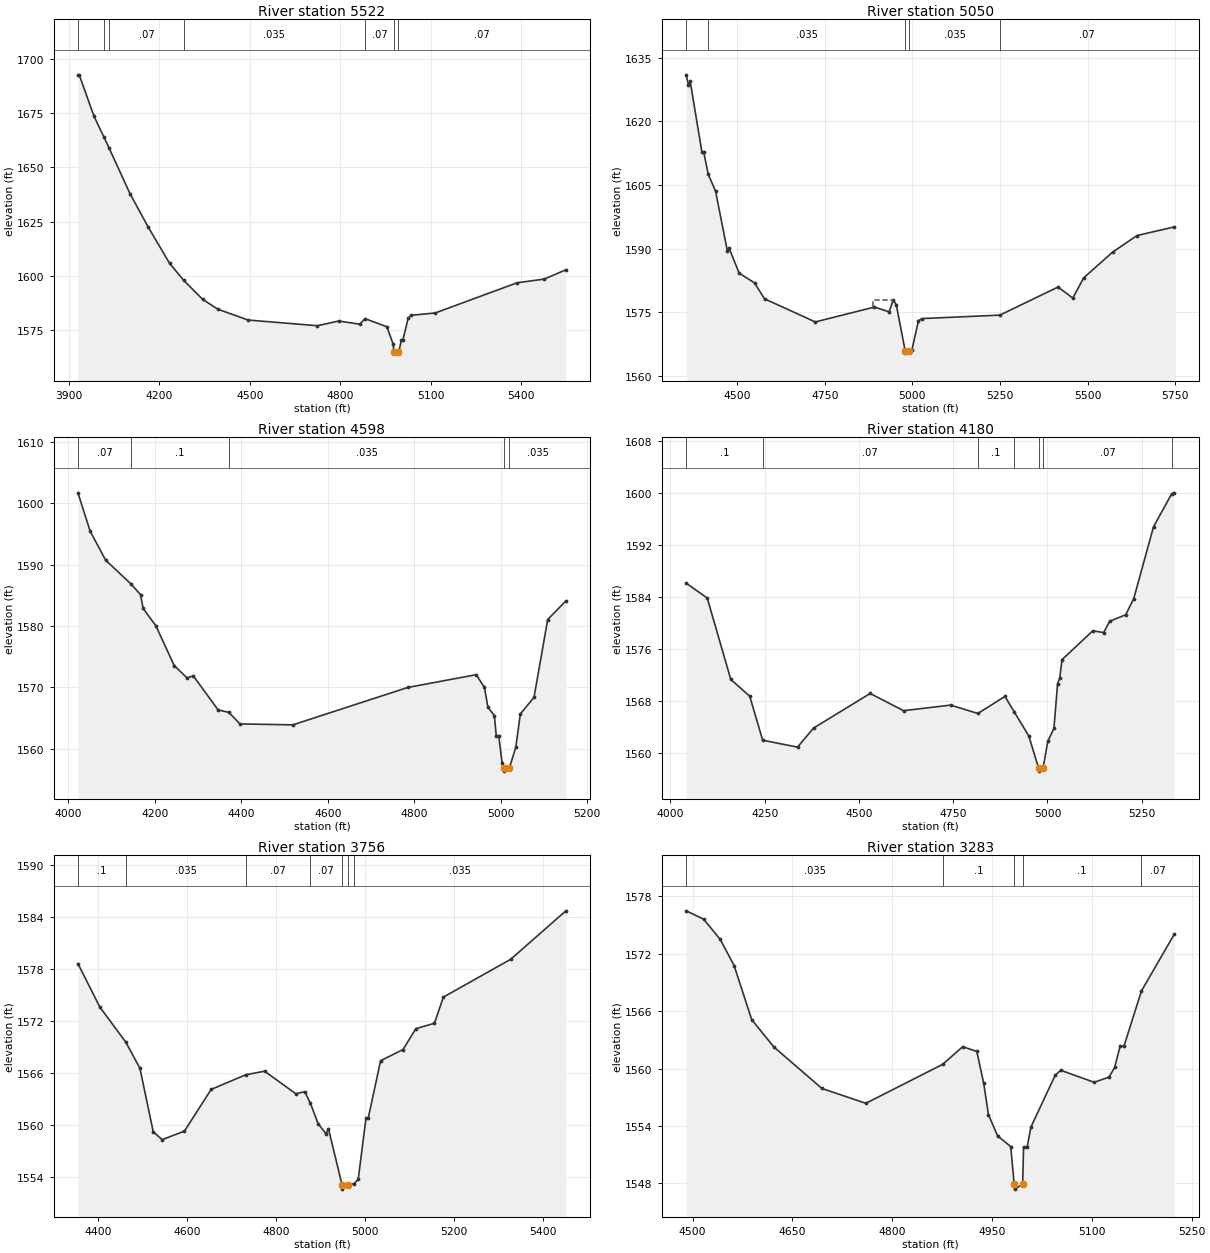
Type RM Length L Ch R = 1 ,5522    ,472,472,472
BEGIN DESCRIPTION:
Stream0518 8.0
END DESCRIPTION:
XS GIS Cut Line= 3
      1980159.17     13870501.68        1980125.       13871575.
       1980160.1     13872116.81
#Sta/Elev= 30
  3930.6 1692.65  3934.8 1692.65  3983.9 1673.53  4016.3 1664.08  4033.4 1659.04
    4104 1637.57    4164 1622.33  4234.1 1605.77  4281.4 1597.84  4344.1 1589.09
  4394.2 1584.58  4494.2 1579.59  4724.3 1576.96  4794.4 1579.14  4864.4 1577.67
  4881.8 1580.23  4954.4 1576.48  4974.4  1568.7  4978.4 1564.83  4978.9 1564.33
  4990.4 1564.83  4994.5 1565.32    5002 1570.18    5007 1570.18  5024.5  1580.3
  5034.5 1581.76  5114.7 1582.86  5385.3 1596.75  5475.4 1598.46  5547.4 1602.76
#Mann= 7 ,-1 , 0
  3930.6     .07       0  4016.3      .1       0  4033.4     .07       0
  4281.4    .035       0  4881.8     .07       0  4978.4     .05       0
  4990.4     .07       0
Bank Sta=4978.4,4990.4
XS Rating Curve= 0 ,0
Exp/Cntr=0.3,0.1

Type RM Length L Ch R = 1 ,5050    ,452,452,452
BEGIN DESCRIPTION:
Stream0518 7.0
END DESCRIPTION:
XS GIS Cut Line= 3
      1979546.86     13870758.89        1979725.       13871375.
      1979952.09     13872090.69
#Sta/Elev= 30
  4354.8 1631.01    4361  1628.7  4366.2  1629.5  4399.8  1612.7    4405 1612.68
  4417.8 1607.53  4438.7 1603.51  4472.3 1589.45  4477.5 1590.03  4505.9  1584.2
  4549.9 1581.89  4578.3 1578.14  4723.2 1572.68    4892  1576.2  4933.7 1575.05
  4945.7 1577.94  4954.5 1576.62  4979.7 1565.82  4980.2 1565.32  4991.8 1565.82
  4998.8 1566.08  5017.5 1572.96  5027.6 1573.48  5249.7 1574.29  5415.8 1580.92
  5457.8 1578.32  5489.2 1583.11  5571.3 1589.15  5641.1 1593.08    5747  1595.1
#Mann= 5 ,-1 , 0
  4354.8      .1       0  4417.8    .035       0  4979.7    .035       0
  4991.8    .035       0  5249.7     .07       0
#XS Ineff= 1 ,-1
 4888.89 4946.141577.975
Permanent Ineff=
       F
Bank Sta=4979.7,4991.8
XS Rating Curve= 0 ,0
Exp/Cntr=0.3,0.1

Type RM Length L Ch R = 1 ,4598    ,418,418,418
BEGIN DESCRIPTION:
Stream0518 6.0
END DESCRIPTION:
XS GIS Cut Line= 3
      1978925.01     13870925.01        1979475.       13871725.
      1979524.99     13871874.98
#Sta/Elev= 30
  4022.2 1601.72  4050.6 1595.44  4086.4 1590.72  4145.5 1586.82    4167 1585.11
    4173 1582.87  4202.8 1579.99  4244.8 1573.55  4274.5 1571.53  4289.2 1571.85
  4346.3 1566.32  4371.6 1565.89    4397 1564.02  4519.5 1563.87  4785.3 1569.97
  4943.6 1572.05  4962.7 1569.97  4970.7 1566.74  4985.6 1565.39    4990 1562.11
  4995.6 1562.11  5003.6 1557.63    5008 1556.82  5008.5 1556.32  5020.2 1556.82
  5035.2 1560.19  5045.7 1565.64  5077.3 1568.36    5109 1581.05  5151.1 1584.09
#Mann= 5 ,-1 , 0
  4022.2     .07       0  4145.5      .1       0  4371.6    .035       0
    5008    .035       0  5020.2    .035       0
Bank Sta=5008,5020.2
XS Rating Curve= 0 ,0
Exp/Cntr=0.3,0.1

Type RM Length L Ch R = 1 ,4180    ,424,424,424
BEGIN DESCRIPTION:
Stream0518 5.0
END DESCRIPTION:
XS GIS Cut Line= 3
      1978912.42     13871115.62        1979225.       13872025.
      1979396.51     13872309.73
#Sta/Elev= 30
  4041.9 1586.13  4097.7 1583.84  4160.2 1571.32  4210.4 1568.74  4244.7 1561.97
  4337.1  1560.9  4379.6 1563.83  4529.8 1569.16  4618.3 1566.51  4743.2 1567.37
  4815.4 1566.08  4887.2 1568.71  4911.8 1566.33  4950.6  1562.6  4976.2 1557.71
  4976.7 1557.21  4988.5 1557.71  5000.9 1561.81  5017.1 1563.77  5026.8 1570.67
  5032.6 1571.55  5038.5 1574.36  5120.2  1578.8  5149.1 1578.53  5164.7 1580.26
  5207.4 1581.27  5228.8 1583.76  5281.2 1594.81  5329.6  1599.9  5335.9 1600.03
#Mann= 7 ,-1 , 0
  4041.9      .1       0  4244.7     .07       0  4815.4      .1       0
  4911.8     .07       0  4976.2     .05       0  4988.5     .07       0
  5329.6      .1       0
#XS Ineff= 1 ,-1
 4524.22 4880.49 1568.16
Permanent Ineff=
       F
Bank Sta=4976.2,4988.5
XS Rating Curve= 0 ,0
Exp/Cntr=0.3,0.1

Type RM Length L Ch R = 1 ,3756    ,473,473,473
BEGIN DESCRIPTION:
Stream0518 4.0
END DESCRIPTION:
XS GIS Cut Line= 3
      1978838.45     13871175.94        1978875.       13871825.
      1978815.94       13872268.
#Sta/Elev= 30
  4354.8 1578.63  4403.9 1573.63  4462.3 1569.58  4494.1 1566.57  4524.1 1559.23
  4544.2 1558.33  4594.2 1559.31  4654.3 1564.12    4732 1565.81  4774.5 1566.22
  4844.6 1563.62  4864.7 1563.86  4877.2 1562.56  4894.7 1560.17  4912.9 1558.99
  4917.9 1559.61  4948.5 1553.12    4949 1552.62  4961.1 1553.12  4975.9 1553.26
  4984.9 1553.75  5002.4 1560.81  5007.4 1560.81  5035.2 1567.43  5085.6 1568.72
  5114.6 1571.13  5156.2 1571.75  5176.4 1574.77  5327.7 1579.13  5451.8 1584.72
#Mann= 7 ,-1 , 0
  4354.8      .1       0  4462.3    .035       0    4732     .07       0
  4877.2     .07       0  4948.5     .05       0  4961.1     .07       0
  4975.9    .035       0
Bank Sta=4948.5,4961.1
XS Rating Curve= 0 ,0
Exp/Cntr=0.3,0.1

Type RM Length L Ch R = 1 ,3283    ,484,484,484
BEGIN DESCRIPTION:
Stream0518 3.0
END DESCRIPTION:
XS GIS Cut Line= 3
      1978617.61     13871135.84        1978475.       13871625.
      1978375.01     13871824.97
#Sta/Elev= 30
  4490.5  1576.5  4516.7 1575.63  4541.7 1573.51  4562.5 1570.77  4588.9 1565.12
  4622.3 1562.25  4694.5 1557.91  4760.4 1556.36  4875.9 1560.44  4905.9 1562.28
  4927.1 1561.79  4937.5 1558.45  4944.6 1555.18  4958.4 1552.95  4978.1 1551.83
  4983.3 1547.88  4983.8 1547.38    4996 1547.88  4997.4  1551.8  5002.8  1551.8
  5008.4 1553.87  5044.7 1559.27  5053.1 1559.82  5103.4 1558.56  5125.8  1559.1
  5134.2 1560.11  5142.6 1562.39  5148.2 1562.33  5174.5 1568.12  5223.6 1574.03
#Mann= 5 ,-1 , 0
  4490.5    .035       0  4875.9      .1       0  4983.3     .05       0
    4996      .1       0  5174.5     .07       0
Bank Sta=4983.3,4996
XS Rating Curve= 0 ,0
Exp/Cntr=0.3,0.1

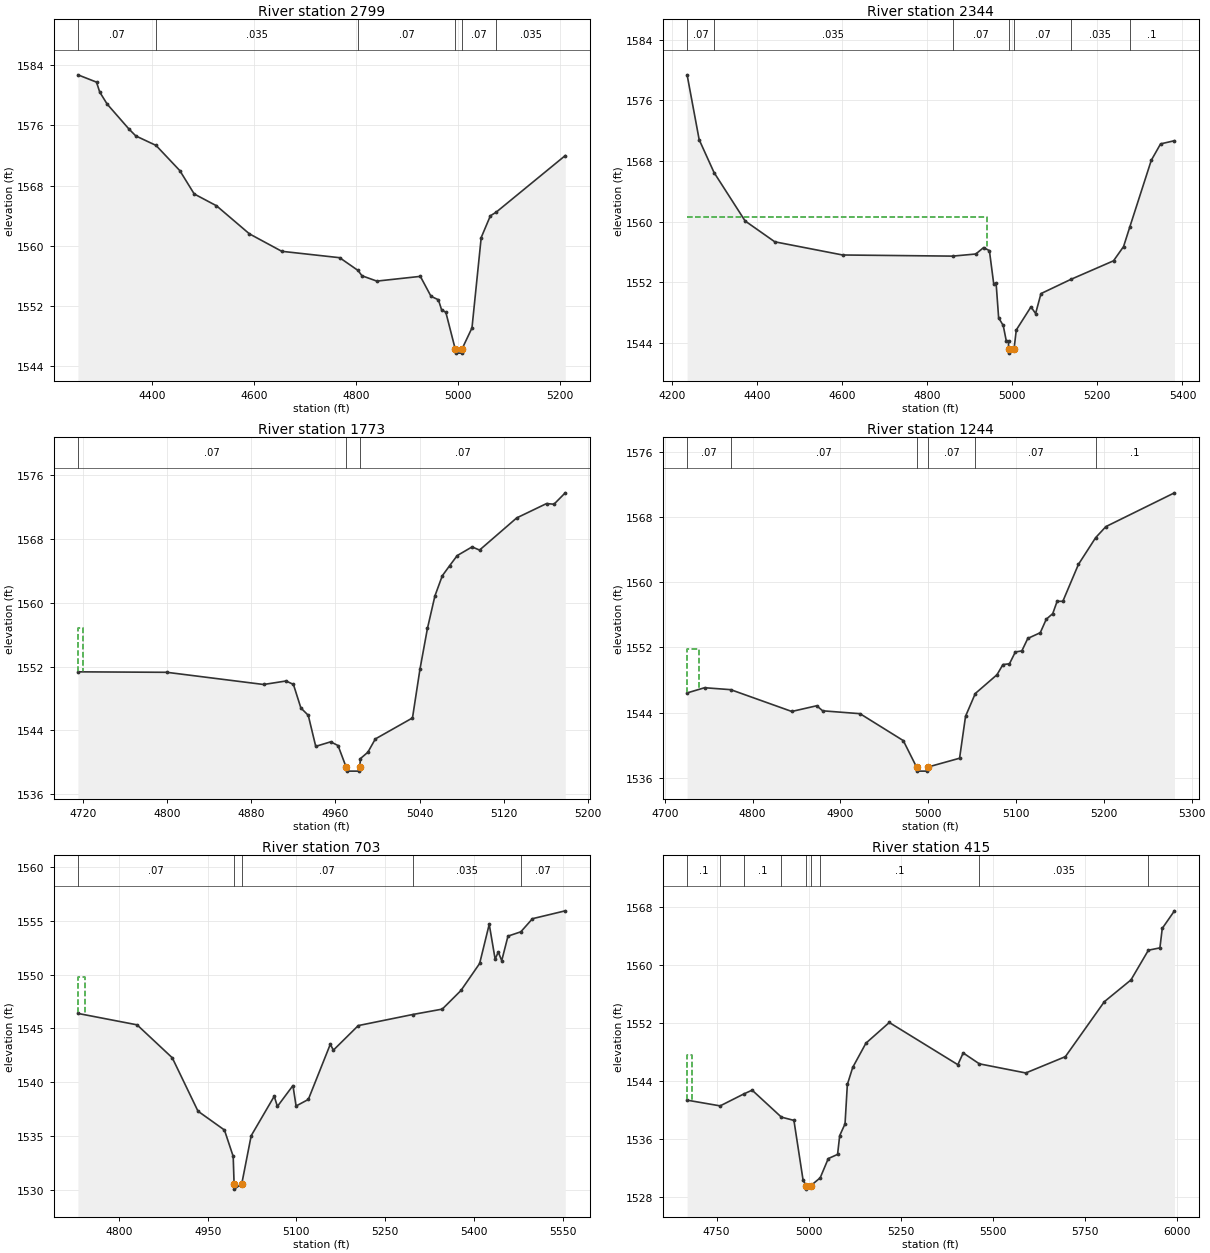
Type RM Length L Ch R = 1 ,2799    ,455,455,455
BEGIN DESCRIPTION:
Stream0518 2.0
END DESCRIPTION:
XS GIS Cut Line= 3
      1978475.03     13870924.97        1978025.       13871525.
        1977975.       13871725.
#Sta/Elev= 30
  4254.5 1582.72    4291 1581.75  4297.3 1580.43  4311.8 1578.84  4354.5 1575.53
  4368.1  1574.6  4407.8 1573.34  4454.5 1569.99  4482.7 1566.89  4526.4 1565.32
    4591 1561.59  4654.5 1559.27  4768.1 1558.42  4804.2 1556.72  4811.8 1556.02
    4841 1555.31  4926.4 1555.94  4947.3 1553.29  4961.8 1552.83  4968.1 1551.49
  4976.4 1551.17    4995 1546.24  4995.5 1545.74  5007.3 1545.74  5007.8 1546.24
  5027.7 1549.09  5045.8  1561.1  5063.8 1563.99    5075 1564.46  5210.7 1571.99
#Mann= 6 ,-1 , 0
  4254.5     .07       0  4407.8    .035       0  4804.2     .07       0
    4995     .05       0  5007.8     .07       0    5075    .035       0
Bank Sta=4995,5007.8
XS Rating Curve= 0 ,0
Exp/Cntr=0.3,0.1

Type RM Length L Ch R = 1 ,2344    ,571,571,571
BEGIN DESCRIPTION:
Stream0518 1.0
END DESCRIPTION:
XS GIS Cut Line= 3
      1977918.97     13870669.11        1977625.       13871375.
      1977774.98     13871724.96
#Sta/Elev= 30
  4235.8 1579.38  4264.2 1570.81  4299.1 1566.48  4372.2 1560.08  4441.9 1557.33
  4601.2 1555.59  4859.9 1555.44  4914.3 1555.72  4932.7 1556.57  4946.3 1556.16
  4956.6 1551.71    4962 1551.91    4968 1547.29  4978.8 1546.28  4985.8 1544.29
  4991.2 1544.27  4991.3 1543.13  4991.8 1542.63  5004.1 1543.13  5009.5 1545.69
    5044 1548.74  5054.9 1547.86  5067.5 1550.49  5137.8 1552.37    5238 1554.82
  5261.6  1556.7  5275.9 1559.22  5326.8  1568.1  5348.6 1570.26  5381.2 1570.68
#Mann= 7 ,-1 , 0
  4235.8     .07       0  4299.1    .035       0  4859.9     .07       0
  4991.3     .05       0  5004.1     .07       0  5137.8    .035       0
  5275.9      .1       0
#XS Ineff= 2 , 0
         4939.66  1560.6
Permanent Ineff=
       F       F
Bank Sta=4991.3,5004.1
XS Rating Curve= 0 ,0
Exp/Cntr=0.3,0.1

Type RM Length L Ch R = 1 ,1773    ,529,529,529
BEGIN DESCRIPTION:
Stream0518 0.3
END DESCRIPTION:
XS GIS Cut Line= 2
      1977272.84     13871657.65       1977601.2     13871983.93
#Sta/Elev= 30
  4715.5 1551.34    4800 1551.28  4891.9 1549.75  4913.2 1550.19  4920.2 1549.76
  4927.3  1546.8  4934.3 1545.88  4941.4 1541.98  4955.6 1542.55  4962.6 1542.08
  4970.3 1539.37  4970.8 1538.87  4982.7 1538.87  4983.2 1539.37  4983.9 1540.45
  4990.9 1541.24    4998 1542.91  5033.3 1545.55  5040.4 1551.67  5047.5 1556.79
  5054.6 1560.87  5061.6  1563.4  5068.7 1564.69  5075.8 1565.94  5089.9 1567.03
    5097 1566.63  5132.3 1570.67  5160.6 1572.47  5167.7 1572.39  5178.4 1573.82
#Mann= 3 ,-1 , 0
  4715.5     .07       0  4970.3     .05       0  4983.2     .07       0
#XS Ineff= 2 , 0
         4719.98 1556.88
Permanent Ineff=
       F       F
Bank Sta=4970.3,4983.2
XS Rating Curve= 0 ,0
Exp/Cntr=0.3,0.1

Type RM Length L Ch R = 1 ,1244    ,541,541,541
BEGIN DESCRIPTION:
Stream0518 0.2
END DESCRIPTION:
XS GIS Cut Line= 3
      1976917.64     13871994.08      1977205.64     13872307.45
      1977330.14     13872342.67
#Sta/Elev= 30
  4725.4 1546.43  4745.3 1547.07  4775.1 1546.83  4844.6 1544.16    4873 1544.86
  4879.8 1544.24  4922.3 1543.89  4971.6 1540.59  4986.7 1537.35  4987.2 1536.85
  4999.1 1536.85  4999.6 1537.35  5035.7 1538.43  5042.5 1543.57  5053.6 1546.36
  5078.3 1548.66  5085.1 1549.91  5092.5    1550  5099.2 1551.45  5106.6 1551.58
  5113.4 1553.11  5127.6 1553.81  5134.4 1555.46  5141.8 1556.15  5146.8 1557.66
  5153.3 1557.66  5171.1 1562.19  5190.7 1565.46  5202.3 1566.81  5280.4 1570.95
#Mann= 6 ,-1 , 0
  4725.4     .07       0  4775.1     .07       0  4986.7     .05       0
  4999.6     .07       0  5053.6     .07       0  5190.7      .1       0
#XS Ineff= 2 , 0
         4739.01 1551.76
Permanent Ineff=
       F       F
Bank Sta=4986.7,4999.6
XS Rating Curve= 0 ,0
Exp/Cntr=0.3,0.1

Type RM Length L Ch R = 1 ,703     ,288,288,288
BEGIN DESCRIPTION:
Stream0518 0.1
END DESCRIPTION:
XS GIS Cut Line= 3
      1976553.92     13872278.33      1976698.33     13872539.09
      1977196.81     13872706.14
#Sta/Elev= 30
  4730.6  1546.4  4830.6 1545.34  4890.1 1542.28  4933.6 1537.32  4978.3 1535.57
  4993.1 1533.12  4994.6 1530.58  4995.1 1530.08  5007.6 1530.58  5023.5 1535.04
  5062.5 1538.71  5067.8 1537.76  5094.1  1539.7  5099.4  1537.8  5120.1 1538.41
  5157.2 1543.53  5162.5 1542.99  5204.5 1545.27  5296.6  1546.3  5346.5  1546.8
  5378.1 1548.53  5409.7 1551.04  5425.9 1554.68  5435.9 1551.44  5441.2 1552.11
    5447  1551.3  5457.6 1553.58  5479.3 1553.98    5499  1555.2  5554.4 1555.93
#Mann= 5 ,-1 , 0
  4730.6     .07       0  4994.6     .05       0  5007.6     .07       0
  5296.6    .035       0  5479.3     .07       0
#XS Ineff= 2 , 0
         4742.38 1549.76
Permanent Ineff=
       F       F
Bank Sta=4994.6,5007.6
XS Rating Curve= 0 ,0
Exp/Cntr=0.3,0.1

Type RM Length L Ch R = 1 ,415     ,0,0,0
BEGIN DESCRIPTION:
Stream0518 0.5
END DESCRIPTION:
XS GIS Cut Line= 4
      1976324.55     13872257.56      1976397.48     13872528.42
      1976440.88     13872644.74      1977166.13     13873210.37
#Sta/Elev= 30
  4669.9 1541.37  4759.7 1540.58  4823.4 1542.21  4846.6 1542.75  4926.1 1539.03
  4960.2 1538.58  4985.2  1530.3  4993.6  1529.6  4994.1  1529.1  5006.6  1529.6
  5031.6 1530.66  5053.5 1533.31  5078.8 1533.89  5084.6 1536.48  5099.1  1538.1
  5105.4 1543.53  5119.9 1545.88  5155.9 1549.23  5219.4 1552.08  5405.7 1546.26
  5420.2 1547.88  5464.1 1546.38  5590.3 1545.12  5697.9 1547.37  5803.8 1554.95
  5876.1 1557.95  5923.5 1562.05  5954.8 1562.37  5961.2 1565.06  5994.3 1567.48
#Mann= 9 ,-1 , 0
  4669.9      .1       0  4759.7     .07       0  4823.4      .1       0
  4926.1     .07       0  4993.6     .05       0  5006.6     .07       0
  5031.6      .1       0  5464.1    .035       0  5923.5     .07       0
#XS Ineff= 2 , 0
         4683.92 1547.64 5236.36         1550.84
Permanent Ineff=
       F       F
Bank Sta=4993.6,5006.6
XS Rating Curve= 0 ,0
Exp/Cntr=0.3,0.1

Chan Stop Cuts=-1
Use User Specified Reach Order=0
Composite Channel Slope=5