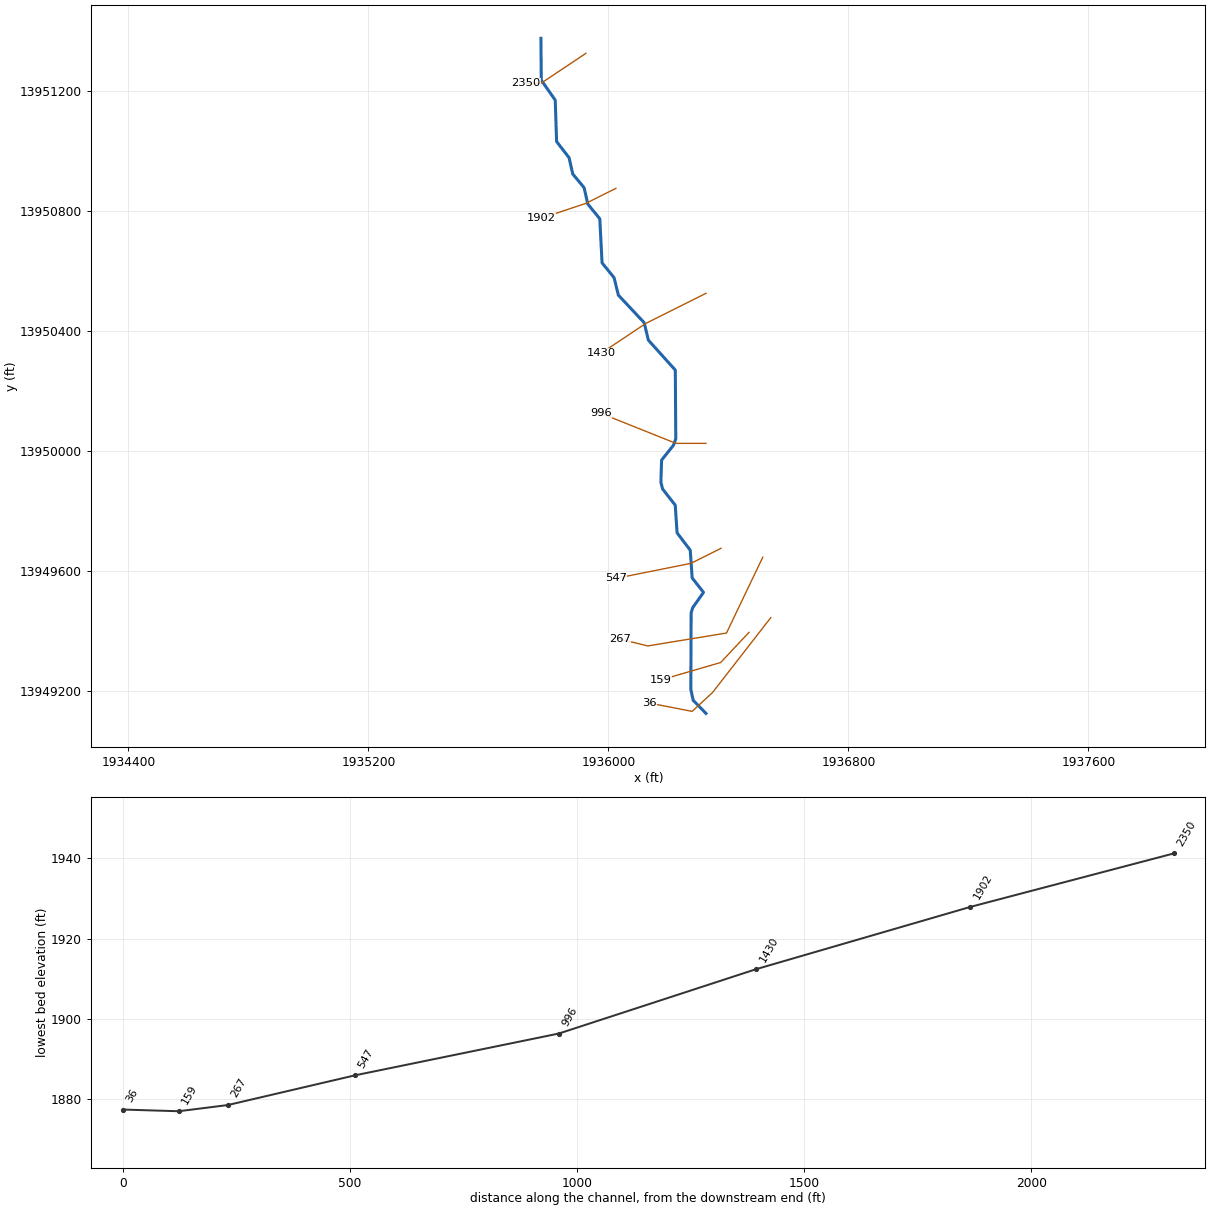
--- Stream0519.prj (project) ---

Proj Title=Stream0519 Base Level Engineering
Current Plan=p01
Default Exp/Contr=0.3,0.1
English Units
Geom File=g01
Flow File=f01
Plan File=p01
Y Axis Title=Elevation
X Axis Title(PF)=Main Channel Distance
X Axis Title(XS)=Station
BEGIN DESCRIPTION:
Stream0519
END DESCRIPTION:
DSS Export Rating Curves= 0
DSS Export Rating Curve Sorted= 0
DSS Export Volume Flow Curves= 0
DXF OffsetX= 0
DXF OffsetY= 0
DXF ScaleX= 1
DXF ScaleY= 10

--- Stream0519.p01 (plan) ---

Plan Title=Multiple Run
Short Identifier=Multiple
Geom File=g01
Flow File=f01
Subcritical Flow
K Sum by GR= 0
Std Step Tol= 0.01
Critical Tol= 0.01
Num of Std Step Trials= 20
Max Error Tol= 0.3
Flow Tol Ratio= 0.001
Split Flow NTrial= 30
Split Flow Tol= 0.02
Split Flow Ratio= 0.02
Log Output Level= 0
Friction Slope Method= 1
Unsteady Friction Slope Method= 2
Unsteady Bridges Friction Slope Method= 1
Parabolic Critical Depth
Global Vel Dist=  1 , 1 , 1
Global Log Level= 0
CheckData=True
Encroach Param= -1, 0, 0, 0
BEGIN DESCRIPTION:
Multiple Run
END DESCRIPTION:

--- Stream0519.f01 (steady flow) ---

Flow Title=Multiple
Program Version=4.10
Number of Profiles= 7
Profile Names=10-year,25-year,50-year,1pct_min,100-year,1pct_plu,500-year
River Rch & RM=Stream0519,Reach-1         ,2350
     471     761    1023     669    1335    2664    2234
Boundary for River Rch & Prof#=Stream0519,Reach-1         , 1
Up Type= 0
Dn Type= 3
Dn Slope=0.005
Boundary for River Rch & Prof#=Stream0519,Reach-1         , 2
Up Type= 0
Dn Type= 3
Dn Slope=0.005
Boundary for River Rch & Prof#=Stream0519,Reach-1         , 3
Up Type= 0
Dn Type= 3
Dn Slope=0.005
Boundary for River Rch & Prof#=Stream0519,Reach-1         , 4
Up Type= 0
Dn Type= 3
Dn Slope=0.005
Boundary for River Rch & Prof#=Stream0519,Reach-1         , 5
Up Type= 0
Dn Type= 3
Dn Slope=0.005
Boundary for River Rch & Prof#=Stream0519,Reach-1         , 6
Up Type= 0
Dn Type= 3
Dn Slope=0.005
Boundary for River Rch & Prof#=Stream0519,Reach-1         , 7
Up Type= 0
Dn Type= 3
Dn Slope=0.005
DSS Import GetInterval= 0
DSS Import GetPeak= 0
DSS Import FillOption= 0

--- Stream0519.g01 (geometry) ---

Geom Title=Existing Conditions

River Reach=Stream0519,Reach-1
Reach XY= 30
      1935775.00     13951375.00      1935776.17     13951235.48
      1935822.73     13951169.06      1935827.25     13951030.93
      1935868.88     13950977.18      1935881.08     13950922.80
      1935918.92     13950877.20      1935931.12     13950822.82
      1935971.24     13950773.44      1935978.76     13950626.56
      1936018.86     13950577.17      1936033.16     13950518.95
      1936119.13     13950427.28      1936133.18     13950368.96
      1936222.94     13950269.14      1936224.48     13950040.22
      1936216.85     13950018.94      1936177.17     13949969.02
      1936174.90     13949895.10      1936180.68     13949872.69
      1936222.64     13949819.03      1936228.85     13949726.60
      1936272.65     13949669.02      1936279.09     13949576.50
      1936316.92     13949528.30      1936281.02     13949477.45
      1936275.66     13949459.84      1936274.64     13949204.85
      1936282.43     13949168.65      1936325.00     13949125.00

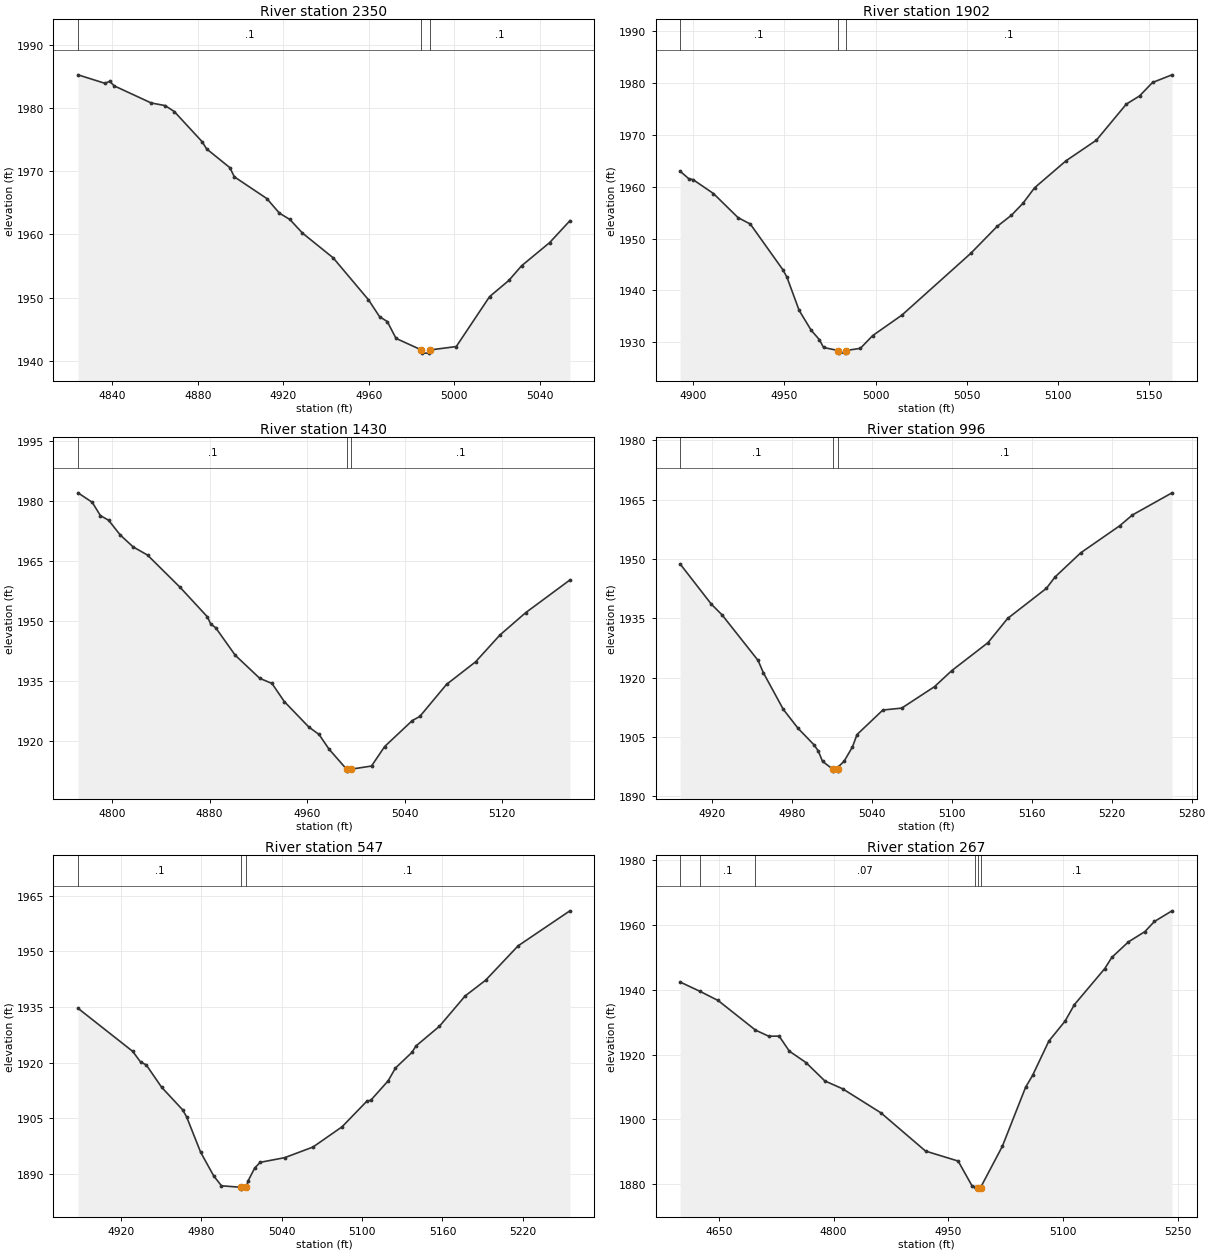
Type RM Length L Ch R = 1,2350,448,448,448
BEGIN DESCRIPTION:
Stream0519 5.0
END DESCRIPTION:
XS GIS Cut Line= 3
      1935925.01     13951325.00      1935775.00     13951225.00
      1935724.98     13951225.00
#Sta/Elev= 30
  4823.9 1985.21  4836.5 1983.87  4838.7 1984.18  4840.9 1983.46  4858.2 1980.76
  4864.7 1980.35  4869.0 1979.40  4882.0 1974.65  4884.1 1973.51  4895.0 1970.54
  4897.1 1969.09  4912.3 1965.66  4918.2 1963.35  4923.1 1962.35  4929.0 1960.20
  4943.4 1956.28  4959.9 1949.66  4965.1 1946.99  4968.7 1946.22  4972.8 1943.56
  4984.7 1941.73  4984.9 1941.23  4988.4 1941.23  4988.7 1941.73  5001.0 1942.27
  5016.6 1950.16  5025.6 1952.71  5031.6 1955.04  5044.7 1958.69  5054.2 1962.15
#Mann=3,-1,0
  4823.9     0.1       0  4984.7    0.05       0  4988.7     0.1       0
Bank Sta=4984.7,4988.7
Exp/Cntr=0.3,0.1

Type RM Length L Ch R = 1,1902,472,472,472
BEGIN DESCRIPTION:
Stream0519 4.0
END DESCRIPTION:
XS GIS Cut Line= 3
      1936024.97     13950874.99      1935925.00     13950825.00
      1935774.98     13950774.99
#Sta/Elev= 30
  4892.8 1962.99  4897.6 1961.53  4899.9 1961.37  4911.1 1958.68  4924.6 1954.03
  4931.3 1952.80  4949.1 1944.02  4951.4 1942.55  4958.1 1936.14  4964.7 1932.31
  4969.2 1930.49  4971.5 1928.98  4979.6 1928.39  4979.8 1927.89  4983.3 1927.89
  4983.6 1928.39  4991.7 1928.81  4998.4 1931.26  5014.5 1935.23  5052.3 1947.15
  5066.7 1952.33  5074.6 1954.50  5080.9 1956.80  5087.3 1959.80  5104.6 1965.02
  5121.2 1968.98  5137.6 1975.93  5144.9 1977.52  5152.0 1980.11  5162.7 1981.59
#Mann=3,-1,0
  4892.8     0.1       0  4979.6    0.05       0  4983.6     0.1       0
Bank Sta=4979.6,4983.6
Exp/Cntr=0.3,0.1

Type RM Length L Ch R = 1,1430,434,434,434
BEGIN DESCRIPTION:
Stream0519 3.0
END DESCRIPTION:
XS GIS Cut Line= 3
      1936325.03     13950525.01      1936125.00     13950425.00
      1935975.01     13950325.01
#Sta/Elev= 30
  4771.9 1982.08  4783.6 1979.70  4790.3 1976.37  4797.0 1975.22  4806.6 1971.51
  4817.2 1968.53  4829.0 1966.48  4855.8 1958.38  4878.2 1950.99  4880.9 1949.19
  4884.9 1948.30  4901.0 1941.39  4921.1 1935.61  4931.2 1934.31  4941.3 1929.78
  4961.4 1923.41  4969.8 1921.54  4978.1 1917.83  4992.4 1912.85  4992.7 1912.35
  4996.4 1912.85  5012.9 1913.63  5023.7 1918.51  5046.4 1925.02  5052.6 1926.06
  5074.5 1934.08  5098.3 1939.72  5118.3 1946.44  5139.4 1952.03  5175.8 1960.24
#Mann=3,-1,0
  4771.9     0.1       0  4992.4    0.05       0  4996.4     0.1       0
Bank Sta=4992.4,4996.4
Exp/Cntr=0.3,0.1

Type RM Length L Ch R = 1,996,449,449,449
BEGIN DESCRIPTION:
Stream0519 2.0
END DESCRIPTION:
XS GIS Cut Line= 3
      1936325.00     13950025.00      1936225.00     13950025.00
      1935974.96     13950125.01
#Sta/Elev= 30
  4895.9 1948.73  4919.4 1938.53  4927.4 1935.84  4954.4 1924.33  4958.4 1921.20
  4973.4 1911.92  4984.4 1907.16  4996.4 1902.97  4999.6 1901.43  5002.8 1898.79
  5010.5 1896.81  5010.8 1896.31  5014.3 1896.31  5014.5 1896.81  5014.8 1897.45
  5019.0 1898.81  5025.3 1902.45  5028.7 1905.56  5048.1 1911.77  5062.3 1912.26
  5086.9 1917.69  5099.8 1921.73  5127.0 1928.81  5141.8 1934.95  5170.9 1942.56
  5177.3 1945.41  5196.7 1951.56  5225.8 1958.36  5235.5 1961.13  5265.2 1966.73
#Mann=3,-1,0
  4895.9     0.1       0  5010.5    0.05       0  5014.5     0.1       0
Bank Sta=5010.5,5014.5
Exp/Cntr=0.3,0.1

Type RM Length L Ch R = 1,547,280,280,280
BEGIN DESCRIPTION:
Stream0519 1.0
END DESCRIPTION:
XS GIS Cut Line= 3
      1936375.04     13949675.02      1936275.00     13949625.00
      1936024.99     13949575.00
#Sta/Elev= 30
  4888.2 1934.62  4929.0 1923.01  4934.8 1920.17  4939.1 1919.36  4950.5 1913.37
  4966.2 1907.26  4969.2 1905.35  4979.6 1895.86  4989.4 1889.44  4995.2 1886.78
  5009.7 1886.38  5010.0 1885.88  5013.7 1886.38  5014.9 1888.02  5020.0 1891.58
  5024.0 1893.10  5042.3 1894.36  5063.4 1897.22  5085.1 1902.68  5103.5 1909.55
  5106.6 1909.87  5119.5 1915.08  5124.9 1918.51  5137.2 1922.73  5140.2 1924.45
  5157.7 1929.77  5176.9 1937.95  5192.2 1942.20  5216.4 1951.46  5255.0 1960.89
#Mann=3,-1,0
  4888.2     0.1       0  5009.7    0.05       0  5013.7     0.1       0
Bank Sta=5009.7,5013.7
Exp/Cntr=0.3,0.1

Type RM Length L Ch R = 1,267,108,108,108
BEGIN DESCRIPTION:
Stream0519 0.0
END DESCRIPTION:
XS GIS Cut Line= 4
      1936514.49     13949645.63      1936393.46     13949392.71
      1936130.97     13949349.82      1936037.20     13949372.77
#Sta/Elev= 30
  4599.5 1942.44  4625.6 1939.54  4649.1 1936.74  4698.0 1927.59  4715.2 1925.71
  4728.9 1925.73  4742.2 1921.10  4763.9 1917.58  4788.7 1911.88  4812.0 1909.45
  4861.9 1902.04  4920.3 1890.22  4962.9 1887.14  4981.1 1879.45  4984.6 1879.22
  4988.2 1878.97  4988.5 1878.47  4992.2 1878.97  5020.6 1891.68  5051.0 1909.92
  5060.2 1913.62  5081.4 1924.19  5102.7 1930.39  5114.8 1935.45  5154.5 1946.58
  5163.8 1950.07  5185.4 1954.83  5207.0 1958.02  5219.4 1961.14  5242.4 1964.43
#Mann=6,-1,0
  4599.5    0.07       0  4625.6     0.1       0  4698.0    0.07       0
  4984.6     0.1       0  4988.2    0.05       0  4992.2     0.1       0
Bank Sta=4988.2,4992.2
Exp/Cntr=0.3,0.1

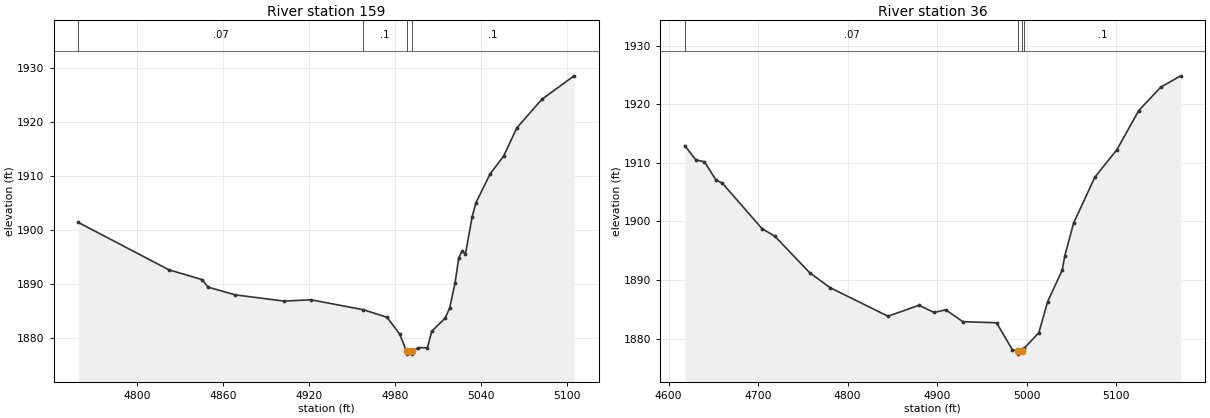
Type RM Length L Ch R = 1,159,123,123,123
BEGIN DESCRIPTION:
Stream0519 0.1
END DESCRIPTION:
XS GIS Cut Line= 3
      1936468.53     13949395.03      1936374.11     13949294.46
      1936174.15     13949236.28
#Sta/Elev= 30
  4758.7 1901.36  4821.9 1892.58  4845.1 1890.76  4849.3 1889.36  4868.4 1887.92
  4902.4 1886.77  4921.2 1887.01  4957.7 1885.17  4974.3 1883.76  4983.1 1880.63
  4987.9 1877.43  4988.2 1876.93  4991.7 1876.93  4991.9 1877.43  4996.2 1878.15
  5002.4 1878.09  5005.5 1881.18  5014.9 1883.63  5018.0 1885.50  5021.8 1890.21
  5024.3 1894.80  5026.6 1896.00  5029.0 1895.53  5033.7 1902.44  5036.3 1905.01
  5046.2 1910.35  5055.7 1913.70  5064.9 1918.91  5082.3 1924.20  5104.9 1928.56
#Mann=4,-1,0
  4758.7    0.07       0  4957.7     0.1       0  4987.9    0.05       0
  4991.9     0.1       0
Bank Sta=4987.9,4991.9
Exp/Cntr=0.3,0.1

Type RM Length L Ch R = 1,36,0,0,0
BEGIN DESCRIPTION:
Stream0519 0.2
END DESCRIPTION:
XS GIS Cut Line= 4
      1936541.18     13949444.12      1936346.73     13949194.13
      1936279.03     13949131.63      1936136.67     13949159.40
#Sta/Elev= 30
  4618.2 1912.94  4630.6 1910.50  4640.2 1910.19  4653.0 1907.07  4659.9 1906.58
  4704.6 1898.75  4718.6 1897.51  4757.7 1891.25  4780.6 1888.69  4845.2 1883.82
  4879.8 1885.69  4896.7 1884.47  4909.8 1884.91  4928.8 1882.89  4966.5 1882.70
  4984.0 1878.13  4990.5 1877.85  4990.8 1877.35  4994.5 1877.85  4997.5 1878.38
  5013.7 1881.00  5023.6 1886.33  5039.8 1891.68  5042.8 1894.18  5052.6 1899.75
  5076.4 1907.59  5100.9 1912.24  5125.3 1918.93  5149.8 1922.91  5172.1 1924.86
#Mann=4,-1,0
  4618.2    0.07       0  4990.5    0.05       0  4994.5    0.07       0
  4997.5     0.1       0
Bank Sta=4990.5,4994.5
Exp/Cntr=0.3,0.1

Chan Stop Cuts=-1