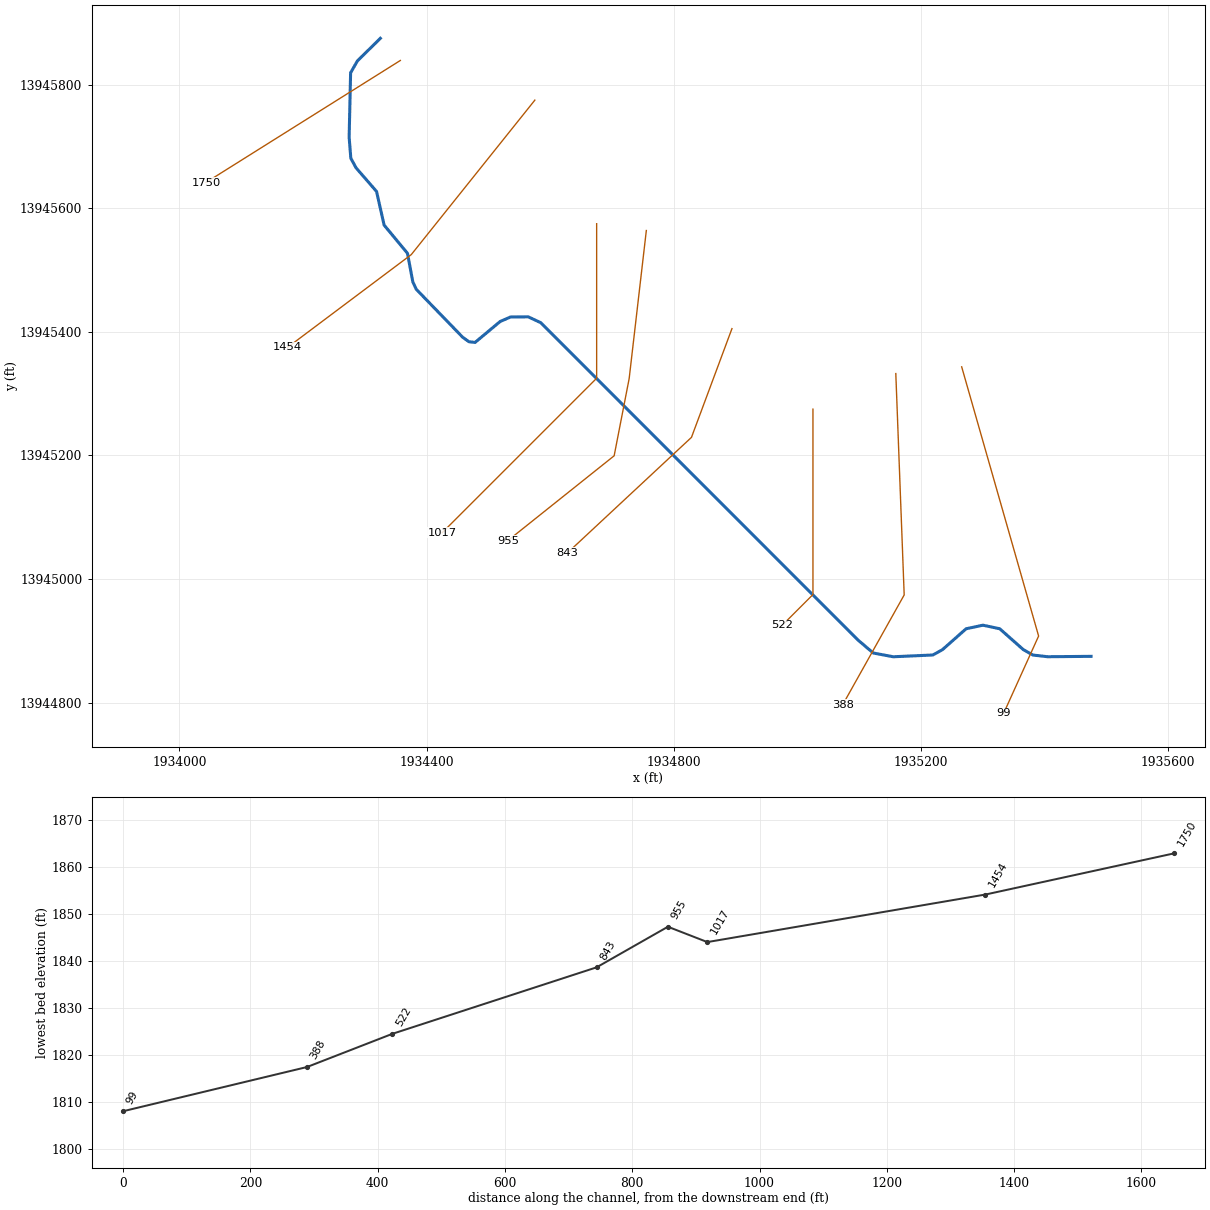
--- Stream0521.prj (project) ---

Proj Title=Stream0521 Base Level Engineering
Current Plan=p01
Default Exp/Contr=0.3,0.1
English Units
Geom File=g01
Flow File=f01
Plan File=p01
Y Axis Title=Elevation
X Axis Title(PF)=Main Channel Distance
X Axis Title(XS)=Station
BEGIN DESCRIPTION:
Stream0521
END DESCRIPTION:
DSS Export Rating Curves= 0
DSS Export Rating Curve Sorted= 0
DSS Export Volume Flow Curves= 0
DXF OffsetX= 0
DXF OffsetY= 0
DXF ScaleX= 1
DXF ScaleY= 10

--- Stream0521.p01 (plan) ---

Plan Title=Multiple Run
Short Identifier=Multiple
Geom File=g01
Flow File=f01
Subcritical Flow
K Sum by GR= 0
Std Step Tol= 0.01
Critical Tol= 0.01
Num of Std Step Trials= 20
Max Error Tol= 0.3
Flow Tol Ratio= 0.001
Split Flow NTrial= 30
Split Flow Tol= 0.02
Split Flow Ratio= 0.02
Log Output Level= 0
Friction Slope Method= 1
Unsteady Friction Slope Method= 2
Unsteady Bridges Friction Slope Method= 1
Parabolic Critical Depth
Global Vel Dist=  1 , 1 , 1
Global Log Level= 0
CheckData=True
Encroach Param= -1, 0, 0, 0
BEGIN DESCRIPTION:
Multiple Run
END DESCRIPTION:

--- Stream0521.f01 (steady flow) ---

Flow Title=Multiple
Number of Profiles=7
Profile Names=10-year,25-year,50-year,1pct_min,100-year,1pct_plu,500-year
River Rch & RM= Stream0521,Reach-1,1750
     413     661     885     576    1149    2292    1903
Boundary for River Rch & Prof#=Stream0521,Reach-1,1
Up Type=0
Dn Type=3
Dn Slope=0.005
Boundary for River Rch & Prof#=Stream0521,Reach-1,2
Up Type=0
Dn Type=3
Dn Slope=0.005
Boundary for River Rch & Prof#=Stream0521,Reach-1,3
Up Type=0
Dn Type=3
Dn Slope=0.005
Boundary for River Rch & Prof#=Stream0521,Reach-1,4
Up Type=0
Dn Type=3
Dn Slope=0.005
Boundary for River Rch & Prof#=Stream0521,Reach-1,5
Up Type=0
Dn Type=3
Dn Slope=0.005
Boundary for River Rch & Prof#=Stream0521,Reach-1,6
Up Type=0
Dn Type=3
Dn Slope=0.005
Boundary for River Rch & Prof#=Stream0521,Reach-1,7
Up Type=0
Dn Type=3
Dn Slope=0.005

--- Stream0521.g01 (geometry) ---

Geom Title=Existing Conditions
Program Version=4.10

River Reach=Stream0521      ,Reach-1
Reach XY= 30
        1934325.       13945875.      1934287.91      13945838.5
      1934276.88     13945819.21      1934274.49     13945714.83
      1934277.23     13945680.93      1934285.79     13945665.33
      1934318.88     13945627.18      1934331.08      13945572.8
       1934368.9     13945527.18       1934377.5     13945481.02
      1934383.14     13945468.91      1934458.26     13945391.29
      1934468.25     13945384.14      1934478.22     13945382.91
      1934518.95     13945416.88      1934535.64     13945424.11
      1934564.36     13945424.35      1934584.68      13945414.8
      1935098.13     13944901.15      1935122.57      13944880.4
      1935154.92     13944874.33      1935219.03     13944877.19
      1935234.65     13944885.87      1935272.82     13944919.62
        1935300.     13944925.41      1935327.19     13944919.67
      1935365.33     13944885.92      1935380.86     13944877.13
      1935404.73     13944874.38        1935475.       13944875.

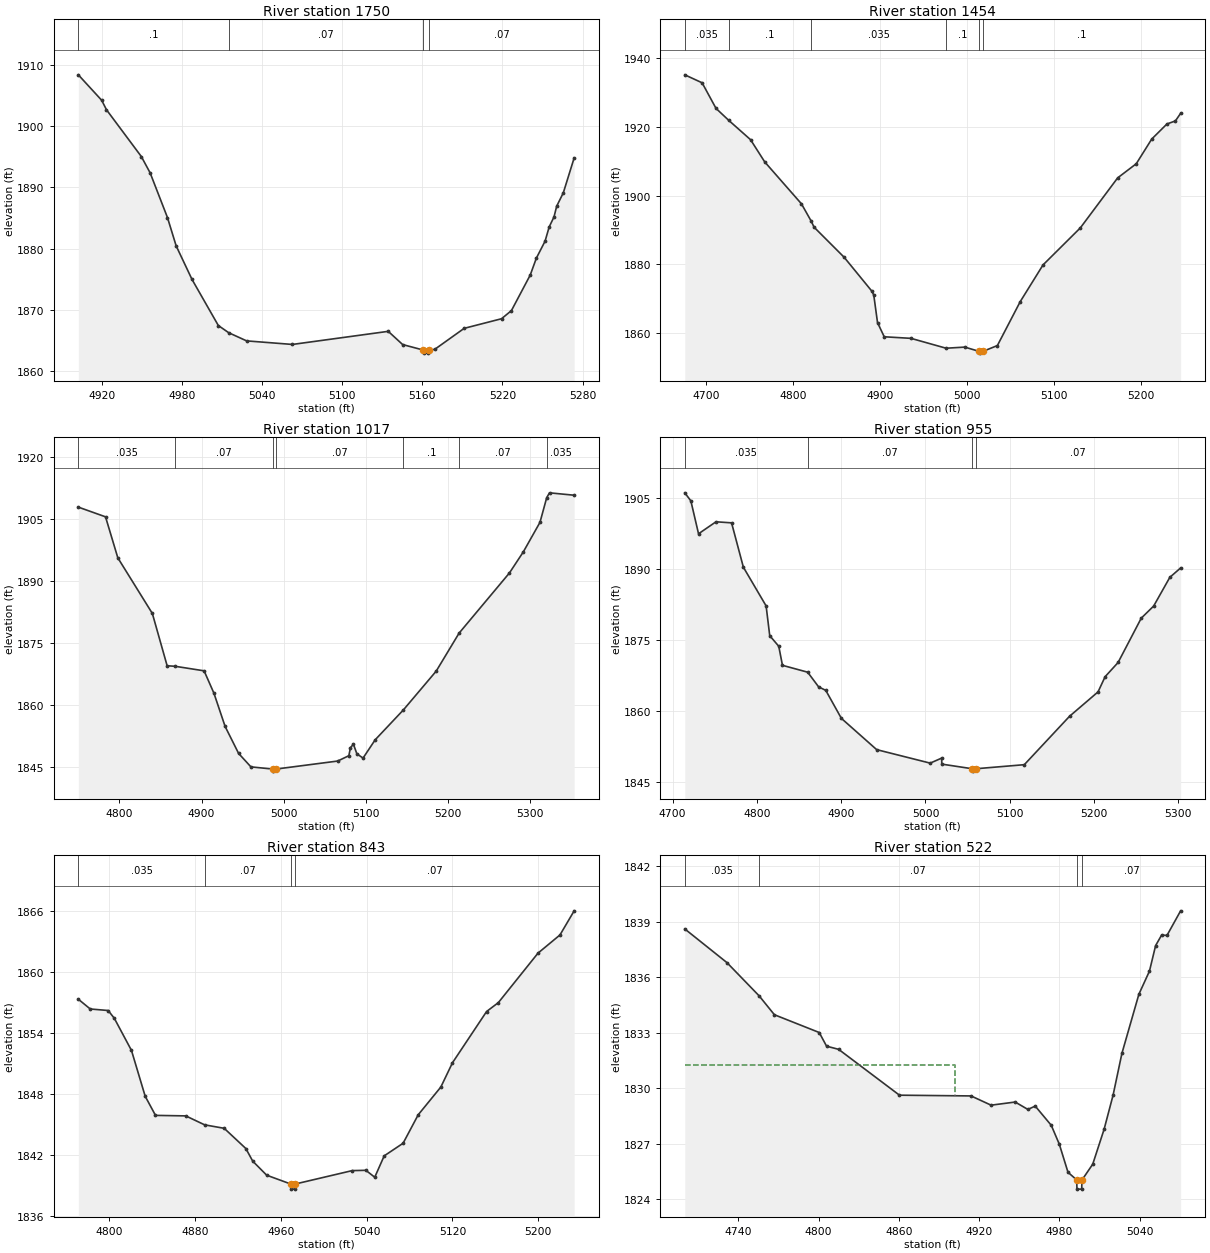
Type RM Length L Ch R = 1 ,1750    ,296,296,296
BEGIN DESCRIPTION:
Stream0521 4.0
END DESCRIPTION:
XS GIS Cut Line= 2
      1934357.38     13945839.21      1934042.72     13945641.72
#Sta/Elev= 30
  4902.2 1908.38  4919.7 1904.22  4923.3 1902.67  4949.4 1895.03    4956 1892.36
    4969 1885.05  4975.5 1880.43  4987.4 1874.94  5007.1 1867.42  5014.9 1866.24
  5028.3 1864.91  5062.6 1864.33  5134.4 1866.47  5145.2 1864.31  5160.7 1863.41
  5160.9 1862.91  5164.4 1862.91  5164.7 1863.41  5169.2 1863.52  5191.3 1866.96
  5219.3 1868.53  5226.7 1869.86  5240.8 1875.67  5245.4 1878.44  5251.9  1881.2
    5255 1883.54  5258.6 1885.16  5260.6 1886.91  5265.6 1889.12  5273.7 1894.81
#Mann= 4 ,-1 , 0
  4902.2      .1       0  5014.9     .07       0  5160.7     .05       0
  5164.7     .07       0
Bank Sta=5160.7,5164.7
XS Rating Curve= 0 ,0
Exp/Cntr=0.3,0.1

Type RM Length L Ch R = 1 ,1454    ,437,437,437
BEGIN DESCRIPTION:
Stream0521 3.0
END DESCRIPTION:
XS GIS Cut Line= 3
      1934574.99     13945774.98        1934375.       13945525.
      1934175.03     13945375.02
#Sta/Elev= 30
  4675.1 1935.18    4695 1932.86    4711 1925.41  4725.7 1921.91  4750.7  1916.3
    4767 1909.83  4809.2 1897.64  4820.4 1892.61  4823.7 1890.84  4858.3 1882.08
  4890.3 1872.17  4892.4 1871.04  4896.7 1863.04  4904.4 1858.93  4935.2 1858.47
  4975.5  1855.6    4997 1855.92  5013.8 1854.67    5014 1854.17  5017.8 1854.67
  5034.5 1856.37  5060.8 1869.17    5087 1879.85  5129.9 1890.63  5172.8 1905.18
  5194.2  1909.3    5212 1916.49  5229.5 1920.88  5239.2 1921.76  5245.2 1923.97
#Mann= 6 ,-1 , 0
  4675.1    .035       0  4725.7      .1       0  4820.4    .035       0
  4975.5      .1       0  5013.8     .05       0  5017.8      .1       0
Bank Sta=5013.8,5017.8
XS Rating Curve= 0 ,0
Exp/Cntr=0.3,0.1

Type RM Length L Ch R = 1 ,1017    ,62,62,62
BEGIN DESCRIPTION:
Stream0521 2.0
END DESCRIPTION:
XS GIS Cut Line= 3
        1934675.     13945575.04        1934675.       13945325.
        1934425.       13945075.
#Sta/Elev= 30
    4750 1907.97  4783.1 1905.62  4798.1 1895.68  4840.1 1882.23  4858.1 1869.57
  4868.2 1869.43  4903.1 1868.34  4915.1 1862.91  4928.7 1854.87  4945.1 1848.35
  4960.1 1845.09  4986.6 1844.56  4986.8 1844.06  4990.6 1844.56  5065.7  1846.5
  5079.3 1847.79  5081.3 1849.74  5084.9 1850.58  5089.1 1848.24  5096.6 1847.22
  5111.4 1851.65  5145.8  1858.9  5185.7 1868.28  5213.5 1877.46  5274.8 1892.03
  5291.7 1897.13    5312 1904.29  5320.2 1910.27  5323.6 1911.43  5353.6 1910.85
#Mann= 7 ,-1 , 0
    4750    .035       0  4868.2     .07       0  4986.6     .05       0
  4990.6     .07       0  5145.8      .1       0  5213.5     .07       0
  5320.2    .035       0
Bank Sta=4986.6,4990.6
XS Rating Curve= 0 ,0
Exp/Cntr=0.3,0.1

Type RM Length L Ch R = 1 ,955     ,112,112,112
BEGIN DESCRIPTION:
Stream0521 1.1
END DESCRIPTION:
XS GIS Cut Line= 4
      1934755.39     13945564.07      1934727.62     13945324.51
      1934703.31     13945199.51      1934531.44     13945062.36
#Sta/Elev= 30
  4714.4 1906.11  4721.6 1904.41  4730.7 1897.46  4751.4 1899.99  4769.9 1899.77
  4783.9  1890.4  4810.9 1882.22  4815.2 1875.93  4825.9  1873.7  4830.3 1869.67
  4860.2 1868.22  4873.2 1865.12  4881.7 1864.38  4900.2 1858.47  4942.1 1851.86
  5005.6 1849.01  5019.2 1850.07  5019.4  1848.8  5055.6 1847.82  5055.9 1847.32
  5059.6 1847.82  5117.3 1848.68    5171 1858.91  5204.8 1864.06  5213.2 1867.27
  5228.6 1870.27  5256.1 1879.64  5270.8 1882.19    5290 1888.26  5302.8 1890.24
#Mann= 4 ,-1 , 0
  4714.4    .035       0  4860.2     .07       0  5055.6     .05       0
  5059.6     .07       0
Bank Sta=5055.6,5059.6
XS Rating Curve= 0 ,0
Exp/Cntr=0.3,0.1

Type RM Length L Ch R = 1 ,843     ,321,321,321
BEGIN DESCRIPTION:
Mapping XS 726bd99c
END DESCRIPTION:
XS GIS Cut Line= 3
      1934893.93     13945405.28      1934828.44     13945229.37
      1934627.75     13945042.39
#Sta/Elev= 30
  4771.4 1857.36  4782.5  1856.4  4799.2 1856.25  4804.9 1855.49  4820.9 1852.33
  4833.7 1847.82  4843.3 1845.94  4871.5 1845.89  4889.1 1845.01  4907.3 1844.67
  4927.5 1842.68  4933.9 1841.44  4946.9 1840.06  4969.4 1839.19  4969.6 1838.69
  4973.1 1838.69  4973.4 1839.19  5026.6 1840.51  5039.3 1840.54  5047.6 1839.86
  5056.4 1841.96    5074  1843.2  5088.1    1846  5109.2 1848.73    5120 1851.11
  5151.8 1856.15  5162.8 1857.03  5199.7 1861.89  5220.2 1863.68  5233.4 1866.05
#Mann= 4 ,-1 , 0
  4771.4    .035       0  4889.1     .07       0  4969.4     .05       0
  4973.4     .07       0
Bank Sta=4969.4,4973.4
XS Rating Curve= 0 ,0
Exp/Cntr=0.3,0.1

Type RM Length L Ch R = 1 ,522     ,134,134,134
BEGIN DESCRIPTION:
Stream0521 1.0
END DESCRIPTION:
XS GIS Cut Line= 3
        1935025.     13945274.98        1935025.       13944975.
      1934974.99     13944924.99
#Sta/Elev= 30
    4700 1838.62  4731.5  1836.8  4755.6    1835    4767 1833.98  4800.5 1833.02
    4806 1832.28    4815 1832.11  4860.5 1829.63    4914 1829.59    4929 1829.09
    4947 1829.26  4956.5 1828.86    4962 1829.04    4974    1828    4980 1826.98
  4986.5 1825.46    4993 1825.05  4993.2 1824.55  4996.7 1824.55    4997 1825.05
    5005  1825.9  5013.5 1827.79  5020.2 1829.63  5026.8 1831.89  5039.5 1835.09
  5047.4 1836.34    5052 1837.72  5056.5 1838.29  5060.5 1838.27  5070.7  1839.6
#Mann= 4 ,-1 , 0
    4700    .035       0  4755.6     .07       0    4993     .05       0
    4997     .07       0
#XS Ineff= 2 , 0
         4901.79 1831.24
Permanent Ineff=
       F       F
Bank Sta=4993,4997
XS Rating Curve= 0 ,0
Exp/Cntr=0.3,0.1

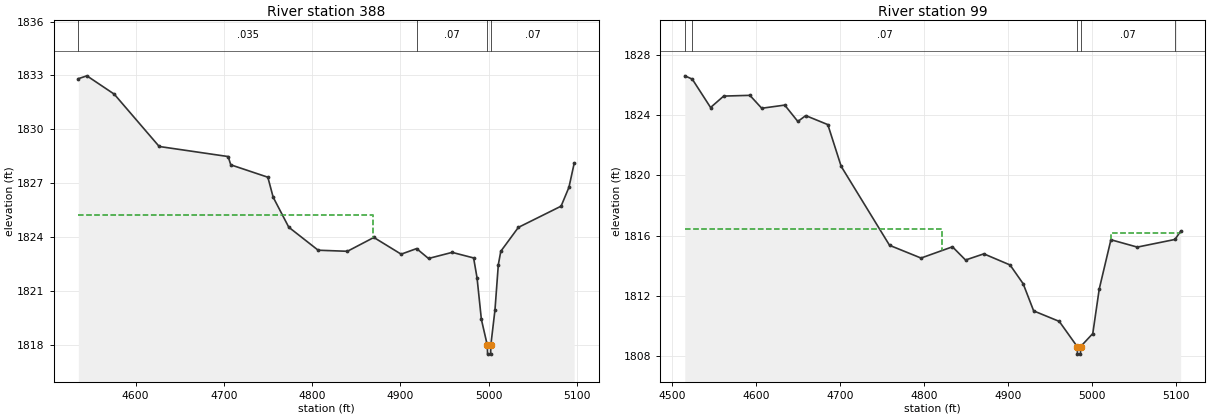
Type RM Length L Ch R = 1 ,388     ,289,289,289
BEGIN DESCRIPTION:
Stream0521 0.1
END DESCRIPTION:
XS GIS Cut Line= 3
      1935159.06     13945332.58      1935172.63     13944974.35
      1935073.34     13944797.04
#Sta/Elev= 30
  4535.2 1832.82  4544.9 1832.98  4575.9 1831.96  4626.8 1829.05  4704.9 1828.49
  4707.9 1828.03  4749.9 1827.34  4755.9 1826.23  4773.6 1824.56  4806.9 1823.28
    4840 1823.22    4870 1823.99  4900.9 1823.06  4918.4 1823.37  4931.9 1822.82
  4958.7 1823.16    4983 1822.85  4986.9 1821.74  4991.8 1819.43  4998.5    1818
  4998.8  1817.5  5002.3  1817.5  5002.5    1818  5007.2 1819.96    5011 1822.48
  5013.8 1823.22  5033.7 1824.55  5082.1 1825.73    5091 1826.78  5096.9 1828.11
#Mann= 4 ,-1 , 0
  4535.2    .035       0  4918.4     .07       0  4998.5     .05       0
  5002.5     .07       0
#XS Ineff= 2 , 0
         4869.28 1825.24
Permanent Ineff=
       F       F
Bank Sta=4998.5,5002.5
XS Rating Curve= 0 ,0
Exp/Cntr=0.3,0.1

Type RM Length L Ch R = 1 ,99      ,0,0,0
BEGIN DESCRIPTION:
Stream0521 0.0
END DESCRIPTION:
XS GIS Cut Line= 3
      1935265.65     13945343.47      1935390.14     13944907.86
      1935333.52     13944782.72
#Sta/Elev= 30
  4514.8 1826.64  4523.7 1826.42  4545.5 1824.53  4561.1 1825.29  4592.3 1825.34
  4606.4 1824.48  4633.8 1824.69  4649.4  1823.6  4658.8 1823.99  4685.1 1823.39
    4701 1820.61  4758.6 1815.35  4796.1  1814.5  4833.5 1815.25  4849.1 1814.37
  4870.9 1814.78  4902.1 1814.04  4917.7 1812.79  4930.2 1810.98  4960.7 1810.28
  4982.1  1808.6  4982.4  1808.1  4985.9  1808.1  4986.1  1808.6  5000.6 1809.47
  5008.3 1812.44  5022.2 1815.72  5053.6 1815.23  5098.5 1815.74  5105.2 1816.29
#Mann= 5 ,-1 , 0
  4514.8      .1       0  4523.7     .07       0  4982.1     .05       0
  4986.1     .07       0  5098.5      .1       0
#XS Ineff= 2 , 0
         4820.96 1816.45 5022.65         1816.18
Permanent Ineff=
       F       F
Bank Sta=4982.1,4986.1
XS Rating Curve= 0 ,0
Exp/Cntr=0.3,0.1

Chan Stop Cuts=-1
Use User Specified Reach Order=0
Composite Channel Slope=5