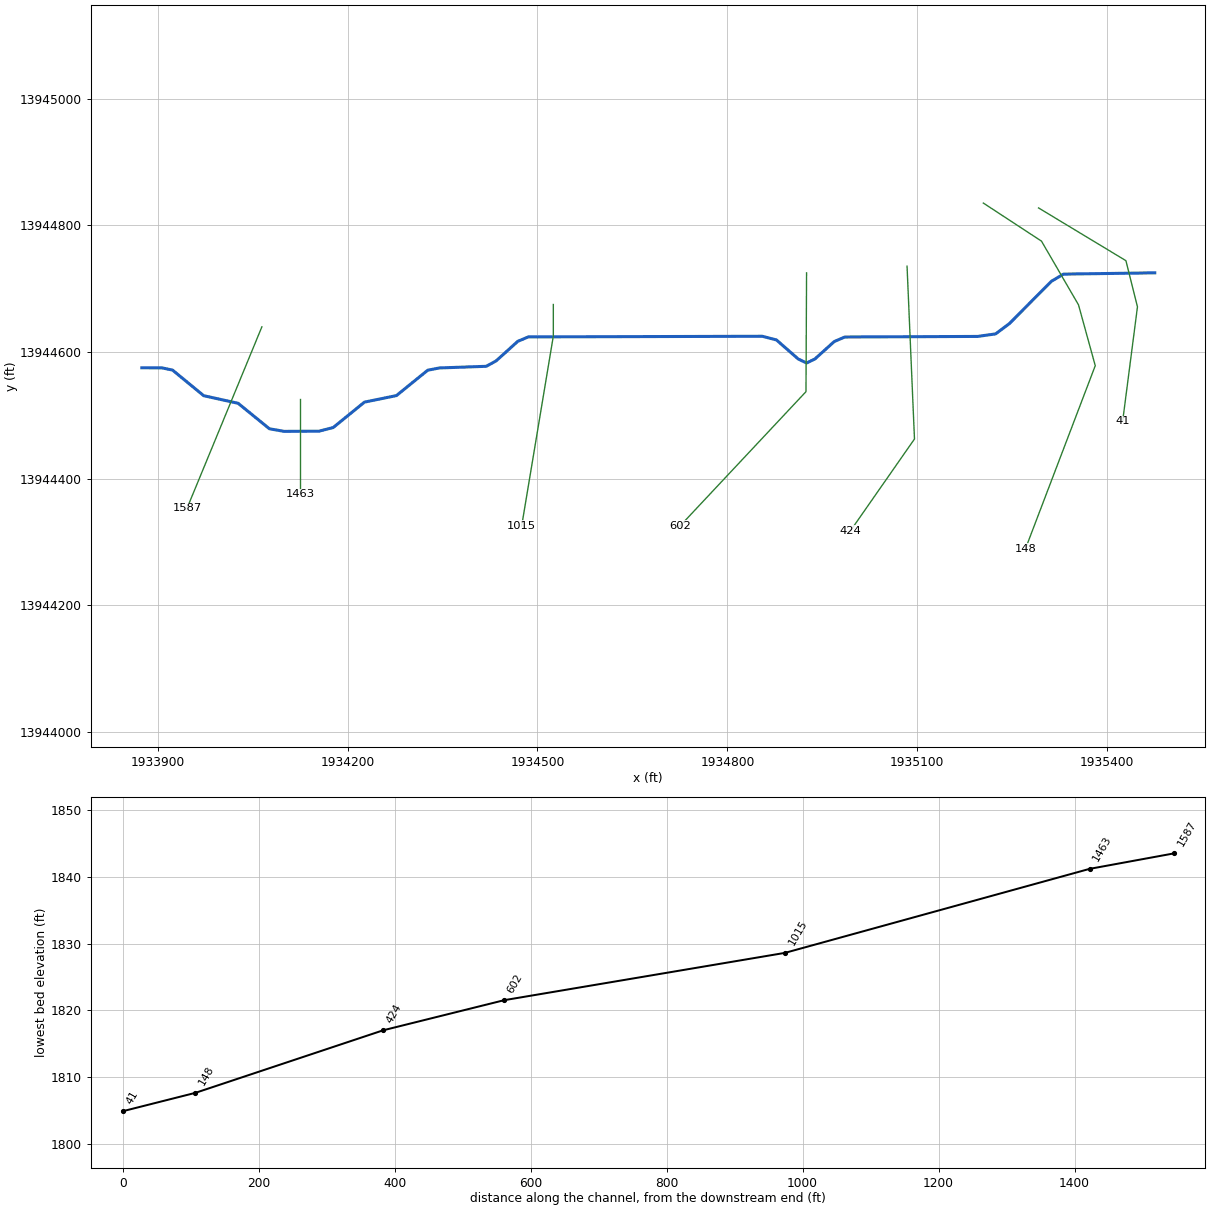
--- Stream0522.prj (project) ---

Proj Title=Stream0522 Base Level Engineering
Current Plan=p01
Default Exp/Contr=0.3,0.1
English Units
Geom File=g01
Flow File=f01
Plan File=p01
Y Axis Title=Elevation
X Axis Title(PF)=Main Channel Distance
X Axis Title(XS)=Station
BEGIN DESCRIPTION:
Stream0522
END DESCRIPTION:
DSS Export Rating Curves= 0
DSS Export Rating Curve Sorted= 0
DSS Export Volume Flow Curves= 0
DXF OffsetX= 0
DXF OffsetY= 0
DXF ScaleX= 1
DXF ScaleY= 10

--- Stream0522.p01 (plan) ---

Plan Title=Multiple Run
Short Identifier=Multiple
Geom File=g01
Flow File=f01
Subcritical Flow
K Sum by GR= 0
Std Step Tol= 0.01
Critical Tol= 0.01
Num of Std Step Trials= 20
Max Error Tol= 0.3
Flow Tol Ratio= 0.001
Split Flow NTrial= 30
Split Flow Tol= 0.02
Split Flow Ratio= 0.02
Log Output Level= 0
Friction Slope Method= 1
Unsteady Friction Slope Method= 2
Unsteady Bridges Friction Slope Method= 1
Parabolic Critical Depth
Global Vel Dist=  1 , 1 , 1
Global Log Level= 0
CheckData=True
Encroach Param= -1, 0, 0, 0
BEGIN DESCRIPTION:
Multiple Run
END DESCRIPTION:

--- Stream0522.f01 (steady flow) ---

Flow Title=Multiple
Program Version=4.10
Number of Profiles= 7
Profile Names=10-year,25-year,50-year,1pct_min,100-year,1pct_plu,500-year
River Rch & RM=Stream0522,Reach-1         ,1587
     378     602     801     519    1035    2066    1700
Boundary for River Rch & Prof#=Stream0522,Reach-1         , 1
Up Type= 0
Dn Type= 3
Dn Slope=0.008
Boundary for River Rch & Prof#=Stream0522,Reach-1         , 2
Up Type= 0
Dn Type= 3
Dn Slope=0.008
Boundary for River Rch & Prof#=Stream0522,Reach-1         , 3
Up Type= 0
Dn Type= 3
Dn Slope=0.008
Boundary for River Rch & Prof#=Stream0522,Reach-1         , 4
Up Type= 0
Dn Type= 3
Dn Slope=0.008
Boundary for River Rch & Prof#=Stream0522,Reach-1         , 5
Up Type= 0
Dn Type= 3
Dn Slope=0.008
Boundary for River Rch & Prof#=Stream0522,Reach-1         , 6
Up Type= 0
Dn Type= 3
Dn Slope=0.008
Boundary for River Rch & Prof#=Stream0522,Reach-1         , 7
Up Type= 0
Dn Type= 3
Dn Slope=0.008
DSS Import GetInterval= 0
DSS Import GetPeak= 0
DSS Import FillOption= 0

--- Stream0522.g01 (geometry) ---

Geom Title=Existing Conditions
Program Version=4.10

River Reach=Stream0522      ,Reach-1
Reach XY= 30
        1933875.       13944575.      1933906.81      13944574.9
      1933923.51      13944571.4      1933972.75     13944530.95
      1934027.19     13944518.89      1934076.58     13944478.67
        1934100.     13944474.59       1934154.9     13944474.89
      1934177.32     13944480.65      1934226.73     13944520.81
      1934277.18     13944531.11      1934326.58     13944571.17
      1934345.09     13944574.77      1934419.02     13944577.36
      1934434.63     13944585.89      1934468.94     13944616.86
       1934485.5     13944623.78      1934855.02     13944624.82
      1934877.45     13944618.98      1934911.79     13944588.95
        1934925.     13944582.56      1934938.21     13944588.95
      1934968.81     13944616.55      1934985.44     13944623.62
      1935195.18     13944624.57      1935223.53     13944628.55
      1935245.15     13944644.65      1935311.69     13944711.61
      1935330.84     13944722.98        1935475.       13944725.

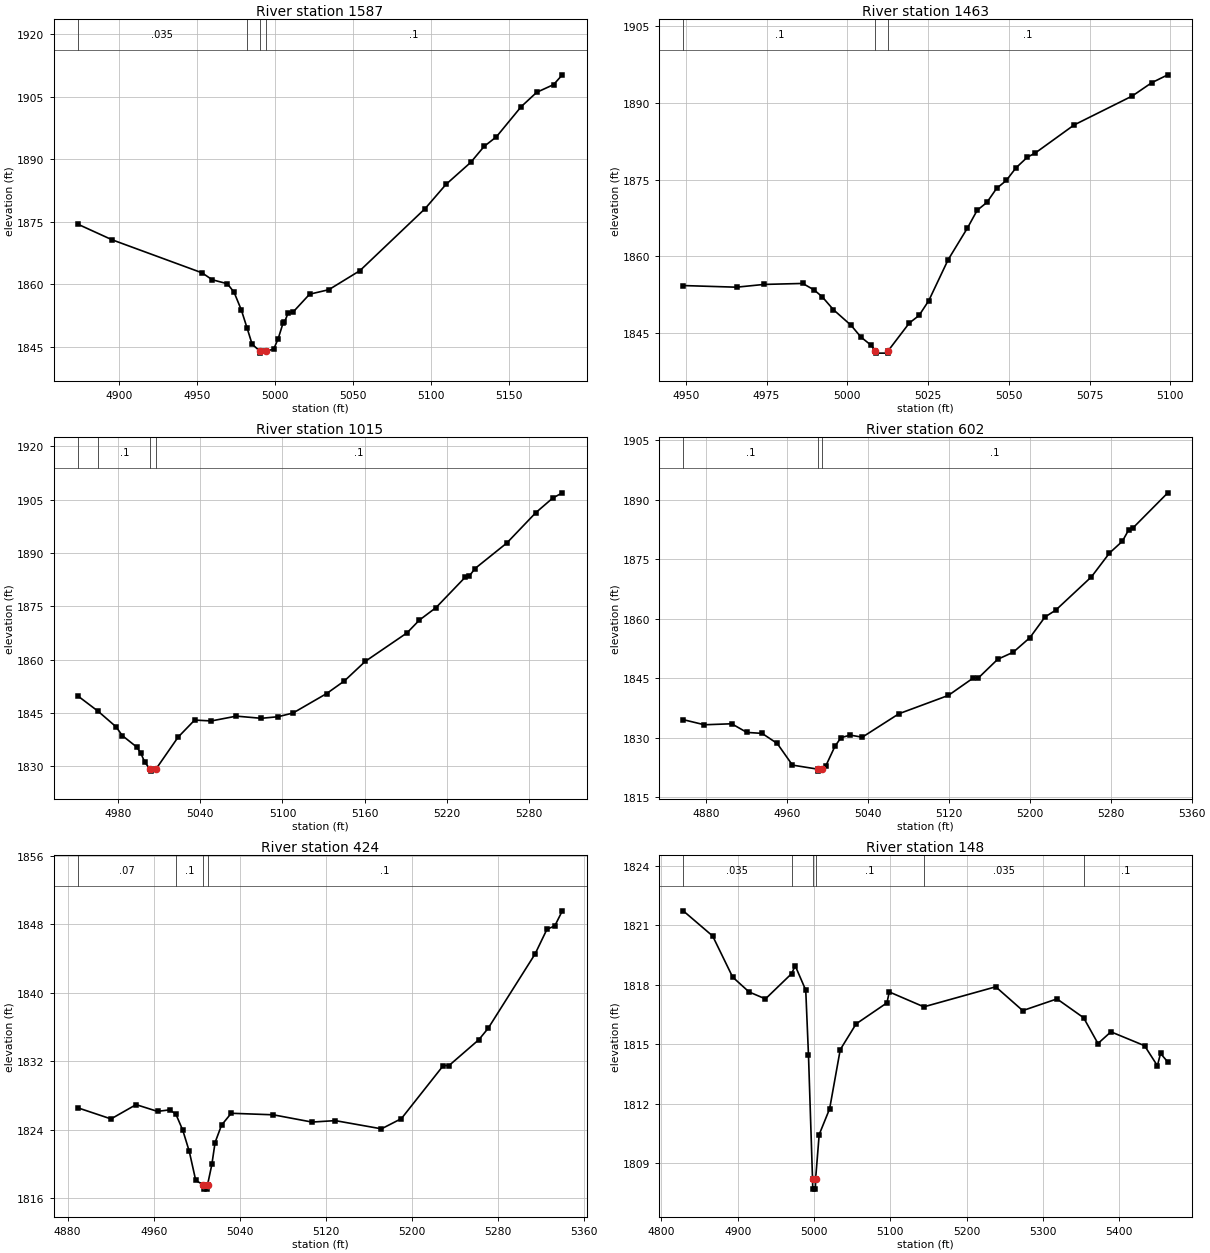
Type RM Length L Ch R = 1 ,1587    ,124,124,124
BEGIN DESCRIPTION:
Stream0522 4.0
END DESCRIPTION:
XS GIS Cut Line= 2
      1934064.62     13944639.62      1933946.33     13944352.86
#Sta/Elev= 30
  4873.7 1874.43  4895.7 1870.67  4953.2 1862.75  4959.8 1861.08  4969.5 1860.12
  4973.8 1858.04  4978.4 1853.83    4982 1849.59  4985.3 1845.62  4990.2 1843.96
  4990.4 1843.46  4994.2 1843.96  4999.1  1844.4    5002 1846.93  5005.2 1850.77
    5006 1850.87  5008.3 1853.05  5011.7 1853.39  5022.1 1857.61  5034.4 1858.69
  5054.3 1863.26  5096.1 1878.18  5109.4 1883.97  5125.3 1889.28  5133.8 1893.09
  5141.7 1895.41  5157.6 1902.66  5167.5 1906.09  5178.3 1907.94  5183.9 1910.29
#Mann= 4 ,-1 , 0
  4873.7    .035       0    4982      .1       0  4990.2     .05       0
  4994.2      .1       0
Bank Sta=4990.2,4994.2
XS Rating Curve= 0 ,0
Exp/Cntr=0.3,0.1

Type RM Length L Ch R = 1 ,1463    ,448,448,448
BEGIN DESCRIPTION:
Stream0522 3.0
END DESCRIPTION:
XS GIS Cut Line= 3
        1934125.     13944525.01        1934125.       13944475.
        1934125.     13944375.01
#Sta/Elev= 30
  4949.2 1854.33  4965.7 1854.01  4974.2 1854.55  4986.2 1854.74  4989.7 1853.48
  4992.2 1852.16  4995.7 1849.62  5001.2 1846.55  5004.2 1844.29  5007.2 1842.77
  5008.7 1841.65    5009 1841.15  5012.5 1841.15  5012.7 1841.65  5019.2 1847.03
  5022.2 1848.49  5025.2 1851.37  5031.2 1859.36  5037.2 1865.57  5040.2 1869.01
  5043.2 1870.54  5046.2 1873.27  5049.2 1874.82  5052.2 1877.28  5055.7 1879.35
  5058.2 1880.19  5070.2 1885.65  5088.2  1891.3  5094.2 1893.88  5099.2 1895.43
#Mann= 3 ,-1 , 0
  4949.2      .1       0  5008.7     .05       0  5012.7      .1       0
Bank Sta=5008.7,5012.7
XS Rating Curve= 0 ,0
Exp/Cntr=0.3,0.1

Type RM Length L Ch R = 1 ,1015    ,413,413,413
BEGIN DESCRIPTION:
Stream0522 2.0
END DESCRIPTION:
XS GIS Cut Line= 3
        1934525.     13944674.99        1934525.       13944625.
        1934475.     13944325.03
#Sta/Elev= 30
  4950.4 1849.77  4965.4  1845.4  4978.4 1841.06  4982.9 1838.61  4993.4  1835.4
  4996.4 1833.72  4999.4 1831.06  5003.4  1829.1  5003.7  1828.6  5007.4  1829.1
  5023.7 1838.15  5035.8 1842.96    5048 1842.72  5066.3 1844.07  5084.5 1843.46
  5096.7  1843.9  5107.7 1844.95  5132.3 1850.43  5145.3 1853.99  5160.5 1859.48
    5191 1867.49  5200.1 1871.11  5212.2  1874.6  5233.5 1883.14  5236.6 1883.52
  5240.7 1885.59  5263.9 1892.76  5285.2 1901.34  5297.4 1905.39  5304.5 1906.89
#Mann= 4 ,-1 , 0
  4950.4    .035       0  4965.4      .1       0  5003.4     .05       0
  5007.4      .1       0
Bank Sta=5003.4,5007.4
XS Rating Curve= 0 ,0
Exp/Cntr=0.3,0.1

Type RM Length L Ch R = 1 ,602     ,178,178,178
BEGIN DESCRIPTION:
Stream0522 1.0
END DESCRIPTION:
XS GIS Cut Line= 3
        1934925.     13944724.97      1934924.08      13944537.3
      1934725.01     13944325.01
#Sta/Elev= 30
  4857.7 1834.51  4878.6 1833.22  4905.6 1833.47  4920.6 1831.29  4935.6 1831.05
  4950.6  1828.5  4965.6 1823.05  4990.6 1822.03  4990.9 1821.53  4994.6 1822.03
  4998.6 1822.86  5007.6  1827.8  5013.6 1829.97  5022.6 1830.61  5034.6 1830.09
  5070.8    1836  5119.6 1840.62  5144.3 1845.03  5149.3 1845.03  5168.4 1849.74
  5183.7 1851.51  5200.2 1855.19  5215.1  1860.4  5225.7 1862.12    5261 1870.53
  5278.8 1876.52  5291.5 1879.49    5298 1882.46  5302.1 1882.88  5336.4 1891.71
#Mann= 3 ,-1 , 0
  4857.7      .1       0  4990.6     .05       0  4994.6      .1       0
Bank Sta=4990.6,4994.6
XS Rating Curve= 0 ,0
Exp/Cntr=0.3,0.1

Type RM Length L Ch R = 1 ,424     ,276,276,276
BEGIN DESCRIPTION:
Stream0522 0.1
END DESCRIPTION:
XS GIS Cut Line= 3
      1935083.72     13944735.53      1935095.45     13944462.53
      1934994.19      13944317.3
#Sta/Elev= 30
  4889.4 1826.54  4920.3 1825.24  4943.6 1826.91  4963.5 1826.12  4974.9  1826.3
  4980.6 1825.79    4987 1823.91    4993 1821.45    4999 1818.06    5006 1817.53
  5006.3 1817.03  5009.8 1817.03    5010 1817.53    5014 1819.91    5017 1822.48
    5023 1824.51    5032  1825.9  5071.1 1825.72  5107.1 1824.87  5128.7 1825.04
  5171.6 1824.08  5190.1 1825.27  5229.1 1831.48  5234.4 1831.48  5262.1  1834.5
  5270.8 1835.84  5314.4 1844.53  5325.4 1847.41  5332.7 1847.81  5339.7 1849.57
#Mann= 4 ,-1 , 0
  4889.4     .07       0  4980.6      .1       0    5006     .05       0
    5010      .1       0
Bank Sta=5006,5010
XS Rating Curve= 0 ,0
Exp/Cntr=0.3,0.1

Type RM Length L Ch R = 1 ,148     ,107,107,107
BEGIN DESCRIPTION:
Stream0522 0.0
END DESCRIPTION:
XS GIS Cut Line= 5
      1935204.23     13944835.21      1935296.07     13944775.07
      1935354.52     13944674.47        1935381.     13944578.36
      1935270.86     13944289.35
#Sta/Elev= 30
  4828.5 1821.72  4867.1 1820.45  4893.3 1818.38  4914.8 1817.63  4936.3 1817.28
  4970.5 1818.55  4975.3 1818.95  4989.1 1817.72  4992.7 1814.43    4998 1808.19
  4998.3 1807.69  5001.8 1807.69    5002 1808.19  5006.7 1810.44  5020.4 1811.74
  5034.3 1814.72  5055.1 1816.02  5095.5 1817.08  5098.6 1817.63  5143.9 1816.88
  5238.1 1817.89  5273.5 1816.69  5318.4 1817.28  5353.3 1816.33  5372.1 1815.03
  5389.1 1815.62  5433.2 1814.92    5450 1813.91  5454.1 1814.53  5463.6  1814.1
#Mann= 6 ,-1 , 0
  4828.5    .035       0  4970.5      .1       0    4998     .05       0
    5002      .1       0  5143.9    .035       0  5353.3      .1       0
Bank Sta=4998,5002
XS Rating Curve= 0 ,0
Exp/Cntr=0.3,0.1

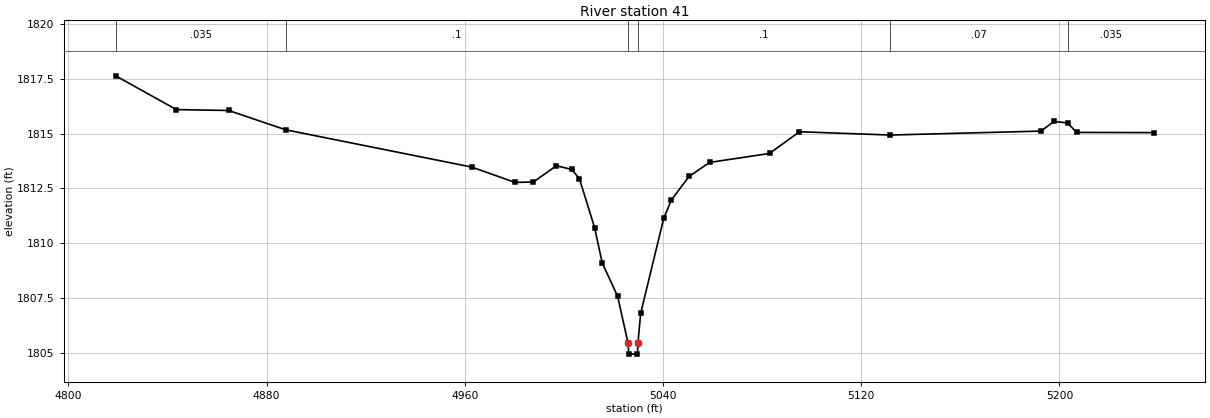
Type RM Length L Ch R = 1 ,41      ,0,0,0
BEGIN DESCRIPTION:
Stream0522 0.3
END DESCRIPTION:
XS GIS Cut Line= 4
      1935291.44     13944827.53      1935429.44     13944744.21
      1935447.67      13944671.3      1935424.23     13944490.27
#Sta/Elev= 30
  4819.1 1817.63  4843.6 1816.09  4864.7 1816.05  4887.7 1815.17  4962.8 1813.47
  4980.3 1812.77  4987.7 1812.79    4997 1813.53  5003.2 1813.36  5006.3 1812.93
  5012.4 1810.71  5015.5 1809.09  5021.7 1807.58  5025.9 1805.44  5026.2 1804.94
  5029.7 1804.94  5029.9 1805.44    5031  1806.8  5040.3 1811.13  5043.4 1811.97
  5050.5 1813.04  5058.8 1813.68    5083 1814.09  5095.1 1815.08  5131.7 1814.93
  5192.5 1815.11  5197.9 1815.55  5203.3 1815.48    5207 1815.05    5238 1815.04
#Mann= 6 ,-1 , 0
  4819.1    .035       0  4887.7      .1       0  5025.9     .05       0
  5029.9      .1       0  5131.7     .07       0  5203.3    .035       0
Bank Sta=5025.9,5029.9
XS Rating Curve= 0 ,0
Exp/Cntr=0.3,0.1

Chan Stop Cuts=-1
Use User Specified Reach Order=0
Composite Channel Slope=5