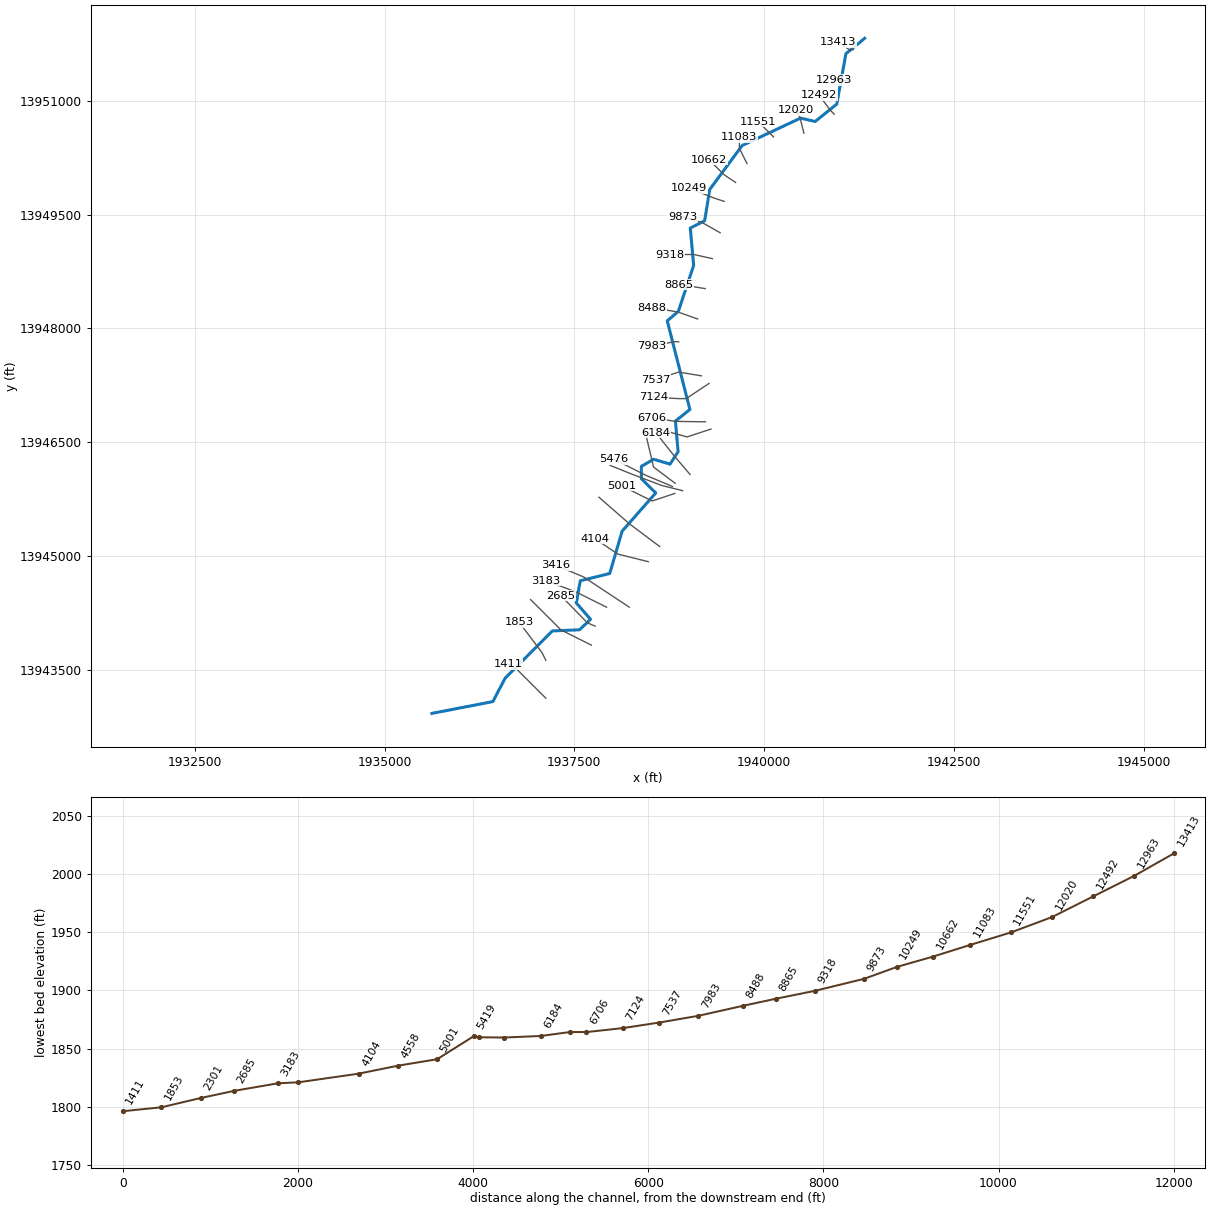
--- Stream0523.prj (project) ---

Proj Title=Stream0523 Base Level Engineering
Current Plan=p01
Default Exp/Contr=0.3,0.1
English Units
Geom File=g01
Flow File=f01
Plan File=p01
BEGIN DESCRIPTION:
Stream0523
END DESCRIPTION:

--- Stream0523.p01 (plan) ---

Plan Title=Multiple Run
Short Identifier=Multiple
Geom File=g01
Flow File=f01
Subcritical Flow
K Sum by GR= 0
Std Step Tol= 0.01
Critical Tol= 0.01
Num of Std Step Trials= 20
Max Error Tol= 0.3
Flow Tol Ratio= 0.001
Split Flow NTrial= 30
Split Flow Tol= 0.02
Split Flow Ratio= 0.02
Log Output Level= 0
Friction Slope Method= 1
Unsteady Friction Slope Method= 2
Unsteady Bridges Friction Slope Method= 1
Parabolic Critical Depth
Global Vel Dist=  1 , 1 , 1
Global Log Level= 0
CheckData=True
Encroach Param= -1, 0, 0, 0
BEGIN DESCRIPTION:
Multiple Run
END DESCRIPTION:

--- Stream0523.f01 (steady flow) ---

Flow Title=Multiple
Number of Profiles=7
Profile Names=10-year,25-year,50-year,1pct_min,100-year,1pct_plu,500-year
River Rch & RM= Stream0523,Reach-1,13413
     176     263     336     210     419     836     635
River Rch & RM= Stream0523,Reach-1,12492
     760    1270    1746    1164    2323    4636    4053
River Rch & RM= Stream0523,Reach-1,9318
     910    1535    2124    1423    2840    5667    5008
River Rch & RM= Stream0523,Reach-1,7124
    1641    2870    4068    2786    5560   11093   10255
River Rch & RM= Stream0523,Reach-1,5767
    1850    3243    4603    3153    6292   12554   11617
Boundary for River Rch & Prof#=Stream0523,Reach-1,1
Up Type=0
Dn Type=3
Dn Slope=0.005
Boundary for River Rch & Prof#=Stream0523,Reach-1,2
Up Type=0
Dn Type=3
Dn Slope=0.005
Boundary for River Rch & Prof#=Stream0523,Reach-1,3
Up Type=0
Dn Type=3
Dn Slope=0.005
Boundary for River Rch & Prof#=Stream0523,Reach-1,4
Up Type=0
Dn Type=3
Dn Slope=0.005
Boundary for River Rch & Prof#=Stream0523,Reach-1,5
Up Type=0
Dn Type=3
Dn Slope=0.005
Boundary for River Rch & Prof#=Stream0523,Reach-1,6
Up Type=0
Dn Type=3
Dn Slope=0.005
Boundary for River Rch & Prof#=Stream0523,Reach-1,7
Up Type=0
Dn Type=3
Dn Slope=0.005

--- Stream0523.g01 (geometry) ---

Geom Title=Existing Conditions

River Reach=Stream0523,Reach-1
Reach XY= 30
      1941325.00     13951825.00      1941078.82     13951623.42
      1940958.56     13950958.21      1940673.50     13950728.46
      1940481.04     13950773.37      1939711.43     13950411.53
      1939284.12     13949831.76      1939216.99     13949418.62
      1939028.43     13949323.77      1939072.74     13948830.94
      1938871.55     13948226.25      1938724.47     13948100.12
      1939023.39     13946931.03      1938832.69     13946778.67
      1938867.67     13946374.90      1938761.51     13946211.29
      1938545.20     13946275.37      1938384.03     13946182.02
      1938384.15     13946018.27      1938573.40     13945831.51
      1938130.47     13945327.45      1937967.00     13944768.61
      1937578.61     13944673.52      1937527.05     13944380.86
      1937714.05     13944165.00      1937569.15     13944027.06
      1937211.27     13944011.80      1936588.62     13943388.22
      1936427.70     13943080.36      1935625.00     13942925.00

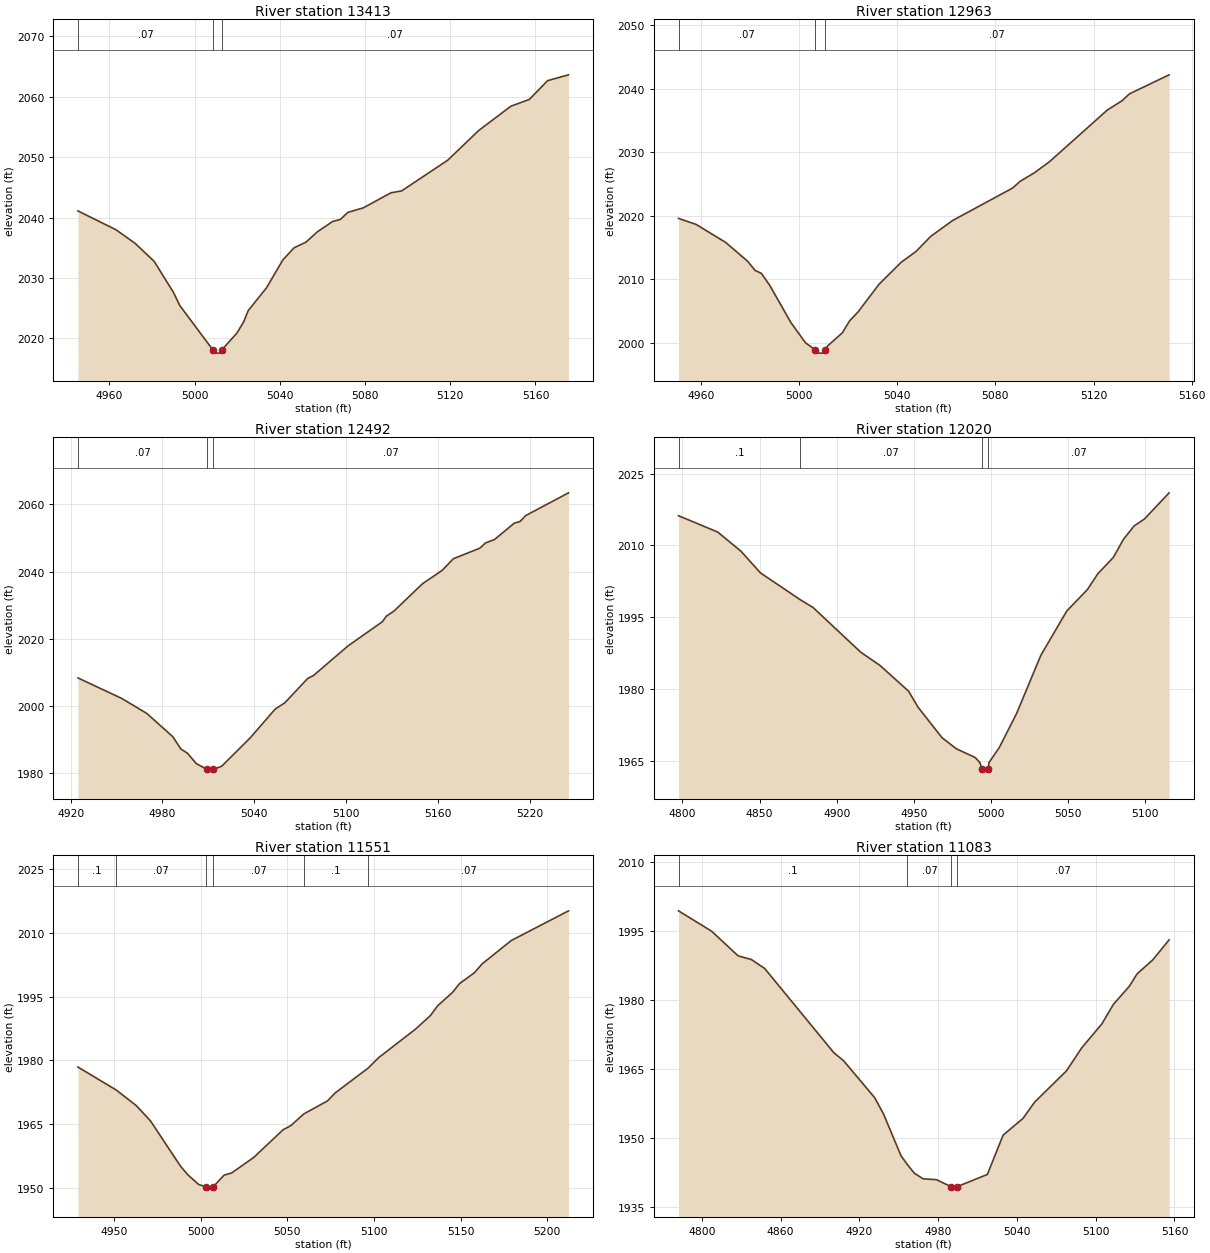
Type RM Length L Ch R = 1,13413,450,450,450
BEGIN DESCRIPTION:
Stream0523 30.0
END DESCRIPTION:
XS GIS Cut Line= 3
      1941174.96     13951675.00      1941125.00     13951675.00
      1940975.03     13951774.98
#Sta/Elev= 30
  4945.3 2041.09  4963.1 2037.98  4972.1 2035.73  4981.1 2032.72  4990.1 2027.60
  4993.1 2025.41  5008.7 2018.03  5008.9 2017.53  5012.4 2017.53  5012.7 2018.03
  5019.8 2020.81  5023.0 2022.66  5025.2 2024.58  5033.8 2028.36  5041.5 2033.00
  5046.7 2034.98  5052.3 2035.92  5057.7 2037.64  5064.8 2039.34  5068.4 2039.67
  5072.0 2040.86  5079.2 2041.60  5092.2 2044.10  5097.2 2044.41  5118.8 2049.49
  5133.4 2054.43  5148.5 2058.45  5157.1 2059.56  5165.7 2062.68  5175.5 2063.64
#Mann=3,-1,0
  4945.3    0.07       0  5008.7    0.05       0  5012.7    0.07       0
Bank Sta=5008.7,5012.7
Exp/Cntr=0.3,0.1

Type RM Length L Ch R = 1,12963,471,471,471
BEGIN DESCRIPTION:
Stream0523 29.0
END DESCRIPTION:
XS GIS Cut Line= 3
      1941125.00     13951275.00      1941075.00     13951275.00
      1940925.00     13951275.00
#Sta/Elev= 30
  4950.8 2019.58  4958.0 2018.63  4970.0 2015.81  4979.0 2012.84  4982.0 2011.41
  4984.6 2010.93  4988.0 2009.05  4996.6 2003.22  5002.6 2000.01  5006.6 1998.90
  5006.9 1998.40  5010.4 1998.40  5010.6 1998.90  5011.6 1999.53  5017.6 2001.60
  5020.6 2003.50  5024.0 2004.88  5032.6 2009.25  5041.6 2012.69  5047.6 2014.37
  5053.6 2016.75  5062.6 2019.26  5087.0 2024.35  5090.0 2025.39  5096.0 2026.78
  5102.0 2028.48  5125.6 2036.61  5131.6 2038.07  5134.6 2039.15  5150.8 2042.15
#Mann=3,-1,0
  4950.8    0.07       0  5006.6    0.05       0  5010.6    0.07       0
Bank Sta=5006.6,5010.6
Exp/Cntr=0.3,0.1

Type RM Length L Ch R = 1,12492,472,472,472
BEGIN DESCRIPTION:
Stream0523 28.0
END DESCRIPTION:
XS GIS Cut Line= 3
      1940924.98     13950825.02      1940875.00     13950875.00
      1940724.99     13951075.02
#Sta/Elev= 30
  4924.8 2008.36  4953.4 2002.26  4969.8 1997.80  4986.8 1990.88  4992.1 1987.21
  4996.3 1986.00  5002.2 1982.86  5009.3 1981.13  5009.5 1980.63  5013.3 1981.13
  5018.8 1982.10  5037.5 1990.57  5053.7 1999.08  5060.0 2000.95  5075.0 2008.20
  5078.8 2009.08  5101.3 2017.86  5123.8 2025.07  5126.5 2026.77  5131.3 2028.21
  5150.0 2036.36  5162.9 2040.36  5170.2 2043.81  5187.5 2046.95  5191.3 2048.53
  5197.2 2049.55  5210.0 2054.39  5213.8 2054.89  5217.5 2056.65  5245.5 2063.42
#Mann=3,-1,0
  4924.8    0.07       0  5009.3    0.05       0  5013.3    0.07       0
Bank Sta=5009.3,5013.3
Exp/Cntr=0.3,0.1

Type RM Length L Ch R = 1,12020,469,469,469
BEGIN DESCRIPTION:
Stream0523 27.0
END DESCRIPTION:
XS GIS Cut Line= 3
      1940524.99     13950575.03      1940475.00     13950775.00
      1940425.01     13950874.97
#Sta/Elev= 30
  4797.5 2016.20  4822.9 2012.79  4838.0 2008.78  4850.6 2004.26  4876.3 1998.68
  4884.7 1997.03  4915.6 1987.69  4928.0 1984.95  4946.6 1979.55  4952.7 1976.22
  4968.2 1969.86  4977.5 1967.53  4989.8 1965.69  4992.9 1964.59  4994.0 1963.36
  4994.3 1962.86  4997.8 1962.86  4998.0 1963.36  4998.8 1964.70  5005.4 1967.81
  5016.6 1974.91  5032.3 1987.05  5049.1 1996.30  5062.5 2000.79  5069.2 2004.08
  5079.2 2007.46  5085.9 2011.30  5092.7 2014.06  5099.4 2015.51  5115.4 2020.98
#Mann=4,-1,0
  4797.5     0.1       0  4876.3    0.07       0  4994.0    0.05       0
  4998.0    0.07       0
Bank Sta=4994,4998
Exp/Cntr=0.3,0.1

Type RM Length L Ch R = 1,11551,468,468,468
BEGIN DESCRIPTION:
Stream0523 26.0
END DESCRIPTION:
XS GIS Cut Line= 3
      1940125.01     13950524.99      1940075.00     13950575.00
      1939924.97     13950725.03
#Sta/Elev= 30
  4929.3 1978.43  4951.4 1973.02  4963.0 1969.34  4971.2 1965.73  4988.3 1955.19
  4992.7 1953.07  4998.9 1950.81  5003.2 1950.21  5003.4 1949.71  5006.9 1949.71
  5007.2 1950.21  5013.6 1953.01  5017.9 1953.51  5030.6 1957.14  5047.6 1963.68
  5052.1 1964.66  5059.6 1967.41  5073.2 1970.47  5077.6 1972.33  5096.7 1978.20
  5102.7 1980.64  5124.0 1987.36  5132.6 1990.56  5136.7 1992.83  5145.2 1995.95
  5149.4 1998.08  5157.9 2000.61  5162.4 2002.71  5179.1 2008.17  5212.2 2015.18
#Mann=6,-1,0
  4929.3     0.1       0  4951.4    0.07       0  5003.2    0.05       0
  5007.2    0.07       0  5059.6     0.1       0  5096.7    0.07       0
Bank Sta=5003.2,5007.2
Exp/Cntr=0.3,0.1

Type RM Length L Ch R = 1,11083,421,421,421
BEGIN DESCRIPTION:
Stream0523 25.0
END DESCRIPTION:
XS GIS Cut Line= 3
      1939775.00     13950174.99      1939675.00     13950375.00
      1939675.00     13950524.98
#Sta/Elev= 30
  4782.3 1999.46  4807.6 1995.01  4827.7 1989.66  4837.8 1988.87  4847.9 1986.93
  4900.4 1968.67  4908.2 1966.80  4931.7 1958.82  4938.4 1955.29  4951.8 1946.17
  4956.5 1944.31  4961.9 1942.40  4968.6 1941.18  4978.7 1941.00  4990.1 1939.44
  4990.3 1938.94  4993.8 1938.94  4994.1 1939.44  5017.5 1942.13  5029.5 1950.68
  5044.7 1954.34  5053.5 1957.86  5077.7 1964.65  5089.5 1969.71  5104.7 1974.87
  5113.5 1979.13  5125.7 1983.08  5131.5 1985.75  5143.4 1988.77  5155.9 1993.15
#Mann=4,-1,0
  4782.3     0.1       0  4956.5    0.07       0  4990.1    0.05       0
  4994.1    0.07       0
Bank Sta=4990.1,4994.1
Exp/Cntr=0.3,0.1

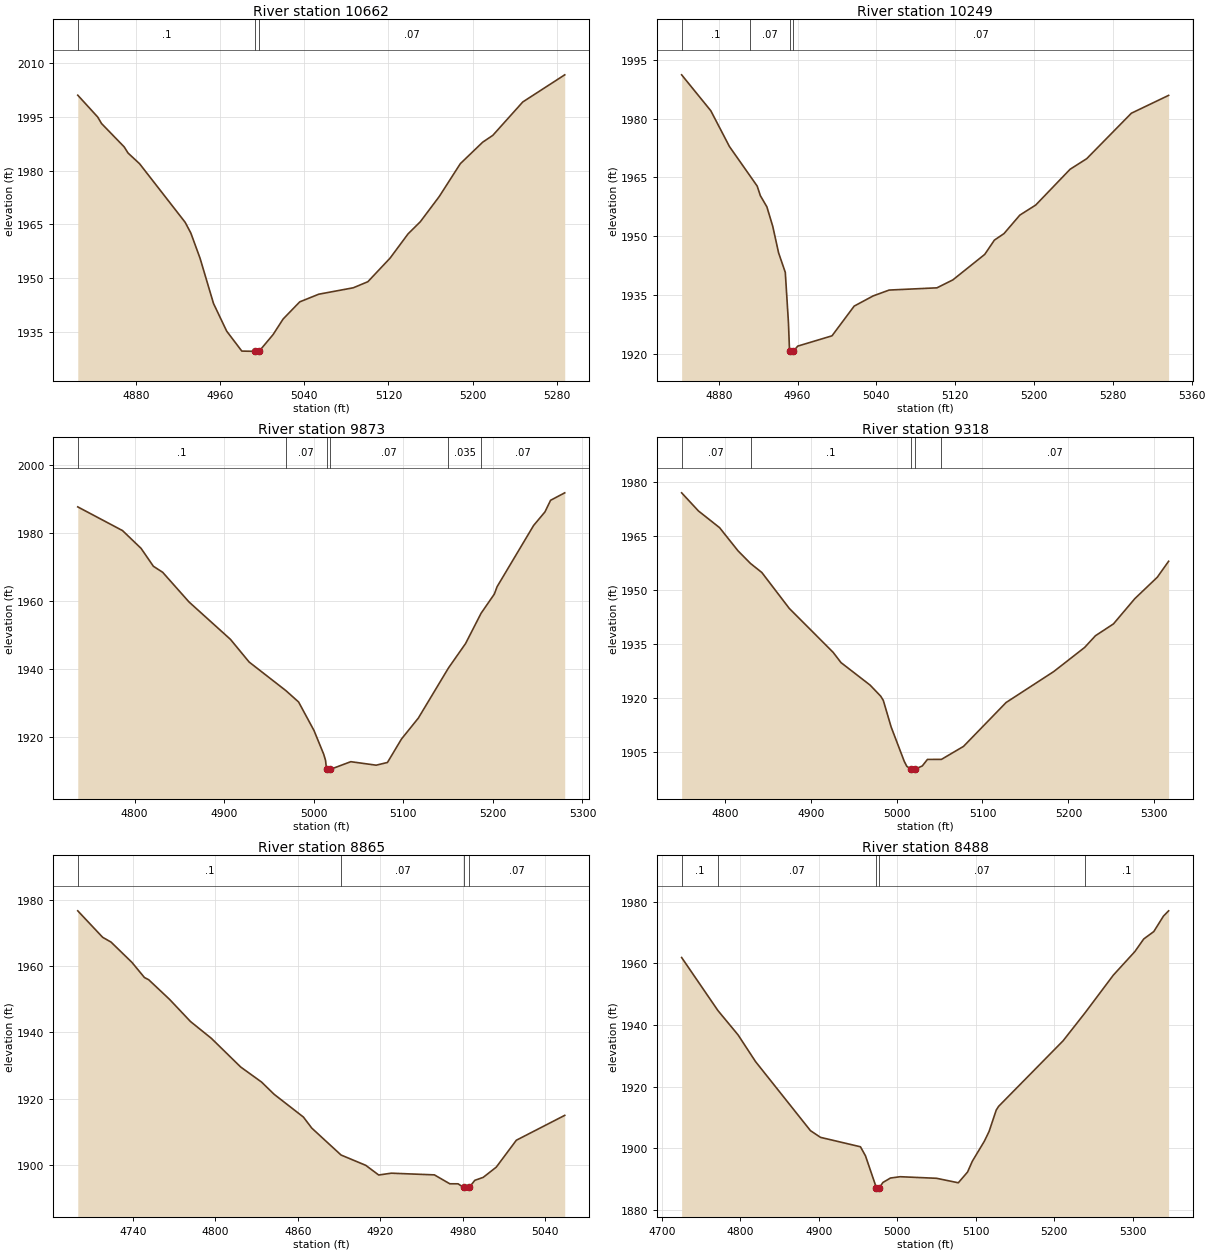
Type RM Length L Ch R = 1,10662,413,413,413
BEGIN DESCRIPTION:
Stream0523 24.0
END DESCRIPTION:
XS GIS Cut Line= 3
      1939624.97     13949925.02      1939475.00     13950025.00
      1939274.99     13950225.01
#Sta/Elev= 30
  4824.5 2001.06  4843.5 1994.95  4847.1 1993.15  4868.7 1986.60  4872.3 1984.91
  4883.3 1981.91  4926.6 1965.56  4932.0 1962.58  4940.8 1955.51  4953.6 1942.87
  4966.1 1935.16  4980.5 1929.58  4992.9 1929.51  4993.2 1929.01  4996.9 1929.51
  5010.2 1934.17  5019.8 1938.54  5035.6 1943.33  5053.7 1945.47  5086.5 1947.26
  5100.4 1948.96  5121.6 1955.58  5138.6 1962.32  5150.2 1965.69  5168.3 1972.77
  5188.3 1981.93  5209.6 1987.94  5219.2 1989.84  5247.7 1999.17  5287.6 2006.75
#Mann=3,-1,0
  4824.5     0.1       0  4992.9    0.05       0  4996.9    0.07       0
Bank Sta=4992.9,4996.9
Exp/Cntr=0.3,0.1

Type RM Length L Ch R = 1,10249,376,376,376
BEGIN DESCRIPTION:
Stream0523 23.0
END DESCRIPTION:
XS GIS Cut Line= 3
      1939474.96     13949675.01      1939325.00     13949725.00
      1939013.06     13949850.20
#Sta/Elev= 30
  4842.4 1991.22  4872.0 1982.05  4890.9 1972.91  4911.4 1965.56  4919.1 1962.79
  4922.3 1960.34  4928.9 1957.51  4934.9 1952.49  4940.8 1945.74  4947.6 1940.76
  4950.8 1927.92  4951.9 1920.63  4952.2 1920.13  4955.9 1920.63  4960.2 1921.92
  4995.0 1924.55  5017.5 1932.14  5036.8 1934.75  5053.0 1936.24  5101.5 1936.81
  5117.6 1938.83  5150.0 1945.35  5159.8 1949.00  5169.5 1950.65  5185.6 1955.38
  5201.8 1957.97  5236.6 1967.09  5253.5 1969.80  5298.8 1981.41  5336.6 1985.97
#Mann=4,-1,0
  4842.4     0.1       0  4911.4    0.07       0  4951.9    0.05       0
  4955.9    0.07       0
Bank Sta=4951.9,4955.9
Exp/Cntr=0.3,0.1

Type RM Length L Ch R = 1,9873,555,555,555
BEGIN DESCRIPTION:
Stream0523 22.0
END DESCRIPTION:
XS GIS Cut Line= 3
      1939421.64     13949261.77      1939189.55     13949393.27
      1938925.04     13949474.99
#Sta/Elev= 30
  4736.6 1987.73  4786.6 1980.74  4807.3 1975.50  4821.0 1970.24  4831.4 1968.46
  4860.8 1959.72  4907.1 1948.69  4927.9 1942.03  4968.9 1933.61  4983.1 1930.26
  5000.3 1921.86  5011.1 1914.90  5013.2 1913.06  5014.3 1910.39  5014.6 1909.89
  5018.3 1910.39  5041.4 1912.67  5069.7 1911.64  5082.3 1912.44  5098.0 1919.36
  5116.8 1925.52  5150.4 1940.27  5169.5 1947.47  5186.8 1956.38  5201.6 1962.04
  5204.7 1964.22  5245.5 1982.27  5258.1 1986.24  5264.4 1989.67  5280.2 1991.87
#Mann=6,-1,0
  4736.6     0.1       0  4968.9    0.07       0  5014.3    0.05       0
  5018.3    0.07       0  5150.4   0.035       0  5186.8    0.07       0
Bank Sta=5014.3,5018.3
Exp/Cntr=0.3,0.1

Type RM Length L Ch R = 1,9318,453,453,453
BEGIN DESCRIPTION:
Stream0523 21.0
END DESCRIPTION:
XS GIS Cut Line= 3
      1939319.32     13948920.51      1939075.00     13948975.00
      1938758.32     13948974.84
#Sta/Elev= 30
  4749.7 1977.00  4769.3 1971.96  4793.9 1967.32  4815.4 1960.88  4829.9 1957.38
  4843.1 1954.87  4875.0 1944.91  4926.1 1932.70  4935.3 1929.84  4969.1 1923.61
  4981.4 1920.55  4984.5 1919.36  4993.7 1911.93  5008.9 1902.43  5011.9 1901.03
  5017.2 1900.21  5017.5 1899.71  5021.2 1900.21  5029.9 1901.15  5035.9 1902.96
  5052.2 1902.97  5077.9 1906.58  5127.5 1918.77  5182.9 1927.35  5218.9 1934.05
  5231.5 1937.31  5252.5 1940.60  5277.4 1947.62  5303.5 1953.55  5316.7 1957.99
#Mann=5,-1,0
  4749.7    0.07       0  4829.9     0.1       0  5017.2    0.05       0
  5021.2     0.1       0  5052.2    0.07       0
Bank Sta=5017.2,5021.2
Exp/Cntr=0.3,0.1

Type RM Length L Ch R = 1,8865,377,377,377
BEGIN DESCRIPTION:
Stream0523 20.0
END DESCRIPTION:
XS GIS Cut Line= 3
      1939225.05     13948524.99      1938925.00     13948575.00
      1938874.98     13948575.00
#Sta/Elev= 30
  4699.9 1976.61  4718.0 1968.64  4724.1 1967.20  4739.3 1961.09  4748.4 1956.53
  4751.5 1955.86  4766.7 1949.94  4781.9 1943.28  4797.1 1938.21  4818.4 1929.59
  4833.6 1925.05  4842.7 1921.38  4864.0 1914.53  4870.1 1911.20  4891.4 1903.09
  4909.4 1899.98  4918.8 1897.07  4927.9 1897.62  4959.3 1897.11  4970.5 1894.43
  4976.5 1894.42  4980.6 1893.32  4980.9 1892.82  4984.4 1892.82  4984.6 1893.32
  4988.7 1895.47  4994.8 1896.36  5004.3 1899.44  5018.9 1907.54  5054.1 1915.03
#Mann=4,-1,0
  4699.9     0.1       0  4891.4    0.07       0  4980.6    0.05       0
  4984.6    0.07       0
Bank Sta=4980.6,4984.6
Exp/Cntr=0.3,0.1

Type RM Length L Ch R = 1,8488,505,505,505
BEGIN DESCRIPTION:
Stream0523 19.0
END DESCRIPTION:
XS GIS Cut Line= 3
      1939124.97     13948125.01      1938868.61     13948215.88
      1938525.05     13948274.99
#Sta/Elev= 30
  4725.1 1961.93  4771.4 1944.69  4797.0 1936.81  4819.3 1928.13  4889.3 1905.70
  4902.1 1903.53  4953.0 1900.47  4959.4 1897.53  4973.2 1887.22  4973.5 1886.72
  4977.2 1887.22  4981.6 1888.88  4991.2 1890.32  5003.6 1890.75  5049.9 1890.24
  5077.7 1888.78  5089.5 1892.28  5095.6 1895.80  5110.8 1902.24  5116.9 1905.44
  5126.0 1912.37  5129.1 1913.61  5211.2 1934.88  5239.2 1943.96  5275.3 1956.22
  5302.6 1963.83  5314.0 1967.95  5326.8 1970.35  5339.1 1975.36  5345.7 1977.09
#Mann=5,-1,0
  4725.1     0.1       0  4771.4    0.07       0  4973.2    0.05       0
  4977.2    0.07       0  5239.2     0.1       0
Bank Sta=4973.2,4977.2
Exp/Cntr=0.3,0.1

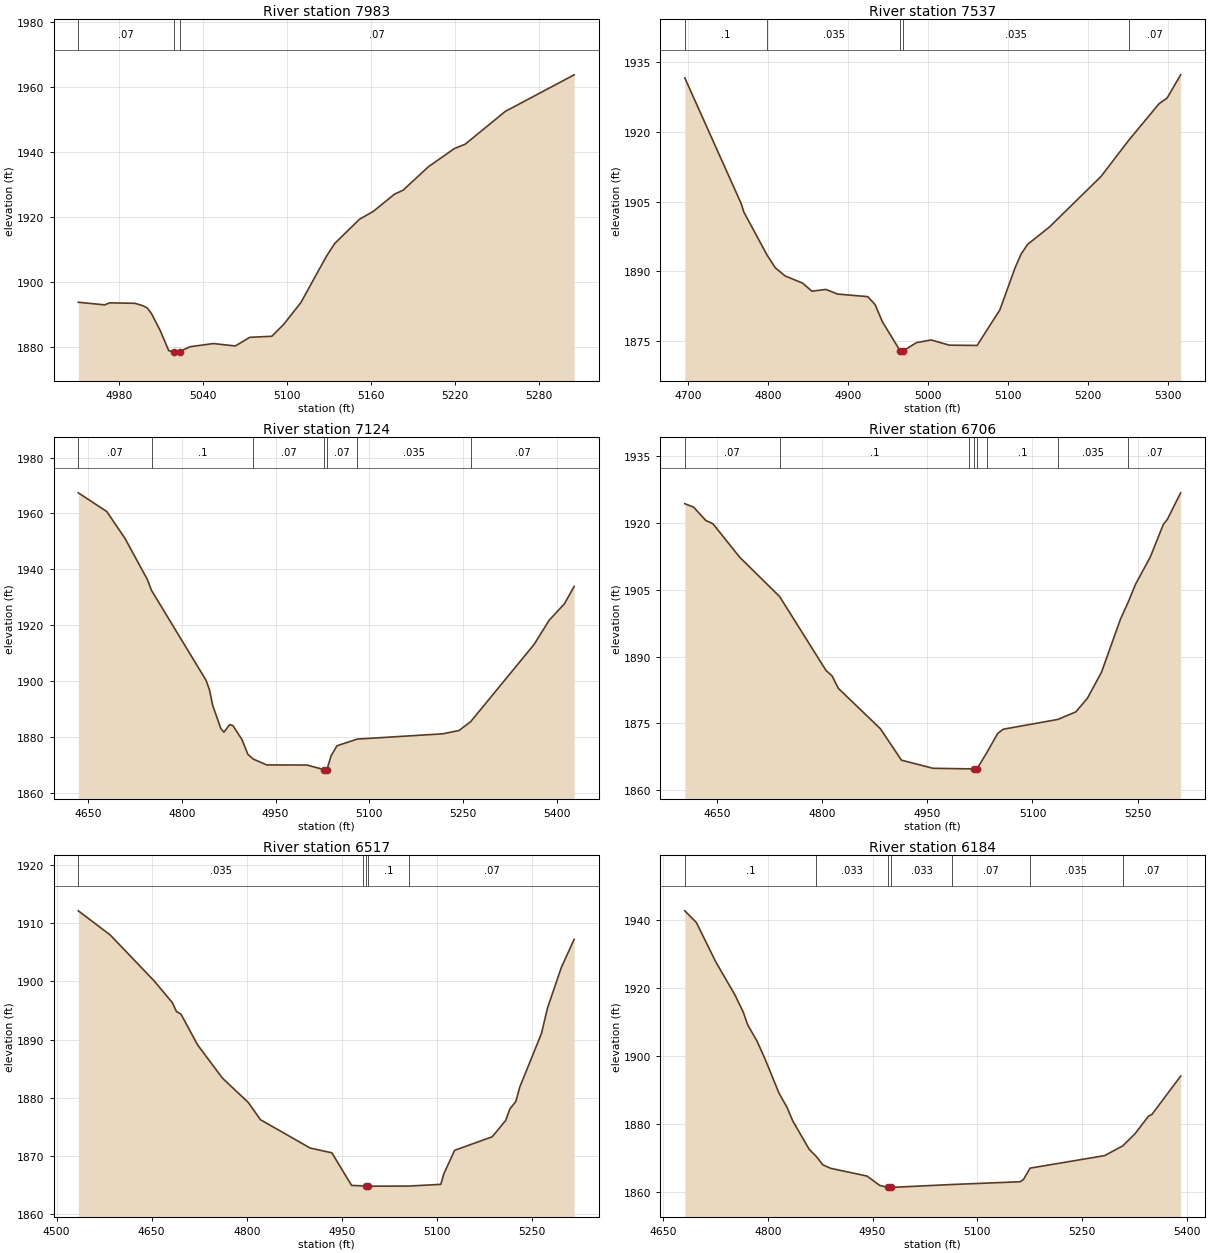
Type RM Length L Ch R = 1,7983,446,446,446
BEGIN DESCRIPTION:
Stream0523 18.0
END DESCRIPTION:
XS GIS Cut Line= 3
      1938874.96     13947825.00      1938825.00     13947825.00
      1938525.00     13947775.00
#Sta/Elev= 30
  4950.8 1893.87  4969.6 1893.07  4973.2 1893.68  4991.2 1893.55  4997.2 1892.76
  5000.2 1892.05  5003.2 1890.26  5009.3 1885.15  5015.4 1878.94  5019.2 1878.71
  5019.5 1878.21  5023.2 1878.71  5030.6 1880.18  5047.3 1881.16  5062.9 1880.41
  5073.2 1883.07  5089.0 1883.40  5097.5 1887.08  5109.7 1893.75  5127.9 1907.96
  5134.0 1912.01  5151.6 1919.41  5161.4 1921.82  5176.6 1927.14  5182.7 1928.35
  5200.9 1935.61  5219.2 1941.13  5227.2 1942.55  5255.7 1952.61  5304.9 1963.87
#Mann=3,-1,0
  4950.8    0.07       0  5019.2    0.05       0  5023.2    0.07       0
Bank Sta=5019.2,5023.2
Exp/Cntr=0.3,0.1

Type RM Length L Ch R = 1,7537,413,413,413
BEGIN DESCRIPTION:
Stream0523 17.0
END DESCRIPTION:
XS GIS Cut Line= 3
      1939174.96     13947375.01      1938875.00     13947425.00
      1938575.03     13947325.01
#Sta/Elev= 30
  4695.9 1931.55  4766.6 1904.50  4769.7 1902.76  4799.0 1893.46  4809.2 1890.76
  4821.4 1889.03  4843.3 1887.48  4854.9 1885.75  4872.5 1886.13  4887.1 1885.13
  4924.8 1884.58  4933.9 1882.89  4943.1 1879.18  4965.3 1872.95  4965.6 1872.45
  4969.3 1872.95  4985.6 1874.69  5004.0 1875.28  5026.8 1874.16  5061.6 1874.10
  5090.1 1881.75  5109.0 1890.73  5116.6 1893.72  5124.9 1895.82  5152.2 1899.55
  5216.6 1910.39  5251.3 1918.16  5289.3 1926.02  5299.3 1927.22  5316.2 1932.21
#Mann=5,-1,0
  4695.9     0.1       0  4799.0   0.035       0  4965.3   0.035       0
  4969.3   0.035       0  5251.3    0.07       0
Bank Sta=4965.3,4969.3
Exp/Cntr=0.3,0.1

Type RM Length L Ch R = 1,7124,418,418,418
BEGIN DESCRIPTION:
Stream0523 16.0
END DESCRIPTION:
XS GIS Cut Line= 4
      1939275.01     13947275.00      1938975.00     13947075.00
      1938875.00     13947075.00      1938542.67     13947093.44
#Sta/Elev= 30
  4634.4 1967.37  4679.9 1960.68  4709.0 1951.07  4744.8 1936.37  4751.5 1932.43
  4838.8 1900.23  4844.2 1896.87  4849.4 1891.26  4862.4 1882.96  4867.4 1881.66
  4876.6 1884.37  4881.8 1884.02  4896.2 1879.03  4905.7 1873.73  4914.3 1872.03
  4935.9 1869.93  5000.2 1869.89  5028.2 1868.21  5028.4 1867.71  5032.2 1868.21
  5038.8 1873.16  5048.2 1876.78  5080.8 1879.18  5217.5 1881.07  5243.6 1882.26
  5262.3 1885.45  5363.8 1913.11  5387.9 1921.78  5411.9 1927.54  5427.8 1933.84
#Mann=7,-1,0
  4634.4    0.07       0  4751.5     0.1       0  4914.3    0.07       0
  5028.2    0.05       0  5032.2    0.07       0  5080.8   0.035       0
  5262.3    0.07       0
Bank Sta=5028.2,5032.2
Exp/Cntr=0.3,0.1

Type RM Length L Ch R = 1,6706,189,189,189
BEGIN DESCRIPTION:
Stream0523 15.0
END DESCRIPTION:
XS GIS Cut Line= 3
      1939228.26     13946769.04      1938825.00     13946775.00
      1938525.04     13946824.99
#Sta/Elev= 30
  4604.0 1924.32  4616.7 1923.53  4634.1 1920.54  4644.1 1919.83  4682.1 1912.34
  4739.3 1903.47  4805.5 1886.87  4814.1 1885.66  4823.1 1882.85  4883.1 1873.78
  4913.1 1866.73  4958.1 1864.91  5009.8 1864.78  5016.9 1864.77  5017.2 1864.27
  5020.9 1864.77  5035.8 1868.68  5050.5 1872.76  5058.4 1873.68  5136.3 1875.88
  5161.9 1877.58  5178.3 1880.61  5198.4 1886.44  5225.7 1898.43  5236.7 1902.25
  5247.0 1906.21  5268.3 1912.41  5286.6 1919.63  5292.6 1920.84  5311.4 1926.76
#Mann=8,-1,0
  4604.0    0.07       0  4739.3     0.1       0  5009.8    0.07       0
  5016.9    0.05       0  5020.9    0.07       0  5035.8     0.1       0
  5136.3   0.035       0  5236.7    0.07       0
Bank Sta=5016.9,5020.9
Exp/Cntr=0.3,0.1

Type RM Length L Ch R = 1,6517,333,333,333
BEGIN DESCRIPTION:
Mapping XS 738dcf8e
END DESCRIPTION:
XS GIS Cut Line= 3
      1939300.06     13946672.98      1938985.83     13946570.01
      1938550.88     13946690.15
#Sta/Elev= 30
  4534.4 1912.13  4584.8 1907.97  4654.2 1900.06  4682.7 1896.35  4689.1 1894.84
  4696.3 1894.37  4722.4 1889.11  4761.6 1883.39  4802.6 1879.18  4821.6 1876.24
  4900.0 1871.37  4934.2 1870.55  4965.3 1864.95  4983.9 1864.87  4987.8 1864.81
  4988.1 1864.31  4991.8 1864.81  5055.8 1864.84  5106.0 1865.13  5110.7 1866.92
  5127.8 1870.98  5187.0 1873.30  5208.3 1876.10  5215.0 1878.11  5224.3 1879.36
  5230.5 1881.84  5264.8 1891.07  5274.1 1895.37  5295.9 1902.35  5316.3 1907.23
#Mann=5,-1,0
  4534.4   0.035       0  4983.9     0.1       0  4987.8    0.05       0
  4991.8     0.1       0  5055.8    0.07       0
Bank Sta=4987.8,4991.8
Exp/Cntr=0.3,0.1

Type RM Length L Ch R = 1,6184,417,417,417
BEGIN DESCRIPTION:
Stream0523 14.0
END DESCRIPTION:
XS GIS Cut Line= 3
      1939024.98     13946075.02      1938811.68     13946324.85
      1938575.03     13946624.97
#Sta/Elev= 30
  4680.8 1942.57  4697.4 1939.14  4725.0 1927.67  4752.6 1917.93  4764.4 1912.94
  4771.2 1909.02  4784.2 1904.40  4796.0 1899.03  4815.7 1889.14  4827.6 1884.79
  4835.4 1880.99  4859.1 1872.60  4869.3 1870.51  4878.8 1868.03  4890.0 1867.02
  4942.0 1864.75  4960.2 1862.01  4972.0 1861.42  4972.2 1860.92  4976.2 1861.42
  5064.2 1862.28  5161.8 1863.09  5166.2 1863.73  5175.7 1867.08  5282.5 1870.75
  5308.6 1873.62  5326.1 1877.15  5345.4 1882.33  5350.3 1882.82  5391.5 1894.06
#Mann=7,-1,0
  4680.8     0.1       0  4869.3   0.033       0  4972.0   0.033       0
  4976.2   0.033       0  5064.2    0.07       0  5175.7   0.035       0
  5308.6    0.07       0
Bank Sta=4972,4976.2
Exp/Cntr=0.3,0.1

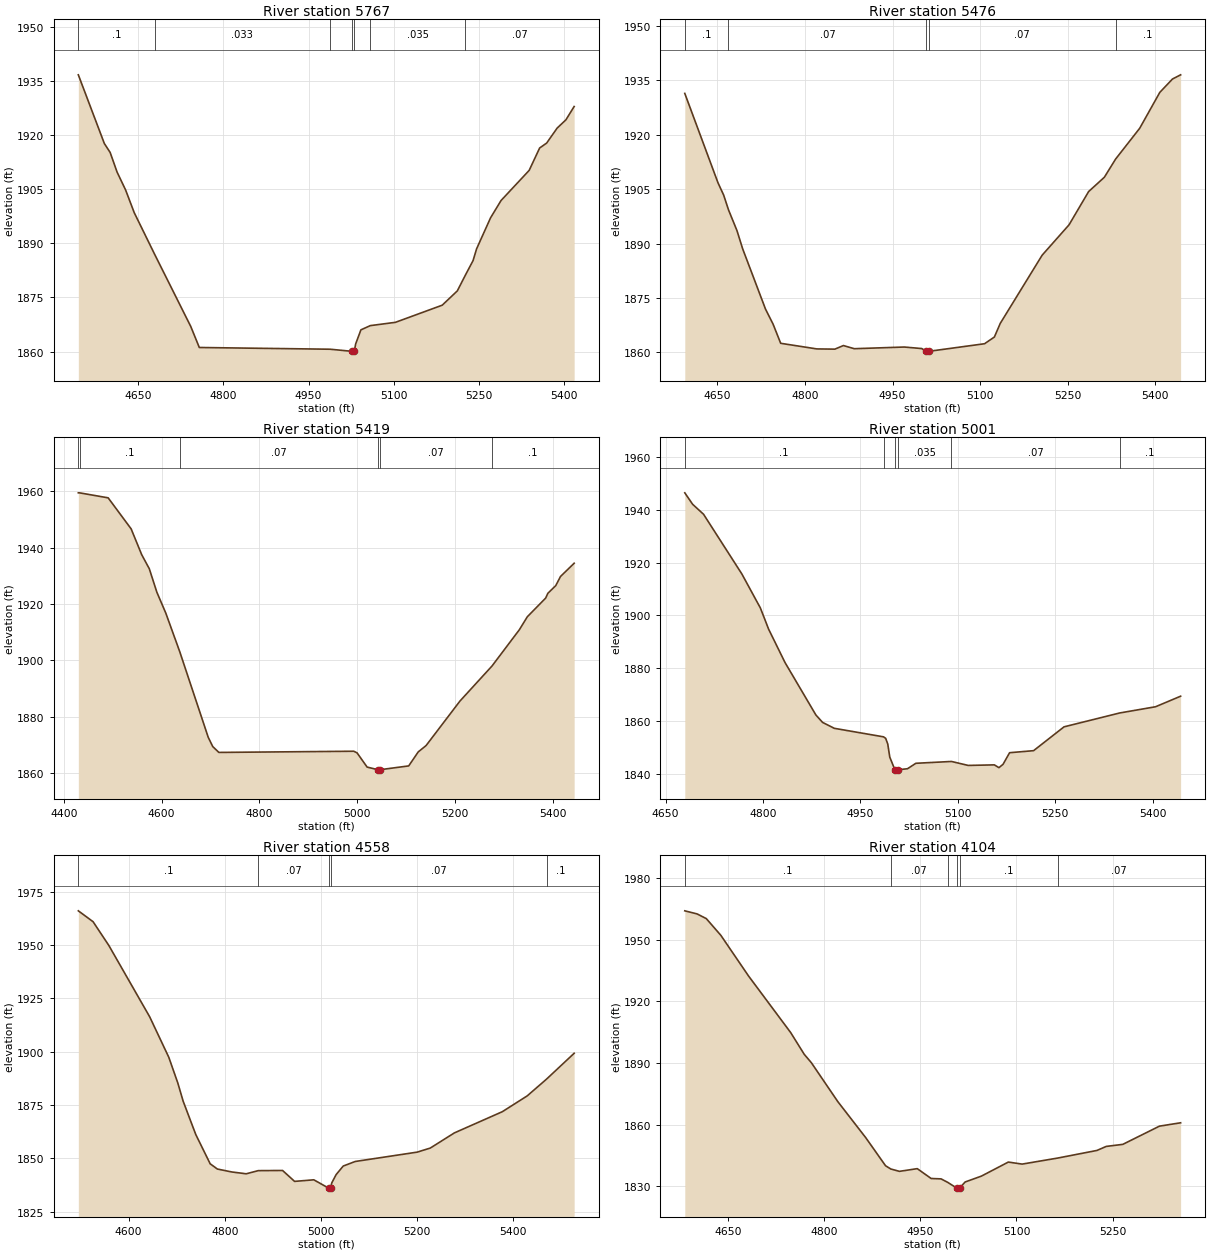
Type RM Length L Ch R = 1,5767,291,291,291
BEGIN DESCRIPTION:
Stream0523 13.0
END DESCRIPTION:
XS GIS Cut Line= 3
      1938829.03     13945958.22      1938544.52     13946172.70
      1938425.00     13946674.98
#Sta/Elev= 30
  4544.8 1936.64  4590.6 1917.62  4600.8 1915.15  4613.0 1909.72  4628.1 1904.73
  4643.1 1898.51  4678.9 1887.02  4742.7 1866.97  4757.7 1861.16  4988.0 1860.68
  5026.1 1860.10  5026.4 1859.60  5030.4 1860.10  5032.9 1862.15  5042.1 1866.04
  5058.6 1867.21  5103.0 1868.13  5185.2 1872.87  5211.8 1876.83  5226.1 1881.23
  5239.5 1885.22  5245.7 1888.47  5270.3 1897.06  5288.8 1901.86  5338.2 1910.18
  5356.7 1916.39  5369.0 1917.75  5387.5 1921.90  5402.9 1924.18  5417.4 1927.87
#Mann=7,-1,0
  4544.8     0.1       0  4678.9   0.033       0  4988.0    0.07       0
  5026.1    0.05       0  5030.4    0.07       0  5058.6   0.035       0
  5226.1    0.07       0
Bank Sta=5026.1,5030.4
Exp/Cntr=0.3,0.1

Type RM Length L Ch R = 1,5476,57,57,57
BEGIN DESCRIPTION:
Stream0523 12.0
END DESCRIPTION:
XS GIS Cut Line= 3
      1938793.90     13945916.24      1938439.47     13946065.37
      1938024.99     13946275.00
#Sta/Elev= 30
  4594.2 1931.41  4651.0 1906.78  4660.8 1903.36  4669.0 1899.33  4683.5 1893.60
  4693.3 1888.56  4732.4 1871.95  4745.4 1867.79  4758.4 1862.52  4820.2 1860.97
  4851.2 1860.91  4865.8 1861.90  4884.4 1861.03  4970.0 1861.49  4999.9 1861.07
  5007.9 1860.31  5008.2 1859.81  5012.2 1860.31  5107.5 1862.40  5124.3 1864.25
  5134.4 1868.02  5206.1 1886.81  5252.1 1895.17  5285.7 1904.35  5312.6 1908.29
  5331.8 1913.29  5373.1 1921.79  5407.6 1931.70  5429.3 1935.38  5443.2 1936.53
#Mann=5,-1,0
  4594.2     0.1       0  4669.0    0.07       0  5007.9    0.05       0
  5012.2    0.07       0  5331.8     0.1       0
Bank Sta=5007.9,5012.2
Exp/Cntr=0.3,0.1

Type RM Length L Ch R = 1,5419,418,418,418
BEGIN DESCRIPTION:
Stream0523 12.1
END DESCRIPTION:
XS GIS Cut Line= 4
      1938927.35     13945861.40      1938653.90     13945929.11
      1938289.32     13946067.13      1937971.62     13946194.73
#Sta/Elev= 30
  4429.9 1959.39  4432.6 1959.38  4490.9 1957.61  4537.9 1946.61  4559.5 1937.46
  4575.0 1932.49  4590.4 1924.20  4608.9 1916.69  4637.3 1903.07  4695.5 1872.74
  4704.8 1869.44  4717.3 1867.37  4993.2 1867.79  4999.9 1867.21  5020.4 1862.18
  5042.4 1861.24  5042.7 1860.74  5046.7 1861.24  5105.5 1862.59  5124.9 1867.54
  5141.1 1869.82  5210.3 1885.58  5275.9 1898.02  5331.8 1910.87  5348.0 1915.45
  5385.6 1922.09  5390.0 1923.77  5406.2 1926.51  5415.9 1929.74  5443.8 1934.43
#Mann=6,-1,0
  4429.9    0.07       0  4432.6     0.1       0  4637.3    0.07       0
  5042.4    0.05       0  5046.7    0.07       0  5275.9     0.1       0
Bank Sta=5042.4,5046.7
Exp/Cntr=0.3,0.1

Type RM Length L Ch R = 1,5001,443,443,443
BEGIN DESCRIPTION:
Stream0523 11.0
END DESCRIPTION:
XS GIS Cut Line= 3
      1938824.97     13945824.99      1938525.00     13945725.00
      1938125.01     13945924.99
#Sta/Elev= 30
  4679.5 1946.43  4691.5 1942.11  4708.4 1938.30  4767.4 1915.67  4795.9 1902.79
  4808.5 1894.80  4833.8 1882.13  4881.3 1862.27  4891.6 1859.45  4909.7 1857.20
  4985.5 1853.97  4988.8 1853.40  4992.0 1851.24  4995.1 1846.28  5003.0 1841.48
  5003.3 1840.98  5007.3 1841.48  5022.4 1841.89  5035.3 1843.95  5090.1 1844.64
  5115.8 1843.14  5156.1 1843.35  5163.2 1842.29  5169.5 1843.57  5179.6 1847.96
  5216.5 1848.73  5263.4 1857.76  5349.0 1863.01  5404.3 1865.37  5442.9 1869.37
#Mann=6,-1,0
  4679.5     0.1       0  4985.5   0.035       0  5003.0   0.035       0
  5007.3   0.035       0  5090.1    0.07       0  5349.0     0.1       0
Bank Sta=5003,5007.3
Exp/Cntr=0.3,0.1

Type RM Length L Ch R = 1,4558,454,454,454
BEGIN DESCRIPTION:
Stream0523 10.0
END DESCRIPTION:
XS GIS Cut Line= 3
      1938625.00     13945125.00      1938225.00     13945425.00
      1937825.01     13945775.00
#Sta/Elev= 30
  4495.3 1966.04  4526.0 1960.93  4558.7 1949.82  4643.7 1916.35  4683.5 1897.35
  4702.2 1885.32  4713.5 1876.66  4739.6 1861.13  4769.6 1847.38  4784.6 1844.92
  4814.6 1843.55  4844.6 1842.69  4869.5 1844.17  4920.2 1844.25  4945.2 1839.13
  4985.2 1839.87  5015.8 1836.00  5016.1 1835.50  5020.2 1836.00  5022.5 1838.40
  5031.6 1842.30  5046.4 1846.33  5071.4 1848.47  5200.2 1852.85  5227.5 1854.76
  5277.6 1861.87  5377.3 1871.81  5429.1 1879.23  5469.3 1887.09  5526.8 1899.22
#Mann=5,-1,0
  4495.3     0.1       0  4869.5    0.07       0  5015.8    0.05       0
  5020.2    0.07       0  5469.3     0.1       0
Bank Sta=5015.8,5020.2
Exp/Cntr=0.3,0.1

Type RM Length L Ch R = 1,4104,688,688,688
BEGIN DESCRIPTION:
Stream0523 9.0
END DESCRIPTION:
XS GIS Cut Line= 3
      1938475.01     13944925.00      1938075.00     13945025.00
      1937774.98     13945225.01
#Sta/Elev= 30
  4583.0 1964.11  4602.1 1962.61  4616.5 1960.33  4639.2 1952.17  4682.5 1932.32
  4748.1 1904.80  4769.1 1894.27  4780.3 1890.14  4821.7 1871.12  4865.0 1853.67
  4895.9 1839.98  4904.2 1838.37  4917.6 1837.24  4945.4 1838.55  4967.0 1833.76
  4982.5 1833.57  4992.7 1831.90  5007.0 1829.08  5007.3 1828.58  5011.4 1829.08
  5020.0 1832.06  5045.3 1834.91  5087.3 1841.75  5108.9 1840.77  5164.5 1843.72
  5225.5 1847.42  5240.0 1849.38  5265.8 1850.38  5322.9 1859.25  5355.9 1860.89
#Mann=6,-1,0
  4583.0     0.1       0  4904.2    0.07       0  4992.7     0.1       0
  5007.0    0.05       0  5011.4     0.1       0  5164.5    0.07       0
Bank Sta=5007,5011.4
Exp/Cntr=0.3,0.1

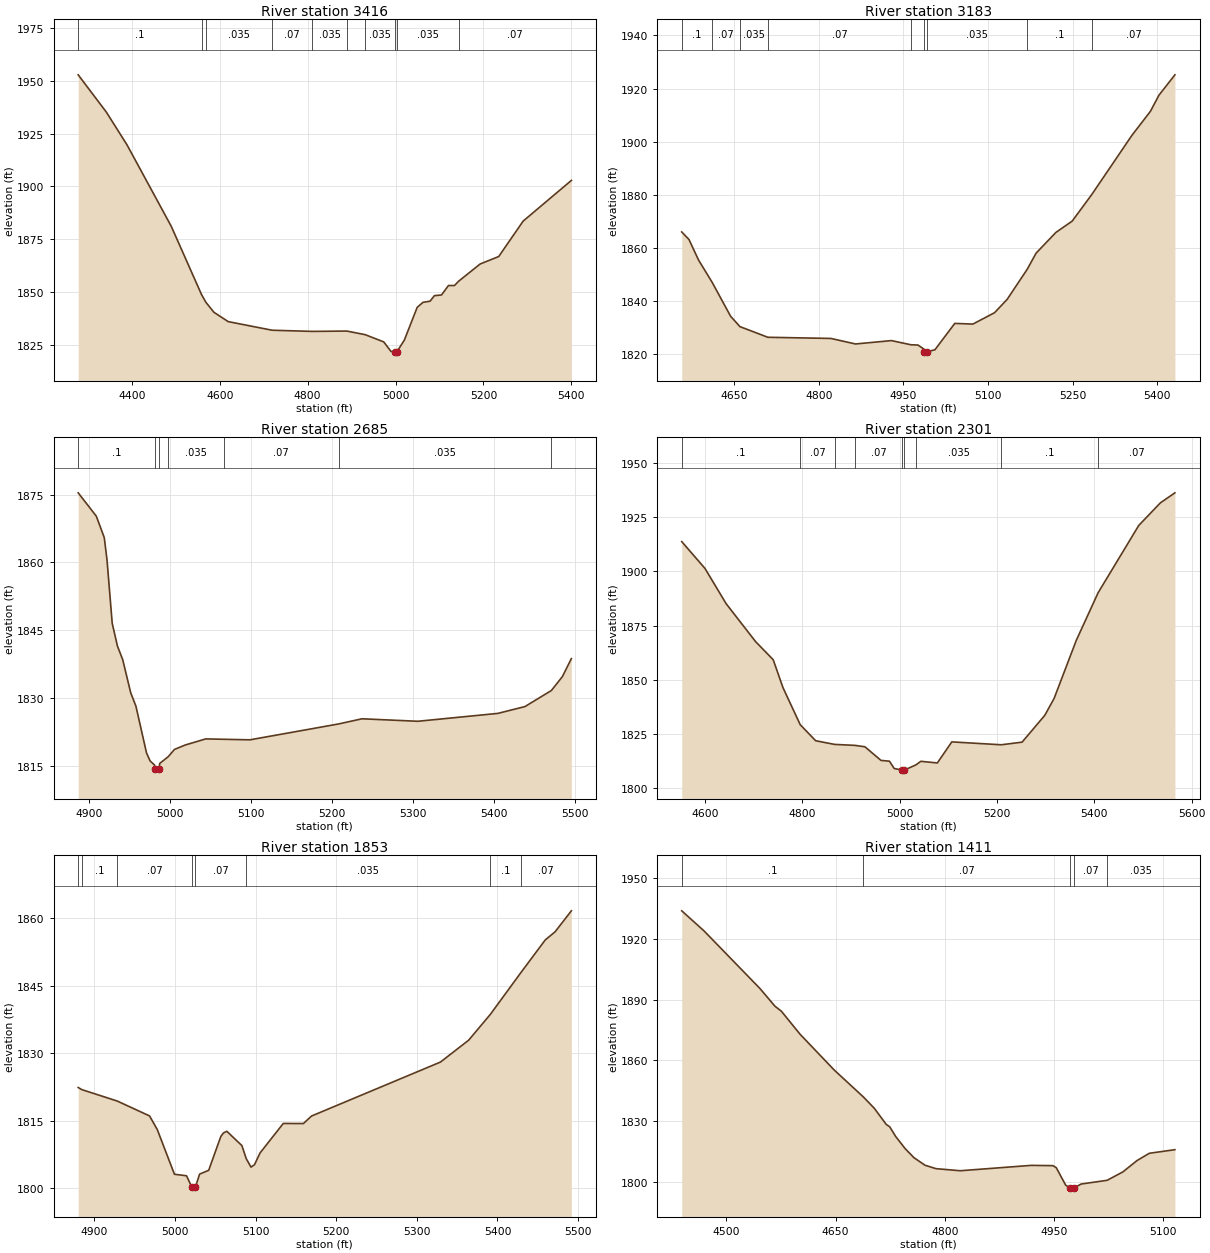
Type RM Length L Ch R = 1,3416,233,233,233
BEGIN DESCRIPTION:
Stream0523 8.0
END DESCRIPTION:
XS GIS Cut Line= 3
      1938225.01     13944325.00      1937621.46     13944724.49
      1937254.01     13944878.75
#Sta/Elev= 30
  4277.9 1952.75  4342.1 1935.08  4388.9 1919.68  4489.6 1881.17  4558.7 1848.82
  4568.5 1845.21  4586.8 1840.49  4619.2 1836.08  4719.2 1832.01  4810.1 1831.45
  4889.3 1831.61  4930.9 1829.91  4973.2 1826.49  4989.7 1821.99  4998.2 1821.68
  4998.6 1821.18  5002.8 1821.68  5020.1 1827.34  5049.3 1842.80  5062.4 1845.18
  5078.7 1845.75  5088.5 1848.35  5104.7 1848.67  5120.5 1853.14  5134.0 1853.12
  5143.8 1855.20  5192.6 1863.32  5234.9 1866.85  5290.5 1883.60  5400.2 1902.83
#Mann=10,-1,0
  4277.9     0.1       0  4558.7    0.07       0  4568.5   0.035       0
  4719.2    0.07       0  4810.1   0.035       0  4889.3     0.1       0
  4930.9   0.035       0  4998.2   0.035       0  5002.8   0.035       0
  5143.8    0.07       0
Bank Sta=4998.2,5002.8
Exp/Cntr=0.3,0.1

Type RM Length L Ch R = 1,3183,498,498,498
BEGIN DESCRIPTION:
Stream0523 7.0
END DESCRIPTION:
XS GIS Cut Line= 3
      1937925.00     13944325.00      1937525.00     13944525.00
      1937125.01     13944675.00
#Sta/Elev= 30
  4556.9 1865.98  4569.8 1863.11  4586.6 1855.44  4611.0 1846.94  4643.6 1834.20
  4660.1 1830.31  4709.6 1826.30  4821.4 1825.86  4865.0 1823.78  4928.7 1825.05
  4963.5 1823.47  4975.7 1823.38  4985.7 1821.93  4986.8 1820.83  4987.1 1820.33
  4991.4 1820.83  5005.8 1821.59  5041.0 1831.53  5073.1 1831.27  5111.5 1835.55
  5133.9 1840.59  5169.3 1851.86  5185.2 1857.99  5220.4 1865.82  5249.2 1870.06
  5283.9 1880.07  5355.0 1902.34  5387.8 1911.38  5403.1 1917.51  5431.3 1925.16
#Mann=9,-1,0
  4556.9     0.1       0  4611.0    0.07       0  4660.1   0.035       0
  4709.6    0.07       0  4963.5   0.035       0  4986.8   0.035       0
  4991.4   0.035       0  5169.3     0.1       0  5283.9    0.07       0
Bank Sta=4986.8,4991.4
Exp/Cntr=0.3,0.1

Type RM Length L Ch R = 1,2685,384,384,384
BEGIN DESCRIPTION:
Stream0523 6.0
END DESCRIPTION:
XS GIS Cut Line= 3
      1937775.00     13944075.00      1937672.75     13944118.89
      1937325.01     13944474.99
#Sta/Elev= 30
  4886.3 1875.39  4908.7 1870.22  4918.5 1865.49  4921.9 1860.55  4928.3 1846.55
  4934.8 1841.50  4941.3 1838.50  4951.1 1831.22  4957.6 1828.23  4970.7 1817.87
  4975.1 1816.12  4980.5 1815.24  4981.5 1814.37  4981.8 1813.87  4986.1 1814.37
  4987.0 1815.58  4997.4 1817.05  5005.2 1818.67  5018.7 1819.66  5043.8 1820.99
  5066.0 1820.91  5098.4 1820.79  5207.9 1824.30  5236.8 1825.44  5305.7 1824.89
  5404.5 1826.63  5438.0 1828.14  5470.6 1831.69  5484.2 1834.76  5495.3 1838.74
#Mann=7,-1,0
  4886.3     0.1       0  4981.5   0.035       0  4986.1     0.1       0
  4997.4   0.035       0  5066.0    0.07       0  5207.9   0.035       0
  5470.6     0.1       0
Bank Sta=4981.5,4986.1
Exp/Cntr=0.3,0.1

Type RM Length L Ch R = 1,2301,448,448,448
BEGIN DESCRIPTION:
Stream0523 5.0
END DESCRIPTION:
XS GIS Cut Line= 3
      1937724.98     13943825.01      1937325.00     13944025.00
      1936924.98     13944425.02
#Sta/Elev= 30
  4552.7 1913.78  4600.3 1901.42  4643.9 1885.09  4704.2 1867.61  4740.6 1859.17
  4760.7 1846.24  4796.1 1829.14  4827.8 1821.74  4866.7 1820.04  4908.1 1819.60
  4929.0 1818.94  4961.9 1812.65  4979.3 1812.28  4989.1 1808.90  5005.4 1808.19
  5005.7 1807.69  5010.1 1808.19  5033.3 1810.53  5043.8 1812.22  5077.7 1811.47
  5107.4 1821.21  5208.9 1819.87  5251.7 1821.08  5298.3 1833.46  5317.5 1841.29
  5363.0 1868.11  5407.9 1890.15  5491.4 1921.26  5535.9 1931.72  5565.6 1936.33
#Mann=9,-1,0
  4552.7     0.1       0  4796.1    0.07       0  4866.7   0.035       0
  4908.1    0.07       0  5005.4    0.05       0  5010.1    0.07       0
  5033.3   0.035       0  5208.9     0.1       0  5407.9    0.07       0
Bank Sta=5005.4,5010.1
Exp/Cntr=0.3,0.1

Type RM Length L Ch R = 1,1853,442,442,442
BEGIN DESCRIPTION:
Stream0523 4.0
END DESCRIPTION:
XS GIS Cut Line= 3
      1937125.02     13943624.96      1937075.00     13943725.00
      1936775.03     13944124.96
#Sta/Elev= 30
  4879.9 1822.37  4884.4 1821.90  4928.3 1819.36  4968.4 1816.05  4978.0 1813.02
  4999.3 1803.07  5014.3 1802.73  5020.7 1800.26  5021.0 1799.76  5025.4 1800.26
  5030.5 1803.10  5041.8 1803.95  5056.8 1811.46  5060.0 1812.24  5064.3 1812.63
  5083.0 1809.44  5088.4 1806.53  5094.3 1804.66  5098.6 1805.19  5105.5 1807.81
  5134.3 1814.37  5159.3 1814.35  5169.3 1816.02  5329.3 1828.03  5364.3 1832.90
  5391.1 1838.62  5429.1 1847.94  5459.3 1855.20  5471.5 1857.01  5491.7 1861.68
#Mann=8,-1,0
  4879.9    0.07       0  4884.4     0.1       0  4928.3    0.07       0
  5020.7    0.05       0  5025.4    0.07       0  5088.4   0.035       0
  5391.1     0.1       0  5429.1    0.07       0
Bank Sta=5020.7,5025.4
Exp/Cntr=0.3,0.1

Type RM Length L Ch R = 1,1411,447,447,447
BEGIN DESCRIPTION:
Stream0523 3.0
END DESCRIPTION:
XS GIS Cut Line= 3
      1937124.98     13943125.02      1936725.00     13943525.00
      1936624.97     13943575.02
#Sta/Elev= 30
  4438.7 1933.99  4469.2 1924.11  4546.2 1895.56  4566.7 1886.85  4575.6 1884.34
  4601.4 1872.91  4648.0 1855.33  4688.3 1841.92  4703.2 1836.37  4719.8 1828.30
  4724.4 1827.21  4732.5 1822.47  4745.6 1816.41  4757.7 1811.93  4772.8 1808.20
  4788.0 1806.49  4821.3 1805.46  4918.9 1808.12  4948.6 1807.98  4953.2 1806.99
  4966.2 1798.31  4972.3 1796.87  4972.7 1796.37  4977.1 1796.87  4987.4 1798.89
  5023.1 1800.73  5044.7 1804.88  5064.2 1810.50  5081.0 1814.09  5116.2 1815.88
#Mann=5,-1,0
  4438.7     0.1       0  4688.3    0.07       0  4972.3    0.05       0
  4977.1    0.07       0  5023.1   0.035       0
Bank Sta=4972.3,4977.1
Exp/Cntr=0.3,0.1