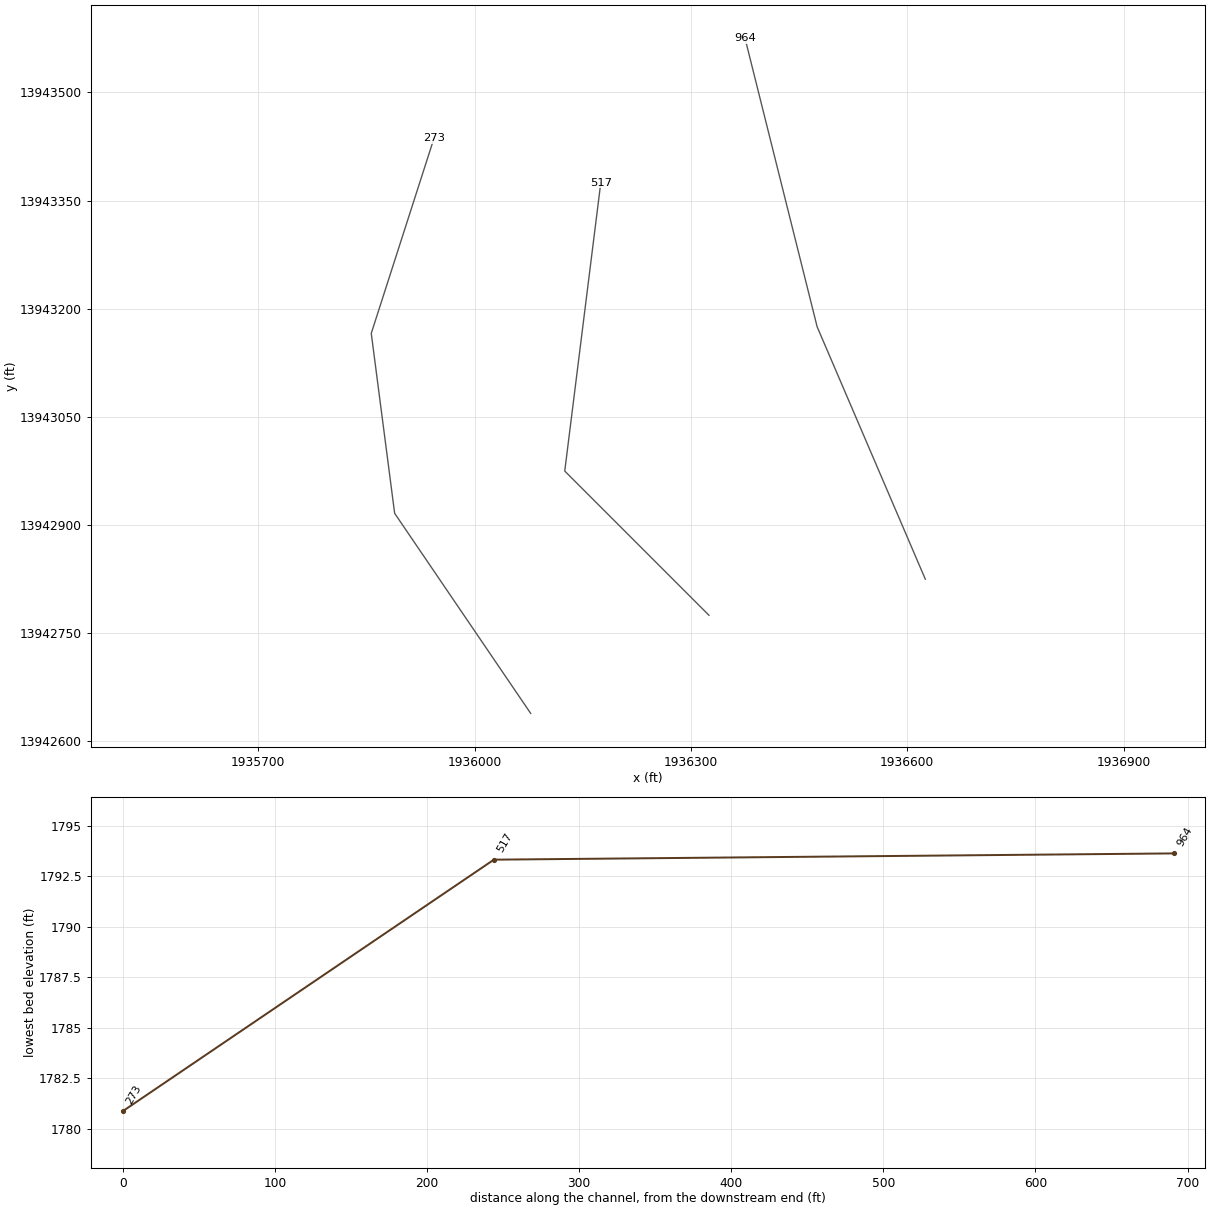
HEC-RAS study Stream0523.prj: Stream0523 Base Level Engineering

--- Stream0523.g01 (geometry) --- (continued)

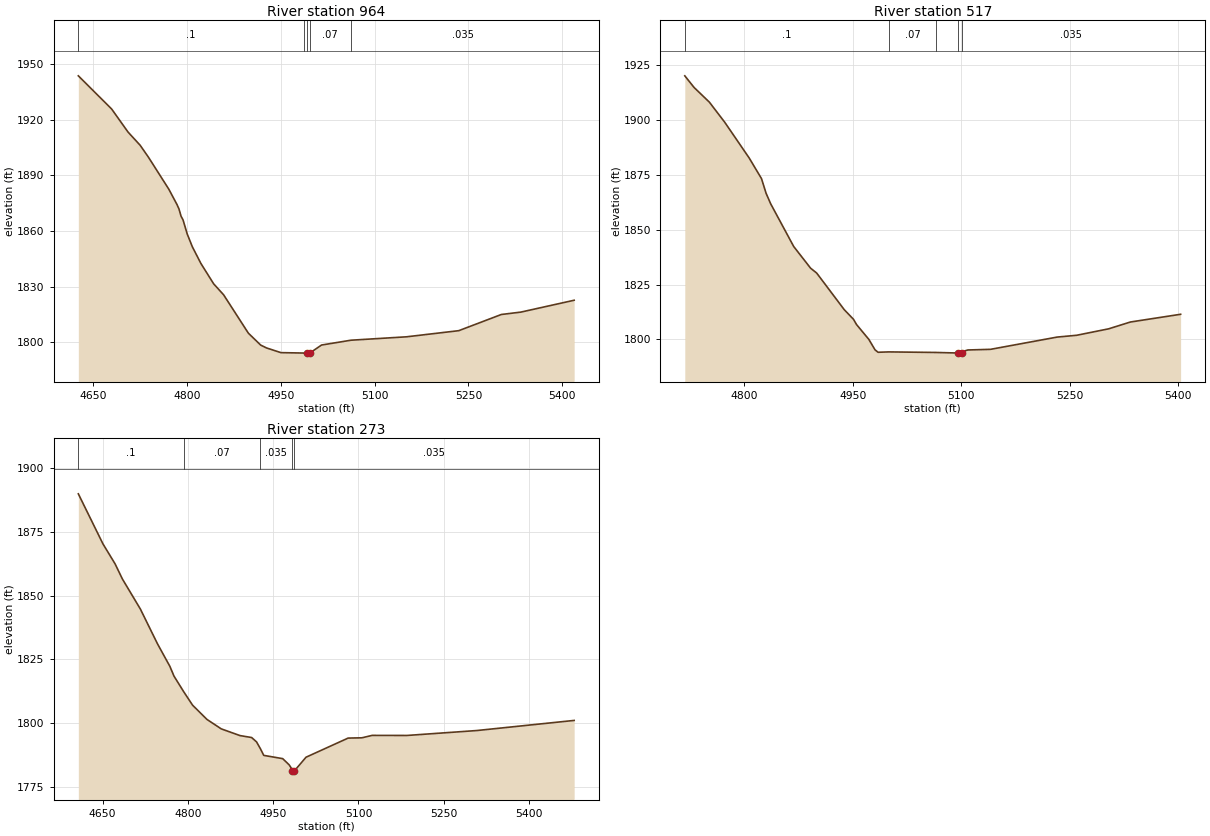
Type RM Length L Ch R = 1,964,447,447,447
BEGIN DESCRIPTION:
Stream0523 2.0
END DESCRIPTION:
XS GIS Cut Line= 3
      1936624.99     13942825.03      1936475.00     13943175.00
      1936374.99     13943575.03
#Sta/Elev= 30
  4626.1 1943.68  4679.4 1925.79  4705.5 1913.41  4725.1 1906.20  4738.2 1899.84
  4770.8 1882.58  4783.9 1874.30  4787.1 1871.89  4790.4 1868.02  4793.6 1865.99
  4800.2 1858.48  4808.5 1851.50  4822.2 1842.49  4842.6 1831.53  4858.5 1825.62
  4898.1 1804.93  4917.7 1798.54  4927.0 1796.99  4950.2 1794.44  4987.1 1794.22
  4991.2 1794.14  4991.5 1793.64  4996.0 1794.14  5015.1 1798.54  5062.1 1801.14
  5151.2 1802.98  5234.7 1806.29  5302.7 1815.01  5333.9 1816.29  5419.2 1822.69
#Mann=5,-1,0
  4626.1     0.1       0  4987.1    0.07       0  4991.2    0.05       0
  4996.0    0.07       0  5062.1   0.035       0
Bank Sta=4991.2,4996
Exp/Cntr=0.3,0.1

Type RM Length L Ch R = 1,517,244,244,244
BEGIN DESCRIPTION:
Stream0523 1.0
END DESCRIPTION:
XS GIS Cut Line= 3
      1936324.99     13942775.01      1936125.00     13942975.00
      1936175.00     13943374.96
#Sta/Elev= 30
  4717.8 1919.96  4730.6 1914.68  4751.8 1907.98  4773.0 1898.86  4806.9 1882.56
  4823.9 1873.20  4830.3 1866.48  4836.6 1861.74  4868.5 1842.28  4891.8 1832.45
  4900.3 1830.20  4938.4 1813.55  4951.2 1809.16  4955.4 1806.78  4972.4 1800.04
  4980.9 1795.32  4985.1 1794.18  5000.4 1794.34  5064.9 1794.09  5096.0 1793.83
  5096.4 1793.33  5100.9 1793.83  5101.4 1794.48  5109.4 1795.22  5140.7 1795.51
  5232.8 1801.08  5259.9 1801.91  5304.0 1804.83  5334.2 1807.94  5403.7 1811.46
#Mann=5,-1,0
  4717.8     0.1       0  5000.4    0.07       0  5064.9   0.035       0
  5096.0    0.05       0  5100.9   0.035       0
Bank Sta=5096,5100.9
Exp/Cntr=0.3,0.1

Type RM Length L Ch R = 1,273,0,0,0
BEGIN DESCRIPTION:
Stream0523 0.0
END DESCRIPTION:
XS GIS Cut Line= 4
      1936077.76     13942638.97      1935889.12     13942916.38
      1935856.70     13943165.92      1935943.81     13943436.85
#Sta/Elev= 30
  4607.5 1889.87  4650.8 1870.26  4672.1 1862.45  4685.0 1856.50  4716.5 1844.78
  4746.6 1831.15  4768.4 1822.32  4775.7 1818.47  4792.8 1812.35  4808.3 1807.11
  4833.7 1801.50  4858.8 1797.81  4891.8 1795.18  4912.2 1794.42  4920.8 1792.72
  4927.5 1790.08  4933.5 1787.43  4966.8 1786.15  4978.1 1783.74  4981.9 1782.43
  4982.5 1781.37  4982.9 1780.87  4987.4 1781.37  5007.8 1786.71  5081.8 1794.20
  5106.0 1794.31  5124.1 1795.26  5185.2 1795.23  5308.1 1797.16  5479.2 1801.12
#Mann=5,-1,0
  4607.5     0.1       0  4792.8    0.07       0  4927.5   0.035       0
  4982.5   0.035       0  4987.4   0.035       0
Bank Sta=4982.5,4987.4
Exp/Cntr=0.3,0.1

Chan Stop Cuts=-1