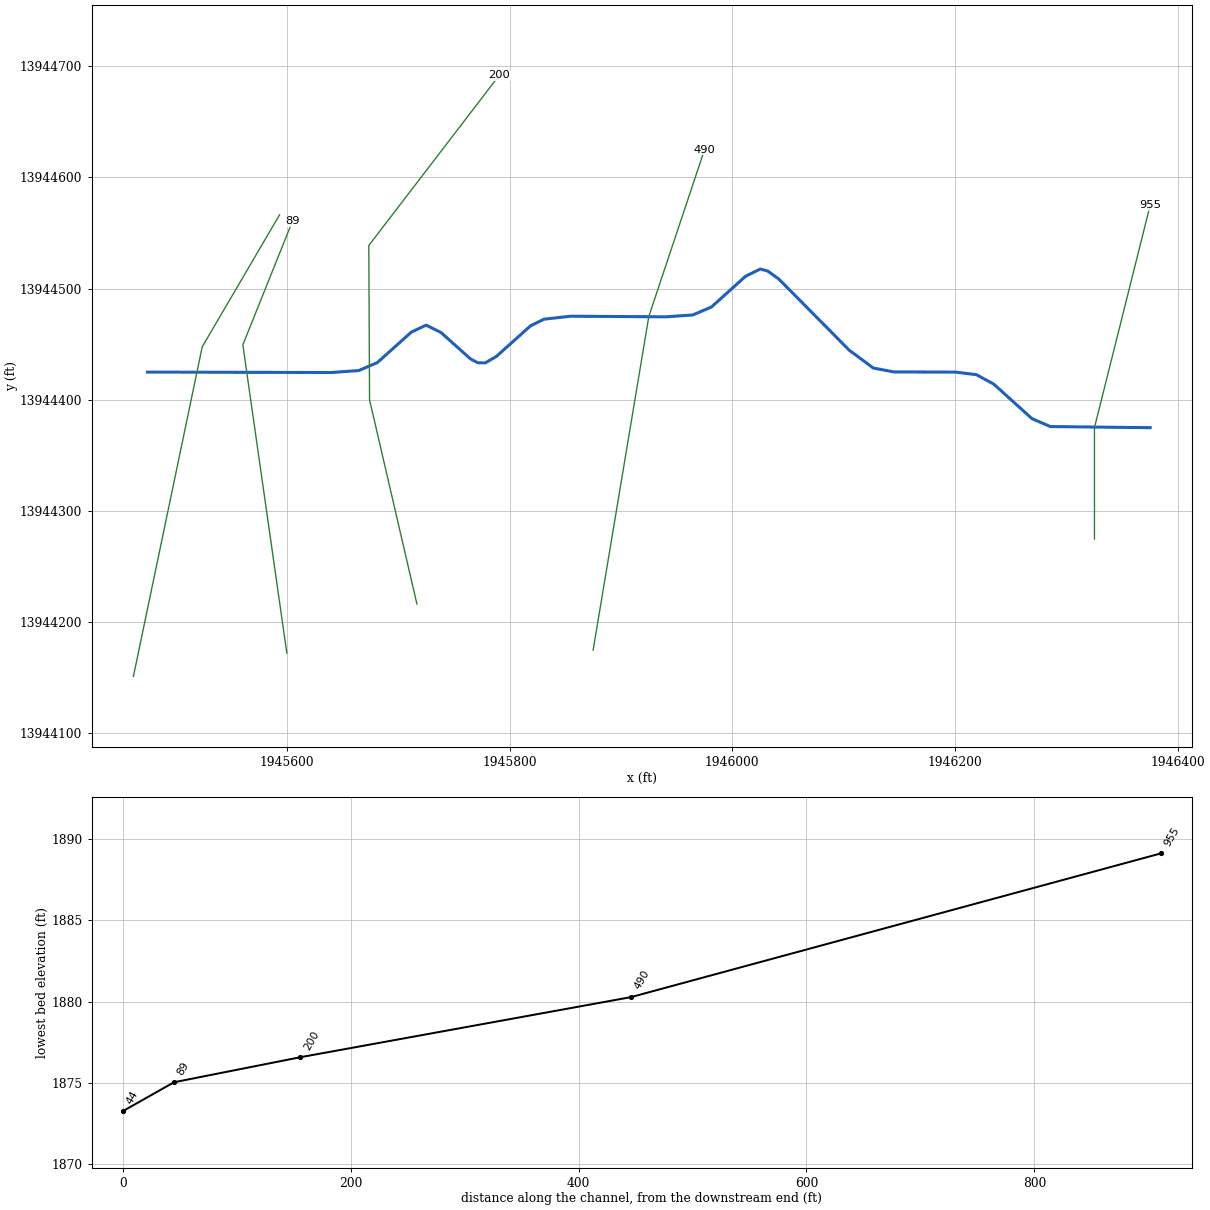
--- Stream0524.prj (project) ---

Proj Title=Stream0524 Base Level Engineering
Current Plan=p01
Default Exp/Contr=0.3,0.1
English Units
Geom File=g01
Flow File=f01
Plan File=p01
BEGIN DESCRIPTION:
Stream0524
END DESCRIPTION:

--- Stream0524.p01 (plan) ---

Plan Title=Multiple Run
Short Identifier=Multiple
Geom File=g01
Flow File=f01
Subcritical Flow
K Sum by GR= 0
Std Step Tol= 0.01
Critical Tol= 0.01
Num of Std Step Trials= 20
Max Error Tol= 0.3
Flow Tol Ratio= 0.001
Split Flow NTrial= 30
Split Flow Tol= 0.02
Split Flow Ratio= 0.02
Log Output Level= 0
Friction Slope Method= 1
Unsteady Friction Slope Method= 2
Unsteady Bridges Friction Slope Method= 1
Parabolic Critical Depth
Global Vel Dist=  1 , 1 , 1
Global Log Level= 0
CheckData=True
Encroach Param= -1, 0, 0, 0
BEGIN DESCRIPTION:
Multiple Run
END DESCRIPTION:

--- Stream0524.f01 (steady flow) ---

Flow Title=Multiple
Number of Profiles=7
Profile Names=10-year,25-year,50-year,1pct_min,100-year,1pct_plu,500-year
River Rch & RM= Stream0524,Reach-1,955
     826    1388    1918    1285    2564    5116    4514
Boundary for River Rch & Prof#=Stream0524,Reach-1,1
Up Type=0
Dn Type=3
Dn Slope=0.005
Boundary for River Rch & Prof#=Stream0524,Reach-1,2
Up Type=0
Dn Type=3
Dn Slope=0.005
Boundary for River Rch & Prof#=Stream0524,Reach-1,3
Up Type=0
Dn Type=3
Dn Slope=0.005
Boundary for River Rch & Prof#=Stream0524,Reach-1,4
Up Type=0
Dn Type=3
Dn Slope=0.005
Boundary for River Rch & Prof#=Stream0524,Reach-1,5
Up Type=0
Dn Type=3
Dn Slope=0.005
Boundary for River Rch & Prof#=Stream0524,Reach-1,6
Up Type=0
Dn Type=3
Dn Slope=0.005
Boundary for River Rch & Prof#=Stream0524,Reach-1,7
Up Type=0
Dn Type=3
Dn Slope=0.005

--- Stream0524.g01 (geometry) ---

Geom Title=Existing Conditions

River Reach=Stream0524,Reach-1
Reach XY= 30
      1946375.00     13944375.00      1946285.42     13944376.02
      1946268.93     13944383.11      1946234.65     13944414.16
      1946219.03     13944422.66      1946200.00     13944425.00
      1946145.05     13944425.13      1946126.50     13944428.64
      1946104.85     13944444.71      1946041.69     13944508.67
      1946031.73     13944515.85      1946025.10     13944517.67
      1946011.84     13944511.17      1945981.19     13944483.48
      1945964.56     13944476.40      1945940.19     13944474.67
      1945854.83     13944475.25      1945830.86     13944472.54
      1945818.81     13944466.56      1945788.16     13944439.07
      1945778.22     13944433.28      1945771.59     13944433.35
      1945764.95     13944436.83      1945738.37     13944460.65
      1945725.10     13944467.21      1945711.84     13944460.93
      1945681.19     13944433.43      1945664.57     13944426.37
      1945640.21     13944424.61      1945475.00     13944425.00

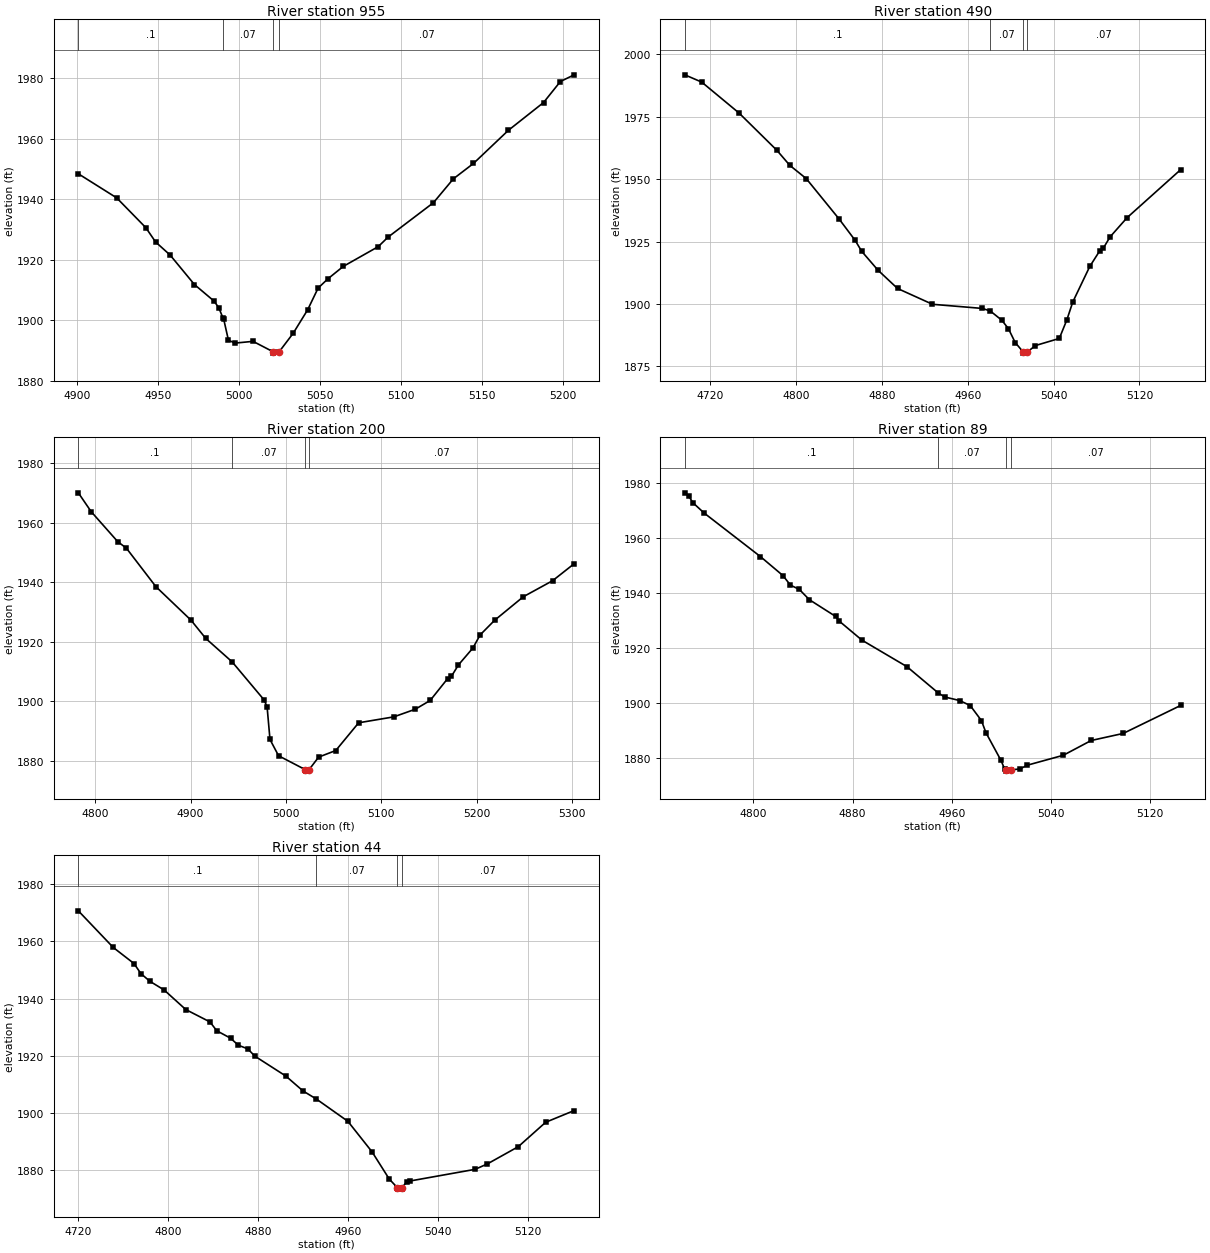
Type RM Length L Ch R = 1,955,465,465,465
BEGIN DESCRIPTION:
Stream0524 2.0
END DESCRIPTION:
XS GIS Cut Line= 3
      1946325.00     13944274.95      1946325.00     13944375.00
      1946375.00     13944575.00
#Sta/Elev= 30
  4900.6 1948.40  4924.3 1940.43  4942.3 1930.57  4948.3 1925.86  4957.3 1921.52
  4972.3 1911.78  4984.3 1906.36  4987.3 1904.16  4989.8 1900.88  4990.3 1900.50
  4993.3 1893.36  4997.4 1892.42  5008.5 1892.99  5020.7 1889.60  5020.9 1889.10
  5024.7 1889.60  5033.3 1895.68  5042.2 1903.41  5048.7 1910.63  5054.9 1913.75
  5064.2 1917.77  5085.8 1924.31  5091.9 1927.47  5119.9 1938.84  5132.2 1946.73
  5144.6 1951.81  5166.2 1962.78  5187.9 1971.96  5198.3 1978.91  5206.8 1981.12
#Mann=4,-1,0
  4900.6     0.1       0  4989.8    0.07       0  5020.7    0.05       0
  5024.7    0.07       0
Bank Sta=5020.7,5024.7
Exp/Cntr=0.3,0.1

Type RM Length L Ch R = 1,490,290,290,290
BEGIN DESCRIPTION:
Stream0524 1.0
END DESCRIPTION:
XS GIS Cut Line= 3
      1945875.01     13944175.03      1945925.00     13944475.00
      1945974.99     13944624.98
#Sta/Elev= 30
  4696.2 1991.79  4712.0 1988.87  4746.8 1976.47  4782.0 1961.56  4794.1 1955.51
  4809.4 1950.21  4839.8 1934.15  4855.0 1925.46  4861.1 1921.07  4876.3 1913.50
  4894.5 1906.18  4927.1 1899.84  4973.6 1898.18  4981.0 1897.15  4991.8 1893.42
  4997.9 1890.05  5004.2 1884.50  5011.6 1880.77  5011.9 1880.27  5015.6 1880.77
  5023.1 1883.31  5045.3 1886.15  5052.3 1893.54  5057.9 1900.79  5073.7 1914.99
  5083.1 1921.33  5086.4 1922.37  5092.7 1926.88  5108.5 1934.55  5158.4 1953.78
#Mann=4,-1,0
  4696.2     0.1       0  4981.0    0.07       0  5011.6    0.05       0
  5015.6    0.07       0
Bank Sta=5011.6,5015.6
Exp/Cntr=0.3,0.1

Type RM Length L Ch R = 1,200,111,111,111
BEGIN DESCRIPTION:
Stream0524 0.0
END DESCRIPTION:
XS GIS Cut Line= 4
      1945716.84     13944216.49      1945674.34     13944400.10
      1945673.67     13944538.82      1945790.82     13944691.96
#Sta/Elev= 30
  4782.3 1970.00  4795.8 1963.67  4823.5 1953.66  4832.8 1951.38  4863.6 1938.52
  4900.5 1927.24  4915.9 1921.14  4943.6 1913.26  4977.3 1900.41  4980.3 1898.05
  4983.3 1887.20  4992.3 1881.74  5020.3 1877.08  5020.6 1876.58  5024.3 1877.08
  5034.3 1881.28  5052.3 1883.50  5076.3 1892.81  5113.1 1894.79  5135.7 1897.36
  5151.3 1900.30  5169.7 1907.67  5173.5 1908.36  5181.0 1912.26  5196.1 1917.90
  5203.7 1922.31  5218.8 1927.19  5249.0 1935.12  5279.7 1940.50  5302.3 1946.20
#Mann=4,-1,0
  4782.3     0.1       0  4943.6    0.07       0  5020.3    0.05       0
  5024.3    0.07       0
Bank Sta=5020.3,5024.3
Exp/Cntr=0.3,0.1

Type RM Length L Ch R = 1,89,45,45,45
BEGIN DESCRIPTION:
Stream0524 0.1
END DESCRIPTION:
XS GIS Cut Line= 3
      1945600.09     13944172.29      1945560.61     13944449.50
      1945605.12     13944560.61
#Sta/Elev= 30
  4744.8 1976.43  4748.2 1975.15  4751.2 1972.88  4760.3 1969.10  4805.8 1953.19
  4823.9 1946.29  4830.0 1942.79  4837.1 1941.25  4845.2 1937.50  4866.4 1931.40
  4869.4 1929.66  4887.6 1922.76  4923.9 1913.09  4949.0 1903.56  4954.3 1902.05
  4966.4 1900.76  4974.9 1898.92  4983.9 1893.47  4987.6 1889.01  4999.7 1878.93
  5002.7 1875.73  5003.8 1875.54  5004.0 1875.04  5007.8 1875.54  5014.9 1875.81
  5020.8 1877.19  5049.9 1880.81  5072.4 1886.20  5098.2 1888.77  5144.5 1898.96
#Mann=4,-1,0
  4744.8     0.1       0  4949.0    0.07       0  5003.8    0.05       0
  5007.8    0.07       0
Bank Sta=5003.8,5007.8
Exp/Cntr=0.3,0.1

Type RM Length L Ch R = 1,44,0,0,0
BEGIN DESCRIPTION:
Stream0524 0.3
END DESCRIPTION:
XS GIS Cut Line= 3
      1945462.36     13944151.25      1945524.16     13944447.75
      1945593.59     13944566.47
#Sta/Elev= 30
  4720.4 1970.74  4751.4 1957.91  4769.8 1952.29  4776.0 1948.75  4783.9 1946.07
  4796.6 1943.02  4815.8 1936.17  4837.3 1931.83  4843.4 1928.72  4855.6 1926.13
  4862.5 1923.67  4871.0 1922.37  4877.1 1919.86  4904.7 1912.87  4920.0 1907.64
  4931.9 1904.80  4959.8 1897.02  4981.3 1886.31  4996.6 1876.77  5003.8 1873.76
  5004.1 1873.26  5007.6 1873.26  5007.8 1873.76  5011.9 1875.71  5015.0 1876.11
  5072.8 1880.19  5083.8 1882.11  5111.2 1888.14  5135.5 1896.68  5160.8 1900.78
#Mann=4,-1,0
  4720.4     0.1       0  4931.9    0.07       0  5003.8    0.05       0
  5007.8    0.07       0
Bank Sta=5003.8,5007.8
Exp/Cntr=0.3,0.1

Chan Stop Cuts=-1