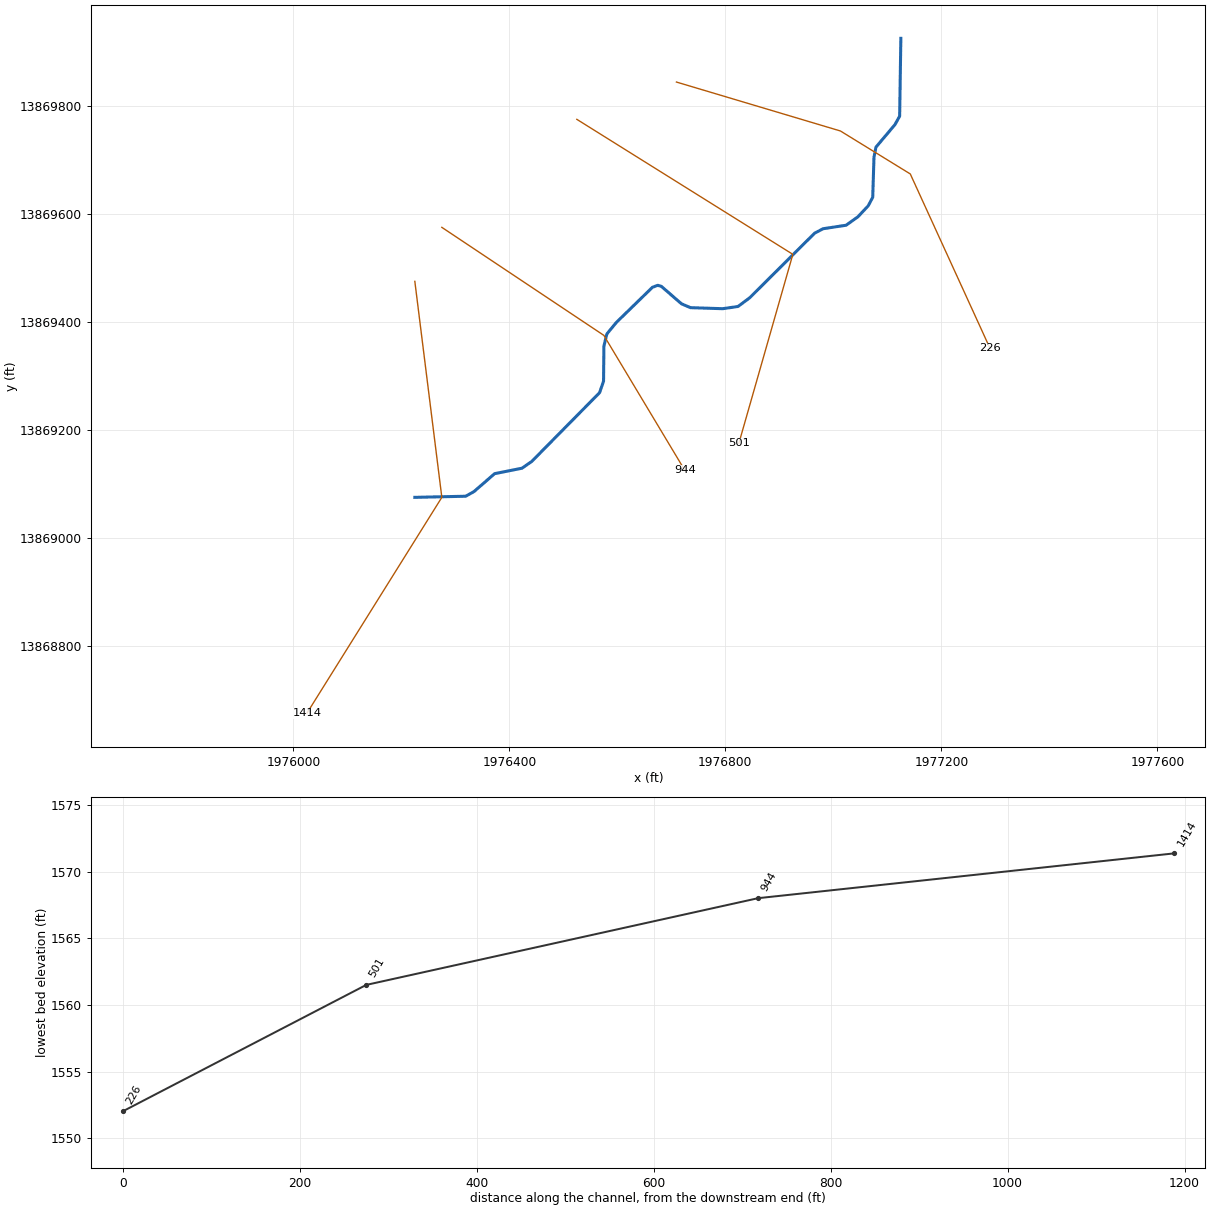
--- Stream0525.prj (project) ---

Proj Title=Stream0525 Base Level Engineering
Current Plan=p01
Default Exp/Contr=0.3,0.1
English Units
Geom File=g01
Flow File=f01
Plan File=p01
BEGIN DESCRIPTION:
Stream0525
END DESCRIPTION:

--- Stream0525.p01 (plan) ---

Plan Title=Multiple Run
Short Identifier=Multiple
Geom File=g01
Flow File=f01
Subcritical Flow
K Sum by GR= 0
Std Step Tol= 0.01
Critical Tol= 0.01
Num of Std Step Trials= 20
Max Error Tol= 0.3
Flow Tol Ratio= 0.001
Split Flow NTrial= 30
Split Flow Tol= 0.02
Split Flow Ratio= 0.02
Log Output Level= 0
Friction Slope Method= 1
Unsteady Friction Slope Method= 2
Unsteady Bridges Friction Slope Method= 1
Parabolic Critical Depth
Global Vel Dist=  1 , 1 , 1
Global Log Level= 0
CheckData=True
Encroach Param= -1, 0, 0, 0
BEGIN DESCRIPTION:
Multiple Run
END DESCRIPTION:

--- Stream0525.f01 (steady flow) ---

Flow Title=Multiple
Number of Profiles=7
Profile Names=10-year,25-year,50-year,1pct_min,100-year,1pct_plu,500-year
River Rch & RM= Stream0525,Reach-1,1414
    1335    2313    3262    2230    4449    8878    8194
Boundary for River Rch & Prof#=Stream0525,Reach-1,1
Up Type=0
Dn Type=3
Dn Slope=0.005
Boundary for River Rch & Prof#=Stream0525,Reach-1,2
Up Type=0
Dn Type=3
Dn Slope=0.005
Boundary for River Rch & Prof#=Stream0525,Reach-1,3
Up Type=0
Dn Type=3
Dn Slope=0.005
Boundary for River Rch & Prof#=Stream0525,Reach-1,4
Up Type=0
Dn Type=3
Dn Slope=0.005
Boundary for River Rch & Prof#=Stream0525,Reach-1,5
Up Type=0
Dn Type=3
Dn Slope=0.005
Boundary for River Rch & Prof#=Stream0525,Reach-1,6
Up Type=0
Dn Type=3
Dn Slope=0.005
Boundary for River Rch & Prof#=Stream0525,Reach-1,7
Up Type=0
Dn Type=3
Dn Slope=0.005

--- Stream0525.g01 (geometry) ---

Geom Title=Existing Conditions

River Reach=Stream0525,Reach-1
Reach XY= 30
      1976225.00     13869075.00      1976319.14     13869077.07
      1976334.67     13869085.79      1976372.82     13869118.89
      1976423.37     13869128.94      1976441.68     13869141.64
      1976567.14     13869268.83      1976574.47     13869290.22
      1976575.13     13869354.95      1976580.52     13869377.46
      1976597.88     13869398.63      1976664.92     13869463.91
      1976674.89     13869467.69      1976681.52     13869465.71
      1976718.83     13869433.42      1976735.48     13869426.27
      1976795.08     13869424.34      1976823.50     13869428.46
      1976845.15     13869444.58      1976965.34     13869564.21
      1976981.09     13869572.45      1977023.60     13869578.88
      1977045.57     13869594.59      1977064.61     13869614.90
      1977072.93     13869630.71      1977075.25     13869704.89
      1977078.86     13869723.40      1977114.16     13869765.35
      1977122.78     13869780.92      1977125.00     13869925.00

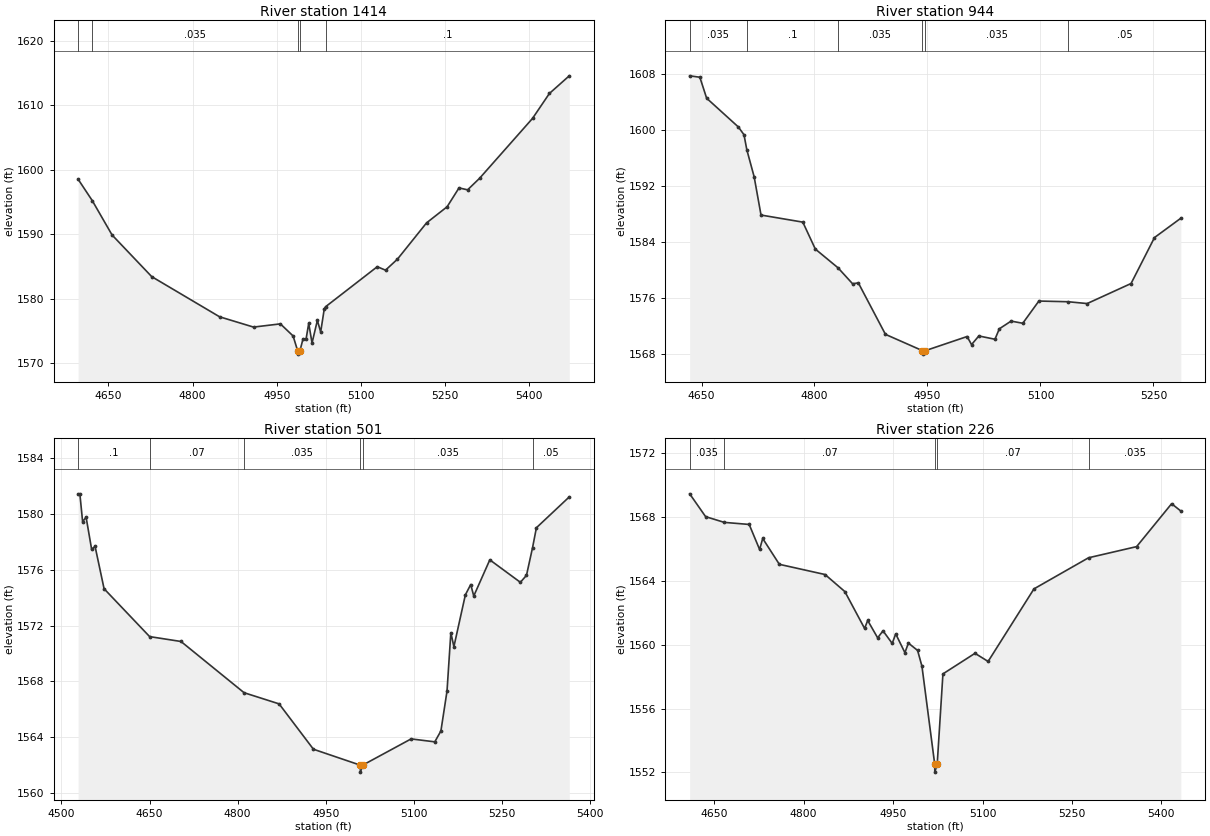
Type RM Length L Ch R = 1,1414,470,470,470
BEGIN DESCRIPTION:
Stream0525 3.0
END DESCRIPTION:
XS GIS Cut Line= 3
      1976224.99     13869475.05      1976275.00     13869075.00
      1976024.98     13868674.97
#Sta/Elev= 30
  4596.1 1598.54  4621.3 1595.22  4656.6 1589.88  4727.2 1583.41  4848.1 1577.17
  4908.6 1575.57  4956.4 1576.07  4979.1 1574.19  4987.2 1571.87  4987.4 1571.37
  4991.2 1571.87  4996.7 1573.72  5002.2 1573.72  5006.9 1576.15  5012.8 1573.10
  5022.3 1576.61  5028.2 1574.81  5034.6 1578.41  5036.9 1578.73  5129.0 1584.95
  5143.7 1584.41  5164.9 1586.12  5216.8 1591.76  5253.4 1594.26  5274.6 1597.19
  5289.9 1596.89  5311.2 1598.68  5405.5 1607.98  5435.6 1611.86  5471.0 1614.60
#Mann=5,-1,0
  4596.1    0.07       0  4621.3   0.035       0  4987.2   0.035       0
  4991.2   0.035       0  5036.9     0.1       0
Bank Sta=4987.2,4991.2
Exp/Cntr=0.3,0.1

Type RM Length L Ch R = 1,944,443,443,443
BEGIN DESCRIPTION:
Stream0525 2.0
END DESCRIPTION:
XS GIS Cut Line= 3
      1976274.99     13869575.01      1976575.00     13869375.00
      1976724.99     13869125.01
#Sta/Elev= 30
  4634.3 1607.69  4647.8 1607.49  4656.8 1604.50  4698.9 1600.40  4706.4 1599.29
  4710.2 1597.13  4719.9 1593.29  4729.0 1587.84  4784.5 1586.83  4801.1 1582.99
  4831.2 1580.32  4850.6 1578.04  4858.2 1578.17  4894.2 1570.83  4943.2 1568.51
  4943.5 1568.01  4947.3 1568.51  5002.6 1570.52  5008.5 1569.37  5018.2 1570.60
  5039.6 1570.13  5045.4 1571.62  5061.0 1572.72  5076.5 1572.41  5097.9 1575.58
  5136.7 1575.48  5162.0 1575.22  5220.3 1578.08  5251.4 1584.63  5286.4 1587.39
#Mann=6,-1,0
  4634.3   0.035       0  4710.2     0.1       0  4831.2   0.035       0
  4943.2   0.035       0  4947.3   0.035       0  5136.7    0.05       0
Bank Sta=4943.2,4947.3
Exp/Cntr=0.3,0.1

Type RM Length L Ch R = 1,501,275,275,275
BEGIN DESCRIPTION:
Stream0525 1.0
END DESCRIPTION:
XS GIS Cut Line= 3
      1976524.99     13869775.01      1976925.00     13869525.00
      1976825.01     13869175.02
#Sta/Elev= 30
  4528.5 1581.44  4531.5 1581.44  4536.2 1579.44  4542.1 1579.77  4551.5 1577.47
  4557.4 1577.67  4572.7 1574.64  4650.2 1571.21  4703.6 1570.86  4810.9 1567.19
  4870.5 1566.39  4928.9 1563.14  5008.6 1562.00  5008.9 1561.50  5012.7 1562.00
  5095.1 1563.88  5135.4 1563.67  5145.8 1564.45  5156.2 1567.31  5162.7 1571.49
  5167.9 1570.49  5187.4 1574.20  5196.5 1574.94  5201.7 1574.12  5229.0 1576.71
  5281.0 1575.10  5291.4 1575.60  5301.7 1577.58  5308.3 1579.01  5364.2 1581.22
#Mann=6,-1,0
  4528.5     0.1       0  4650.2    0.07       0  4810.9   0.035       0
  5008.6   0.035       0  5012.7   0.035       0  5301.7    0.05       0
Bank Sta=5008.6,5012.7
Exp/Cntr=0.3,0.1

Type RM Length L Ch R = 1,226,0,0,0
BEGIN DESCRIPTION:
Stream0525 0.0
END DESCRIPTION:
XS GIS Cut Line= 4
      1976709.40     13869844.08      1977013.16     13869753.43
      1977142.47     13869673.87      1977290.12     13869350.95
#Sta/Elev= 30
  4608.8 1569.47  4635.5 1568.04  4666.8 1567.68  4708.6 1567.55  4726.1 1565.98
  4731.3 1566.67  4759.2 1565.05  4835.9 1564.41  4869.1 1563.34  4902.2 1561.03
  4907.4 1561.53  4924.1 1560.44  4933.1 1560.88  4948.5 1560.09  4954.4 1560.69
  4969.8 1559.51  4975.7 1560.11  4991.1 1559.65  4998.4 1558.66  5019.8 1552.52
  5020.0 1552.02  5024.0 1552.52  5033.6 1558.18  5087.4 1559.47  5109.4 1558.96
  5186.3 1563.51  5277.8 1565.46  5358.5 1566.16  5417.2 1568.85  5432.7 1568.39
#Mann=5,-1,0
  4608.8   0.035       0  4666.8    0.07       0  5019.8    0.05       0
  5024.0    0.07       0  5277.8   0.035       0
Bank Sta=5019.8,5024
Exp/Cntr=0.3,0.1

Chan Stop Cuts=-1