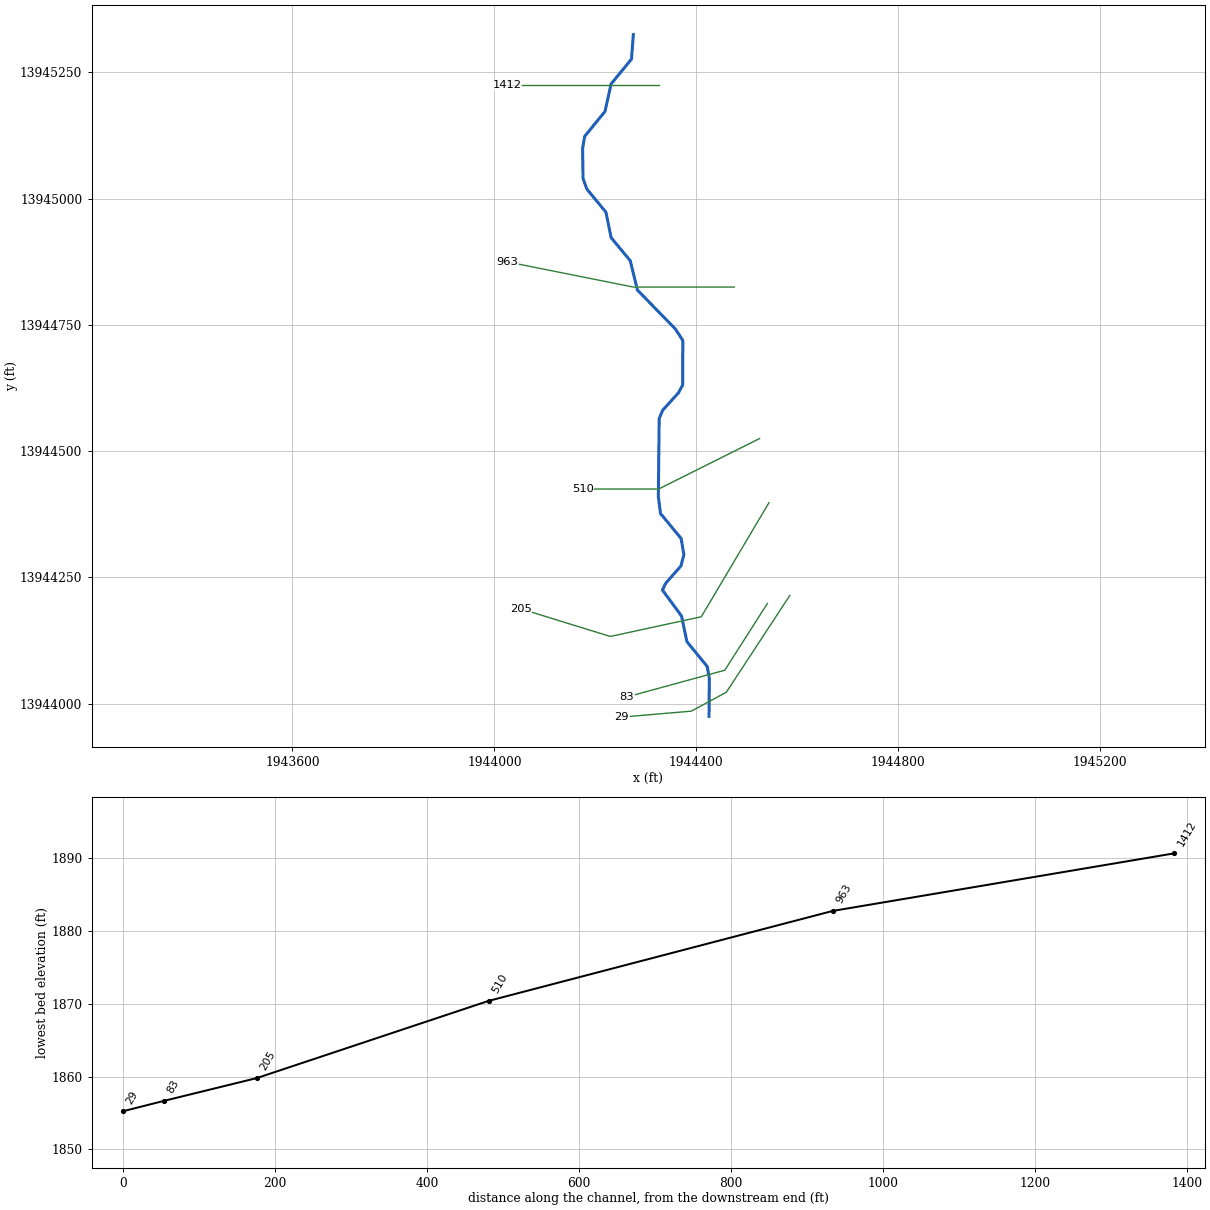
--- Stream0526.prj (project) ---

Proj Title=Stream0526 Base Level Engineering
Current Plan=p01
Default Exp/Contr=0.3,0.1
English Units
Geom File=g01
Flow File=f01
Plan File=p01
BEGIN DESCRIPTION:
Stream0526
END DESCRIPTION:

--- Stream0526.p01 (plan) ---

Plan Title=Multiple Run
Short Identifier=Multiple
Geom File=g01
Flow File=f01
Subcritical Flow
K Sum by GR= 0
Std Step Tol= 0.01
Critical Tol= 0.01
Num of Std Step Trials= 20
Max Error Tol= 0.3
Flow Tol Ratio= 0.001
Split Flow NTrial= 30
Split Flow Tol= 0.02
Split Flow Ratio= 0.02
Log Output Level= 0
Friction Slope Method= 1
Unsteady Friction Slope Method= 2
Unsteady Bridges Friction Slope Method= 1
Parabolic Critical Depth
Global Vel Dist=  1 , 1 , 1
Global Log Level= 0
CheckData=True
Encroach Param= -1, 0, 0, 0
BEGIN DESCRIPTION:
Multiple Run
END DESCRIPTION:

--- Stream0526.f01 (steady flow) ---

Flow Title=Multiple
Number of Profiles=7
Profile Names=10-year,25-year,50-year,1pct_min,100-year,1pct_plu,500-year
River Rch & RM= Stream0526,Reach-1,1412
     649    1072    1465     971    1938    3866    3338
Boundary for River Rch & Prof#=Stream0526,Reach-1,1
Up Type=0
Dn Type=3
Dn Slope=0.005
Boundary for River Rch & Prof#=Stream0526,Reach-1,2
Up Type=0
Dn Type=3
Dn Slope=0.005
Boundary for River Rch & Prof#=Stream0526,Reach-1,3
Up Type=0
Dn Type=3
Dn Slope=0.005
Boundary for River Rch & Prof#=Stream0526,Reach-1,4
Up Type=0
Dn Type=3
Dn Slope=0.005
Boundary for River Rch & Prof#=Stream0526,Reach-1,5
Up Type=0
Dn Type=3
Dn Slope=0.005
Boundary for River Rch & Prof#=Stream0526,Reach-1,6
Up Type=0
Dn Type=3
Dn Slope=0.005
Boundary for River Rch & Prof#=Stream0526,Reach-1,7
Up Type=0
Dn Type=3
Dn Slope=0.005

--- Stream0526.g01 (geometry) ---

Geom Title=Existing Conditions

River Reach=Stream0526,Reach-1
Reach XY= 30
      1944275.00     13945325.00      1944271.40     13945276.49
      1944230.95     13945227.25      1944218.89     13945172.81
      1944178.67     13945123.42      1944174.59     13945100.00
      1944175.37     13945040.27      1944183.04     13945018.95
      1944220.81     13944973.26      1944231.08     13944922.80
      1944268.90     13944877.19      1944283.16     13944818.95
      1944358.56     13944741.74      1944373.03     13944719.11
      1944372.84     13944630.98      1944364.19     13944615.37
      1944333.15     13944581.06      1944326.22     13944564.50
      1944324.57     13944409.82      1944328.81     13944376.55
      1944369.60     13944327.17      1944375.17     13944295.13
      1944369.35     13944272.71      1944339.01     13944238.23
      1944332.56     13944225.00      1944370.58     13944173.36
      1944381.06     13944122.82      1944421.37     13944073.50
      1944425.48     13944050.20      1944425.00     13943975.00

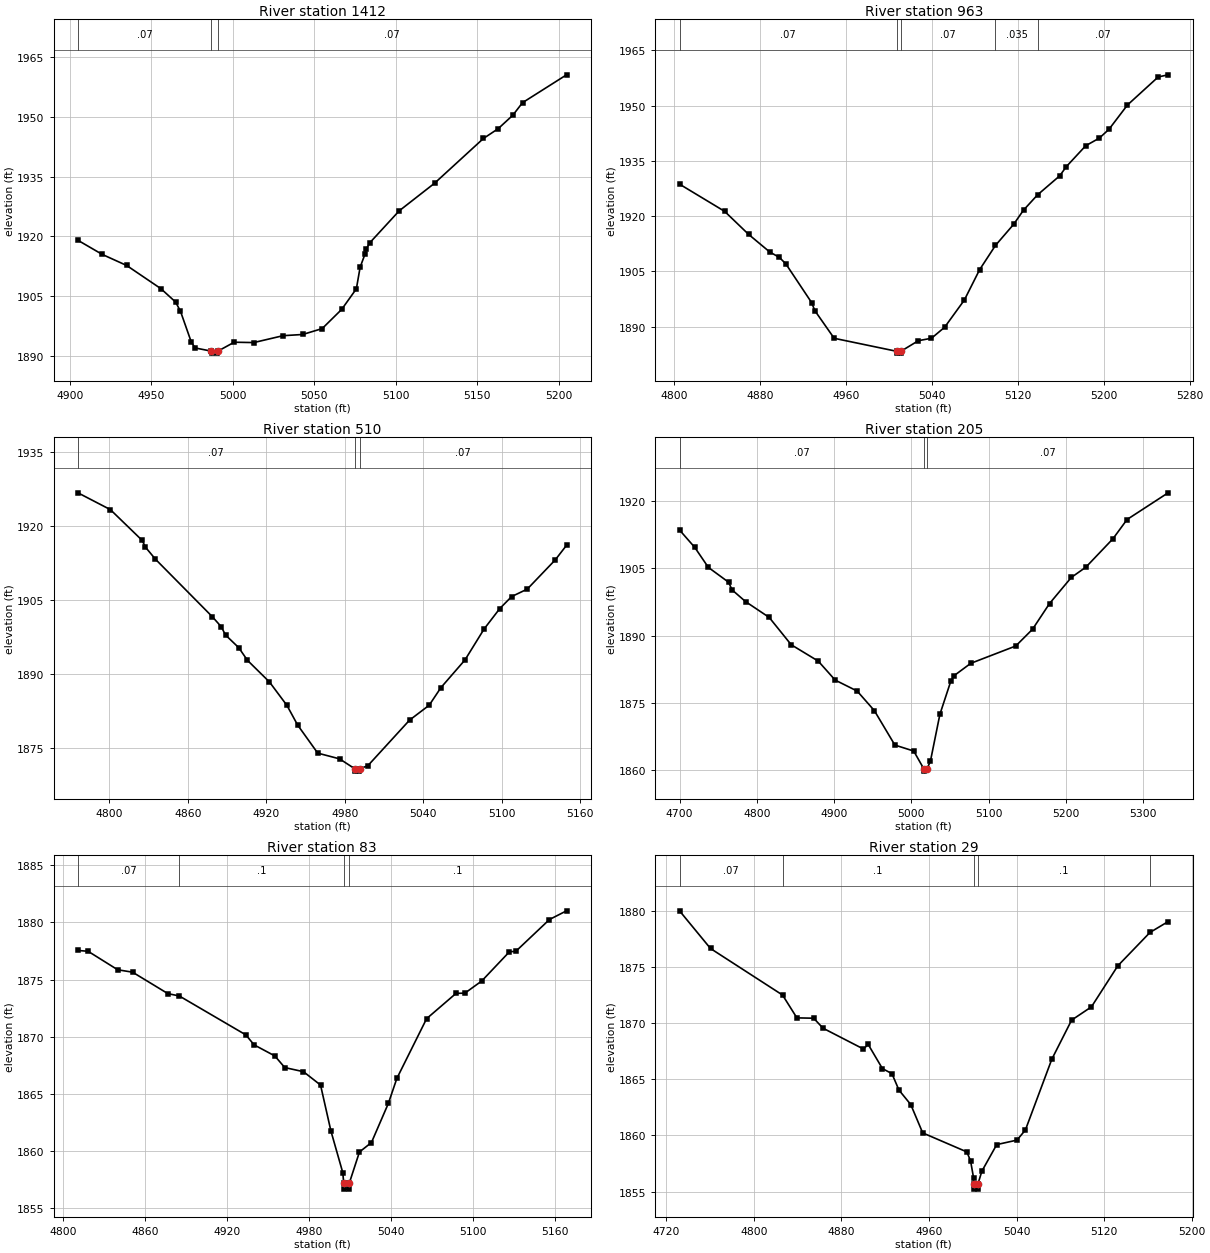
Type RM Length L Ch R = 1,1412,449,449,449
BEGIN DESCRIPTION:
Stream0526 3.0
END DESCRIPTION:
XS GIS Cut Line= 3
      1944324.96     13945225.00      1944225.00     13945225.00
      1944025.06     13945225.00
#Sta/Elev= 30
  4904.9 1919.01  4919.8 1915.47  4934.8 1912.69  4955.8 1906.87  4964.8 1903.52
  4967.8 1901.22  4974.4 1893.53  4976.8 1891.98  4986.8 1891.18  4987.0 1890.68
  4990.5 1890.68  4990.8 1891.18  5000.8 1893.42  5012.8 1893.33  5030.8 1895.06
  5042.8 1895.36  5054.8 1896.84  5066.8 1901.67  5075.8 1906.84  5078.1 1912.25
  5081.1 1915.55  5081.8 1916.80  5084.1 1918.42  5102.1 1926.42  5123.8 1933.35
  5153.8 1944.59  5162.8 1947.03  5171.8 1950.41  5177.8 1953.58  5204.8 1960.57
#Mann=3,-1,0
  4904.9    0.07       0  4986.8    0.05       0  4990.8    0.07       0
Bank Sta=4986.8,4990.8
Exp/Cntr=0.3,0.1

Type RM Length L Ch R = 1,963,453,453,453
BEGIN DESCRIPTION:
Stream0526 2.0
END DESCRIPTION:
XS GIS Cut Line= 3
      1944475.05     13944825.00      1944275.00     13944825.00
      1944025.10     13944874.98
#Sta/Elev= 30
  4804.7 1928.68  4846.7 1921.29  4869.0 1915.04  4888.7 1910.25  4897.7 1908.77
  4903.7 1907.02  4927.7 1896.50  4930.7 1894.31  4948.7 1886.80  5006.8 1883.27
  5007.0 1882.77  5010.5 1882.77  5010.8 1883.27  5027.1 1886.15  5039.3 1886.81
  5051.6 1889.82  5069.9 1897.19  5084.1 1905.43  5098.9 1912.04  5115.8 1917.76
  5125.0 1921.62  5138.1 1925.78  5158.7 1930.94  5164.8 1933.42  5182.9 1939.11
  5195.6 1941.19  5204.6 1943.59  5221.8 1950.19  5250.4 1957.80  5259.6 1958.38
#Mann=5,-1,0
  4804.7    0.07       0  5006.8    0.05       0  5010.8    0.07       0
  5098.9   0.035       0  5138.1    0.07       0
Bank Sta=5006.8,5010.8
Exp/Cntr=0.3,0.1

Type RM Length L Ch R = 1,510,305,305,305
BEGIN DESCRIPTION:
Stream0526 1.0
END DESCRIPTION:
XS GIS Cut Line= 3
      1944524.99     13944524.99      1944325.00     13944425.00
      1944175.09     13944425.00
#Sta/Elev= 30
  4776.0 1926.66  4800.8 1923.26  4825.1 1917.04  4827.6 1915.67  4835.2 1913.25
  4878.8 1901.59  4885.5 1899.60  4888.8 1897.92  4898.9 1895.36  4905.6 1892.79
  4922.4 1888.42  4935.8 1883.67  4943.9 1879.73  4959.3 1874.04  4976.0 1872.88
  4987.5 1870.90  4987.7 1870.40  4991.2 1870.40  4991.5 1870.90  4997.6 1871.49
  5029.5 1880.71  5044.5 1883.72  5053.5 1887.29  5071.9 1892.89  5086.5 1899.14
  5098.5 1903.27  5107.5 1905.68  5119.5 1907.20  5140.9 1913.11  5149.5 1916.05
#Mann=3,-1,0
  4776.0    0.07       0  4987.5    0.05       0  4991.5    0.07       0
Bank Sta=4987.5,4991.5
Exp/Cntr=0.3,0.1

Type RM Length L Ch R = 1,205,122,122,122
BEGIN DESCRIPTION:
Stream0526 0.0
END DESCRIPTION:
XS GIS Cut Line= 4
      1944543.76     13944398.07      1944409.63     13944172.04
      1944229.48     13944133.02      1944052.37     13944187.65
#Sta/Elev= 30
  4699.9 1913.55  4719.7 1909.66  4737.2 1905.22  4763.5 1901.90  4767.8 1900.22
  4785.4 1897.59  4816.0 1894.06  4844.5 1887.97  4879.5 1884.32  4901.4 1880.09
  4929.9 1877.64  4952.1 1873.29  4978.7 1865.60  5003.1 1864.27  5016.2 1860.29
  5016.4 1859.79  5020.2 1860.29  5024.7 1861.98  5037.0 1872.46  5051.0 1879.79
  5055.4 1881.08  5076.9 1883.82  5135.2 1887.69  5156.9 1891.42  5178.9 1897.15
  5207.1 1902.97  5226.0 1905.27  5261.1 1911.61  5279.3 1915.89  5332.4 1921.84
#Mann=3,-1,0
  4699.9    0.07       0  5016.2    0.05       0  5020.2    0.07       0
Bank Sta=5016.2,5020.2
Exp/Cntr=0.3,0.1

Type RM Length L Ch R = 1,83,54,54,54
BEGIN DESCRIPTION:
Stream0526 0.1
END DESCRIPTION:
XS GIS Cut Line= 3
      1944540.52     13944198.37      1944456.18     13944066.16
      1944262.20     13944013.20
#Sta/Elev= 30
  4810.8 1877.55  4818.2 1877.48  4839.9 1875.86  4850.8 1875.65  4876.7 1873.77
  4885.0 1873.57  4933.8 1870.16  4939.8 1869.29  4955.0 1868.32  4962.3 1867.30
  4976.0 1866.94  4988.5 1865.77  4996.1 1861.75  5004.8 1858.10  5005.5 1857.16
  5005.8 1856.66  5009.3 1856.66  5009.5 1857.16  5017.0 1859.91  5025.8 1860.74
  5038.2 1864.17  5044.4 1866.35  5066.2 1871.58  5087.8 1873.80  5094.2 1873.81
  5106.6 1874.88  5126.9 1877.44  5131.5 1877.47  5156.2 1880.26  5168.7 1881.02
#Mann=4,-1,0
  4810.8    0.07       0  4885.0     0.1       0  5005.5    0.05       0
  5009.5     0.1       0
Bank Sta=5005.5,5009.5
Exp/Cntr=0.3,0.1

Type RM Length L Ch R = 1,29,0,0,0
BEGIN DESCRIPTION:
Stream0526 0.2
END DESCRIPTION:
XS GIS Cut Line= 4
      1944584.98     13944214.30      1944459.26     13944022.60
      1944389.82     13943985.10      1944252.30     13943973.29
#Sta/Elev= 30
  4732.2 1879.98  4760.5 1876.63  4826.3 1872.49  4839.4 1870.46  4854.7 1870.43
  4863.3 1869.54  4900.2 1867.69  4904.5 1868.10  4917.5 1865.95  4926.2 1865.50
  4932.6 1864.04  4943.4 1862.75  4954.3 1860.23  4994.6 1858.54  4998.0 1857.75
  5000.7 1856.26  5000.9 1855.73  5001.1 1855.23  5004.6 1855.23  5004.9 1855.73
  5008.3 1856.82  5021.9 1859.19  5040.4 1859.59  5048.1 1860.49  5072.2 1866.78
  5090.3 1870.26  5108.4 1871.44  5132.5 1875.09  5161.9 1878.06  5178.4 1879.02
#Mann=5,-1,0
  4732.2    0.07       0  4826.3     0.1       0  5000.9    0.05       0
  5004.9     0.1       0  5161.9    0.07       0
Bank Sta=5000.9,5004.9
Exp/Cntr=0.3,0.1

Chan Stop Cuts=-1