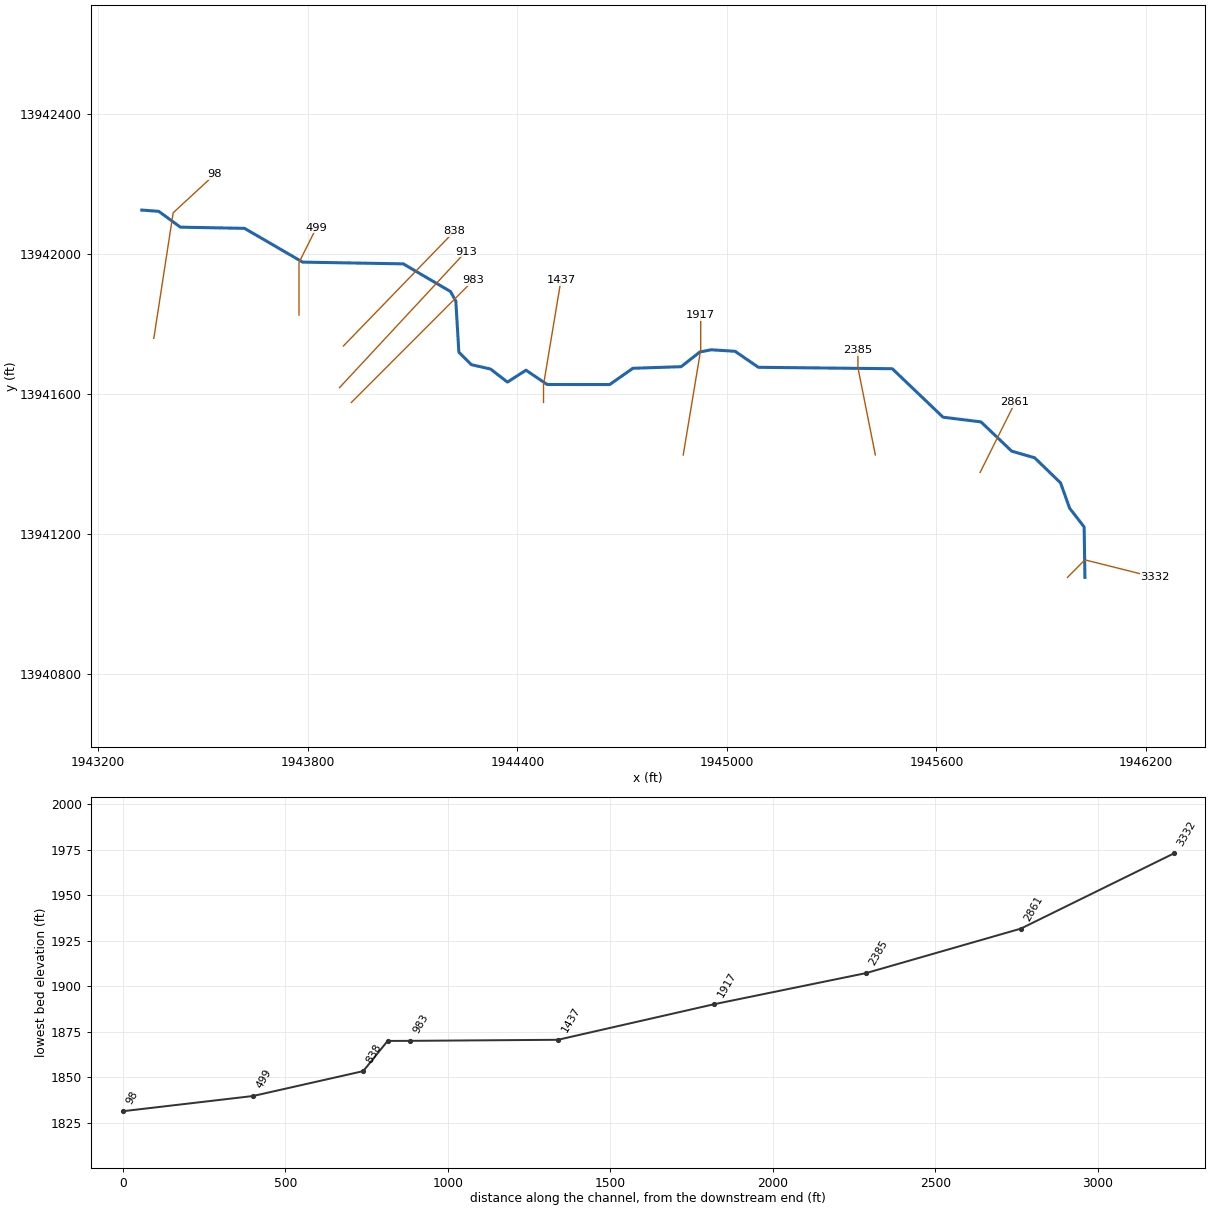
--- Stream0527.prj (project) ---

Proj Title=Stream0527 Base Level Engineering
Current Plan=p01
Default Exp/Contr=0.3,0.1
English Units
Geom File=g01
Flow File=f01
Plan File=p01
Y Axis Title=Elevation
X Axis Title(PF)=Main Channel Distance
X Axis Title(XS)=Station
BEGIN DESCRIPTION:
Stream0527
END DESCRIPTION:
DSS Export Rating Curves= 0
DSS Export Rating Curve Sorted= 0
DSS Export Volume Flow Curves= 0
DXF OffsetX= 0
DXF OffsetY= 0
DXF ScaleX= 1
DXF ScaleY= 10

--- Stream0527.p01 (plan) ---

Plan Title=Multiple Run
Short Identifier=Multiple
Geom File=g01
Flow File=f01
Subcritical Flow
K Sum by GR= 0
Std Step Tol= 0.01
Critical Tol= 0.01
Num of Std Step Trials= 20
Max Error Tol= 0.3
Flow Tol Ratio= 0.001
Split Flow NTrial= 30
Split Flow Tol= 0.02
Split Flow Ratio= 0.02
Log Output Level= 0
Friction Slope Method= 1
Unsteady Friction Slope Method= 2
Unsteady Bridges Friction Slope Method= 1
Parabolic Critical Depth
Global Vel Dist=  1 , 1 , 1
Global Log Level= 0
CheckData=True
Encroach Param= -1, 0, 0, 0
BEGIN DESCRIPTION:
Multiple Run
END DESCRIPTION:

--- Stream0527.f01 (steady flow) ---

Flow Title=Multiple
Program Version=4.10
Number of Profiles= 7
Profile Names=10-year,25-year,50-year,1pct_min,100-year,1pct_plu,500-year
River Rch & RM=Stream0527,Reach-1         ,3332
     489     794    1073     705    1406    2805    2373
Boundary for River Rch & Prof#=Stream0527,Reach-1         , 1
Up Type= 0
Dn Type= 3
Dn Slope=0.01
Boundary for River Rch & Prof#=Stream0527,Reach-1         , 2
Up Type= 0
Dn Type= 3
Dn Slope=0.01
Boundary for River Rch & Prof#=Stream0527,Reach-1         , 3
Up Type= 0
Dn Type= 3
Dn Slope=0.01
Boundary for River Rch & Prof#=Stream0527,Reach-1         , 4
Up Type= 0
Dn Type= 3
Dn Slope=0.01
Boundary for River Rch & Prof#=Stream0527,Reach-1         , 5
Up Type= 0
Dn Type= 3
Dn Slope=0.01
Boundary for River Rch & Prof#=Stream0527,Reach-1         , 6
Up Type= 0
Dn Type= 3
Dn Slope=0.01
Boundary for River Rch & Prof#=Stream0527,Reach-1         , 7
Up Type= 0
Dn Type= 3
Dn Slope=0.01
DSS Import GetInterval= 0
DSS Import GetPeak= 0
DSS Import FillOption= 0

--- Stream0527.g01 (geometry) ---

Geom Title=Existing Conditions
Program Version=4.10

River Reach=Stream0527      ,Reach-1
Reach XY= 30
        1946025.       13941075.      1946022.81     13941219.09
      1945981.14     13941272.83      1945955.23     13941345.13
      1945881.07     13941416.85      1945815.33      13941435.8
      1945727.42     13941519.46      1945618.83     13941532.86
      1945473.54     13941671.46      1945090.22     13941675.52
       1945023.4      13941721.3      1944954.95     13941725.59
      1944922.69     13941719.32      1944869.06     13941677.27
      1944730.94     13941672.73      1944664.49     13941626.22
      1944485.43     13941626.37       1944424.9      13941667.2
      1944371.76     13941633.24      1944323.32     13941670.54
      1944268.62     13941682.98       1944232.7     13941718.52
        1944224.     13941864.71      1944208.72     13941892.14
      1944073.45     13941971.25       1943785.5      13941976.2
      1943619.07     13942072.76      1943435.46     13942076.12
      1943373.49     13942121.35        1943325.       13942125.

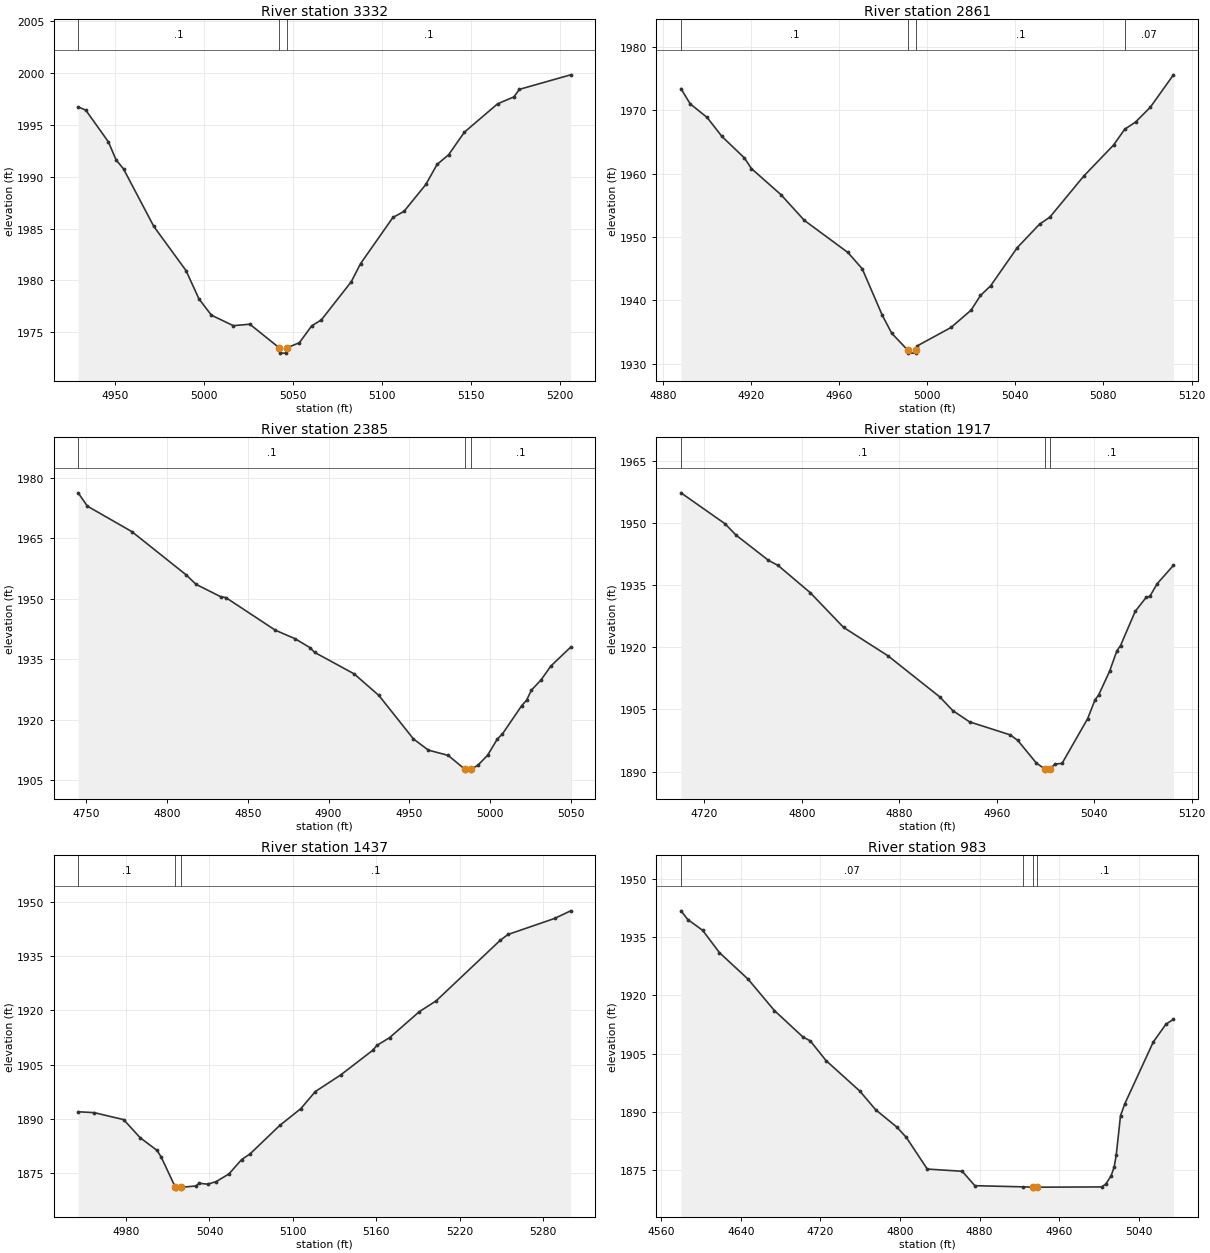
Type RM Length L Ch R = 1 ,3332    ,471,471,471
BEGIN DESCRIPTION:
Stream0527 7.0
END DESCRIPTION:
XS GIS Cut Line= 3
      1945975.03     13941075.03        1946025.       13941125.
      1946224.97     13941075.01
#Sta/Elev= 30
  4929.2 1996.75  4933.5 1996.43  4946.2 1993.37  4950.5 1991.64  4954.7 1990.76
  4971.7 1985.22  4989.8 1980.96  4997.1 1978.22  5004.1 1976.65  5016.4 1975.64
  5025.7 1975.78  5042.3 1973.49  5042.5 1972.99    5046 1972.99  5046.3 1973.49
  5053.5 1973.99  5060.4 1975.61  5065.9  1976.2  5082.7 1979.88  5087.9 1981.62
  5106.1 1986.08  5112.3 1986.66  5124.6 1989.26  5130.9 1991.19  5137.4 1992.13
  5146.3 1994.31  5164.9 1997.04  5174.1 1997.71  5177.2 1998.44    5206 1999.84
#Mann= 3 ,-1 , 0
  4929.2      .1       0  5042.3     .05       0  5046.3      .1       0
Bank Sta=5042.3,5046.3
XS Rating Curve= 0 ,0
Exp/Cntr=0.3,0.1

Type RM Length L Ch R = 1 ,2861    ,476,476,476
BEGIN DESCRIPTION:
Stream0527 6.0
END DESCRIPTION:
XS GIS Cut Line= 3
      1945725.01     13941375.03        1945775.       13941475.
      1945825.01     13941575.02
#Sta/Elev= 30
  4888.2 1973.44  4892.4 1971.03  4900.1 1968.88  4906.8 1965.89    4917 1962.49
  4920.2 1960.81  4933.6 1956.69  4944.2 1952.63    4964 1947.55  4970.5 1944.98
  4979.6 1937.64  4983.9 1934.79  4991.1 1932.15  4991.3 1931.65  4994.8 1931.65
  4995.1 1932.15  4995.3 1932.76  5010.8  1935.7  5019.9 1938.43  5024.2 1940.76
  5028.8 1942.29  5040.9 1948.32    5051 1952.02  5055.7 1953.14  5071.1 1959.63
  5084.6 1964.52  5089.7 1967.03  5094.6 1968.16  5101.3  1970.5  5111.8 1975.62
#Mann= 4 ,-1 , 0
  4888.2      .1       0  4991.1     .05       0  4995.1      .1       0
  5089.7     .07       0
Bank Sta=4991.1,4995.1
XS Rating Curve= 0 ,0
Exp/Cntr=0.3,0.1

Type RM Length L Ch R = 1 ,2385    ,468,468,468
BEGIN DESCRIPTION:
Stream0527 5.0
END DESCRIPTION:
XS GIS Cut Line= 3
      1945424.99     13941425.04        1945375.       13941675.
        1945375.     13941724.99
#Sta/Elev= 30
    4745 1976.21  4750.7 1972.91  4778.3 1966.58  4811.9 1955.86    4818 1953.52
  4833.3 1950.45  4836.4 1950.25    4867 1942.17  4879.2 1940.06  4888.4 1937.86
  4891.4 1936.66  4915.9 1931.32  4931.2 1925.97  4952.6 1915.19  4961.8 1912.43
  4974.1 1911.12  4984.3 1907.72  4984.5 1907.22    4988 1907.22  4988.3 1907.72
  4992.4 1908.65  4998.5 1911.17  5004.6 1915.23  5007.6  1916.4  5019.6 1923.45
  5022.6 1924.78  5025.6 1927.31  5031.5 1929.79  5037.6 1933.25  5049.9 1937.95
#Mann= 3 ,-1 , 0
    4745      .1       0  4984.3     .05       0  4988.3      .1       0
Bank Sta=4984.3,4988.3
XS Rating Curve= 0 ,0
Exp/Cntr=0.3,0.1

Type RM Length L Ch R = 1 ,1917    ,480,480,480
BEGIN DESCRIPTION:
Stream0527 4.0
END DESCRIPTION:
XS GIS Cut Line= 3
      1944875.01     13941425.04        1944925.       13941725.
        1944925.       13941825.
#Sta/Elev= 30
  4700.9 1957.37    4737 1949.91  4746.1 1947.15  4772.7 1941.05  4780.6 1939.82
    4807 1933.23  4834.3 1924.85  4870.8 1917.97  4913.4 1908.01  4923.9 1904.74
  4937.7 1902.01  4971.2 1898.85  4977.3 1897.51  4992.5 1892.06  4999.6  1890.6
  4999.9  1890.1  5003.6  1890.6  5007.7  1891.8  5013.6 1891.97  5034.6 1902.78
  5040.6  1907.3  5043.6 1908.49  5052.6 1914.24  5058.6 1919.19  5061.6 1920.46
  5073.6  1928.7  5082.7 1932.13  5085.6 1932.34  5091.7 1935.42    5105 1939.84
#Mann= 3 ,-1 , 0
  4700.9      .1       0  4999.6     .05       0  5003.6      .1       0
Bank Sta=4999.6,5003.6
XS Rating Curve= 0 ,0
Exp/Cntr=0.3,0.1

Type RM Length L Ch R = 1 ,1437    ,454,454,454
BEGIN DESCRIPTION:
Stream0527 3.0
END DESCRIPTION:
XS GIS Cut Line= 3
        1944475.     13941575.04        1944475.       13941625.
        1944525.       13941925.
#Sta/Elev= 30
  4945.6 1891.98  4957.2 1891.73  4978.3  1889.8  4990.2 1884.79  5002.3 1881.29
  5005.3 1879.45  5015.5 1871.07  5015.8 1870.57  5019.3 1870.57  5019.5 1871.07
  5030.1 1871.44  5032.7 1872.19  5038.8 1871.94  5044.9 1872.67    5054 1874.77
  5063.1 1878.74  5069.2 1880.32  5090.5 1888.18  5105.7 1892.85  5116.1 1897.56
  5134.4 1902.18  5157.4 1908.99  5160.4 1910.34  5169.6 1912.51  5190.9 1919.68
    5203 1922.67  5249.1 1939.44  5254.7 1941.04  5288.2 1945.48  5299.7 1947.58
#Mann= 3 ,-1 , 0
  4945.6      .1       0  5015.5     .05       0  5019.5      .1       0
Bank Sta=5015.5,5019.5
XS Rating Curve= 0 ,0
Exp/Cntr=0.3,0.1

Type RM Length L Ch R = 1 ,983     ,70,70,70
BEGIN DESCRIPTION:
Stream0527 2.0
END DESCRIPTION:
XS GIS Cut Line= 3
      1943924.97     13941574.97        1944225.       13941875.
      1944274.98     13941924.98
#Sta/Elev= 30
  4579.8 1941.85  4586.7  1939.6  4601.6 1936.82  4618.5 1931.05  4647.2 1924.23
  4673.7 1916.11  4702.4 1909.28  4709.8 1908.27  4725.6 1903.19  4759.6  1895.3
  4775.5 1890.49  4796.7 1886.03  4806.2 1883.38  4827.4 1875.17  4862.5  1874.6
  4875.2 1870.88  4923.6 1870.58  4933.7 1870.49    4934 1869.99  4937.7 1870.49
  5002.5 1870.56  5006.7 1871.27  5012.1 1873.41  5015.2 1875.66  5017.3 1878.79
  5021.6 1888.95  5025.8 1891.96  5054.5 1907.97  5067.3 1912.59  5074.8 1913.84
#Mann= 4 ,-1 , 0
  4579.8     .07       0  4923.6      .1       0  4933.7     .05       0
  4937.7      .1       0
Bank Sta=4933.7,4937.7
XS Rating Curve= 0 ,0
Exp/Cntr=0.3,0.1

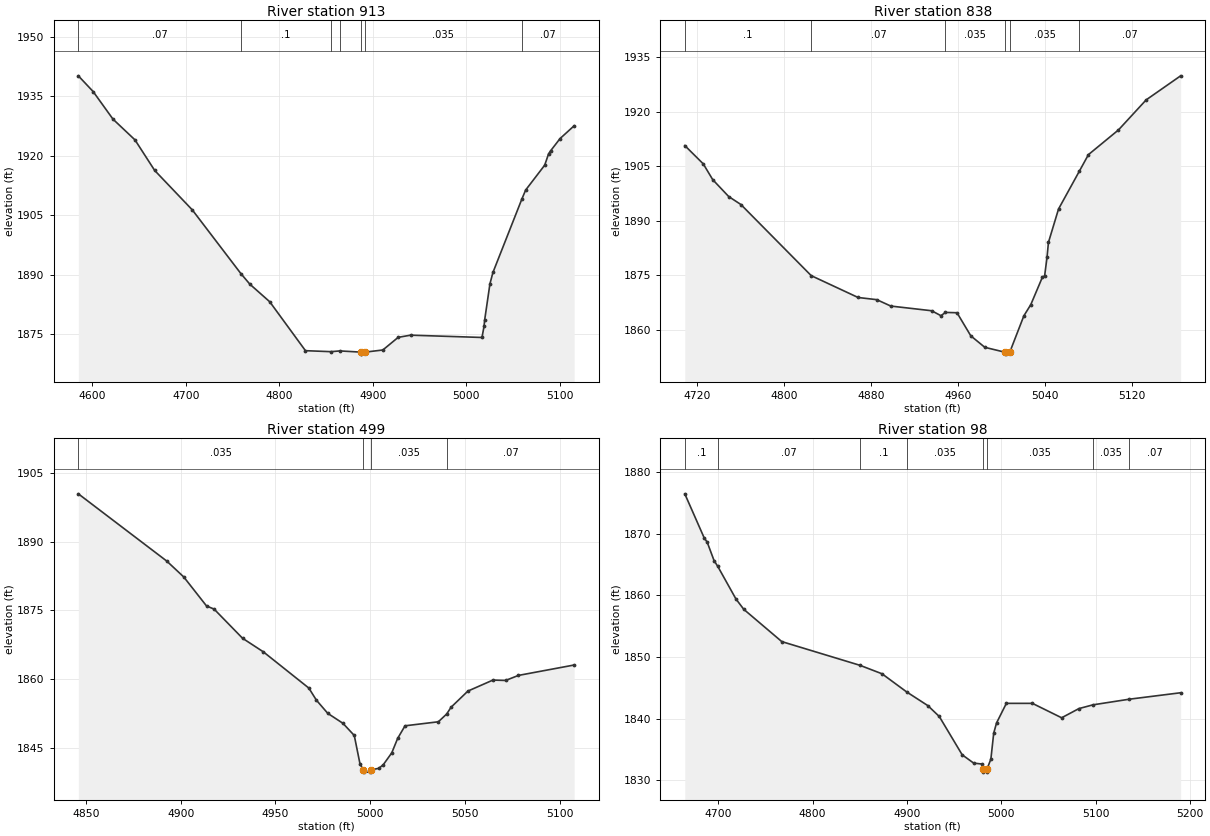
Type RM Length L Ch R = 1 ,913     ,75,75,75
BEGIN DESCRIPTION:
Stream0527 1.1
END DESCRIPTION:
XS GIS Cut Line= 2
      1943890.97     13941617.29      1944252.29     13942005.72
#Sta/Elev= 30
    4585 1940.11  4600.9 1936.13  4622.1 1929.18  4645.6 1923.96  4666.7 1916.25
    4707 1906.29  4758.9 1890.25  4768.5 1887.58  4789.8 1883.14    4828 1870.81
  4855.2 1870.56  4864.9 1870.75  4887.6 1870.44  4887.8 1869.94  4891.6 1870.44
  4910.8 1870.98  4927.2 1874.17  4940.5 1874.72  5016.9 1874.14  5019.1 1876.98
  5019.7 1878.46  5025.4 1887.68  5028.6 1890.53  5059.5 1909.01  5063.6 1911.31
    5084 1917.59  5088.1 1920.42  5090.2 1921.17  5100.4 1924.29  5115.5 1927.52
#Mann= 7 ,-1 , 0
    4585     .07       0  4758.9      .1       0  4855.2     .07       0
  4864.9    .035       0  4887.6    .035       0  4891.6    .035       0
  5059.5     .07       0
Bank Sta=4887.6,4891.6
XS Rating Curve= 0 ,0
Exp/Cntr=0.3,0.1

Type RM Length L Ch R = 1 ,838     ,339,339,339
BEGIN DESCRIPTION:
Mapping XS 51173b16
END DESCRIPTION:
XS GIS Cut Line= 2
      1943902.16     13941736.48       1944219.6     13942063.98
#Sta/Elev= 30
  4708.8 1910.76  4725.8 1905.71  4734.5 1901.37  4749.2 1896.72  4760.4 1894.53
  4825.1 1874.95  4868.2 1868.94  4885.4 1868.34  4898.3 1866.58  4935.9 1865.29
  4944.4 1863.93  4948.6 1864.83  4959.2 1864.74  4971.9 1858.38  4984.8 1855.22
  5003.7 1853.85  5003.9 1853.35  5007.7 1853.85  5020.7 1863.89  5027.1 1866.99
  5037.7 1874.49  5039.8 1874.89    5042 1879.97  5043.3 1884.09  5052.6  1893.3
  5071.8 1903.74  5080.1 1908.26  5107.7 1915.05  5133.2 1923.33  5164.9 1929.95
#Mann= 6 ,-1 , 0
  4708.8      .1       0  4825.1     .07       0  4948.6    .035       0
  5003.7    .035       0  5007.7    .035       0  5071.8     .07       0
Bank Sta=5003.7,5007.7
XS Rating Curve= 0 ,0
Exp/Cntr=0.3,0.1

Type RM Length L Ch R = 1 ,499     ,401,401,401
BEGIN DESCRIPTION:
Stream0527 1.0
END DESCRIPTION:
XS GIS Cut Line= 3
        1943775.     13941824.99        1943775.       13941975.
      1943824.99     13942074.99
#Sta/Elev= 30
  4845.9 1900.42  4892.6 1885.74  4901.6 1882.26  4913.6 1875.94  4917.6 1875.26
  4932.6  1868.9  4943.6 1865.93  4967.6 1858.03  4971.6 1855.39  4977.6 1852.51
  4985.6 1850.34  4991.6 1847.68  4994.6 1841.52  4996.3 1840.18  4996.6 1839.68
  5000.1 1839.68  5000.3 1840.18  5004.5  1840.5  5006.9 1841.29  5011.4 1843.89
  5014.5 1847.04  5018.4 1849.79    5036 1850.67  5040.4 1852.37  5042.7 1853.84
  5051.6 1857.37  5064.8 1859.77  5071.5 1859.69  5078.3 1860.79  5107.7 1863.06
#Mann= 4 ,-1 , 0
  4845.9    .035       0  4996.3    .035       0  5000.3    .035       0
  5040.4     .07       0
Bank Sta=4996.3,5000.3
XS Rating Curve= 0 ,0
Exp/Cntr=0.3,0.1

Type RM Length L Ch R = 1 ,98      ,0,0,0
BEGIN DESCRIPTION:
Stream0527 0.0
END DESCRIPTION:
XS GIS Cut Line= 3
      1943359.32     13941758.09      1943414.81     13942117.33
      1943533.91     13942227.14
#Sta/Elev= 30
  4664.6 1876.47    4685 1869.37  4688.4  1868.6  4695.6 1865.64  4699.6 1864.68
  4718.8 1859.41  4727.1 1857.73  4767.4 1852.49  4850.3 1848.64  4873.6 1847.27
  4899.6 1844.34  4922.2  1842.1  4934.3 1840.34  4958.6 1834.12  4970.8 1832.77
  4979.9 1832.62  4980.9 1831.81  4981.1 1831.31  4984.6 1831.31  4984.9 1831.81
    4989 1833.42    4992 1837.63    4995 1839.29  5005.4 1842.47    5033 1842.47
    5064 1840.13  5082.3 1841.62  5097.2 1842.23  5135.5 1843.14  5190.1 1844.19
#Mann= 8 ,-1 , 0
  4664.6      .1       0  4699.6     .07       0  4850.3      .1       0
  4899.6    .035       0  4980.9    .035       0  4984.9    .035       0
  5097.2    .035       0  5135.5     .07       0
Bank Sta=4980.9,4984.9
XS Rating Curve= 0 ,0
Exp/Cntr=0.3,0.1

Chan Stop Cuts=-1
Use User Specified Reach Order=0
Composite Channel Slope=5