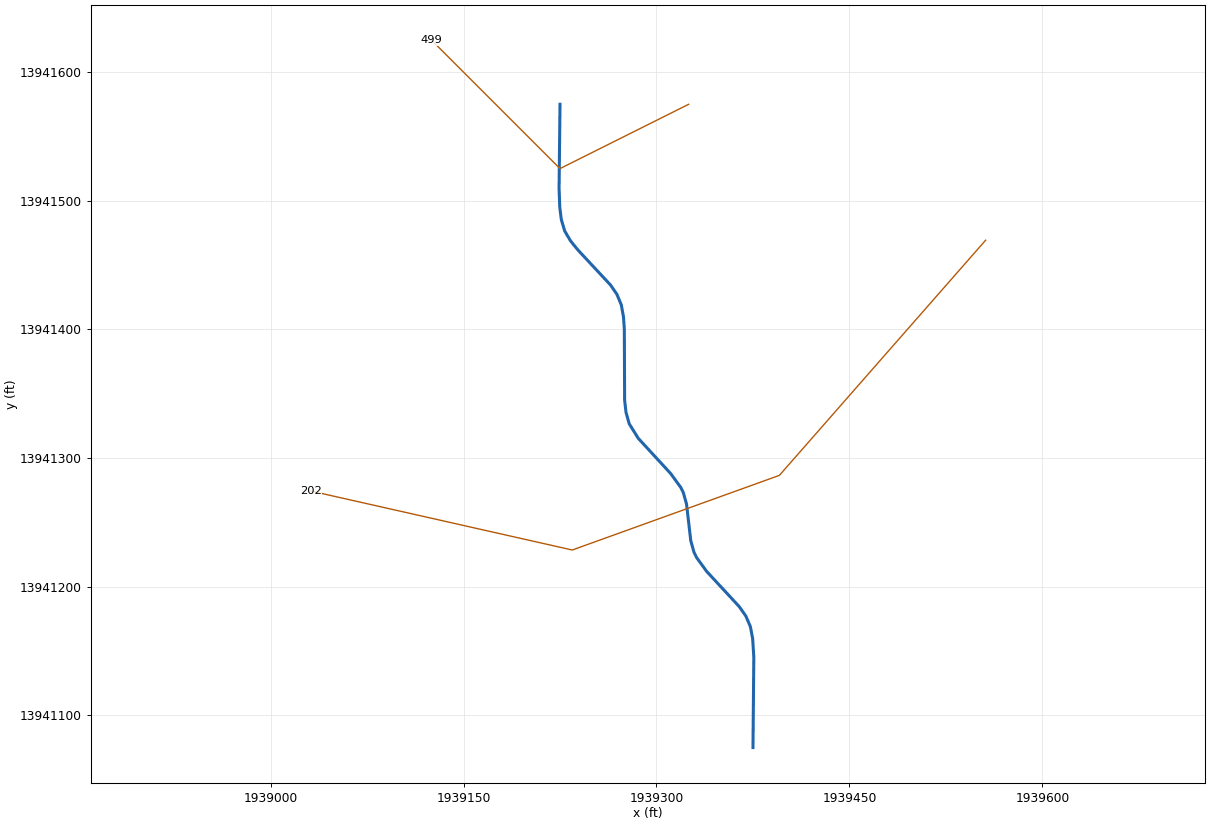
--- Stream0528.prj (project) ---

Proj Title=Stream0528 Base Level Engineering
Current Plan=p01
Default Exp/Contr=0.3,0.1
English Units
Geom File=g01
Flow File=f01
Plan File=p01
BEGIN DESCRIPTION:
Stream0528
END DESCRIPTION:

--- Stream0528.p01 (plan) ---

Plan Title=Multiple Run
Short Identifier=Multiple
Geom File=g01
Flow File=f01
Subcritical Flow
K Sum by GR= 0
Std Step Tol= 0.01
Critical Tol= 0.01
Num of Std Step Trials= 20
Max Error Tol= 0.3
Flow Tol Ratio= 0.001
Split Flow NTrial= 30
Split Flow Tol= 0.02
Split Flow Ratio= 0.02
Log Output Level= 0
Friction Slope Method= 1
Unsteady Friction Slope Method= 2
Unsteady Bridges Friction Slope Method= 1
Parabolic Critical Depth
Global Vel Dist=  1 , 1 , 1
Global Log Level= 0
CheckData=True
Encroach Param= -1, 0, 0, 0
BEGIN DESCRIPTION:
Multiple Run
END DESCRIPTION:

--- Stream0528.f01 (steady flow) ---

Flow Title=Multiple
Number of Profiles=7
Profile Names=10-year,25-year,50-year,1pct_min,100-year,1pct_plu,500-year
River Rch & RM= Stream0528,Reach-1,499
     846    1423    1966    1317    2628    5244    4628
Boundary for River Rch & Prof#=Stream0528,Reach-1,1
Up Type=0
Dn Type=3
Dn Slope=0.005
Boundary for River Rch & Prof#=Stream0528,Reach-1,2
Up Type=0
Dn Type=3
Dn Slope=0.005
Boundary for River Rch & Prof#=Stream0528,Reach-1,3
Up Type=0
Dn Type=3
Dn Slope=0.005
Boundary for River Rch & Prof#=Stream0528,Reach-1,4
Up Type=0
Dn Type=3
Dn Slope=0.005
Boundary for River Rch & Prof#=Stream0528,Reach-1,5
Up Type=0
Dn Type=3
Dn Slope=0.005
Boundary for River Rch & Prof#=Stream0528,Reach-1,6
Up Type=0
Dn Type=3
Dn Slope=0.005
Boundary for River Rch & Prof#=Stream0528,Reach-1,7
Up Type=0
Dn Type=3
Dn Slope=0.005

--- Stream0528.g01 (geometry) ---

Geom Title=Existing Conditions

River Reach=Stream0528,Reach-1
Reach XY= 30
      1939225.00     13941575.00      1939224.29     13941509.71
      1939224.82     13941494.92      1939226.02     13941485.42
      1939228.66     13941476.52      1939233.11     13941468.93
      1939238.82     13941461.87      1939264.16     13941434.65
      1939269.23     13941427.32      1939272.67     13941419.03
      1939274.35     13941409.73      1939275.00     13941400.00
      1939275.23     13941345.09      1939276.31     13941335.54
      1939278.83     13941326.58      1939285.84     13941315.35
      1939310.97     13941288.04      1939318.89     13941277.18
      1939320.82     13941273.27      1939323.33     13941264.31
      1939326.66     13941235.69      1939329.17     13941226.73
      1939331.09     13941222.81      1939338.99     13941211.94
      1939364.21     13941184.67      1939369.37     13941177.38
      1939372.93     13941169.14      1939374.73     13941159.89
      1939375.64     13941145.27      1939375.00     13941075.00

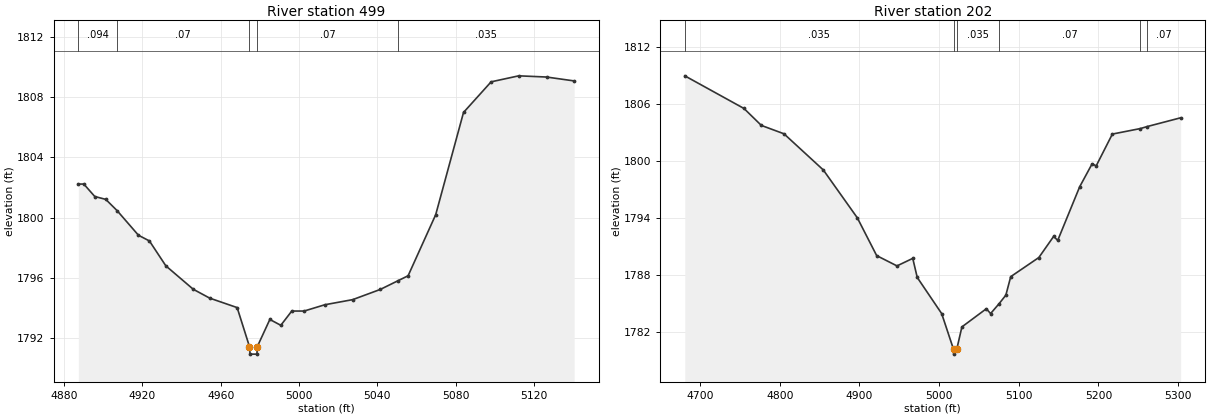
Type RM Length L Ch R = 1,499,297,297,297
BEGIN DESCRIPTION:
Stream0528 1.0
END DESCRIPTION:
XS GIS Cut Line= 3
      1939325.00     13941575.00      1939225.00     13941525.00
      1939125.01     13941624.99
#Sta/Elev= 30
  4887.3 1802.23  4890.1 1802.23  4895.7 1801.40  4901.3 1801.21  4907.1 1800.46
  4918.0 1798.82  4923.6 1798.44  4932.0 1796.78  4946.0 1795.22  4954.4 1794.63
  4968.4 1794.00  4974.7 1791.40  4975.0 1790.90  4978.5 1790.90  4978.7 1791.40
  4985.1 1793.21  4990.7 1792.82  4996.3 1793.77  5002.6 1793.77  5013.2 1794.19
  5027.4 1794.53  5041.5 1795.21  5050.7 1795.80  5055.7 1796.12  5069.8 1800.19
  5084.0 1807.00  5098.1 1809.04  5112.2 1809.44  5126.4 1809.36  5140.5 1809.10
#Mann=5,-1,0
  4887.3   0.094       0  4907.1    0.07       0  4974.7    0.05       0
  4978.7    0.07       0  5050.7   0.035       0
Bank Sta=4974.7,4978.7
Exp/Cntr=0.3,0.1

Type RM Length L Ch R = 1,202,0,0,0
BEGIN DESCRIPTION:
Stream0528 0.0
END DESCRIPTION:
XS GIS Cut Line= 4
      1939555.84     13941469.38      1939395.50     13941286.56
      1939234.52     13941228.56      1939031.41     13941274.40
#Sta/Elev= 30
  4680.7 1808.96  4755.0 1805.53  4776.8 1803.75  4805.2 1802.87  4854.6 1799.07
  4897.3 1794.04  4921.6 1790.07  4947.1 1788.99  4966.9 1789.78  4972.5 1787.78
  5003.2 1783.98  5018.1 1780.22  5018.3 1779.72  5022.1 1780.22  5028.6 1782.58
  5059.3 1784.49  5064.6 1783.98  5075.2 1785.01  5083.8 1785.92  5089.9 1787.86
  5125.2 1789.87  5143.8 1792.09  5148.9 1791.67  5176.5 1797.31  5192.1 1799.72
  5197.2 1799.50  5217.5 1802.84  5252.7 1803.42  5261.2 1803.63  5303.2 1804.55
#Mann=6,-1,0
  4680.7   0.035       0  5018.1   0.035       0  5022.1   0.035       0
  5075.2    0.07       0  5252.7   0.035       0  5261.2    0.07       0
Bank Sta=5018.1,5022.1
Exp/Cntr=0.3,0.1

Chan Stop Cuts=-1