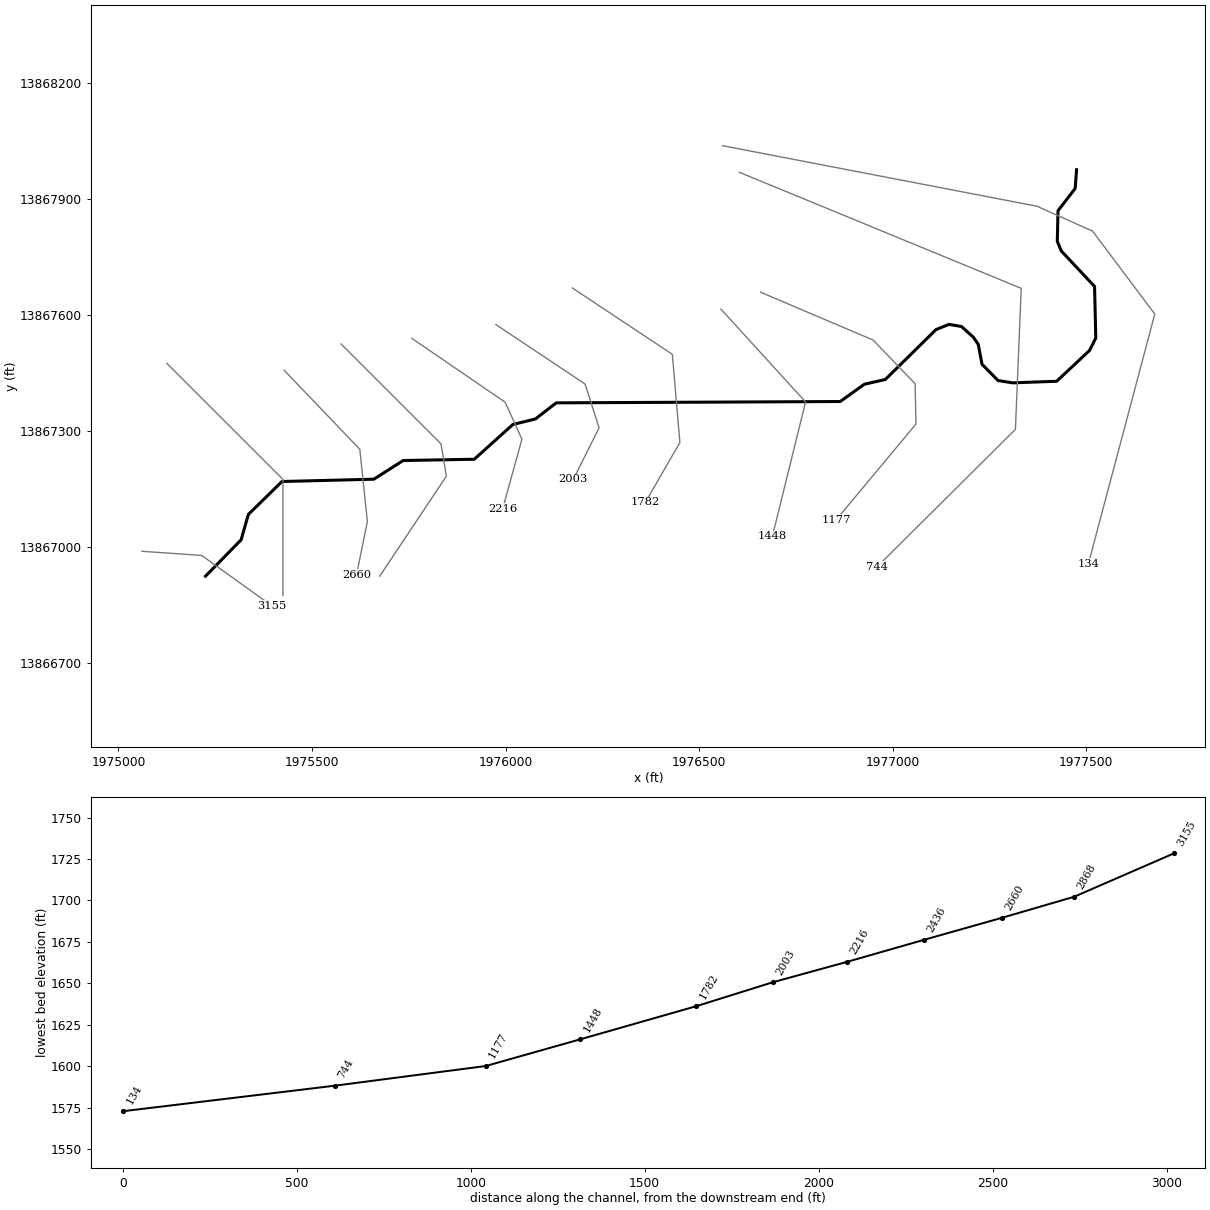
--- Stream0531.prj (project) ---

Proj Title=Stream0531 Base Level Engineering
Current Plan=p01
Default Exp/Contr=0.3,0.1
English Units
Geom File=g01
Flow File=f01
Plan File=p01
BEGIN DESCRIPTION:
Stream0531
END DESCRIPTION:

--- Stream0531.p01 (plan) ---

Plan Title=Multiple Run
Short Identifier=Multiple
Geom File=g01
Flow File=f01
Subcritical Flow
K Sum by GR= 0
Std Step Tol= 0.01
Critical Tol= 0.01
Num of Std Step Trials= 20
Max Error Tol= 0.3
Flow Tol Ratio= 0.001
Split Flow NTrial= 30
Split Flow Tol= 0.02
Split Flow Ratio= 0.02
Log Output Level= 0
Friction Slope Method= 1
Unsteady Friction Slope Method= 2
Unsteady Bridges Friction Slope Method= 1
Parabolic Critical Depth
Global Vel Dist=  1 , 1 , 1
Global Log Level= 0
CheckData=True
Encroach Param= -1, 0, 0, 0
BEGIN DESCRIPTION:
Multiple Run
END DESCRIPTION:

--- Stream0531.f01 (steady flow) ---

Flow Title=Multiple
Number of Profiles=7
Profile Names=10-year,25-year,50-year,1pct_min,100-year,1pct_plu,500-year
River Rch & RM= Stream0531,Reach-1,3155
     257     400     527     339     677    1351    1098
Boundary for River Rch & Prof#=Stream0531,Reach-1,1
Up Type=0
Dn Type=3
Dn Slope=0.005
Boundary for River Rch & Prof#=Stream0531,Reach-1,2
Up Type=0
Dn Type=3
Dn Slope=0.005
Boundary for River Rch & Prof#=Stream0531,Reach-1,3
Up Type=0
Dn Type=3
Dn Slope=0.005
Boundary for River Rch & Prof#=Stream0531,Reach-1,4
Up Type=0
Dn Type=3
Dn Slope=0.005
Boundary for River Rch & Prof#=Stream0531,Reach-1,5
Up Type=0
Dn Type=3
Dn Slope=0.005
Boundary for River Rch & Prof#=Stream0531,Reach-1,6
Up Type=0
Dn Type=3
Dn Slope=0.005
Boundary for River Rch & Prof#=Stream0531,Reach-1,7
Up Type=0
Dn Type=3
Dn Slope=0.005

--- Stream0531.g01 (geometry) ---

Geom Title=Existing Conditions

River Reach=Stream0531,Reach-1
Reach XY= 30
      1975225.00     13866925.00      1975316.89     13867018.93
      1975335.76     13867084.70      1975422.53     13867169.55
      1975659.78     13867175.52      1975735.51     13867223.78
      1975919.14     13867227.07      1976018.95     13867316.84
      1976077.17     13867331.14      1976130.93     13867372.76
      1976864.50     13867376.20      1976926.75     13867420.78
      1976981.06     13867433.14      1977111.80     13867561.89
      1977145.23     13867575.50      1977177.54     13867570.04
      1977208.50     13867542.21      1977221.10     13867523.60
      1977230.75     13867472.45      1977272.30     13867430.35
      1977309.76     13867424.44      1977423.54     13867428.52
      1977508.59     13867508.20      1977524.64     13867540.16
      1977521.46     13867673.53      1977435.46     13867765.22
      1977425.24     13867790.22      1977427.02     13867869.08
      1977471.35     13867926.51      1977475.00     13867975.00

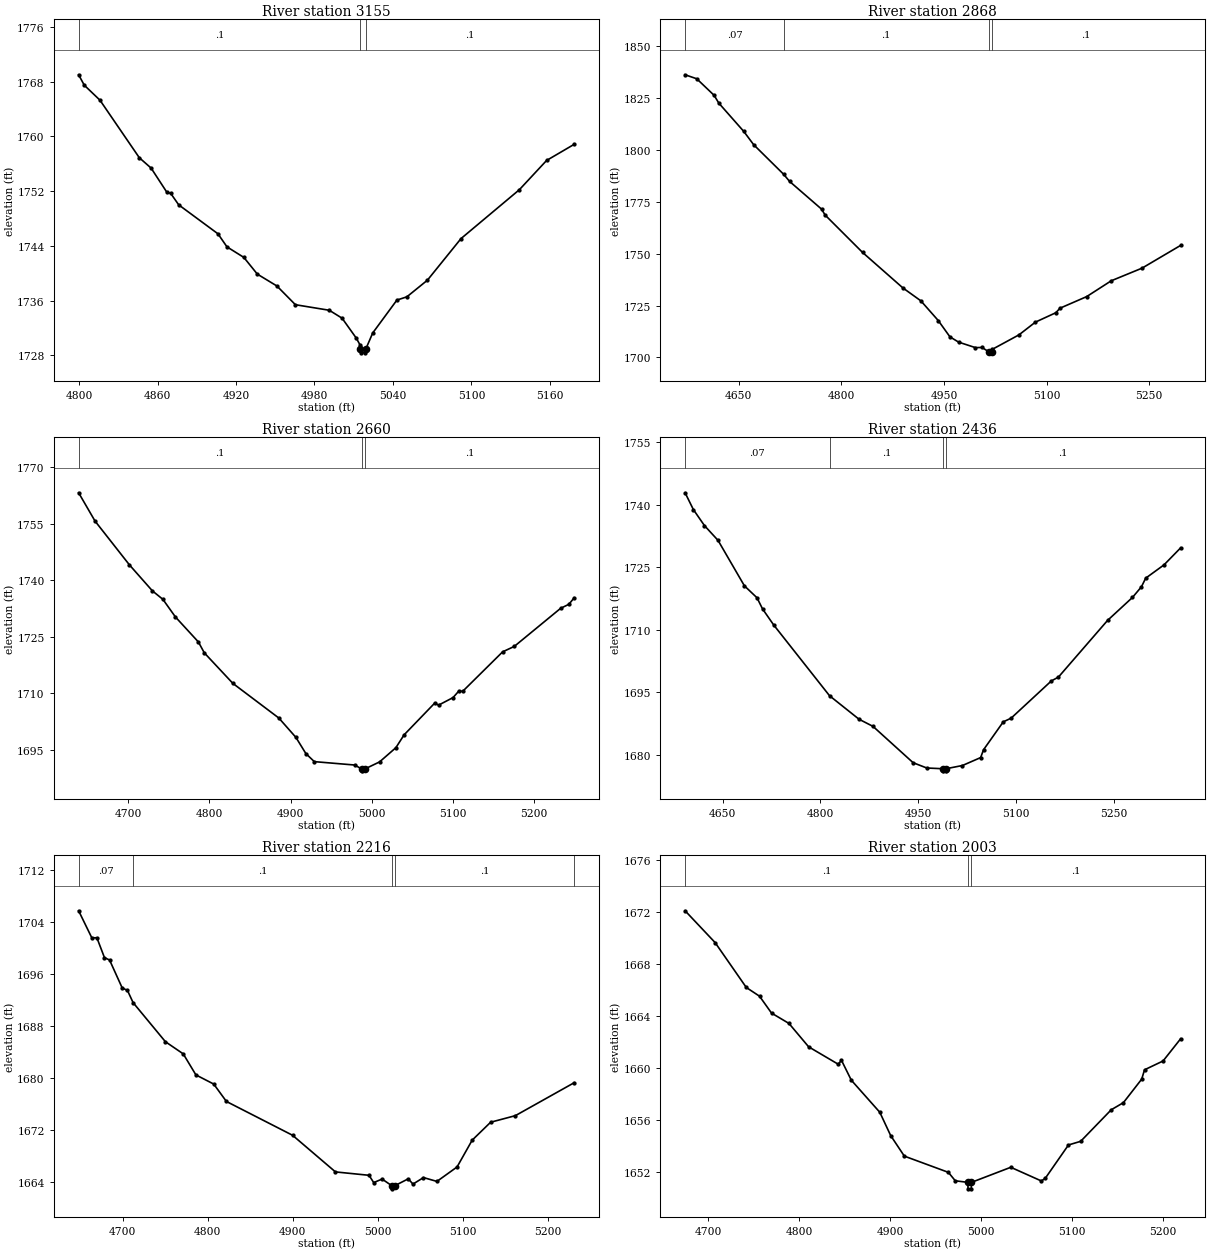
Type RM Length L Ch R = 1,3155,287,287,287
BEGIN DESCRIPTION:
Stream0531 6.0
END DESCRIPTION:
XS GIS Cut Line= 3
      1975060.74     13866989.30      1975214.97     13866978.59
      1975397.11     13866847.88
#Sta/Elev= 30
  4799.7 1769.00  4804.0 1767.48  4816.0 1765.29  4846.1 1756.88  4855.1 1755.37
  4867.1 1751.85  4870.1 1751.67  4876.2 1750.00  4906.2 1745.77  4913.1 1743.86
  4926.0 1742.32  4936.3 1739.88  4951.3 1738.14  4965.4 1735.41  4991.3 1734.60
  5001.1 1733.44  5011.9 1730.54  5014.8 1729.54  5015.1 1728.88  5015.4 1728.38
  5018.9 1728.38  5019.1 1728.88  5024.5 1731.28  5043.0 1736.09  5050.6 1736.56
  5066.3 1738.99  5092.0 1745.07  5136.6 1752.21  5157.4 1756.48  5178.5 1758.84
#Mann=3,-1,0
  4799.7     0.1       0  5015.1    0.05       0  5019.1     0.1       0
Bank Sta=5015.1,5019.1
Exp/Cntr=0.3,0.1

Type RM Length L Ch R = 1,2868,208,208,208
BEGIN DESCRIPTION:
Stream0531 5.0
END DESCRIPTION:
XS GIS Cut Line= 3
      1975125.01     13867474.99      1975425.00     13867175.00
      1975425.00     13866874.96
#Sta/Elev= 30
  4571.5 1836.24  4588.5 1834.32  4613.9 1826.34  4620.8 1822.57  4657.3 1808.92
  4671.7 1802.54  4715.8 1788.18  4724.2 1784.84  4770.9 1771.49  4776.1 1768.64
  4830.8 1750.62  4889.7 1733.52  4916.1 1727.26  4941.6 1717.73  4958.6 1709.90
  4971.3 1707.35  4995.8 1704.71  5005.5 1704.78  5015.4 1702.69  5015.7 1702.19
  5019.4 1702.69  5020.5 1703.88  5059.5 1710.86  5083.5 1716.99  5113.4 1721.53
  5119.4 1723.70  5158.4 1729.29  5194.4 1736.93  5239.4 1743.02  5295.8 1753.99
#Mann=4,-1,0
  4571.5    0.07       0  4715.8     0.1       0  5015.4    0.05       0
  5019.4     0.1       0
Bank Sta=5015.4,5019.4
Exp/Cntr=0.3,0.1

Type RM Length L Ch R = 1,2660,224,224,224
BEGIN DESCRIPTION:
Stream05331 A
END DESCRIPTION:
XS GIS Cut Line= 4
      1975428.22     13867456.83      1975623.52     13867252.85
      1975643.05     13867066.22      1975615.11     13866928.67
#Sta/Elev= 30
  4638.9 1763.19  4659.1 1755.69  4701.5 1744.07  4729.8 1737.18  4742.7 1734.94
  4758.1 1730.28  4786.4 1723.65  4793.7 1720.76  4828.9 1712.66  4885.5 1703.48
  4906.6 1698.33  4918.8 1694.06  4929.2 1691.92  4979.0 1691.02  4987.5 1689.98
  4987.8 1689.48  4991.5 1689.98  5009.6 1691.85  5029.7 1695.62  5039.8 1699.02
  5077.3 1707.39  5082.4 1706.91  5100.1 1708.90  5107.0 1710.58  5112.1 1710.58
  5161.2 1721.03  5175.5 1722.46  5232.6 1732.56  5242.8 1733.63  5249.3 1735.35
#Mann=3,-1,0
  4638.9     0.1       0  4987.5    0.05       0  4991.5     0.1       0
Bank Sta=4987.5,4991.5
Exp/Cntr=0.3,0.1

Type RM Length L Ch R = 1,2436,220,220,220
BEGIN DESCRIPTION:
Stream0531 4.0
END DESCRIPTION:
XS GIS Cut Line= 4
      1975575.01     13867524.99      1975833.36     13867266.64
      1975847.03     13867183.05      1975675.00     13866925.00
#Sta/Elev= 30
  4592.3 1742.88  4605.0 1738.85  4622.0 1735.01  4642.8 1731.47  4683.3 1720.56
  4702.6 1717.70  4711.1 1715.03  4728.1 1711.20  4813.9 1694.20  4859.1 1688.57
  4880.6 1686.85  4942.1 1678.14  4963.1 1676.87  4988.4 1676.69  4988.7 1676.19
  4992.2 1676.19  4992.4 1676.69  5017.8 1677.47  5045.7 1679.37  5050.1 1681.24
  5080.4 1687.94  5092.5 1688.83  5154.2 1697.76  5165.0 1698.67  5240.4 1712.27
  5278.6 1717.78  5292.4 1720.34  5298.9 1722.40  5327.0 1725.59  5352.5 1729.67
#Mann=4,-1,0
  4592.3    0.07       0  4813.9     0.1       0  4988.4    0.05       0
  4992.4     0.1       0
Bank Sta=4988.4,4992.4
Exp/Cntr=0.3,0.1

Type RM Length L Ch R = 1,2216,213,213,213
BEGIN DESCRIPTION:
Stream05331 B
END DESCRIPTION:
XS GIS Cut Line= 4
      1975758.08     13867539.30      1975998.95     13867374.38
      1976042.35     13867278.89      1975992.60     13867099.37
#Sta/Elev= 30
  4648.0 1705.68  4663.5 1701.53  4669.5 1701.53  4678.4 1698.48  4684.4 1698.12
  4699.3 1693.82  4705.4 1693.46  4712.1 1691.57  4750.1 1685.57  4771.1 1683.70
  4786.0 1680.47  4807.0 1679.06  4821.9 1676.39  4899.7 1671.20  4950.2 1665.57
  4989.7 1665.05  4995.2 1663.93  5005.1 1664.47  5016.3 1663.47  5016.5 1662.97
  5020.3 1663.47  5035.9 1664.51  5041.4 1663.70  5053.8 1664.70  5069.6 1664.11
  5093.3 1666.33  5111.1 1670.45  5132.8 1673.20  5161.9 1674.21  5231.1 1679.27
#Mann=5,-1,0
  4648.0    0.07       0  4712.1     0.1       0  5016.3    0.05       0
  5020.3     0.1       0  5231.1   0.035       0
Bank Sta=5016.3,5020.3
Exp/Cntr=0.3,0.1

Type RM Length L Ch R = 1,2003,221,221,221
BEGIN DESCRIPTION:
Stream0531 3.0
END DESCRIPTION:
XS GIS Cut Line= 4
      1975974.98     13867575.01      1976205.55     13867421.30
      1976241.59     13867308.19      1976175.01     13867175.03
#Sta/Elev= 30
  4674.4 1672.10  4707.4 1669.65  4741.7 1666.19  4756.2 1665.52  4769.4 1664.22
  4788.6 1663.42  4810.2 1661.62  4842.7 1660.28  4846.3 1660.58  4857.1 1659.05
  4888.4 1656.58  4900.4 1654.78  4915.4 1653.20  4963.8 1651.95  4971.4 1651.30
  4985.2 1651.18  4985.4 1650.68  4988.9 1650.68  4989.2 1651.18  5032.4 1652.34
  5065.9 1651.29  5070.2 1651.48  5095.8 1654.06  5109.2 1654.34  5142.8 1656.77
  5156.2 1657.32  5176.3 1659.13  5179.4 1659.85  5199.8 1660.53  5219.1 1662.24
#Mann=3,-1,0
  4674.4     0.1       0  4985.2    0.05       0  4989.2     0.1       0
Bank Sta=4985.2,4989.2
Exp/Cntr=0.3,0.1

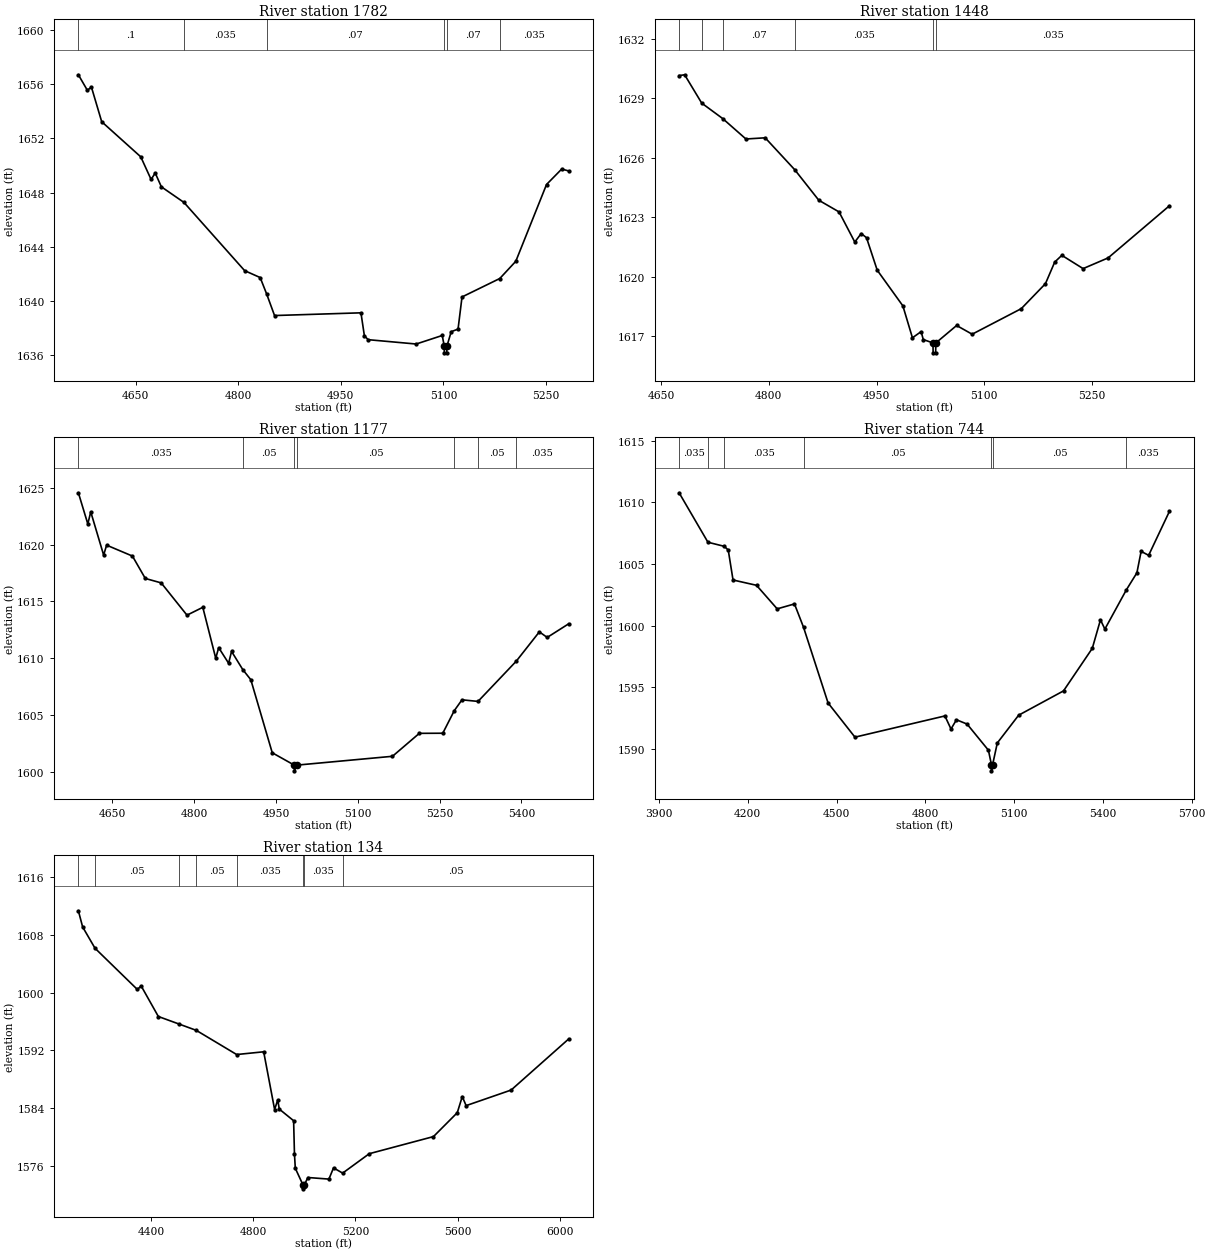
Type RM Length L Ch R = 1,1782,334,334,334
BEGIN DESCRIPTION:
Stream05331 C
END DESCRIPTION:
XS GIS Cut Line= 4
      1976172.56     13867669.52      1976430.81     13867498.08
      1976450.34     13867270.21      1976361.36     13867116.13
#Sta/Elev= 30
  4566.5 1656.68  4579.6 1655.54  4585.6 1655.77  4600.6 1653.22  4657.7 1650.63
  4672.8 1648.96  4678.8 1649.44  4687.8 1648.42  4720.8 1647.27  4809.5 1642.24
  4832.2 1641.73  4841.6 1640.53  4853.2 1638.93  4979.5 1639.13  4984.5 1637.44
  4990.0 1637.15  5060.2 1636.83  5098.3 1637.46  5101.2 1636.68  5101.4 1636.18
  5104.9 1636.18  5105.2 1636.68  5111.4 1637.74  5121.4 1637.93  5127.2 1640.30
  5182.4 1641.66  5205.8 1642.93  5250.7 1648.59  5272.9 1649.73  5283.1 1649.59
#Mann=6,-1,0
  4566.5     0.1       0  4720.8   0.035       0  4841.6    0.07       0
  5101.2    0.05       0  5105.2    0.07       0  5182.4   0.035       0
Bank Sta=5101.2,5105.2
Exp/Cntr=0.3,0.1

Type RM Length L Ch R = 1,1448,271,271,271
BEGIN DESCRIPTION:
Stream0531 2.0
END DESCRIPTION:
XS GIS Cut Line= 3
      1976556.31     13867615.02      1976775.00     13867375.00
      1976689.18     13867027.85
#Sta/Elev= 30
  4675.2 1630.15  4682.9 1630.19  4706.7 1628.76  4735.9 1627.98  4768.2 1626.95
  4795.0 1627.01  4836.1 1625.40  4869.6 1623.86  4897.8 1623.27  4919.7 1621.75
  4928.6 1622.18  4936.0 1621.97  4950.9 1620.33  4986.6 1618.53  4999.9 1616.92
  5012.0 1617.23  5015.0 1616.83  5028.5 1616.66  5028.7 1616.16  5032.2 1616.16
  5032.5 1616.66  5061.4 1617.54  5083.0 1617.10  5151.4 1618.39  5185.0 1619.65
  5197.9 1620.74  5207.8 1621.08  5237.4 1620.41  5272.2 1620.95  5357.5 1623.58
#Mann=6,-1,0
  4675.2    0.07       0  4706.7   0.035       0  4735.9    0.07       0
  4836.1   0.035       0  5028.5   0.035       0  5032.5   0.035       0
Bank Sta=5028.5,5032.5
Exp/Cntr=0.3,0.1

Type RM Length L Ch R = 1,1177,433,433,433
BEGIN DESCRIPTION:
Stream05331 D
END DESCRIPTION:
XS GIS Cut Line= 5
      1976658.63     13867658.69      1976949.47     13867534.97
      1977057.98     13867422.12      1977060.15     13867317.96
      1976854.01     13867070.59
#Sta/Elev= 30
  4587.8 1624.56  4605.1 1621.82  4610.5 1622.88  4634.1 1619.08  4639.6 1619.95
  4686.9 1618.99  4710.5 1617.02  4739.6 1616.63  4786.9 1613.79  4815.9 1614.48
  4839.6 1610.00  4845.0 1610.93  4863.2 1609.56  4868.6 1610.60  4889.3 1608.99
  4903.9 1608.11  4943.2 1601.68  4983.7 1600.59  4983.9 1600.09  4987.7 1600.59
  5163.6 1601.37  5212.8 1603.39  5255.8 1603.40  5276.8 1605.38  5291.0 1606.34
  5320.4 1606.20  5390.5 1609.74  5432.8 1612.32  5447.2 1611.83  5486.6 1613.03
#Mann=7,-1,0
  4587.8   0.035       0  4889.3    0.05       0  4983.7    0.05       0
  4987.7    0.05       0  5276.8   0.035       0  5320.4    0.05       0
  5390.5   0.035       0
Bank Sta=4983.7,4987.7
Exp/Cntr=0.3,0.1

Type RM Length L Ch R = 1,744,610,610,610
BEGIN DESCRIPTION:
Stream0531 1.0
END DESCRIPTION:
XS GIS Cut Line= 4
      1976603.45     13867968.56      1977332.02     13867668.56
      1977317.02     13867304.29      1976959.21     13866948.63
#Sta/Elev= 30
  3967.8 1610.78  4065.3 1606.77  4120.3 1606.44  4133.9 1606.14  4150.1 1603.71
  4229.4 1603.28  4299.3 1601.37  4357.7 1601.77  4388.3 1599.88  4471.3 1593.74
  4562.1 1590.97  4866.1 1592.69  4886.7 1591.63  4905.1 1592.38  4941.1 1592.03
  5013.2 1589.91  5023.3 1588.74  5023.5 1588.24  5027.3 1588.74  5043.2 1590.50
  5115.3 1592.75  5266.9 1594.72  5364.2 1598.17  5391.8 1600.48  5406.7 1599.73
  5479.5 1602.92  5514.9 1604.29  5529.2 1606.03  5554.6 1605.71  5624.8 1609.27
#Mann=7,-1,0
  3967.8   0.035       0  4065.3    0.05       0  4120.3   0.035       0
  4388.3    0.05       0  5023.3    0.05       0  5027.3    0.05       0
  5479.5   0.035       0
Bank Sta=5023.3,5027.3
Exp/Cntr=0.3,0.1

Type RM Length L Ch R = 1,134,0,0,0
BEGIN DESCRIPTION:
Stream0531 0.0
END DESCRIPTION:
XS GIS Cut Line= 5
      1976560.60     13868037.12      1977372.73     13867880.70
      1977516.30     13867816.41      1977677.00     13867602.14
      1977505.58     13866957.14
#Sta/Elev= 30
  4115.6 1611.34  4132.3 1609.10  4180.7 1606.15  4346.4 1600.44  4361.5 1600.92
  4428.7 1596.69  4509.4 1595.65  4577.2 1594.77  4735.3 1591.42  4841.1 1591.80
  4883.9 1583.80  4896.1 1585.13  4902.2 1583.86  4958.3 1582.25  4961.6 1577.63
  4964.9 1575.66  4995.5 1573.31  4995.7 1572.81  4999.5 1573.31  5014.2 1574.38
  5096.4 1574.16  5114.5 1575.71  5150.3 1574.99  5254.5 1577.68  5505.8 1580.05
  5599.0 1583.36  5618.6 1585.60  5633.6 1584.34  5809.9 1586.50  6035.2 1593.58
#Mann=8,-1,0
  4115.6   0.035       0  4180.7    0.05       0  4509.4   0.035       0
  4577.2    0.05       0  4735.3   0.035       0  4995.5   0.035       0
  4999.5   0.035       0  5150.3    0.05       0
Bank Sta=4995.5,4999.5
Exp/Cntr=0.3,0.1

Chan Stop Cuts=-1