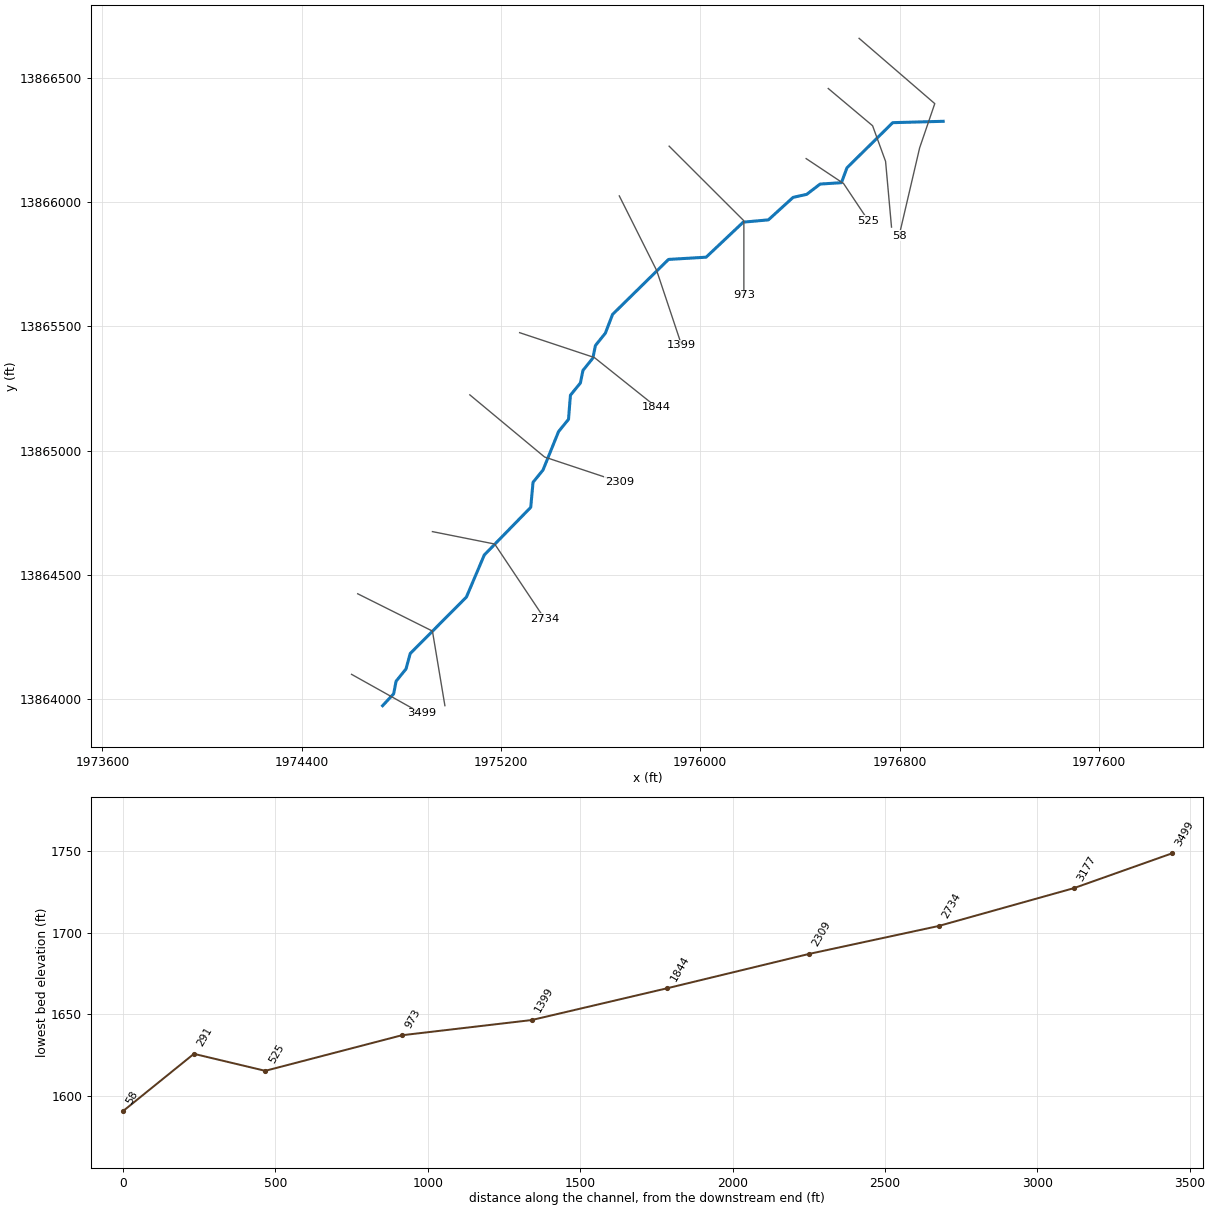
--- Stream0532.prj (project) ---

Proj Title=Stream0532 Base Level Engineering
Current Plan=p01
Default Exp/Contr=0.3,0.1
English Units
Geom File=g01
Flow File=f01
Plan File=p01
BEGIN DESCRIPTION:
Stream0532
END DESCRIPTION:

--- Stream0532.p01 (plan) ---

Plan Title=Multiple Run
Short Identifier=Multiple
Geom File=g01
Flow File=f01
Subcritical Flow
K Sum by GR= 0
Std Step Tol= 0.01
Critical Tol= 0.01
Num of Std Step Trials= 20
Max Error Tol= 0.3
Flow Tol Ratio= 0.001
Split Flow NTrial= 30
Split Flow Tol= 0.02
Split Flow Ratio= 0.02
Log Output Level= 0
Friction Slope Method= 1
Unsteady Friction Slope Method= 2
Unsteady Bridges Friction Slope Method= 1
Parabolic Critical Depth
Global Vel Dist=  1 , 1 , 1
Global Log Level= 0
CheckData=True
Encroach Param= -1, 0, 0, 0
BEGIN DESCRIPTION:
Multiple Run
END DESCRIPTION:

--- Stream0532.f01 (steady flow) ---

Flow Title=Multiple
Number of Profiles=7
Profile Names=10-year,25-year,50-year,1pct_min,100-year,1pct_plu,500-year
River Rch & RM= Stream0532,Reach-1,3499
     129     191     242     151     301     601     456
River Rch & RM= Stream0532,Reach-1,2734
     505     831    1132     753    1502    2996    2604
Boundary for River Rch & Prof#=Stream0532,Reach-1,1
Up Type=0
Dn Type=3
Dn Slope=0.005
Boundary for River Rch & Prof#=Stream0532,Reach-1,2
Up Type=0
Dn Type=3
Dn Slope=0.005
Boundary for River Rch & Prof#=Stream0532,Reach-1,3
Up Type=0
Dn Type=3
Dn Slope=0.005
Boundary for River Rch & Prof#=Stream0532,Reach-1,4
Up Type=0
Dn Type=3
Dn Slope=0.005
Boundary for River Rch & Prof#=Stream0532,Reach-1,5
Up Type=0
Dn Type=3
Dn Slope=0.005
Boundary for River Rch & Prof#=Stream0532,Reach-1,6
Up Type=0
Dn Type=3
Dn Slope=0.005
Boundary for River Rch & Prof#=Stream0532,Reach-1,7
Up Type=0
Dn Type=3
Dn Slope=0.005

--- Stream0532.g01 (geometry) ---

Geom Title=Existing Conditions

River Reach=Stream0532,Reach-1
Reach XY= 30
      1974725.00     13863975.00      1974769.33     13864022.64
      1974779.04     13864073.33      1974818.90     13864122.81
      1974835.76     13864184.68      1975061.38     13864411.79
      1975133.14     13864581.06      1975319.48     13864772.57
      1975328.83     13864873.41      1975368.88     13864922.82
      1975431.12     13865077.18      1975471.17     13865126.58
      1975478.83     13865223.42      1975518.88     13865272.82
      1975529.16     13865323.28      1975568.92     13865372.80
      1975579.16     13865423.28      1975618.90     13865472.81
      1975648.01     13865548.47      1975872.55     13865769.53
      1976023.53     13865778.54      1976172.57     13865919.48
      1976273.50     13865928.63      1976372.71     13866019.15
      1976427.17     13866031.14      1976481.05     13866072.63
      1976566.66     13866078.16      1976588.74     13866137.95
      1976772.55     13866319.54      1976975.00     13866325.00

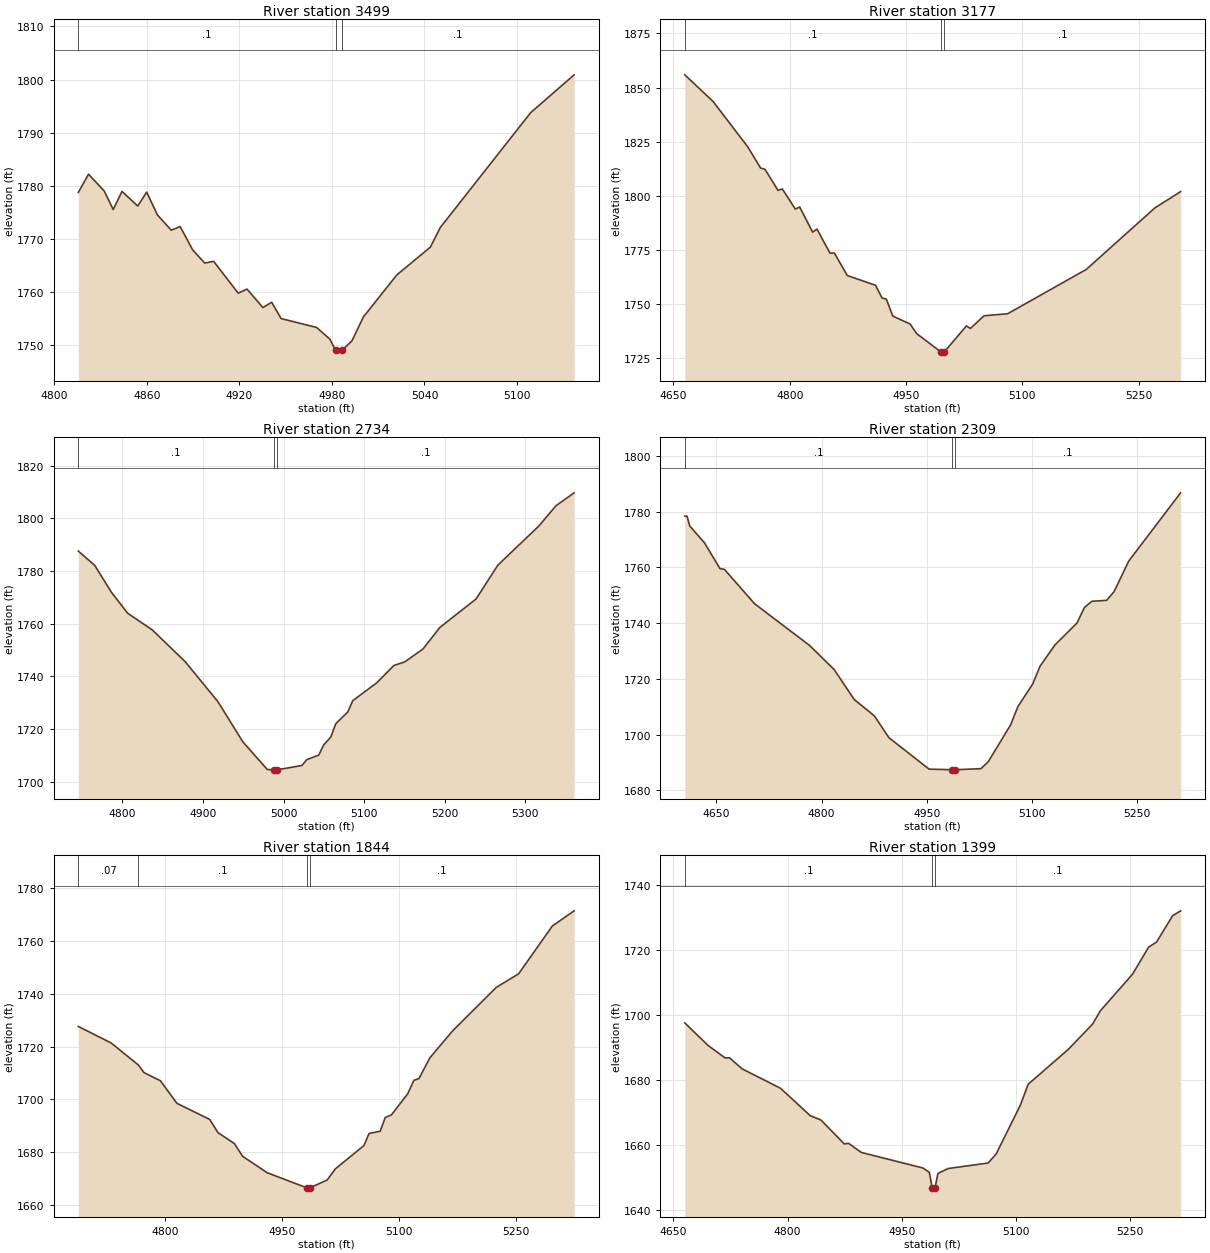
Type RM Length L Ch R = 1,3499,322,322,322
BEGIN DESCRIPTION:
Stream0532 8.0
END DESCRIPTION:
XS GIS Cut Line= 2
      1974600.32     13864101.04      1974880.66     13863944.05
#Sta/Elev= 30
  4815.7 1778.77  4822.3 1782.21  4832.5 1779.04  4838.3 1775.56  4844.0 1778.97
  4854.2 1776.22  4860.0 1778.84  4866.9 1774.56  4875.9 1771.68  4881.7 1772.36
  4889.8 1767.97  4897.6 1765.50  4903.4 1765.82  4919.3 1759.83  4925.0 1760.60
  4935.3 1757.13  4941.0 1758.12  4947.1 1755.06  4970.1 1753.39  4978.7 1751.19
  4982.4 1749.06  4982.7 1748.56  4986.4 1749.06  4993.0 1750.86  5000.4 1755.35
  5022.1 1763.27  5043.8 1768.48  5050.3 1772.20  5108.8 1793.77  5137.0 1800.89
#Mann=3,-1,0
  4815.7     0.1       0  4982.4    0.05       0  4986.4     0.1       0
Bank Sta=4982.4,4986.4
Exp/Cntr=0.3,0.1

Type RM Length L Ch R = 1,3177,443,443,443
BEGIN DESCRIPTION:
Stream0532 7.0
END DESCRIPTION:
XS GIS Cut Line= 3
      1974624.99     13864425.01      1974925.00     13864275.00
      1974975.01     13863974.96
#Sta/Elev= 30
  4664.6 1855.86  4701.0 1843.59  4745.7 1822.63  4762.4 1812.77  4768.0 1812.21
  4784.8 1802.47  4790.4 1803.11  4807.2 1793.80  4812.8 1794.76  4829.5 1783.14
  4835.1 1784.56  4851.9 1773.43  4857.5 1773.51  4874.2 1763.11  4910.6 1758.58
  4919.0 1752.74  4924.6 1752.16  4932.9 1744.34  4955.3 1740.66  4963.7 1736.24
  4995.2 1727.72  4995.5 1727.22  4999.2 1727.72  5027.9 1739.81  5033.0 1738.63
  5050.7 1744.50  5081.1 1745.42  5182.5 1765.91  5271.2 1794.40  5304.2 1801.88
#Mann=3,-1,0
  4664.6     0.1       0  4995.2    0.05       0  4999.2     0.1       0
Bank Sta=4995.2,4999.2
Exp/Cntr=0.3,0.1

Type RM Length L Ch R = 1,2734,425,425,425
BEGIN DESCRIPTION:
Stream0532 6.0
END DESCRIPTION:
XS GIS Cut Line= 3
      1974925.00     13864675.00      1975175.00     13864625.00
      1975374.99     13864325.01
#Sta/Elev= 30
  4745.3 1787.60  4765.7 1782.17  4786.1 1772.10  4806.5 1764.01  4837.1 1757.68
  4877.9 1745.63  4918.7 1730.39  4949.3 1715.26  4979.9 1704.65  4988.1 1704.55
  4988.3 1704.05  4992.1 1704.55  5022.8 1706.18  5028.8 1708.39  5043.8 1710.15
  5049.8 1713.96  5058.8 1717.03  5064.9 1722.07  5079.9 1726.53  5085.9 1730.78
  5115.9 1737.62  5137.0 1744.17  5150.5 1745.54  5173.0 1750.38  5194.1 1758.61
  5239.1 1769.45  5266.2 1782.31  5317.2 1797.20  5338.3 1804.86  5360.8 1809.73
#Mann=3,-1,0
  4745.3     0.1       0  4988.1    0.05       0  4992.1     0.1       0
Bank Sta=4988.1,4992.1
Exp/Cntr=0.3,0.1

Type RM Length L Ch R = 1,2309,465,465,465
BEGIN DESCRIPTION:
Stream0532 5.0
END DESCRIPTION:
XS GIS Cut Line= 3
      1975075.03     13865224.97      1975375.00     13864975.00
      1975675.00     13864875.00
#Sta/Elev= 30
  4605.0 1778.38  4608.2 1778.38  4612.1 1774.83  4632.9 1768.86  4655.1 1759.59
  4661.6 1759.26  4704.5 1746.96  4782.6 1732.05  4817.8 1723.38  4846.4 1712.64
  4875.1 1706.77  4895.9 1698.93  4953.2 1687.64  4986.3 1687.43  4986.6 1686.93
  4990.3 1687.43  5027.1 1687.81  5037.6 1690.33  5069.3 1703.48  5079.8 1710.08
  5100.9 1718.19  5111.4 1724.58  5132.5 1732.16  5164.1 1740.08  5174.7 1745.66
  5185.2 1747.84  5206.3 1748.19  5216.8 1751.28  5237.9 1762.33  5311.7 1786.74
#Mann=3,-1,0
  4605.0     0.1       0  4986.3    0.05       0  4990.3     0.1       0
Bank Sta=4986.3,4990.3
Exp/Cntr=0.3,0.1

Type RM Length L Ch R = 1,1844,445,445,445
BEGIN DESCRIPTION:
Stream0532 4.0
END DESCRIPTION:
XS GIS Cut Line= 3
      1975274.99     13865475.00      1975575.00     13865375.00
      1975825.01     13865174.99
#Sta/Elev= 30
  4688.3 1727.64  4730.5 1721.35  4765.4 1713.00  4772.6 1710.11  4793.7 1707.02
  4814.8 1698.47  4857.0 1692.33  4867.5 1687.35  4888.6 1683.20  4899.1 1678.39
  4930.7 1672.12  4981.5 1666.40  4981.7 1665.90  4985.5 1666.40  5007.7 1669.36
  5018.1 1673.57  5055.0 1682.46  5061.4 1687.01  5075.8 1687.89  5082.2 1693.08
  5090.2 1694.09  5111.0 1702.02  5119.0 1707.21  5125.4 1707.83  5139.8 1715.85
  5168.6 1725.92  5224.6 1742.42  5253.5 1747.63  5296.7 1765.75  5324.7 1771.51
#Mann=4,-1,0
  4688.3    0.07       0  4765.4     0.1       0  4981.5    0.05       0
  4985.5     0.1       0
Bank Sta=4981.5,4985.5
Exp/Cntr=0.3,0.1

Type RM Length L Ch R = 1,1399,426,426,426
BEGIN DESCRIPTION:
Stream0532 3.0
END DESCRIPTION:
XS GIS Cut Line= 3
      1975675.01     13866024.98      1975825.00     13865725.00
      1975924.99     13865425.02
#Sta/Elev= 30
  4664.9 1697.46  4695.6 1690.52  4718.0 1686.68  4723.6 1686.76  4740.4 1683.32
  4790.7 1677.38  4829.8 1668.94  4843.8 1667.63  4874.5 1660.27  4880.1 1660.46
  4896.9 1657.65  4977.9 1652.87  4986.3 1651.52  4989.9 1646.88  4990.2 1646.38
  4993.9 1646.88  4997.5 1651.17  5010.8 1652.71  5063.5 1654.40  5074.1 1657.20
  5105.7 1672.09  5116.2 1678.62  5168.9 1689.33  5200.6 1697.04  5211.1 1701.21
  5253.3 1712.43  5274.4 1720.74  5284.9 1722.31  5306.0 1730.41  5316.5 1731.91
#Mann=3,-1,0
  4664.9     0.1       0  4989.9    0.05       0  4993.9     0.1       0
Bank Sta=4989.9,4993.9
Exp/Cntr=0.3,0.1

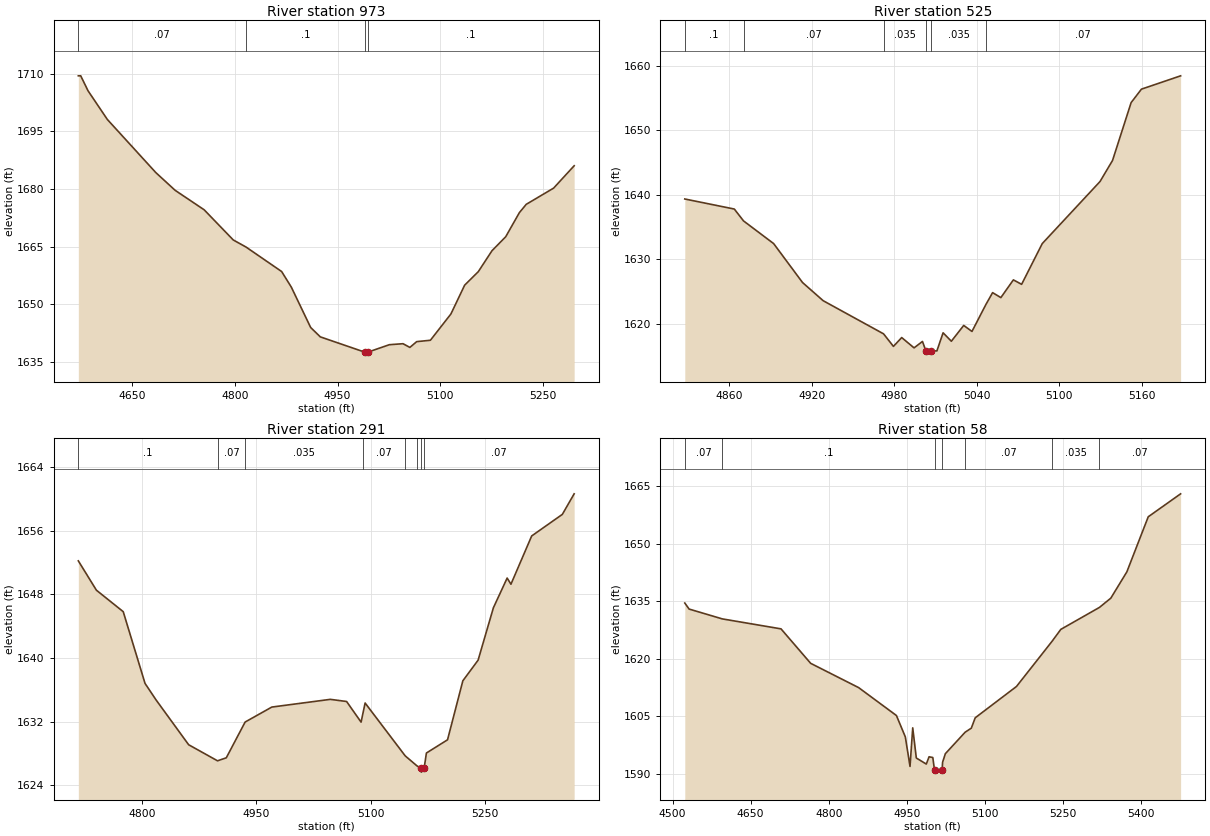
Type RM Length L Ch R = 1,973,448,448,448
BEGIN DESCRIPTION:
Stream0532 2.0
END DESCRIPTION:
XS GIS Cut Line= 3
      1975875.01     13866224.99      1976175.00     13865925.00
      1976175.00     13865624.96
#Sta/Elev= 30
  4571.4 1709.49  4574.9 1709.49  4585.5 1705.62  4613.8 1698.13  4684.5 1684.32
  4712.8 1679.69  4755.2 1674.62  4797.7 1666.77  4816.4 1664.92  4868.4 1658.55
  4882.5 1654.50  4910.8 1643.98  4924.9 1641.54  4990.1 1637.55  4990.4 1637.05
  4994.1 1637.55  5025.7 1639.50  5045.7 1639.76  5055.7 1638.80  5065.7 1640.30
  5085.7 1640.66  5115.7 1647.51  5135.7 1654.99  5155.7 1658.52  5175.7 1663.97
  5195.7 1667.60  5215.7 1673.88  5225.7 1676.04  5265.7 1680.26  5295.7 1686.08
#Mann=4,-1,0
  4571.4    0.07       0  4816.4     0.1       0  4990.1    0.05       0
  4994.1     0.1       0
Bank Sta=4990.1,4994.1
Exp/Cntr=0.3,0.1

Type RM Length L Ch R = 1,525,234,234,234
BEGIN DESCRIPTION:
Stream0532 1.0
END DESCRIPTION:
XS GIS Cut Line= 3
      1976425.01     13866174.99      1976575.00     13866075.00
      1976674.98     13865925.03
#Sta/Elev= 30
  4827.7 1639.32  4863.7 1637.76  4870.4 1635.92  4892.3 1632.40  4913.3 1626.36
  4928.3 1623.54  4972.2 1618.40  4979.4 1616.45  4985.4 1617.82  4994.4 1616.22
  5000.5 1617.22  5003.0 1615.75  5003.2 1615.25  5007.0 1615.75  5011.0 1615.75
  5015.5 1618.56  5021.5 1617.25  5030.5 1619.70  5036.5 1618.77  5046.6 1622.94
  5051.5 1624.79  5057.5 1624.02  5066.6 1626.77  5072.6 1626.08  5087.6 1632.40
  5129.6 1642.03  5138.7 1645.30  5152.2 1654.27  5159.7 1656.36  5188.2 1658.43
#Mann=6,-1,0
  4827.7     0.1       0  4870.4    0.07       0  4972.2   0.035       0
  5003.0   0.035       0  5007.0   0.035       0  5046.6    0.07       0
Bank Sta=5003,5007
Exp/Cntr=0.3,0.1

Type RM Length L Ch R = 1,291,233,233,233
BEGIN DESCRIPTION:
Stream0532 0.0
END DESCRIPTION:
XS GIS Cut Line= 4
      1976513.74     13866456.86      1976691.71     13866307.10
      1976743.80     13866163.87      1976767.63     13865899.55
#Sta/Elev= 30
  4716.5 1652.19  4740.2 1648.51  4775.4 1645.81  4804.0 1636.80  4818.3 1634.75
  4861.2 1629.10  4899.1 1627.08  4910.6 1627.46  4935.3 1631.95  4970.3 1633.83
  5047.1 1634.80  5068.4 1634.53  5087.4 1631.94  5089.9 1633.07  5092.7 1634.34
  5145.3 1627.70  5160.8 1626.44  5166.1 1626.16  5166.4 1625.66  5170.1 1626.16
  5173.1 1628.06  5200.8 1629.72  5220.9 1637.13  5240.9 1639.72  5261.0 1646.31
  5279.0 1650.03  5284.0 1649.26  5311.2 1655.32  5351.4 1658.03  5366.9 1660.61
#Mann=8,-1,0
  4716.5     0.1       0  4899.1    0.07       0  4935.3   0.035       0
  5089.9    0.07       0  5145.3   0.035       0  5160.8    0.07       0
  5166.1   0.035       0  5170.1    0.07       0
Bank Sta=5166.1,5170.1
Exp/Cntr=0.3,0.1

Type RM Length L Ch R = 1,58,0,0,0
BEGIN DESCRIPTION:
Stream0532 0.1
END DESCRIPTION:
XS GIS Cut Line= 4
      1976637.49     13866658.64      1976941.28     13866396.08
      1976880.51     13866218.13      1976798.05     13865864.39
#Sta/Elev= 30
  4523.4 1634.53  4531.7 1632.96  4595.5 1630.40  4708.3 1627.80  4765.3 1618.82
  4857.5 1612.49  4930.1 1605.22  4947.2 1599.64  4956.2 1591.96  4961.4 1602.01
  4968.3 1594.15  4987.5 1592.57  4992.8 1594.47  5000.0 1594.27  5003.3 1590.97
  5003.8 1590.47  5017.9 1590.97  5018.8 1593.05  5024.1 1595.27  5062.1 1600.87
  5074.0 1601.93  5081.5 1604.63  5160.8 1612.79  5229.2 1624.57  5246.0 1627.67
  5320.2 1633.39  5342.1 1635.81  5372.9 1642.66  5414.0 1657.01  5476.2 1662.99
#Mann=7,-1,0
  4523.4    0.07       0  4595.5     0.1       0  5003.3    0.05       0
  5017.9     0.1       0  5062.1    0.07       0  5229.2   0.035       0
  5320.2    0.07       0
Bank Sta=5003.3,5017.9
Exp/Cntr=0.3,0.1

Chan Stop Cuts=-1