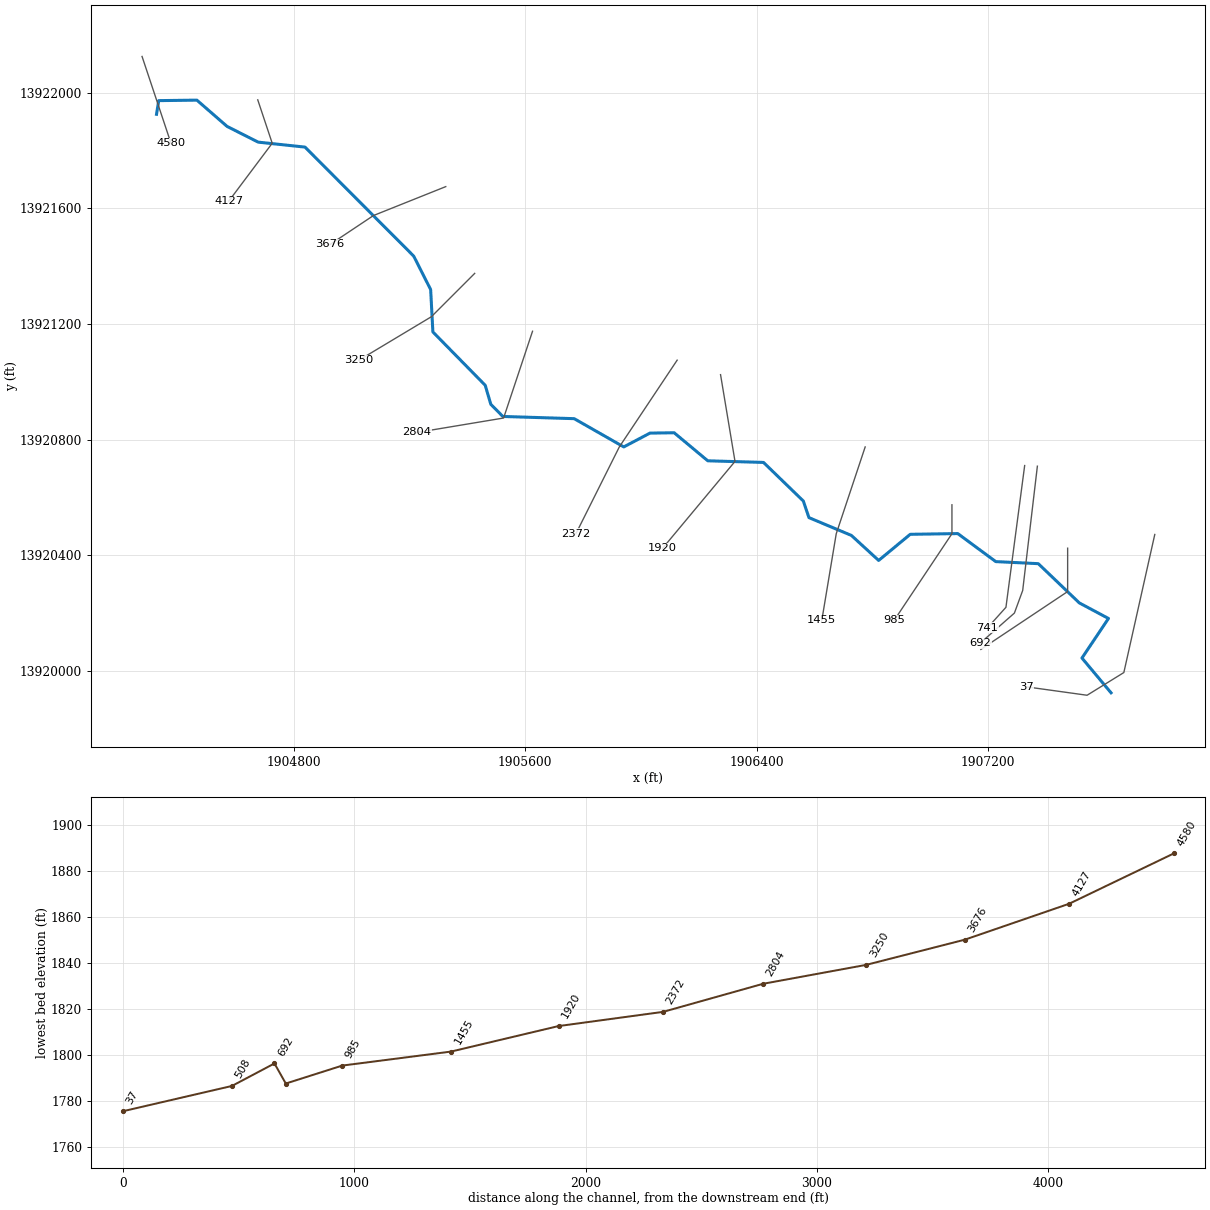
--- Stream0533.prj (project) ---

Proj Title=Stream0533 Base Level Engineering
Current Plan=p01
Default Exp/Contr=0.3,0.1
English Units
Geom File=g01
Flow File=f01
Plan File=p01
BEGIN DESCRIPTION:
Stream0533
END DESCRIPTION:

--- Stream0533.p01 (plan) ---

Plan Title=Multiple Run
Short Identifier=Multiple
Geom File=g01
Flow File=f01
Subcritical Flow
K Sum by GR= 0
Std Step Tol= 0.01
Critical Tol= 0.01
Num of Std Step Trials= 20
Max Error Tol= 0.3
Flow Tol Ratio= 0.001
Split Flow NTrial= 30
Split Flow Tol= 0.02
Split Flow Ratio= 0.02
Log Output Level= 0
Friction Slope Method= 1
Unsteady Friction Slope Method= 2
Unsteady Bridges Friction Slope Method= 1
Parabolic Critical Depth
Global Vel Dist=  1 , 1 , 1
Global Log Level= 0
CheckData=True
Encroach Param= -1, 0, 0, 0
BEGIN DESCRIPTION:
Multiple Run
END DESCRIPTION:

--- Stream0533.f01 (steady flow) ---

Flow Title=Multiple
Number of Profiles=7
Profile Names=10-year,25-year,50-year,1pct_min,100-year,1pct_plu,500-year
River Rch & RM= Stream0533,Reach-1,4580
     482     782    1056     693    1383    2760    2335
River Rch & RM= Stream0533,Reach-1,3250
    1067    1825    2549    1725    3441    6866    6184
Boundary for River Rch & Prof#=Stream0533,Reach-1,1
Up Type=0
Dn Type=3
Dn Slope=0.005
Boundary for River Rch & Prof#=Stream0533,Reach-1,2
Up Type=0
Dn Type=3
Dn Slope=0.005
Boundary for River Rch & Prof#=Stream0533,Reach-1,3
Up Type=0
Dn Type=3
Dn Slope=0.005
Boundary for River Rch & Prof#=Stream0533,Reach-1,4
Up Type=0
Dn Type=3
Dn Slope=0.005
Boundary for River Rch & Prof#=Stream0533,Reach-1,5
Up Type=0
Dn Type=3
Dn Slope=0.005
Boundary for River Rch & Prof#=Stream0533,Reach-1,6
Up Type=0
Dn Type=3
Dn Slope=0.005
Boundary for River Rch & Prof#=Stream0533,Reach-1,7
Up Type=0
Dn Type=3
Dn Slope=0.005

--- Stream0533.g01 (geometry) ---

Geom Title=Existing Conditions

River Reach=Stream0533,Reach-1
Reach XY= 30
      1904325.00     13921925.00      1904332.71     13921972.31
      1904464.55     13921973.97      1904568.95     13921883.16
      1904676.56     13921828.76      1904838.32     13921811.63
      1905214.24     13921434.68      1905272.75     13921319.07
      1905280.47     13921172.55      1905461.36     13920988.20
      1905480.74     13920922.42      1905522.30     13920880.36
      1905769.07     13920872.76      1905940.39     13920775.08
      1906030.97     13920822.81      1906114.52     13920824.06
      1906230.86     13920727.07      1906423.54     13920721.46
      1906561.27     13920587.98      1906580.61     13920530.59
      1906727.30     13920469.14      1906821.67     13920382.61
      1906930.85     13920472.93      1907095.18     13920475.43
      1907226.47     13920378.56      1907373.53     13920371.46
      1907515.36     13920235.78      1907616.15     13920181.95
      1907524.50     13920045.17      1907625.00     13919925.00

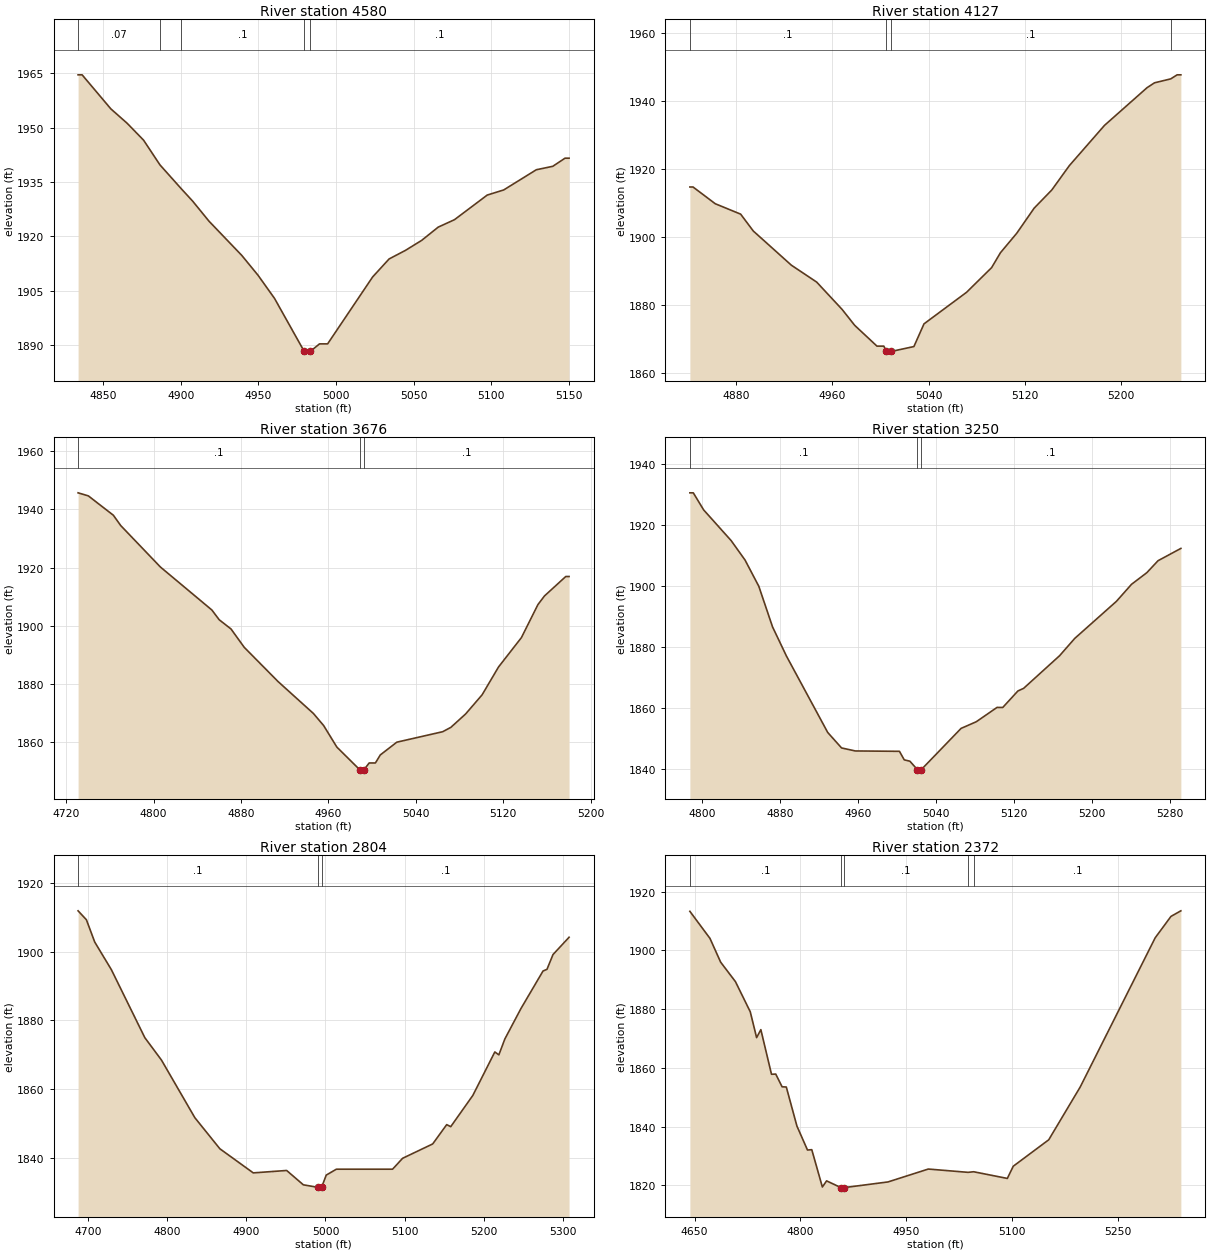
Type RM Length L Ch R = 1,4580,453,453,453
BEGIN DESCRIPTION:
Stream0533 10.0
END DESCRIPTION:
XS GIS Cut Line= 3
      1904275.00     13922124.99      1904325.00     13921975.00
      1904375.00     13921825.01
#Sta/Elev= 30
  4833.9 1964.53  4836.5 1964.53  4855.0 1955.14  4865.5 1951.17  4876.1 1946.50
  4886.6 1939.71  4900.3 1933.14  4907.7 1929.69  4918.2 1924.17  4939.3 1914.74
  4949.8 1909.25  4960.4 1902.88  4979.5 1888.28  4979.7 1887.78  4983.2 1887.78
  4983.5 1888.28  4989.4 1890.33  4994.6 1890.33  5023.6 1908.79  5034.2 1913.75
  5044.7 1916.11  5055.2 1918.88  5065.8 1922.52  5076.3 1924.58  5097.4 1931.37
  5108.0 1932.78  5129.0 1938.35  5139.6 1939.30  5147.5 1941.54  5150.1 1941.54
#Mann=5,-1,0
  4833.9    0.07       0  4886.6   0.035       0  4900.3     0.1       0
  4979.5    0.05       0  4983.5     0.1       0
Bank Sta=4979.5,4983.5
Exp/Cntr=0.3,0.1

Type RM Length L Ch R = 1,4127,451,451,451
BEGIN DESCRIPTION:
Stream0533 9.0
END DESCRIPTION:
XS GIS Cut Line= 3
      1904675.00     13921975.00      1904725.00     13921825.00
      1904575.01     13921625.01
#Sta/Elev= 30
  4841.5 1914.70  4844.1 1914.70  4862.6 1909.77  4883.7 1906.71  4894.2 1901.75
  4925.8 1891.71  4946.9 1886.72  4968.0 1878.70  4978.5 1874.00  4997.0 1867.89
  5002.7 1867.89  5004.9 1866.33  5005.2 1865.83  5008.7 1865.83  5008.9 1866.33
  5027.7 1867.76  5036.1 1874.44  5071.5 1883.73  5092.3 1890.98  5099.6 1895.34
  5113.2 1901.10  5127.7 1908.49  5142.3 1913.81  5156.9 1920.98  5186.1 1932.81
  5221.5 1943.91  5227.7 1945.34  5241.2 1946.50  5246.5 1947.69  5249.6 1947.69
#Mann=4,-1,0
  4841.5     0.1       0  5004.9    0.05       0  5008.9     0.1       0
  5241.2    0.07       0
Bank Sta=5004.9,5008.9
Exp/Cntr=0.3,0.1

Type RM Length L Ch R = 1,3676,426,426,426
BEGIN DESCRIPTION:
Stream0533 8.0
END DESCRIPTION:
XS GIS Cut Line= 3
      1905324.96     13921674.99      1905075.00     13921575.00
      1904925.00     13921475.00
#Sta/Elev= 30
  4730.8 1945.64  4740.2 1944.59  4763.1 1937.95  4769.8 1934.43  4806.2 1920.18
  4853.3 1905.44  4860.0 1902.10  4870.8 1898.94  4882.9 1892.65  4913.9 1880.90
  4946.2 1869.97  4955.6 1865.82  4967.7 1858.43  4988.6 1850.68  4988.8 1850.18
  4992.6 1850.68  4997.3 1852.98  5003.0 1852.98  5007.5 1855.74  5022.6 1860.11
  5064.6 1863.70  5072.1 1865.20  5085.6 1869.79  5100.7 1876.36  5115.7 1885.89
  5136.7 1895.99  5151.8 1907.31  5157.8 1910.27  5177.3 1916.94  5180.3 1916.94
#Mann=3,-1,0
  4730.8     0.1       0  4988.6    0.05       0  4992.6     0.1       0
Bank Sta=4988.6,4992.6
Exp/Cntr=0.3,0.1

Type RM Length L Ch R = 1,3250,446,446,446
BEGIN DESCRIPTION:
Stream0533 7.0
END DESCRIPTION:
XS GIS Cut Line= 3
      1905425.00     13921375.00      1905275.00     13921225.00
      1905024.98     13921074.99
#Sta/Elev= 30
  4787.5 1930.68  4791.0 1930.68  4801.6 1925.08  4829.9 1914.95  4844.1 1908.58
  4858.2 1899.97  4872.3 1886.62  4886.5 1877.07  4928.9 1851.92  4943.1 1846.83
  4957.2 1845.84  5002.5 1845.72  5007.4 1842.92  5013.2 1842.47  5020.9 1839.71
  5021.2 1839.21  5024.9 1839.71  5065.7 1853.25  5081.3 1855.44  5102.6 1860.15
  5108.5 1860.14  5124.0 1865.55  5129.9 1866.42  5166.8 1877.15  5182.3 1882.82
  5225.1 1895.02  5240.6 1900.62  5256.2 1904.41  5267.8 1908.37  5291.2 1912.41
#Mann=3,-1,0
  4787.5     0.1       0  5020.9    0.05       0  5024.9     0.1       0
Bank Sta=5020.9,5024.9
Exp/Cntr=0.3,0.1

Type RM Length L Ch R = 1,2804,432,432,432
BEGIN DESCRIPTION:
Stream0533 6.0
END DESCRIPTION:
XS GIS Cut Line= 3
      1905624.98     13921174.95      1905525.00     13920875.00
      1905225.02     13920825.00
#Sta/Elev= 30
  4687.5 1911.83  4698.0 1909.24  4708.5 1902.77  4729.6 1894.71  4771.8 1874.98
  4792.9 1868.44  4835.0 1851.72  4866.6 1842.69  4908.8 1835.68  4951.0 1836.38
  4972.1 1832.21  4991.1 1831.46  4991.4 1830.96  4995.1 1831.46  5001.0 1835.03
  5013.8 1836.75  5084.8 1836.75  5097.5 1839.92  5135.5 1844.09  5153.2 1849.70
  5158.3 1849.11  5186.2 1858.18  5214.0 1870.82  5219.1 1869.98  5226.7 1874.61
  5247.0 1883.43  5274.9 1894.34  5279.9 1894.83  5287.5 1899.12  5307.8 1904.15
#Mann=3,-1,0
  4687.5     0.1       0  4991.1    0.05       0  4995.1     0.1       0
Bank Sta=4991.1,4995.1
Exp/Cntr=0.3,0.1

Type RM Length L Ch R = 1,2372,452,452,452
BEGIN DESCRIPTION:
Stream0533 5.0
END DESCRIPTION:
XS GIS Cut Line= 3
      1906124.99     13921074.99      1905925.00     13920775.00
      1905774.98     13920474.96
#Sta/Elev= 30
  4643.3 1913.26  4671.8 1904.04  4686.9 1895.97  4707.9 1889.33  4728.9 1879.07
  4737.9 1870.28  4743.9 1873.00  4759.0 1857.81  4765.0 1857.88  4774.0 1853.56
  4780.0 1853.47  4795.0 1840.22  4810.0 1832.04  4816.1 1832.15  4831.1 1819.46
  4837.1 1821.54  4857.6 1819.23  4857.9 1818.73  4861.6 1819.23  4924.2 1821.18
  4981.3 1825.56  5037.6 1824.44  5045.6 1824.64  5093.3 1822.37  5101.7 1826.52
  5152.0 1835.52  5196.7 1853.52  5302.9 1904.25  5325.3 1911.54  5339.3 1913.43
#Mann=5,-1,0
  4643.3     0.1       0  4857.6    0.05       0  4861.6     0.1       0
  5037.6    0.07       0  5045.6     0.1       0
Bank Sta=4857.6,4861.6
Exp/Cntr=0.3,0.1

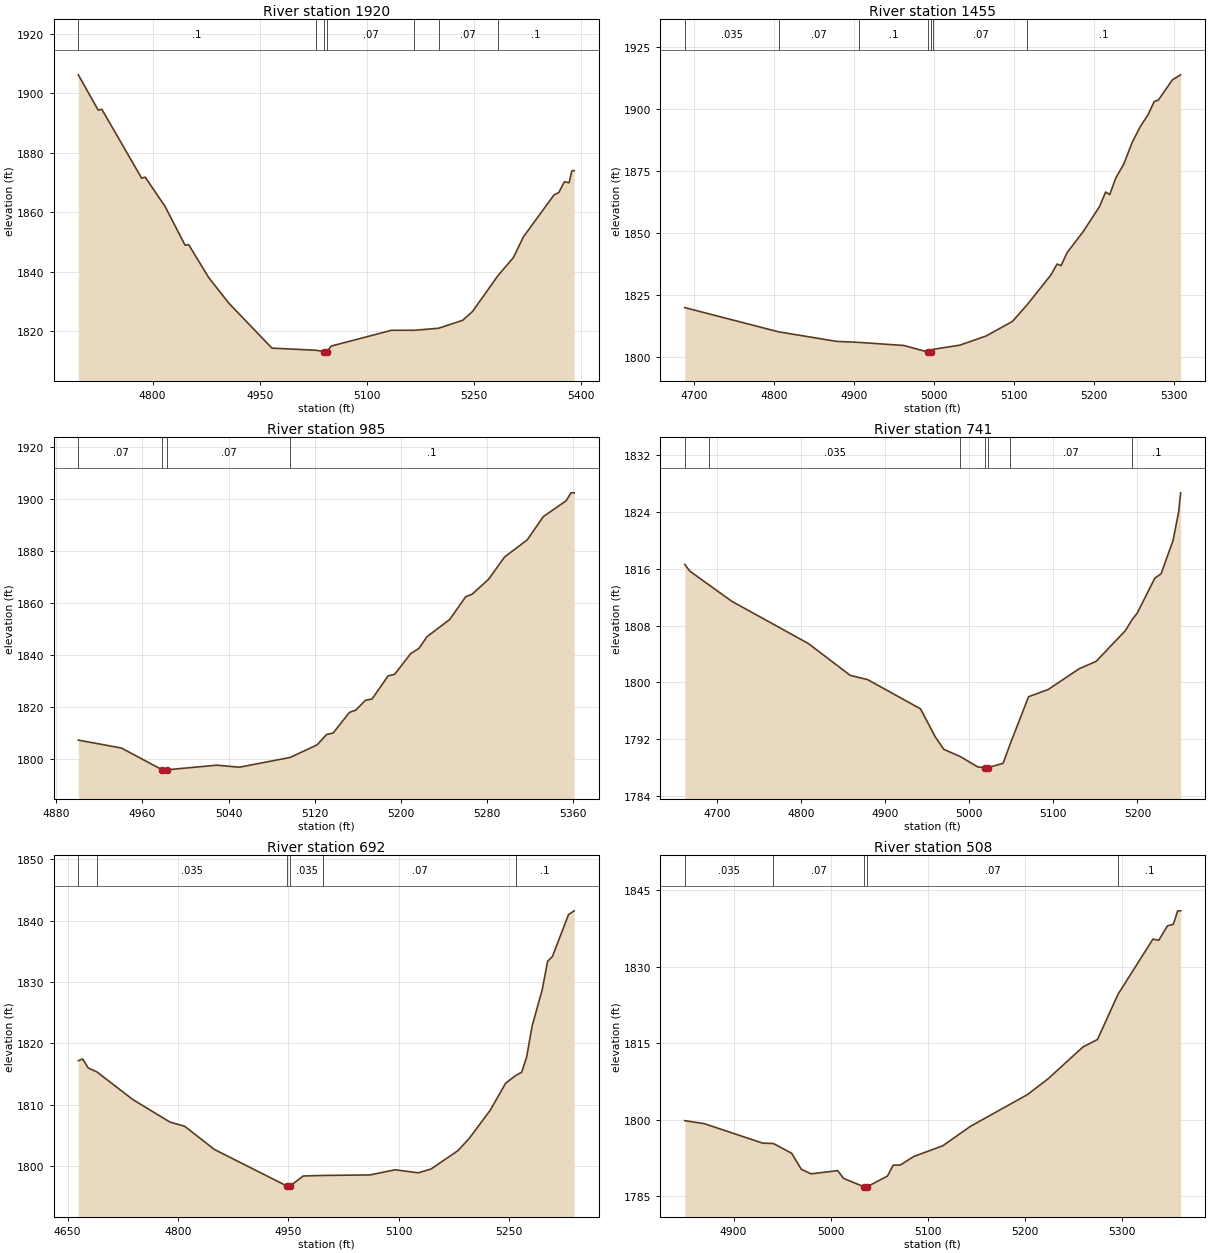
Type RM Length L Ch R = 1,1920,465,465,465
BEGIN DESCRIPTION:
Stream0533 4.0
END DESCRIPTION:
XS GIS Cut Line= 3
      1906275.01     13921024.96      1906325.00     13920725.00
      1906075.01     13920425.01
#Sta/Elev= 30
  4695.9 1906.25  4723.7 1894.37  4728.8 1894.65  4784.6 1871.46  4789.6 1871.80
  4817.5 1861.90  4845.4 1848.89  4850.5 1849.06  4878.3 1838.08  4906.2 1829.51
  4967.1 1814.23  5028.2 1813.52  5040.3 1813.04  5040.6 1812.54  5044.3 1813.04
  5050.1 1814.91  5134.7 1820.24  5166.3 1820.23  5200.6 1820.92  5234.3 1823.60
  5248.0 1826.53  5283.7 1838.61  5305.3 1844.72  5319.6 1851.76  5362.5 1865.87
  5369.0 1866.62  5376.8 1870.25  5383.4 1869.90  5387.3 1873.97  5390.5 1873.97
#Mann=7,-1,0
  4695.9     0.1       0  5028.2    0.07       0  5040.3    0.05       0
  5044.3    0.07       0  5166.3     0.1       0  5200.6    0.07       0
  5283.7     0.1       0
Bank Sta=5040.3,5044.3
Exp/Cntr=0.3,0.1

Type RM Length L Ch R = 1,1455,470,470,470
BEGIN DESCRIPTION:
Stream0533 3.0
END DESCRIPTION:
XS GIS Cut Line= 3
      1906775.00     13920775.01      1906675.00     13920475.00
      1906625.00     13920174.98
#Sta/Elev= 30
  4688.3 1819.82  4805.9 1810.01  4878.0 1806.18  4906.8 1805.75  4962.4 1804.51
  4992.0 1801.92  4992.2 1801.42  4996.0 1801.92  4999.4 1802.97  5032.4 1804.64
  5065.4 1808.36  5098.3 1814.25  5117.1 1821.14  5146.5 1833.07  5154.1 1837.43
  5159.1 1836.79  5166.7 1842.04  5187.0 1850.64  5207.3 1860.70  5214.9 1866.55
  5220.0 1865.50  5227.6 1872.22  5237.7 1877.93  5247.9 1886.44  5258.0 1892.86
  5268.1 1897.89  5275.7 1903.14  5280.8 1903.69  5298.5 1911.91  5308.7 1913.90
#Mann=7,-1,0
  4688.3   0.035       0  4805.9    0.07       0  4906.8     0.1       0
  4992.0    0.05       0  4996.0     0.1       0  4999.4    0.07       0
  5117.1     0.1       0
Bank Sta=4992,4996
Exp/Cntr=0.3,0.1

Type RM Length L Ch R = 1,985,244,244,244
BEGIN DESCRIPTION:
Stream0533 2.0
END DESCRIPTION:
XS GIS Cut Line= 3
      1907075.00     13920575.03      1907075.00     13920475.00
      1906874.99     13920174.98
#Sta/Elev= 30
  4900.4 1807.27  4940.4 1804.21  4978.4 1795.82  4978.7 1795.32  4982.4 1795.82
  5029.0 1797.61  5050.0 1796.83  5097.2 1800.59  5122.1 1805.41  5131.1 1809.44
  5137.1 1809.98  5152.2 1817.92  5158.2 1818.83  5167.2 1822.62  5173.2 1823.08
  5188.2 1832.02  5194.2 1832.59  5209.2 1840.58  5216.8 1842.56  5224.3 1847.08
  5245.3 1853.67  5260.3 1862.49  5266.3 1863.47  5281.4 1869.15  5296.4 1877.78
  5317.4 1884.36  5332.4 1893.34  5353.5 1899.40  5358.0 1902.47  5361.0 1902.47
#Mann=4,-1,0
  4900.4    0.07       0  4978.4    0.05       0  4982.4    0.07       0
  5097.2     0.1       0
Bank Sta=4978.4,4982.4
Exp/Cntr=0.3,0.1

Type RM Length L Ch R = 1,741,49,49,49
BEGIN DESCRIPTION:
Mapping XS 6884057d
END DESCRIPTION:
XS GIS Cut Line= 3
      1907326.44     13920710.66      1907261.68     13920220.55
      1907197.57     13920149.32
#Sta/Elev= 30
  4661.2 1816.64  4666.9 1815.72  4690.0 1813.75  4717.3 1811.43  4808.1 1805.50
  4858.3 1800.99  4878.7 1800.41  4941.8 1796.28  4959.4 1792.32  4969.5 1790.57
  4988.9 1789.57  5009.9 1788.09  5018.4 1788.00  5018.6 1787.50  5022.1 1787.50
  5022.4 1788.00  5040.1 1788.61  5048.7 1791.38  5070.4 1797.99  5093.8 1799.01
  5130.9 1801.95  5150.8 1802.97  5185.6 1807.30  5193.5 1808.83  5199.8 1809.79
  5220.7 1814.70  5228.2 1815.33  5242.4 1820.02  5249.1 1824.07  5251.4 1826.73
#Mann=7,-1,0
  4661.2     0.1       0  4690.0   0.035       0  4988.9     0.1       0
  5018.4    0.05       0  5022.4     0.1       0  5048.7    0.07       0
  5193.5     0.1       0
Bank Sta=5018.4,5022.4
Exp/Cntr=0.3,0.1

Type RM Length L Ch R = 1,692,184,184,184
BEGIN DESCRIPTION:
Stream0533 1.1
END DESCRIPTION:
XS GIS Cut Line= 4
      1907370.38     13920708.50      1907319.60     13920278.79
      1907290.95     13920200.66      1907172.45     13920096.48
#Sta/Elev= 30
  4664.6 1817.17  4670.5 1817.45  4678.2 1815.97  4689.7 1815.36  4738.6 1810.85
  4789.0 1807.18  4809.1 1806.49  4849.4 1802.72  4948.1 1796.75  4948.3 1796.25
  4952.1 1796.75  4970.2 1798.39  4997.6 1798.48  5060.8 1798.56  5095.0 1799.40
  5126.6 1798.91  5143.9 1799.53  5180.5 1802.53  5195.9 1804.54  5224.3 1809.11
  5245.2 1813.51  5258.7 1814.75  5267.0 1815.29  5273.7 1817.76  5281.3 1822.88
  5295.0 1828.78  5302.2 1833.37  5308.8 1834.15  5330.6 1840.97  5338.3 1841.59
#Mann=6,-1,0
  4664.6     0.1       0  4689.7   0.035       0  4948.1    0.05       0
  4952.1   0.035       0  4997.6    0.07       0  5258.7     0.1       0
Bank Sta=4948.1,4952.1
Exp/Cntr=0.3,0.1

Type RM Length L Ch R = 1,508,471,471,471
BEGIN DESCRIPTION:
Stream0533 1.0
END DESCRIPTION:
XS GIS Cut Line= 3
      1907475.00     13920424.99      1907475.00     13920275.00
      1907175.04     13920075.02
#Sta/Elev= 30
  4849.8 1799.85  4869.8 1799.27  4929.8 1795.46  4941.0 1795.37  4959.8 1793.47
  4969.8 1790.32  4979.8 1789.44  5007.3 1790.06  5013.3 1788.54  5033.8 1786.94
  5034.1 1786.44  5037.6 1786.44  5037.8 1786.94  5058.4 1788.99  5064.4 1791.13
  5071.9 1791.18  5085.4 1792.82  5115.5 1794.94  5144.0 1798.75  5202.6 1804.96
  5223.6 1808.01  5259.7 1814.28  5274.7 1815.75  5295.9 1824.63  5331.8 1835.41
  5337.8 1835.19  5346.8 1838.02  5352.8 1838.31  5357.3 1840.95  5360.3 1840.95
#Mann=5,-1,0
  4849.8   0.035       0  4941.0    0.07       0  5033.8    0.05       0
  5037.8    0.07       0  5295.9     0.1       0
Bank Sta=5033.8,5037.8
Exp/Cntr=0.3,0.1

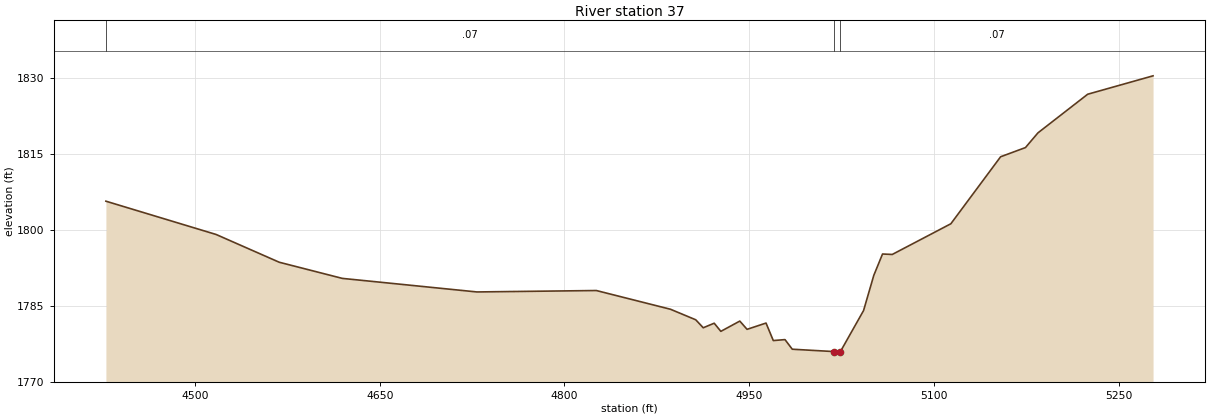
Type RM Length L Ch R = 1,37,0,0,0
BEGIN DESCRIPTION:
Stream0533 0.0
END DESCRIPTION:
XS GIS Cut Line= 4
      1907776.26     13920472.37      1907669.30     13919994.99
      1907542.22     13919916.52      1907332.41     13919945.65
#Sta/Elev= 30
  4427.6 1805.66  4517.1 1799.08  4568.4 1793.59  4619.6 1790.40  4728.9 1787.72
  4825.9 1788.00  4886.1 1784.30  4906.6 1782.22  4912.7 1780.64  4921.6 1781.54
  4927.0 1779.93  4942.4 1781.96  4948.3 1780.33  4963.7 1781.57  4969.6 1778.11
  4979.1 1778.30  4985.0 1776.40  5019.1 1775.93  5019.5 1775.43  5024.1 1775.93
  5042.9 1784.04  5051.2 1790.99  5058.3 1795.22  5066.2 1795.13  5113.8 1801.20
  5154.2 1814.44  5174.4 1816.26  5184.5 1819.16  5224.9 1826.80  5278.0 1830.44
#Mann=3,-1,0
  4427.6    0.07       0  5019.1    0.05       0  5024.1    0.07       0
Bank Sta=5019.1,5024.1
Exp/Cntr=0.3,0.1

Chan Stop Cuts=-1