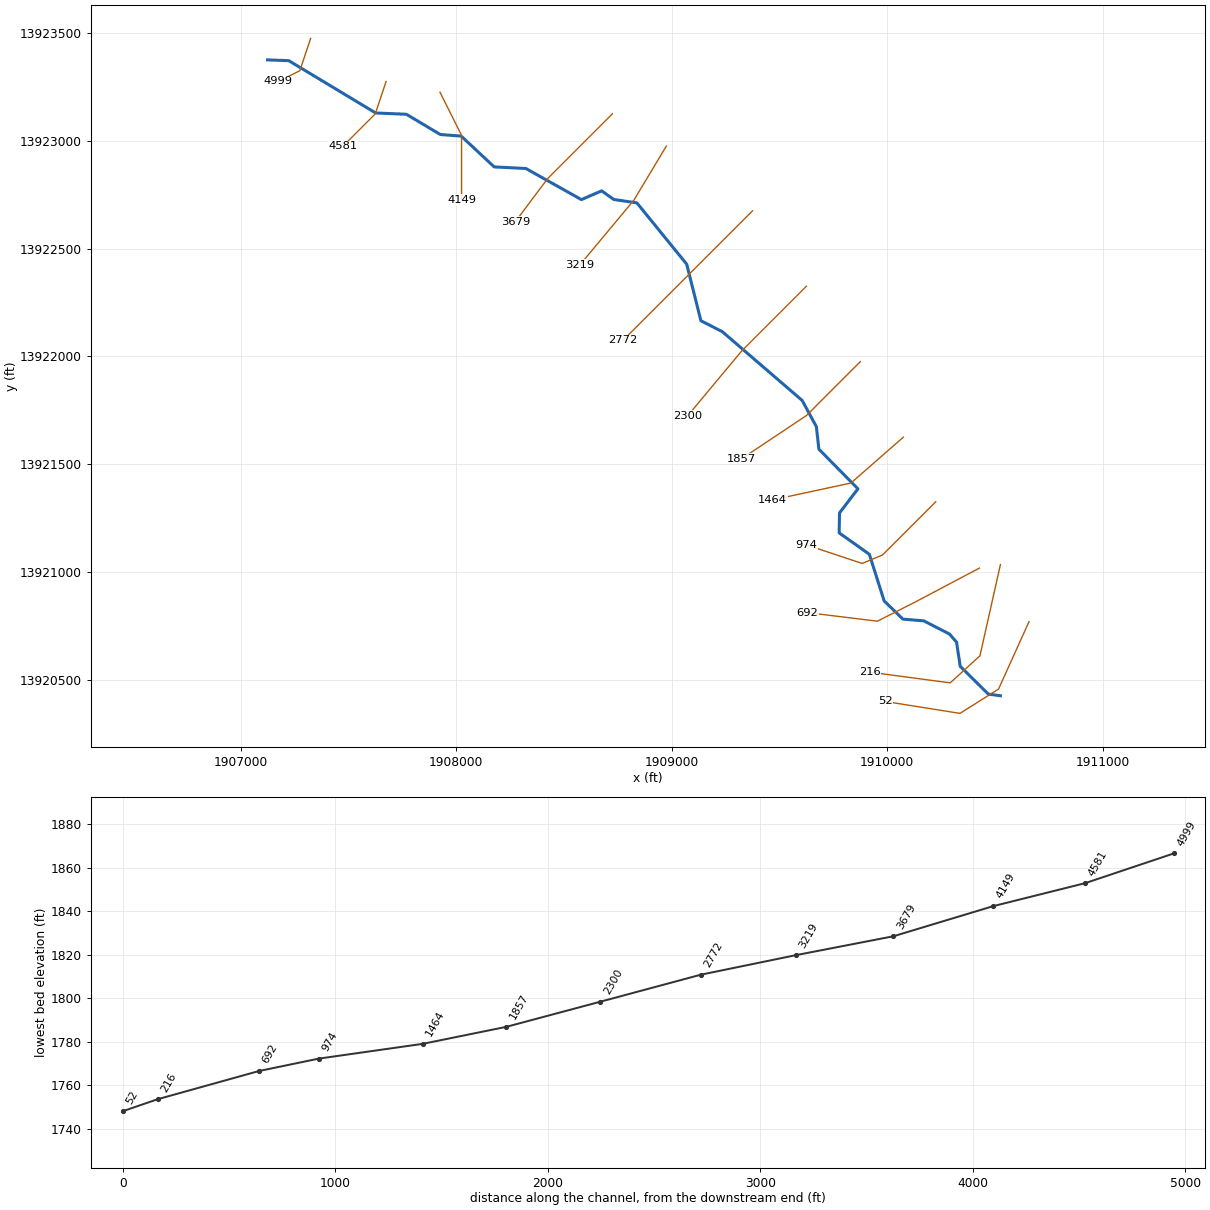
--- Stream0534.prj (project) ---

Proj Title=Stream0534 Base Level Engineering
Current Plan=p01
Default Exp/Contr=0.3,0.1
English Units
Geom File=g01
Flow File=f01
Plan File=p01
Y Axis Title=Elevation
X Axis Title(PF)=Main Channel Distance
X Axis Title(XS)=Station
BEGIN DESCRIPTION:
Stream0534
END DESCRIPTION:
DSS Export Rating Curves= 0
DSS Export Rating Curve Sorted= 0
DSS Export Volume Flow Curves= 0
DXF OffsetX= 0
DXF OffsetY= 0
DXF ScaleX= 1
DXF ScaleY= 10

--- Stream0534.p01 (plan) ---

Plan Title=Multiple Run
Short Identifier=Multiple
Geom File=g01
Flow File=f01
Subcritical Flow
K Sum by GR= 0
Std Step Tol= 0.01
Critical Tol= 0.01
Num of Std Step Trials= 20
Max Error Tol= 0.3
Flow Tol Ratio= 0.001
Split Flow NTrial= 30
Split Flow Tol= 0.02
Split Flow Ratio= 0.02
Log Output Level= 0
Friction Slope Method= 1
Unsteady Friction Slope Method= 2
Unsteady Bridges Friction Slope Method= 1
Parabolic Critical Depth
Global Vel Dist=  1 , 1 , 1
Global Log Level= 0
CheckData=True
Encroach Param= -1, 0, 0, 0
BEGIN DESCRIPTION:
Multiple Run
END DESCRIPTION:

--- Stream0534.f01 (steady flow) ---

Flow Title=Multiple
Program Version=4.10
Number of Profiles= 7
Profile Names=10-year,25-year,50-year,1pct_min,100-year,1pct_plu,500-year
River Rch & RM=Stream0534,Reach-1         ,4999
     678    1123    1536    1019    2033    4057    3509
Boundary for River Rch & Prof#=Stream0534,Reach-1         , 1
Up Type= 0
Dn Type= 3
Dn Slope=0.007
Boundary for River Rch & Prof#=Stream0534,Reach-1         , 2
Up Type= 0
Dn Type= 3
Dn Slope=0.007
Boundary for River Rch & Prof#=Stream0534,Reach-1         , 3
Up Type= 0
Dn Type= 3
Dn Slope=0.007
Boundary for River Rch & Prof#=Stream0534,Reach-1         , 4
Up Type= 0
Dn Type= 3
Dn Slope=0.007
Boundary for River Rch & Prof#=Stream0534,Reach-1         , 5
Up Type= 0
Dn Type= 3
Dn Slope=0.007
Boundary for River Rch & Prof#=Stream0534,Reach-1         , 6
Up Type= 0
Dn Type= 3
Dn Slope=0.007
Boundary for River Rch & Prof#=Stream0534,Reach-1         , 7
Up Type= 0
Dn Type= 3
Dn Slope=0.007
DSS Import GetInterval= 0
DSS Import GetPeak= 0
DSS Import FillOption= 0

--- Stream0534.g01 (geometry) ---

Geom Title=Existing Conditions
Program Version=4.10

River Reach=Stream0534      ,Reach-1
Reach XY= 30
        1907125.       13923375.       1907223.5     13923371.37
      1907626.56     13923128.76      1907769.07     13923122.75
      1907926.59     13923028.83       1908023.5     13923021.39
      1908176.47     13922878.54      1908323.44     13922871.24
      1908581.12     13922726.84      1908674.99     13922767.41
       1908730.9     13922727.55      1908838.33     13922711.61
      1909069.48     13922427.43      1909135.39      13922164.9
      1909234.66     13922114.21      1909605.22     13921795.09
      1909671.17     13921673.41      1909682.86     13921568.83
      1909864.04       13921385.      1909778.48      13921273.5
      1909776.89     13921180.71      1909916.98     13921081.34
      1909985.51     13920865.19      1910072.56     13920780.52
      1910169.03     13920772.67      1910288.63     13920711.55
      1910321.47     13920673.72       1910338.4      13920561.7
      1910468.79     13920432.76        1910525.       13920425.

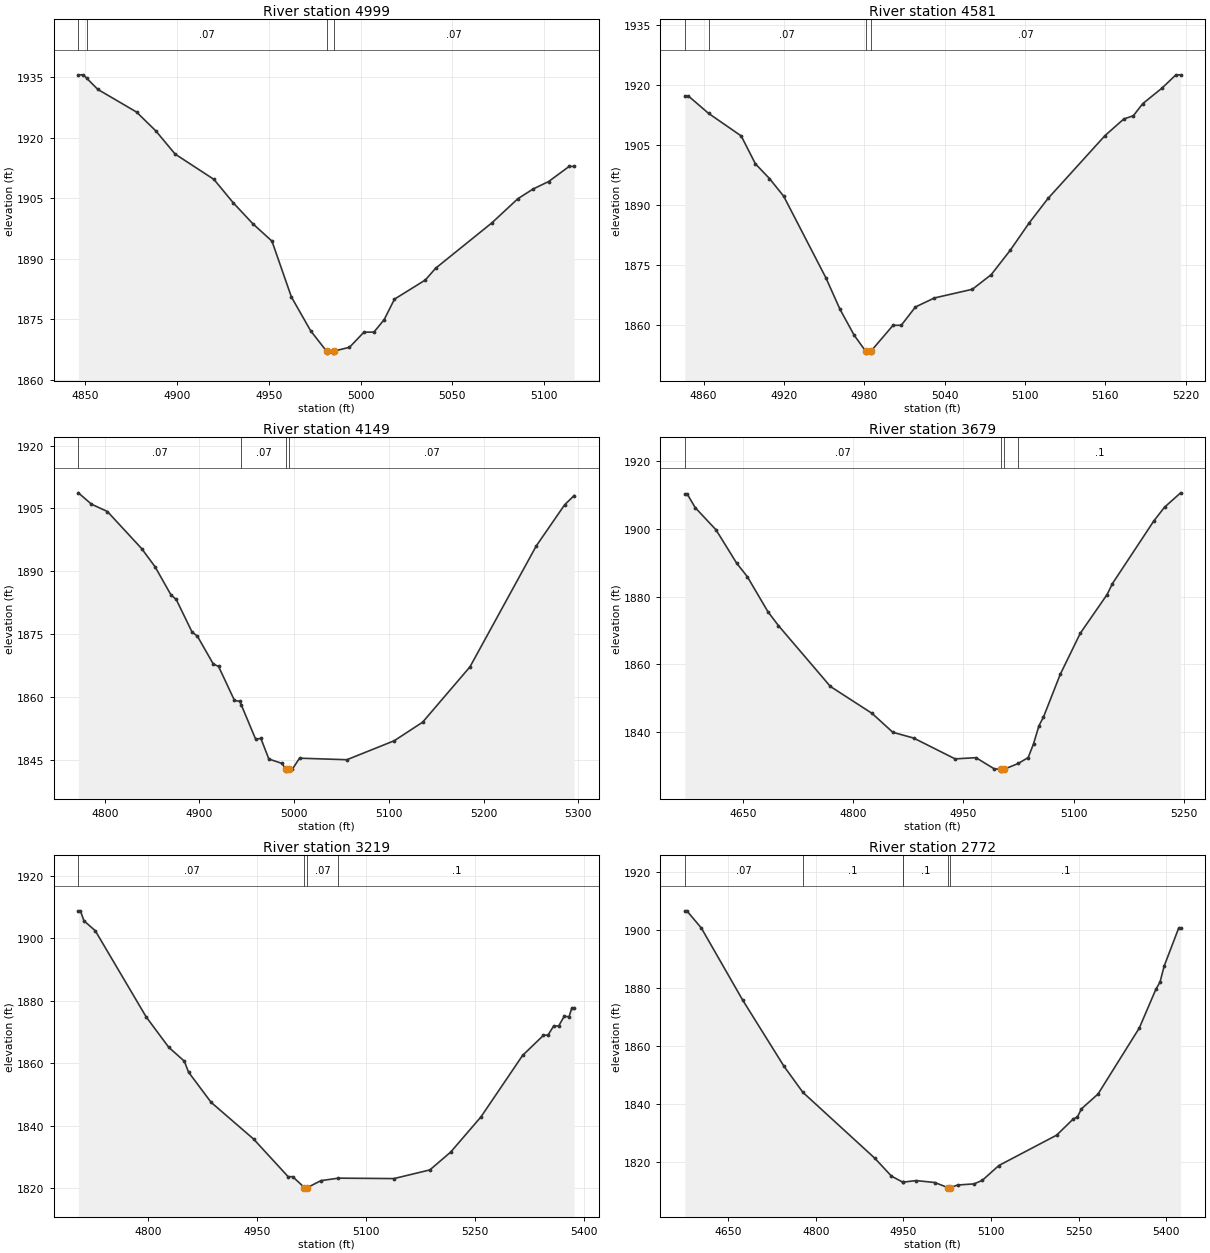
Type RM Length L Ch R = 1 ,4999    ,418,418,418
BEGIN DESCRIPTION:
Stream0534 10.0
END DESCRIPTION:
XS GIS Cut Line= 3
      1907325.01     13923475.03        1907275.       13923325.
      1907175.04     13923275.02
#Sta/Elev= 30
  4846.4 1935.62  4849.1 1935.62  4850.9  1934.8    4857 1932.01  4878.1 1926.38
  4888.6  1921.7  4899.1 1915.95  4920.2 1909.68  4930.8 1903.83  4941.3 1898.71
  4951.8 1894.35  4962.4 1880.48  4972.9 1872.08  4981.5 1867.06  4981.7 1866.56
  4985.2 1866.56  4985.5 1867.06    4994 1868.01  5001.9 1871.77  5007.3 1871.77
  5012.9 1874.89  5018.5 1879.96  5035.3 1884.71  5040.9 1887.63  5071.6 1898.92
  5085.6 1904.86    5094  1907.3  5102.4 1909.14  5113.6  1912.9  5116.3  1912.9
#Mann= 4 ,-1 , 0
  4846.4     .07       0  4850.9     .07       0  4981.5     .05       0
  4985.5     .07       0
Bank Sta=4981.5,4985.5
XS Rating Curve= 0 ,0
Exp/Cntr=0.3,0.1

Type RM Length L Ch R = 1 ,4581    ,432,432,432
BEGIN DESCRIPTION:
Stream0534 9.0
END DESCRIPTION:
XS GIS Cut Line= 3
      1907674.99     13923274.98        1907625.       13923125.
      1907475.02     13922975.02
#Sta/Elev= 30
    4846  1917.3  4848.6  1917.3  4863.7 1912.94  4888.1 1907.28  4898.7  1900.3
  4909.2 1896.61  4919.8  1892.2  4951.4 1871.71  4961.9 1863.84  4972.5 1857.35
    4981 1853.38  4981.3 1852.88  4984.8 1852.88    4985 1853.38  5001.5 1859.85
  5007.6 1859.85  5018.2 1864.44  5032.4  1866.7  5060.7 1868.87  5074.8 1872.54
    5089 1878.65  5103.1 1885.48  5117.2 1891.62  5159.7 1907.35  5173.8 1911.53
  5180.9 1912.33  5187.9 1915.36  5202.1  1919.2  5212.7 1922.58  5216.2 1922.58
#Mann= 4 ,-1 , 0
    4846     .07       0  4863.7     .07       0    4981     .05       0
    4985     .07       0
Bank Sta=4981,4985
XS Rating Curve= 0 ,0
Exp/Cntr=0.3,0.1

Type RM Length L Ch R = 1 ,4149    ,470,470,470
BEGIN DESCRIPTION:
Stream0534 8.0
END DESCRIPTION:
XS GIS Cut Line= 3
      1907925.02     13923224.96        1908025.       13923025.
        1908025.     13922724.96
#Sta/Elev= 30
  4772.1 1908.73    4786 1906.02  4802.8 1904.27  4839.1 1895.39  4853.1  1891.1
  4869.9 1884.39  4875.5 1883.28  4892.2 1875.52  4897.8 1874.54  4914.6  1867.9
  4920.2  1867.3    4937  1859.2  4942.6 1858.99  4944.4 1858.02  4959.3 1849.97
  4964.9 1850.12  4973.3 1845.22  4987.3 1844.16  4990.9 1842.83  4991.1 1842.33
  4994.9 1842.83  4998.2 1842.83  5005.7 1845.42  5055.7 1845.05  5105.7 1849.58
  5135.7 1854.01  5185.7 1867.22  5255.7 1896.07  5285.7 1905.89  5295.7 1908.09
#Mann= 4 ,-1 , 0
  4772.1     .07       0  4944.4     .07       0  4990.9     .05       0
  4994.9     .07       0
Bank Sta=4990.9,4994.9
XS Rating Curve= 0 ,0
Exp/Cntr=0.3,0.1

Type RM Length L Ch R = 1 ,3679    ,460,460,460
BEGIN DESCRIPTION:
Stream0534 7.0
END DESCRIPTION:
XS GIS Cut Line= 3
      1908725.01     13923125.01        1908425.       13922825.
      1908274.98     13922624.98
#Sta/Elev= 30
    4571 1910.16  4574.5 1910.16  4585.2 1906.21  4613.4 1899.69  4641.7 1889.78
  4655.9  1885.9  4684.1  1875.5  4698.3 1871.43    4769 1853.46  4825.6 1845.53
  4853.9 1839.94  4882.1 1838.25  4938.7 1832.09    4967 1832.45  4991.7 1829.17
  5000.6 1828.98  5000.8 1828.48  5004.6 1828.98  5024.5 1830.74    5038 1832.49
  5045.3 1836.55  5052.6 1841.85  5058.8 1844.45  5081.7 1857.09  5108.8 1869.14
  5145.3 1880.58  5152.6 1883.82  5208.8 1902.28  5223.4 1906.35  5245.3 1910.59
#Mann= 4 ,-1 , 0
    4571     .07       0  5000.6     .05       0  5004.6     .07       0
  5024.5      .1       0
Bank Sta=5000.6,5004.6
XS Rating Curve= 0 ,0
Exp/Cntr=0.3,0.1

Type RM Length L Ch R = 1 ,3219    ,447,447,447
BEGIN DESCRIPTION:
Stream0534 6.0
END DESCRIPTION:
XS GIS Cut Line= 3
      1908974.99     13922974.98        1908825.       13922725.
      1908575.02     13922425.03
#Sta/Elev= 30
  4704.3 1908.72  4707.2 1908.72    4712 1905.55  4727.6 1902.36  4797.6 1874.83
  4828.7  1865.1    4850  1860.7  4855.9 1857.17    4887  1847.5  4945.3  1835.8
  4992.9 1823.76  4999.1 1823.76  5015.3 1820.28  5015.6 1819.78  5019.3 1820.28
  5038.1  1822.5  5062.1 1823.29  5138.4 1823.15  5187.8 1825.92  5216.5 1831.63
  5258.1 1842.87  5315.4 1862.52    5344 1868.92  5350.5 1869.07  5358.3 1871.99
  5364.9 1871.88  5372.7 1875.05  5379.2 1874.84  5383.1 1877.68  5386.3 1877.68
#Mann= 4 ,-1 , 0
  4704.3     .07       0  5015.3     .05       0  5019.3     .07       0
  5062.1      .1       0
Bank Sta=5015.3,5019.3
XS Rating Curve= 0 ,0
Exp/Cntr=0.3,0.1

Type RM Length L Ch R = 1 ,2772    ,472,472,472
BEGIN DESCRIPTION:
Stream0534 5.0
END DESCRIPTION:
XS GIS Cut Line= 3
      1909375.01     13922675.01        1909075.       13922375.
      1908775.03     13922075.03
#Sta/Elev= 30
  4575.8 1906.67  4579.3 1906.67  4604.1 1900.75  4674.8 1875.94  4745.5 1853.14
  4777.9 1844.14  4901.1 1821.42  4929.4 1815.29  4948.7 1813.21  4948.9  1813.2
  4971.8 1813.74  5003.6 1813.08  5026.4  1811.3  5026.6  1810.8  5030.4  1811.3
  5042.5 1812.21  5070.8 1812.61  5084.9 1813.82  5113.2 1818.93  5212.2  1829.4
  5240.5 1834.97  5247.6 1835.62  5254.6 1838.47  5282.9 1843.55  5353.6 1866.31
  5381.9 1879.63    5389 1882.09  5396.1 1887.62  5420.8 1900.63  5424.3 1900.63
#Mann= 6 ,-1 , 0
  4575.8     .07       0  4777.9      .1       0  4948.7     .07       0
  4948.9      .1       0  5026.4     .05       0  5030.4      .1       0
Bank Sta=5026.4,5030.4
XS Rating Curve= 0 ,0
Exp/Cntr=0.3,0.1

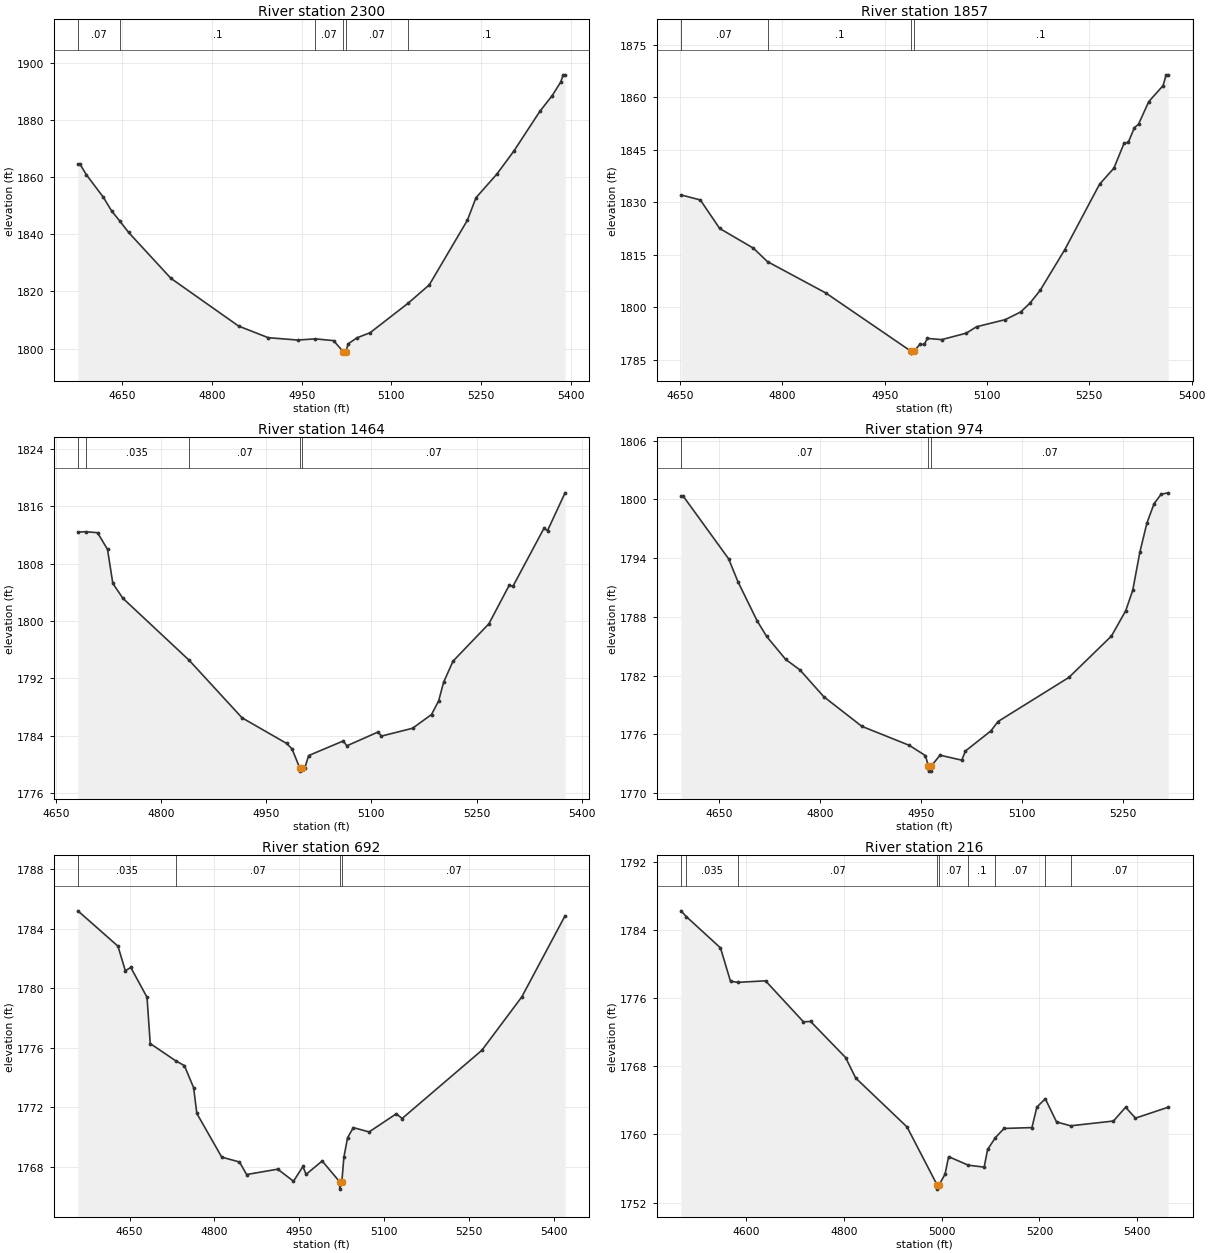
Type RM Length L Ch R = 1 ,2300    ,443,443,443
BEGIN DESCRIPTION:
Stream0534 4.0
END DESCRIPTION:
XS GIS Cut Line= 3
      1909625.02     13922325.02        1909325.       13922025.
      1909075.01     13921725.01
#Sta/Elev= 30
  4575.7 1864.47  4579.3 1864.47  4589.9 1860.78  4618.2 1852.95  4632.3 1848.07
  4645.9 1844.57  4660.6  1840.6  4731.3 1824.56  4844.4 1807.88  4893.9 1803.82
  4943.4 1802.98  4972.7  1803.4  5003.3 1802.78  5019.5 1798.91  5019.7 1798.41
  5023.5 1798.91    5028 1801.69  5042.3 1803.75  5064.4 1805.55  5127.7 1815.81
  5163.4 1822.28  5227.1 1844.88  5241.5 1852.75  5276.6 1861.07  5305.2 1869.18
  5348.2 1882.93    5369 1888.47  5383.3 1893.25  5387.3 1895.73  5390.5 1895.73
#Mann= 6 ,-1 , 0
  4575.7     .07       0  4645.9      .1       0  4972.7     .07       0
  5019.5     .05       0  5023.5     .07       0  5127.7      .1       0
Bank Sta=5019.5,5023.5
XS Rating Curve= 0 ,0
Exp/Cntr=0.3,0.1

Type RM Length L Ch R = 1 ,1857    ,393,393,393
BEGIN DESCRIPTION:
Stream0534 3.0
END DESCRIPTION:
XS GIS Cut Line= 3
      1909875.02     13921975.02        1909625.       13921725.
      1909325.03     13921525.02
#Sta/Elev= 30
  4651.5 1832.05  4679.8 1830.61  4708.1 1822.48  4757.6 1816.83  4778.3 1812.98
  4863.7 1804.04  4988.9 1787.35  4989.2 1786.85  4992.9 1787.35  5001.5 1789.34
  5008.1 1789.34  5012.6 1791.06  5033.6 1790.71  5069.7 1792.56  5084.7 1794.39
  5126.8 1796.42  5149.3 1798.61  5162.8 1801.09  5177.8 1804.75  5213.9 1816.37
    5265 1835.11    5286 1839.69    5301 1846.86    5307 1847.05  5316.1 1851.26
  5322.1 1852.27  5337.1 1858.69  5358.1 1863.29  5362.6 1866.36  5365.6 1866.36
#Mann= 4 ,-1 , 0
  4651.5     .07       0  4778.3      .1       0  4988.9     .05       0
  4992.9      .1       0
Bank Sta=4988.9,4992.9
XS Rating Curve= 0 ,0
Exp/Cntr=0.3,0.1

Type RM Length L Ch R = 1 ,1464    ,490,490,490
BEGIN DESCRIPTION:
Stream0534 2.0
END DESCRIPTION:
XS GIS Cut Line= 3
        1910075.       13921625.      1909831.34     13921411.89
      1909468.81     13921334.06
#Sta/Elev= 30
  4681.6  1812.4  4692.5 1812.44  4709.6 1812.31  4723.8 1809.98  4731.4 1805.23
  4745.7 1803.16  4840.2 1794.51  4915.6 1786.48  4979.2  1782.9  4986.8 1782.15
  4997.6 1779.54  4997.8 1779.04  5001.6 1779.54  5005.3 1779.54  5010.5 1781.21
  5059.9 1783.25    5065 1782.57  5109.3 1784.49  5114.4 1783.93  5158.7 1785.02
  5185.7 1786.94  5195.9 1788.85    5203 1791.46  5216.4 1794.39  5267.5  1799.6
  5296.6    1805  5301.7 1804.82    5346 1812.92  5351.1  1812.6  5376.1 1817.87
#Mann= 5 ,-1 , 0
  4681.6     .07       0  4692.5    .035       0  4840.2     .07       0
  4997.6     .05       0  5001.6     .07       0
Bank Sta=4997.6,5001.6
XS Rating Curve= 0 ,0
Exp/Cntr=0.3,0.1

Type RM Length L Ch R = 1 ,974     ,282,282,282
BEGIN DESCRIPTION:
Stream0534 1.0
END DESCRIPTION:
XS GIS Cut Line= 4
      1910224.99     13921324.99      1909978.36     13921078.36
      1909883.55     13921038.82      1909625.04     13921124.99
#Sta/Elev= 30
    4593 1800.32  4596.5 1800.32  4663.7 1793.94  4677.8 1791.57  4706.1  1787.6
  4720.3    1786  4748.5 1783.66  4769.8 1782.58  4805.1 1779.85  4861.7 1776.82
  4932.4 1774.87  4956.3 1773.82  4960.6 1772.74  4960.8 1772.24  4964.3 1772.24
  4964.6 1772.74  4977.9 1773.87  5010.2 1773.36  5015.7  1774.3  5053.5 1776.35
  5064.1 1777.31  5169.5 1781.82  5232.7 1786.05  5253.8 1788.62  5264.3 1790.72
  5274.9 1794.62  5285.4  1797.6    5296 1799.57  5306.5 1800.54    5317 1800.68
#Mann= 3 ,-1 , 0
    4593     .07       0  4960.6     .05       0  4964.6     .07       0
Bank Sta=4960.6,4964.6
XS Rating Curve= 0 ,0
Exp/Cntr=0.3,0.1

Type RM Length L Ch R = 1 ,692     ,476,476,476
BEGIN DESCRIPTION:
Stream0534 0.0
END DESCRIPTION:
XS GIS Cut Line= 4
      1910427.62     13921017.37      1910127.09     13920858.52
      1909954.14     13920770.97      1909628.95     13920810.85
#Sta/Elev= 30
  4558.6  1785.2  4629.4 1782.83  4642.5 1781.18  4652.1  1781.4  4680.8  1779.4
  4686.5 1776.29  4731.3 1775.14  4746.9 1774.81  4763.2 1773.33  4768.9  1771.6
  4812.9 1768.67  4844.3 1768.34  4856.9  1767.5  4911.9 1767.86  4939.8 1767.05
  4956.5 1768.04  4962.1 1767.51  4990.5 1768.41  5021.3 1767.02  5021.6 1766.52
  5025.3 1767.02  5028.9 1768.66  5035.4 1769.97  5045.6 1770.65  5073.5 1770.36
  5121.7 1771.58  5131.8 1771.26  5272.9 1775.84  5343.4 1779.42    5420 1784.87
#Mann= 4 ,-1 , 0
  4558.6    .035       0  4731.3     .07       0  5021.3     .05       0
  5025.3     .07       0
Bank Sta=5021.3,5025.3
XS Rating Curve= 0 ,0
Exp/Cntr=0.3,0.1

Type RM Length L Ch R = 1 ,216     ,164,164,164
BEGIN DESCRIPTION:
Stream0534 0.1
END DESCRIPTION:
XS GIS Cut Line= 4
        1910525.     13921033.82      1910430.01     13920610.34
      1910291.92     13920484.82      1909918.57     13920534.79
#Sta/Elev= 30
  4466.2 1786.23  4476.9 1785.56    4547 1781.88  4567.5 1777.96    4583 1777.84
  4639.2 1778.02  4716.8 1773.21  4731.5 1773.25  4803.2 1769.01  4823.7 1766.62
  4928.8 1760.88  4990.4 1754.08  4990.6 1753.58  4994.4 1754.08  5006.6 1755.32
    5014 1757.39  5054.1 1756.39  5086.8 1756.16  5093.8 1758.23  5109.5  1759.6
  5127.5  1760.7  5184.6  1760.8  5194.7 1763.21  5211.9 1764.18    5235 1761.46
  5263.8 1761.01  5351.5 1761.57  5376.3 1763.19  5396.5 1761.91  5463.5 1763.19
#Mann= 9 ,-1 , 0
  4466.2     .07       0  4476.9    .035       0    4583     .07       0
  4990.4     .05       0  4994.4     .07       0  5054.1      .1       0
  5109.5     .07       0  5211.9      .1       0  5263.8     .07       0
Bank Sta=4990.4,4994.4
XS Rating Curve= 0 ,0
Exp/Cntr=0.3,0.1

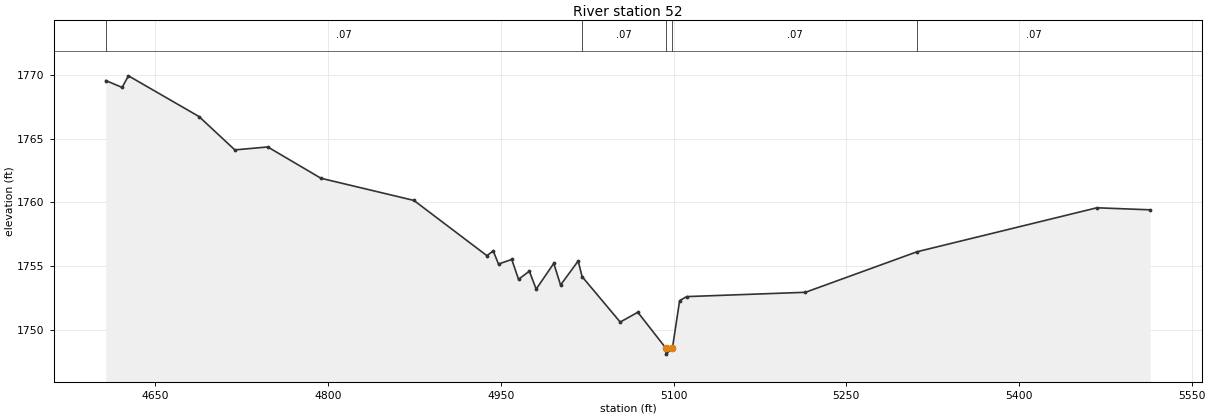
Type RM Length L Ch R = 1 ,52      ,0,0,0
BEGIN DESCRIPTION:
Stream0534 0.2
END DESCRIPTION:
XS GIS Cut Line= 4
      1910657.71     13920768.79      1910516.23     13920456.04
      1910337.34     13920343.32      1909989.32      13920398.7
#Sta/Elev= 30
  4606.9 1769.57  4621.1 1769.03  4626.6 1769.94  4687.9 1766.74    4719 1764.12
  4747.6 1764.35  4793.8 1761.89  4874.5 1760.15  4937.9 1755.81  4943.4 1756.18
    4948 1755.15  4959.5 1755.51  4965.4 1753.95  4974.8 1754.59  4980.7 1753.18
    4996  1755.2  5001.9  1753.5  5017.2 1755.39  5020.6 1754.16  5053.7 1750.59
    5069 1751.36  5093.1 1748.57  5093.6 1748.07  5099.1 1748.57  5105.3 1752.27
  5111.4 1752.59  5214.6 1752.93  5311.7 1756.12  5467.7 1759.57    5514 1759.41
#Mann= 5 ,-1 , 0
  4606.9     .07       0  5020.6     .07       0  5093.1     .05       0
  5099.1     .07       0  5311.7     .07       0
Bank Sta=5093.1,5099.1
XS Rating Curve= 0 ,0
Exp/Cntr=0.3,0.1

Chan Stop Cuts=-1
Use User Specified Reach Order=0
Composite Channel Slope=5