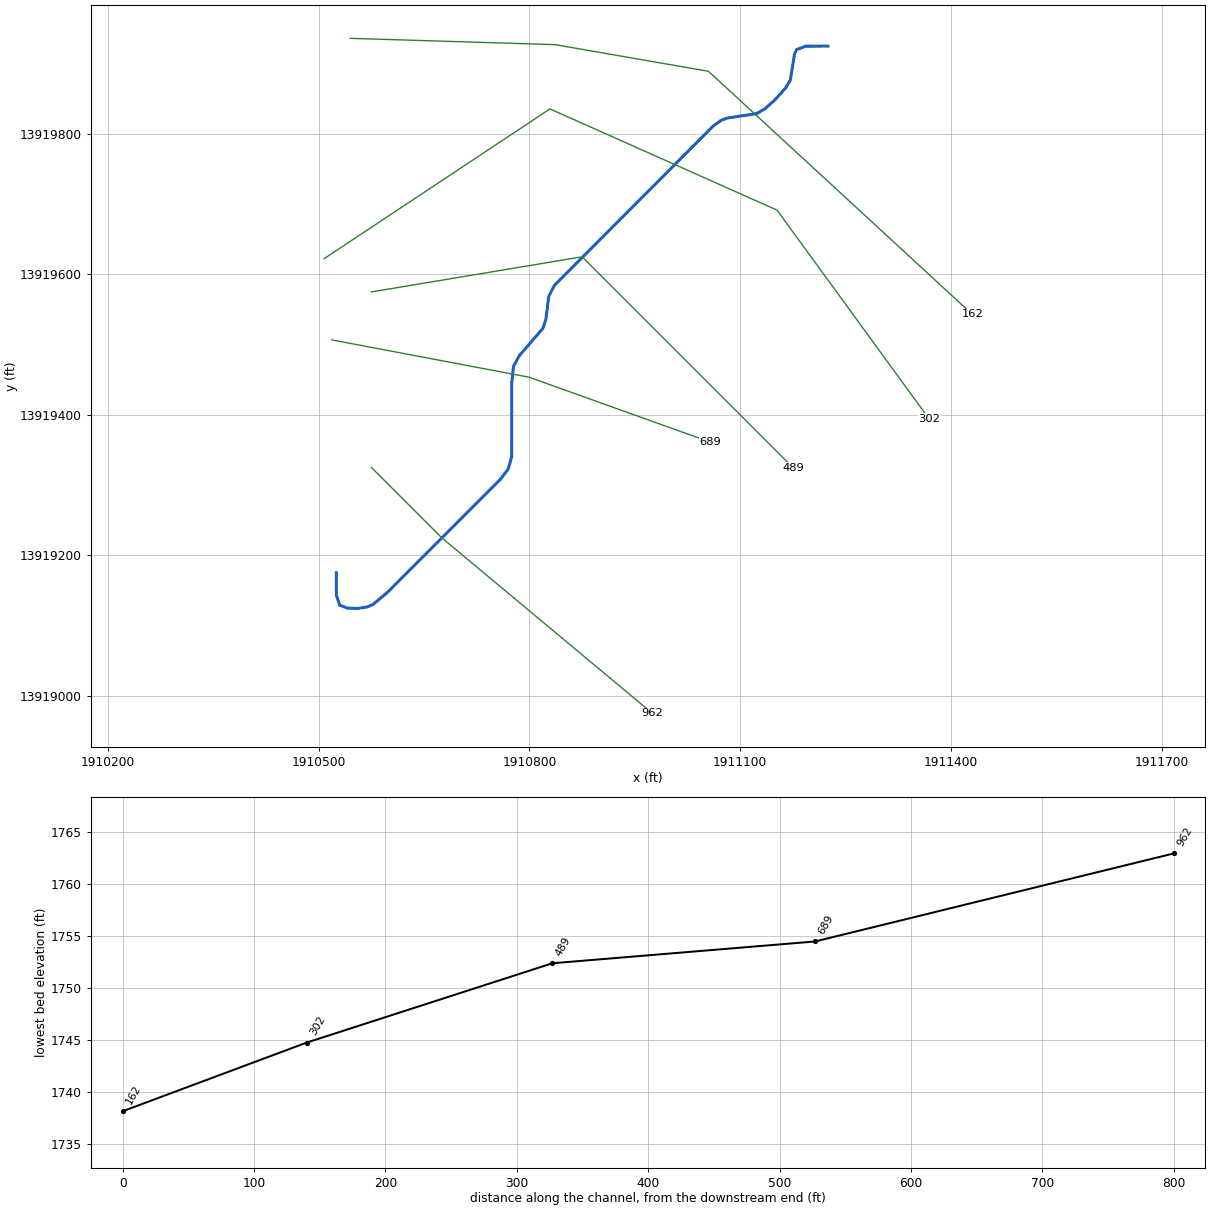
--- Stream0535.prj (project) ---

Proj Title=Stream0535 Base Level Engineering
Current Plan=p01
Default Exp/Contr=0.3,0.1
English Units
Geom File=g01
Flow File=f01
Plan File=p01
BEGIN DESCRIPTION:
Stream0535
END DESCRIPTION:

--- Stream0535.p01 (plan) ---

Plan Title=Multiple Run
Short Identifier=Multiple
Geom File=g01
Flow File=f01
Subcritical Flow
K Sum by GR= 0
Std Step Tol= 0.01
Critical Tol= 0.01
Num of Std Step Trials= 20
Max Error Tol= 0.3
Flow Tol Ratio= 0.001
Split Flow NTrial= 30
Split Flow Tol= 0.02
Split Flow Ratio= 0.02
Log Output Level= 0
Friction Slope Method= 1
Unsteady Friction Slope Method= 2
Unsteady Bridges Friction Slope Method= 1
Parabolic Critical Depth
Global Vel Dist=  1 , 1 , 1
Global Log Level= 0
CheckData=True
Encroach Param= -1, 0, 0, 0
BEGIN DESCRIPTION:
Multiple Run
END DESCRIPTION:

--- Stream0535.f01 (steady flow) ---

Flow Title=Multiple
Number of Profiles=7
Profile Names=10-year,25-year,50-year,1pct_min,100-year,1pct_plu,500-year
River Rch & RM= Stream0535,Reach-1,962
     597     986    1346     893    1783    3557    3075
Boundary for River Rch & Prof#=Stream0535,Reach-1,1
Up Type=0
Dn Type=3
Dn Slope=0.005
Boundary for River Rch & Prof#=Stream0535,Reach-1,2
Up Type=0
Dn Type=3
Dn Slope=0.005
Boundary for River Rch & Prof#=Stream0535,Reach-1,3
Up Type=0
Dn Type=3
Dn Slope=0.005
Boundary for River Rch & Prof#=Stream0535,Reach-1,4
Up Type=0
Dn Type=3
Dn Slope=0.005
Boundary for River Rch & Prof#=Stream0535,Reach-1,5
Up Type=0
Dn Type=3
Dn Slope=0.005
Boundary for River Rch & Prof#=Stream0535,Reach-1,6
Up Type=0
Dn Type=3
Dn Slope=0.005
Boundary for River Rch & Prof#=Stream0535,Reach-1,7
Up Type=0
Dn Type=3
Dn Slope=0.005

--- Stream0535.g01 (geometry) ---

Geom Title=Existing Conditions

River Reach=Stream0535,Reach-1
Reach XY= 30
      1910525.00     13919175.00      1910525.07     13919142.63
      1910529.92     13919128.93      1910540.94     13919124.82
      1910554.78     13919124.31      1910568.79     13919126.42
      1910577.13     13919129.98      1910598.37     13919147.73
      1910758.57     13919308.24      1910769.53     13919322.55
      1910774.60     13919340.16      1910774.67     13919445.14
      1910777.25     13919469.07      1910785.80     13919484.67
      1910818.86     13919522.83      1910823.28     13919535.71
      1910827.50     13919568.97      1910835.76     13919584.68
      1911061.80     13919811.37      1911072.73     13919819.14
      1911081.08     13919822.46      1911123.56     13919828.90
      1911134.99     13919835.66      1911148.83     13919847.90
      1911164.43     13919865.11      1911171.32     13919876.56
      1911177.25     13919913.18      1911180.34     13919920.04
      1911193.47     13919924.91      1911225.00     13919925.00

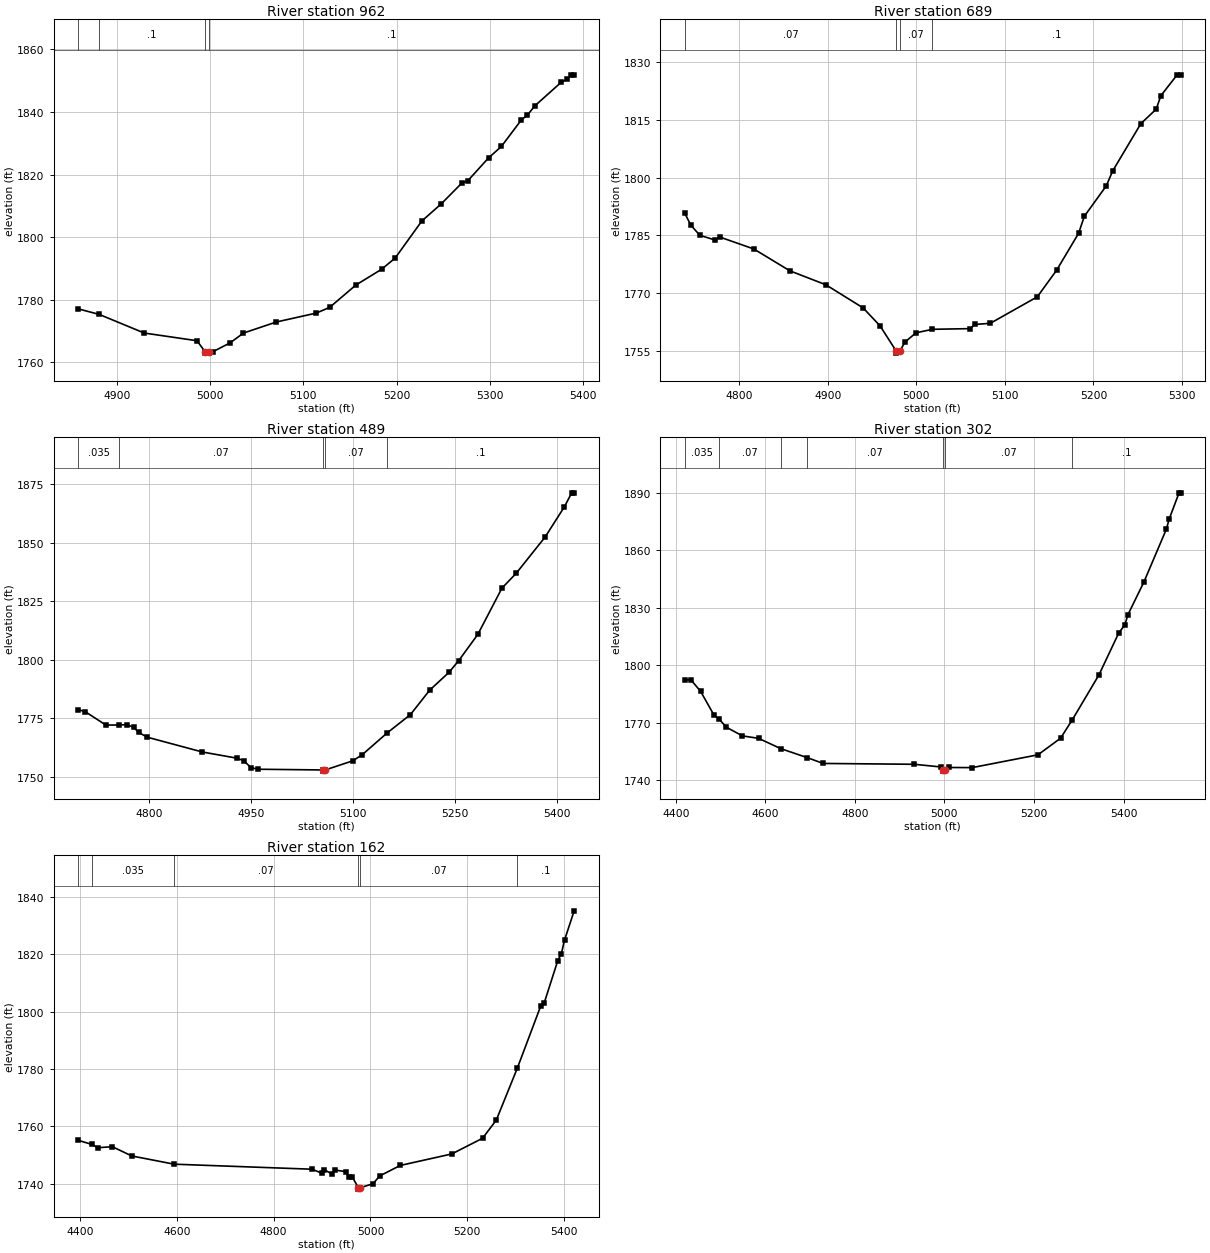
Type RM Length L Ch R = 1,962,273,273,273
BEGIN DESCRIPTION:
Stream0535 2.0
END DESCRIPTION:
XS GIS Cut Line= 3
      1910574.98     13919325.02      1910675.00     13919225.00
      1910975.03     13918974.97
#Sta/Elev= 30
  4858.5 1777.10  4880.8 1775.35  4929.2 1769.39  4985.8 1766.93  4994.4 1763.47
  4994.7 1762.97  4998.2 1762.97  4998.4 1763.47  5003.2 1763.47  5021.4 1766.26
  5035.7 1769.38  5070.9 1772.91  5113.8 1775.76  5128.2 1777.59  5156.2 1784.70
  5184.1 1789.79  5198.5 1793.36  5227.1 1805.19  5247.9 1810.65  5270.1 1817.33
  5276.6 1818.10  5298.7 1825.35  5312.4 1828.98  5333.8 1837.45  5340.3 1838.99
  5348.2 1841.93  5376.8 1849.54  5383.3 1850.42  5387.2 1851.87  5390.5 1851.87
#Mann=4,-1,0
  4858.5   0.035       0  4880.8     0.1       0  4994.4    0.05       0
  4998.4     0.1       0
Bank Sta=4994.4,4998.4
Exp/Cntr=0.3,0.1

Type RM Length L Ch R = 1,689,200,200,200
BEGIN DESCRIPTION:
Mapping XS 563725b1
END DESCRIPTION:
XS GIS Cut Line= 3
      1910518.33     13919506.76      1910799.47     13919453.54
      1911057.40     13919361.18
#Sta/Elev= 30
  4738.4 1790.76  4745.2 1787.67  4755.4 1785.04  4772.7 1783.81  4777.8 1784.60
  4816.4 1781.49  4857.1 1775.83  4897.8 1772.21  4939.8 1766.22  4958.9 1761.58
  4977.3 1754.99  4977.5 1754.49  4981.3 1754.99  4987.1 1757.37  4999.6 1759.76
  5018.2 1760.67  5060.8 1760.84  5066.1 1761.92  5083.5 1762.22  5136.6 1769.09
  5158.4 1775.98  5183.3 1785.58  5189.7 1789.96  5214.6 1797.89  5221.6 1801.67
  5253.5 1813.97  5270.9 1817.75  5276.2 1821.25  5294.6 1826.65  5298.5 1826.65
#Mann=4,-1,0
  4738.4    0.07       0  4977.3    0.05       0  4981.3    0.07       0
  5018.2     0.1       0
Bank Sta=4977.3,4981.3
Exp/Cntr=0.3,0.1

Type RM Length L Ch R = 1,489,187,187,187
BEGIN DESCRIPTION:
Stream0535 1.0
END DESCRIPTION:
XS GIS Cut Line= 3
      1910575.04     13919575.01      1910875.00     13919625.00
      1911175.02     13919324.98
#Sta/Elev= 30
  4696.3 1778.64  4706.4 1777.79  4736.8 1772.07  4756.2 1772.10  4767.2 1772.25
  4777.4 1771.15  4785.0 1768.90  4797.6 1766.88  4878.7 1760.55  4929.4 1757.92
  4939.6 1756.80  4949.7 1753.92  4959.8 1753.20  5055.0 1752.89  5055.2 1752.39
  5059.0 1752.89  5099.4 1756.79  5113.5 1759.43  5149.5 1768.59  5184.2 1776.55
  5212.5 1786.99  5240.8 1794.58  5255.0 1799.55  5283.2 1810.81  5318.6 1830.56
  5339.8 1836.98  5382.2 1852.46  5410.5 1865.39  5421.1 1871.28  5424.7 1871.28
#Mann=5,-1,0
  4696.3   0.035       0  4756.2    0.07       0  5055.0    0.05       0
  5059.0    0.07       0  5149.5     0.1       0
Bank Sta=5055,5059
Exp/Cntr=0.3,0.1

Type RM Length L Ch R = 1,302,140,140,140
BEGIN DESCRIPTION:
Stream0535 0.0
END DESCRIPTION:
XS GIS Cut Line= 4
      1910507.74     13919622.44      1910829.15     13919835.54
      1911152.36     13919691.49      1911368.81     13919394.36
#Sta/Elev= 30
  4420.3 1792.56  4434.5 1792.20  4455.5 1786.44  4485.6 1773.92  4497.5 1771.75
  4513.0 1767.67  4549.0 1763.13  4585.0 1761.87  4634.3 1756.51  4693.6 1751.80
  4729.2 1748.76  4932.8 1748.32  4992.2 1746.92  4996.5 1745.25  4996.7 1744.75
  5000.5 1745.25  5009.4 1746.65  5061.9 1746.58  5208.9 1753.27  5259.2 1761.90
  5285.1 1771.36  5344.9 1794.91  5388.9 1816.68  5402.9 1821.14  5409.8 1826.38
  5445.4 1843.44  5495.6 1871.04  5501.9 1876.33  5523.9 1889.98  5527.4 1889.98
#Mann=7,-1,0
  4420.3   0.035       0  4497.5    0.07       0  4634.3   0.035       0
  4693.6    0.07       0  4996.5    0.05       0  5000.5    0.07       0
  5285.1     0.1       0
Bank Sta=4996.5,5000.5
Exp/Cntr=0.3,0.1

Type RM Length L Ch R = 1,162,0,0,0
BEGIN DESCRIPTION:
Stream0535 0.1
END DESCRIPTION:
XS GIS Cut Line= 4
      1910544.78     13919936.03      1910836.14     13919927.06
      1911054.79     13919889.13      1911430.51     13919542.95
#Sta/Elev= 30
  4396.5 1755.16  4424.4 1753.73  4436.7 1752.58  4466.8 1752.94  4506.8 1749.71
  4594.5 1746.84  4879.7 1745.08  4899.9 1743.65  4904.9 1744.87  4920.2 1743.45
  4927.0 1744.79  4948.6 1744.24  4955.3 1742.30  4962.7 1742.31  4974.9 1738.64
  4975.2 1738.14  4978.9 1738.64  5005.3 1740.02  5019.0 1742.73  5061.4 1746.39
  5168.0 1750.41  5231.5 1755.87  5259.9 1762.20  5303.4 1780.33  5351.7 1801.98
  5358.9 1803.05  5386.9 1817.81  5394.3 1820.24  5401.1 1825.09  5420.8 1835.20
#Mann=6,-1,0
  4396.5     0.1       0  4424.4   0.035       0  4594.5    0.07       0
  4974.9    0.05       0  4978.9    0.07       0  5303.4     0.1       0
Bank Sta=4974.9,4978.9
Exp/Cntr=0.3,0.1

Chan Stop Cuts=-1