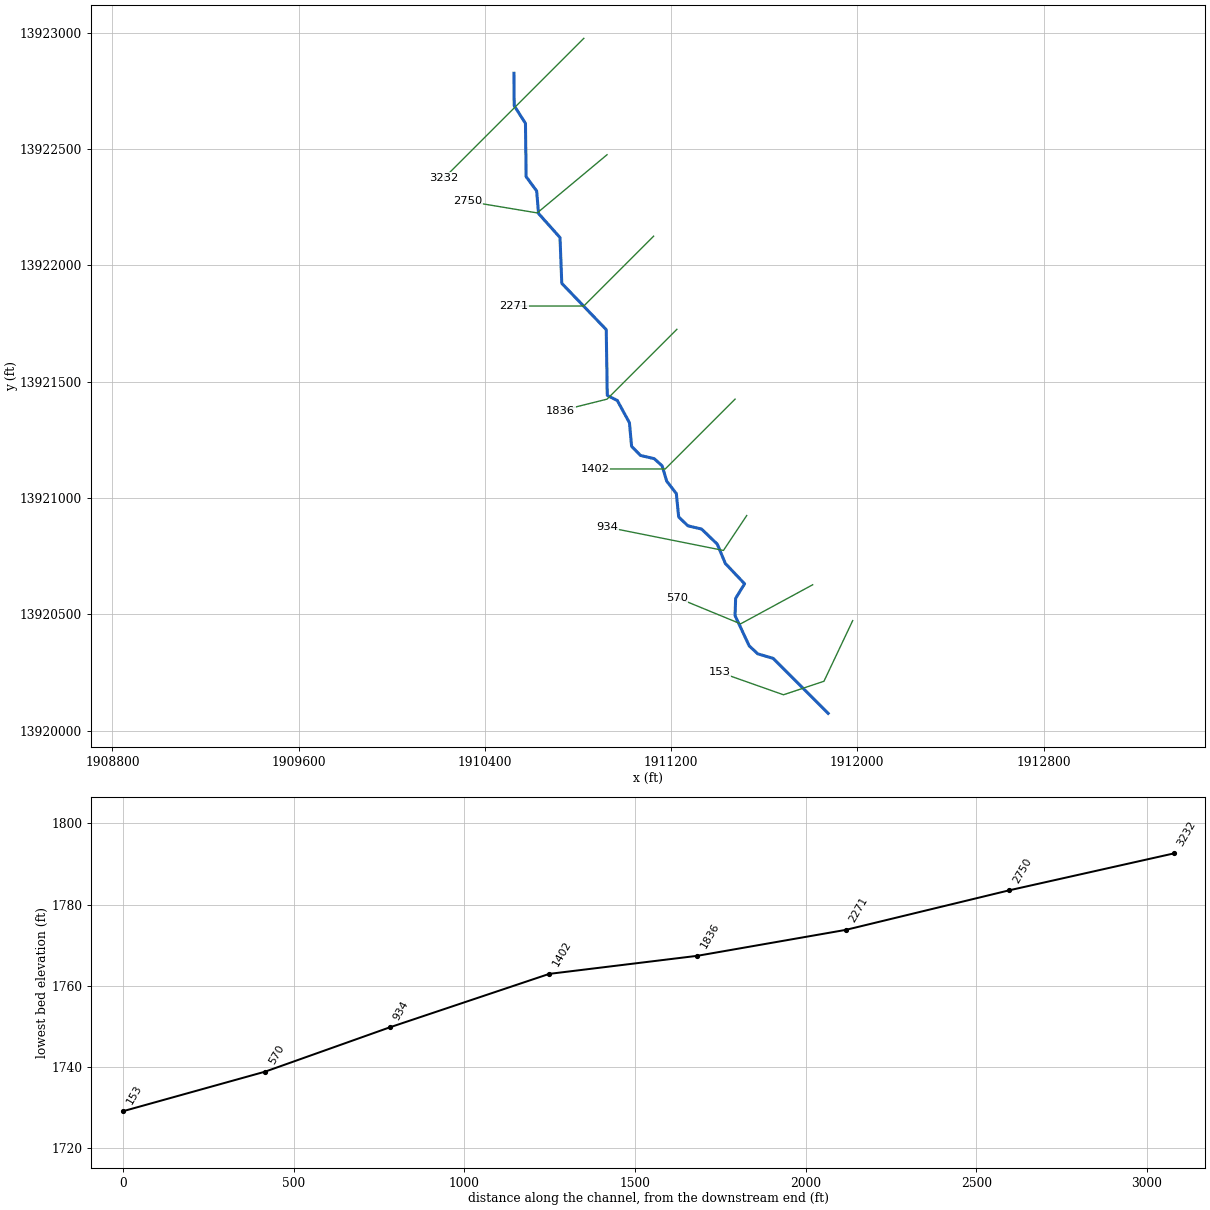
--- Stream0536.prj (project) ---

Proj Title=Stream0536 Base Level Engineering
Current Plan=p01
Default Exp/Contr=0.3,0.1
English Units
Geom File=g01
Flow File=f01
Plan File=p01
BEGIN DESCRIPTION:
Stream0536
END DESCRIPTION:

--- Stream0536.p01 (plan) ---

Plan Title=Multiple Run
Short Identifier=Multiple
Geom File=g01
Flow File=f01
Subcritical Flow
K Sum by GR= 0
Std Step Tol= 0.01
Critical Tol= 0.01
Num of Std Step Trials= 20
Max Error Tol= 0.3
Flow Tol Ratio= 0.001
Split Flow NTrial= 30
Split Flow Tol= 0.02
Split Flow Ratio= 0.02
Log Output Level= 0
Friction Slope Method= 1
Unsteady Friction Slope Method= 2
Unsteady Bridges Friction Slope Method= 1
Parabolic Critical Depth
Global Vel Dist=  1 , 1 , 1
Global Log Level= 0
CheckData=True
Encroach Param= -1, 0, 0, 0
BEGIN DESCRIPTION:
Multiple Run
END DESCRIPTION:

--- Stream0536.f01 (steady flow) ---

Flow Title=Multiple
Number of Profiles=7
Profile Names=10-year,25-year,50-year,1pct_min,100-year,1pct_plu,500-year
River Rch & RM= Stream0536,Reach-1,3232
     735    1220    1670    1107    2210    4409    3815
Boundary for River Rch & Prof#=Stream0536,Reach-1,1
Up Type=0
Dn Type=3
Dn Slope=0.005
Boundary for River Rch & Prof#=Stream0536,Reach-1,2
Up Type=0
Dn Type=3
Dn Slope=0.005
Boundary for River Rch & Prof#=Stream0536,Reach-1,3
Up Type=0
Dn Type=3
Dn Slope=0.005
Boundary for River Rch & Prof#=Stream0536,Reach-1,4
Up Type=0
Dn Type=3
Dn Slope=0.005
Boundary for River Rch & Prof#=Stream0536,Reach-1,5
Up Type=0
Dn Type=3
Dn Slope=0.005
Boundary for River Rch & Prof#=Stream0536,Reach-1,6
Up Type=0
Dn Type=3
Dn Slope=0.005
Boundary for River Rch & Prof#=Stream0536,Reach-1,7
Up Type=0
Dn Type=3
Dn Slope=0.005

--- Stream0536.g01 (geometry) ---

Geom Title=Existing Conditions

River Reach=Stream0536,Reach-1
Reach XY= 30
      1910525.00     13922825.00      1910526.17     13922685.48
      1910574.48     13922609.78      1910577.26     13922380.94
      1910622.64     13922319.02      1910630.54     13922222.58
      1910722.93     13922119.14      1910730.46     13921922.55
      1910921.46     13921723.54      1910925.92     13921440.94
      1910968.97     13921419.21      1911021.18     13921323.44
      1911030.42     13921222.33      1911068.64     13921183.03
      1911127.51     13921169.24      1911161.52     13921138.56
      1911181.15     13921072.85      1911222.67     13921019.03
      1911232.74     13920918.55      1911272.43     13920880.74
      1911331.04     13920866.84      1911398.73     13920801.88
      1911433.20     13920718.95      1911515.85     13920631.73
      1911477.37     13920569.11      1911474.90     13920495.10
      1911535.63     13920365.00      1911572.46     13920330.75
      1911638.20     13920311.36      1911875.00     13920075.00

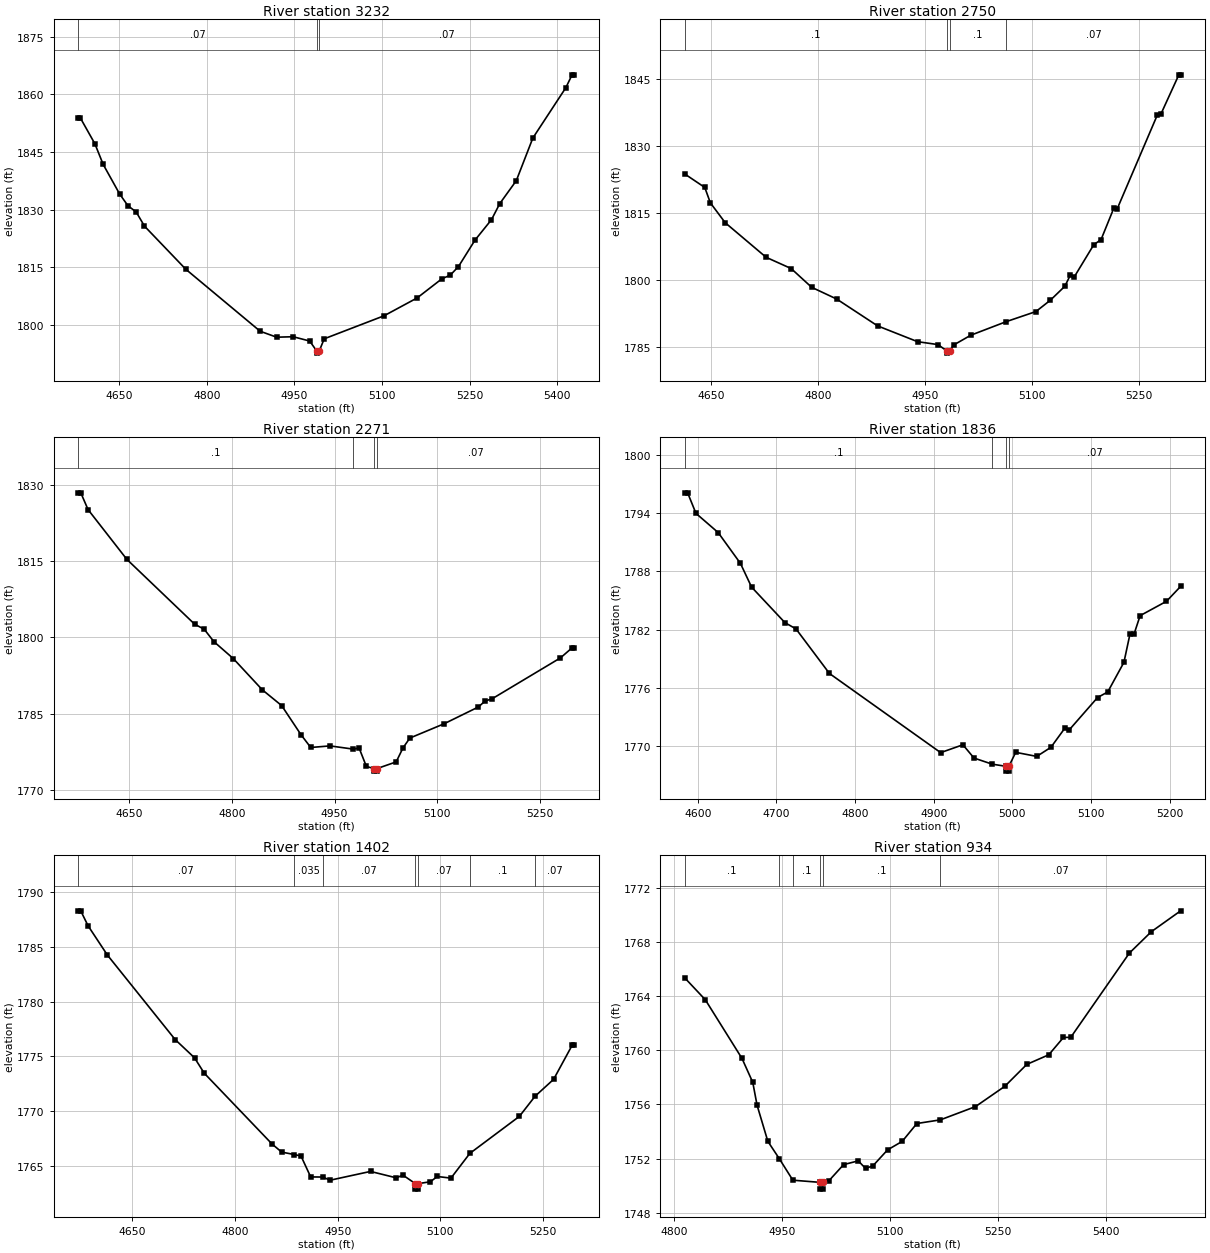
Type RM Length L Ch R = 1,3232,482,482,482
BEGIN DESCRIPTION:
Stream0536 7.0
END DESCRIPTION:
XS GIS Cut Line= 3
      1910825.02     13922975.02      1910525.00     13922675.00
      1910224.97     13922374.97
#Sta/Elev= 30
  4580.2 1853.82  4583.8 1853.82  4608.5 1847.14  4622.7 1841.76  4650.9 1834.05
  4665.1 1830.99  4679.2 1829.37  4693.4 1825.68  4764.1 1814.45  4891.4 1798.30
  4919.6 1796.75  4947.9 1796.87  4976.2 1795.75  4988.4 1793.10  4988.6 1792.60
  4992.4 1793.10  5001.0 1796.33  5103.5 1802.33  5160.1 1806.98  5202.5 1811.97
  5216.6 1812.89  5230.8 1815.15  5259.1 1822.04  5287.3 1827.36  5301.5 1831.55
  5329.8 1837.53  5358.1 1848.63  5414.6 1861.75  5425.2 1865.09  5428.8 1865.09
#Mann=3,-1,0
  4580.2    0.07       0  4988.4    0.05       0  4992.4    0.07       0
Bank Sta=4988.4,4992.4
Exp/Cntr=0.3,0.1

Type RM Length L Ch R = 1,2750,479,479,479
BEGIN DESCRIPTION:
Stream0536 6.0
END DESCRIPTION:
XS GIS Cut Line= 3
      1910924.99     13922474.99      1910625.00     13922225.00
      1910325.04     13922274.99
#Sta/Elev= 30
  4613.7 1823.76  4641.7 1820.74  4649.5 1817.28  4670.3 1812.82  4727.6 1805.05
  4762.7 1802.52  4791.4 1798.31  4826.5 1795.67  4883.8 1789.64  4939.8 1786.09
  4968.4 1785.44  4980.7 1784.02  4981.0 1783.52  4984.7 1784.02  4990.5 1785.36
  5014.3 1787.54  5064.1 1790.60  5105.6 1792.86  5125.9 1795.42  5146.1 1798.54
  5153.7 1801.01  5158.8 1800.51  5186.7 1807.89  5196.8 1809.01  5214.6 1816.04
  5219.6 1815.99  5275.4 1836.92  5280.5 1837.16  5305.8 1846.04  5308.3 1846.04
#Mann=4,-1,0
  4613.7     0.1       0  4980.7    0.05       0  4984.7     0.1       0
  5064.1    0.07       0
Bank Sta=4980.7,4984.7
Exp/Cntr=0.3,0.1

Type RM Length L Ch R = 1,2271,435,435,435
BEGIN DESCRIPTION:
Stream0536 5.0
END DESCRIPTION:
XS GIS Cut Line= 3
      1911125.03     13922125.03      1910825.00     13921825.00
      1910525.01     13921825.00
#Sta/Elev= 30
  4575.7 1828.37  4579.3 1828.37  4589.9 1825.08  4646.5 1815.33  4745.5 1802.61
  4759.6 1801.60  4773.7 1799.18  4802.0 1795.86  4844.4 1789.73  4872.7 1786.63
  4901.0 1780.91  4915.2 1778.41  4943.4 1778.72  4977.2 1778.09  4985.9 1778.29
  4996.5 1774.68  5008.0 1774.27  5008.3 1773.77  5011.8 1773.77  5012.0 1774.27
  5040.0 1775.58  5050.0 1778.34  5060.0 1780.26  5110.0 1783.06  5160.0 1786.35
  5170.0 1787.53  5180.0 1787.95  5280.0 1795.99  5297.5 1798.02  5300.0 1798.02
#Mann=4,-1,0
  4575.7     0.1       0  4977.2    0.07       0  5008.0    0.05       0
  5012.0    0.07       0
Bank Sta=5008,5012
Exp/Cntr=0.3,0.1

Type RM Length L Ch R = 1,1836,434,434,434
BEGIN DESCRIPTION:
Stream0536 4.0
END DESCRIPTION:
XS GIS Cut Line= 3
      1911225.01     13921725.01      1910925.00     13921425.00
      1910725.04     13921375.01
#Sta/Elev= 30
  4583.6 1796.11  4587.2 1796.11  4597.8 1793.99  4626.0 1792.01  4654.3 1788.83
  4668.5 1786.38  4710.9 1782.71  4725.0 1782.06  4767.5 1777.46  4908.9 1769.29
  4937.2 1770.10  4951.3 1768.73  4974.4 1768.10  4991.7 1767.88  4992.0 1767.38
  4995.5 1767.38  4995.7 1767.88  5004.3 1769.32  5031.1 1768.90  5049.1 1769.84
  5067.2 1771.86  5072.3 1771.63  5108.4 1774.98  5121.3 1775.55  5141.9 1778.61
  5149.6 1781.53  5154.8 1781.53  5162.5 1783.43  5196.0 1784.91  5214.0 1786.45
#Mann=4,-1,0
  4583.6     0.1       0  4974.4    0.07       0  4991.7    0.05       0
  4995.7    0.07       0
Bank Sta=4991.7,4995.7
Exp/Cntr=0.3,0.1

Type RM Length L Ch R = 1,1402,468,468,468
BEGIN DESCRIPTION:
Stream0536 3.0
END DESCRIPTION:
XS GIS Cut Line= 3
      1911475.01     13921425.01      1911175.00     13921125.00
      1910874.97     13921125.00
#Sta/Elev= 30
  4571.2 1788.25  4574.7 1788.25  4585.4 1786.89  4613.6 1784.23  4712.6 1776.54
  4740.9 1774.88  4755.1 1773.48  4854.1 1767.04  4868.2 1766.30  4886.5 1766.08
  4896.5 1765.94  4910.6 1764.04  4928.3 1764.03  4938.9 1763.74  4998.0 1764.54
  5035.5 1763.96  5045.5 1764.20  5063.5 1763.43  5063.7 1762.93  5067.2 1762.93
  5067.5 1763.43  5085.5 1763.60  5095.5 1764.08  5115.5 1763.93  5143.1 1766.18
  5215.5 1769.55  5238.4 1771.38  5265.5 1772.92  5293.0 1776.07  5295.5 1776.07
#Mann=7,-1,0
  4571.2    0.07       0  4886.5   0.035       0  4928.3    0.07       0
  5063.5    0.05       0  5067.5    0.07       0  5143.1     0.1       0
  5238.4    0.07       0
Bank Sta=5063.5,5067.5
Exp/Cntr=0.3,0.1

Type RM Length L Ch R = 1,934,364,364,364
BEGIN DESCRIPTION:
Stream0536 2.0
END DESCRIPTION:
XS GIS Cut Line= 3
      1911524.98     13920924.97      1911425.00     13920775.00
      1910925.05     13920874.99
#Sta/Elev= 30
  4814.4 1765.35  4842.9 1763.74  4894.0 1759.40  4909.0 1757.63  4915.0 1755.94
  4930.0 1753.27  4945.8 1752.00  4964.8 1750.40  5002.8 1750.24  5003.1 1749.74
  5006.6 1749.74  5006.8 1750.24  5015.0 1750.36  5035.4 1751.55  5055.8 1751.83
  5066.0 1751.27  5076.2 1751.46  5096.6 1752.64  5117.0 1753.27  5137.4 1754.59
  5170.1 1754.86  5219.0 1755.84  5259.8 1757.34  5290.4 1758.96  5321.0 1759.67
  5341.4 1760.95  5351.6 1760.96  5433.2 1767.19  5463.8 1768.77  5504.5 1770.31
#Mann=6,-1,0
  4814.4     0.1       0  4945.8    0.07       0  4964.8     0.1       0
  5002.8    0.05       0  5006.8     0.1       0  5170.1    0.07       0
Bank Sta=5002.8,5006.8
Exp/Cntr=0.3,0.1

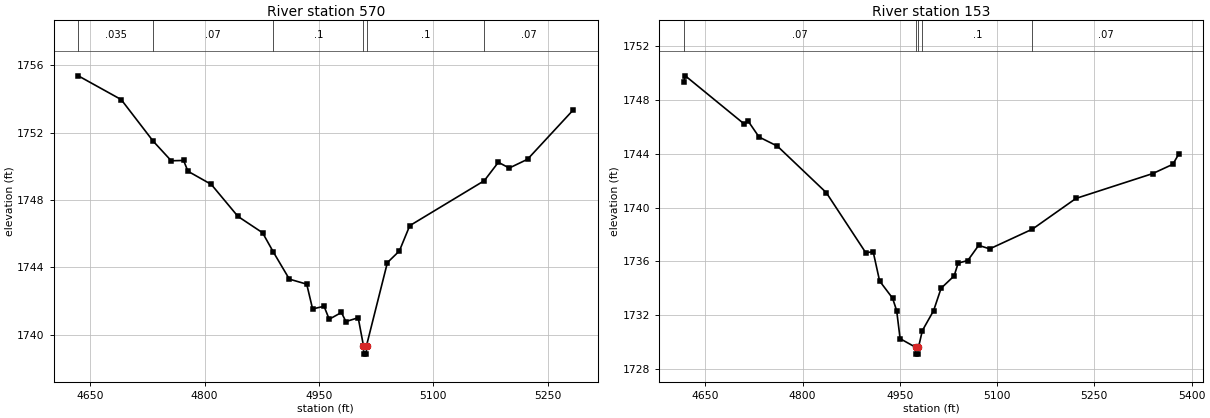
Type RM Length L Ch R = 1,570,417,417,417
BEGIN DESCRIPTION:
Stream0536 1.0
END DESCRIPTION:
XS GIS Cut Line= 3
      1911808.31     13920627.52      1911498.81     13920459.56
      1911224.32     13920572.64
#Sta/Elev= 30
  4634.3 1755.37  4690.6 1753.96  4732.4 1751.50  4756.2 1750.33  4772.4 1750.35
  4778.1 1749.71  4808.7 1748.93  4843.7 1747.03  4876.0 1746.06  4890.2 1744.91
  4911.1 1743.31  4933.9 1743.01  4941.6 1741.54  4956.6 1741.70  4963.4 1740.93
  4979.4 1741.33  4985.3 1740.79  5001.4 1741.02  5008.3 1739.36  5008.6 1738.86
  5012.1 1738.86  5012.3 1739.36  5039.7 1744.29  5055.4 1744.98  5069.0 1746.48
  5166.8 1749.15  5185.2 1750.24  5199.5 1749.90  5223.5 1750.42  5283.3 1753.34
#Mann=6,-1,0
  4634.3   0.035       0  4732.4    0.07       0  4890.2     0.1       0
  5008.3    0.05       0  5012.3     0.1       0  5166.8    0.07       0
Bank Sta=5008.3,5012.3
Exp/Cntr=0.3,0.1

Type RM Length L Ch R = 1,153,0,0,0
BEGIN DESCRIPTION:
Stream0536 0.0
END DESCRIPTION:
XS GIS Cut Line= 4
      1911980.40     13920473.70      1911856.84     13920212.98
      1911682.87     13920154.91      1911408.39     13920251.78
#Sta/Elev= 30
  4616.8 1749.32  4619.3 1749.80  4710.3 1746.21  4715.8 1746.46  4733.0 1745.25
  4761.3 1744.57  4836.7 1741.11  4897.7 1736.63  4908.9 1736.73  4918.9 1734.54
  4938.9 1733.26  4945.2 1732.33  4950.5 1730.25  4974.8 1729.60  4975.1 1729.10
  4978.6 1729.10  4978.8 1729.60  4984.8 1730.85  5002.1 1732.33  5013.7 1734.00
  5033.8 1734.92  5040.0 1735.87  5054.8 1736.06  5071.6 1737.19  5088.7 1736.93
  5154.6 1738.40  5221.6 1740.68  5340.0 1742.53  5371.0 1743.22  5379.8 1743.95
#Mann=5,-1,0
  4616.8    0.07       0  4974.8    0.05       0  4978.8    0.07       0
  4984.8     0.1       0  5154.6    0.07       0
Bank Sta=4974.8,4978.8
Exp/Cntr=0.3,0.1

Chan Stop Cuts=-1