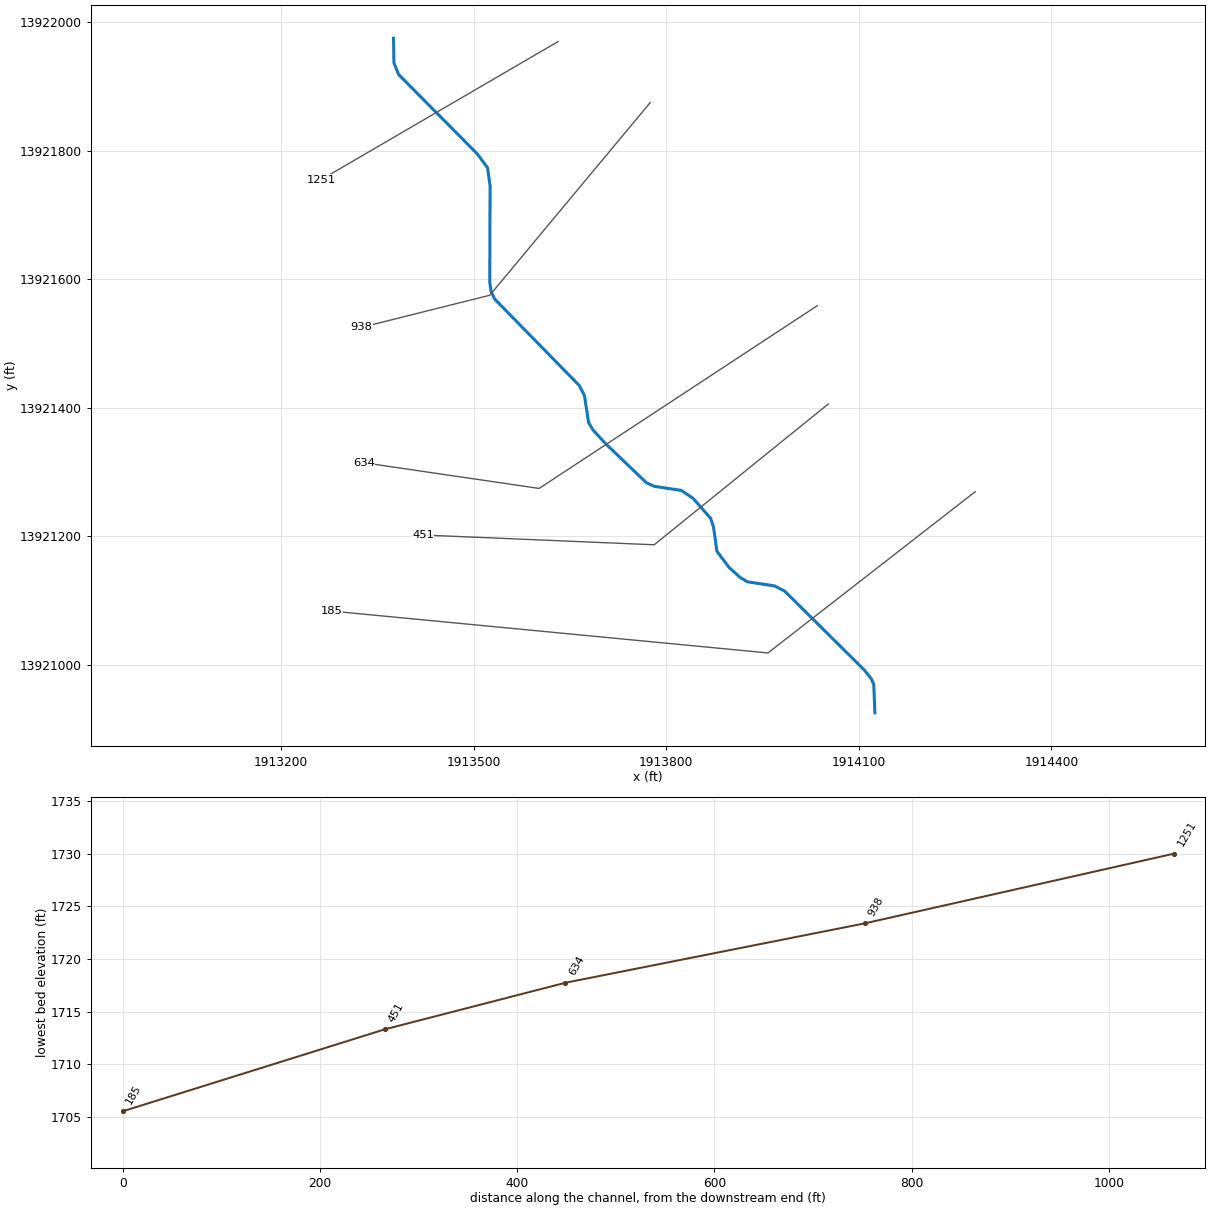
--- Stream0537.prj (project) ---

Proj Title=Stream0537 Base Level Engineering
Current Plan=p01
Default Exp/Contr=0.3,0.1
English Units
Geom File=g01
Flow File=f01
Plan File=p01
BEGIN DESCRIPTION:
Stream0537
END DESCRIPTION:

--- Stream0537.p01 (plan) ---

Plan Title=Multiple Run
Short Identifier=Multiple
Geom File=g01
Flow File=f01
Subcritical Flow
K Sum by GR= 0
Std Step Tol= 0.01
Critical Tol= 0.01
Num of Std Step Trials= 20
Max Error Tol= 0.3
Flow Tol Ratio= 0.001
Split Flow NTrial= 30
Split Flow Tol= 0.02
Split Flow Ratio= 0.02
Log Output Level= 0
Friction Slope Method= 1
Unsteady Friction Slope Method= 2
Unsteady Bridges Friction Slope Method= 1
Parabolic Critical Depth
Global Vel Dist=  1 , 1 , 1
Global Log Level= 0
CheckData=True
Encroach Param= -1, 0, 0, 0
BEGIN DESCRIPTION:
Multiple Run
END DESCRIPTION:

--- Stream0537.f01 (steady flow) ---

Flow Title=Multiple
Number of Profiles=7
Profile Names=10-year,25-year,50-year,1pct_min,100-year,1pct_plu,500-year
River Rch & RM= Stream0537,Reach-1,1251
     894    1507    2085    1397    2788    5563    4917
Boundary for River Rch & Prof#=Stream0537,Reach-1,1
Up Type=0
Dn Type=3
Dn Slope=0.005
Boundary for River Rch & Prof#=Stream0537,Reach-1,2
Up Type=0
Dn Type=3
Dn Slope=0.005
Boundary for River Rch & Prof#=Stream0537,Reach-1,3
Up Type=0
Dn Type=3
Dn Slope=0.005
Boundary for River Rch & Prof#=Stream0537,Reach-1,4
Up Type=0
Dn Type=3
Dn Slope=0.005
Boundary for River Rch & Prof#=Stream0537,Reach-1,5
Up Type=0
Dn Type=3
Dn Slope=0.005
Boundary for River Rch & Prof#=Stream0537,Reach-1,6
Up Type=0
Dn Type=3
Dn Slope=0.005
Boundary for River Rch & Prof#=Stream0537,Reach-1,7
Up Type=0
Dn Type=3
Dn Slope=0.005

--- Stream0537.g01 (geometry) ---

Geom Title=Existing Conditions

River Reach=Stream0537,Reach-1
Reach XY= 30
      1913375.00     13921975.00      1913375.59     13921936.84
      1913382.76     13921918.79      1913505.40     13921795.16
      1913521.46     13921773.54      1913525.43     13921745.18
      1913524.96     13921594.98      1913527.06     13921580.85
      1913532.81     13921568.81      1913664.22     13921434.68
      1913672.46     13921418.95      1913678.97     13921376.64
      1913685.77     13921365.30      1913704.58     13921344.77
      1913768.95     13921283.16      1913781.08     13921277.55
      1913823.57     13921271.11      1913842.05     13921258.50
      1913869.24     13921227.51      1913873.50     13921214.46
      1913878.90     13921176.46      1913897.86     13921151.17
      1913915.01     13921135.65      1913926.43     13921128.89
      1913968.91     13921122.45      1913984.66     13921114.22
      1914108.42     13920991.70      1914119.69     13920977.52
      1914123.32     13920968.86      1914125.00     13920925.00

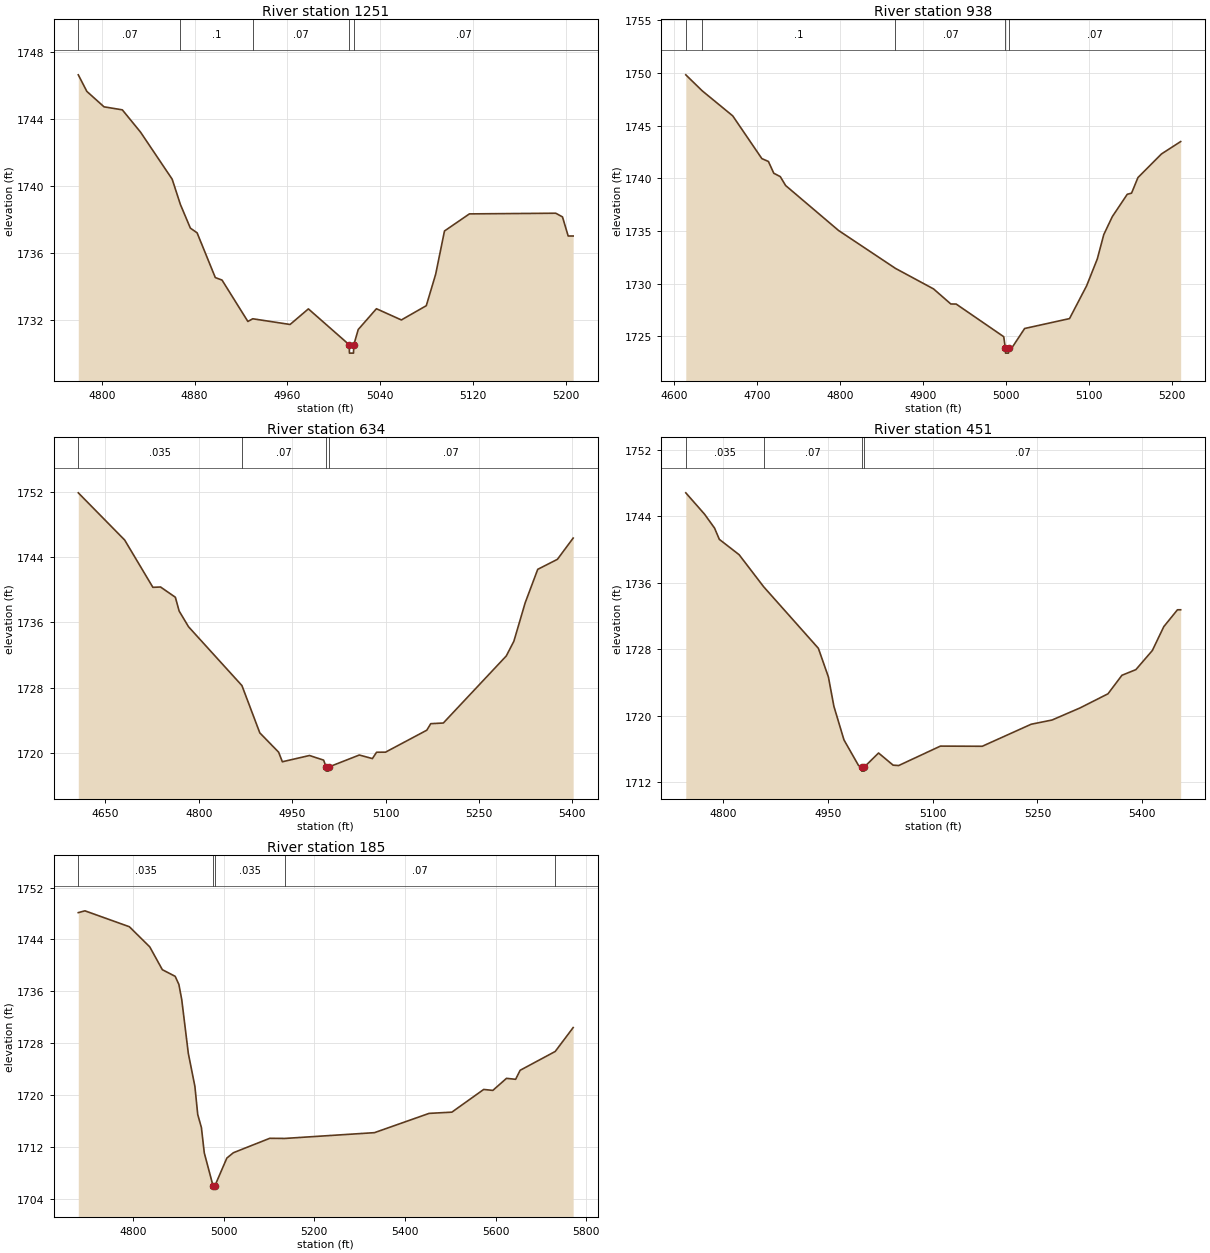
Type RM Length L Ch R = 1,1251,313,313,313
BEGIN DESCRIPTION:
Stream0537 3.0
END DESCRIPTION:
XS GIS Cut Line= 2
      1913631.39     13921969.93      1913262.48     13921755.10
#Sta/Elev= 30
  4779.6 1746.61  4787.0 1745.62  4801.8 1744.70  4817.6 1744.52  4833.3 1743.19
  4860.6 1740.38  4867.7 1738.87  4876.3 1737.46  4882.1 1737.18  4897.8 1734.51
  4903.6 1734.36  4925.9 1731.89  4930.1 1732.05  4962.3 1731.71  4978.1 1732.64
  5013.3 1730.50  5013.5 1730.00  5017.0 1730.00  5017.3 1730.50  5021.1 1731.41
  5036.8 1732.65  5058.3 1731.98  5079.8 1732.83  5087.9 1734.71  5095.5 1737.29
  5117.0 1738.31  5191.5 1738.35  5197.3 1738.13  5202.2 1736.99  5206.5 1736.99
#Mann=5,-1,0
  4779.6    0.07       0  4867.7     0.1       0  4930.1    0.07       0
  5013.3    0.05       0  5017.3    0.07       0
Bank Sta=5013.3,5017.3
Exp/Cntr=0.3,0.1

Type RM Length L Ch R = 1,938,304,304,304
BEGIN DESCRIPTION:
Stream0537 1.0
END DESCRIPTION:
XS GIS Cut Line= 3
      1913774.98     13921874.98      1913525.00     13921575.00
      1913325.04     13921525.01
#Sta/Elev= 30
  4614.0 1749.83  4633.8 1748.31  4670.6 1745.93  4705.7 1741.87  4713.6 1741.60
  4720.1 1740.48  4727.9 1740.16  4734.4 1739.31  4798.2 1735.04  4866.8 1731.44
  4912.7 1729.49  4933.5 1728.06  4940.0 1728.05  4997.3 1724.95  4999.2 1723.89
  4999.5 1723.39  5003.0 1723.39  5003.2 1723.89  5007.1 1723.89  5022.5 1725.73
  5076.6 1726.67  5097.3 1729.80  5110.1 1732.34  5117.9 1734.65  5128.2 1736.36
  5146.2 1738.48  5151.4 1738.59  5159.1 1740.07  5187.4 1742.31  5210.6 1743.49
#Mann=5,-1,0
  4614.0    0.07       0  4633.8     0.1       0  4866.8    0.07       0
  4999.2    0.05       0  5003.2    0.07       0
Bank Sta=4999.2,5003.2
Exp/Cntr=0.3,0.1

Type RM Length L Ch R = 1,634,183,183,183
BEGIN DESCRIPTION:
Stream0537 2.0
END DESCRIPTION:
XS GIS Cut Line= 3
      1914035.42     13921558.82      1913601.86     13921274.24
      1913328.69     13921314.22
#Sta/Elev= 30
  4606.5 1751.93  4681.0 1746.13  4726.3 1740.32  4738.6 1740.36  4762.4 1739.10
  4768.4 1737.42  4783.5 1735.48  4869.3 1728.25  4898.0 1722.44  4928.2 1720.07
  4934.2 1718.89  4977.8 1719.66  5000.5 1719.09  5004.5 1718.24  5004.7 1717.74
  5008.2 1717.74  5008.5 1718.24  5057.8 1719.72  5078.8 1719.28  5085.5 1720.06
  5099.9 1720.07  5166.2 1722.77  5172.5 1723.57  5192.7 1723.65  5293.8 1731.89
  5306.0 1733.70  5324.1 1738.41  5344.3 1742.53  5375.9 1743.76  5401.2 1746.37
#Mann=4,-1,0
  4606.5   0.035       0  4869.3    0.07       0  5004.5    0.05       0
  5008.5    0.07       0
Bank Sta=5004.5,5008.5
Exp/Cntr=0.3,0.1

Type RM Length L Ch R = 1,451,266,266,266
BEGIN DESCRIPTION:
Stream0537 4.0
END DESCRIPTION:
XS GIS Cut Line= 3
      1914052.37     13921405.68      1913781.14     13921186.52
      1913420.87     13921201.71
#Sta/Elev= 30
  4746.0 1746.80  4772.9 1744.23  4787.2 1742.56  4794.1 1741.20  4822.4 1739.36
  4857.6 1735.50  4936.0 1728.10  4950.4 1724.65  4958.3 1721.11  4972.7 1717.08
  4993.5 1714.01  4997.9 1713.82  4998.2 1713.32  5001.7 1713.32  5001.9 1713.82
  5022.3 1715.50  5043.1 1714.04  5051.1 1713.99  5110.9 1716.33  5170.9 1716.31
  5241.0 1718.96  5271.0 1719.47  5311.0 1720.92  5351.1 1722.62  5371.1 1724.85
  5391.1 1725.53  5414.7 1727.83  5431.1 1730.70  5450.7 1732.73  5455.3 1732.73
#Mann=4,-1,0
  4746.0   0.035       0  4857.6    0.07       0  4997.9    0.05       0
  5001.9    0.07       0
Bank Sta=4997.9,5001.9
Exp/Cntr=0.3,0.1

Type RM Length L Ch R = 1,185,0,0,0
BEGIN DESCRIPTION:
Stream0537 0.0
END DESCRIPTION:
XS GIS Cut Line= 3
      1914281.43     13921269.19      1913958.40     13921018.13
      1913278.53     13921083.28
#Sta/Elev= 30
  4679.1 1748.13  4693.8 1748.41  4791.8 1745.96  4836.8 1742.86  4864.6 1739.34
  4892.9 1738.32  4901.1 1737.07  4907.4 1734.74  4921.9 1726.46  4936.4 1721.38
  4942.7 1717.03  4950.8 1715.02  4957.2 1711.10  4976.5 1706.03  4976.8 1705.53
  4980.5 1706.03  5006.9 1710.31  5021.4 1711.14  5101.7 1713.36  5134.9 1713.34
  5332.7 1714.23  5453.3 1717.20  5503.5 1717.39  5573.8 1720.89  5593.9 1720.74
  5624.1 1722.60  5644.2 1722.45  5654.2 1723.84  5731.6 1726.74  5771.2 1730.42
#Mann=5,-1,0
  4679.1   0.035       0  4976.5   0.035       0  4980.5   0.035       0
  5134.9    0.07       0  5731.6   0.035       0
Bank Sta=4976.5,4980.5
Exp/Cntr=0.3,0.1

Chan Stop Cuts=-1