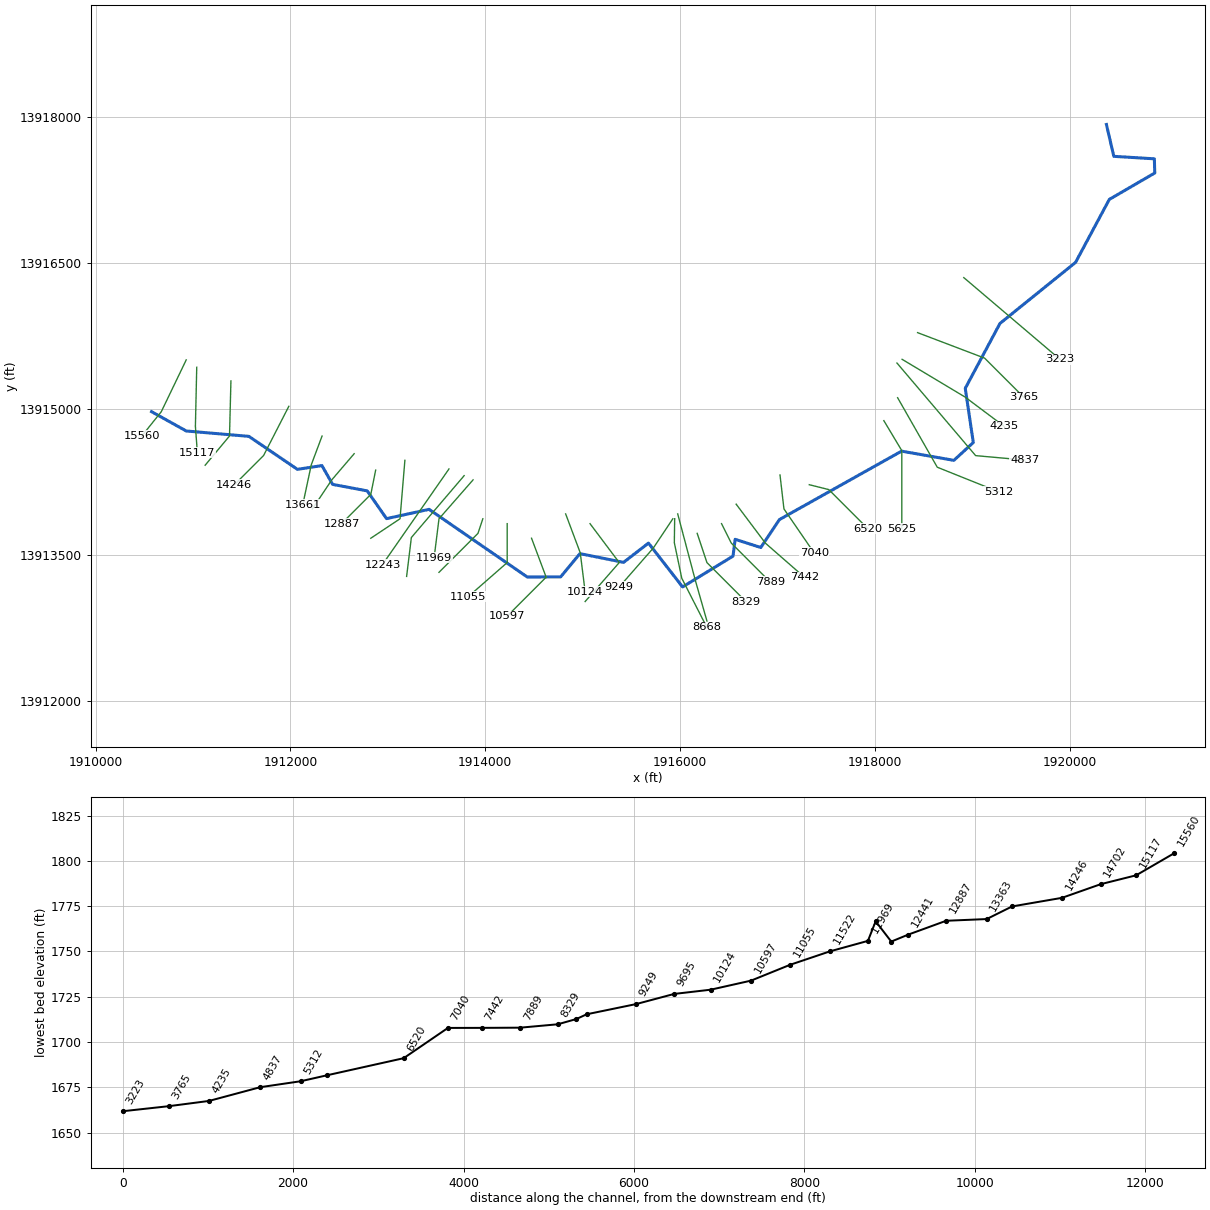
--- Stream0538.prj (project) ---

Proj Title=Stream0538 Base Level Engineering
Current Plan=p01
Default Exp/Contr=0.3,0.1
English Units
Geom File=g01
Flow File=f01
Plan File=p01
Y Axis Title=Elevation
X Axis Title(PF)=Main Channel Distance
X Axis Title(XS)=Station
BEGIN DESCRIPTION:
Stream0538
END DESCRIPTION:
DSS Export Rating Curves= 0
DSS Export Rating Curve Sorted= 0
DSS Export Volume Flow Curves= 0
DXF OffsetX= 0
DXF OffsetY= 0
DXF ScaleX= 1
DXF ScaleY= 10

--- Stream0538.p01 (plan) ---

Plan Title=Multiple Run
Short Identifier=Multiple
Geom File=g01
Flow File=f01
Subcritical Flow
K Sum by GR= 0
Std Step Tol= 0.01
Critical Tol= 0.01
Num of Std Step Trials= 20
Max Error Tol= 0.3
Flow Tol Ratio= 0.001
Split Flow NTrial= 30
Split Flow Tol= 0.02
Split Flow Ratio= 0.02
Log Output Level= 0
Friction Slope Method= 1
Unsteady Friction Slope Method= 2
Unsteady Bridges Friction Slope Method= 1
Parabolic Critical Depth
Global Vel Dist=  1 , 1 , 1
Global Log Level= 0
CheckData=True
Encroach Param= -1, 0, 0, 0
BEGIN DESCRIPTION:
Multiple Run
END DESCRIPTION:

--- Stream0538.f01 (steady flow) ---

Flow Title=Multiple
Number of Profiles=7
Profile Names=10-year,25-year,50-year,1pct_min,100-year,1pct_plu,500-year
River Rch & RM= Stream0538,Reach-1,15560
    1572    2740    3877    2650    5287   10550    9714
River Rch & RM= Stream0538,Reach-1,12060
    1723    3008    4260    2913    5812   11597   10688
River Rch & RM= Stream0538,Reach-1,8668
    2324    4121    5895    4067    8115   16191   15196
River Rch & RM= Stream0538,Reach-1,5625
    2930    5240    7538    5223   10421   20794   19698
Boundary for River Rch & Prof#=Stream0538,Reach-1,1
Up Type=0
Dn Type=3
Dn Slope=0.005
Boundary for River Rch & Prof#=Stream0538,Reach-1,2
Up Type=0
Dn Type=3
Dn Slope=0.005
Boundary for River Rch & Prof#=Stream0538,Reach-1,3
Up Type=0
Dn Type=3
Dn Slope=0.005
Boundary for River Rch & Prof#=Stream0538,Reach-1,4
Up Type=0
Dn Type=3
Dn Slope=0.005
Boundary for River Rch & Prof#=Stream0538,Reach-1,5
Up Type=0
Dn Type=3
Dn Slope=0.005
Boundary for River Rch & Prof#=Stream0538,Reach-1,6
Up Type=0
Dn Type=3
Dn Slope=0.005
Boundary for River Rch & Prof#=Stream0538,Reach-1,7
Up Type=0
Dn Type=3
Dn Slope=0.005

--- Stream0538.g01 (geometry) ---

Geom Title=Existing Conditions
Program Version=4.10

River Reach=Stream0538      ,Reach-1
Reach XY= 30
        1910575.       13914975.      1910931.11      13914776.8
      1911573.75     13914721.55      1912071.77     13914382.85
      1912323.51      13914421.4      1912433.15     13914228.37
      1912788.32     13914161.63      1912986.81     13913876.62
      1913423.36     13913971.86      1914430.85     13913277.06
      1914773.75     13913278.45      1914971.58     13913517.21
      1915419.07     13913427.23        1915675.       13913625.
        1916025.       13913175.      1916542.65     13913491.42
      1916564.57     13913664.17      1916827.57       13913580.
      1917018.94     13913866.86      1918272.58     13914569.59
      1918809.66      13914475.2      1919008.79     13914658.33
       1918926.2      13915214.5       1919282.5     13915881.32
      1920058.35     13916508.33      1920404.83      13917155.4
      1920871.26     13917426.56      1920867.06     13917572.18
      1920450.97     13917597.65        1920375.       13917925.

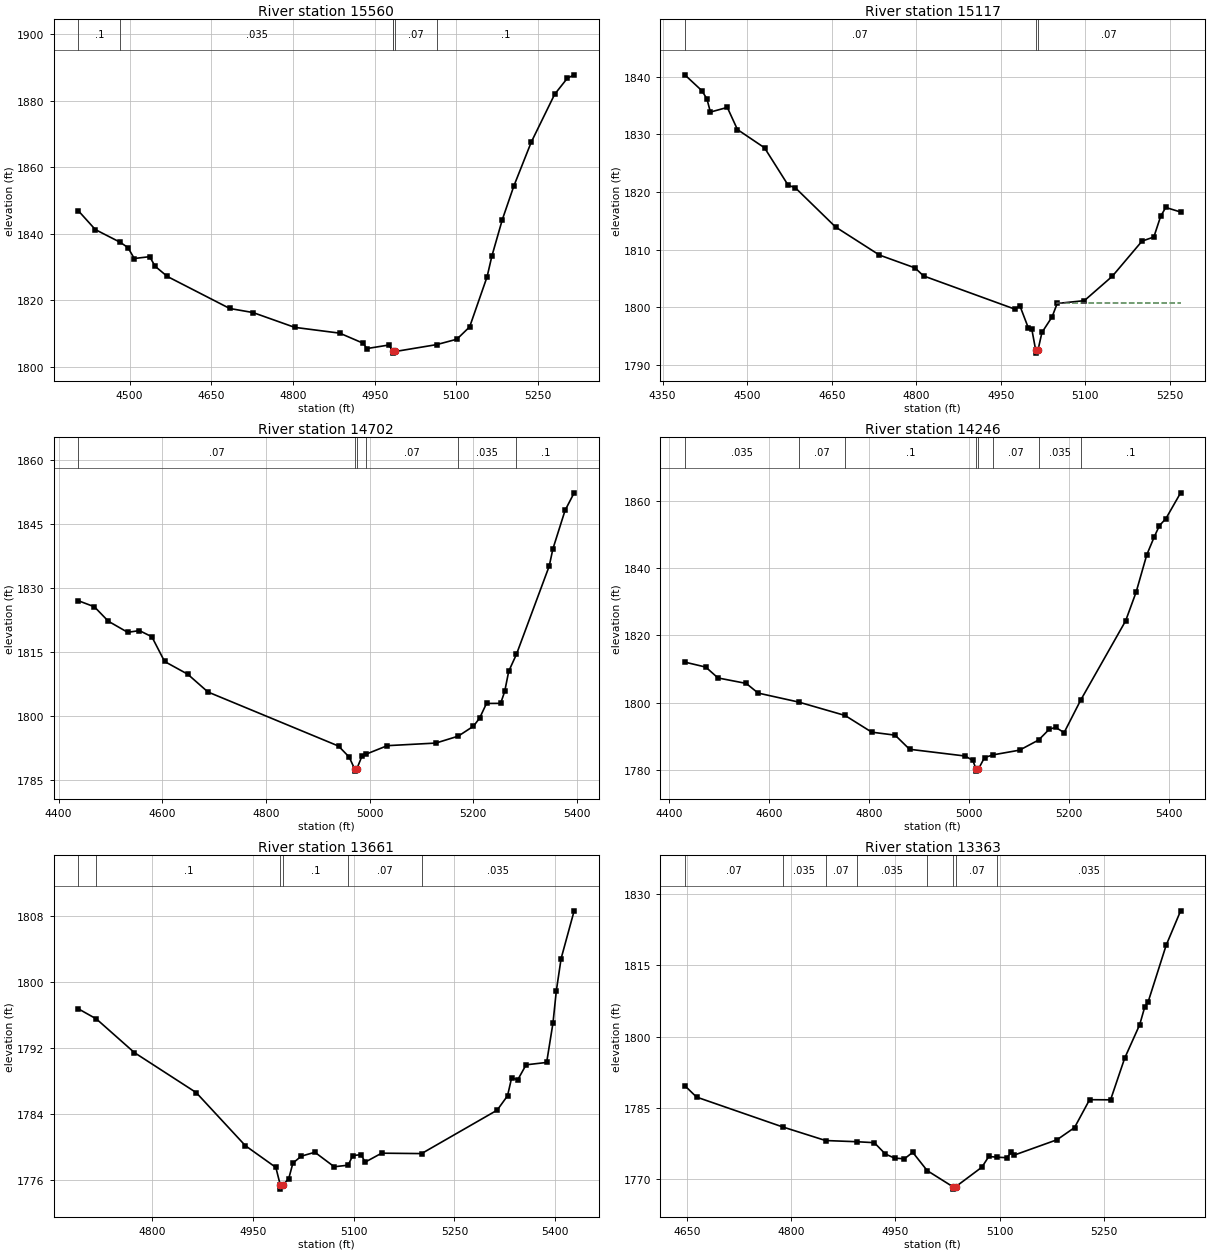
Type RM Length L Ch R = 1 ,15560   ,443,443,443
BEGIN DESCRIPTION:
Stream0538 31.0
END DESCRIPTION:
XS GIS Cut Line= 3
      1910930.76     13915507.05        1910675.       13914975.
      1910474.99     13914724.99
#Sta/Elev= 30
  4405.8 1846.89    4437 1841.24  4482.7 1837.42  4496.9 1835.83  4508.5 1832.55
  4536.8  1833.1  4546.8 1830.22  4569.2 1827.16  4683.8 1817.54  4726.5 1816.32
  4803.1 1811.87  4885.8 1810.13  4928.9  1807.1  4935.6  1805.5  4975.8 1806.56
    4984 1804.73  4984.2 1804.63  4984.4 1804.13  4988.2 1804.63  5063.9 1806.69
  5100.9 1808.31  5124.4 1812.02  5156.4 1827.06  5165.2 1833.28  5184.4 1844.24
  5205.5  1854.3  5237.5  1867.5  5280.5 1881.88  5303.6 1886.66  5316.3 1887.72
#Mann= 6 ,-1 , 0
  4405.8      .1       0  4482.7    .035       0    4984     .07       0
  4984.2     .05       0  4988.2     .07       0  5063.9      .1       0
Bank Sta=4984.2,4988.2
XS Rating Curve= 0 ,0
Exp/Cntr=0.3,0.1

Type RM Length L Ch R = 1 ,15117   ,415,415,415
BEGIN DESCRIPTION:
Stream0538 30.0
END DESCRIPTION:
XS GIS Cut Line= 3
      1911038.65     13915431.31        1911025.       13914825.
      1911045.26     13914552.61
#Sta/Elev= 30
  4389.4  1840.3  4419.8 1837.54  4428.7 1836.11  4434.8 1833.84  4464.8 1834.65
  4482.8 1830.81  4530.8 1827.65  4572.8 1821.15  4585.4 1820.72  4656.8 1813.92
  4734.8 1809.04  4797.8 1806.82  4812.9 1805.43  4974.9 1799.67  4983.9 1800.24
  4998.9 1796.39  5004.9 1796.25  5011.9 1792.54  5012.2 1792.04  5015.9 1792.54
    5023 1795.63    5041 1798.33    5050 1800.65  5098.2 1801.14  5147.8 1805.37
  5200.5 1811.46  5221.5 1812.18  5233.6 1815.77  5242.6  1817.3    5269 1816.51
#Mann= 3 ,-1 , 0
  4389.4     .07       0  5011.9     .05       0  5015.9     .07       0
#XS Ineff= 2 , 0
                         5049.95         1800.78
Permanent Ineff=
       F       F
Bank Sta=5011.9,5015.9
XS Rating Curve= 0 ,0
Exp/Cntr=0.3,0.1

Type RM Length L Ch R = 1 ,14702   ,456,456,456
BEGIN DESCRIPTION:
Stream0538 29.0
END DESCRIPTION:
XS GIS Cut Line= 3
      1911389.58     13915290.84        1911375.       13914725.
      1911125.03     13914425.03
#Sta/Elev= 30
  4438.2 1827.11  4469.1 1825.69  4496.1  1822.3  4533.4  1819.7  4556.1  1820.1
    4580 1818.66  4604.6 1812.86  4649.2 1809.88  4688.2 1805.71  4940.1 1793.03
  4960.6 1790.46  4971.3 1787.65  4971.5 1787.15  4975.3 1787.65  4985.3 1790.65
  4992.3 1791.08  5034.2 1793.12  5127.9 1793.73    5171 1795.35  5200.4 1797.68
  5212.3 1799.58  5225.6 1803.02  5252.9 1803.04  5260.7 1805.84  5268.5 1810.58
  5283.4 1814.55  5346.6 1835.24  5353.7 1839.27  5377.2  1848.3  5394.7 1852.41
#Mann= 6 ,-1 , 0
  4438.2     .07       0  4971.3     .05       0  4975.3     .07       0
  4992.3     .07       0    5171    .035       0  5283.4      .1       0
Bank Sta=4971.3,4975.3
XS Rating Curve= 0 ,0
Exp/Cntr=0.3,0.1

Type RM Length L Ch R = 1 ,14246   ,585,585,585
BEGIN DESCRIPTION:
Stream0538 28.0
END DESCRIPTION:
XS GIS Cut Line= 3
      1911983.84      13915030.3        1911725.       13914525.
        1911425.       13914225.
#Sta/Elev= 30
    4432 1812.02  4473.9 1810.54  4498.4 1807.31  4554.9 1805.68  4578.7 1802.81
  4659.9 1800.13  4752.6 1796.15    4806 1791.18  4852.8 1790.29  4881.7 1786.09
    4993 1784.08  5008.3 1782.76    5015 1780.09  5015.2 1779.59    5019 1780.09
  5031.7 1783.63  5049.5 1784.45  5101.8 1785.83  5139.9 1788.85  5161.2 1792.05
    5174 1792.61  5190.9 1791.05  5223.9 1800.67  5313.9 1824.27  5335.1  1832.9
  5356.2 1843.91  5371.1 1849.24  5381.6 1852.62  5394.6 1854.73    5424 1862.38
#Mann= 8 ,-1 , 0
    4432    .035       0  4659.9     .07       0  4752.6      .1       0
    5015     .05       0    5019      .1       0  5049.5     .07       0
  5139.9    .035       0  5223.9      .1       0
Bank Sta=5015,5019
XS Rating Curve= 0 ,0
Exp/Cntr=0.3,0.1

Type RM Length L Ch R = 1 ,13661   ,298,298,298
BEGIN DESCRIPTION:
Stream0538 27.0
END DESCRIPTION:
XS GIS Cut Line= 3
      1912324.99     13914724.97      1912214.46     13914430.11
      1912126.34       13914017.
#Sta/Elev= 30
  4690.7 1796.77  4717.5 1795.54    4774 1791.45  4865.9 1786.59  4939.1 1780.13
  4984.4 1777.49    4991 1775.35  4991.3 1774.85    4995 1775.35  5003.6 1776.14
  5009.8 1778.02  5022.3 1778.86  5042.5 1779.33  5071.2 1777.57  5091.9 1777.76
  5098.8 1778.93  5111.1 1779.04  5117.2 1778.13  5141.7 1779.22  5201.1 1779.17
  5313.5 1784.45  5328.9 1786.19    5335 1788.37  5344.2 1788.15  5356.5 1789.96
  5387.1 1790.25  5396.5 1795.04  5401.5 1798.97  5408.6 1802.88    5428 1808.68
#Mann= 6 ,-1 , 0
  4690.7     .07       0  4717.5      .1       0    4991     .05       0
    4995      .1       0  5091.9     .07       0  5201.1    .035       0
Bank Sta=4991,4995
XS Rating Curve= 0 ,0
Exp/Cntr=0.3,0.1

Type RM Length L Ch R = 1 ,13363   ,476,476,476
BEGIN DESCRIPTION:
Stream0538 26.0
END DESCRIPTION:
XS GIS Cut Line= 3
      1912654.32     13914543.27        1912425.       13914275.
      1912224.99     13913974.98
#Sta/Elev= 30
  4646.8 1789.66  4663.7 1787.26  4787.5 1780.98  4849.4 1778.11  4894.2 1777.86
  4919.5 1777.66  4935.3 1775.28  4948.8  1774.4  4962.9 1774.27  4974.8 1775.63
  4995.6 1771.78  5032.6 1768.38  5032.9 1767.88  5036.6 1768.38  5074.3  1772.5
  5084.3 1774.76    5096  1774.6  5110.3  1774.5  5116.7 1775.64    5121 1775.05
  5182.5 1778.28  5207.6 1780.83  5229.3 1786.71  5259.5 1786.68  5279.8 1795.45
  5301.4  1802.5  5308.7 1806.24  5313.6 1807.32  5339.5 1819.23  5360.3 1826.47
#Mann= 8 ,-1 , 0
  4646.8     .07       0  4787.5    .035       0  4849.4     .07       0
  4894.2    .035       0  4995.6     .07       0  5032.6     .05       0
  5036.6     .07       0    5096    .035       0
Bank Sta=5032.6,5036.6
XS Rating Curve= 0 ,0
Exp/Cntr=0.3,0.1

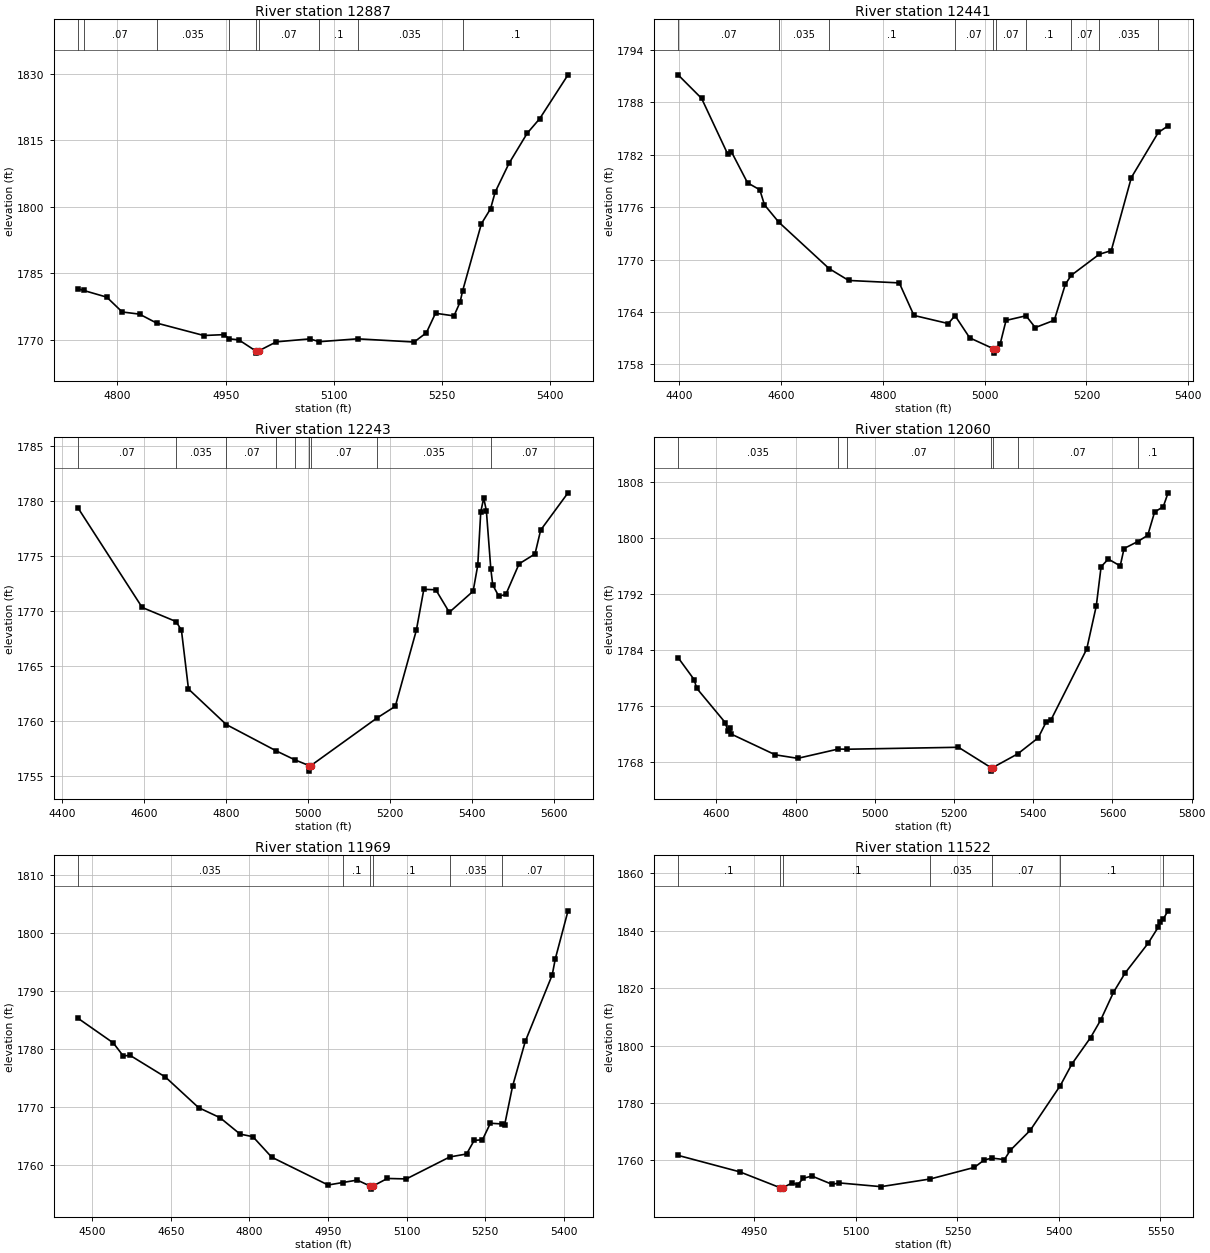
Type RM Length L Ch R = 1 ,12887   ,446,446,446
BEGIN DESCRIPTION:
Stream0538 25.0
END DESCRIPTION:
XS GIS Cut Line= 3
      1912874.99     13914374.96        1912825.       13914125.
      1912524.98     13913824.98
#Sta/Elev= 30
  4745.4 1781.47  4753.2 1781.09  4785.2 1779.58  4806.6 1776.23  4830.6 1775.74
  4854.2 1773.73  4919.8 1770.91  4947.8 1771.11  4955.1 1770.16  4968.2 1769.93
  4991.7 1767.43    4992 1766.93  4995.7 1767.43  5020.3 1769.48  5066.8 1770.15
  5079.7 1769.51  5132.8 1770.16  5211.2 1769.44  5228.2 1771.51  5240.9 1775.94
  5266.5 1775.34    5275 1778.46  5278.4 1780.94  5304.5 1796.16  5317.2 1799.54
  5323.6 1803.31  5342.7 1809.78  5368.1 1816.63  5385.3 1819.89  5424.6 1829.81
#Mann= 9 ,-1 , 0
  4745.4    .035       0  4753.2     .07       0  4854.2    .035       0
  4955.1     .07       0  4991.7     .05       0  4995.7     .07       0
  5079.7      .1       0  5132.8    .035       0  5278.4      .1       0
Bank Sta=4991.7,4995.7
XS Rating Curve= 0 ,0
Exp/Cntr=0.3,0.1

Type RM Length L Ch R = 1 ,12441   ,198,198,198
BEGIN DESCRIPTION:
Stream0538 24.0
END DESCRIPTION:
XS GIS Cut Line= 3
        1913175.     13914475.03        1913125.       13913875.
      1912824.97     13913674.98
#Sta/Elev= 30
  4397.7 1791.17  4443.9 1788.47  4495.1  1782.1  4502.6 1782.34  4534.2 1778.79
  4558.3 1777.99  4567.4 1776.27  4595.4 1774.29  4694.4 1768.96  4732.9  1767.6
  4832.3 1767.32  4861.1 1763.59  4928.6 1762.66  4941.8 1763.57  4970.7 1761.02
  5017.4 1759.77  5017.7 1759.27  5021.4 1759.77  5030.3 1760.27  5042.1 1763.02
  5081.3 1763.55  5099.5  1762.2  5136.9 1763.04  5158.5 1767.15    5170 1768.18
  5225.2  1770.6  5248.8 1771.02  5288.3  1779.4  5341.2 1784.56  5360.4 1785.32
#Mann= 10 ,-1 , 0
  4397.7     .07       0  4595.4    .035       0  4694.4      .1       0
  4941.8     .07       0  5017.4     .05       0  5021.4     .07       0
  5081.3      .1       0    5170     .07       0  5225.2    .035       0
  5341.2    .063       0
Bank Sta=5017.4,5021.4
XS Rating Curve= 0 ,0
Exp/Cntr=0.3,0.1

Type RM Length L Ch R = 1 ,12243   ,183,183,183
BEGIN DESCRIPTION:
Mapping XS bc61c4f0
END DESCRIPTION:
XS GIS Cut Line= 2
      1913627.19     13914386.43      1912945.45     13913405.22
#Sta/Elev= 30
    4439 1779.38  4595.4 1770.33  4677.9 1769.05  4691.1 1768.27  4708.3 1762.91
  4800.4 1759.68  4922.9 1757.27  4968.1 1756.46  5002.6 1755.94  5002.8 1755.44
  5006.6 1755.94  5167.8 1760.27  5212.7 1761.34  5263.9 1768.25  5282.2 1771.98
  5311.4 1771.94  5344.3 1769.89  5402.4 1771.81  5413.7 1774.17    5421 1779.02
  5428.2 1780.29  5434.7 1779.13  5445.5 1773.85  5450.2 1772.38  5464.9 1771.36
  5482.1 1771.51  5514.5  1774.3  5553.3  1775.2  5567.1 1777.37  5633.8 1780.76
#Mann= 9 ,-1 , 0
    4439     .07       0  4677.9    .035       0  4800.4     .07       0
  4922.9    .035       0  4968.1     .07       0  5002.6     .05       0
  5006.6     .07       0  5167.8    .035       0  5445.5     .07       0
Bank Sta=5002.6,5006.6
XS Rating Curve= 0 ,0
Exp/Cntr=0.3,0.1

Type RM Length L Ch R = 1 ,12060   ,91,91,91
BEGIN DESCRIPTION:
Stream0538 23.1
END DESCRIPTION:
XS GIS Cut Line= 3
      1913783.07     13914317.78      1913241.42     13913682.38
      1913192.81     13913283.07
#Sta/Elev= 30
  4503.2 1782.87  4543.7 1779.73  4550.1  1778.5  4622.4 1773.57  4628.5 1772.44
  4635.2 1772.78  4637.7 1771.93  4748.7 1768.97  4805.4 1768.47  4907.8  1769.8
  4928.6 1769.77  5211.2 1770.05  5293.3 1767.14  5293.5 1766.64  5297.4 1767.14
  5360.9 1769.11  5412.5  1771.4  5432.2 1773.62    5445 1773.99    5535 1784.09
  5559.2 1790.27  5571.3 1795.86  5589.4 1796.96  5619.6 1795.98  5629.3 1798.47
  5664.1 1799.47  5689.1 1800.36  5706.4 1803.68  5728.4 1804.46  5740.4 1806.43
#Mann= 7 ,-1 , 0
  4503.2    .035       0  4907.8     .07       0  4928.6     .07       0
  5293.3     .05       0  5297.4     .07       0  5360.9     .07       0
  5664.1      .1       0
Bank Sta=5293.3,5297.4
XS Rating Curve= 0 ,0
Exp/Cntr=0.3,0.1

Type RM Length L Ch R = 1 ,11969   ,447,447,447
BEGIN DESCRIPTION:
Stream0538 23.0
END DESCRIPTION:
XS GIS Cut Line= 3
      1913874.98     13914274.98        1913525.       13913875.
        1913475.     13913474.99
#Sta/Elev= 30
  4473.2  1785.3  4540.3 1781.06  4559.6 1778.79  4572.2 1778.92  4639.9 1775.16
  4703.1 1769.89  4744.1 1768.15  4782.3 1765.32  4806.7 1764.88  4842.6 1761.34
  4950.2 1756.54  4978.1 1756.97  5005.7 1757.39  5030.9 1756.33  5031.1 1755.83
    5035 1756.33  5063.2 1757.67  5099.4 1757.59  5182.2 1761.38  5214.3 1761.89
  5228.8 1764.24  5244.6 1764.34  5259.7  1767.2  5281.8 1767.07  5286.9 1766.91
    5302 1773.57  5326.2  1781.3  5377.6 1792.77  5383.6 1795.58  5407.8 1803.84
#Mann= 6 ,-1 , 0
  4473.2    .035       0  4978.1      .1       0  5030.9     .05       0
    5035      .1       0  5182.2    .035       0  5281.8     .07       0
Bank Sta=5030.9,5035
XS Rating Curve= 0 ,0
Exp/Cntr=0.3,0.1

Type RM Length L Ch R = 1 ,11522   ,467,467,467
BEGIN DESCRIPTION:
Stream0538 22.0
END DESCRIPTION:
XS GIS Cut Line= 3
      1913974.99     13913874.97        1913925.       13913725.
      1913524.98     13913324.98
#Sta/Elev= 30
  4837.4 1761.78  4928.5 1756.05  4988.1 1750.53  4988.3 1750.03  4992.2 1750.53
  5005.6 1752.16  5013.9 1751.57  5022.6 1753.82  5035.1 1754.58    5065 1751.69
  5075.6 1752.19  5137.2 1750.89  5210.2 1753.58    5275 1757.59  5289.8 1760.21
  5301.5 1760.82  5319.4 1760.32  5328.1 1763.53  5357.6 1770.51  5402.1 1786.11
  5419.2 1793.62  5446.7 1802.78  5461.6 1808.86  5480.6 1818.57  5497.8 1825.29
  5531.8 1835.65  5546.5 1841.17  5548.7 1842.87  5553.7 1843.93  5561.2 1846.93
#Mann= 7 ,-1 , 0
  4837.4      .1       0  4988.1     .05       0  4992.2      .1       0
  5210.2    .035       0  5301.5     .07       0  5402.1      .1       0
  5553.7     .07       0
Bank Sta=4988.1,4992.2
XS Rating Curve= 0 ,0
Exp/Cntr=0.3,0.1

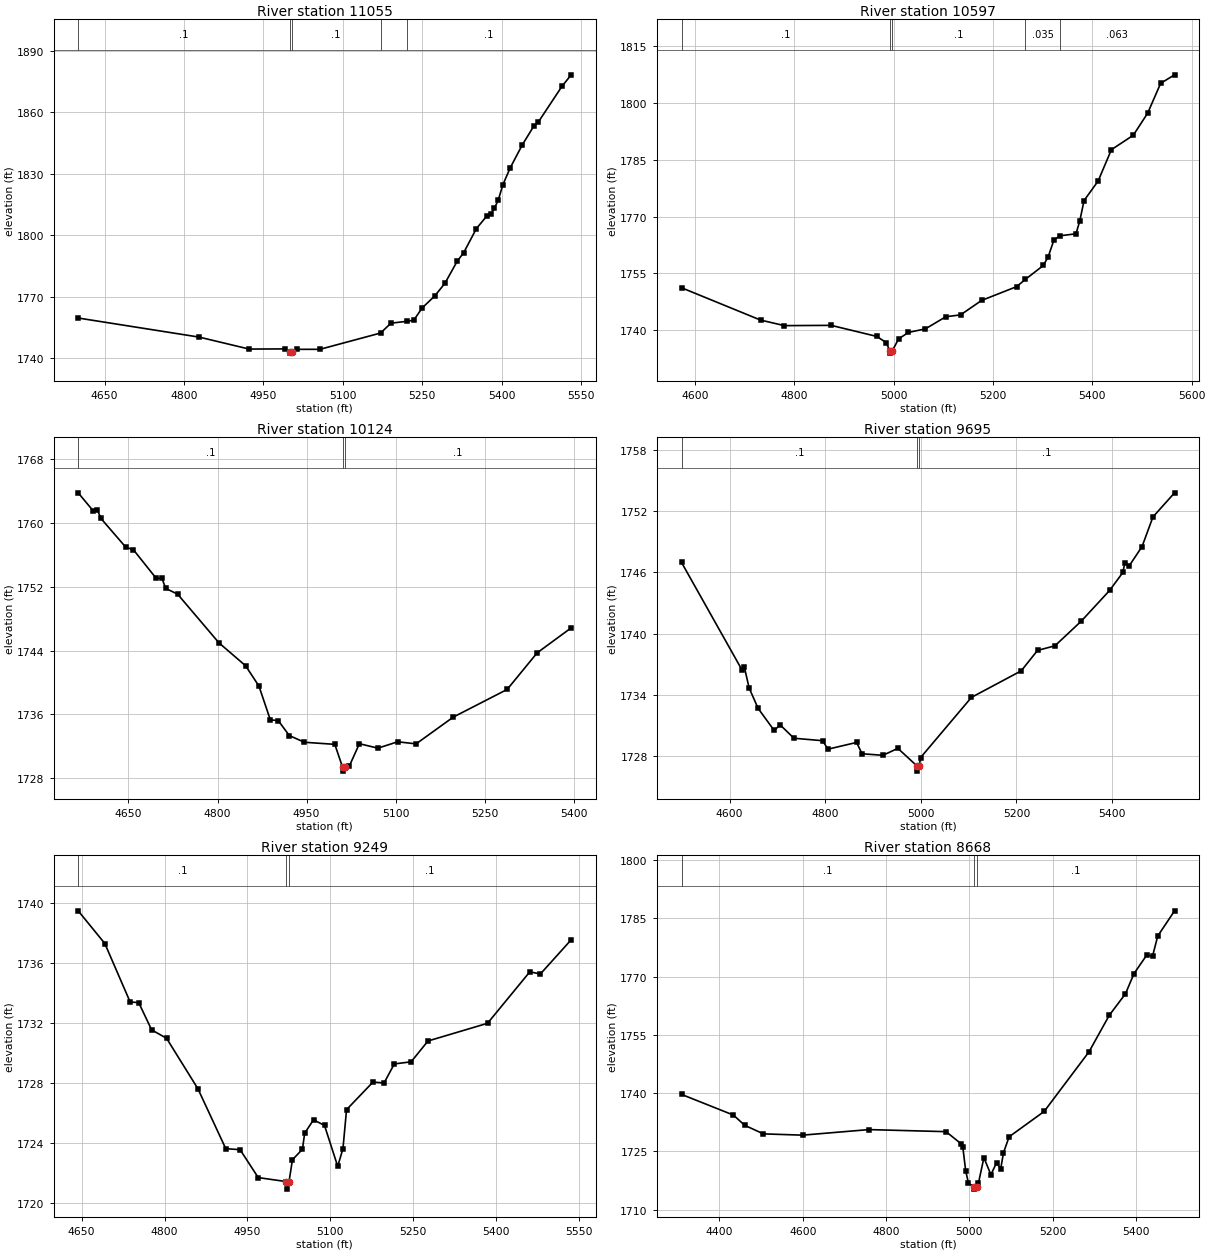
Type RM Length L Ch R = 1 ,11055   ,458,458,458
BEGIN DESCRIPTION:
Stream0538 21.0
END DESCRIPTION:
XS GIS Cut Line= 3
        1914225.     13913824.98        1914225.       13913425.
      1913824.99     13913074.99
#Sta/Elev= 30
    4600 1759.72  4828.8 1750.41    4923 1744.59  4990.2 1744.67  4999.5 1743.11
  4999.8 1742.61  5003.7 1743.11  5013.5 1744.46  5056.8 1744.47  5171.4 1752.41
  5190.8 1757.19  5220.8 1758.12  5233.9 1758.63  5250.3 1764.73  5273.7 1770.47
  5293.1 1776.72  5315.9 1787.31  5328.4 1791.58  5352.4 1803.32  5371.5 1809.25
  5379.7 1810.34  5386.4 1813.27  5393.4    1817  5402.5 1824.72  5416.1 1832.82
  5438.9 1844.02  5460.8 1853.24  5469.3  1855.2  5513.9 1872.59  5531.5 1878.25
#Mann= 5 ,-1 , 0
    4600      .1       0  4999.5     .05       0  5003.7      .1       0
  5171.4    .035       0  5220.8      .1       0
Bank Sta=4999.5,5003.7
XS Rating Curve= 0 ,0
Exp/Cntr=0.3,0.1

Type RM Length L Ch R = 1 ,10597   ,473,473,473
BEGIN DESCRIPTION:
Stream0538 20.0
END DESCRIPTION:
XS GIS Cut Line= 3
      1914475.01     13913674.96        1914625.       13913275.
      1914225.03     13912875.03
#Sta/Elev= 30
  4572.8 1751.16  4731.9 1742.62  4779.9 1741.15  4874.1 1741.22  4965.8  1738.3
    4985 1736.67  4992.5 1734.38  4992.8 1733.88  4996.8 1734.38  5009.9 1737.65
  5029.8 1739.36  5063.8 1740.29  5104.9  1743.5  5134.6 1743.99    5177 1747.81
  5247.4 1751.45  5265.4  1753.4  5301.4 1757.06  5311.1 1759.35  5322.6 1763.75
  5334.5  1764.9  5367.1 1765.43  5374.8 1768.85  5383.3 1774.21  5411.7 1779.39
  5438.4 1787.67  5482.5 1791.49  5511.4 1797.32  5537.6 1805.22  5565.6 1807.46
#Mann= 5 ,-1 , 0
  4572.8      .1       0  4992.5     .05       0  4996.8      .1       0
  5265.4    .035       0  5334.5    .063       0
Bank Sta=4992.5,4996.8
XS Rating Curve= 0 ,0
Exp/Cntr=0.3,0.1

Type RM Length L Ch R = 1 ,10124   ,429,429,429
BEGIN DESCRIPTION:
Stream0538 19.0
END DESCRIPTION:
XS GIS Cut Line= 3
      1914825.02     13913924.95        1914975.       13913525.
        1915025.     13913124.96
#Sta/Elev= 30
  4565.3 1763.79  4590.9  1761.5  4597.3 1761.69  4603.7 1760.57  4645.4 1756.97
  4658.2 1756.66  4696.7 1753.06  4706.3 1753.07  4712.7  1751.8  4732.7 1751.08
  4802.4 1744.97  4847.2  1742.1  4869.7 1739.55  4888.9 1735.31  4902.2 1735.22
  4920.9 1733.34  4946.3  1732.5  4997.5 1732.24  5010.5 1729.38  5010.8 1728.88
  5014.8 1729.38  5021.7 1729.48  5038.9 1732.32  5070.1 1731.76  5103.3 1732.56
  5134.4  1732.3  5197.1 1735.66  5287.8 1739.13  5338.3 1743.72  5395.6 1746.85
#Mann= 3 ,-1 , 0
  4565.3      .1       0  5010.5     .05       0  5014.8      .1       0
Bank Sta=5010.5,5014.8
XS Rating Curve= 0 ,0
Exp/Cntr=0.3,0.1

Type RM Length L Ch R = 1 ,9695    ,446,446,446
BEGIN DESCRIPTION:
Stream0538 18.0
END DESCRIPTION:
XS GIS Cut Line= 3
        1915075.       13913825.        1915375.       13913425.
      1915025.01     13913025.01
#Sta/Elev= 30
  4499.4 1746.97  4625.7 1736.46  4630.7 1736.75  4640.7 1734.69  4659.5 1732.69
  4693.2 1730.52  4705.7 1731.07  4734.5 1729.76  4794.5 1729.52  4805.7 1728.69
  4865.7 1729.35    4877 1728.24  4920.7 1728.09    4952 1728.77  4992.1 1727.04
  4992.4 1726.54  4996.4 1727.04  4999.6 1727.87  5105.9 1733.76  5210.1 1736.36
  5244.2 1738.36  5280.6 1738.81  5335.6 1741.22    5395 1744.23  5422.7 1745.99
  5426.9 1746.94  5435.3 1746.59  5462.9 1748.53  5485.7 1751.43  5530.9 1753.79
#Mann= 3 ,-1 , 0
  4499.4      .1       0  4992.1     .05       0  4996.4      .1       0
Bank Sta=4992.1,4996.4
XS Rating Curve= 0 ,0
Exp/Cntr=0.3,0.1

Type RM Length L Ch R = 1 ,9249    ,581,581,581
BEGIN DESCRIPTION:
Stream0538 17.0
END DESCRIPTION:
XS GIS Cut Line= 3
      1915925.02     13913875.04        1915725.       13913575.
        1915375.       13913175.
#Sta/Elev= 30
  4643.8  1739.5    4692 1737.32  4737.8 1733.42  4753.3 1733.38  4776.7 1731.56
  4803.7    1731  4860.5 1727.63  4910.8 1723.64  4936.8 1723.57  4969.6 1721.71
  5020.7 1721.44    5021 1720.94  5025.3 1721.44  5031.5  1722.9  5049.6  1723.6
  5053.6 1724.67  5069.6 1725.56  5089.5 1725.19  5113.4 1722.46  5122.9 1723.64
  5129.4 1726.24  5177.2 1728.08  5197.3 1728.02  5215.8 1729.29  5246.2 1729.43
  5276.8 1730.82  5384.5    1732    5461 1735.43  5480.2 1735.29  5535.9 1737.57
#Mann= 3 ,-1 , 0
  4643.8      .1       0  5020.7     .05       0  5025.3      .1       0
Bank Sta=5020.7,5025.3
XS Rating Curve= 0 ,0
Exp/Cntr=0.3,0.1

Type RM Length L Ch R = 1 ,8668    ,120,120,120
BEGIN DESCRIPTION:
Stream0538 16.1
END DESCRIPTION:
XS GIS Cut Line= 4
      1915943.85     13913875.57      1915940.38     13913629.02
      1916016.76     13913264.44       1916273.7     13912760.99
#Sta/Elev= 30
  4308.9 1739.69  4433.5 1734.37  4460.5 1731.74  4505.5 1729.53  4599.5  1729.2
  4758.9 1730.63  4944.2  1730.1  4981.3 1726.91  4984.6  1726.1  4991.4 1720.05
  4998.1 1716.83  5012.1  1715.8  5012.6  1715.3  5017.8  1715.8    5022 1716.79
  5035.2 1723.39    5052 1719.03  5065.5 1722.06  5075.6 1720.55  5082.2 1724.65
  5095.8 1728.78    5180 1735.31  5287.8 1750.68  5336.5 1760.09  5375.3 1765.61
  5395.6 1770.78  5426.5 1775.59  5440.3 1775.28  5452.8 1780.48  5493.2 1786.97
#Mann= 3 ,-1 , 0
  4308.9      .1       0  5012.1     .05       0  5017.8      .1       0
Bank Sta=5012.1,5017.8
XS Rating Curve= 0 ,0
Exp/Cntr=0.3,0.1

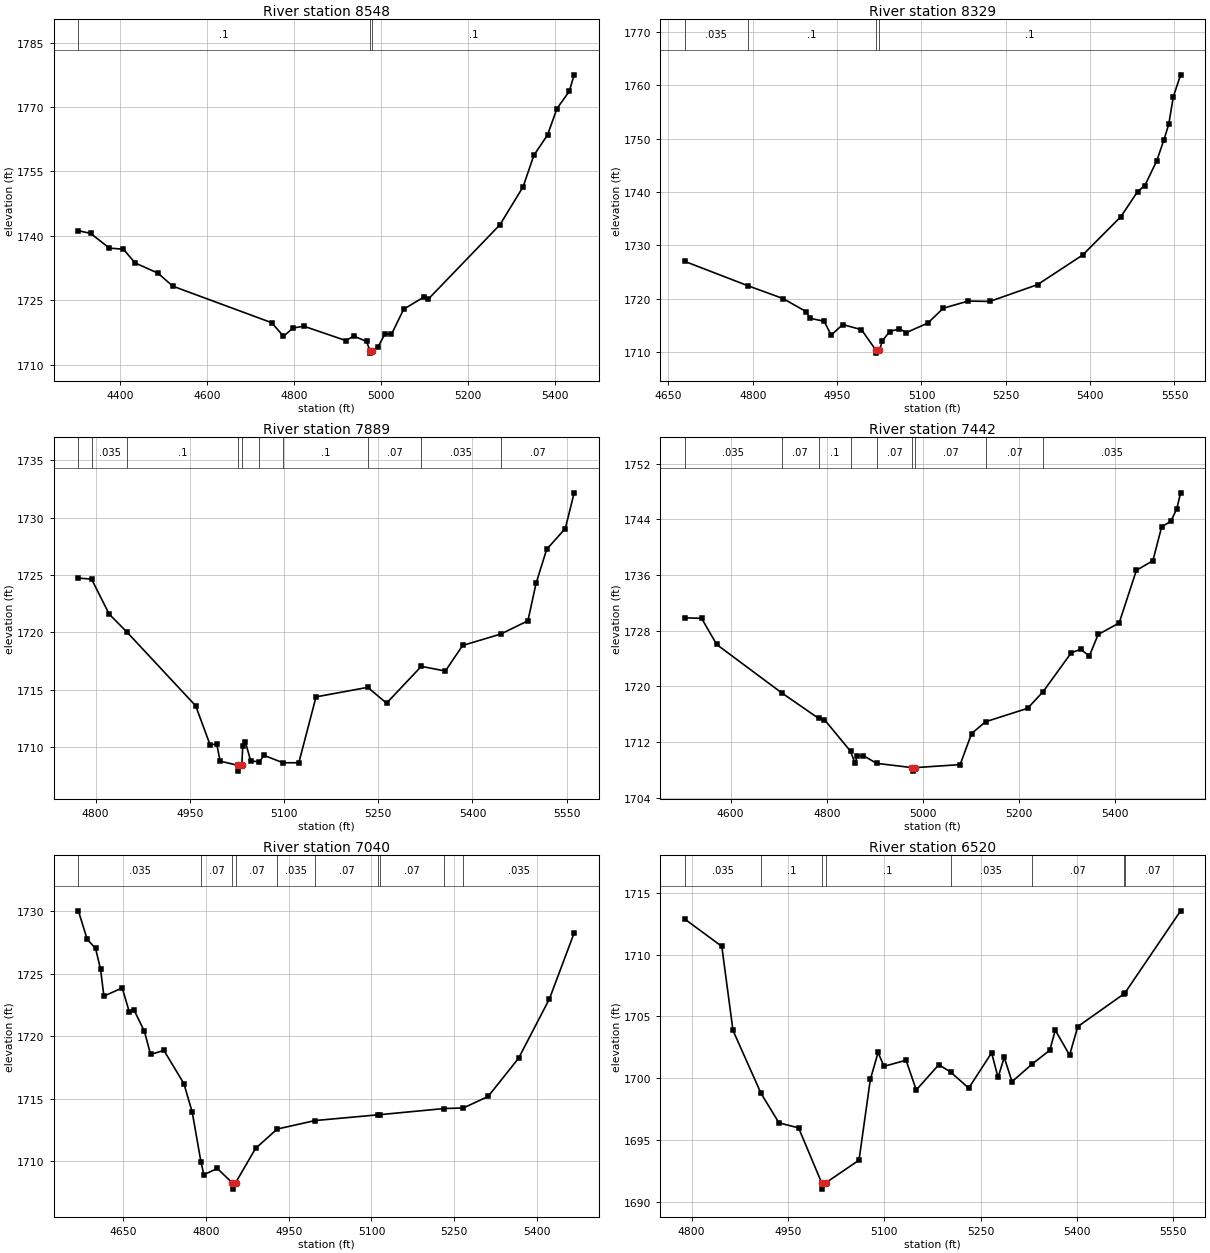
Type RM Length L Ch R = 1 ,8548    ,219,219,219
BEGIN DESCRIPTION:
Stream0538 16.0
END DESCRIPTION:
XS GIS Cut Line= 3
        1915975.     13913924.98       1916156.8      13913239.4
        1916275.       13912825.
#Sta/Elev= 30
  4304.2 1741.19  4332.2 1740.59  4375.6 1737.15  4407.9 1736.89  4434.6  1733.7
  4487.3 1731.31  4521.5 1728.28  4748.9 1719.77    4776 1716.61  4797.7 1718.53
  4822.5 1718.97  4919.8  1715.6  4937.4 1716.67  4967.2  1715.4  4974.9 1713.19
  4975.3 1712.69  4980.6 1713.19  4993.2 1714.12  5009.6 1717.22  5024.3 1717.08
  5052.4 1722.92  5099.2 1725.77  5108.5 1725.22  5273.6 1742.57  5326.9 1751.41
  5351.9 1758.79  5383.1 1763.48  5404.9 1769.65    5433 1773.64  5444.4  1777.5
#Mann= 3 ,-1 , 0
  4304.2      .1       0  4974.9     .05       0  4980.6      .1       0
Bank Sta=4974.9,4980.6
XS Rating Curve= 0 ,0
Exp/Cntr=0.3,0.1

Type RM Length L Ch R = 1 ,8329    ,440,440,440
BEGIN DESCRIPTION:
Stream0538 15.0
END DESCRIPTION:
XS GIS Cut Line= 3
        1916175.     13913725.01        1916275.       13913425.
      1916674.98     13913025.02
#Sta/Elev= 30
    4679 1726.99  4790.8 1722.44    4854 1720.01  4895.1 1717.55  4901.5 1716.32
  4926.8 1715.77  4939.4 1713.16  4959.8 1715.14  4993.2 1714.18  5019.3 1710.28
  5019.8 1709.78    5025 1710.28  5030.5 1712.11  5043.4 1713.83  5060.4 1714.34
  5073.1 1713.64  5111.3 1715.42  5138.7  1718.2    5183 1719.55  5221.6 1719.48
  5306.4 1722.63  5386.7 1728.19  5454.9 1735.41  5484.4  1740.1  5497.3 1741.21
  5518.6 1745.91  5530.9  1749.7  5539.8 1752.72  5547.9 1757.88  5560.9 1761.99
#Mann= 4 ,-1 , 0
    4679    .035       0  4790.8      .1       0  5019.3     .05       0
    5025      .1       0
Bank Sta=5019.3,5025
XS Rating Curve= 0 ,0
Exp/Cntr=0.3,0.1

Type RM Length L Ch R = 1 ,7889    ,447,447,447
BEGIN DESCRIPTION:
Stream0538 14.0
END DESCRIPTION:
XS GIS Cut Line= 3
      1916424.98     13913825.03        1916525.       13913625.
      1916924.98     13913225.02
#Sta/Elev= 30
  4772.6 1724.73  4793.7 1724.64  4821.7 1721.59  4850.6 1719.99  4959.4  1713.6
  4982.4 1710.19  4992.9 1710.28  4998.3 1708.78  5027.1 1708.41  5027.5 1707.91
  5032.8 1708.41  5034.3 1710.09  5038.4 1710.48    5047 1708.79  5060.6 1708.73
  5068.4 1709.28  5098.4 1708.64  5123.6 1708.64    5151 1714.38  5233.4 1715.21
  5263.2 1713.83  5318.6 1717.04  5356.9 1716.63  5384.3 1718.86  5444.9 1719.85
  5488.3 1721.01  5501.2 1724.26  5518.1 1727.23  5547.8 1729.05  5561.9 1732.16
#Mann= 10 ,-1 , 0
  4772.6      .1       0  4793.7    .035       0  4850.6      .1       0
  5027.1     .05       0  5032.8      .1       0  5060.6    .033       0
  5098.4      .1       0  5233.4     .07       0  5318.6    .035       0
  5444.9     .07       0
Bank Sta=5027.1,5032.8
XS Rating Curve= 0 ,0
Exp/Cntr=0.3,0.1

Type RM Length L Ch R = 1 ,7442    ,402,402,402
BEGIN DESCRIPTION:
Stream0538 13.0
END DESCRIPTION:
XS GIS Cut Line= 3
      1916575.02     13914024.97        1916875.       13913625.
      1917275.03     13913274.98
#Sta/Elev= 30
  4504.6 1729.85  4539.6 1729.77  4570.9 1726.01  4706.1 1719.06  4783.4 1715.37
  4795.2 1715.19  4849.4 1710.66  4858.4 1708.97  4863.7 1709.93  4875.9 1710.04
  4903.5 1708.92  4977.9  1708.3  4978.4  1707.8  4983.8  1708.3  5077.4 1708.74
  5101.3 1713.21  5130.3  1714.9  5217.8 1716.83  5250.3 1719.25  5308.6 1724.82
  5328.1 1725.31  5346.3 1724.37  5364.5 1727.45  5408.2  1729.1  5444.1 1736.68
  5478.4 1738.06  5496.6 1742.93  5515.9 1743.73  5528.2 1745.56  5536.1 1747.82
#Mann= 9 ,-1 , 0
  4504.6    .035       0  4706.1     .07       0  4783.4      .1       0
  4849.4     .07       0  4903.5     .07       0  4977.9     .05       0
  4983.8     .07       0  5130.3     .07       0  5250.3    .035       0
Bank Sta=4977.9,4983.8
XS Rating Curve= 0 ,0
Exp/Cntr=0.3,0.1

Type RM Length L Ch R = 1 ,7040    ,520,520,520
BEGIN DESCRIPTION:
Stream0538 12.0
END DESCRIPTION:
XS GIS Cut Line= 3
        1917025.     13914324.96      1917065.38     13913976.24
        1917375.       13913525.
#Sta/Elev= 30
  4568.9 1730.05    4585 1727.77  4600.1 1727.04  4609.2 1725.37  4615.2 1723.22
  4648.4 1723.88  4661.4 1721.93  4669.6 1722.13  4688.7 1720.39  4699.8 1718.55
  4723.9 1718.88  4760.2 1716.21  4775.3 1713.92    4791 1709.96  4796.4 1708.92
  4820.6 1709.43  4847.8 1708.27  4848.3 1707.77  4853.7 1708.27    4890 1711.03
  4929.2 1712.58  4997.9 1713.26    5112 1713.72  5114.6 1713.73  5231.4 1714.22
  5266.7 1714.27  5311.3 1715.19  5366.4 1718.24  5422.4    1723  5467.2 1728.28
#Mann= 10 ,-1 , 0
  4568.9    .035       0    4791     .07       0  4847.8     .05       0
  4853.7     .07       0  4929.2    .035       0  4997.9     .07       0
    5112    .035       0  5114.6     .07       0  5231.4    .033       0
  5266.7    .035       0
Bank Sta=4847.8,4853.7
XS Rating Curve= 0 ,0
Exp/Cntr=0.3,0.1

Type RM Length L Ch R = 1 ,6520    ,895,895,895
BEGIN DESCRIPTION:
Stream0538 11.0
END DESCRIPTION:
XS GIS Cut Line= 3
      1917325.02       13914225.        1917525.       13914175.
      1917924.99     13913775.01
#Sta/Elev= 30
  4789.5 1712.86  4847.1 1710.66  4864.5 1703.87  4908.2 1698.78  4936.1  1696.4
  4966.6    1696  5002.6 1691.55  5003.1 1691.05  5008.6 1691.55  5060.7 1693.39
  5078.3 1699.91  5090.4 1702.09  5099.5 1700.97  5133.9 1701.46  5149.8 1699.06
  5184.9  1701.1  5203.2 1700.51  5231.5 1699.21  5267.1 1702.06  5277.1 1700.07
  5286.7 1701.69  5298.9 1699.73  5330.3 1701.16  5357.7 1702.27  5366.2 1703.89
  5388.5 1701.87  5401.2 1704.18  5472.8 1706.81  5474.3 1706.87  5561.3 1713.53
#Mann= 8 ,-1 , 0
  4789.5    .035       0  4908.2      .1       0  5002.6     .05       0
  5008.6      .1       0  5203.2    .035       0  5330.3     .07       0
  5472.8    .035       0  5474.3     .07       0
Bank Sta=5002.6,5008.6
XS Rating Curve= 0 ,0
Exp/Cntr=0.3,0.1

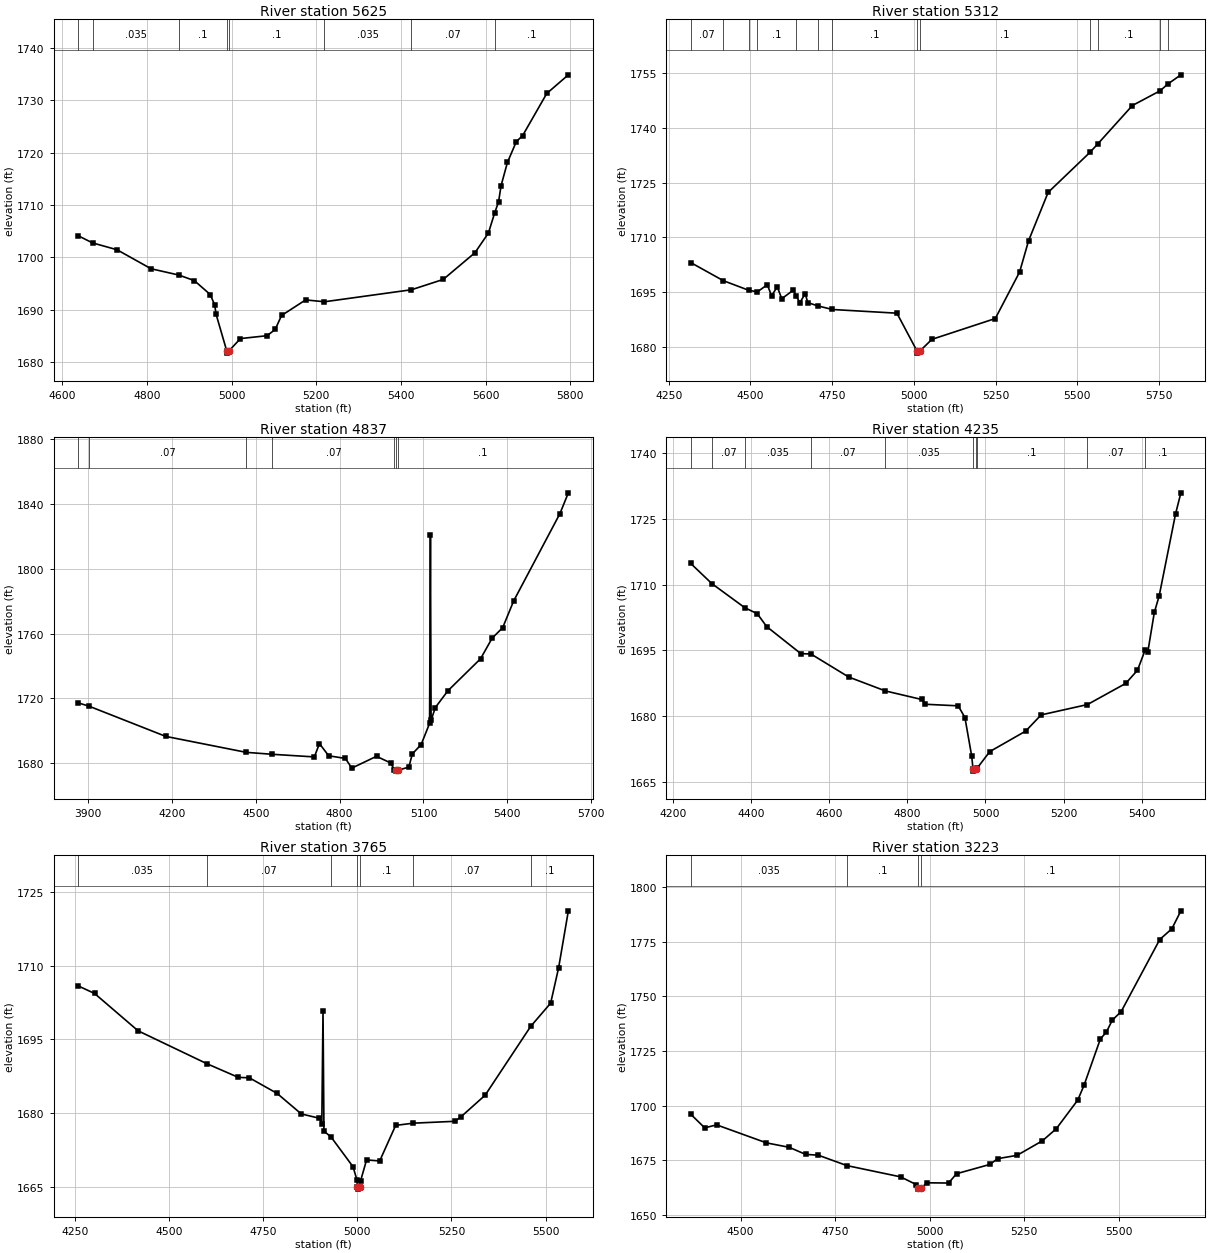
Type RM Length L Ch R = 1 ,5625    ,313,313,313
BEGIN DESCRIPTION:
Stream0538 10.0
END DESCRIPTION:
XS GIS Cut Line= 3
      1918090.62     13914883.02        1918275.       13914575.
        1918275.     13913774.99
#Sta/Elev= 30
  4636.8 1704.11    4671 1702.73  4728.9 1701.42  4809.4 1697.79  4875.4 1696.58
  4911.7 1695.52  4949.2 1692.87  4959.7  1690.9  4963.2 1689.06    4988 1682.17
  4988.5 1681.67  4994.4 1682.17  5020.6 1684.45  5083.6    1685  5102.8 1686.19
  5117.8 1688.86  5174.8 1691.84  5219.2 1691.48    5425 1693.78    5500 1695.75
    5575 1700.85  5606.8 1704.61  5621.7 1708.48  5630.8 1710.56  5636.8 1713.68
  5651.8 1718.11  5672.8 1722.07  5687.8 1723.24  5744.8 1731.28  5795.8 1734.84
#Mann= 8 ,-1 , 0
  4636.8     .07       0    4671    .035       0  4875.4      .1       0
    4988     .05       0  4994.4      .1       0  5219.2    .035       0
    5425     .07       0  5621.7      .1       0
Bank Sta=4988,4994.4
XS Rating Curve= 0 ,0
Exp/Cntr=0.3,0.1

Type RM Length L Ch R = 1 ,5312    ,475,475,475
BEGIN DESCRIPTION:
Stream0538 9.0
END DESCRIPTION:
XS GIS Cut Line= 3
      1918232.09     13915118.36      1918639.11     13914404.59
      1919268.86     13914151.95
#Sta/Elev= 30
    4317 1703.13  4417.3 1698.15  4495.1 1695.52  4521.5 1695.11  4551.7 1697.05
  4564.7 1694.04  4582.2 1696.46    4596 1693.22  4631.3 1695.58  4639.7 1694.03
  4651.3 1692.13  4667.7 1694.61  4675.5 1692.15  4705.9 1691.27  4750.9 1690.27
  4948.3 1689.26  5010.2 1678.83  5010.7 1678.33  5017.7 1678.83  5055.3  1682.1
  5249.3  1687.8  5323.7 1700.53  5351.1 1709.09  5410.9 1722.31  5539.7 1733.34
  5563.3 1735.63  5668.7 1746.09  5753.8 1750.13  5777.1 1751.97  5817.2 1754.49
#Mann= 13 ,-1 , 0
    4317     .07       0  4417.3    .035       0  4495.1     .07       0
  4521.5      .1       0  4639.7    .035       0  4705.9     .07       0
  4750.9      .1       0  5010.2     .05       0  5017.7      .1       0
  5539.7     .07       0  5563.3      .1       0  5753.8     .07       0
  5777.1      .1       0
Bank Sta=5010.2,5017.7
XS Rating Curve= 0 ,0
Exp/Cntr=0.3,0.1

Type RM Length L Ch R = 1 ,4837    ,602,602,602
BEGIN DESCRIPTION:
Stream0538 8.0
END DESCRIPTION:
XS GIS Cut Line= 3
      1918225.03     13915474.96      1919032.97     13914523.56
      1919535.97     13914478.35
#Sta/Elev= 30
  3864.8 1717.21  3903.6 1715.17  4178.4 1696.49  4466.2 1686.64  4559.5 1685.44
  4709.7 1683.82    4728 1692.05  4760.9 1684.52  4820.7 1682.89  4843.7 1676.91
    4932  1684.2  4982.9 1680.06  4996.2 1675.74  5001.1 1675.55  5001.6 1675.05
  5008.6 1675.55  5047.8 1677.57    5060 1685.69  5091.5  1691.4  5121.8 1704.52
  5124.8 1820.85  5127.2  1706.4  5142.2 1714.27  5187.4 1724.67  5304.1 1744.42
  5345.6 1757.16  5383.2  1763.6  5422.4 1780.09    5588 1834.06    5618 1846.84
#Mann= 7 ,-1 , 0
  3864.8    .035       0  3903.6     .07       0  4466.2      .1       0
  4559.5     .07       0  4996.2      .1       0  5001.1     .05       0
  5008.6      .1       0
Bank Sta=5001.1,5008.6
XS Rating Curve= 0 ,0
Exp/Cntr=0.3,0.1

Type RM Length L Ch R = 1 ,4235    ,470,470,470
BEGIN DESCRIPTION:
Stream0538 7.0
END DESCRIPTION:
XS GIS Cut Line= 3
      1918277.83     13915513.06        1918925.       13915125.
        1919325.       13914825.
#Sta/Elev= 30
  4245.5 1714.84  4299.7 1710.23  4384.3 1704.71  4416.1 1703.35  4440.1 1700.42
  4527.6 1694.24  4553.3 1694.17  4650.1 1688.91  4743.9 1685.74  4836.8 1683.79
    4846  1682.7  4930.2 1682.34  4947.4 1679.68  4964.9 1670.82  4968.1 1667.95
  4968.6 1667.45  4975.7 1667.95  4978.2 1668.06  5011.1 1671.91  5102.8 1676.57
  5142.4 1680.27  5260.9 1682.63    5359 1687.46    5389 1690.46  5408.4 1695.02
  5415.3 1694.57  5432.1 1703.64  5444.6 1707.45  5486.5 1726.15  5500.1 1730.92
#Mann= 10 ,-1 , 0
  4245.5    .035       0  4299.7     .07       0  4384.3    .035       0
  4553.3     .07       0  4743.9    .035       0  4968.1     .05       0
  4975.7    .035       0  4978.2      .1       0  5260.9     .07       0
  5408.4      .1       0
Bank Sta=4968.1,4975.7
XS Rating Curve= 0 ,0
Exp/Cntr=0.3,0.1

Type RM Length L Ch R = 1 ,3765    ,542,542,542
BEGIN DESCRIPTION:
Stream0538 6.0
END DESCRIPTION:
XS GIS Cut Line= 3
      1918436.82     13915786.94        1919125.       13915525.
      1919524.98     13915125.02
#Sta/Elev= 30
  4258.6 1705.88  4302.4 1704.33    4418 1696.74  4600.3 1690.07  4684.4 1687.27
  4713.3  1687.2  4787.2 1684.02  4851.4 1679.85  4899.5 1678.97  4905.9 1677.76
  4909.1 1700.85  4911.6 1676.33  4929.9 1675.22  4988.7 1669.13  4999.4  1666.4
  5000.2 1665.07  5000.7 1664.57  5007.9 1665.07  5008.7 1666.21  5024.8 1670.51
  5059.6 1670.29    5102 1677.52  5148.6 1677.97    5259 1678.35  5275.1 1679.24
  5339.6 1683.65  5460.5 1697.63  5513.6 1702.36  5534.8 1709.56  5560.6 1721.12
#Mann= 7 ,-1 , 0
  4258.6    .035       0  4600.3     .07       0  4929.9      .1       0
  5000.2     .05       0  5007.9      .1       0  5148.6     .07       0
  5460.5      .1       0
Bank Sta=5000.2,5007.9
XS Rating Curve= 0 ,0
Exp/Cntr=0.3,0.1

Type RM Length L Ch R = 1 ,3223    ,373,373,373
BEGIN DESCRIPTION:
Stream0538 5.1
END DESCRIPTION:
XS GIS Cut Line= 2
       1918911.3     13916352.15      1919899.35     13915511.78
#Sta/Elev= 30
  4367.9  1696.1  4405.2  1689.8  4436.8 1691.17  4568.4 1682.94  4628.9 1680.89
  4672.2 1677.66  4705.7  1677.3  4781.5 1672.53  4923.3 1667.39    4965 1663.84
  4970.3 1662.27  4970.8 1661.77  4978.3 1662.27  4992.8 1664.66  5050.3 1664.56
  5071.5 1668.82  5159.5 1673.06  5180.3 1675.71  5231.5 1677.22  5298.4 1683.85
  5335.5 1689.43  5392.1 1702.51  5408.7 1709.26    5452 1730.49  5467.8  1733.6
  5483.5 1739.07    5507    1743  5609.1 1775.96  5641.1 1780.88    5665 1789.08
#Mann= 4 ,-1 , 0
  4367.9    .035       0  4781.5      .1       0  4970.3     .05       0
  4978.3      .1       0
Bank Sta=4970.3,4978.3
XS Rating Curve= 0 ,0
Exp/Cntr=0.3,0.1