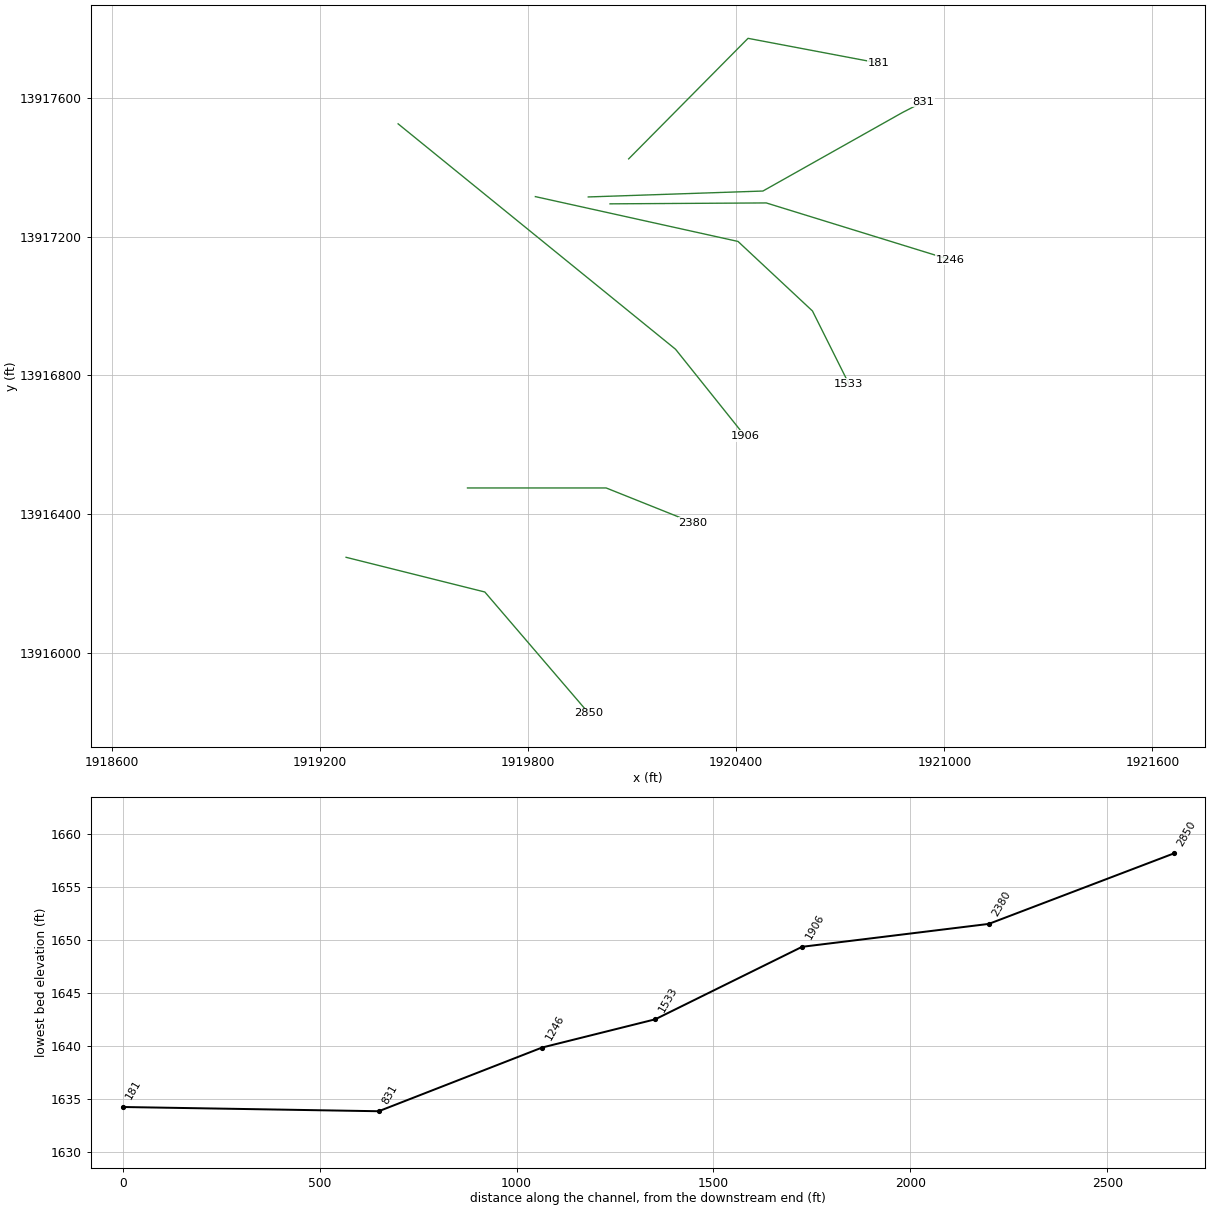
HEC-RAS study Stream0538.prj: Stream0538 Base Level Engineering

--- Stream0538.g01 (geometry) --- (continued)

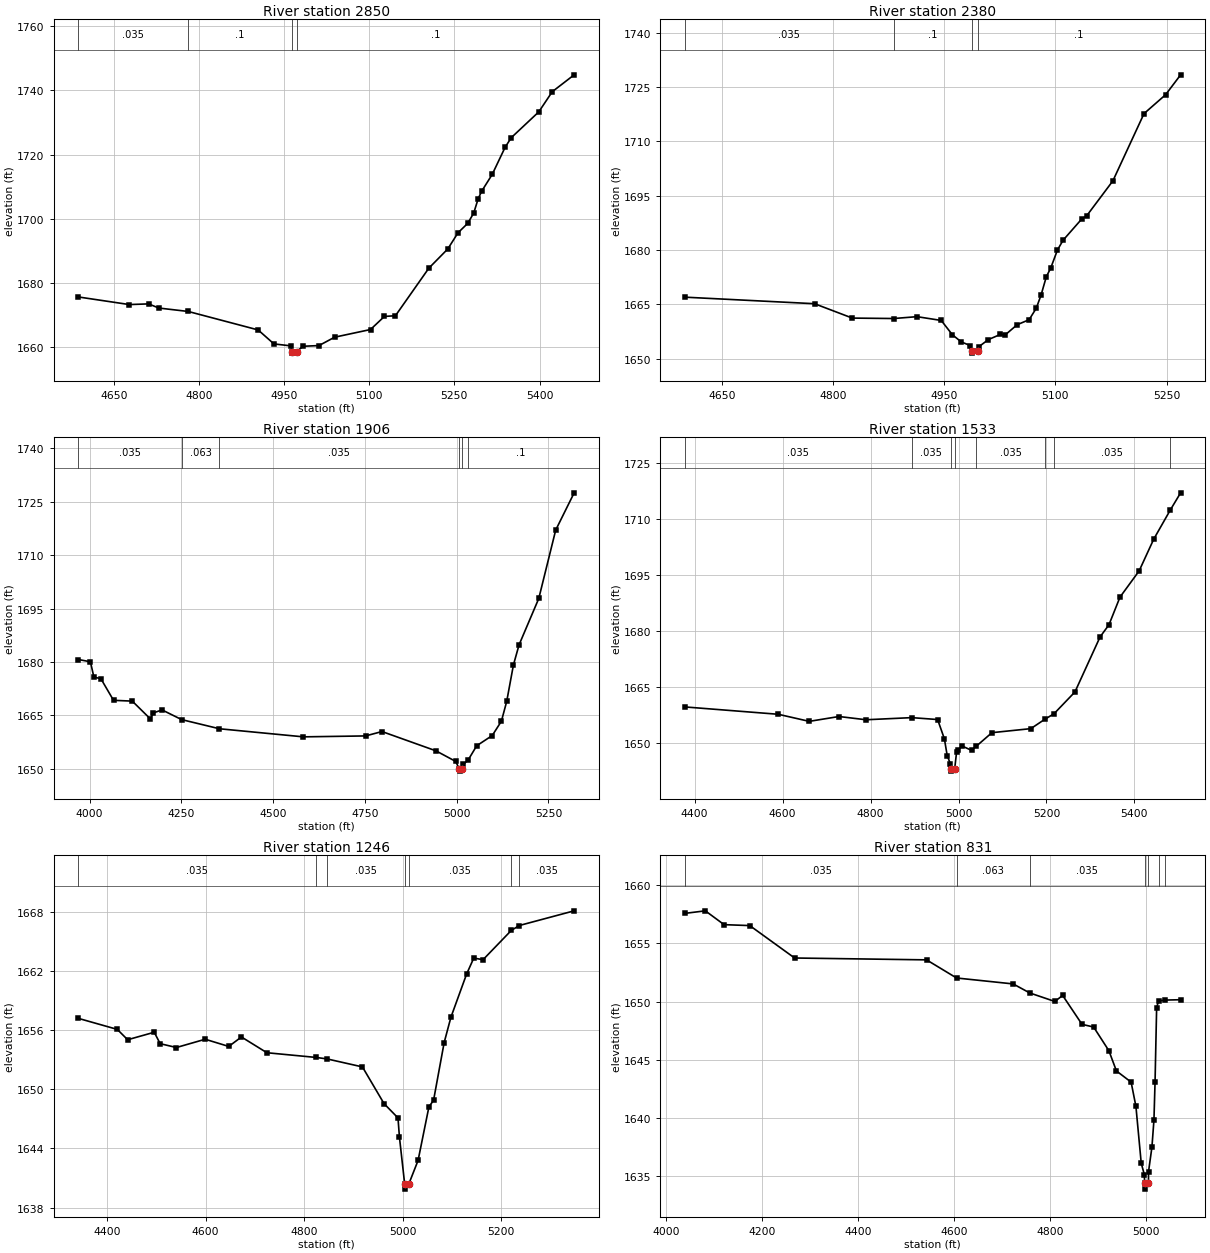
Type RM Length L Ch R = 1 ,2850    ,470,470,470
BEGIN DESCRIPTION:
Stream0538 5.0
END DESCRIPTION:
XS GIS Cut Line= 3
      1919275.01       13916275.        1919675.       13916175.
      1919975.02     13915824.98
#Sta/Elev= 30
  4587.7 1675.67  4677.5  1673.3  4711.5 1673.51  4729.4 1672.22  4781.3 1671.15
  4904.4  1665.4  4932.2 1661.05    4962 1660.44  4964.2 1658.68  4964.7 1658.18
  4972.2 1658.68  4983.6 1660.32  5011.5 1660.53  5039.1 1663.14  5102.3 1665.53
  5126.8 1669.61  5146.2 1669.82  5205.1 1684.64  5238.4 1690.61  5256.4 1695.64
  5273.6  1698.6  5284.1  1701.8    5292 1706.28  5298.3 1708.65  5316.7 1713.83
  5339.4 1722.27  5350.2 1725.26  5398.7  1733.3  5422.4 1739.57    5461 1744.83
#Mann= 4 ,-1 , 0
  4587.7    .035       0  4781.3      .1       0  4964.2     .05       0
  4972.2      .1       0
Bank Sta=4964.2,4972.2
XS Rating Curve= 0 ,0
Exp/Cntr=0.3,0.1

Type RM Length L Ch R = 1 ,2380    ,474,474,474
BEGIN DESCRIPTION:
Stream0538 4.0
END DESCRIPTION:
XS GIS Cut Line= 3
      1919625.05       13916475.        1920025.       13916475.
      1920274.99       13916375.
#Sta/Elev= 30
  4599.8 1666.99  4774.9 1665.18  4825.9 1661.21  4881.8 1661.09  4913.2  1661.6
  4945.9 1660.56  4960.9 1656.62  4972.9 1654.63  4985.2 1653.61  4986.8 1652.03
  4987.3 1651.53  4994.9 1652.03  4996.9 1653.34  5009.6 1655.28  5025.7 1656.69
  5032.2 1656.56  5048.4 1659.38  5064.5 1660.76  5074.2 1663.94  5080.7 1667.62
  5087.8 1672.67  5093.6 1674.99  5102.8 1680.04  5110.4 1682.73  5135.6  1688.6
  5142.1 1689.44  5177.6 1699.13  5219.6  1717.7  5248.7 1722.91    5269 1728.41
#Mann= 4 ,-1 , 0
  4599.8    .035       0  4881.8      .1       0  4986.8     .05       0
  4994.9      .1       0
Bank Sta=4986.8,4994.9
XS Rating Curve= 0 ,0
Exp/Cntr=0.3,0.1

Type RM Length L Ch R = 1 ,1906    ,373,373,373
BEGIN DESCRIPTION:
Stream0538 3.0
END DESCRIPTION:
XS GIS Cut Line= 3
      1919424.99     13917525.01        1920225.       13916875.
      1920424.97     13916625.04
#Sta/Elev= 30
  3969.2  1680.7  4002.1 1680.06  4011.6 1675.76  4030.6 1675.32  4065.1 1669.24
  4116.2 1669.02  4165.3 1664.04  4173.8 1665.72  4197.3 1666.55  4250.7 1663.83
  4353.7 1661.26  4582.5 1658.99  4751.8 1659.25  4796.5 1660.48  4943.5 1655.07
  4997.6 1652.08  5007.3 1649.87  5007.8 1649.37  5015.5 1649.87  5018.4 1651.26
  5031.6 1652.55  5054.6 1656.49  5096.9 1659.36  5121.9 1663.39  5136.3 1668.93
  5154.6 1679.15  5169.9 1684.79  5223.7 1697.83  5269.8 1717.02  5320.1 1727.48
#Mann= 6 ,-1 , 0
  3969.2    .035       0  4250.7    .063       0  4353.7    .035       0
  5007.3    .035       0  5015.5    .035       0  5031.6      .1       0
Bank Sta=5007.3,5015.5
XS Rating Curve= 0 ,0
Exp/Cntr=0.3,0.1

Type RM Length L Ch R = 1 ,1533    ,287,287,287
BEGIN DESCRIPTION:
Stream0538 2.0
END DESCRIPTION:
XS GIS Cut Line= 4
      1919820.77     13917315.16      1920405.11      13917185.9
      1920619.81     13916985.39      1920725.02     13916774.96
#Sta/Elev= 30
  4377.6 1659.74    4590 1657.77  4660.6 1655.87  4728.2 1657.17  4789.7  1656.3
  4893.6 1656.87  4952.5 1656.36  4967.9 1651.19  4974.3  1646.7  4981.6 1644.46
    4983 1643.03  4983.5 1642.53  4991.2 1643.03  4995.6  1647.6    4998 1648.14
  5008.4 1649.25  5029.6  1648.1    5040 1649.16    5076 1652.84  5164.5 1653.92
  5196.7 1656.46  5217.1  1657.9  5264.8 1663.76    5322 1678.52  5342.1 1681.75
  5367.2 1689.17  5410.8 1696.21  5443.8 1704.68  5481.7 1712.54  5505.1 1717.13
#Mann= 8 ,-1 , 0
  4377.6    .035       0  4893.6    .035       0    4983    .035       0
  4991.2    .035       0    5040    .035       0  5196.7      .1       0
  5217.1    .035       0  5481.7     .07       0
Bank Sta=4983,4991.2
XS Rating Curve= 0 ,0
Exp/Cntr=0.3,0.1

Type RM Length L Ch R = 1 ,1246    ,415,415,415
BEGIN DESCRIPTION:
Stream0538 1.1
END DESCRIPTION:
XS GIS Cut Line= 3
      1920036.08     13917294.32      1920486.55     13917296.93
      1921017.81     13917132.86
#Sta/Elev= 30
  4341.5 1657.21  4420.6 1656.09  4441.6 1655.04  4495.6  1655.8  4507.6 1654.64
  4540.6 1654.25    4599 1655.09  4646.8 1654.36  4672.6 1655.32  4724.3 1653.72
  4824.7 1653.24  4846.6 1653.09  4918.2 1652.28  4962.1 1648.55  4990.4  1647.1
  4993.3 1645.16    5004 1640.37  5004.5 1639.87  5012.2 1640.37  5031.2 1642.79
  5053.2 1648.23  5062.6 1648.89  5084.1 1654.75  5097.8 1657.32  5129.6  1661.7
  5144.2 1663.33  5163.1 1663.17  5220.4 1666.14  5236.7 1666.64    5348 1668.13
#Mann= 7 ,-1 , 0
  4341.5    .035       0  4824.7    .063       0  4846.6    .035       0
    5004    .035       0  5012.2    .035       0  5220.4     .07       0
  5236.7    .035       0
Bank Sta=5004,5012.2
XS Rating Curve= 0 ,0
Exp/Cntr=0.3,0.1

Type RM Length L Ch R = 1 ,831     ,650,650,650
BEGIN DESCRIPTION:
Stream0538 1.0
END DESCRIPTION:
XS GIS Cut Line= 4
      1919973.32     13917314.19      1920476.92     13917331.23
       1920879.8      13917557.9      1920939.64     13917588.58
#Sta/Elev= 30
  4039.3 1657.59  4082.1 1657.81  4121.2 1656.62  4174.7 1656.54  4268.2 1653.75
  4543.2 1653.59  4605.7 1652.03  4723.6 1651.52  4758.4 1650.74  4810.5 1650.01
  4826.8 1650.53  4867.2 1648.04  4891.4 1647.81  4923.2 1645.77  4938.9 1644.03
  4969.5 1643.07  4979.5 1640.99  4990.6 1636.09  4997.2 1635.09  4997.5 1634.36
    4998 1633.86  5005.7 1634.36  5005.8 1635.36  5012.9 1637.48  5017.1 1639.81
  5019.4 1643.08  5022.7 1649.48  5026.7 1650.05  5040.5 1650.13  5072.7 1650.16
#Mann= 7 ,-1 , 0
  4039.3    .035       0  4605.7    .063       0  4758.4    .035       0
  4997.5    .035       0  5005.7    .035       0  5026.7     .07       0
  5040.5    .035       0
Bank Sta=4997.5,5005.7
XS Rating Curve= 0 ,0
Exp/Cntr=0.3,0.1

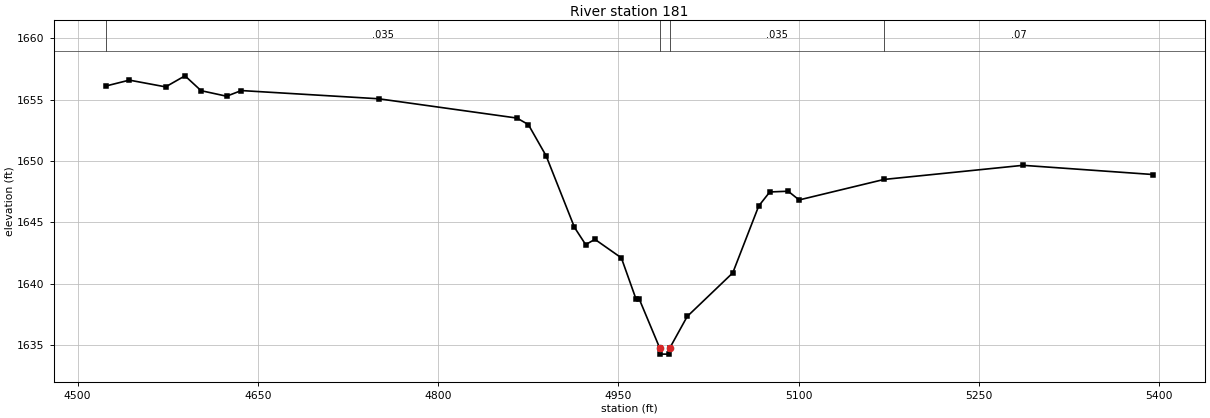
Type RM Length L Ch R = 1 ,181     ,0,0,0
BEGIN DESCRIPTION:
Stream0538 0.0
END DESCRIPTION:
XS GIS Cut Line= 3
      1920089.82     13917423.98      1920434.02     13917771.58
      1920809.48     13917700.57
#Sta/Elev= 30
  4523.6  1656.1  4543.1 1656.58  4573.3 1656.03  4589.4 1656.93  4602.8 1655.72
    4624 1655.27  4636.3 1655.73  4750.6 1655.06  4865.6 1653.49  4875.1 1652.96
  4889.9 1650.41  4913.5 1644.58  4922.8 1643.18  4930.5 1643.61  4952.5  1642.1
  4964.6 1638.77  4967.4 1638.74  4984.4 1634.76  4984.9 1634.26  4992.3 1634.26
  4992.8 1634.76  5007.3 1637.33  5045.2 1640.88  5066.8 1646.33    5076 1647.47
  5091.3 1647.53  5100.4 1646.82  5171.1 1648.49  5286.7 1649.64  5394.9 1648.89
#Mann= 4 ,-1 , 0
  4523.6    .035       0  4984.4    .035       0  4992.8    .035       0
  5171.1     .07       0
Bank Sta=4984.4,4992.8
XS Rating Curve= 0 ,0
Exp/Cntr=0.3,0.1

Chan Stop Cuts=-1
Use User Specified Reach Order=0
Composite Channel Slope=5