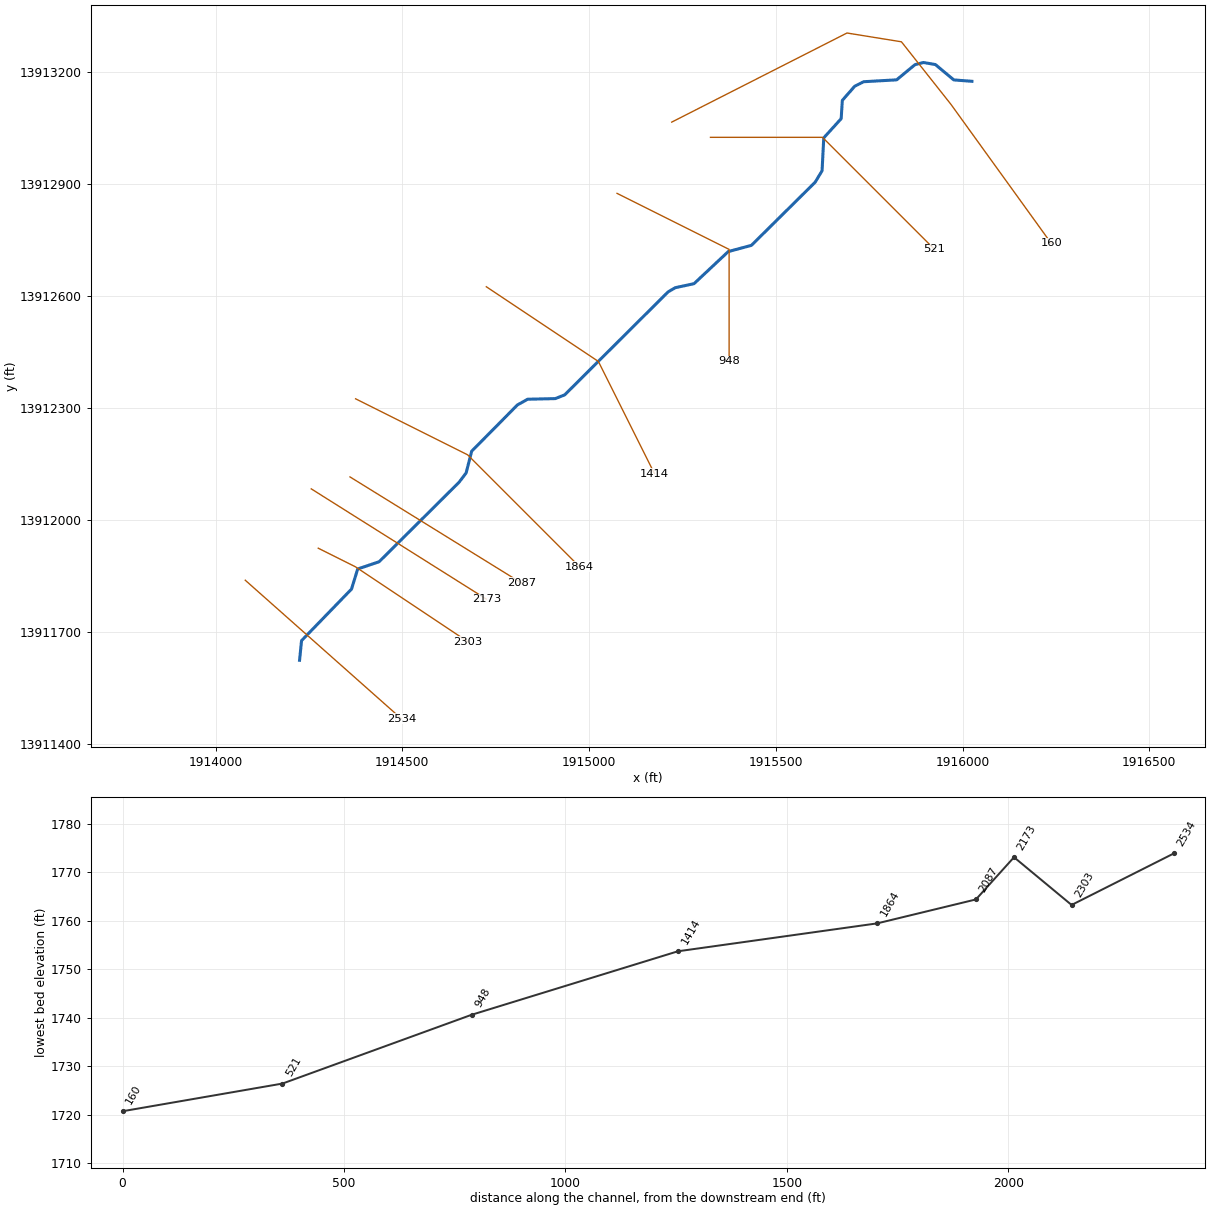
--- Stream0540.prj (project) ---

Proj Title=Stream0540 Base Level Engineering
Current Plan=p01
Default Exp/Contr=0.3,0.1
English Units
Geom File=g01
Flow File=f01
Plan File=p01
Y Axis Title=Elevation
X Axis Title(PF)=Main Channel Distance
X Axis Title(XS)=Station
BEGIN DESCRIPTION:
Stream0540
END DESCRIPTION:
DSS Export Rating Curves= 0
DSS Export Rating Curve Sorted= 0
DSS Export Volume Flow Curves= 0
DXF OffsetX= 0
DXF OffsetY= 0
DXF ScaleX= 1
DXF ScaleY= 10

--- Stream0540.p01 (plan) ---

Plan Title=Multiple Run
Short Identifier=Multiple
Geom File=g01
Flow File=f01
Subcritical Flow
K Sum by GR= 0
Std Step Tol= 0.01
Critical Tol= 0.01
Num of Std Step Trials= 20
Max Error Tol= 0.3
Flow Tol Ratio= 0.001
Split Flow NTrial= 30
Split Flow Tol= 0.02
Split Flow Ratio= 0.02
Log Output Level= 0
Friction Slope Method= 1
Unsteady Friction Slope Method= 2
Unsteady Bridges Friction Slope Method= 1
Parabolic Critical Depth
Global Vel Dist=  1 , 1 , 1
Global Log Level= 0
CheckData=True
Encroach Param= -1, 0, 0, 0
BEGIN DESCRIPTION:
Multiple Run
END DESCRIPTION:

--- Stream0540.f01 (steady flow) ---

Flow Title=Multiple
Program Version=4.10
Number of Profiles= 7
Profile Names=10-year,25-year,50-year,1pct_min,100-year,1pct_plu,500-year
River Rch & RM=Stream0540,Reach-1         ,2534
     705    1173    1611    1073    2141    4272    3727
Boundary for River Rch & Prof#=Stream0540,Reach-1         , 1
Up Type= 0
Dn Type= 3
Dn Slope=0.005
Boundary for River Rch & Prof#=Stream0540,Reach-1         , 2
Up Type= 0
Dn Type= 3
Dn Slope=0.005
Boundary for River Rch & Prof#=Stream0540,Reach-1         , 3
Up Type= 0
Dn Type= 3
Dn Slope=0.005
Boundary for River Rch & Prof#=Stream0540,Reach-1         , 4
Up Type= 0
Dn Type= 3
Dn Slope=0.005
Boundary for River Rch & Prof#=Stream0540,Reach-1         , 5
Up Type= 0
Dn Type= 3
Dn Slope=0.005
Boundary for River Rch & Prof#=Stream0540,Reach-1         , 6
Up Type= 0
Dn Type= 3
Dn Slope=0.005
Boundary for River Rch & Prof#=Stream0540,Reach-1         , 7
Up Type= 0
Dn Type= 3
Dn Slope=0.005
DSS Import GetInterval= 0
DSS Import GetPeak= 0
DSS Import FillOption= 0

--- Stream0540.g01 (geometry) ---

Geom Title=Existing Conditions
Program Version=4.10

River Reach=Stream0540      ,Reach-1
Reach XY= 30
        1914225.       13911625.      1914230.31     13911677.52
      1914364.11     13911815.58      1914380.62     13911869.38
      1914437.98     13911888.73      1914651.98     13912101.53
      1914671.02     13912126.65      1914685.78     13912184.68
      1914808.25     13912308.54      1914835.48     13912323.83
      1914909.78     13912325.53      1914934.79     13912335.52
      1915211.79     13912611.37      1915231.05     13912622.47
      1915281.04     13912633.18      1915372.72     13912719.13
      1915434.68     13912735.78      1915605.38     13912904.84
      1915623.88     13912935.46      1915628.39     13913023.59
        1915675.       13913075.      1915678.12     13913124.01
      1915711.35     13913161.88      1915735.35     13913173.92
      1915823.41     13913178.89      1915872.81     13913219.64
      1915895.17     13913225.34      1915927.25     13913219.88
      1915976.49     13913178.69        1916025.       13913175.

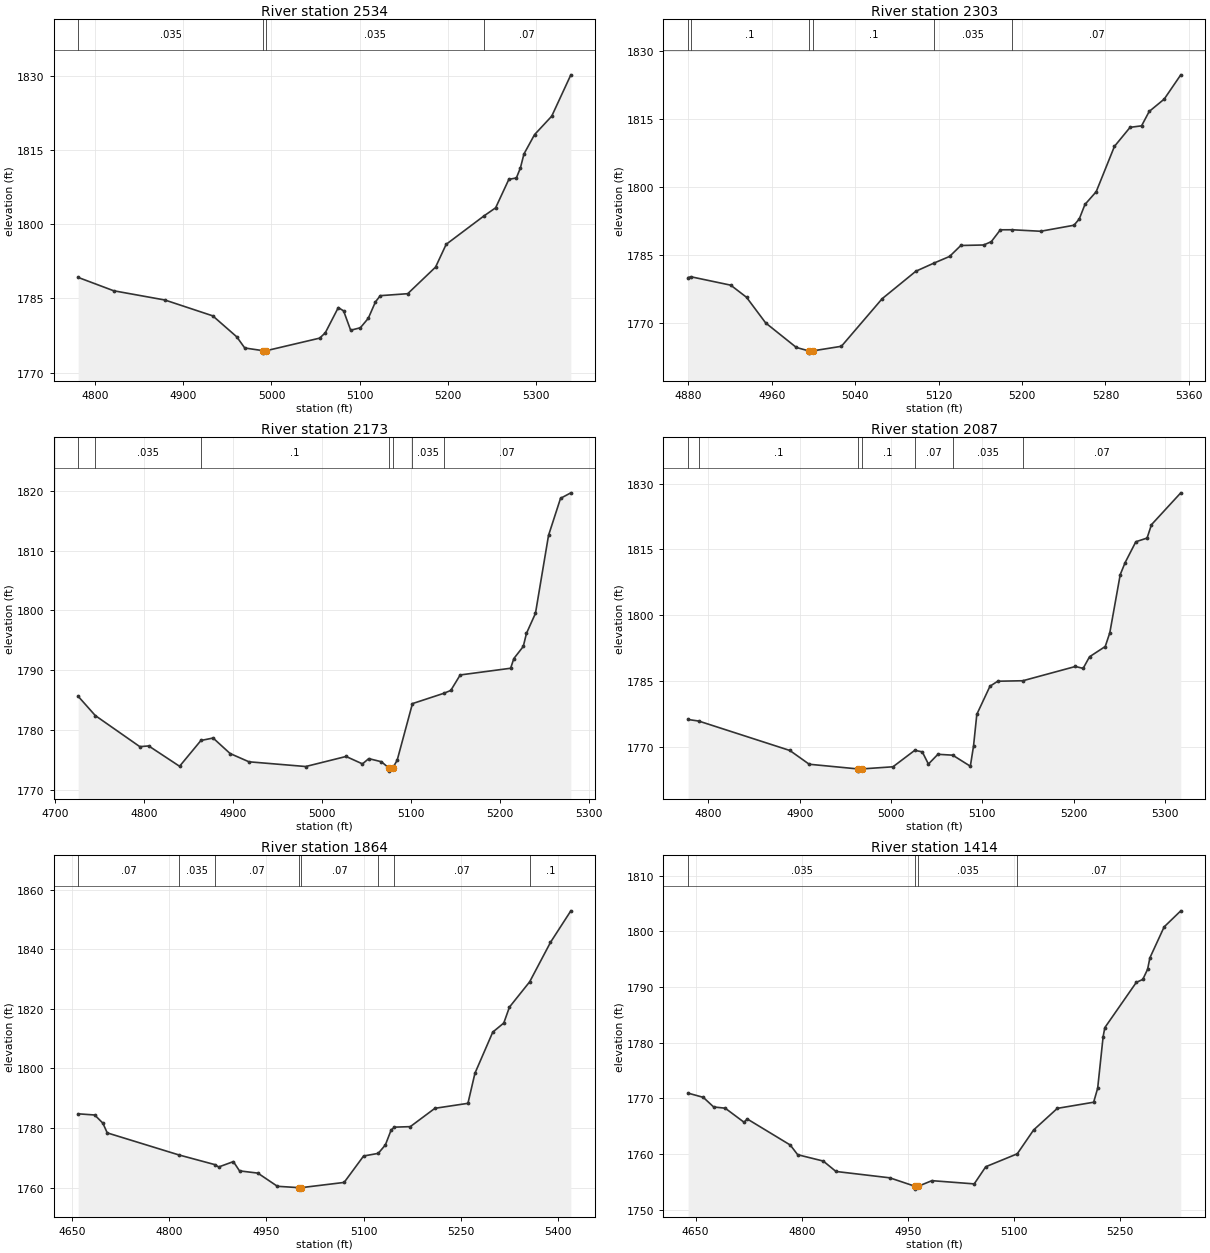
Type RM Length L Ch R = 1 ,2534    ,231,231,231
BEGIN DESCRIPTION:
Stream0540 6.0
END DESCRIPTION:
XS GIS Cut Line= 2
      1914079.62     13911839.28      1914497.59     13911468.54
#Sta/Elev= 30
  4780.8 1789.24  4821.1 1786.54  4879.2 1784.67  4933.4 1781.47  4960.6 1777.23
  4969.7 1774.97  4990.3 1774.43  4990.5 1773.93  4994.3 1774.43  5054.6 1776.96
    5061 1778.03  5075.8 1783.15  5081.8 1782.47  5089.8 1778.56  5100.8 1779.06
  5109.8 1780.98  5117.9 1784.29  5123.4 1785.55  5154.5 1785.95  5186.1 1791.33
  5198.1 1795.93  5240.7 1801.64  5254.2 1803.32  5269.2 1809.08  5277.7 1809.35
  5282.3 1811.39  5286.3  1814.2  5298.3 1818.11  5317.8 1821.85  5339.5 1830.21
#Mann= 4 ,-1 , 0
  4780.8    .035       0  4990.3    .035       0  4994.3    .035       0
  5240.7     .07       0
Bank Sta=4990.3,4994.3
XS Rating Curve= 0 ,0
Exp/Cntr=0.3,0.1

Type RM Length L Ch R = 1 ,2303    ,130,130,130
BEGIN DESCRIPTION:
Stream0540 5.0
END DESCRIPTION:
XS GIS Cut Line= 3
      1914274.99     13911925.01        1914375.       13911875.
      1914675.02     13911674.99
#Sta/Elev= 30
  4879.8 1779.97  4882.4 1780.15  4920.7 1778.29  4935.8 1775.62  4954.2 1769.95
  4983.6 1764.54  4995.4 1763.79  4995.6 1763.29  4999.4 1763.79  5026.8  1764.8
  5065.9 1775.31  5098.2 1781.37  5115.7 1783.18  5130.5 1784.63  5141.3 1787.05
  5163.2 1787.16  5170.5 1787.89  5179.2 1790.51  5190.6 1790.52  5217.9 1790.19
  5249.8 1791.52  5254.9 1792.92  5260.3  1796.1  5271.1 1798.92  5288.6 1808.93
  5303.6 1813.13  5314.6 1813.46  5321.9 1816.63  5336.3 1819.36  5352.2 1824.72
#Mann= 6 ,-1 , 0
  4879.8    .035       0  4882.4      .1       0  4995.4     .05       0
  4999.4      .1       0  5115.7    .035       0  5190.6     .07       0
Bank Sta=4995.4,4999.4
XS Rating Curve= 0 ,0
Exp/Cntr=0.3,0.1

Type RM Length L Ch R = 1 ,2173    ,86,86,86
BEGIN DESCRIPTION:
Stream0540 5.1
END DESCRIPTION:
XS GIS Cut Line= 2
      1914256.33     13912083.89      1914725.06     13911788.77
#Sta/Elev= 30
  4726.1 1785.64  4745.3 1782.43  4795.4 1777.23  4805.4 1777.35  4840.1 1773.95
  4864.1 1778.26  4877.8 1778.67  4896.9 1776.08  4918.1  1774.7  4981.9 1773.91
  5027.3 1775.59  5045.7 1774.35  5052.8 1775.23    5067 1774.71  5075.6 1773.64
  5075.9 1773.14  5079.6 1773.64  5084.7 1774.94  5101.9 1784.42  5136.9 1786.13
    5145 1786.62  5155.6 1789.21  5212.3 1790.33  5215.9 1791.95  5226.5 1793.97
  5230.1 1796.16  5240.2  1799.5  5254.9 1812.53  5268.4 1818.72    5280 1819.64
#Mann= 7 ,-1 , 0
  4726.1     .07       0  4745.3    .035       0  4864.1      .1       0
  5075.6     .05       0  5079.6      .1       0  5101.9    .035       0
  5136.9     .07       0
Bank Sta=5075.6,5079.6
XS Rating Curve= 0 ,0
Exp/Cntr=0.3,0.1

Type RM Length L Ch R = 1 ,2087    ,223,223,223
BEGIN DESCRIPTION:
Mapping XS c4270037
END DESCRIPTION:
XS GIS Cut Line= 2
      1914360.03     13912115.88      1914818.72     13911832.06
#Sta/Elev= 30
  4777.8 1776.21  4789.5 1775.85  4889.2 1769.14  4910.4    1766  4963.8 1764.93
  4964.1 1764.43  4967.8 1764.93  5002.1 1765.42    5026 1769.18  5034.2 1768.82
  5040.9 1766.04  5051.3 1768.27  5067.5 1768.07  5086.8 1765.55  5090.3 1770.16
  5093.9 1777.39  5108.3  1783.8  5116.8 1784.94  5144.3 1785.05  5201.8  1788.3
  5210.3 1787.87  5217.3 1790.52  5234.5 1792.86  5239.5    1796  5250.9 1809.26
  5256.3 1812.02    5268 1816.76  5280.3  1817.6  5285.1 1820.65  5317.2 1827.92
#Mann= 7 ,-1 , 0
  4777.8    .035       0  4789.5      .1       0  4963.8     .05       0
  4967.8      .1       0    5026     .07       0  5067.5    .035       0
  5144.3     .07       0
Bank Sta=4963.8,4967.8
XS Rating Curve= 0 ,0
Exp/Cntr=0.3,0.1

Type RM Length L Ch R = 1 ,1864    ,450,450,450
BEGIN DESCRIPTION:
Stream0540 4.0
END DESCRIPTION:
XS GIS Cut Line= 3
      1914375.02     13912324.99        1914675.       13912175.
      1914975.03     13911874.97
#Sta/Elev= 30
  4659.8 1784.78  4685.3 1784.38  4697.9 1781.64  4704.6 1778.38    4815 1770.98
  4870.2 1767.74  4876.5 1766.93  4899.1 1768.73  4908.6 1765.62  4936.8 1764.87
    4967 1760.44    5000 1759.99  5000.2 1759.49    5004 1759.99  5069.9 1761.74
  5099.9 1770.61  5122.5  1771.5  5133.5 1774.33  5142.3  1779.3  5147.4  1780.3
  5171.9 1780.47  5209.9 1786.63  5260.8  1788.3  5271.6  1798.4  5299.1 1812.22
  5316.1 1815.27  5324.8 1820.61    5356 1829.11  5388.1 1842.36  5419.5 1852.94
#Mann= 8 ,-1 , 0
  4659.8     .07       0    4815    .035       0  4870.2     .07       0
    5000     .05       0    5004     .07       0  5122.5    .035       0
  5147.4     .07       0    5356      .1       0
Bank Sta=5000,5004
XS Rating Curve= 0 ,0
Exp/Cntr=0.3,0.1

Type RM Length L Ch R = 1 ,1414    ,466,466,466
BEGIN DESCRIPTION:
Stream0540 3.0
END DESCRIPTION:
XS GIS Cut Line= 3
        1914725.       13912625.        1915025.       13912425.
      1915175.01     13912124.97
#Sta/Elev= 30
  4639.4 1770.96  4660.8 1770.21  4675.5 1768.48  4691.8 1768.26  4718.5 1765.73
  4722.9 1766.33  4783.7 1761.65  4794.2 1759.91  4830.3 1758.77  4848.3  1756.9
  4924.3 1755.76  4960.2 1754.23  4960.4 1753.73  4964.2 1754.23  4983.8 1755.25
  5043.6 1754.67  5059.9 1757.75  5104.4 1760.07  5127.5 1764.35    5161 1768.23
  5212.3 1769.33    5218 1771.85  5225.7  1781.1  5228.1 1782.72  5272.6 1790.85
  5281.7 1791.37  5288.5 1793.19  5291.8 1795.26  5311.9 1800.81  5335.4 1803.69
#Mann= 4 ,-1 , 0
  4639.4    .035       0  4960.2    .035       0  4964.2    .035       0
  5104.4     .07       0
Bank Sta=4960.2,4964.2
XS Rating Curve= 0 ,0
Exp/Cntr=0.3,0.1

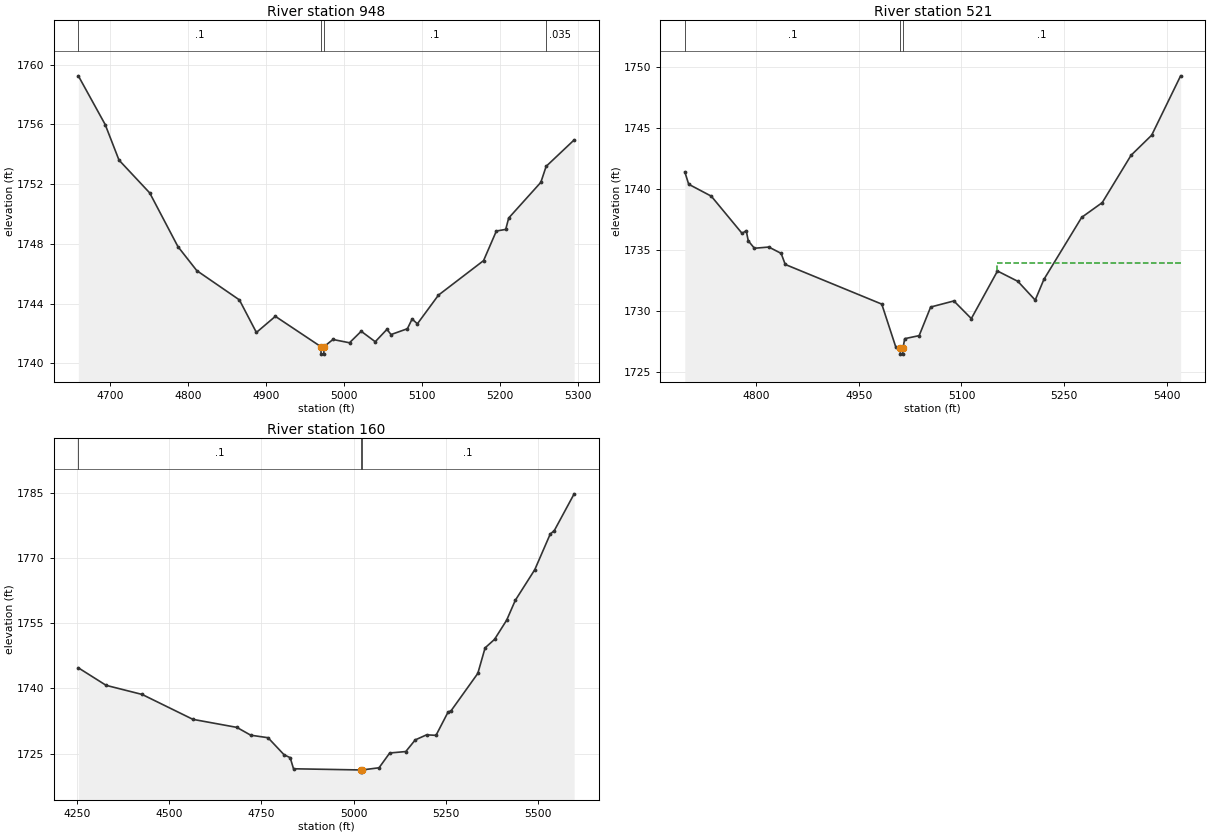
Type RM Length L Ch R = 1 ,948     ,427,427,427
BEGIN DESCRIPTION:
Stream0540 2.0
END DESCRIPTION:
XS GIS Cut Line= 3
      1915074.99     13912875.01        1915375.       13912725.
        1915375.     13912425.02
#Sta/Elev= 30
  4659.8 1759.25  4694.2 1755.99  4711.9 1753.61  4751.3 1751.41  4787.4 1747.82
  4811.6 1746.21  4866.2 1744.25    4888 1742.07  4912.3 1743.15  4970.6 1741.12
  4970.9 1740.62  4974.4 1740.62  4974.6 1741.12  4986.1  1741.6  5007.3 1741.38
  5022.3 1742.15  5040.3 1741.45  5055.3 1742.28  5060.5 1741.93  5081.5 1742.32
  5087.5 1742.97  5094.3 1742.65  5121.3 1744.57  5179.1 1746.88  5195.5 1748.86
  5207.5 1748.97  5211.3 1749.73  5252.5 1752.12  5259.3 1753.19  5295.2 1754.96
#Mann= 4 ,-1 , 0
  4659.8      .1       0  4970.6     .05       0  4974.6      .1       0
  5259.3    .035       0
Bank Sta=4970.6,4974.6
XS Rating Curve= 0 ,0
Exp/Cntr=0.3,0.1

Type RM Length L Ch R = 1 ,521     ,361,361,361
BEGIN DESCRIPTION:
Stream0540 1.0
END DESCRIPTION:
XS GIS Cut Line= 3
      1915325.03       13913025.        1915625.       13913025.
      1915924.98     13912725.02
#Sta/Elev= 30
  4695.9 1741.41  4701.6 1740.39  4734.6 1739.41  4779.6 1736.35  4785.6 1736.58
  4788.6 1735.74  4797.6 1735.13  4818.6 1735.23  4836.6 1734.71  4842.6  1733.8
  4983.6 1730.54  5004.2 1726.99  5010.6 1726.93  5010.8 1726.43  5014.3 1726.43
  5014.6 1726.93  5017.1  1727.7  5038.2 1727.95    5055  1730.3  5088.9  1730.8
  5114.4 1729.35  5152.6 1733.26  5182.4 1732.41  5207.7 1730.87  5220.4 1732.57
  5275.6 1737.67  5305.6 1738.88  5347.7 1742.77  5377.8 1744.42  5420.1  1749.3
#Mann= 3 ,-1 , 0
  4695.9      .1       0  5010.6     .05       0  5014.6      .1       0
#XS Ineff= 2 , 0
                          5152.3         1733.88
Permanent Ineff=
       F       F
#Block Obstruct= 2 , 0
                         5085.78         1730.26
Bank Sta=5010.6,5014.6
XS Rating Curve= 0 ,0
Exp/Cntr=0.3,0.1

Type RM Length L Ch R = 1 ,160     ,0,0,0
BEGIN DESCRIPTION:
Stream0540 0.0
END DESCRIPTION:
XS GIS Cut Line= 5
       1915221.4     13913065.75      1915690.59     13913304.31
      1915836.34     13913280.76      1915968.94     13913113.23
       1916237.3     13912741.28
#Sta/Elev= 30
  4252.8  1744.7  4328.3 1740.67    4426 1738.58    4564 1732.85  4683.1 1731.01
    4721 1729.21  4767.9 1728.63  4811.6  1724.7    4828 1724.05  4837.1 1721.49
    5019 1721.22  5019.2 1720.72    5023 1721.22  5069.3 1721.72  5098.3 1725.12
  5141.9 1725.45  5167.6 1728.13  5198.3 1729.29    5224 1729.18  5256.7 1734.52
    5265 1734.84  5337.5 1743.42  5357.3 1749.29  5382.9 1751.24  5415.8 1755.65
  5439.3 1760.22  5492.2 1767.27  5534.1 1775.45  5545.2 1776.25  5599.1  1784.7
#Mann= 3 ,-1 , 0
  4252.8      .1       0    5019     .05       0    5023      .1       0
Bank Sta=5019,5023
XS Rating Curve= 0 ,0
Exp/Cntr=0.3,0.1

Chan Stop Cuts=-1
Use User Specified Reach Order=0
Composite Channel Slope=5