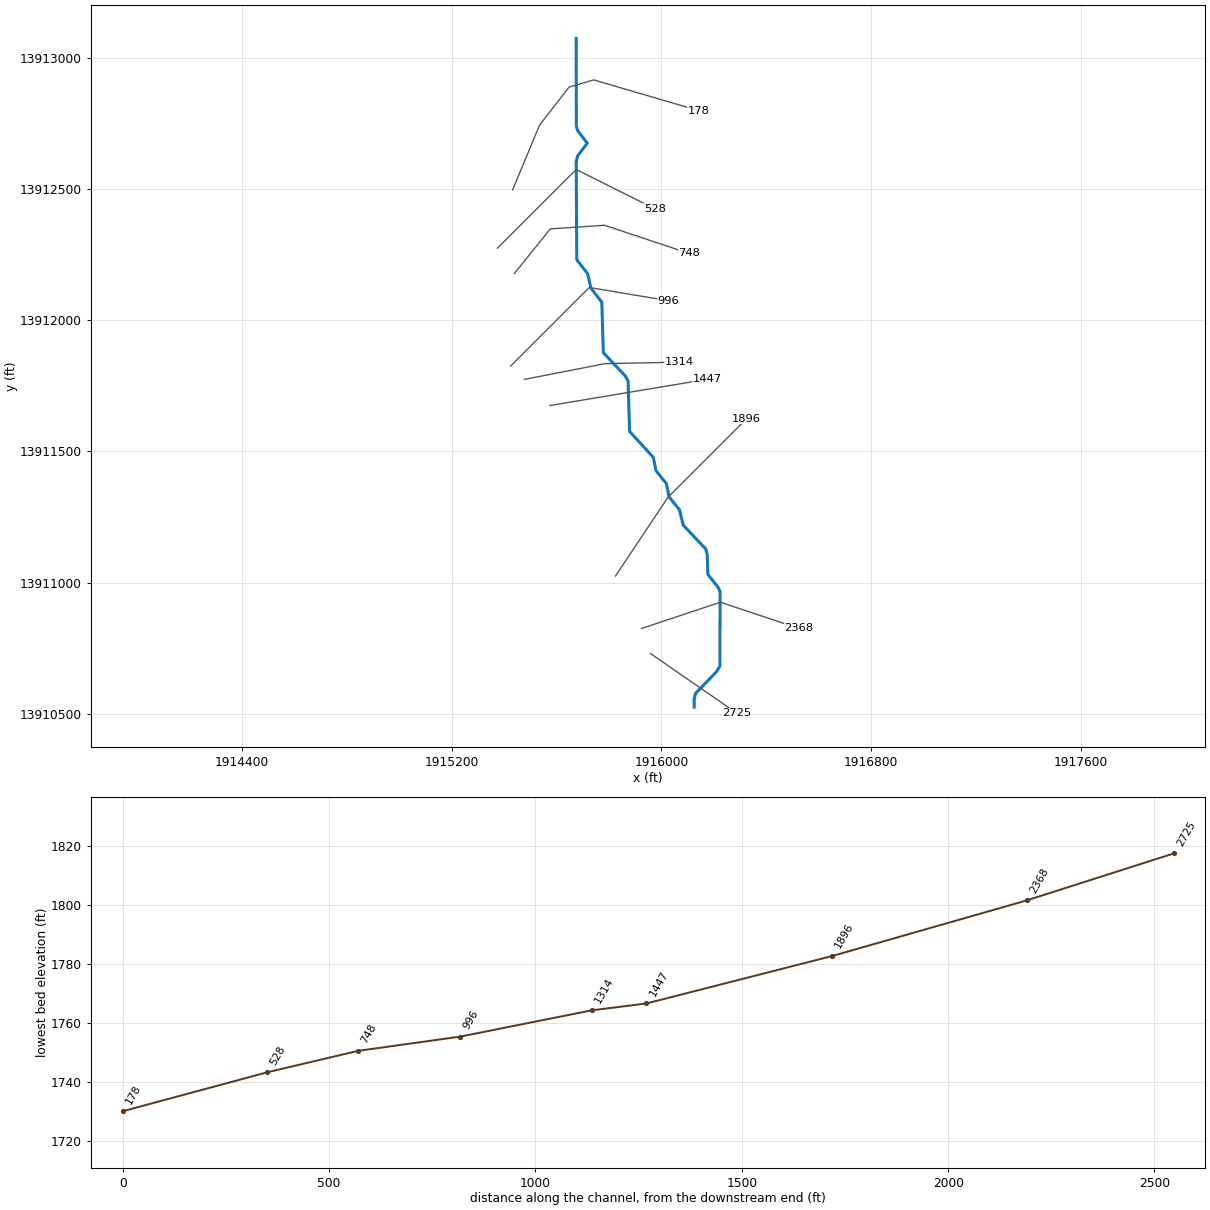
--- Stream0541.prj (project) ---

Proj Title=Stream0541 Base Level Engineering
Current Plan=p01
Default Exp/Contr=0.3,0.1
English Units
Geom File=g01
Flow File=f01
Plan File=p01
Y Axis Title=Elevation
X Axis Title(PF)=Main Channel Distance
X Axis Title(XS)=Station
BEGIN DESCRIPTION:
Stream0541
END DESCRIPTION:
DSS Export Rating Curves= 0
DSS Export Rating Curve Sorted= 0
DSS Export Volume Flow Curves= 0
DXF OffsetX= 0
DXF OffsetY= 0
DXF ScaleX= 1
DXF ScaleY= 10

--- Stream0541.p01 (plan) ---

Plan Title=Multiple Run
Short Identifier=Multiple
Geom File=g01
Flow File=f01
Subcritical Flow
K Sum by GR= 0
Std Step Tol= 0.01
Critical Tol= 0.01
Num of Std Step Trials= 20
Max Error Tol= 0.3
Flow Tol Ratio= 0.001
Split Flow NTrial= 30
Split Flow Tol= 0.02
Split Flow Ratio= 0.02
Log Output Level= 0
Friction Slope Method= 1
Unsteady Friction Slope Method= 2
Unsteady Bridges Friction Slope Method= 1
Parabolic Critical Depth
Global Vel Dist=  1 , 1 , 1
Global Log Level= 0
CheckData=True
Encroach Param= -1, 0, 0, 0
BEGIN DESCRIPTION:
Multiple Run
END DESCRIPTION:

--- Stream0541.f01 (steady flow) ---

Flow Title=Multiple
Program Version=4.10
Number of Profiles= 7
Profile Names=10-year,25-year,50-year,1pct_min,100-year,1pct_plu,500-year
River Rch & RM=Stream0541,Reach-1         ,2725
     473     767    1036     680    1358    2709    2292
Boundary for River Rch & Prof#=Stream0541,Reach-1         , 1
Up Type= 0
Dn Type= 3
Dn Slope=0.007
Boundary for River Rch & Prof#=Stream0541,Reach-1         , 2
Up Type= 0
Dn Type= 3
Dn Slope=0.007
Boundary for River Rch & Prof#=Stream0541,Reach-1         , 3
Up Type= 0
Dn Type= 3
Dn Slope=0.007
Boundary for River Rch & Prof#=Stream0541,Reach-1         , 4
Up Type= 0
Dn Type= 3
Dn Slope=0.007
Boundary for River Rch & Prof#=Stream0541,Reach-1         , 5
Up Type= 0
Dn Type= 3
Dn Slope=0.007
Boundary for River Rch & Prof#=Stream0541,Reach-1         , 6
Up Type= 0
Dn Type= 3
Dn Slope=0.007
Boundary for River Rch & Prof#=Stream0541,Reach-1         , 7
Up Type= 0
Dn Type= 3
Dn Slope=0.007
DSS Import GetInterval= 0
DSS Import GetPeak= 0
DSS Import FillOption= 0

--- Stream0541.g01 (geometry) ---

Geom Title=Existing Conditions

River Reach=Stream0541,Reach-1
Reach XY= 30
      1916125.00     13910525.00      1916124.93     13910556.88
      1916130.33     13910577.51      1916208.56     13910658.24
      1916222.94     13910680.85      1916223.78     13910964.50
      1916216.86     13910981.06      1916177.36     13911030.98
      1916174.87     13911104.95      1916169.46     13911127.42
      1916083.16     13911218.95      1916068.90     13911277.19
      1916029.16     13911326.72      1916018.92     13911377.20
      1915979.19     13911426.74      1915969.15     13911477.29
      1915878.55     13911576.47      1915872.93     13911769.14
      1915861.60     13911788.31      1915778.55     13911876.47
      1915772.76     13912069.07      1915731.12     13912122.82
      1915718.88     13912177.18      1915677.24     13912230.93
      1915675.18     13912605.02      1915681.02     13912627.45
      1915717.44     13912675.00      1915681.02     13912722.55
      1915675.66     13912740.16      1915675.00     13913075.00

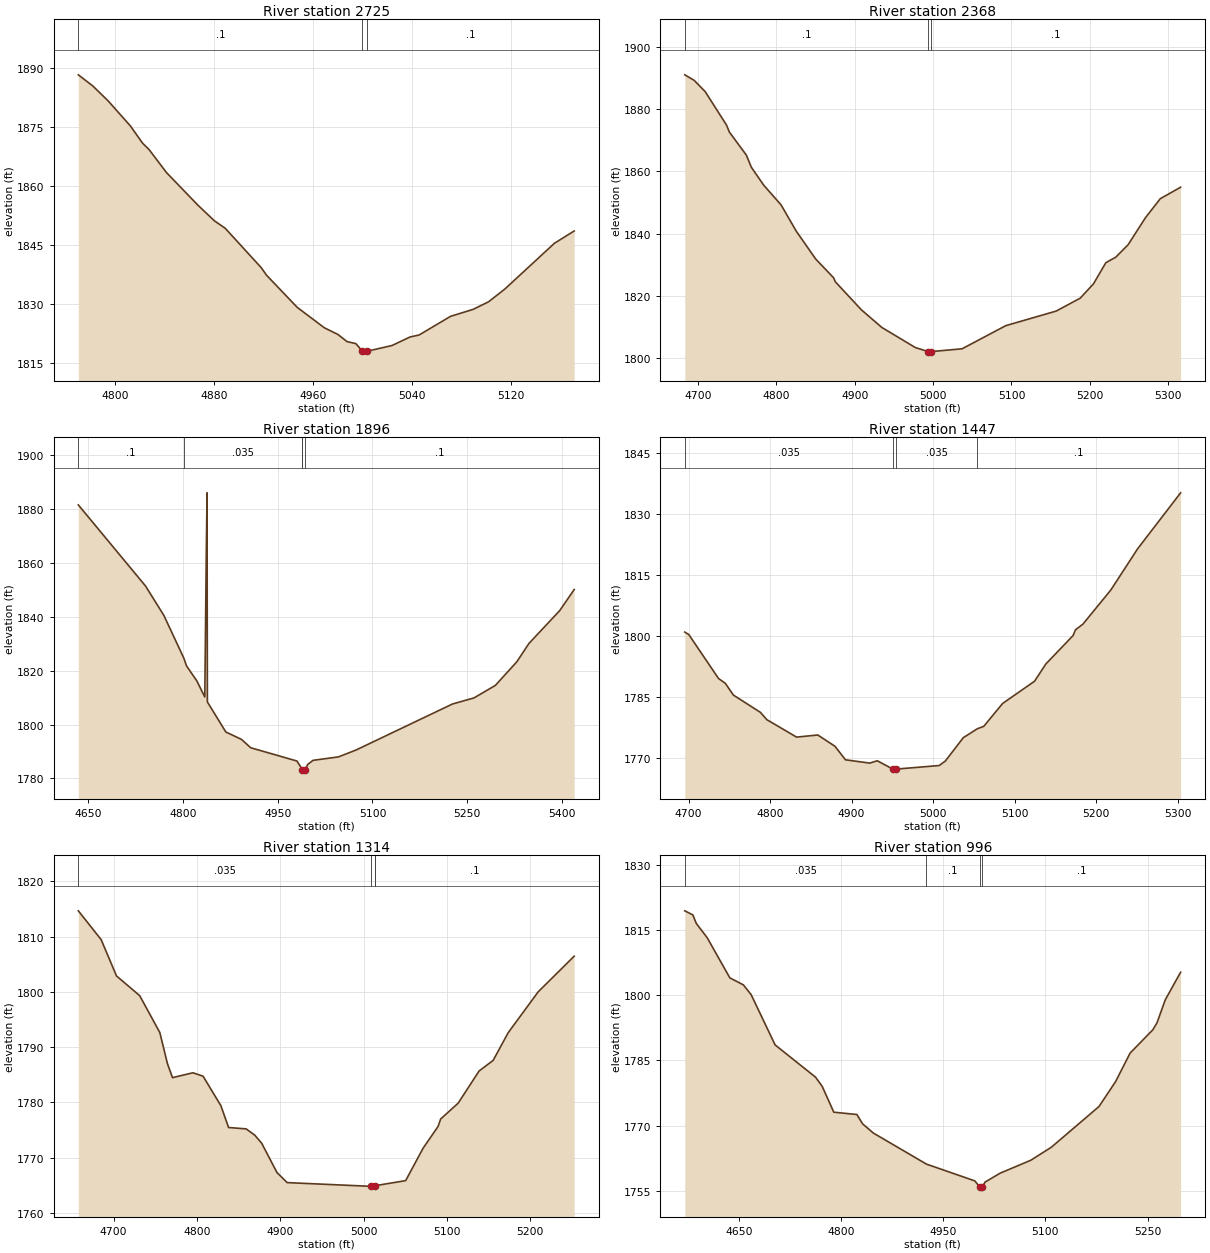
Type RM Length L Ch R = 1,2725,357,357,357
BEGIN DESCRIPTION:
Stream0541 6.0
END DESCRIPTION:
XS GIS Cut Line= 2
      1915958.79     13910729.03      1916288.64     13910501.18
#Sta/Elev= 30
  4770.0 1888.19  4781.6 1885.39  4793.9 1881.64  4812.1 1875.21  4821.9 1870.85
  4827.2 1869.21  4841.3 1863.36  4866.8 1855.05  4880.0 1851.12  4888.7 1849.24
  4917.9 1839.21  4922.2 1837.29  4947.0 1829.13  4968.9 1823.95  4979.9 1822.25
  4987.2 1820.45  4994.4 1819.92  4999.7 1818.01  5000.0 1817.51  5003.5 1817.51
  5003.7 1818.01  5023.6 1819.44  5038.2 1821.61  5045.5 1822.11  5071.0 1826.86
  5089.2 1828.62  5101.7 1830.55  5114.8 1833.77  5154.9 1845.40  5170.9 1848.53
#Mann=3,-1,0
  4770.0     0.1       0  4999.7    0.05       0  5003.7     0.1       0
Bank Sta=4999.7,5003.7
Exp/Cntr=0.3,0.1

Type RM Length L Ch R = 1,2368,472,472,472
BEGIN DESCRIPTION:
Stream0541 5.0
END DESCRIPTION:
XS GIS Cut Line= 3
      1915924.96     13910824.99      1916225.00     13910925.00
      1916525.00     13910825.00
#Sta/Elev= 30
  4683.3 1891.00  4695.2 1889.24  4709.4 1885.58  4736.5 1874.86  4740.2 1872.60
  4761.8 1865.21  4768.2 1861.30  4784.0 1855.53  4806.1 1849.21  4825.6 1840.71
  4850.4 1831.77  4873.1 1825.78  4875.4 1824.47  4908.6 1815.47  4934.7 1809.80
  4977.4 1803.35  4993.8 1802.06  4994.1 1801.56  4997.8 1802.06  5037.0 1802.95
  5092.8 1810.39  5157.1 1815.08  5187.7 1819.22  5204.6 1823.82  5220.4 1830.62
  5233.0 1832.38  5248.8 1836.39  5271.0 1845.10  5289.9 1851.20  5315.8 1854.88
#Mann=3,-1,0
  4683.3     0.1       0  4993.8    0.05       0  4997.8     0.1       0
Bank Sta=4993.8,4997.8
Exp/Cntr=0.3,0.1

Type RM Length L Ch R = 1,1896,449,449,449
BEGIN DESCRIPTION:
Stream0541 4.0
END DESCRIPTION:
XS GIS Cut Line= 3
      1915824.98     13911024.97      1916025.00     13911325.00
      1916325.04     13911625.04
#Sta/Elev= 30
  4634.4 1881.61  4740.8 1851.47  4769.7 1840.60  4801.4 1824.68  4805.7 1821.79
  4821.9 1816.25  4834.6 1810.24  4837.0 1864.47  4838.2 1886.10  4838.4 1846.79
  4838.7 1808.39  4867.9 1797.23  4892.8 1794.46  4907.2 1791.38  4980.4 1786.45
  4989.1 1783.27  4989.2 1783.19  4989.5 1782.69  4993.2 1783.19  4997.5 1785.18
  5006.0 1786.70  5046.4 1787.99  5073.9 1790.52  5226.7 1807.63  5260.8 1809.90
  5294.5 1814.53  5328.5 1823.30  5347.7 1830.12  5396.6 1842.38  5419.3 1850.16
#Mann=5,-1,0
  4634.4     0.1       0  4801.4   0.035       0  4989.1     0.1       0
  4989.2    0.05       0  4993.2     0.1       0
Bank Sta=4989.2,4993.2
Exp/Cntr=0.3,0.1

Type RM Length L Ch R = 1,1447,133,133,133
BEGIN DESCRIPTION:
Stream0541 3.0
END DESCRIPTION:
XS GIS Cut Line= 3
      1915574.97     13911675.00      1915875.00     13911725.00
      1916175.00     13911775.00
#Sta/Elev= 30
  4695.4 1800.93  4700.3 1800.32  4736.8 1789.48  4745.1 1788.30  4755.0 1785.40
  4788.2 1781.13  4796.0 1779.34  4832.5 1775.03  4858.6 1775.55  4879.7 1772.76
  4892.5 1769.43  4922.3 1768.62  4931.6 1769.19  4950.7 1767.14  4951.0 1766.64
  4954.7 1767.14  5007.5 1768.02  5015.0 1769.12  5037.1 1774.89  5054.3 1777.09
  5062.2 1777.69  5085.4 1783.34  5124.5 1788.81  5138.3 1793.05  5171.7 1800.06
  5174.8 1801.51  5183.9 1802.90  5218.3 1811.37  5250.8 1821.43  5303.7 1835.27
#Mann=4,-1,0
  4695.4   0.035       0  4950.7   0.035       0  4954.7   0.035       0
  5054.3     0.1       0
Bank Sta=4950.7,4954.7
Exp/Cntr=0.3,0.1

Type RM Length L Ch R = 1,1314,318,318,318
BEGIN DESCRIPTION:
Mapping XS 0f03db89
END DESCRIPTION:
XS GIS Cut Line= 3
      1915477.86     13911774.62      1915785.32     13911834.65
      1916066.99     13911840.37
#Sta/Elev= 30
  4657.6 1814.65  4685.0 1809.44  4703.4 1802.87  4731.2 1799.31  4755.4 1792.63
  4764.5 1787.02  4770.6 1784.47  4795.1 1785.35  4807.3 1784.73  4828.7 1779.39
  4837.9 1775.45  4859.0 1775.20  4869.3 1774.07  4877.6 1772.61  4896.0 1767.30
  4908.2 1765.48  5009.4 1764.80  5009.6 1764.30  5013.4 1764.80  5014.2 1764.93
  5050.4 1765.84  5071.4 1771.72  5089.3 1775.64  5092.4 1776.99  5113.4 1779.85
  5138.5 1785.67  5155.4 1787.59  5173.4 1792.59  5209.4 1799.99  5252.6 1806.44
#Mann=4,-1,0
  4657.6   0.035       0  5009.4   0.035       0  5013.4   0.035       0
  5014.2     0.1       0
Bank Sta=5009.4,5013.4
Exp/Cntr=0.3,0.1

Type RM Length L Ch R = 1,996,248,248,248
BEGIN DESCRIPTION:
Stream0541 2.0
END DESCRIPTION:
XS GIS Cut Line= 3
      1915425.02     13911825.02      1915725.00     13912125.00
      1916025.03     13912074.99
#Sta/Elev= 30
  4570.2 1819.37  4582.0 1818.44  4587.1 1816.47  4603.2 1813.17  4636.4 1803.96
  4656.3 1802.35  4667.7 1800.10  4702.9 1788.55  4762.3 1781.14  4772.1 1779.02
  4789.1 1773.09  4823.0 1772.56  4831.5 1770.40  4847.2 1768.30  4925.2 1761.16
  4996.3 1757.30  5003.4 1755.91  5003.6 1755.41  5007.4 1755.91  5011.2 1757.01
  5033.1 1759.05  5078.4 1762.04  5108.8 1765.05  5178.7 1774.40  5203.1 1780.13
  5224.4 1786.68  5257.8 1792.03  5263.9 1793.64  5276.1 1798.94  5298.6 1805.26
#Mann=4,-1,0
  4570.2   0.035       0  4925.2     0.1       0  5003.4    0.05       0
  5007.4     0.1       0
Bank Sta=5003.4,5007.4
Exp/Cntr=0.3,0.1

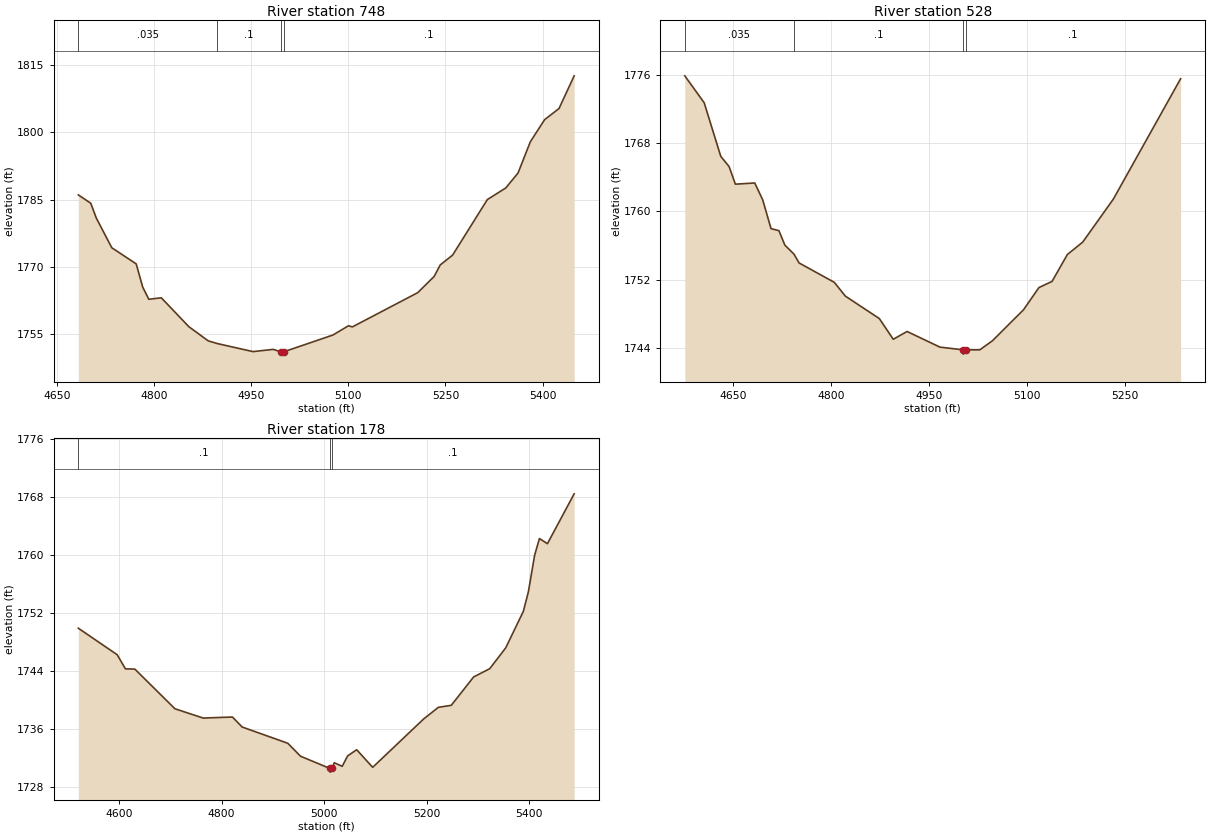
Type RM Length L Ch R = 1,748,220,220,220
BEGIN DESCRIPTION:
Stream0541 2.1
END DESCRIPTION:
XS GIS Cut Line= 4
      1915439.35     13912178.35      1915576.49     13912348.47
      1915783.08     13912362.35      1916106.04     13912254.70
#Sta/Elev= 30
  4682.8 1786.05  4702.0 1784.19  4710.6 1780.88  4734.5 1774.27  4772.2 1770.68
  4782.3 1765.49  4791.7 1762.79  4811.0 1763.12  4853.5 1756.69  4883.4 1753.53
  4897.7 1752.92  4952.7 1751.13  4983.9 1751.63  4995.8 1751.07  4996.1 1750.57
  4999.8 1751.07  5076.0 1754.82  5100.2 1756.89  5106.1 1756.63  5207.2 1764.27
  5232.5 1767.88  5241.9 1770.44  5261.0 1772.63  5314.7 1785.01  5343.1 1787.59
  5362.1 1790.92  5381.1 1797.88  5403.2 1802.82  5425.4 1805.29  5448.8 1812.58
#Mann=4,-1,0
  4682.8   0.035       0  4897.7     0.1       0  4995.8    0.05       0
  4999.8     0.1       0
Bank Sta=4995.8,4999.8
Exp/Cntr=0.3,0.1

Type RM Length L Ch R = 1,528,350,350,350
BEGIN DESCRIPTION:
Stream0541 1.0
END DESCRIPTION:
XS GIS Cut Line= 3
      1915374.98     13912274.98      1915675.00     13912575.00
      1915975.00     13912425.00
#Sta/Elev= 30
  4576.2 1775.87  4605.9 1772.72  4631.3 1766.45  4644.1 1765.25  4653.7 1763.19
  4683.4 1763.33  4695.6 1761.35  4708.3 1757.99  4720.4 1757.75  4729.5 1756.06
  4743.5 1755.00  4751.3 1753.97  4805.3 1751.70  4822.2 1750.09  4874.3 1747.46
  4895.6 1745.04  4916.8 1745.95  4967.1 1744.12  5002.7 1743.80  5003.0 1743.30
  5006.7 1743.80  5028.2 1743.80  5047.5 1744.86  5095.3 1748.50  5118.8 1751.09
  5138.9 1751.81  5162.4 1754.96  5185.9 1756.41  5232.8 1761.44  5335.9 1775.53
#Mann=4,-1,0
  4576.2   0.035       0  4743.5     0.1       0  5002.7    0.05       0
  5006.7     0.1       0
Bank Sta=5002.7,5006.7
Exp/Cntr=0.3,0.1

Type RM Length L Ch R = 1,178,0,0,0
BEGIN DESCRIPTION:
Stream0541 0.0
END DESCRIPTION:
XS GIS Cut Line= 5
      1915432.63     13912497.08      1915535.36     13912743.97
      1915648.01     13912889.20      1915741.76     13912916.55
      1916142.82     13912799.35
#Sta/Elev= 30
  4520.7 1749.91  4596.5 1746.26  4612.5 1744.32  4631.0 1744.28  4709.0 1738.83
  4764.0 1737.55  4821.2 1737.69  4840.0 1736.32  4929.1 1734.08  4953.9 1732.30
  5011.4 1730.61  5011.6 1730.11  5015.4 1730.61  5019.6 1731.40  5035.2 1730.91
  5045.7 1732.34  5063.4 1733.19  5094.6 1730.77  5193.9 1737.42  5222.8 1739.03
  5247.8 1739.30  5291.5 1743.21  5322.8 1744.34  5354.0 1747.21  5388.4 1752.24
  5398.2 1754.94  5410.4 1759.97  5419.7 1762.25  5435.3 1761.54  5487.4 1768.40
#Mann=3,-1,0
  4520.7     0.1       0  5011.4    0.05       0  5015.4     0.1       0
Bank Sta=5011.4,5015.4
Exp/Cntr=0.3,0.1

Chan Stop Cuts=-1