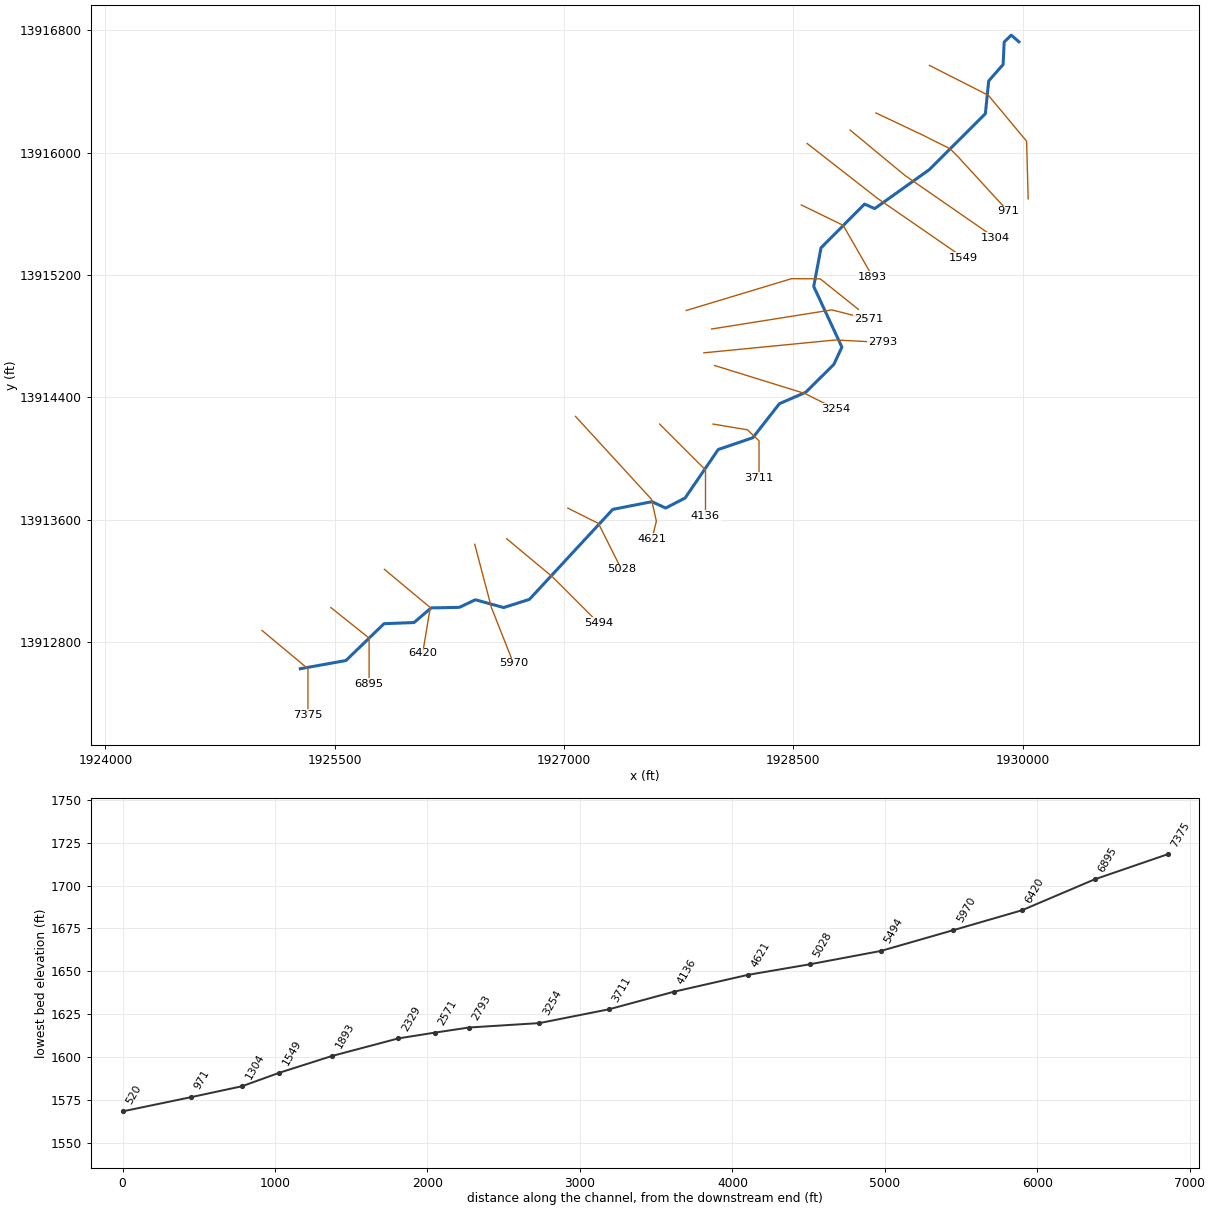
--- Stream0545.prj (project) ---

Proj Title=Stream0545 Base Level Engineering
Current Plan=p01
Default Exp/Contr=0.3,0.1
English Units
Geom File=g01
Flow File=f01
Plan File=p01
Y Axis Title=Elevation
X Axis Title(PF)=Main Channel Distance
X Axis Title(XS)=Station
BEGIN DESCRIPTION:
Stream0545
END DESCRIPTION:
DSS Export Rating Curves= 0
DSS Export Rating Curve Sorted= 0
DSS Export Volume Flow Curves= 0
DXF OffsetX= 0
DXF OffsetY= 0
DXF ScaleX= 1
DXF ScaleY= 10

--- Stream0545.p01 (plan) ---

Plan Title=Multiple Run
Short Identifier=Multiple
Geom File=g01
Flow File=f01
Subcritical Flow
K Sum by GR= 0
Std Step Tol= 0.01
Critical Tol= 0.01
Num of Std Step Trials= 20
Max Error Tol= 0.3
Flow Tol Ratio= 0.001
Split Flow NTrial= 30
Split Flow Tol= 0.02
Split Flow Ratio= 0.02
Log Output Level= 0
Friction Slope Method= 1
Unsteady Friction Slope Method= 2
Unsteady Bridges Friction Slope Method= 1
Parabolic Critical Depth
Global Vel Dist=  1 , 1 , 1
Global Log Level= 0
CheckData=True
Encroach Param= -1, 0, 0, 0
BEGIN DESCRIPTION:
Multiple Run
END DESCRIPTION:

--- Stream0545.f01 (steady flow) ---

Flow Title=Multiple
Number of Profiles=7
Profile Names=10-year,25-year,50-year,1pct_min,100-year,1pct_plu,500-year
River Rch & RM= Stream0545,Reach-1,7375
     807    1355    1872    1253    2501    4990    4401
River Rch & RM= Stream0545,Reach-1,1893
     944    1600    2222    1495    2984    5953    5305
Boundary for River Rch & Prof#=Stream0545,Reach-1,1
Up Type=0
Dn Type=3
Dn Slope=0.005
Boundary for River Rch & Prof#=Stream0545,Reach-1,2
Up Type=0
Dn Type=3
Dn Slope=0.005
Boundary for River Rch & Prof#=Stream0545,Reach-1,3
Up Type=0
Dn Type=3
Dn Slope=0.005
Boundary for River Rch & Prof#=Stream0545,Reach-1,4
Up Type=0
Dn Type=3
Dn Slope=0.005
Boundary for River Rch & Prof#=Stream0545,Reach-1,5
Up Type=0
Dn Type=3
Dn Slope=0.005
Boundary for River Rch & Prof#=Stream0545,Reach-1,6
Up Type=0
Dn Type=3
Dn Slope=0.005
Boundary for River Rch & Prof#=Stream0545,Reach-1,7
Up Type=0
Dn Type=3
Dn Slope=0.005

--- Stream0545.g01 (geometry) ---

Geom Title=Existing Conditions
Program Version=4.10

River Reach=Stream0545      ,Reach-1
Reach XY= 30
        1925275.       13912625.      1925573.54     13912678.54
      1925822.55     13912919.54      1926019.14     13912927.07
      1926130.86     13913022.93       1926314.5     13913026.22
      1926420.28      13913075.9      1926604.94     13913025.05
       1926773.5     13913078.61      1927318.79      13913667.2
      1927575.01     13913717.41       1927664.3      13913675.8
      1927791.71     13913741.63      1928008.21     13914058.56
      1928234.71     13914135.75      1928408.29     13914358.37
      1928581.06     13914433.14      1928764.25     13914615.32
      1928816.95     13914728.29      1928632.78      13915125.1
      1928680.52     13915377.43        1928965.     13915663.76
      1929031.67      13915634.3      1929388.21     13915888.63
       1929755.4     13916254.84      1929777.07     13916469.14
      1929871.44     13916576.47      1929878.49     13916723.96
      1929924.67     13916768.56        1929975.       13916725.

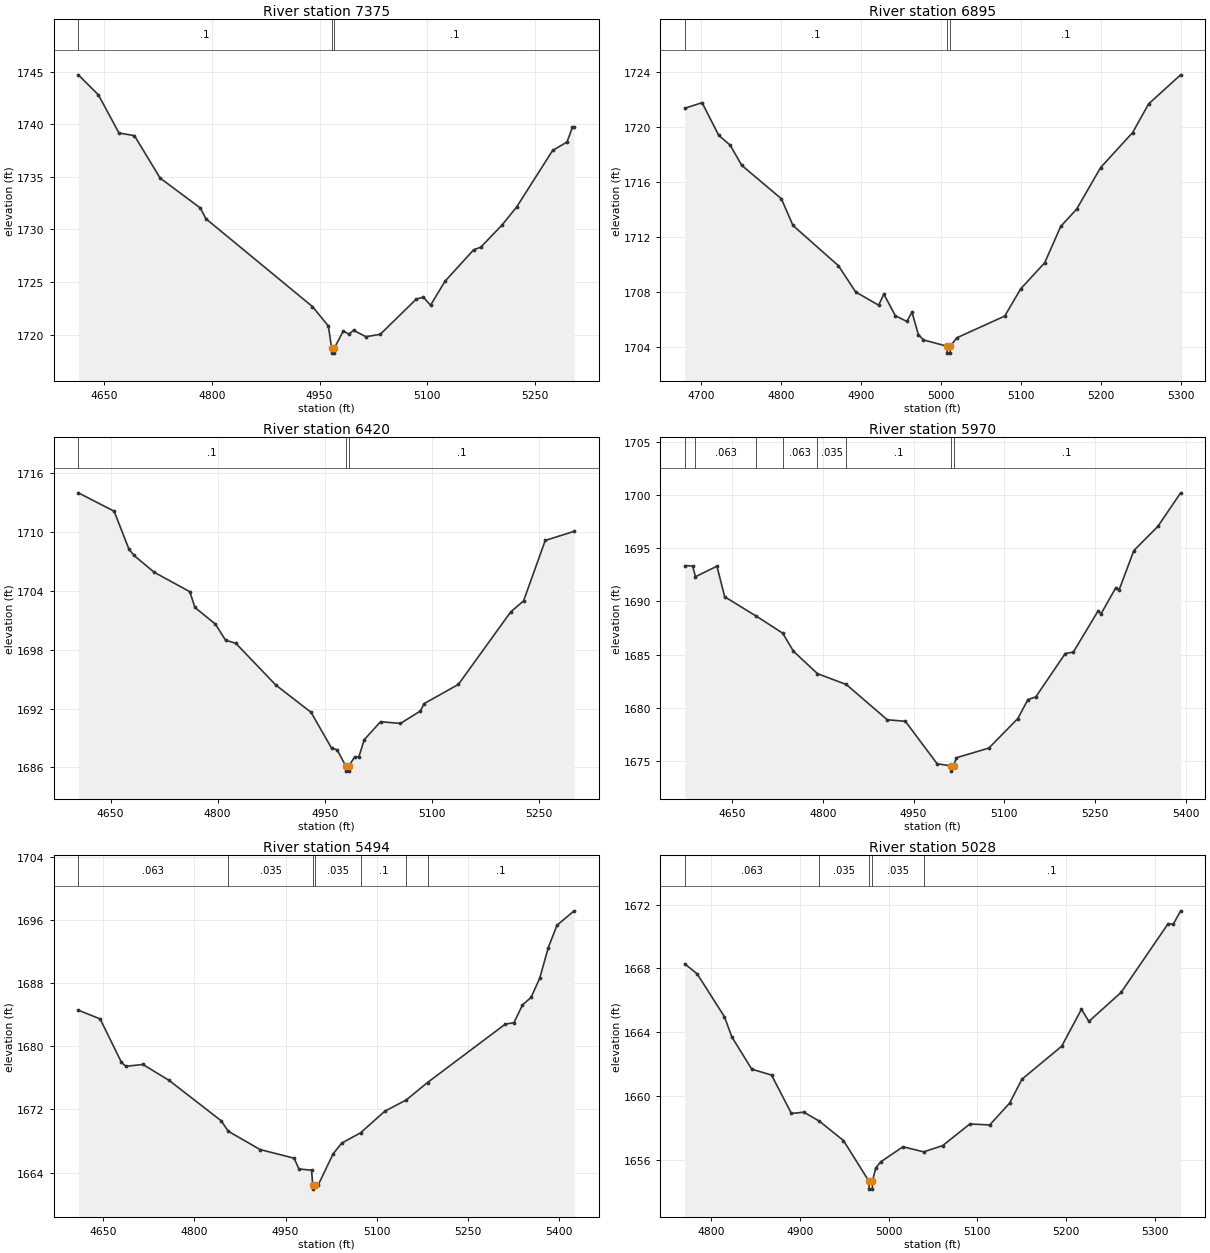
Type RM Length L Ch R = 1 ,7375    ,480,480,480
BEGIN DESCRIPTION:
Stream0545 16.0
END DESCRIPTION:
XS GIS Cut Line= 3
      1925025.01     13912874.99        1925325.       13912625.
        1925325.       13912325.
#Sta/Elev= 30
  4614.1 1744.69  4642.1 1742.78  4670.7 1739.16  4692.2 1738.91    4728 1734.88
    4784 1732.03  4791.8 1731.01  4940.2 1722.66  4962.3 1720.82  4966.8 1718.74
  4967.1 1718.24  4970.6 1718.24  4970.8 1718.74  4983.1 1720.35  4990.9 1720.04
  4997.4 1720.41  5014.6  1719.8  5034.6 1720.03  5084.6 1723.37  5094.6 1723.56
  5104.6 1722.79  5124.6 1725.06  5164.6 1728.06  5174.6 1728.31  5204.6 1730.45
  5224.6 1732.14  5274.6  1737.5  5294.6  1738.3  5302.1 1739.69  5304.6 1739.69
#Mann= 3 ,-1 , 0
  4614.1      .1       0  4966.8     .05       0  4970.8      .1       0
Bank Sta=4966.8,4970.8
XS Rating Curve= 0 ,0
Exp/Cntr=0.3,0.1

Type RM Length L Ch R = 1 ,6895    ,475,475,475
BEGIN DESCRIPTION:
Stream0545 15.0
END DESCRIPTION:
XS GIS Cut Line= 3
      1925475.01     13913024.99        1925725.       13912825.
        1925725.     13912525.04
#Sta/Elev= 30
  4679.9 1721.37  4701.5 1721.78  4722.3 1719.41  4736.7 1718.69  4751.1 1717.23
  4800.7  1714.8  4815.2 1712.86    4872 1709.94  4893.6 1708.03  4922.4 1707.07
  4928.8 1707.88  4943.2 1706.31  4957.6 1705.89    4964 1706.56    4972 1704.94
  4978.4 1704.55    5008 1704.09  5008.3 1703.59  5011.8 1703.59    5012 1704.09
    5020  1704.7    5080 1706.28    5100 1708.26    5130 1710.15    5150 1712.79
    5170 1714.05    5200 1717.07    5240 1719.61    5260 1721.69    5300  1723.8
#Mann= 3 ,-1 , 0
  4679.9      .1       0    5008     .05       0    5012      .1       0
Bank Sta=5008,5012
XS Rating Curve= 0 ,0
Exp/Cntr=0.3,0.1

Type RM Length L Ch R = 1 ,6420    ,450,450,450
BEGIN DESCRIPTION:
Stream0545 14.0
END DESCRIPTION:
XS GIS Cut Line= 3
      1925825.02     13913274.98        1926125.       13913025.
        1926075.     13912725.02
#Sta/Elev= 30
  4604.8 1713.97  4654.9  1712.1  4675.7 1708.24  4682.9 1707.59  4710.9 1705.89
    4761  1703.9  4768.1  1702.3  4796.8  1700.6  4811.1 1698.96  4825.4 1698.65
  4881.4  1694.4  4930.8 1691.62  4959.5 1687.98  4967.3 1687.81  4979.6 1686.13
  4979.9 1685.63  4983.4 1685.63  4983.6 1686.13    4992 1687.09  4997.8 1687.09
  5005.4 1688.84  5028.2 1690.66  5056.1 1690.49    5084 1691.75  5089.1  1692.5
  5137.2 1694.46  5210.7 1701.86  5228.5 1702.96  5258.9 1709.12  5299.4 1710.05
#Mann= 3 ,-1 , 0
  4604.8      .1       0  4979.6     .05       0  4983.6      .1       0
Bank Sta=4979.6,4983.6
XS Rating Curve= 0 ,0
Exp/Cntr=0.3,0.1

Type RM Length L Ch R = 1 ,5970    ,476,476,476
BEGIN DESCRIPTION:
Stream0545 13.0
END DESCRIPTION:
XS GIS Cut Line= 3
      1926415.72      13913438.8        1926525.       13913025.
      1926669.16     13912659.91
#Sta/Elev= 30
  4571.4 1693.37  4584.3 1693.34  4589.1 1692.33  4624.6 1693.32  4637.4 1690.44
    4690 1688.61  4733.4 1687.02  4751.2 1685.32  4790.9 1683.21  4838.7 1682.19
  4906.5 1678.87  4936.4 1678.73    4989 1674.73  5012.3 1674.54  5012.5 1674.04
  5016.3 1674.54  5020.9  1675.3  5074.6 1676.21  5122.5 1678.99  5139.2 1680.77
  5152.2 1681.02  5200.9  1685.1  5214.4 1685.24    5255 1689.08  5260.4 1688.86
  5284.8 1691.31  5290.2  1691.1  5314.5 1694.79  5354.2 1697.06  5391.9 1700.22
#Mann= 8 ,-1 , 0
  4571.4    .094       0  4589.1    .063       0    4690    .035       0
  4733.4    .063       0  4790.9    .035       0  4838.7      .1       0
  5012.3     .05       0  5016.3      .1       0
Bank Sta=5012.3,5016.3
XS Rating Curve= 0 ,0
Exp/Cntr=0.3,0.1

Type RM Length L Ch R = 1 ,5494    ,466,466,466
BEGIN DESCRIPTION:
Stream0545 12.0
END DESCRIPTION:
XS GIS Cut Line= 3
      1926625.02     13913474.98        1926925.       13913225.
      1927225.03     13912924.97
#Sta/Elev= 30
  4609.5 1684.57  4645.3 1683.46  4680.4 1677.96  4687.6 1677.46  4715.6  1677.7
  4758.5 1675.69  4843.8  1670.6    4856 1669.24  4908.2 1666.93  4964.2 1665.83
    4972 1664.47  4992.8 1664.32  4994.7 1662.42    4995 1661.92  4998.7 1662.42
  5003.5 1662.42  5028.3  1666.4  5042.4 1667.74  5073.5 1669.06  5113.1 1671.78
  5148.5 1673.21  5183.3 1675.41  5311.1  1682.8  5325.3 1682.98  5339.4 1685.23
  5353.5 1686.19  5367.7 1688.61  5381.8 1692.48    5396 1695.31  5424.3 1697.14
#Mann= 7 ,-1 , 0
  4609.5    .063       0    4856    .035       0  4994.7    .035       0
  4998.7    .035       0  5073.5      .1       0  5148.5     .07       0
  5183.3      .1       0
Bank Sta=4994.7,4998.7
XS Rating Curve= 0 ,0
Exp/Cntr=0.3,0.1

Type RM Length L Ch R = 1 ,5028    ,407,407,407
BEGIN DESCRIPTION:
Stream0545 11.0
END DESCRIPTION:
XS GIS Cut Line= 3
        1927025.       13913675.        1927225.       13913575.
      1927374.99     13913275.02
#Sta/Elev= 30
  4770.3 1668.29  4784.3 1667.66    4815 1664.97  4823.4  1663.7  4845.8 1661.68
  4868.1 1661.31  4890.5  1658.9  4904.5 1658.98  4921.9 1658.42  4949.2  1657.2
  4977.9 1654.65  4978.2 1654.15  4981.7 1654.15  4981.9 1654.65  4985.5 1655.47
  4991.1 1655.86  5016.3 1656.81  5039.6 1656.49    5061 1656.88  5091.7 1658.24
  5114.1 1658.18  5136.5 1659.55  5150.4 1661.05  5195.2 1663.12  5217.5 1665.44
  5225.9 1664.68  5262.2  1666.5  5315.3 1670.82  5320.9 1670.77  5329.3 1671.62
#Mann= 5 ,-1 , 0
  4770.3    .063       0  4921.9    .035       0  4977.9    .035       0
  4981.9    .035       0  5039.6      .1       0
Bank Sta=4977.9,4981.9
XS Rating Curve= 0 ,0
Exp/Cntr=0.3,0.1

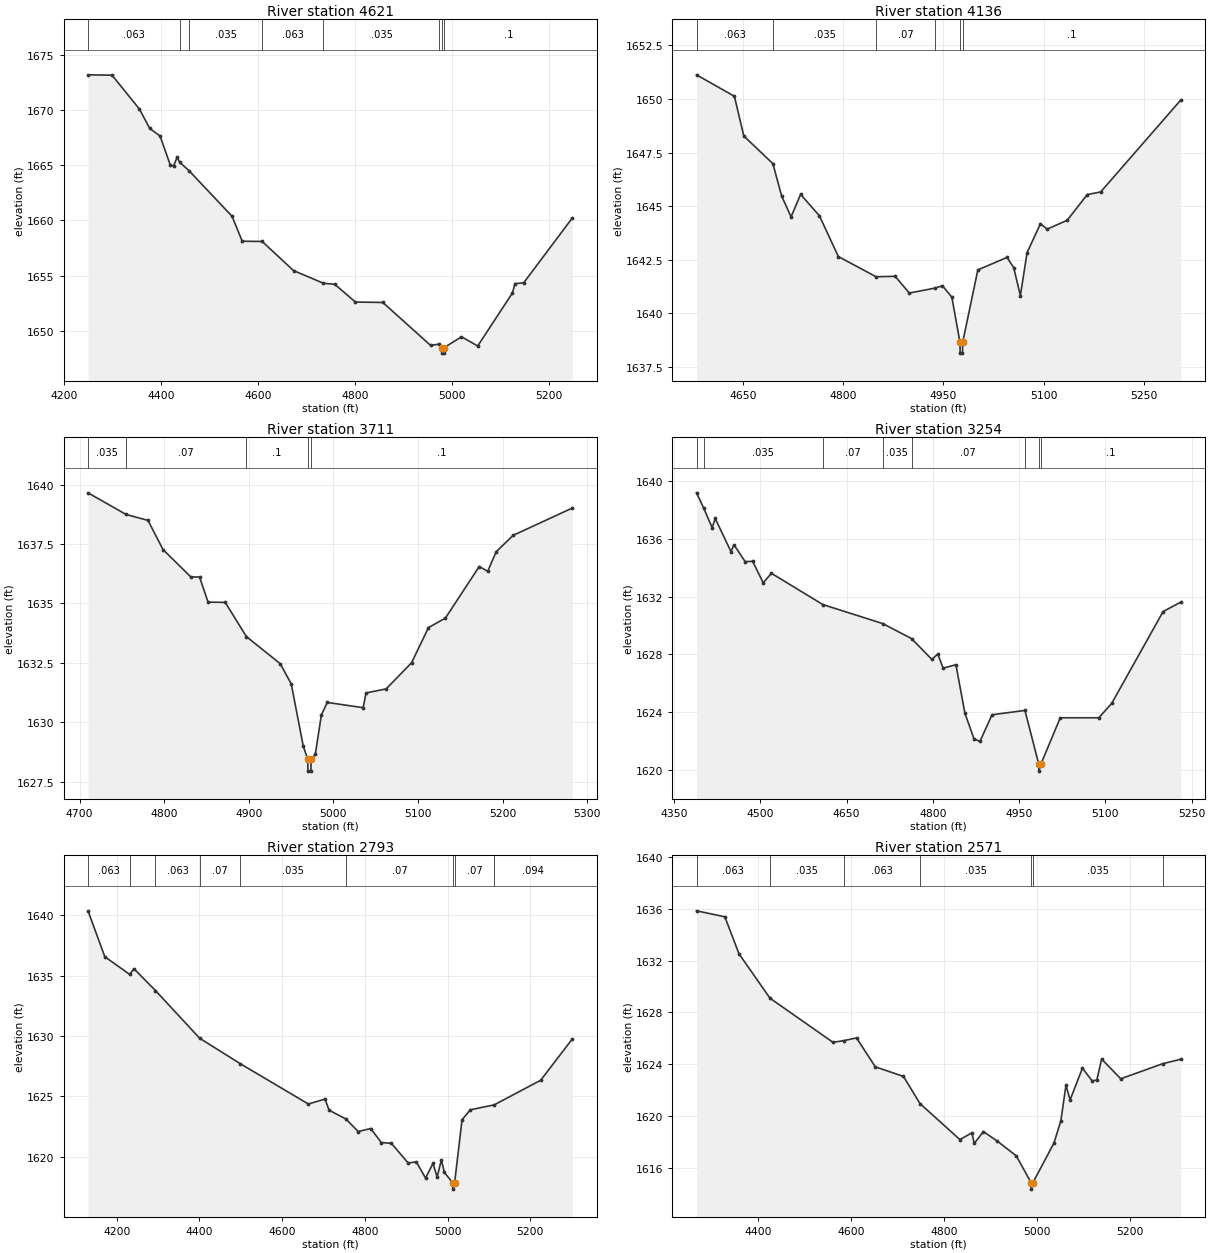
Type RM Length L Ch R = 1 ,4621    ,485,485,485
BEGIN DESCRIPTION:
Stream0545 10.0
END DESCRIPTION:
XS GIS Cut Line= 4
      1927075.02     13914274.98       1927571.5     13913733.36
      1927603.69     13913589.77        1927575.       13913475.
#Sta/Elev= 30
  4248.9 1673.19  4298.5 1673.16  4355.2 1670.08  4376.2 1668.34  4397.8 1667.64
  4418.7 1665.03  4425.5 1664.92  4432.9 1665.72  4438.5 1665.25  4457.4 1664.51
  4546.4 1660.37  4567.4 1658.11  4608.5 1658.09  4673.4 1655.45  4735.2  1654.3
  4758.5 1654.21  4801.1  1652.6  4857.8 1652.56  4956.4 1648.67  4974.6 1648.79
  4980.5 1648.47  4980.8 1647.97  4984.3 1647.97  4984.5 1648.47  5020.2 1649.45
  5053.7 1648.62  5125.4 1653.42  5130.7 1654.27  5148.6 1654.34  5249.1 1660.22
#Mann= 8 ,-1 , 0
  4248.9    .063       0  4438.5    .094       0  4457.4    .035       0
  4608.5    .063       0  4735.2    .035       0  4974.6      .1       0
  4980.5     .05       0  4984.5      .1       0
Bank Sta=4980.5,4984.5
XS Rating Curve= 0 ,0
Exp/Cntr=0.3,0.1

Type RM Length L Ch R = 1 ,4136    ,425,425,425
BEGIN DESCRIPTION:
Stream0545 9.0
END DESCRIPTION:
XS GIS Cut Line= 3
      1927625.01     13914224.99        1927925.       13913925.
        1927925.     13913624.95
#Sta/Elev= 30
  4580.8 1651.12  4637.4 1650.12  4651.5 1648.27    4695 1646.98  4708.1 1645.47
  4722.2  1644.5  4736.4 1645.55  4764.6 1644.55  4792.9 1642.65  4849.3 1641.71
  4877.8 1641.73    4899 1640.95  4937.3 1641.18  4948.5 1641.29  4962.6 1640.76
  4974.8 1638.65    4975 1638.15  4978.5 1638.15  4978.8 1638.65  5001.5 1642.03
  5045.1 1642.61  5055.1 1642.14  5065.1 1640.83  5075.1 1642.83  5095.1 1644.18
  5105.1 1643.93  5135.1 1644.34  5165.1 1645.54  5185.1 1645.66  5305.1 1649.95
#Mann= 6 ,-1 , 0
  4580.8    .063       0    4695    .035       0  4849.3     .07       0
  4937.3      .1       0  4974.8     .05       0  4978.8      .1       0
Bank Sta=4974.8,4978.8
XS Rating Curve= 0 ,0
Exp/Cntr=0.3,0.1

Type RM Length L Ch R = 1 ,3711    ,457,457,457
BEGIN DESCRIPTION:
Stream0545 8.0
END DESCRIPTION:
XS GIS Cut Line= 4
      1927975.03     13914224.99      1928199.15     13914187.64
        1928275.     13914115.61        1928275.     13913875.02
#Sta/Elev= 30
    4710 1639.65    4755 1638.74  4780.9 1638.49  4798.7 1637.26  4831.6 1636.11
  4841.8 1636.11  4851.9 1635.05  4872.2 1635.04  4897.2  1633.6  4937.2 1632.46
  4950.2 1631.61  4964.4 1628.99  4969.7 1628.44  4969.9 1627.94  4973.4 1627.94
  4973.7 1628.44  4978.6 1628.64  4985.8  1630.3  4992.7 1630.83  5035.2 1630.61
  5038.6 1631.23  5062.4  1631.4  5092.4  1632.5  5112.4 1633.98  5132.4 1634.38
  5172.4 1636.55  5182.4 1636.35  5192.4 1637.17  5212.4 1637.86  5282.4 1639.01
#Mann= 5 ,-1 , 0
    4710    .035       0    4755     .07       0  4897.2      .1       0
  4969.7     .05       0  4973.7      .1       0
Bank Sta=4969.7,4973.7
XS Rating Curve= 0 ,0
Exp/Cntr=0.3,0.1

Type RM Length L Ch R = 1 ,3254    ,461,461,461
BEGIN DESCRIPTION:
Stream0545 7.0
END DESCRIPTION:
XS GIS Cut Line= 3
      1927984.28     13914608.15        1928575.       13914425.
      1928775.03     13914324.99
#Sta/Elev= 30
  4389.1 1639.19  4401.3 1638.15  4416.3 1636.77  4421.6 1637.41  4448.9 1635.12
  4454.2 1635.59  4473.6 1634.42  4486.7 1634.44    4505 1632.95  4519.3 1633.61
  4608.8 1631.44    4713 1630.12    4763 1629.08  4798.2 1627.64  4808.6 1628.01
  4817.9 1627.03  4840.1 1627.27  4855.7 1623.91  4871.5 1622.13  4881.9 1621.95
  4902.9  1623.8  4960.1  1624.1    4984 1620.39  4984.3 1619.89    4988 1620.39
  5021.5 1623.59  5088.6 1623.59    5111 1624.59  5200.4 1630.96  5231.2 1631.61
#Mann= 8 ,-1 , 0
  4389.1    .063       0  4401.3    .035       0  4608.8     .07       0
    4713    .035       0    4763     .07       0  4960.1      .1       0
    4984     .05       0    4988      .1       0
Bank Sta=4984,4988
XS Rating Curve= 0 ,0
Exp/Cntr=0.3,0.1

Type RM Length L Ch R = 1 ,2793    ,222,222,222
BEGIN DESCRIPTION:
Stream0545 6.0
END DESCRIPTION:
XS GIS Cut Line= 3
      1927914.58     13914691.03        1928775.       13914775.
      1929081.39     13914759.22
#Sta/Elev= 30
  4130.5 1640.37  4171.1 1636.57  4231.4  1635.1  4241.4 1635.58  4293.6 1633.77
  4400.4 1629.82  4499.2  1627.7  4663.4 1624.37  4703.6 1624.78  4713.7 1623.85
  4754.2 1623.13    4784 1622.09  4814.2 1622.34  4839.9 1621.18  4864.4 1621.11
  4904.6 1619.49  4924.7 1619.57  4946.7 1618.24  4964.9 1619.45  4974.9 1618.32
    4985 1619.74  4992.5  1618.7    5013 1617.82  5013.3 1617.32    5017 1617.82
  5035.1 1623.07  5055.1 1623.89  5112.9  1624.3  5225.3 1626.34  5301.8 1629.76
#Mann= 9 ,-1 , 0
  4130.5    .063       0  4231.4    .035       0  4293.6    .063       0
  4400.4     .07       0  4499.2    .035       0  4754.2     .07       0
    5013     .05       0    5017     .07       0  5112.9    .094       0
Bank Sta=5013,5017
XS Rating Curve= 0 ,0
Exp/Cntr=0.3,0.1

Type RM Length L Ch R = 1 ,2571    ,242,242,242
BEGIN DESCRIPTION:
Mapping XS 7753134c
END DESCRIPTION:
XS GIS Cut Line= 3
      1927964.72     13914846.68      1928751.24     13914971.88
      1928990.42     13914910.73
#Sta/Elev= 30
  4267.3 1635.84  4328.3 1635.38  4358.7 1632.53  4425.6  1629.1  4561.2  1625.7
  4584.4 1625.83  4611.9 1626.04  4652.4 1623.81  4713.1 1623.07  4748.6 1620.98
  4834.6  1618.2  4860.4 1618.72  4865.5  1617.9  4885.3 1618.82  4915.6 1618.07
  4956.2 1616.94  4987.9 1614.88  4988.1 1614.38  4991.9 1614.88  5037.2 1617.93
  5052.1 1619.65  5063.1 1622.39    5072 1621.26  5098.6 1623.71  5119.2 1622.74
  5129.5 1622.78  5139.9 1624.41  5181.1 1622.89  5271.4 1624.05  5310.6  1624.4
#Mann= 7 ,-1 , 0
  4267.3    .063       0  4425.6    .035       0  4584.4    .063       0
  4748.6    .035       0  4987.9    .035       0  4991.9    .035       0
  5271.4    .094       0
Bank Sta=4987.9,4991.9
XS Rating Curve= 0 ,0
Exp/Cntr=0.3,0.1

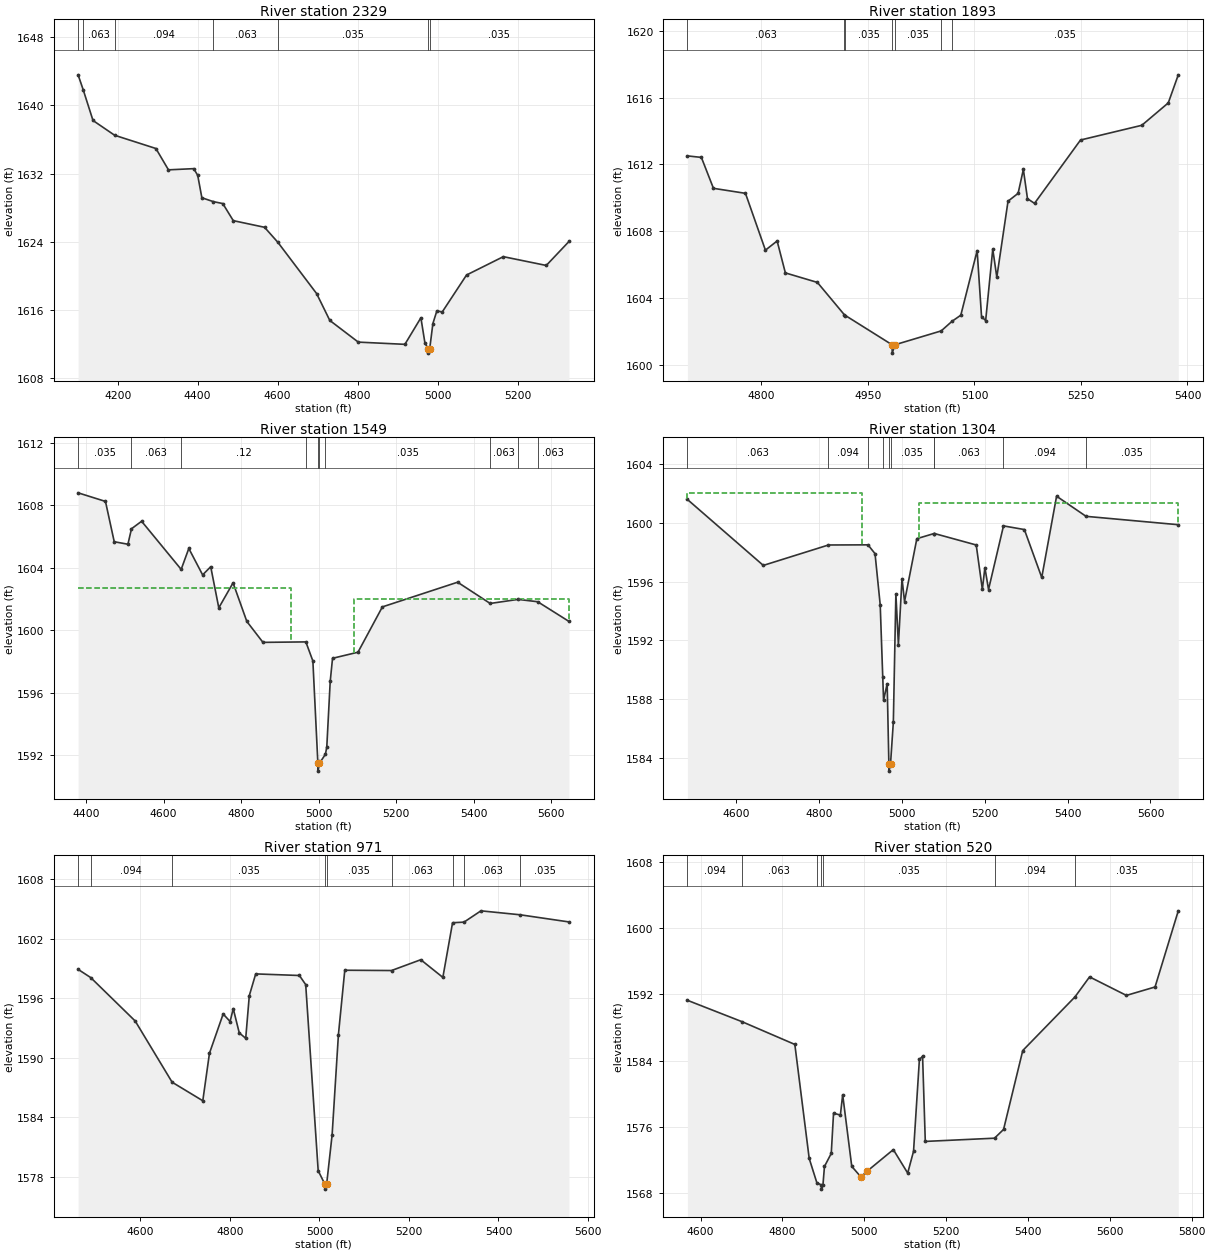
Type RM Length L Ch R = 1 ,2329    ,436,436,436
BEGIN DESCRIPTION:
Stream0545 5.0
END DESCRIPTION:
XS GIS Cut Line= 4
      1927798.77     13914967.87      1928487.82     13915175.83
        1928675.       13915175.      1928925.01     13914974.99
#Sta/Elev= 30
  4101.1 1643.57  4114.1 1641.79  4138.4 1638.22  4192.5 1636.49  4295.6 1634.94
    4327 1632.44  4390.1 1632.58  4400.1  1631.8  4410.5 1629.17  4438.9 1628.72
  4462.8 1628.49    4489 1626.49  4567.2 1625.71  4600.5 1623.95  4697.3 1617.95
  4730.3  1614.8  4801.5 1612.26    4918    1612    4958 1615.11    4968 1612.19
    4976 1611.47  4976.3 1610.97    4980 1611.47    4988 1614.44    4998 1615.93
  5011.2 1615.78  5072.1 1620.12  5164.1 1622.27  5271.4 1621.24  5328.2 1624.05
#Mann= 7 ,-1 , 0
  4101.1    .035       0  4114.1    .063       0  4192.5    .094       0
  4438.9    .063       0  4600.5    .035       0    4976    .035       0
    4980    .035       0
Bank Sta=4976,4980
XS Rating Curve= 0 ,0
Exp/Cntr=0.3,0.1

Type RM Length L Ch R = 1 ,1893    ,344,344,344
BEGIN DESCRIPTION:
Stream0545 4.0
END DESCRIPTION:
XS GIS Cut Line= 3
      1928551.35     13915658.14        1928825.       13915525.
      1929017.95     13915189.44
#Sta/Elev= 30
  4695.7 1612.51  4715.4 1612.42  4732.4 1610.57  4777.5 1610.27  4805.6 1606.87
  4822.1 1607.42  4833.7 1605.51  4878.8 1604.94  4916.5 1603.02  4918.3 1602.96
    4984 1601.21  4984.2 1600.71    4988 1601.21  5053.2 1602.04  5068.3 1602.61
  5080.8 1602.98  5103.8 1606.84    5110 1602.89  5115.8 1602.66  5125.8 1606.93
  5131.5 1605.25  5147.3  1609.8  5161.5 1610.27  5168.9  1611.7  5174.7 1609.95
  5184.6 1609.67  5249.4 1613.46  5335.7 1614.34    5373 1615.68  5387.1 1617.36
#Mann= 7 ,-1 , 0
  4695.7    .063       0  4916.5     .12       0  4918.3    .035       0
    4984    .035       0    4988    .035       0  5053.2    .063       0
  5068.3    .035       0
Bank Sta=4984,4988
XS Rating Curve= 0 ,0
Exp/Cntr=0.3,0.1

Type RM Length L Ch R = 1 ,1549    ,245,245,245
BEGIN DESCRIPTION:
Stream0545 3.1
END DESCRIPTION:
XS GIS Cut Line= 3
      1928589.89     13916059.94      1929049.37     13915701.55
      1929611.51      13915313.5
#Sta/Elev= 30
  4379.5 1608.79  4450.1 1608.24  4472.7 1605.66    4508  1605.5  4517.2 1606.49
  4543.3 1606.97  4645.3 1603.89    4665 1605.23  4700.6 1603.54  4721.5 1604.06
  4742.3 1601.43  4779.1 1603.03  4814.6 1600.56  4856.2 1599.22  4966.8 1599.25
  4984.9 1598.03  4997.8 1591.48  4998.1 1590.98  5001.8 1591.48  5017.3 1592.06
  5020.8 1592.53  5029.6 1596.72  5035.6  1598.2  5101.2 1598.59  5164.1 1601.49
  5358.1 1603.07  5442.1 1601.71  5513.9 1601.97  5564.6 1601.82  5645.3 1600.56
#Mann= 10 ,-1 , 0
  4379.5    .035       0  4517.2    .063       0  4645.3     .12       0
  4966.8    .035       0  4997.8    .035       0  5001.8    .035       0
  5017.3    .035       0  5442.1    .063       0  5513.9    .035       0
  5564.6    .063       0
#XS Ineff= 2 , 0
         4928.25  1602.7 5089.69         1602.02
Permanent Ineff=
       F       F
Bank Sta=4997.8,5001.8
XS Rating Curve= 0 ,0
Exp/Cntr=0.3,0.1

Type RM Length L Ch R = 1 ,1304    ,333,333,333
BEGIN DESCRIPTION:
Stream0545 3.0
END DESCRIPTION:
XS GIS Cut Line= 3
      1928870.34       13916148.      1929228.95     13915851.53
      1929820.24     13915441.91
#Sta/Elev= 30
  4482.5  1601.6  4665.7 1597.11    4823  1598.5  4918.3 1598.51  4935.3 1597.91
  4947.8 1594.43  4953.9 1589.53  4955.9 1587.93  4964.6 1589.06  4968.7 1583.61
    4969 1583.11  4972.7 1583.61  4979.5 1586.45  4985.6 1595.18  4991.7 1591.72
  5000.4 1596.21  5006.5 1594.65  5036.2 1598.93  5076.6 1599.27  5078.7 1599.28
  5179.5  1598.5  5194.3 1595.48  5200.4 1596.96  5209.2 1595.47  5245.3  1599.8
  5295.7 1599.55  5337.6 1596.29  5373.4 1601.82  5444.5 1600.45  5667.1 1599.88
#Mann= 10 ,-1 , 0
  4482.5    .063       0    4823    .094       0  4918.3     .12       0
  4953.9    .035       0  4968.7    .035       0  4972.7    .035       0
  5076.6    .035       0  5078.7    .063       0  5245.3    .094       0
  5444.5    .035       0
#XS Ineff= 2 , 0
         4903.81 1602.05 5041.93         1601.33
Permanent Ineff=
       F       F
Bank Sta=4968.7,4972.7
XS Rating Curve= 0 ,0
Exp/Cntr=0.3,0.1

Type RM Length L Ch R = 1 ,971     ,451,451,451
BEGIN DESCRIPTION:
Stream0545 2.0
END DESCRIPTION:
XS GIS Cut Line= 5
      1929039.67     13916259.81      1929343.21     13916116.27
        1929525.       13916025.        1929575.       13915975.
      1929903.97     13915616.17
#Sta/Elev= 30
  4460.8 1598.93    4489  1598.1  4588.4 1593.72  4670.9 1587.55  4739.4 1585.68
  4754.3 1590.47  4784.9 1594.43  4800.4 1593.67  4807.4 1594.97  4820.9 1592.52
  4835.3 1591.98  4843.3 1596.28  4857.6 1598.47  4955.2 1598.31  4969.3 1597.39
  4997.2 1578.63  5012.1 1577.27  5012.4 1576.77  5016.1 1577.27  5028.3 1582.23
  5042.4 1592.35  5056.6 1598.84    5161 1598.81  5226.4  1599.9  5275.7 1598.12
  5297.4 1603.63  5322.9 1603.69  5360.8 1604.83  5448.5 1604.43  5557.5 1603.71
#Mann= 9 ,-1 , 0
  4460.8    .063       0    4489    .094       0  4670.9    .035       0
  5012.1    .035       0  5016.1    .035       0    5161    .063       0
  5297.4    .094       0  5322.9    .063       0  5448.5    .035       0
#XS Ineff= 2 , 0
         4929.45 1596.97
Permanent Ineff=
       F       F
Bank Sta=5012.1,5016.1
XS Rating Curve= 0 ,0
Exp/Cntr=0.3,0.1

Type RM Length L Ch R = 1 ,520     ,0,0,0
BEGIN DESCRIPTION:
Stream0545 1.0
END DESCRIPTION:
XS GIS Cut Line= 4
      1929389.55     13916570.76        1929775.       13916375.
        1930025.       13916075.      1930035.28     13915698.26
#Sta/Elev= 30
  4567.7  1591.3  4701.3 1588.71  4830.3 1585.96  4865.4 1572.17    4884 1569.25
    4895 1568.96  4895.3 1568.46    4899 1568.96  4902.7  1571.2  4919.3 1572.78
  4924.9 1577.64  4941.6 1577.42  4947.2 1579.88  4969.4 1571.21  4991.7 1569.94
  5007.2 1570.64    5071 1573.24  5106.1  1570.4  5120.4 1573.04  5134.7 1584.14
  5142.5 1584.53  5149.1 1574.23  5318.3 1574.62  5340.4 1575.68  5387.3 1585.22
  5514.9 1591.71  5550.6 1594.13  5640.6 1591.89  5710.6 1592.91  5767.4 1602.12
#Mann= 7 ,-1 , 0
  4567.7    .094       0  4701.3    .063       0    4884    .035       0
    4895    .035       0    4899    .035       0  5318.3    .094       0
  5514.9    .035       0
#XS Ineff= 2 , 0
          4925.2  1577.6 5139.98         1583.06
Permanent Ineff=
       F       F
Bank Sta=4991.7,5007.2
XS Rating Curve= 0 ,0
Exp/Cntr=0.3,0.1

Chan Stop Cuts=-1
Use User Specified Reach Order=0
Composite Channel Slope=5