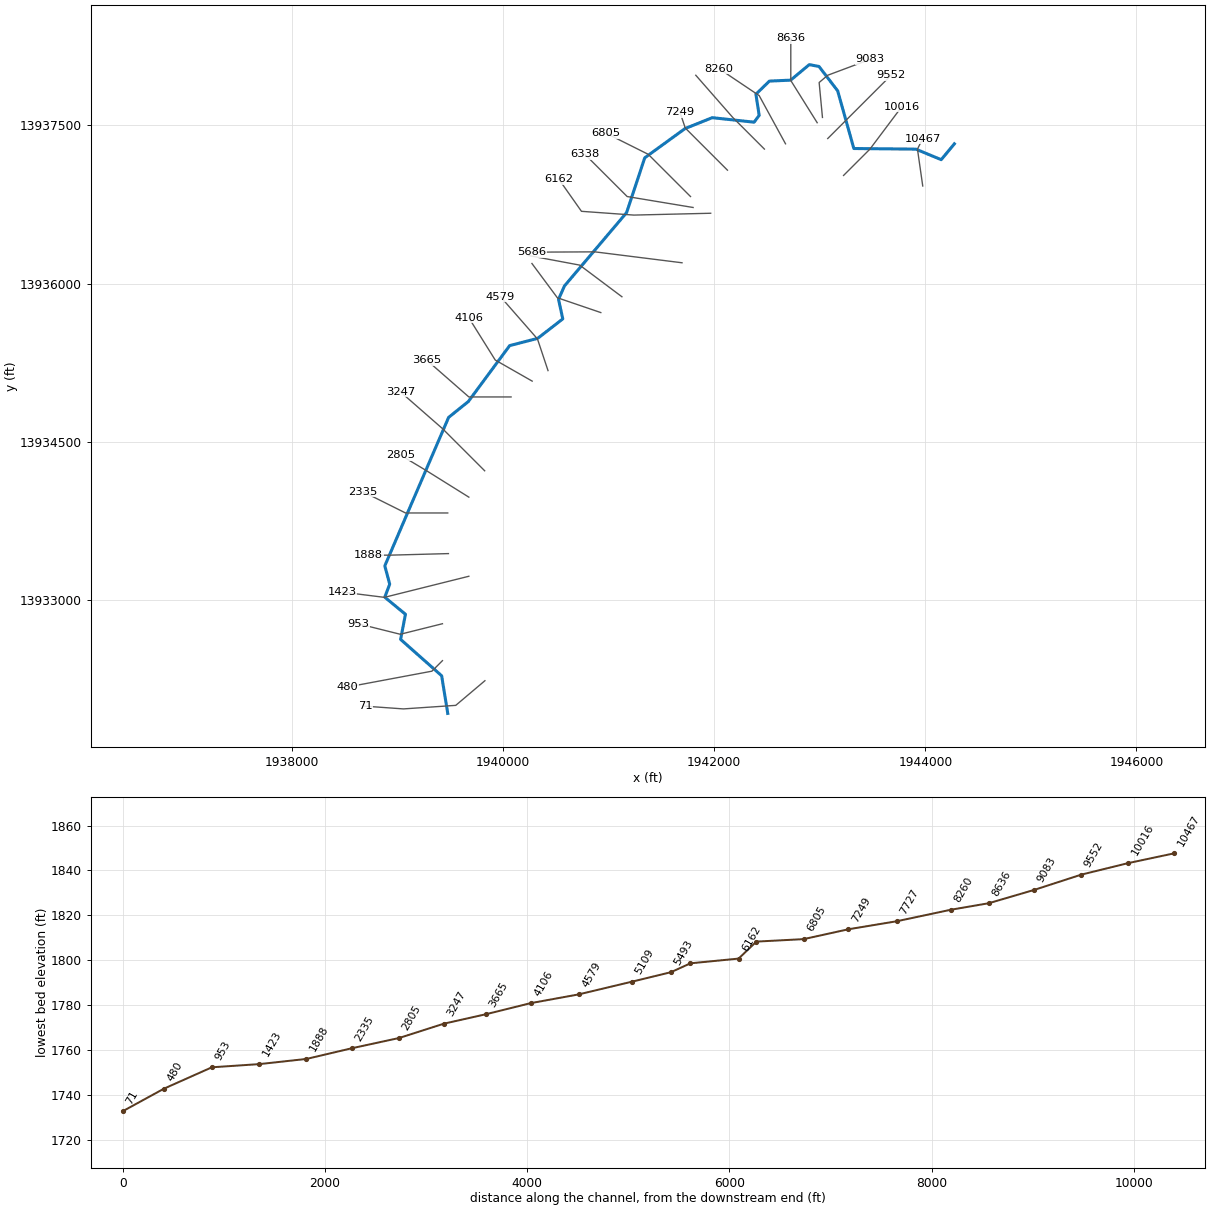
--- Stream0546.prj (project) ---

Proj Title=Stream0546 Base Level Engineering
Current Plan=p01
Default Exp/Contr=0.3,0.1
English Units
Geom File=g01
Flow File=f01
Plan File=p01
BEGIN DESCRIPTION:
Stream0546
END DESCRIPTION:

--- Stream0546.p01 (plan) ---

Plan Title=Multiple Run
Short Identifier=Multiple
Geom File=g01
Flow File=f01
Subcritical Flow
K Sum by GR= 0
Std Step Tol= 0.01
Critical Tol= 0.01
Num of Std Step Trials= 20
Max Error Tol= 0.3
Flow Tol Ratio= 0.001
Split Flow NTrial= 30
Split Flow Tol= 0.02
Split Flow Ratio= 0.02
Log Output Level= 0
Friction Slope Method= 1
Unsteady Friction Slope Method= 2
Unsteady Bridges Friction Slope Method= 1
Parabolic Critical Depth
Global Vel Dist=  1 , 1 , 1
Global Log Level= 0
CheckData=True
Encroach Param= -1, 0, 0, 0
BEGIN DESCRIPTION:
Multiple Run
END DESCRIPTION:

--- Stream0546.f01 (steady flow) ---

Flow Title=Multiple
Number of Profiles=7
Profile Names=10-year,25-year,50-year,1pct_min,100-year,1pct_plu,500-year
River Rch & RM= Stream0546,Reach-1,10467
    2200    3879    5526    3796    7575   15113   14067
River Rch & RM= Stream0546,Reach-1,3247
    2461    4360    6233    4294    8567   17094   16003
Boundary for River Rch & Prof#=Stream0546,Reach-1,1
Up Type=0
Dn Type=3
Dn Slope=0.005
Boundary for River Rch & Prof#=Stream0546,Reach-1,2
Up Type=0
Dn Type=3
Dn Slope=0.005
Boundary for River Rch & Prof#=Stream0546,Reach-1,3
Up Type=0
Dn Type=3
Dn Slope=0.005
Boundary for River Rch & Prof#=Stream0546,Reach-1,4
Up Type=0
Dn Type=3
Dn Slope=0.005
Boundary for River Rch & Prof#=Stream0546,Reach-1,5
Up Type=0
Dn Type=3
Dn Slope=0.005
Boundary for River Rch & Prof#=Stream0546,Reach-1,6
Up Type=0
Dn Type=3
Dn Slope=0.005
Boundary for River Rch & Prof#=Stream0546,Reach-1,7
Up Type=0
Dn Type=3
Dn Slope=0.005

--- Stream0546.g01 (geometry) ---

Geom Title=Existing Conditions

River Reach=Stream0546,Reach-1
Reach XY= 30
      1944275.00     13937325.00      1944150.04     13937174.50
      1943909.79     13937274.49      1943322.26     13937280.34
      1943169.16     13937827.29      1942991.79     13938058.61
      1942899.97     13938075.51      1942723.54     13937928.54
      1942522.55     13937919.54      1942394.58     13937795.16
      1942425.44     13937595.00      1942377.62     13937529.99
      1941980.94     13937572.74      1941722.71     13937469.16
      1941341.30     13937192.13      1941169.53     13936672.55
      1940580.84     13935977.29      1940524.59     13935850.00
      1940564.94     13935665.00      1940327.43     13935480.52
      1940061.69     13935411.60      1939669.41     13934880.61
      1939483.14     13934731.06      1938878.67     13933323.41
      1938925.32     13933149.96      1938878.43     13933026.55
      1939074.47     13932864.53      1939028.53     13932626.47
      1939417.31     13932281.48      1939475.00     13931925.00

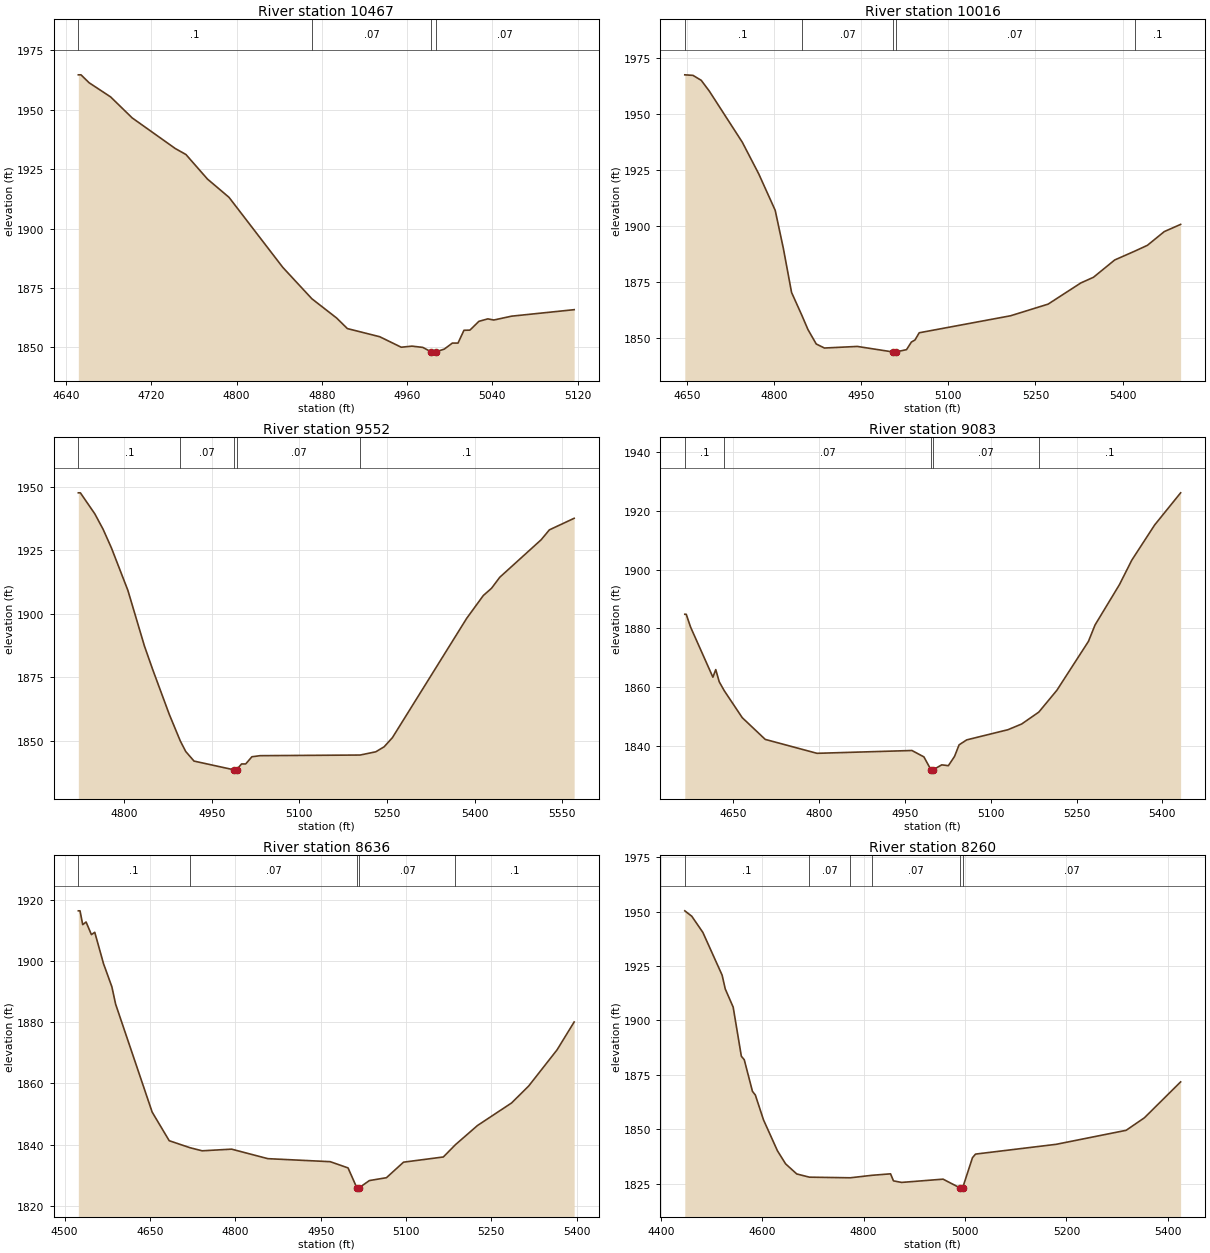
Type RM Length L Ch R = 1,10467,451,451,451
BEGIN DESCRIPTION:
Stream0546 23.0
END DESCRIPTION:
XS GIS Cut Line= 3
      1943975.00     13936925.02      1943925.00     13937275.00
      1943974.99     13937374.97
#Sta/Elev= 30
  4651.4 1964.75  4653.9 1964.75  4661.5 1961.42  4681.7 1955.45  4701.9 1946.63
  4742.3 1933.75  4752.4 1931.20  4772.6 1920.86  4792.8 1913.18  4843.3 1883.68
  4870.6 1870.46  4893.8 1862.37  4903.9 1857.92  4934.2 1854.50  4954.4 1850.08
  4964.5 1850.53  4974.6 1850.01  4982.7 1848.09  4983.0 1847.59  4986.7 1848.09
  4994.8 1849.28  5002.4 1851.82  5007.7 1851.82  5013.3 1857.21  5018.9 1857.27
  5027.3 1860.97  5035.7 1862.01  5041.3 1861.53  5058.0 1863.15  5116.7 1865.88
#Mann=4,-1,0
  4651.4     0.1       0  4870.6    0.07       0  4982.7    0.05       0
  4986.7    0.07       0
Bank Sta=4982.7,4986.7
Exp/Cntr=0.3,0.1

Type RM Length L Ch R = 1,10016,464,464,464
BEGIN DESCRIPTION:
Stream0546 22.0
END DESCRIPTION:
XS GIS Cut Line= 3
      1943225.00     13937025.00      1943475.00     13937275.00
      1943774.97     13937674.96
#Sta/Elev= 30
  4646.5 1967.61  4660.6 1967.37  4674.8 1965.15  4688.9 1960.26  4745.5 1937.50
  4773.8 1923.35  4802.1 1907.09  4816.2 1890.02  4830.3 1870.37  4847.5 1860.47
  4858.6 1853.77  4872.8 1847.35  4886.9 1845.56  4943.5 1846.27  5005.3 1843.78
  5005.5 1843.28  5009.4 1843.78  5028.2 1844.84  5036.5 1848.22  5042.8 1849.17
  5050.0 1852.37  5207.3 1859.97  5271.9 1865.17  5328.2 1874.63  5350.0 1877.17
  5386.5 1884.89  5421.2 1888.86  5442.8 1891.44  5471.9 1897.58  5500.0 1900.79
#Mann=5,-1,0
  4646.5     0.1       0  4847.5    0.07       0  5005.3    0.05       0
  5009.4    0.07       0  5421.2     0.1       0
Bank Sta=5005.3,5009.4
Exp/Cntr=0.3,0.1

Type RM Length L Ch R = 1,9552,469,469,469
BEGIN DESCRIPTION:
Stream0546 21.0
END DESCRIPTION:
XS GIS Cut Line= 3
      1943075.00     13937375.00      1943275.00     13937575.00
      1943674.98     13937974.98
#Sta/Elev= 30
  4721.7 1947.63  4725.2 1947.63  4750.0 1939.33  4764.1 1933.29  4778.3 1925.98
  4806.5 1909.26  4834.8 1887.38  4849.0 1878.09  4877.3 1860.49  4896.2 1850.01
  4905.5 1845.86  4919.7 1842.09  4988.3 1838.64  4988.6 1838.14  4992.4 1838.64
  5001.0 1840.96  5008.1 1840.96  5018.7 1843.79  5032.8 1844.22  5204.0 1844.47
  5230.8 1845.75  5245.0 1847.71  5259.1 1851.28  5386.4 1898.29  5414.7 1907.22
  5428.8 1910.08  5442.9 1914.41  5513.7 1929.16  5527.8 1933.06  5570.2 1937.61
#Mann=5,-1,0
  4721.7     0.1       0  4896.2    0.07       0  4988.3    0.05       0
  4992.4    0.07       0  5204.0     0.1       0
Bank Sta=4988.3,4992.4
Exp/Cntr=0.3,0.1

Type RM Length L Ch R = 1,9083,447,447,447
BEGIN DESCRIPTION:
Stream0546 20.0
END DESCRIPTION:
XS GIS Cut Line= 4
      1943025.00     13937575.02      1942993.61     13937906.15
      1943075.00     13937975.00      1943474.98     13938124.99
#Sta/Elev= 30
  4565.4 1884.77  4567.9 1884.77  4575.4 1880.45  4614.5 1863.32  4619.5 1865.91
  4625.6 1861.74  4634.5 1858.67  4665.8 1849.52  4706.0 1842.11  4796.4 1837.37
  4962.3 1838.33  4983.2 1836.16  4995.4 1831.80  4995.7 1831.30  4999.6 1831.80
  5014.4 1833.44  5026.0 1833.16  5036.7 1836.30  5044.7 1840.26  5058.0 1841.95
  5130.1 1845.42  5154.1 1847.37  5184.0 1851.42  5215.6 1858.87  5270.7 1875.52
  5282.3 1881.14  5325.0 1894.91  5346.4 1903.19  5386.4 1915.21  5431.8 1926.17
#Mann=5,-1,0
  4565.4     0.1       0  4634.5    0.07       0  4995.4    0.05       0
  4999.6    0.07       0  5184.0     0.1       0
Bank Sta=4995.4,4999.6
Exp/Cntr=0.3,0.1

Type RM Length L Ch R = 1,8636,376,376,376
BEGIN DESCRIPTION:
Stream0546 19.0
END DESCRIPTION:
XS GIS Cut Line= 3
      1942975.02     13937524.96      1942725.00     13937925.00
      1942725.00     13938324.96
#Sta/Elev= 30
  4524.0 1916.47  4527.0 1916.47  4531.7 1911.94  4537.6 1912.82  4547.0 1908.69
  4552.9 1909.44  4568.3 1899.17  4583.0 1891.60  4589.5 1885.97  4653.8 1850.61
  4683.8 1841.24  4720.4 1838.95  4741.6 1837.94  4793.5 1838.48  4857.2 1835.37
  4966.9 1834.38  4998.2 1832.34  5013.5 1825.90  5013.8 1825.40  5018.0 1825.90
  5035.7 1828.20  5065.7 1829.14  5095.7 1834.22  5165.7 1835.92  5186.8 1839.91
  5225.7 1846.21  5285.7 1853.60  5315.7 1859.13  5365.7 1870.99  5395.7 1880.10
#Mann=5,-1,0
  4524.0     0.1       0  4720.4    0.07       0  5013.5    0.05       0
  5018.0    0.07       0  5186.8     0.1       0
Bank Sta=5013.5,5018
Exp/Cntr=0.3,0.1

Type RM Length L Ch R = 1,8260,533,533,533
BEGIN DESCRIPTION:
Stream0546 18.0
END DESCRIPTION:
XS GIS Cut Line= 3
      1942675.01     13937324.98      1942425.47     13937782.02
      1942046.25     13938036.81
#Sta/Elev= 30
  4447.5 1950.33  4461.3 1947.83  4483.1 1940.43  4521.1 1920.78  4527.3 1914.42
  4542.9 1906.07  4559.0 1883.54  4564.7 1881.96  4580.9 1867.41  4586.6 1865.72
  4602.7 1854.30  4630.2 1840.09  4646.3 1834.09  4668.2 1829.46  4693.2 1827.98
  4773.9 1827.70  4817.0 1828.85  4853.2 1829.52  4858.9 1826.29  4875.0 1825.57
  4956.7 1827.07  4990.6 1822.99  4990.9 1822.49  4995.2 1822.99  5014.7 1836.92
  5020.7 1838.58  5179.7 1843.07  5317.7 1849.51  5353.7 1855.26  5425.1 1871.75
#Mann=6,-1,0
  4447.5     0.1       0  4693.2    0.07       0  4773.9     0.1       0
  4817.0    0.07       0  4990.6    0.05       0  4995.2    0.07       0
Bank Sta=4990.6,4995.2
Exp/Cntr=0.3,0.1

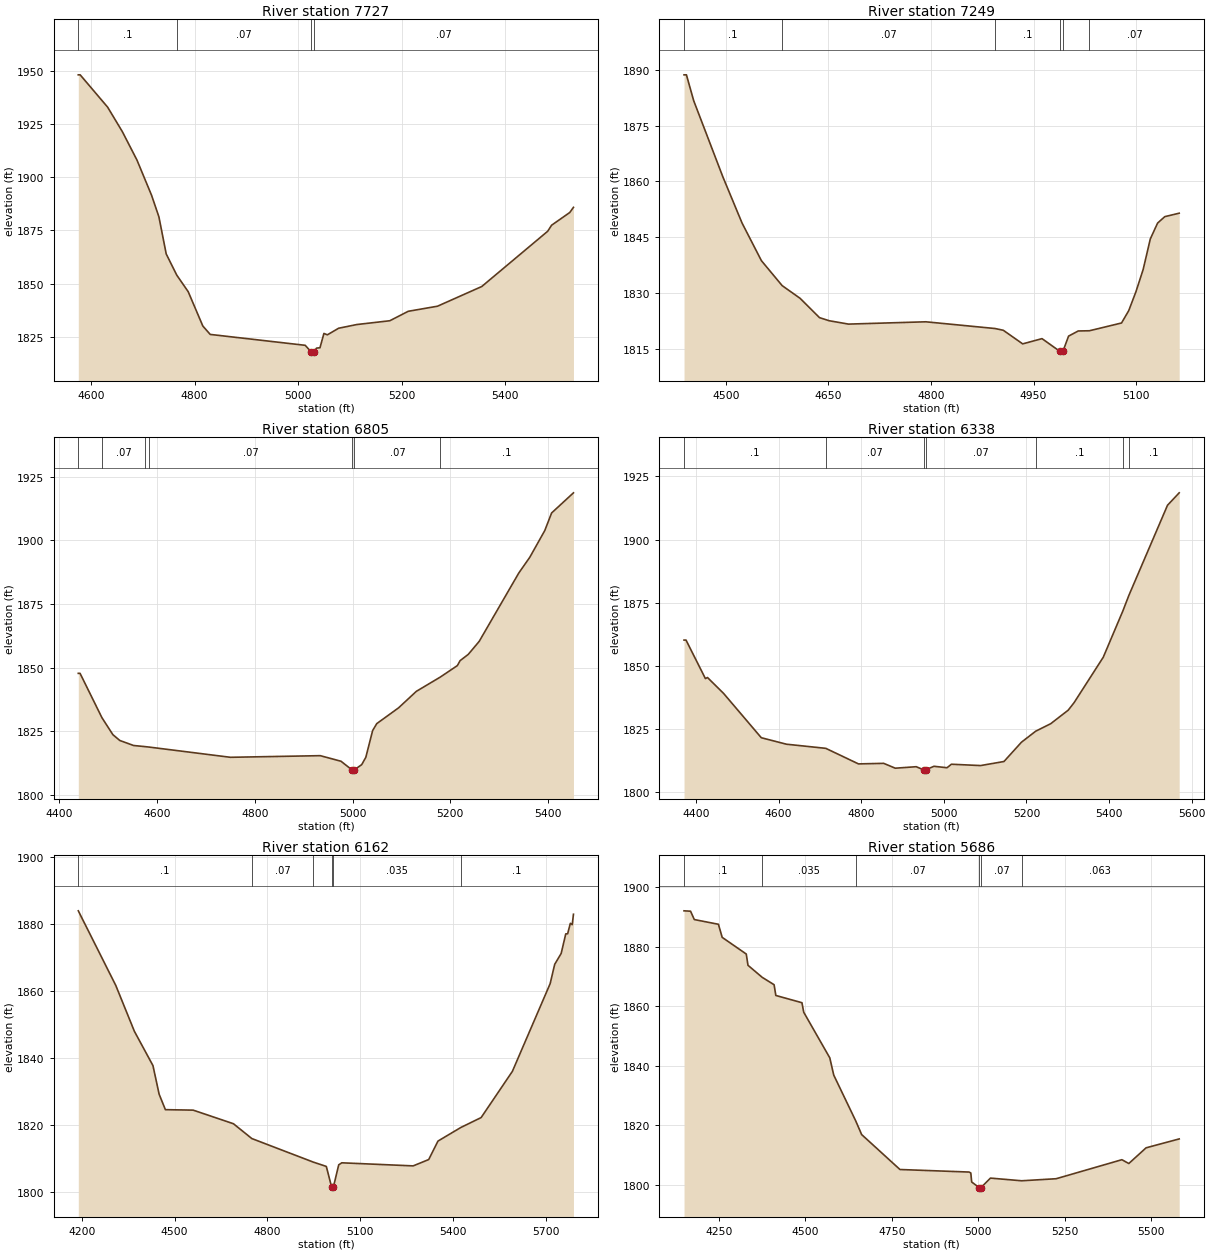
Type RM Length L Ch R = 1,7727,478,478,478
BEGIN DESCRIPTION:
Stream0546 17.0
END DESCRIPTION:
XS GIS Cut Line= 3
      1942475.01     13937274.99      1942175.00     13937575.00
      1941825.00     13937975.01
#Sta/Elev= 30
  4575.6 1948.10  4579.2 1948.10  4632.2 1932.92  4660.5 1921.47  4688.8 1908.09
  4717.0 1891.55  4731.2 1881.41  4745.3 1863.97  4765.6 1854.05  4787.8 1846.22
  4816.0 1830.11  4830.2 1826.17  5013.6 1821.05  5025.5 1817.88  5025.9 1817.38
  5030.2 1817.88  5035.5 1819.74  5042.1 1819.90  5049.7 1826.62  5056.4 1825.98
  5078.2 1829.08  5113.3 1830.81  5176.9 1832.59  5212.5 1837.03  5269.0 1839.42
  5354.4 1848.67  5481.6 1874.61  5489.2 1877.46  5524.3 1883.44  5531.4 1885.86
#Mann=4,-1,0
  4575.6     0.1       0  4765.6    0.07       0  5025.5    0.05       0
  5030.2    0.07       0
Bank Sta=5025.5,5030.2
Exp/Cntr=0.3,0.1

Type RM Length L Ch R = 1,7249,444,444,444
BEGIN DESCRIPTION:
Stream0546 16.0
END DESCRIPTION:
XS GIS Cut Line= 3
      1942125.00     13937075.00      1941725.00     13937475.00
      1941675.00     13937625.01
#Sta/Elev= 30
  4439.1 1888.70  4442.6 1888.70  4453.2 1881.75  4495.7 1861.32  4523.9 1848.82
  4552.2 1838.69  4582.5 1831.98  4608.8 1828.55  4637.1 1823.36  4651.2 1822.53
  4679.5 1821.62  4792.6 1822.24  4893.7 1820.43  4905.8 1819.96  4934.1 1816.30
  4962.4 1817.71  4988.3 1814.31  4988.6 1813.81  4993.0 1814.31  5001.2 1818.39
  5015.3 1819.77  5031.7 1819.83  5078.6 1821.92  5089.1 1825.23  5099.6 1830.30
  5110.2 1836.31  5120.7 1844.55  5131.3 1848.80  5141.8 1850.53  5162.9 1851.47
#Mann=6,-1,0
  4439.1     0.1       0  4582.5    0.07       0  4893.7     0.1       0
  4988.3    0.05       0  4993.0     0.1       0  5031.7    0.07       0
Bank Sta=4988.3,4993
Exp/Cntr=0.3,0.1

Type RM Length L Ch R = 1,6805,467,467,467
BEGIN DESCRIPTION:
Stream0546 15.0
END DESCRIPTION:
XS GIS Cut Line= 3
      1941775.03     13936824.97      1941375.00     13937225.00
      1940975.04     13937424.98
#Sta/Elev= 30
  4438.9 1847.81  4442.5 1847.81  4487.3 1830.38  4509.7 1823.72  4523.8 1821.45
  4552.1 1819.47  4575.5 1819.03  4583.6 1818.86  4750.1 1814.84  4933.9 1815.48
  4976.3 1813.29  4998.7 1809.91  4999.0 1809.41  5003.5 1809.91  5018.6 1811.95
  5027.0 1814.81  5041.0 1825.34  5049.4 1828.06  5094.1 1834.27  5130.4 1840.74
  5179.6 1846.37  5214.3 1850.85  5219.9 1852.79  5236.6 1855.25  5259.0 1860.37
  5340.0 1887.22  5362.4 1893.37  5393.1 1903.87  5407.1 1910.79  5451.8 1918.70
#Mann=7,-1,0
  4438.9     0.1       0  4487.3    0.07       0  4575.5   0.035       0
  4583.6    0.07       0  4998.7    0.05       0  5003.5    0.07       0
  5179.6     0.1       0
Bank Sta=4998.7,5003.5
Exp/Cntr=0.3,0.1

Type RM Length L Ch R = 1,6338,176,176,176
BEGIN DESCRIPTION:
Stream0546 14.0
END DESCRIPTION:
XS GIS Cut Line= 3
      1941799.49     13936721.28      1941175.00     13936825.00
      1940775.02     13937224.98
#Sta/Elev= 30
  4371.2 1860.20  4376.0 1860.20  4422.9 1844.96  4428.0 1845.37  4467.0 1839.07
  4558.2 1821.54  4619.0 1818.97  4714.4 1817.33  4793.5 1811.17  4854.5 1811.39
  4882.6 1809.47  4933.3 1810.06  4951.2 1808.81  4951.5 1808.31  4956.0 1808.81
  4976.3 1810.23  5007.8 1809.65  5018.4 1811.04  5089.1 1810.51  5145.7 1812.12
  5188.1 1819.77  5222.5 1824.12  5258.8 1827.08  5301.2 1832.44  5315.4 1835.41
  5386.1 1853.42  5433.5 1871.72  5448.1 1877.90  5541.6 1913.58  5569.9 1918.50
#Mann=7,-1,0
  4371.2     0.1       0  4714.4    0.07       0  4951.2    0.05       0
  4956.0    0.07       0  5222.5     0.1       0  5433.5    0.07       0
  5448.1     0.1       0
Bank Sta=4951.2,4956
Exp/Cntr=0.3,0.1

Type RM Length L Ch R = 1,6162,476,476,476
BEGIN DESCRIPTION:
Stream0546 13.1
END DESCRIPTION:
XS GIS Cut Line= 4
      1941966.21     13936666.61      1941238.00     13936649.21
      1940741.92     13936684.95      1940526.30     13936991.29
#Sta/Elev= 30
  4189.0 1883.85  4310.2 1861.56  4370.3 1847.87  4430.3 1837.63  4450.3 1829.07
  4470.5 1824.47  4560.3 1824.33  4690.4 1820.27  4749.9 1815.84  4949.1 1808.79
  4990.6 1807.52  5008.1 1801.24  5008.5 1800.74  5013.2 1801.24  5030.7 1808.00
  5040.7 1808.60  5271.3 1807.68  5321.5 1809.57  5351.5 1815.09  5425.4 1819.15
  5491.0 1822.11  5592.0 1835.91  5714.0 1862.09  5728.8 1867.88  5749.7 1871.13
  5764.5 1876.97  5770.6 1876.99  5779.3 1880.12  5785.4 1879.72  5789.4 1882.83
#Mann=6,-1,0
  4189.0     0.1       0  4749.9    0.07       0  4949.1   0.035       0
  5008.1   0.035       0  5013.2   0.035       0  5425.4     0.1       0
Bank Sta=5008.1,5013.2
Exp/Cntr=0.3,0.1

Type RM Length L Ch R = 1,5686,193,193,193
BEGIN DESCRIPTION:
Stream0546 13.0
END DESCRIPTION:
XS GIS Cut Line= 3
      1941694.48     13936197.13      1940868.62     13936300.63
      1940269.35     13936297.73
#Sta/Elev= 30
  4149.3 1891.99  4168.2 1891.86  4179.0 1889.06  4248.7 1887.48  4259.6 1883.09
  4329.2 1877.50  4334.2 1873.72  4375.3 1869.68  4409.7 1867.20  4414.7 1863.60
  4490.2 1861.17  4495.3 1857.99  4570.7 1842.68  4582.1 1836.90  4645.6 1821.55
  4662.8 1816.94  4773.6 1805.22  4973.3 1804.37  4978.4 1804.06  4980.9 1801.04
  5002.7 1799.14  5003.1 1798.64  5007.8 1799.14  5035.2 1802.34  5125.4 1801.44
  5225.2 1802.13  5415.2 1808.51  5435.2 1807.23  5485.2 1812.50  5580.9 1815.48
#Mann=6,-1,0
  4149.3     0.1       0  4375.3   0.035       0  4645.6    0.07       0
  5002.7    0.05       0  5007.8    0.07       0  5125.4   0.063       0
Bank Sta=5002.7,5007.8
Exp/Cntr=0.3,0.1

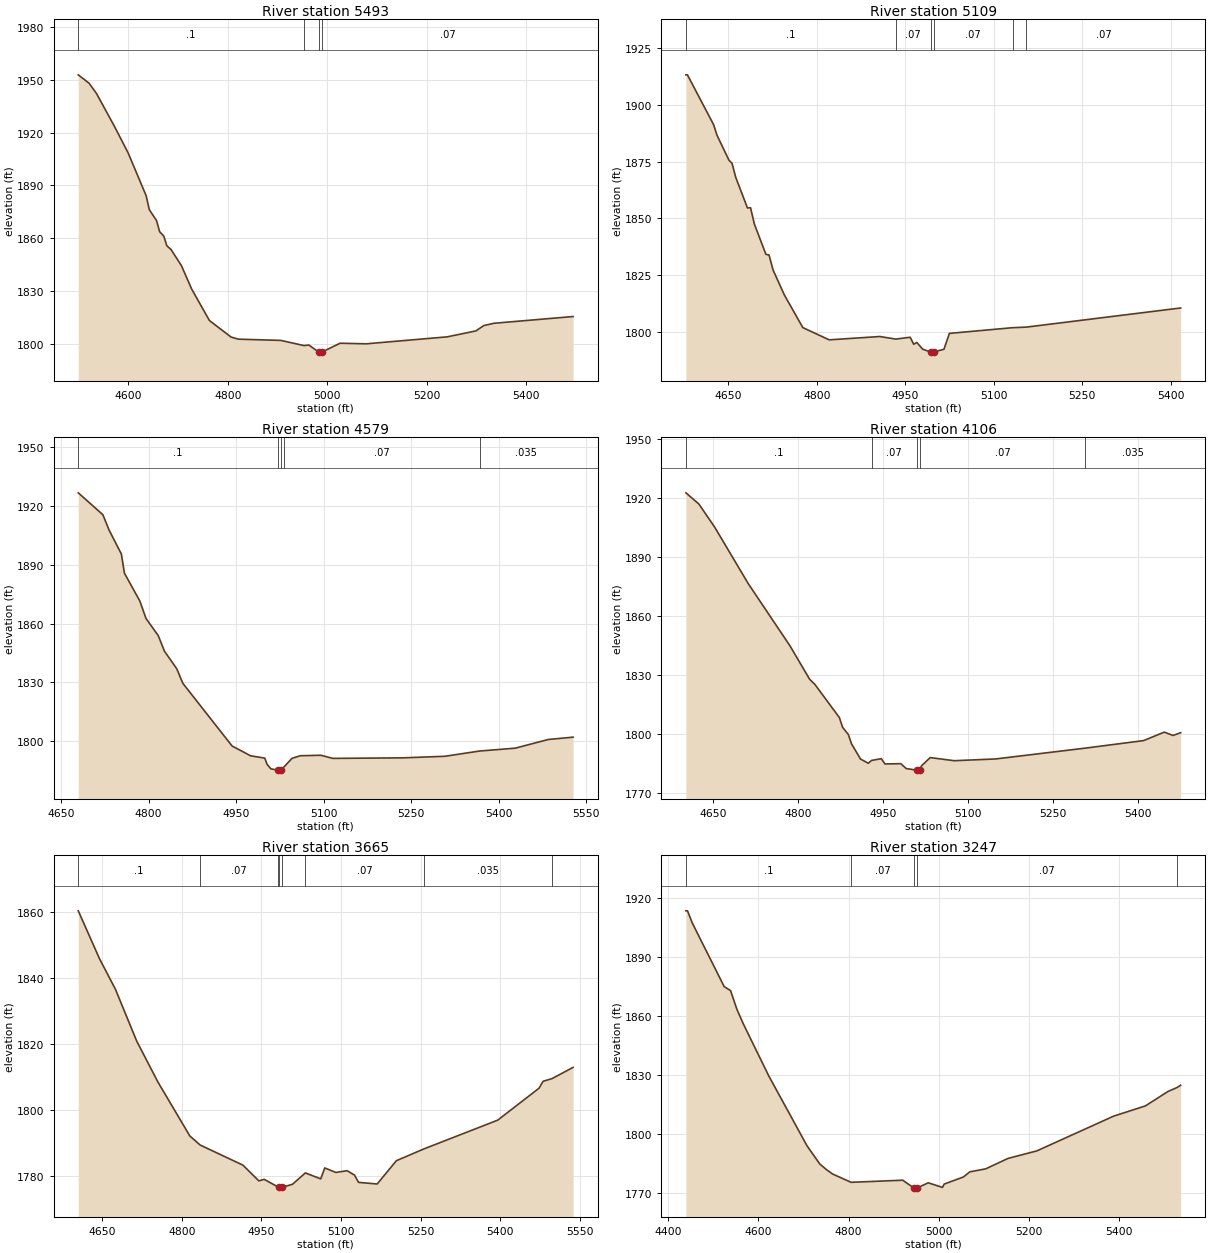
Type RM Length L Ch R = 1,5493,384,384,384
BEGIN DESCRIPTION:
Stream0546 12.0
END DESCRIPTION:
XS GIS Cut Line= 3
      1941125.01     13935874.99      1940725.00     13936175.00
      1940238.78     13936266.15
#Sta/Elev= 30
  4499.5 1952.76  4521.4 1947.94  4536.0 1942.20  4571.4 1923.92  4599.5 1908.54
  4636.0 1884.07  4642.2 1876.23  4656.8 1869.99  4663.1 1863.63  4671.4 1861.17
  4677.6 1855.63  4686.0 1853.54  4706.8 1844.40  4727.6 1831.00  4763.1 1813.21
  4806.8 1803.79  4821.4 1802.61  4906.8 1801.90  4953.2 1798.97  4963.1 1799.28
  4983.4 1795.18  4983.8 1794.68  4988.6 1795.18  5025.8 1800.30  5078.4 1799.97
  5241.2 1803.93  5298.8 1807.29  5314.9 1810.35  5335.3 1811.64  5494.2 1815.47
#Mann=4,-1,0
  4499.5     0.1       0  4953.2    0.07       0  4983.4    0.05       0
  4988.6    0.07       0
Bank Sta=4983.4,4988.6
Exp/Cntr=0.3,0.1

Type RM Length L Ch R = 1,5109,530,530,530
BEGIN DESCRIPTION:
Stream0546 11.0
END DESCRIPTION:
XS GIS Cut Line= 3
      1940924.99     13935725.00      1940513.54     13935865.43
      1940272.76     13936190.14
#Sta/Elev= 30
  4578.0 1913.27  4580.6 1913.27  4625.0 1891.29  4630.8 1886.59  4651.0 1875.63
  4656.3 1874.20  4662.5 1868.07  4682.4 1854.52  4687.6 1854.65  4694.2 1847.37
  4713.7 1834.06  4719.0 1833.77  4725.9 1827.12  4745.0 1816.14  4776.3 1801.74
  4821.0 1796.34  4906.9 1797.81  4933.8 1796.68  4958.4 1797.48  4964.3 1794.39
  4969.6 1795.20  4979.5 1792.23  4992.9 1790.98  4993.4 1790.48  4998.4 1790.98
  5015.6 1792.18  5024.8 1799.19  5131.9 1801.70  5155.4 1801.96  5417.0 1810.40
#Mann=6,-1,0
  4578.0     0.1       0  4933.8    0.07       0  4992.9    0.05       0
  4998.4    0.07       0  5131.9     0.1       0  5155.4    0.07       0
Bank Sta=4992.9,4998.4
Exp/Cntr=0.3,0.1

Type RM Length L Ch R = 1,4579,473,473,473
BEGIN DESCRIPTION:
Stream0546 10.0
END DESCRIPTION:
XS GIS Cut Line= 3
      1940425.01     13935174.96      1940325.00     13935475.00
      1939974.99     13935875.02
#Sta/Elev= 30
  4679.5 1926.61  4721.7 1915.44  4732.2 1907.69  4753.3 1895.43  4758.6 1885.65
  4785.0 1871.47  4795.5 1862.61  4816.6 1853.81  4827.1 1845.94  4848.2 1836.98
  4858.7 1829.52  4943.1 1797.58  4974.7 1792.60  4999.1 1791.41  5002.9 1788.31
  5009.5 1785.96  5021.0 1785.28  5021.4 1784.78  5026.6 1785.28  5032.3 1787.00
  5045.6 1791.27  5059.8 1792.62  5095.0 1792.87  5115.8 1791.27  5236.4 1791.55
  5307.6 1792.34  5367.2 1795.02  5428.1 1796.48  5485.0 1800.91  5527.3 1802.09
#Mann=5,-1,0
  4679.5     0.1       0  5021.0    0.05       0  5026.6     0.1       0
  5032.3    0.07       0  5367.2   0.035       0
Bank Sta=5021,5026.6
Exp/Cntr=0.3,0.1

Type RM Length L Ch R = 1,4106,441,441,441
BEGIN DESCRIPTION:
Stream0546 9.0
END DESCRIPTION:
XS GIS Cut Line= 3
      1940274.97     13935075.02      1939925.00     13935275.00
      1939674.99     13935675.02
#Sta/Elev= 30
  4601.3 1922.45  4624.3 1916.76  4652.4 1904.92  4711.4 1876.34  4785.5 1844.56
  4820.1 1827.62  4829.5 1824.97  4872.6 1808.18  4878.4 1803.17  4888.5 1799.53
  4894.2 1794.77  4910.1 1787.03  4923.8 1784.92  4929.5 1786.33  4946.8 1787.23
  4953.3 1784.55  4981.3 1784.69  4990.7 1782.23  5009.2 1781.40  5009.7 1780.90
  5014.8 1781.40  5017.9 1783.60  5033.3 1787.79  5075.7 1786.20  5148.8 1787.09
  5307.6 1792.60  5410.6 1796.43  5447.2 1800.74  5462.5 1799.04  5476.1 1800.46
#Mann=5,-1,0
  4601.3     0.1       0  4929.5    0.07       0  5009.2    0.05       0
  5014.8    0.07       0  5307.6   0.035       0
Bank Sta=5009.2,5014.8
Exp/Cntr=0.3,0.1

Type RM Length L Ch R = 1,3665,418,418,418
BEGIN DESCRIPTION:
Stream0546 8.0
END DESCRIPTION:
XS GIS Cut Line= 3
      1940075.05     13934925.00      1939675.00     13934925.00
      1939274.97     13935275.03
#Sta/Elev= 30
  4605.3 1860.31  4645.3 1845.79  4675.3 1836.53  4715.3 1820.84  4755.3 1808.42
  4815.3 1792.10  4834.7 1789.35  4915.3 1783.25  4945.3 1778.48  4955.3 1778.95
  4981.6 1776.62  4982.5 1776.48  4983.0 1775.98  4988.1 1776.48  5008.7 1777.46
  5032.8 1780.89  5061.8 1779.09  5069.4 1782.40  5090.3 1781.04  5111.6 1781.56
  5125.4 1780.23  5133.0 1778.03  5168.1 1777.54  5204.2 1784.59  5256.6 1788.20
  5395.0 1796.88  5472.8 1806.56  5480.4 1808.65  5497.6 1809.49  5536.9 1812.87
#Mann=8,-1,0
  4605.3     0.1       0  4834.7    0.07       0  4981.6     0.1       0
  4982.5    0.05       0  4988.1     0.1       0  5032.8    0.07       0
  5256.6   0.035       0  5497.6    0.07       0
Bank Sta=4982.5,4988.1
Exp/Cntr=0.3,0.1

Type RM Length L Ch R = 1,3247,442,442,442
BEGIN DESCRIPTION:
Stream0546 7.0
END DESCRIPTION:
XS GIS Cut Line= 3
      1939825.02     13934224.98      1939425.00     13934625.00
      1939025.01     13934974.99
#Sta/Elev= 30
  4439.3 1913.38  4442.9 1913.38  4453.5 1907.20  4524.2 1874.82  4538.3 1872.80
  4552.5 1863.23  4566.6 1855.88  4623.2 1829.31  4708.0 1793.77  4736.3 1784.53
  4750.5 1781.78  4764.6 1779.45  4805.7 1775.22  4920.2 1776.29  4945.4 1772.25
  4945.9 1771.75  4951.4 1772.25  4976.7 1774.97  5008.3 1772.63  5012.1 1774.31
  5054.8 1777.95  5069.1 1780.56  5104.2 1782.07  5153.5 1787.37  5217.6 1791.21
  5388.0 1808.91  5458.2 1814.09  5508.5 1821.46  5527.9 1823.40  5536.5 1824.62
#Mann=5,-1,0
  4439.3     0.1       0  4805.7    0.07       0  4945.4    0.05       0
  4951.4    0.07       0  5527.9     0.1       0
Bank Sta=4945.4,4951.4
Exp/Cntr=0.3,0.1

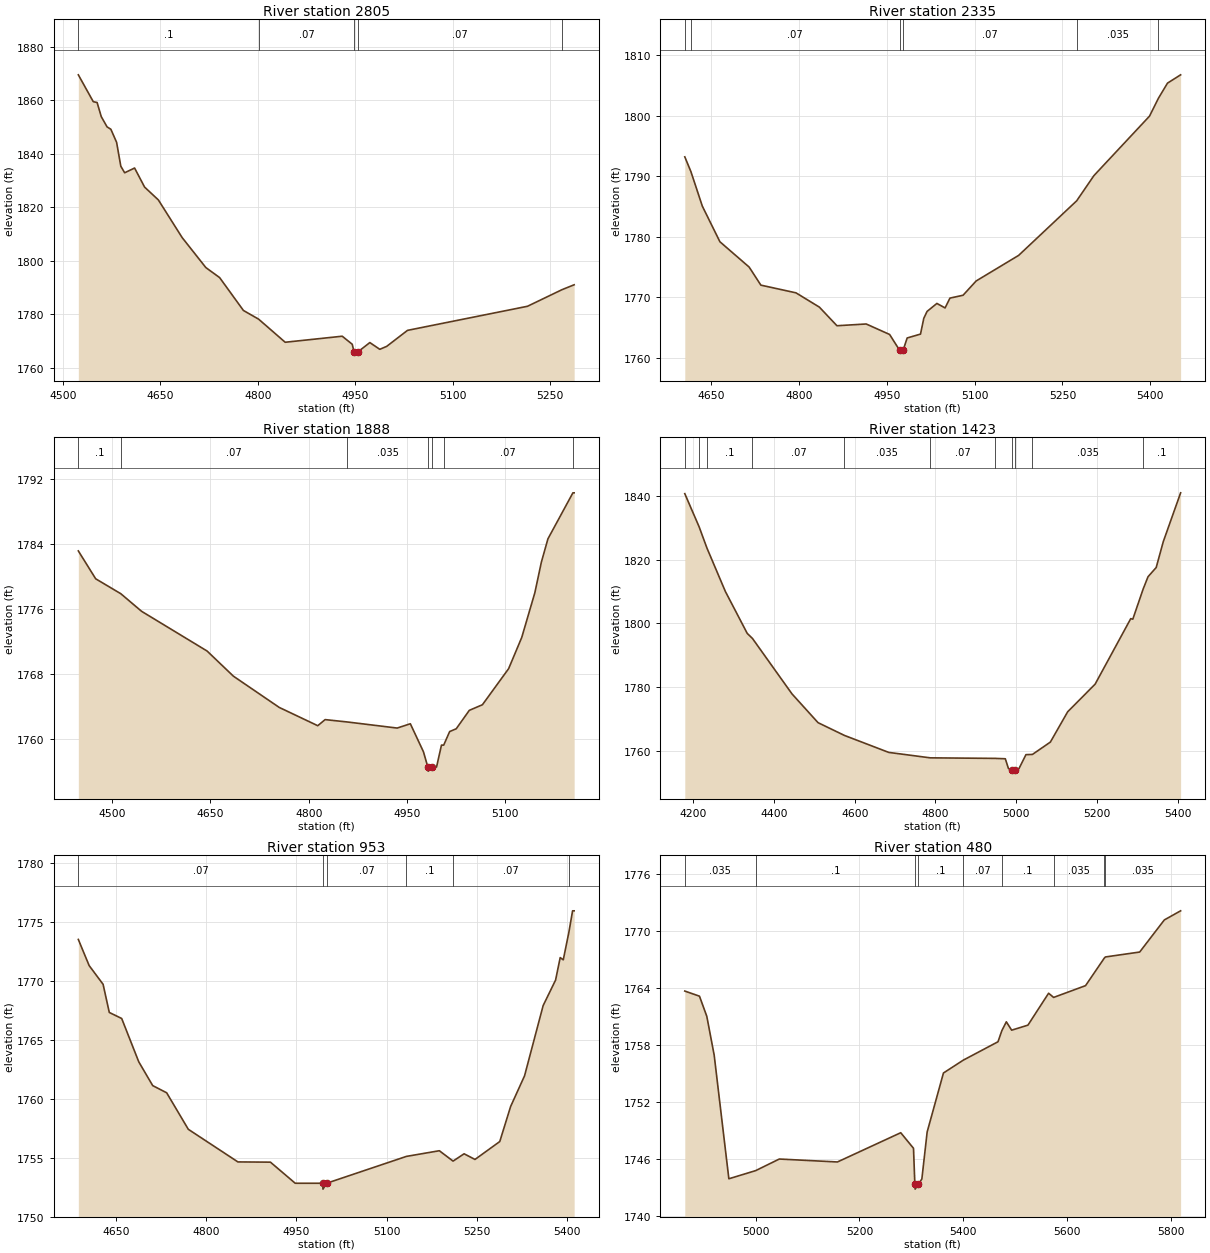
Type RM Length L Ch R = 1,2805,470,470,470
BEGIN DESCRIPTION:
Stream0546 6.0
END DESCRIPTION:
XS GIS Cut Line= 3
      1939674.98     13933975.02      1939275.00     13934225.00
      1939025.02     13934374.99
#Sta/Elev= 30
  4523.7 1869.55  4546.7 1859.50  4552.6 1859.19  4559.0 1853.91  4567.9 1850.07
  4573.8 1849.17  4582.6 1844.29  4589.1 1835.33  4595.0 1832.89  4610.3 1834.66
  4625.7 1827.53  4646.9 1822.72  4683.5 1808.63  4720.0 1797.40  4741.2 1793.65
  4777.8 1781.35  4801.2 1778.10  4842.1 1769.45  4929.9 1771.71  4945.3 1768.70
  4948.1 1765.88  4948.6 1765.38  4954.2 1765.88  4972.4 1769.33  4987.7 1766.81
  4998.3 1767.90  5030.4 1773.90  5215.0 1782.91  5268.2 1789.13  5286.9 1790.96
#Mann=5,-1,0
  4523.7     0.1       0  4801.2    0.07       0  4948.1    0.05       0
  4954.2    0.07       0  5268.2   0.035       0
Bank Sta=4948.1,4954.2
Exp/Cntr=0.3,0.1

Type RM Length L Ch R = 1,2335,447,447,447
BEGIN DESCRIPTION:
Stream0546 5.0
END DESCRIPTION:
XS GIS Cut Line= 3
      1939475.04     13933825.00      1939075.00     13933825.00
      1938674.96     13934025.02
#Sta/Elev= 30
  4604.7 1793.18  4615.1 1790.76  4634.7 1785.04  4664.7 1779.17  4714.7 1774.99
  4734.7 1772.01  4794.7 1770.74  4834.7 1768.38  4864.7 1765.31  4914.7 1765.60
  4954.7 1763.87  4971.6 1761.29  4972.1 1760.79  4977.9 1761.29  4984.7 1763.29
  5007.5 1763.93  5013.1 1766.53  5018.7 1767.67  5035.5 1768.99  5049.5 1768.25
  5057.8 1769.87  5080.2 1770.34  5102.6 1772.70  5175.2 1776.92  5274.4 1785.93
  5303.8 1790.08  5398.9 1799.91  5414.1 1802.86  5429.6 1805.35  5452.0 1806.72
#Mann=6,-1,0
  4604.7     0.1       0  4615.1    0.07       0  4971.6    0.05       0
  4977.9    0.07       0  5274.4   0.035       0  5414.1    0.07       0
Bank Sta=4971.6,4977.9
Exp/Cntr=0.3,0.1

Type RM Length L Ch R = 1,1888,465,465,465
BEGIN DESCRIPTION:
Stream0546 4.0
END DESCRIPTION:
XS GIS Cut Line= 3
      1939481.47     13933439.85      1938925.00     13933425.00
      1938724.97     13933425.00
#Sta/Elev= 30
  4448.4 1783.15  4474.9 1779.72  4513.3 1777.88  4544.9 1775.72  4644.9 1770.83
  4685.0 1767.74  4755.0 1763.89  4813.8 1761.64  4825.0 1762.39  4858.8 1762.10
  4935.0 1761.35  4955.1 1761.88  4975.1 1758.43  4981.8 1756.55  4982.3 1756.05
  4988.3 1756.55  4995.1 1756.56  5002.6 1759.25  5006.0 1759.25  5015.1 1760.92
  5025.1 1761.26  5045.1 1763.53  5065.1 1764.22  5105.1 1768.66  5125.1 1772.50
  5145.1 1778.00  5155.1 1781.78  5165.1 1784.64  5203.2 1790.30  5205.1 1790.30
#Mann=7,-1,0
  4448.4     0.1       0  4513.3    0.07       0  4858.8   0.035       0
  4981.8   0.035       0  4988.3   0.035       0  5006.0    0.07       0
  5203.2     0.1       0
Bank Sta=4981.8,4988.3
Exp/Cntr=0.3,0.1

Type RM Length L Ch R = 1,1423,470,470,470
BEGIN DESCRIPTION:
Stream0546 3.0
END DESCRIPTION:
XS GIS Cut Line= 3
      1939675.03     13933225.01      1938875.00     13933025.00
      1938474.97     13933075.00
#Sta/Elev= 30
  4179.2 1840.64  4214.6 1830.28  4234.0 1823.62  4279.7 1810.00  4333.8 1796.88
  4346.8 1795.29  4444.7 1777.93  4509.1 1768.93  4574.5 1764.93  4684.3 1759.61
  4787.0 1757.91  4947.8 1757.74  4972.9 1757.62  4980.7 1754.54  4990.3 1754.25
  4990.8 1753.75  4996.8 1754.25  5006.4 1754.47  5024.0 1758.91  5040.1 1758.98
  5084.5 1762.85  5127.3 1772.33  5195.3 1780.99  5283.5 1801.50  5288.6 1801.33
  5314.3 1810.80  5326.3 1814.63  5346.5 1817.51  5364.1 1825.63  5407.0 1840.90
#Mann=11,-1,0
  4179.2     0.1       0  4214.6    0.07       0  4234.0     0.1       0
  4346.8    0.07       0  4574.5   0.035       0  4787.0    0.07       0
  4947.8     0.1       0  4990.3    0.05       0  4996.8     0.1       0
  5040.1   0.035       0  5314.3     0.1       0
Bank Sta=4990.3,4996.8
Exp/Cntr=0.3,0.1

Type RM Length L Ch R = 1,953,473,473,473
BEGIN DESCRIPTION:
Stream0546 2.0
END DESCRIPTION:
XS GIS Cut Line= 3
      1939424.97     13932774.99      1939025.00     13932675.00
      1938624.99     13932775.00
#Sta/Elev= 30
  4587.2 1773.53  4605.2 1771.31  4628.4 1769.72  4638.7 1767.33  4659.3 1766.82
  4687.7 1763.14  4710.9 1761.12  4734.1 1760.51  4770.1 1757.41  4852.6 1754.64
  4906.7 1754.62  4947.9 1752.83  4993.6 1752.83  4994.1 1752.33  5000.2 1752.83
  5132.9 1755.11  5187.6 1755.59  5210.4 1754.71  5228.8 1755.33  5246.9 1754.85
  5288.1 1756.37  5306.1 1759.34  5329.3 1761.95  5360.2 1767.91  5380.9 1770.08
  5388.6 1771.99  5393.7 1771.80  5403.1 1774.16  5409.2 1775.96  5411.8 1775.96
#Mann=6,-1,0
  4587.2    0.07       0  4993.6    0.05       0  5000.2    0.07       0
  5132.9     0.1       0  5210.4    0.07       0  5403.1   0.035       0
Bank Sta=4993.6,5000.2
Exp/Cntr=0.3,0.1

Type RM Length L Ch R = 1,480,409,409,409
BEGIN DESCRIPTION:
Stream0546 1.0
END DESCRIPTION:
XS GIS Cut Line= 3
      1939425.01     13932425.01      1939325.00     13932325.00
      1938524.98     13932175.00
#Sta/Elev= 30
  4863.4 1763.69  4891.7 1763.15  4905.8 1761.03  4920.0 1756.95  4948.3 1743.92
  5000.0 1744.78  5045.5 1746.00  5157.5 1745.69  5279.5 1748.77  5304.1 1747.13
  5306.7 1743.33  5307.2 1742.83  5313.4 1743.33  5320.2 1743.90  5330.4 1748.85
  5361.8 1755.06  5399.9 1756.41  5466.9 1758.35  5474.4 1759.53  5483.0 1760.45
  5493.2 1759.57  5524.6 1760.10  5564.4 1763.46  5574.1 1763.02  5635.6 1764.26
  5671.6 1767.15  5673.8 1767.28  5739.9 1767.80  5787.4 1771.18  5818.8 1772.14
#Mann=9,-1,0
  4863.4   0.035       0  5000.0     0.1       0  5306.7   0.035       0
  5313.4     0.1       0  5399.9    0.07       0  5474.4     0.1       0
  5574.1   0.035       0  5671.6     0.1       0  5673.8   0.035       0
Bank Sta=5306.7,5313.4
Exp/Cntr=0.3,0.1

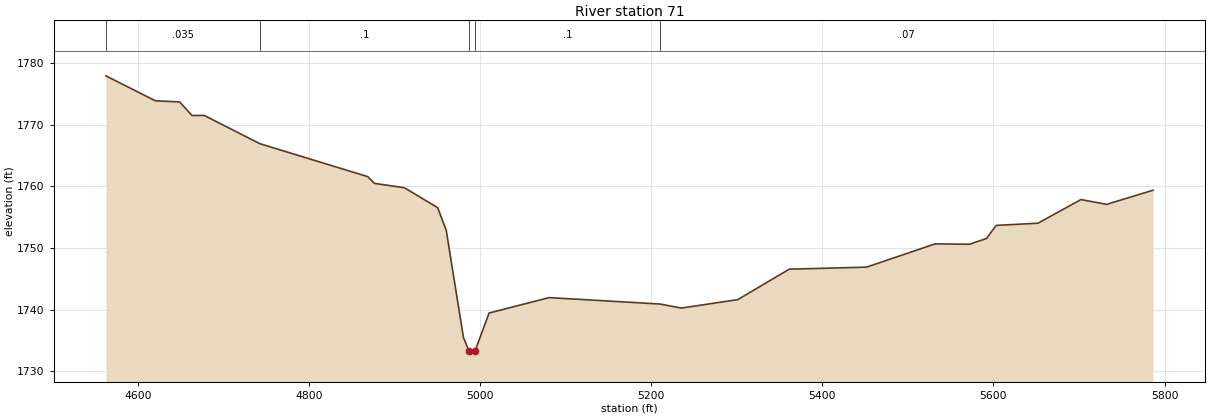
Type RM Length L Ch R = 1,71,0,0,0
BEGIN DESCRIPTION:
Stream0546 0.0
END DESCRIPTION:
XS GIS Cut Line= 4
      1939827.17     13932234.63      1939550.90     13932000.96
      1939055.16     13931967.35      1938690.91     13931993.32
#Sta/Elev= 30
  4562.7 1777.97  4620.4 1773.92  4649.0 1773.72  4663.3 1771.53  4677.6 1771.54
  4742.7 1766.94  4868.7 1761.60  4876.5 1760.50  4911.6 1759.79  4950.5 1756.55
  4960.5 1752.86  4980.6 1735.46  4987.1 1733.26  4987.6 1732.76  4994.1 1733.26
  5010.6 1739.44  5080.8 1741.94  5210.2 1740.90  5235.3 1740.24  5301.3 1741.62
  5361.4 1746.56  5451.7 1746.89  5531.9 1750.67  5572.0 1750.61  5592.0 1751.55
  5603.2 1753.67  5652.2 1754.03  5702.3 1757.87  5732.4 1757.09  5786.6 1759.39
#Mann=5,-1,0
  4562.7   0.035       0  4742.7     0.1       0  4987.1    0.05       0
  4994.1     0.1       0  5210.2    0.07       0
Bank Sta=4987.1,4994.1
Exp/Cntr=0.3,0.1

Chan Stop Cuts=-1