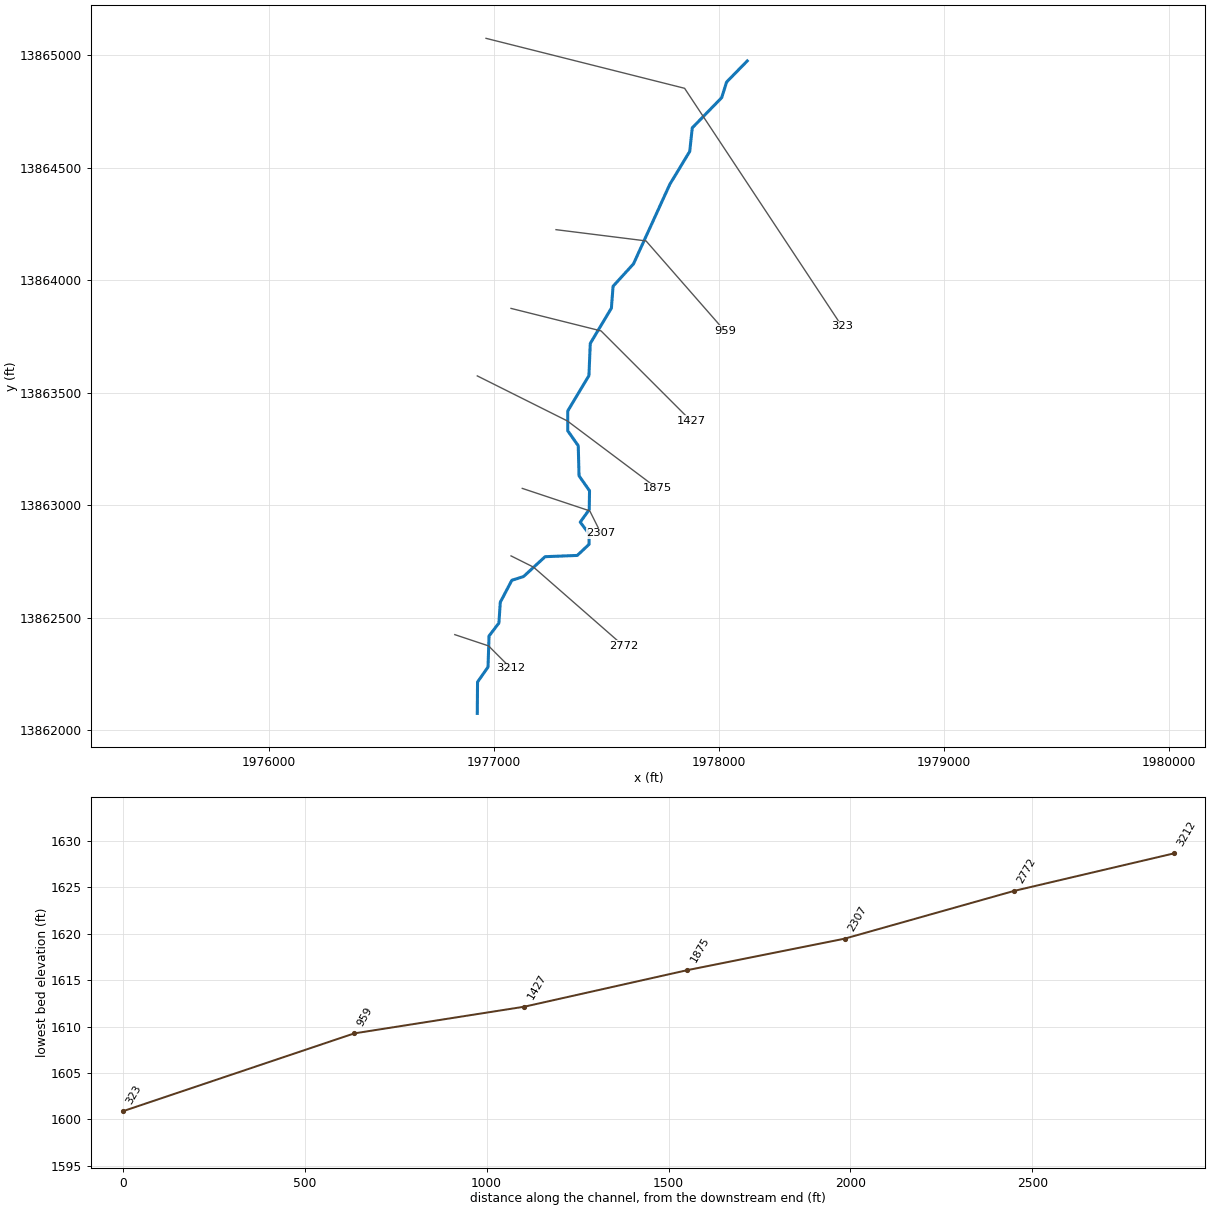
--- Stream0547.prj (project) ---

Proj Title=Stream0547 Base Level Engineering
Current Plan=p01
Default Exp/Contr=0.3,0.1
English Units
Geom File=g01
Flow File=f01
Plan File=p01
Y Axis Title=Elevation
X Axis Title(PF)=Main Channel Distance
X Axis Title(XS)=Station
BEGIN DESCRIPTION:
Stream0547
END DESCRIPTION:
DSS Export Rating Curves= 0
DSS Export Rating Curve Sorted= 0
DSS Export Volume Flow Curves= 0
DXF OffsetX= 0
DXF OffsetY= 0
DXF ScaleX= 1
DXF ScaleY= 10

--- Stream0547.p01 (plan) ---

Plan Title=Multiple Run
Short Identifier=Multiple
Geom File=g01
Flow File=f01
Subcritical Flow
K Sum by GR= 0
Std Step Tol= 0.01
Critical Tol= 0.01
Num of Std Step Trials= 20
Max Error Tol= 0.3
Flow Tol Ratio= 0.001
Split Flow NTrial= 30
Split Flow Tol= 0.02
Split Flow Ratio= 0.02
Log Output Level= 0
Friction Slope Method= 1
Unsteady Friction Slope Method= 2
Unsteady Bridges Friction Slope Method= 1
Parabolic Critical Depth
Global Vel Dist=  1 , 1 , 1
Global Log Level= 0
CheckData=True
Encroach Param= -1, 0, 0, 0
BEGIN DESCRIPTION:
Multiple Run
END DESCRIPTION:

--- Stream0547.f01 (steady flow) ---

Flow Title=Multiple
Number of Profiles=7
Profile Names=10-year,25-year,50-year,1pct_min,100-year,1pct_plu,500-year
River Rch & RM= Stream0547,Reach-1,3212
    2314    4135    5957    4150    8281   16522   15854
Boundary for River Rch & Prof#=Stream0547,Reach-1,1
Up Type=0
Dn Type=3
Dn Slope=0.005
Boundary for River Rch & Prof#=Stream0547,Reach-1,2
Up Type=0
Dn Type=3
Dn Slope=0.005
Boundary for River Rch & Prof#=Stream0547,Reach-1,3
Up Type=0
Dn Type=3
Dn Slope=0.005
Boundary for River Rch & Prof#=Stream0547,Reach-1,4
Up Type=0
Dn Type=3
Dn Slope=0.005
Boundary for River Rch & Prof#=Stream0547,Reach-1,5
Up Type=0
Dn Type=3
Dn Slope=0.005
Boundary for River Rch & Prof#=Stream0547,Reach-1,6
Up Type=0
Dn Type=3
Dn Slope=0.005
Boundary for River Rch & Prof#=Stream0547,Reach-1,7
Up Type=0
Dn Type=3
Dn Slope=0.005

--- Stream0547.g01 (geometry) ---

Geom Title=Existing Conditions
Program Version=4.10

River Reach=Stream0547      ,Reach-1
Reach XY= 30
        1976925.       13862075.      1976926.17     13862214.52
      1976972.73     13862280.94      1976977.27     13862419.06
      1977021.14      13862476.6      1977027.32     13862569.06
      1977078.51     13862666.52      1977130.74      13862683.3
      1977226.47     13862771.45      1977369.37     13862776.99
      1977421.94      13862826.4      1977421.44     13862873.32
       1977382.6     13862924.99      1977422.64     13862980.89
      1977423.89     13863064.45      1977377.27     13863130.94
      1977373.77     13863264.49      1977327.17     13863330.98
      1977327.14     13863419.03      1977421.24     13863576.56
      1977427.25     13863719.07      1977521.17     13863876.59
      1977528.62      13863973.5      1977619.15     13864072.71
      1977781.08      13864427.2      1977869.23     13864572.68
      1977880.52     13864677.43      1978011.37     13864811.79
      1978033.11     13864881.07        1978125.       13864975.

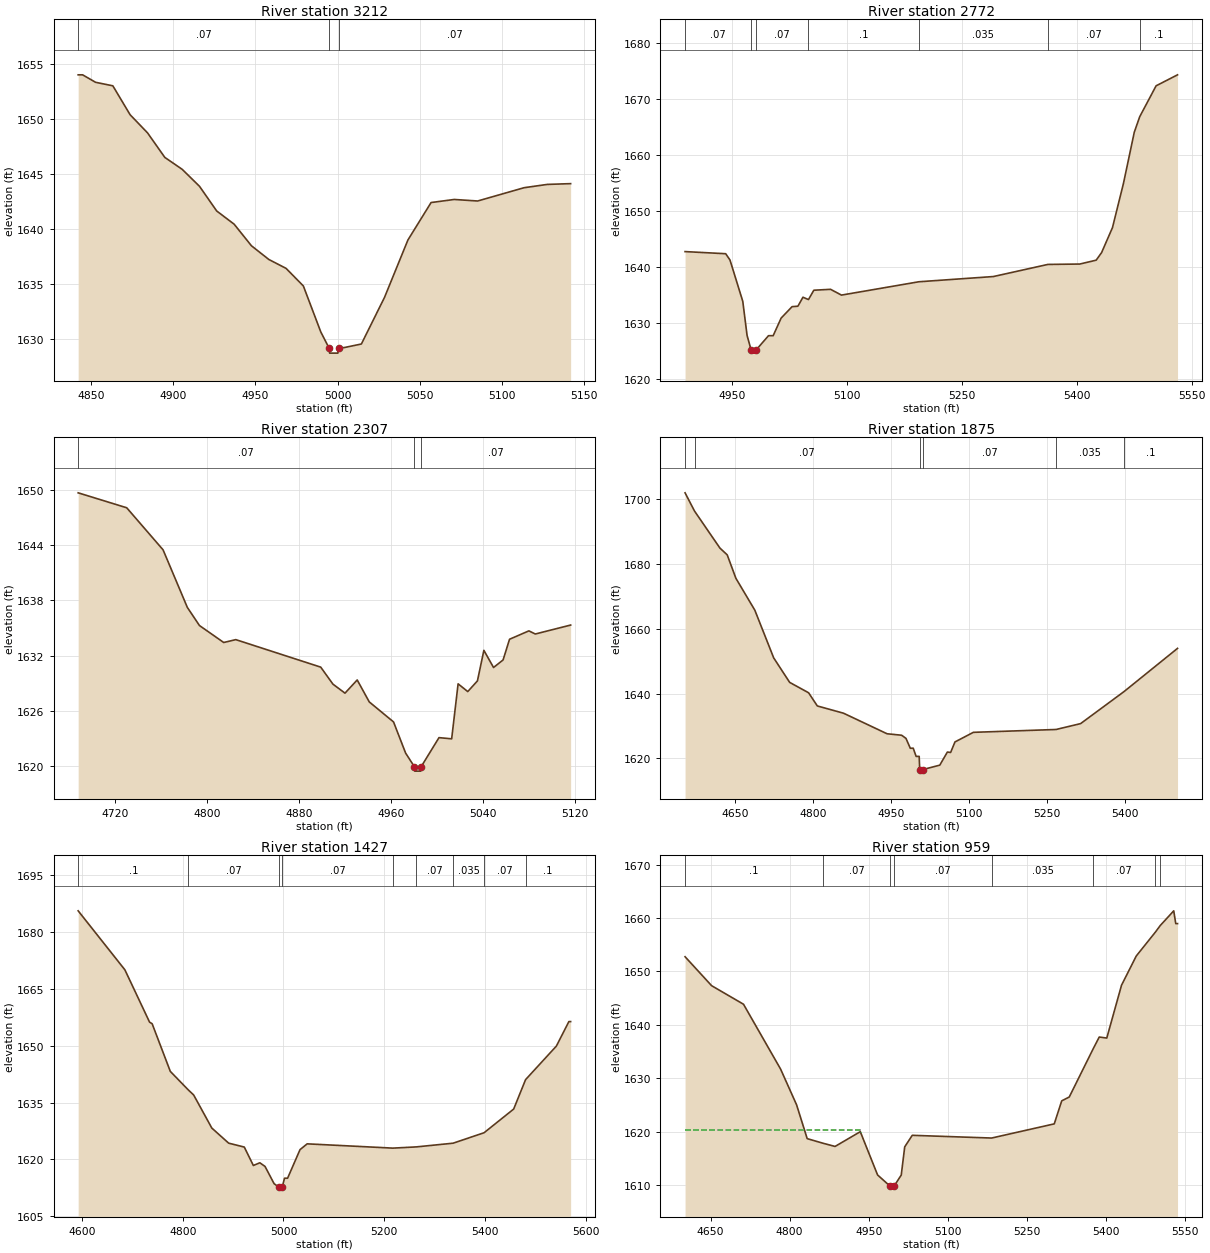
Type RM Length L Ch R = 1 ,3212    ,440,440,440
BEGIN DESCRIPTION:
Stream0547 6.0
END DESCRIPTION:
XS GIS Cut Line= 3
      1976824.98     13862425.01        1976975.       13862375.
      1977075.03     13862274.97
#Sta/Elev= 30
  4842.2 1653.99  4844.9 1653.99  4852.8 1653.31  4863.3 1652.99  4873.8 1650.36
  4884.4 1648.71  4894.9 1646.48  4905.5 1645.39    4916 1643.85  4926.5  1641.6
  4937.1  1640.4  4947.6 1638.44  4958.2 1637.19  4968.7 1636.38  4979.2 1634.78
  4989.8  1630.6  4994.7 1629.17  4995.2 1628.67  5000.2 1628.67  5000.7 1629.17
  5003.9 1629.17  5014.5  1629.5  5028.6 1633.75  5042.8 1638.96  5056.9 1642.37
    5071 1642.65  5085.2 1642.51  5113.5 1643.72  5127.6 1644.02  5141.8 1644.09
#Mann= 3 ,-1 , 0
  4842.2     .07       0  4994.7     .05       0  5000.7     .07       0
Bank Sta=4994.7,5000.7
XS Rating Curve= 0 ,0
Exp/Cntr=0.3,0.1

Type RM Length L Ch R = 1 ,2772    ,465,465,465
BEGIN DESCRIPTION:
Stream0547 5.0
END DESCRIPTION:
XS GIS Cut Line= 3
      1977075.04     13862774.98        1977175.       13862725.
      1977575.02     13862374.98
#Sta/Elev= 30
  4888.3 1642.73  4941.4 1642.35    4947 1641.22  4963.7 1633.86  4969.3 1627.78
  4974.7 1625.12  4975.2 1624.62  4980.7 1625.12  4997.3 1627.73  5003.4 1627.73
  5013.8 1630.87  5028.1 1632.91  5035.7 1632.99  5042.3 1634.59  5049.5 1634.17
  5056.5 1635.84  5078.4    1636  5092.6 1634.97  5193.8 1637.35    5291 1638.28
  5362.2 1640.44  5403.9 1640.51  5425.3  1641.2  5432.4 1642.55  5446.6    1647
  5460.9 1654.86  5475.1 1664.02  5482.2 1666.79  5503.6  1672.3  5531.6 1674.26
#Mann= 7 ,-1 , 0
  4888.3     .07       0  4974.7     .05       0  4980.7     .07       0
  5049.5      .1       0  5193.8    .035       0  5362.2     .07       0
  5482.2      .1       0
Bank Sta=4974.7,4980.7
XS Rating Curve= 0 ,0
Exp/Cntr=0.3,0.1

Type RM Length L Ch R = 1 ,2307    ,432,432,432
BEGIN DESCRIPTION:
Stream0547 4.0
END DESCRIPTION:
XS GIS Cut Line= 3
      1977124.99       13863075.        1977425.       13862975.
      1977474.98     13862875.04
#Sta/Elev= 30
    4688 1649.64  4730.2 1648.02  4761.8 1643.46  4782.9 1637.22  4793.4 1635.26
  4814.5 1633.42    4825 1633.73  4898.8 1630.75  4909.4 1628.91  4919.9 1627.93
  4930.5 1629.36    4941 1626.98  4962.1 1624.81  4972.6 1621.43  4980.1 1619.98
  4980.6 1619.48  4985.7 1619.48  4986.2 1619.98  5001.6 1623.11  5012.6 1622.98
  5018.2 1628.94  5026.6  1628.1    5035 1629.26  5040.6 1632.57    5049 1630.71
  5057.3 1631.53  5062.9 1633.77  5079.7 1634.68  5085.3 1634.34    5116 1635.31
#Mann= 3 ,-1 , 0
    4688     .07       0  4980.1     .05       0  4986.2     .07       0
Bank Sta=4980.1,4986.2
XS Rating Curve= 0 ,0
Exp/Cntr=0.3,0.1

Type RM Length L Ch R = 1 ,1875    ,448,448,448
BEGIN DESCRIPTION:
Stream0547 3.0
END DESCRIPTION:
XS GIS Cut Line= 3
        1976925.       13863575.        1977325.       13863375.
      1977724.99     13863075.01
#Sta/Elev= 30
  4553.7 1701.83  4571.9 1696.21  4620.8  1684.8  4634.8 1682.71  4651.5 1675.49
  4687.9 1665.67  4724.2 1650.97  4754.9 1643.43  4791.3 1640.23  4808.1 1636.17
  4858.4 1633.94  4942.2  1627.6  4970.2 1627.15  4978.6 1626.18  4986.9 1623.13
  4992.5 1623.16  4998.1 1620.63    5004 1620.63    5005 1616.59  5005.5 1616.09
  5011.4 1616.59  5043.6 1617.93  5058.2 1621.96  5064.5 1621.85  5072.8 1625.08
  5108.2 1628.04  5267.3 1628.92  5314.5 1630.73  5398.1 1640.61  5500.9 1653.91
#Mann= 6 ,-1 , 0
  4553.7      .1       0  4571.9     .07       0    5005     .05       0
  5011.4     .07       0  5267.3    .035       0  5398.1      .1       0
Bank Sta=5005,5011.4
XS Rating Curve= 0 ,0
Exp/Cntr=0.3,0.1

Type RM Length L Ch R = 1 ,1427    ,468,468,468
BEGIN DESCRIPTION:
Stream0547 2.0
END DESCRIPTION:
XS GIS Cut Line= 3
      1977074.98       13863875.        1977475.       13863775.
      1977874.99     13863375.01
#Sta/Elev= 30
  4592.3 1685.59  4685.1 1670.02  4734.1 1656.22  4739.2  1655.8  4775.3 1643.22
  4811.1 1638.32  4821.7 1636.99  4857.7 1628.27  4891.2 1624.28  4922.2 1623.25
  4940.2 1618.39  4953.1  1619.1  4963.4 1618.14  4981.4 1613.59  4991.1 1612.65
  4991.6 1612.15  4997.5 1612.65  5002.1 1615.03  5008.2 1615.03  5032.9 1622.57
  5047.1  1624.1  5217.4 1622.97  5263.5 1623.29  5336.9 1624.27  5398.4 1627.03
  5457.2 1633.28  5480.8 1641.04    5542  1649.9  5566.8 1656.36  5570.3 1656.36
#Mann= 9 ,-1 , 0
  4592.3      .1       0  4811.1     .07       0  4991.1     .05       0
  4997.5     .07       0  5217.4    .035       0  5263.5     .07       0
  5336.9    .035       0  5398.4     .07       0  5480.8      .1       0
Bank Sta=4991.1,4997.5
XS Rating Curve= 0 ,0
Exp/Cntr=0.3,0.1

Type RM Length L Ch R = 1 ,959     ,636,636,636
BEGIN DESCRIPTION:
Stream0547 1.0
END DESCRIPTION:
XS GIS Cut Line= 3
      1977274.96       13864225.        1977675.       13864175.
      1978025.03     13863774.97
#Sta/Elev= 30
  4601.6 1652.76    4652 1647.34  4712.5 1643.87    4783 1631.72  4813.3 1625.04
  4833.4 1618.72  4863.7 1617.85  4886.3 1617.26  4934.2 1620.02    4967 1611.92
  4991.4 1609.77  4991.9 1609.27  4997.9 1609.77  5011.9  1611.9  5018.5 1617.18
  5032.8 1619.34  5183.4 1618.83  5302.3 1621.48  5316.5 1625.79  5330.8 1626.51
  5376.4 1635.57  5387.7 1637.73    5402 1637.54    5430 1647.43    5458  1652.9
  5493.9 1657.32  5503.6 1658.61  5529.1 1661.35  5532.9 1658.96  5536.3 1658.96
#Mann= 8 ,-1 , 0
  4601.6      .1       0  4863.7     .07       0  4991.4     .05       0
  4997.9     .07       0  5183.4    .035       0  5376.4     .07       0
  5493.9      .1       0  5503.6     .07       0
#XS Ineff= 2 , 0
         4934.83 1620.39
Permanent Ineff=
       F       F
Bank Sta=4991.4,4997.9
XS Rating Curve= 0 ,0
Exp/Cntr=0.3,0.1

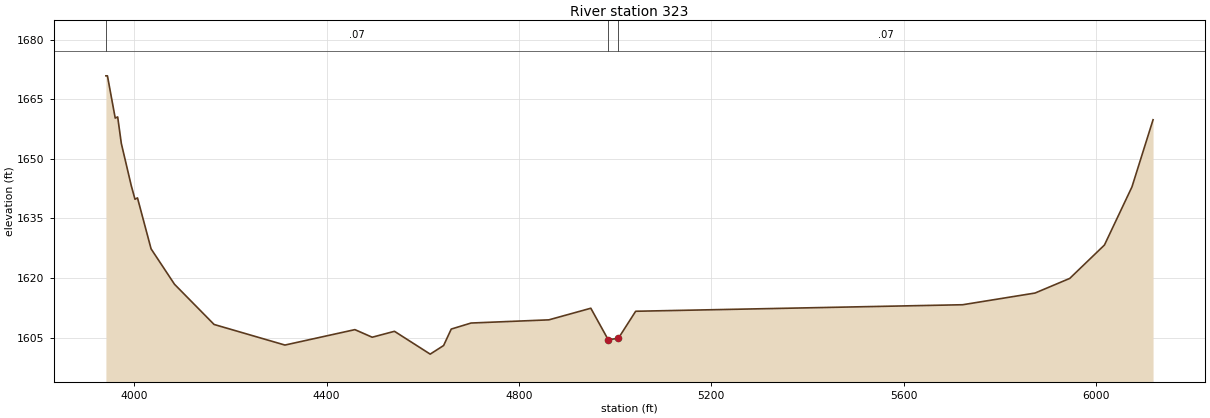
Type RM Length L Ch R = 1 ,323     ,0,0,0
BEGIN DESCRIPTION:
Stream0547 0.0
END DESCRIPTION:
XS GIS Cut Line= 3
      1976963.86      13865075.4      1977846.47     13864853.33
      1978545.75     13863795.72
#Sta/Elev= 30
  3940.8 1670.87    3944 1670.87  3960.2 1660.24  3965.3 1660.54  3972.9 1653.85
  3993.5 1643.28  4001.3 1639.83  4006.5 1640.17  4034.8 1627.35  4083.5 1618.45
  4165.8 1608.34  4313.2 1603.16  4458.7 1607.04  4494.7 1605.13    4541 1606.62
  4615.3 1600.88  4643.2 1603.04  4659.1 1607.18  4700.3  1608.7  4862.1  1609.5
  4949.4 1612.42  4985.5 1604.52  5006.6 1604.84  5042.7 1611.66  5722.8  1613.3
  5873.3 1616.24  5945.5 1619.92  6017.7 1628.32  6074.9 1642.93  6118.8 1659.82
#Mann= 3 ,-1 , 0
  3940.8     .07       0  4985.5     .05       0  5006.6     .07       0
#Block Obstruct= 2 , 0
         4964.61 1603.26
Bank Sta=4985.5,5006.6
XS Rating Curve= 0 ,0
Exp/Cntr=0.3,0.1

Chan Stop Cuts=-1
Use User Specified Reach Order=0
Composite Channel Slope=5