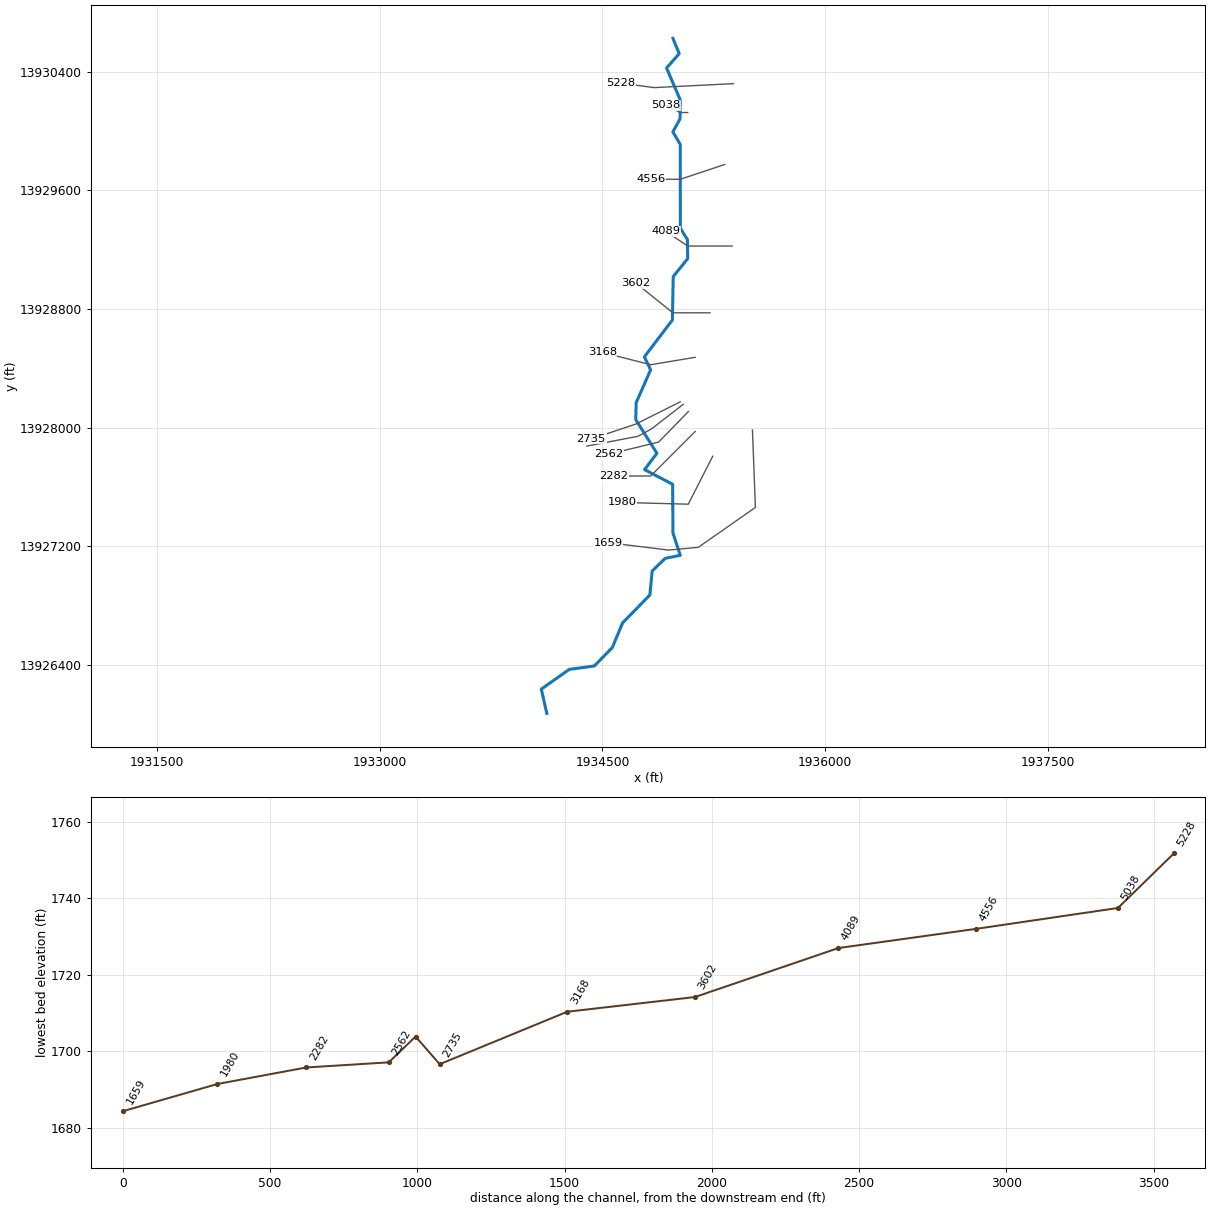
--- Stream0549.prj (project) ---

Proj Title=Stream0549 Base Level Engineering
Current Plan=p01
Default Exp/Contr=0.3,0.1
English Units
Geom File=g01
Flow File=f01
Plan File=p01
BEGIN DESCRIPTION:
Stream0549
END DESCRIPTION:

--- Stream0549.p01 (plan) ---

Plan Title=Multiple Run
Short Identifier=Multiple
Geom File=g01
Flow File=f01
Subcritical Flow
K Sum by GR= 0
Std Step Tol= 0.01
Critical Tol= 0.01
Num of Std Step Trials= 20
Max Error Tol= 0.3
Flow Tol Ratio= 0.001
Split Flow NTrial= 30
Split Flow Tol= 0.02
Split Flow Ratio= 0.02
Log Output Level= 0
Friction Slope Method= 1
Unsteady Friction Slope Method= 2
Unsteady Bridges Friction Slope Method= 1
Parabolic Critical Depth
Global Vel Dist=  1 , 1 , 1
Global Log Level= 0
CheckData=True
Encroach Param= -1, 0, 0, 0
BEGIN DESCRIPTION:
Multiple Run
END DESCRIPTION:

--- Stream0549.f01 (steady flow) ---

Flow Title=Multiple
Number of Profiles=7
Profile Names=10-year,25-year,50-year,1pct_min,100-year,1pct_plu,500-year
River Rch & RM= Stream0549,Reach-1,5228
    1075    1833    2556    1725    3442    6867    6156
Boundary for River Rch & Prof#=Stream0549,Reach-1,1
Up Type=0
Dn Type=3
Dn Slope=0.005
Boundary for River Rch & Prof#=Stream0549,Reach-1,2
Up Type=0
Dn Type=3
Dn Slope=0.005
Boundary for River Rch & Prof#=Stream0549,Reach-1,3
Up Type=0
Dn Type=3
Dn Slope=0.005
Boundary for River Rch & Prof#=Stream0549,Reach-1,4
Up Type=0
Dn Type=3
Dn Slope=0.005
Boundary for River Rch & Prof#=Stream0549,Reach-1,5
Up Type=0
Dn Type=3
Dn Slope=0.005
Boundary for River Rch & Prof#=Stream0549,Reach-1,6
Up Type=0
Dn Type=3
Dn Slope=0.005
Boundary for River Rch & Prof#=Stream0549,Reach-1,7
Up Type=0
Dn Type=3
Dn Slope=0.005

--- Stream0549.g01 (geometry) ---

Geom Title=Existing Conditions

River Reach=Stream0549,Reach-1
Reach XY= 30
      1934975.00     13930625.00      1935017.38     13930521.61
      1934932.34     13930425.10      1935024.50     13930209.78
      1935022.72     13930080.93      1934974.72     13929995.18
      1935024.46     13929909.79      1935025.07     13929345.03
      1935072.75     13929269.06      1935074.63     13929140.17
      1934977.07     13929019.14      1934971.45     13928726.47
      1934782.83     13928478.40      1934824.85     13928390.42
      1934727.25     13928169.06      1934724.54     13928054.84
      1934867.15     13927828.23      1934783.83     13927718.01
      1934973.03     13927619.35      1934975.52     13927290.21
      1935024.58     13927140.64      1934922.62     13927119.46
      1934835.47     13927034.82      1934819.53     13926872.55
      1934635.76     13926684.68      1934566.86     13926518.94
      1934445.16     13926394.61      1934276.47     13926371.45
      1934087.97     13926238.57      1934125.00     13926075.00

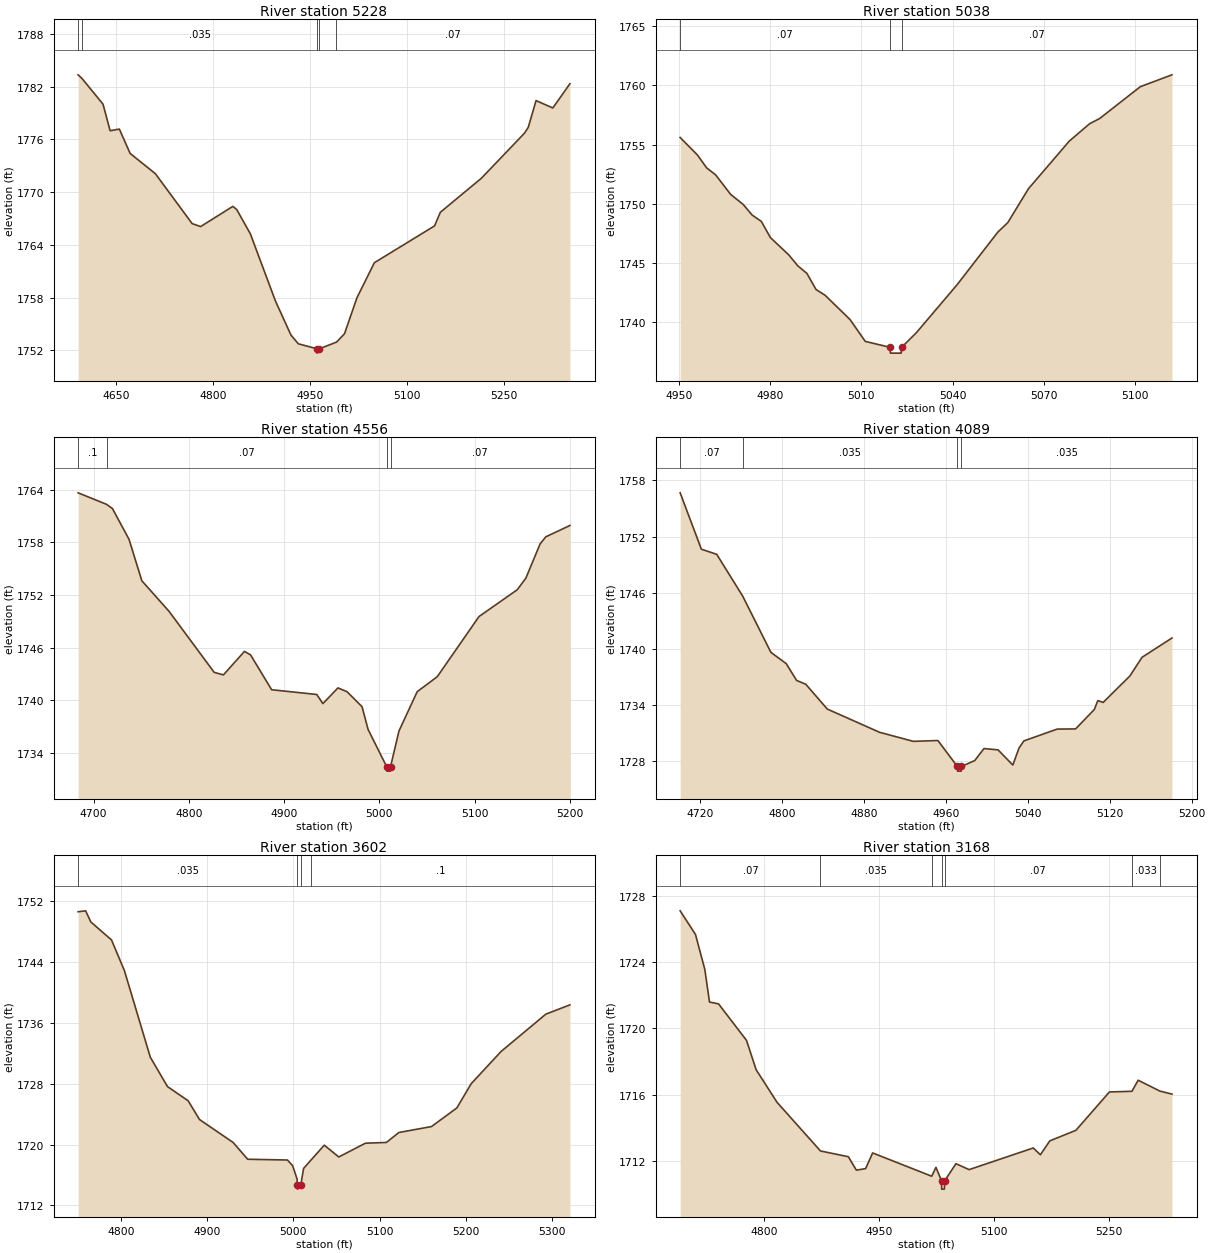
Type RM Length L Ch R = 1,5228,190,190,190
BEGIN DESCRIPTION:
Mapping XS 1cc710e3
END DESCRIPTION:
XS GIS Cut Line= 3
      1935383.82     13930319.64      1934849.87     13930292.77
      1934624.30     13930322.89
#Sta/Elev= 30
  4590.7 1783.33  4596.9 1782.90  4629.3 1779.99  4640.3 1776.97  4654.6 1777.16
  4671.3 1774.39  4710.4 1772.09  4767.4 1766.41  4780.5 1766.07  4830.5 1768.37
  4836.5 1768.01  4857.6 1765.25  4896.6 1757.59  4920.6 1753.73  4932.0 1752.74
  4960.7 1752.18  4960.9 1751.68  4964.7 1752.18  4991.1 1752.93  5003.5 1753.88
  5022.8 1757.97  5049.8 1761.96  5143.1 1766.15  5152.1 1767.70  5215.7 1771.57
  5282.3 1776.68  5288.3 1777.35  5300.4 1780.40  5326.4 1779.56  5352.9 1782.32
#Mann=5,-1,0
  4590.7    0.07       0  4596.9   0.035       0  4960.7    0.05       0
  4964.7   0.035       0  4991.1    0.07       0
Bank Sta=4960.7,4964.7
Exp/Cntr=0.3,0.1

Type RM Length L Ch R = 1,5038,482,482,482
BEGIN DESCRIPTION:
Stream0549 7.0
END DESCRIPTION:
XS GIS Cut Line= 3
      1935075.04     13930125.00      1935025.00     13930125.00
      1934925.04     13930174.98
#Sta/Elev= 30
  4950.4 1755.61  4956.1 1754.13  4959.1 1753.05  4962.1 1752.45  4967.0 1750.81
  4971.1 1749.97  4974.1 1749.06  4977.1 1748.53  4980.1 1747.16  4986.1 1745.71
  4989.1 1744.78  4992.1 1744.14  4995.1 1742.78  4998.1 1742.29  5006.3 1740.24
  5011.3 1738.40  5019.3 1737.91  5019.6 1737.41  5023.1 1737.41  5023.3 1737.91
  5028.1 1739.13  5041.5 1743.18  5054.9 1747.62  5058.2 1748.43  5065.0 1751.29
  5078.4 1755.30  5085.1 1756.77  5088.4 1757.21  5101.8 1759.90  5112.2 1760.90
#Mann=3,-1,0
  4950.4    0.07       0  5019.3    0.05       0  5023.3    0.07       0
Bank Sta=5019.3,5023.3
Exp/Cntr=0.3,0.1

Type RM Length L Ch R = 1,4556,467,467,467
BEGIN DESCRIPTION:
Stream0549 6.0
END DESCRIPTION:
XS GIS Cut Line= 3
      1935324.98     13929774.99      1935025.00     13929675.00
      1934825.00     13929675.00
#Sta/Elev= 30
  4683.8 1763.65  4713.6 1762.34  4719.8 1761.86  4737.2 1758.36  4750.7 1753.63
  4779.4 1750.13  4826.6 1743.20  4836.3 1742.91  4858.4 1745.59  4864.8 1745.19
  4886.9 1741.22  4934.3 1740.68  4940.7 1739.64  4956.5 1741.43  4966.0 1741.00
  4981.8 1739.29  4988.1 1736.71  5007.7 1732.45  5008.0 1731.95  5011.5 1731.95
  5011.7 1732.45  5020.6 1736.53  5039.7 1741.00  5060.7 1742.70  5104.6 1749.56
  5144.7 1752.61  5153.7 1753.92  5168.7 1757.83  5174.7 1758.64  5200.0 1759.93
#Mann=4,-1,0
  4683.8     0.1       0  4713.6    0.07       0  5007.7    0.05       0
  5011.7    0.07       0
Bank Sta=5007.7,5011.7
Exp/Cntr=0.3,0.1

Type RM Length L Ch R = 1,4089,487,487,487
BEGIN DESCRIPTION:
Stream0549 5.0
END DESCRIPTION:
XS GIS Cut Line= 3
      1935375.05     13929225.00      1935075.00     13929225.00
      1934925.02     13929324.99
#Sta/Elev= 30
  4700.4 1756.67  4721.1 1750.65  4736.1 1750.10  4761.5 1745.63  4789.0 1739.63
  4804.0 1738.42  4814.1 1736.63  4823.1 1736.22  4844.1 1733.57  4895.1 1731.09
  4928.1 1730.12  4952.1 1730.21  4971.1 1727.44  4971.4 1726.94  4974.9 1726.94
  4975.1 1727.44  4988.1 1728.07  4997.1 1729.35  5010.9 1729.21  5025.3 1727.59
  5031.3 1729.40  5036.1 1730.17  5068.6 1731.43  5086.6 1731.45  5104.9 1733.53
  5108.3 1734.47  5113.5 1734.28  5139.5 1737.09  5151.5 1739.10  5180.7 1741.16
#Mann=4,-1,0
  4700.4    0.07       0  4761.5   0.035       0  4971.1   0.035       0
  4975.1   0.035       0
Bank Sta=4971.1,4975.1
Exp/Cntr=0.3,0.1

Type RM Length L Ch R = 1,3602,434,434,434
BEGIN DESCRIPTION:
Stream0549 4.0
END DESCRIPTION:
XS GIS Cut Line= 3
      1935225.03     13928775.00      1934975.00     13928775.00
      1934724.99     13928975.01
#Sta/Elev= 30
  4750.4 1750.62  4759.1 1750.74  4765.1 1749.28  4789.1 1746.91  4804.1 1742.86
  4834.1 1731.48  4854.0 1727.62  4878.0 1725.75  4891.1 1723.29  4930.1 1720.27
  4947.0 1718.06  4993.1 1717.96  4999.1 1717.21  5004.3 1715.45  5004.5 1714.63
  5004.7 1714.13  5008.5 1714.63  5011.8 1716.85  5020.9 1718.02  5035.8 1719.91
  5052.6 1718.36  5083.5 1720.17  5107.8 1720.27  5122.3 1721.58  5160.1 1722.36
  5189.5 1724.81  5206.2 1728.01  5240.8 1732.24  5292.7 1737.15  5320.6 1738.37
#Mann=4,-1,0
  4750.4   0.035       0  5004.5   0.035       0  5008.5   0.035       0
  5020.9     0.1       0
Bank Sta=5004.5,5008.5
Exp/Cntr=0.3,0.1

Type RM Length L Ch R = 1,3168,433,433,433
BEGIN DESCRIPTION:
Stream0549 3.0
END DESCRIPTION:
XS GIS Cut Line= 3
      1935125.04     13928475.01      1934825.00     13928425.00
      1934497.91     13928508.66
#Sta/Elev= 30
  4690.5 1727.12  4710.5 1725.69  4722.7 1723.57  4728.8 1721.60  4740.6 1721.49
  4777.1 1719.28  4789.6 1717.51  4817.0 1715.53  4873.6 1712.59  4910.0 1712.24
  4920.4 1711.43  4932.5 1711.52  4941.7 1712.47  5018.8 1711.06  5024.3 1711.60
  5031.6 1710.78  5031.8 1710.28  5035.3 1710.28  5035.6 1710.78  5050.4 1711.82
  5067.6 1711.46  5151.3 1712.77  5160.6 1712.36  5172.9 1713.20  5207.0 1713.84
  5250.7 1716.16  5280.1 1716.20  5288.2 1716.87  5316.7 1716.21  5332.3 1716.03
#Mann=7,-1,0
  4690.5    0.07       0  4873.6   0.035       0  5018.8    0.07       0
  5031.6   0.035       0  5035.6    0.07       0  5280.1   0.033       0
  5316.7     0.1       0
Bank Sta=5031.6,5035.6
Exp/Cntr=0.3,0.1

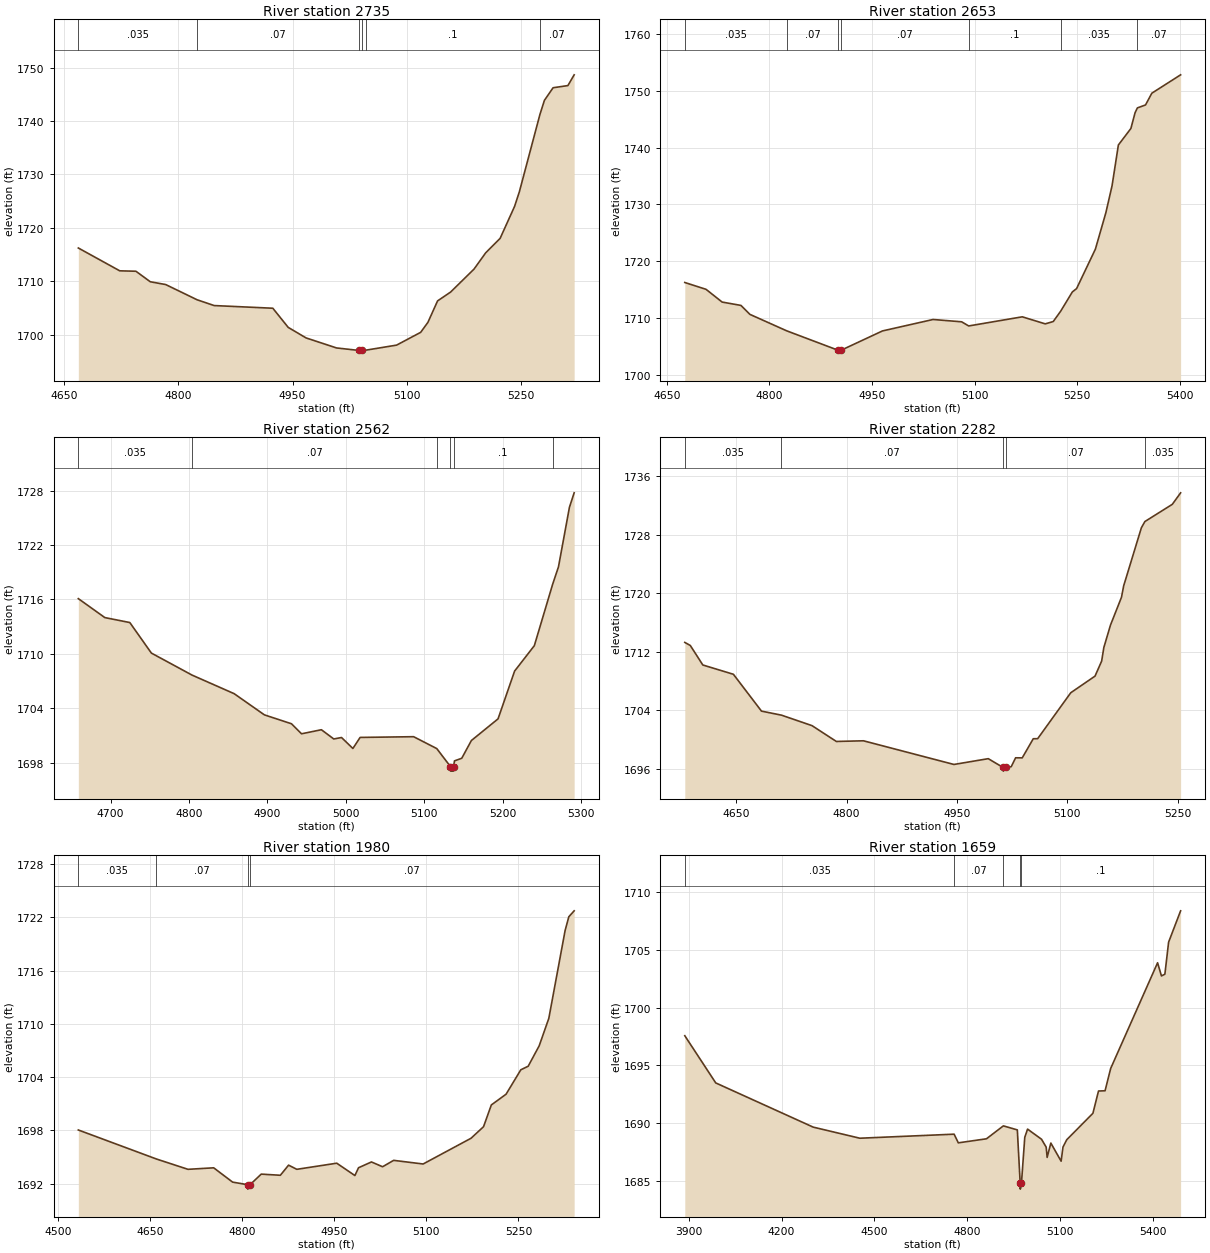
Type RM Length L Ch R = 1,2735,82,82,82
BEGIN DESCRIPTION:
Stream0549 2.0
END DESCRIPTION:
XS GIS Cut Line= 3
      1935024.96     13928174.98      1934725.00     13928025.00
      1934424.99     13927925.00
#Sta/Elev= 30
  4668.5 1716.24  4722.9 1711.97  4744.2 1711.89  4763.1 1709.92  4783.3 1709.40
  4824.6 1706.55  4847.0 1705.47  4924.1 1704.97  4944.3 1701.39  4967.7 1699.42
  5007.8 1697.54  5037.4 1697.07  5037.6 1696.57  5041.4 1697.07  5047.1 1697.14
  5086.8 1698.07  5118.4 1700.46  5127.9 1702.32  5140.6 1706.34  5157.7 1707.99
  5188.5 1712.29  5203.8 1715.33  5222.8 1718.04  5241.8 1724.02  5248.1 1726.76
  5275.1 1741.21  5281.0 1743.86  5292.4 1746.22  5311.9 1746.63  5320.1 1748.64
#Mann=6,-1,0
  4668.5   0.035       0  4824.6    0.07       0  5037.4    0.05       0
  5041.4    0.07       0  5047.1     0.1       0  5275.1    0.07       0
Bank Sta=5037.4,5041.4
Exp/Cntr=0.3,0.1

Type RM Length L Ch R = 1,2653,91,91,91
BEGIN DESCRIPTION:
Stream0549 2.1
END DESCRIPTION:
XS GIS Cut Line= 4
      1935044.22     13928157.74      1934828.95     13927991.08
      1934738.68     13927942.47      1934394.92     13927876.50
#Sta/Elev= 30
  4676.2 1716.24  4707.2 1715.04  4730.8 1712.79  4758.3 1712.20  4771.4 1710.62
  4825.2 1707.72  4900.5 1704.29  4900.7 1703.79  4904.2 1703.79  4904.5 1704.29
  4965.1 1707.70  5039.1 1709.72  5080.9 1709.31  5091.2 1708.58  5169.5 1710.19
  5203.1 1708.95  5214.8 1709.36  5225.6 1711.17  5242.8 1714.59  5248.9 1715.16
  5276.4 1722.12  5291.7 1728.53  5300.8 1733.31  5310.0 1740.48  5328.3 1743.39
  5334.4 1746.16  5337.8 1747.02  5349.7 1747.54  5358.9 1749.61  5401.0 1752.85
#Mann=7,-1,0
  4676.2   0.035       0  4825.2    0.07       0  4900.5    0.05       0
  4904.5    0.07       0  5091.2     0.1       0  5225.6   0.035       0
  5337.8    0.07       0
Bank Sta=4900.5,4904.5
Exp/Cntr=0.3,0.1

Type RM Length L Ch R = 1,2562,280,280,280
BEGIN DESCRIPTION:
Mapping XS 914ae2a8
END DESCRIPTION:
XS GIS Cut Line= 3
      1935078.99     13928109.19      1934878.83     13927903.59
      1934542.89     13927822.21
#Sta/Elev= 30
  4658.8 1716.09  4692.6 1714.00  4724.5 1713.45  4752.0 1710.08  4803.9 1707.65
  4857.6 1705.60  4896.2 1703.26  4930.7 1702.28  4943.6 1701.17  4968.9 1701.62
  4984.7 1700.60  4994.6 1700.76  5009.1 1699.55  5018.3 1700.77  5086.6 1700.85
  5116.1 1699.54  5133.6 1697.55  5133.9 1697.05  5137.4 1697.05  5137.6 1697.55
  5138.7 1698.18  5148.0 1698.47  5160.3 1700.43  5194.3 1702.82  5215.4 1708.09
  5240.6 1710.90  5263.8 1717.63  5271.4 1719.60  5285.4 1726.18  5291.4 1727.77
#Mann=6,-1,0
  4658.8   0.035       0  4803.9    0.07       0  5116.1     0.1       0
  5133.6    0.05       0  5137.6     0.1       0  5263.8   0.035       0
Bank Sta=5133.6,5137.6
Exp/Cntr=0.3,0.1

Type RM Length L Ch R = 1,2282,302,302,302
BEGIN DESCRIPTION:
Stream0549 1.0
END DESCRIPTION:
XS GIS Cut Line= 3
      1935125.03     13927975.03      1934825.00     13927675.00
      1934575.01     13927675.00
#Sta/Elev= 30
  4579.9 1713.28  4587.4 1712.86  4604.4 1710.20  4646.0 1708.93  4684.2 1703.90
  4711.4 1703.35  4752.9 1701.92  4786.0 1699.76  4822.9 1699.85  4945.9 1696.62
  4992.6 1697.41  5012.8 1696.21  5013.1 1695.71  5016.8 1696.21  5023.8 1696.31
  5029.8 1697.53  5038.8 1697.52  5053.8 1700.13  5059.8 1700.14  5104.8 1706.41
  5137.8 1708.68  5146.8 1710.73  5149.8 1712.59  5158.8 1715.64  5173.8 1719.45
  5176.8 1721.02  5200.8 1728.92  5205.6 1729.78  5242.9 1732.13  5254.2 1733.70
#Mann=5,-1,0
  4579.9   0.035       0  4711.4    0.07       0  5012.8    0.05       0
  5016.8    0.07       0  5205.6   0.035       0
Bank Sta=5012.8,5016.8
Exp/Cntr=0.3,0.1

Type RM Length L Ch R = 1,1980,321,321,321
BEGIN DESCRIPTION:
Stream0549 0.0
END DESCRIPTION:
XS GIS Cut Line= 3
      1935243.38     13927808.32      1935078.50     13927485.03
      1934634.56     13927496.74
#Sta/Elev= 30
  4533.6 1698.05  4660.8 1694.78  4712.1 1693.62  4753.9 1693.79  4784.7 1692.18
  4809.1 1691.89  4809.4 1691.39  4813.1 1691.89  4831.3 1693.08  4862.4 1692.95
  4875.8 1694.09  4889.2 1693.62  4954.2 1694.31  4983.7 1692.92  4989.7 1693.80
  5010.7 1694.45  5028.8 1693.91  5046.8 1694.63  5094.8 1694.22  5172.8 1697.12
  5193.1 1698.42  5205.8 1700.87  5229.8 1702.08  5253.8 1704.83  5265.8 1705.23
  5283.7 1707.53  5299.4 1710.63  5325.9 1720.52  5331.9 1722.06  5340.6 1722.73
#Mann=4,-1,0
  4533.6   0.035       0  4660.8    0.07       0  4809.1    0.05       0
  4813.1    0.07       0
Bank Sta=4809.1,4813.1
Exp/Cntr=0.3,0.1

Type RM Length L Ch R = 1,1659,0,0,0
BEGIN DESCRIPTION:
Stream0549 0.1
END DESCRIPTION:
XS GIS Cut Line= 5
      1935511.03     13927985.10      1935531.00     13927463.02
      1935145.83     13927193.99      1934944.79     13927175.68
      1934538.82     13927225.72
#Sta/Elev= 30
  3887.3 1697.56  3987.4 1693.47  4302.6 1689.64  4453.3 1688.68  4758.1 1689.03
  4771.7 1688.28  4862.7 1688.63  4917.4 1689.75  4962.5 1689.40  4971.8 1684.77
  4972.1 1684.27  4975.8 1684.77  4986.6 1688.76  4995.6 1689.47  5040.8 1688.59
  5055.8 1687.91  5058.9 1687.02  5070.9 1688.26  5104.1 1686.69  5110.2 1687.92
  5122.3 1688.55  5206.9 1690.84  5225.0 1692.77  5246.2 1692.79  5264.3 1694.72
  5416.0 1703.88  5428.5 1702.74  5439.6 1702.89  5451.7 1705.67  5490.5 1708.38
#Mann=5,-1,0
  3887.3   0.035       0  4758.1    0.07       0  4917.4     0.1       0
  4971.8    0.05       0  4975.8     0.1       0
Bank Sta=4971.8,4975.8
Exp/Cntr=0.3,0.1

Chan Stop Cuts=-1