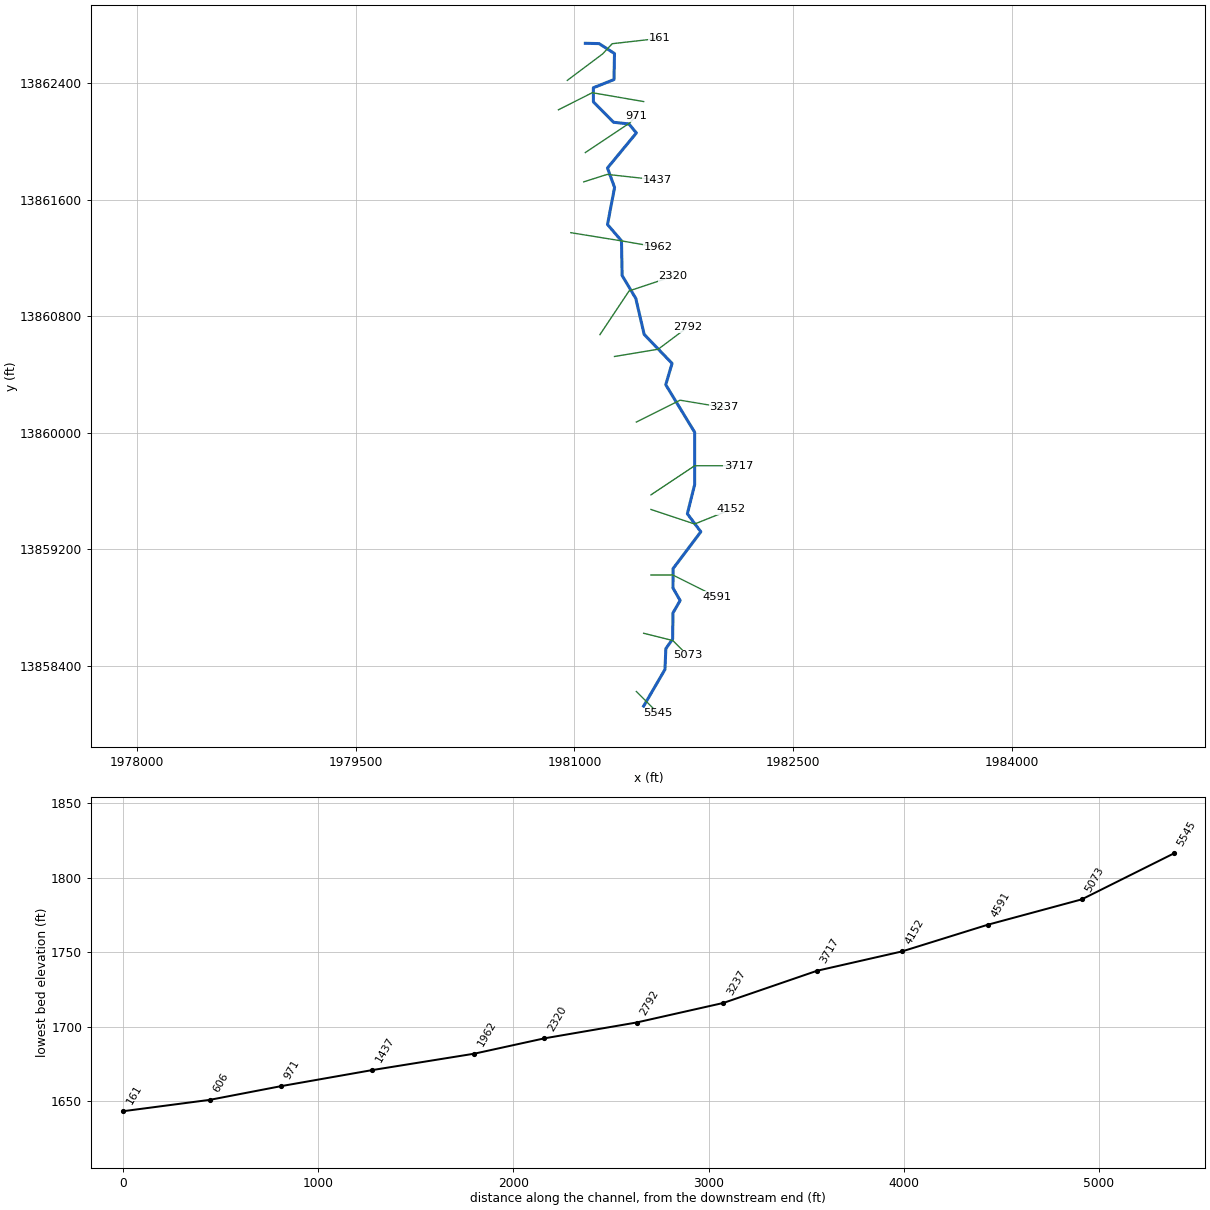
--- Stream0552.prj (project) ---

Proj Title=Stream0552 Base Level Engineering
Current Plan=p01
Default Exp/Contr=0.3,0.1
English Units
Geom File=g01
Flow File=f01
Plan File=p01
BEGIN DESCRIPTION:
Stream0552
END DESCRIPTION:

--- Stream0552.p01 (plan) ---

Plan Title=Multiple Run
Short Identifier=Multiple
Geom File=g01
Flow File=f01
Subcritical Flow
K Sum by GR= 0
Std Step Tol= 0.01
Critical Tol= 0.01
Num of Std Step Trials= 20
Max Error Tol= 0.3
Flow Tol Ratio= 0.001
Split Flow NTrial= 30
Split Flow Tol= 0.02
Split Flow Ratio= 0.02
Log Output Level= 0
Friction Slope Method= 1
Unsteady Friction Slope Method= 2
Unsteady Bridges Friction Slope Method= 1
Parabolic Critical Depth
Global Vel Dist=  1 , 1 , 1
Global Log Level= 0
CheckData=True
Encroach Param= -1, 0, 0, 0
BEGIN DESCRIPTION:
Multiple Run
END DESCRIPTION:

--- Stream0552.f01 (steady flow) ---

Flow Title=Multiple
Number of Profiles=7
Profile Names=10-year,25-year,50-year,1pct_min,100-year,1pct_plu,500-year
River Rch & RM= Stream0552,Reach-1,5545
     168     253     327     207     412     823     643
River Rch & RM= Stream0552,Reach-1,4591
     740    1245    1723    1160    2314    4617    4122
Boundary for River Rch & Prof#=Stream0552,Reach-1,1
Up Type=0
Dn Type=3
Dn Slope=0.005
Boundary for River Rch & Prof#=Stream0552,Reach-1,2
Up Type=0
Dn Type=3
Dn Slope=0.005
Boundary for River Rch & Prof#=Stream0552,Reach-1,3
Up Type=0
Dn Type=3
Dn Slope=0.005
Boundary for River Rch & Prof#=Stream0552,Reach-1,4
Up Type=0
Dn Type=3
Dn Slope=0.005
Boundary for River Rch & Prof#=Stream0552,Reach-1,5
Up Type=0
Dn Type=3
Dn Slope=0.005
Boundary for River Rch & Prof#=Stream0552,Reach-1,6
Up Type=0
Dn Type=3
Dn Slope=0.005
Boundary for River Rch & Prof#=Stream0552,Reach-1,7
Up Type=0
Dn Type=3
Dn Slope=0.005

--- Stream0552.g01 (geometry) ---

Geom Title=Existing Conditions

River Reach=Stream0552,Reach-1
Reach XY= 30
      1981475.00     13858125.00      1981621.24     13858376.56
      1981627.27     13858519.06      1981673.78     13858585.51
      1981676.24     13858764.50      1981725.40     13858850.00
      1981676.23     13858935.50      1981677.05     13859069.14
      1981867.39     13859321.67      1981774.95     13859444.99
      1981824.93     13859645.03      1981824.94     13860004.97
      1981626.63     13860331.04      1981669.91     13860477.30
      1981478.61     13860676.50      1981421.17     13860923.42
      1981327.24     13861080.93      1981322.93     13861319.14
      1981226.97     13861430.89      1981275.50     13861685.17
      1981226.79     13861818.91      1981425.17     13862059.78
      1981373.78     13862121.47      1981268.83     13862132.86
      1981130.37     13862272.64      1981129.96     13862369.89
      1981271.56     13862426.22      1981274.96     13862604.82
      1981169.17     13862672.94      1981075.00     13862675.00

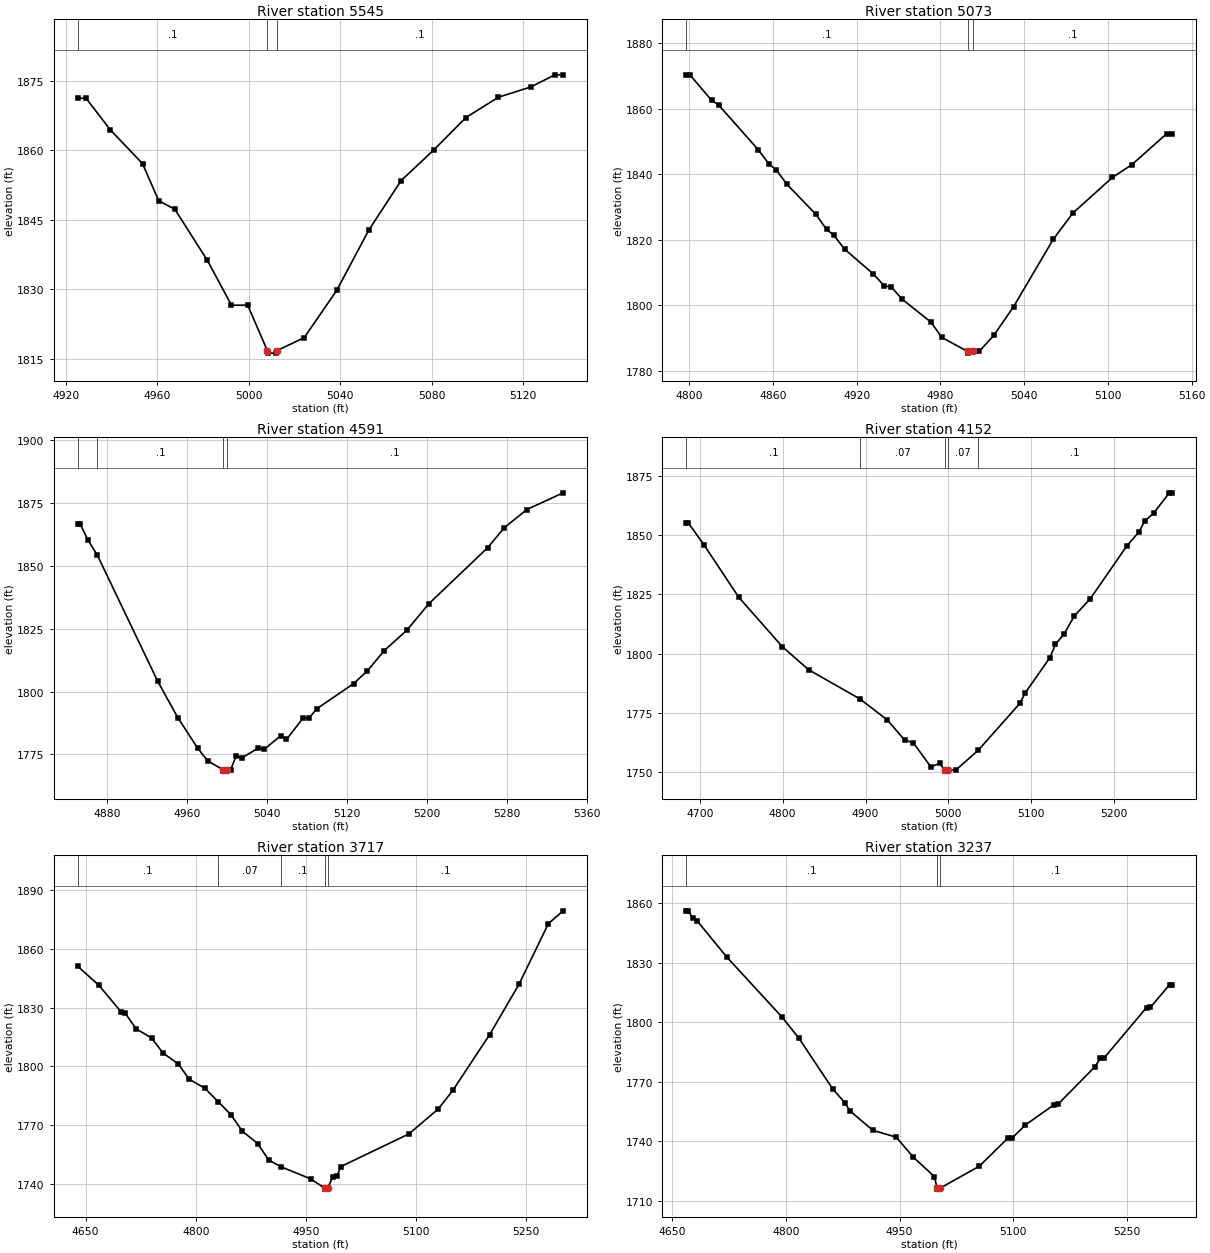
Type RM Length L Ch R = 1,5545,472,472,472
BEGIN DESCRIPTION:
Stream0552 12.0
END DESCRIPTION:
XS GIS Cut Line= 3
      1981424.99     13858225.01      1981475.00     13858175.00
      1981575.03     13858074.97
#Sta/Elev= 23
  4925.3 1871.22  4928.9 1871.22  4939.5 1864.41  4953.6 1857.12  4960.7 1849.11
  4967.7 1847.30  4981.9 1836.32  4992.5 1826.61  4999.6 1826.61  5008.2 1816.78
  5008.4 1816.28  5011.9 1816.28  5012.2 1816.78  5024.3 1819.62  5038.5 1829.78
  5052.6 1842.85  5066.7 1853.48  5080.9 1860.04  5095.0 1867.05  5109.2 1871.43
  5123.3 1873.63  5133.9 1876.26  5137.5 1876.26
#Mann=3,-1,0
  4925.3     0.1       0  5008.2    0.05       0  5012.2     0.1       0
Bank Sta=5008.2,5012.2
Exp/Cntr=0.3,0.1

Type RM Length L Ch R = 1,5073,482,482,482
BEGIN DESCRIPTION:
Stream0552 11.0
END DESCRIPTION:
XS GIS Cut Line= 3
      1981474.97     13858625.01      1981675.00     13858575.00
      1981775.00     13858475.00
#Sta/Elev= 30
  4798.0 1870.36  4800.6 1870.36  4816.1 1862.60  4821.2 1861.15  4849.6 1847.48
  4857.3 1843.10  4862.5 1841.32  4870.2 1836.90  4890.8 1827.79  4898.5 1823.18
  4903.7 1821.41  4911.4 1817.14  4932.0 1809.56  4939.8 1805.96  4944.9 1805.60
  4952.6 1801.89  4973.3 1794.85  4981.0 1790.21  4999.6 1785.91  4999.9 1785.41
  5003.6 1785.91  5007.7 1785.91  5018.3 1790.82  5032.5 1799.63  5060.8 1820.11
  5074.9 1828.15  5103.2 1839.03  5117.3 1842.98  5142.1 1852.39  5145.6 1852.39
#Mann=3,-1,0
  4798.0     0.1       0  4999.6    0.05       0  5003.6     0.1       0
Bank Sta=4999.6,5003.6
Exp/Cntr=0.3,0.1

Type RM Length L Ch R = 1,4591,439,439,439
BEGIN DESCRIPTION:
Stream0552 10.0
END DESCRIPTION:
XS GIS Cut Line= 3
      1981525.02     13859025.00      1981675.00     13859025.00
      1981975.00     13858875.00
#Sta/Elev= 30
  4850.5 1866.54  4853.0 1866.54  4860.5 1860.35  4870.0 1854.27  4930.5 1804.01
  4950.5 1789.65  4970.5 1777.39  4980.5 1772.41  4996.0 1768.85  4996.2 1768.35
  5000.0 1768.85  5003.3 1768.85  5008.9 1774.35  5014.5 1773.62  5031.2 1777.54
  5036.8 1776.99  5053.6 1782.46  5059.2 1780.93  5076.0 1789.54  5081.5 1789.34
  5089.9 1793.25  5126.3 1803.13  5140.2 1808.23  5157.0 1816.29  5179.4 1824.29
  5201.7 1834.95  5260.4 1857.19  5277.2 1865.18  5299.6 1872.37  5335.9 1879.02
#Mann=4,-1,0
  4850.5    0.07       0  4870.0     0.1       0  4996.0    0.05       0
  5000.0     0.1       0
Bank Sta=4996,5000
Exp/Cntr=0.3,0.1

Type RM Length L Ch R = 1,4152,435,435,435
BEGIN DESCRIPTION:
Stream0552 9.0
END DESCRIPTION:
XS GIS Cut Line= 3
      1981525.02     13859474.99      1981825.00     13859375.00
      1982075.04     13859475.01
#Sta/Elev= 30
  4683.7 1855.09  4686.3 1855.09  4704.8 1846.04  4746.9 1823.85  4799.6 1802.93
  4831.2 1793.24  4893.6 1780.80  4926.1 1772.08  4947.2 1763.56  4957.7 1762.36
  4978.8 1752.25  4989.4 1753.69  4995.3 1750.94  4995.5 1750.44  4999.3 1750.94
  5009.3 1751.01  5036.1 1759.28  5086.1 1778.99  5092.8 1783.52  5122.4 1798.31
  5129.1 1803.89  5139.9 1808.49  5152.0 1815.97  5170.9 1823.02  5215.3 1845.48
  5230.1 1851.45  5236.8 1855.93  5247.6 1859.29  5266.5 1867.84  5269.2 1867.84
#Mann=5,-1,0
  4683.7     0.1       0  4893.6    0.07       0  4995.3    0.05       0
  4999.3    0.07       0  5036.1     0.1       0
Bank Sta=4995.3,4999.3
Exp/Cntr=0.3,0.1

Type RM Length L Ch R = 1,3717,480,480,480
BEGIN DESCRIPTION:
Stream0552 8.0
END DESCRIPTION:
XS GIS Cut Line= 3
      1981524.99     13859574.99      1981825.00     13859775.00
      1982125.03     13859775.00
#Sta/Elev= 30
  4639.4 1851.00  4668.0 1841.40  4698.0 1827.96  4704.0 1827.04  4719.0 1819.09
  4740.1 1814.46  4755.1 1806.91  4776.1 1801.30  4791.1 1793.45  4812.2 1788.93
  4830.7 1781.96  4848.2 1775.23  4863.3 1767.00  4884.3 1760.67  4899.3 1752.26
  4916.5 1748.78  4956.4 1742.68  4975.4 1737.96  4975.7 1737.46  4979.4 1737.96
  4986.4 1743.65  4992.5 1744.21  4997.0 1748.88  5090.0 1765.57  5130.0 1778.28
  5150.0 1787.84  5200.0 1816.19  5240.0 1841.90  5280.0 1872.80  5300.0 1879.31
#Mann=5,-1,0
  4639.4     0.1       0  4830.7    0.07       0  4916.5     0.1       0
  4975.4    0.05       0  4979.4     0.1       0
Bank Sta=4975.4,4979.4
Exp/Cntr=0.3,0.1

Type RM Length L Ch R = 1,3237,445,445,445
BEGIN DESCRIPTION:
Stream0552 7.0
END DESCRIPTION:
XS GIS Cut Line= 3
      1981424.99     13860075.00      1981725.00     13860225.00
      1982025.04     13860174.99
#Sta/Elev= 30
  4668.9 1856.28  4671.7 1856.28  4677.3 1852.51  4682.9 1851.37  4722.0 1833.08
  4794.7 1802.83  4817.0 1792.21  4861.8 1766.45  4878.5 1759.19  4884.1 1755.48
  4914.9 1745.50  4945.6 1742.06  4968.0 1732.03  4995.9 1722.17  4999.5 1716.34
  4999.8 1715.84  5003.5 1716.34  5055.0 1727.37  5093.0 1741.64  5098.1 1741.52
  5115.8 1748.19  5153.9 1758.53  5158.9 1758.69  5207.1 1777.45  5214.7 1781.78
  5219.8 1782.11  5275.5 1807.47  5280.6 1807.53  5305.9 1819.01  5308.5 1819.01
#Mann=3,-1,0
  4668.9     0.1       0  4999.5    0.05       0  5003.5     0.1       0
Bank Sta=4999.5,5003.5
Exp/Cntr=0.3,0.1

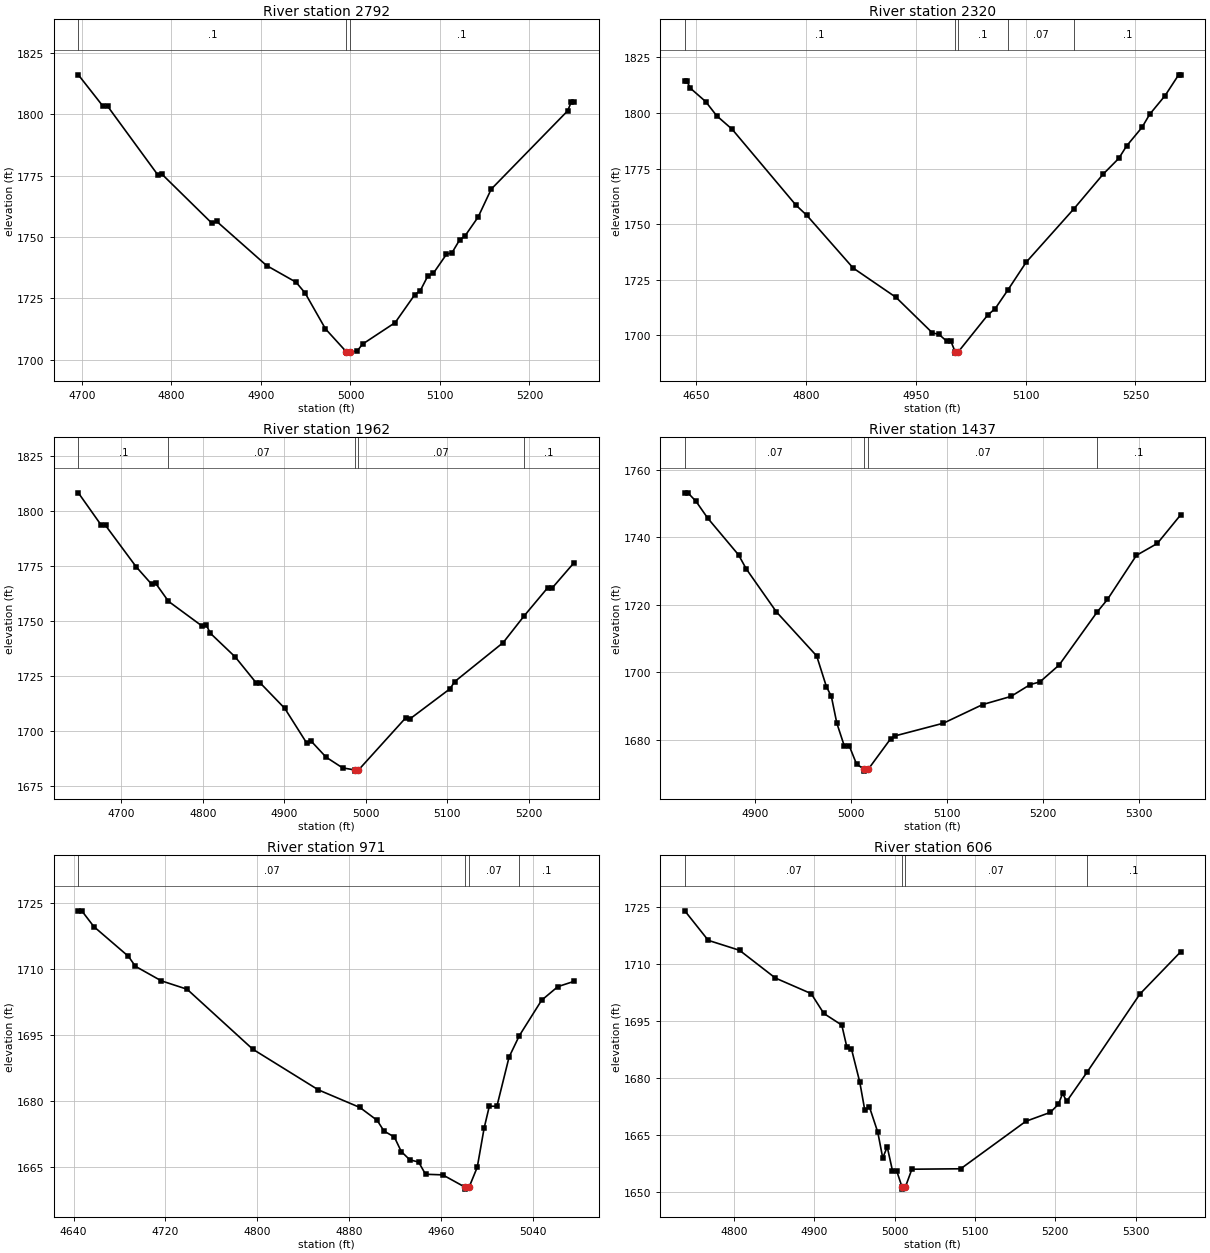
Type RM Length L Ch R = 1,2792,472,472,472
BEGIN DESCRIPTION:
Stream0552 6.0
END DESCRIPTION:
XS GIS Cut Line= 3
      1981275.04     13860525.01      1981575.00     13860575.00
      1981775.00     13860725.00
#Sta/Elev= 30
  4695.9 1816.05  4723.7 1803.15  4728.8 1803.17  4784.6 1775.36  4789.6 1775.49
  4845.4 1755.52  4850.5 1756.36  4906.2 1738.39  4939.2 1731.59  4949.3 1727.19
  4972.1 1712.57  4995.5 1703.20  4995.7 1702.70  4999.5 1703.20  5007.3 1703.47
  5013.5 1706.36  5050.0 1715.14  5071.9 1726.51  5078.1 1728.19  5086.5 1734.14
  5092.7 1735.25  5107.3 1742.96  5113.5 1743.60  5121.9 1748.74  5128.1 1750.48
  5142.7 1758.13  5157.3 1769.48  5242.7 1801.37  5246.9 1805.11  5250.0 1805.11
#Mann=3,-1,0
  4695.9     0.1       0  4995.5    0.05       0  4999.5     0.1       0
Bank Sta=4995.5,4999.5
Exp/Cntr=0.3,0.1

Type RM Length L Ch R = 1,2320,358,358,358
BEGIN DESCRIPTION:
Stream0552 5.0
END DESCRIPTION:
XS GIS Cut Line= 3
      1981175.01     13860675.02      1981375.00     13860975.00
      1981675.03     13861075.01
#Sta/Elev= 30
  4634.9 1814.23  4637.9 1814.23  4642.4 1811.19  4663.4 1805.15  4678.4 1798.78
  4699.5 1792.72  4786.6 1758.61  4801.6 1753.96  4864.7 1730.33  4923.3 1717.12
  4972.9 1701.16  4981.9 1700.49  4992.4 1697.44  4998.1 1697.44  5004.0 1692.57
  5004.2 1692.07  5008.0 1692.57  5048.1 1709.07  5058.7 1712.13  5076.0 1720.50
  5100.8 1732.90  5166.2 1757.01  5206.3 1772.65  5227.3 1779.62  5237.9 1785.18
  5259.0 1793.56  5269.5 1799.45  5290.6 1807.88  5309.0 1817.18  5311.7 1817.18
#Mann=5,-1,0
  4634.9     0.1       0  5004.0    0.05       0  5008.0     0.1       0
  5076.0    0.07       0  5166.2     0.1       0
Bank Sta=5004,5008
Exp/Cntr=0.3,0.1

Type RM Length L Ch R = 1,1962,525,525,525
BEGIN DESCRIPTION:
Stream0552 4.0
END DESCRIPTION:
XS GIS Cut Line= 3
      1980974.99     13861375.00      1981326.58     13861318.04
      1981575.00     13861275.00
#Sta/Elev= 30
  4647.4 1808.44  4675.7 1793.60  4680.8 1793.59  4718.3 1774.80  4737.4 1766.81
  4742.4 1767.18  4758.0 1759.06  4799.0 1747.87  4804.1 1748.44  4809.5 1744.49
  4839.9 1733.74  4865.7 1721.91  4870.8 1721.81  4900.7 1710.33  4927.4 1694.66
  4932.5 1695.66  4951.3 1688.16  4971.6 1683.27  4987.1 1682.29  4987.3 1681.79
  4991.1 1682.29  5049.2 1706.11  5054.2 1705.55  5103.5 1719.29  5108.9 1722.45
  5168.6 1740.27  5194.2 1752.37  5223.3 1765.28  5228.4 1764.98  5255.7 1776.70
#Mann=5,-1,0
  4647.4     0.1       0  4758.0    0.07       0  4987.1    0.05       0
  4991.1    0.07       0  5194.2     0.1       0
Bank Sta=4987.1,4991.1
Exp/Cntr=0.3,0.1

Type RM Length L Ch R = 1,1437,466,466,466
BEGIN DESCRIPTION:
Stream0552 3.0
END DESCRIPTION:
XS GIS Cut Line= 3
      1981063.97     13861723.85      1981225.00     13861775.00
      1981570.86     13861736.98
#Sta/Elev= 30
  4826.5 1753.17  4829.7 1753.17  4838.1 1750.69  4850.3 1745.70  4882.6 1734.76
  4890.5 1730.66  4922.0 1717.90  4964.0 1704.84  4974.1 1695.77  4979.3 1692.84
  4985.0 1684.92  4992.8 1678.16  4998.0 1678.16  5005.5 1672.85  5013.6 1671.22
  5013.8 1670.72  5017.6 1671.22  5041.0 1680.28  5046.0 1681.18  5096.1 1684.92
  5137.0 1690.44  5166.5 1692.85  5186.6 1696.37  5196.7 1697.15  5216.8 1702.17
  5256.4 1717.87  5267.1 1721.57  5297.3 1734.64  5319.1 1738.17  5343.4 1746.63
#Mann=4,-1,0
  4826.5    0.07       0  5013.6    0.05       0  5017.6    0.07       0
  5256.4     0.1       0
Bank Sta=5013.6,5017.6
Exp/Cntr=0.3,0.1

Type RM Length L Ch R = 1,971,365,365,365
BEGIN DESCRIPTION:
Stream0552 2.0
END DESCRIPTION:
XS GIS Cut Line= 3
      1981075.00     13861925.00      1981375.00     13862125.00
      1981425.03     13862175.03
#Sta/Elev= 30
  4644.2 1723.21  4647.2 1723.21  4657.7 1719.62  4687.8 1712.86  4693.8 1710.61
  4716.3 1707.31  4738.8 1705.39  4795.9 1691.77  4853.0 1682.52  4889.1 1678.52
  4904.1 1675.60  4910.1 1673.16  4919.1 1671.80  4925.1 1668.50  4932.6 1666.61
  4940.2 1666.12  4946.2 1663.34  4961.2 1663.20  4980.2 1660.46  4980.5 1659.96
  4984.2 1660.46  4991.2 1664.93  4997.2 1673.84  5001.7 1678.80  5008.3 1678.80
  5018.9 1689.98  5027.8 1694.83  5047.2 1702.89  5061.3 1705.98  5075.5 1707.19
#Mann=4,-1,0
  4644.2    0.07       0  4980.2    0.05       0  4984.2    0.07       0
  5027.8     0.1       0
Bank Sta=4980.2,4984.2
Exp/Cntr=0.3,0.1

Type RM Length L Ch R = 1,606,445,445,445
BEGIN DESCRIPTION:
Stream0552 1.0
END DESCRIPTION:
XS GIS Cut Line= 3
      1980890.37     13862218.65      1981122.58     13862335.84
      1981474.96     13862275.01
#Sta/Elev= 30
  4738.5 1723.95  4767.7 1716.19  4806.7 1713.57  4851.3 1706.28  4895.9 1702.18
  4911.7 1696.96  4934.1 1693.89  4940.5 1688.02  4946.1 1687.65  4956.5 1678.89
  4962.8 1671.44  4968.4 1672.44  4978.9 1665.74  4985.1 1658.96  4990.7 1661.87
  4997.2 1655.62  5002.4 1655.62  5009.2 1651.26  5009.5 1650.76  5013.2 1651.26
  5021.4 1656.00  5082.2 1656.11  5163.4 1668.60  5193.9 1670.95  5204.0 1673.10
  5209.2 1675.92  5214.3 1673.84  5239.5 1681.47  5305.5 1702.07  5356.2 1713.15
#Mann=4,-1,0
  4738.5    0.07       0  5009.2    0.05       0  5013.2    0.07       0
  5239.5     0.1       0
Bank Sta=5009.2,5013.2
Exp/Cntr=0.3,0.1

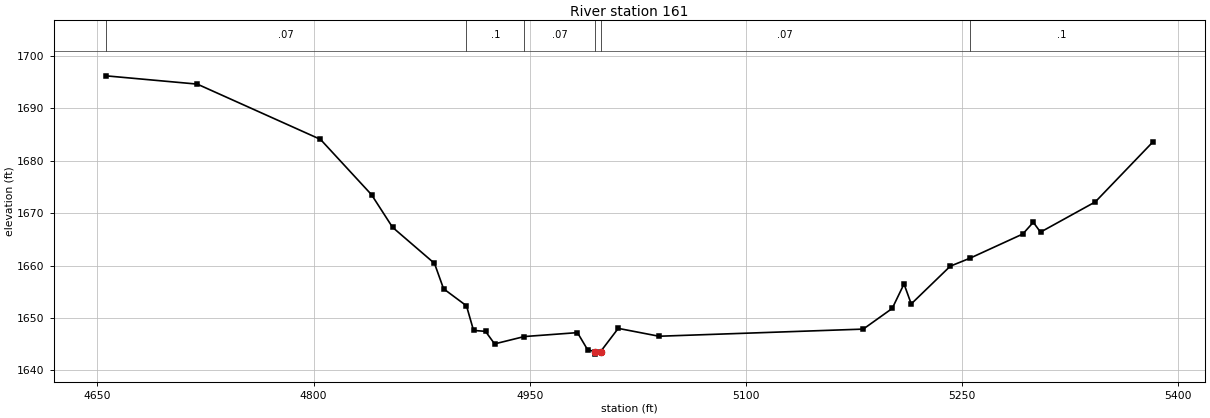
Type RM Length L Ch R = 1,161,0,0,0
BEGIN DESCRIPTION:
Stream0552 0.0
END DESCRIPTION:
XS GIS Cut Line= 4
      1980951.16     13862420.49      1981194.20     13862602.77
      1981259.30     13862672.21      1981584.84     13862709.10
#Sta/Elev= 30
  4655.9 1696.17  4719.3 1694.59  4804.8 1684.05  4840.2 1673.51  4854.8 1667.29
  4883.9 1660.41  4890.2 1655.57  4906.1 1652.32  4911.0 1647.63  4919.3 1647.45
  4925.6 1645.06  4946.2 1646.46  4983.1 1647.21  4990.2 1643.92  4995.2 1643.61
  4995.5 1643.11  4999.2 1643.61  5011.4 1648.02  5039.7 1646.52  5181.4 1647.88
  5201.5 1651.82  5209.7 1656.49  5214.7 1652.68  5241.8 1659.88  5255.4 1661.39
  5292.1 1666.01  5299.4 1668.25  5304.4 1666.37  5342.4 1672.13  5382.5 1683.60
#Mann=6,-1,0
  4655.9    0.07       0  4906.1     0.1       0  4946.2    0.07       0
  4995.2    0.05       0  4999.2    0.07       0  5255.4     0.1       0
Bank Sta=4995.2,4999.2
Exp/Cntr=0.3,0.1

Chan Stop Cuts=-1