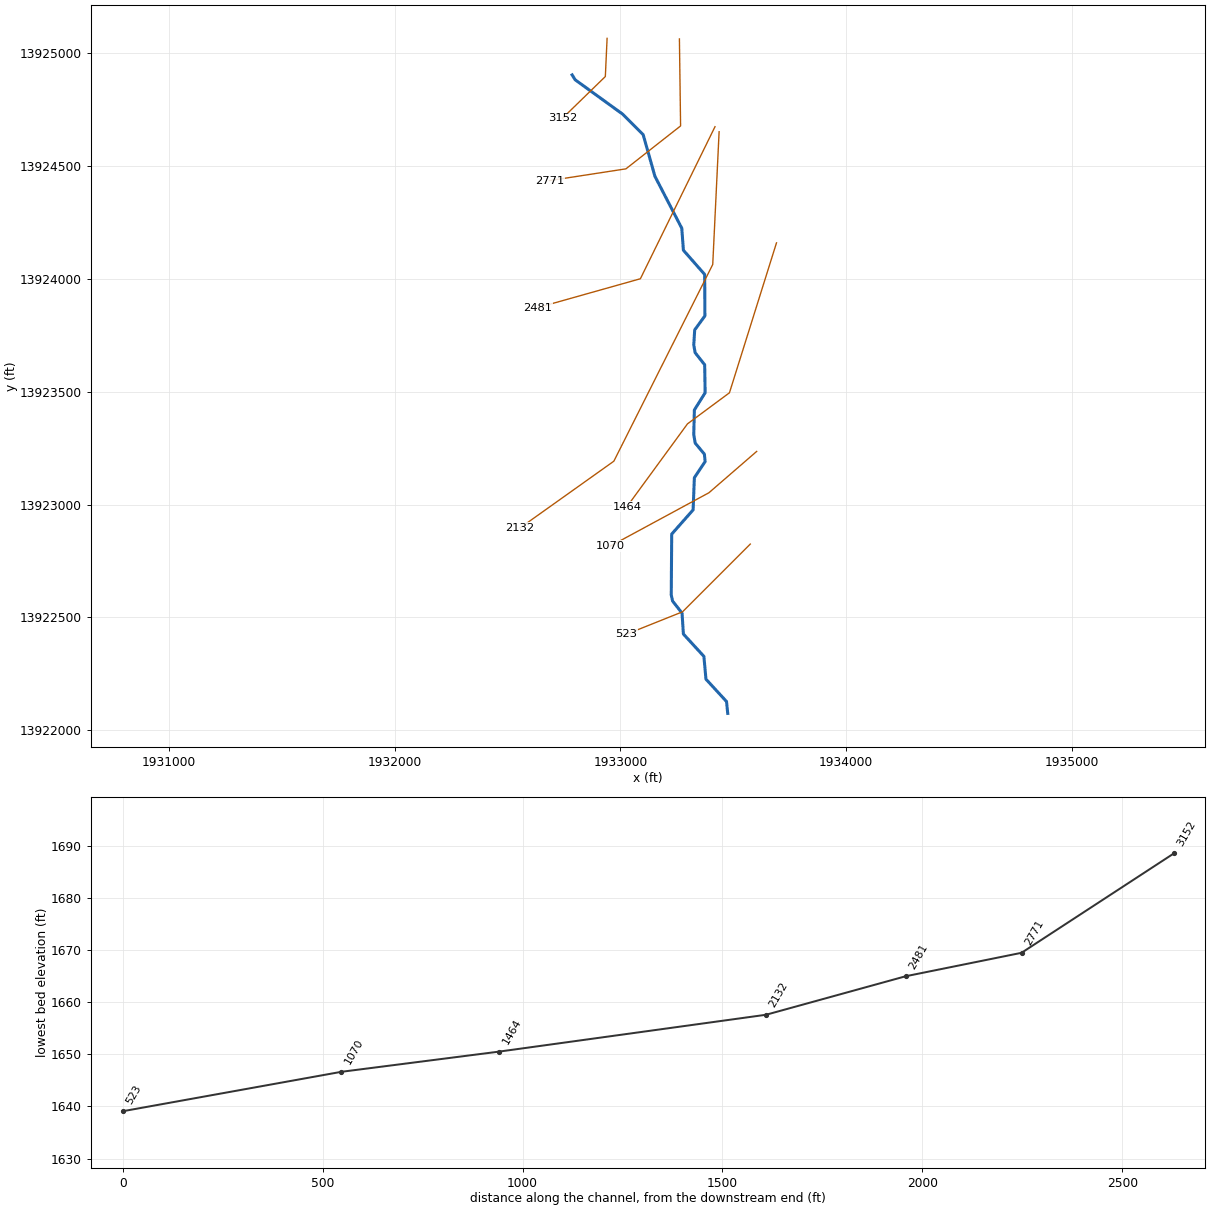
--- Stream0553.prj (project) ---

Proj Title=Stream0553 Base Level Engineering
Current Plan=p01
Default Exp/Contr=0.3,0.1
English Units
Geom File=g01
Flow File=f01
Plan File=p01
Y Axis Title=Elevation
X Axis Title(PF)=Main Channel Distance
X Axis Title(XS)=Station
BEGIN DESCRIPTION:
Stream0553
END DESCRIPTION:
DSS Export Rating Curves= 0
DSS Export Rating Curve Sorted= 0
DSS Export Volume Flow Curves= 0
DXF OffsetX= 0
DXF OffsetY= 0
DXF ScaleX= 1
DXF ScaleY= 10

--- Stream0553.p01 (plan) ---

Plan Title=Multiple Run
Short Identifier=Multiple
Geom File=g01
Flow File=f01
Subcritical Flow
K Sum by GR= 0
Std Step Tol= 0.01
Critical Tol= 0.01
Num of Std Step Trials= 20
Max Error Tol= 0.3
Flow Tol Ratio= 0.001
Split Flow NTrial= 30
Split Flow Tol= 0.02
Split Flow Ratio= 0.02
Log Output Level= 0
Friction Slope Method= 1
Unsteady Friction Slope Method= 2
Unsteady Bridges Friction Slope Method= 1
Parabolic Critical Depth
Global Vel Dist=  1 , 1 , 1
Global Log Level= 0
CheckData=True
Encroach Param= -1, 0, 0, 0
BEGIN DESCRIPTION:
Multiple Run
END DESCRIPTION:

--- Stream0553.f01 (steady flow) ---

Flow Title=Multiple
Number of Profiles=7
Profile Names=10-year,25-year,50-year,1pct_min,100-year,1pct_plu,500-year
River Rch & RM= Stream0553,Reach-1,3152
     340     533     703     451     899    1794    1445
Boundary for River Rch & Prof#=Stream0553,Reach-1,1
Up Type=0
Dn Type=3
Dn Slope=0.005
Boundary for River Rch & Prof#=Stream0553,Reach-1,2
Up Type=0
Dn Type=3
Dn Slope=0.005
Boundary for River Rch & Prof#=Stream0553,Reach-1,3
Up Type=0
Dn Type=3
Dn Slope=0.005
Boundary for River Rch & Prof#=Stream0553,Reach-1,4
Up Type=0
Dn Type=3
Dn Slope=0.005
Boundary for River Rch & Prof#=Stream0553,Reach-1,5
Up Type=0
Dn Type=3
Dn Slope=0.005
Boundary for River Rch & Prof#=Stream0553,Reach-1,6
Up Type=0
Dn Type=3
Dn Slope=0.005
Boundary for River Rch & Prof#=Stream0553,Reach-1,7
Up Type=0
Dn Type=3
Dn Slope=0.005

--- Stream0553.g01 (geometry) ---

Geom Title=Existing Conditions
Program Version=4.10

River Reach=Stream0553      ,Reach-1
Reach XY= 30
       1932785.8      13924903.1      1932799.31     13924881.34
      1933009.32     13924729.49      1933100.47     13924638.34
      1933152.55     13924453.88      1933271.54      13924223.7
      1933278.62      13924126.5      1933372.94     13924019.14
      1933373.88     13923835.46      1933328.65     13923773.49
      1933324.59     13923706.08      1933330.74     13923672.66
      1933372.89     13923619.12      1933374.95     13923495.04
      1933327.25     13923419.06      1933324.54     13923309.84
      1933330.78     13923272.65      1933371.63     13923223.26
      1933374.91     13923190.39      1933327.29     13923119.07
       1933321.7     13922976.37      1933226.89     13922869.22
       1933224.8     13922599.92      1933230.74     13922572.66
      1933272.64     13922519.02      1933278.62      13922426.5
      1933369.46     13922327.42      1933378.61      13922226.5
      1933469.67     13922127.51        1933475.       13922075.

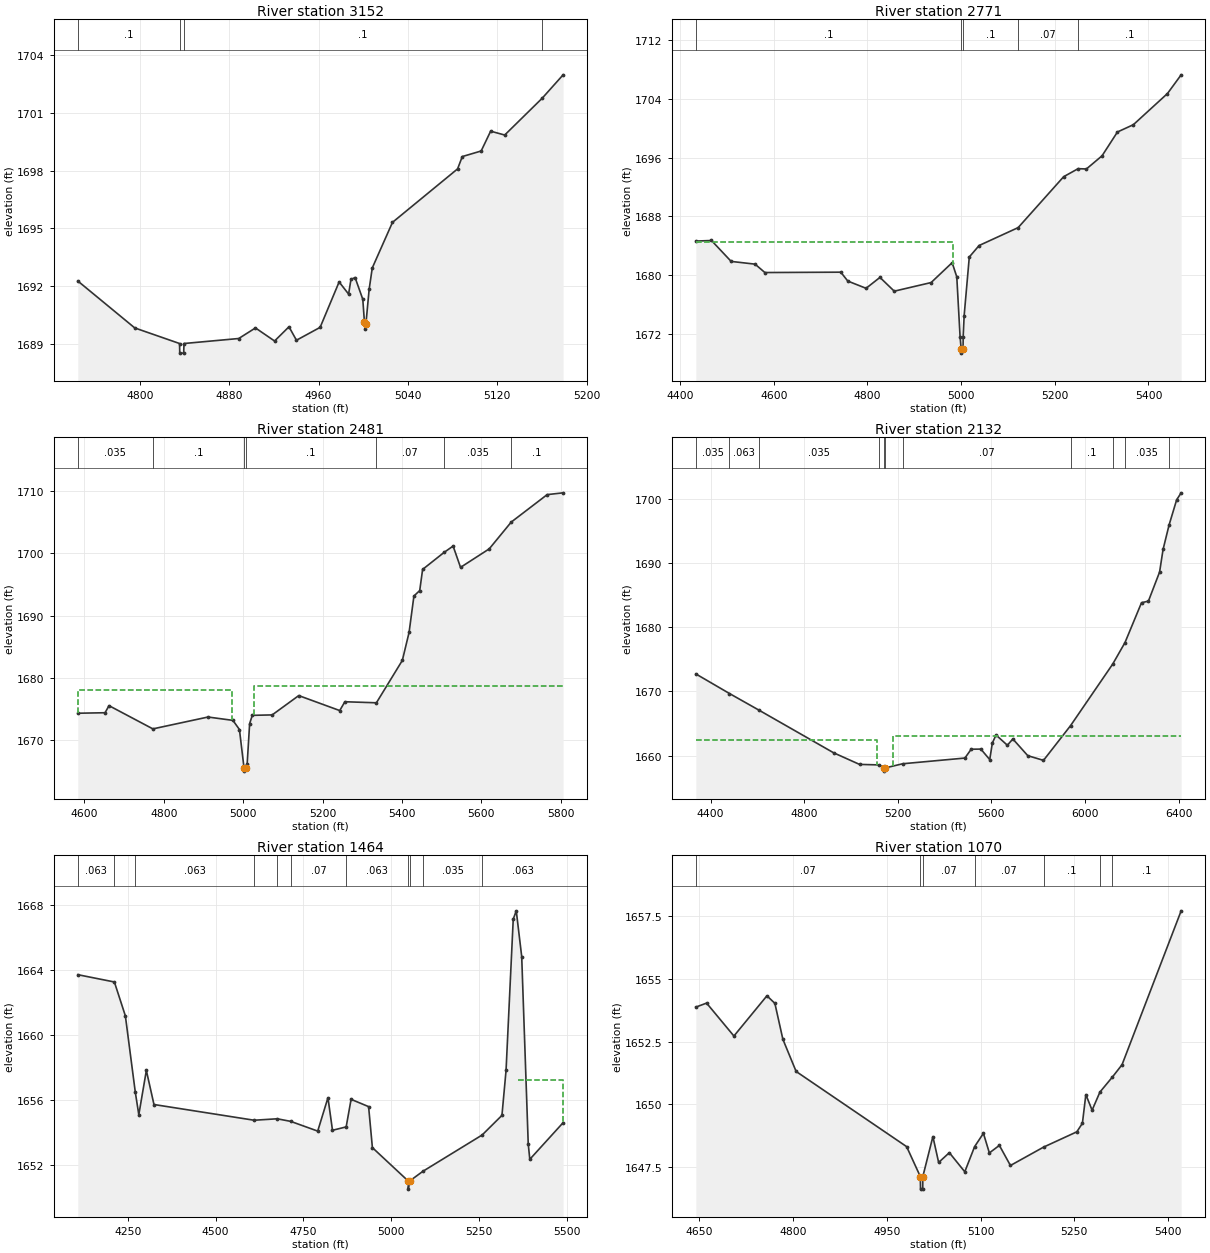
Type RM Length L Ch R = 1 ,3152    ,381,381,381
BEGIN DESCRIPTION:
Stream0553 7.0
END DESCRIPTION:
XS GIS Cut Line= 3
      1932940.69     13925065.08      1932932.88     13924895.84
      1932742.78     13924710.95
#Sta/Elev= 30
  4744.4 1692.26  4795.4 1689.82  4835.5 1689.01  4835.7 1688.51  4839.2 1688.51
  4839.5 1689.01  4888.5 1689.27  4903.5 1689.82  4920.6 1689.14  4933.5 1689.88
  4940.2 1689.18  4961.4 1689.85  4978.4 1692.21  4986.9 1691.58    4989 1692.34
  4992.7 1692.44  4999.6 1691.31  5001.1 1690.11  5001.7 1689.76  5002.4 1690.03
  5005.3 1691.83  5008.1 1692.94  5026.2 1695.31  5084.5 1698.09  5088.7 1698.73
  5105.6 1699.02  5114.1 1700.05  5126.7 1699.85  5160.2 1701.76    5179 1702.98
#Mann= 4 ,-1 , 0
  4744.4      .1       0  4835.5     .05       0  4839.5      .1       0
  5160.2     .07       0
#Block Obstruct= 2 , 0
         4977.22 1691.86
Bank Sta=5001.1,5002.4
XS Rating Curve= 0 ,0
Exp/Cntr=0.3,0.1

Type RM Length L Ch R = 1 ,2771    ,290,290,290
BEGIN DESCRIPTION:
Stream0553 6.0
END DESCRIPTION:
XS GIS Cut Line= 4
        1933261.      13925062.5      1933266.21     13924677.09
      1933024.02     13924486.99      1932685.44      13924434.9
#Sta/Elev= 30
  4433.8 1684.66  4467.2 1684.74  4509.2  1681.9  4560.2 1681.53  4581.2 1680.39
  4743.2 1680.44  4758.2 1679.23  4797.2 1678.25  4826.8 1679.73  4857.3 1677.86
    4936 1679.03  4980.9 1681.73  4990.8  1679.8  4997.9  1671.6  5000.2 1669.95
  5000.4 1669.45  5004.2 1669.95  5004.4 1671.63  5006.5 1674.53  5017.5  1682.5
  5038.5 1684.06  5121.8 1686.49  5218.9  1693.4  5249.8 1694.49  5267.5 1694.45
  5300.9 1696.24  5333.7 1699.47  5367.7 1700.46  5440.5 1704.69  5469.7 1707.23
#Mann= 5 ,-1 , 0
  4433.8      .1       0  5000.2     .05       0  5004.2      .1       0
  5121.8     .07       0  5249.8      .1       0
#XS Ineff= 2 , 0
         4982.62 1684.55
Permanent Ineff=
       F       F
Bank Sta=5000.2,5004.2
XS Rating Curve= 0 ,0
Exp/Cntr=0.3,0.1

Type RM Length L Ch R = 1 ,2481    ,349,349,349
BEGIN DESCRIPTION:
Stream0553 5.0
END DESCRIPTION:
XS GIS Cut Line= 3
      1933418.63     13924673.66      1933088.13     13924000.16
      1932633.61     13923872.24
#Sta/Elev= 30
  4583.5 1674.27  4652.1 1674.35  4662.1 1675.49  4772.6 1671.75  4911.5 1673.66
  4974.2 1673.12  4990.6 1671.65  5002.2 1665.45  5002.4 1664.95  5006.2 1665.45
  5010.1 1666.12  5016.3 1672.59    5023 1673.93  5073.1    1674    5140 1677.11
  5243.2  1674.7  5256.2 1676.12  5335.6 1675.95  5400.9 1682.77  5417.9 1687.28
  5430.1 1693.14  5444.7 1694.02    5452 1697.42  5506.1 1700.16  5528.8 1701.18
  5547.5 1697.75  5619.8 1700.73  5675.2 1705.04  5765.7 1709.46  5805.9 1709.75
#Mann= 7 ,-1 , 0
  4583.5    .035       0  4772.6      .1       0  5002.2     .05       0
  5006.2      .1       0  5335.6     .07       0  5506.1    .035       0
  5675.2      .1       0
#XS Ineff= 2 , 0
         4970.63 1678.08 5028.17         1678.68
Permanent Ineff=
       F       F
Bank Sta=5002.2,5006.2
XS Rating Curve= 0 ,0
Exp/Cntr=0.3,0.1

Type RM Length L Ch R = 1 ,2132    ,668,668,668
BEGIN DESCRIPTION:
Stream0553 4.0
END DESCRIPTION:
XS GIS Cut Line= 4
      1933436.84      13924651.4      1933408.63     13924063.25
      1932970.68      13923192.1      1932555.28     13922896.51
#Sta/Elev= 30
  4337.1 1672.74  4480.9 1669.68  4605.2 1667.12  4925.9 1660.43  5036.5 1658.62
  5119.7 1658.54  5142.4 1658.07  5142.6 1657.57  5146.4 1658.07  5220.9 1658.72
  5486.8 1659.61  5513.7 1660.99  5554.9 1661.01  5592.9 1659.37  5604.1 1661.96
  5619.7 1663.21  5668.2 1661.61  5691.7 1662.59  5755.5 1659.98  5822.6 1659.25
  5938.1 1664.66  6118.6 1674.29  6170.8 1677.63  6241.4 1683.85  6270.9  1684.1
  6318.7 1688.64  6333.5 1692.16  6359.5 1696.02  6391.7 1699.92  6410.8    1701
#Mann= 11 ,-1 , 0
  4337.1    .035       0  4480.9    .063       0  4605.2    .035       0
  5119.7     .07       0  5142.4     .05       0  5146.4     .07       0
  5220.9     .07       0  5938.1      .1       0  6118.6     .07       0
  6170.8    .035       0  6359.5     .07       0
#XS Ineff= 2 , 0
         5111.39 1662.46 5178.82         1663.05
Permanent Ineff=
       F       F
Bank Sta=5142.4,5146.4
XS Rating Curve= 0 ,0
Exp/Cntr=0.3,0.1

Type RM Length L Ch R = 1 ,1464    ,394,394,394
BEGIN DESCRIPTION:
Stream0553 3.0
END DESCRIPTION:
XS GIS Cut Line= 4
      1933691.01     13924159.19      1933482.67      13923495.1
      1933296.73      13923357.4        1933028.     13922989.84
#Sta/Elev= 30
  4107.2 1663.73  4211.4 1663.28  4242.7 1661.19    4271 1656.48    4281 1655.09
  4302.5 1657.82  4324.2 1655.72  4609.7 1654.75  4675.3 1654.84  4713.8 1654.68
  4790.7 1654.08  4819.9 1656.14  4832.8 1654.13  4871.8 1654.34  4885.8 1656.04
  4935.7 1655.59  4946.5 1653.06  5048.6    1651  5048.8  1650.5  5052.6    1651
  5090.4  1651.6  5259.2 1653.84  5315.6 1655.05  5327.3 1657.82  5347.8 1667.16
  5356.4 1667.67  5371.9 1664.85  5390.5 1653.29    5395 1652.34  5489.9  1654.6
#Mann= 11 ,-1 , 0
  4107.2    .063       0  4211.4     .12       0    4271    .063       0
  4609.7    .035       0  4675.3    .063       0  4713.8     .07       0
  4871.8    .063       0  5048.6     .05       0  5052.6    .063       0
  5090.4    .035       0  5259.2    .063       0
#XS Ineff= 2 , 0
                         5360.24         1657.26
Permanent Ineff=
       F       F
Bank Sta=5048.6,5052.6
XS Rating Curve= 0 ,0
Exp/Cntr=0.3,0.1

Type RM Length L Ch R = 1 ,1070    ,547,547,547
BEGIN DESCRIPTION:
Stream0553 2.0
END DESCRIPTION:
XS GIS Cut Line= 3
      1933603.32      13923235.4      1933391.84     13923052.34
      1932955.22     13922816.16
#Sta/Elev= 30
  4644.7 1653.87  4661.9 1654.03  4705.6 1652.72  4758.4 1654.32  4771.1 1654.02
  4783.9 1652.59  4805.1 1651.31  4981.8 1648.32  5003.7 1647.13    5004 1646.63
  5007.5 1646.63  5007.7 1647.13  5023.8 1648.72    5033 1647.69  5050.1 1648.08
  5074.8 1647.32  5090.5 1648.32  5104.6 1648.85  5114.1 1648.07  5130.1 1648.37
  5147.8 1647.57  5200.7  1648.3    5254 1648.91  5262.9 1649.25  5268.4 1650.39
  5278.4 1649.77  5290.9 1650.49  5310.9 1651.09  5326.3 1651.58  5420.8  1657.7
#Mann= 7 ,-1 , 0
  4644.7     .07       0  5003.7     .05       0  5007.7     .07       0
  5090.5     .07       0  5200.7      .1       0  5290.9     .07       0
  5310.9      .1       0
Bank Sta=5003.7,5007.7
XS Rating Curve= 0 ,0
Exp/Cntr=0.3,0.1

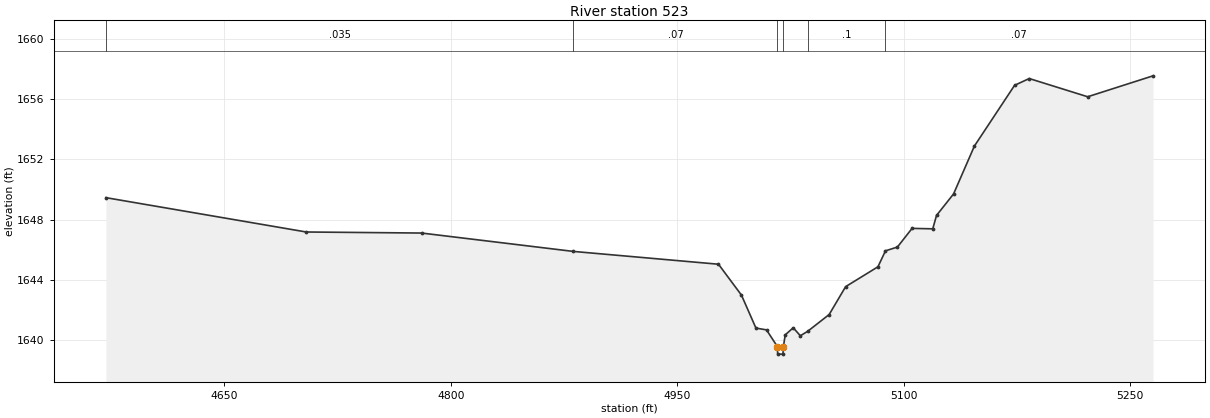
Type RM Length L Ch R = 1 ,523     ,0,0,0
BEGIN DESCRIPTION:
Stream0553 1.0
END DESCRIPTION:
XS GIS Cut Line= 3
      1933574.97     13922824.97        1933275.       13922525.
      1933024.98     13922424.99
#Sta/Elev= 30
  4571.6 1649.46  4704.3 1647.18  4780.7 1647.11  4881.2 1645.89  4977.3 1645.04
  4992.5 1642.99  5002.1  1640.8  5009.1 1640.68  5016.3 1639.57  5016.5 1639.07
    5020 1639.07  5020.3 1639.57  5021.5 1640.35  5026.8 1640.82  5031.5 1640.29
  5036.3 1640.58  5050.6  1641.7  5061.5 1643.55  5082.9 1644.87  5087.9 1645.93
  5095.8 1646.18  5105.5 1647.42  5119.2 1647.39  5121.7 1648.28    5133 1649.71
  5146.8 1652.89  5173.4 1656.92  5183.1 1657.37  5221.8 1656.16  5265.1 1657.55
#Mann= 6 ,-1 , 0
  4571.6    .035       0  4881.2     .07       0  5016.3     .05       0
  5020.3     .07       0  5036.3      .1       0  5087.9     .07       0
Bank Sta=5016.3,5020.3
XS Rating Curve= 0 ,0
Exp/Cntr=0.3,0.1

Chan Stop Cuts=-1
Use User Specified Reach Order=0
Composite Channel Slope=5