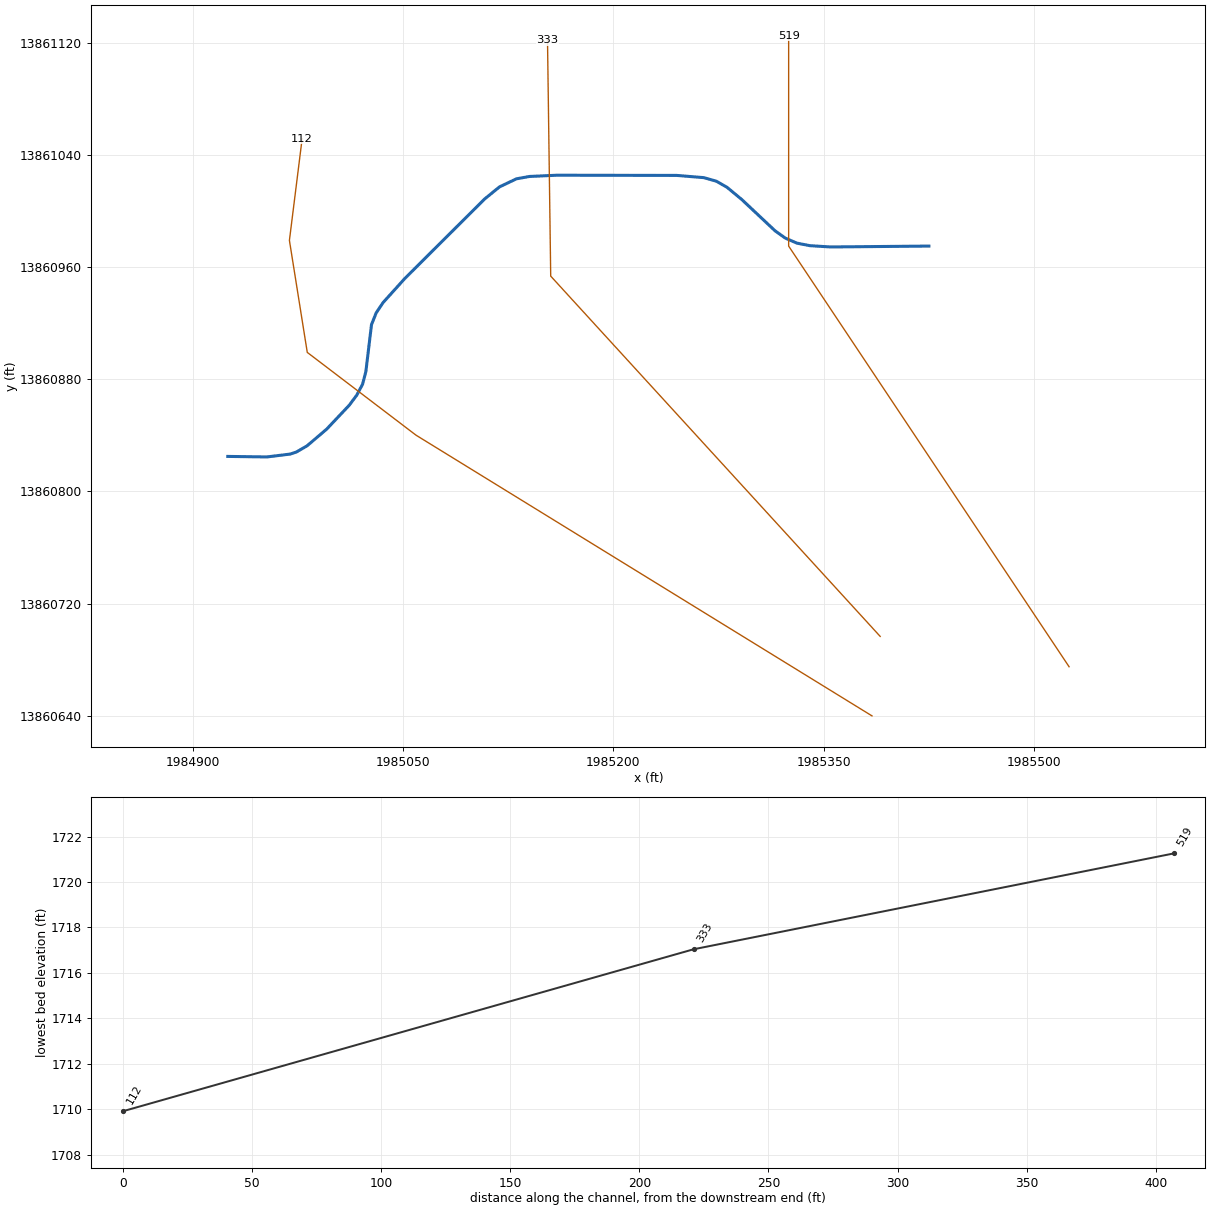
--- Stream0554.prj (project) ---

Proj Title=Stream0554 Base Level Engineering
Current Plan=p01
Default Exp/Contr=0.3,0.1
English Units
Geom File=g01
Flow File=f01
Plan File=p01
BEGIN DESCRIPTION:
Stream0554
END DESCRIPTION:

--- Stream0554.p01 (plan) ---

Plan Title=Multiple Run
Short Identifier=Multiple
Geom File=g01
Flow File=f01
Subcritical Flow
K Sum by GR= 0
Std Step Tol= 0.01
Critical Tol= 0.01
Num of Std Step Trials= 20
Max Error Tol= 0.3
Flow Tol Ratio= 0.001
Split Flow NTrial= 30
Split Flow Tol= 0.02
Split Flow Ratio= 0.02
Log Output Level= 0
Friction Slope Method= 1
Unsteady Friction Slope Method= 2
Unsteady Bridges Friction Slope Method= 1
Parabolic Critical Depth
Global Vel Dist=  1 , 1 , 1
Global Log Level= 0
CheckData=True
Encroach Param= -1, 0, 0, 0
BEGIN DESCRIPTION:
Multiple Run
END DESCRIPTION:

--- Stream0554.f01 (steady flow) ---

Flow Title=Multiple
Number of Profiles=7
Profile Names=10-year,25-year,50-year,1pct_min,100-year,1pct_plu,500-year
River Rch & RM= Stream0554,Reach-1,519
     633    1051    1443     963    1922    3834    3367
Boundary for River Rch & Prof#=Stream0554,Reach-1,1
Up Type=0
Dn Type=3
Dn Slope=0.005
Boundary for River Rch & Prof#=Stream0554,Reach-1,2
Up Type=0
Dn Type=3
Dn Slope=0.005
Boundary for River Rch & Prof#=Stream0554,Reach-1,3
Up Type=0
Dn Type=3
Dn Slope=0.005
Boundary for River Rch & Prof#=Stream0554,Reach-1,4
Up Type=0
Dn Type=3
Dn Slope=0.005
Boundary for River Rch & Prof#=Stream0554,Reach-1,5
Up Type=0
Dn Type=3
Dn Slope=0.005
Boundary for River Rch & Prof#=Stream0554,Reach-1,6
Up Type=0
Dn Type=3
Dn Slope=0.005
Boundary for River Rch & Prof#=Stream0554,Reach-1,7
Up Type=0
Dn Type=3
Dn Slope=0.005

--- Stream0554.g01 (geometry) ---

Geom Title=Existing Conditions

River Reach=Stream0554,Reach-1
Reach XY= 30
      1985425.00     13860975.00      1985354.74     13860974.37
      1985340.12     13860975.29      1985330.87     13860977.10
      1985322.64     13860980.68      1985315.35     13860985.86
      1985291.60     13861008.17      1985281.07     13861016.91
      1985273.44     13861021.26      1985264.50     13861023.81
      1985245.14     13861025.39      1985159.81     13861025.53
      1985140.16     13861024.64      1985130.85     13861022.96
      1985118.79     13861017.20      1985108.20     13861008.59
      1985051.27     13860951.88      1985035.76     13860934.69
      1985030.83     13860927.30      1985027.51     13860918.95
      1985023.50     13860885.53      1985021.14     13860876.47
      1985017.02     13860868.70      1985011.61     13860861.46
      1984995.64     13860844.55      1984981.63     13860832.59
      1984973.97     13860828.14      1984969.61     13860826.68
      1984952.89     13860824.62      1984925.00     13860825.00

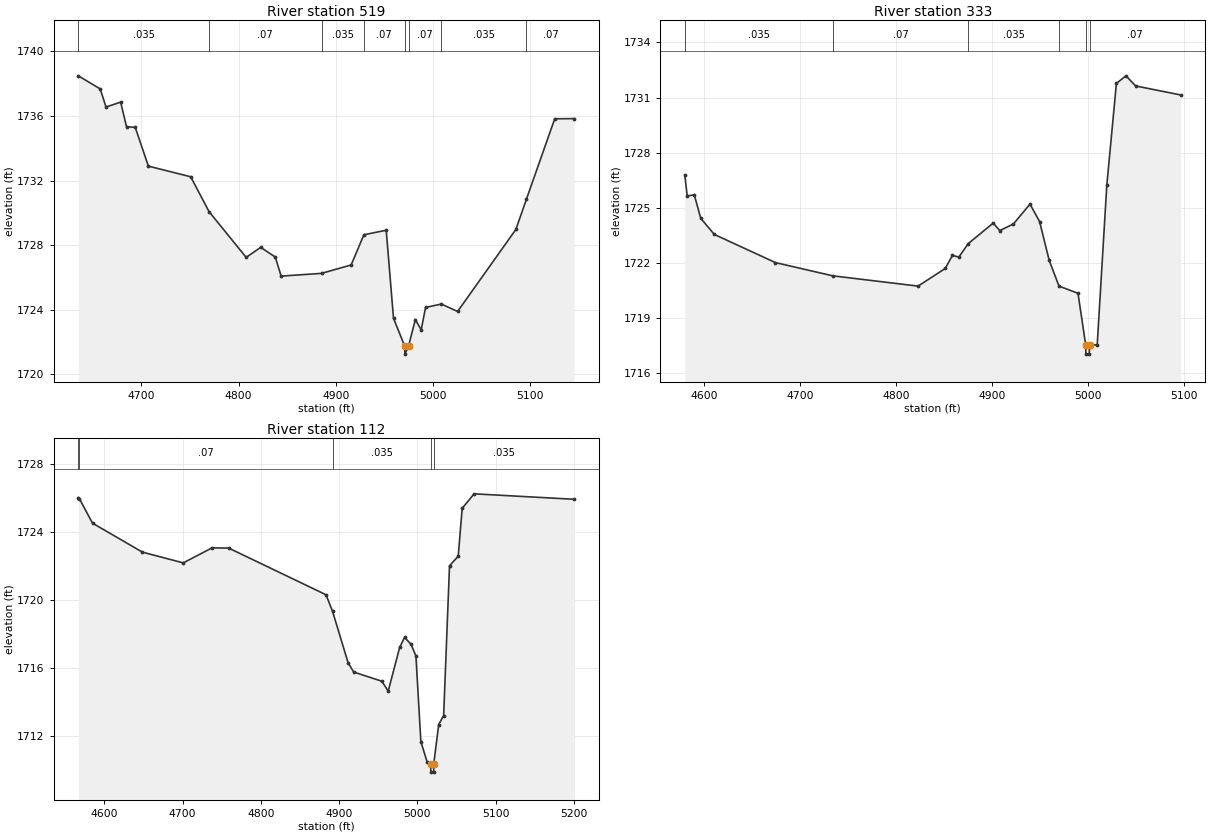
Type RM Length L Ch R = 1,519,186,186,186
BEGIN DESCRIPTION:
Stream0554 1.0
END DESCRIPTION:
XS GIS Cut Line= 3
      1985524.99     13860675.01      1985325.00     13860975.00
      1985325.00     13861124.95
#Sta/Elev= 30
  4635.0 1738.49  4657.5 1737.68  4663.5 1736.56  4678.6 1736.86  4684.6 1735.34
  4693.6 1735.30  4707.1 1732.90  4750.7 1732.24  4769.6 1730.08  4807.8 1727.25
  4822.8 1727.87  4837.8 1727.27  4843.8 1726.09  4885.4 1726.26  4915.9 1726.78
  4929.0 1728.65  4952.0 1728.93  4959.5 1723.48  4971.0 1721.76  4971.3 1721.26
  4975.0 1721.76  4982.0 1723.40  4988.0 1722.76  4992.5 1724.15  5008.8 1724.36
  5025.5 1723.90  5085.5 1728.98  5096.4 1730.86  5125.5 1735.83  5145.5 1735.84
#Mann=8,-1,0
  4635.0   0.035       0  4769.6    0.07       0  4885.4   0.035       0
  4929.0    0.07       0  4971.0    0.05       0  4975.0    0.07       0
  5008.8   0.035       0  5096.4    0.07       0
Bank Sta=4971,4975
Exp/Cntr=0.3,0.1

Type RM Length L Ch R = 1,333,221,221,221
BEGIN DESCRIPTION:
Stream0554 0.0
END DESCRIPTION:
XS GIS Cut Line= 3
      1985390.27     13860696.65      1985155.32     13860953.58
      1985153.03     13861121.91
#Sta/Elev= 30
  4580.0 1726.79  4582.5 1725.65  4589.9 1725.70  4596.7 1724.42  4610.8 1723.55
  4674.4 1722.02  4734.1 1721.30  4823.0 1720.74  4851.3 1721.70  4858.8 1722.41
  4865.5 1722.32  4875.2 1723.05  4901.3 1724.17  4908.1 1723.76  4922.3 1724.12
  4939.6 1725.20  4949.6 1724.25  4959.6 1722.14  4969.8 1720.74  4989.6 1720.35
  4997.6 1717.54  4997.8 1717.04  5001.3 1717.04  5001.6 1717.54  5009.6 1717.54
  5019.6 1726.22  5029.6 1731.77  5039.6 1732.18  5049.6 1731.63  5096.5 1731.14
#Mann=6,-1,0
  4580.0   0.035       0  4734.1    0.07       0  4875.2   0.035       0
  4969.8    0.07       0  4997.6    0.05       0  5001.6    0.07       0
Bank Sta=4997.6,5001.6
Exp/Cntr=0.3,0.1

Type RM Length L Ch R = 1,112,0,0,0
BEGIN DESCRIPTION:
Stream0554 0.1
END DESCRIPTION:
XS GIS Cut Line= 5
      1985384.45     13860639.95      1985059.26     13860840.15
      1984981.71     13860899.18      1984968.98     13860979.04
      1984978.05     13861051.57
#Sta/Elev= 30
  4566.9 1726.01  4568.2 1725.95  4585.0 1724.51  4648.8 1722.81  4700.9 1722.18
  4737.6 1723.06  4758.9 1723.05  4883.3 1720.31  4891.6 1719.34  4911.5 1716.32
  4918.6 1715.78  4954.6 1715.24  4962.7 1714.66  4977.3 1717.22  4983.6 1717.81
  4991.8 1717.41  4998.1 1716.72  5004.4 1711.70  5012.6 1710.48  5016.9 1710.41
  5017.2 1709.91  5020.7 1709.91  5020.9 1710.41  5027.2 1712.70  5033.5 1713.23
  5041.0 1722.01  5052.1 1722.57  5057.2 1725.38  5072.4 1726.23  5200.2 1725.91
#Mann=5,-1,0
  4566.9   0.035       0  4568.2    0.07       0  4891.6   0.035       0
  5016.9   0.035       0  5020.9   0.035       0
Bank Sta=5016.9,5020.9
Exp/Cntr=0.3,0.1

Chan Stop Cuts=-1