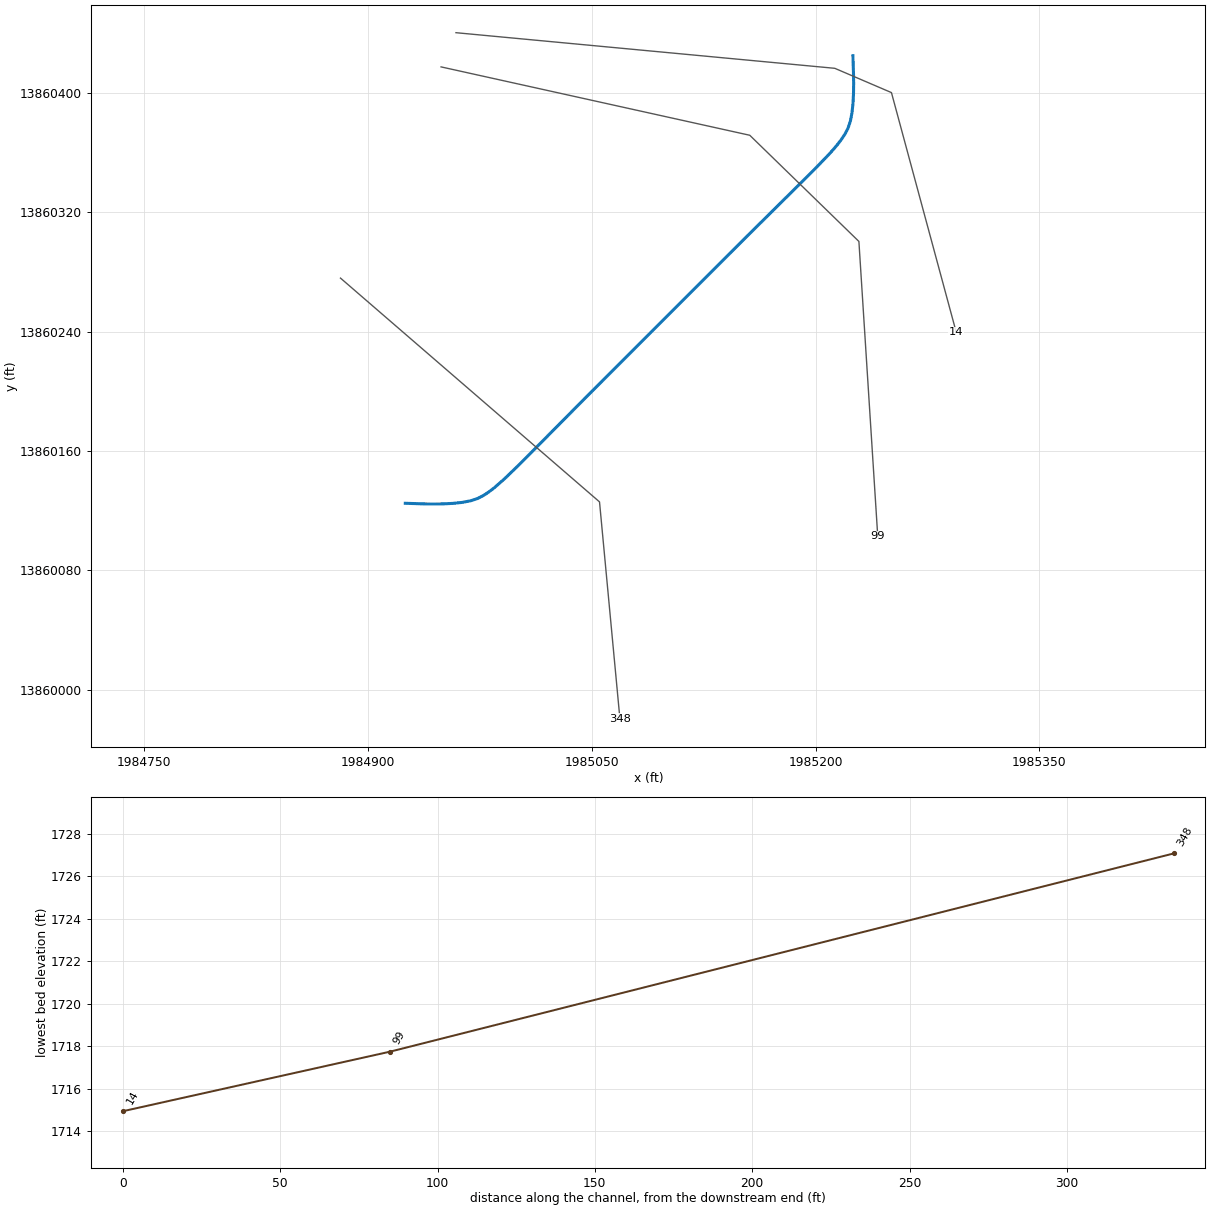
--- Stream0555.prj (project) ---

Proj Title=Stream0555 Base Level Engineering
Current Plan=p01
Default Exp/Contr=0.3,0.1
English Units
Geom File=g01
Flow File=f01
Plan File=p01
Y Axis Title=Elevation
X Axis Title(PF)=Main Channel Distance
X Axis Title(XS)=Station
BEGIN DESCRIPTION:
Stream0555
END DESCRIPTION:
DSS Export Rating Curves= 0
DSS Export Rating Curve Sorted= 0
DSS Export Volume Flow Curves= 0
DXF OffsetX= 0
DXF OffsetY= 0
DXF ScaleX= 1
DXF ScaleY= 10

--- Stream0555.p01 (plan) ---

Plan Title=Multiple Run
Short Identifier=Multiple
Geom File=g01
Flow File=f01
Subcritical Flow
K Sum by GR= 0
Std Step Tol= 0.01
Critical Tol= 0.01
Num of Std Step Trials= 20
Max Error Tol= 0.3
Flow Tol Ratio= 0.001
Split Flow NTrial= 30
Split Flow Tol= 0.02
Split Flow Ratio= 0.02
Log Output Level= 0
Friction Slope Method= 1
Unsteady Friction Slope Method= 2
Unsteady Bridges Friction Slope Method= 1
Parabolic Critical Depth
Global Vel Dist=  1 , 1 , 1
Global Log Level= 0
CheckData=True
Encroach Param= -1, 0, 0, 0
BEGIN DESCRIPTION:
Multiple Run
END DESCRIPTION:

--- Stream0555.f01 (steady flow) ---

Flow Title=Multiple
Program Version=4.10
Number of Profiles= 7
Profile Names=10-year,25-year,50-year,1pct_min,100-year,1pct_plu,500-year
River Rch & RM=Stream0555,Reach-1         ,348
     270     423     559     361     720    1436    1173
Boundary for River Rch & Prof#=Stream0555,Reach-1         , 1
Up Type= 0
Dn Type= 3
Dn Slope=0.005
Boundary for River Rch & Prof#=Stream0555,Reach-1         , 2
Up Type= 0
Dn Type= 3
Dn Slope=0.005
Boundary for River Rch & Prof#=Stream0555,Reach-1         , 3
Up Type= 0
Dn Type= 3
Dn Slope=0.005
Boundary for River Rch & Prof#=Stream0555,Reach-1         , 4
Up Type= 0
Dn Type= 3
Dn Slope=0.005
Boundary for River Rch & Prof#=Stream0555,Reach-1         , 5
Up Type= 0
Dn Type= 3
Dn Slope=0.005
Boundary for River Rch & Prof#=Stream0555,Reach-1         , 6
Up Type= 0
Dn Type= 3
Dn Slope=0.005
Boundary for River Rch & Prof#=Stream0555,Reach-1         , 7
Up Type= 0
Dn Type= 3
Dn Slope=0.005
DSS Import GetInterval= 0
DSS Import GetPeak= 0
DSS Import FillOption= 0

--- Stream0555.g01 (geometry) ---

Geom Title=Existing Conditions

River Reach=Stream0555,Reach-1
Reach XY= 30
      1984925.00     13860125.00      1984937.98     13860124.57
      1984943.96     13860124.50      1984950.37     13860124.59
      1984956.88     13860124.93      1984963.16     13860125.59
      1984968.86     13860126.68      1984973.64     13860128.27
      1984977.52     13860130.31      1984981.21     13860132.76
      1984984.79     13860135.51      1984991.70     13860141.58
      1985001.80     13860151.35      1985045.02     13860194.94
      1985098.34     13860248.33      1985155.06     13860304.98
      1985198.65     13860348.20      1985208.42     13860358.30
      1985211.53     13860361.73      1985214.49     13860365.21
      1985217.24     13860368.79      1985219.69     13860372.48
      1985221.73     13860376.36      1985223.32     13860381.14
      1985224.41     13860386.84      1985225.07     13860393.12
      1985225.41     13860399.63      1985225.50     13860406.04
      1985225.43     13860412.02      1985225.00     13860425.00

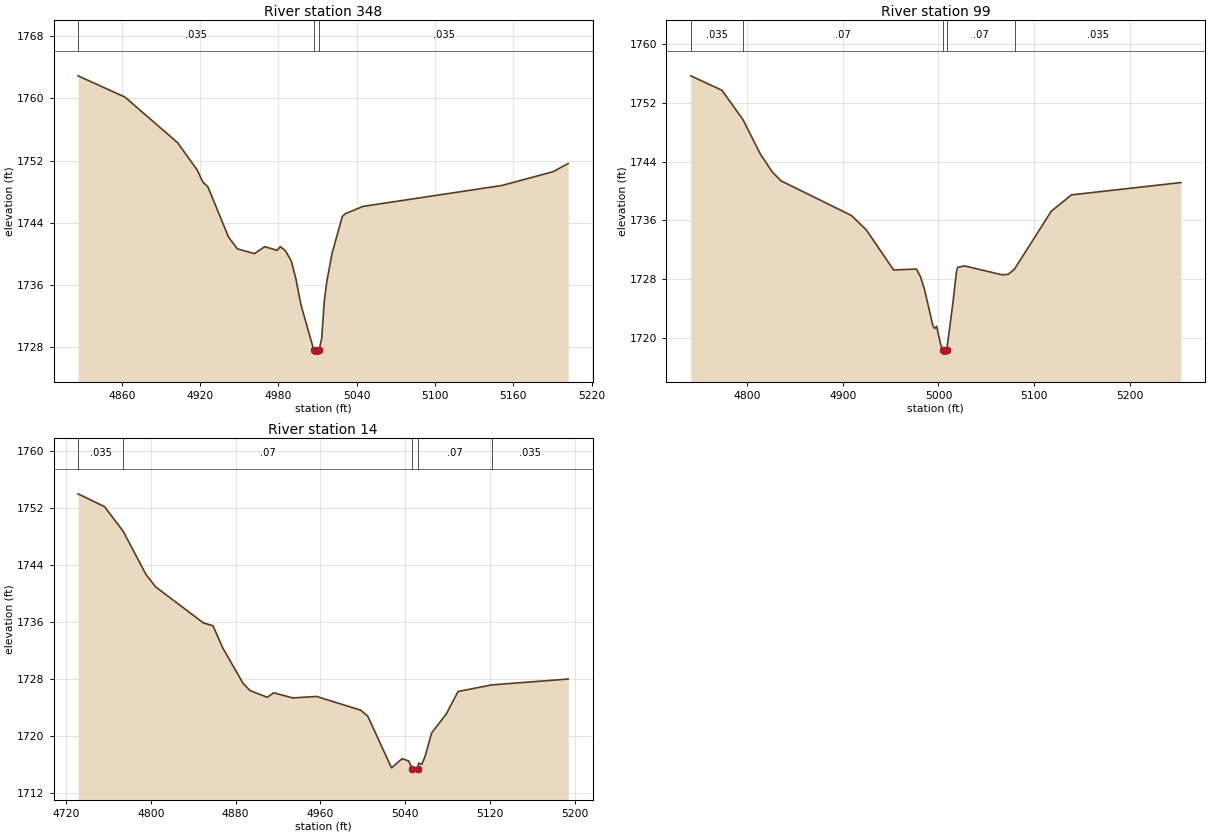
Type RM Length L Ch R = 1,348,249,249,249
BEGIN DESCRIPTION:
Stream0555 2.0
END DESCRIPTION:
XS GIS Cut Line= 3
      1984881.56     13860275.92      1985055.17     13860125.93
      1985068.86     13859980.40
#Sta/Elev= 30
  4826.5 1762.91  4862.5 1760.17  4902.8 1754.30  4918.0 1750.73  4922.0 1749.27
  4926.0 1748.62  4941.8 1742.16  4948.6 1740.63  4961.6 1740.02  4969.6 1740.92
  4979.0 1740.44  4981.5 1740.91  4985.4 1740.40  4989.9 1739.06  4993.4 1736.81
  4997.3 1733.43  5007.2 1727.58  5007.5 1727.08  5011.0 1727.08  5011.2 1727.58
  5013.2 1729.09  5015.2 1733.94  5017.1 1736.39  5021.1 1740.02  5029.0 1744.80
  5031.2 1745.15  5044.9 1746.10  5151.2 1748.79  5190.4 1750.56  5202.1 1751.62
#Mann=3,-1,0
  4826.5   0.035       0  5007.2   0.035       0  5011.2   0.035       0
Bank Sta=5007.2,5011.2
Exp/Cntr=0.3,0.1

Type RM Length L Ch R = 1,99,85,85,85
BEGIN DESCRIPTION:
Stream0555 1.0
END DESCRIPTION:
XS GIS Cut Line= 4
      1984948.97     13860417.48      1985155.88     13860371.65
      1985229.02     13860300.49      1985241.65     13860102.97
#Sta/Elev= 30
  4741.3 1755.68  4773.9 1753.71  4796.0 1749.67  4813.9 1745.04  4826.2 1742.61
  4835.4 1741.38  4909.1 1736.64  4924.5 1734.70  4953.2 1729.21  4977.0 1729.34
  4981.3 1728.27  4985.4 1726.58  4994.2 1721.60  4996.0 1721.23  4998.1 1721.54
  5002.0 1719.19  5004.6 1718.24  5004.9 1717.74  5008.4 1717.74  5008.6 1718.24
  5015.1 1724.74  5018.7 1728.87  5020.0 1729.56  5027.1 1729.77  5066.6 1728.55
  5073.1 1728.63  5079.5 1729.35  5117.8 1737.22  5138.9 1739.45  5253.2 1741.13
#Mann=5,-1,0
  4741.3   0.035       0  4796.0    0.07       0  5004.6    0.05       0
  5008.6    0.07       0  5079.5   0.035       0
Bank Sta=5004.6,5008.6
Exp/Cntr=0.3,0.1

Type RM Length L Ch R = 1,14,0,0,0
BEGIN DESCRIPTION:
Stream0555 0.0
END DESCRIPTION:
XS GIS Cut Line= 4
      1984958.96     13860440.40      1985212.86     13860416.53
      1985250.84     13860400.25      1985294.25     13860239.66
#Sta/Elev= 30
  4731.3 1753.98  4756.3 1752.18  4773.9 1748.73  4795.4 1742.67  4804.5 1740.93
  4849.7 1735.86  4858.7 1735.47  4867.8 1732.39  4887.1 1727.38  4893.7 1726.37
  4909.9 1725.43  4916.0 1726.06  4934.0 1725.34  4956.4 1725.55  4998.2 1723.62
  5004.8 1722.79  5027.2 1715.53  5037.2 1716.82  5043.4 1716.50  5046.8 1715.43
  5047.3 1714.93  5052.3 1715.43  5052.7 1716.19  5055.8 1716.03  5058.9 1717.14
  5065.1 1720.43  5079.0 1723.11  5090.0 1726.24  5121.8 1727.17  5194.0 1727.99
#Mann=5,-1,0
  4731.3   0.035       0  4773.9    0.07       0  5046.8    0.05       0
  5052.3    0.07       0  5121.8   0.035       0
Bank Sta=5046.8,5052.3
Exp/Cntr=0.3,0.1

Chan Stop Cuts=-1