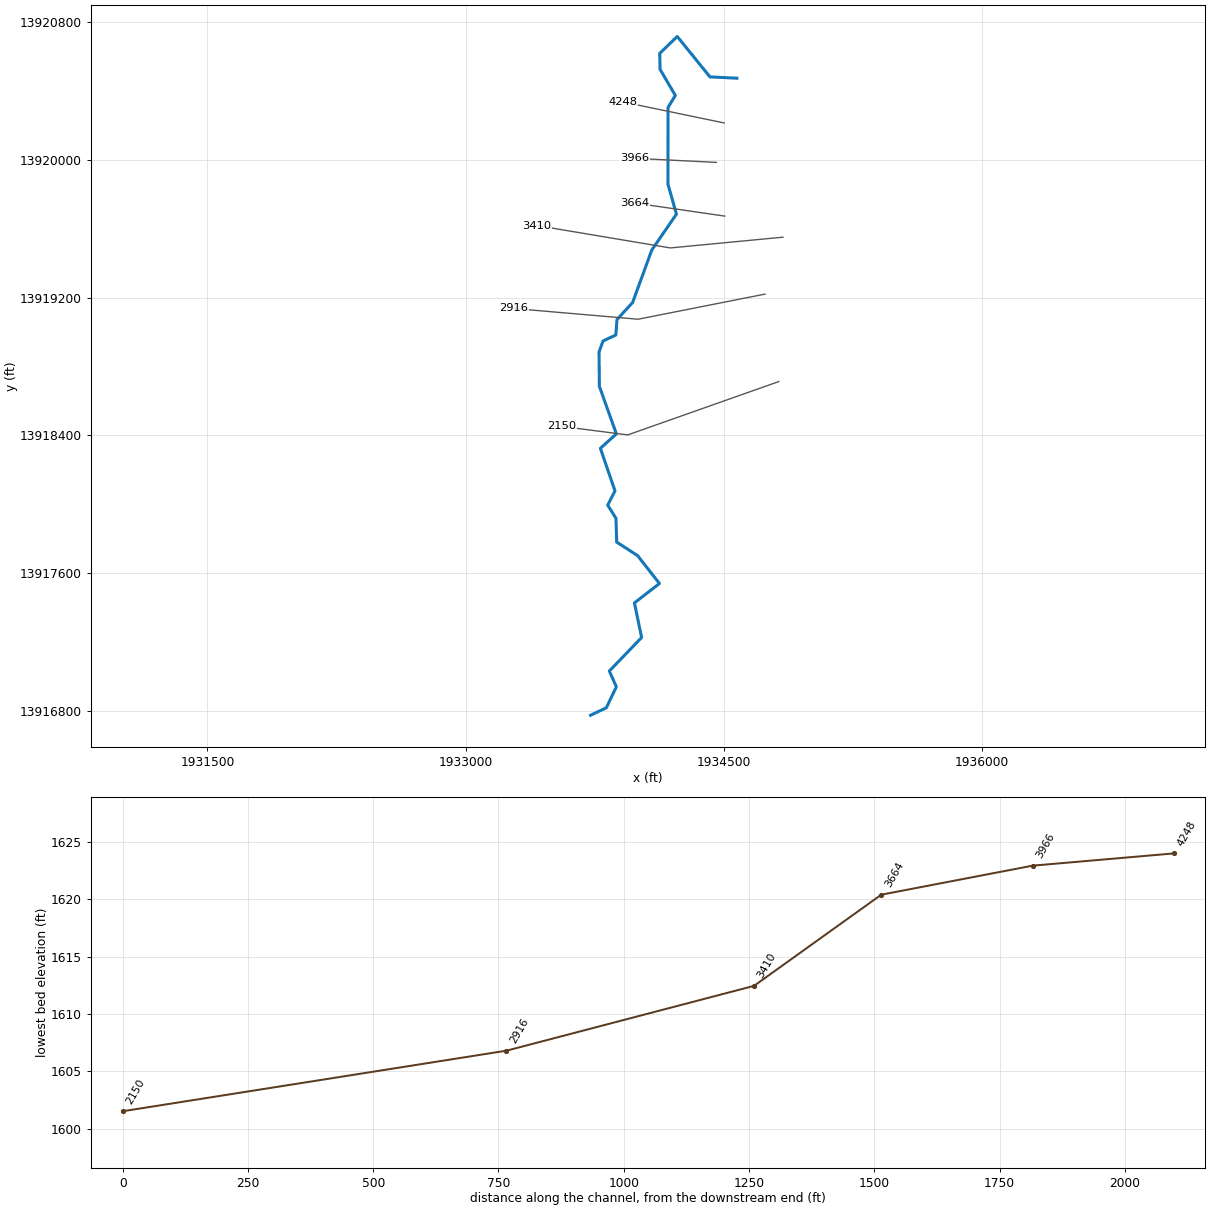
--- Stream0556.prj (project) ---

Proj Title=Stream0556 Base Level Engineering
Current Plan=p01
Default Exp/Contr=0.3,0.1
English Units
Geom File=g01
Flow File=f01
Plan File=p01
BEGIN DESCRIPTION:
Stream0556
END DESCRIPTION:

--- Stream0556.p01 (plan) ---

Plan Title=Multiple Run
Short Identifier=Multiple
Geom File=g01
Flow File=f01
Subcritical Flow
K Sum by GR= 0
Std Step Tol= 0.01
Critical Tol= 0.01
Num of Std Step Trials= 20
Max Error Tol= 0.3
Flow Tol Ratio= 0.001
Split Flow NTrial= 30
Split Flow Tol= 0.02
Split Flow Ratio= 0.02
Log Output Level= 0
Friction Slope Method= 1
Unsteady Friction Slope Method= 2
Unsteady Bridges Friction Slope Method= 1
Parabolic Critical Depth
Global Vel Dist=  1 , 1 , 1
Global Log Level= 0
CheckData=True
Encroach Param= -1, 0, 0, 0
BEGIN DESCRIPTION:
Multiple Run
END DESCRIPTION:

--- Stream0556.f01 (steady flow) ---

Flow Title=Multiple
Number of Profiles=7
Profile Names=10-year,25-year,50-year,1pct_min,100-year,1pct_plu,500-year
River Rch & RM= Stream0556,Reach-1,4248
     711    1174    1601    1057    2109    4209    3611
Boundary for River Rch & Prof#=Stream0556,Reach-1,1
Up Type=0
Dn Type=3
Dn Slope=0.005
Boundary for River Rch & Prof#=Stream0556,Reach-1,2
Up Type=0
Dn Type=3
Dn Slope=0.005
Boundary for River Rch & Prof#=Stream0556,Reach-1,3
Up Type=0
Dn Type=3
Dn Slope=0.005
Boundary for River Rch & Prof#=Stream0556,Reach-1,4
Up Type=0
Dn Type=3
Dn Slope=0.005
Boundary for River Rch & Prof#=Stream0556,Reach-1,5
Up Type=0
Dn Type=3
Dn Slope=0.005
Boundary for River Rch & Prof#=Stream0556,Reach-1,6
Up Type=0
Dn Type=3
Dn Slope=0.005
Boundary for River Rch & Prof#=Stream0556,Reach-1,7
Up Type=0
Dn Type=3
Dn Slope=0.005

--- Stream0556.g01 (geometry) ---

Geom Title=Existing Conditions

River Reach=Stream0556,Reach-1
Reach XY= 30
      1934575.00     13920475.00      1934418.51     13920482.67
      1934228.56     13920717.48      1934126.96     13920619.13
      1934128.67     13920526.59      1934217.47     13920375.01
      1934175.18     13920305.02      1934174.57     13919859.82
      1934223.92     13919685.54      1934080.85     13919477.29
      1933969.46     13919172.58      1933878.66     13919073.43
      1933871.81     13918983.35      1933797.83     13918948.85
      1933774.49     13918885.25      1933776.22     13918685.50
      1933875.10     13918409.23      1933782.26     13918325.30
      1933866.89     13918078.29      1933824.79     13917995.21
      1933872.70     13917919.07      1933876.99     13917780.68
      1933998.46     13917701.98      1934125.16     13917540.24
      1933979.99     13917427.55      1934021.54     13917226.50
      1933834.15     13917031.73      1933874.86     13916940.41
      1933817.05     13916818.69      1933725.00     13916775.00

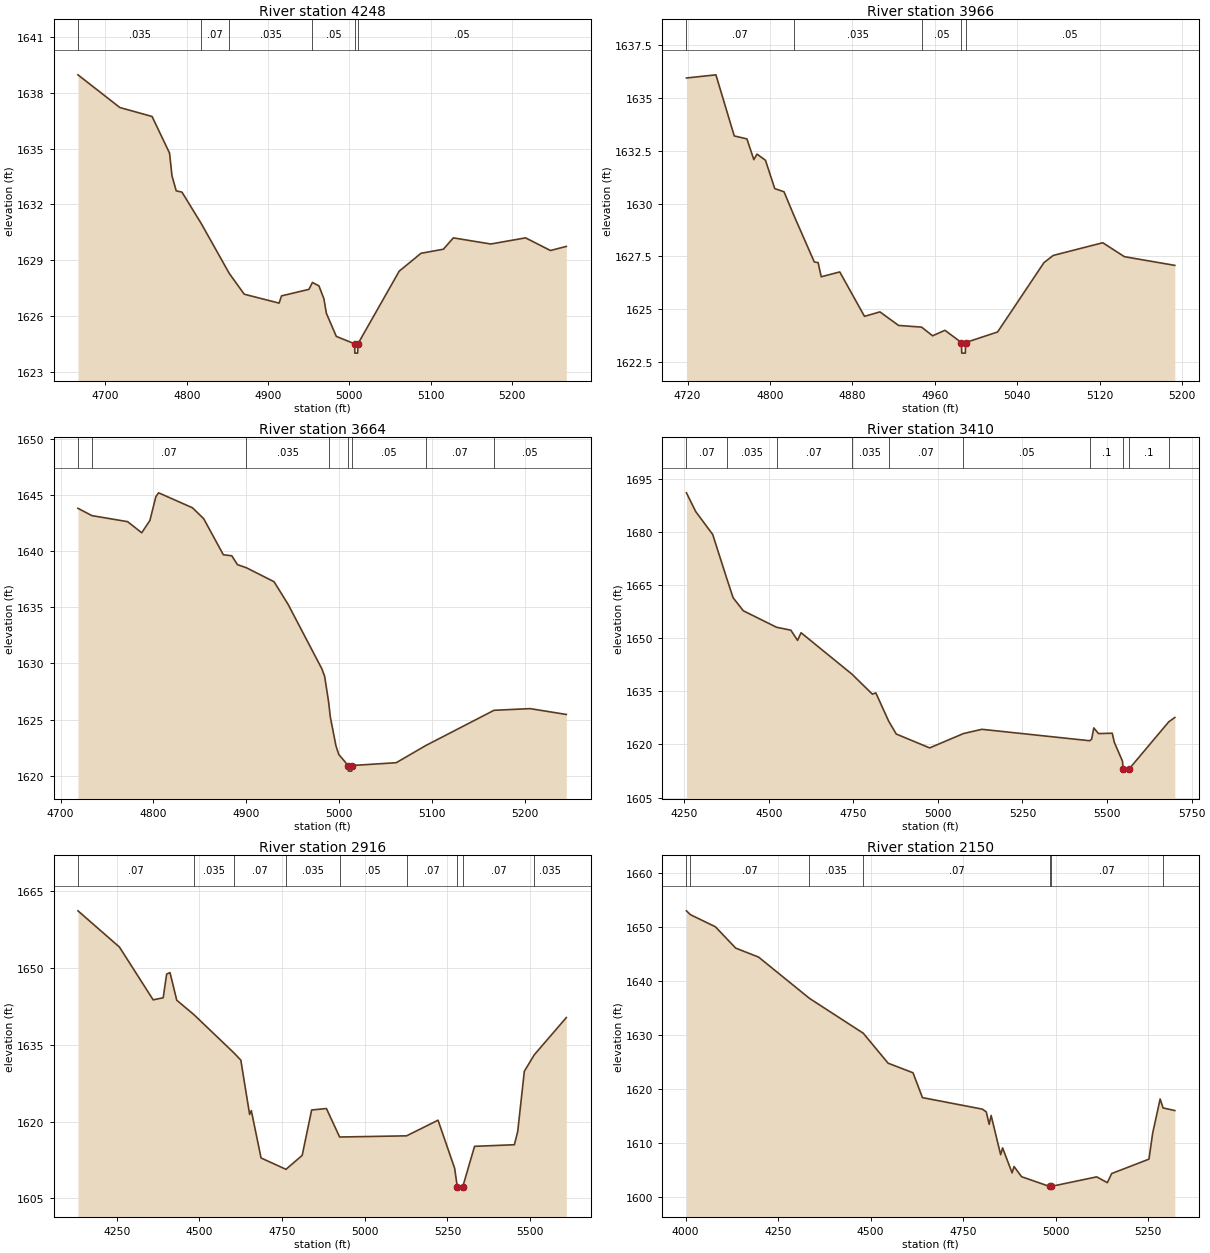
Type RM Length L Ch R = 1,4248,282,282,282
BEGIN DESCRIPTION:
Stream0556 4.0
END DESCRIPTION:
XS GIS Cut Line= 2
      1934501.46     13920215.06      1933913.07     13920337.04
#Sta/Elev= 30
  4666.2 1638.97  4717.8 1637.21  4757.4 1636.73  4778.9 1634.76  4781.9 1633.54
  4787.1 1632.73  4794.2 1632.66  4817.9 1630.97  4852.5 1628.28  4870.8 1627.17
  4913.7 1626.69  4916.7 1627.08  4950.4 1627.43  4954.7 1627.80  4962.7 1627.62
  4968.8 1626.93  4971.9 1626.14  4984.1 1624.90  5006.7 1624.50  5006.9 1624.00
  5010.4 1624.00  5010.7 1624.50  5061.5 1628.41  5088.3 1629.37  5115.9 1629.59
  5128.1 1630.20  5174.1 1629.87  5217.0 1630.20  5247.6 1629.52  5267.1 1629.74
#Mann=6,-1,0
  4666.2   0.035       0  4817.9    0.07       0  4852.5   0.035       0
  4954.7    0.05       0  5006.7    0.05       0  5010.7    0.05       0
Bank Sta=5006.7,5010.7
Exp/Cntr=0.3,0.1

Type RM Length L Ch R = 1,3966,302,302,302
BEGIN DESCRIPTION:
Stream0556 3.0
END DESCRIPTION:
XS GIS Cut Line= 2
      1934455.74     13919985.98      1933982.33     13920009.68
#Sta/Elev= 30
  4718.9 1635.94  4747.5 1636.09  4765.3 1633.20  4777.6 1633.06  4784.3 1632.08
  4787.4 1632.34  4795.6 1632.05  4804.6 1630.71  4813.6 1630.56  4823.2 1629.44
  4843.0 1627.24  4846.7 1627.21  4849.7 1626.54  4867.7 1626.77  4891.7 1624.67
  4906.7 1624.88  4924.8 1624.24  4947.1 1624.16  4957.8 1623.75  4969.8 1624.01
  4985.8 1623.43  4986.1 1622.93  4989.6 1622.93  4989.8 1623.43  5020.9 1623.93
  5065.9 1627.21  5074.9 1627.55  5123.0 1628.15  5144.0 1627.49  5192.9 1627.08
#Mann=5,-1,0
  4718.9    0.07       0  4823.2   0.035       0  4947.1    0.05       0
  4985.8    0.05       0  4989.8    0.05       0
Bank Sta=4985.8,4989.8
Exp/Cntr=0.3,0.1

Type RM Length L Ch R = 1,3664,254,254,254
BEGIN DESCRIPTION:
Stream0556 2.0
END DESCRIPTION:
XS GIS Cut Line= 2
      1934504.12     13919674.11      1933983.57     13919749.61
#Sta/Elev= 30
  4718.7 1643.82  4733.7 1643.17  4772.2 1642.63  4787.4 1641.64  4796.2 1642.74
  4802.6 1644.86  4805.6 1645.20  4842.0 1643.87  4854.1 1642.90  4875.3 1639.68
  4884.4 1639.59  4890.5 1638.80  4900.2 1638.52  4929.9 1637.28  4945.0 1635.27
  4981.4 1629.52  4984.4 1628.85  4988.7 1626.56  4990.5 1625.23  4996.6 1622.65
  4999.6 1621.89  5009.7 1620.90  5010.0 1620.40  5013.5 1620.40  5013.7 1620.90
  5061.5 1621.15  5093.1 1622.67  5166.8 1625.82  5205.7 1625.97  5244.7 1625.45
#Mann=8,-1,0
  4718.7   0.035       0  4733.7    0.07       0  4900.2   0.035       0
  4988.7    0.05       0  5009.7    0.05       0  5013.7    0.05       0
  5093.1    0.07       0  5166.8    0.05       0
Bank Sta=5009.7,5013.7
Exp/Cntr=0.3,0.1

Type RM Length L Ch R = 1,3410,494,494,494
BEGIN DESCRIPTION:
Stream0556 C
END DESCRIPTION:
XS GIS Cut Line= 3
      1934842.24     13919551.71      1934188.60     13919489.21
      1933412.57     13919619.42
#Sta/Elev= 30
  4256.7 1691.04  4284.1 1685.75  4334.3 1679.28  4376.0 1666.82  4394.6 1661.42
  4424.7 1657.74  4522.9 1653.08  4565.3 1652.25  4585.1 1649.37  4595.5 1651.53
  4745.6 1639.86  4806.4 1634.18  4816.5 1634.55  4854.4 1626.57  4876.8 1622.93
  4975.6 1619.01  5075.2 1623.05  5129.9 1624.26  5449.0 1621.03  5454.4 1621.48
  5460.7 1624.65  5474.7 1623.05  5515.2 1623.16  5521.4 1620.59  5545.6 1615.25
  5547.4 1612.95  5547.9 1612.45  5564.1 1612.95  5682.3 1626.37  5700.2 1627.60
#Mann=10,-1,0
  4256.7    0.07       0  4376.0   0.035       0  4522.9    0.07       0
  4745.6   0.035       0  4854.4    0.07       0  5075.2    0.05       0
  5449.0     0.1       0  5547.4    0.05       0  5564.1     0.1       0
  5682.3   0.035       0
Bank Sta=5547.4,5564.1
Exp/Cntr=0.3,0.1

Type RM Length L Ch R = 1,2916,766,766,766
BEGIN DESCRIPTION:
Stream0556  B
END DESCRIPTION:
XS GIS Cut Line= 3
      1934738.04     13919220.97      1934001.10     13919075.15
      1933278.61     13919137.52
#Sta/Elev= 30
  4133.1 1661.22  4258.5 1654.14  4360.5 1643.81  4390.8 1644.22  4401.2 1648.85
  4411.4 1649.14  4431.8 1643.74  4483.5 1640.93  4605.0 1633.42  4625.5 1632.02
  4652.1 1621.41  4657.2 1622.15  4686.7 1612.89  4762.0 1610.67  4811.0 1613.40
  4839.6 1622.28  4884.3 1622.56  4924.2 1616.99  5126.7 1617.22  5221.7 1620.28
  5271.9 1610.88  5279.9 1607.30  5280.4 1606.80  5296.6 1607.30  5332.1 1615.17
  5452.5 1615.48  5462.6 1618.08  5482.6 1629.84  5512.7 1633.07  5609.5 1640.34
#Mann=9,-1,0
  4133.1    0.07       0  4483.5   0.035       0  4605.0    0.07       0
  4762.0   0.035       0  4924.2    0.05       0  5126.7    0.07       0
  5279.9    0.05       0  5296.6    0.07       0  5512.7   0.035       0
Bank Sta=5279.9,5296.6
Exp/Cntr=0.3,0.1

Type RM Length L Ch R = 1,2150,0,0,0
BEGIN DESCRIPTION:
Stream0556 A
END DESCRIPTION:
XS GIS Cut Line= 3
      1934818.78     13918713.16      1933941.20     13918403.27
      1933555.75     13918452.76
#Sta/Elev= 30
  4002.3 1653.01  4013.0 1652.30  4080.5 1650.06  4135.4 1646.11  4197.2 1644.45
  4334.5 1636.82  4479.9 1630.37  4547.1 1624.82  4614.3 1623.05  4639.9 1618.45
  4801.7 1616.32  4812.3 1615.81  4820.1 1613.51  4825.4 1615.15  4851.1 1607.89
  4856.4 1609.15  4882.0 1604.53  4887.3 1605.70  4907.6 1603.82  4983.2 1602.02
  4983.5 1601.52  4987.2 1602.02  5110.6 1603.79  5139.4 1602.72  5151.0 1604.40
  5251.8 1607.07  5261.9 1611.91  5282.0 1618.20  5290.0 1616.54  5321.6 1616.06
#Mann=7,-1,0
  4002.3   0.035       0  4013.0    0.07       0  4334.5   0.035       0
  4479.9    0.07       0  4983.2    0.05       0  4987.2    0.07       0
  5290.0     0.1       0
Bank Sta=4983.2,4987.2
Exp/Cntr=0.3,0.1

Chan Stop Cuts=-1