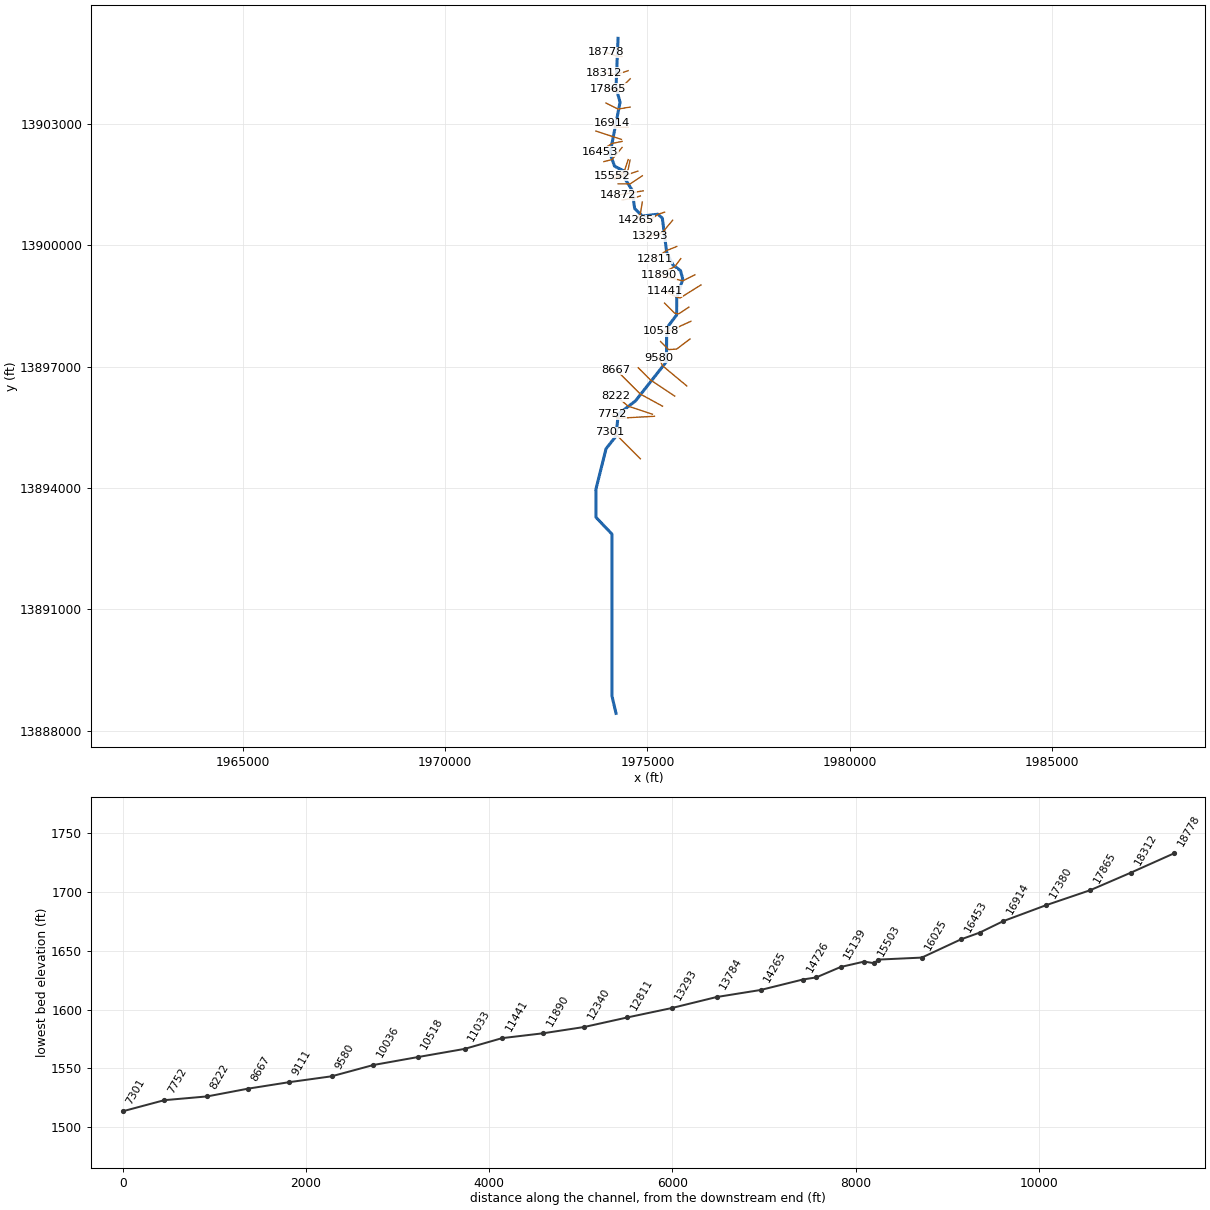
--- Stream0557.prj (project) ---

Proj Title=Stream0557 Base Level Engineering
Current Plan=p01
Default Exp/Contr=0.3,0.1
English Units
Geom File=g01
Flow File=f01
Plan File=p01
Y Axis Title=Elevation
X Axis Title(PF)=Main Channel Distance
X Axis Title(XS)=Station
BEGIN DESCRIPTION:
Stream0557
END DESCRIPTION:
DSS Export Rating Curves= 0
DSS Export Rating Curve Sorted= 0
DSS Export Volume Flow Curves= 0
DXF OffsetX= 0
DXF OffsetY= 0
DXF ScaleX= 1
DXF ScaleY= 10

--- Stream0557.p01 (plan) ---

Plan Title=Multiple Run
Short Identifier=Multiple
Geom File=g01
Flow File=f01
Subcritical Flow
K Sum by GR= 0
Std Step Tol= 0.01
Critical Tol= 0.01
Num of Std Step Trials= 20
Max Error Tol= 0.3
Flow Tol Ratio= 0.001
Split Flow NTrial= 30
Split Flow Tol= 0.02
Split Flow Ratio= 0.02
Log Output Level= 0
Friction Slope Method= 1
Unsteady Friction Slope Method= 2
Unsteady Bridges Friction Slope Method= 1
Parabolic Critical Depth
Global Vel Dist=  1 , 1 , 1
Global Log Level= 0
CheckData=True
Encroach Param= -1, 0, 0, 0
BEGIN DESCRIPTION:
Multiple Run
END DESCRIPTION:

--- Stream0557.f01 (steady flow) ---

Flow Title=Multiple
Program Version=4.10
Number of Profiles= 7
Profile Names=10-year,25-year,50-year,1pct_min,100-year,1pct_plu,500-year
River Rch & RM=Stream0557,Reach-1         ,18778
     371     597     802     526    1050    2095    1771
River Rch & RM=Stream0557,Reach-1         ,17865
    1205    2081    2929    1997    3985    7951    7306
River Rch & RM=Stream0557,Reach-1         ,6425
    1529    2657    3756    2569    5127   10229    9460
Boundary for River Rch & Prof#=Stream0557,Reach-1         , 1
Up Type= 0
Dn Type= 3
Dn Slope=0.005
Boundary for River Rch & Prof#=Stream0557,Reach-1         , 2
Up Type= 0
Dn Type= 3
Dn Slope=0.005
Boundary for River Rch & Prof#=Stream0557,Reach-1         , 3
Up Type= 0
Dn Type= 3
Dn Slope=0.005
Boundary for River Rch & Prof#=Stream0557,Reach-1         , 4
Up Type= 0
Dn Type= 3
Dn Slope=0.005
Boundary for River Rch & Prof#=Stream0557,Reach-1         , 5
Up Type= 0
Dn Type= 3
Dn Slope=0.005
Boundary for River Rch & Prof#=Stream0557,Reach-1         , 6
Up Type= 0
Dn Type= 3
Dn Slope=0.005
Boundary for River Rch & Prof#=Stream0557,Reach-1         , 7
Up Type= 0
Dn Type= 3
Dn Slope=0.005
DSS Import GetInterval= 0
DSS Import GetPeak= 0
DSS Import FillOption= 0

--- Stream0557.g01 (geometry) ---

Geom Title=Existing Conditions
Program Version=4.10

River Reach=Stream0557      ,Reach-1
Reach XY= 30
        1974275.       13905125.      1974224.41     13903904.95
      1974325.28     13903545.18      1974076.82     13902281.12
      1974188.39     13901961.67      1974472.38     13901816.54
      1974426.62     13901681.04      1974621.36      13901373.5
      1974685.48      13900915.2      1974876.46     13900728.53
      1975259.84     13900774.64      1975369.55     13900677.47
      1975477.07     13899830.86      1975635.75     13899515.29
      1975819.27     13899377.55       1975875.5     13899164.83
      1975726.22      13898714.5      1975722.76     13898280.93
      1975528.54     13898023.54      1975476.22     13897764.49
      1975471.38      13897126.5      1974705.37     13896154.53
       1974280.4     13895827.71      1974222.94     13895280.85
      1973978.62      13894973.5      1973726.22      13893964.5
      1973728.54     13893276.46      1974124.62     13892859.84
      1974124.64     13888854.85        1974225.       13888425.

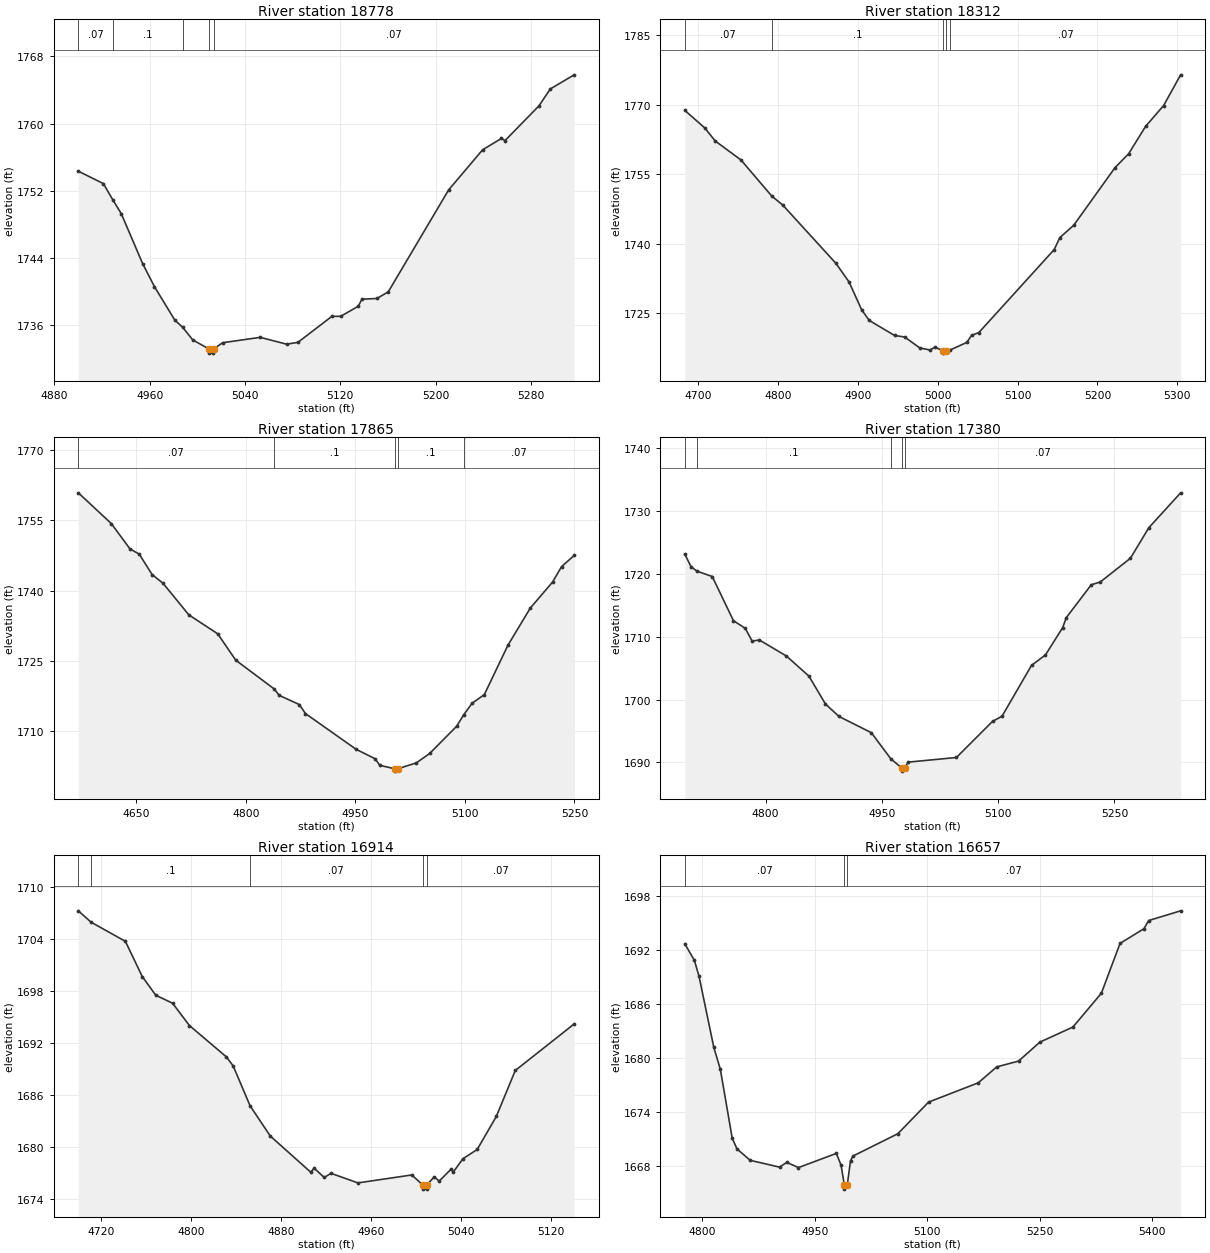
Type RM Length L Ch R = 1 ,18778   ,466,466,466
BEGIN DESCRIPTION:
Stream0557 38.0
END DESCRIPTION:
XS GIS Cut Line= 3
      1974374.98       13904675.        1974275.       13904675.
      1973975.01       13904775.
#Sta/Elev= 30
  4900.1 1754.32  4921.1 1752.84    4929 1750.92  4936.1 1749.27  4954.1  1743.3
    4964 1740.56  4981.1 1736.57  4987.7 1735.72  4996.1 1734.22  5009.7 1733.14
  5009.9 1732.64  5013.4 1732.64  5013.7 1733.14  5021.2 1733.88  5052.8 1734.52
  5074.9 1733.71  5084.4 1733.92  5112.9 1737.02  5120.4 1737.03    5135 1738.22
  5138.2 1739.07  5150.8 1739.15  5160.3 1739.95  5210.9 1752.08  5239.4 1756.86
  5255.2 1758.22  5258.3 1757.97  5286.8 1762.11  5296.3 1764.12  5316.3  1765.8
#Mann= 5 ,-1 , 0
  4900.1     .07       0    4929      .1       0  4987.7     .07       0
  5009.7     .05       0  5013.7     .07       0
Bank Sta=5009.7,5013.7
XS Rating Curve= 0 ,0
Exp/Cntr=0.3,0.1

Type RM Length L Ch R = 1 ,18312   ,447,447,447
BEGIN DESCRIPTION:
Stream0557 37.0
END DESCRIPTION:
XS GIS Cut Line= 3
      1974524.98     13904324.99        1974225.       13904225.
      1973925.05     13904274.99
#Sta/Elev= 30
  4683.7 1768.76    4709 1764.92  4721.6 1762.18    4754 1758.06  4792.4  1750.3
  4806.2 1748.35  4872.6 1735.81  4889.2 1731.76    4905 1725.74  4914.5 1723.46
  4946.1 1720.23  4958.8 1719.89  4977.8 1717.53  4990.4  1717.1  4996.7  1717.7
    5007 1716.92  5007.3 1716.42    5011 1716.92  5015.9 1717.12  5036.4 1718.72
  5042.5 1720.25  5051.6 1720.86  5145.9 1738.76  5152.9 1741.33  5170.2 1743.97
  5221.9 1756.41  5238.9 1759.39  5260.2 1765.31  5282.7 1769.79    5304 1776.42
#Mann= 5 ,-1 , 0
  4683.7     .07       0  4792.4      .1       0    5007     .05       0
    5011      .1       0  5015.9     .07       0
Bank Sta=5007,5011
XS Rating Curve= 0 ,0
Exp/Cntr=0.3,0.1

Type RM Length L Ch R = 1 ,17865   ,485,485,485
BEGIN DESCRIPTION:
Stream0557 36.0
END DESCRIPTION:
XS GIS Cut Line= 3
      1974575.03     13904125.03        1974275.       13903825.
      1974025.06     13903874.99
#Sta/Elev= 30
  4570.5 1760.91  4615.8 1754.32  4641.2 1748.93    4654 1747.79  4671.6 1743.43
  4686.5 1741.58  4721.9 1734.82  4761.4 1730.78  4786.2 1725.13  4838.7    1719
  4845.6 1717.62  4873.2 1715.65  4881.6 1713.73    4951 1706.09  4977.1 1704.06
  4983.5 1702.66    5004 1701.92  5004.3 1701.42    5008 1701.92  5033.6 1703.19
  5051.9 1705.21  5088.6 1710.99  5098.3 1713.44    5110 1715.95  5126.6 1717.76
    5159 1728.34  5189.6 1736.27  5220.2 1741.85  5232.4 1745.13  5249.7 1747.52
#Mann= 5 ,-1 , 0
  4570.5     .07       0  4838.7      .1       0    5004     .05       0
    5008      .1       0  5098.3     .07       0
Bank Sta=5004,5008
XS Rating Curve= 0 ,0
Exp/Cntr=0.3,0.1

Type RM Length L Ch R = 1 ,17380   ,466,466,466
BEGIN DESCRIPTION:
Stream0557 35.0
END DESCRIPTION:
XS GIS Cut Line= 3
      1974574.96     13903424.99        1974275.       13903375.
      1973975.01       13903525.
#Sta/Elev= 30
  4695.8 1723.15  4703.9 1721.13  4711.7 1720.42  4731.2 1719.58  4758.6 1712.54
  4773.8 1711.33  4782.6 1709.31  4792.1 1709.47  4826.9 1706.92  4855.9 1703.72
  4877.2 1699.29  4894.7  1697.3  4936.4 1694.72  4961.4 1690.58  4975.6  1689.1
  4975.8  1688.6  4979.6  1689.1  4983.7 1690.03  5046.1 1690.77  5092.7 1696.52
  5104.9 1697.33    5143 1705.44    5161  1707.1  5183.2 1711.45  5187.8 1713.03
  5220.1 1718.27  5231.7 1718.71  5270.5 1722.48  5294.3 1727.35  5335.3  1732.9
#Mann= 5 ,-1 , 0
  4695.8     .07       0  4711.7      .1       0  4961.4     .07       0
  4975.6     .05       0  4979.6     .07       0
Bank Sta=4975.6,4979.6
XS Rating Curve= 0 ,0
Exp/Cntr=0.3,0.1

Type RM Length L Ch R = 1 ,16914   ,257,257,257
BEGIN DESCRIPTION:
Stream0557 34.0
END DESCRIPTION:
XS GIS Cut Line= 3
      1974524.95       13902925.        1974225.       13902925.
      1974124.98     13903025.02
#Sta/Elev= 30
  4699.6  1707.3  4710.9 1705.99  4741.5 1703.77  4756.5  1699.7  4768.5 1697.54
  4783.5 1696.61  4798.5 1694.03  4831.5 1690.39  4837.5 1689.34  4852.5 1684.74
  4870.5 1681.24  4906.5 1677.06  4909.5 1677.52  4918.5 1676.45  4924.5 1676.93
  4948.5 1675.82  4996.5 1676.74    5006  1675.6  5006.3  1675.1  5009.8  1675.1
    5010  1675.6  5016.5 1676.53  5020.8 1676.02  5031.4 1677.41  5033.5  1677.1
    5042 1678.62  5054.7 1679.69  5071.7 1683.51  5088.6 1688.83    5141 1694.21
#Mann= 5 ,-1 , 0
  4699.6     .07       0  4710.9      .1       0  4852.5     .07       0
    5006     .05       0    5010     .07       0
Bank Sta=5006,5010
XS Rating Curve= 0 ,0
Exp/Cntr=0.3,0.1

Type RM Length L Ch R = 1 ,16657   ,204,204,204
BEGIN DESCRIPTION:
Mapping XS 983ff893
END DESCRIPTION:
XS GIS Cut Line= 2
      1974357.12     13902625.04      1973728.52     13902830.11
#Sta/Elev= 30
  4776.5 1692.68  4789.2 1690.86  4795.4  1689.1  4815.2 1681.15  4823.9 1678.71
  4839.7 1671.06    4846 1669.86  4863.6 1668.58  4902.8 1667.82  4912.5 1668.35
  4928.1 1667.77  4978.6 1669.35  4984.9 1668.04  4989.2 1665.87  4989.4 1665.37
  4993.2 1665.87  4997.5 1668.53  5000.7 1669.05  5060.6 1671.54  5101.6 1675.06
  5167.9 1677.21  5192.4 1678.98  5221.6 1679.63    5250 1681.74  5294.1 1683.42
    5332 1687.18  5356.9 1692.73  5388.8 1694.37  5395.1 1695.28  5437.7 1696.36
#Mann= 3 ,-1 , 0
  4776.5     .07       0  4989.2     .05       0  4993.2     .07       0
Bank Sta=4989.2,4993.2
XS Rating Curve= 0 ,0
Exp/Cntr=0.3,0.1

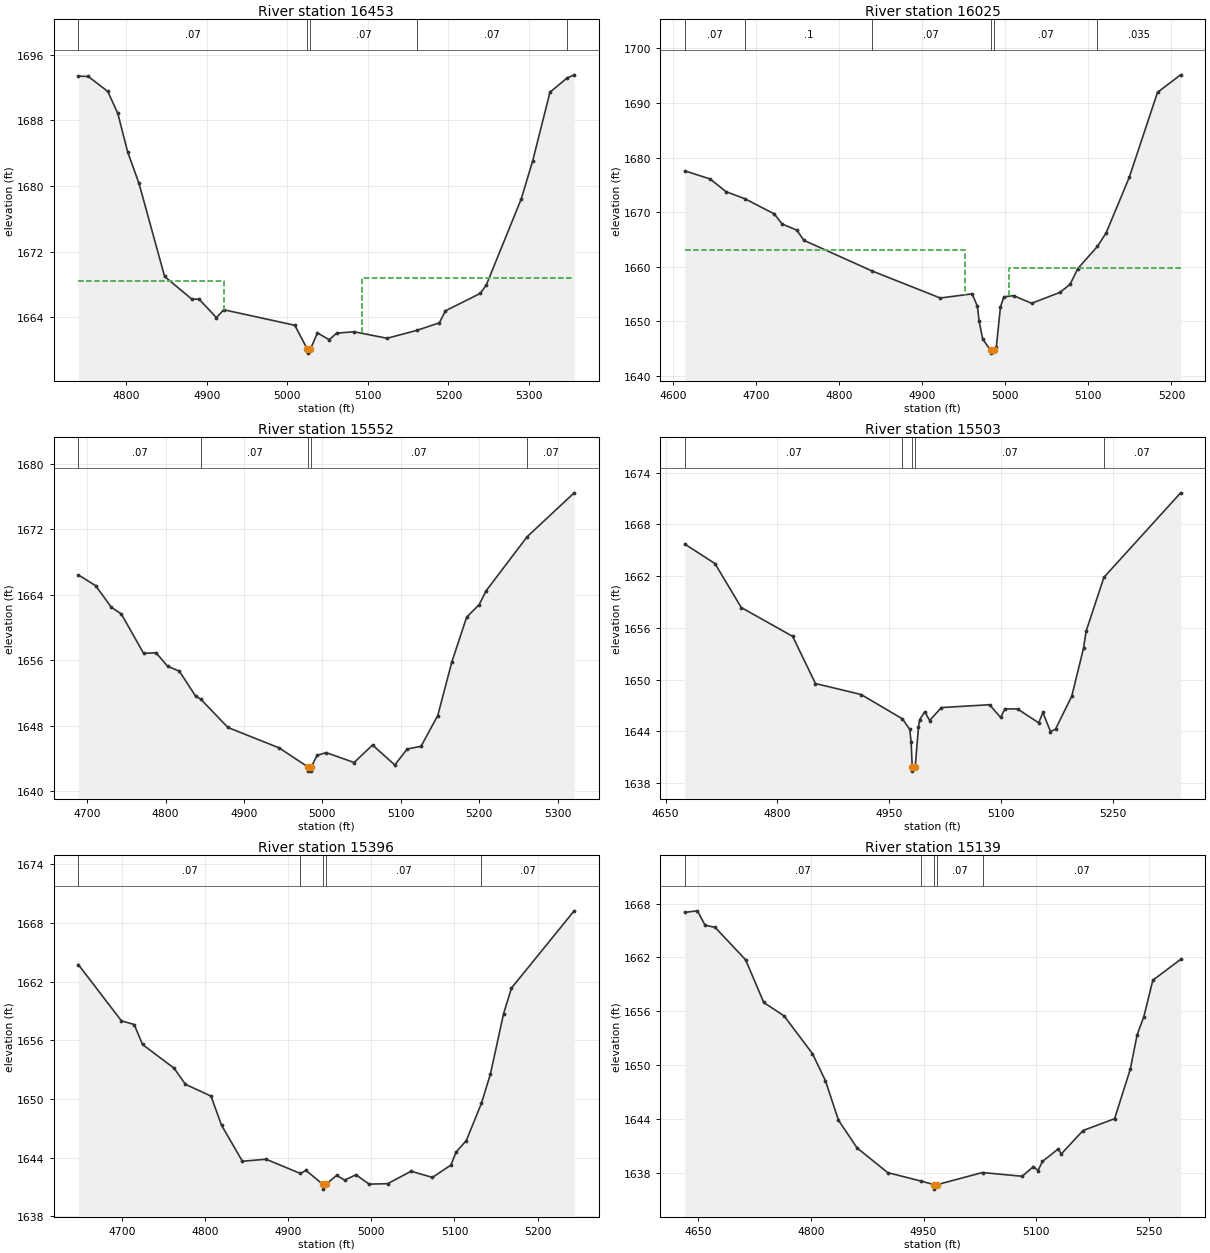
Type RM Length L Ch R = 1 ,16453   ,428,428,428
BEGIN DESCRIPTION:
Stream0557 33.0
END DESCRIPTION:
XS GIS Cut Line= 3
      1974375.05     13902575.01        1974125.       13902525.
      1973825.04     13902325.03
#Sta/Elev= 30
  4740.6 1693.37  4752.9 1693.33  4777.1 1691.52  4789.6 1688.83  4801.8 1684.16
  4815.9 1680.32  4847.7 1668.99  4881.4 1666.24  4890.5 1666.23    4912 1663.98
  4921.1 1664.94  5009.3 1663.05  5024.8 1660.16  5025.1 1659.66  5028.8 1660.16
  5037.4 1662.12  5052.1 1661.29  5061.2 1662.09  5082.8 1662.26  5123.9 1661.47
  5160.9 1662.43  5188.8 1663.35  5196.3 1664.81  5239.6 1666.93  5247.2 1667.99
  5290.5 1678.45  5304.5 1683.02  5326.1 1691.42  5347.1 1693.13  5356.1 1693.53
#Mann= 5 ,-1 , 0
  4740.6     .07       0  5024.8     .05       0  5028.8     .07       0
  5160.9     .07       0  5347.1    .035       0
#XS Ineff= 2 , 0
         4921.68 1668.49 5093.01         1668.81
Permanent Ineff=
       F       F
Bank Sta=5024.8,5028.8
XS Rating Curve= 0 ,0
Exp/Cntr=0.3,0.1

Type RM Length L Ch R = 1 ,16025   ,473,473,473
BEGIN DESCRIPTION:
Stream0557 32.0
END DESCRIPTION:
XS GIS Cut Line= 3
      1974374.97     13902424.97        1974125.       13902125.
      1973925.03     13902075.01
#Sta/Elev= 30
  4614.4 1677.56  4644.9 1676.08    4664 1673.75  4686.7 1672.46  4722.1 1669.67
  4731.5 1667.83  4749.2  1666.7  4757.7 1664.84  4839.3 1659.25  4921.8 1654.27
  4960.1 1655.03  4966.5 1652.75  4968.6 1649.97  4972.9 1646.73  4982.5 1644.67
  4982.8 1644.17  4986.5 1644.67  4989.2 1645.22  4994.2 1652.62  4998.3 1654.48
    5010  1654.7  5031.7  1653.3  5065.7 1655.29    5078 1656.77  5087.3 1659.67
  5110.9 1663.72  5121.3 1666.17  5149.2 1676.37  5183.2 1691.95    5211 1695.16
#Mann= 6 ,-1 , 0
  4614.4     .07       0  4686.7      .1       0  4839.3     .07       0
  4982.5     .05       0  4986.5     .07       0  5110.9    .035       0
#XS Ineff= 2 , 0
         4951.05 1663.11  5004.9         1659.76
Permanent Ineff=
       F       F
Bank Sta=4982.5,4986.5
XS Rating Curve= 0 ,0
Exp/Cntr=0.3,0.1

Type RM Length L Ch R = 1 ,15552   ,49,49,49
BEGIN DESCRIPTION:
Stream0557 31.0
END DESCRIPTION:
XS GIS Cut Line= 3
      1974525.01     13902125.03        1974425.       13901825.
      1974124.99       13901725.
#Sta/Elev= 30
  4688.7 1666.42  4710.8 1665.11  4730.9 1662.46  4743.5 1661.66    4772 1656.84
  4787.8 1656.92  4802.5 1655.28  4817.6 1654.67  4838.4 1651.61  4844.7 1651.27
  4879.5  1647.8  4944.8 1645.31  4981.8 1642.97  4982.1 1642.47  4985.6 1642.47
  4985.8 1642.97  4993.3  1644.4  5004.9 1644.73  5040.5 1643.52    5064 1645.66
  5092.4 1643.22  5108.2 1645.17  5125.9  1645.5  5147.2 1649.26  5165.2 1655.81
  5184.1 1661.27    5200 1662.79  5208.9 1664.48  5261.2 1671.08  5321.2 1676.44
#Mann= 5 ,-1 , 0
  4688.7     .07       0  4844.7     .07       0  4981.8     .05       0
  4985.8     .07       0  5261.2     .07       0
Bank Sta=4981.8,4985.8
XS Rating Curve= 0 ,0
Exp/Cntr=0.3,0.1

Type RM Length L Ch R = 1 ,15503   ,107,107,107
BEGIN DESCRIPTION:
Stream0557 31.1
END DESCRIPTION:
XS GIS Cut Line= 4
      1974571.74     13902112.61      1974518.37     13901852.24
      1974467.58     13901811.87      1974173.27      13901654.3
#Sta/Elev= 30
  4675.8 1665.73  4716.2 1663.47  4751.5 1658.37  4820.3 1655.03  4850.9 1649.56
  4912.2 1648.28  4967.5 1645.46  4977.3 1644.24  4979.1  1642.8  4980.6  1639.9
  4980.8  1639.4  4984.6  1639.9    4989 1644.55  4990.6 1645.38  4997.5 1646.29
  5003.9 1645.27  5019.6 1646.77  5084.2  1647.1  5099.1 1645.62  5104.7 1646.62
  5121.7 1646.61  5150.1    1645  5155.7 1646.21  5165.9 1643.98  5172.7 1644.28
  5194.4 1648.09  5210.2 1653.66  5213.6 1655.61  5237.5 1661.87  5340.3 1671.67
#Mann= 5 ,-1 , 0
  4675.8     .07       0  4967.5     .07       0  4980.6     .05       0
  4984.6     .07       0  5237.5     .07       0
Bank Sta=4980.6,4984.6
XS Rating Curve= 0 ,0
Exp/Cntr=0.3,0.1

Type RM Length L Ch R = 1 ,15396   ,257,257,257
BEGIN DESCRIPTION:
Mapping XS ee5505ae
END DESCRIPTION:
XS GIS Cut Line= 2
      1974763.01     13901839.83      1974198.73     13901646.45
#Sta/Elev= 30
  4647.5 1663.74  4699.3 1657.99  4714.7 1657.61  4724.7 1655.57  4762.7 1653.14
  4776.4 1651.49  4807.1 1650.29  4819.8  1647.3  4844.9 1643.62  4873.3 1643.83
  4914.7 1642.37  4921.3 1642.69  4941.5 1641.27  4941.7 1640.77  4945.5 1641.27
  4958.3 1642.18  4967.8 1641.69  4981.5 1642.24  4997.4 1641.28  5019.7 1641.33
  5047.8  1642.6  5073.5 1641.97  5095.7 1643.23    5102 1644.57  5114.2 1645.73
  5132.5 1649.56  5143.3 1652.56  5159.1 1658.72  5168.6 1661.34    5244 1669.24
#Mann= 5 ,-1 , 0
  4647.5     .07       0  4914.7     .07       0  4941.5     .05       0
  4945.5     .07       0  5132.5     .07       0
Bank Sta=4941.5,4945.5
XS Rating Curve= 0 ,0
Exp/Cntr=0.3,0.1

Type RM Length L Ch R = 1 ,15139   ,267,267,267
BEGIN DESCRIPTION:
Stream0557 30.0
END DESCRIPTION:
XS GIS Cut Line= 3
      1974874.99     13901724.99        1974575.       13901525.
      1974275.04       13901525.
#Sta/Elev= 30
  4631.9 1667.02  4648.7 1667.19  4658.9 1665.59  4672.2 1665.35  4712.9 1661.74
  4737.1 1656.98  4764.1 1655.49    4802 1651.28  4819.3 1648.26  4836.6 1643.87
  4861.4 1640.78  4902.2 1638.03  4946.4 1637.09    4964 1636.69  4964.2 1636.19
    4968 1636.69  5028.5 1638.04  5081.4 1637.62  5096.4 1638.71  5102.4 1638.26
  5108.4 1639.28  5129.4 1640.67  5133.4 1640.11  5162.4 1642.72  5204.4 1644.03
  5225.4 1649.57  5234.4 1653.36  5243.4  1655.4  5255.4 1659.46  5292.4 1661.78
#Mann= 5 ,-1 , 0
  4631.9     .07       0  4946.4     .07       0    4964     .05       0
    4968     .07       0  5028.5     .07       0
Bank Sta=4964,4968
XS Rating Curve= 0 ,0
Exp/Cntr=0.3,0.1

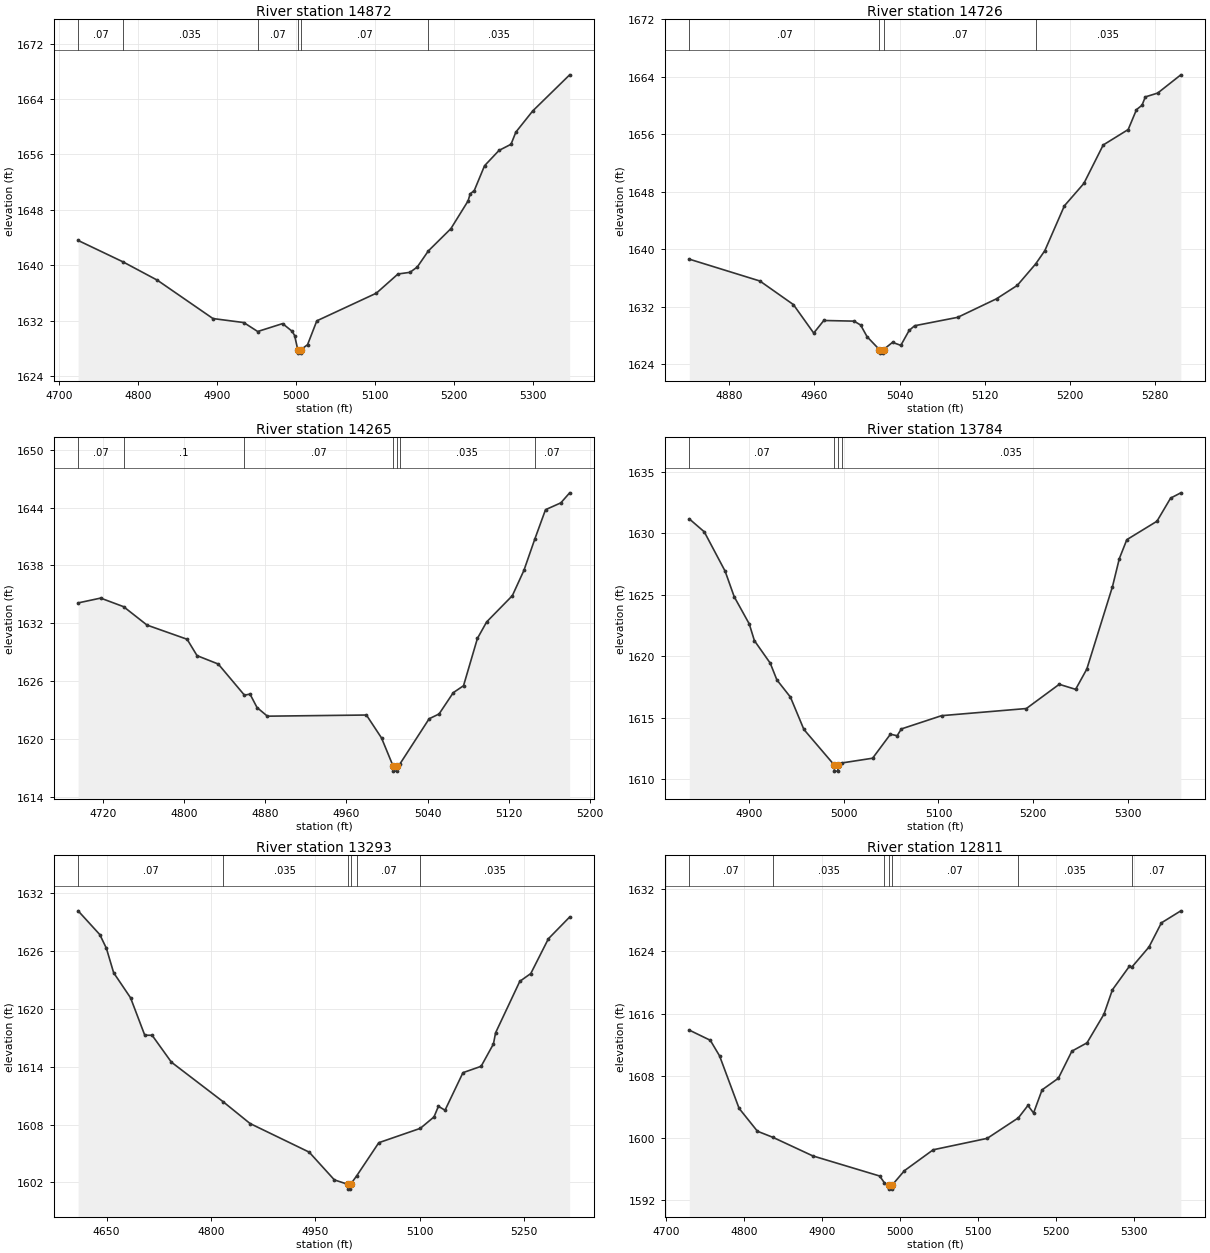
Type RM Length L Ch R = 1 ,14872   ,146,146,146
BEGIN DESCRIPTION:
Mapping XS ce89ea9f
END DESCRIPTION:
XS GIS Cut Line= 2
      1974897.08     13901351.56      1974283.85     13901248.09
#Sta/Elev= 30
    4724 1643.59  4780.6 1640.51  4824.3 1637.85  4894.6 1632.32  4933.6 1631.74
  4951.2 1630.45  4982.7 1631.59  4994.8 1630.48  4997.9 1629.87  5001.9 1627.83
  5002.2 1627.33  5005.7 1627.33  5005.9 1627.83  5014.3 1628.55    5026 1631.99
  5101.3 1635.98  5128.7 1638.75  5143.9 1638.99  5153.1 1639.76  5167.1 1642.08
  5195.6 1645.29  5217.4  1649.3    5220 1650.31  5225.2 1650.79  5238.2 1654.37
  5256.5 1656.58  5271.7 1657.47  5277.8 1659.22  5299.1 1662.27  5345.9 1667.49
#Mann= 6 ,-1 , 0
    4724     .07       0  4780.6    .035       0  4951.2     .07       0
  5001.9     .05       0  5005.9     .07       0  5167.1    .035       0
Bank Sta=5001.9,5005.9
XS Rating Curve= 0 ,0
Exp/Cntr=0.3,0.1

Type RM Length L Ch R = 1 ,14726   ,461,461,461
BEGIN DESCRIPTION:
Stream0557 29.0
END DESCRIPTION:
XS GIS Cut Line= 3
        1974825.       13901225.        1974675.       13901175.
      1974375.05     13901125.01
#Sta/Elev= 30
  4842.3 1638.62  4908.7 1635.58  4940.2  1632.3  4959.3 1628.34  4968.8 1630.09
  4997.2    1630  5003.4 1629.46  5009.5 1627.83    5021 1626.05  5021.2 1625.55
  5024.7 1625.55    5025 1626.05  5033.4 1627.05  5041.2 1626.63    5049  1628.7
  5054.2 1629.36  5094.7 1630.53  5131.2 1633.11  5150.7 1634.97    5168 1637.96
  5176.6  1639.8    5195 1646.04  5213.3 1649.15  5231.5  1654.5    5255 1656.65
  5262.8 1659.42    5268 1660.03  5271.1 1661.19  5282.7 1661.72  5304.5 1664.26
#Mann= 4 ,-1 , 0
  4842.3     .07       0    5021     .05       0    5025     .07       0
    5168    .035       0
Bank Sta=5021,5025
XS Rating Curve= 0 ,0
Exp/Cntr=0.3,0.1

Type RM Length L Ch R = 1 ,14265   ,481,481,481
BEGIN DESCRIPTION:
Stream0557 28.0
END DESCRIPTION:
XS GIS Cut Line= 3
        1974875.     13901074.98        1974825.       13900775.
        1974725.     13900624.99
#Sta/Elev= 30
  4695.6 1634.11  4717.8 1634.61  4740.4 1633.72  4763.5 1631.81    4803 1630.34
  4812.8 1628.64  4833.7 1627.77  4859.5 1624.54    4865 1624.65  4871.9 1623.26
  4882.1 1622.36  4979.7 1622.48  4994.6  1620.1  5006.1 1617.16  5006.3 1616.66
  5009.8 1616.66  5010.1 1617.16    5013 1617.45  5041.5 1622.09  5051.3 1622.59
  5065.3  1624.8  5075.4 1625.52  5089.1 1630.43  5098.2 1632.14  5123.5 1634.86
  5134.9 1637.48  5145.5 1640.69  5156.2 1643.78  5171.3 1644.49    5180 1645.53
#Mann= 7 ,-1 , 0
  4695.6     .07       0  4740.4      .1       0  4859.5     .07       0
  5006.1     .05       0  5010.1     .07       0    5013    .035       0
  5145.5     .07       0
Bank Sta=5006.1,5010.1
XS Rating Curve= 0 ,0
Exp/Cntr=0.3,0.1

Type RM Length L Ch R = 1 ,13784   ,491,491,491
BEGIN DESCRIPTION:
Stream0557 27.0
END DESCRIPTION:
XS GIS Cut Line= 3
      1975424.98     13900824.99        1975275.       13900775.
      1974975.04     13900575.03
#Sta/Elev= 30
  4837.1 1631.18  4852.9 1630.13  4874.9 1626.93  4884.5 1624.85  4900.3 1622.65
  4905.8 1621.28  4922.5 1619.45  4929.5 1618.09  4943.8 1616.69    4958 1614.06
    4990 1611.17  4990.3 1610.67  4993.8 1610.67    4994 1611.17  4997.7 1611.33
  5030.5 1611.72  5049.3 1613.67  5056.4 1613.55  5060.8  1614.1  5103.3 1615.18
  5192.7 1615.76  5227.4 1617.73  5244.7 1617.32  5256.5 1618.97  5283.6 1625.68
  5290.8 1627.95  5298.7 1629.49  5330.5 1630.99  5344.9 1632.87  5355.7  1633.3
#Mann= 4 ,-1 , 0
  4837.1     .07       0    4990    .035       0    4994     .07       0
  4997.7    .035       0
Bank Sta=4990,4994
XS Rating Curve= 0 ,0
Exp/Cntr=0.3,0.1

Type RM Length L Ch R = 1 ,13293   ,482,482,482
BEGIN DESCRIPTION:
Stream0557 26.0
END DESCRIPTION:
XS GIS Cut Line= 3
      1975624.98     13900624.98        1975375.       13900325.
      1975075.02     13900225.01
#Sta/Elev= 30
  4609.1 1630.19  4640.3 1627.72  4649.7 1626.31  4660.2 1623.76  4684.5 1621.16
  4704.9 1617.28  4715.5 1617.27  4743.2 1614.48  4817.3 1610.39  4856.3 1608.11
  4941.3 1605.14  4977.5 1602.26  4996.8  1601.8  4997.1  1601.3  5000.6  1601.3
  5000.8  1601.8  5009.6 1602.68  5041.4 1606.12  5101.1 1607.61  5120.8  1608.8
  5127.1  1609.9  5136.6 1609.49  5162.4 1613.39  5188.5 1614.05  5206.2 1616.37
  5209.3 1617.53  5244.1 1622.87  5259.9 1623.68  5285.2 1627.29  5315.8 1629.55
#Mann= 6 ,-1 , 0
  4609.1     .07       0  4817.3    .035       0  4996.8    .035       0
  5000.8    .035       0  5009.6     .07       0  5101.1    .035       0
Bank Sta=4996.8,5000.8
XS Rating Curve= 0 ,0
Exp/Cntr=0.3,0.1

Type RM Length L Ch R = 1 ,12811   ,471,471,471
BEGIN DESCRIPTION:
Stream0557 25.0
END DESCRIPTION:
XS GIS Cut Line= 3
      1975725.02     13899975.01        1975475.       13899875.
      1975175.03     13899675.02
#Sta/Elev= 30
  4730.2 1613.86  4757.1 1612.55    4769 1610.54    4794 1603.78  4817.5 1600.83
  4837.2 1600.05  4888.5 1597.65  4974.1 1595.06    4980 1594.21  4985.9 1593.87
  4986.2 1593.37  4989.7 1593.37  4989.9 1593.87  5005.9 1595.75  5042.7 1598.44
  5111.9 1599.91  5151.9 1602.56  5164.1 1604.15  5171.3 1603.18  5182.2 1606.16
  5203.1 1607.66  5220.4 1611.15  5239.8 1612.22  5261.5 1615.91  5272.3 1619.05
  5293.9 1622.06  5297.5 1622.01  5319.2 1624.57  5335.1 1627.68    5360 1629.23
#Mann= 7 ,-1 , 0
  4730.2     .07       0  4837.2    .035       0    4980     .07       0
  4985.9     .05       0  4989.9     .07       0  5151.9    .035       0
  5297.5     .07       0
Bank Sta=4985.9,4989.9
XS Rating Curve= 0 ,0
Exp/Cntr=0.3,0.1

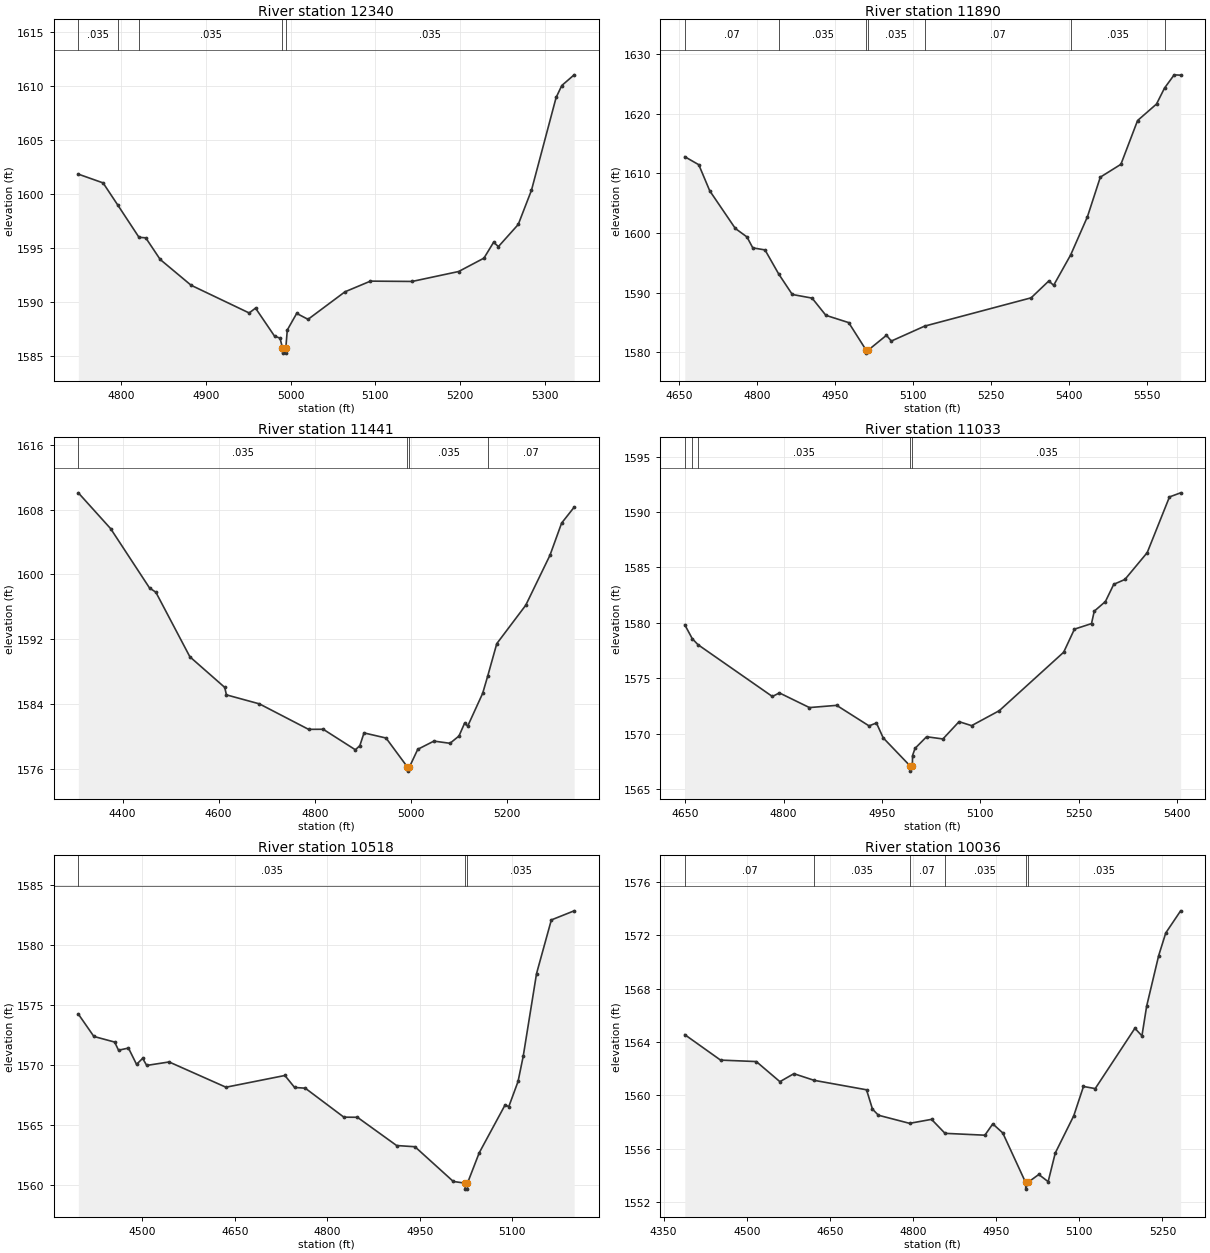
Type RM Length L Ch R = 1 ,12340   ,450,450,450
BEGIN DESCRIPTION:
Stream0557 24.0
END DESCRIPTION:
XS GIS Cut Line= 3
      1975825.01     13899675.01        1975675.       13899475.
      1975375.02     13899325.01
#Sta/Elev= 30
  4749.5 1601.83  4778.7 1601.02  4796.3 1598.94  4821.1 1595.98  4829.1 1595.93
  4846.1 1593.93  4882.6 1591.54  4951.2 1588.97  4958.7 1589.42  4981.2 1586.82
  4987.6 1586.64  4990.5 1585.75  4990.7 1585.25  4994.2 1585.25  4994.5 1585.75
  4996.2 1587.39  5007.3 1588.93  5020.7 1588.38  5064.3 1590.93  5094.4 1591.92
  5143.6 1591.89  5198.5 1592.81  5228.4 1594.05  5239.8 1595.52  5245.5 1595.12
  5268.9 1597.17  5284.5 1600.34  5313.6 1608.93  5320.3 1610.04  5334.9 1611.03
#Mann= 5 ,-1 , 0
  4749.5    .035       0  4796.3     .07       0  4821.1    .035       0
  4990.5    .035       0  4994.5    .035       0
Bank Sta=4990.5,4994.5
XS Rating Curve= 0 ,0
Exp/Cntr=0.3,0.1

Type RM Length L Ch R = 1 ,11890   ,449,449,449
BEGIN DESCRIPTION:
Stream0557 23.0
END DESCRIPTION:
XS GIS Cut Line= 3
      1976175.04     13899275.02        1975875.       13899125.
      1975275.02     13899274.99
#Sta/Elev= 30
  4660.4 1612.77  4687.3 1611.43  4708.4 1607.06  4757.6 1600.76    4780 1599.34
  4791.2 1597.51  4814.7 1597.17  4841.1 1593.13  4867.2 1589.71  4905.3  1589.1
  4931.8 1586.22  4975.7    1585  5009.3 1580.39  5009.6 1579.89  5013.3 1580.39
  5048.4 1582.88  5057.7 1581.91  5121.8 1584.41  5326.7 1589.15  5360.7 1591.97
    5370 1591.24  5402.8 1596.34    5435 1602.72  5459.8 1609.35  5499.4  1611.5
  5531.5 1618.83  5567.9 1621.59  5583.3 1624.26  5601.9 1626.48  5614.3 1626.42
#Mann= 7 ,-1 , 0
  4660.4     .07       0  4841.1    .035       0  5009.3    .035       0
  5013.3    .035       0  5121.8     .07       0  5402.8    .035       0
  5583.3     .07       0
Bank Sta=5009.3,5013.3
XS Rating Curve= 0 ,0
Exp/Cntr=0.3,0.1

Type RM Length L Ch R = 1 ,11441   ,408,408,408
BEGIN DESCRIPTION:
Stream0557 22.0
END DESCRIPTION:
XS GIS Cut Line= 4
      1976325.01       13899025.      1975809.85     13898701.74
        1975725.       13898725.      1975424.98     13898875.01
#Sta/Elev= 30
    4308 1610.06  4375.3 1605.64  4456.2 1598.33  4469.3 1597.81  4540.1 1589.85
  4612.6 1586.08  4616.1 1585.16  4684.7 1584.05    4787 1580.91  4817.5 1580.92
  4884.4 1578.39  4893.7  1578.9  4902.4 1580.47  4948.2 1579.84  4992.8 1576.26
  4993.1 1575.76  4996.8 1576.26  5014.2 1578.45  5047.8 1579.46  5081.3 1579.19
    5100 1580.09  5111.5 1581.65  5118.2 1581.32  5149.2 1585.34  5159.8 1587.49
  5178.6 1591.47  5238.9 1596.21  5289.3 1602.37  5313.5 1606.33  5339.6 1608.29
#Mann= 4 ,-1 , 0
    4308    .035       0  4992.8    .035       0  4996.8    .035       0
  5159.8     .07       0
Bank Sta=4992.8,4996.8
XS Rating Curve= 0 ,0
Exp/Cntr=0.3,0.1

Type RM Length L Ch R = 1 ,11033   ,515,515,515
BEGIN DESCRIPTION:
Stream0557 21.0
END DESCRIPTION:
XS GIS Cut Line= 4
      1976024.98     13898474.99      1975775.77     13898308.84
      1975676.31     13898323.69      1975424.99     13898575.01
#Sta/Elev= 30
  4649.6 1579.83    4661 1578.58  4669.7 1578.04    4783 1573.37  4793.8 1573.69
  4839.5 1572.37    4881 1572.57  4930.3 1570.72  4941.6 1570.98  4951.9 1569.64
  4992.4 1567.14  4992.6 1566.64  4996.4 1567.14  4996.6 1568.04  5000.4 1568.69
    5018 1569.74  5042.9 1569.54  5067.5  1571.1  5086.6 1570.74  5128.8 1572.09
  5226.9 1577.36  5243.3 1579.44  5269.3 1579.94  5273.5 1581.06  5290.5 1581.93
  5303.2 1583.48  5320.2 1583.92  5354.2 1586.34  5388.1 1591.36  5405.1 1591.73
#Mann= 5 ,-1 , 0
  4649.6    .035       0    4661     .07       0  4669.7    .035       0
  4992.4    .035       0  4996.4    .035       0
Bank Sta=4992.4,4996.4
XS Rating Curve= 0 ,0
Exp/Cntr=0.3,0.1

Type RM Length L Ch R = 1 ,10518   ,482,482,482
BEGIN DESCRIPTION:
Stream0557 20.0
END DESCRIPTION:
XS GIS Cut Line= 3
      1976074.99     13898124.99        1975525.       13897875.
      1975325.04       13897875.
#Sta/Elev= 30
  4396.3 1574.26  4421.5 1572.39  4455.2 1571.92  4461.5 1571.24  4477.6 1571.42
  4490.7 1570.06  4500.6 1570.56  4507.2 1569.97  4543.5 1570.26  4635.7 1568.15
  4731.3 1569.13    4747 1568.13  4764.3 1568.07  4826.9 1565.65  4848.9 1565.64
  4912.5 1563.28  4942.2 1563.18  5004.4 1560.28  5023.4 1560.14  5023.7 1559.64
  5027.2 1559.64  5027.4 1560.14  5046.4 1562.67  5088.4 1566.67  5094.4 1566.53
  5109.4 1568.63  5117.8 1570.74  5139.4 1577.64  5163.4 1582.12  5200.4 1582.88
#Mann= 3 ,-1 , 0
  4396.3    .035       0  5023.4    .035       0  5027.4    .035       0
Bank Sta=5023.4,5027.4
XS Rating Curve= 0 ,0
Exp/Cntr=0.3,0.1

Type RM Length L Ch R = 1 ,10036   ,456,456,456
BEGIN DESCRIPTION:
Stream0557 19.0
END DESCRIPTION:
XS GIS Cut Line= 4
      1976052.88     13897686.12      1975724.61     13897437.48
        1975525.       13897425.      1975325.03     13897624.97
#Sta/Elev= 30
  4388.3 1564.55  4452.8 1562.64  4517.3 1562.53  4559.9 1561.02  4585.1 1561.62
  4621.7 1561.12  4716.2 1560.41  4726.9 1558.96  4737.6  1558.5  4793.9 1557.89
  4833.5 1558.19  4857.8 1557.14  4929.7    1557    4944 1557.85    4962 1557.17
  5003.2 1553.45  5003.5 1552.95  5007.2 1553.45    5027 1554.05  5043.9 1553.51
  5056.7 1555.66  5090.1 1558.46  5107.6 1560.66  5128.8  1560.5  5200.4 1565.03
  5213.1 1564.46  5221.6 1566.69  5243.3 1570.49  5256.1 1572.19  5282.9 1573.85
#Mann= 6 ,-1 , 0
  4388.3     .07       0  4621.7    .035       0  4793.9     .07       0
  4857.8    .035       0  5003.2    .035       0  5007.2    .035       0
Bank Sta=5003.2,5007.2
XS Rating Curve= 0 ,0
Exp/Cntr=0.3,0.1

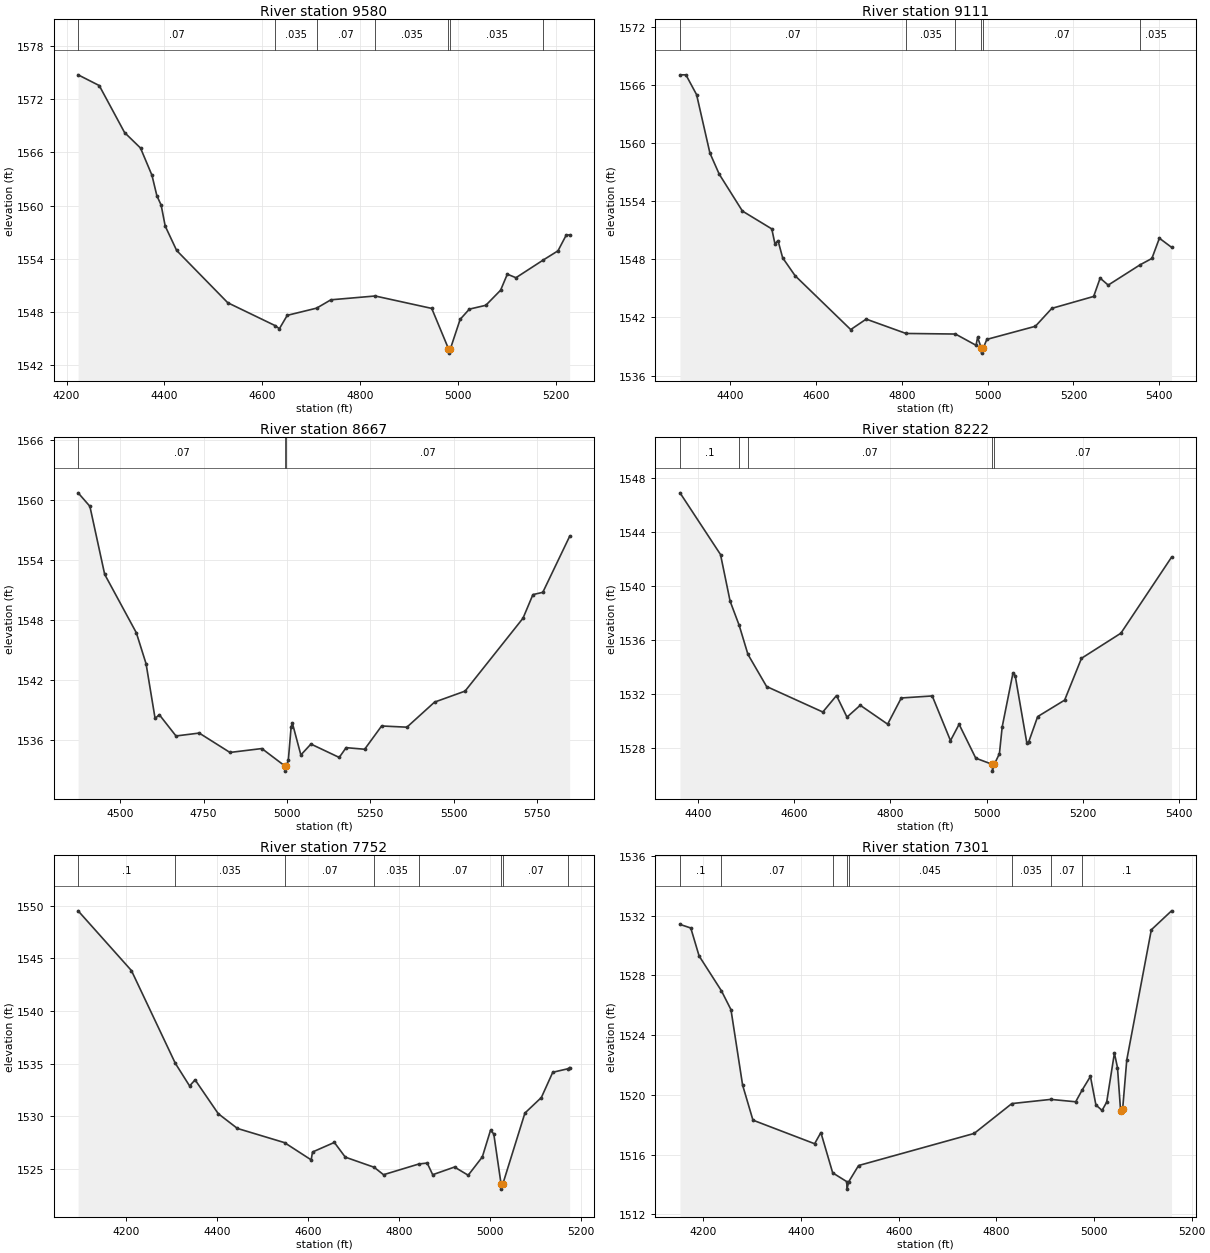
Type RM Length L Ch R = 1 ,9580    ,469,469,469
BEGIN DESCRIPTION:
Stream0557 18.0
END DESCRIPTION:
XS GIS Cut Line= 3
        1975975.       13896525.        1975375.       13897025.
      1975275.02     13897224.97
#Sta/Elev= 30
  4223.6 1574.73  4266.8 1573.52  4318.6 1568.22  4351.1 1566.48  4374.5 1563.41
  4384.5 1561.11  4393.3 1560.04  4401.6 1557.68    4425 1554.93  4529.4 1549.04
  4626.3 1546.46  4634.9 1546.11    4651 1547.62    4711 1548.43  4740.2 1549.37
  4830.7  1549.8  4946.3  1548.4  4980.5 1543.86  4980.7 1543.36  4984.5 1543.86
  5004.4 1547.17  5023.2 1548.32  5056.8 1548.75    5087 1550.45  5100.8 1552.26
  5118.4 1551.86  5174.3 1553.86  5204.3 1554.89  5221.1 1556.66  5228.2 1556.69
#Mann= 7 ,-1 , 0
  4223.6     .07       0  4626.3    .035       0    4711     .07       0
  4830.7    .035       0  4980.5    .035       0  4984.5    .035       0
  5174.3     .07       0
Bank Sta=4980.5,4984.5
XS Rating Curve= 0 ,0
Exp/Cntr=0.3,0.1

Type RM Length L Ch R = 1 ,9111    ,444,444,444
BEGIN DESCRIPTION:
Stream0557 17.0
END DESCRIPTION:
XS GIS Cut Line= 3
      1975675.04     13896274.98        1975075.       13896675.
      1974775.01     13896974.99
#Sta/Elev= 30
  4283.3 1567.03  4297.1 1567.03    4322 1564.98    4353 1558.96  4374.7 1556.78
  4428.8 1552.97  4497.2 1551.13  4504.5  1549.6  4511.7 1549.92  4522.5 1548.15
  4551.5  1546.3  4681.1 1540.74  4717.2 1541.82  4809.9 1540.34  4925.2 1540.28
  4973.1 1539.12  4976.8 1539.94  4985.6 1538.81  4985.9 1538.31  4989.6 1538.81
  4998.4 1539.73  5111.4 1541.08  5149.8 1542.93  5247.2 1544.16  5262.3 1546.05
  5281.1 1545.33  5355.6 1547.43  5382.9 1548.08  5400.4 1550.17  5428.7 1549.23
#Mann= 6 ,-1 , 0
  4283.3     .07       0  4809.9    .035       0  4925.2     .07       0
  4985.6     .05       0  4989.6     .07       0  5355.6    .035       0
Bank Sta=4985.6,4989.6
XS Rating Curve= 0 ,0
Exp/Cntr=0.3,0.1

Type RM Length L Ch R = 1 ,8667    ,445,445,445
BEGIN DESCRIPTION:
Stream0557 16.0
END DESCRIPTION:
XS GIS Cut Line= 3
      1975375.01       13896025.        1974825.       13896325.
      1974225.02     13896924.98
#Sta/Elev= 30
  4373.5 1560.72  4408.8 1559.37  4453.2 1552.56  4548.2 1546.71  4577.4 1543.61
  4604.5 1538.13  4617.1 1538.51  4667.2 1536.38  4736.9 1536.67  4829.1 1534.73
  4924.8 1535.12  4994.6 1533.36  4994.8 1532.86  4998.6 1533.36  5004.2 1533.94
  5012.7 1537.29  5016.5 1537.66  5041.9 1534.48  5072.1 1535.57    5157 1534.23
  5177.7 1535.21  5233.3 1535.05  5284.2 1537.38  5360.1 1537.26  5443.1 1539.77
  5534.6 1540.87  5708.5 1548.17  5738.2 1550.53  5767.9 1550.76  5848.5 1556.37
#Mann= 3 ,-1 , 0
  4373.5     .07       0  4994.6     .05       0  4998.6     .07       0
Bank Sta=4994.6,4998.6
XS Rating Curve= 0 ,0
Exp/Cntr=0.3,0.1

Type RM Length L Ch R = 1 ,8222    ,470,470,470
BEGIN DESCRIPTION:
Stream0557 15.0
END DESCRIPTION:
XS GIS Cut Line= 3
        1975125.       13895825.        1974525.       13896025.
      1974225.05     13896274.96
#Sta/Elev= 30
  4362.1 1546.91  4446.4 1542.34  4466.4 1538.88  4485.3 1537.09  4503.5 1534.94
  4542.3 1532.56  4659.3 1530.67  4687.8 1531.89  4709.6 1530.29  4737.2 1531.17
  4794.2 1529.77  4822.6 1531.71    4887 1531.86    4925 1528.55  4942.9 1529.76
  4977.6 1527.25  5012.1 1526.79  5012.3 1526.29  5016.1 1526.79  5026.8 1527.58
  5032.6 1529.57  5054.9 1533.54  5059.6 1533.37  5083.7 1528.41  5087.7 1528.45
  5106.4 1530.33  5162.5 1531.55  5197.6 1534.65  5279.6 1536.51    5385 1542.14
#Mann= 5 ,-1 , 0
  4362.1      .1       0  4485.3    .035       0  4503.5     .07       0
  5012.1     .05       0  5016.1     .07       0
Bank Sta=5012.1,5016.1
XS Rating Curve= 0 ,0
Exp/Cntr=0.3,0.1

Type RM Length L Ch R = 1 ,7752    ,451,451,451
BEGIN DESCRIPTION:
Stream0557 14.0
END DESCRIPTION:
XS GIS Cut Line= 3
      1975174.97       13895775.        1974275.       13895725.
      1974125.03     13895824.98
#Sta/Elev= 30
  4094.3 1549.53  4211.6 1543.85  4308.1 1535.04  4339.6 1532.88  4351.7 1533.46
  4402.7 1530.24  4444.8 1528.84  4548.5 1527.49  4607.1 1525.85  4610.1  1526.6
  4658.1 1527.51  4682.2 1526.11  4745.6 1525.15  4766.3 1524.44  4844.1 1525.46
  4862.4 1525.55  4874.5 1524.44  4922.5 1525.17  4952.6 1524.39  4983.7 1526.13
  5001.7 1528.66  5008.9 1528.32  5024.9 1523.57  5025.1 1523.07  5028.9 1523.57
  5077.4  1530.3  5113.6 1531.78  5138.7 1534.18  5172.6 1534.52  5175.9 1534.63
#Mann= 8 ,-1 , 0
  4094.3      .1       0  4308.1    .035       0  4548.5     .07       0
  4745.6    .035       0  4844.1     .07       0  5024.9     .05       0
  5028.9     .07       0  5172.6      .1       0
Bank Sta=5024.9,5028.9
XS Rating Curve= 0 ,0
Exp/Cntr=0.3,0.1

Type RM Length L Ch R = 1 ,7301    ,445,445,445
BEGIN DESCRIPTION:
Stream0557 13.0
END DESCRIPTION:
XS GIS Cut Line= 3
      1974824.99     13894725.01        1974225.       13895325.
      1974075.03     13895374.99
#Sta/Elev= 30
  4152.1 1531.42  4174.2 1531.18  4191.2 1529.31    4237 1526.97  4256.5 1525.71
  4280.3 1520.66  4301.5 1518.31  4427.8 1516.73  4440.6 1517.48  4464.8 1514.78
  4493.7 1514.19    4494 1513.69  4497.7 1514.19  4517.8 1515.27  4754.5 1517.42
  4831.7 1519.42  4911.4  1519.7  4962.4 1519.54  4975.7 1520.33  4992.6 1521.24
  5003.8 1519.33  5016.4 1518.96  5025.9 1519.52  5041.7  1522.8    5048 1521.83
  5054.4 1518.93 5058.59 1519.06    5067 1522.34  5117.3 1531.06  5158.7 1532.33
#Mann= 8 ,-1 , 0
  4152.1      .1       0    4237     .07       0  4464.8    .045       0
  4493.7     .05       0  4497.7    .045       0  4831.7    .035       0
  4911.4     .07       0  4975.7      .1       0
#Block Obstruct= 2 , 0
         4784.02 1518.43 5058.13         1518.98
Bank Sta=5054.4,5058.59
XS Rating Curve= 0 ,0
Exp/Cntr=0.3,0.1