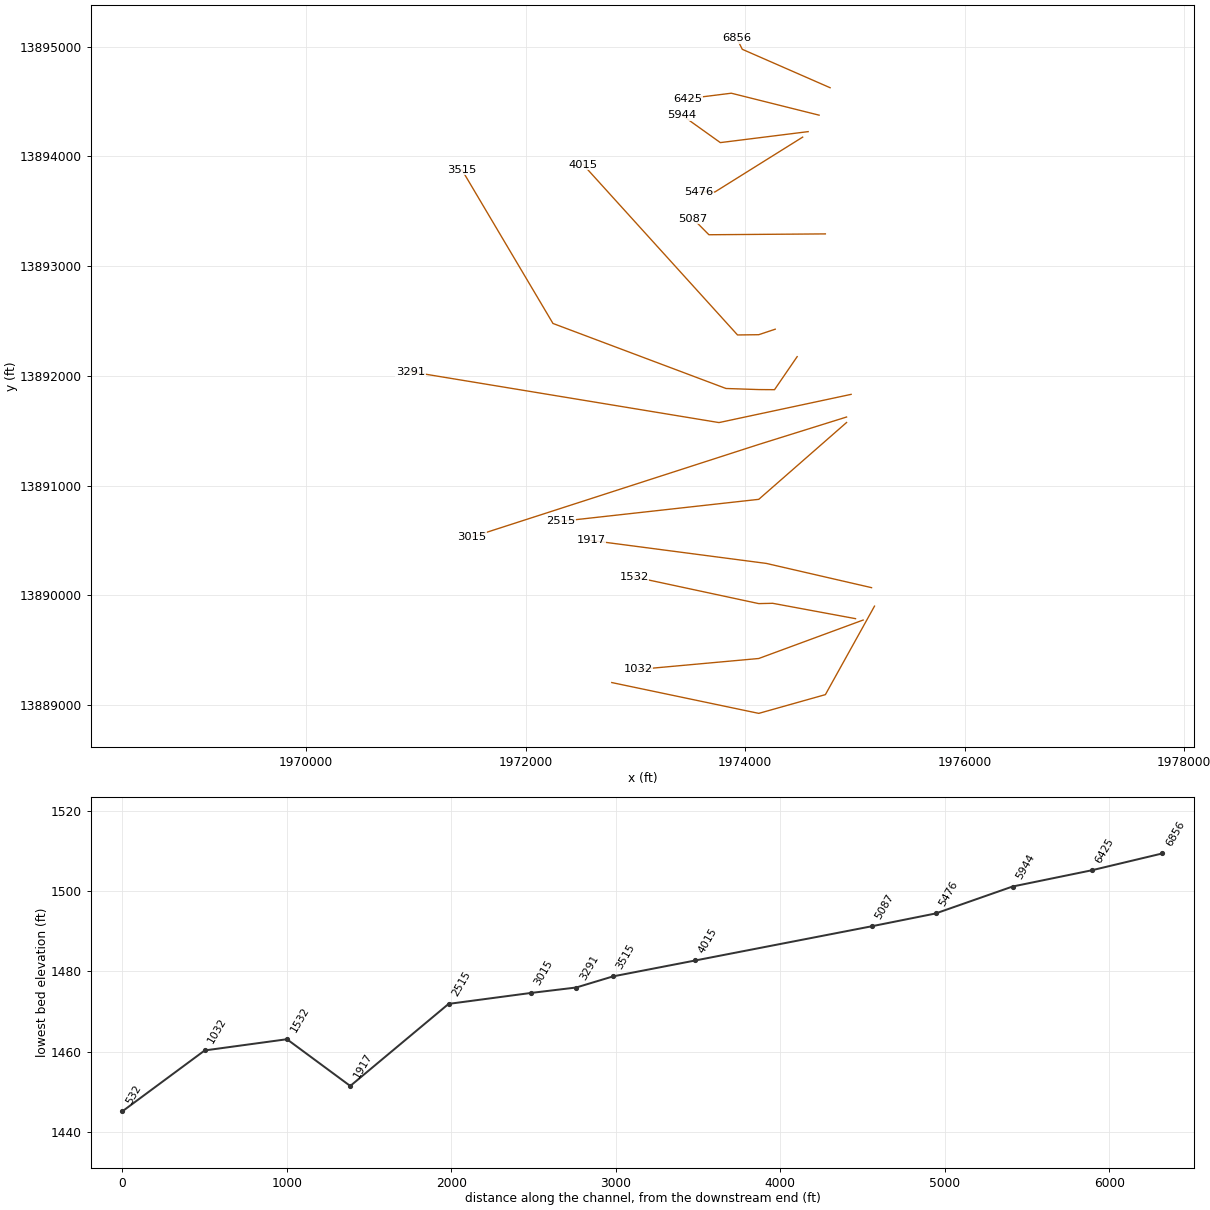
HEC-RAS study Stream0557.prj: Stream0557 Base Level Engineering

--- Stream0557.g01 (geometry) --- (continued)

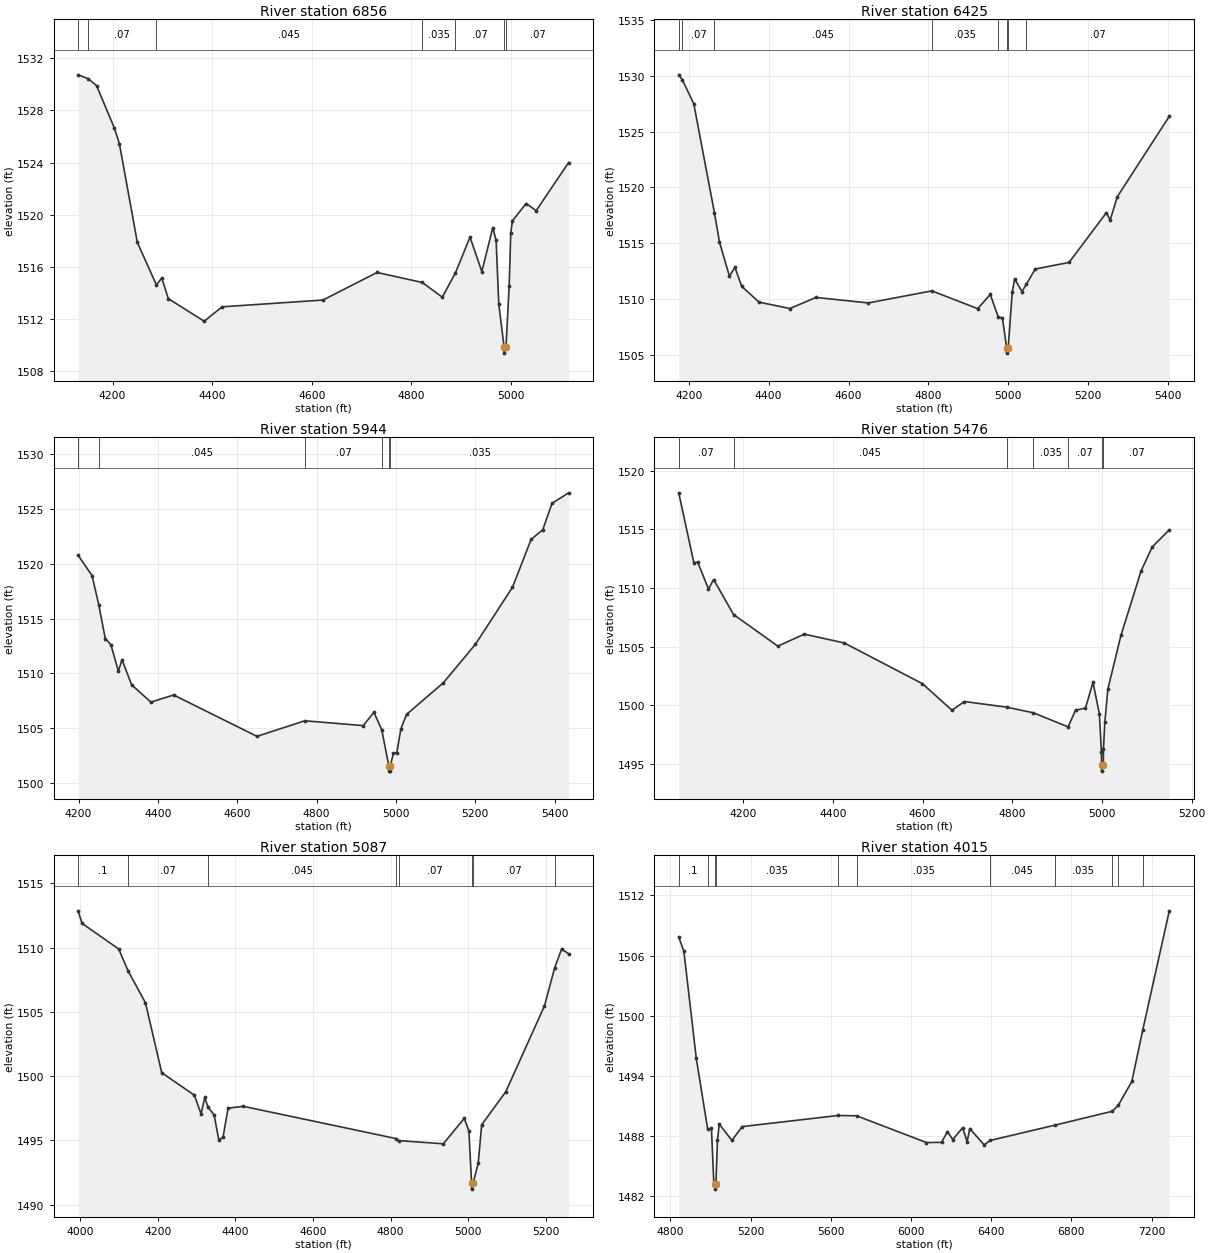
Type RM Length L Ch R = 1 ,6856    ,431,431,431
BEGIN DESCRIPTION:
Stream0557 12.0
END DESCRIPTION:
XS GIS Cut Line= 3
      1974775.01     13894624.99        1973975.       13894975.
      1973925.01     13895074.97
#Sta/Elev= 30
  4130.7 1530.74  4150.6 1530.45  4167.8 1529.91  4203.8 1526.63  4213.7 1525.44
  4249.7 1517.86    4288 1514.59  4298.8 1515.12  4311.9 1513.54  4383.9  1511.8
    4420 1512.91  4622.5 1513.43    4731 1515.55  4821.9 1514.78    4862 1513.65
  4888.5 1515.52  4917.7 1518.27  4941.4 1515.62  4963.5    1519  4970.1 1518.01
  4975.5  1513.1    4986 1509.85  4986.3 1509.35    4990 1509.85  4996.3 1514.51
  4999.6 1518.61  5002.8 1519.51  5030.3 1520.85  5050.5  1520.3  5115.7    1524
#Mann= 7 ,-1 , 0
  4130.7      .1       0  4150.6     .07       0    4288    .045       0
  4821.9    .035       0  4888.5     .07       0    4986     .05       0
    4990     .07       0
Bank Sta=4986,4990
XS Rating Curve= 0 ,0
Exp/Cntr=0.3,0.1

Type RM Length L Ch R = 1 ,6425    ,481,481,481
BEGIN DESCRIPTION:
Stream0557 11.0
END DESCRIPTION:
XS GIS Cut Line= 3
      1974674.98     13894375.01        1973875.       13894575.
      1973475.01       13894525.
#Sta/Elev= 30
    4175 1530.09    4184 1529.65  4212.6  1527.5  4264.4 1517.71    4277 1515.09
  4301.8 1512.05  4315.7 1512.83  4332.7 1511.12    4376 1509.71  4453.3 1509.14
  4518.2 1510.13  4649.6 1509.64  4808.2 1510.72  4923.3 1509.13  4954.7  1510.4
  4974.3 1508.41  4985.2 1508.28  4995.5 1505.64  4995.7 1505.14  4999.6 1505.64
  5009.7 1510.65  5015.7 1511.79  5033.9 1510.66  5045.2 1511.32  5067.1 1512.68
  5151.8 1513.27  5245.5 1517.74  5254.6 1517.06  5272.7 1519.17  5402.7 1526.37
#Mann= 8 ,-1 , 0
    4175      .1       0    4184     .07       0  4264.4    .045       0
  4808.2    .035       0  4974.3     .07       0  4995.5    .035       0
  4999.6     .07       0  5045.2     .07       0
Bank Sta=4995.5,4999.6
XS Rating Curve= 0 ,0
Exp/Cntr=0.3,0.1

Type RM Length L Ch R = 1 ,5944    ,468,468,468
BEGIN DESCRIPTION:
Stream0557 10.0
END DESCRIPTION:
XS GIS Cut Line= 3
      1974574.98       13894225.        1973775.       13894125.
      1973425.02     13894374.99
#Sta/Elev= 30
  4198.8 1520.78    4234 1518.93    4251 1516.26  4267.3 1513.19  4281.5 1512.63
  4300.3 1510.22  4309.6 1511.25  4333.8 1508.97  4382.2 1507.39  4439.6 1508.04
  4649.7 1504.27  4770.3 1505.69  4917.3 1505.25  4944.5 1506.46  4964.3 1504.85
  4981.8  1501.6    4982  1501.1  4985.6  1501.1  4985.9  1501.6  4993.7 1502.75
    5002 1502.76  5012.4 1504.96  5026.7 1506.27  5119.3 1509.15  5200.4 1512.67
  5293.6 1517.86  5340.5 1522.22    5370 1523.11  5393.2 1525.51  5435.1 1526.47
#Mann= 6 ,-1 , 0
  4198.8     .07       0    4251    .045       0  4770.3     .07       0
  4964.3    .035       0  4981.8    .035       0  4985.9    .035       0
Bank Sta=4981.8,4985.9
XS Rating Curve= 0 ,0
Exp/Cntr=0.3,0.1

Type RM Length L Ch R = 1 ,5476    ,389,389,389
BEGIN DESCRIPTION:
Stream0557 9.0
END DESCRIPTION:
XS GIS Cut Line= 3
      1974524.99     13894174.99        1973725.       13893675.
      1973574.99       13893675.
#Sta/Elev= 30
  4056.6  1518.1  4090.2 1512.16  4098.9 1512.19  4122.9 1509.91  4134.4 1510.71
  4178.8 1507.73  4277.5 1505.04  4336.5 1506.06  4425.5 1505.31  4599.7 1501.84
  4665.5 1499.58  4693.4 1500.32  4787.4 1499.84    4847 1499.36  4924.5 1498.16
    4941 1499.58  4963.2 1499.76  4979.9 1501.96  4994.1 1499.27  4998.8 1495.98
  4998.9 1494.89  4999.2 1494.39    5003 1494.89  5003.3  1496.3  5006.3 1498.55
    5013 1501.37  5042.3 1505.96  5087.3 1511.46    5112 1513.49    5150 1514.95
#Mann= 7 ,-1 , 0
  4056.6     .07       0  4178.8    .045       0  4787.4     .07       0
    4847    .035       0  4924.5     .07       0  4998.9     .05       0
    5003     .07       0
Bank Sta=4998.9,5003
XS Rating Curve= 0 ,0
Exp/Cntr=0.3,0.1

Type RM Length L Ch R = 1 ,5087    ,1072,1072,1072
BEGIN DESCRIPTION:
Stream0557 8.1
END DESCRIPTION:
XS GIS Cut Line= 3
      1974731.84     13893293.24      1973670.87     13893285.61
      1973527.17     13893430.55
#Sta/Elev= 30
  3994.1 1512.87  4004.4 1511.89  4098.9  1509.9  4123.1 1508.19  4167.9 1505.71
  4209.9 1500.26  4293.9 1498.52  4311.3 1497.06  4320.9 1498.35  4329.1 1497.58
  4344.9 1496.99  4356.9 1495.05  4367.9 1495.23  4380.9  1497.5  4419.9 1497.65
  4813.7 1495.14  4820.5 1494.98    4936 1494.73    4990 1496.71    5002 1495.73
  5008.9  1491.7  5009.2  1491.2  5013.1  1491.7    5026 1493.21    5035 1496.21
  5097.4  1498.8  5196.9 1505.47  5223.3 1508.44    5241 1509.89  5259.2 1509.53
#Mann= 8 ,-1 , 0
  3994.1      .1       0  4123.1     .07       0  4329.1    .045       0
  4813.7    .035       0  4820.5     .07       0  5008.9     .05       0
  5013.1     .07       0  5223.3      .1       0
Bank Sta=5008.9,5013.1
XS Rating Curve= 0 ,0
Exp/Cntr=0.3,0.1

Type RM Length L Ch R = 1 ,4015    ,500,500,500
BEGIN DESCRIPTION:
Stream0557 8.0
END DESCRIPTION:
XS GIS Cut Line= 4
      1974274.99       13892425.        1974125.       13892375.
      1973931.55      13892372.6      1972525.01     13893924.99
#Sta/Elev= 30
  4841.9 1507.84  4867.5 1506.44  4929.4 1495.74  4986.3 1488.67    5005 1488.75
    5017 1483.26  5022.6 1483.19  5022.9 1482.69  5027.3 1483.19    5035 1487.55
    5044 1489.18    5107 1487.55    5158 1488.93  5636.4 1490.04    5729 1490.01
  6077.4 1487.34  6152.5 1487.36  6182.2 1488.43  6208.5 1487.64  6257.7 1488.82
    6280 1487.43  6293.4 1488.73  6364.8 1487.11  6395.5 1487.55  6716.2 1489.07
  7003.9 1490.46  7033.6 1491.05  7101.6 1493.44    7156 1498.59  7288.3 1510.47
#Mann= 11 ,-1 , 0
  4841.9      .1       0  4986.3    .035       0  5022.6    .035       0
  5027.3    .035       0  5636.4     .07       0    5729    .035       0
  6395.5    .045       0  6716.2    .035       0  7003.9     .07       0
  7033.6    .035       0    7156     .07       0
#Block Obstruct= 2 , 0
                         5653.85         1490.13
Bank Sta=5022.6,5027.3
XS Rating Curve= 0 ,0
Exp/Cntr=0.3,0.1

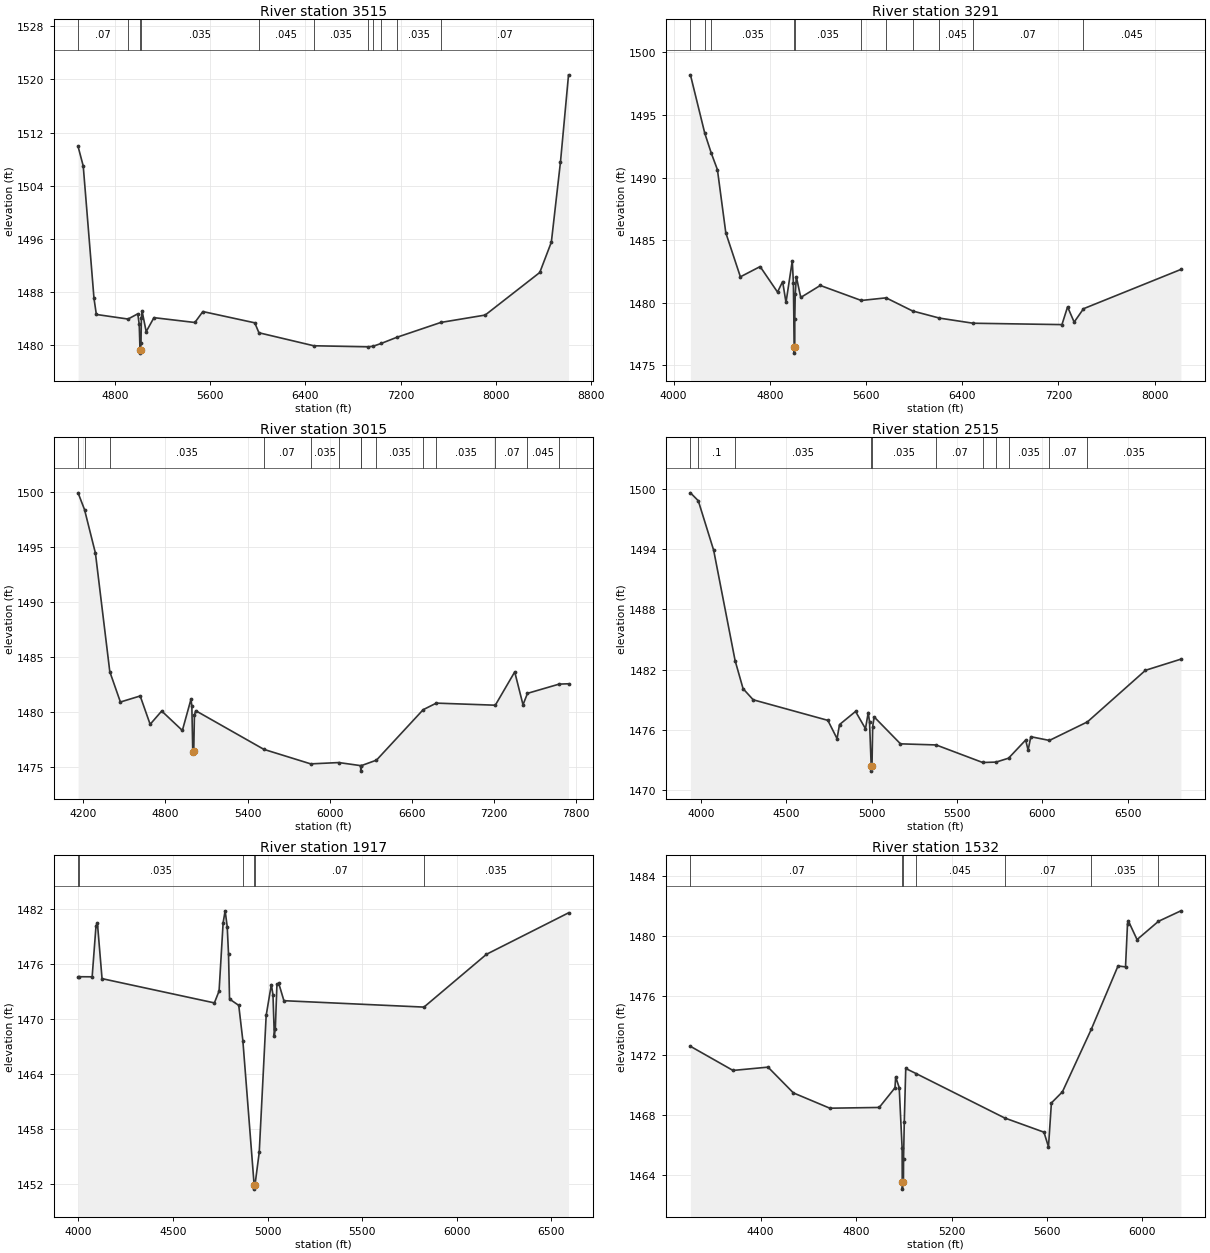
Type RM Length L Ch R = 1 ,3515    ,224,224,224
BEGIN DESCRIPTION:
Stream0557 7.0
END DESCRIPTION:
XS GIS Cut Line= 6
      1974475.01     13892175.02      1974268.64     13891874.01
        1974125.       13891875.       1973826.5     13891884.91
       1972250.2     13892477.32      1971420.01     13893877.73
#Sta/Elev= 30
  4491.4  1509.9  4534.8 1506.95  4625.2 1486.98  4644.9 1484.56  4910.8 1483.87
    4993 1484.66    5005 1483.06  5011.7 1479.23    5012 1478.73  5016.4 1479.23
    5020 1480.27    5023 1484.09  5029.4 1485.04  5063.5 1481.97  5128.7 1484.08
  5472.3 1483.35  5539.6    1485  5975.4  1483.3  6010.5  1481.8  6471.1 1479.84
  6930.5 1479.68  6969.5 1479.77  7038.7  1480.2    7166  1481.1  7538.6 1483.36
  7910.5 1484.47    8369 1490.89  8466.3 1495.47  8543.1 1507.59  8610.6  1520.7
#Mann= 11 ,-1 , 0
  4491.4     .07       0  4910.8    .035       0  5011.7    .035       0
  5016.4    .035       0  6010.5    .045       0  6471.1    .035       0
  6930.5     .07       0  6969.5    .035       0  7038.7     .07       0
    7166    .035       0  7538.6     .07       0
#Block Obstruct= 2 , 0
                         5218.78         1483.41
Bank Sta=5011.7,5016.4
XS Rating Curve= 0 ,0
Exp/Cntr=0.3,0.1

Type RM Length L Ch R = 1 ,3291    ,276,276,276
BEGIN DESCRIPTION:
Mapping XS ee7e924a
END DESCRIPTION:
XS GIS Cut Line= 3
      1974966.52     13891831.39      1973762.81      13891574.3
      1970952.02     13892037.72
#Sta/Elev= 30
  4139.5 1498.21  4258.9 1493.54  4313.3 1491.94    4364 1490.63  4433.8 1485.58
  4555.1 1482.06  4719.4 1482.88    4864 1480.84  4906.5 1481.68  4934.5 1480.01
  4986.7 1483.34  4995.9 1481.59  5002.8 1476.46  5003.1 1475.96  5007.5 1476.46
  5007.6  1478.7  5011.2 1480.65  5020.4 1482.07  5057.3 1480.41  5219.8 1481.37
  5560.7 1480.17  5766.9 1480.38  5987.5 1479.33  6211.2 1478.76  6490.8 1478.35
  7229.8 1478.24  7276.6 1479.66  7331.3 1478.44    7409 1479.51  8219.1 1482.65
#Mann= 11 ,-1 , 0
  4139.5    .035       0  4258.9      .1       0  4313.3    .035       0
  5002.8    .035       0  5007.5    .035       0  5560.7     .07       0
  5766.9    .035       0  5987.5     .07       0  6211.2    .045       0
  6490.8     .07       0    7409    .045       0
#Block Obstruct= 2 , 0
                         5148.85         1480.49
Bank Sta=5002.8,5007.5
XS Rating Curve= 0 ,0
Exp/Cntr=0.3,0.1

Type RM Length L Ch R = 1 ,3015    ,500,500,500
BEGIN DESCRIPTION:
Stream0557 6.0
END DESCRIPTION:
XS GIS Cut Line= 3
      1974925.05     13891625.01        1974125.       13891375.
      1971513.99     13890532.08
#Sta/Elev= 30
  4161.8 1499.93    4209  1498.4  4288.6 1494.44  4393.6 1483.65  4470.9 1480.89
  4615.5 1481.44  4688.2 1478.86  4772.6 1480.07  4923.5  1478.3  4986.4 1481.14
  4992.7 1480.52  4999.5 1476.37 5006.64 1476.43  5011.5  1479.7    5021  1480.1
    5519 1476.58  5860.8 1475.26    6066 1475.38    6226  1475.1  6226.3  1474.6
  6230.7  1475.1  6341.1  1475.6  6681.9 1480.19  6778.1 1480.79  7208.9  1480.6
  7350.7 1483.63  7411.2 1480.64  7443.9 1481.68  7675.1 1482.52  7743.7 1482.55
#Mann= 14 ,-1 , 0
  4161.8    .035       0    4209      .1       0  4393.6    .035       0
    5519     .07       0  5860.8    .035       0    6066     .07       0
    6226    .035       0  6230.7     .07       0  6341.1    .035       0
  6681.9     .07       0  6778.1    .035       0  7208.9     .07       0
  7443.9    .045       0  7675.1    .035       0
#Block Obstruct= 2 , 0
                         5054.94         1478.74
Bank Sta=4999.5,5006.64
XS Rating Curve= 0 ,0
Exp/Cntr=0.3,0.1

Type RM Length L Ch R = 1 ,2515    ,598,598,598
BEGIN DESCRIPTION:
Stream0557 5.0
END DESCRIPTION:
XS GIS Cut Line= 3
      1974924.99     13891574.99        1974125.       13890875.
      1972324.98       13890675.
#Sta/Elev= 30
    3937 1499.62  3983.1 1498.83  4073.3 1493.89  4198.8  1482.9  4245.5  1480.1
    4305 1478.99  4742.4 1476.94  4796.2 1475.12  4810.7 1476.52  4904.6 1477.83
  4962.8 1476.11    4979 1477.72  4986.7 1476.77  4996.3 1472.38  4996.6 1471.88
    5001 1472.38    5005 1476.32  5013.9 1477.28    5168  1474.6  5376.7 1474.49
  5649.6 1472.74    5728 1472.78  5801.3 1473.17  5901.5 1474.98  5915.8 1473.97
  5931.7 1475.31  6040.6 1474.94  6263.5 1476.79  6603.5 1481.93  6811.1 1483.04
#Mann= 11 ,-1 , 0
    3937    .035       0  3983.1      .1       0  4198.8    .035       0
  4996.3    .035       0    5001    .035       0  5376.7     .07       0
  5649.6    .035       0    5728     .07       0  5801.3    .035       0
  6040.6     .07       0  6263.5    .035       0
#Block Obstruct= 2 , 0
          4895.1 1476.59 5041.96         1475.99
Bank Sta=4996.3,5001
XS Rating Curve= 0 ,0
Exp/Cntr=0.3,0.1

Type RM Length L Ch R = 1 ,1917    ,385,385,385
BEGIN DESCRIPTION:
Stream0557 4.0
END DESCRIPTION:
XS GIS Cut Line= 3
      1975152.57      13890070.4      1974193.66     13890291.24
      1972597.71     13890500.37
#Sta/Elev= 30
  3997.8 1474.63  4003.4 1474.65  4072.3 1474.64  4092.7 1480.22  4100.2 1480.48
  4124.6 1474.44  4718.7 1471.79  4743.5 1473.09  4764.9 1480.55  4775.5 1481.85
  4786.5 1480.12  4793.3 1477.17  4798.8 1472.21  4847.5 1471.52  4869.2 1467.67
  4928.7 1451.94  4929.1 1451.44  4933.6 1451.94  4955.8 1455.45  4992.5 1470.42
  5019.8 1473.79  5028.5 1472.67  5035.5 1468.22    5041 1468.99  5049.4  1473.8
  5059.1 1473.92  5086.3 1472.03  5826.9 1471.33  6157.4  1477.1  6591.4 1481.63
#Mann= 6 ,-1 , 0
  3997.8     .07       0  4003.4    .035       0  4869.2     .07       0
  4928.7     .05       0  4933.6     .07       0  5826.9    .035       0
#Block Obstruct= 2 , 0
         4762.24 1473.61 5017.48         1473.19
Bank Sta=4928.7,4933.6
XS Rating Curve= 0 ,0
Exp/Cntr=0.3,0.1

Type RM Length L Ch R = 1 ,1532    ,500,500,500
BEGIN DESCRIPTION:
Stream0557 3.0
END DESCRIPTION:
XS GIS Cut Line= 4
      1975006.51     13889787.99      1974251.87     13889927.85
        1974125.       13889925.       1972989.3      13890168.5
#Sta/Elev= 30
  4105.6 1472.61  4284.1    1471  4430.9 1471.22  4537.3  1469.5  4689.9 1468.48
    4897 1468.53    4963 1469.84    4966 1470.57  4980.8 1469.85    4993  1465.8
  4993.5 1463.58  4993.9 1463.08  4998.5 1463.58    4999  1465.1    5002 1467.54
  5008.2 1471.13  5051.7 1470.79  5422.6 1467.83  5587.6 1466.88  5606.5  1465.9
  5618.7 1468.83  5664.8 1469.57    5786 1473.75  5897.9 1477.97  5929.4 1477.91
  5937.8  1480.8  5940.9 1480.99  5977.7 1479.73  6067.4 1480.95  6161.5 1481.65
#Mann= 7 ,-1 , 0
  4105.6     .07       0  4993.5     .05       0  4998.5     .07       0
  5051.7    .045       0  5422.6     .07       0    5786    .035       0
  6067.4     .07       0
Bank Sta=4993.5,4998.5
XS Rating Curve= 0 ,0
Exp/Cntr=0.3,0.1

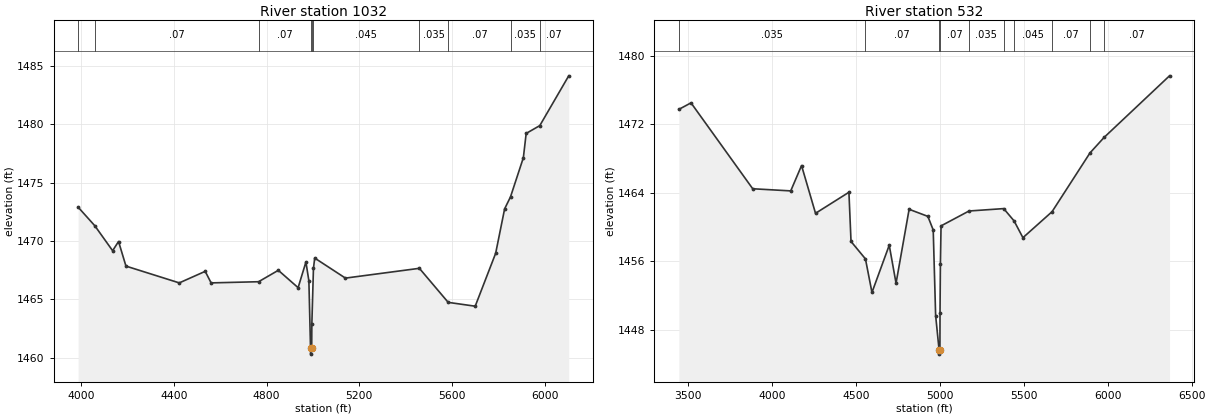
Type RM Length L Ch R = 1 ,1032    ,500,500,500
BEGIN DESCRIPTION:
Stream0557 2.0
END DESCRIPTION:
XS GIS Cut Line= 3
      1975075.93      13889775.3        1974125.       13889425.
      1973025.03       13889325.
#Sta/Elev= 30
  3986.6  1472.9  4058.9  1471.3  4135.7 1469.16  4161.3 1469.95  4193.3 1467.84
  4423.4  1466.4  4535.3 1467.39  4560.9  1466.4  4765.8  1466.5  4850.9 1467.48
  4936.4 1465.99  4970.1 1468.19  4982.9 1466.57    4990 1460.79  4990.4 1460.29
    4995 1460.79  4995.7 1462.88  5002.6 1467.64    5008 1468.53  5140.6 1466.81
  5459.8 1467.65  5584.2 1464.73  5700.8  1464.4  5789.1 1468.94  5827.8 1472.75
  5853.2 1473.78  5908.7 1477.14  5920.8 1479.22  5979.6 1479.89  6104.5 1484.16
#Mann= 10 ,-1 , 0
  3986.6    .035       0  4058.9     .07       0  4765.8     .07       0
    4990     .05       0    4995     .07       0  5002.6    .045       0
  5459.8    .035       0  5584.2     .07       0  5853.2    .035       0
  5979.6     .07       0
Bank Sta=4990,4995
XS Rating Curve= 0 ,0
Exp/Cntr=0.3,0.1

Type RM Length L Ch R = 1 ,532     ,0,0,0
BEGIN DESCRIPTION:
Stream0557 1.0
END DESCRIPTION:
XS GIS Cut Line= 4
      1975179.53     13889901.94      1974731.99     13889095.76
        1974125.       13888925.      1972785.94     13889205.76
#Sta/Elev= 30
  3447.3 1473.76  3519.7 1474.52    3887 1464.48  4113.3 1464.23  4177.7 1467.19
  4260.9 1461.61  4459.7 1464.07  4472.2 1458.32  4558.1 1456.28  4596.9 1452.36
  4699.7 1457.88  4740.2 1453.44  4818.1 1462.08  4929.7 1461.25  4961.5 1459.66
  4975.9 1449.66  4996.4 1445.65  4996.8 1445.15  5001.4 1445.65    5002 1449.91
  5004.3 1455.72  5008.1 1460.14  5174.6 1461.88  5381.1 1462.16  5442.9 1460.72
  5495.5 1458.76    5669  1461.8  5894.8 1468.67  5978.7 1470.48  6368.1 1477.68
#Mann= 10 ,-1 , 0
  3447.3    .035       0  4558.1     .07       0  4996.4     .05       0
  5001.4     .07       0  5174.6    .035       0  5381.1     .07       0
  5442.9    .045       0    5669     .07       0  5894.8    .035       0
  5978.7     .07       0
Bank Sta=4996.4,5001.4
XS Rating Curve= 0 ,0
Exp/Cntr=0.3,0.1

Chan Stop Cuts=-1
Use User Specified Reach Order=0
Composite Channel Slope=5