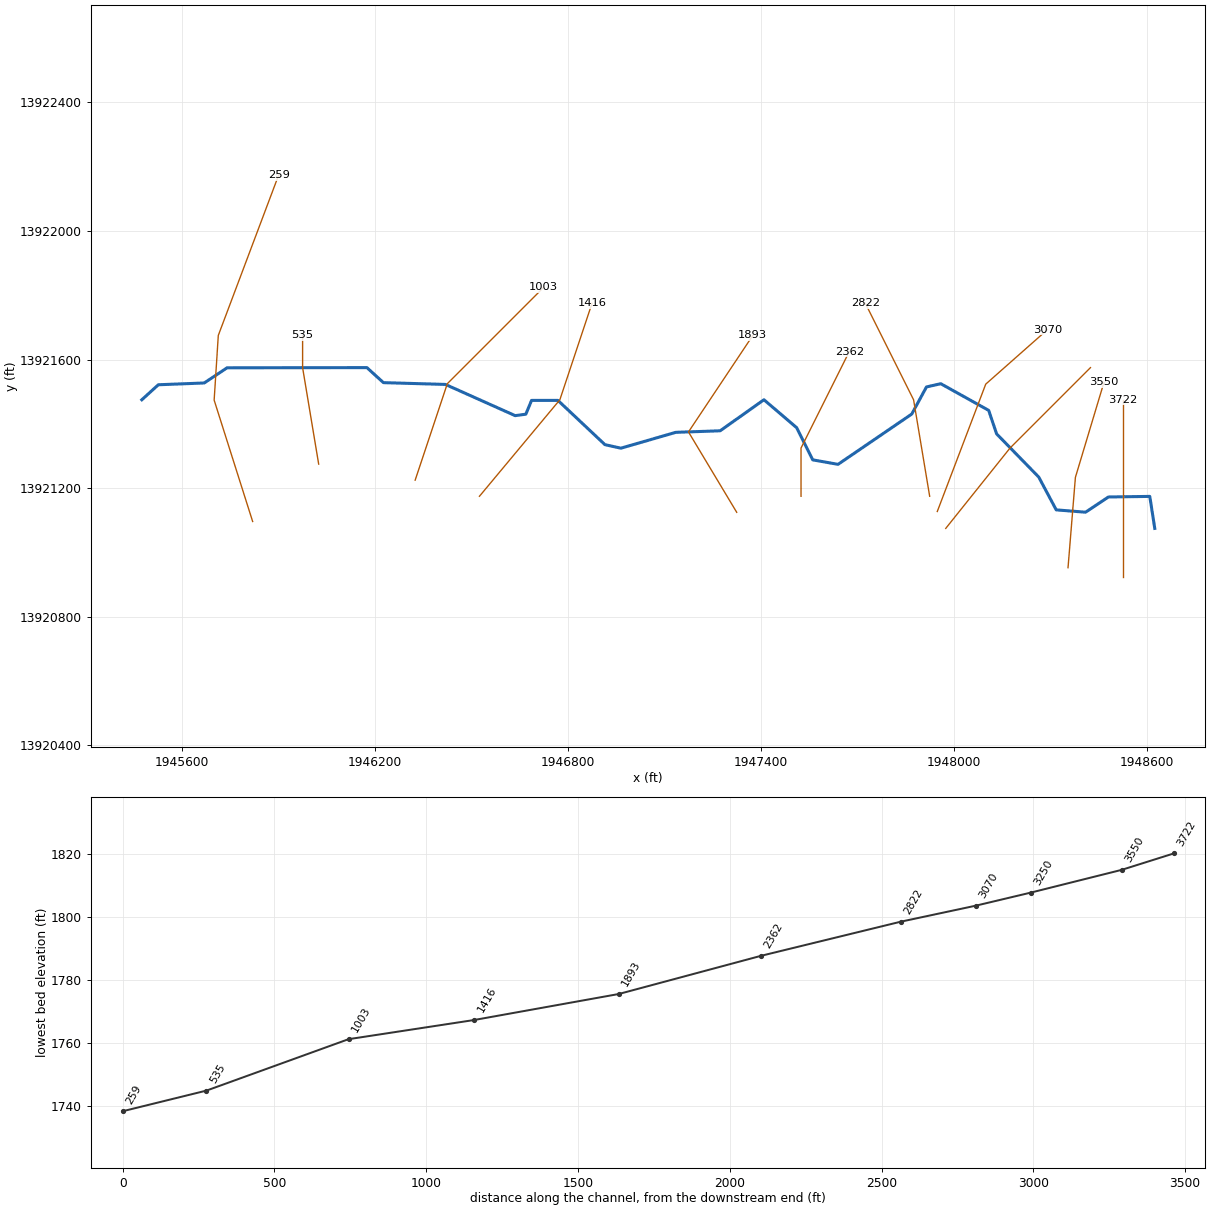
--- Stream0558.prj (project) ---

Proj Title=Stream0558 Base Level Engineering
Current Plan=p01
Default Exp/Contr=0.3,0.1
English Units
Geom File=g01
Flow File=f01
Plan File=p01
Y Axis Title=Elevation
X Axis Title(PF)=Main Channel Distance
X Axis Title(XS)=Station
BEGIN DESCRIPTION:
Stream0558
END DESCRIPTION:
DSS Export Rating Curves= 0
DSS Export Rating Curve Sorted= 0
DSS Export Volume Flow Curves= 0
DXF OffsetX= 0
DXF OffsetY= 0
DXF ScaleX= 1
DXF ScaleY= 10

--- Stream0558.p01 (plan) ---

Plan Title=Multiple Run
Short Identifier=Multiple
Geom File=g01
Flow File=f01
Subcritical Flow
K Sum by GR= 0
Std Step Tol= 0.01
Critical Tol= 0.01
Num of Std Step Trials= 20
Max Error Tol= 0.3
Flow Tol Ratio= 0.001
Split Flow NTrial= 30
Split Flow Tol= 0.02
Split Flow Ratio= 0.02
Log Output Level= 0
Friction Slope Method= 1
Unsteady Friction Slope Method= 2
Unsteady Bridges Friction Slope Method= 1
Parabolic Critical Depth
Global Vel Dist=  1 , 1 , 1
Global Log Level= 0
CheckData=True
Encroach Param= -1, 0, 0, 0
BEGIN DESCRIPTION:
Multiple Run
END DESCRIPTION:

--- Stream0558.f01 (steady flow) ---

Flow Title=Multiple
Program Version=4.10
Number of Profiles= 7
Profile Names=10-year,25-year,50-year,1pct_min,100-year,1pct_plu,500-year
River Rch & RM=Stream0558,Reach-1         ,3722
     411     657     879     573    1144    2282    1899
River Rch & RM=Stream0558,Reach-1         ,3250
     834    1400    1933    1295    2583    5155    4545
River Rch & RM=Stream0558,Reach-1         ,535
    1269    2194    3089    2107    4204    8388    7676
Boundary for River Rch & Prof#=Stream0558,Reach-1         , 1
Up Type= 0
Dn Type= 3
Dn Slope=0.008
Boundary for River Rch & Prof#=Stream0558,Reach-1         , 2
Up Type= 0
Dn Type= 3
Dn Slope=0.008
Boundary for River Rch & Prof#=Stream0558,Reach-1         , 3
Up Type= 0
Dn Type= 3
Dn Slope=0.008
Boundary for River Rch & Prof#=Stream0558,Reach-1         , 4
Up Type= 0
Dn Type= 3
Dn Slope=0.008
Boundary for River Rch & Prof#=Stream0558,Reach-1         , 5
Up Type= 0
Dn Type= 3
Dn Slope=0.008
Boundary for River Rch & Prof#=Stream0558,Reach-1         , 6
Up Type= 0
Dn Type= 3
Dn Slope=0.008
Boundary for River Rch & Prof#=Stream0558,Reach-1         , 7
Up Type= 0
Dn Type= 3
Dn Slope=0.008
DSS Import GetInterval= 0
DSS Import GetPeak= 0
DSS Import FillOption= 0

--- Stream0558.g01 (geometry) ---

Geom Title=Existing Conditions
Program Version=4.10

River Reach=Stream0558      ,Reach-1
Reach XY= 30
        1948625.       13921075.      1948609.51     13921174.53
      1948480.95     13921172.75      1948409.72     13921125.37
      1948318.55     13921132.64      1948264.21     13921234.66
      1948133.17     13921368.97      1948108.51     13921442.05
      1947959.53       13921525.      1947915.02     13921514.89
      1947869.37     13921430.66      1947640.07     13921274.21
      1947561.35     13921288.19      1947511.37     13921388.23
      1947409.65     13921475.11      1947273.53     13921378.56
      1947135.51     13921373.77      1946964.81     13921324.45
       1946915.2     13921335.47      1946769.02     13921473.07
        1946687.      13921473.1      1946669.21     13921430.22
      1946636.04     13921425.68      1946419.06     13921522.74
      1946226.36     13921528.29        1946175.       13921575.
      1945740.22     13921574.48      1945669.06     13921527.27
      1945526.37      13921521.7        1945475.       13921475.

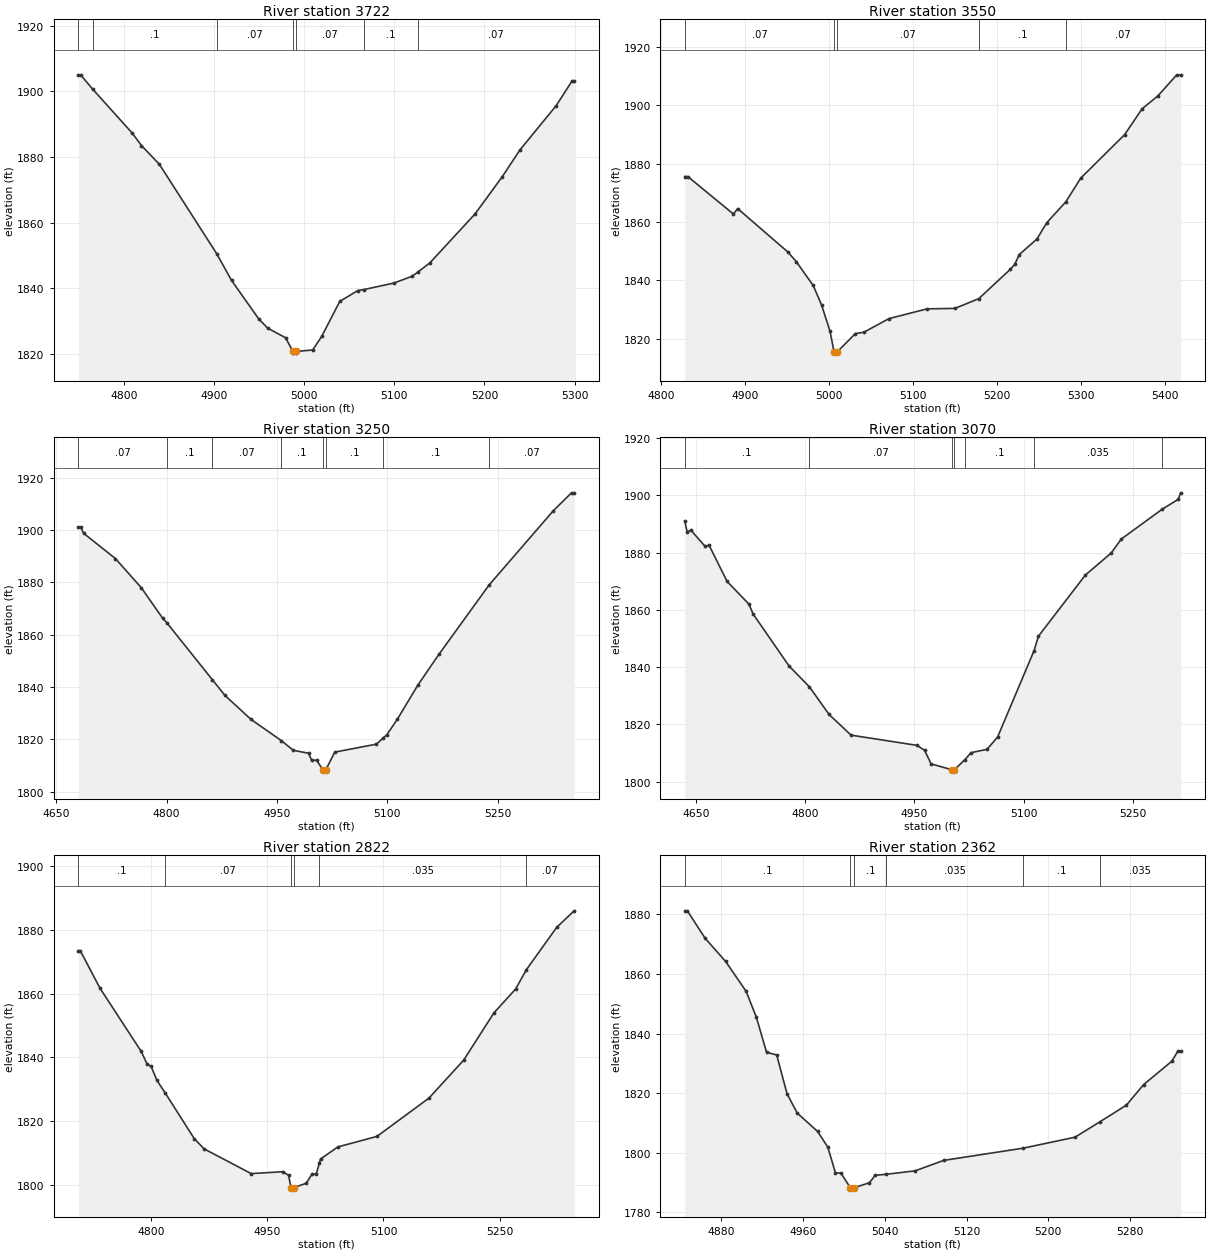
Type RM Length L Ch R = 1 ,3722    ,172,172,172
BEGIN DESCRIPTION:
Stream0558 8.0
END DESCRIPTION:
XS GIS Cut Line= 3
        1948525.     13920924.99        1948525.       13921175.
        1948525.     13921474.99
#Sta/Elev= 30
  4749.5 1905.07    4752 1905.07  4765.7 1900.62  4809.5 1887.24  4819.5 1883.53
  4839.5 1877.77  4902.9 1850.61  4919.5 1842.42  4949.5 1830.75  4959.5 1827.89
  4979.5 1824.95  4987.5 1820.78  4987.8 1820.28  4991.3 1820.28  4991.5 1820.78
  5009.5 1821.25  5019.5  1825.4  5039.5 1836.04  5059.5 1839.34  5066.5 1839.66
  5099.5 1841.62  5119.5 1843.67  5126.1 1844.96  5139.5 1847.79  5189.5 1862.67
  5219.5 1873.93  5239.5 1882.24  5279.5 1895.66    5297 1903.12  5299.5 1903.12
#Mann= 7 ,-1 , 0
  4749.5     .07       0  4765.7      .1       0  4902.9     .07       0
  4987.5     .05       0  4991.5     .07       0  5066.5      .1       0
  5126.1     .07       0
Bank Sta=4987.5,4991.5
XS Rating Curve= 0 ,0
Exp/Cntr=0.3,0.1

Type RM Length L Ch R = 1 ,3550    ,300,300,300
BEGIN DESCRIPTION:
Mapping XS 9be98fc4
END DESCRIPTION:
XS GIS Cut Line= 3
      1948355.26     13920952.71      1948378.18     13921233.69
       1948466.9     13921528.83
#Sta/Elev= 30
    4828 1875.54  4831.6 1875.54  4885.9  1862.7  4890.9 1864.57  4950.7 1849.69
  4960.7 1846.39  4980.8 1838.23  4990.8 1831.54  5000.9 1822.51  5005.6 1815.56
  5005.9 1815.06  5009.6 1815.56    5031 1821.75    5041  1822.2  5071.1 1826.89
  5116.4 1830.23  5149.4 1830.38  5177.8  1833.7  5215.5 1843.79  5220.7 1845.48
  5226.1 1848.83    5247 1854.12  5258.9 1859.77  5281.5 1866.89  5299.2    1875
  5351.4 1889.89  5372.3 1898.77  5391.1 1903.18  5413.5 1910.39  5418.1 1910.39
#Mann= 5 ,-1 , 0
    4828     .07       0  5005.6     .05       0  5009.6     .07       0
  5177.8      .1       0  5281.5     .07       0
Bank Sta=5005.6,5009.6
XS Rating Curve= 0 ,0
Exp/Cntr=0.3,0.1

Type RM Length L Ch R = 1 ,3250    ,180,180,180
BEGIN DESCRIPTION:
Stream0558 7.0
END DESCRIPTION:
XS GIS Cut Line= 3
      1947975.02     13921075.02        1948175.       13921325.
      1948425.02     13921575.02
#Sta/Elev= 30
  4680.1 1901.12  4683.3 1901.12  4687.3 1898.82  4730.5 1889.13  4765.7 1877.97
  4794.5 1866.38  4800.1 1864.66  4862.3 1842.76  4879.4 1836.77  4914.6 1827.64
  4955.8 1819.52  4972.2 1815.81    4993 1814.66    4997    1812  5003.8    1812
  5012.4 1808.33  5012.6 1807.83  5016.1 1807.83  5016.4 1808.33  5028.5  1815.1
  5085.1 1818.15  5094.4  1820.5  5099.2 1821.72  5113.4  1827.6  5141.6  1840.8
  5169.9 1852.45  5238.1 1878.99  5325.5 1907.45  5350.2 1914.29  5353.8 1914.29
#Mann= 8 ,-1 , 0
  4680.1     .07       0  4800.1      .1       0  4862.3     .07       0
  4955.8      .1       0  5012.4     .05       0  5016.4      .1       0
  5094.4      .1       0  5238.1     .07       0
Bank Sta=5012.4,5016.4
XS Rating Curve= 0 ,0
Exp/Cntr=0.3,0.1

Type RM Length L Ch R = 1 ,3070    ,248,248,248
BEGIN DESCRIPTION:
Mapping XS e95f8d66
END DESCRIPTION:
XS GIS Cut Line= 3
      1947948.68     13921127.57      1948099.36     13921523.64
      1948291.38      13921693.3
#Sta/Elev= 30
    4635 1890.93  4638.2 1887.21  4643.5 1887.76  4662.9 1882.14  4668.3 1882.56
    4693 1869.92  4723.1 1861.96  4728.5 1858.62    4778 1840.39  4805.8 1833.17
  4832.9 1823.48    4863 1816.27  4953.3 1812.71  4963.9 1810.97  4972.7 1806.26
  5000.8 1804.21  5001.1 1803.71  5004.8 1804.21  5018.8 1807.62  5027.6 1810.16
  5049.5 1811.31    5064 1815.61    5114 1845.75    5120 1850.81  5184.5 1872.18
  5219.6 1879.79  5233.8 1884.74  5289.7 1895.11  5311.6 1898.55    5315 1900.84
#Mann= 7 ,-1 , 0
    4635      .1       0  4805.8     .07       0  5000.8     .05       0
  5004.8     .07       0  5018.8      .1       0    5114    .035       0
  5289.7     .07       0
Bank Sta=5000.8,5004.8
XS Rating Curve= 0 ,0
Exp/Cntr=0.3,0.1

Type RM Length L Ch R = 1 ,2822    ,460,460,460
BEGIN DESCRIPTION:
Stream0558 6.0
END DESCRIPTION:
XS GIS Cut Line= 3
        1947925.     13921174.99        1947875.       13921475.
      1947724.98     13921775.04
#Sta/Elev= 30
  4706.4 1873.53  4708.9 1873.53  4734.3 1861.75  4787.5 1841.87  4795.1 1837.88
  4800.2  1837.2  4807.8 1832.78  4818.7 1828.73  4855.9 1814.49  4868.6 1811.26
  4929.4 1803.48    4970 1804.08  4977.6 1802.96  4980.7 1799.11  4980.9 1798.61
  4984.7 1799.11  5000.4 1800.46    5008 1803.37  5013.3 1803.37  5017.4 1806.83
  5018.9 1808.09  5041.3 1811.88  5091.6 1815.17  5158.7 1827.21  5203.4 1839.11
  5242.5 1853.98  5270.5 1861.47  5284.4 1867.56  5323.6 1880.88    5346 1886.04
#Mann= 6 ,-1 , 0
  4706.4      .1       0  4818.7     .07       0  4980.7     .05       0
  4984.7     .07       0  5017.4    .035       0  5284.4     .07       0
Bank Sta=4980.7,4984.7
XS Rating Curve= 0 ,0
Exp/Cntr=0.3,0.1

Type RM Length L Ch R = 1 ,2362    ,469,469,469
BEGIN DESCRIPTION:
Stream0558 5.0
END DESCRIPTION:
XS GIS Cut Line= 3
        1947525.     13921174.99        1947525.       13921325.
      1947674.99     13921624.98
#Sta/Elev= 30
  4844.1 1881.19  4846.6 1881.19  4864.1 1871.94  4884.1 1864.19  4904.1 1854.19
  4914.1 1845.55  4924.1 1833.74  4934.1  1832.8  4944.1 1819.87  4954.1 1813.34
  4974.1 1807.15  4984.1  1801.9  4991.6  1793.2  4996.9  1793.2  5006.1 1788.29
  5006.3 1787.79  5010.1 1788.29  5024.9 1789.94  5030.4 1792.41  5041.5 1792.78
  5069.6 1793.93  5097.5 1797.43  5175.2 1801.53  5226.1 1805.21  5250.5 1810.39
  5276.4 1815.97  5293.2 1822.85  5321.1 1830.78  5326.7 1834.08  5329.5 1834.08
#Mann= 6 ,-1 , 0
  4844.1      .1       0  5006.1     .05       0  5010.1      .1       0
  5041.5    .035       0  5175.2      .1       0  5250.5    .035       0
Bank Sta=5006.1,5010.1
XS Rating Curve= 0 ,0
Exp/Cntr=0.3,0.1

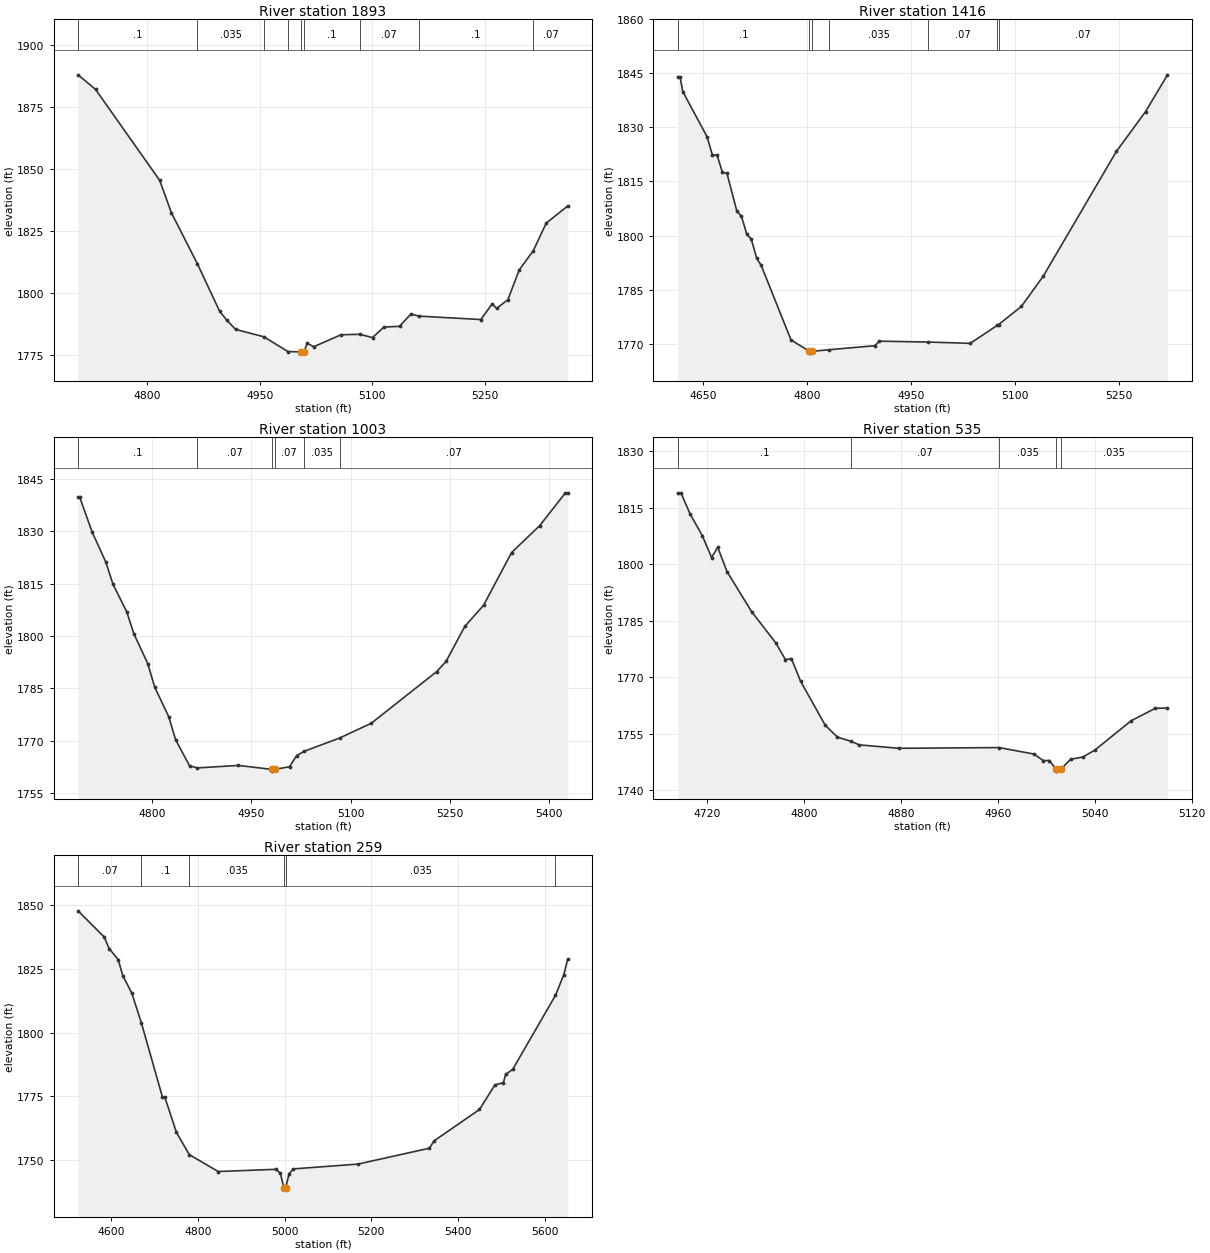
Type RM Length L Ch R = 1 ,1893    ,477,477,477
BEGIN DESCRIPTION:
Stream0558 4.0
END DESCRIPTION:
XS GIS Cut Line= 3
      1947324.98     13921125.03        1947175.       13921375.
      1947375.02     13921675.03
#Sta/Elev= 30
  4708.1 1887.86  4731.4    1882  4816.9 1845.29  4832.5 1832.21  4867.1 1811.65
  4896.6 1792.58  4906.3 1788.89    4918 1785.22  4955.4 1782.27  4987.7  1776.3
  5005.1 1776.17  5005.4 1775.67  5009.1 1776.17  5013.1 1779.66  5022.1 1778.26
  5058.2 1783.07    5083 1783.27  5100.3 1781.95  5115.3 1786.16  5136.3 1786.49
  5151.3 1791.43  5161.9  1790.6  5244.5 1789.21  5259.5 1795.52  5265.5  1793.7
  5280.5 1797.22  5295.6 1809.22  5314.3 1816.95  5331.6 1828.11  5360.2 1834.99
#Mann= 9 ,-1 , 0
  4708.1      .1       0  4867.1    .035       0  4955.4     .07       0
  4987.7      .1       0  5005.1     .05       0  5009.1      .1       0
    5083     .07       0  5161.9      .1       0  5314.3     .07       0
Bank Sta=5005.1,5009.1
XS Rating Curve= 0 ,0
Exp/Cntr=0.3,0.1

Type RM Length L Ch R = 1 ,1416    ,413,413,413
BEGIN DESCRIPTION:
Stream0558 3.0
END DESCRIPTION:
XS GIS Cut Line= 3
      1946524.99     13921174.99        1946775.       13921475.
      1946875.02     13921775.05
#Sta/Elev= 30
  4613.5 1844.04  4616.8 1844.04  4620.7 1839.94  4655.8 1827.39  4663.6 1822.26
  4670.1  1822.4  4677.9 1817.56  4684.5 1817.25  4698.8 1806.75  4705.3 1805.44
  4713.1 1800.37  4719.6 1799.02  4727.4 1793.71  4733.9 1791.73  4776.9 1771.07
  4803.5 1767.91  4803.8 1767.41  4807.5 1767.91  4831.8 1768.35  4897.9 1769.47
  4904.4 1770.73  4975.2 1770.48  5035.6 1770.12  5074.7 1775.12  5076.5 1775.32
  5109.4 1780.36  5141.1 1788.78  5246.5 1823.32  5288.6 1834.36  5320.3 1844.57
#Mann= 7 ,-1 , 0
  4613.5      .1       0  4803.5     .05       0  4807.5      .1       0
  4831.8    .035       0  4975.2     .07       0  5074.7    .035       0
  5076.5     .07       0
Bank Sta=4803.5,4807.5
XS Rating Curve= 0 ,0
Exp/Cntr=0.3,0.1

Type RM Length L Ch R = 1 ,1003    ,468,468,468
BEGIN DESCRIPTION:
Stream0558 2.0
END DESCRIPTION:
XS GIS Cut Line= 3
        1946325.     13921225.01        1946425.       13921525.
      1946725.01     13921825.01
#Sta/Elev= 30
  4687.9 1839.68  4690.5 1839.68    4709 1829.88  4730.1 1821.08  4740.6 1814.91
  4761.7 1806.87  4772.2 1800.71  4793.3 1792.11  4803.8  1785.4  4824.9 1776.97
  4835.5 1770.32  4856.5 1762.86  4868.3 1762.26  4930.3 1762.97    4981 1761.84
  4981.3 1761.34    4985 1761.84  5007.7 1762.59  5018.3 1765.73  5029.6    1767
  5083.3  1770.8  5131.4 1775.05  5230.4 1789.85  5244.5 1792.77  5272.8 1802.77
  5301.1  1808.8  5343.5 1823.89    5386 1831.59  5424.9 1840.98  5428.4 1840.98
#Mann= 6 ,-1 , 0
  4687.9      .1       0  4868.3     .07       0    4981     .05       0
    4985     .07       0  5029.6    .035       0  5083.3     .07       0
Bank Sta=4981,4985
XS Rating Curve= 0 ,0
Exp/Cntr=0.3,0.1

Type RM Length L Ch R = 1 ,535     ,276,276,276
BEGIN DESCRIPTION:
Stream0558 1.0
END DESCRIPTION:
XS GIS Cut Line= 3
      1946025.01     13921274.95        1945975.       13921575.
        1945975.     13921675.02
#Sta/Elev= 30
  4695.8  1818.9  4698.4  1818.9    4706 1813.28  4716.1  1807.5  4723.7 1801.73
  4728.8 1804.42  4736.4 1798.01  4756.7 1787.38  4776.9 1778.99  4784.6 1774.64
  4789.6 1774.91  4797.2 1768.85  4817.5 1757.22  4827.6 1754.05    4839 1752.92
  4845.4 1752.01  4878.3 1751.09  4961.1 1751.28  4989.8 1749.56  4997.4 1747.85
  5002.5 1747.85    5008 1745.53  5008.2 1745.03    5012 1745.53    5020 1748.18
    5030 1748.76    5040  1750.6    5070  1758.4    5090 1761.72    5100 1761.76
#Mann= 5 ,-1 , 0
  4695.8      .1       0    4839     .07       0  4961.1    .035       0
    5008    .035       0    5012    .035       0
Bank Sta=5008,5012
XS Rating Curve= 0 ,0
Exp/Cntr=0.3,0.1

Type RM Length L Ch R = 1 ,259     ,0,0,0
BEGIN DESCRIPTION:
Stream0558 0.0
END DESCRIPTION:
XS GIS Cut Line= 4
      1945819.65     13921096.53      1945699.93     13921473.91
      1945712.83      13921675.1      1945900.56     13922173.82
#Sta/Elev= 30
  4522.9 1847.83  4583.4 1837.52  4594.7    1833  4615.7 1828.63  4626.2 1822.39
  4647.2 1815.43  4669.4 1803.65  4717.8 1774.63    4723 1774.74    4750  1760.8
  4779.8 1752.02  4846.5  1745.4    4980 1746.27    4990 1744.71  4998.1 1738.98
  4998.3 1738.48  5002.1 1738.98  5010.1 1744.52  5020.1 1746.43  5168.8 1748.31
    5334 1754.56  5344.8 1757.45  5449.6 1769.77  5485.2 1779.43  5504.7  1780.3
    5510 1783.56  5526.3 1785.55  5624.9  1814.6  5643.9 1822.63  5653.3 1828.89
#Mann= 6 ,-1 , 0
  4522.9     .07       0  4669.4      .1       0  4779.8    .035       0
  4998.1    .035       0  5002.1    .035       0  5624.9      .1       0
Bank Sta=4998.1,5002.1
XS Rating Curve= 0 ,0
Exp/Cntr=0.3,0.1

Chan Stop Cuts=-1
Use User Specified Reach Order=0
Composite Channel Slope=5