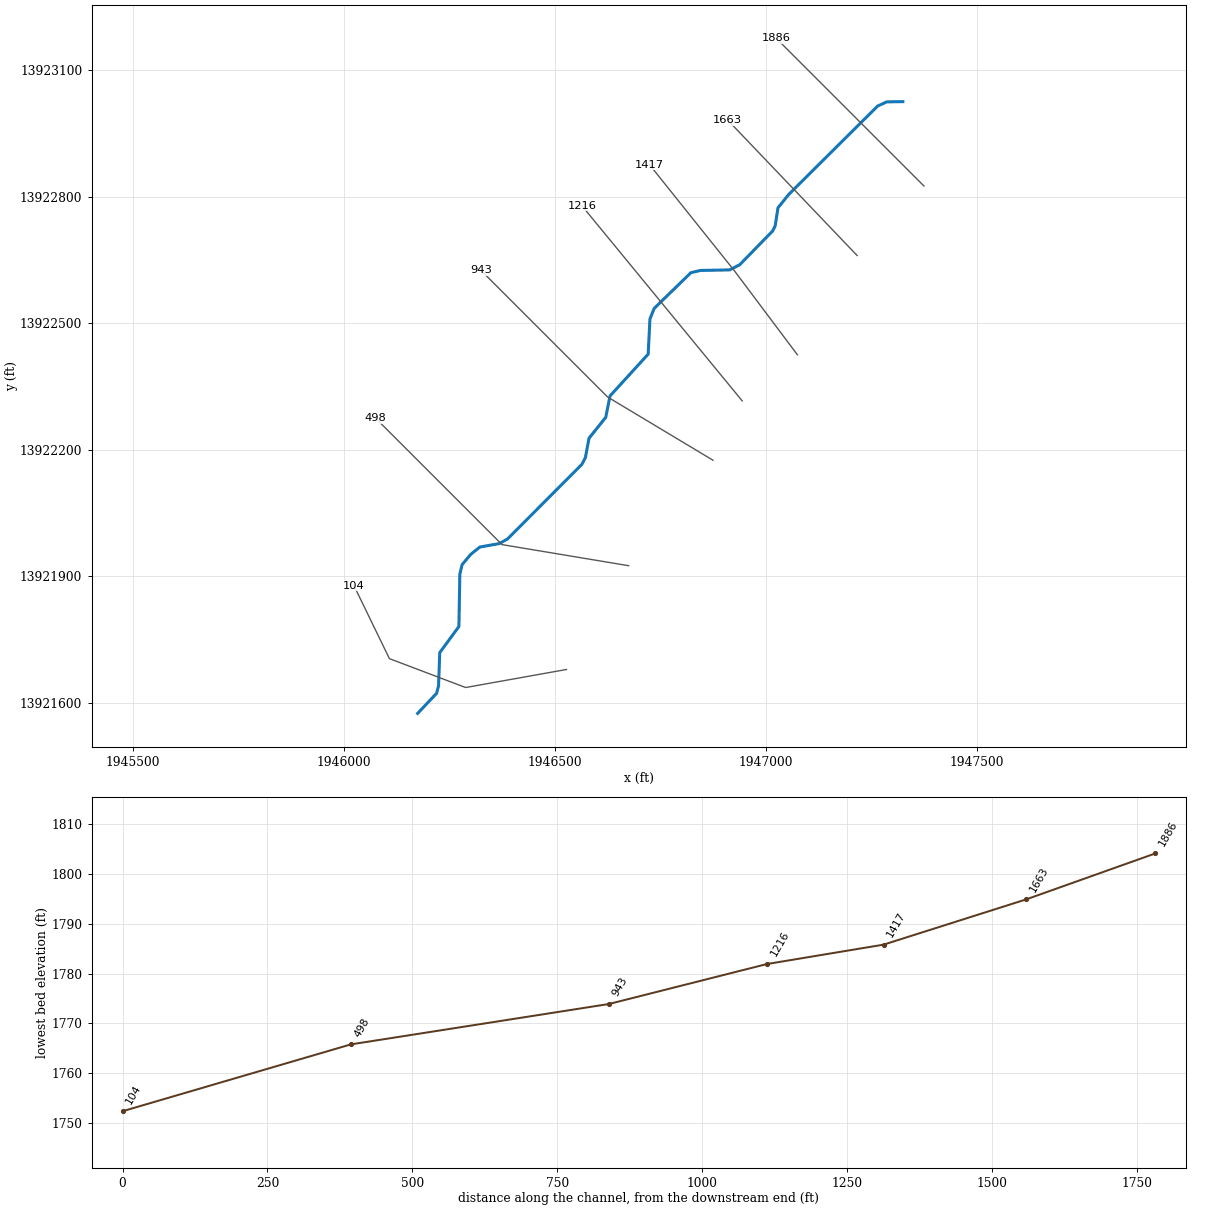
--- Stream0559.prj (project) ---

Proj Title=Stream0559 Base Level Engineering
Current Plan=p01
Default Exp/Contr=0.3,0.1
English Units
Geom File=g01
Flow File=f01
Plan File=p01
Y Axis Title=Elevation
X Axis Title(PF)=Main Channel Distance
X Axis Title(XS)=Station
BEGIN DESCRIPTION:
Stream0559
END DESCRIPTION:
DSS Export Rating Curves= 0
DSS Export Rating Curve Sorted= 0
DSS Export Volume Flow Curves= 0
DXF OffsetX= 0
DXF OffsetY= 0
DXF ScaleX= 1
DXF ScaleY= 10

--- Stream0559.p01 (plan) ---

Plan Title=Multiple Run
Short Identifier=Multiple
Geom File=g01
Flow File=f01
Subcritical Flow
K Sum by GR= 0
Std Step Tol= 0.01
Critical Tol= 0.01
Num of Std Step Trials= 20
Max Error Tol= 0.3
Flow Tol Ratio= 0.001
Split Flow NTrial= 30
Split Flow Tol= 0.02
Split Flow Ratio= 0.02
Log Output Level= 0
Friction Slope Method= 1
Unsteady Friction Slope Method= 2
Unsteady Bridges Friction Slope Method= 1
Parabolic Critical Depth
Global Vel Dist=  1 , 1 , 1
Global Log Level= 0
CheckData=True
Encroach Param= -1, 0, 0, 0
BEGIN DESCRIPTION:
Multiple Run
END DESCRIPTION:

--- Stream0559.f01 (steady flow) ---

Flow Title=Multiple
Number of Profiles=7
Profile Names=10-year,25-year,50-year,1pct_min,100-year,1pct_plu,500-year
River Rch & RM= Stream0559,Reach-1,1886
     563     920    1248     822    1641    3274    2789
Boundary for River Rch & Prof#=Stream0559,Reach-1,1
Up Type=0
Dn Type=3
Dn Slope=0.005
Boundary for River Rch & Prof#=Stream0559,Reach-1,2
Up Type=0
Dn Type=3
Dn Slope=0.005
Boundary for River Rch & Prof#=Stream0559,Reach-1,3
Up Type=0
Dn Type=3
Dn Slope=0.005
Boundary for River Rch & Prof#=Stream0559,Reach-1,4
Up Type=0
Dn Type=3
Dn Slope=0.005
Boundary for River Rch & Prof#=Stream0559,Reach-1,5
Up Type=0
Dn Type=3
Dn Slope=0.005
Boundary for River Rch & Prof#=Stream0559,Reach-1,6
Up Type=0
Dn Type=3
Dn Slope=0.005
Boundary for River Rch & Prof#=Stream0559,Reach-1,7
Up Type=0
Dn Type=3
Dn Slope=0.005

--- Stream0559.g01 (geometry) ---

Geom Title=Existing Conditions
Program Version=4.10

River Reach=Stream0559      ,Reach-1
Reach XY= 30
        1947325.       13923025.      1947286.84     13923024.41
      1947265.21     13923014.49      1947054.62     13922805.16
      1947028.98     13922773.35      1947022.47     13922731.04
      1947016.85     13922718.93      1946938.33     13922638.39
      1946914.52     13922626.16      1946845.05     13922624.87
      1946822.56     13922619.48      1946735.51     13922534.81
      1946725.52     13922509.79      1946721.37      13922426.5
      1946630.85     13922327.29      1946620.81     13922276.73
       1946581.1     13922227.19       1946572.5     13922181.04
      1946564.24     13922165.32       1946388.2     13921988.64
      1946368.91     13921977.55      1946322.43     13921969.26
      1946301.03     13921952.19      1946280.36      13921927.7
      1946274.93     13921905.11      1946272.73     13921780.94
      1946227.32     13921719.04      1946224.47     13921640.22
      1946219.78     13921622.45        1946175.       13921575.

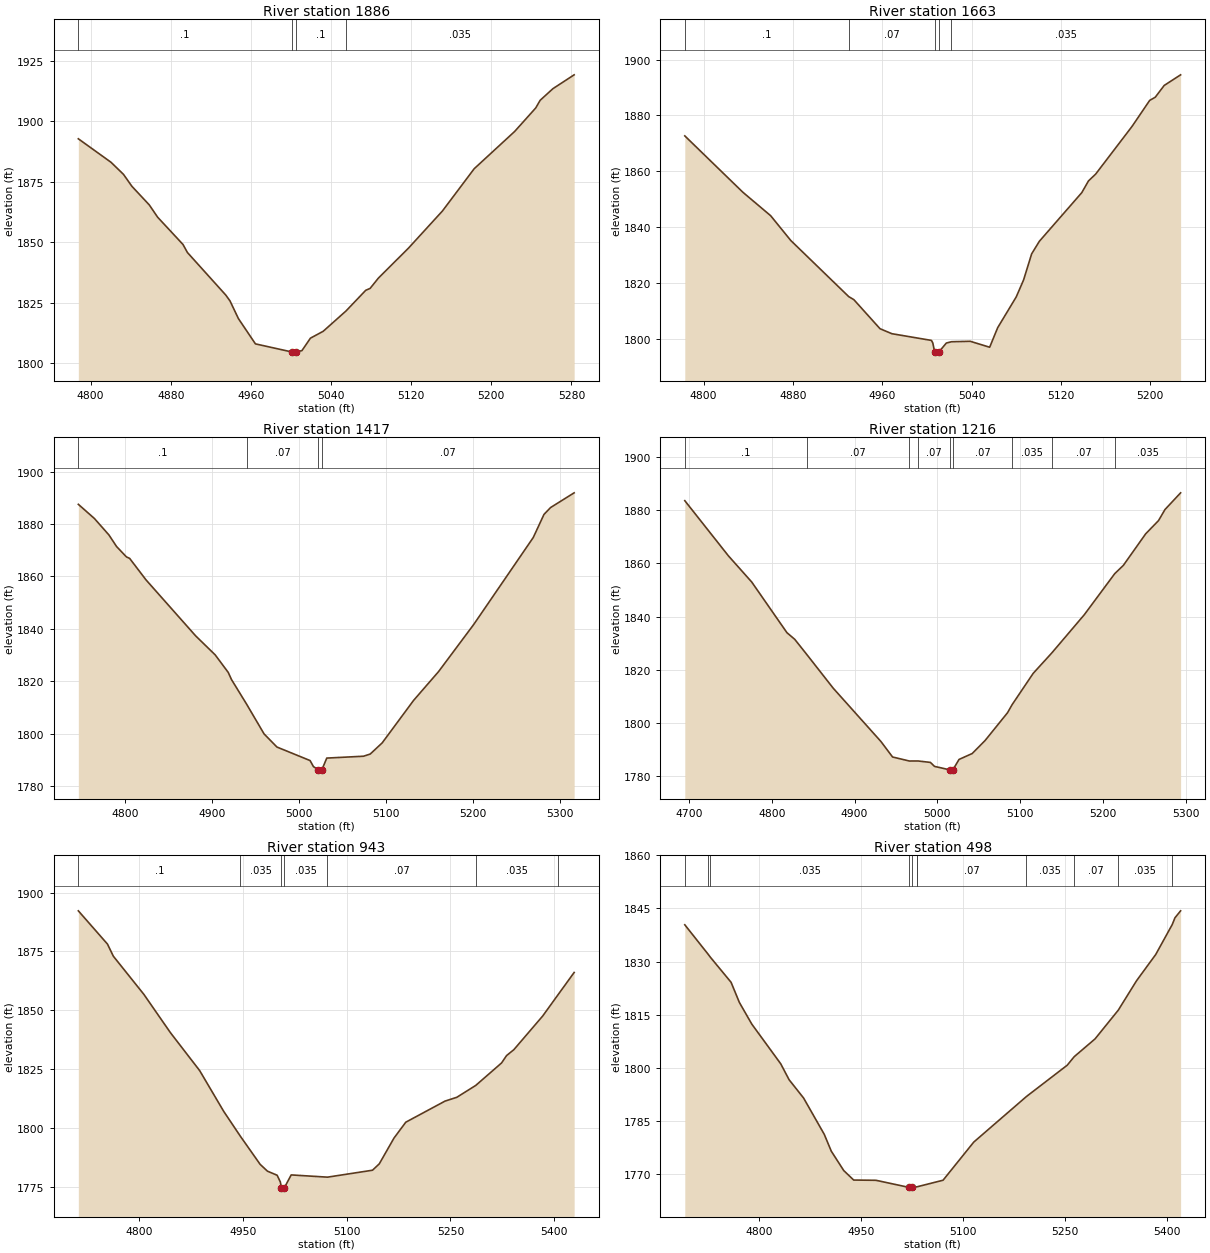
Type RM Length L Ch R = 1 ,1886    ,223,223,223
BEGIN DESCRIPTION:
Stream0559 4.0
END DESCRIPTION:
XS GIS Cut Line= 3
      1947374.99     13922825.01        1947225.       13922975.
      1947024.97     13923175.03
#Sta/Elev= 30
  4787.7 1892.79  4820.3 1883.08  4832.8 1878.06  4841.2 1873.12  4858.5 1865.45
  4866.9 1860.33  4892.2 1849.05  4896.6 1845.73  4934.8 1828.17  4939.1 1825.71
  4947.5 1818.39  4964.5 1807.92  5000.6 1804.59  5000.8 1804.09  5004.6 1804.59
  5010.9 1805.11  5019.4 1810.27  5032.2 1813.14  5054.9 1821.52  5074.6 1830.08
    5079 1830.88  5087.3 1835.15  5117.3 1847.54  5151.2 1862.91  5182.9  1880.4
  5223.3 1895.82  5244.3 1905.53  5248.8 1908.74  5261.5 1913.53  5282.7 1919.26
#Mann= 4 ,-1 , 0
  4787.7      .1       0  5000.6     .05       0  5004.6      .1       0
  5054.9    .035       0
Bank Sta=5000.6,5004.6
XS Rating Curve= 0 ,0
Exp/Cntr=0.3,0.1

Type RM Length L Ch R = 1 ,1663    ,246,246,246
BEGIN DESCRIPTION:
Mapping XS c9752f5c
END DESCRIPTION:
XS GIS Cut Line= 2
      1947216.53     13922660.27      1946909.81      13922981.3
#Sta/Elev= 30
  4783.1 1872.69  4835.1  1852.5    4860 1844.09    4878 1835.22  4929.9 1815.11
  4934.5 1814.02  4957.9 1803.62  4968.5 1801.83    5004 1799.42  5005.2 1798.49
  5006.8 1795.37  5007.1 1794.87  5010.8 1795.37  5017.3 1798.48  5021.9 1798.95
  5038.7 1799.11  5056.1 1796.98  5063.3 1803.99  5079.9 1815.01  5086.5 1821.11
  5093.7 1830.43  5100.6 1834.93  5138.6 1852.36  5144.6 1856.56    5151 1858.99
  5183.6 1876.08  5199.4  1885.4  5204.4 1886.54  5212.4 1890.76  5227.1 1894.56
#Mann= 5 ,-1 , 0
  4783.1      .1       0  4929.9     .07       0  5006.8     .05       0
  5010.8     .07       0  5021.9    .035       0
Bank Sta=5006.8,5010.8
XS Rating Curve= 0 ,0
Exp/Cntr=0.3,0.1

Type RM Length L Ch R = 1 ,1417    ,201,201,201
BEGIN DESCRIPTION:
Stream0559 3.0
END DESCRIPTION:
XS GIS Cut Line= 3
      1947075.03     13922424.96        1946925.       13922625.
        1946725.       13922875.
#Sta/Elev= 30
  4745.8 1887.51  4764.3  1882.1    4781 1875.83  4789.8 1871.41  4801.1 1867.47
  4804.8  1866.9  4823.6 1858.72  4880.7 1837.37  4903.2 1830.11  4918.2 1823.43
  4921.9 1820.73  4939.4 1811.28  4959.4 1799.99  4974.2 1794.98  5012.3 1789.83
  5016.2 1787.52  5021.9  1786.3  5022.1  1785.8  5025.9  1786.3  5031.5 1790.77
  5073.8 1791.48  5081.5 1792.32  5095.2 1796.55  5131.4 1812.78  5160.1 1823.75
  5200.6 1841.75    5269 1874.87  5281.3 1883.66  5288.9 1886.28    5316 1891.89
#Mann= 4 ,-1 , 0
  4745.8      .1       0  4939.4     .07       0  5021.9     .05       0
  5025.9     .07       0
Bank Sta=5021.9,5025.9
XS Rating Curve= 0 ,0
Exp/Cntr=0.3,0.1

Type RM Length L Ch R = 1 ,1216    ,273,273,273
BEGIN DESCRIPTION:
Mapping XS 55a10ae9
END DESCRIPTION:
XS GIS Cut Line= 2
      1946944.28     13922315.61      1946564.05     13922778.46
#Sta/Elev= 30
  4694.9 1883.56  4747.5 1862.86  4775.8 1852.97  4818.3 1833.95  4827.7 1831.46
  4842.2 1825.79  4874.2 1813.09  4931.8 1793.07  4945.9 1787.23  4966.2 1785.72
  4976.8 1785.73  4991.6  1785.2  4996.6  1783.7  5014.8 1782.42    5015 1781.92
  5018.8 1782.42  5026.2 1786.31  5042.1 1788.53  5057.6 1793.39  5084.8 1803.87
  5090.3 1806.88  5115.8 1818.67  5138.4 1826.38  5177.5 1840.69  5214.3 1856.13
  5224.7 1859.24  5251.7 1871.11  5267.2 1876.07    5275 1880.23  5293.9 1886.51
#Mann= 9 ,-1 , 0
  4694.9      .1       0  4842.2     .07       0  4966.2    .035       0
  4976.8     .07       0  5014.8     .05       0  5018.8     .07       0
  5090.3    .035       0  5138.4     .07       0  5214.3    .035       0
Bank Sta=5014.8,5018.8
XS Rating Curve= 0 ,0
Exp/Cntr=0.3,0.1

Type RM Length L Ch R = 1 ,943     ,445,445,445
BEGIN DESCRIPTION:
Stream0559 2.0
END DESCRIPTION:
XS GIS Cut Line= 3
      1946875.03     13922174.98        1946625.       13922325.
      1946325.03     13922624.97
#Sta/Elev= 30
  4712.8 1892.24  4754.9 1878.09  4763.3 1872.97  4807.4 1856.72  4845.9 1840.37
  4887.9 1824.33  4922.8 1806.91  4946.9 1796.32  4975.3 1784.43  4985.8 1781.54
  4999.8  1779.8  5004.4 1776.98  5006.1  1774.4  5006.4  1773.9  5010.1  1774.4
  5020.1 1779.94  5072.5 1778.99  5137.5 1781.94  5147.3 1784.66  5168.5  1795.6
  5185.5 1802.35  5242.2 1811.33  5259.2 1812.95  5286.5 1817.99  5323.8 1827.55
    5331 1830.68  5341.6 1833.21  5383.2 1847.52  5405.8 1856.75  5428.6 1866.03
#Mann= 7 ,-1 , 0
  4712.8      .1       0  4946.9    .035       0  5006.1    .035       0
  5010.1    .035       0  5072.5     .07       0  5286.5    .035       0
  5405.8     .07       0
Bank Sta=5006.1,5010.1
XS Rating Curve= 0 ,0
Exp/Cntr=0.3,0.1

Type RM Length L Ch R = 1 ,498     ,394,394,394
BEGIN DESCRIPTION:
Stream0559 1.0
END DESCRIPTION:
XS GIS Cut Line= 3
      1946675.02       13921925.        1946375.       13921975.
      1946075.02     13922274.98
#Sta/Elev= 30
    4691 1840.39  4725.3 1832.08  4728.7 1831.21    4759 1824.16  4771.2 1818.47
  4789.4 1812.38    4832 1801.15  4844.2 1796.68  4865.5 1791.52  4895.9 1781.26
  4906.2 1776.52  4924.5 1771.05  4939.1 1768.37  4971.9  1768.3  5020.1 1766.31
  5020.4 1765.81  5024.1 1766.31  5032.3 1766.47  5070.4 1768.32  5115.5 1779.08
  5192.9 1791.94  5252.8 1800.77  5263.1 1803.18  5293.7  1808.2  5327.8  1816.3
  5354.6 1824.59  5382.8    1832  5407.1 1840.46  5411.1 1842.37  5419.4 1844.33
#Mann= 11 ,-1 , 0
    4691     .07       0  4725.3      .1       0  4728.7    .035       0
  5020.1    .035       0  5024.1    .035       0  5032.3    .035       0
  5032.3     .07       0  5192.9    .035       0  5263.1     .07       0
  5327.8    .035       0  5407.1     .07       0
Bank Sta=5020.1,5024.1
XS Rating Curve= 0 ,0
Exp/Cntr=0.3,0.1

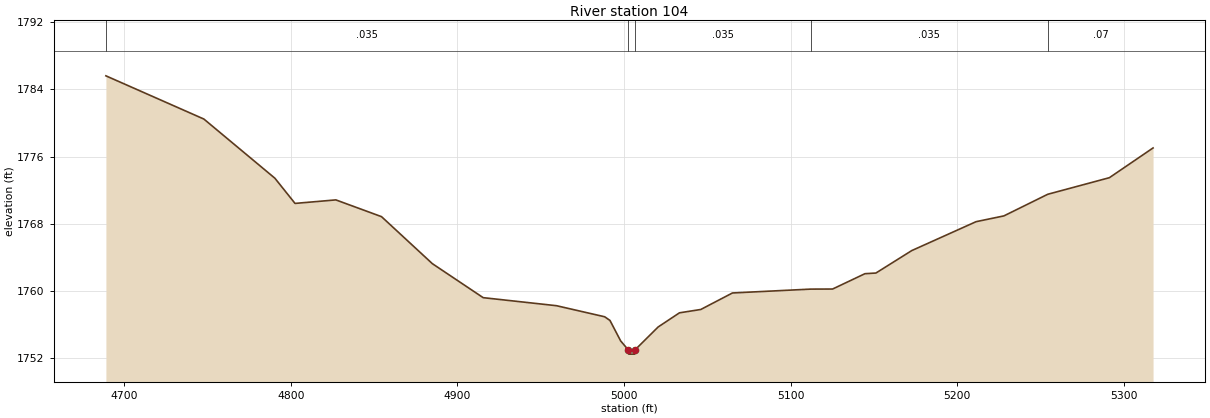
Type RM Length L Ch R = 1 ,104     ,0,0,0
BEGIN DESCRIPTION:
Stream0559 0.0
END DESCRIPTION:
XS GIS Cut Line= 4
      1946527.75     13921679.04      1946288.66     13921636.27
      1946108.01     13921704.75      1946023.95     13921877.73
#Sta/Elev= 30
  4689.1 1785.63  4747.9 1780.47  4790.5 1773.41  4802.6  1770.4  4827.1 1770.82
  4854.5 1768.82    4885 1763.21  4915.5 1759.15  4959.5 1758.19  4988.4 1756.87
  4991.6 1756.43    4998 1753.99  5002.6 1752.91  5002.9 1752.41  5006.4 1752.41
  5006.6 1752.91  5020.5 1755.65  5033.3 1757.34  5046.1 1757.74  5065.1 1759.71
    5112 1760.17  5125.2 1760.18  5144.6 1762.01  5151.2 1762.09  5172.7 1764.77
  5211.3 1768.22    5228 1768.91  5254.3 1771.49  5291.3 1773.47  5317.5 1777.02
#Mann= 5 ,-1 , 0
  4689.1    .035       0  5002.6    .035       0  5006.6    .035       0
    5112    .035       0  5254.3     .07       0
Bank Sta=5002.6,5006.6
XS Rating Curve= 0 ,0
Exp/Cntr=0.3,0.1

Chan Stop Cuts=-1
Use User Specified Reach Order=0
Composite Channel Slope=5