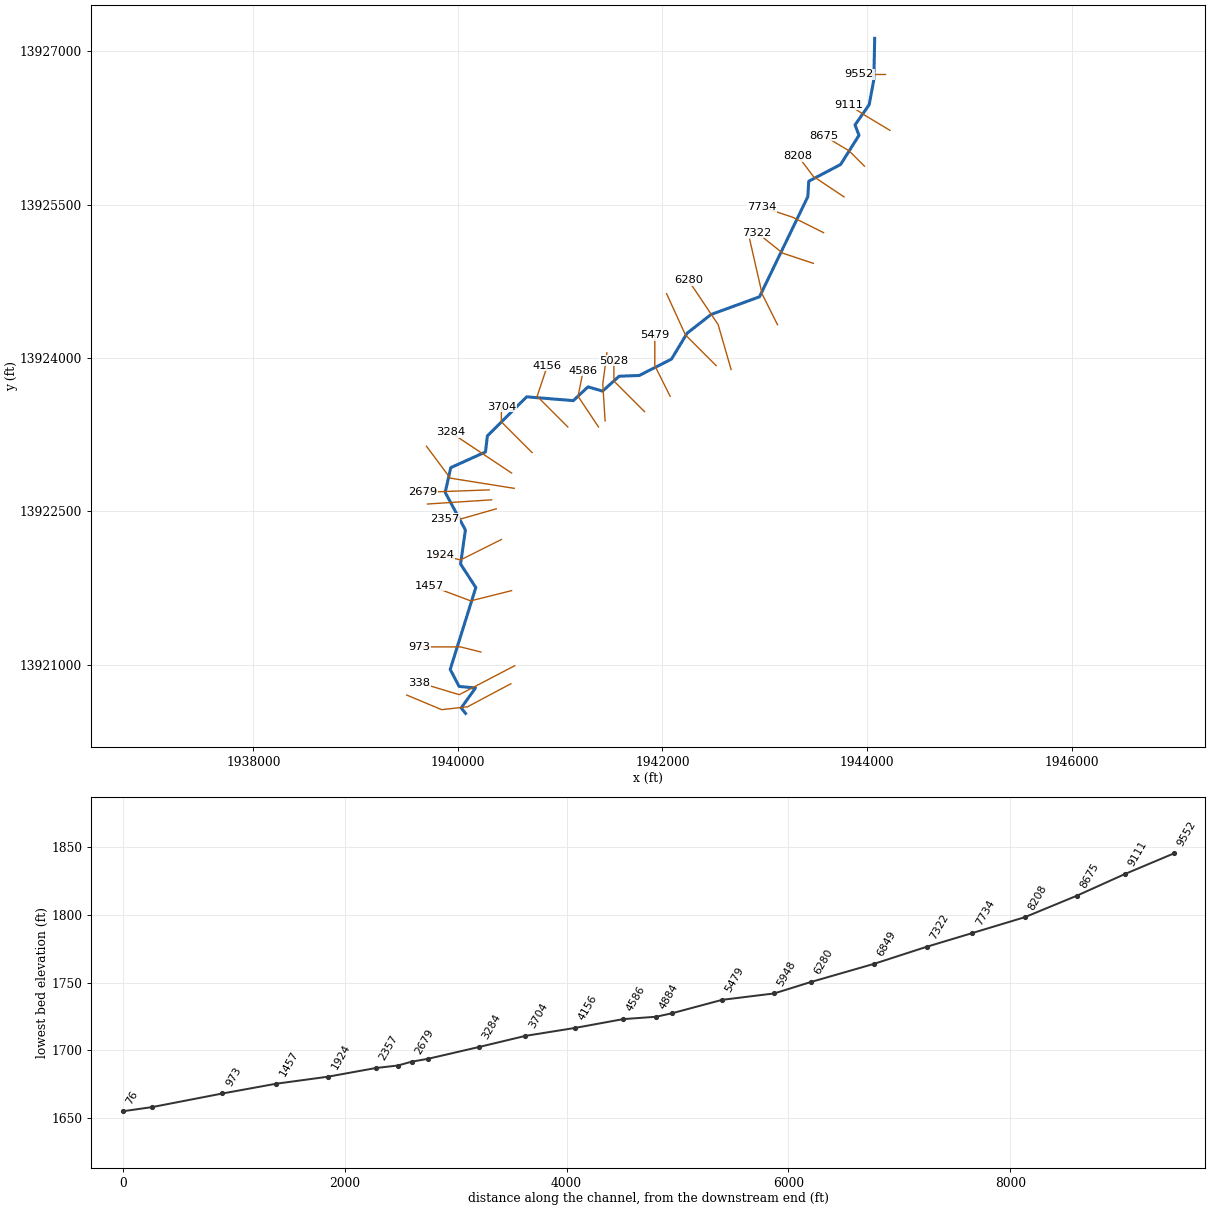
--- Stream0562.prj (project) ---

Proj Title=Stream0562 Base Level Engineering
Current Plan=p01
Default Exp/Contr=0.3,0.1
English Units
Geom File=g01
Flow File=f01
Plan File=p01
Y Axis Title=Elevation
X Axis Title(PF)=Main Channel Distance
X Axis Title(XS)=Station
BEGIN DESCRIPTION:
Stream0562
END DESCRIPTION:
DSS Export Rating Curves= 0
DSS Export Rating Curve Sorted= 0
DSS Export Volume Flow Curves= 0
DXF OffsetX= 0
DXF OffsetY= 0
DXF ScaleX= 1
DXF ScaleY= 10

--- Stream0562.p01 (plan) ---

Plan Title=Multiple Run
Short Identifier=Multiple
Geom File=g01
Flow File=f01
Subcritical Flow
K Sum by GR= 0
Std Step Tol= 0.01
Critical Tol= 0.01
Num of Std Step Trials= 20
Max Error Tol= 0.3
Flow Tol Ratio= 0.001
Split Flow NTrial= 30
Split Flow Tol= 0.02
Split Flow Ratio= 0.02
Log Output Level= 0
Friction Slope Method= 1
Unsteady Friction Slope Method= 2
Unsteady Bridges Friction Slope Method= 1
Parabolic Critical Depth
Global Vel Dist=  1 , 1 , 1
Global Log Level= 0
CheckData=True
Encroach Param= -1, 0, 0, 0
BEGIN DESCRIPTION:
Multiple Run
END DESCRIPTION:

--- Stream0562.f01 (steady flow) ---

Flow Title=Multiple
Program Version=4.10
Number of Profiles= 7
Profile Names=10-year,25-year,50-year,1pct_min,100-year,1pct_plu,500-year
River Rch & RM=Stream0562,Reach-1         ,9552
     476     768    1033     675    1347    2688    2253
River Rch & RM=Stream0562,Reach-1         ,6849
    1912    3374    4817    3323    6630   13228   12400
River Rch & RM=Stream0562,Reach-1         ,2679
    1882    3324    4744    3270    6525   13019   12194
Boundary for River Rch & Prof#=Stream0562,Reach-1         , 1
Up Type= 0
Dn Type= 3
Dn Slope=0.01
Boundary for River Rch & Prof#=Stream0562,Reach-1         , 2
Up Type= 0
Dn Type= 3
Dn Slope=0.01
Boundary for River Rch & Prof#=Stream0562,Reach-1         , 3
Up Type= 0
Dn Type= 3
Dn Slope=0.01
Boundary for River Rch & Prof#=Stream0562,Reach-1         , 4
Up Type= 0
Dn Type= 3
Dn Slope=0.01
Boundary for River Rch & Prof#=Stream0562,Reach-1         , 5
Up Type= 0
Dn Type= 3
Dn Slope=0.01
Boundary for River Rch & Prof#=Stream0562,Reach-1         , 6
Up Type= 0
Dn Type= 3
Dn Slope=0.01
Boundary for River Rch & Prof#=Stream0562,Reach-1         , 7
Up Type= 0
Dn Type= 3
Dn Slope=0.01
DSS Import GetInterval= 0
DSS Import GetPeak= 0
DSS Import FillOption= 0

--- Stream0562.g01 (geometry) ---

Geom Title=Existing Conditions
Program Version=4.10

River Reach=Stream0562      ,Reach-1
Reach XY= 30
        1944075.       13927125.      1944066.92      13926721.7
      1944021.25     13926476.55      1943882.83      13926278.4
      1943921.63     13926176.74      1943741.79     13925891.44
      1943430.36      13925727.7      1943421.24     13925576.56
      1942948.84     13924597.85        1942475.       13924425.
       1942241.3     13924242.13      1942088.22     13923988.62
      1941773.45     13923828.75      1941576.46     13923821.46
      1941414.52     13923675.94      1941271.58      13923717.2
      1941128.42      13923582.8      1940672.41     13923619.86
      1940288.65     13923238.33      1940269.44     13923080.62
      1939930.35     13922927.74      1939875.77     13922685.69
       1940073.2     13922318.89       1940026.2      13921985.5
      1940175.21     13921754.95      1939924.89      13920954.9
      1940011.59     13920788.53      1940171.99     13920773.63
      1940032.25     13920578.33        1940075.       13920525.

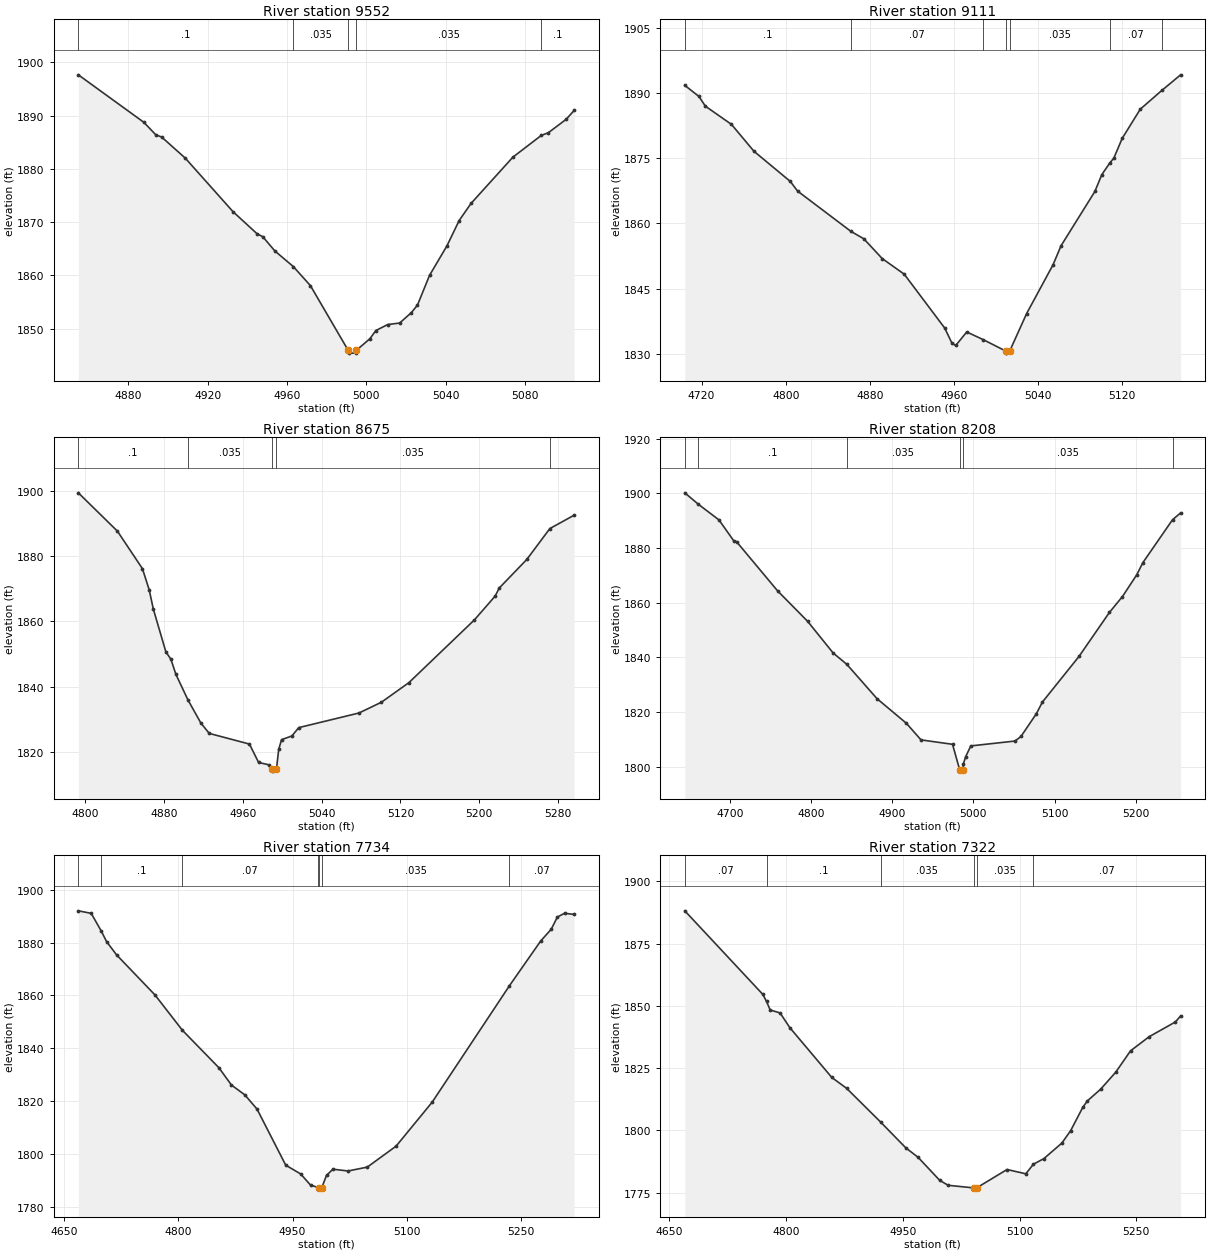
Type RM Length L Ch R = 1 ,9552    ,441,441,441
BEGIN DESCRIPTION:
Stream0562 20.0
END DESCRIPTION:
XS GIS Cut Line= 3
      1944174.97       13926775.        1944025.       13926775.
      1943924.97       13926775.
#Sta/Elev= 30
  4854.8 1897.68  4887.8 1888.77  4893.9  1886.4  4896.8    1886  4908.7 1882.04
  4932.8 1871.97  4944.9 1867.83  4947.8 1867.27  4953.9 1864.59  4963.2 1861.66
  4971.8 1858.09  4990.9  1845.9  4991.2  1845.4  4994.7  1845.4  4994.9  1845.9
  5001.8  1848.1  5004.8 1849.64  5010.8 1850.77  5016.8 1851.05  5022.7    1853
  5025.8 1854.43  5031.9 1860.02  5040.7 1865.58  5046.8  1870.3  5052.8 1873.52
  5073.9 1882.21  5088.2 1886.29  5091.8 1886.81  5100.8 1889.33  5104.8    1891
#Mann= 5 ,-1 , 0
  4854.8      .1       0  4963.2    .035       0  4990.9    .035       0
  4994.9    .035       0  5088.2      .1       0
Bank Sta=4990.9,4994.9
XS Rating Curve= 0 ,0
Exp/Cntr=0.3,0.1

Type RM Length L Ch R = 1 ,9111    ,436,436,436
BEGIN DESCRIPTION:
Stream0562 19.0
END DESCRIPTION:
XS GIS Cut Line= 3
      1944225.01     13926224.99        1943975.       13926375.
      1943825.03     13926474.98
#Sta/Elev= 30
    4704 1891.75  4717.4 1889.21  4723.6 1886.96  4748.4 1882.78  4769.8  1876.6
  4804.4 1869.66  4811.3 1867.45  4862.2 1858.16  4874.3 1856.49  4891.8 1851.94
  4912.8 1848.34  4951.3 1835.96  4958.3 1832.43  4961.8 1831.95  4972.3 1835.05
  4987.9  1833.3  5009.2 1830.69  5009.5 1830.19  5013.2 1830.69  5029.3  1839.3
  5054.5 1850.55    5062 1854.87  5094.2 1867.35  5100.8 1871.22  5108.7 1874.01
  5112.2 1874.99  5120.2 1879.56  5137.4 1886.27  5157.9 1890.58  5175.8 1894.17
#Mann= 7 ,-1 , 0
    4704      .1       0  4862.2     .07       0  4987.9    .035       0
  5009.2    .035       0  5013.2    .035       0  5108.7     .07       0
  5157.9      .1       0
Bank Sta=5009.2,5013.2
XS Rating Curve= 0 ,0
Exp/Cntr=0.3,0.1

Type RM Length L Ch R = 1 ,8675    ,467,467,467
BEGIN DESCRIPTION:
Stream0562 18.0
END DESCRIPTION:
XS GIS Cut Line= 3
      1943975.02     13925874.98        1943825.       13926025.
      1943575.09     13926174.95
#Sta/Elev= 30
  4792.9 1899.35  4832.6 1887.61    4858 1876.12  4864.9  1869.6  4869.1 1863.71
  4881.8 1850.65  4886.9 1848.38    4892 1843.74  4904.3 1835.88  4917.4 1828.81
  4925.9 1825.65  4966.7 1822.39    4976 1816.75  4986.6 1816.03  4990.1  1814.6
  4990.4  1814.1  4994.1  1814.6  4996.4 1820.73  4999.3 1823.74  5009.8 1824.87
  5016.8 1827.43  5077.9  1831.9  5100.7  1835.2  5128.7 1841.22  5195.2 1860.43
  5216.2  1867.7  5220.5 1870.22  5248.4 1878.94  5271.8  1888.4  5296.5  1892.5
#Mann= 5 ,-1 , 0
  4792.9      .1       0  4904.3    .035       0  4990.1    .035       0
  4994.1    .035       0  5271.8     .07       0
Bank Sta=4990.1,4994.1
XS Rating Curve= 0 ,0
Exp/Cntr=0.3,0.1

Type RM Length L Ch R = 1 ,8208    ,474,474,474
BEGIN DESCRIPTION:
Stream0562 17.0
END DESCRIPTION:
XS GIS Cut Line= 3
      1943775.01       13925575.        1943475.       13925775.
      1943324.98     13925975.03
#Sta/Elev= 30
  4644.7 1900.18  4661.5 1895.97  4686.8 1890.26  4704.8 1882.69  4708.5 1882.27
  4758.9 1864.32  4795.9 1853.17  4827.4 1841.56  4844.2 1837.41  4881.5 1824.82
  4917.6 1815.83  4935.6 1809.75  4974.4 1808.14  4983.2 1798.82  4983.4 1798.32
  4987.2 1798.82  4987.8 1801.01  4990.6 1803.61  4996.9 1807.55  5051.3 1809.33
  5058.7 1811.01  5077.6 1819.31  5085.1  1823.6  5130.1 1840.28  5167.6  1856.4
  5183.7 1862.23  5201.3 1870.19  5208.8 1874.62  5245.3 1890.32  5255.3 1892.83
#Mann= 6 ,-1 , 0
  4644.7     .07       0  4661.5      .1       0  4844.2    .035       0
  4983.2    .035       0  4987.2    .035       0  5245.3     .07       0
Bank Sta=4983.2,4987.2
XS Rating Curve= 0 ,0
Exp/Cntr=0.3,0.1

Type RM Length L Ch R = 1 ,7734    ,412,412,412
BEGIN DESCRIPTION:
Stream0562 16.0
END DESCRIPTION:
XS GIS Cut Line= 3
      1943575.04     13925224.98        1943275.       13925375.
      1942974.98     13925475.01
#Sta/Elev= 30
  4668.5    1892  4685.4 1891.05  4698.4 1884.47  4705.7 1880.31  4718.9 1875.28
  4769.2 1860.16  4805.3 1846.76  4853.3 1832.56  4869.8 1826.01  4887.4 1822.29
  4903.4  1816.9  4941.1 1795.68  4960.7 1792.35  4973.8  1788.1  4983.4 1787.27
  4984.4  1787.1  4984.7  1786.6  4988.4  1787.1  4994.7 1791.81  5003.1 1794.15
    5023 1793.47  5048.3 1794.94  5086.2 1802.89  5133.6 1819.54  5235.2 1863.66
  5276.2 1880.57  5290.1 1885.04  5298.1 1889.65  5307.6 1891.08  5320.2 1890.63
#Mann= 7 ,-1 , 0
  4668.5     .07       0  4698.4      .1       0  4805.3     .07       0
  4983.4    .035       0  4984.4    .035       0  4988.4    .035       0
  5235.2     .07       0
Bank Sta=4984.4,4988.4
XS Rating Curve= 0 ,0
Exp/Cntr=0.3,0.1

Type RM Length L Ch R = 1 ,7322    ,473,473,473
BEGIN DESCRIPTION:
Stream0562 15.0
END DESCRIPTION:
XS GIS Cut Line= 3
      1943474.98     13924925.01        1943175.       13925025.
      1942924.97     13925225.02
#Sta/Elev= 30
  4670.4 1888.13  4770.6 1854.58  4775.3 1851.75    4780 1848.34  4792.7 1847.15
  4805.3 1841.21  4859.1 1821.26  4878.1  1816.9  4921.9 1803.32    4954 1793.03
  4969.8 1789.23  4997.6 1779.97  5008.4 1777.99    5041 1776.95  5041.3 1776.45
    5045 1776.95    5084 1784.32  5108.1  1782.6  5117.8 1786.43  5131.4 1788.72
  5154.4 1794.94  5165.7 1799.95  5181.3 1809.32  5187.2 1811.88  5204.1 1816.54
  5223.6 1823.41  5242.5 1831.95  5266.5 1837.63  5300.1 1843.54  5306.8 1845.97
#Mann= 6 ,-1 , 0
  4670.4     .07       0  4775.3      .1       0  4921.9    .035       0
    5041    .035       0    5045    .035       0  5117.8     .07       0
Bank Sta=5041,5045
XS Rating Curve= 0 ,0
Exp/Cntr=0.3,0.1

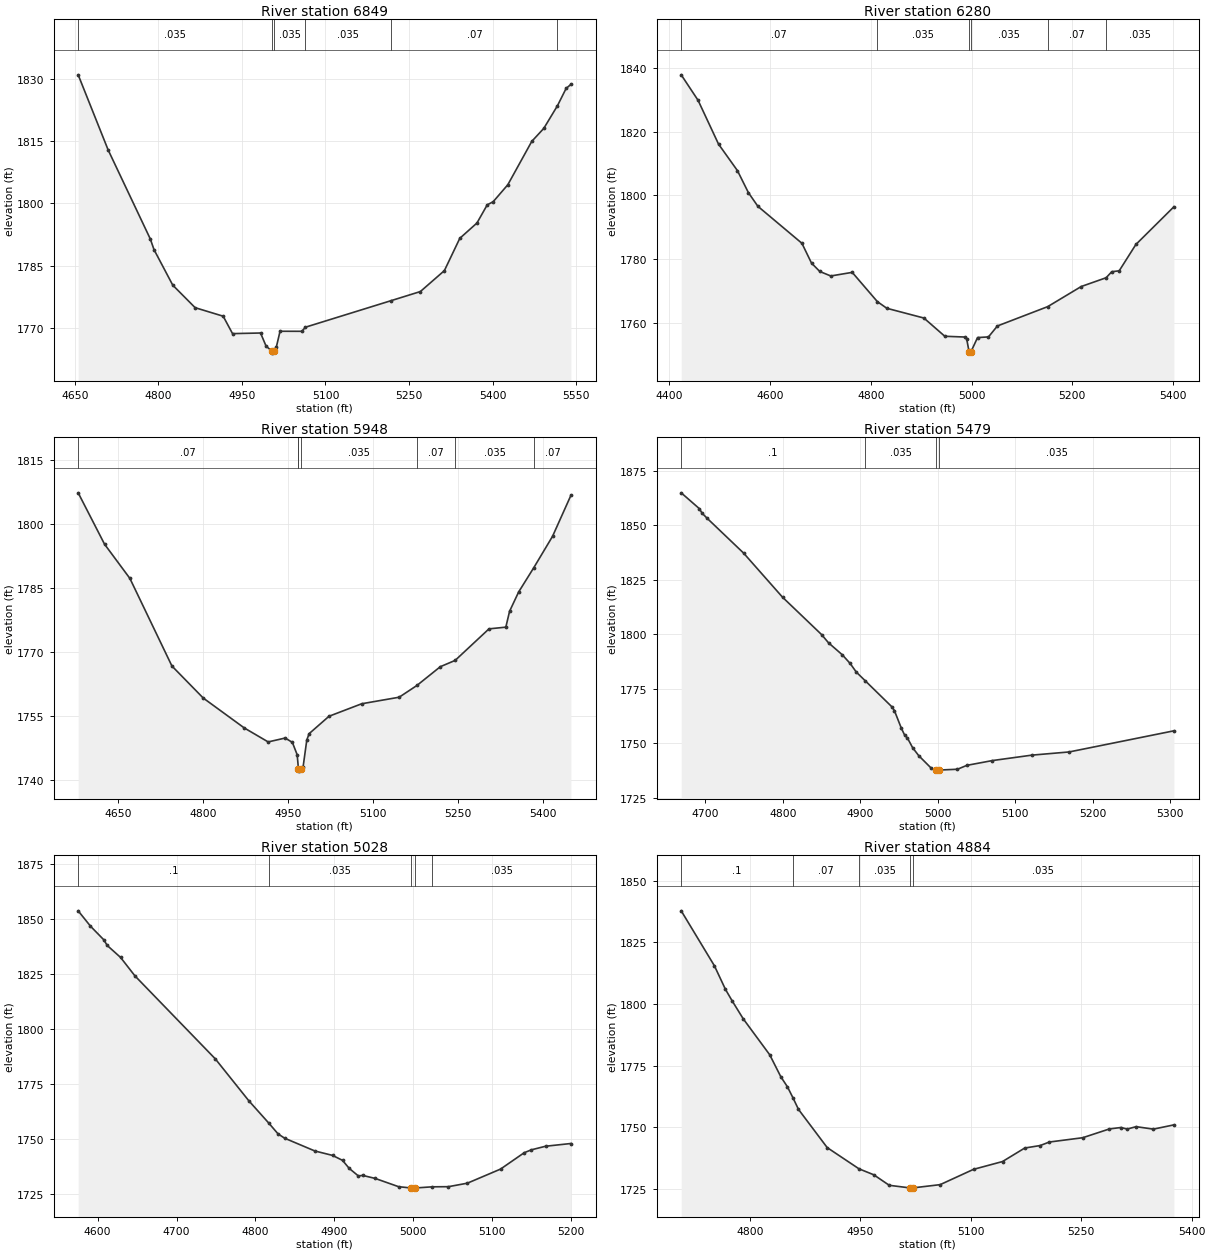
Type RM Length L Ch R = 1 ,6849    ,569,569,569
BEGIN DESCRIPTION:
Stream0562 14.0
END DESCRIPTION:
XS GIS Cut Line= 3
      1943124.99     13924325.02        1942975.       13924625.
      1942852.43     13925160.25
#Sta/Elev= 30
  4656.1 1830.97  4709.8  1812.9  4785.6 1791.41  4792.3 1788.82  4825.9 1780.28
  4866.1 1774.85  4916.4  1772.8  4933.2  1768.6  4983.5 1768.75  4993.4  1765.6
  5003.7  1764.4    5004  1763.9  5007.7  1764.4  5011.9  1765.4  5018.5 1769.17
  5057.8 1769.16  5063.9 1770.14  5218.2 1776.56  5270.4 1778.74  5313.5 1783.78
  5341.2 1791.57    5372 1795.26  5390.4 1799.63  5401.1 1800.39  5427.4 1804.48
  5470.4 1814.93    5492 1818.07  5516.5 1823.52    5532 1827.68  5540.6 1828.66
#Mann= 6 ,-1 , 0
  4656.1    .035       0  5003.7    .035       0  5007.7    .035       0
  5063.9    .035       0  5218.2     .07       0  5516.5    .035       0
Bank Sta=5003.7,5007.7
XS Rating Curve= 0 ,0
Exp/Cntr=0.3,0.1

Type RM Length L Ch R = 1 ,6280    ,332,332,332
BEGIN DESCRIPTION:
Mapping XS a421b795
END DESCRIPTION:
XS GIS Cut Line= 3
      1942671.34     13923886.66      1942544.37     13924326.48
      1942254.45     13924758.55
#Sta/Elev= 30
  4423.6 1837.82  4457.1 1829.82  4497.7 1816.08  4535.2 1807.77    4557 1800.85
  4575.8 1796.57  4663.2 1784.97  4682.3 1778.74  4698.7 1776.12  4720.5 1774.71
  4763.1 1775.84    4813 1766.66  4831.8 1764.57  4905.4 1761.51  4946.9 1755.79
  4986.6 1755.55  4990.2 1755.05    4995    1751  4995.2  1750.5    4999    1751
  5011.9 1755.38  5033.6 1755.59  5051.3 1759.02  5151.2 1765.09  5217.7  1771.4
  5267.1 1774.15  5278.3 1776.04  5293.1 1776.33  5326.2 1784.59  5401.7 1796.42
#Mann= 6 ,-1 , 0
  4423.6     .07       0    4813    .035       0    4995    .035       0
    4999    .035       0  5151.2     .07       0  5267.1    .035       0
Bank Sta=4995,4999
XS Rating Curve= 0 ,0
Exp/Cntr=0.3,0.1

Type RM Length L Ch R = 1 ,5948    ,469,469,469
BEGIN DESCRIPTION:
Stream0562 13.0
END DESCRIPTION:
XS GIS Cut Line= 3
      1942525.03     13923924.97        1942225.       13924225.
      1942040.08      13924629.2
#Sta/Elev= 30
  4579.9 1807.22  4626.4 1795.19  4671.1 1787.17  4745.2 1766.66  4800.4 1759.16
  4872.7 1752.16  4914.9 1748.88  4944.9 1749.79  4957.6 1748.77  4966.1 1745.87
  4968.1 1742.84  4968.3 1742.54  4968.6 1742.04  4972.3 1742.54  4976.6 1743.11
    4983  1749.3  4987.1 1750.81  5022.2 1754.89  5079.9 1757.82  5145.9 1759.35
  5177.2  1762.1  5218.5  1766.5  5244.6 1767.97  5304.3 1775.36    5334 1775.76
  5340.6 1779.48  5356.6    1784  5383.4 1789.71  5416.4 1797.04  5448.7 1806.61
#Mann= 7 ,-1 , 0
  4579.9     .07       0  4968.1    .035       0  4968.3    .035       0
  4972.3    .035       0  5177.2     .07       0  5244.6    .035       0
  5383.4     .07       0
Bank Sta=4968.3,4972.3
XS Rating Curve= 0 ,0
Exp/Cntr=0.3,0.1

Type RM Length L Ch R = 1 ,5479    ,451,451,451
BEGIN DESCRIPTION:
Stream0562 12.0
END DESCRIPTION:
XS GIS Cut Line= 3
      1942075.01     13923624.98        1941925.       13923925.
        1941925.     13924224.96
#Sta/Elev= 30
  4669.1 1864.83  4692.5 1857.58    4696 1855.51  4702.5 1853.18  4749.5 1837.24
  4799.8 1816.99  4850.1 1799.89  4859.1  1796.1  4876.9  1790.6    4887 1786.63
  4894.9 1782.69  4906.3 1778.75  4940.7 1766.81    4944 1765.08    4953 1756.97
  4957.4 1753.69  4960.8 1752.53  4967.5 1748.07  4975.4  1744.4  4991.2 1738.78
    4998 1737.81  4998.2 1737.31  5001.7 1737.31    5002 1737.81  5025.4 1738.17
  5037.4 1739.95  5070.4 1742.15  5121.4 1744.64  5169.4  1746.1  5304.5 1755.78
#Mann= 4 ,-1 , 0
  4669.1      .1       0  4906.3    .035       0    4998    .035       0
    5002    .035       0
Bank Sta=4998,5002
XS Rating Curve= 0 ,0
Exp/Cntr=0.3,0.1

Type RM Length L Ch R = 1 ,5028    ,144,144,144
BEGIN DESCRIPTION:
Stream0562 11.0
END DESCRIPTION:
XS GIS Cut Line= 3
      1941824.97     13923475.03        1941525.       13923775.
        1941525.     13923974.99
#Sta/Elev= 30
  4575.4 1853.65    4591 1846.68  4607.9 1840.49  4612.2 1837.94  4629.1 1832.52
  4647.3 1824.15  4749.1 1786.52  4791.5 1767.54  4816.7 1757.45  4828.6 1752.49
    4837 1750.52  4875.2 1744.74  4897.6 1742.73  4910.3 1740.48  4918.8 1736.82
  4930.4 1733.41  4935.8 1733.66  4951.6 1732.29  4981.3 1728.54  4997.6 1727.93
  4997.9 1727.43  5001.6 1727.93  5024.1 1728.48  5044.5 1728.54  5068.5 1730.13
  5110.5 1736.52  5140.5 1743.95  5149.5 1745.25  5167.5 1746.88  5199.6 1748.12
#Mann= 5 ,-1 , 0
  4575.4      .1       0  4816.7    .035       0  4997.6    .035       0
  5001.6    .035       0  5024.1    .035       0
Bank Sta=4997.6,5001.6
XS Rating Curve= 0 ,0
Exp/Cntr=0.3,0.1

Type RM Length L Ch R = 1 ,4884    ,298,298,298
BEGIN DESCRIPTION:
Mapping XS edb7150b
END DESCRIPTION:
XS GIS Cut Line= 3
      1941439.24     13923384.86      1941416.69     13923745.38
      1941456.82     13924050.73
#Sta/Elev= 30
  4706.7 1837.83  4751.8 1815.51  4766.8 1805.94  4775.8 1801.32  4790.9    1794
  4826.9 1779.39    4842 1770.46    4851 1766.36  4858.6 1761.84    4866  1757.2
    4905 1741.69  4948.2 1733.07  4968.2 1730.66  4989.3 1726.38  5017.3 1725.33
  5017.6 1724.83  5021.3 1725.33  5058.4 1726.65  5103.7 1732.86  5143.1 1736.03
  5173.3 1741.52  5194.3 1742.53  5206.6 1743.95    5252  1745.7  5288.3 1749.27
  5303.9 1749.85  5312.5 1749.22  5324.6 1750.19    5348 1749.19  5375.9 1750.92
#Mann= 5 ,-1 , 0
  4706.7      .1       0  4858.6     .07       0  4948.2    .035       0
  5017.3    .035       0  5021.3    .035       0
Bank Sta=5017.3,5021.3
XS Rating Curve= 0 ,0
Exp/Cntr=0.3,0.1

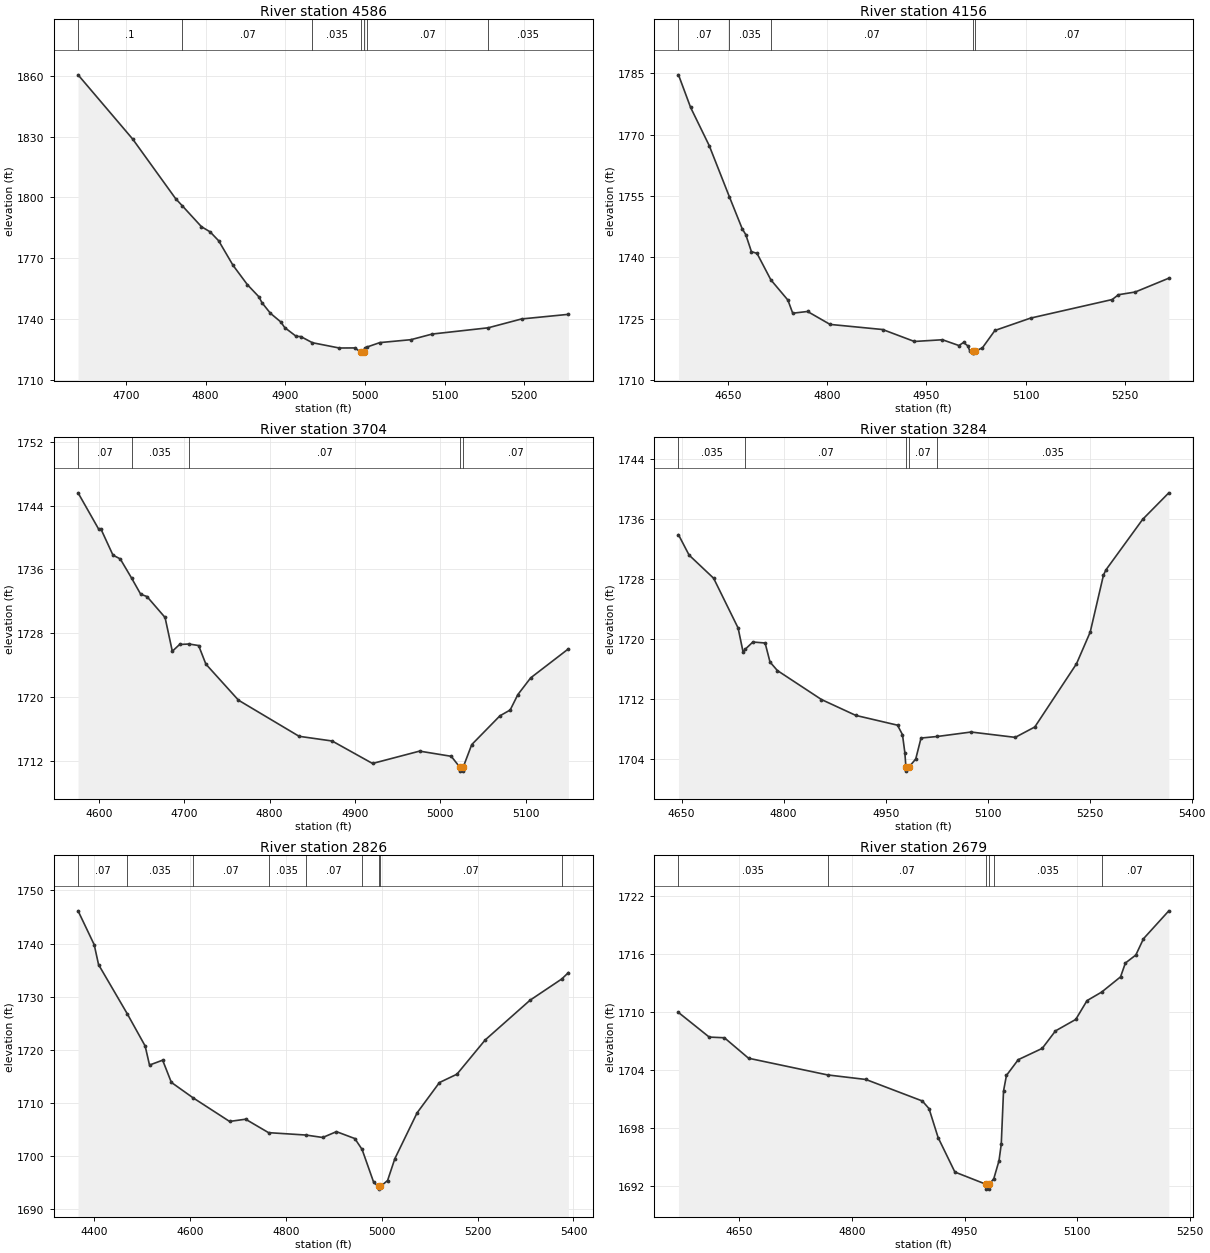
Type RM Length L Ch R = 1 ,4586    ,430,430,430
BEGIN DESCRIPTION:
Stream0562 10.0
END DESCRIPTION:
XS GIS Cut Line= 3
      1941374.99     13923325.01        1941175.       13923625.
        1941225.     13923875.01
#Sta/Elev= 30
  4639.8 1860.56  4708.4 1828.81  4762.2 1799.43  4770.8 1795.79  4794.7 1785.53
  4805.5 1783.01  4816.3 1778.58  4834.3 1766.47  4852.4 1756.87  4866.8  1750.9
  4870.6 1748.01  4881.2 1742.79  4894.3 1738.47  4899.2  1735.7  4913.7 1731.34
  4919.3 1731.27    4934 1728.21  4967.7  1725.6  4987.3 1725.64  4994.6 1723.57
  4994.8 1723.07  4998.6 1723.57  4999.7 1725.48  5002.1 1726.03  5018.6 1728.27
  5057.6 1729.71  5084.4  1732.5  5154.6 1735.58  5196.5 1739.95  5255.3 1742.23
#Mann= 7 ,-1 , 0
  4639.8      .1       0  4770.8     .07       0    4934    .035       0
  4994.6    .035       0  4998.6    .035       0  5002.1     .07       0
  5154.6    .035       0
Bank Sta=4994.6,4998.6
XS Rating Curve= 0 ,0
Exp/Cntr=0.3,0.1

Type RM Length L Ch R = 1 ,4156    ,452,452,452
BEGIN DESCRIPTION:
Stream0562 9.0
END DESCRIPTION:
XS GIS Cut Line= 3
      1941074.97     13923325.03        1940775.       13923625.
      1940874.99     13923924.96
#Sta/Elev= 30
  4575.7 1784.65    4594 1776.68  4622.1 1767.35  4652.4  1754.9  4671.9 1747.03
  4677.3 1745.59  4685.8 1741.44  4694.3    1741  4715.2 1734.53  4740.9 1729.59
  4748.2 1726.38  4770.6  1726.8  4804.6 1723.64    4884 1722.39  4931.9 1719.47
  4974.3 1719.89  4999.1 1718.48  5006.1 1719.22  5012.4 1718.42  5015.6 1717.16
  5019.9 1717.12  5020.2 1716.62  5023.9 1717.12  5034.6 1717.91  5053.5 1722.16
  5107.3 1725.18  5230.6 1729.72  5240.1  1730.9  5265.4 1731.56  5316.1 1734.94
#Mann= 5 ,-1 , 0
  4575.7     .07       0  4652.4    .035       0  4715.2     .07       0
  5019.9     .05       0  5023.9     .07       0
Bank Sta=5019.9,5023.9
XS Rating Curve= 0 ,0
Exp/Cntr=0.3,0.1

Type RM Length L Ch R = 1 ,3704    ,420,420,420
BEGIN DESCRIPTION:
Stream0562 8.0
END DESCRIPTION:
XS GIS Cut Line= 3
        1940725.       13923075.        1940425.       13923375.
        1940425.     13923525.04
#Sta/Elev= 30
  4575.7 1745.61  4599.7 1741.08  4602.4 1741.09  4616.6 1737.79  4625.1 1737.32
  4638.3 1734.93  4649.1 1732.88  4656.4  1732.6  4677.6 1729.97  4686.1 1725.73
  4694.6 1726.58  4705.6 1726.64  4716.9 1726.45  4725.4 1724.12  4763.6 1719.59
  4834.6 1715.06  4873.3 1714.47  4920.6 1711.65  4975.7  1713.2  5012.8 1712.55
  5022.8 1711.19    5023 1710.69  5026.5 1710.69  5026.8 1711.19  5036.8 1714.02
  5069.8 1717.63  5081.8 1718.36  5090.8 1720.29  5105.8 1722.39    5150 1726.03
#Mann= 5 ,-1 , 0
  4575.7     .07       0  4638.3    .035       0  4705.6     .07       0
  5022.8     .05       0  5026.8     .07       0
Bank Sta=5022.8,5026.8
XS Rating Curve= 0 ,0
Exp/Cntr=0.3,0.1

Type RM Length L Ch R = 1 ,3284    ,458,458,458
BEGIN DESCRIPTION:
Stream0562 7.0
END DESCRIPTION:
XS GIS Cut Line= 3
      1940524.96     13922875.02        1940225.       13923075.
      1939924.97     13923275.02
#Sta/Elev= 30
  4645.3 1733.89  4660.9 1731.18    4697  1728.1    4733 1721.48  4740.3 1718.29
  4743.1 1718.63  4754.7 1719.62  4772.7 1719.49  4779.9 1716.96  4790.7 1715.83
  4855.6 1711.97  4906.1 1709.86  4967.4 1708.56  4974.7  1707.3  4978.2 1704.91
  4979.8 1702.95  4980.1 1702.45  4983.8 1702.95  4994.2 1704.06    5002 1706.85
  5026.2 1707.06  5075.6 1707.65  5140.5 1706.94  5169.3 1708.32  5230.6 1716.72
  5250.8 1720.94  5270.3 1728.52  5273.9 1729.21    5328 1735.94  5366.4 1739.46
#Mann= 5 ,-1 , 0
  4645.3    .035       0  4743.1     .07       0  4979.8     .05       0
  4983.8     .07       0  5026.2    .035       0
Bank Sta=4979.8,4983.8
XS Rating Curve= 0 ,0
Exp/Cntr=0.3,0.1

Type RM Length L Ch R = 1 ,2826    ,147,147,147
BEGIN DESCRIPTION:
Stream0562 6.0
END DESCRIPTION:
XS GIS Cut Line= 3
      1940551.22     13922725.14        1939925.       13922825.
      1939692.69     13923137.11
#Sta/Elev= 30
  4366.2 1746.15  4399.9 1739.77    4409 1736.02  4469.2 1726.72  4506.2 1720.71
  4515.3 1717.12  4542.7 1718.04  4560.9 1713.86  4605.8 1710.98  4682.4 1706.51
  4715.8 1706.93  4763.7  1704.4  4841.6 1703.95  4876.8 1703.49  4905.4 1704.59
  4943.7 1703.29  4958.9 1701.24  4983.2 1695.02  4993.3 1694.27  4993.6 1693.77
  4997.3 1694.27  5012.1 1695.39  5027.2 1699.49  5073.7 1708.13  5120.3 1713.83
  5156.8  1715.4  5215.8 1721.85  5309.3 1729.32  5375.5 1733.32  5389.4 1734.52
#Mann= 9 ,-1 , 0
  4366.2     .07       0  4469.2    .035       0  4605.8     .07       0
  4763.7    .035       0  4841.6     .07       0  4958.9     .07       0
  4993.3     .05       0  4997.3     .07       0  5375.5     .07       0
Bank Sta=4993.3,4997.3
XS Rating Curve= 0 ,0
Exp/Cntr=0.3,0.1

Type RM Length L Ch R = 1 ,2679    ,124,124,124
BEGIN DESCRIPTION:
Mapping XS 5491ec29
END DESCRIPTION:
XS GIS Cut Line= 2
       1940305.1     13922710.07      1939653.24      13922686.1
#Sta/Elev= 30
  4569.4 1709.96  4610.3 1707.41  4630.5 1707.34  4662.6 1705.22  4767.8 1703.49
  4818.7 1703.02  4893.8 1700.79  4902.7    1700  4914.8    1697  4937.1 1693.43
  4978.6 1692.16  4978.9 1691.66  4982.6 1691.66  4982.8 1692.16  4988.9 1692.75
  4995.8  1694.6  4998.8 1696.32  5001.8 1701.82  5005.7 1703.44  5021.4 1705.07
  5053.3 1706.24  5070.9 1708.05  5097.9 1709.24  5112.9 1711.19  5132.3 1712.07
  5157.5 1713.65  5163.9 1715.08  5177.8 1715.91    5188  1717.6  5221.7 1720.49
#Mann= 6 ,-1 , 0
  4569.4    .035       0  4767.8     .07       0  4978.6     .05       0
  4982.8     .07       0  4988.9    .035       0  5132.3     .07       0
Bank Sta=4978.6,4982.8
XS Rating Curve= 0 ,0
Exp/Cntr=0.3,0.1

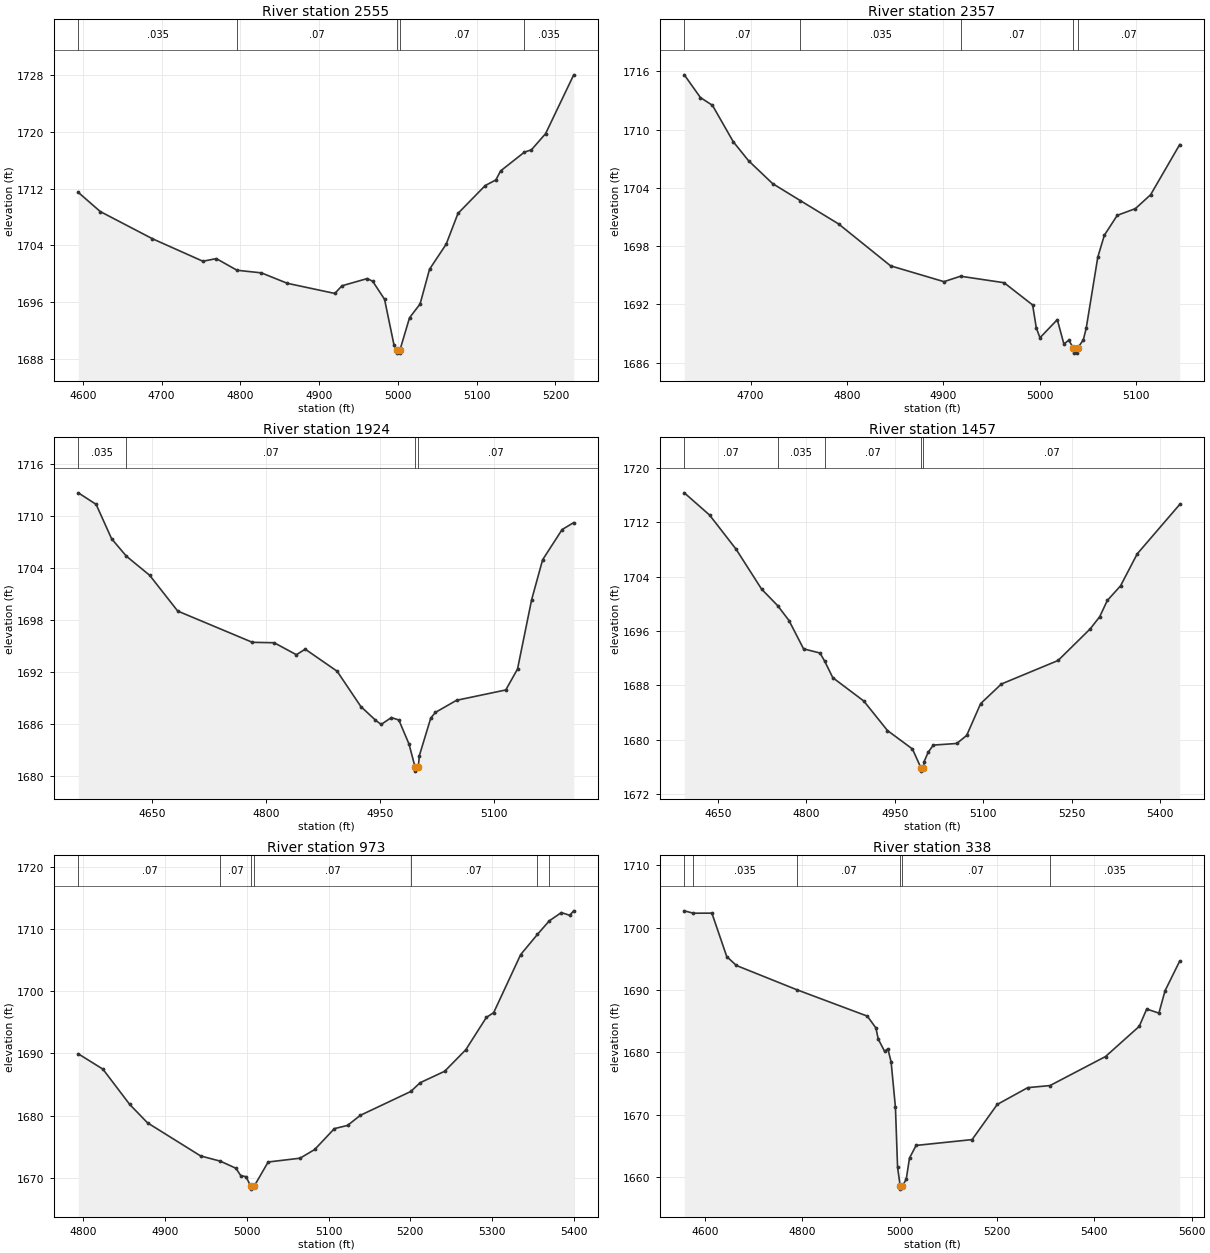
Type RM Length L Ch R = 1 ,2555    ,198,198,198
BEGIN DESCRIPTION:
Mapping XS 0ed10d6d
END DESCRIPTION:
XS GIS Cut Line= 2
      1940329.81     13922613.09      1939702.36     13922571.91
#Sta/Elev= 30
  4594.4 1711.48  4622.3 1708.78  4688.5 1704.95  4752.5 1701.78  4769.6 1702.15
  4795.8 1700.51  4826.8 1700.14  4859.7 1698.67    4920 1697.24    4929 1698.32
  4961.2 1699.34  4968.1 1698.95  4983.1 1696.42  4995.1 1689.98  4998.6 1689.33
  4998.9 1688.83  5002.6 1688.83  5002.8 1689.33  5014.8 1693.81  5028.2 1695.76
  5040.2 1700.65  5061.3 1704.18  5076.3 1708.52  5110.8 1712.44  5124.4 1713.24
  5130.4 1714.51  5160.7 1717.16  5169.5 1717.48  5187.5 1719.76  5223.2 1728.05
#Mann= 5 ,-1 , 0
  4594.4    .035       0  4795.8     .07       0  4998.6     .05       0
  5002.8     .07       0  5160.7    .035       0
Bank Sta=4998.6,5002.8
XS Rating Curve= 0 ,0
Exp/Cntr=0.3,0.1

Type RM Length L Ch R = 1 ,2357    ,433,433,433
BEGIN DESCRIPTION:
Stream0562 5.0
END DESCRIPTION:
XS GIS Cut Line= 3
      1940374.96     13922524.99        1940025.       13922425.
      1939874.96       13922425.
#Sta/Elev= 30
  4631.3 1715.65    4648 1713.31  4660.5 1712.51  4682.1 1708.76  4697.9 1706.81
  4722.9 1704.45  4751.8 1702.69  4791.3  1700.3  4845.3 1695.98  4900.7 1694.35
  4917.9 1694.91  4963.1 1694.24  4992.7 1691.95  4996.5 1689.59  5000.3 1688.57
  5018.3 1690.44  5025.1 1687.94  5030.3 1688.32    5035 1687.49  5035.3 1686.99
    5039 1686.99  5039.3 1687.49  5045.3 1688.36  5048.3 1689.56  5060.3 1696.87
  5067.1 1699.13  5080.5 1701.18  5099.3 1701.87  5115.1  1703.3  5145.3 1708.47
#Mann= 5 ,-1 , 0
  4631.3     .07       0  4751.8    .035       0  4917.9     .07       0
    5035     .05       0  5039.3     .07       0
Bank Sta=5035,5039.3
XS Rating Curve= 0 ,0
Exp/Cntr=0.3,0.1

Type RM Length L Ch R = 1 ,1924    ,467,467,467
BEGIN DESCRIPTION:
Stream0562 4.0
END DESCRIPTION:
XS GIS Cut Line= 3
      1940424.97     13922224.99        1940025.       13922025.
      1939825.04     13922074.99
#Sta/Elev= 30
  4552.4 1712.63  4575.9  1711.3  4596.3 1707.34  4615.8 1705.33  4646.4 1703.14
  4683.5 1699.01  4781.9 1695.41  4810.7 1695.36    4840 1693.98  4851.6 1694.62
  4893.7 1692.08    4925 1688.01  4944.3 1686.44  4951.8 1685.95  4965.2 1686.74
  4975.1 1686.46  4988.5 1683.69  4996.4 1681.07  4996.7 1680.57  5000.7 1681.07
  5002.2 1682.37  5017.2 1686.69  5023.4 1687.34  5051.2 1688.73  5116.1 1689.92
  5131.6 1692.33  5150.2 1700.31  5164.7 1704.92  5190.4  1708.4  5205.7  1709.2
#Mann= 4 ,-1 , 0
  4552.4    .035       0  4615.8     .07       0  4996.4     .05       0
  5000.7     .07       0
Bank Sta=4996.4,5000.7
XS Rating Curve= 0 ,0
Exp/Cntr=0.3,0.1

Type RM Length L Ch R = 1 ,1457    ,484,484,484
BEGIN DESCRIPTION:
Stream0562 3.0
END DESCRIPTION:
XS GIS Cut Line= 3
      1940524.98     13921724.99        1940125.       13921625.
      1939724.99       13921775.
#Sta/Elev= 30
  4593.2 1716.33    4636 1713.06  4680.9 1708.04  4724.2 1702.16  4751.3 1699.74
  4770.6 1697.54  4795.3 1693.37  4823.1 1692.76  4831.2 1691.54  4844.8 1689.13
  4897.3  1685.7  4937.5 1681.35  4979.8 1678.64  4994.1 1675.88  4994.4 1675.38
  4998.5 1675.88  4999.4 1676.74  5006.5 1678.17  5015.2 1679.21  5054.9 1679.45
  5071.7 1680.63  5095.3 1685.31  5130.5  1688.2  5226.6 1691.66  5281.1 1696.32
  5297.1  1698.1    5310 1700.49  5332.4 1702.64  5360.7 1707.35  5432.7 1714.62
#Mann= 5 ,-1 , 0
  4593.2     .07       0  4751.3    .035       0  4831.2     .07       0
  4994.1     .05       0  4998.5     .07       0
Bank Sta=4994.1,4998.5
XS Rating Curve= 0 ,0
Exp/Cntr=0.3,0.1

Type RM Length L Ch R = 1 ,973     ,635,635,635
BEGIN DESCRIPTION:
Stream0562 2.0
END DESCRIPTION:
XS GIS Cut Line= 3
      1940225.05     13921124.99        1940025.       13921175.
        1939625.       13921175.
#Sta/Elev= 30
  4793.8 1689.92  4823.9 1687.46  4856.7 1681.79  4878.5 1678.83  4943.5 1673.51
  4967.7 1672.67  4986.7 1671.53  4992.5 1670.36  4999.1 1670.17  5004.6 1668.68
    5005 1668.18  5009.1 1668.68  5026.1 1672.54  5065.1 1673.15  5083.1 1674.55
  5107.1  1677.9  5123.3 1678.42  5138.9 1680.04  5200.6 1683.87  5212.1 1685.28
  5242.1 1687.12  5267.9 1690.57  5293.1 1695.77  5302.1 1696.55  5335.1 1705.87
  5355.6 1709.11  5370.1 1711.29  5384.9 1712.62  5395.1 1712.18    5400  1712.9
#Mann= 7 ,-1 , 0
  4793.8     .07       0  4967.7     .07       0  5004.6     .05       0
  5009.1     .07       0  5200.6     .07       0  5355.6    .035       0
  5370.1     .07       0
Bank Sta=5004.6,5009.1
XS Rating Curve= 0 ,0
Exp/Cntr=0.3,0.1

Type RM Length L Ch R = 1 ,338     ,262,262,262
BEGIN DESCRIPTION:
Stream0562 1.0
END DESCRIPTION:
XS GIS Cut Line= 3
       1940556.2     13920991.31       1940013.1     13920707.78
      1939624.97     13920825.01
#Sta/Elev= 30
  4557.4 1702.68  4575.8  1702.3  4614.1 1702.31  4644.6 1695.36  4664.4 1693.93
  4788.5 1690.05  4933.5 1685.82  4951.2 1683.92  4955.9 1682.15    4969 1680.19
  4975.7 1680.58  4982.4  1678.5  4991.3  1671.2  4995.7 1661.59  5001.1 1658.62
  5001.4 1658.12  5005.6 1658.62  5013.5 1659.71  5020.2  1663.1  5033.8 1665.12
  5148.8 1666.05  5200.5 1671.68  5263.2 1674.37  5308.9  1674.7    5423 1679.35
  5492.3 1684.18  5507.7 1686.96  5532.7  1686.3  5545.3 1689.87  5575.5 1694.64
#Mann= 6 ,-1 , 0
  4557.4     .07       0  4575.8    .035       0  4788.5     .07       0
  5001.1     .05       0  5005.6     .07       0  5308.9    .035       0
Bank Sta=5001.1,5005.6
XS Rating Curve= 0 ,0
Exp/Cntr=0.3,0.1

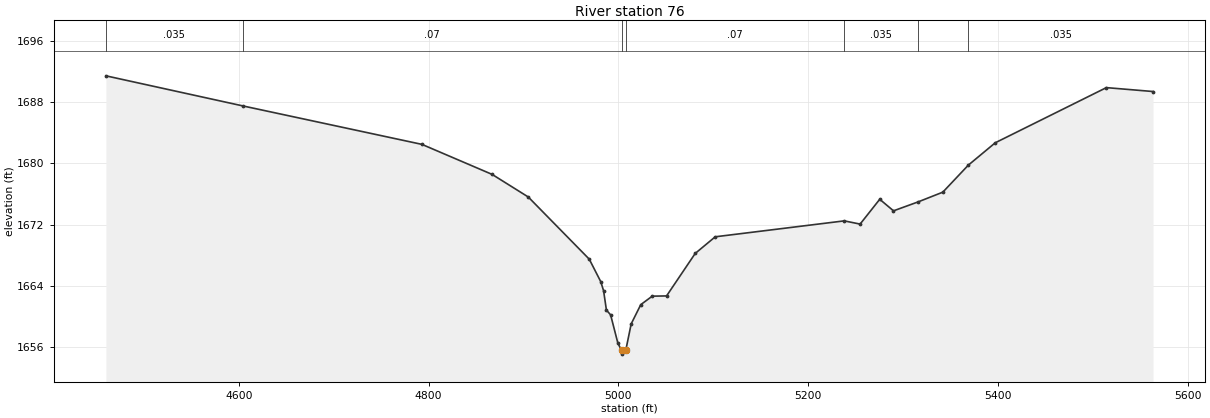
Type RM Length L Ch R = 1 ,76      ,0,0,0
BEGIN DESCRIPTION:
Stream0562 0.0
END DESCRIPTION:
XS GIS Cut Line= 4
      1940517.87      13920814.9      1940094.27     13920589.21
       1939840.8     13920561.44      1939500.53     13920703.79
#Sta/Elev= 30
  4459.8 1691.42  4604.2 1687.49  4792.9 1682.47  4866.9 1678.55    4905  1675.6
  4969.3 1667.48  4981.4 1664.55  4984.4 1663.36  4987.4 1660.83  4991.8 1660.21
  4999.5  1656.5  5003.3 1655.58  5003.6 1655.08  5007.8 1655.58  5013.5 1659.03
  5023.6 1661.54  5035.7 1662.65  5050.8 1662.68    5081 1668.23  5102.1  1670.4
  5238.1 1672.48  5254.8 1672.06  5275.5  1675.3    5290 1673.79  5316.2 1674.97
    5342 1676.23  5368.9 1679.76  5397.3 1682.68  5514.4 1689.88  5563.6 1689.37
#Mann= 7 ,-1 , 0
  4459.8    .035       0  4604.2     .07       0  5003.3     .05       0
  5007.8     .07       0  5238.1    .035       0  5316.2     .07       0
  5368.9    .035       0
Bank Sta=5003.3,5007.8
XS Rating Curve= 0 ,0
Exp/Cntr=0.3,0.1

Chan Stop Cuts=-1
Use User Specified Reach Order=0
Composite Channel Slope=5