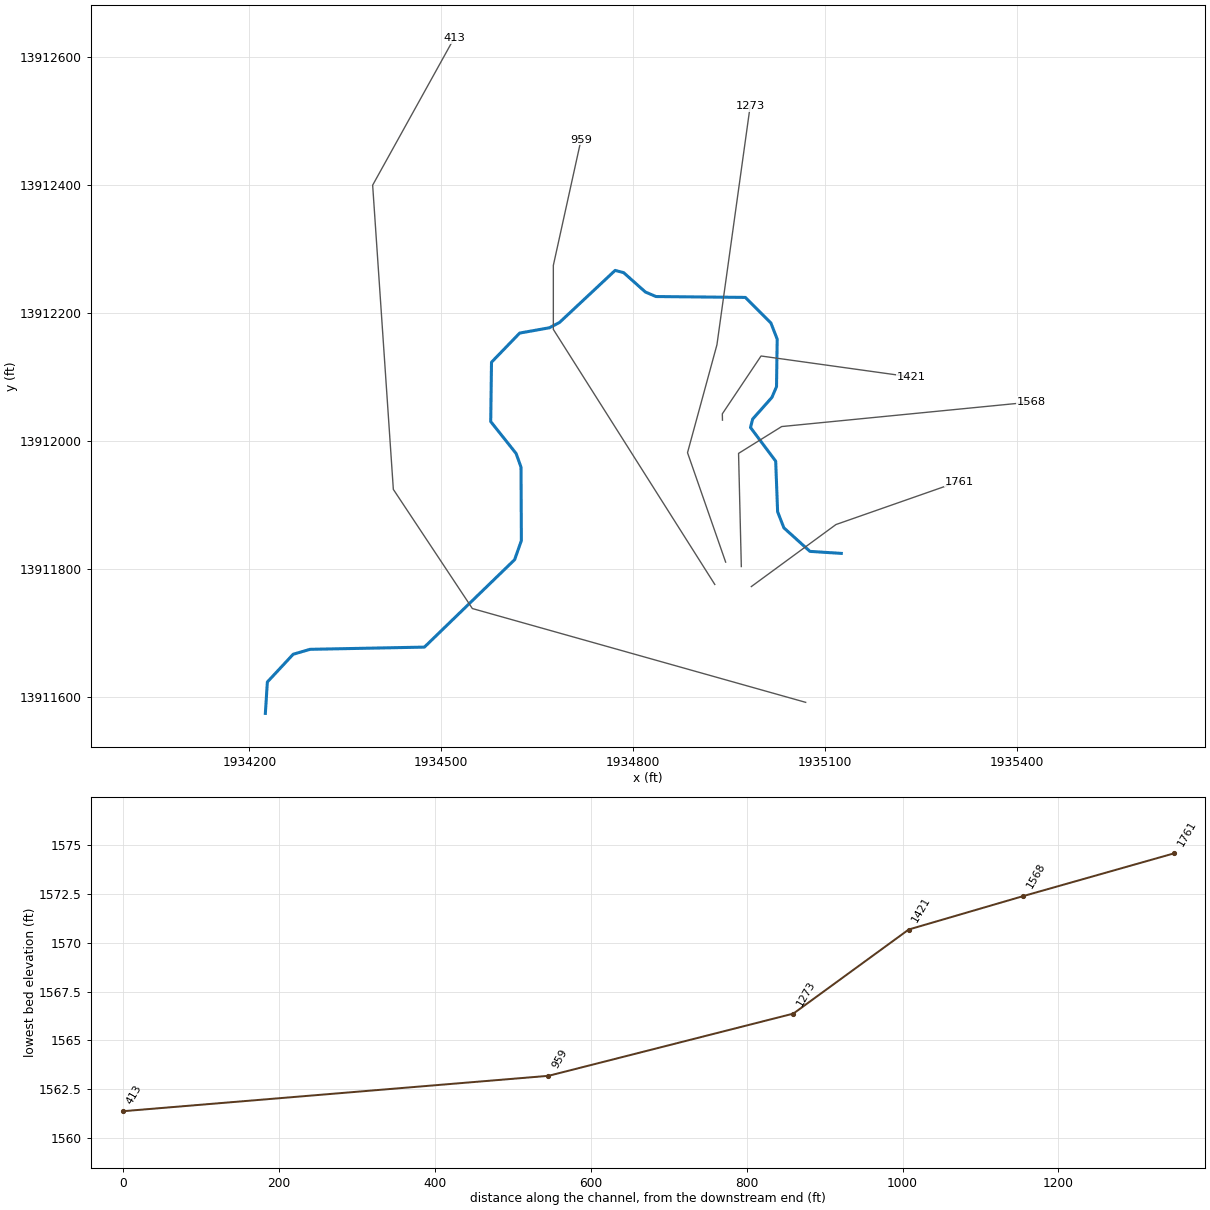
--- Stream0567.prj (project) ---

Proj Title=Stream0567 Base Level Engineering
Current Plan=p01
Default Exp/Contr=0.3,0.1
English Units
Geom File=g01
Flow File=f01
Plan File=p01
BEGIN DESCRIPTION:
Stream0567
END DESCRIPTION:

--- Stream0567.p01 (plan) ---

Plan Title=Multiple Run
Short Identifier=Multiple
Geom File=g01
Flow File=f01
Subcritical Flow
K Sum by GR= 0
Std Step Tol= 0.01
Critical Tol= 0.01
Num of Std Step Trials= 20
Max Error Tol= 0.3
Flow Tol Ratio= 0.001
Split Flow NTrial= 30
Split Flow Tol= 0.02
Split Flow Ratio= 0.02
Log Output Level= 0
Friction Slope Method= 1
Unsteady Friction Slope Method= 2
Unsteady Bridges Friction Slope Method= 1
Parabolic Critical Depth
Global Vel Dist=  1 , 1 , 1
Global Log Level= 0
CheckData=True
Encroach Param= -1, 0, 0, 0
BEGIN DESCRIPTION:
Multiple Run
END DESCRIPTION:

--- Stream0567.f01 (steady flow) ---

Flow Title=Multiple
Number of Profiles=7
Profile Names=10-year,25-year,50-year,1pct_min,100-year,1pct_plu,500-year
River Rch & RM= Stream0567,Reach-1,1761
    1072    1834    2564    1736    3465    6913    6238
River Rch & RM= Stream0567,Reach-1,1273
    1335    2314    3261    2224    4437    8853    8107
Boundary for River Rch & Prof#=Stream0567,Reach-1,1
Up Type=0
Dn Type=3
Dn Slope=0.005
Boundary for River Rch & Prof#=Stream0567,Reach-1,2
Up Type=0
Dn Type=3
Dn Slope=0.005
Boundary for River Rch & Prof#=Stream0567,Reach-1,3
Up Type=0
Dn Type=3
Dn Slope=0.005
Boundary for River Rch & Prof#=Stream0567,Reach-1,4
Up Type=0
Dn Type=3
Dn Slope=0.005
Boundary for River Rch & Prof#=Stream0567,Reach-1,5
Up Type=0
Dn Type=3
Dn Slope=0.005
Boundary for River Rch & Prof#=Stream0567,Reach-1,6
Up Type=0
Dn Type=3
Dn Slope=0.005
Boundary for River Rch & Prof#=Stream0567,Reach-1,7
Up Type=0
Dn Type=3
Dn Slope=0.005

--- Stream0567.g01 (geometry) ---

Geom Title=Existing Conditions

River Reach=Stream0567,Reach-1
Reach XY= 30
      1935125.00     13911825.00      1935075.99     13911828.12
      1935035.26     13911864.90      1935025.46     13911890.12
      1935022.45     13911969.10      1934983.08     13912021.70
      1934986.47     13912034.91      1935016.59     13912068.83
      1935023.74     13912085.47      1935024.81     13912159.78
      1935015.01     13912184.95      1934975.00     13912225.00
      1934835.41     13912226.35      1934818.80     13912233.47
      1934784.85     13912263.68      1934771.59     13912267.20
      1934684.66     13912185.83      1934668.91     13912177.57
      1934622.42     13912169.26      1934578.37     13912123.72
      1934577.16     13912030.98      1934616.86     13911981.06
      1934624.49     13911959.78      1934625.06     13911844.99
      1934614.53     13911815.20      1934473.54     13911678.54
      1934294.90     13911675.09      1934268.53     13911667.42
      1934228.12     13911624.02      1934225.00     13911575.00

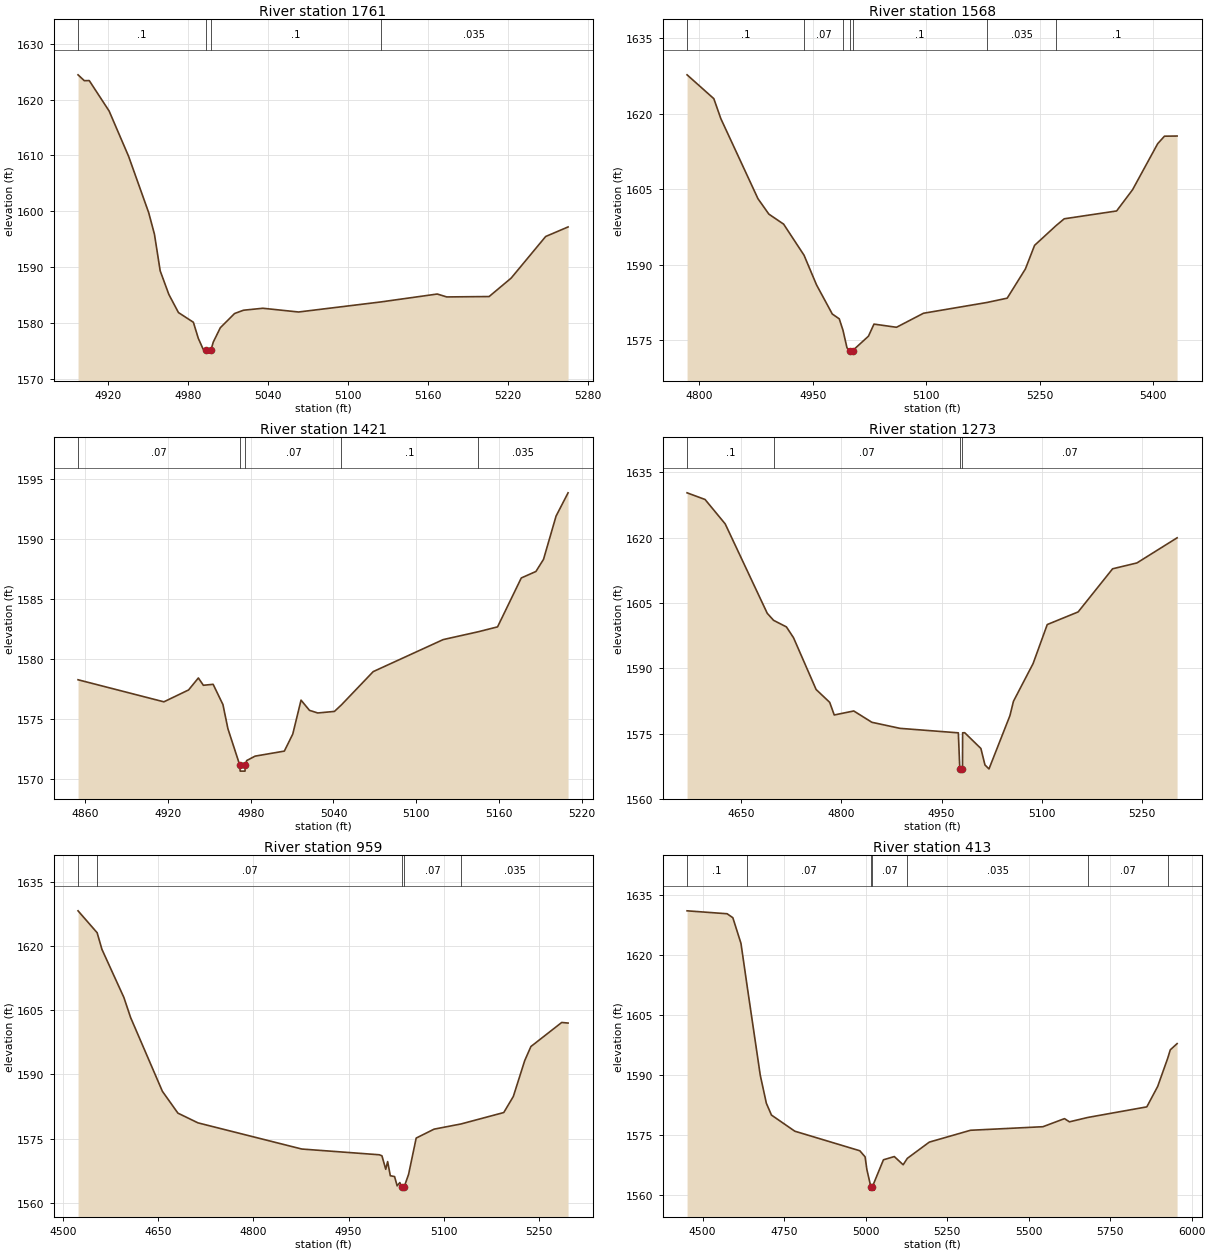
Type RM Length L Ch R = 1,1761,193,193,193
BEGIN DESCRIPTION:
Stream0567 5.0
END DESCRIPTION:
XS GIS Cut Line= 3
      1934984.38     13911773.15      1935116.59     13911870.05
      1935308.74     13911937.31
#Sta/Elev= 30
  4897.7 1624.43  4902.4 1623.38  4906.1 1623.40  4921.0 1617.95  4935.6 1609.84
  4950.7 1599.72  4955.0 1595.87  4959.3 1589.31  4965.8 1585.08  4973.0 1581.83
  4984.2 1580.09  4987.9 1577.20  4991.5 1575.29  4993.3 1575.06  4993.6 1574.56
  4997.1 1574.56  4997.3 1575.06  4999.1 1576.53  5004.4 1579.11  5015.1 1581.66
  5021.8 1582.25  5036.3 1582.60  5063.1 1581.93  5124.7 1583.73  5167.1 1585.15
  5174.2 1584.63  5206.0 1584.70  5222.5 1588.00  5248.4 1595.46  5265.2 1597.17
#Mann=4,-1,0
  4897.7     0.1       0  4993.3    0.05       0  4997.3     0.1       0
  5124.7   0.035       0
Bank Sta=4993.3,4997.3
Exp/Cntr=0.3,0.1

Type RM Length L Ch R = 1,1568,147,147,147
BEGIN DESCRIPTION:
Stream0567 4.0
END DESCRIPTION:
XS GIS Cut Line= 4
      1934968.76     13911804.41      1934964.43     13911981.27
      1935031.84     13912023.20      1935421.76     13912061.51
#Sta/Elev= 30
  4783.8 1627.72  4819.2 1622.98  4828.4 1619.03  4877.6 1603.08  4892.0 1600.02
  4911.5 1598.03  4938.5 1591.85  4955.0 1585.96  4975.9 1580.15  4985.1 1579.20
  4990.0 1576.93  4995.3 1573.44  4998.8 1572.88  4999.0 1572.38  5002.8 1572.88
  5023.7 1575.75  5031.0 1578.15  5060.8 1577.52  5096.5 1580.31  5180.4 1582.45
  5207.2 1583.31  5231.3 1589.13  5243.4 1593.81  5271.7 1597.72  5282.6 1599.09
  5351.9 1600.65  5373.0 1604.87  5406.2 1614.02  5415.2 1615.52  5431.9 1615.55
#Mann=7,-1,0
  4783.8     0.1       0  4938.5    0.07       0  4990.0     0.1       0
  4998.8    0.05       0  5002.8     0.1       0  5180.4   0.035       0
  5271.7     0.1       0
Bank Sta=4998.8,5002.8
Exp/Cntr=0.3,0.1

Type RM Length L Ch R = 1,1421,148,148,148
BEGIN DESCRIPTION:
Stream0567 3.0
END DESCRIPTION:
XS GIS Cut Line= 4
      1934939.29     13912033.20      1934939.06     13912043.05
      1934999.58     13912133.45      1935233.77     13912100.79
#Sta/Elev= 30
  4854.9 1578.29  4917.1 1576.45  4935.0 1577.44  4942.1 1578.44  4945.7 1577.83
  4952.8 1577.91  4959.9 1576.22  4963.5 1574.21  4972.1 1571.17  4972.4 1570.67
  4975.9 1570.67  4976.1 1571.17  4977.1 1571.55  4983.2 1571.92  5004.4 1572.34
  5010.5 1573.76  5016.5 1576.59  5022.6 1575.74  5028.6 1575.52  5040.7 1575.65
  5045.8 1576.20  5068.8 1578.97  5119.5 1581.64  5144.8 1582.29  5158.9 1582.70
  5176.1 1586.78  5186.7 1587.32  5192.2 1588.33  5201.3 1591.94  5210.0 1593.88
#Mann=5,-1,0
  4854.9    0.07       0  4972.1    0.05       0  4976.1    0.07       0
  5045.8     0.1       0  5144.8   0.035       0
Bank Sta=4972.1,4976.1
Exp/Cntr=0.3,0.1

Type RM Length L Ch R = 1,1273,314,314,314
BEGIN DESCRIPTION:
Stream0567 1.1
END DESCRIPTION:
XS GIS Cut Line= 4
      1934944.26     13911811.38      1934884.68     13911982.36
      1934930.66     13912151.01      1934982.59     13912524.04
#Sta/Elev= 30
  4569.5 1630.26  4596.4 1628.73  4626.5 1623.13  4689.4 1602.59  4698.8 1600.99
  4718.0 1599.48  4728.6 1597.01  4762.4 1585.11  4782.7 1582.16  4789.5 1579.26
  4818.7 1580.18  4845.8 1577.58  4887.8 1576.19  4975.0 1575.16  4977.2 1566.87
  4977.4 1566.37  4981.2 1566.87  4981.4 1575.17  4984.5 1575.19  5008.7 1571.57
  5014.8 1567.79  5020.8 1566.87  5052.1 1579.10  5057.4 1582.41  5086.7 1591.05
  5107.9 1600.02  5154.1 1602.92  5205.6 1612.82  5241.9 1614.16  5302.0 1619.93
#Mann=4,-1,0
  4569.5     0.1       0  4698.8    0.07       0  4977.2    0.05       0
  4981.2    0.07       0
Bank Sta=4977.2,4981.2
Exp/Cntr=0.3,0.1

Type RM Length L Ch R = 1,959,546,546,546
BEGIN DESCRIPTION:
Stream0567 2.0
END DESCRIPTION:
XS GIS Cut Line= 4
      1934927.30     13911776.46      1934675.00     13912175.00
      1934675.00     13912275.00      1934718.27     13912471.30
#Sta/Elev= 30
  4523.5 1628.16  4553.6 1623.05  4561.2 1619.16  4595.8 1607.93  4606.4 1603.25
  4656.5 1586.03  4681.0 1580.93  4712.6 1578.66  4876.3 1572.55  4998.6 1571.21
  5002.7 1570.97  5008.7 1567.82  5011.7 1569.62  5015.9 1566.32  5022.6 1566.12
  5026.7 1563.96  5030.9 1564.72  5033.7 1563.69  5034.0 1563.19  5037.7 1563.69
  5044.7 1566.63  5056.7 1575.11  5084.9 1577.19  5127.3 1578.40  5194.8 1581.07
  5209.9 1584.83  5227.8 1593.18  5237.6 1596.48  5286.2 1602.10  5296.2 1601.96
#Mann=5,-1,0
  4523.5     0.1       0  4553.6    0.07       0  5033.7    0.05       0
  5037.7    0.07       0  5127.3   0.035       0
Bank Sta=5033.7,5037.7
Exp/Cntr=0.3,0.1

Type RM Length L Ch R = 1,413,0,0,0
BEGIN DESCRIPTION:
Stream0567 1.0
END DESCRIPTION:
XS GIS Cut Line= 5
      1935069.32     13911592.24      1934548.45     13911738.82
      1934425.00     13911925.00      1934392.66     13912400.38
      1934519.83     13912629.83
#Sta/Elev= 30
  4452.1 1630.94  4574.8 1630.21  4592.5 1629.22  4617.5 1622.79  4637.2 1611.68
  4676.7 1589.83  4695.4 1582.83  4711.0 1579.89  4782.6 1575.86  4982.1 1570.97
  4998.3 1569.44  5003.7 1566.27  5016.1 1561.88  5016.3 1561.38  5020.1 1561.88
  5054.5 1568.71  5087.9 1569.52  5115.0 1567.47  5127.8 1569.07  5195.2 1573.13
  5321.6 1576.09  5543.9 1576.98  5610.0 1579.00  5625.2 1578.20  5681.8 1579.30
  5862.5 1581.94  5895.8 1587.04  5926.6 1594.09  5934.5 1596.20  5955.4 1597.75
#Mann=7,-1,0
  4452.1     0.1       0  4637.2    0.07       0  5016.1    0.05       0
  5020.1    0.07       0  5127.8   0.035       0  5681.8    0.07       0
  5926.6     0.1       0
Bank Sta=5016.1,5020.1
Exp/Cntr=0.3,0.1

Chan Stop Cuts=-1