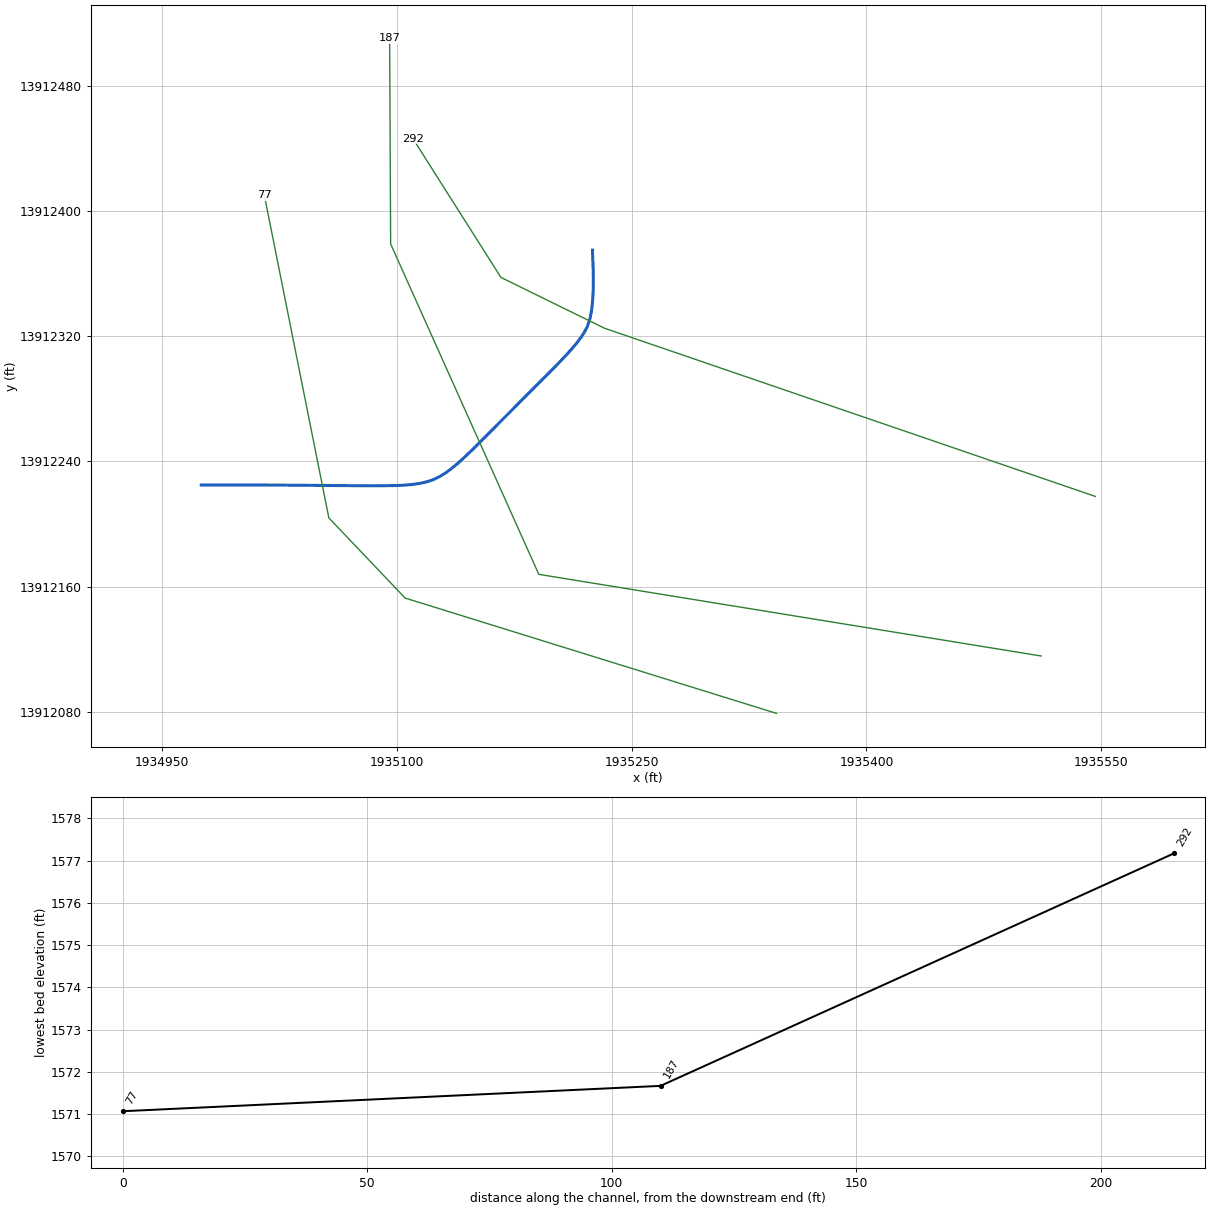
--- Stream0568.prj (project) ---

Proj Title=Stream0568 Base Level Engineering
Current Plan=p01
Default Exp/Contr=0.3,0.1
English Units
Geom File=g01
Flow File=f01
Plan File=p01
Y Axis Title=Elevation
X Axis Title(PF)=Main Channel Distance
X Axis Title(XS)=Station
BEGIN DESCRIPTION:
Stream0568
END DESCRIPTION:
DSS Export Rating Curves= 0
DSS Export Rating Curve Sorted= 0
DSS Export Volume Flow Curves= 0
DXF OffsetX= 0
DXF OffsetY= 0
DXF ScaleX= 1
DXF ScaleY= 10

--- Stream0568.p01 (plan) ---

Plan Title=Multiple Run
Short Identifier=Multiple
Geom File=g01
Flow File=f01
Subcritical Flow
K Sum by GR= 0
Std Step Tol= 0.01
Critical Tol= 0.01
Num of Std Step Trials= 20
Max Error Tol= 0.3
Flow Tol Ratio= 0.001
Split Flow NTrial= 30
Split Flow Tol= 0.02
Split Flow Ratio= 0.02
Log Output Level= 0
Friction Slope Method= 1
Unsteady Friction Slope Method= 2
Unsteady Bridges Friction Slope Method= 1
Parabolic Critical Depth
Global Vel Dist=  1 , 1 , 1
Global Log Level= 0
CheckData=True
Encroach Param= -1, 0, 0, 0
BEGIN DESCRIPTION:
Multiple Run
END DESCRIPTION:

--- Stream0568.f01 (steady flow) ---

Flow Title=Multiple
Program Version=4.10
Number of Profiles= 7
Profile Names=10-year,25-year,50-year,1pct_min,100-year,1pct_plu,500-year
River Rch & RM=Stream0568,Reach-1         ,292
     478     774    1042     683    1362    2717    2285
Boundary for River Rch & Prof#=Stream0568,Reach-1         , 1
Up Type= 0
Dn Type= 3
Dn Slope=0.007
Boundary for River Rch & Prof#=Stream0568,Reach-1         , 2
Up Type= 0
Dn Type= 3
Dn Slope=0.007
Boundary for River Rch & Prof#=Stream0568,Reach-1         , 3
Up Type= 0
Dn Type= 3
Dn Slope=0.007
Boundary for River Rch & Prof#=Stream0568,Reach-1         , 4
Up Type= 0
Dn Type= 3
Dn Slope=0.007
Boundary for River Rch & Prof#=Stream0568,Reach-1         , 5
Up Type= 0
Dn Type= 3
Dn Slope=0.007
Boundary for River Rch & Prof#=Stream0568,Reach-1         , 6
Up Type= 0
Dn Type= 3
Dn Slope=0.007
Boundary for River Rch & Prof#=Stream0568,Reach-1         , 7
Up Type= 0
Dn Type= 3
Dn Slope=0.007
DSS Import GetInterval= 0
DSS Import GetPeak= 0
DSS Import FillOption= 0

--- Stream0568.g01 (geometry) ---

Geom Title=Existing Conditions
Program Version=4.10

River Reach=Stream0568      ,Reach-1
Reach XY= 30
        1935225.       13912375.      1935224.96     13912374.07
      1935225.43     13912362.02       1935225.5     13912356.04
      1935225.41     13912349.63      1935225.08     13912343.11
      1935224.42     13912336.83      1935223.33     13912331.13
      1935221.74     13912326.34       1935219.7     13912322.46
      1935217.25     13912318.76       1935214.5     13912315.18
      1935211.54     13912311.69      1935208.44     13912308.25
      1935201.99     13912301.48      1935148.58     13912247.82
       1935141.8      13912241.4      1935138.35     13912238.34
      1935134.83     13912235.44      1935131.22     13912232.77
      1935127.48     13912230.41      1935123.56     13912228.48
      1935119.18       13912227.       1935114.6     13912225.98
      1935109.88     13912225.31      1935105.05     13912224.88
      1935100.16     13912224.62      1935085.25     13912224.41
      1935030.06     13912224.86        1934975.       13912225.

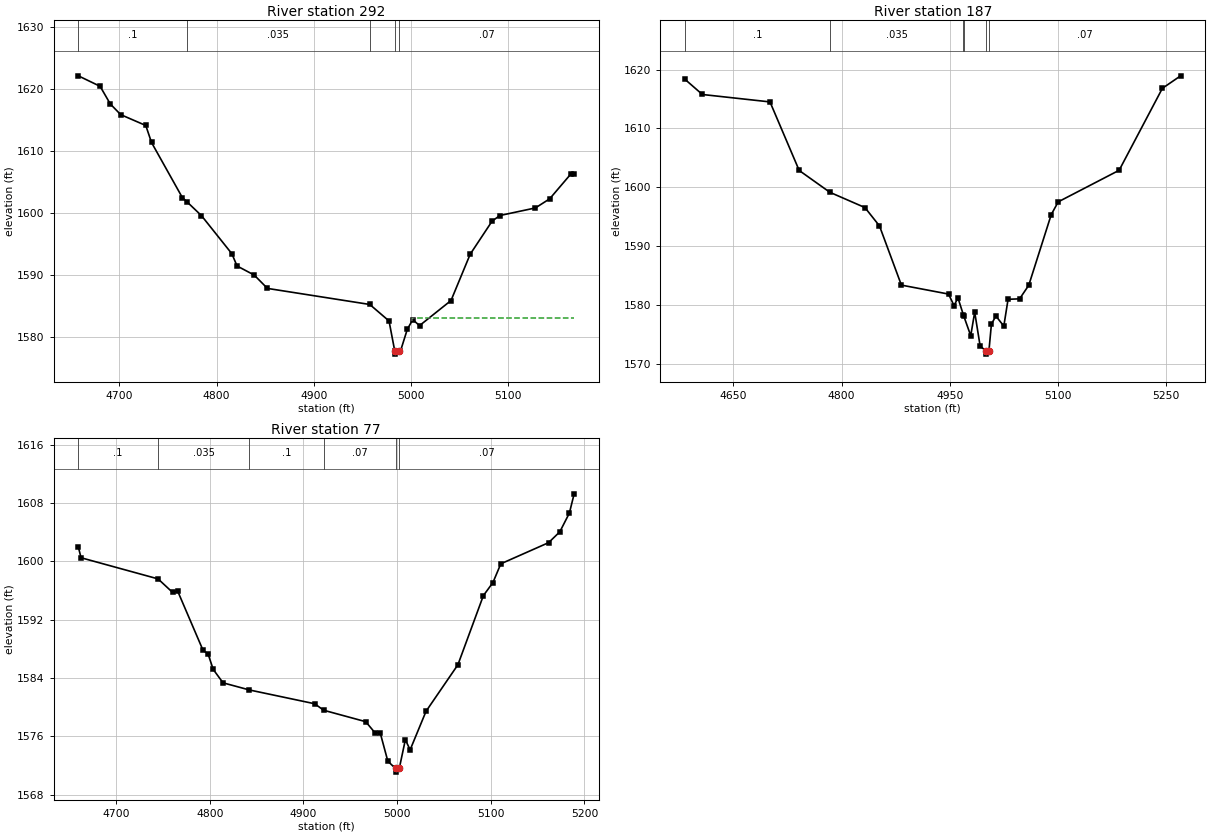
Type RM Length L Ch R = 1 ,292     ,105,105,105
BEGIN DESCRIPTION:
Stream0568 2.0
END DESCRIPTION:
XS GIS Cut Line= 4
      1935546.21     13912217.67      1935232.64     13912325.11
      1935166.44     13912357.59      1935110.23     13912446.27
#Sta/Elev= 30
  4657.7 1622.06  4680.1 1620.37  4690.6 1617.52  4701.3  1615.8  4727.1 1614.05
    4733 1611.31  4764.7 1602.43  4769.4 1601.75  4784.4 1599.51  4815.7 1593.36
    4821 1591.39  4838.7 1589.92  4852.3 1587.77  4957.6 1585.18  4977.4 1582.52
  4983.3 1577.67  4983.5 1577.17  4987.3 1577.67  4989.2 1577.67  4996.2 1581.17
  5001.8 1582.73  5008.8 1581.77  5041.2 1585.82  5060.9 1593.28  5083.5 1598.63
  5091.5 1599.53    5128 1600.75  5142.7 1602.22  5164.2 1606.17  5167.9 1606.17
#Mann= 5 ,-1 , 0
  4657.7      .1       0  4769.4    .035       0  4957.6     .07       0
  4983.3     .05       0  4987.3     .07       0
#XS Ineff= 2 , 0
                            5001         1582.93
Permanent Ineff=
       F       F
Bank Sta=4983.3,4987.3
XS Rating Curve= 0 ,0
Exp/Cntr=0.3,0.1

Type RM Length L Ch R = 1 ,187     ,110,110,110
BEGIN DESCRIPTION:
Stream0568 1.0
END DESCRIPTION:
XS GIS Cut Line= 4
      1935511.64      13912115.7      1935190.65     13912167.88
        1935096.     13912378.95      1935095.36     13912510.32
#Sta/Elev= 30
  4582.5 1618.36  4606.9 1615.76  4700.7  1614.5  4741.2 1602.86  4783.8 1599.15
  4832.4 1596.56  4852.6 1593.44    4883 1583.39  4948.4 1581.87    4956 1579.92
  4961.5 1581.21  4968.9 1578.38  4969.5 1578.15  4979.2  1574.8  4984.7  1578.8
  4992.2 1573.08  5000.4 1572.17  5000.6 1571.67  5004.4 1572.17  5007.9 1576.77
  5014.1 1578.14  5025.1 1576.43    5031 1580.98    5047 1581.06  5059.7 1583.36
  5090.9 1595.37  5100.6 1597.53  5185.1 1602.89  5245.1 1616.81  5270.4 1618.93
#Mann= 6 ,-1 , 0
  4582.5      .1       0  4783.8    .035       0  4968.9      .1       0
  4969.5     .07       0  5000.4     .05       0  5004.4     .07       0
Bank Sta=5000.4,5004.4
XS Rating Curve= 0 ,0
Exp/Cntr=0.3,0.1

Type RM Length L Ch R = 1 ,77      ,0,0,0
BEGIN DESCRIPTION:
Stream0568 0.0
END DESCRIPTION:
XS GIS Cut Line= 4
      1935342.53     13912079.05      1935105.23     13912152.74
      1935056.52     13912203.95      1935015.31     13912410.01
#Sta/Elev= 30
  4659.7 1601.96  4662.6 1600.48  4744.8 1597.58  4760.3 1595.73  4765.6 1595.95
  4792.9 1587.76  4798.1 1587.32  4803.7 1585.16  4814.2 1583.32  4842.4 1582.34
    4912 1580.45  4921.6 1579.56  4966.5 1577.99  4976.3 1576.48  4981.9 1576.48
  4990.1 1572.57  4998.3 1571.57  4998.6 1571.07  5002.3 1571.57  5008.8 1575.52
  5013.9 1574.13  5030.9 1579.42  5064.9  1585.8  5092.1 1595.29  5102.3 1597.08
  5110.7 1599.65  5161.7 1602.55  5173.7 1604.04  5183.9 1606.61    5189 1609.25
#Mann= 6 ,-1 , 0
  4659.7      .1       0  4744.8    .035       0  4842.4      .1       0
  4921.6     .07       0  4998.3     .05       0  5002.3     .07       0
Bank Sta=4998.3,5002.3
XS Rating Curve= 0 ,0
Exp/Cntr=0.3,0.1

Chan Stop Cuts=-1
Use User Specified Reach Order=0
Composite Channel Slope=5