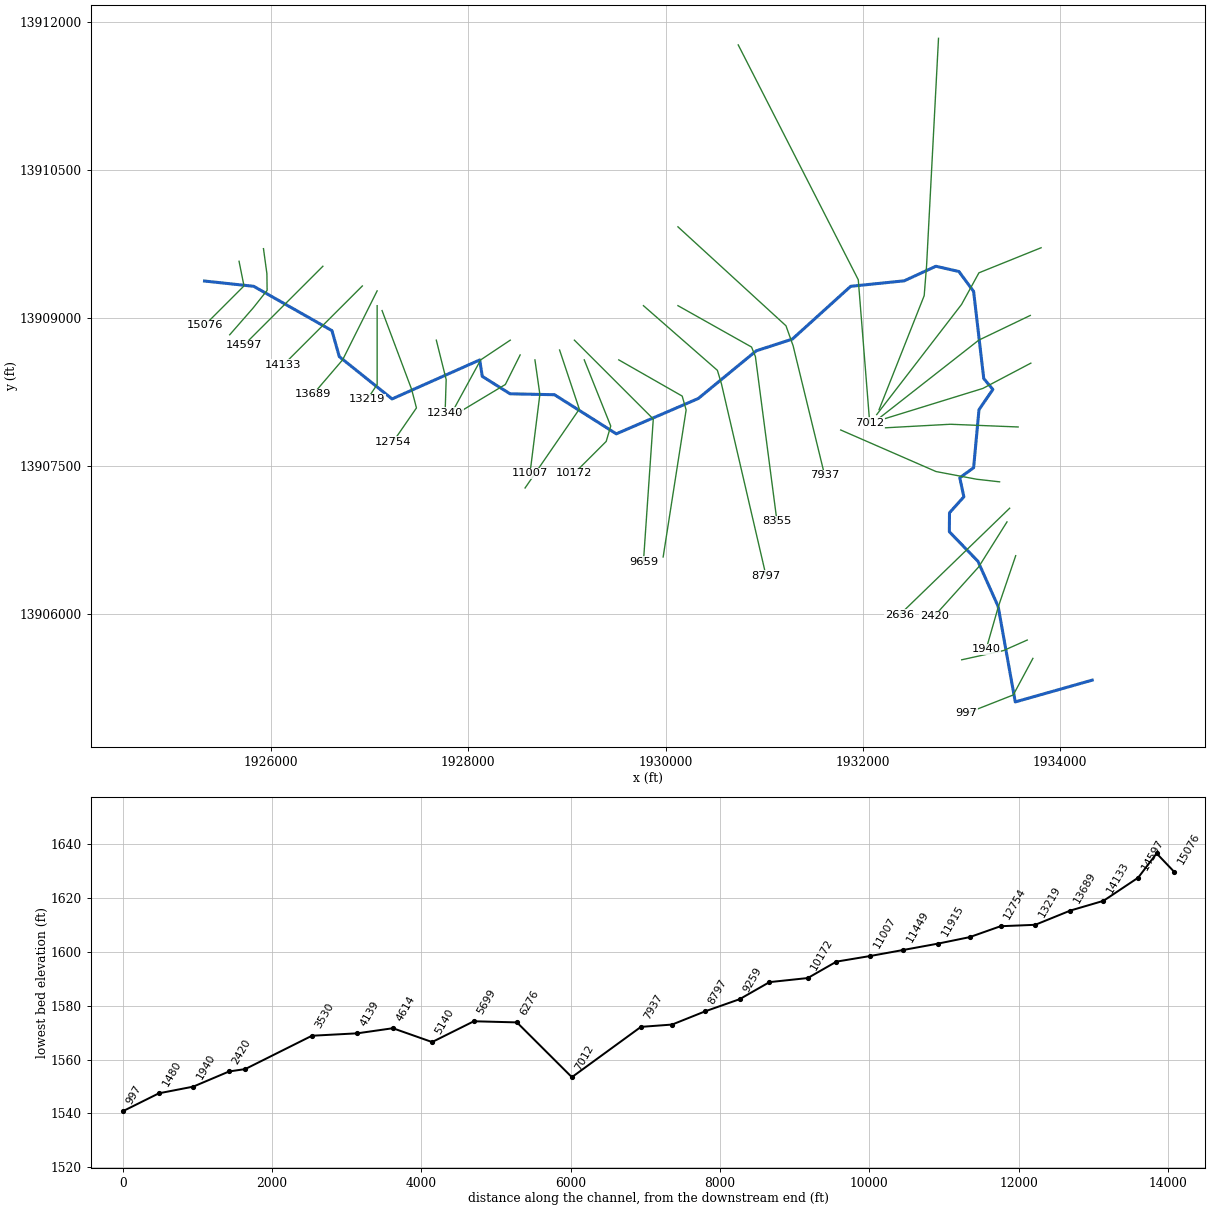
--- Stream0569.prj (project) ---

Proj Title=Stream0569 Base Level Engineering
Current Plan=p01
Default Exp/Contr=0.3,0.1
English Units
Geom File=g01
Flow File=f01
Plan File=p01
BEGIN DESCRIPTION:
Stream0569
END DESCRIPTION:

--- Stream0569.p01 (plan) ---

Plan Title=Multiple Run
Short Identifier=Multiple
Geom File=g01
Flow File=f01
Subcritical Flow
K Sum by GR= 0
Std Step Tol= 0.01
Critical Tol= 0.01
Num of Std Step Trials= 20
Max Error Tol= 0.3
Flow Tol Ratio= 0.001
Split Flow NTrial= 30
Split Flow Tol= 0.02
Split Flow Ratio= 0.02
Log Output Level= 0
Friction Slope Method= 1
Unsteady Friction Slope Method= 2
Unsteady Bridges Friction Slope Method= 1
Parabolic Critical Depth
Global Vel Dist=  1 , 1 , 1
Global Log Level= 0
CheckData=True
Encroach Param= -1, 0, 0, 0
BEGIN DESCRIPTION:
Multiple Run
END DESCRIPTION:

--- Stream0569.f01 (steady flow) ---

Flow Title=Multiple
Number of Profiles=7
Profile Names=10-year,25-year,50-year,1pct_min,100-year,1pct_plu,500-year
River Rch & RM= Stream0569,Reach-1,15076
    2266    4011    5731    3950    7881   15725   14736
River Rch & RM= Stream0569,Reach-1,5699
    2775    4957    7127    4938    9853   19659   18624
River Rch & RM= Stream0569,Reach-1,2636
    3260    5862    8464    5885   11742   23429   22357
River Rch & RM= Stream0569,Reach-1,524
    3436    6192    8954    6234   12439   24819   23747
Boundary for River Rch & Prof#=Stream0569,Reach-1,1
Up Type=0
Dn Type=3
Dn Slope=0.005
Boundary for River Rch & Prof#=Stream0569,Reach-1,2
Up Type=0
Dn Type=3
Dn Slope=0.005
Boundary for River Rch & Prof#=Stream0569,Reach-1,3
Up Type=0
Dn Type=3
Dn Slope=0.005
Boundary for River Rch & Prof#=Stream0569,Reach-1,4
Up Type=0
Dn Type=3
Dn Slope=0.005
Boundary for River Rch & Prof#=Stream0569,Reach-1,5
Up Type=0
Dn Type=3
Dn Slope=0.005
Boundary for River Rch & Prof#=Stream0569,Reach-1,6
Up Type=0
Dn Type=3
Dn Slope=0.005
Boundary for River Rch & Prof#=Stream0569,Reach-1,7
Up Type=0
Dn Type=3
Dn Slope=0.005

--- Stream0569.g01 (geometry) ---

Geom Title=Existing Conditions

River Reach=Stream0569,Reach-1
Reach XY= 30
      1925325.00     13909375.00      1925823.54     13909321.46
      1926616.85     13908871.62      1926691.27     13908607.79
      1927226.58     13908178.67      1928114.85     13908574.07
      1928141.04     13908407.86      1928422.46     13908230.70
      1928873.45     13908221.25      1929500.03     13907824.50
      1930331.17     13908182.86      1930918.95     13908666.84
      1931284.79     13908785.52      1931876.46     13909321.46
      1932419.14     13909377.07      1932740.39     13909524.91
      1932973.75     13909471.55      1933122.94     13909269.14
      1933225.62     13908385.62      1933317.90     13908275.00
      1933177.24     13908069.07      1933123.02     13907480.67
      1932982.69     13907378.67      1933023.96     13907185.44
      1932878.50     13907023.55      1932876.68     13906831.14
      1933166.86     13906531.06      1933371.45     13906073.53
      1933545.14     13905104.08      1934325.00     13905325.00

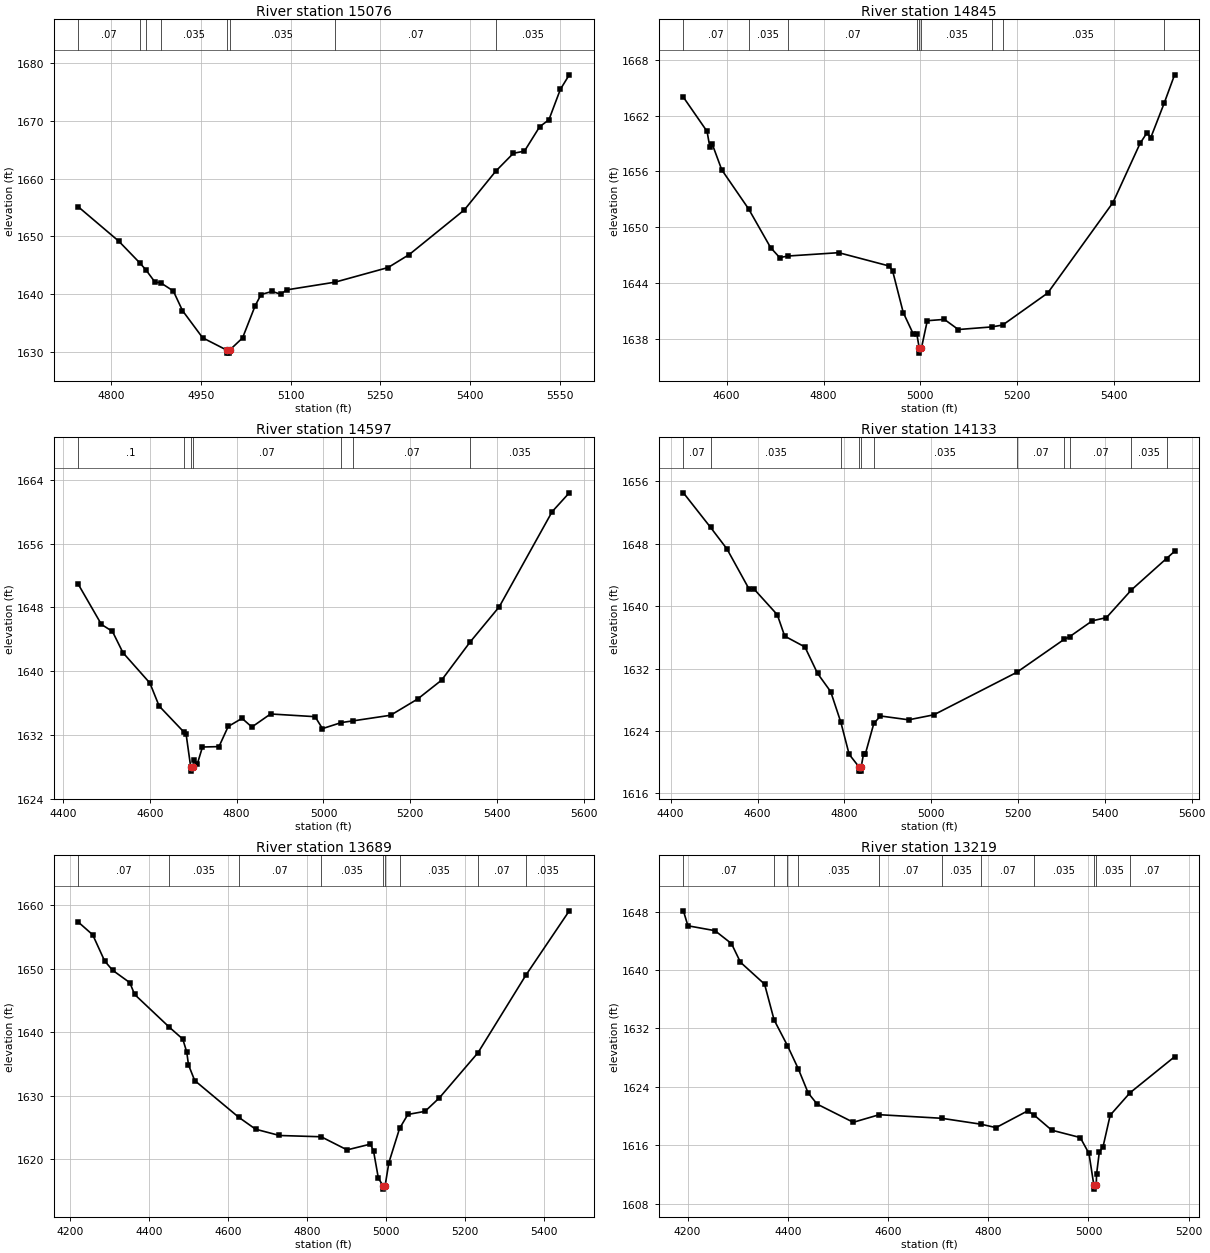
Type RM Length L Ch R = 1,15076,231,231,231
BEGIN DESCRIPTION:
Stream0569 24.0
END DESCRIPTION:
XS GIS Cut Line= 3
      1925674.99     13909575.04      1925725.00     13909325.00
      1925324.98     13908924.98
#Sta/Elev= 30
  4745.1 1655.14  4813.2 1649.14  4848.9 1645.30  4858.6 1644.14  4873.7 1642.03
  4882.8 1641.95  4904.2 1640.51  4919.5 1637.11  4953.2 1632.39  4993.9 1630.23
  4994.2 1629.73  4997.9 1629.73  4998.1 1630.23  5019.9 1632.37  5041.1 1637.99
  5050.9 1639.90  5069.4 1640.44  5083.6 1639.94  5093.4 1640.70  5174.4 1642.04
  5263.1 1644.58  5298.5 1646.84  5390.4 1654.57  5443.0 1661.30  5472.4 1664.40
  5490.9 1664.77  5516.3 1669.00  5531.8 1670.22  5550.9 1675.49  5565.8 1678.01
#Mann=8,-1,0
  4745.1    0.07       0  4848.9   0.035       0  4858.6    0.07       0
  4882.8   0.035       0  4993.9   0.035       0  4998.1   0.035       0
  5174.4    0.07       0  5443.0   0.035       0
Bank Sta=4993.9,4998.1
Exp/Cntr=0.3,0.1

Type RM Length L Ch R = 1,14845,248,248,248
BEGIN DESCRIPTION:
Stream0569 D
END DESCRIPTION:
XS GIS Cut Line= 5
      1925922.57     13909703.47      1925957.28     13909449.61
      1925959.46     13909280.34      1925818.40     13909102.39
      1925580.31     13908829.68
#Sta/Elev= 30
  4510.6 1663.99  4559.5 1660.31  4565.0 1658.68  4570.1 1658.96  4589.8 1656.18
  4645.3 1651.97  4690.7 1647.81  4709.5 1646.73  4726.5 1646.90  4831.4 1647.26
  4936.1 1645.82  4942.9 1645.27  4964.7 1640.82  4985.6 1638.49  4992.8 1638.50
  4997.9 1636.95  4998.1 1636.45  5002.1 1636.95  5014.4 1639.94  5049.7 1640.08
  5078.5 1638.99  5147.3 1639.27  5170.0 1639.47  5263.2 1642.92  5398.0 1652.66
  5454.0 1659.03  5468.3 1660.17  5475.9 1659.62  5503.8 1663.36  5525.2 1666.40
#Mann=9,-1,0
  4510.6    0.07       0  4645.3   0.035       0  4726.5    0.07       0
  4992.8   0.035       0  4997.9   0.035       0  5002.1   0.035       0
  5147.3    0.07       0  5170.0   0.035       0  5503.8    0.07       0
Bank Sta=4997.9,5002.1
Exp/Cntr=0.3,0.1

Type RM Length L Ch R = 1,14597,464,464,464
BEGIN DESCRIPTION:
Stream0569 23.0
END DESCRIPTION:
XS GIS Cut Line= 3
      1926524.99     13909524.99      1926125.00     13909125.00
      1925725.04     13908725.04
#Sta/Elev= 30
  4434.8 1650.95  4488.5 1645.87  4513.9 1644.99  4538.1 1642.32  4600.2 1638.50
  4621.4 1635.62  4678.6 1632.34  4683.6 1632.07  4694.2 1627.94  4694.5 1627.44
  4698.5 1627.94  4702.1 1628.83  4709.1 1628.29  4721.2 1630.47  4759.3 1630.52
  4780.5 1633.05  4812.4 1634.07  4835.0 1632.98  4878.1 1634.62  4980.6 1634.28
  4997.6 1632.78  5041.0 1633.54  5068.8 1633.76  5154.6 1634.46  5216.9 1636.50
  5272.0 1638.87  5337.4 1643.64  5404.9 1648.09  5526.6 1660.03  5566.1 1662.40
#Mann=7,-1,0
  4434.8     0.1       0  4678.6    0.07       0  4694.2    0.05       0
  4698.5    0.07       0  5041.0   0.035       0  5068.8    0.07       0
  5337.4   0.035       0
Bank Sta=4694.2,4698.5
Exp/Cntr=0.3,0.1

Type RM Length L Ch R = 1,14133,444,444,444
BEGIN DESCRIPTION:
Stream0569 22.0
END DESCRIPTION:
XS GIS Cut Line= 3
      1926924.99     13909324.99      1926525.00     13908925.00
      1926124.97     13908524.97
#Sta/Elev= 30
  4429.3 1654.54  4492.0 1650.10  4529.7 1647.34  4580.6 1642.20  4591.9 1642.21
  4645.6 1638.91  4662.6 1636.17  4709.2 1634.78  4738.3 1631.39  4768.6 1629.05
  4792.1 1625.10  4811.1 1621.01  4834.4 1619.36  4834.7 1618.86  4838.4 1618.86
  4838.7 1619.36  4844.3 1621.10  4848.6 1621.10  4867.9 1624.97  4883.2 1625.93
  4948.3 1625.44  5006.2 1626.08  5197.0 1631.52  5307.0 1635.78  5319.1 1636.10
  5371.1 1638.13  5403.7 1638.54  5461.2 1642.09  5542.1 1646.12  5560.7 1647.04
#Mann=11,-1,0
  4429.3    0.07       0  4492.0   0.035       0  4792.1    0.07       0
  4834.4   0.035       0  4838.7    0.07       0  4867.9   0.035       0
  5197.0    0.07       0  5307.0   0.035       0  5319.1    0.07       0
  5461.2   0.035       0  5542.1    0.07       0
Bank Sta=4834.4,4838.7
Exp/Cntr=0.3,0.1

Type RM Length L Ch R = 1,13689,470,470,470
BEGIN DESCRIPTION:
Stream0569 21.0
END DESCRIPTION:
XS GIS Cut Line= 3
      1927075.02     13909275.04      1926725.00     13908575.00
      1926425.03     13908225.04
#Sta/Elev= 30
  4221.1 1657.40  4258.1 1655.37  4288.3 1651.24  4308.4 1649.78  4352.0 1647.82
  4364.2 1645.96  4452.3 1640.78  4486.1 1638.92  4496.2 1636.87  4500.6 1634.85
  4516.3 1632.38  4627.5 1626.60  4670.6 1624.70  4731.0 1623.71  4836.5 1623.51
  4902.1 1621.44  4961.3 1622.35  4969.1 1621.26  4981.4 1616.96  4993.6 1615.75
  4994.0 1615.25  4998.3 1615.75  5008.0 1619.44  5035.0 1624.82  5056.0 1627.03
  5099.5 1627.52  5135.7 1629.64  5233.6 1636.77  5354.5 1648.97  5464.7 1659.15
#Mann=9,-1,0
  4221.1    0.07       0  4452.3   0.035       0  4627.5    0.07       0
  4836.5   0.035       0  4993.6    0.05       0  4998.3   0.035       0
  5035.0   0.035       0  5233.6    0.07       0  5354.5   0.035       0
Bank Sta=4993.6,4998.3
Exp/Cntr=0.3,0.1

Type RM Length L Ch R = 1,13219,465,465,465
BEGIN DESCRIPTION:
Stream0569 20.0
END DESCRIPTION:
XS GIS Cut Line= 3
      1927075.00     13909124.96      1927075.00     13908325.00
      1926975.02     13908175.03
#Sta/Elev= 30
  4191.6 1648.11  4200.6 1646.06  4254.6 1645.39  4287.5 1643.62  4305.5 1641.06
  4353.6 1638.06  4372.6 1633.16  4399.3 1629.63  4421.0 1626.44  4440.5 1623.16
  4458.5 1621.62  4530.6 1619.13  4582.5 1620.17  4706.8 1619.68  4785.2 1618.87
  4815.5 1618.40  4878.5 1620.69  4891.1 1620.14  4926.6 1618.05  4983.5 1617.04
  5000.9 1614.87  5010.8 1610.47  5011.1 1609.97  5015.5 1610.47  5016.1 1612.01
  5021.6 1615.04  5029.0 1615.77  5043.3 1620.10  5082.8 1623.17  5171.8 1628.11
#Mann=11,-1,0
  4191.6    0.07       0  4372.6   0.035       0  4399.3    0.07       0
  4421.0   0.035       0  4582.5    0.07       0  4706.8   0.035       0
  4785.2    0.07       0  4891.1   0.035       0  5010.8   0.035       0
  5015.5   0.035       0  5082.8    0.07       0
Bank Sta=5010.8,5015.5
Exp/Cntr=0.3,0.1

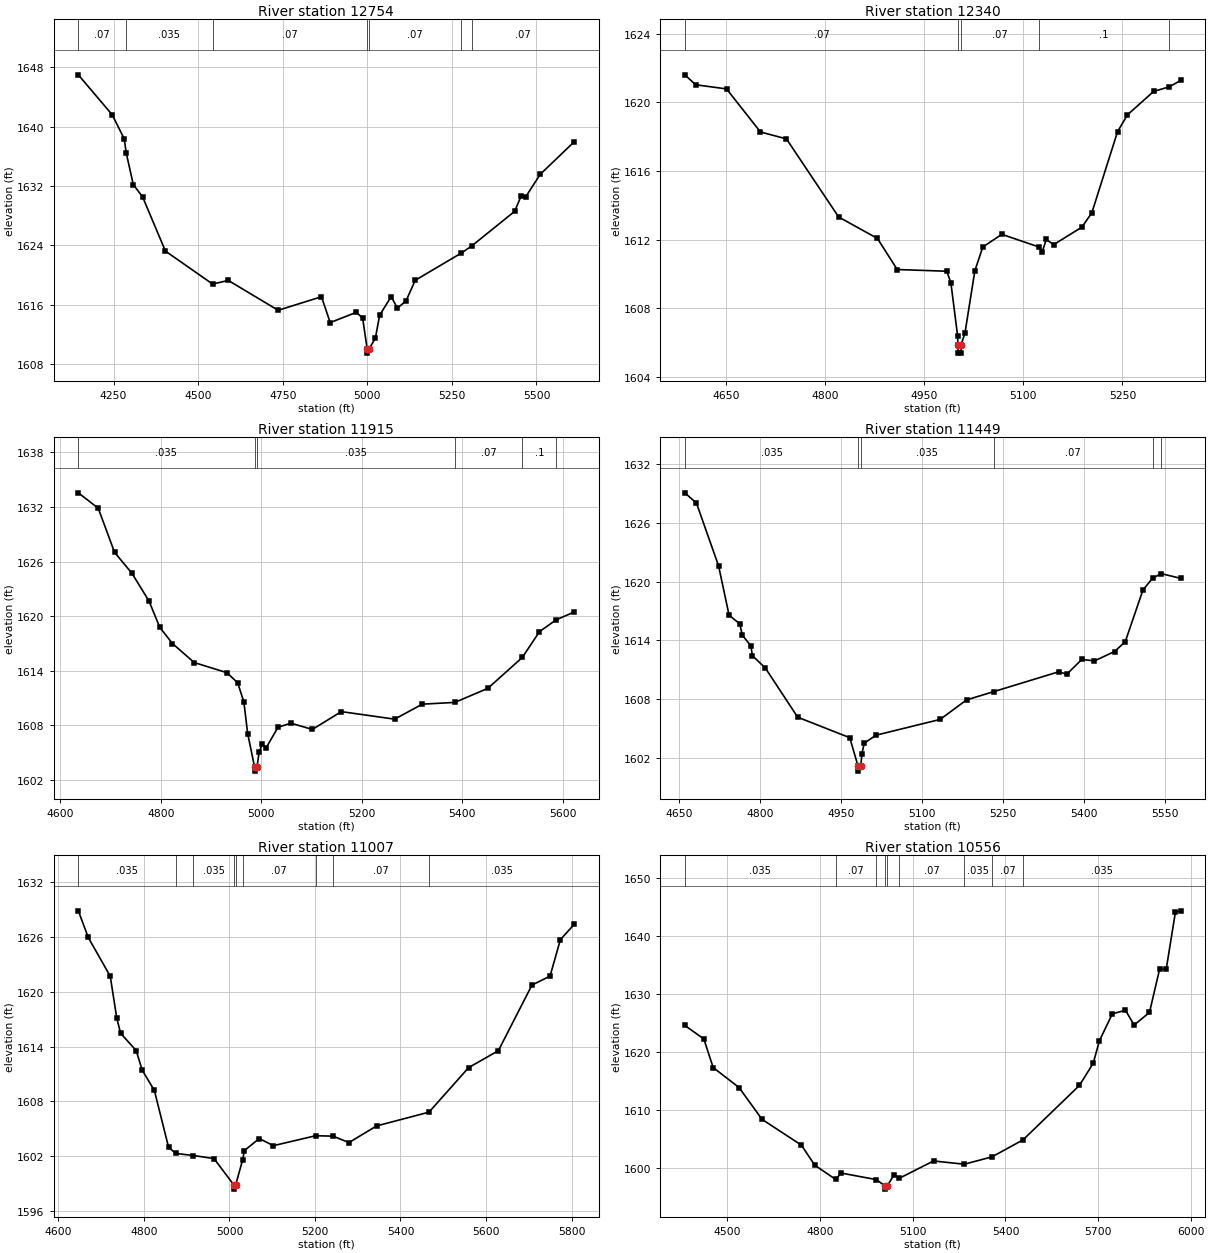
Type RM Length L Ch R = 1,12754,414,414,414
BEGIN DESCRIPTION:
Stream0569 19.0
END DESCRIPTION:
XS GIS Cut Line= 4
      1927124.99     13909075.04      1927425.00     13908275.00
      1927473.55     13908087.19      1927236.81     13907743.57
#Sta/Elev= 30
  4145.8 1646.99  4246.3 1641.58  4281.5 1638.34  4287.3 1636.48  4308.2 1632.19
  4336.0 1630.50  4403.2 1623.21  4542.7 1618.76  4589.1 1619.25  4736.5 1615.22
  4864.6 1617.05  4890.3 1613.56  4967.2 1614.94  4986.1 1614.20  4999.9 1609.94
  5000.3 1609.44  5004.7 1609.94  5024.0 1611.48  5036.4 1614.54  5070.5 1617.06
  5089.1 1615.52  5114.4 1616.48  5141.8 1619.27  5276.8 1622.91  5308.4 1623.89
  5435.6 1628.57  5455.0 1630.67  5467.7 1630.48  5511.1 1633.56  5611.5 1637.95
#Mann=7,-1,0
  4145.8    0.07       0  4287.3   0.035       0  4542.7    0.07       0
  4999.9    0.05       0  5004.7    0.07       0  5276.8     0.1       0
  5308.4    0.07       0
Bank Sta=4999.9,5004.7
Exp/Cntr=0.3,0.1

Type RM Length L Ch R = 1,12340,425,425,425
BEGIN DESCRIPTION:
Stream0569 18.0
END DESCRIPTION:
XS GIS Cut Line= 3
      1927675.01     13908774.98      1927775.00     13908375.00
      1927764.21     13908036.56
#Sta/Elev= 30
  4587.3 1621.60  4603.8 1621.02  4650.5 1620.78  4701.9 1618.27  4741.2 1617.87
  4820.3 1613.32  4879.0 1612.07  4909.0 1610.26  4984.1 1610.16  4990.3 1609.48
  5000.5 1606.38  5000.9 1605.89  5001.3 1605.39  5005.6 1605.39  5005.9 1605.89
  5011.6 1606.56  5026.6 1610.19  5038.6 1611.57  5067.4 1612.31  5123.8 1611.57
  5128.7 1611.30  5134.7 1612.01  5146.0 1611.71  5188.7 1612.73  5203.7 1613.56
  5242.7 1618.29  5257.7 1619.27  5297.2 1620.63  5320.8 1620.90  5338.2 1621.27
#Mann=5,-1,0
  4587.3    0.07       0  5000.9    0.05       0  5005.9    0.07       0
  5123.8     0.1       0  5320.8    0.07       0
Bank Sta=5000.9,5005.9
Exp/Cntr=0.3,0.1

Type RM Length L Ch R = 1,11915,466,466,466
BEGIN DESCRIPTION:
Stream0569 17.0
END DESCRIPTION:
XS GIS Cut Line= 3
      1928424.99     13908774.99      1928125.00     13908575.00
      1927825.02     13908025.04
#Sta/Elev= 30
  4635.8 1633.56  4675.4 1631.87  4707.9 1627.02  4742.5 1624.72  4776.4 1621.68
  4798.0 1618.77  4823.2 1617.00  4866.5 1614.91  4931.4 1613.80  4953.0 1612.69
  4965.3 1610.58  4972.9 1607.10  4986.5 1603.48  4986.9 1602.98  4991.6 1603.48
  4995.6 1605.05  5002.1 1605.98  5008.9 1605.47  5033.2 1607.80  5058.9 1608.25
  5101.7 1607.56  5159.3 1609.52  5265.4 1608.69  5320.6 1610.34  5385.2 1610.53
  5451.1 1612.08  5519.7 1615.48  5553.8 1618.31  5587.1 1619.61  5622.8 1620.46
#Mann=6,-1,0
  4635.8   0.035       0  4986.5   0.035       0  4991.6   0.035       0
  5385.2    0.07       0  5519.7     0.1       0  5587.1    0.07       0
Bank Sta=4986.5,4991.6
Exp/Cntr=0.3,0.1

Type RM Length L Ch R = 1,11449,442,442,442
BEGIN DESCRIPTION:
Stream0569 16.0
END DESCRIPTION:
XS GIS Cut Line= 3
      1928525.02     13908625.04      1928375.00     13908325.00
      1927875.04     13908025.02
#Sta/Elev= 30
  4660.3 1629.10  4681.9 1628.05  4722.9 1621.62  4742.3 1616.58  4762.1 1615.69
  4766.9 1614.53  4782.6 1613.45  4785.6 1612.43  4809.4 1611.18  4869.4 1606.14
  4965.9 1604.04  4981.3 1601.12  4981.7 1600.62  4986.4 1601.12  4988.3 1602.39
  4992.8 1603.49  5014.7 1604.30  5133.3 1605.91  5182.3 1607.91  5232.9 1608.76
  5353.7 1610.80  5367.7 1610.52  5395.7 1612.05  5419.2 1611.90  5456.4 1612.86
  5476.2 1613.86  5508.9 1619.14  5526.8 1620.37  5542.9 1620.83  5578.8 1620.35
#Mann=6,-1,0
  4660.3   0.035       0  4981.3   0.035       0  4986.4   0.035       0
  5232.9    0.07       0  5526.8     0.1       0  5542.9    0.07       0
Bank Sta=4981.3,4986.4
Exp/Cntr=0.3,0.1

Type RM Length L Ch R = 1,11007,451,451,451
BEGIN DESCRIPTION:
Stream0569 15.0
END DESCRIPTION:
XS GIS Cut Line= 3
      1928675.00     13908574.97      1928725.00     13908225.00
      1928625.01     13907425.05
#Sta/Elev= 30
  4646.5 1628.87  4669.7 1625.95  4721.2 1621.70  4736.4 1617.11  4745.4 1615.46
  4781.8 1613.57  4795.9 1611.42  4824.3 1609.20  4857.6 1602.97  4874.4 1602.30
  4915.6 1602.07  4963.7 1601.74  5009.6 1598.89  5010.0 1598.39  5014.7 1598.89
  5030.8 1601.60  5034.9 1602.61  5069.6 1603.93  5102.8 1603.15  5201.8 1604.24
  5242.1 1604.19  5279.5 1603.49  5344.0 1605.31  5466.7 1606.82  5559.4 1611.70
  5628.9 1613.55  5707.5 1620.74  5749.8 1621.72  5774.0 1625.72  5806.2 1627.38
#Mann=9,-1,0
  4646.5   0.035       0  4874.4    0.07       0  4915.6   0.035       0
  5009.6   0.035       0  5014.7   0.035       0  5030.8    0.07       0
  5201.8   0.035       0  5242.1    0.07       0  5466.7   0.035       0
Bank Sta=5009.6,5014.7
Exp/Cntr=0.3,0.1

Type RM Length L Ch R = 1,10556,384,384,384
BEGIN DESCRIPTION:
Stream0569 14.0
END DESCRIPTION:
XS GIS Cut Line= 3
      1928925.01     13908674.96      1929125.00     13908075.00
      1928575.02     13907275.03
#Sta/Elev= 30
  4363.1 1624.56  4424.7 1622.22  4454.8 1617.29  4538.5 1613.84  4612.9 1608.35
  4740.1 1603.90  4783.6 1600.42  4850.6 1598.00  4869.0 1599.08  4982.5 1597.95
  5011.7 1596.81  5012.0 1596.31  5016.8 1596.81  5040.1 1598.79  5056.3 1598.17
  5167.4 1601.17  5266.7 1600.61  5356.0 1601.87  5456.2 1604.79  5639.1 1614.20
  5683.6 1618.03  5703.8 1621.91  5745.5 1626.56  5788.0 1627.17  5816.0 1624.62
  5865.6 1626.80  5898.4 1634.28  5919.6 1634.21  5949.4 1644.09  5966.3 1644.33
#Mann=9,-1,0
  4363.1   0.035       0  4850.6    0.07       0  4982.5   0.035       0
  5011.7   0.035       0  5016.8   0.035       0  5056.3    0.07       0
  5266.7   0.035       0  5356.0    0.07       0  5456.2   0.035       0
Bank Sta=5011.7,5016.8
Exp/Cntr=0.3,0.1

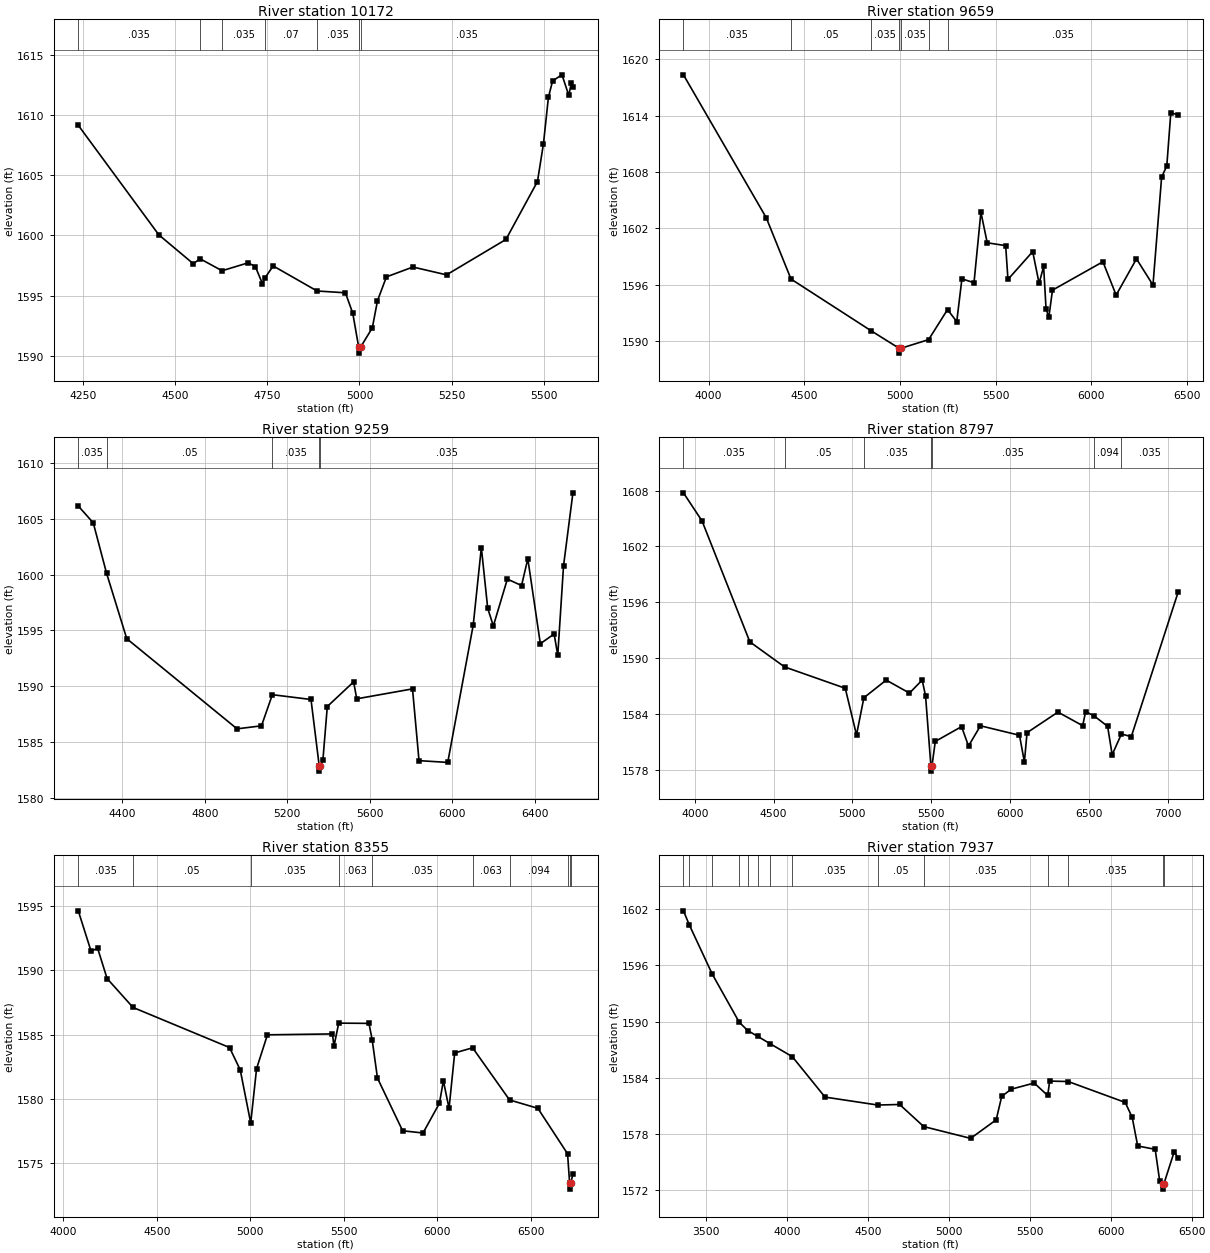
Type RM Length L Ch R = 1,10172,513,513,513
BEGIN DESCRIPTION:
Stream0569 13.0
END DESCRIPTION:
XS GIS Cut Line= 4
      1929175.01     13908574.98      1929443.48     13907903.80
      1929397.59     13907747.59      1929075.00     13907425.00
#Sta/Elev= 30
  4237.2 1609.14  4455.8 1600.04  4549.4 1597.64  4567.4 1598.06  4627.3 1597.06
  4698.1 1597.72  4717.5 1597.41  4736.9 1595.98  4743.7 1596.47  4766.0 1597.46
  4885.0 1595.38  4961.9 1595.23  4981.8 1593.54  4997.9 1590.72  4998.3 1590.22
  5003.1 1590.72  5034.9 1592.32  5048.9 1594.57  5073.1 1596.55  5145.0 1597.37
  5236.2 1596.72  5397.4 1599.66  5482.9 1604.47  5499.2 1607.62  5512.6 1611.46
  5524.0 1612.83  5549.4 1613.33  5567.8 1611.63  5574.9 1612.67  5579.1 1612.31
#Mann=7,-1,0
  4237.2   0.035       0  4567.4    0.07       0  4627.3   0.035       0
  4743.7    0.07       0  4885.0   0.035       0  4997.9   0.035       0
  5003.1   0.035       0
Bank Sta=4997.9,5003.1
Exp/Cntr=0.3,0.1

Type RM Length L Ch R = 1,9659,400,400,400
BEGIN DESCRIPTION:
Stream0569 12.0
END DESCRIPTION:
XS GIS Cut Line= 3
      1929075.00     13908775.00      1929875.00     13907975.00
      1929775.00     13906525.02
#Sta/Elev= 30
  3868.7 1618.35  4301.4 1603.13  4430.6 1596.60  4848.6 1591.10  4997.1 1589.21
  4997.6 1588.71  5003.0 1589.21  5149.9 1590.15  5248.7 1593.35  5296.8 1592.06
  5323.8 1596.62  5387.0 1596.21  5423.0 1603.72  5456.1 1600.46  5552.4 1600.16
  5564.4 1596.56  5693.7 1599.52  5727.2 1596.14  5750.8 1597.94  5763.4 1593.45
  5777.9 1592.52  5797.1 1595.42  6060.6 1598.44  6129.7 1594.89  6236.0 1598.75
  6322.2 1595.96  6367.3 1607.44  6394.4 1608.65  6415.4 1614.31  6453.5 1614.08
#Mann=7,-1,0
  3868.7   0.035       0  4430.6    0.05       0  4848.6   0.035       0
  4997.1   0.035       0  5003.0   0.035       0  5149.9    0.05       0
  5248.7   0.035       0
Bank Sta=4997.1,5003
Exp/Cntr=0.3,0.1

Type RM Length L Ch R = 1,9259,462,462,462
BEGIN DESCRIPTION:
Stream0569 11.0
END DESCRIPTION:
XS GIS Cut Line= 4
      1929524.98     13908575.01      1930168.20     13908207.46
      1930208.09     13908066.79      1929975.01     13906575.04
#Sta/Elev= 30
  4187.2 1606.14  4259.8 1604.63  4324.2 1600.12  4422.1 1594.25  4956.5 1586.17
  5075.0 1586.44  5127.6 1589.23  5314.9 1588.80  5354.5 1582.88  5355.0 1582.38
  5360.4 1582.88  5372.6 1583.38  5393.9 1588.17  5521.4 1590.38  5536.6 1588.86
  5806.8 1589.75  5838.3 1583.32  5977.5 1583.16  6101.0 1595.47  6140.3 1602.42
  6171.2 1596.97  6198.5 1595.39  6266.4 1599.59  6335.1 1599.01  6365.5 1601.41
  6426.2 1593.80  6493.0 1594.67  6510.6 1592.77  6538.6 1600.78  6584.1 1607.32
#Mann=5,-1,0
  4187.2   0.035       0  4324.2    0.05       0  5127.6   0.035       0
  5354.5    0.05       0  5360.4   0.035       0
Bank Sta=5354.5,5360.4
Exp/Cntr=0.3,0.1

Type RM Length L Ch R = 1,8797,442,442,442
BEGIN DESCRIPTION:
Stream0569 10.0
END DESCRIPTION:
XS GIS Cut Line= 4
      1929775.01     13909124.99      1930525.07     13908468.69
      1930565.81     13908333.12      1931017.81     13906385.90
#Sta/Elev= 30
  3928.6 1607.76  4046.8 1604.73  4349.8 1591.75  4570.2 1589.06  4954.8 1586.77
  5026.2 1581.76  5072.9 1585.75  5214.5 1587.65  5362.0 1586.25  5442.7 1587.65
  5464.2 1585.94  5498.2 1578.37  5498.7 1577.87  5504.2 1578.37  5525.8 1581.06
  5692.4 1582.65  5736.5 1580.57  5812.2 1582.74  6059.9 1581.72  6090.9 1578.86
  6107.8 1582.00  6303.8 1584.21  6460.6 1582.75  6479.3 1584.26  6533.2 1583.80
  6618.8 1582.68  6647.5 1579.63  6706.5 1581.86  6768.9 1581.57  7065.8 1597.08
#Mann=7,-1,0
  3928.6   0.035       0  4570.2    0.05       0  5072.9   0.035       0
  5498.2    0.05       0  5504.2   0.035       0  6533.2   0.094       0
  6706.5   0.035       0
Bank Sta=5498.2,5504.2
Exp/Cntr=0.3,0.1

Type RM Length L Ch R = 1,8355,418,418,418
BEGIN DESCRIPTION:
Stream0569 9.0
END DESCRIPTION:
XS GIS Cut Line= 4
      1930125.02     13909124.99      1930871.16     13908705.29
      1930910.37     13908609.17      1931129.04     13906938.10
#Sta/Elev= 30
  4079.7 1594.63  4148.5 1591.47  4182.9 1591.73  4233.8 1589.36  4372.5 1587.11
  4888.5 1583.99  4945.8 1582.25  5001.8 1578.12  5033.2 1582.35  5091.2 1584.98
  5439.1 1585.05  5446.9 1584.08  5472.4 1585.89  5634.2 1585.87  5651.4 1584.59
  5679.7 1581.61  5814.3 1577.51  5923.3 1577.34  6011.0 1579.65  6032.1 1581.41
  6062.4 1579.25  6092.6 1583.57  6188.5 1583.97  6386.1 1579.91  6537.4 1579.26
  6696.3 1575.72  6707.0 1573.47  6707.5 1572.97  6713.0 1573.47  6724.9 1574.11
#Mann=10,-1,0
  4079.7   0.035       0  4372.5    0.05       0  5001.8   0.035       0
  5472.4   0.063       0  5651.4   0.035       0  6188.5   0.063       0
  6386.1   0.094       0  6696.3   0.035       0  6707.0    0.05       0
  6713.0   0.035       0
Bank Sta=6707,6713
Exp/Cntr=0.3,0.1

Type RM Length L Ch R = 1,7937,925,925,925
BEGIN DESCRIPTION:
Stream0569 8.0
END DESCRIPTION:
XS GIS Cut Line= 4
      1930125.00     13909925.00      1931220.48     13908920.81
      1931292.83     13908717.78      1931612.58     13907403.55
#Sta/Elev= 30
  3362.2 1601.83  3398.8 1600.31  3539.5 1595.09  3706.6 1589.93  3758.6 1589.05
  3820.9 1588.42  3896.4 1587.65  4034.1 1586.26  4236.3 1581.94  4562.3 1581.09
  4697.0 1581.15  4845.8 1578.79  5135.4 1577.53  5293.1 1579.51  5327.2 1582.01
  5385.7 1582.78  5527.8 1583.44  5611.3 1582.11  5623.5 1583.65  5737.9 1583.60
  6089.7 1581.37  6132.9 1579.78  6166.9 1576.72  6274.9 1576.36  6302.7 1572.99
  6321.3 1572.61  6321.8 1572.11  6327.4 1572.61  6392.3 1576.10  6416.4 1575.44
#Mann=14,-1,0
  3362.2    0.05       0  3398.8   0.035       0  3539.5    0.05       0
  3706.6   0.035       0  3758.6    0.05       0  3820.9   0.035       0
  3896.4    0.05       0  4034.1   0.035       0  4562.3    0.05       0
  4845.8   0.035       0  5611.3   0.063       0  5737.9   0.035       0
  6321.3   0.035       0  6327.4   0.035       0
Bank Sta=6321.3,6327.4
Exp/Cntr=0.3,0.1

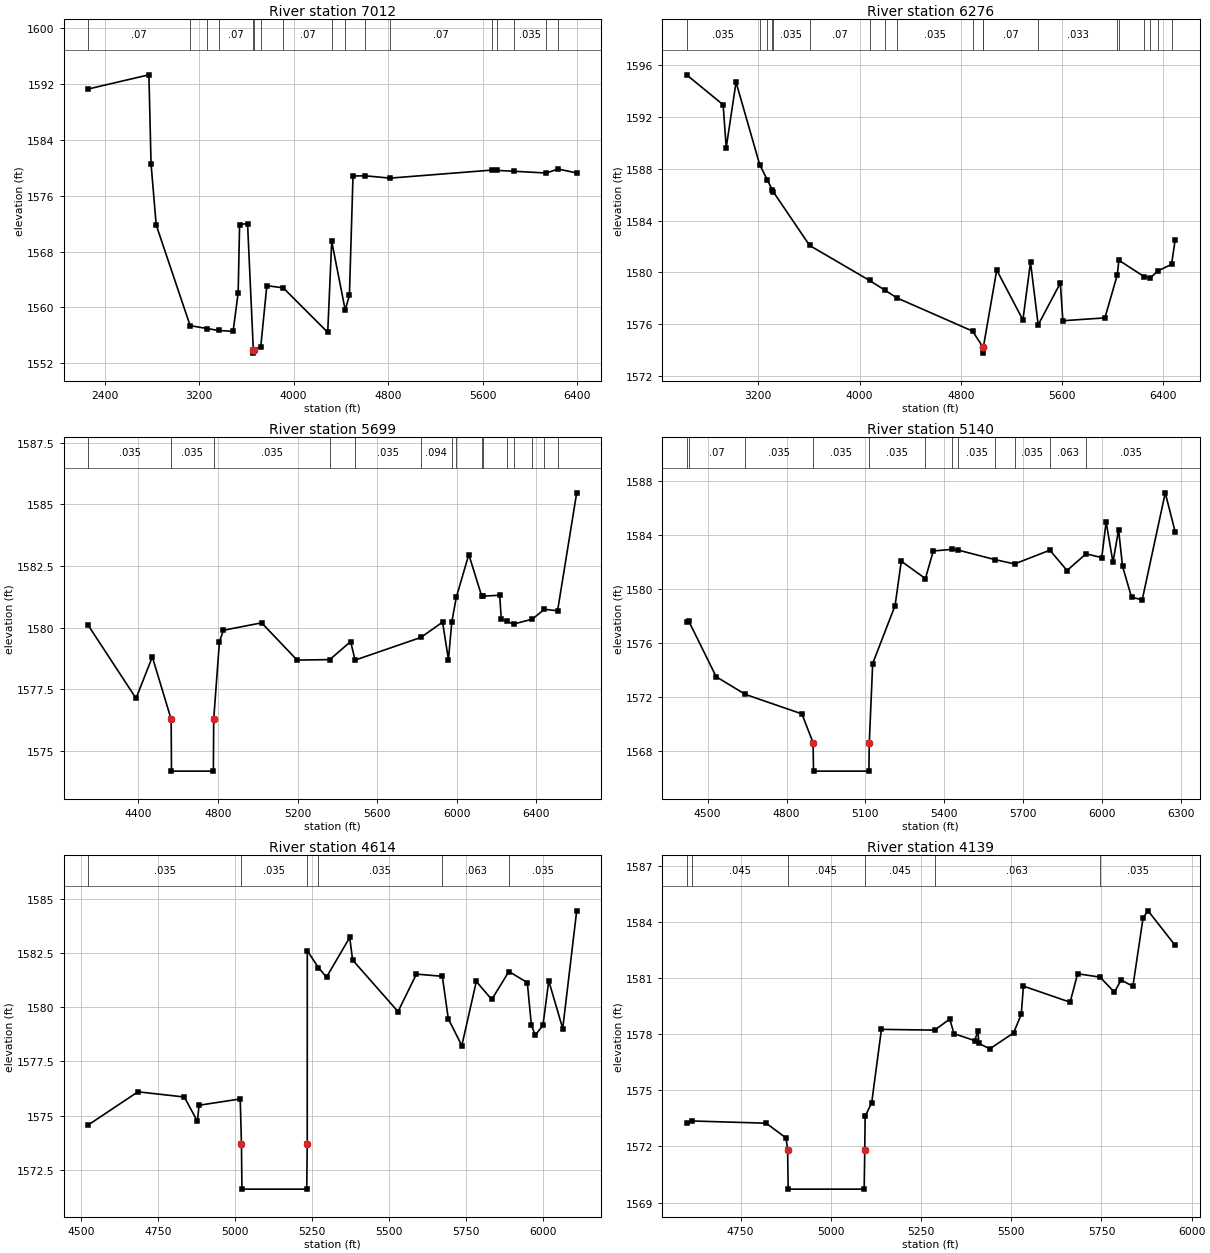
Type RM Length L Ch R = 1,7012,736,736,736
BEGIN DESCRIPTION:
Stream0569 7.2
END DESCRIPTION:
XS GIS Cut Line= 3
      1930736.30     13911770.96      1931953.41     13909387.72
      1932069.46     13907934.59
#Sta/Elev= 30
  2261.2 1591.32  2774.7 1593.35  2793.0 1580.57  2836.4 1571.83  3123.6 1557.39
  3264.9 1556.98  3364.5 1556.70  3487.3 1556.57  3530.1 1562.09  3542.3 1571.89
  3609.6 1572.02  3658.4 1553.95  3658.9 1553.45  3664.6 1553.95  3721.5 1554.40
  3772.8 1563.12  3911.1 1562.81  4288.0 1556.43  4321.8 1569.48  4435.8 1559.64
  4471.4 1561.72  4502.0 1578.85  4606.7 1578.87  4815.5 1578.54  5675.6 1579.69
  5720.9 1579.65  5866.5 1579.52  6138.8 1579.27  6237.2 1579.85  6395.0 1579.28
#Mann=17,-1,0
  2261.2    0.07       0  3123.6   0.033       0  3264.9   0.035       0
  3364.5    0.07       0  3658.4    0.05       0  3664.6    0.07       0
  3721.5   0.035       0  3911.1    0.07       0  4321.8   0.035       0
  4435.8    0.07       0  4606.7   0.035       0  4815.5    0.07       0
  5675.6   0.035       0  5720.9    0.07       0  5866.5   0.035       0
  6138.8   0.094       0  6237.2   0.035       0
Bank Sta=3658.4,3664.6
Exp/Cntr=0.3,0.1

Type RM Length L Ch R = 1,6276,577,577,577
BEGIN DESCRIPTION:
Stream0569 7.1
END DESCRIPTION:
XS GIS Cut Line= 4
      1932767.03     13911837.60      1932646.21     13909534.13
      1932621.70     13909226.26      1932164.15     13908069.34
#Sta/Elev= 30
  2633.7 1595.25  2922.2 1592.94  2946.7 1589.63  3024.3 1594.68  3211.1 1588.32
  3269.7 1587.17  3309.7 1586.39  3317.9 1586.23  3605.7 1582.08  4079.0 1579.38
  4202.0 1578.62  4293.7 1578.04  4892.9 1575.47  4972.9 1574.27  4973.4 1573.77
  4979.1 1574.27  5084.1 1580.18  5290.8 1576.33  5350.9 1580.78  5411.6 1575.95
  5586.7 1579.18  5606.5 1576.27  5938.8 1576.49  6036.6 1579.81  6049.0 1580.94
  6250.8 1579.66  6297.0 1579.57  6358.0 1580.12  6465.1 1580.62  6493.3 1582.47
#Mann=19,-1,0
  2633.7   0.035       0  3211.1    0.07       0  3269.7   0.035       0
  3309.7    0.07       0  3317.9   0.035       0  3605.7    0.07       0
  4079.0   0.035       0  4202.0    0.07       0  4293.7   0.035       0
  4892.9    0.07       0  4972.9    0.05       0  4979.1    0.07       0
  5411.6   0.033       0  6036.6   0.094       0  6049.0   0.035       0
  6250.8   0.094       0  6297.0   0.035       0  6358.0   0.094       0
  6465.1   0.035       0
Bank Sta=4972.9,4979.1
Exp/Cntr=0.3,0.1

Type RM Length L Ch R = 1,5699,559,559,559
BEGIN DESCRIPTION:
Stream0569 7.0
END DESCRIPTION:
XS GIS Cut Line= 4
      1933807.18     13909712.67      1933176.85     13909458.32
      1933000.48     13909137.19      1932140.65     13908020.19
#Sta/Elev= 30
  4147.5 1580.10  4387.9 1577.14  4469.8 1578.82  4564.5 1576.29  4566.1 1574.19
  4776.7 1574.19  4778.3 1576.29  4807.1 1579.43  4827.2 1579.90  5019.2 1580.20
  5197.6 1578.69  5361.9 1578.71  5466.6 1579.44  5489.2 1578.69  5820.3 1579.61
  5928.9 1580.23  5958.4 1578.71  5975.4 1580.24  5998.1 1581.24  6060.8 1582.97
  6125.4 1581.29  6130.6 1581.28  6216.0 1581.32  6224.0 1580.35  6252.6 1580.26
  6285.8 1580.15  6379.8 1580.35  6441.0 1580.75  6507.1 1580.69  6603.2 1585.47
#Mann=15,-1,0
  4147.5   0.035       0  4564.5   0.035       0  4778.3   0.035       0
  5361.9   0.063       0  5489.2   0.035       0  5820.3   0.094       0
  5975.4   0.035       0  5998.1   0.094       0  6125.4   0.035       0
  6130.6   0.094       0  6252.6   0.035       0  6285.8   0.094       0
  6379.8   0.035       0  6441.0   0.094       0  6507.1   0.035       0
Bank Sta=4564.5,4778.3
Exp/Cntr=0.3,0.1

Type RM Length L Ch R = 1,5140,526,526,526
BEGIN DESCRIPTION:
Stream0569 6.0
END DESCRIPTION:
XS GIS Cut Line= 3
      1933697.52     13909025.79      1933175.00     13908775.00
      1932168.52     13907985.62
#Sta/Elev= 30
  4419.9 1577.59  4427.8 1577.63  4532.5 1573.49  4643.2 1572.18  4858.7 1570.73
  4901.2 1568.58  4902.8 1566.48  5113.4 1566.48  5115.0 1568.58  5127.9 1574.47
  5213.2 1578.78  5236.7 1582.07  5328.5 1580.78  5358.5 1582.83  5428.8 1582.95
  5450.7 1582.91  5594.9 1582.18  5668.0 1581.87  5802.1 1582.89  5867.5 1581.38
  5939.6 1582.62  5999.5 1582.34  6016.2 1584.99  6042.2 1581.99  6063.6 1584.41
  6078.6 1581.70  6112.8 1579.40  6153.5 1579.20  6241.2 1587.15  6278.6 1584.27
#Mann=12,-1,0
  4419.9   0.035       0  4427.8    0.07       0  4643.2   0.035       0
  4901.2   0.035       0  5115.0   0.035       0  5328.5   0.035       0
  5428.8   0.063       0  5450.7   0.035       0  5594.9   0.063       0
  5668.0   0.035       0  5802.1   0.063       0  5939.6   0.035       0
Bank Sta=4901.2,5115
Exp/Cntr=0.3,0.1

Type RM Length L Ch R = 1,4614,475,475,475
BEGIN DESCRIPTION:
Stream0569 5.4
END DESCRIPTION:
XS GIS Cut Line= 3
      1933702.87     13908541.64      1933216.50     13908285.14
      1932225.26     13907979.01
#Sta/Elev= 30
  4523.2 1574.57  4684.8 1576.10  4835.4 1575.86  4878.1 1574.74  4883.3 1575.48
  5017.1 1575.77  5021.1 1573.71  5022.7 1571.61  5233.3 1571.61  5234.9 1573.71
  5235.1 1582.61  5271.1 1581.83  5297.5 1581.39  5372.9 1583.22  5382.4 1582.18
  5529.9 1579.80  5589.6 1581.53  5673.8 1581.43  5693.3 1579.47  5737.2 1578.23
  5784.3 1581.19  5834.5 1580.36  5890.2 1581.65  5950.0 1581.14  5963.2 1579.18
  5975.8 1578.71  6000.9 1579.17  6019.7 1581.22  6065.1 1579.02  6110.5 1584.45
#Mann=6,-1,0
  4523.2   0.035       0  5021.1   0.035       0  5234.9   0.035       0
  5271.1   0.035       0  5673.8   0.063       0  5890.2   0.035       0
Bank Sta=5021.1,5234.9
Exp/Cntr=0.3,0.1

Type RM Length L Ch R = 1,4139,609,609,609
BEGIN DESCRIPTION:
Stream0569 5.3
END DESCRIPTION:
XS GIS Cut Line= 3
      1933574.42     13907894.03      1932886.68     13907921.61
      1932222.26     13907885.36
#Sta/Elev= 30
  4600.4 1573.23  4614.5 1573.36  4820.9 1573.24  4876.1 1572.45  4880.3 1571.82
  4881.9 1569.72  5092.5 1569.72  5094.1 1571.82  5095.2 1573.61  5113.3 1574.33
  5140.3 1578.25  5287.9 1578.21  5329.5 1578.80  5341.5 1578.02  5398.6 1577.65
  5407.6 1578.15  5410.6 1577.50  5440.6 1577.21  5506.5 1578.06  5527.8 1579.06
  5533.8 1580.56  5663.2 1579.70  5684.0 1581.22  5746.2 1581.04  5786.1 1580.23
  5804.2 1580.89  5837.2 1580.55  5865.4 1584.21  5879.3 1584.58  5954.1 1582.74
#Mann=6,-1,0
  4600.4   0.035       0  4614.5   0.045       0  4880.3   0.045       0
  5094.1   0.045       0  5287.9   0.063       0  5746.2   0.035       0
Bank Sta=4880.3,5094.1
Exp/Cntr=0.3,0.1

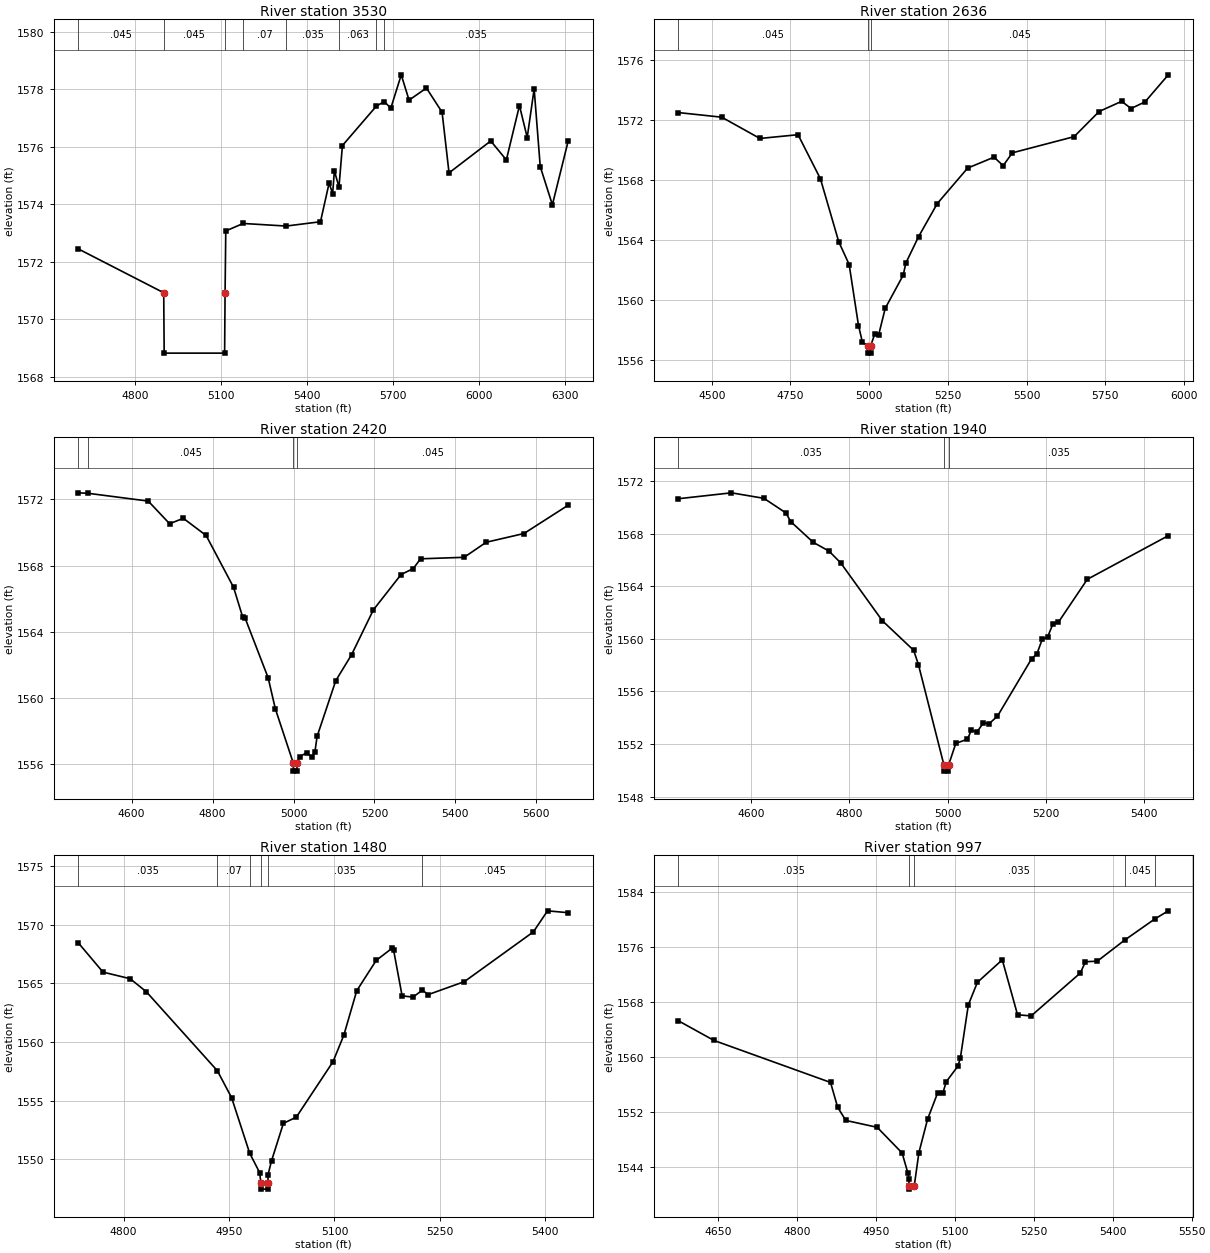
Type RM Length L Ch R = 1,3530,894,894,894
BEGIN DESCRIPTION:
Stream0569 5.2
END DESCRIPTION:
XS GIS Cut Line= 4
      1933386.13     13907337.42      1933153.80     13907363.76
      1932741.64     13907441.94      1931775.33     13907863.53
#Sta/Elev= 30
  4602.6 1572.45  4901.1 1570.92  4902.7 1568.82  5113.3 1568.82  5114.9 1570.92
  5117.3 1573.07  5178.1 1573.33  5327.7 1573.24  5447.3 1573.39  5477.5 1574.74
  5489.6 1574.36  5495.7 1575.16  5511.8 1574.60  5523.7 1576.04  5641.9 1577.41
  5669.6 1577.57  5692.4 1577.34  5728.7 1578.50  5755.9 1577.62  5816.5 1578.04
  5871.0 1577.20  5895.2 1575.09  6040.5 1576.20  6094.9 1575.54  6140.6 1577.43
  6167.6 1576.32  6191.8 1578.01  6213.0 1575.31  6255.3 1573.98  6310.2 1576.19
#Mann=8,-1,0
  4602.6   0.045       0  4901.1   0.045       0  5114.9   0.045       0
  5178.1    0.07       0  5327.7   0.035       0  5511.8   0.063       0
  5641.9   0.094       0  5669.6   0.035       0
Bank Sta=4901.1,5114.9
Exp/Cntr=0.3,0.1

Type RM Length L Ch R = 1,2636,216,216,216
BEGIN DESCRIPTION:
Stream0569 5.1
END DESCRIPTION:
XS GIS Cut Line= 2
      1933488.38     13907069.70      1932370.16     13905985.83
#Sta/Elev= 30
  4393.2 1572.52  4531.6 1572.21  4652.8 1570.79  4774.0 1571.04  4845.2 1568.09
  4903.5 1563.88  4936.4 1562.37  4966.1 1558.29  4978.8 1557.16  4995.2 1556.95
  4995.7 1556.45  5004.4 1556.45  5004.9 1556.95  5017.8 1557.73  5029.7 1557.63
  5051.0 1559.44  5108.2 1561.66  5116.6 1562.47  5157.0 1564.23  5216.4 1566.44
  5312.9 1568.81  5396.8 1569.54  5425.7 1568.97  5455.0 1569.83  5651.3 1570.91
  5730.7 1572.59  5802.3 1573.27  5832.4 1572.79  5876.9 1573.24  5950.5 1575.04
#Mann=3,-1,0
  4393.2   0.045       0  4995.2   0.045       0  5004.9   0.045       0
Bank Sta=4995.2,5004.9
Exp/Cntr=0.3,0.1

Type RM Length L Ch R = 1,2420,480,480,480
BEGIN DESCRIPTION:
Stream0569 5.0
END DESCRIPTION:
XS GIS Cut Line= 3
      1933461.33     13906930.89      1933175.00     13906475.00
      1932725.02     13905975.02
#Sta/Elev= 30
  4467.5 1572.40  4492.8 1572.37  4641.0 1571.90  4693.8 1570.53  4727.6 1570.86
  4784.0 1569.82  4851.7 1566.69  4874.3 1564.89  4879.9 1564.85  4937.3 1561.21
  4955.0 1559.34  4999.2 1556.07  4999.7 1555.57  5008.4 1555.57  5008.9 1556.07
  5015.1 1556.44  5032.1 1556.68  5044.8 1556.42  5052.9 1556.75  5058.2 1557.67
  5104.3 1561.04  5143.4 1562.61  5197.2 1565.32  5265.7 1567.46  5295.9 1567.82
  5313.8 1568.41  5421.5 1568.50  5476.0 1569.41  5569.4 1569.94  5678.5 1571.65
#Mann=4,-1,0
  4467.5   0.035       0  4492.8   0.045       0  4999.2   0.045       0
  5008.9   0.045       0
Bank Sta=4999.2,5008.9
Exp/Cntr=0.3,0.1

Type RM Length L Ch R = 1,1940,460,460,460
BEGIN DESCRIPTION:
Stream0569 4.0
END DESCRIPTION:
XS GIS Cut Line= 3
      1933549.67     13906587.99      1933375.00     13906075.00
      1933249.16     13905636.41
#Sta/Elev= 30
  4451.2 1570.66  4559.7 1571.11  4625.9 1570.69  4670.6 1569.58  4680.4 1568.92
  4726.4 1567.34  4758.3 1566.68  4782.2 1565.78  4867.0 1561.38  4930.8 1559.13
  4940.5 1558.04  4992.2 1550.44  4992.7 1549.94  5001.7 1549.94  5002.2 1550.44
  5016.6 1552.05  5040.4 1552.37  5048.1 1553.04  5059.7 1552.92  5073.0 1553.62
  5083.9 1553.53  5101.5 1554.12  5170.9 1558.48  5181.8 1558.86  5192.6 1559.96
  5203.5 1560.14  5214.4 1561.13  5225.3 1561.25  5284.4 1564.53  5449.4 1567.85
#Mann=3,-1,0
  4451.2   0.035       0  4992.2   0.035       0  5002.2   0.035       0
Bank Sta=4992.2,5002.2
Exp/Cntr=0.3,0.1

Type RM Length L Ch R = 1,1480,483,483,483
BEGIN DESCRIPTION:
Stream0569 3.0
END DESCRIPTION:
XS GIS Cut Line= 3
      1933666.70     13905732.16      1933425.00     13905625.00
      1933002.36     13905531.72
#Sta/Elev= 30
  4735.2 1568.47  4770.7 1565.95  4809.3 1565.39  4832.3 1564.28  4933.4 1557.55
  4953.7 1555.25  4979.3 1550.54  4993.5 1548.88  4995.4 1547.97  4995.9 1547.47
  5004.9 1547.47  5005.4 1547.97  5005.5 1548.71  5010.5 1549.89  5027.3 1553.07
  5045.7 1553.60  5097.9 1558.32  5113.3 1560.58  5131.7 1564.37  5159.4 1566.95
  5181.6 1567.97  5184.0 1567.86  5196.2 1563.93  5211.6 1563.82  5225.2 1564.42
  5233.1 1564.03  5284.8 1565.14  5383.0 1569.38  5403.1 1571.17  5432.4 1571.01
#Mann=6,-1,0
  4735.2   0.035       0  4933.4    0.07       0  4979.3   0.035       0
  4995.4   0.035       0  5005.4   0.035       0  5225.2   0.045       0
Bank Sta=4995.4,5005.4
Exp/Cntr=0.3,0.1

Type RM Length L Ch R = 1,997,473,473,473
BEGIN DESCRIPTION:
Stream0569 2.0
END DESCRIPTION:
XS GIS Cut Line= 3
      1933723.98     13905546.10      1933525.00     13905175.00
      1933050.51     13904987.98
#Sta/Elev= 30
  4574.5 1565.34  4642.5 1562.46  4863.9 1556.35  4877.4 1552.74  4892.9 1550.82
  4952.5 1549.82  4999.9 1546.08  5011.0 1543.12  5012.8 1542.33  5013.0 1541.32
  5013.5 1540.82  5023.0 1541.32  5031.8 1546.14  5048.3 1551.01  5067.6 1554.87
  5077.3 1554.81  5083.8 1556.46  5105.8 1558.71  5110.5 1559.87  5125.7 1567.64
  5142.9 1570.92  5190.2 1574.20  5219.2 1566.20  5245.0 1566.03  5338.5 1572.28
  5348.2 1573.92  5370.7 1574.00  5422.4 1577.05  5479.7 1580.13  5505.6 1581.33
#Mann=5,-1,0
  4574.5   0.035       0  5013.0   0.035       0  5023.0   0.035       0
  5422.4   0.045       0  5479.7   0.035       0
Bank Sta=5013,5023
Exp/Cntr=0.3,0.1