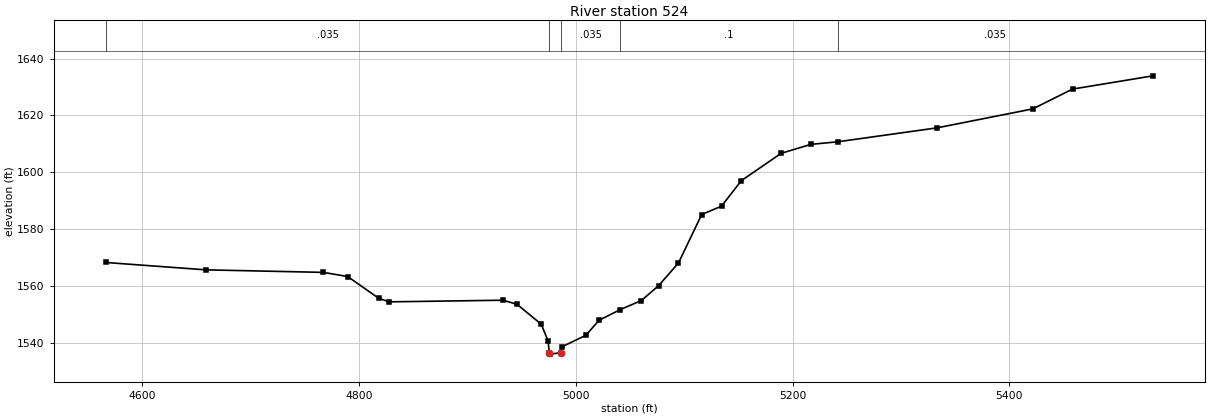
HEC-RAS study Stream0569.prj: Stream0569 Base Level Engineering

--- Stream0569.g01 (geometry) --- (continued)

Type RM Length L Ch R = 1,524,0,0,0
BEGIN DESCRIPTION:
Stream0569 1.0
END DESCRIPTION:
XS GIS Cut Line= 3
      1933727.86     13905632.80      1933875.00     13905225.00
      1933975.14     13904702.03
#Sta/Elev= 30
  4566.5 1568.28  4658.8 1565.69  4767.2 1564.80  4789.5 1563.34  4818.2 1555.69
  4827.8 1554.43  4933.0 1555.01  4945.8 1553.55  4968.1 1546.57  4974.5 1540.57
  4975.5 1536.54  4976.0 1536.04  4986.3 1536.54  4987.3 1538.64  5009.2 1542.64
  5021.4 1547.94  5041.1 1551.72  5060.5 1554.90  5076.4 1560.14  5094.7 1568.11
  5116.1 1585.15  5134.4 1588.10  5152.7 1597.07  5189.4 1606.68  5216.9 1609.84
  5241.6 1610.74  5333.0 1615.63  5421.5 1622.31  5458.2 1629.28  5532.5 1633.95
#Mann=5,-1,0
  4566.5   0.035       0  4975.5   0.035       0  4986.3   0.035       0
  5041.1     0.1       0  5241.6   0.035       0
Bank Sta=4975.5,4986.3
Exp/Cntr=0.3,0.1

Chan Stop Cuts=-1