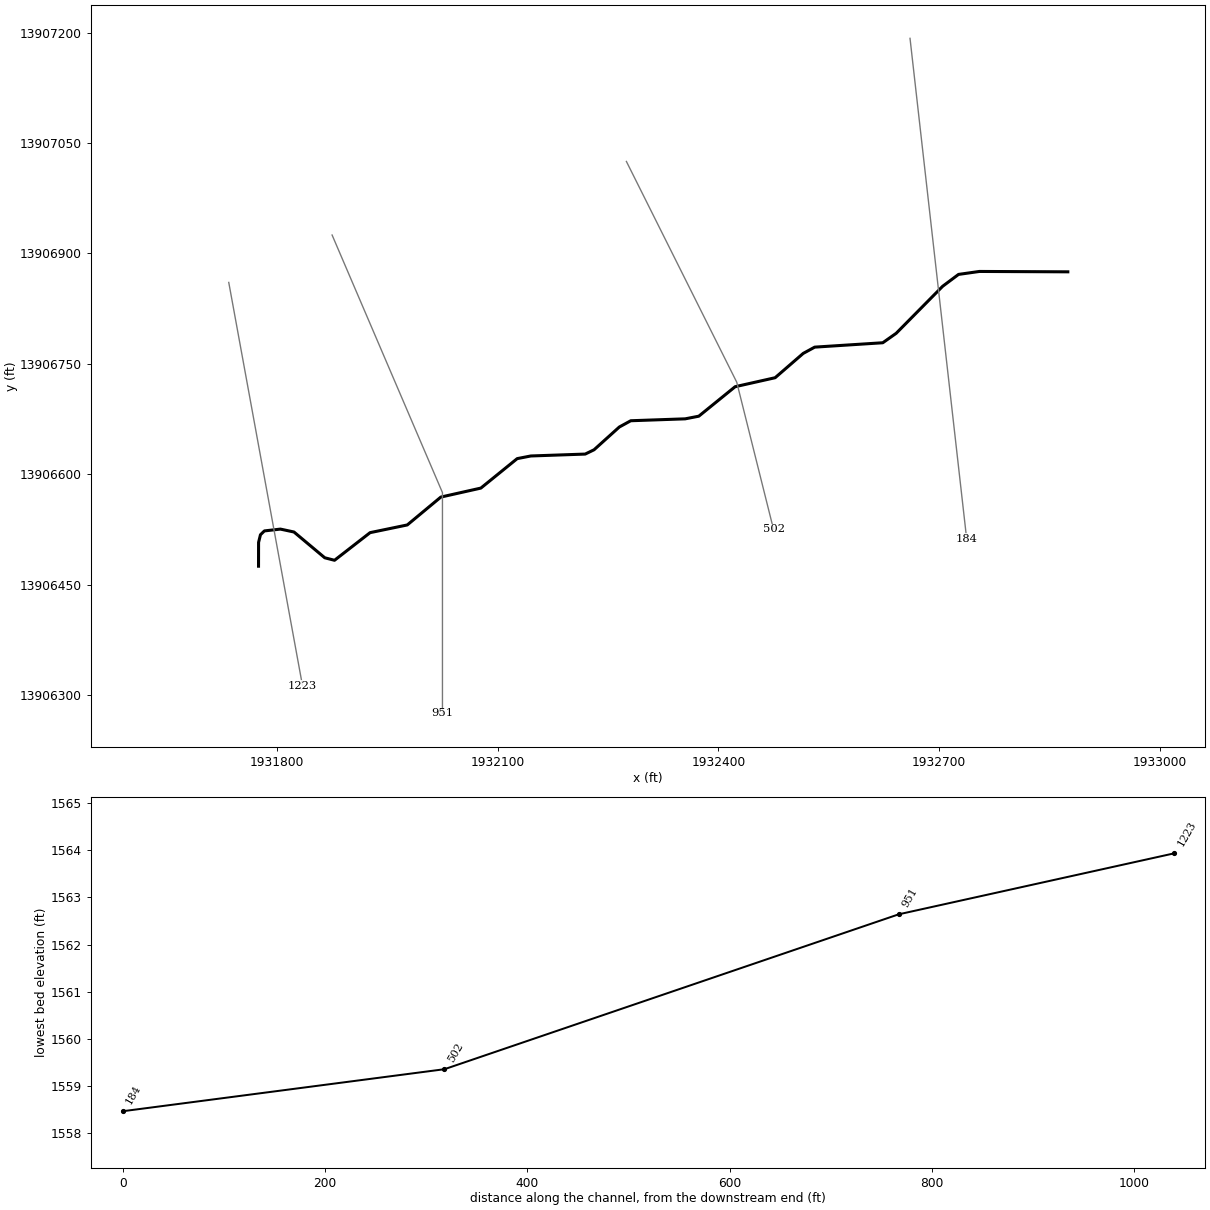
--- Stream0570.prj (project) ---

Proj Title=Stream0570 Base Level Engineering
Current Plan=p01
Default Exp/Contr=0.3,0.1
English Units
Geom File=g01
Flow File=f01
Plan File=p01
Y Axis Title=Elevation
X Axis Title(PF)=Main Channel Distance
X Axis Title(XS)=Station
BEGIN DESCRIPTION:
Stream0570
END DESCRIPTION:
DSS Export Rating Curves= 0
DSS Export Rating Curve Sorted= 0
DSS Export Volume Flow Curves= 0
DXF OffsetX= 0
DXF OffsetY= 0
DXF ScaleX= 1
DXF ScaleY= 10

--- Stream0570.p01 (plan) ---

Plan Title=Multiple Run
Short Identifier=Multiple
Geom File=g01
Flow File=f01
Subcritical Flow
K Sum by GR= 0
Std Step Tol= 0.01
Critical Tol= 0.01
Num of Std Step Trials= 20
Max Error Tol= 0.3
Flow Tol Ratio= 0.001
Split Flow NTrial= 30
Split Flow Tol= 0.02
Split Flow Ratio= 0.02
Log Output Level= 0
Friction Slope Method= 1
Unsteady Friction Slope Method= 2
Unsteady Bridges Friction Slope Method= 1
Parabolic Critical Depth
Global Vel Dist=  1 , 1 , 1
Global Log Level= 0
CheckData=True
Encroach Param= -1, 0, 0, 0
BEGIN DESCRIPTION:
Multiple Run
END DESCRIPTION:

--- Stream0570.f01 (steady flow) ---

Flow Title=Multiple
Program Version=4.10
Number of Profiles= 7
Profile Names=10-year,25-year,50-year,1pct_min,100-year,1pct_plu,500-year
River Rch & RM=Stream0570,Reach-1         ,1223
    1112    1901    2656    1796    3584    7151    6440
Boundary for River Rch & Prof#=Stream0570,Reach-1         , 1
Up Type= 0
Dn Type= 3
Dn Slope=0.006
Boundary for River Rch & Prof#=Stream0570,Reach-1         , 2
Up Type= 0
Dn Type= 3
Dn Slope=0.006
Boundary for River Rch & Prof#=Stream0570,Reach-1         , 3
Up Type= 0
Dn Type= 3
Dn Slope=0.006
Boundary for River Rch & Prof#=Stream0570,Reach-1         , 4
Up Type= 0
Dn Type= 3
Dn Slope=0.006
Boundary for River Rch & Prof#=Stream0570,Reach-1         , 5
Up Type= 0
Dn Type= 3
Dn Slope=0.006
Boundary for River Rch & Prof#=Stream0570,Reach-1         , 6
Up Type= 0
Dn Type= 3
Dn Slope=0.006
Boundary for River Rch & Prof#=Stream0570,Reach-1         , 7
Up Type= 0
Dn Type= 3
Dn Slope=0.006
DSS Import GetInterval= 0
DSS Import GetPeak= 0
DSS Import FillOption= 0

--- Stream0570.g01 (geometry) ---

Geom Title=Existing Conditions

River Reach=Stream0570,Reach-1
Reach XY= 30
      1931775.00     13906475.00      1931775.07     13906507.33
      1931777.62     13906517.72      1931783.01     13906522.94
      1931804.78     13906525.40      1931823.19     13906521.46
      1931865.04     13906486.43      1931878.29     13906483.03
      1931926.64     13906520.58      1931977.19     13906531.05
      1932022.80     13906568.92      1932077.18     13906581.12
      1932126.58     13906621.17      1932145.09     13906624.77
      1932219.03     13906627.35      1932231.04     13906633.19
      1932265.37     13906664.11      1932280.97     13906672.65
      1932354.91     13906675.23      1932373.42     13906678.83
      1932422.82     13906718.89      1932477.18     13906731.11
      1932515.35     13906764.16      1932530.97     13906772.67
      1932623.50     13906778.62      1932641.74     13906791.49
      1932704.85     13906855.35      1932726.45     13906871.49
      1932754.79     13906875.51      1932875.00     13906875.00

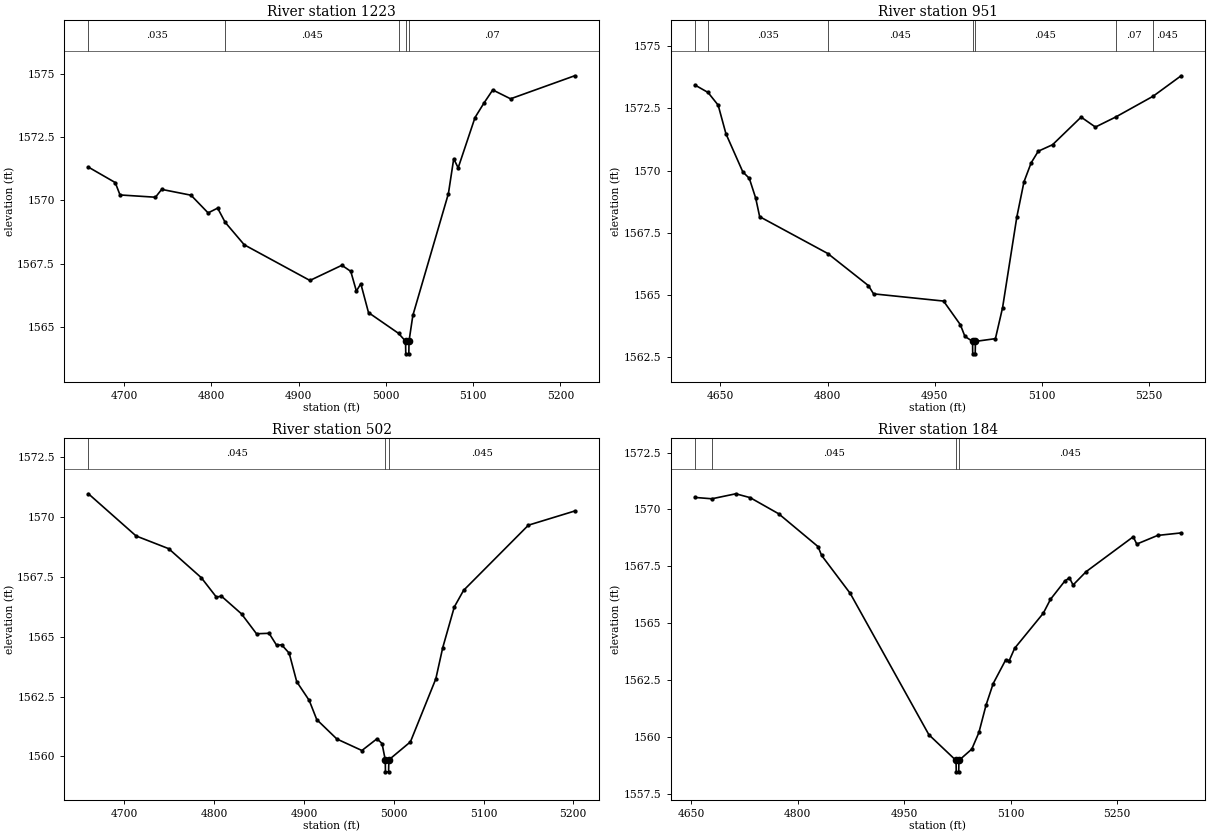
Type RM Length L Ch R = 1,1223,272,272,272
BEGIN DESCRIPTION:
Stream0570 3.0
END DESCRIPTION:
XS GIS Cut Line= 2
      1931734.54     13906860.58      1931834.73     13906312.77
#Sta/Elev= 30
  4659.3 1571.31  4690.0 1570.70  4695.5 1570.21  4736.1 1570.12  4743.2 1570.43
  4776.8 1570.20  4796.4 1569.50  4807.3 1569.69  4815.9 1569.13  4837.8 1568.24
  4913.0 1566.83  4949.6 1567.43  4959.8 1567.19  4966.2 1566.41  4971.3 1566.70
  4980.1 1565.56  5014.5 1564.74  5022.5 1564.43  5022.8 1563.93  5026.3 1563.93
  5026.5 1564.43  5030.9 1565.45  5071.6 1570.26  5077.7 1571.64  5082.8 1571.28
  5102.1 1573.27  5112.3 1573.84  5122.4 1574.36  5142.8 1574.01  5216.2 1574.92
#Mann=5,-1,0
  4659.3   0.035       0  4815.9   0.045       0  5014.5    0.07       0
  5022.5   0.045       0  5026.5    0.07       0
Bank Sta=5022.5,5026.5
Exp/Cntr=0.3,0.1

Type RM Length L Ch R = 1,951,449,449,449
BEGIN DESCRIPTION:
Stream0570 2.0
END DESCRIPTION:
XS GIS Cut Line= 3
      1931875.00     13906925.01      1932025.00     13906575.00
      1932025.00     13906275.00
#Sta/Elev= 30
  4614.2 1573.44  4632.6 1573.14  4646.8 1572.63  4657.7 1571.48  4681.3 1569.95
  4690.4 1569.69  4699.4 1568.89  4704.9 1568.15  4800.3 1566.67  4857.2 1565.38
  4864.4 1565.05  4962.4 1564.76  4985.9 1563.81  4992.3 1563.34  5003.0 1563.14
  5003.2 1562.64  5006.7 1562.64  5007.0 1563.14  5035.0 1563.25  5045.0 1564.49
  5065.0 1568.14  5075.0 1569.55  5085.0 1570.31  5095.0 1570.78  5115.0 1571.04
  5155.0 1572.15  5175.0 1571.75  5203.2 1572.15  5255.9 1572.99  5295.0 1573.81
#Mann=7,-1,0
  4614.2   0.094       0  4632.6   0.035       0  4800.3   0.045       0
  5003.0   0.045       0  5007.0   0.045       0  5203.2    0.07       0
  5255.9   0.045       0
Bank Sta=5003,5007
Exp/Cntr=0.3,0.1

Type RM Length L Ch R = 1,502,318,318,318
BEGIN DESCRIPTION:
Stream0570 1.0
END DESCRIPTION:
XS GIS Cut Line= 3
      1932275.02     13907024.97      1932425.00     13906725.00
      1932474.99     13906525.03
#Sta/Elev= 30
  4660.0 1570.96  4713.1 1569.20  4749.4 1568.67  4785.7 1567.46  4802.5 1566.65
  4808.1 1566.69  4830.5 1565.95  4847.2 1565.12  4861.2 1565.14  4869.6 1564.64
  4875.2 1564.66  4883.6 1564.31  4892.0 1563.12  4905.9 1562.34  4914.3 1561.54
  4936.7 1560.73  4964.6 1560.25  4981.4 1560.74  4987.0 1560.54  4990.6 1559.86
  4990.8 1559.36  4994.3 1559.36  4994.6 1559.86  5018.6 1560.61  5046.9 1563.24
  5054.6 1564.54  5067.5 1566.24  5077.8 1566.93  5150.0 1569.65  5201.5 1570.24
#Mann=3,-1,0
  4660.0   0.045       0  4990.6   0.045       0  4994.6   0.045       0
Bank Sta=4990.6,4994.6
Exp/Cntr=0.3,0.1

Type RM Length L Ch R = 1,184,0,0,0
BEGIN DESCRIPTION:
Stream0570 0.0
END DESCRIPTION:
XS GIS Cut Line= 2
      1932660.51     13907192.28      1932737.50     13906512.22
#Sta/Elev= 30
  4655.4 1570.53  4679.3 1570.47  4713.0 1570.69  4733.2 1570.52  4773.4 1569.81
  4828.7 1568.37  4833.8 1567.98  4874.1 1566.31  4984.8 1560.10  5023.0 1558.97
  5023.3 1558.47  5026.8 1558.47  5027.0 1558.97  5045.2 1559.47  5055.2 1560.20
  5065.3 1561.41  5075.3 1562.35  5092.9 1563.39  5097.9 1563.36  5105.5 1563.90
  5145.8 1565.44  5155.9 1566.05  5176.0 1566.85  5182.6 1567.00  5187.7 1566.68
  5206.2 1567.27  5272.4 1568.80  5277.4 1568.48  5306.8 1568.86  5339.8 1568.97
#Mann=4,-1,0
  4655.4   0.035       0  4679.3   0.045       0  5023.0   0.045       0
  5027.0   0.045       0
Bank Sta=5023,5027
Exp/Cntr=0.3,0.1

Chan Stop Cuts=-1