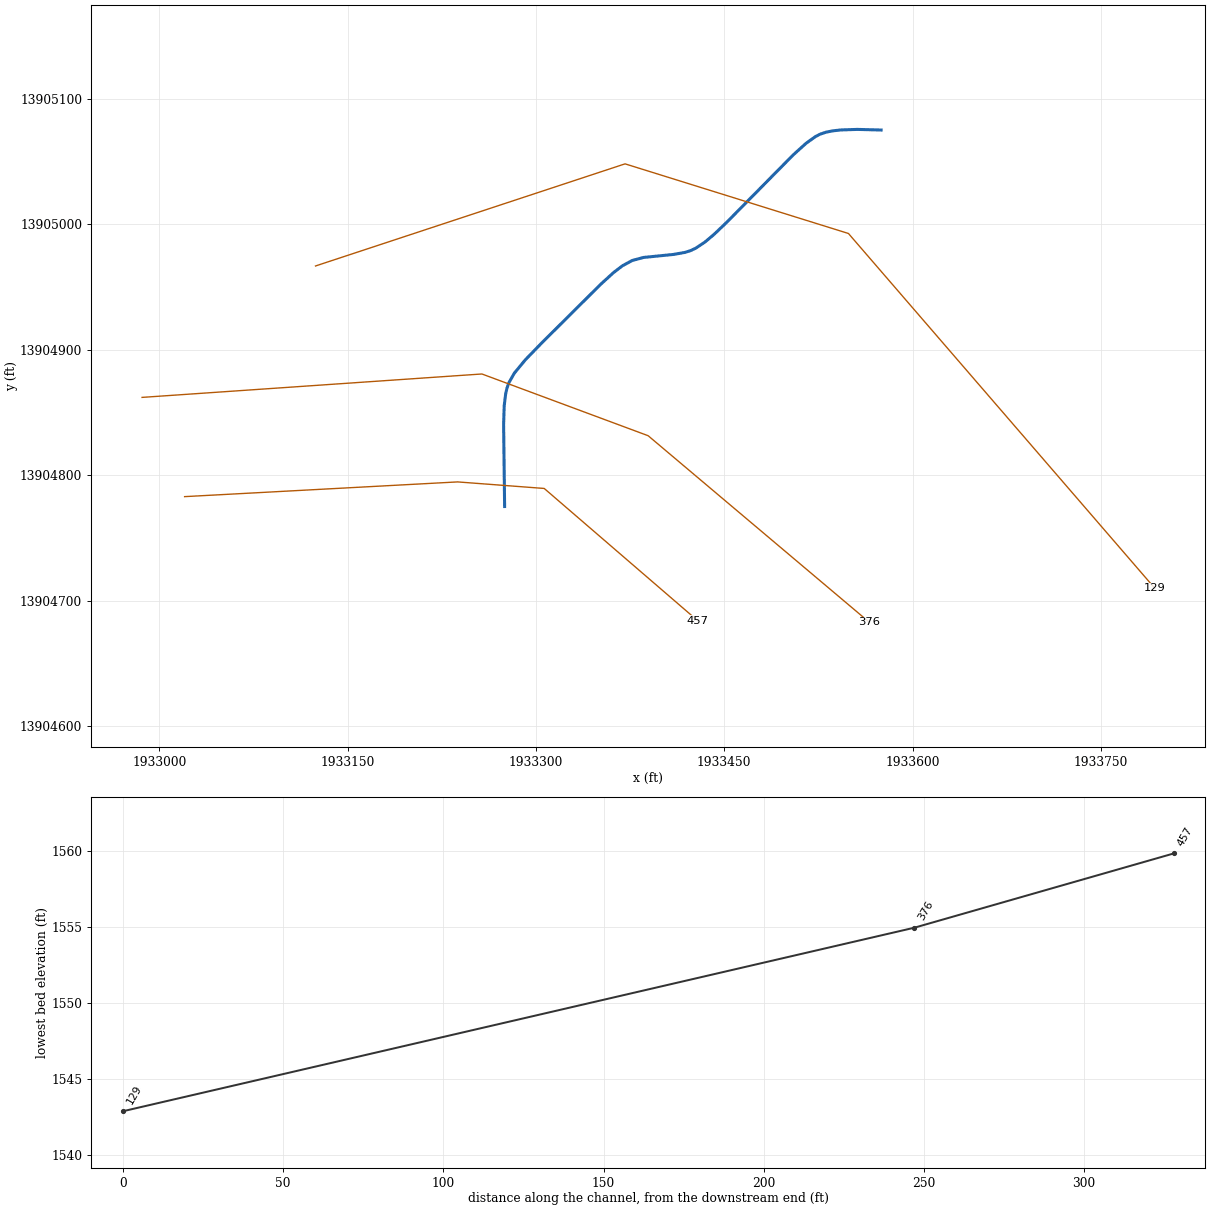
--- Stream0571.prj (project) ---

Proj Title=Stream0571 Base Level Engineering
Current Plan=p01
Default Exp/Contr=0.3,0.1
English Units
Geom File=g01
Flow File=f01
Plan File=p01
BEGIN DESCRIPTION:
Stream0571
END DESCRIPTION:

--- Stream0571.p01 (plan) ---

Plan Title=Multiple Run
Short Identifier=Multiple
Geom File=g01
Flow File=f01
Subcritical Flow
K Sum by GR= 0
Std Step Tol= 0.01
Critical Tol= 0.01
Num of Std Step Trials= 20
Max Error Tol= 0.3
Flow Tol Ratio= 0.001
Split Flow NTrial= 30
Split Flow Tol= 0.02
Split Flow Ratio= 0.02
Log Output Level= 0
Friction Slope Method= 1
Unsteady Friction Slope Method= 2
Unsteady Bridges Friction Slope Method= 1
Parabolic Critical Depth
Global Vel Dist=  1 , 1 , 1
Global Log Level= 0
CheckData=True
Encroach Param= -1, 0, 0, 0
BEGIN DESCRIPTION:
Multiple Run
END DESCRIPTION:

--- Stream0571.f01 (steady flow) ---

Flow Title=Multiple
Number of Profiles=7
Profile Names=10-year,25-year,50-year,1pct_min,100-year,1pct_plu,500-year
River Rch & RM= Stream0571,Reach-1,457
     597     976    1324     872    1740    3472    2959
Boundary for River Rch & Prof#=Stream0571,Reach-1,1
Up Type=0
Dn Type=3
Dn Slope=0.005
Boundary for River Rch & Prof#=Stream0571,Reach-1,2
Up Type=0
Dn Type=3
Dn Slope=0.005
Boundary for River Rch & Prof#=Stream0571,Reach-1,3
Up Type=0
Dn Type=3
Dn Slope=0.005
Boundary for River Rch & Prof#=Stream0571,Reach-1,4
Up Type=0
Dn Type=3
Dn Slope=0.005
Boundary for River Rch & Prof#=Stream0571,Reach-1,5
Up Type=0
Dn Type=3
Dn Slope=0.005
Boundary for River Rch & Prof#=Stream0571,Reach-1,6
Up Type=0
Dn Type=3
Dn Slope=0.005
Boundary for River Rch & Prof#=Stream0571,Reach-1,7
Up Type=0
Dn Type=3
Dn Slope=0.005

--- Stream0571.g01 (geometry) ---

Geom Title=Existing Conditions

River Reach=Stream0571,Reach-1
Reach XY= 30
      1933275.00     13904775.00      1933274.20     13904840.33
      1933274.67     13904855.14      1933275.81     13904864.67
      1933276.85     13904869.24      1933278.38     13904873.61
      1933282.73     13904881.24      1933291.42     13904891.80
      1933304.50     13904905.27      1933351.48     13904952.01
      1933361.76     13904961.38      1933368.93     13904966.85
      1933376.63     13904971.03      1933385.63     13904973.46
      1933409.63     13904975.88      1933418.95     13904977.54
      1933423.35     13904978.98      1933427.29     13904980.86
      1933434.67     13904985.78      1933441.67     13904991.66
      1933451.81     13905001.32      1933504.93     13905055.17
      1933515.23     13905064.46      1933522.49     13905069.67
      1933526.36     13905071.71      1933531.15     13905073.31
      1933536.85     13905074.40      1933543.12     13905075.07
      1933556.04     13905075.50      1933575.00     13905075.00

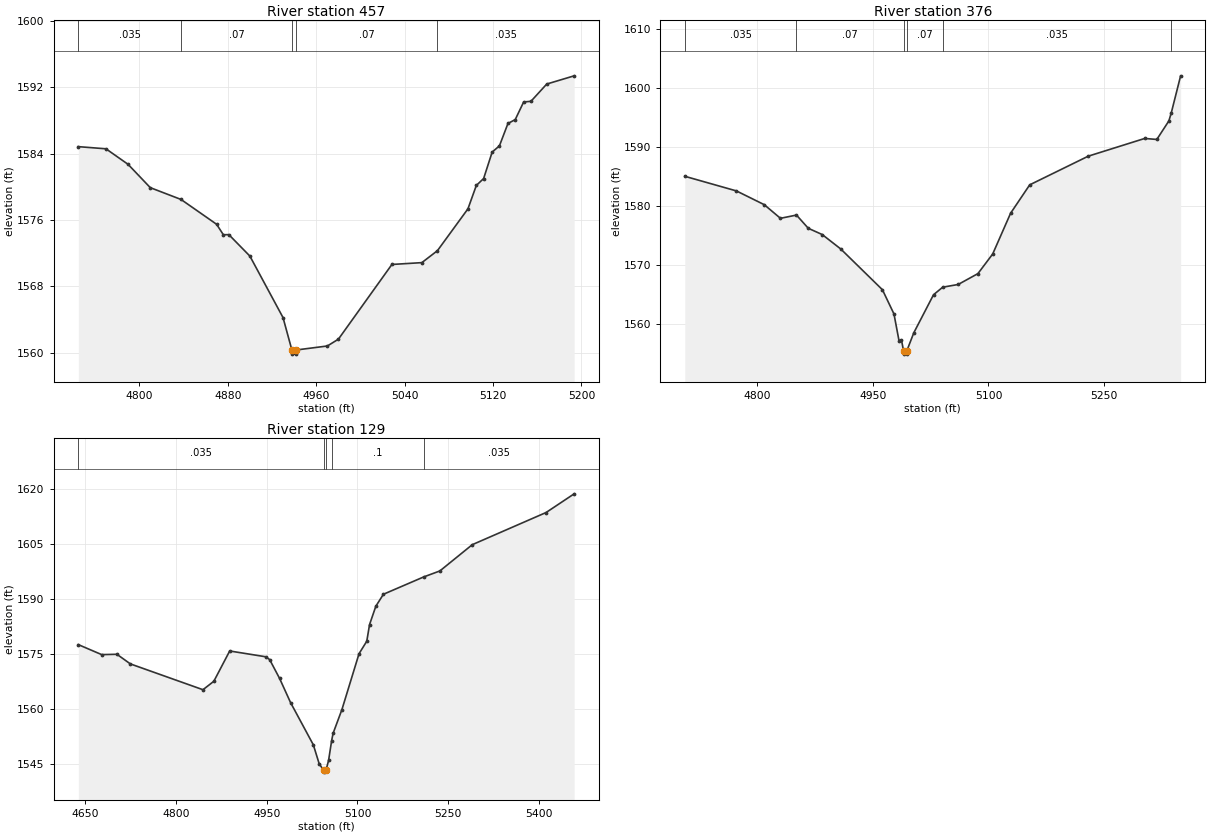
Type RM Length L Ch R = 1,457,81,81,81
BEGIN DESCRIPTION:
Stream0571 A
END DESCRIPTION:
XS GIS Cut Line= 4
      1933020.04     13904782.88      1933237.54     13904794.61
      1933306.55     13904789.40      1933428.95     13904683.92
#Sta/Elev= 30
  4744.8 1584.83  4769.8 1584.57  4789.8 1582.70  4809.9 1579.89  4837.7 1578.47
  4869.9 1575.48  4876.0 1574.22  4881.0 1574.23  4900.0 1571.65  4930.0 1564.24
  4938.0 1560.34  4938.3 1559.84  4941.8 1559.84  4942.0 1560.34  4970.1 1560.82
  4980.1 1561.64  5028.5 1570.64  5055.6 1570.86  5069.7 1572.30  5097.3 1577.34
  5104.9 1580.16  5111.5 1580.99  5119.2 1584.17  5125.8 1584.93  5133.5 1587.62
  5140.1 1588.09  5147.7 1590.21  5154.3 1590.29  5168.6 1592.37  5193.4 1593.36
#Mann=5,-1,0
  4744.8   0.035       0  4837.7    0.07       0  4938.0    0.05       0
  4942.0    0.07       0  5069.7   0.035       0
Bank Sta=4938,4942
Exp/Cntr=0.3,0.1

Type RM Length L Ch R = 1,376,247,247,247
BEGIN DESCRIPTION:
Stream0571 2.0
END DESCRIPTION:
XS GIS Cut Line= 4
      1932986.13     13904861.96      1933256.91     13904880.62
      1933389.35     13904831.42      1933565.62     13904682.74
#Sta/Elev= 30
  4706.0 1585.08  4773.0 1582.60  4809.1 1580.27  4830.1 1577.96  4850.9 1578.51
  4866.2 1576.27  4884.3 1575.21  4908.3 1572.77  4962.4 1565.86  4977.4 1561.75
  4983.9 1557.24  4987.1 1557.36  4989.9 1555.45  4990.2 1554.95  4993.7 1554.95
  4993.9 1555.45  5003.1 1558.56  5028.7 1565.01  5040.6 1566.29  5060.7 1566.75
  5086.3 1568.59  5105.5 1571.92  5128.7 1578.82  5153.5 1583.63  5229.5 1588.49
  5302.7 1591.49  5318.4 1591.32  5334.1 1594.47  5337.2 1595.84  5349.3 1602.10
#Mann=6,-1,0
  4706.0   0.035       0  4850.9    0.07       0  4989.9    0.05       0
  4993.9    0.07       0  5040.6   0.035       0  5337.2   0.063       0
Bank Sta=4989.9,4993.9
Exp/Cntr=0.3,0.1

Type RM Length L Ch R = 1,129,0,0,0
BEGIN DESCRIPTION:
Stream0571 1.0
END DESCRIPTION:
XS GIS Cut Line= 4
      1933124.34     13904966.68      1933370.96     13905048.05
      1933548.94     13904992.57      1933793.01     13904709.88
#Sta/Elev= 30
  4638.6 1577.60  4677.2 1574.88  4702.4 1574.97  4724.6 1572.35  4844.6 1565.32
  4862.6 1567.62  4888.8 1575.87  4948.5 1574.29  4954.9 1573.51  4971.3 1568.39
  4989.4 1561.82  5027.1 1550.29  5036.6 1545.21  5044.0 1543.37  5044.3 1542.87
  5048.0 1543.37  5052.3 1546.09  5057.3 1551.43  5059.7 1553.43  5074.3 1559.90
  5102.6 1575.13  5115.4 1578.53  5120.0 1583.07  5130.4 1588.07  5142.9 1591.32
  5209.3 1596.03  5236.2 1597.67  5289.8 1604.83  5411.8 1613.59  5458.2 1618.68
#Mann=5,-1,0
  4638.6   0.035       0  5044.0   0.035       0  5048.0   0.035       0
  5057.3     0.1       0  5209.3   0.035       0
Bank Sta=5044,5048
Exp/Cntr=0.3,0.1

Chan Stop Cuts=-1