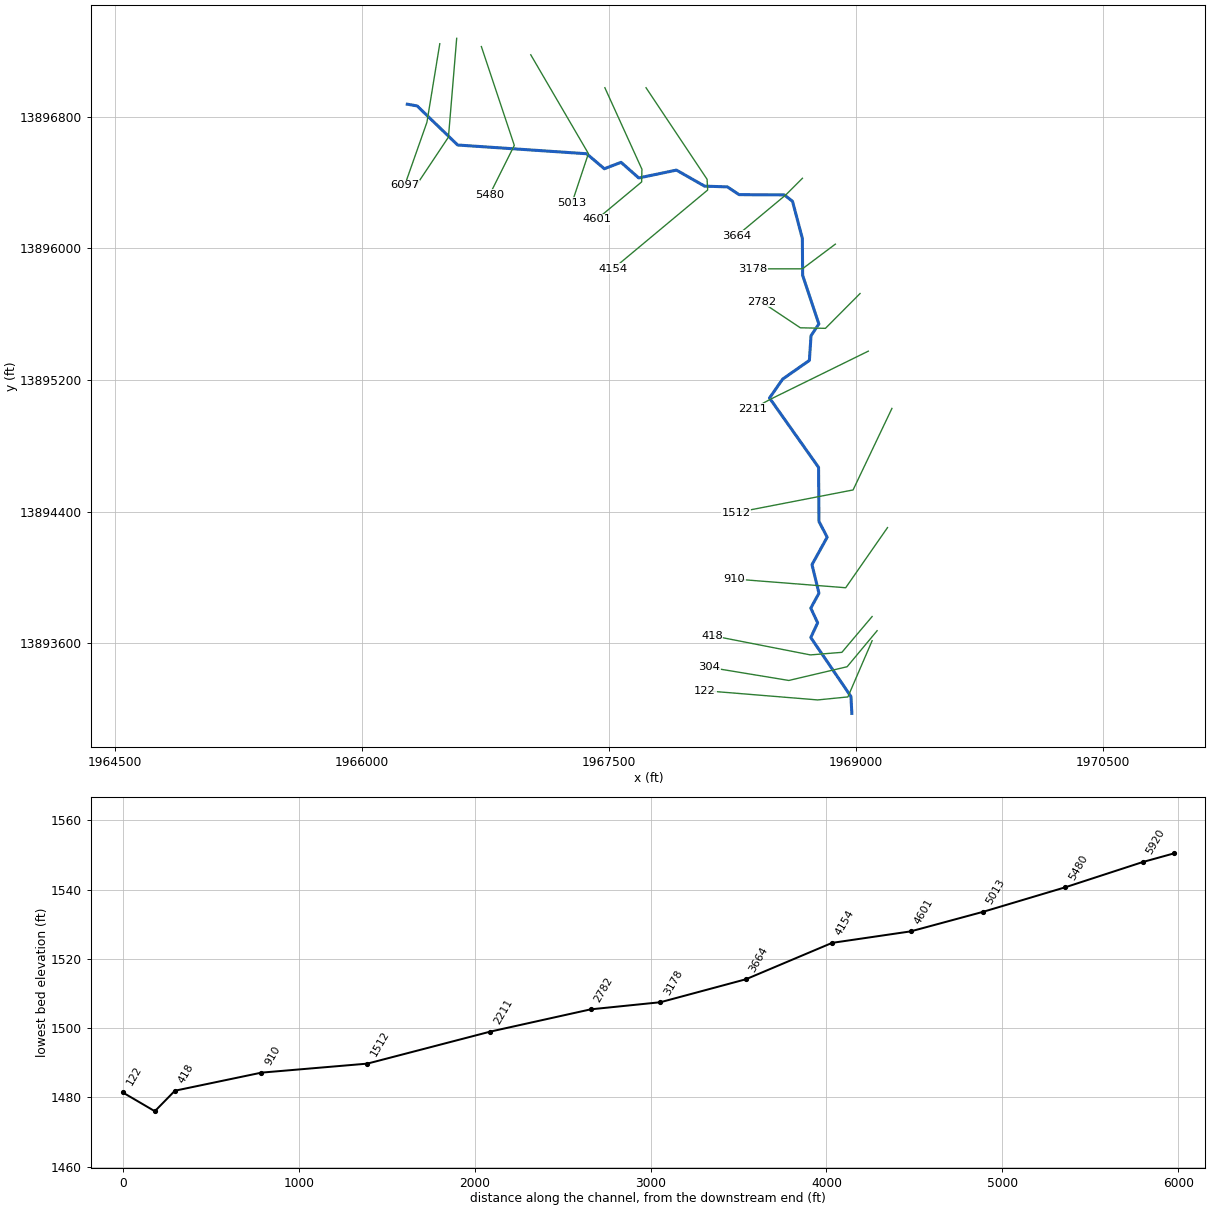
--- Stream0572.prj (project) ---

Proj Title=Stream0572 Base Level Engineering
Current Plan=p01
Default Exp/Contr=0.3,0.1
English Units
Geom File=g01
Flow File=f01
Plan File=p01
BEGIN DESCRIPTION:
Stream0572
END DESCRIPTION:

--- Stream0572.p01 (plan) ---

Plan Title=Multiple Run
Short Identifier=Multiple
Geom File=g01
Flow File=f01
Subcritical Flow
K Sum by GR= 0
Std Step Tol= 0.01
Critical Tol= 0.01
Num of Std Step Trials= 20
Max Error Tol= 0.3
Flow Tol Ratio= 0.001
Split Flow NTrial= 30
Split Flow Tol= 0.02
Split Flow Ratio= 0.02
Log Output Level= 0
Friction Slope Method= 1
Unsteady Friction Slope Method= 2
Unsteady Bridges Friction Slope Method= 1
Parabolic Critical Depth
Global Vel Dist=  1 , 1 , 1
Global Log Level= 0
CheckData=True
Encroach Param= -1, 0, 0, 0
BEGIN DESCRIPTION:
Multiple Run
END DESCRIPTION:

--- Stream0572.f01 (steady flow) ---

Flow Title=Multiple
Number of Profiles=7
Profile Names=10-year,25-year,50-year,1pct_min,100-year,1pct_plu,500-year
River Rch & RM= Stream0572,Reach-1,6097
    1210    2063    2876    1940    3870    7722    6914
Boundary for River Rch & Prof#=Stream0572,Reach-1,1
Up Type=0
Dn Type=3
Dn Slope=0.005
Boundary for River Rch & Prof#=Stream0572,Reach-1,2
Up Type=0
Dn Type=3
Dn Slope=0.005
Boundary for River Rch & Prof#=Stream0572,Reach-1,3
Up Type=0
Dn Type=3
Dn Slope=0.005
Boundary for River Rch & Prof#=Stream0572,Reach-1,4
Up Type=0
Dn Type=3
Dn Slope=0.005
Boundary for River Rch & Prof#=Stream0572,Reach-1,5
Up Type=0
Dn Type=3
Dn Slope=0.005
Boundary for River Rch & Prof#=Stream0572,Reach-1,6
Up Type=0
Dn Type=3
Dn Slope=0.005
Boundary for River Rch & Prof#=Stream0572,Reach-1,7
Up Type=0
Dn Type=3
Dn Slope=0.005

--- Stream0572.g01 (geometry) ---

Geom Title=Existing Conditions

River Reach=Stream0572,Reach-1
Reach XY= 30
      1966275.00     13896875.00      1966334.79     13896864.49
      1966580.85     13896627.06      1967364.57     13896573.94
      1967471.60     13896482.84      1967573.35     13896521.83
      1967680.89     13896426.97      1967909.73     13896474.63
      1968080.93     13896377.25      1968219.06     13896372.73
      1968290.22     13896325.52      1968564.74     13896324.02
      1968614.68     13896285.18      1968674.48     13896059.78
      1968676.22     13895835.50      1968774.62     13895540.27
      1968727.27     13895469.06      1968717.19     13895318.79
      1968554.86     13895205.23      1968475.01     13895090.42
      1968772.94     13894669.15      1968775.54     13894340.21
      1968825.29     13894245.17      1968733.04     13894078.32
      1968775.38     13893904.86      1968725.82     13893814.29
      1968767.38     13893725.00      1968725.65     13893635.64
      1968969.64     13893277.49      1968975.00     13893175.00

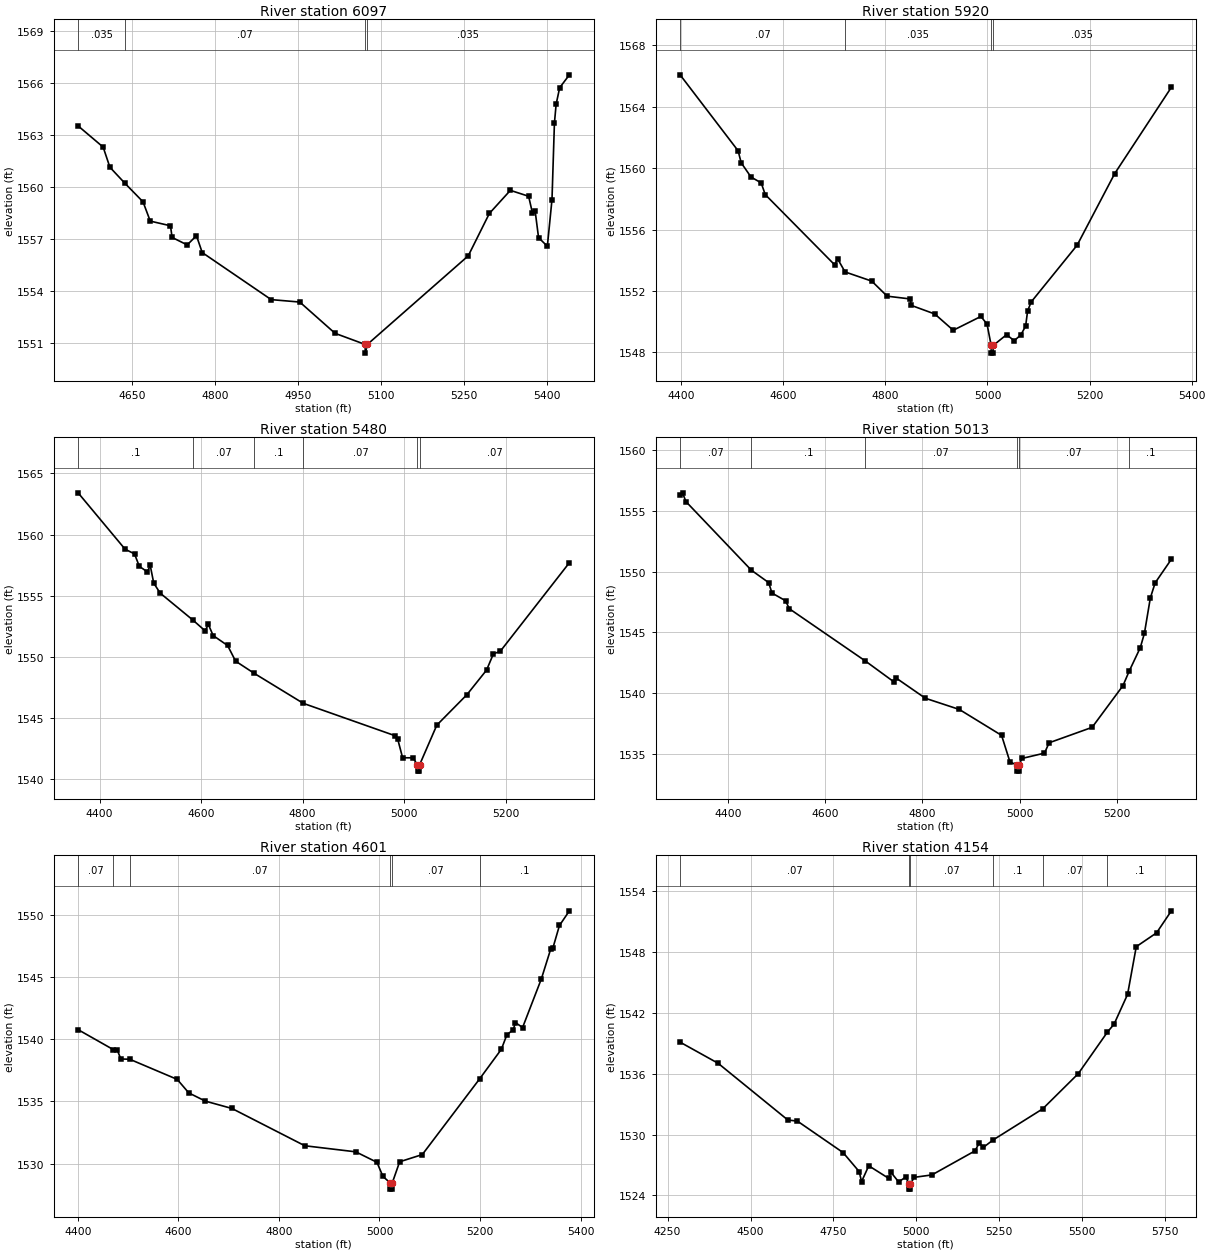
Type RM Length L Ch R = 1,6097,177,177,177
BEGIN DESCRIPTION:
Stream0572 12.0
END DESCRIPTION:
XS GIS Cut Line= 3
      1966472.37     13897242.38      1966394.25     13896764.99
      1966259.71     13896383.04
#Sta/Elev= 30
  4551.8 1563.52  4597.1 1562.30  4609.3 1561.14  4636.4 1560.22  4669.2 1559.15
  4682.3 1558.04  4718.9 1557.77  4721.8 1557.10  4749.1 1556.67  4765.9 1557.20
  4776.3 1556.23  4901.1 1553.52  4952.8 1553.38  5016.6 1551.58  5071.0 1550.94
  5071.3 1550.44  5075.0 1550.94  5257.5 1556.04  5295.7 1558.48  5333.7 1559.81
  5366.7 1559.47  5373.7 1558.50  5378.4 1558.65  5384.7 1557.09  5400.6 1556.59
  5409.0 1559.28  5413.4 1563.68  5416.5 1564.77  5422.9 1565.72  5440.5 1566.46
#Mann=4,-1,0
  4551.8   0.035       0  4636.4    0.07       0  5071.0    0.05       0
  5075.0   0.035       0
Bank Sta=5071,5075
Exp/Cntr=0.3,0.1

Type RM Length L Ch R = 1,5920,440,440,440
BEGIN DESCRIPTION:
Stream0572 11.0
END DESCRIPTION:
XS GIS Cut Line= 3
      1966575.00     13897274.96      1966525.00     13896675.00
      1966325.00     13896375.00
#Sta/Elev= 30
  4397.7 1566.08  4511.4 1561.13  4517.4 1560.35  4536.7 1559.42  4556.6 1559.04
  4564.5 1558.28  4700.6 1553.70  4706.2 1554.10  4720.9 1553.24  4773.3 1552.64
  4803.4 1551.66  4848.6 1551.48  4850.7 1551.06  4896.7 1550.50  4932.9 1549.44
  4987.1 1550.34  4999.1 1549.84  5007.2 1548.45  5007.4 1547.95  5010.9 1547.95
  5011.2 1548.45  5037.3 1549.15  5052.4 1548.76  5065.4 1549.14  5074.7 1549.71
  5078.6 1550.70  5085.5 1551.28  5175.6 1554.98  5249.3 1559.65  5360.3 1565.27
#Mann=4,-1,0
  4397.7    0.07       0  4720.9   0.035       0  5007.2   0.035       0
  5011.2   0.035       0
Bank Sta=5007.2,5011.2
Exp/Cntr=0.3,0.1

Type RM Length L Ch R = 1,5480,467,467,467
BEGIN DESCRIPTION:
Stream0572 10.0
END DESCRIPTION:
XS GIS Cut Line= 3
      1966724.99     13897225.04      1966925.00     13896625.00
      1966775.00     13896325.01
#Sta/Elev= 30
  4357.7 1563.42  4450.3 1558.81  4468.8 1558.43  4478.3 1557.41  4494.1 1556.96
  4499.8 1557.48  4506.7 1556.04  4519.4 1555.22  4583.8 1553.02  4607.9 1552.14
  4614.3 1552.66  4623.8 1551.75  4652.2 1550.94  4668.0 1549.66  4704.4 1548.67
  4801.4 1546.21  4981.1 1543.58  4987.4 1543.28  4997.0 1541.76  5017.4 1541.76
  5026.3 1541.17  5026.5 1540.67  5030.0 1540.67  5030.3 1541.17  5064.4 1544.43
  5123.7 1546.92  5162.4 1548.93  5175.9 1550.26  5189.3 1550.46  5325.6 1557.71
#Mann=6,-1,0
  4357.7     0.1       0  4583.8    0.07       0  4704.4     0.1       0
  4801.4    0.07       0  5026.3    0.05       0  5030.3    0.07       0
Bank Sta=5026.3,5030.3
Exp/Cntr=0.3,0.1

Type RM Length L Ch R = 1,5013,412,412,412
BEGIN DESCRIPTION:
Stream0572 9.0
END DESCRIPTION:
XS GIS Cut Line= 3
      1967025.00     13897175.00      1967375.00     13896575.00
      1967274.98     13896274.95
#Sta/Elev= 30
  4301.5 1556.27  4306.5 1556.47  4313.5 1555.75  4448.1 1550.11  4483.7 1549.09
  4490.6 1548.23  4518.4 1547.60  4526.3 1546.94  4682.5 1542.65  4740.7 1540.95
  4745.1 1541.27  4806.2 1539.58  4876.1 1538.66  4963.0 1536.53  4980.3 1534.34
  4995.0 1534.09  4995.2 1533.59  4998.7 1533.59  4999.0 1534.09  5004.7 1534.63
  5051.3 1535.07  5060.8 1535.92  5149.3 1537.19  5212.8 1540.62  5225.8 1541.83
  5248.4 1543.74  5256.9 1544.92  5269.1 1547.83  5279.0 1549.07  5312.4 1551.01
#Mann=6,-1,0
  4301.5    0.07       0  4448.1     0.1       0  4682.5    0.07       0
  4995.0    0.05       0  4999.0    0.07       0  5225.8     0.1       0
Bank Sta=4995,4999
Exp/Cntr=0.3,0.1

Type RM Length L Ch R = 1,4601,447,447,447
BEGIN DESCRIPTION:
Stream0572 8.0
END DESCRIPTION:
XS GIS Cut Line= 4
      1967475.01     13896974.99      1967700.16     13896479.65
      1967698.37     13896402.81      1967425.01     13896175.01
#Sta/Elev= 30
  4400.8 1540.77  4471.0 1539.16  4478.8 1539.11  4485.8 1538.41  4503.4 1538.39
  4597.8 1536.77  4620.9 1535.68  4653.8 1535.02  4706.6 1534.43  4851.5 1531.43
  4952.9 1530.94  4994.9 1530.10  5006.9 1528.96  5021.4 1528.44  5021.6 1527.94
  5025.1 1527.94  5025.4 1528.44  5040.1 1530.14  5085.1 1530.72  5198.9 1536.80
  5242.3 1539.19  5253.4 1540.37  5265.7 1540.75  5270.4 1541.34  5284.5 1540.94
  5321.9 1544.86  5340.7 1547.29  5345.0 1547.37  5357.8 1549.15  5377.6 1550.33
#Mann=6,-1,0
  4400.8    0.07       0  4471.0     0.1       0  4503.4    0.07       0
  5021.4    0.05       0  5025.4    0.07       0  5198.9     0.1       0
Bank Sta=5021.4,5025.4
Exp/Cntr=0.3,0.1

Type RM Length L Ch R = 1,4154,490,490,490
BEGIN DESCRIPTION:
Stream0572 7.0
END DESCRIPTION:
XS GIS Cut Line= 4
      1967725.03     13896974.96      1968095.88     13896418.67
      1968099.36     13896353.63      1967524.96     13895874.97
#Sta/Elev= 30
  4287.6 1539.10  4402.2 1537.02  4612.5 1531.43  4641.4 1531.32  4779.1 1528.22
  4827.6 1526.35  4834.8 1525.36  4856.5 1526.92  4917.2 1525.67  4922.6 1526.31
  4946.6 1525.33  4968.0 1525.81  4978.1 1525.12  4978.4 1524.62  4981.9 1524.62
  4982.1 1525.12  4993.3 1525.78  5046.9 1526.02  5176.9 1528.39  5189.6 1529.17
  5202.3 1528.74  5231.2 1529.46  5381.0 1532.53  5488.3 1536.00  5576.3 1540.10
  5596.1 1540.87  5636.9 1543.81  5663.1 1548.51  5724.3 1549.87  5769.0 1552.04
#Mann=6,-1,0
  4287.6    0.07       0  4978.1    0.05       0  4982.1    0.07       0
  5231.2     0.1       0  5381.0    0.07       0  5576.3     0.1       0
Bank Sta=4978.1,4982.1
Exp/Cntr=0.3,0.1

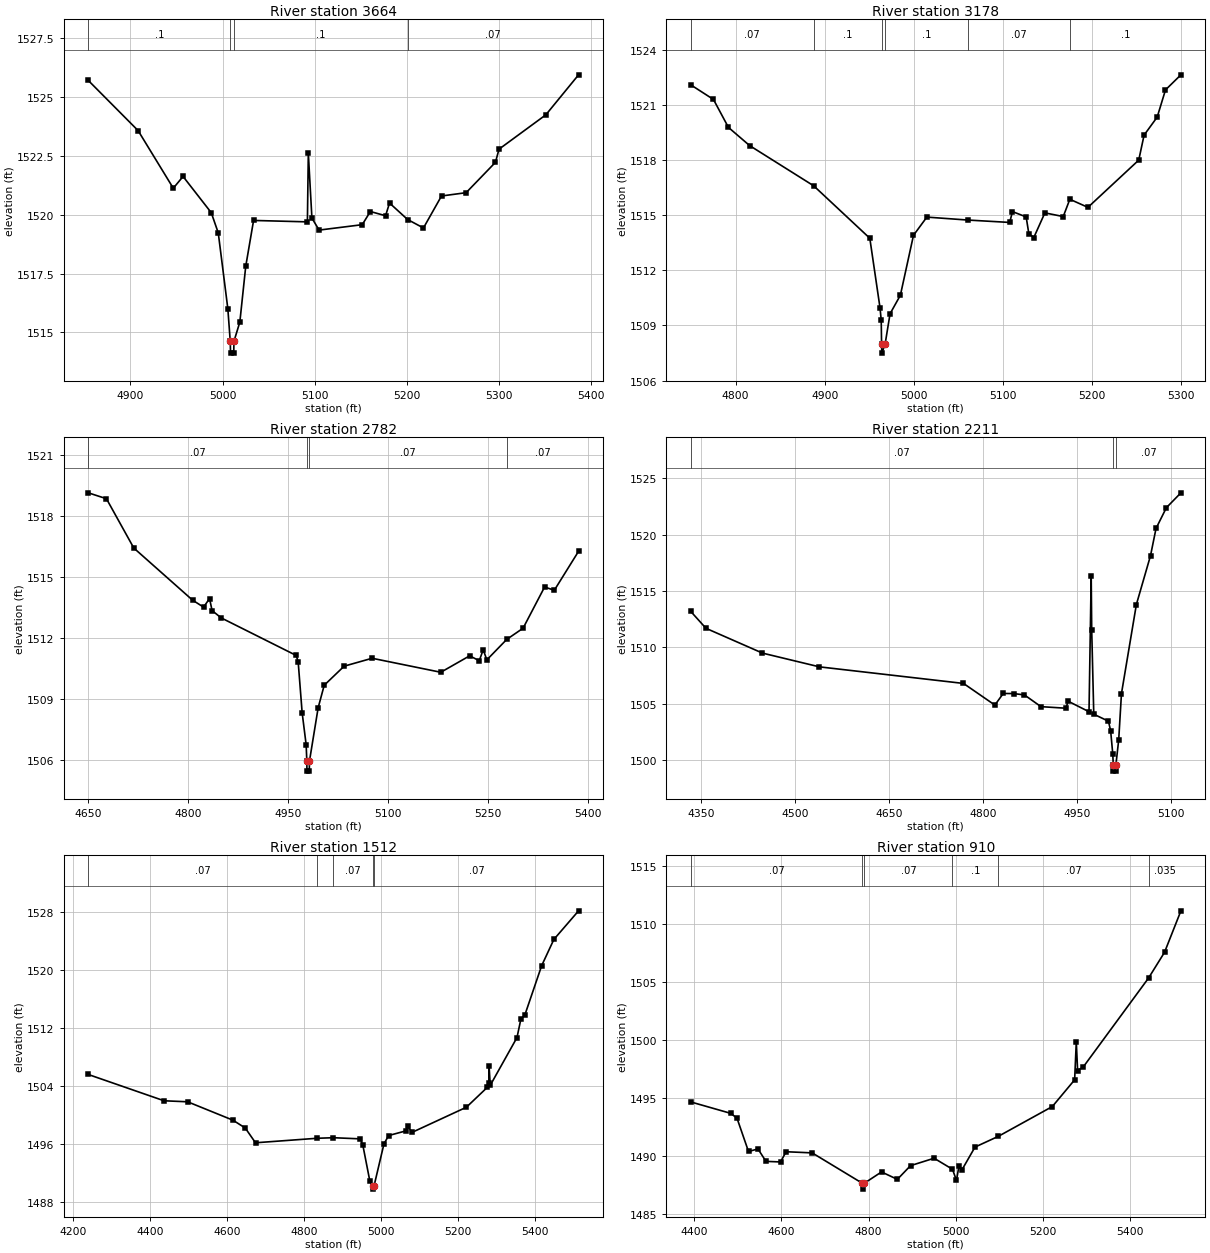
Type RM Length L Ch R = 1,3664,486,486,486
BEGIN DESCRIPTION:
Stream0572 6.0
END DESCRIPTION:
XS GIS Cut Line= 3
      1968674.99     13896424.99      1968575.00     13896325.00
      1968275.02     13896075.01
#Sta/Elev= 30
  4854.3 1525.71  4908.3 1523.58  4946.5 1521.13  4957.1 1521.63  4987.7 1520.09
  4995.3 1519.23  5005.7 1516.00  5008.3 1514.62  5008.6 1514.12  5012.1 1514.12
  5012.3 1514.62  5018.7 1515.44  5025.1 1517.81  5033.6 1519.76  5092.0 1519.70
  5093.0 1522.62  5096.9 1519.86  5104.7 1519.35  5151.5 1519.58  5160.3 1520.14
  5176.8 1519.96  5181.1 1520.50  5200.7 1519.80  5217.9 1519.44  5237.5 1520.80
  5264.2 1520.94  5296.0 1522.23  5299.9 1522.79  5350.7 1524.25  5386.2 1525.95
#Mann=4,-1,0
  4854.3     0.1       0  5008.3    0.05       0  5012.3     0.1       0
  5200.7    0.07       0
Bank Sta=5008.3,5012.3
Exp/Cntr=0.3,0.1

Type RM Length L Ch R = 1,3178,396,396,396
BEGIN DESCRIPTION:
Stream0572 5.0
END DESCRIPTION:
XS GIS Cut Line= 3
      1968875.00     13896025.00      1968675.00     13895875.00
      1968375.00     13895875.00
#Sta/Elev= 30
  4749.6 1522.09  4775.2 1521.29  4792.0 1519.77  4815.8 1518.78  4887.7 1516.59
  4950.6 1513.74  4962.1 1509.94  4963.4 1509.28  4963.8 1507.99  4964.1 1507.49
  4967.8 1507.99  4973.3 1509.63  4984.9 1510.64  4999.6 1513.90  5014.6 1514.89
  5060.4 1514.73  5107.6 1514.60  5110.6 1515.19  5126.0 1514.90  5129.0 1513.99
  5134.6 1513.78  5147.0 1515.12  5167.6 1514.92  5175.0 1515.86  5195.3 1515.42
  5252.3 1517.99  5258.3 1519.35  5273.0 1520.33  5282.3 1521.81  5299.6 1522.63
#Mann=6,-1,0
  4749.6    0.07       0  4887.7     0.1       0  4963.8    0.05       0
  4967.8     0.1       0  5060.4    0.07       0  5175.0     0.1       0
Bank Sta=4963.8,4967.8
Exp/Cntr=0.3,0.1

Type RM Length L Ch R = 1,2782,571,571,571
BEGIN DESCRIPTION:
Stream0572 4.0
END DESCRIPTION:
XS GIS Cut Line= 4
      1969025.02     13895725.02      1968814.65     13895513.50
      1968662.04     13895516.97      1968424.97     13895675.02
#Sta/Elev= 30
  4650.6 1519.15  4677.8 1518.86  4718.9 1516.43  4807.2 1513.86  4823.6 1513.52
  4832.6 1513.94  4836.4 1513.35  4850.0 1512.99  4962.6 1511.14  4965.6 1510.83
  4971.6 1508.31  4977.6 1506.74  4978.6 1505.94  4978.8 1505.44  4982.3 1505.44
  4982.6 1505.94  4995.6 1508.56  5004.7 1509.67  5034.6 1510.61  5076.6 1511.00
  5179.7 1510.31  5223.0 1511.12  5237.4 1510.88  5243.4 1511.42  5248.8 1510.92
  5278.7 1511.93  5303.2 1512.48  5335.5 1514.51  5350.1 1514.35  5386.5 1516.27
#Mann=4,-1,0
  4650.6    0.07       0  4978.6   0.035       0  4982.6    0.07       0
  5278.7    0.07       0
Bank Sta=4978.6,4982.6
Exp/Cntr=0.3,0.1

Type RM Length L Ch R = 1,2211,699,699,699
BEGIN DESCRIPTION:
Stream0572 3.0
END DESCRIPTION:
XS GIS Cut Line= 3
      1969074.98     13895374.99      1968476.76     13895081.13
      1968375.01     13895025.00
#Sta/Elev= 30
  4333.5 1513.19  4358.0 1511.68  4448.2 1509.48  4539.2 1508.26  4769.1 1506.79
  4819.2 1504.87  4832.6 1505.90  4849.3 1505.89  4866.4 1505.77  4892.8 1504.73
  4932.9 1504.59  4935.9 1505.22  4969.5 1504.28  4973.0 1516.33  4973.8 1511.54
  4977.1 1504.06  5000.5 1503.44  5004.0 1502.60  5007.4 1500.55  5008.3 1499.51
  5008.5 1499.01  5012.0 1499.01  5012.3 1499.51  5016.9 1501.78  5021.3 1505.89
  5045.1 1513.79  5067.7 1518.13  5076.5 1520.54  5093.0 1522.38  5116.2 1523.70
#Mann=3,-1,0
  4333.5    0.07       0  5008.3    0.05       0  5012.3    0.07       0
Bank Sta=5008.3,5012.3
Exp/Cntr=0.3,0.1

Type RM Length L Ch R = 1,1512,602,602,602
BEGIN DESCRIPTION:
Stream0572 2.0
END DESCRIPTION:
XS GIS Cut Line= 3
      1969218.58     13895027.25      1968982.57     13894532.06
      1968272.37     13894394.31
#Sta/Elev= 30
  4240.0 1505.60  4436.6 1501.97  4497.7 1501.83  4615.3 1499.29  4647.2 1498.21
  4673.8 1496.17  4832.7 1496.79  4875.9 1496.87  4946.0 1496.71  4952.4 1495.81
  4970.4 1490.90  4977.6 1490.27  4977.9 1489.77  4981.6 1490.27  5007.1 1496.02
  5019.3 1497.17  5065.2 1497.83  5068.2 1498.46  5080.5 1497.62  5221.0 1501.08
  5274.9 1503.81  5279.1 1504.44  5279.8 1506.75  5282.9 1504.11  5352.2 1510.70
  5362.3 1513.24  5372.7 1513.83  5416.2 1520.62  5447.9 1524.25  5512.0 1528.20
#Mann=5,-1,0
  4240.0    0.07       0  4832.7     0.1       0  4875.9    0.07       0
  4977.6    0.05       0  4981.6    0.07       0
Bank Sta=4977.6,4981.6
Exp/Cntr=0.3,0.1

Type RM Length L Ch R = 1,910,492,492,492
BEGIN DESCRIPTION:
Stream0572 1.0
END DESCRIPTION:
XS GIS Cut Line= 3
      1969191.68     13894303.31      1968937.72     13893938.05
      1968261.28     13893991.18
#Sta/Elev= 30
  4392.3 1494.68  4484.5 1493.69  4498.6 1493.27  4524.9 1490.41  4546.6 1490.63
  4564.9 1489.56  4598.4 1489.51  4611.0 1490.39  4670.8 1490.29  4786.0 1487.67
  4786.3 1487.17  4790.0 1487.67  4829.7 1488.65  4866.0 1488.01  4896.1 1489.19
  4950.2 1489.83  4992.3 1488.88  5001.4 1487.92  5007.1 1489.14  5013.4 1488.79
  5043.9 1490.79  5097.1 1491.71  5221.1 1494.28  5272.2 1496.58  5276.0 1499.85
  5279.0 1497.38  5292.0 1497.69  5441.5 1505.34  5478.2 1507.56  5515.7 1511.13
#Mann=6,-1,0
  4392.3    0.07       0  4786.0    0.05       0  4790.0    0.07       0
  4992.3     0.1       0  5097.1    0.07       0  5441.5   0.035       0
Bank Sta=4786,4790
Exp/Cntr=0.3,0.1

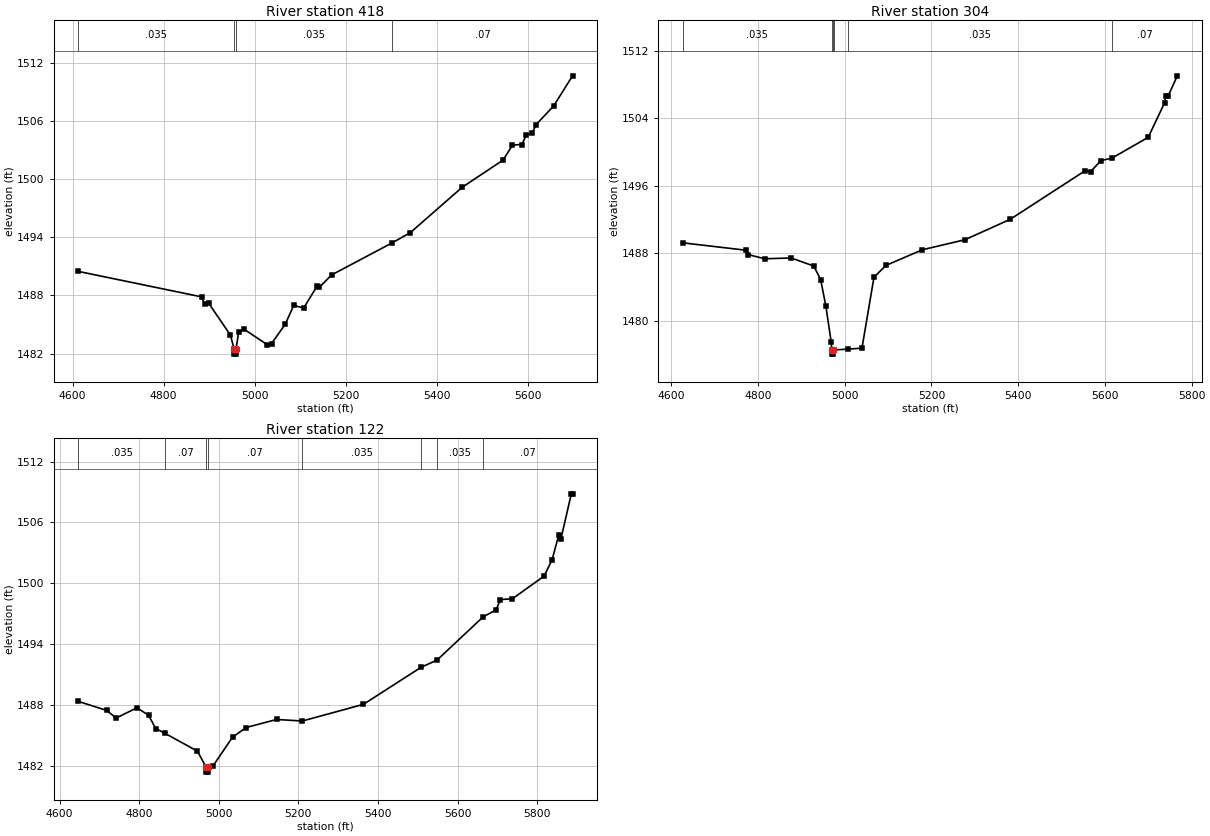
Type RM Length L Ch R = 1,418,114,114,114
BEGIN DESCRIPTION:
Stream0572 D1
END DESCRIPTION:
XS GIS Cut Line= 4
      1969098.18     13893763.20      1968914.59     13893545.75
      1968723.18     13893530.13      1968125.49     13893647.32
#Sta/Elev= 30
  4612.5 1490.48  4883.6 1487.85  4890.1 1487.08  4899.4 1487.17  4946.8 1483.91
  4954.9 1482.45  4955.1 1481.95  4958.6 1481.95  4958.9 1482.45  4964.8 1484.19
  4976.9 1484.51  5027.1 1482.94  5037.1 1483.04  5067.2 1485.04  5085.7 1486.97
  5107.7 1486.71  5136.8 1488.94  5141.9 1488.82  5168.8 1490.11  5302.3 1493.43
  5342.0 1494.48  5455.8 1499.15  5545.8 1501.96  5566.2 1503.50  5586.6 1503.56
  5596.8 1504.53  5610.1 1504.73  5617.2 1505.57  5656.5 1507.52  5698.2 1510.64
#Mann=4,-1,0
  4612.5   0.035       0  4954.9   0.035       0  4958.9   0.035       0
  5302.3    0.07       0
Bank Sta=4954.9,4958.9
Exp/Cntr=0.3,0.1

Type RM Length L Ch R = 1,304,182,182,182
BEGIN DESCRIPTION:
Stream0572 0.0
END DESCRIPTION:
XS GIS Cut Line= 4
      1969128.63     13893677.02      1968946.34     13893458.27
      1968592.17     13893374.94      1968107.80     13893454.80
#Sta/Elev= 30
  4627.5 1489.22  4773.7 1488.34  4778.0 1487.83  4815.9 1487.33  4876.8 1487.43
  4929.0 1486.47  4944.7 1484.87  4956.8 1481.71  4969.1 1477.44  4970.1 1476.53
  4970.4 1476.03  4973.9 1476.03  4974.1 1476.53  4976.1 1476.53  5007.1 1476.62
  5040.0 1476.74  5067.7 1485.15  5095.4 1486.55  5179.2 1488.40  5277.3 1489.59
  5381.4 1492.00  5554.7 1497.78  5566.9 1497.66  5591.2 1498.98  5615.7 1499.25
  5699.9 1501.73  5737.7 1505.83  5740.3 1506.63  5746.2 1506.67  5767.0 1509.02
#Mann=6,-1,0
  4627.5   0.035       0  4970.1    0.05       0  4974.1   0.035       0
  4976.1    0.07       0  5007.1   0.035       0  5615.7    0.07       0
Bank Sta=4970.1,4974.1
Exp/Cntr=0.3,0.1

Type RM Length L Ch R = 1,122,0,0,0
BEGIN DESCRIPTION:
Stream0572 D2
END DESCRIPTION:
XS GIS Cut Line= 4
      1969098.18     13893616.05      1968951.05     13893274.92
      1968767.45     13893256.69      1968083.85     13893312.68
#Sta/Elev= 30
  4647.0 1488.40  4718.5 1487.51  4742.1 1486.76  4794.5 1487.77  4823.5 1487.04
  4841.6 1485.73  4865.1 1485.25  4946.5 1483.50  4968.0 1481.94  4968.3 1481.44
  4971.8 1481.44  4972.0 1481.94  4985.8 1482.06  5034.6 1484.88  5069.0 1485.83
  5145.2 1486.62  5210.1 1486.47  5363.5 1488.11  5508.2 1491.75  5548.7 1492.47
  5664.1 1496.71  5697.1 1497.41  5707.1 1498.41  5737.9 1498.50  5817.5 1500.73
  5837.6 1502.35  5854.4 1504.79  5859.4 1504.34  5885.8 1508.82  5888.9 1508.82
#Mann=8,-1,0
  4647.0   0.035       0  4865.1    0.07       0  4968.0    0.05       0
  4972.0    0.07       0  5210.1   0.035       0  5508.2    0.07       0
  5548.7   0.035       0  5664.1    0.07       0
Bank Sta=4968,4972
Exp/Cntr=0.3,0.1

Chan Stop Cuts=-1