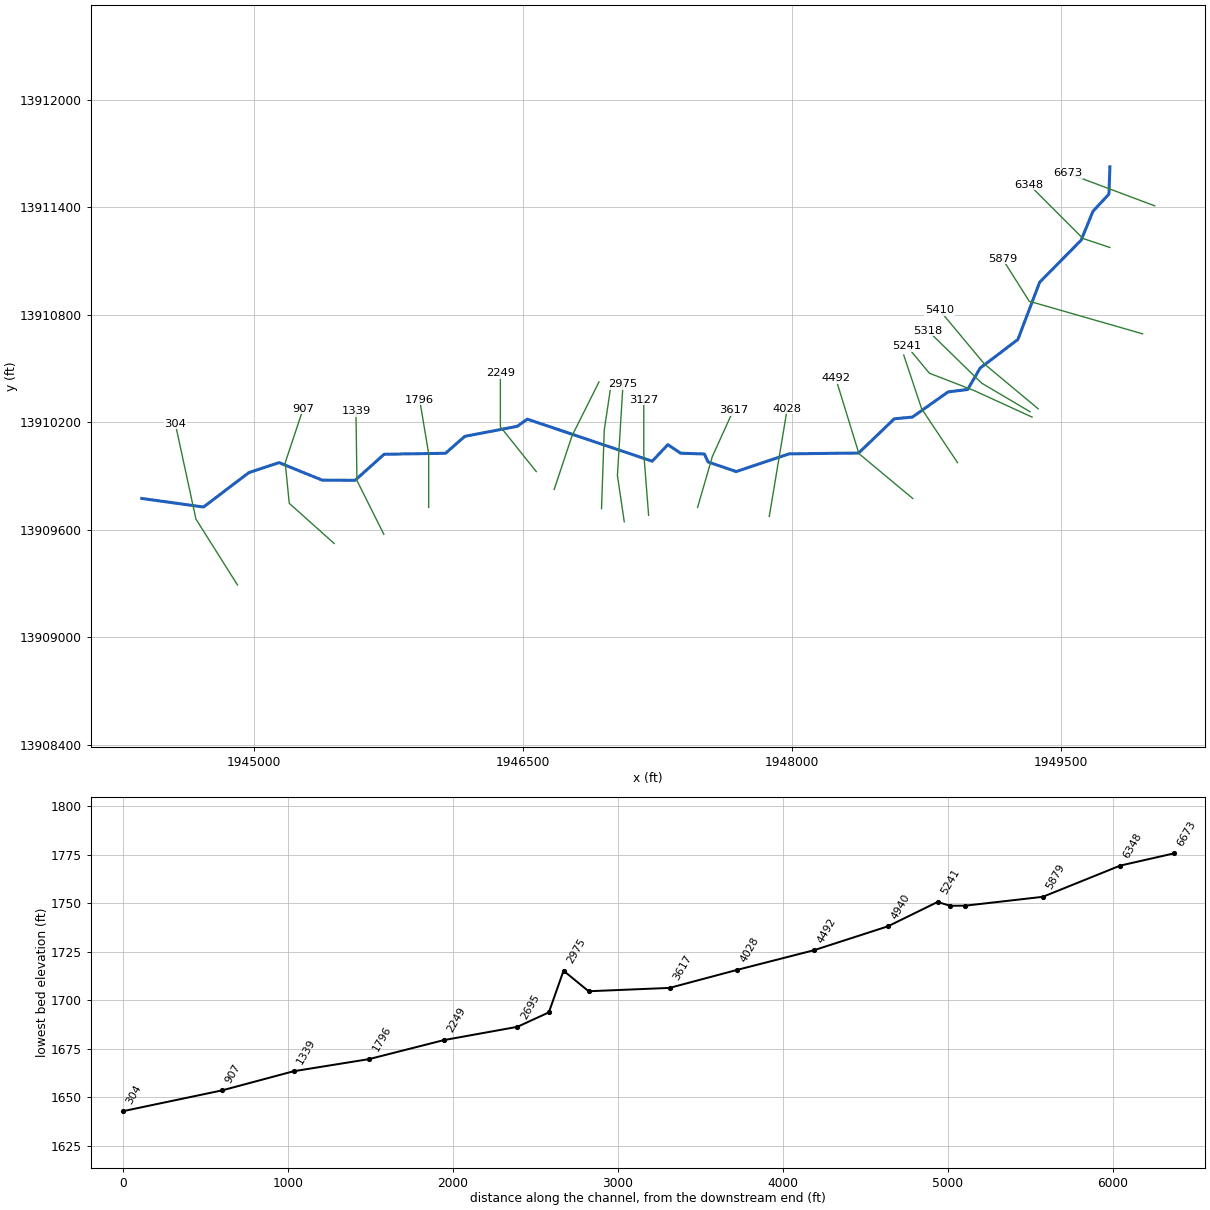
--- Stream0573.prj (project) ---

Proj Title=Stream0573 Base Level Engineering
Current Plan=p01
Default Exp/Contr=0.3,0.1
English Units
Geom File=g01
Flow File=f01
Plan File=p01
BEGIN DESCRIPTION:
Stream0573
END DESCRIPTION:

--- Stream0573.p01 (plan) ---

Plan Title=Multiple Run
Short Identifier=Multiple
Geom File=g01
Flow File=f01
Subcritical Flow
K Sum by GR= 0
Std Step Tol= 0.01
Critical Tol= 0.01
Num of Std Step Trials= 20
Max Error Tol= 0.3
Flow Tol Ratio= 0.001
Split Flow NTrial= 30
Split Flow Tol= 0.02
Split Flow Ratio= 0.02
Log Output Level= 0
Friction Slope Method= 1
Unsteady Friction Slope Method= 2
Unsteady Bridges Friction Slope Method= 1
Parabolic Critical Depth
Global Vel Dist=  1 , 1 , 1
Global Log Level= 0
CheckData=True
Encroach Param= -1, 0, 0, 0
BEGIN DESCRIPTION:
Multiple Run
END DESCRIPTION:

--- Stream0573.f01 (steady flow) ---

Flow Title=Multiple
Number of Profiles=7
Profile Names=10-year,25-year,50-year,1pct_min,100-year,1pct_plu,500-year
River Rch & RM= Stream0573,Reach-1,6673
    1190    2035    2844    1923    3837    7655    6892
Boundary for River Rch & Prof#=Stream0573,Reach-1,1
Up Type=0
Dn Type=3
Dn Slope=0.005
Boundary for River Rch & Prof#=Stream0573,Reach-1,2
Up Type=0
Dn Type=3
Dn Slope=0.005
Boundary for River Rch & Prof#=Stream0573,Reach-1,3
Up Type=0
Dn Type=3
Dn Slope=0.005
Boundary for River Rch & Prof#=Stream0573,Reach-1,4
Up Type=0
Dn Type=3
Dn Slope=0.005
Boundary for River Rch & Prof#=Stream0573,Reach-1,5
Up Type=0
Dn Type=3
Dn Slope=0.005
Boundary for River Rch & Prof#=Stream0573,Reach-1,6
Up Type=0
Dn Type=3
Dn Slope=0.005
Boundary for River Rch & Prof#=Stream0573,Reach-1,7
Up Type=0
Dn Type=3
Dn Slope=0.005

--- Stream0573.g01 (geometry) ---

Geom Title=Existing Conditions

River Reach=Stream0573,Reach-1
Reach XY= 30
      1949775.00     13911625.00      1949769.56     13911472.54
      1949680.85     13911377.29      1949614.24     13911215.32
      1949383.14     13910981.06      1949261.60     13910661.69
      1949051.17     13910502.13      1948981.45     13910382.75
      1948872.58     13910369.46      1948673.41     13910228.83
      1948572.57     13910219.48      1948373.54     13910028.54
      1947985.50     13910023.78      1947690.39     13909925.09
      1947533.50     13909978.56      1947513.03     13910023.02
      1947380.92     13910027.31      1947309.23     13910075.10
      1947221.96     13909982.82      1946525.00     13910217.44
      1946469.14     13910177.47      1946176.50     13910121.38
      1946069.14     13910027.07      1945726.46     13910021.46
      1945564.57     13909876.05      1945380.94     13909877.26
      1945140.39     13909974.91      1944972.57     13909919.48
      1944719.07     13909727.23      1944375.00     13909775.00

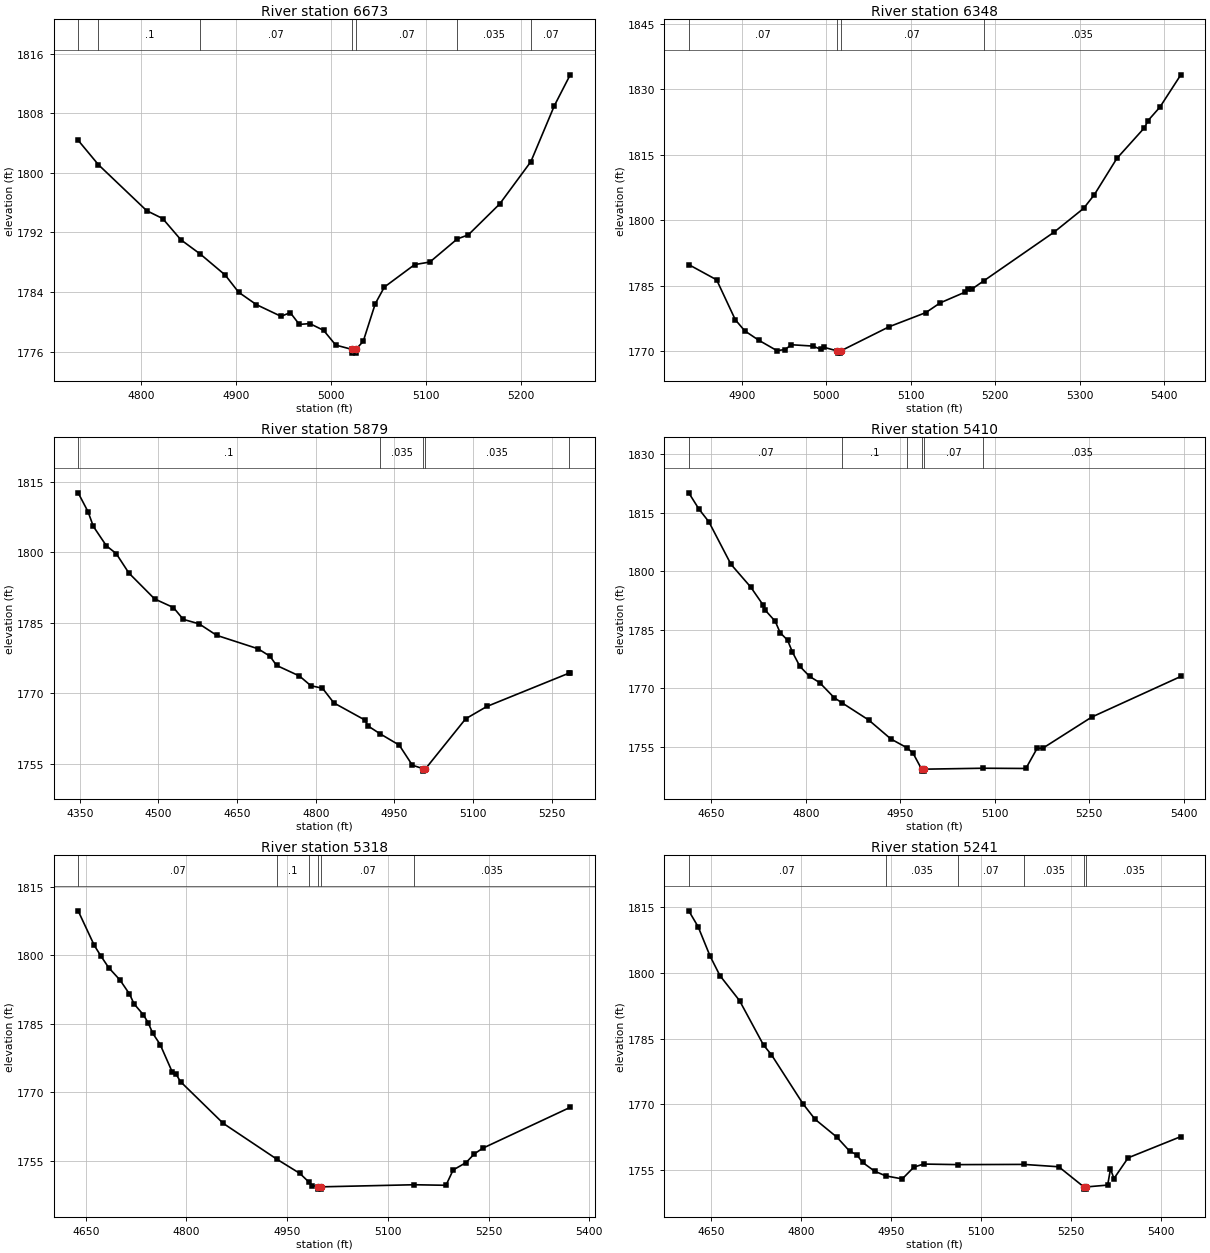
Type RM Length L Ch R = 1,6673,325,325,325
BEGIN DESCRIPTION:
Stream0573 14.0
END DESCRIPTION:
XS GIS Cut Line= 2
      1950025.21     13911407.08      1949539.07     13911589.38
#Sta/Elev= 30
  4733.2 1804.37  4754.6 1801.09  4805.5 1794.92  4822.4 1793.86  4841.6 1791.01
  4862.3 1789.07  4888.4 1786.27  4902.5 1783.97  4921.2 1782.31  4947.3 1780.73
  4957.0 1781.23  4966.6 1779.64  4977.6 1779.76  4992.2 1778.85  5005.0 1776.87
  5022.2 1776.29  5022.5 1775.79  5026.0 1775.79  5026.2 1776.29  5034.0 1777.37
  5046.7 1782.42  5056.3 1784.66  5088.3 1787.68  5104.3 1788.02  5133.3 1791.13
  5144.8 1791.66  5178.0 1795.82  5210.9 1801.50  5235.7 1809.02  5252.4 1813.16
#Mann=7,-1,0
  4733.2    0.07       0  4754.6     0.1       0  4862.3    0.07       0
  5022.2    0.05       0  5026.2    0.07       0  5133.3   0.035       0
  5210.9    0.07       0
Bank Sta=5022.2,5026.2
Exp/Cntr=0.3,0.1

Type RM Length L Ch R = 1,6348,469,469,469
BEGIN DESCRIPTION:
Stream0573 13.0
END DESCRIPTION:
XS GIS Cut Line= 3
      1949775.01     13911175.00      1949625.00     13911225.00
      1949324.99     13911525.01
#Sta/Elev= 30
  4837.1 1789.79  4870.1 1786.30  4892.2 1777.15  4903.4 1774.60  4920.0 1772.45
  4941.4 1770.08  4950.9 1770.31  4958.7 1771.42  4983.7 1771.12  4993.4 1770.39
  4997.1 1770.84  5012.9 1770.00  5013.2 1769.50  5016.7 1769.50  5016.9 1770.00
  5074.3 1775.55  5117.7 1778.79  5134.7 1781.02  5164.4 1783.50  5167.7 1784.31
  5172.8 1784.26  5186.0 1786.03  5269.5 1797.23  5304.4 1802.67  5317.1 1805.80
  5343.8 1814.13  5376.5 1821.17  5380.7 1822.80  5394.7 1825.87  5419.5 1833.29
#Mann=4,-1,0
  4837.1    0.07       0  5012.9    0.05       0  5016.9    0.07       0
  5186.0   0.035       0
Bank Sta=5012.9,5016.9
Exp/Cntr=0.3,0.1

Type RM Length L Ch R = 1,5879,469,469,469
BEGIN DESCRIPTION:
Stream0573 12.0
END DESCRIPTION:
XS GIS Cut Line= 3
      1949957.28     13910693.33      1949325.00     13910875.00
      1949175.05     13911112.57
#Sta/Elev= 30
  4346.7 1812.72  4365.7 1808.67  4375.6 1805.58  4400.6 1801.42  4419.3 1799.77
  4443.5 1795.62  4492.6 1790.10  4528.5 1788.26  4547.3 1785.74  4577.5 1784.79
  4611.0 1782.34  4689.8 1779.48  4712.7 1777.89  4725.2 1775.93  4768.9 1773.67
  4790.7 1771.60  4812.9 1771.06  4834.6 1767.93  4893.7 1764.29  4899.8 1763.02
  4922.6 1761.36  4959.3 1758.94  4984.3 1754.66  5005.4 1753.89  5005.6 1753.39
  5009.4 1753.89  5086.0 1764.54  5126.4 1767.17  5282.6 1774.25  5285.5 1774.32
#Mann=5,-1,0
  4346.7     0.1       0  4922.6   0.035       0  5005.4   0.035       0
  5009.4   0.035       0  5282.6    0.07       0
Bank Sta=5005.4,5009.4
Exp/Cntr=0.3,0.1

Type RM Length L Ch R = 1,5410,92,92,92
BEGIN DESCRIPTION:
Stream0573 11.0
END DESCRIPTION:
XS GIS Cut Line= 3
      1949374.99     13910275.01      1949075.00     13910525.00
      1948825.01     13910824.99
#Sta/Elev= 30
  4614.4 1820.05  4630.6 1815.88  4646.3 1812.64  4681.4 1801.76  4712.7 1795.94
  4732.2 1791.40  4736.1 1789.96  4751.7 1787.16  4759.5 1784.24  4771.2 1782.35
  4779.0 1779.27  4790.8 1775.63  4806.4 1773.05  4822.0 1771.50  4845.4 1767.60
  4858.2 1766.25  4900.1 1761.90  4935.2 1757.06  4960.9 1754.79  4970.4 1753.42
  4984.0 1749.33  4984.3 1748.83  4987.8 1748.83  4988.0 1749.33  5081.2 1749.57
  5149.5 1749.51  5167.2 1754.63  5176.8 1754.74  5254.0 1762.66  5395.4 1773.06
#Mann=6,-1,0
  4614.4    0.07       0  4858.2     0.1       0  4960.9    0.07       0
  4984.0    0.05       0  4988.0    0.07       0  5081.2   0.035       0
Bank Sta=4984,4988
Exp/Cntr=0.3,0.1

Type RM Length L Ch R = 1,5318,77,77,77
BEGIN DESCRIPTION:
Mapping XS ad5fbbbd
END DESCRIPTION:
XS GIS Cut Line= 3
      1949329.26     13910258.97      1949059.78     13910418.03
      1948759.31     13910711.31
#Sta/Elev= 30
  4638.7 1809.71  4662.8 1802.12  4672.3 1799.88  4684.1 1797.28  4701.1 1794.54
  4715.1 1791.51  4722.0 1789.33  4736.0 1786.91  4742.9 1785.21  4749.9 1782.87
  4760.9 1780.42  4778.6 1774.49  4784.5 1773.94  4791.2 1772.29  4854.7 1763.17
  4934.9 1755.29  4968.8 1752.21  4982.2 1750.33  4987.2 1749.54  4996.1 1749.26
  4996.4 1748.76  4999.9 1748.76  5000.1 1749.26  5139.3 1749.72  5186.5 1749.60
  5197.2 1752.96  5216.5 1754.58  5228.7 1756.48  5241.3 1757.72  5371.5 1766.67
#Mann=6,-1,0
  4638.7    0.07       0  4934.9     0.1       0  4982.2    0.07       0
  4996.1    0.05       0  5000.1    0.07       0  5139.3   0.035       0
Bank Sta=4996.1,5000.1
Exp/Cntr=0.3,0.1

Type RM Length L Ch R = 1,5241,301,301,301
BEGIN DESCRIPTION:
Stream0573 10.1
END DESCRIPTION:
XS GIS Cut Line= 4
      1949340.73     13910228.88      1949016.55     13910377.29
      1948767.85     13910473.65      1948642.86     13910624.69
#Sta/Elev= 30
  4613.4 1814.10  4629.0 1810.48  4648.8 1803.82  4665.3 1799.35  4697.9 1793.66
  4737.9 1783.53  4751.1 1781.32  4803.9 1770.09  4823.7 1766.63  4860.0 1762.56
  4881.2 1759.38  4893.0 1758.57  4902.9 1756.80  4922.7 1754.82  4941.5 1753.73
  4968.9 1753.05  4988.2 1755.72  5004.3 1756.43  5061.8 1756.30  5171.2 1756.35
  5229.5 1755.81  5271.3 1751.22  5271.5 1750.72  5275.0 1750.72  5275.3 1751.22
  5310.9 1751.64  5315.6 1755.30  5321.4 1753.14  5345.0 1757.85  5432.7 1762.68
#Mann=6,-1,0
  4613.4    0.07       0  4941.5   0.035       0  5061.8    0.07       0
  5171.2   0.035       0  5271.3   0.035       0  5275.3   0.035       0
Bank Sta=5271.3,5275.3
Exp/Cntr=0.3,0.1

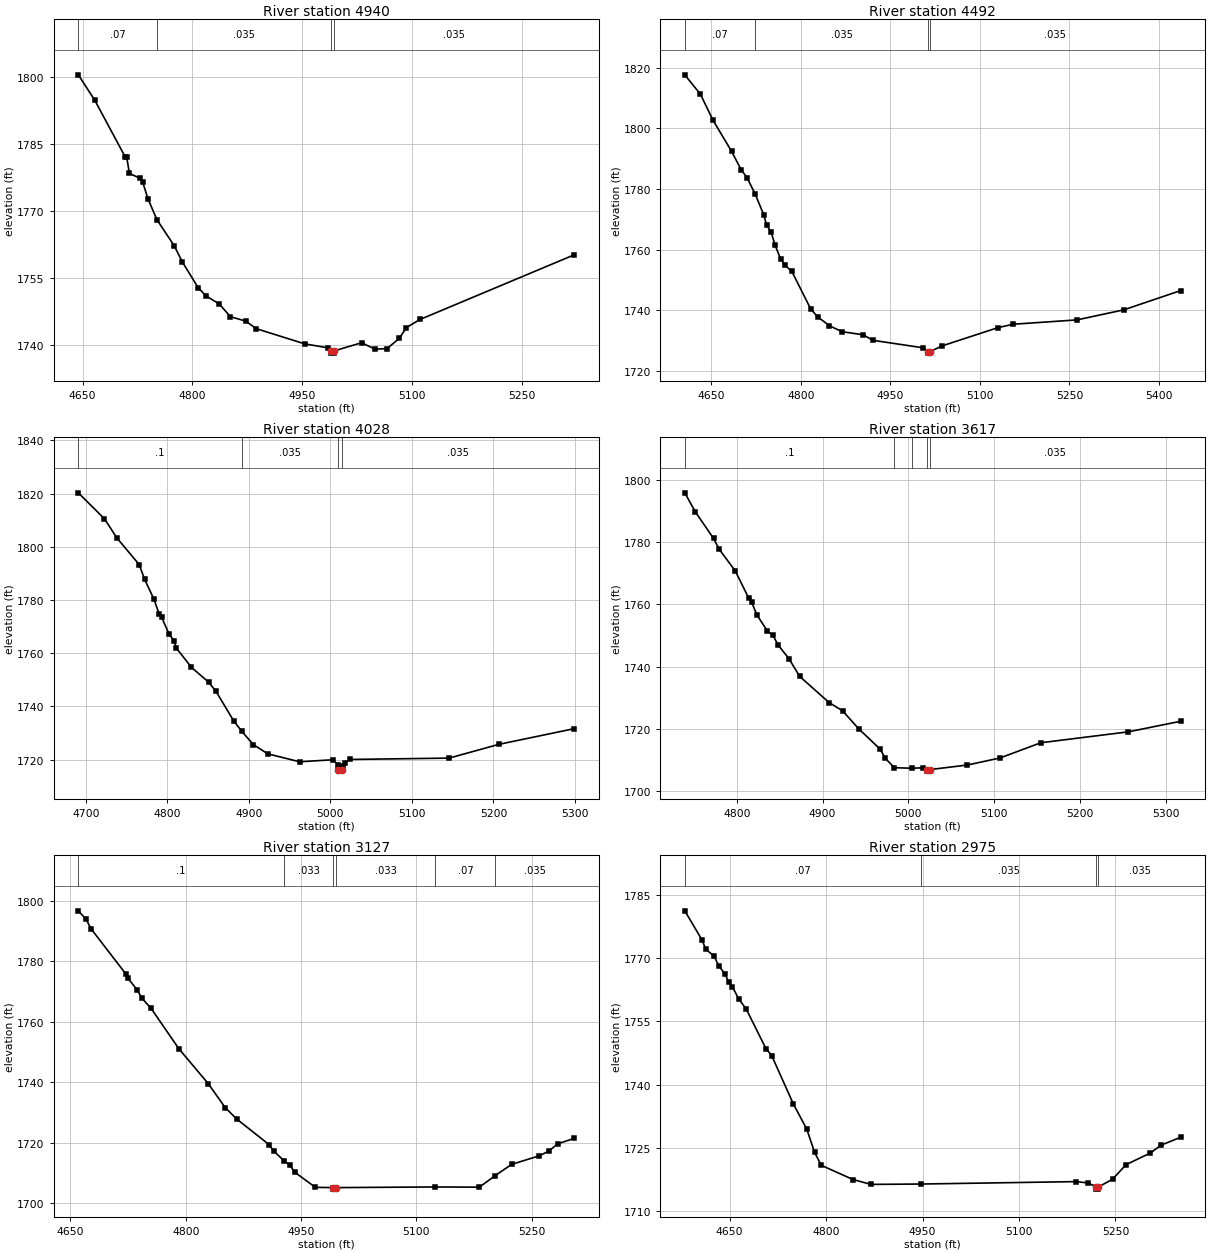
Type RM Length L Ch R = 1,4940,448,448,448
BEGIN DESCRIPTION:
Stream0573 10.0
END DESCRIPTION:
XS GIS Cut Line= 3
      1948924.98     13909975.03      1948725.00     13910275.00
      1948625.01     13910574.96
#Sta/Elev= 30
  4644.2 1800.58  4666.7 1794.86  4708.0 1782.22  4710.3 1782.05  4713.9 1778.46
  4728.4 1777.38  4732.0 1776.54  4739.2 1772.79  4751.5 1768.07  4775.2 1762.20
  4786.1 1758.62  4807.7 1752.85  4818.5 1750.97  4836.5 1749.19  4851.7 1746.33
  4872.6 1745.34  4887.0 1743.64  4953.3 1740.22  4984.4 1739.36  4989.2 1738.65
  4989.4 1738.15  4992.9 1738.15  4993.2 1738.65  5030.7 1740.47  5049.6 1739.02
  5065.6 1739.18  5082.4 1741.48  5091.9 1743.89  5110.8 1745.72  5320.9 1760.20
#Mann=4,-1,0
  4644.2    0.07       0  4751.5   0.035       0  4989.2   0.035       0
  4993.2   0.035       0
Bank Sta=4989.2,4993.2
Exp/Cntr=0.3,0.1

Type RM Length L Ch R = 1,4492,464,464,464
BEGIN DESCRIPTION:
Stream0573 9.0
END DESCRIPTION:
XS GIS Cut Line= 3
      1948675.02     13909774.99      1948375.00     13910025.00
      1948245.46     13910445.78
#Sta/Elev= 30
  4605.6 1817.62  4631.8 1811.22  4652.7 1802.71  4684.0 1792.36  4700.0 1786.34
  4709.8 1783.72  4723.7 1778.22  4737.9 1771.43  4742.6 1768.13  4750.4 1765.64
  4756.6 1761.58  4766.0 1756.98  4773.8 1754.73  4784.8 1752.84  4816.8 1740.30
  4828.5 1737.75  4848.0 1734.85  4869.1 1732.89  4904.5 1731.87  4920.7 1730.05
  5005.2 1727.57  5012.6 1726.32  5012.9 1725.82  5016.6 1726.32  5036.8 1728.21
  5130.4 1734.23  5155.9 1735.35  5262.6 1736.78  5341.1 1740.09  5436.4 1746.45
#Mann=4,-1,0
  4605.6    0.07       0  4723.7   0.035       0  5012.6   0.035       0
  5016.6   0.035       0
Bank Sta=5012.6,5016.6
Exp/Cntr=0.3,0.1

Type RM Length L Ch R = 1,4028,411,411,411
BEGIN DESCRIPTION:
Stream0573 8.0
END DESCRIPTION:
XS GIS Cut Line= 3
      1947875.00     13909675.01      1947925.00     13909975.00
      1947975.00     13910275.03
#Sta/Elev= 30
  4690.8 1820.29  4722.9 1810.51  4738.1 1803.33  4765.5 1793.32  4772.0 1787.87
  4783.7 1780.22  4789.8 1774.84  4792.9 1773.56  4802.0 1767.27  4808.1 1764.72
  4811.2 1761.90  4829.5 1754.73  4850.6 1749.15  4859.8 1745.64  4881.5 1734.54
  4891.4 1730.65  4905.4 1725.71  4923.2 1722.21  4962.3 1719.22  5002.7 1719.98
  5009.3 1718.20  5009.8 1716.21  5010.1 1715.71  5013.8 1716.21  5014.9 1717.66
  5017.9 1718.86  5024.0 1720.10  5145.7 1720.60  5206.5 1725.76  5299.1 1731.66
#Mann=4,-1,0
  4690.8     0.1       0  4891.4   0.035       0  5009.8   0.035       0
  5013.8   0.035       0
Bank Sta=5009.8,5013.8
Exp/Cntr=0.3,0.1

Type RM Length L Ch R = 1,3617,490,490,490
BEGIN DESCRIPTION:
Stream0573 7.0
END DESCRIPTION:
XS GIS Cut Line= 3
      1947475.00     13909725.01      1947557.50     13910009.05
      1947674.17     13910266.25
#Sta/Elev= 30
  4739.4 1795.86  4751.6 1789.78  4772.9 1781.20  4779.7 1777.65  4798.4 1770.69
  4814.0 1761.96  4817.2 1760.83  4823.4 1756.65  4835.8 1751.39  4842.1 1750.06
  4848.4 1746.87  4860.9 1742.53  4873.4 1736.83  4907.7 1728.42  4923.4 1725.78
  4942.1 1720.01  4967.1 1713.48  4973.4 1710.45  4983.7 1707.49  5004.1 1707.31
  5017.1 1707.45  5021.3 1706.88  5021.6 1706.38  5025.1 1706.38  5025.3 1706.88
  5068.8 1708.34  5106.9 1710.60  5154.5 1715.50  5256.5 1719.01  5317.6 1722.41
#Mann=5,-1,0
  4739.4     0.1       0  4983.7   0.033       0  5004.1   0.035       0
  5021.3   0.033       0  5025.3   0.035       0
Bank Sta=5021.3,5025.3
Exp/Cntr=0.3,0.1

Type RM Length L Ch R = 1,3127,152,152,152
BEGIN DESCRIPTION:
Stream0573 6.0
END DESCRIPTION:
XS GIS Cut Line= 3
      1947201.92     13909681.38      1947175.00     13910025.00
      1947175.00     13910325.02
#Sta/Elev= 30
  4660.4 1796.65  4670.7 1793.80  4676.8 1790.76  4721.9 1775.87  4724.9 1774.34
  4736.8 1770.56  4743.0 1767.77  4755.0 1764.41  4791.1 1751.07  4829.2 1739.57
  4851.3 1731.64  4866.3 1727.84  4908.5 1719.35  4914.5 1717.22  4928.0 1714.01
  4935.5 1712.59  4941.6 1710.30  4968.6 1705.25  4991.8 1705.16  4992.1 1704.66
  4995.6 1704.66  4995.8 1705.16  5124.8 1705.38  5181.8 1705.31  5202.6 1709.15
  5223.8 1712.84  5259.8 1715.68  5271.8 1717.18  5283.8 1719.63  5305.1 1721.44
#Mann=6,-1,0
  4660.4     0.1       0  4928.0   0.033       0  4991.8   0.033       0
  4995.8   0.033       0  5124.8    0.07       0  5202.6   0.035       0
Bank Sta=4991.8,4995.8
Exp/Cntr=0.3,0.1

Type RM Length L Ch R = 1,2975,89,89,89
BEGIN DESCRIPTION:
Stream0573 5.1
END DESCRIPTION:
XS GIS Cut Line= 3
      1947066.03     13909644.97      1947027.84     13909903.63
      1947059.09     13910412.31
#Sta/Elev= 30
  4580.2 1781.21  4607.4 1774.20  4612.7 1772.13  4625.8 1770.46  4633.5 1768.03
  4642.6 1766.31  4648.6 1764.23  4654.3 1763.20  4663.8 1760.38  4675.9 1757.89
  4706.3 1748.58  4715.4 1746.88  4748.7 1735.54  4769.9 1729.46  4782.1 1723.94
  4792.4 1720.90  4841.7 1717.53  4869.8 1716.37  4948.2 1716.46  5188.4 1717.03
  5207.9 1716.71  5219.4 1715.75  5219.7 1715.25  5223.2 1715.25  5223.4 1715.75
  5245.5 1717.61  5266.5 1721.06  5304.2 1723.80  5320.6 1725.65  5351.3 1727.54
#Mann=4,-1,0
  4580.2    0.07       0  4948.2   0.035       0  5219.4   0.035       0
  5223.4   0.035       0
Bank Sta=5219.4,5223.4
Exp/Cntr=0.3,0.1

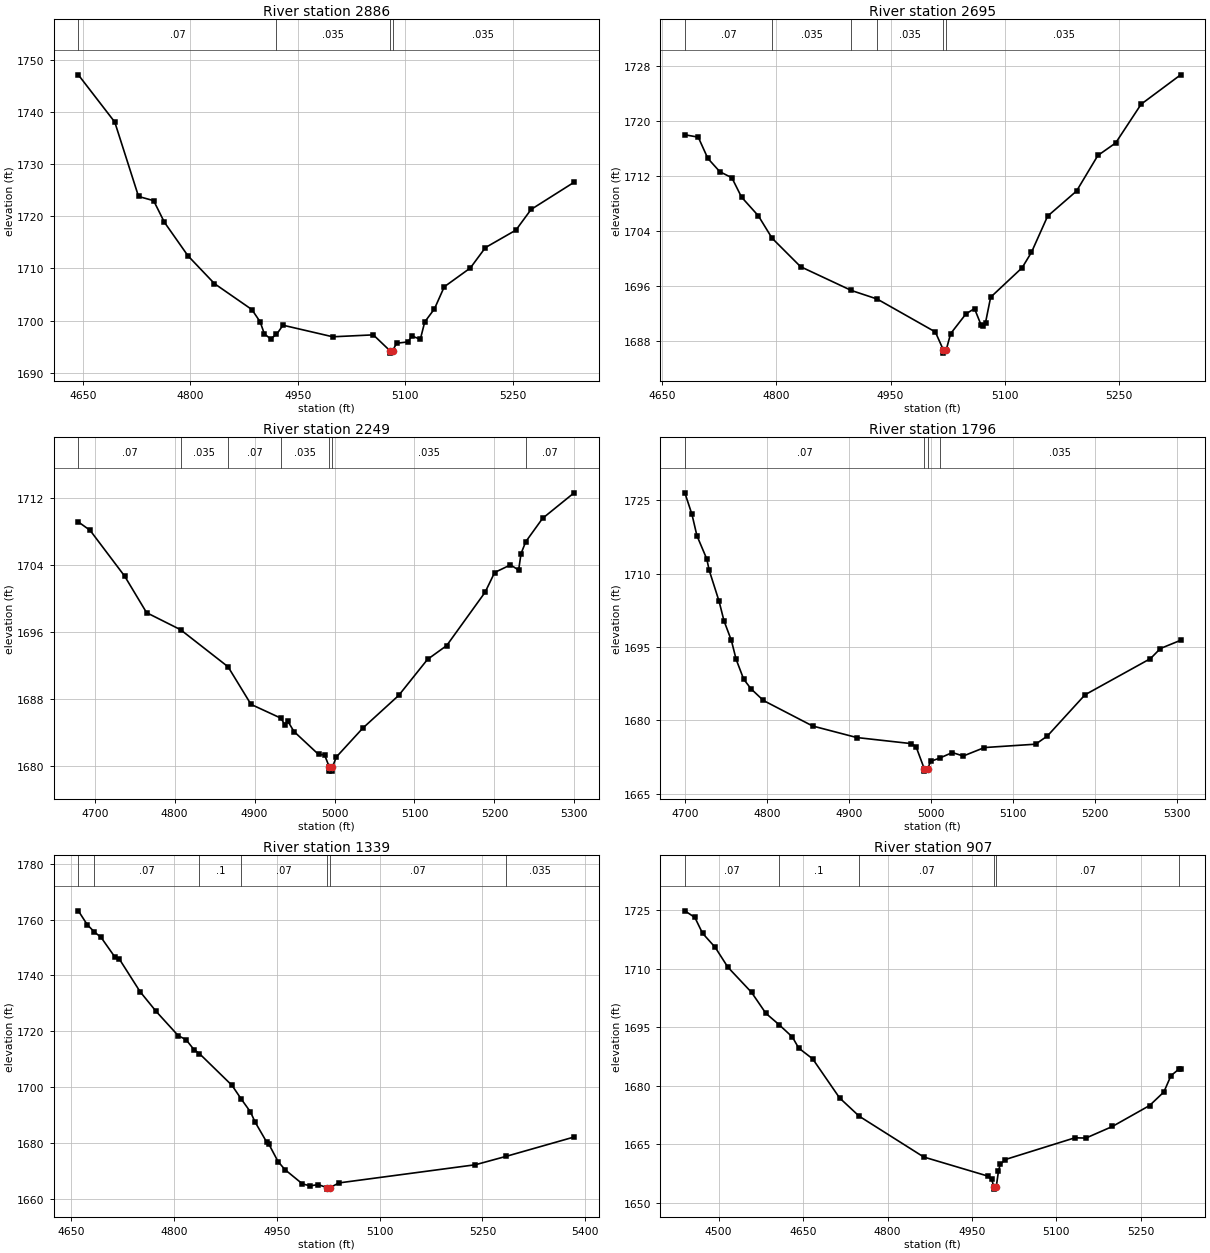
Type RM Length L Ch R = 1,2886,191,191,191
BEGIN DESCRIPTION:
Mapping XS 2df348ba
END DESCRIPTION:
XS GIS Cut Line= 3
      1946939.25     13909718.59      1946954.47     13910156.48
      1946992.27     13910408.10
#Sta/Elev= 30
  4643.4 1747.07  4694.3 1738.02  4727.5 1723.77  4748.6 1722.96  4763.6 1718.83
  4796.6 1712.39  4833.6 1707.06  4885.8 1702.10  4897.4 1699.75  4903.2 1697.46
  4911.9 1696.48  4920.2 1697.32  4929.3 1699.10  4998.9 1696.88  5055.5 1697.25
  5078.4 1694.25  5078.6 1693.75  5082.4 1694.25  5088.2 1695.65  5104.0 1695.90
  5109.3 1697.03  5121.2 1696.41  5127.3 1699.72  5140.9 1702.23  5154.6 1706.46
  5191.0 1710.06  5212.1 1713.97  5254.7 1717.32  5275.9 1721.28  5336.0 1726.49
#Mann=4,-1,0
  4643.4    0.07       0  4920.2   0.035       0  5078.4   0.035       0
  5082.4   0.035       0
Bank Sta=5078.4,5082.4
Exp/Cntr=0.3,0.1

Type RM Length L Ch R = 1,2695,446,446,446
BEGIN DESCRIPTION:
Stream0573 5.0
END DESCRIPTION:
XS GIS Cut Line= 3
      1946675.01     13909825.03      1946775.00     13910125.00
      1946925.00     13910424.99
#Sta/Elev= 30
  4679.6 1718.04  4697.2 1717.70  4709.8 1714.61  4725.6 1712.67  4741.4 1711.79
  4754.1 1708.98  4776.2 1706.26  4794.2 1703.01  4831.7 1698.86  4898.5 1695.40
  4932.3 1694.16  5008.8 1689.37  5019.2 1686.79  5019.4 1686.29  5023.2 1686.79
  5028.9 1689.12  5049.1 1692.00  5060.3 1692.77  5069.2 1690.31  5071.6 1690.26
  5074.8 1690.74  5081.5 1694.42  5122.9 1698.71  5135.2 1700.96  5156.4 1706.21
  5194.4 1709.86  5222.4 1715.03  5245.8 1716.85  5279.3 1722.49  5331.2 1726.76
#Mann=6,-1,0
  4679.6    0.07       0  4794.2   0.035       0  4898.5    0.07       0
  4932.3   0.035       0  5019.2   0.035       0  5023.2   0.035       0
Bank Sta=5019.2,5023.2
Exp/Cntr=0.3,0.1

Type RM Length L Ch R = 1,2249,453,453,453
BEGIN DESCRIPTION:
Stream0573 4.0
END DESCRIPTION:
XS GIS Cut Line= 3
      1946575.01     13909924.99      1946375.00     13910175.00
      1946375.00     13910475.03
#Sta/Elev= 30
  4679.5 1709.14  4694.2 1708.14  4737.5 1702.67  4764.9 1698.32  4807.4 1696.29
  4866.8 1691.87  4895.5 1687.39  4933.0 1685.74  4937.8 1684.95  4941.6 1685.37
  4949.3 1684.15  4980.0 1681.42  4987.5 1681.37  4993.4 1679.93  4993.7 1679.43
  4997.2 1679.43  4997.4 1679.93  5002.3 1681.12  5035.3 1684.55  5080.3 1688.46
  5116.3 1692.75  5140.3 1694.40  5188.3 1700.75  5200.3 1703.11  5220.1 1704.02
  5230.3 1703.40  5233.3 1705.36  5239.2 1706.78  5260.3 1709.57  5299.7 1712.61
#Mann=7,-1,0
  4679.5    0.07       0  4807.4   0.035       0  4866.8    0.07       0
  4933.0   0.035       0  4993.4   0.035       0  4997.4   0.035       0
  5239.2    0.07       0
Bank Sta=4993.4,4997.4
Exp/Cntr=0.3,0.1

Type RM Length L Ch R = 1,1796,457,457,457
BEGIN DESCRIPTION:
Stream0573 3.0
END DESCRIPTION:
XS GIS Cut Line= 3
      1945975.00     13909725.02      1945975.00     13910025.00
      1945925.00     13910324.98
#Sta/Elev= 30
  4700.1 1726.55  4708.8 1722.12  4714.8 1717.79  4726.8 1713.03  4729.8 1710.70
  4741.8 1704.37  4747.8 1700.37  4756.8 1696.35  4762.6 1692.49  4771.8 1688.43
  4780.8 1686.45  4795.8 1684.08  4855.8 1678.86  4909.6 1676.50  4975.8 1675.26
  4981.8 1674.64  4991.8 1670.13  4992.0 1669.63  4995.8 1670.13  4999.8 1671.64
  5010.4 1672.28  5026.0 1673.43  5039.3 1672.72  5065.1 1674.45  5127.5 1675.14
  5141.8 1676.81  5187.7 1685.24  5267.4 1692.64  5279.6 1694.71  5304.2 1696.39
#Mann=4,-1,0
  4700.1    0.07       0  4991.8    0.05       0  4995.8    0.07       0
  5010.4   0.035       0
Bank Sta=4991.8,4995.8
Exp/Cntr=0.3,0.1

Type RM Length L Ch R = 1,1339,432,432,432
BEGIN DESCRIPTION:
Stream0573 2.0
END DESCRIPTION:
XS GIS Cut Line= 3
      1945724.98     13909575.03      1945575.00     13909875.00
      1945569.33     13910262.98
#Sta/Elev= 30
  4660.4 1763.12  4673.4 1758.17  4683.8 1755.53  4693.5 1753.63  4713.7 1746.57
  4720.4 1745.77  4750.6 1734.11  4774.0 1727.05  4806.2 1718.37  4817.6 1716.93
  4829.1 1713.39  4837.0 1711.96  4884.7 1700.54  4898.0 1695.69  4911.6 1691.03
  4918.3 1687.42  4935.0 1680.33  4938.4 1679.49  4951.8 1673.26  4961.9 1670.36
  4987.3 1665.26  4998.5 1664.54  5010.5 1665.00  5023.5 1663.87  5023.7 1663.37
  5027.5 1663.87  5040.5 1665.59  5239.8 1672.11  5284.2 1675.09  5383.8 1682.05
#Mann=7,-1,0
  4660.4     0.1       0  4683.8    0.07       0  4837.0     0.1       0
  4898.0    0.07       0  5023.5    0.05       0  5027.5    0.07       0
  5284.2   0.035       0
Bank Sta=5023.5,5027.5
Exp/Cntr=0.3,0.1

Type RM Length L Ch R = 1,907,603,603,603
BEGIN DESCRIPTION:
Stream0573 1.0
END DESCRIPTION:
XS GIS Cut Line= 4
      1945448.10     13909523.78      1945197.32     13909747.99
      1945175.00     13909975.00      1945274.99     13910274.97
#Sta/Elev= 30
  4440.0 1724.84  4457.8 1723.14  4471.4 1719.10  4493.9 1715.48  4516.4 1710.40
  4558.5 1703.94  4583.9 1698.58  4607.5 1695.65  4630.9 1692.52  4642.4 1689.64
  4667.1 1686.90  4714.9 1676.89  4749.7 1672.21  4864.4 1661.75  4978.3 1656.86
  4985.1 1655.99  4989.1 1654.02  4989.4 1653.52  4993.1 1654.02  4997.1 1658.12
  5000.2 1659.89  5009.4 1661.11  5132.8 1666.67  5152.5 1666.61  5199.4 1669.57
  5265.6 1674.95  5290.9 1678.41  5303.5 1682.58  5317.3 1684.24  5320.7 1684.38
#Mann=6,-1,0
  4440.0    0.07       0  4607.5     0.1       0  4749.7    0.07       0
  4989.1    0.05       0  4993.1    0.07       0  5317.3   0.035       0
Bank Sta=4989.1,4993.1
Exp/Cntr=0.3,0.1

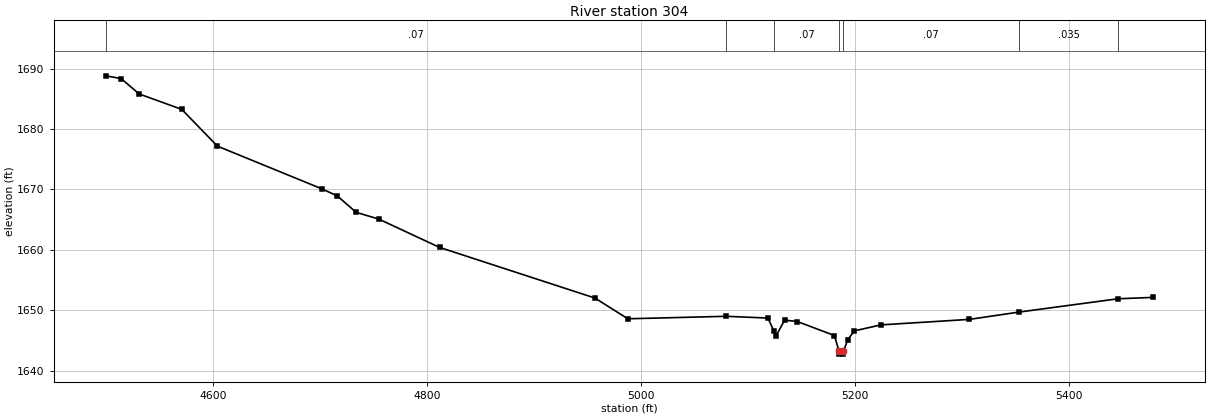
Type RM Length L Ch R = 1,304,0,0,0
BEGIN DESCRIPTION:
Stream0573. 0.0
END DESCRIPTION:
XS GIS Cut Line= 3
      1944908.40     13909292.73      1944676.92     13909660.01
      1944561.64     13910192.64
#Sta/Elev= 30
  4499.8 1688.80  4514.1 1688.34  4530.9 1685.80  4570.7 1683.25  4604.1 1677.16
  4701.9 1670.08  4716.1 1668.93  4733.8 1666.21  4755.1 1665.08  4811.8 1660.40
  4957.1 1652.02  4987.8 1648.59  5079.8 1649.00  5118.8 1648.71  5124.6 1646.49
  5126.6 1645.82  5134.4 1648.37  5146.2 1648.14  5181.0 1645.82  5185.2 1643.24
  5185.5 1642.74  5189.2 1642.74  5189.4 1643.24  5193.5 1645.13  5199.6 1646.59
  5224.5 1647.58  5307.1 1648.49  5353.6 1649.70  5446.1 1651.90  5478.9 1652.13
#Mann=7,-1,0
  4499.8    0.07       0  5079.8   0.035       0  5124.6    0.07       0
  5185.2    0.05       0  5189.4    0.07       0  5353.6   0.035       0
  5446.1    0.07       0
Bank Sta=5185.2,5189.4
Exp/Cntr=0.3,0.1

Chan Stop Cuts=-1