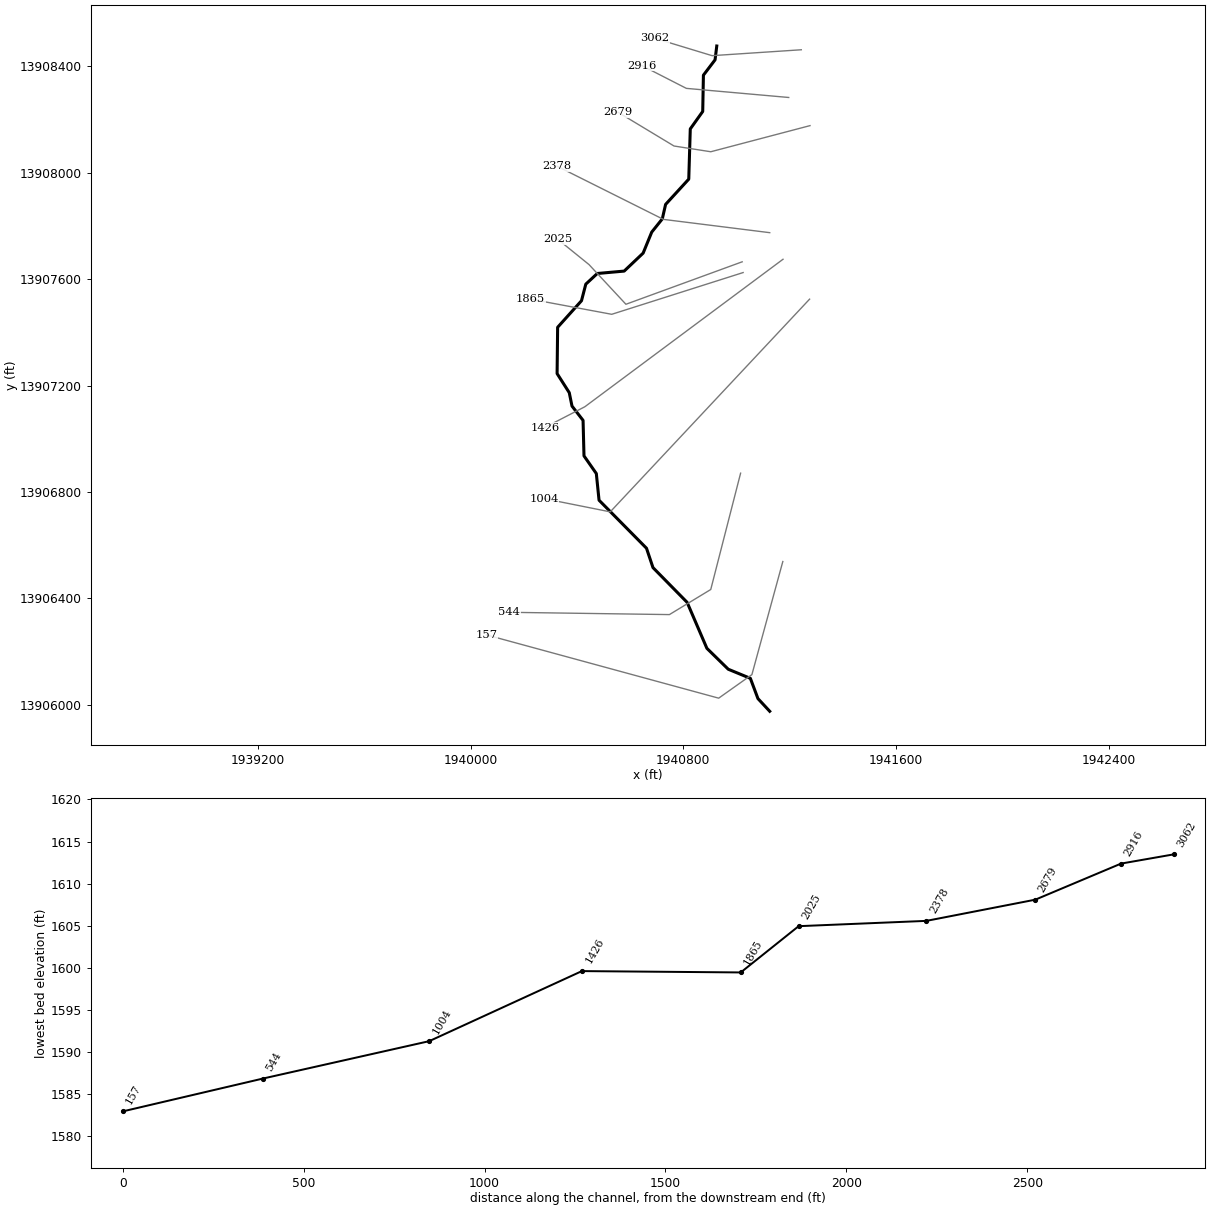
--- Stream0574.prj (project) ---

Proj Title=Stream0574 Base Level Engineering
Current Plan=p01
Default Exp/Contr=0.3,0.1
English Units
Geom File=g01
Flow File=f01
Plan File=p01
BEGIN DESCRIPTION:
Stream0574
END DESCRIPTION:

--- Stream0574.p01 (plan) ---

Plan Title=Multiple Run
Short Identifier=Multiple
Geom File=g01
Flow File=f01
Subcritical Flow
K Sum by GR= 0
Std Step Tol= 0.01
Critical Tol= 0.01
Num of Std Step Trials= 20
Max Error Tol= 0.3
Flow Tol Ratio= 0.001
Split Flow NTrial= 30
Split Flow Tol= 0.02
Split Flow Ratio= 0.02
Log Output Level= 0
Friction Slope Method= 1
Unsteady Friction Slope Method= 2
Unsteady Bridges Friction Slope Method= 1
Parabolic Critical Depth
Global Vel Dist=  1 , 1 , 1
Global Log Level= 0
CheckData=True
Encroach Param= -1, 0, 0, 0
BEGIN DESCRIPTION:
Multiple Run
END DESCRIPTION:

--- Stream0574.f01 (steady flow) ---

Flow Title=Multiple
Number of Profiles=7
Profile Names=10-year,25-year,50-year,1pct_min,100-year,1pct_plu,500-year
River Rch & RM= Stream0574,Reach-1,3062
    1542    2671    3763    2562    5112   10200    9312
River Rch & RM= Stream0574,Reach-1,2378
    1554    2690    3789    2578    5144   10264    9366
Boundary for River Rch & Prof#=Stream0574,Reach-1,1
Up Type=0
Dn Type=3
Dn Slope=0.005
Boundary for River Rch & Prof#=Stream0574,Reach-1,2
Up Type=0
Dn Type=3
Dn Slope=0.005
Boundary for River Rch & Prof#=Stream0574,Reach-1,3
Up Type=0
Dn Type=3
Dn Slope=0.005
Boundary for River Rch & Prof#=Stream0574,Reach-1,4
Up Type=0
Dn Type=3
Dn Slope=0.005
Boundary for River Rch & Prof#=Stream0574,Reach-1,5
Up Type=0
Dn Type=3
Dn Slope=0.005
Boundary for River Rch & Prof#=Stream0574,Reach-1,6
Up Type=0
Dn Type=3
Dn Slope=0.005
Boundary for River Rch & Prof#=Stream0574,Reach-1,7
Up Type=0
Dn Type=3
Dn Slope=0.005

--- Stream0574.g01 (geometry) ---

Geom Title=Existing Conditions

River Reach=Stream0574,Reach-1
Reach XY= 30
      1940925.74     13908477.03      1940919.37     13908425.05
      1940875.55     13908367.36      1940872.91     13908230.87
      1940826.13     13908165.23      1940820.40     13907976.36
      1940733.26     13907881.30      1940720.81     13907826.73
      1940681.10     13907777.18      1940648.74     13907698.11
      1940577.44     13907630.52      1940476.28     13907621.47
      1940433.02     13907581.38      1940416.81     13907518.98
      1940327.06     13907419.14      1940325.06     13907245.03
      1940370.81     13907173.26      1940381.12     13907122.82
      1940422.75     13907069.07      1940426.23     13906935.51
      1940472.64     13906869.02      1940482.86     13906768.83
      1940661.37     13906588.21      1940685.78     13906515.32
      1940814.23     13906384.68      1940888.61     13906211.76
      1940968.95     13906133.16      1941052.17     13906098.86
      1941080.72     13906022.68      1941125.00     13905975.00

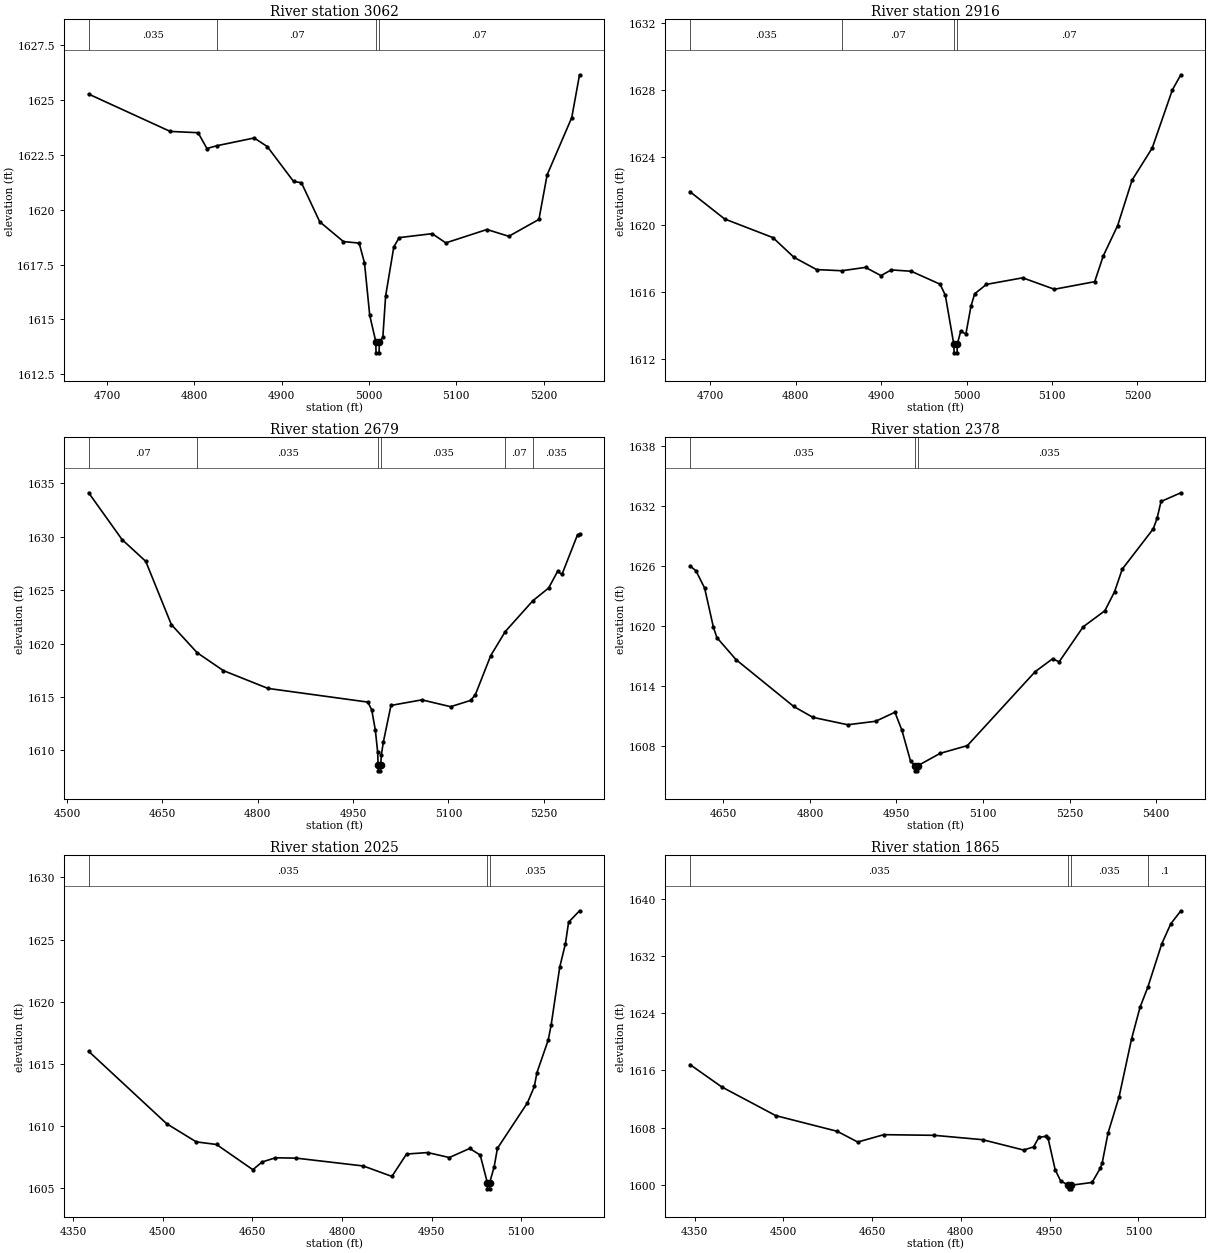
Type RM Length L Ch R = 1,3062,146,146,146
BEGIN DESCRIPTION:
Stream0574 7.0
END DESCRIPTION:
XS GIS Cut Line= 3
      1941243.87     13908462.92      1940908.10     13908440.73
      1940692.34     13908506.27
#Sta/Elev= 30
  4679.1 1625.27  4772.4 1623.57  4804.4 1623.51  4814.5 1622.79  4826.2 1622.92
  4868.6 1623.27  4883.6 1622.88  4913.7 1621.29  4922.7 1621.23  4943.7 1619.45
  4970.8 1618.55  4988.8 1618.48  4994.9 1617.58  5000.9 1615.19  5007.9 1613.98
  5008.1 1613.48  5011.6 1613.48  5011.9 1613.98  5015.9 1614.18  5019.1 1616.07
  5028.5 1618.31  5034.7 1618.73  5072.4 1618.91  5088.0 1618.49  5135.1 1619.10
  5160.1 1618.79  5194.6 1619.56  5204.0 1621.59  5232.2 1624.20  5241.1 1626.15
#Mann=4,-1,0
  4679.1   0.035       0  4826.2    0.07       0  5007.9    0.05       0
  5011.9    0.07       0
Bank Sta=5007.9,5011.9
Exp/Cntr=0.3,0.1

Type RM Length L Ch R = 1,2916,237,237,237
BEGIN DESCRIPTION:
Stream0574 6.0
END DESCRIPTION:
XS GIS Cut Line= 3
      1941196.49     13908283.44      1940811.30     13908317.72
      1940643.97     13908403.40
#Sta/Elev= 30
  4676.2 1621.96  4716.7 1620.34  4773.3 1619.23  4797.9 1618.06  4824.4 1617.33
  4854.0 1617.26  4881.7 1617.46  4899.8 1616.97  4911.8 1617.31  4935.2 1617.23
  4969.0 1616.46  4975.1 1615.81  4985.1 1612.88  4985.4 1612.38  4988.9 1612.38
  4989.1 1612.88  4993.1 1613.66  4999.2 1613.50  5005.2 1615.16  5009.5 1615.89
  5023.3 1616.45  5065.7 1616.84  5102.8 1616.16  5150.0 1616.61  5160.1 1618.15
  5176.9 1619.95  5193.8 1622.65  5217.4 1624.56  5241.0 1628.02  5250.9 1628.91
#Mann=4,-1,0
  4676.2   0.035       0  4854.0    0.07       0  4985.1    0.05       0
  4989.1    0.07       0
Bank Sta=4985.1,4989.1
Exp/Cntr=0.3,0.1

Type RM Length L Ch R = 1,2679,301,301,301
BEGIN DESCRIPTION:
Stream0574 5.0
END DESCRIPTION:
XS GIS Cut Line= 4
      1941276.64     13908177.61      1940903.23     13908079.36
      1940764.92     13908100.94      1940554.16     13908228.01
#Sta/Elev= 30
  4534.1 1634.10  4586.7 1629.72  4623.9 1627.69  4664.2 1621.77  4704.8 1619.14
  4745.9 1617.47  4816.2 1615.80  4973.3 1614.52  4979.4 1613.79  4985.1 1611.90
  4988.7 1609.86  4989.5 1608.59  4989.7 1608.09  4993.2 1608.09  4993.5 1608.59
  4994.5 1609.56  4997.6 1610.76  5009.7 1614.21  5058.3 1614.73  5103.5 1614.09
  5135.1 1614.68  5142.4 1615.21  5166.6 1618.87  5189.5 1621.12  5233.0 1624.01
  5257.7 1625.19  5271.7 1626.74  5278.7 1626.47  5303.2 1630.18  5306.3 1630.21
#Mann=6,-1,0
  4534.1    0.07       0  4704.8   0.035       0  4989.5   0.035       0
  4993.5   0.035       0  5189.5    0.07       0  5233.0   0.035       0
Bank Sta=4989.5,4993.5
Exp/Cntr=0.3,0.1

Type RM Length L Ch R = 1,2378,353,353,353
BEGIN DESCRIPTION:
Stream0574 4.0
END DESCRIPTION:
XS GIS Cut Line= 3
      1941125.02     13907775.00      1940725.00     13907825.00
      1940325.04     13908024.98
#Sta/Elev= 30
  4592.3 1626.02  4602.6 1625.55  4617.7 1623.81  4632.8 1619.92  4638.9 1618.87
  4672.1 1616.67  4771.9 1612.00  4805.2 1610.91  4865.6 1610.17  4914.0 1610.52
  4947.3 1611.42  4959.4 1609.62  4974.5 1606.51  4982.5 1606.07  4982.8 1605.57
  4986.3 1605.57  4986.5 1606.07  5025.8 1607.32  5072.8 1608.09  5190.2 1615.47
  5220.4 1616.76  5231.7 1616.45  5273.4 1619.95  5310.9 1621.55  5327.7 1623.45
  5341.1 1625.71  5394.8 1629.73  5401.5 1630.80  5408.2 1632.46  5442.6 1633.33
#Mann=3,-1,0
  4592.3   0.035       0  4982.5   0.035       0  4986.5   0.035       0
Bank Sta=4982.5,4986.5
Exp/Cntr=0.3,0.1

Type RM Length L Ch R = 1,2025,160,160,160
BEGIN DESCRIPTION:
Stream0574 3.1
END DESCRIPTION:
XS GIS Cut Line= 4
      1941021.43     13907665.45      1940583.95     13907505.74
      1940445.06     13907655.04      1940326.99     13907750.54
#Sta/Elev= 30
  4376.2 1616.01  4506.8 1610.18  4556.3 1608.72  4590.2 1608.51  4651.0 1606.48
  4666.4 1607.10  4688.8 1607.44  4723.9 1607.41  4835.8 1606.78  4883.7 1605.94
  4908.2 1607.74  4943.5 1607.86  4979.8 1607.46  5013.9 1608.19  5031.5 1607.66
  5043.4 1605.44  5043.6 1604.94  5047.1 1604.94  5047.4 1605.44  5054.8 1606.71
  5060.3 1608.20  5110.5 1611.86  5122.1 1613.18  5126.4 1614.29  5145.2 1616.90
  5150.2 1618.12  5164.5 1622.77  5174.1 1624.67  5179.4 1626.40  5197.7 1627.32
#Mann=3,-1,0
  4376.2   0.035       0  5043.4   0.035       0  5047.4   0.035       0
Bank Sta=5043.4,5047.4
Exp/Cntr=0.3,0.1

Type RM Length L Ch R = 1,1865,439,439,439
BEGIN DESCRIPTION:
Stream0574 3.0
END DESCRIPTION:
XS GIS Cut Line= 3
      1941025.02     13907625.01      1940530.57     13907468.01
      1940225.01     13907525.00
#Sta/Elev= 30
  4342.2 1616.81  4395.9 1613.68  4487.2 1609.67  4591.1 1607.48  4625.7 1605.98
  4669.8 1607.01  4754.8 1606.92  4836.6 1606.31  4906.1 1604.86  4922.8 1605.30
  4931.9 1606.63  4944.2 1606.79  4947.2 1606.58  4959.4 1602.10  4968.6 1600.55
  4981.8 1599.94  4982.1 1599.44  4985.6 1599.44  4985.8 1599.94  5021.7 1600.33
  5035.7 1602.33  5038.8 1603.04  5048.7 1607.23  5067.4 1612.31  5088.5 1620.40
  5102.8 1624.82  5115.9 1627.61  5139.5 1633.68  5154.7 1636.47  5171.8 1638.30
#Mann=4,-1,0
  4342.2   0.035       0  4981.8   0.035       0  4985.8   0.035       0
  5115.9     0.1       0
Bank Sta=4981.8,4985.8
Exp/Cntr=0.3,0.1

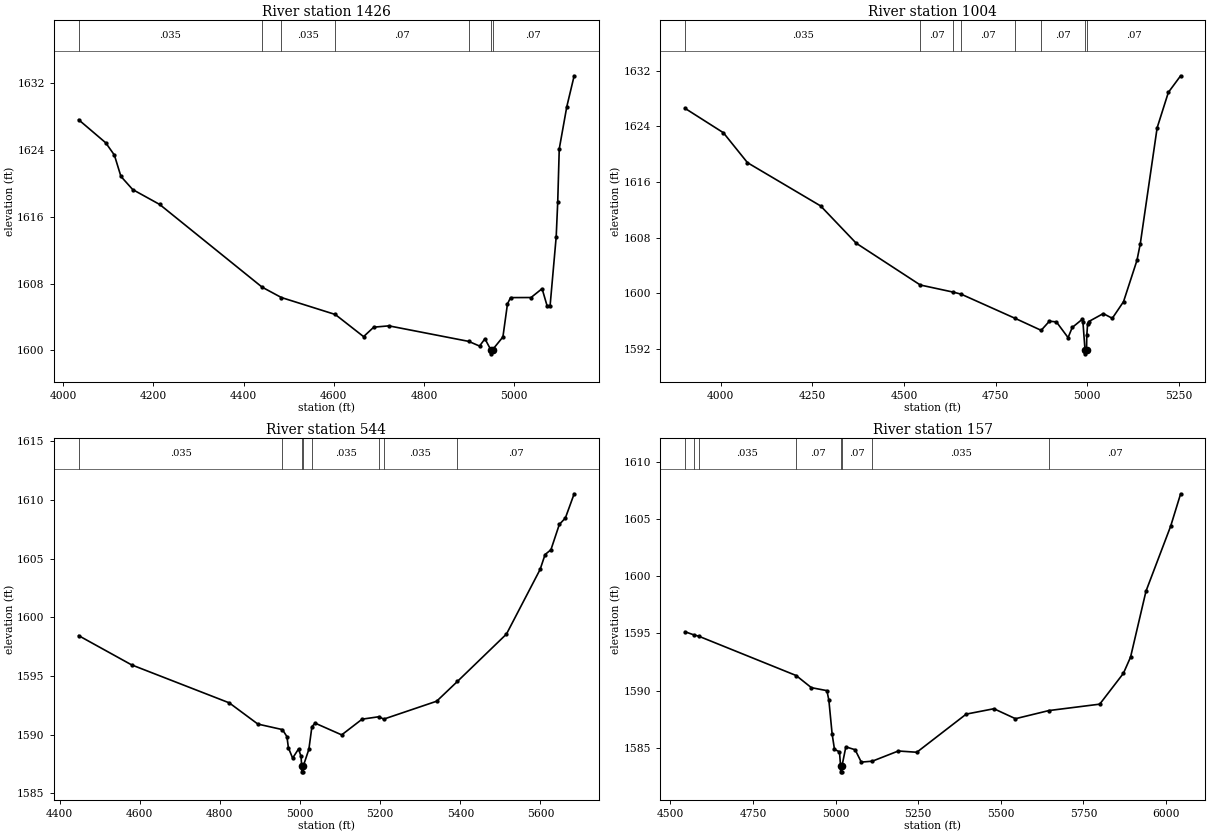
Type RM Length L Ch R = 1,1426,422,422,422
BEGIN DESCRIPTION:
Stream0574 2.0
END DESCRIPTION:
XS GIS Cut Line= 3
      1941175.04     13907675.03      1940429.44     13907120.32
      1940278.36     13907042.18
#Sta/Elev= 30
  4034.0 1627.62  4094.1 1624.86  4113.3 1623.39  4127.8 1620.84  4154.0 1619.26
  4213.8 1617.48  4441.1 1607.58  4483.8 1606.34  4603.4 1604.31  4666.2 1601.66
  4688.7 1602.79  4722.3 1602.95  4899.5 1601.09  4923.5 1600.53  4935.4 1601.40
  4948.3 1600.10  4948.6 1599.60  4952.4 1600.10  4975.3 1601.62  4985.4 1605.57
  4992.2 1606.33  5037.7 1606.34  5062.2 1607.40  5073.2 1605.37  5080.0 1605.37
  5093.5 1613.60  5096.9 1617.76  5100.3 1624.13  5117.1 1629.20  5133.4 1632.88
#Mann=7,-1,0
  4034.0   0.035       0  4441.1    0.07       0  4483.8   0.035       0
  4603.4    0.07       0  4899.5   0.035       0  4948.3    0.05       0
  4952.4    0.07       0
Bank Sta=4948.3,4952.4
Exp/Cntr=0.3,0.1

Type RM Length L Ch R = 1,1004,460,460,460
BEGIN DESCRIPTION:
Stream0574 1.0
END DESCRIPTION:
XS GIS Cut Line= 3
      1941275.03     13907525.03      1940525.00     13906725.00
      1940274.98     13906775.00
#Sta/Elev= 30
  3902.9 1626.57  4007.3 1623.07  4073.1 1618.76  4272.6 1612.54  4369.6 1607.18
  4544.4 1601.17  4634.7 1600.14  4655.9 1599.85  4803.7 1596.36  4874.1 1594.65
  4896.6 1595.97  4915.7 1595.86  4947.5 1593.60  4958.8 1595.06  4985.7 1596.22
  4988.1 1595.78  4993.8 1591.77  4994.1 1591.27  4997.9 1591.77  4998.5 1593.91
  5000.8 1595.57  5003.8 1595.91  5043.5 1597.06  5068.1 1596.38  5098.7 1598.77
  5135.3 1604.70  5144.5 1607.12  5190.4 1623.78  5221.0 1628.87  5254.5 1631.26
#Mann=8,-1,0
  3902.9   0.035       0  4544.4    0.07       0  4634.7   0.035       0
  4655.9    0.07       0  4803.7   0.035       0  4874.1    0.07       0
  4993.8    0.05       0  4997.9    0.07       0
Bank Sta=4993.8,4997.9
Exp/Cntr=0.3,0.1

Type RM Length L Ch R = 1,544,387,387,387
BEGIN DESCRIPTION:
Stream0574 0.0
END DESCRIPTION:
XS GIS Cut Line= 4
      1941015.47     13906870.50      1940903.15     13906433.01
      1940747.56     13906338.63      1940144.78     13906347.25
#Sta/Elev= 30
  4447.6 1598.43  4579.6 1595.94  4823.4 1592.70  4894.9 1590.89  4956.1 1590.42
  4967.4 1589.82  4971.0 1588.87  4981.6 1587.99  4996.3 1588.77  5002.6 1588.13
  5004.1 1587.32  5004.3 1586.82  5007.9 1586.82  5008.2 1587.32  5022.1 1588.74
  5029.7 1590.67  5037.7 1590.97  5104.0 1589.97  5155.0 1591.31  5197.6 1591.52
  5208.6 1591.31  5341.0 1592.84  5392.6 1594.52  5515.1 1598.56  5599.1 1604.07
  5611.5 1605.34  5626.1 1605.75  5647.1 1607.91  5662.1 1608.45  5684.1 1610.52
#Mann=8,-1,0
  4447.6   0.035       0  4956.1    0.07       0  5004.1    0.05       0
  5008.2    0.07       0  5029.7   0.035       0  5197.6    0.07       0
  5208.6   0.035       0  5392.6    0.07       0
Bank Sta=5004.1,5008.2
Exp/Cntr=0.3,0.1

Type RM Length L Ch R = 1,157,0,0,0
BEGIN DESCRIPTION:
Stream0574 0.1
END DESCRIPTION:
XS GIS Cut Line= 4
      1941174.29     13906538.25      1941057.96     13906112.87
      1940932.96     13906024.33      1940059.65     13906262.19
#Sta/Elev= 30
  4544.7 1595.15  4572.1 1594.87  4585.4 1594.77  4880.7 1591.33  4926.8 1590.27
  4973.8 1590.01  4979.7 1589.17  4989.6 1586.21  4996.7 1584.88  5011.8 1584.67
  5015.1 1583.42  5015.3 1582.92  5019.0 1582.92  5019.3 1583.42  5031.1 1585.10
  5059.1 1584.85  5077.8 1583.77  5111.1 1583.85  5189.8 1584.74  5245.8 1584.63
  5395.2 1587.96  5479.0 1588.43  5544.3 1587.56  5645.3 1588.27  5799.2 1588.83
  5870.8 1591.52  5892.5 1592.94  5939.2 1598.70  6013.8 1604.37  6044.0 1607.20
#Mann=8,-1,0
  4544.7   0.035       0  4572.1    0.07       0  4585.4   0.035       0
  4880.7    0.07       0  5015.1    0.05       0  5019.3    0.07       0
  5111.1   0.035       0  5645.3    0.07       0
Bank Sta=5015.1,5019.3
Exp/Cntr=0.3,0.1

Chan Stop Cuts=-1