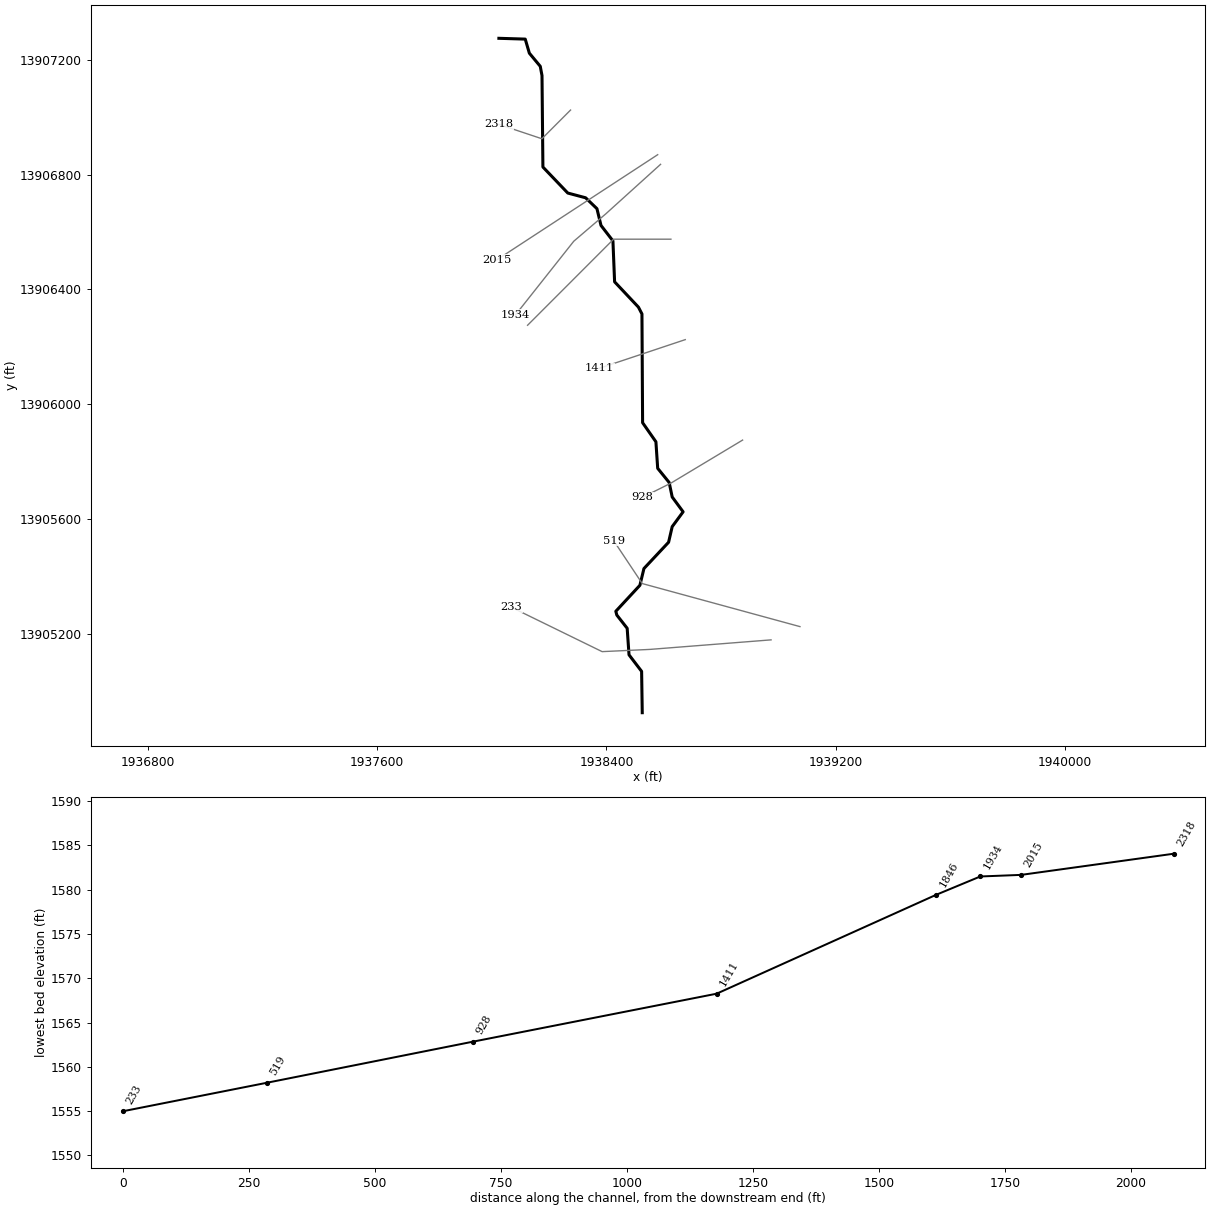
--- Stream0575.prj (project) ---

Proj Title=Stream0575 Base Level Engineering
Current Plan=p01
Default Exp/Contr=0.3,0.1
English Units
Geom File=g01
Flow File=f01
Plan File=p01
BEGIN DESCRIPTION:
Stream0575
END DESCRIPTION:

--- Stream0575.p01 (plan) ---

Plan Title=Multiple Run
Short Identifier=Multiple
Geom File=g01
Flow File=f01
Subcritical Flow
K Sum by GR= 0
Std Step Tol= 0.01
Critical Tol= 0.01
Num of Std Step Trials= 20
Max Error Tol= 0.3
Flow Tol Ratio= 0.001
Split Flow NTrial= 30
Split Flow Tol= 0.02
Split Flow Ratio= 0.02
Log Output Level= 0
Friction Slope Method= 1
Unsteady Friction Slope Method= 2
Unsteady Bridges Friction Slope Method= 1
Parabolic Critical Depth
Global Vel Dist=  1 , 1 , 1
Global Log Level= 0
CheckData=True
Encroach Param= -1, 0, 0, 0
BEGIN DESCRIPTION:
Multiple Run
END DESCRIPTION:

--- Stream0575.f01 (steady flow) ---

Flow Title=Multiple
Number of Profiles=7
Profile Names=10-year,25-year,50-year,1pct_min,100-year,1pct_plu,500-year
River Rch & RM= Stream0575,Reach-1,2318
     707    1169    1596    1056    2107    4204    3620
Boundary for River Rch & Prof#=Stream0575,Reach-1,1
Up Type=0
Dn Type=3
Dn Slope=0.005
Boundary for River Rch & Prof#=Stream0575,Reach-1,2
Up Type=0
Dn Type=3
Dn Slope=0.005
Boundary for River Rch & Prof#=Stream0575,Reach-1,3
Up Type=0
Dn Type=3
Dn Slope=0.005
Boundary for River Rch & Prof#=Stream0575,Reach-1,4
Up Type=0
Dn Type=3
Dn Slope=0.005
Boundary for River Rch & Prof#=Stream0575,Reach-1,5
Up Type=0
Dn Type=3
Dn Slope=0.005
Boundary for River Rch & Prof#=Stream0575,Reach-1,6
Up Type=0
Dn Type=3
Dn Slope=0.005
Boundary for River Rch & Prof#=Stream0575,Reach-1,7
Up Type=0
Dn Type=3
Dn Slope=0.005

--- Stream0575.g01 (geometry) ---

Geom Title=Existing Conditions

River Reach=Stream0575,Reach-1
Reach XY= 30
      1938025.00     13907275.00      1938116.92     13907272.19
      1938131.26     13907223.19      1938169.31     13907177.39
      1938175.37     13907145.16      1938178.53     13906826.45
      1938265.31     13906735.78      1938327.54     13906719.25
      1938366.98     13906681.34      1938381.15     13906622.85
      1938422.75     13906569.07      1938428.56     13906426.47
      1938511.60     13906338.31      1938523.94     13906314.56
      1938526.22     13905935.50      1938572.64     13905869.02
      1938578.83     13905776.58      1938618.91     13905727.17
      1938629.42     13905676.64      1938667.50     13905625.00
      1938629.45     13905573.35      1938616.86     13905518.96
      1938530.87     13905427.28      1938516.80     13905368.95
      1938432.81     13905278.41      1938436.33     13905265.15
      1938472.44     13905219.11      1938478.85     13905126.60
      1938522.78     13905069.08      1938525.00     13904925.00

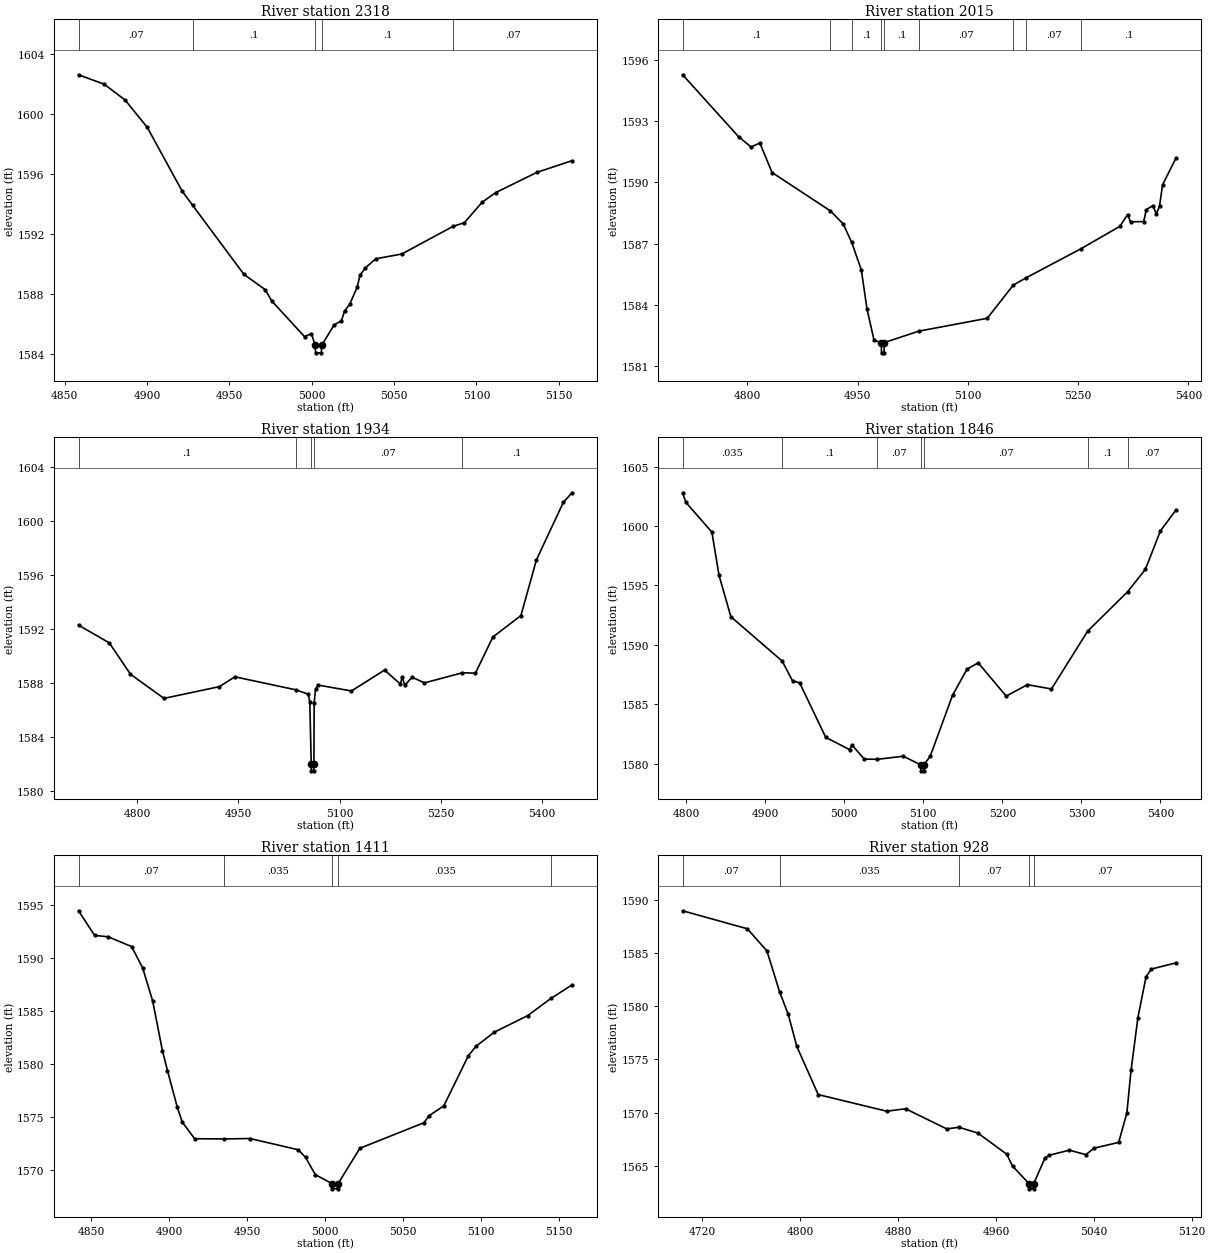
Type RM Length L Ch R = 1,2318,303,303,303
BEGIN DESCRIPTION:
Stream0575 5.0
END DESCRIPTION:
XS GIS Cut Line= 3
      1938274.99     13907024.99      1938175.00     13906925.00
      1938025.01     13906975.00
#Sta/Elev= 30
  4858.5 1602.62  4874.1 1601.99  4886.8 1600.93  4900.2 1599.11  4921.4 1594.85
  4927.7 1593.91  4958.9 1589.29  4971.7 1588.28  4975.9 1587.50  4995.7 1585.13
  4999.9 1585.34  5002.1 1584.55  5002.4 1584.05  5005.9 1584.05  5006.1 1584.55
  5013.6 1585.91  5018.1 1586.19  5020.0 1586.85  5023.1 1587.29  5027.6 1588.43
  5029.4 1589.24  5032.6 1589.72  5038.9 1590.33  5054.7 1590.65  5085.9 1592.50
  5092.7 1592.74  5103.5 1594.11  5111.7 1594.75  5136.7 1596.10  5158.0 1596.88
#Mann=5,-1,0
  4858.5    0.07       0  4927.7     0.1       0  5002.1    0.05       0
  5006.1     0.1       0  5085.9    0.07       0
Bank Sta=5002.1,5006.1
Exp/Cntr=0.3,0.1

Type RM Length L Ch R = 1,2015,81,81,81
BEGIN DESCRIPTION:
Mapping XS c4dd139d
END DESCRIPTION:
XS GIS Cut Line= 2
      1938578.83     13906869.44      1938017.10     13906502.60
#Sta/Elev= 30
  4712.2 1595.26  4788.3 1592.23  4805.2 1591.73  4817.2 1591.92  4833.8 1590.48
  4913.2 1588.60  4930.6 1587.96  4942.1 1587.06  4955.2 1585.71  4962.8 1583.82
  4972.5 1582.27  4982.3 1582.16  4982.6 1581.66  4986.1 1581.66  4986.3 1582.16
  5033.2 1582.72  5126.4 1583.35  5161.7 1584.97  5179.2 1585.33  5254.3 1586.76
  5306.8 1587.85  5317.1 1588.42  5321.2 1588.07  5339.1 1588.08  5342.7 1588.67
  5351.8 1588.86  5356.2 1588.45  5360.6 1588.83  5364.8 1589.88  5383.1 1591.19
#Mann=9,-1,0
  4712.2     0.1       0  4913.2    0.07       0  4942.1     0.1       0
  4982.3    0.05       0  4986.3     0.1       0  5033.2    0.07       0
  5161.7     0.1       0  5179.2    0.07       0  5254.3     0.1       0
Bank Sta=4982.3,4986.3
Exp/Cntr=0.3,0.1

Type RM Length L Ch R = 1,1934,88,88,88
BEGIN DESCRIPTION:
Stream0575 4.1
END DESCRIPTION:
XS GIS Cut Line= 4
      1938588.91     13906835.88      1938397.90     13906663.32
      1938286.14     13906567.83      1938083.25     13906311.78
#Sta/Elev= 30
  4713.3 1592.28  4759.0 1590.96  4790.3 1588.64  4839.9 1586.85  4922.0 1587.72
  4945.0 1588.45  5034.8 1587.49  5053.9 1587.16  5056.0 1586.56  5058.1 1581.98
  5058.3 1581.48  5061.8 1581.48  5062.1 1581.98  5062.4 1586.50  5064.5 1587.52
  5068.0 1587.84  5117.7 1587.40  5166.8 1588.95  5190.3 1587.91  5192.8 1588.46
  5196.7 1587.81  5207.4 1588.42  5225.9 1588.00  5282.1 1588.75  5301.4 1588.72
  5327.3 1591.40  5368.8 1592.99  5391.8 1597.12  5431.6 1601.37  5444.4 1602.09
#Mann=5,-1,0
  4713.3     0.1       0  5034.8    0.07       0  5058.1    0.05       0
  5062.1    0.07       0  5282.1     0.1       0
Bank Sta=5058.1,5062.1
Exp/Cntr=0.3,0.1

Type RM Length L Ch R = 1,1846,435,435,435
BEGIN DESCRIPTION:
Stream0575 4.0
END DESCRIPTION:
XS GIS Cut Line= 3
      1938624.99     13906575.00      1938425.00     13906575.00
      1938125.04     13906275.04
#Sta/Elev= 30
  4795.5 1602.80  4799.5 1602.00  4832.5 1599.49  4841.5 1595.86  4856.5 1592.37
  4921.5 1588.63  4934.5 1586.97  4943.5 1586.81  4976.5 1582.22  5006.8 1581.18
  5009.6 1581.59  5025.2 1580.39  5041.9 1580.37  5074.7 1580.63  5096.7 1579.90
  5097.0 1579.40  5100.5 1579.40  5100.7 1579.90  5108.7 1580.63  5136.9 1585.75
  5155.3 1587.96  5169.4 1588.49  5204.8 1585.69  5231.7 1586.65  5262.1 1586.29
  5307.9 1591.16  5358.4 1594.47  5380.9 1596.36  5400.0 1599.60  5419.7 1601.36
#Mann=7,-1,0
  4795.5   0.035       0  4921.5     0.1       0  5041.9    0.07       0
  5096.7    0.05       0  5100.7    0.07       0  5307.9     0.1       0
  5358.4    0.07       0
Bank Sta=5096.7,5100.7
Exp/Cntr=0.3,0.1

Type RM Length L Ch R = 1,1411,483,483,483
BEGIN DESCRIPTION:
Stream0575 3.0
END DESCRIPTION:
XS GIS Cut Line= 3
      1938675.02     13906225.01      1938525.00     13906175.00
      1938375.05     13906125.02
#Sta/Elev= 30
  4841.9 1594.44  4852.2 1592.12  4860.9 1591.99  4875.9 1591.07  4883.0 1589.06
  4889.4 1585.95  4895.7 1581.24  4898.9 1579.39  4905.2 1575.93  4908.4 1574.53
  4916.3 1572.97  4935.0 1572.95  4951.8 1572.99  4982.7 1571.93  4987.4 1571.21
  4993.7 1569.58  5004.3 1568.75  5004.6 1568.25  5008.1 1568.25  5008.3 1568.75
  5022.2 1572.07  5063.3 1574.48  5066.5 1575.13  5076.0 1576.07  5091.7 1580.78
  5096.5 1581.66  5108.4 1583.01  5129.7 1584.56  5144.6 1586.18  5158.1 1587.45
#Mann=5,-1,0
  4841.9    0.07       0  4935.0   0.035       0  5004.3   0.035       0
  5008.3   0.035       0  5144.6    0.07       0
Bank Sta=5004.3,5008.3
Exp/Cntr=0.3,0.1

Type RM Length L Ch R = 1,928,409,409,409
BEGIN DESCRIPTION:
Stream0575 2.0
END DESCRIPTION:
XS GIS Cut Line= 3
      1938875.01     13905875.01      1938625.00     13905725.00
      1938525.06     13905675.03
#Sta/Elev= 30
  4703.9 1588.95  4756.8 1587.26  4772.8 1585.18  4783.2 1581.32  4790.2 1579.23
  4797.2 1576.22  4814.7 1571.69  4870.7 1570.13  4886.1 1570.36  4919.7 1568.47
  4929.7 1568.62  4945.2 1568.08  4968.7 1566.10  4973.6 1564.97  4986.9 1563.34
  4987.2 1562.84  4990.7 1562.84  4990.9 1563.34  4999.9 1565.69  5003.3 1565.99
  5020.0 1566.47  5033.5 1566.05  5040.2 1566.66  5060.3 1567.20  5067.0 1569.97
  5070.4 1573.96  5076.0 1578.90  5082.7 1582.77  5087.1 1583.48  5107.2 1584.06
#Mann=5,-1,0
  4703.9    0.07       0  4783.2   0.035       0  4929.7    0.07       0
  4986.9    0.05       0  4990.9    0.07       0
Bank Sta=4986.9,4990.9
Exp/Cntr=0.3,0.1

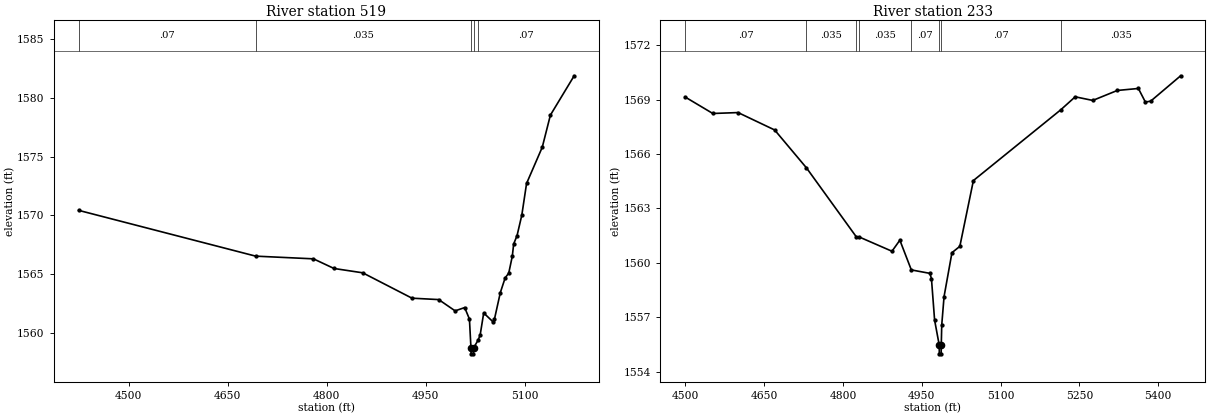
Type RM Length L Ch R = 1,519,286,286,286
BEGIN DESCRIPTION:
Stream0575 1.0
END DESCRIPTION:
XS GIS Cut Line= 3
      1939075.03     13905224.99      1938525.00     13905375.00
      1938425.00     13905525.00
#Sta/Elev= 30
  4424.4 1570.42  4692.5 1566.52  4780.0 1566.29  4811.1 1565.47  4854.6 1565.10
  4929.2 1562.94  4969.7 1562.82  4994.5 1561.86  5009.0 1562.14  5016.2 1561.16
  5018.5 1558.70  5018.8 1558.20  5022.3 1558.20  5022.5 1558.70  5029.3 1559.37
  5032.4 1559.79  5037.8 1561.68  5052.2 1560.91  5054.1 1561.16  5063.0 1563.42
  5070.3 1564.67  5075.7 1565.07  5081.1 1566.51  5083.2 1567.56  5088.3 1568.27
  5095.5 1570.01  5102.7 1572.71  5126.5 1575.80  5138.8 1578.53  5174.8 1581.88
#Mann=5,-1,0
  4424.4    0.07       0  4692.5   0.035       0  5018.5   0.035       0
  5022.5   0.035       0  5029.3    0.07       0
Bank Sta=5018.5,5022.5
Exp/Cntr=0.3,0.1

Type RM Length L Ch R = 1,233,0,0,0
BEGIN DESCRIPTION:
Stream0575 0.0
END DESCRIPTION:
XS GIS Cut Line= 4
      1938974.31     13905178.81      1938551.45     13905145.55
      1938385.04     13905137.80      1938068.72     13905292.32
#Sta/Elev= 30
  4499.8 1569.15  4552.5 1568.24  4600.6 1568.29  4670.2 1567.33  4730.7 1565.24
  4825.4 1561.44  4831.6 1561.42  4893.4 1560.64  4908.4 1561.25  4930.2 1559.61
  4965.5 1559.42  4968.5 1559.13  4974.5 1556.84  4983.2 1555.48  4983.5 1554.98
  4987.0 1554.98  4987.2 1555.48  4988.1 1556.58  4992.5 1558.14  5007.5 1560.56
  5022.5 1560.91  5048.3 1564.54  5214.4 1568.44  5242.0 1569.16  5275.4 1568.96
  5322.1 1569.51  5362.2 1569.62  5375.5 1568.87  5385.6 1568.92  5442.6 1570.32
#Mann=8,-1,0
  4499.8    0.07       0  4730.7   0.035       0  4825.4     0.1       0
  4831.6   0.035       0  4930.2    0.07       0  4983.2    0.05       0
  4987.2    0.07       0  5214.4   0.035       0
Bank Sta=4983.2,4987.2
Exp/Cntr=0.3,0.1

Chan Stop Cuts=-1