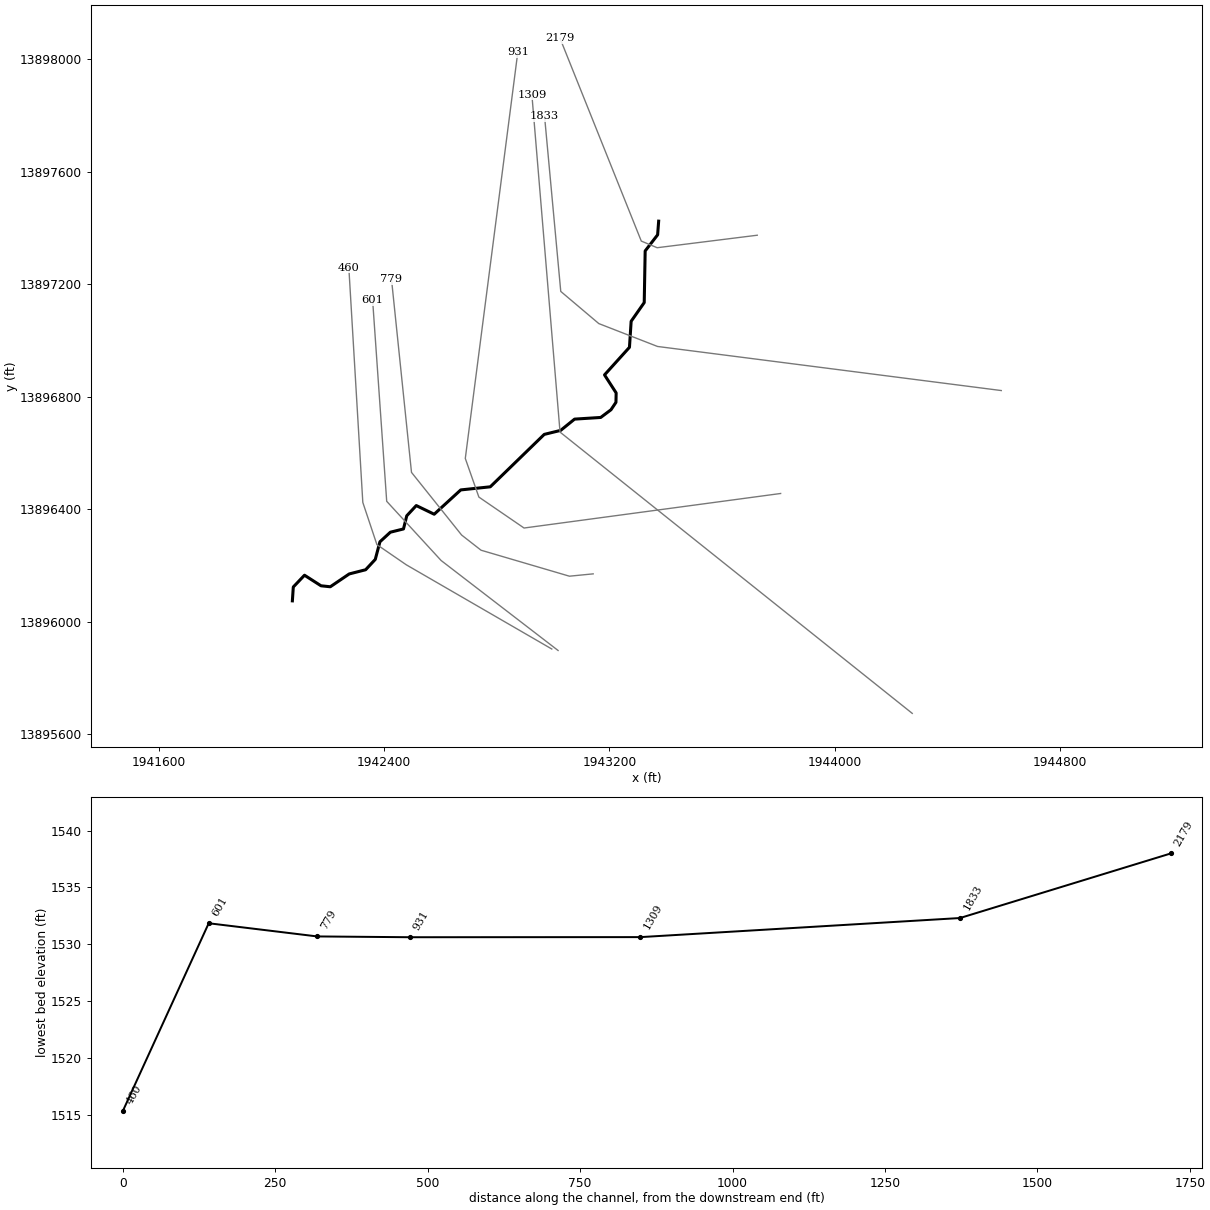
--- Stream0576.prj (project) ---

Proj Title=Stream0576 Base Level Engineering
Current Plan=p01
Default Exp/Contr=0.3,0.1
English Units
Geom File=g01
Flow File=f01
Plan File=p01
BEGIN DESCRIPTION:
Stream0576
END DESCRIPTION:

--- Stream0576.p01 (plan) ---

Plan Title=Multiple Run
Short Identifier=Multiple
Geom File=g01
Flow File=f01
Subcritical Flow
K Sum by GR= 0
Std Step Tol= 0.01
Critical Tol= 0.01
Num of Std Step Trials= 20
Max Error Tol= 0.3
Flow Tol Ratio= 0.001
Split Flow NTrial= 30
Split Flow Tol= 0.02
Split Flow Ratio= 0.02
Log Output Level= 0
Friction Slope Method= 1
Unsteady Friction Slope Method= 2
Unsteady Bridges Friction Slope Method= 1
Parabolic Critical Depth
Global Vel Dist=  1 , 1 , 1
Global Log Level= 0
CheckData=True
Encroach Param= -1, 0, 0, 0
BEGIN DESCRIPTION:
Multiple Run
END DESCRIPTION:

--- Stream0576.f01 (steady flow) ---

Flow Title=Multiple
Number of Profiles=7
Profile Names=10-year,25-year,50-year,1pct_min,100-year,1pct_plu,500-year
River Rch & RM= Stream0576,Reach-1,2179
    1627    2822    3979    2710    5408   10790    9866
Boundary for River Rch & Prof#=Stream0576,Reach-1,1
Up Type=0
Dn Type=3
Dn Slope=0.005
Boundary for River Rch & Prof#=Stream0576,Reach-1,2
Up Type=0
Dn Type=3
Dn Slope=0.005
Boundary for River Rch & Prof#=Stream0576,Reach-1,3
Up Type=0
Dn Type=3
Dn Slope=0.005
Boundary for River Rch & Prof#=Stream0576,Reach-1,4
Up Type=0
Dn Type=3
Dn Slope=0.005
Boundary for River Rch & Prof#=Stream0576,Reach-1,5
Up Type=0
Dn Type=3
Dn Slope=0.005
Boundary for River Rch & Prof#=Stream0576,Reach-1,6
Up Type=0
Dn Type=3
Dn Slope=0.005
Boundary for River Rch & Prof#=Stream0576,Reach-1,7
Up Type=0
Dn Type=3
Dn Slope=0.005

--- Stream0576.g01 (geometry) ---

Geom Title=Existing Conditions

River Reach=Stream0576,Reach-1
Reach XY= 30
      1943375.00     13897425.00      1943371.35     13897376.51
      1943327.13     13897319.12      1943323.78     13897135.50
      1943277.36     13897069.02      1943271.36     13896976.50
      1943182.84     13896878.40      1943224.13     13896814.31
      1943223.43     13896780.85      1943205.77     13896754.43
      1943169.34     13896727.08      1943076.59     13896721.17
      1943027.17     13896681.14      1942968.94     13896666.86
      1942777.43     13896480.52      1942672.57     13896469.45
      1942578.32     13896383.02      1942514.70     13896413.84
      1942480.99     13896377.50      1942469.35     13896330.70
      1942422.80     13896319.11      1942385.71     13896284.96
      1942369.24     13896222.49      1942335.00     13896185.63
      1942276.76     13896170.74      1942209.59     13896125.13
      1942176.62     13896128.60      1942118.04     13896166.19
      1942078.27     13896124.37      1942075.00     13896075.00

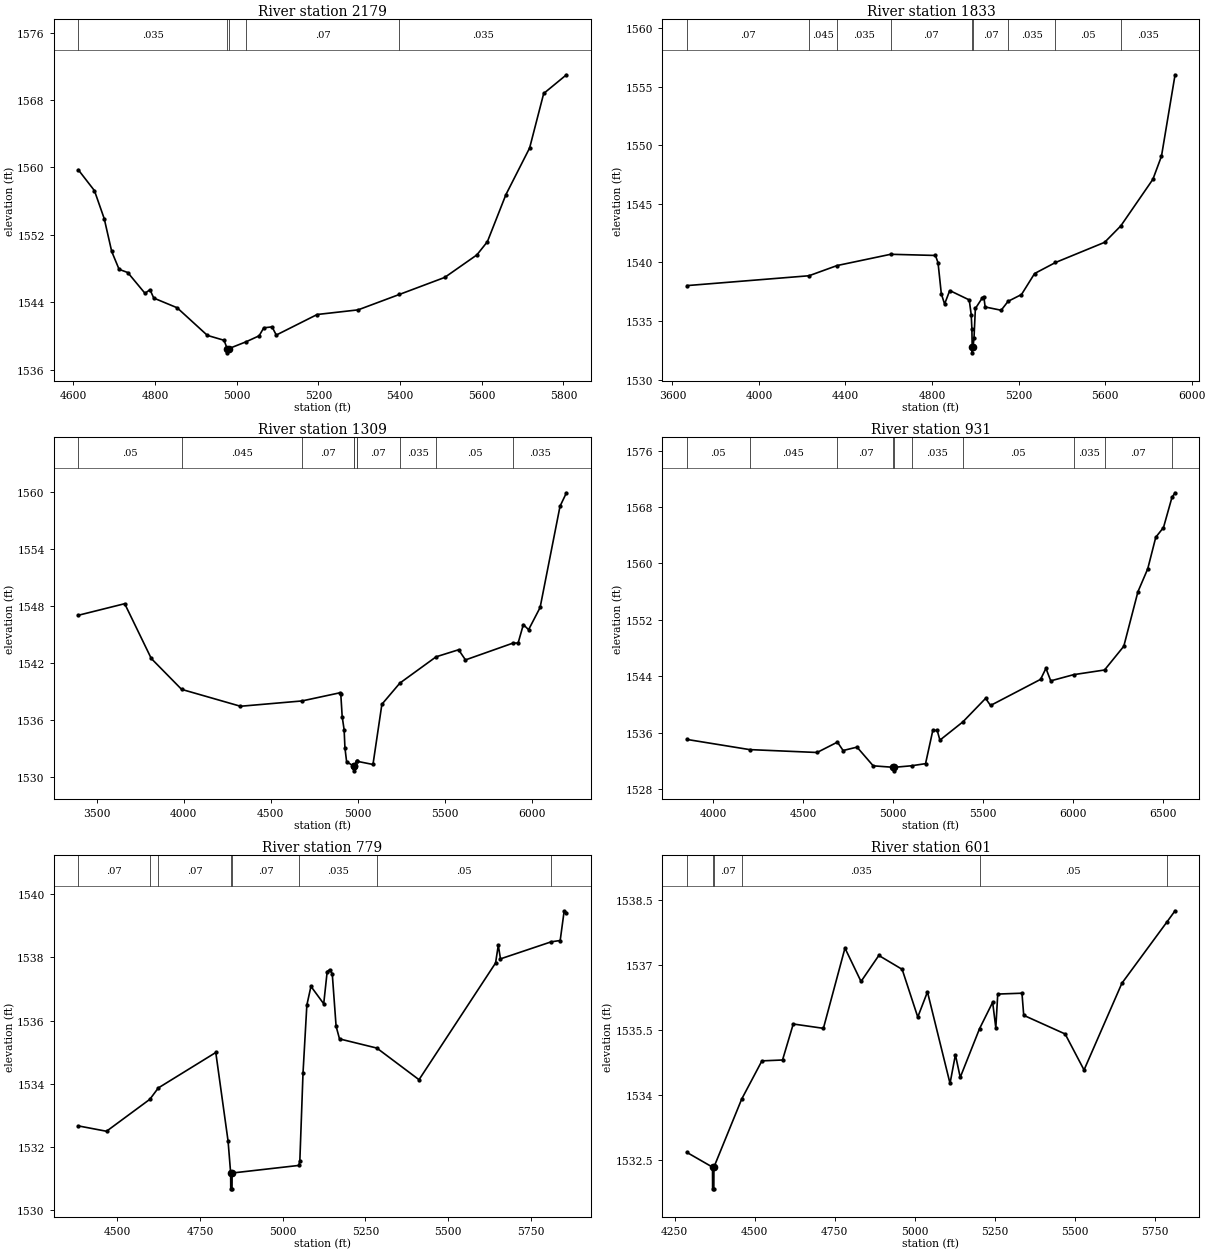
Type RM Length L Ch R = 1,2179,346,346,346
BEGIN DESCRIPTION:
Stream0576 4.0
END DESCRIPTION:
XS GIS Cut Line= 4
      1943724.98     13897375.00      1943369.59     13897330.57
      1943313.31     13897354.22      1943025.00     13898075.00
#Sta/Elev= 30
  4611.9 1559.72  4651.5 1557.24  4675.5 1553.91  4693.8 1550.02  4711.9 1547.90
  4733.1 1547.52  4775.4 1545.05  4787.5 1545.49  4796.8 1544.49  4854.0 1543.34
  4928.1 1540.06  4968.9 1539.48  4976.6 1538.49  4976.8 1537.99  4980.6 1538.49
  5022.8 1539.30  5054.8 1540.01  5066.2 1540.96  5086.5 1541.07  5096.8 1540.10
  5197.0 1542.54  5297.2 1543.09  5398.3 1544.92  5509.3 1546.94  5588.0 1549.61
  5613.8 1551.18  5659.1 1556.76  5717.2 1562.30  5751.7 1568.77  5807.4 1570.99
#Mann=5,-1,0
  4611.9   0.035       0  4976.6   0.035       0  4980.6   0.035       0
  5022.8    0.07       0  5398.3   0.035       0
Bank Sta=4976.6,4980.6
Exp/Cntr=0.3,0.1

Type RM Length L Ch R = 1,1833,524,524,524
BEGIN DESCRIPTION:
Stream0576 3.1
END DESCRIPTION:
XS GIS Cut Line= 5
      1944591.06     13896822.74      1943371.05     13896979.47
      1943162.60     13897060.82      1943027.54     13897175.21
      1942969.99     13897798.07
#Sta/Elev= 30
  3667.0 1538.03  4231.3 1538.87  4361.3 1539.74  4608.9 1540.70  4815.8 1540.60
  4827.8 1539.98  4843.0 1537.33  4858.1 1536.46  4881.9 1537.61  4972.0 1536.81
  4981.1 1535.56  4984.3 1534.34  4985.6 1532.80  4985.8 1532.30  4989.6 1532.80
  4994.0 1533.55  5000.4 1536.08  5032.3 1536.98  5039.5 1537.09  5045.5 1536.21
  5119.6 1535.93  5151.5 1536.69  5213.5 1537.27  5274.1 1539.06  5370.7 1540.00
  5597.8 1541.72  5672.5 1543.12  5820.8 1547.09  5860.5 1549.06  5923.3 1556.00
#Mann=9,-1,0
  3667.0    0.07       0  4231.3   0.045       0  4361.3   0.035       0
  4608.9    0.07       0  4985.6    0.05       0  4989.6    0.07       0
  5151.5   0.035       0  5370.7    0.05       0  5672.5   0.035       0
Bank Sta=4985.6,4989.6
Exp/Cntr=0.3,0.1

Type RM Length L Ch R = 1,1309,378,378,378
BEGIN DESCRIPTION:
Stream0576 3.0
END DESCRIPTION:
XS GIS Cut Line= 3
      1944275.02     13895674.98      1943025.00     13896675.00
      1942925.00     13897875.03
#Sta/Elev= 30
  3394.3 1547.00  3661.1 1548.22  3813.8 1542.45  3988.0 1539.20  4326.4 1537.42
  4679.7 1537.98  4898.1 1538.84  4902.7 1538.72  4910.8 1536.32  4921.9 1534.95
  4926.7 1533.02  4936.3 1531.57  4976.8 1531.12  4977.0 1530.62  4980.9 1531.12
  4993.1 1531.64  4995.1 1531.63  5087.7 1531.29  5138.9 1537.63  5242.3 1539.86
  5450.6 1542.63  5579.7 1543.37  5619.1 1542.30  5892.1 1544.07  5921.6 1544.08
  5951.7 1546.02  5981.8 1545.48  6048.0 1547.82  6162.4 1558.48  6199.3 1559.90
#Mann=10,-1,0
  3394.3    0.05       0  3988.0   0.045       0  4679.7    0.07       0
  4976.8    0.05       0  4980.9    0.07       0  4993.1   0.045       0
  4995.1    0.07       0  5242.3   0.035       0  5450.6    0.05       0
  5892.1   0.035       0
Bank Sta=4976.8,4980.9
Exp/Cntr=0.3,0.1

Type RM Length L Ch R = 1,931,152,152,152
BEGIN DESCRIPTION:
Stream0576 2.0
END DESCRIPTION:
XS GIS Cut Line= 5
      1943807.92     13896456.76      1942897.23     13896333.99
      1942736.88     13896444.06      1942688.73     13896581.39
      1942875.00     13898024.98
#Sta/Elev= 30
  3853.8 1535.06  4202.3 1533.62  4577.7 1533.21  4690.9 1534.68  4722.4 1533.49
  4799.9 1533.97  4889.8 1531.32  5002.5 1531.11  5002.7 1530.61  5006.6 1531.11
  5103.7 1531.33  5180.9 1531.63  5221.5 1536.36  5245.7 1536.33  5260.8 1534.96
  5388.6 1537.55  5514.9 1540.88  5542.2 1539.87  5820.4 1543.57  5850.3 1545.13
  5877.1 1543.36  6004.7 1544.24  6176.2 1544.90  6283.2 1548.26  6362.0 1556.00
  6416.3 1559.23  6461.1 1563.71  6504.0 1565.09  6551.1 1569.36  6568.3 1570.01
#Mann=10,-1,0
  3853.8    0.05       0  4202.3   0.045       0  4690.9    0.07       0
  5002.5    0.05       0  5006.6    0.07       0  5103.7   0.035       0
  5388.6    0.05       0  6004.7   0.035       0  6176.2    0.07       0
  6551.1   0.035       0
Bank Sta=5002.5,5006.6
Exp/Cntr=0.3,0.1

Type RM Length L Ch R = 1,779,178,178,178
BEGIN DESCRIPTION:
Mapping XS 8c831a20
END DESCRIPTION:
XS GIS Cut Line= 6
      1943142.61     13896171.01      1943058.27     13896162.71
      1942744.67     13896255.05      1942675.69     13896309.01
      1942497.77     13896531.80      1942426.84     13897217.99
#Sta/Elev= 30
  4382.7 1532.67  4468.0 1532.50  4598.8 1533.51  4624.5 1533.87  4798.0 1534.99
  4835.1 1532.19  4842.9 1531.18  4843.2 1530.68  4847.0 1530.68  4847.3 1531.18
  5048.6 1531.42  5051.8 1531.56  5061.4 1534.34  5073.0 1536.49  5085.4 1537.08
  5123.9 1536.53  5134.4 1537.55  5142.1 1537.61  5149.7 1537.48  5161.3 1535.82
  5171.6 1535.42  5284.3 1535.13  5411.7 1534.13  5642.9 1537.82  5651.1 1538.38
  5657.7 1537.95  5811.3 1538.49  5838.0 1538.53  5850.1 1539.47  5856.9 1539.41
#Mann=8,-1,0
  4382.7    0.07       0  4598.8   0.045       0  4624.5    0.07       0
  4842.9    0.05       0  4847.3    0.07       0  5048.6   0.035       0
  5284.3    0.05       0  5811.3   0.035       0
Bank Sta=4842.9,4847.3
Exp/Cntr=0.3,0.1

Type RM Length L Ch R = 1,601,141,141,141
BEGIN DESCRIPTION:
Stream0576 0.0
END DESCRIPTION:
XS GIS Cut Line= 4
      1943018.03     13895898.56      1942602.93     13896218.47
      1942409.79     13896428.98      1942359.88     13897142.98
#Sta/Elev= 30
  4287.8 1532.68  4367.9 1532.34  4368.2 1531.84  4372.0 1531.84  4372.3 1532.34
  4459.1 1533.91  4522.3 1534.79  4586.7 1534.81  4620.2 1535.64  4714.4 1535.54
  4781.8 1537.39  4832.0 1536.62  4887.6 1537.22  4960.5 1536.90  5009.3 1535.80
  5039.6 1536.38  5110.1 1534.27  5126.9 1534.93  5142.0 1534.41  5202.2 1535.53
  5243.3 1536.14  5253.2 1535.55  5259.2 1536.33  5334.9 1536.35  5340.4 1535.84
  5469.8 1535.41  5528.9 1534.58  5647.2 1536.58  5787.7 1537.99  5813.3 1538.25
#Mann=6,-1,0
  4287.8    0.07       0  4367.9   0.035       0  4372.3    0.07       0
  4459.1   0.035       0  5202.2    0.05       0  5787.7   0.035       0
Bank Sta=4367.9,4372.3
Exp/Cntr=0.3,0.1

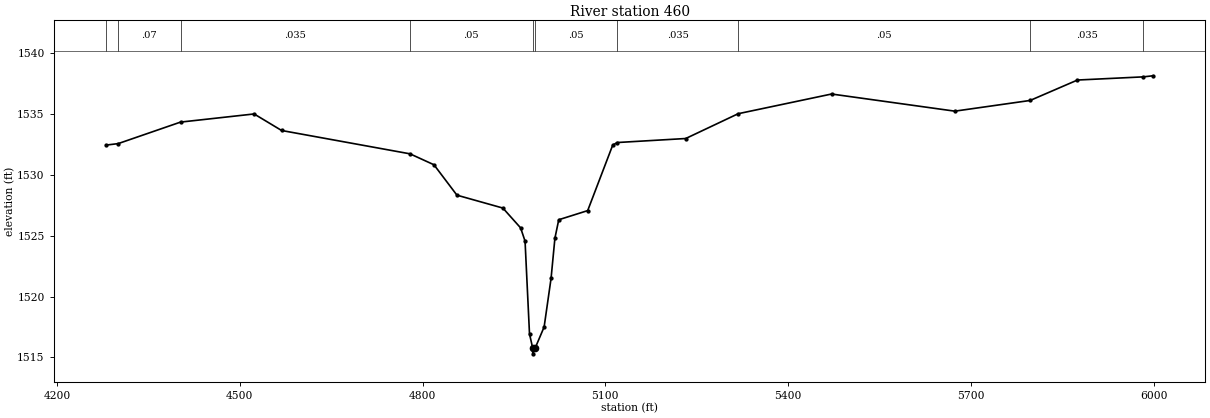
Type RM Length L Ch R = 1,460,0,0,0
BEGIN DESCRIPTION:
Stream0576 1.0
END DESCRIPTION:
XS GIS Cut Line= 5
      1942995.74     13895903.80      1942479.23     13896203.28
      1942375.00     13896275.00      1942325.00     13896425.00
      1942275.35     13897260.14
#Sta/Elev= 30
  4280.8 1532.46  4300.4 1532.58  4402.8 1534.35  4523.6 1535.02  4568.7 1533.66
  4779.5 1531.74  4818.8 1530.84  4856.5 1528.34  4931.9 1527.28  4961.0 1525.65
  4968.3 1524.56  4975.6 1516.93  4980.7 1515.79  4981.0 1515.29  4985.1 1515.79
  4999.6 1517.50  5011.0 1521.50  5017.3 1524.80  5023.6 1526.32  5071.1 1527.07
  5112.2 1532.46  5119.7 1532.67  5232.0 1533.00  5318.1 1535.04  5471.4 1536.66
  5673.7 1535.25  5797.3 1536.13  5875.0 1537.81  5982.7 1538.07  5999.1 1538.16
#Mann=10,-1,0
  4280.8   0.035       0  4300.4    0.07       0  4402.8   0.035       0
  4779.5    0.05       0  4980.7    0.05       0  4985.1    0.05       0
  5119.7   0.035       0  5318.1    0.05       0  5797.3   0.035       0
  5982.7    0.05       0
Bank Sta=4980.7,4985.1
Exp/Cntr=0.3,0.1

Chan Stop Cuts=-1