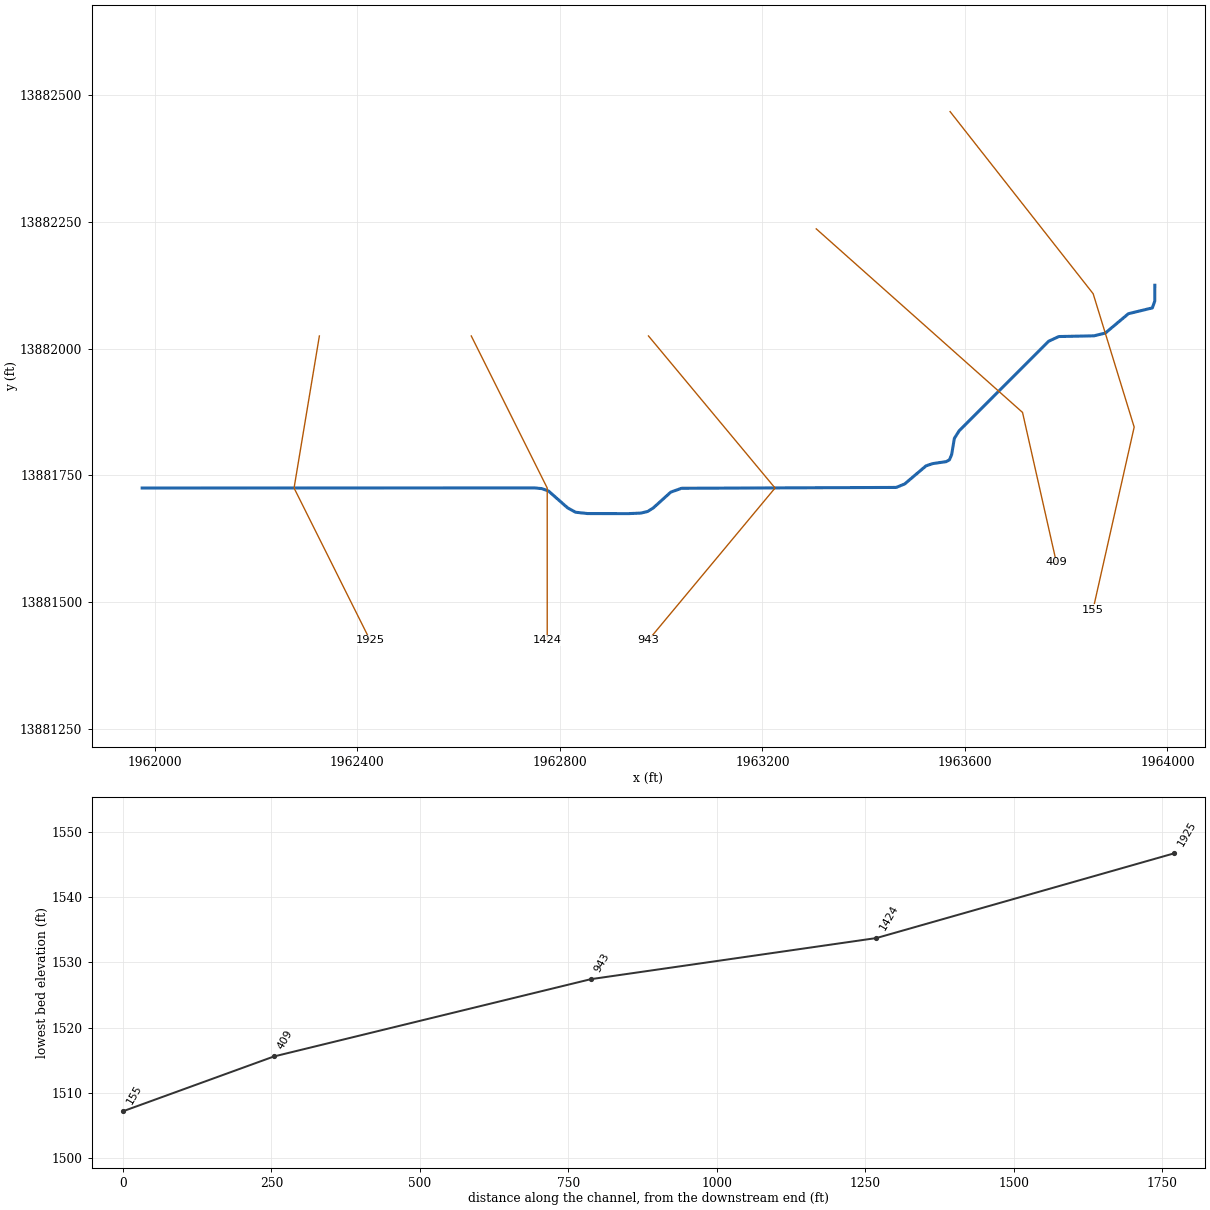
--- Stream0578.prj (project) ---

Proj Title=Stream0578 Base Level Engineering
Current Plan=p01
Default Exp/Contr=0.3,0.1
English Units
Geom File=g01
Flow File=f01
Plan File=p01
BEGIN DESCRIPTION:
Stream0578
END DESCRIPTION:

--- Stream0578.p01 (plan) ---

Plan Title=Multiple Run
Short Identifier=Multiple
Geom File=g01
Flow File=f01
Subcritical Flow
K Sum by GR= 0
Std Step Tol= 0.01
Critical Tol= 0.01
Num of Std Step Trials= 20
Max Error Tol= 0.3
Flow Tol Ratio= 0.001
Split Flow NTrial= 30
Split Flow Tol= 0.02
Split Flow Ratio= 0.02
Log Output Level= 0
Friction Slope Method= 1
Unsteady Friction Slope Method= 2
Unsteady Bridges Friction Slope Method= 1
Parabolic Critical Depth
Global Vel Dist=  1 , 1 , 1
Global Log Level= 0
CheckData=True
Encroach Param= -1, 0, 0, 0
BEGIN DESCRIPTION:
Multiple Run
END DESCRIPTION:

--- Stream0578.f01 (steady flow) ---

Flow Title=Multiple
Number of Profiles=7
Profile Names=10-year,25-year,50-year,1pct_min,100-year,1pct_plu,500-year
River Rch & RM= Stream0578,Reach-1,1925
     536     871    1178     774    1544    3080    2609
Boundary for River Rch & Prof#=Stream0578,Reach-1,1
Up Type=0
Dn Type=3
Dn Slope=0.005
Boundary for River Rch & Prof#=Stream0578,Reach-1,2
Up Type=0
Dn Type=3
Dn Slope=0.005
Boundary for River Rch & Prof#=Stream0578,Reach-1,3
Up Type=0
Dn Type=3
Dn Slope=0.005
Boundary for River Rch & Prof#=Stream0578,Reach-1,4
Up Type=0
Dn Type=3
Dn Slope=0.005
Boundary for River Rch & Prof#=Stream0578,Reach-1,5
Up Type=0
Dn Type=3
Dn Slope=0.005
Boundary for River Rch & Prof#=Stream0578,Reach-1,6
Up Type=0
Dn Type=3
Dn Slope=0.005
Boundary for River Rch & Prof#=Stream0578,Reach-1,7
Up Type=0
Dn Type=3
Dn Slope=0.005

--- Stream0578.g01 (geometry) ---

Geom Title=Existing Conditions

River Reach=Stream0578,Reach-1
Reach XY= 30
      1961975.00     13881725.00      1962750.08     13881725.20
      1962764.50     13881723.78      1962777.33     13881719.25
      1962815.36     13881685.85      1962830.94     13881677.25
      1962854.87     13881674.61      1962935.17     13881674.50
      1962959.78     13881675.51      1962973.43     13881678.77
      1962984.64     13881685.85      1963018.94     13881716.86
      1963040.22     13881724.48      1963464.52     13881726.19
      1963481.12     13881733.08      1963523.16     13881768.72
      1963536.09     13881773.12      1963562.99     13881777.07
      1963569.39     13881780.59      1963573.85     13881791.02
      1963579.13     13881822.99      1963588.73     13881837.98
      1963765.21     13882014.48      1963785.48     13882023.84
      1963854.91     13882025.23      1963877.36     13882030.74
      1963923.00     13882068.96      1963970.10     13882080.28
      1963974.94     13882093.44      1963975.00     13882125.00

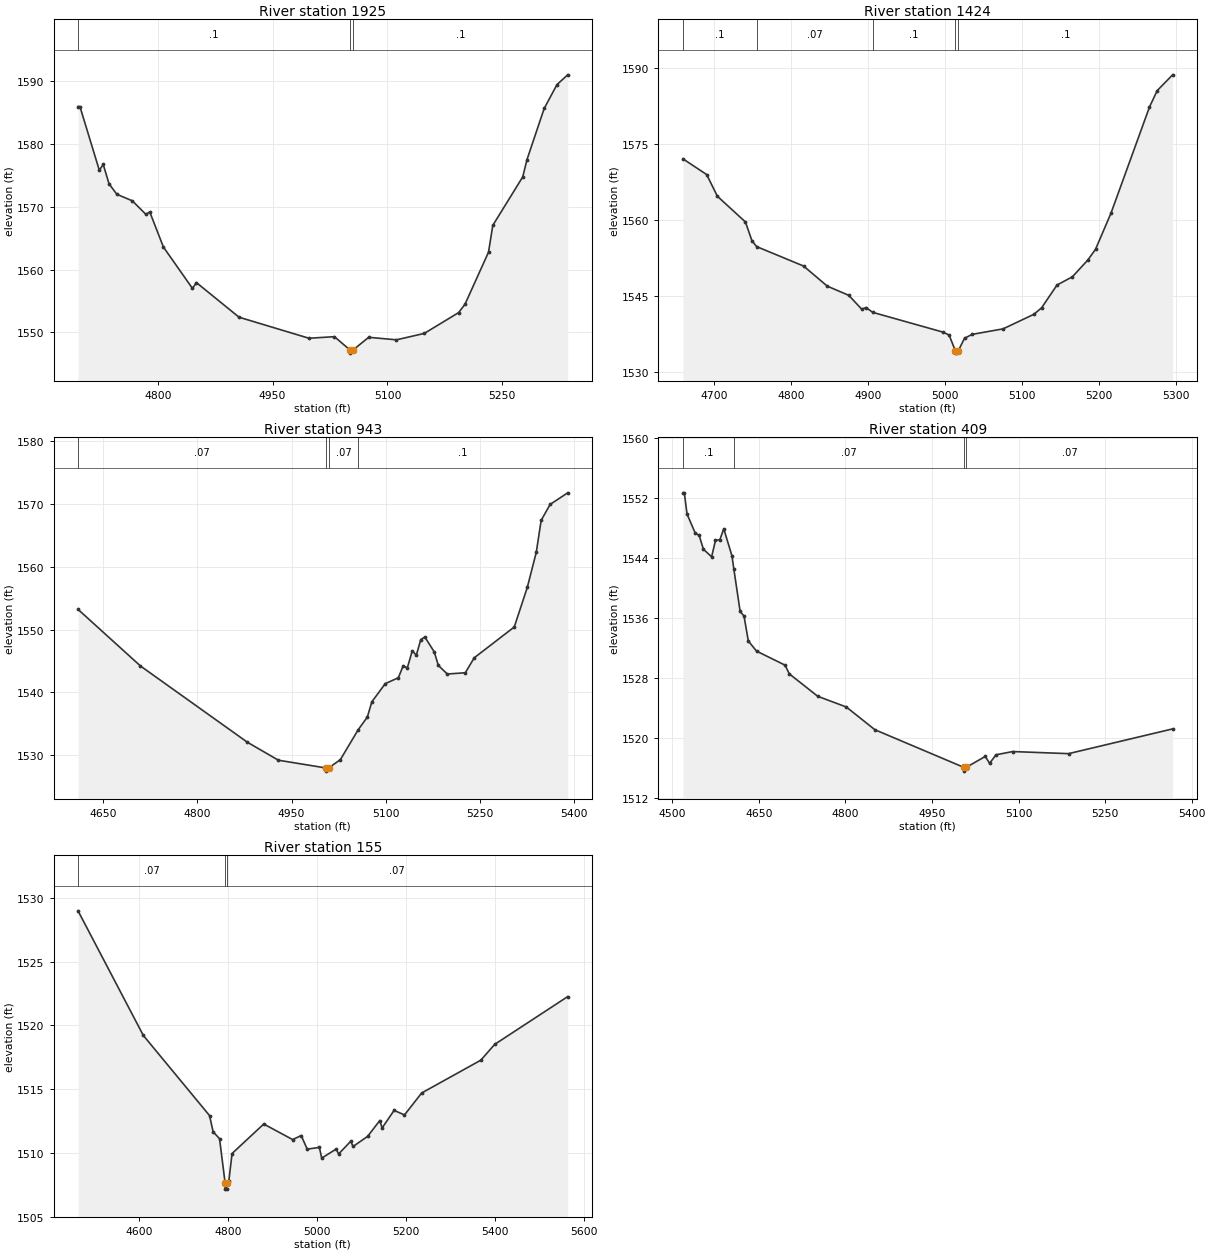
Type RM Length L Ch R = 1,1925,501,501,501
BEGIN DESCRIPTION:
Stream0578 3.0
END DESCRIPTION:
XS GIS Cut Line= 3
      1962324.99     13882024.97      1962275.00     13881725.00
      1962424.99     13881425.01
#Sta/Elev= 30
  4695.9 1585.96  4698.4 1585.96  4723.7 1575.82  4728.8 1576.75  4736.4 1573.66
  4746.6 1571.99  4766.8 1570.95  4784.6 1568.79  4789.6 1569.18  4807.4 1563.59
  4845.4 1556.99  4850.5 1557.93  4906.2 1552.41  4997.5 1549.06  5030.8 1549.31
  5051.1 1547.19  5051.4 1546.69  5055.1 1547.19  5075.5 1549.21  5111.8 1548.81
  5148.1 1549.83  5192.9 1553.14  5201.3 1554.48  5232.0 1562.77  5237.6 1567.04
  5276.7 1574.76  5282.3 1577.53  5304.7 1585.66  5321.4 1589.46  5335.4 1591.02
#Mann=3,-1,0
  4695.9     0.1       0  5051.1    0.05       0  5055.1     0.1       0
Bank Sta=5051.1,5055.1
Exp/Cntr=0.3,0.1

Type RM Length L Ch R = 1,1424,481,481,481
BEGIN DESCRIPTION:
Stream0578 2.0
END DESCRIPTION:
XS GIS Cut Line= 3
      1962624.99     13882025.02      1962775.00     13881725.00
      1962775.00     13881425.03
#Sta/Elev= 30
  4660.0 1572.09  4690.8 1568.98  4704.7 1564.70  4741.1 1559.62  4749.5 1555.93
  4755.6 1554.76  4816.5 1550.92  4847.3 1546.95  4875.2 1545.13  4892.0 1542.39
  4897.6 1542.73  4906.3 1541.77  4997.9 1537.85  5005.4 1537.28  5013.4 1534.22
  5013.7 1533.72  5017.4 1534.22  5025.4 1536.66  5035.4 1537.43  5075.4 1538.51
  5115.4 1541.39  5125.4 1542.67  5145.4 1547.17  5165.4 1548.80  5185.4 1552.11
  5195.4 1554.23  5215.4 1561.34  5265.4 1582.32  5275.4 1585.56  5295.4 1588.68
#Mann=5,-1,0
  4660.0     0.1       0  4755.6    0.07       0  4906.3     0.1       0
  5013.4    0.05       0  5017.4     0.1       0
Bank Sta=5013.4,5017.4
Exp/Cntr=0.3,0.1

Type RM Length L Ch R = 1,943,534,534,534
BEGIN DESCRIPTION:
Stream0578 1.0
END DESCRIPTION:
XS GIS Cut Line= 3
      1962975.00     13882025.00      1963225.00     13881725.00
      1962975.02     13881425.02
#Sta/Elev= 30
  4609.5 1553.22  4709.1 1544.19  4879.6 1532.03  4929.1 1529.16  5005.2 1527.92
  5005.4 1527.42  5009.2 1527.92  5028.0 1529.26  5056.2 1534.00  5071.0 1536.05
  5078.1 1538.47  5099.6 1541.38  5120.4 1542.31  5128.2 1544.24  5134.7 1543.88
  5142.6 1546.59  5149.1 1545.93  5156.2 1548.40  5162.7 1548.81  5177.7 1546.43
  5184.2 1544.28  5198.5 1542.91  5227.2 1543.11  5241.5 1545.50  5305.3 1550.41
  5326.1 1556.73  5340.4 1562.32  5348.2 1567.42  5362.5 1569.96  5390.5 1571.81
#Mann=4,-1,0
  4609.5    0.07       0  5005.2    0.05       0  5009.2    0.07       0
  5056.2     0.1       0
Bank Sta=5005.2,5009.2
Exp/Cntr=0.3,0.1

Type RM Length L Ch R = 1,409,254,254,254
BEGIN DESCRIPTION:
Stream0578 0.0
END DESCRIPTION:
XS GIS Cut Line= 3
      1963306.40     13882236.24      1963713.79     13881874.13
      1963780.66     13881578.14
#Sta/Elev= 30
  4518.5 1552.67  4520.9 1552.67  4525.6 1549.84  4539.8 1547.30  4546.5 1547.01
  4554.0 1545.15  4568.2 1544.14  4574.9 1546.33  4582.5 1546.42  4589.2 1547.88
  4603.4 1544.28  4606.8 1542.46  4617.6 1536.85  4624.3 1536.25  4631.8 1532.92
  4646.0 1531.57  4695.4 1529.70  4702.9 1528.53  4752.2 1525.54  4801.6 1524.12
  4851.1 1521.09  5005.3 1516.07  5005.5 1515.57  5009.3 1516.07  5042.4 1517.53
  5049.9 1516.61  5061.0 1517.75  5090.0 1518.18  5186.7 1517.90  5367.0 1521.20
#Mann=4,-1,0
  4518.5     0.1       0  4606.8    0.07       0  5005.3    0.05       0
  5009.3    0.07       0
Bank Sta=5005.3,5009.3
Exp/Cntr=0.3,0.1

Type RM Length L Ch R = 1,155,0,0,0
BEGIN DESCRIPTION:
Stream0578 0.1
END DESCRIPTION:
XS GIS Cut Line= 4
      1963570.73     13882467.55      1963853.29     13882108.31
      1963934.29     13881845.19      1963852.80     13881484.23
#Sta/Elev= 30
  4461.7 1528.98  4608.7 1519.22  4757.8 1512.94  4765.9 1511.67  4780.3 1511.13
  4792.8 1507.68  4793.0 1507.18  4796.5 1507.18  4796.8 1507.68  4801.1 1507.78
  4808.5 1509.97  4879.8 1512.28  4945.0 1511.06  4964.1 1511.38  4977.7 1510.31
  5005.1 1510.45  5010.3 1509.61  5043.0 1510.32  5048.3 1509.93  5075.7 1510.93
  5080.9 1510.52  5113.6 1511.31  5141.1 1512.55  5146.3 1511.97  5173.3 1513.35
  5196.7 1512.99  5235.3 1514.71  5368.5 1517.28  5399.8 1518.52  5564.1 1522.26
#Mann=3,-1,0
  4461.7    0.07       0  4792.8    0.05       0  4796.8    0.07       0
Bank Sta=4792.8,4796.8
Exp/Cntr=0.3,0.1

Chan Stop Cuts=-1