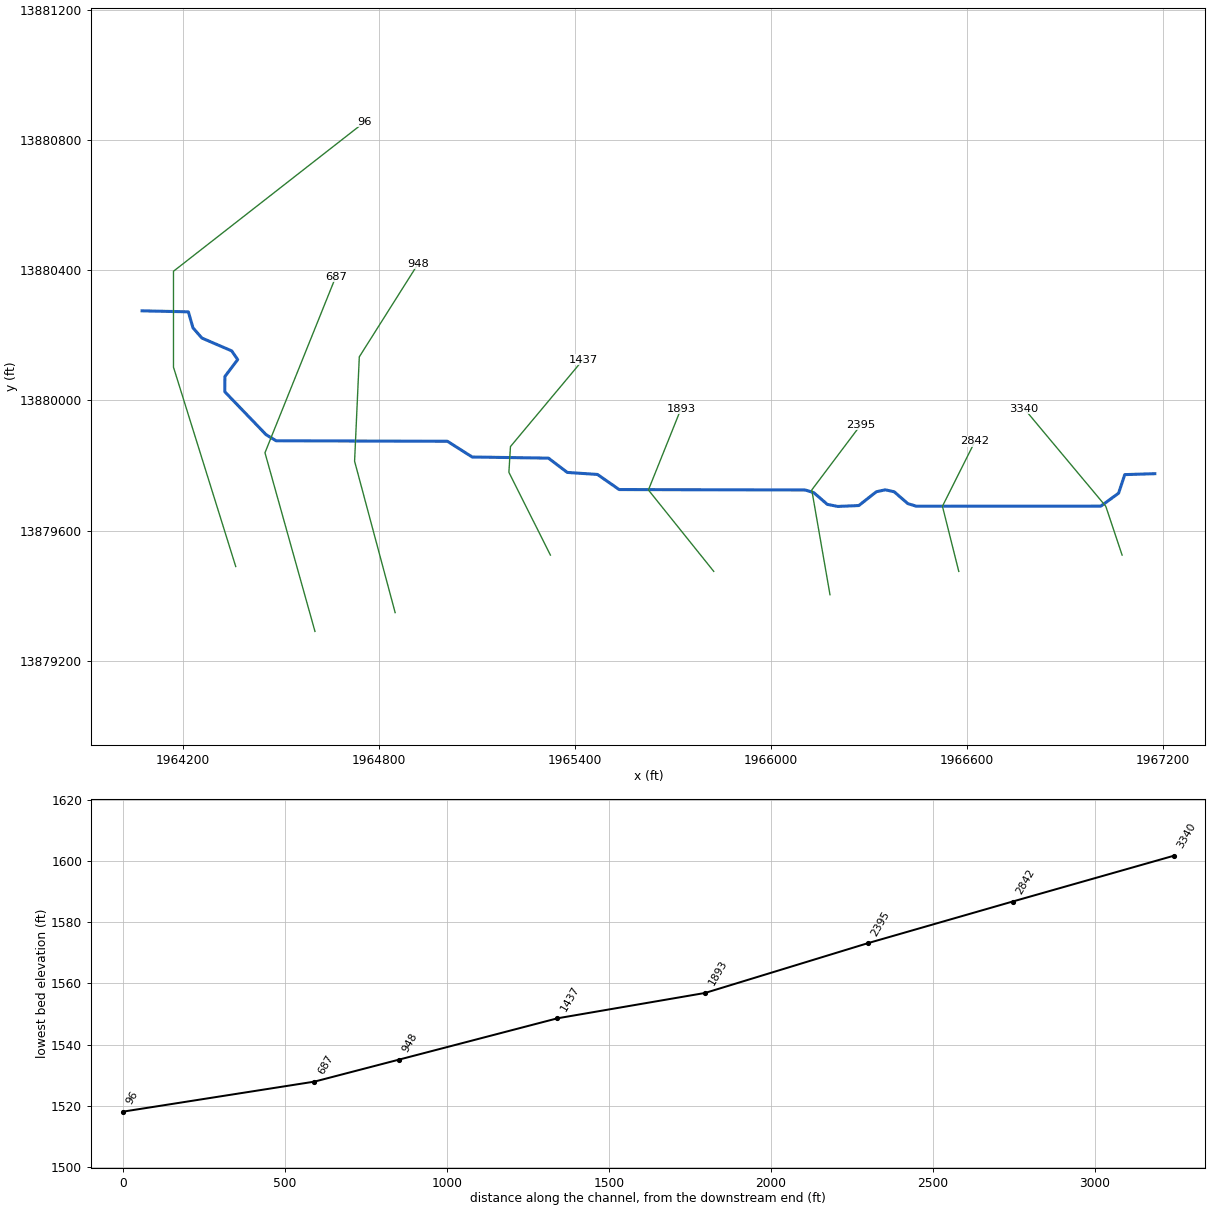
--- Stream0579.prj (project) ---

Proj Title=Stream0579 Base Level Engineering
Current Plan=p01
Default Exp/Contr=0.3,0.1
English Units
Geom File=g01
Flow File=f01
Plan File=p01
Y Axis Title=Elevation
X Axis Title(PF)=Main Channel Distance
X Axis Title(XS)=Station
BEGIN DESCRIPTION:
Stream0579
END DESCRIPTION:
DSS Export Rating Curves= 0
DSS Export Rating Curve Sorted= 0
DSS Export Volume Flow Curves= 0
DXF OffsetX= 0
DXF OffsetY= 0
DXF ScaleX= 1
DXF ScaleY= 10

--- Stream0579.p01 (plan) ---

Plan Title=Multiple Run
Short Identifier=Multiple
Geom File=g01
Flow File=f01
Subcritical Flow
K Sum by GR= 0
Std Step Tol= 0.01
Critical Tol= 0.01
Num of Std Step Trials= 20
Max Error Tol= 0.3
Flow Tol Ratio= 0.001
Split Flow NTrial= 30
Split Flow Tol= 0.02
Split Flow Ratio= 0.02
Log Output Level= 0
Friction Slope Method= 1
Unsteady Friction Slope Method= 2
Unsteady Bridges Friction Slope Method= 1
Parabolic Critical Depth
Global Vel Dist=  1 , 1 , 1
Global Log Level= 0
CheckData=True
Encroach Param= -1, 0, 0, 0
BEGIN DESCRIPTION:
Multiple Run
END DESCRIPTION:

--- Stream0579.f01 (steady flow) ---

Flow Title=Multiple
Number of Profiles=7
Profile Names=10-year,25-year,50-year,1pct_min,100-year,1pct_plu,500-year
River Rch & RM= Stream0579,Reach-1,3340
     186     278     354     221     440     878     665
River Rch & RM= Stream0579,Reach-1,2842
     462     740     989     642    1281    2557    2115
Boundary for River Rch & Prof#=Stream0579,Reach-1,1
Up Type=0
Dn Type=3
Dn Slope=0.005
Boundary for River Rch & Prof#=Stream0579,Reach-1,2
Up Type=0
Dn Type=3
Dn Slope=0.005
Boundary for River Rch & Prof#=Stream0579,Reach-1,3
Up Type=0
Dn Type=3
Dn Slope=0.005
Boundary for River Rch & Prof#=Stream0579,Reach-1,4
Up Type=0
Dn Type=3
Dn Slope=0.005
Boundary for River Rch & Prof#=Stream0579,Reach-1,5
Up Type=0
Dn Type=3
Dn Slope=0.005
Boundary for River Rch & Prof#=Stream0579,Reach-1,6
Up Type=0
Dn Type=3
Dn Slope=0.005
Boundary for River Rch & Prof#=Stream0579,Reach-1,7
Up Type=0
Dn Type=3
Dn Slope=0.005

--- Stream0579.g01 (geometry) ---

Geom Title=Existing Conditions
Program Version=4.10

River Reach=Stream0579      ,Reach-1
Reach XY= 30
        1967175.       13879775.      1967083.12     13879772.14
      1967064.29     13879715.21      1967009.96     13879675.34
      1966445.03     13879675.09      1966418.92     13879683.19
      1966377.18     13879719.62        1966350.      13879725.4
      1966322.82     13879719.62      1966269.03     13879677.19
      1966204.95     13879674.41      1966172.69     13879680.68
      1966131.06     13879716.85      1966104.97     13879724.93
       1965535.5     13879726.22      1965469.02     13879772.64
       1965376.6     13879778.86      1965319.06     13879822.74
       1965085.5     13879826.22      1965009.78     13879874.48
      1964485.43     13879876.05      1964454.83      13879894.6
      1964328.16     13880026.65      1964328.59     13880073.36
      1964367.74      13880125.3       1964349.4       13880152.
      1964258.01     13880191.58      1964230.91     13880222.85
      1964216.74     13880271.97        1964075.       13880275.

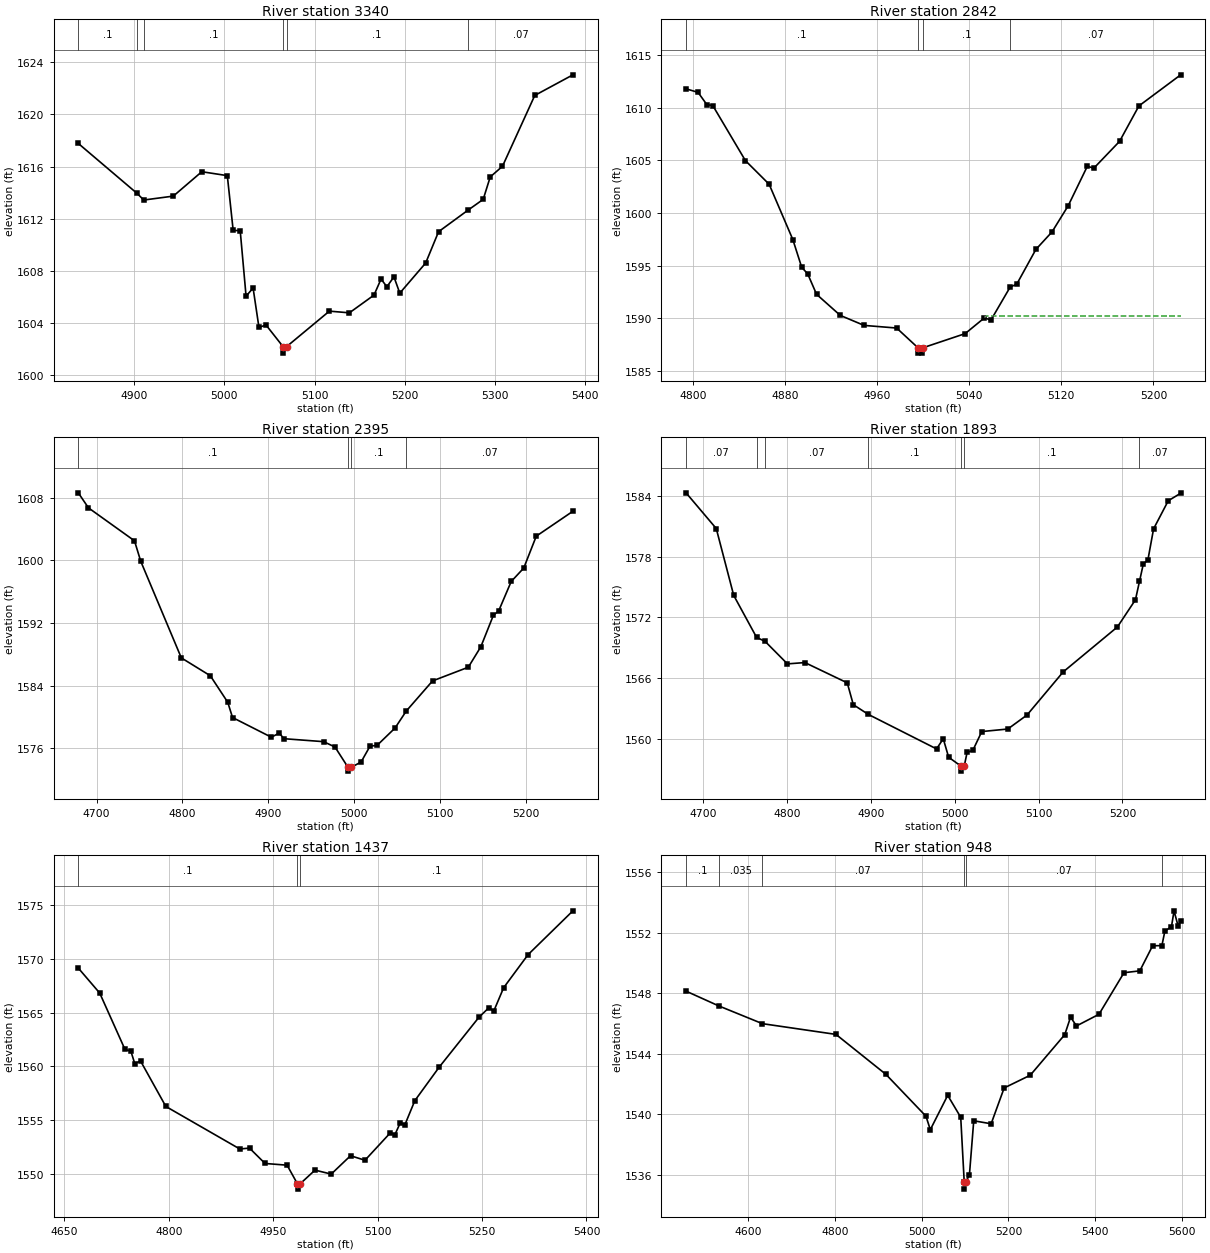
Type RM Length L Ch R = 1 ,3340    ,498,498,498
BEGIN DESCRIPTION:
Stream0579 5.0
END DESCRIPTION:
XS GIS Cut Line= 3
      1967075.01     13879524.98        1967025.       13879675.
      1966775.03     13879974.97
#Sta/Elev= 30
  4837.9 1617.77  4902.9 1613.95  4910.6 1613.43  4943.3 1613.73  4974.9  1615.6
  5003.2  1615.3  5009.7  1611.1  5017.5 1611.08    5024 1606.06  5031.8 1606.68
  5038.3 1603.66  5046.1 1603.85    5065 1602.19  5065.2 1601.69    5069 1602.19
  5116.4 1604.91  5138.6 1604.78  5165.9 1606.14  5173.7 1607.37  5180.2 1606.78
    5188 1607.54  5194.5 1606.29  5223.2  1608.6  5237.5    1611  5269.9 1612.64
    5287 1613.48  5294.8  1615.2  5308.4 1616.02  5344.2 1621.45  5386.5 1623.03
#Mann= 6 ,-1 , 0
  4837.9      .1       0  4902.9    .035       0  4910.6      .1       0
    5065     .05       0    5069      .1       0  5269.9     .07       0
Bank Sta=5065,5069
XS Rating Curve= 0 ,0
Exp/Cntr=0.3,0.1

Type RM Length L Ch R = 1 ,2842    ,447,447,447
BEGIN DESCRIPTION:
Stream0579 4.0
END DESCRIPTION:
XS GIS Cut Line= 3
      1966575.01     13879474.96        1966525.       13879675.
        1966625.     13879874.99
#Sta/Elev= 30
  4793.9 1611.78  4804.3 1611.45    4812 1610.28  4817.1  1610.2  4845.5 1604.97
  4866.1 1602.73  4886.7 1597.48  4894.4 1594.85  4899.6 1594.23  4907.3 1592.29
  4927.9 1590.29  4948.6 1589.34  4976.9 1589.09  4995.5 1587.21  4995.8 1586.71
  4999.3 1586.71  4999.5 1587.21  5036.4 1588.56  5053.2 1590.06  5058.8 1589.84
  5075.6 1592.99  5081.2 1593.24  5097.9 1596.55  5111.9 1598.21  5125.9 1600.68
  5142.6 1604.44  5148.2 1604.25  5170.6  1606.8  5187.4 1610.16  5223.7 1613.11
#Mann= 4 ,-1 , 0
  4793.9      .1       0  4995.5     .05       0  4999.5      .1       0
  5075.6     .07       0
#XS Ineff= 2 , 0
                         5053.65         1590.21
Permanent Ineff=
       F       F
Bank Sta=4995.5,4999.5
XS Rating Curve= 0 ,0
Exp/Cntr=0.3,0.1

Type RM Length L Ch R = 1 ,2395    ,502,502,502
BEGIN DESCRIPTION:
Stream0579 3.0
END DESCRIPTION:
XS GIS Cut Line= 3
      1966180.81     13879403.32        1966125.       13879725.
      1966275.01     13879925.01
#Sta/Elev= 30
  4678.6 1608.61  4690.5 1606.69  4744.1 1602.49  4751.4 1599.88  4798.7 1587.55
  4832.5 1585.27  4852.8 1581.89  4858.4 1579.94  4903.6 1577.43    4913 1577.96
  4918.1 1577.24  4964.5 1576.86  4977.8 1576.18  4992.9  1573.6  4993.2  1573.1
  4996.9  1573.6  5008.2 1574.26  5018.6 1576.28    5027  1576.4  5047.8  1578.6
  5060.9 1580.77  5091.5 1584.61  5133.2 1586.36  5147.8 1588.97  5162.4 1592.98
  5168.6 1593.55  5183.2  1597.3  5197.8 1599.01  5212.4 1603.08  5255.1 1606.26
#Mann= 4 ,-1 , 0
  4678.6      .1       0  4992.9     .05       0  4996.9      .1       0
  5060.9     .07       0
Bank Sta=4992.9,4996.9
XS Rating Curve= 0 ,0
Exp/Cntr=0.3,0.1

Type RM Length L Ch R = 1 ,1893    ,456,456,456
BEGIN DESCRIPTION:
Stream0579 2.0
END DESCRIPTION:
XS GIS Cut Line= 3
      1965824.97     13879475.03        1965625.       13879725.
      1965725.01     13879975.03
#Sta/Elev= 30
    4680 1584.28    4716 1580.76  4736.8 1574.17    4764 1570.04  4774.3 1569.63
  4800.8 1567.42  4821.6 1567.55  4872.1 1565.55  4879.3  1563.4  4897.2 1562.44
  4978.5 1559.04  4986.5 1560.04  4992.9 1558.22  5007.5 1557.35  5007.8 1556.85
  5011.5 1557.35  5014.9  1558.7  5021.7 1558.89  5032.4 1560.75  5063.4    1561
  5086.3 1562.38  5129.4 1566.63    5194 1571.06  5215.5 1573.74  5220.3 1575.55
  5224.9 1577.28  5230.3 1577.65  5237.1 1580.73  5254.6  1583.5  5269.4 1584.24
#Mann= 7 ,-1 , 0
    4680     .07       0    4764      .1       0  4774.3     .07       0
  4897.2      .1       0  5007.5     .05       0  5011.5      .1       0
  5220.3     .07       0
Bank Sta=5007.5,5011.5
XS Rating Curve= 0 ,0
Exp/Cntr=0.3,0.1

Type RM Length L Ch R = 1 ,1437    ,489,489,489
BEGIN DESCRIPTION:
Stream0579 1.0
END DESCRIPTION:
XS GIS Cut Line= 4
      1965325.01     13879524.98      1965197.95     13879779.09
      1965202.67      13879858.2      1965424.97     13880124.96
#Sta/Elev= 30
  4669.9 1569.15  4700.7 1566.82    4737 1561.57  4745.4 1561.42    4751 1560.26
  4759.4 1560.49  4795.7 1556.26  4901.9  1552.3  4915.9 1552.38  4938.2 1550.95
  4969.9 1550.79  4984.7 1549.06  4984.9 1548.56  4988.7 1549.06    5010 1550.33
  5033.3 1549.96    5061 1551.67  5081.8 1551.25  5118.3 1553.81  5124.8 1553.64
  5132.6 1554.75  5139.1 1554.55  5153.4  1556.8  5188.5 1559.93  5245.8 1564.59
  5260.1 1565.47  5266.6 1565.11    5281 1567.32  5316.1  1570.4  5380.5 1574.48
#Mann= 3 ,-1 , 0
  4669.9      .1       0  4984.7     .05       0  4988.7      .1       0
Bank Sta=4984.7,4988.7
XS Rating Curve= 0 ,0
Exp/Cntr=0.3,0.1

Type RM Length L Ch R = 1 ,948     ,261,261,261
BEGIN DESCRIPTION:
Stream0579 0.1
END DESCRIPTION:
XS GIS Cut Line= 4
      1964849.73     13879348.44      1964725.58     13879813.28
      1964740.02     13880133.78      1964920.15     13880419.71
#Sta/Elev= 30
  4457.1 1548.15    4532 1547.18    4633    1546  4802.6 1545.29  4917.6 1542.65
    5010 1539.88    5020 1538.99  5060.1 1541.26  5090.1 1539.81  5098.1 1535.56
  5098.4 1535.06  5102.1 1535.56  5110.1 1535.99  5120.1 1539.58  5160.2 1539.38
  5190.2 1541.75  5250.3 1542.59  5329.8 1545.27  5343.2 1546.43  5356.9 1545.85
  5408.7 1546.62  5466.4 1549.37  5502.8 1549.49  5532.3 1551.15  5553.7 1551.16
  5560.5 1552.11  5575.8 1552.42  5581.7 1553.46  5591.1 1552.45    5597 1552.79
#Mann= 6 ,-1 , 0
  4457.1      .1       0    4532    .035       0    4633     .07       0
  5098.1     .05       0  5102.1     .07       0  5553.7      .1       0
#XS Ineff= 2 , 0
         5060.54 1541.11
Permanent Ineff=
       F       F
Bank Sta=5098.1,5102.1
XS Rating Curve= 0 ,0
Exp/Cntr=0.3,0.1

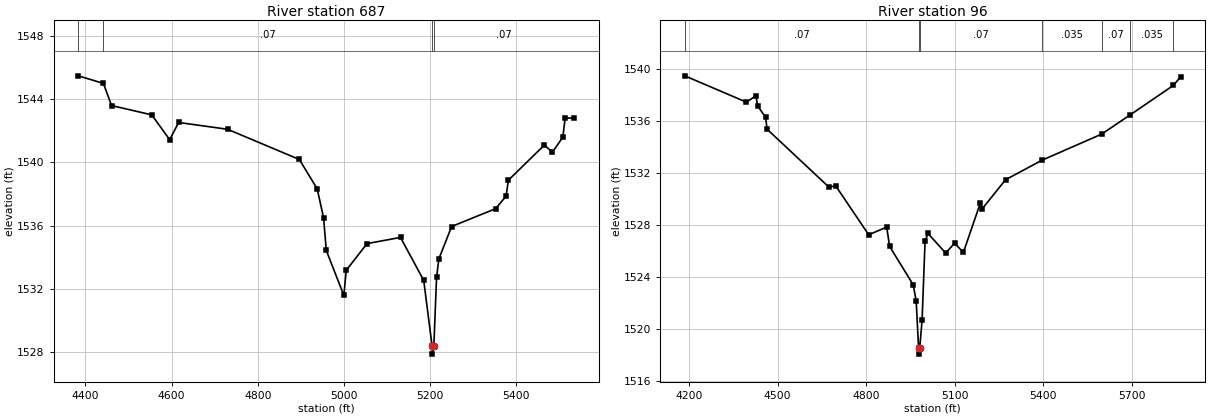
Type RM Length L Ch R = 1 ,687     ,591,591,591
BEGIN DESCRIPTION:
Stream0579 0.2
END DESCRIPTION:
XS GIS Cut Line= 3
      1964604.31     13879290.67      1964451.28     13879839.27
      1964667.83     13880379.21
#Sta/Elev= 30
  4383.5 1545.47  4441.7 1544.99  4460.7 1543.59  4554.1    1543  4595.6 1541.43
  4616.4 1542.52    4730 1542.09  4896.7 1540.18  4938.2 1538.32    4953 1536.48
  4959.2 1534.43  5000.1 1531.58  5005.5 1533.17  5053.9 1534.86  5131.6 1535.25
  5185.5 1532.53    5205 1528.37  5205.3 1527.87    5209 1528.37  5215.3 1532.73
  5220.7  1533.9  5250.3 1535.94  5352.5 1537.07  5376.7 1537.86  5382.1 1538.87
  5465.6 1541.09  5484.3 1540.64  5508.5 1541.59  5513.9  1542.8  5534.8  1542.8
#Mann= 4 ,-1 , 0
  4383.5    .035       0  4441.7     .07       0    5205     .05       0
    5209     .07       0
Bank Sta=5205,5209
XS Rating Curve= 0 ,0
Exp/Cntr=0.3,0.1

Type RM Length L Ch R = 1 ,96      ,0,0,0
BEGIN DESCRIPTION:
Stream0579 0.0
END DESCRIPTION:
XS GIS Cut Line= 4
      1964361.76     13879489.92       1964171.2     13880102.02
       1964171.2     13880396.53      1964757.33     13880855.62
#Sta/Elev= 30
  4185.3 1539.51    4394 1537.48  4426.5 1537.98  4431.7 1537.21    4459 1536.31
  4464.3 1535.39  4672.4 1530.96  4697.2 1531.01  4808.5 1527.26  4869.4 1527.85
  4879.4 1526.36  4959.4  1523.4  4969.4 1522.14  4977.4 1518.56  4977.6 1518.06
  4981.4 1518.56  4989.4 1520.69  4999.4 1526.77  5009.4 1527.36  5069.4 1525.85
  5099.4 1526.61  5129.3  1525.9  5187.1 1529.73  5193.5 1529.27  5272.1  1531.5
  5396.1 1533.01    5598 1535.02  5694.4  1536.5  5840.7 1538.77  5865.4 1539.43
#Mann= 7 ,-1 , 0
  4185.3     .07       0  4977.4     .05       0  4981.4     .07       0
  5396.1    .035       0    5598     .07       0  5694.4    .035       0
  5840.7     .07       0
Bank Sta=4977.4,4981.4
XS Rating Curve= 0 ,0
Exp/Cntr=0.3,0.1

Chan Stop Cuts=-1
Use User Specified Reach Order=0
Composite Channel Slope=5