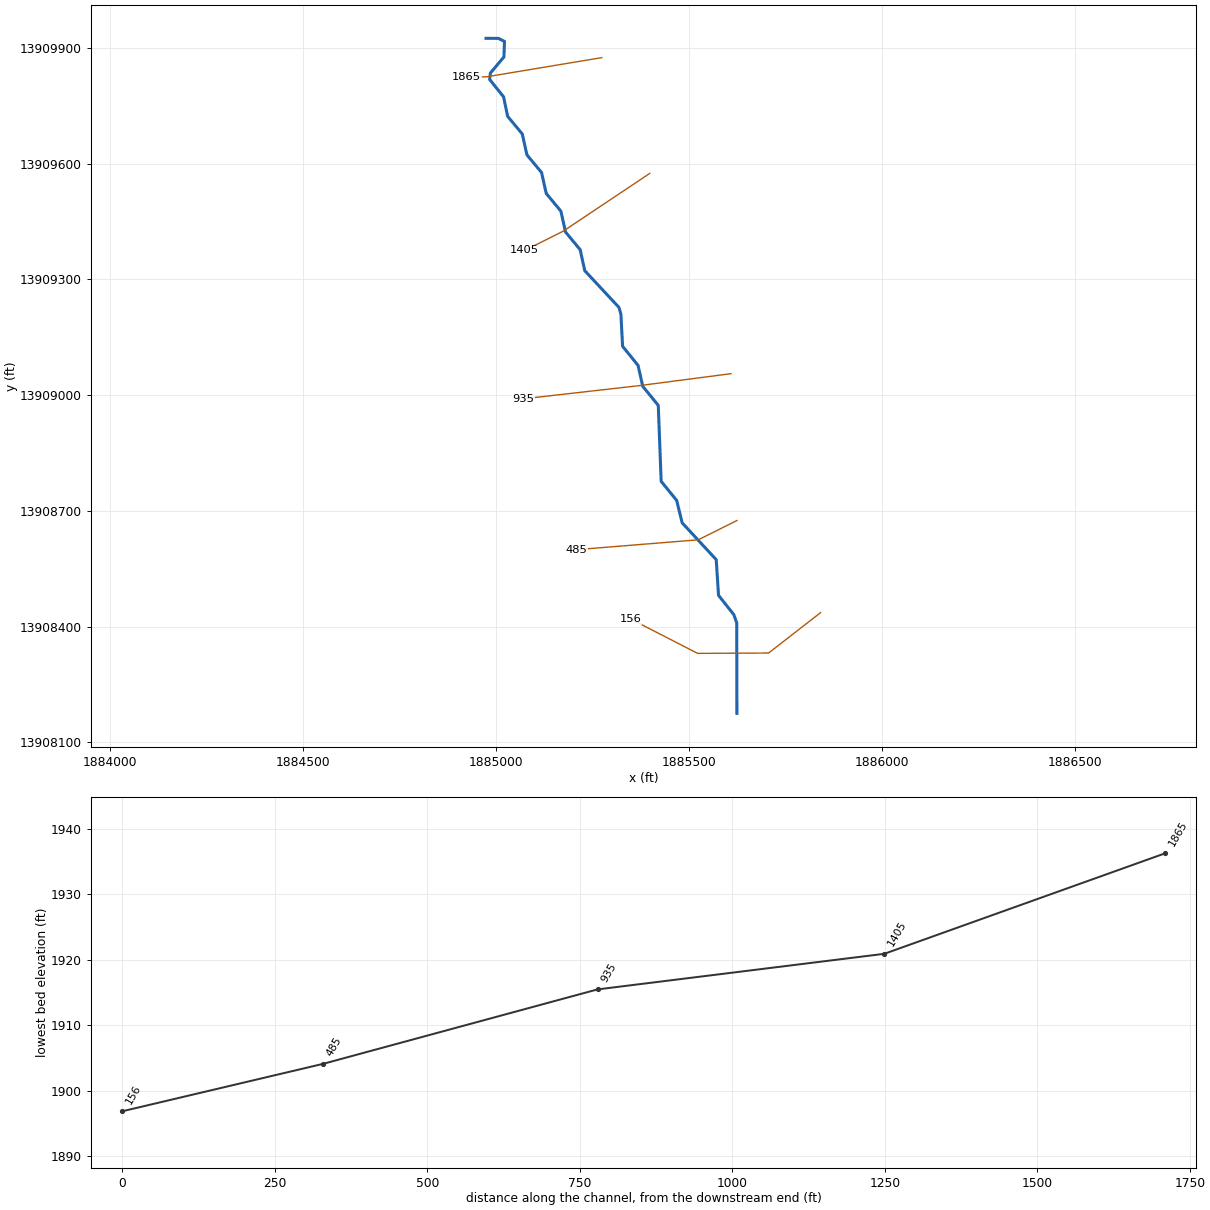
--- Stream0580.prj (project) ---

Proj Title=Stream0580 Base Level Engineering
Current Plan=p01
Default Exp/Contr=0.3,0.1
English Units
Geom File=g01
Flow File=f01
Plan File=p01
Y Axis Title=Elevation
X Axis Title(PF)=Main Channel Distance
X Axis Title(XS)=Station
BEGIN DESCRIPTION:
Stream0580
END DESCRIPTION:
DSS Export Rating Curves= 0
DSS Export Rating Curve Sorted= 0
DSS Export Volume Flow Curves= 0
DXF OffsetX= 0
DXF OffsetY= 0
DXF ScaleX= 1
DXF ScaleY= 10

--- Stream0580.p01 (plan) ---

Plan Title=Multiple Run
Short Identifier=Multiple
Geom File=g01
Flow File=f01
Subcritical Flow
K Sum by GR= 0
Std Step Tol= 0.01
Critical Tol= 0.01
Num of Std Step Trials= 20
Max Error Tol= 0.3
Flow Tol Ratio= 0.001
Split Flow NTrial= 30
Split Flow Tol= 0.02
Split Flow Ratio= 0.02
Log Output Level= 0
Friction Slope Method= 1
Unsteady Friction Slope Method= 2
Unsteady Bridges Friction Slope Method= 1
Parabolic Critical Depth
Global Vel Dist=  1 , 1 , 1
Global Log Level= 0
CheckData=True
Encroach Param= -1, 0, 0, 0
BEGIN DESCRIPTION:
Multiple Run
END DESCRIPTION:

--- Stream0580.f01 (steady flow) ---

Flow Title=Multiple
Program Version=4.10
Number of Profiles= 7
Profile Names=10-year,25-year,50-year,1pct_min,100-year,1pct_plu,500-year
River Rch & RM=Stream0580,Reach-1         ,1865
    1278    2195    3075    2082    4155    8290    7489
Boundary for River Rch & Prof#=Stream0580,Reach-1         , 1
Up Type= 0
Dn Type= 3
Dn Slope=0.008
Boundary for River Rch & Prof#=Stream0580,Reach-1         , 2
Up Type= 0
Dn Type= 3
Dn Slope=0.008
Boundary for River Rch & Prof#=Stream0580,Reach-1         , 3
Up Type= 0
Dn Type= 3
Dn Slope=0.008
Boundary for River Rch & Prof#=Stream0580,Reach-1         , 4
Up Type= 0
Dn Type= 3
Dn Slope=0.008
Boundary for River Rch & Prof#=Stream0580,Reach-1         , 5
Up Type= 0
Dn Type= 3
Dn Slope=0.008
Boundary for River Rch & Prof#=Stream0580,Reach-1         , 6
Up Type= 0
Dn Type= 3
Dn Slope=0.008
Boundary for River Rch & Prof#=Stream0580,Reach-1         , 7
Up Type= 0
Dn Type= 3
Dn Slope=0.008
DSS Import GetInterval= 0
DSS Import GetPeak= 0
DSS Import FillOption= 0

--- Stream0580.g01 (geometry) ---

Geom Title=Existing Conditions
Program Version=4.10

River Reach=Stream0580      ,Reach-1
Reach XY= 30
        1884975.       13909925.      1885007.33     13909924.93
      1885022.94     13909916.99      1885021.46     13909876.81
      1884986.43     13909834.96      1884984.41      13909818.4
      1885020.58     13909773.36      1885031.05     13909722.81
      1885068.92      13909677.2      1885081.08      13909622.8
      1885118.92      13909577.2      1885131.08      13909522.8
      1885168.92      13909477.2      1885181.08      13909422.8
       1885218.9     13909377.19      1885230.85     13909322.71
      1885319.46     13909227.42      1885324.47     13909209.78
      1885328.83     13909126.59      1885368.89     13909077.18
      1885381.12     13909022.82      1885421.25     13908973.45
      1885428.75     13908776.55      1885468.86     13908727.17
      1885483.16     13908668.95      1885571.38      13908573.5
      1885577.36     13908480.98      1885616.86     13908431.06
      1885624.48     13908409.78        1885625.       13908175.

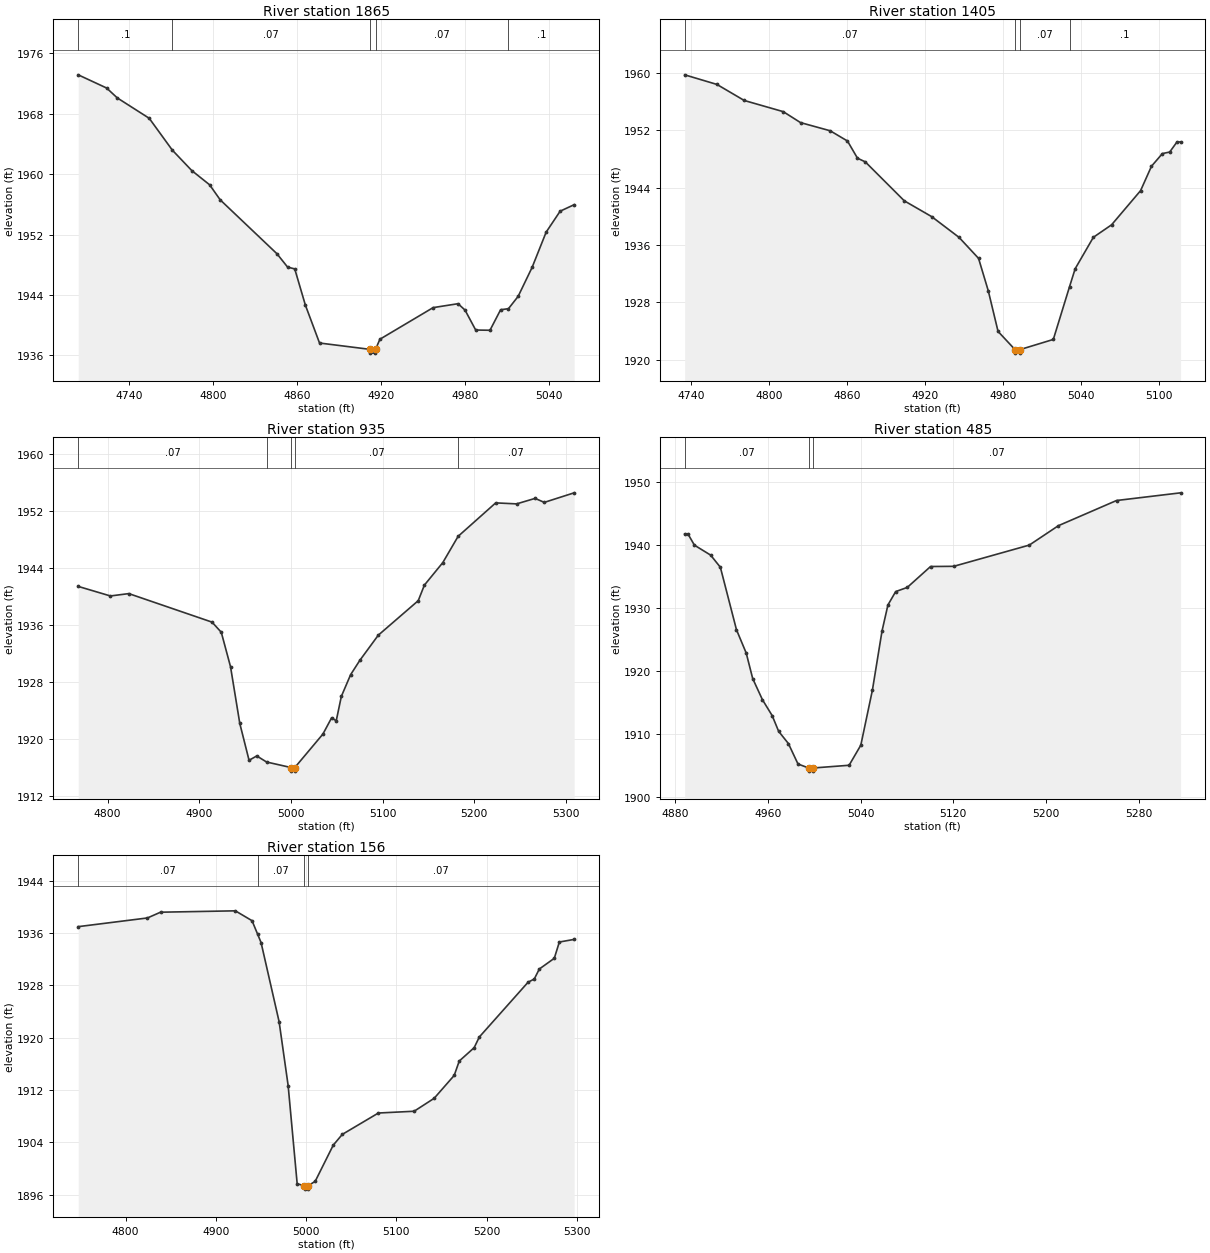
Type RM Length L Ch R = 1 ,1865    ,460,460,460
BEGIN DESCRIPTION:
Stream0580 4.0
END DESCRIPTION:
XS GIS Cut Line= 3
      1885274.98       13909875.        1884975.       13909825.
      1884925.02       13909825.
#Sta/Elev= 30
  4703.7 1973.16    4724 1971.41  4731.6  1970.1  4754.4  1967.4  4770.9 1963.18
  4784.8 1960.47  4797.5 1958.59  4805.1 1956.59  4845.6 1949.45  4853.2 1947.68
  4858.3 1947.44  4865.9 1942.64    4876 1937.62    4912 1936.78  4912.3 1936.28
  4915.8 1936.28    4916 1936.78  4919.1 1938.12  4957.1 1942.31  4974.9 1942.83
  4979.9 1941.98  4987.5 1939.34  4997.7 1939.31  5005.3 1942.03  5010.9 1942.17
  5017.8  1943.8  5027.8 1947.65  5037.8 1952.31  5047.8 1955.09  5057.8 1955.95
#Mann= 5 ,-1 , 0
  4703.7      .1       0  4770.9     .07       0    4912     .05       0
    4916     .07       0  5010.9      .1       0
Bank Sta=4912,4916
XS Rating Curve= 0 ,0
Exp/Cntr=0.3,0.1

Type RM Length L Ch R = 1 ,1405    ,470,470,470
BEGIN DESCRIPTION:
Stream0580 3.0
END DESCRIPTION:
XS GIS Cut Line= 3
       1885399.1     13909574.79        1885175.       13909425.
      1885074.96     13909374.98
#Sta/Elev= 30
  4735.1 1959.77  4759.9 1958.43  4780.9 1956.19  4810.9 1954.63  4824.2  1953.1
    4847 1951.96  4860.3 1950.53    4868 1948.13    4874 1947.62    4904 1942.18
  4925.1 1939.97  4946.1 1937.08  4961.1 1934.15  4968.6 1929.61  4976.1 1923.95
  4989.1 1921.42  4989.4 1920.92  4992.9 1920.92  4993.1 1921.42  5018.6 1922.83
  5031.1 1930.21  5035.4  1932.7  5049.4 1937.09  5063.4 1938.83  5085.7  1943.6
  5094.1 1947.01  5102.5 1948.78  5108.1 1948.99  5113.7  1950.4  5116.5  1950.4
#Mann= 4 ,-1 , 0
  4735.1     .07       0  4989.1     .05       0  4993.1     .07       0
  5031.1      .1       0
Bank Sta=4989.1,4993.1
XS Rating Curve= 0 ,0
Exp/Cntr=0.3,0.1

Type RM Length L Ch R = 1 ,935     ,450,450,450
BEGIN DESCRIPTION:
Stream0580 2.0
END DESCRIPTION:
XS GIS Cut Line= 3
      1885609.78      13909055.7        1885375.       13909025.
      1885072.63     13908990.59
#Sta/Elev= 30
    4768 1941.38  4803.1 1940.04  4823.2 1940.37    4914 1936.37  4924.1 1934.95
  4934.2 1930.11  4944.3 1922.16  4954.4    1917  4962.8 1917.61  4973.5 1916.76
  5000.3 1915.98  5000.5 1915.48    5004 1915.48  5004.3 1915.98    5035 1920.68
  5044.5 1922.96  5049.5 1922.53  5055.1 1925.96  5065.2    1929  5075.2    1931
  5095.4 1934.54    5139 1939.38  5145.7 1941.56  5165.8 1944.72  5182.5  1948.4
  5223.5 1953.09  5246.3 1952.95  5266.5 1953.72  5276.5 1953.16  5309.1  1954.5
#Mann= 5 ,-1 , 0
    4768     .07       0  4973.5     .07       0  5000.3     .05       0
  5004.3     .07       0  5182.5     .07       0
Bank Sta=5000.3,5004.3
XS Rating Curve= 0 ,0
Exp/Cntr=0.3,0.1

Type RM Length L Ch R = 1 ,485     ,329,329,329
BEGIN DESCRIPTION:
Stream0580 1.0
END DESCRIPTION:
XS GIS Cut Line= 3
      1885625.02     13908675.01        1885525.       13908625.
      1885209.86     13908599.44
#Sta/Elev= 30
  4888.2 1941.76    4891 1941.76  4896.6 1939.97  4910.6 1938.39    4919 1936.46
  4932.9 1926.54  4941.3 1922.84  4946.9 1918.79  4955.3 1915.43  4963.7 1912.91
  4969.3 1910.41  4977.7 1908.47    4986 1905.22  4995.2 1904.59  4995.5 1904.09
    4999 1904.09  4999.2 1904.59  5030.1 1905.02  5040.2 1908.21  5050.2 1916.94
  5058.5 1926.33  5063.6 1930.47  5070.3  1932.6  5080.3 1933.26  5100.4 1936.58
  5120.4 1936.61  5185.6 1939.98  5210.7 1943.06  5260.9 1947.06  5316.2 1948.28
#Mann= 3 ,-1 , 0
  4888.2     .07       0  4995.2     .05       0  4999.2     .07       0
Bank Sta=4995.2,4999.2
XS Rating Curve= 0 ,0
Exp/Cntr=0.3,0.1

Type RM Length L Ch R = 1 ,156     ,0,0,0
BEGIN DESCRIPTION:
Stream0580 0.0
END DESCRIPTION:
XS GIS Cut Line= 4
       1885841.7     13908436.15      1885706.99     13908331.45
      1885523.22     13908330.53      1885349.67     13908419.67
#Sta/Elev= 30
  4747.5 1936.98  4824.2 1938.31  4838.7 1939.19  4921.6  1939.4  4940.1 1937.89
  4946.4 1935.79  4950.1 1934.55  4970.1 1922.44  4980.1 1912.68  4990.1 1897.67
  4998.1 1897.34  4998.4 1896.84  5001.9 1896.84  5002.1 1897.34  5010.1 1898.04
  5030.1 1903.57  5040.1 1905.21  5080.1 1908.48  5119.7 1908.75  5141.9 1910.73
  5164.1 1914.23  5169.7 1916.43  5186.2 1918.47  5191.9  1920.1    5246 1928.49
  5252.8 1928.97  5258.4  1930.5    5275 1932.14  5280.6 1934.63    5297 1935.03
#Mann= 4 ,-1 , 0
  4747.5     .07       0  4946.4     .07       0  4998.1     .05       0
  5002.1     .07       0
Bank Sta=4998.1,5002.1
XS Rating Curve= 0 ,0
Exp/Cntr=0.3,0.1

Chan Stop Cuts=-1
Use User Specified Reach Order=0
Composite Channel Slope=5