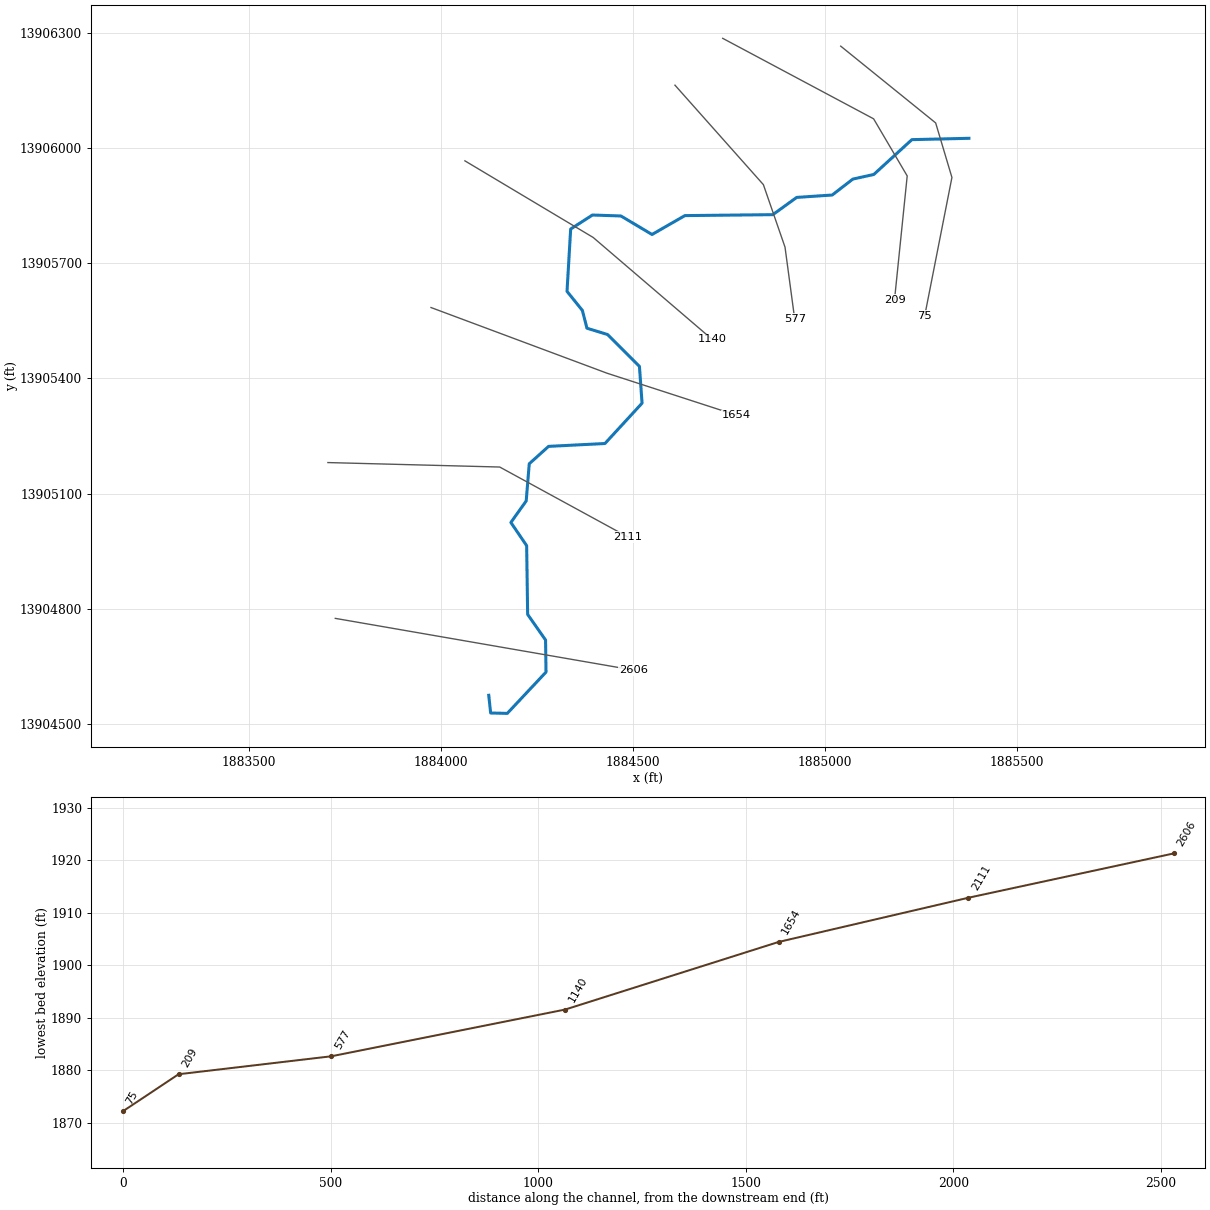
--- Stream0581.prj (project) ---

Proj Title=Stream0581 Base Level Engineering
Current Plan=p01
Default Exp/Contr=0.3,0.1
English Units
Geom File=g01
Flow File=f01
Plan File=p01
BEGIN DESCRIPTION:
Stream0581
END DESCRIPTION:

--- Stream0581.p01 (plan) ---

Plan Title=Multiple Run
Short Identifier=Multiple
Geom File=g01
Flow File=f01
Subcritical Flow
K Sum by GR= 0
Std Step Tol= 0.01
Critical Tol= 0.01
Num of Std Step Trials= 20
Max Error Tol= 0.3
Flow Tol Ratio= 0.001
Split Flow NTrial= 30
Split Flow Tol= 0.02
Split Flow Ratio= 0.02
Log Output Level= 0
Friction Slope Method= 1
Unsteady Friction Slope Method= 2
Unsteady Bridges Friction Slope Method= 1
Parabolic Critical Depth
Global Vel Dist=  1 , 1 , 1
Global Log Level= 0
CheckData=True
Encroach Param= -1, 0, 0, 0
BEGIN DESCRIPTION:
Multiple Run
END DESCRIPTION:

--- Stream0581.f01 (steady flow) ---

Flow Title=Multiple
Number of Profiles=7
Profile Names=10-year,25-year,50-year,1pct_min,100-year,1pct_plu,500-year
River Rch & RM= Stream0581,Reach-1,2606
    1124    1922    2685    1815    3622    7226    6506
Boundary for River Rch & Prof#=Stream0581,Reach-1,1
Up Type=0
Dn Type=3
Dn Slope=0.005
Boundary for River Rch & Prof#=Stream0581,Reach-1,2
Up Type=0
Dn Type=3
Dn Slope=0.005
Boundary for River Rch & Prof#=Stream0581,Reach-1,3
Up Type=0
Dn Type=3
Dn Slope=0.005
Boundary for River Rch & Prof#=Stream0581,Reach-1,4
Up Type=0
Dn Type=3
Dn Slope=0.005
Boundary for River Rch & Prof#=Stream0581,Reach-1,5
Up Type=0
Dn Type=3
Dn Slope=0.005
Boundary for River Rch & Prof#=Stream0581,Reach-1,6
Up Type=0
Dn Type=3
Dn Slope=0.005
Boundary for River Rch & Prof#=Stream0581,Reach-1,7
Up Type=0
Dn Type=3
Dn Slope=0.005

--- Stream0581.g01 (geometry) ---

Geom Title=Existing Conditions

River Reach=Stream0581,Reach-1
Reach XY= 30
      1884125.00     13904575.00      1884129.92     13904528.93
      1884173.21     13904527.97      1884274.07     13904635.47
      1884272.84     13904719.02      1884226.22     13904785.50
      1884223.62     13904964.56      1884182.56     13905025.00
      1884222.44     13905080.90      1884230.40     13905177.71
      1884280.65     13905223.02      1884427.46     13905230.46
      1884524.07     13905335.48      1884517.25     13905431.19
      1884434.44     13905514.12      1884380.59     13905530.61
      1884368.72     13905576.84      1884328.73     13905626.53
      1884338.19     13905788.75      1884394.94     13905825.26
      1884469.03     13905822.81      1884550.00     13905774.60
      1884635.50     13905823.76      1884864.50     13905826.22
      1884926.60     13905871.14      1885019.03     13905877.33
      1885072.83     13905918.86      1885127.29     13905930.85
      1885226.45     13906021.49      1885375.00     13906025.00

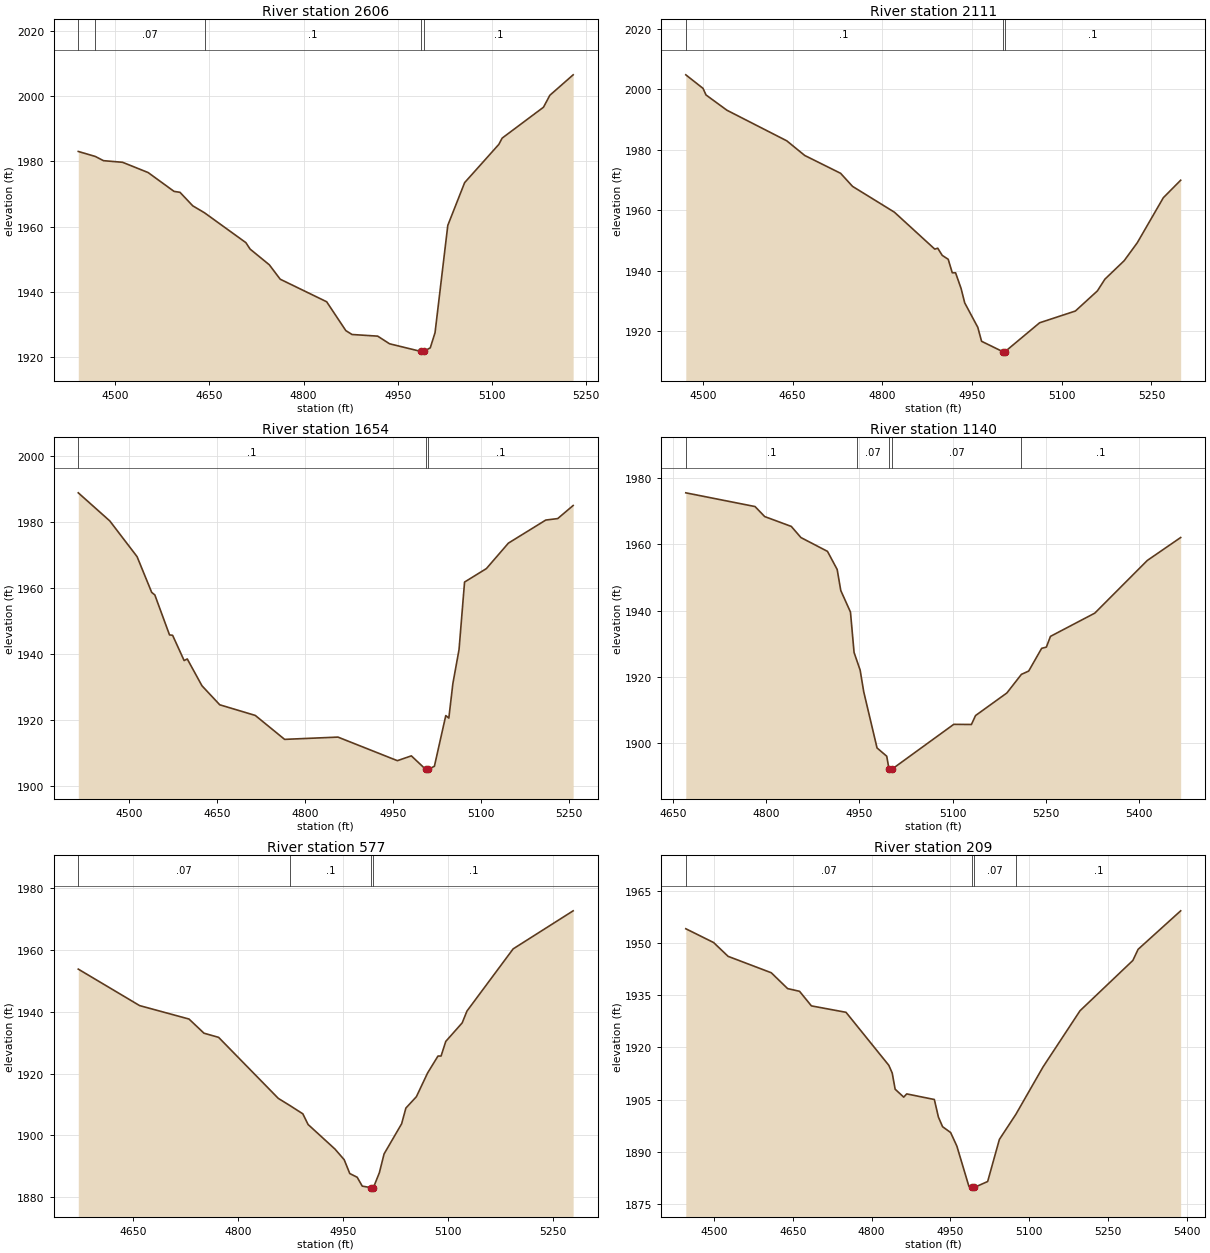
Type RM Length L Ch R = 1,2606,495,495,495
BEGIN DESCRIPTION:
Stream0581 6.0
END DESCRIPTION:
XS GIS Cut Line= 2
      1883725.50     13904775.28      1884501.52     13904640.72
#Sta/Elev= 30
  4441.5 1983.00  4468.6 1981.47  4481.6 1980.18  4512.0 1979.68  4552.6 1976.55
  4593.9 1970.78  4603.4 1970.49  4623.7 1966.36  4642.4 1964.23  4708.2 1955.10
  4715.0 1953.11  4745.5 1948.32  4762.9 1943.90  4836.8 1937.00  4867.3 1928.17
  4877.2 1926.98  4918.0 1926.48  4936.9 1924.14  4987.1 1921.78  4987.3 1921.28
  4991.1 1921.78  5001.7 1922.90  5009.3 1927.54  5029.6 1960.38  5056.4 1973.46
  5110.8 1985.16  5116.1 1987.08  5181.9 1996.54  5192.0 2000.19  5229.1 2006.45
#Mann=5,-1,0
  4441.5     0.1       0  4468.6    0.07       0  4642.4     0.1       0
  4987.1    0.05       0  4991.1     0.1       0
Bank Sta=4987.1,4991.1
Exp/Cntr=0.3,0.1

Type RM Length L Ch R = 1,2111,457,457,457
BEGIN DESCRIPTION:
Stream0581 5.0
END DESCRIPTION:
XS GIS Cut Line= 3
      1883706.21     13905180.88      1884153.55     13905169.25
      1884487.32     13904987.17
#Sta/Elev= 30
  4471.3 2004.72  4500.1 2000.25  4505.1 1998.08  4540.1 1993.03  4640.2 1982.93
  4670.2 1978.10  4730.2 1972.21  4750.2 1967.89  4820.2 1959.37  4887.7 1947.18
  4892.7 1947.47  4900.2 1945.11  4910.2 1943.82  4917.0 1939.36  4922.5 1939.36
  4931.8 1934.14  4937.8 1929.43  4959.7 1921.35  4966.0 1916.75  5001.3 1913.34
  5001.6 1912.84  5005.3 1913.34  5063.1 1922.86  5122.9 1926.74  5159.7 1933.38
  5172.3 1937.26  5204.5 1943.35  5226.4 1949.27  5270.0 1964.15  5299.0 1969.92
#Mann=3,-1,0
  4471.3     0.1       0  5001.3    0.05       0  5005.3     0.1       0
Bank Sta=5001.3,5005.3
Exp/Cntr=0.3,0.1

Type RM Length L Ch R = 1,1654,514,514,514
BEGIN DESCRIPTION:
Stream0581 4.0
END DESCRIPTION:
XS GIS Cut Line= 3
      1883974.65     13905584.45      1884433.19     13905413.39
      1884770.01     13905304.14
#Sta/Elev= 30
  4413.2 1988.83  4466.9 1980.31  4513.4 1969.48  4538.3 1958.65  4543.7 1957.86
  4568.7 1945.75  4574.0 1945.62  4593.6 1937.97  4599.0 1938.44  4624.0 1930.32
  4654.3 1924.55  4714.9 1921.32  4764.9 1914.06  4855.8 1914.75  4957.1 1907.60
  4980.9 1909.06  5005.6 1904.93  5005.9 1904.43  5009.6 1904.93  5020.2 1905.91
  5039.6 1921.28  5044.8 1920.52  5051.7 1931.00  5062.2 1941.30  5071.6 1961.77
  5108.8 1965.85  5146.3 1973.57  5210.0 1980.57  5230.4 1981.02  5256.7 1984.99
#Mann=3,-1,0
  4413.2     0.1       0  5005.6    0.05       0  5009.6     0.1       0
Bank Sta=5005.6,5009.6
Exp/Cntr=0.3,0.1

Type RM Length L Ch R = 1,1140,563,563,563
BEGIN DESCRIPTION:
Stream0581 3.0
END DESCRIPTION:
XS GIS Cut Line= 3
      1884062.88     13905966.33      1884396.75     13905766.90
      1884706.71     13905501.43
#Sta/Elev= 30
  4670.3 1975.52  4781.8 1971.38  4797.4 1968.35  4840.2 1965.39  4855.7 1962.03
  4898.5 1957.86  4914.1 1952.39  4919.9 1946.05  4935.5 1939.56  4941.3 1927.37
  4946.4 1924.59  4951.1 1922.03  4956.9 1915.47  4978.3 1898.56  4993.9 1896.07
  4997.7 1892.07  4997.9 1891.57  5001.7 1892.07  5101.8 1905.68  5130.3 1905.64
  5136.9 1908.33  5187.4 1915.15  5210.8 1920.76  5222.5 1921.75  5243.4 1928.61
  5251.0 1928.98  5257.6 1932.22  5329.0 1939.23  5413.5 1955.11  5467.3 1962.04
#Mann=5,-1,0
  4670.3     0.1       0  4946.4    0.07       0  4997.7    0.05       0
  5001.7    0.07       0  5210.8     0.1       0
Bank Sta=4997.7,5001.7
Exp/Cntr=0.3,0.1

Type RM Length L Ch R = 1,577,368,368,368
BEGIN DESCRIPTION:
Stream0581 2.0
END DESCRIPTION:
XS GIS Cut Line= 4
      1884609.72     13906163.30      1884839.90     13905904.35
      1884896.20     13905741.66      1884921.41     13905554.57
#Sta/Elev= 30
  4571.4 1953.71  4659.1 1941.93  4729.7 1937.59  4751.1 1933.02  4772.0 1931.68
  4857.3 1911.98  4874.1 1909.64  4892.4 1906.99  4899.9 1903.55  4938.3 1895.62
  4951.5 1892.18  4959.5 1887.71  4970.1 1886.51  4977.3 1883.65  4989.3 1883.18
  4989.5 1882.68  4993.3 1883.18  5001.8 1887.99  5008.5 1894.03  5033.6 1903.78
  5039.7 1908.85  5054.7 1912.52  5070.8 1920.21  5085.6 1925.65  5090.0 1925.65
  5096.7 1930.37  5120.2 1936.36  5127.0 1940.17  5193.0 1960.24  5278.8 1972.53
#Mann=4,-1,0
  4571.4    0.07       0  4874.1     0.1       0  4989.3    0.05       0
  4993.3     0.1       0
Bank Sta=4989.3,4993.3
Exp/Cntr=0.3,0.1

Type RM Length L Ch R = 1,209,134,134,134
BEGIN DESCRIPTION:
Stream0581 1.0
END DESCRIPTION:
XS GIS Cut Line= 4
      1884734.01     13906285.23      1885126.85     13906075.70
      1885214.29     13905927.04      1885181.23     13905604.43
#Sta/Elev= 30
  4446.2 1954.10  4499.1 1950.14  4526.7 1946.17  4608.9 1941.45  4640.0 1936.90
  4662.7 1936.12  4685.3 1931.93  4751.2 1930.08  4832.7 1914.84  4839.1 1912.64
  4844.7 1907.98  4861.0 1905.70  4866.7 1906.63  4919.3 1905.02  4927.1 1899.95
  4935.0 1897.20  4950.3 1895.53  4962.2 1891.62  4985.1 1880.06  4991.6 1879.76
  4991.8 1879.26  4995.6 1879.76  5020.8 1881.45  5043.1 1893.54  5074.5 1900.76
  5126.3 1914.40  5196.6 1930.53  5297.2 1944.99  5307.2 1948.19  5388.2 1959.25
#Mann=4,-1,0
  4446.2    0.07       0  4991.6    0.05       0  4995.6    0.07       0
  5074.5     0.1       0
Bank Sta=4991.6,4995.6
Exp/Cntr=0.3,0.1

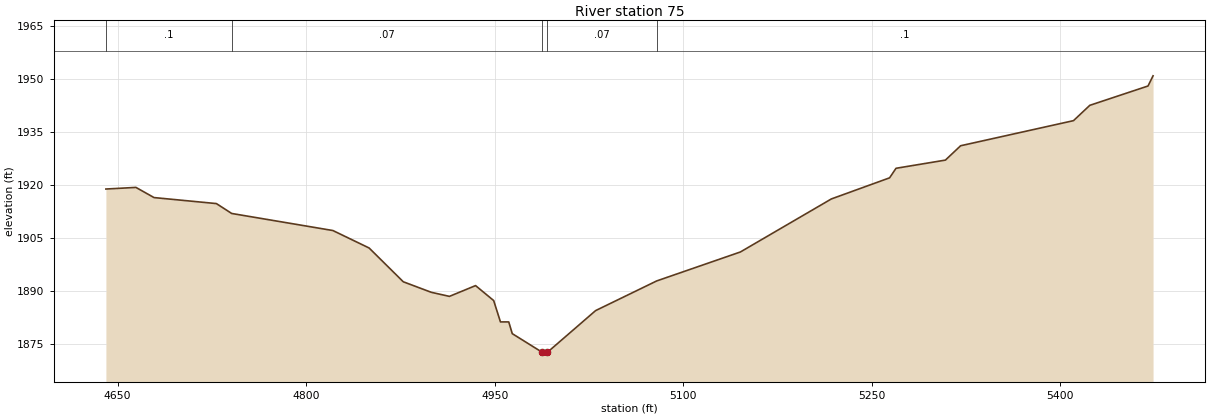
Type RM Length L Ch R = 1,75,0,0,0
BEGIN DESCRIPTION:
Stream0581 0.0
END DESCRIPTION:
XS GIS Cut Line= 4
      1885041.21     13906264.88      1885288.38     13906065.02
      1885330.70     13905923.07      1885259.84     13905562.86
#Sta/Elev= 30
  4640.7 1918.96  4664.6 1919.42  4679.0 1916.54  4728.6 1914.84  4740.8 1912.04
  4821.3 1907.21  4850.1 1902.27  4877.3 1892.70  4899.6 1889.72  4914.0 1888.57
  4934.8 1891.62  4949.2 1887.39  4954.6 1881.34  4961.2 1881.34  4964.0 1878.02
  4987.9 1872.72  4988.1 1872.22  4991.9 1872.72  5030.3 1884.54  5078.9 1892.94
  5145.5 1901.14  5217.9 1916.16  5264.2 1922.13  5269.3 1924.83  5308.6 1927.15
  5320.7 1931.21  5410.5 1938.32  5423.5 1942.66  5469.8 1948.13  5473.8 1951.01
#Mann=5,-1,0
  4640.7     0.1       0  4740.8    0.07       0  4987.9    0.05       0
  4991.9    0.07       0  5078.9     0.1       0
Bank Sta=4987.9,4991.9
Exp/Cntr=0.3,0.1

Chan Stop Cuts=-1