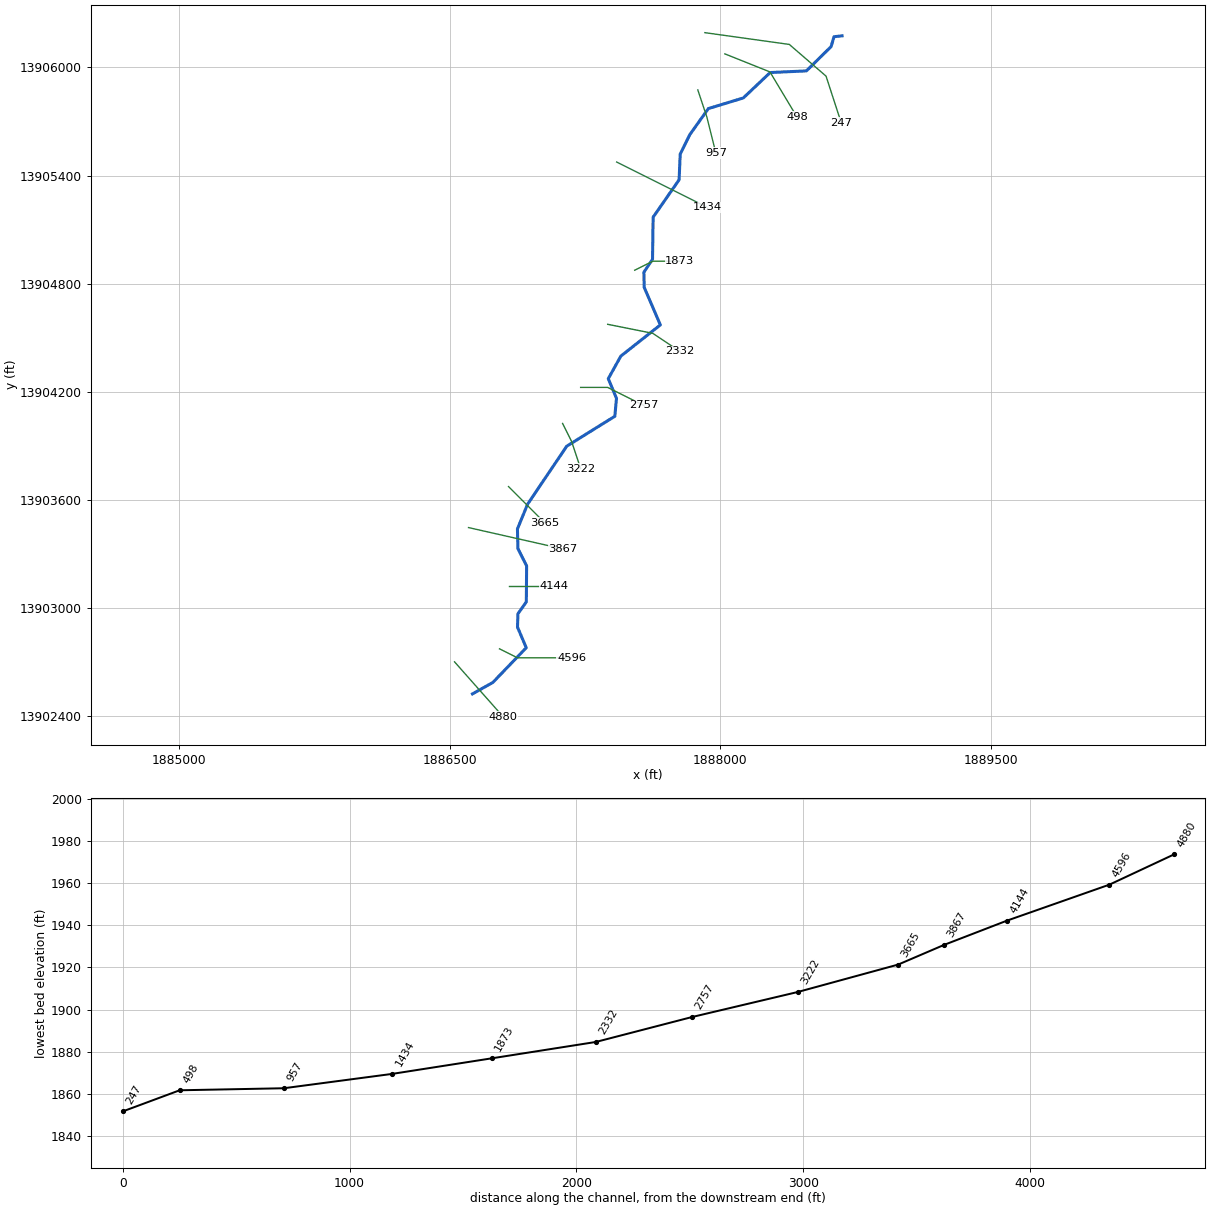
--- Stream0583.prj (project) ---

Proj Title=Stream0583 Base Level Engineering
Current Plan=p01
Default Exp/Contr=0.3,0.1
English Units
Geom File=g01
Flow File=f01
Plan File=p01
Y Axis Title=Elevation
X Axis Title(PF)=Main Channel Distance
X Axis Title(XS)=Station
BEGIN DESCRIPTION:
Stream0583
END DESCRIPTION:
DSS Export Rating Curves= 0
DSS Export Rating Curve Sorted= 0
DSS Export Volume Flow Curves= 0
DXF OffsetX= 0
DXF OffsetY= 0
DXF ScaleX= 1
DXF ScaleY= 10

--- Stream0583.p01 (plan) ---

Plan Title=Multiple Run
Short Identifier=Multiple
Geom File=g01
Flow File=f01
Subcritical Flow
K Sum by GR= 0
Std Step Tol= 0.01
Critical Tol= 0.01
Num of Std Step Trials= 20
Max Error Tol= 0.3
Flow Tol Ratio= 0.001
Split Flow NTrial= 30
Split Flow Tol= 0.02
Split Flow Ratio= 0.02
Log Output Level= 0
Friction Slope Method= 1
Unsteady Friction Slope Method= 2
Unsteady Bridges Friction Slope Method= 1
Parabolic Critical Depth
Global Vel Dist=  1 , 1 , 1
Global Log Level= 0
CheckData=True
Encroach Param= -1, 0, 0, 0
BEGIN DESCRIPTION:
Multiple Run
END DESCRIPTION:

--- Stream0583.f01 (steady flow) ---

Flow Title=Multiple
Number of Profiles=7
Profile Names=10-year,25-year,50-year,1pct_min,100-year,1pct_plu,500-year
River Rch & RM= Stream0583,Reach-1,4880
     915    1553    2161    1457    2907    5800    5190
Boundary for River Rch & Prof#=Stream0583,Reach-1,1
Up Type=0
Dn Type=3
Dn Slope=0.005
Boundary for River Rch & Prof#=Stream0583,Reach-1,2
Up Type=0
Dn Type=3
Dn Slope=0.005
Boundary for River Rch & Prof#=Stream0583,Reach-1,3
Up Type=0
Dn Type=3
Dn Slope=0.005
Boundary for River Rch & Prof#=Stream0583,Reach-1,4
Up Type=0
Dn Type=3
Dn Slope=0.005
Boundary for River Rch & Prof#=Stream0583,Reach-1,5
Up Type=0
Dn Type=3
Dn Slope=0.005
Boundary for River Rch & Prof#=Stream0583,Reach-1,6
Up Type=0
Dn Type=3
Dn Slope=0.005
Boundary for River Rch & Prof#=Stream0583,Reach-1,7
Up Type=0
Dn Type=3
Dn Slope=0.005

--- Stream0583.g01 (geometry) ---

Geom Title=Existing Conditions
Program Version=4.10

River Reach=Stream0583      ,Reach-1
Reach XY= 30
        1886625.       13902525.      1886738.23     13902588.57
      1886923.38     13902781.03      1886874.92     13902895.09
      1886877.17     13902969.02      1886923.78      13903035.5
      1886925.45     13903235.19      1886877.25     13903330.94
      1886874.52     13903440.16      1886930.84     13903577.29
      1887147.86     13903898.84       1887414.7      13904064.9
      1887423.88     13904164.45      1887378.34     13904273.28
      1887447.99     13904398.52      1887667.21     13904571.57
      1887577.17     13904780.97       1887576.1     13904864.45
      1887623.78      13904935.5      1887627.06     13905169.14
      1887771.24     13905376.56      1887777.25     13905519.07
      1887830.84     13905627.29      1887933.48     13905771.49
      1888127.43     13905830.52      1888276.46     13905971.46
      1888477.45     13905980.46      1888614.28     13906115.46
      1888630.33     13906170.08        1888675.       13906175.

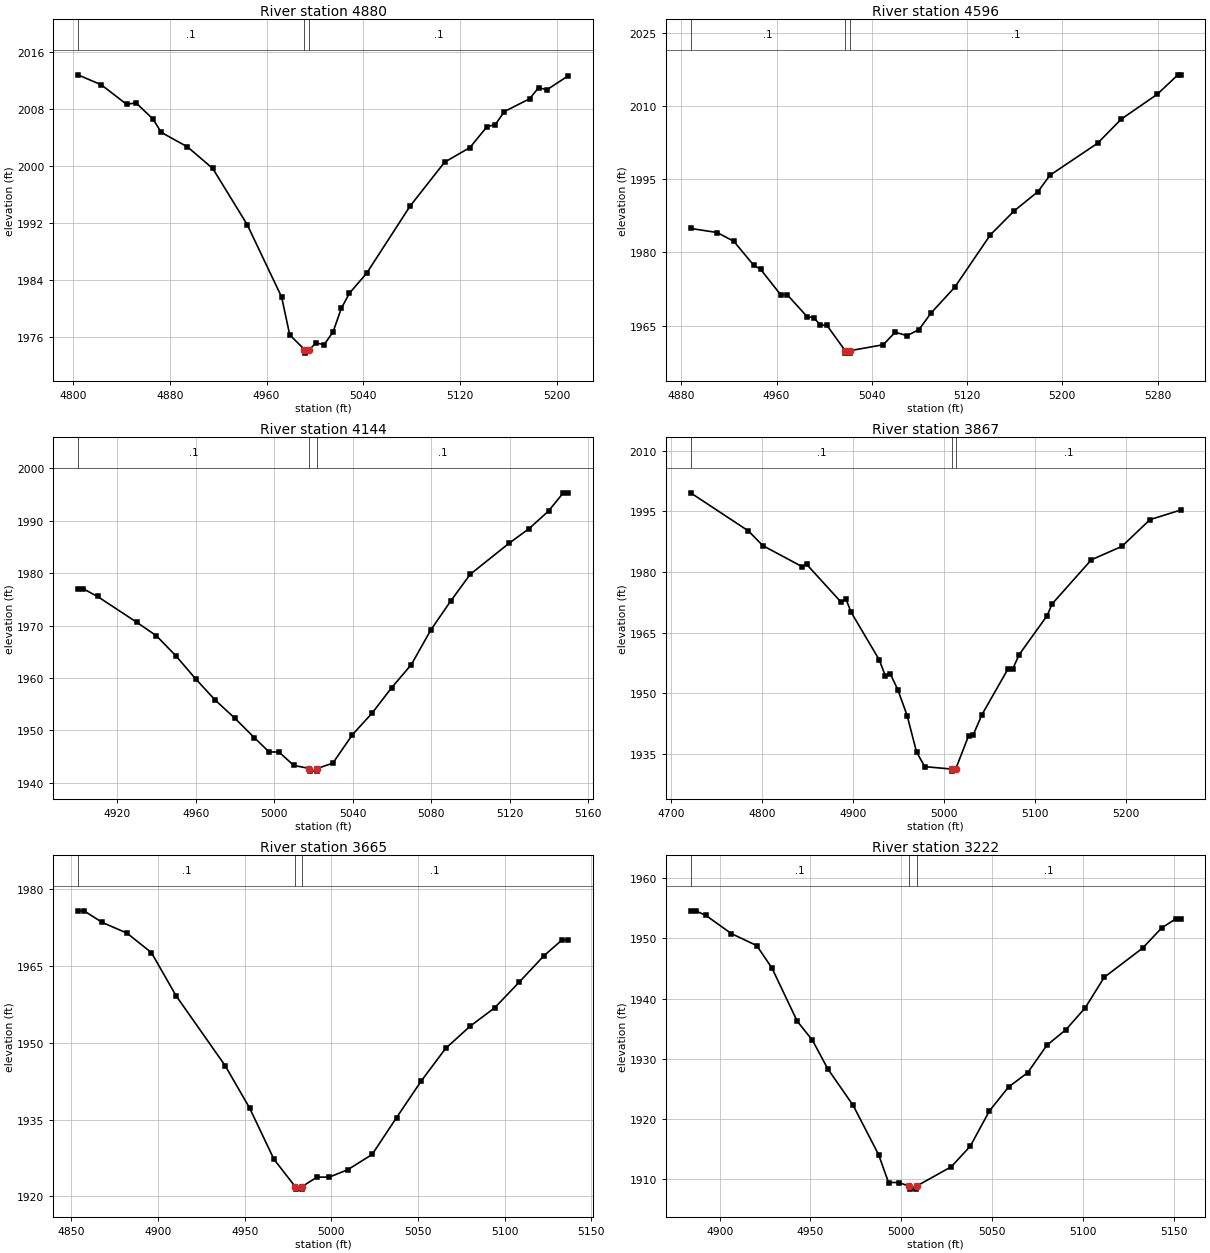
Type RM Length L Ch R = 1 ,4880    ,284,284,284
BEGIN DESCRIPTION:
Stream0583 11.0
END DESCRIPTION:
XS GIS Cut Line= 2
      1886525.56     13902702.77      1886794.16     13902399.52
#Sta/Elev= 30
  4804.1 2012.84  4823.5 2011.43  4844.4 2008.68    4852 2008.91  4866.2 2006.61
  4872.9 2004.75  4894.6 2002.71  4915.5 1999.67    4944 1991.76  4972.4 1981.59
  4979.1 1976.27  4991.3  1974.2  4991.5  1973.7  4995.3  1974.2  5000.8 1975.13
  5007.5 1974.89  5014.9 1976.68  5021.7 1979.98  5028.4 1982.12  5042.6 1984.92
  5078.6 1994.39  5107.1 2000.56    5128 2002.61  5142.2 2005.57  5148.9 2005.82
  5156.4 2007.67  5177.3 2009.47  5184.8 2011.05  5191.5 2010.73  5209.2  2012.7
#Mann= 3 ,-1 , 0
  4804.1      .1       0  4991.3     .05       0  4995.3      .1       0
Bank Sta=4991.3,4995.3
XS Rating Curve= 0 ,0
Exp/Cntr=0.3,0.1

Type RM Length L Ch R = 1 ,4596    ,452,452,452
BEGIN DESCRIPTION:
Stream0583 10.0
END DESCRIPTION:
XS GIS Cut Line= 3
      1886775.01     13902774.99        1886875.       13902725.
      1887175.01       13902725.
#Sta/Elev= 30
  4887.8  1984.9  4910.1 1984.06  4924.1 1982.26  4940.9 1977.32  4946.5 1976.56
  4963.3 1971.36  4968.8 1971.36  4985.6 1966.85  4991.2 1966.61  4996.8 1965.12
  5002.1 1965.12  5017.6 1959.87  5017.8 1959.37  5021.3 1959.37  5021.6 1959.87
  5049.6 1961.09  5059.6 1963.65  5069.6 1962.95  5079.6 1964.19  5089.6 1967.54
  5109.6 1972.85  5139.6  1983.6  5159.6  1988.5  5179.6 1992.45  5189.6 1995.79
  5229.6 2002.34  5249.6  2007.3  5279.6 2012.34  5297.1 2016.35  5299.6 2016.35
#Mann= 3 ,-1 , 0
  4887.8      .1       0  5017.6     .05       0  5021.6      .1       0
Bank Sta=5017.6,5021.6
XS Rating Curve= 0 ,0
Exp/Cntr=0.3,0.1

Type RM Length L Ch R = 1 ,4144    ,277,277,277
BEGIN DESCRIPTION:
Stream0583 9.0
END DESCRIPTION:
XS GIS Cut Line= 3
        1886825.       13903125.        1886925.       13903125.
        1887075.       13903125.
#Sta/Elev= 30
  4899.9 1977.04  4902.4 1977.04  4909.9 1975.54  4929.9 1970.62  4939.9 1968.05
  4949.9  1964.2  4959.9 1959.84  4969.9 1955.78  4979.9 1952.33  4989.9  1948.6
  4997.4 1945.89  5002.4 1945.89  5009.9 1943.34  5017.9 1942.74  5018.2 1942.24
  5021.7 1942.24  5021.9 1942.74  5029.9 1943.77  5039.9  1949.2  5049.9  1953.3
  5059.9 1958.16  5069.9 1962.55  5079.9 1969.19  5089.9 1974.62  5099.9 1979.75
  5119.9 1985.73  5129.9 1988.46  5139.9 1991.84  5147.4  1995.3  5149.9  1995.3
#Mann= 3 ,-1 , 0
  4899.9      .1       0  5017.9     .05       0  5021.9      .1       0
Bank Sta=5017.9,5021.9
XS Rating Curve= 0 ,0
Exp/Cntr=0.3,0.1

Type RM Length L Ch R = 1 ,3867    ,202,202,202
BEGIN DESCRIPTION:
Mapping XS 50832fa6
END DESCRIPTION:
XS GIS Cut Line= 2
      1886603.11     13903447.55      1887128.16     13903328.82
#Sta/Elev= 30
  4721.7 1999.57  4785.2 1990.13  4800.9 1986.52  4844.1 1981.31  4849.2 1981.85
  4887.2 1972.45  4892.4  1973.2  4897.9 1970.03  4928.7 1958.29  4935.5  1954.3
  4940.7 1954.87  4949.2 1950.86  4959.4 1944.48  4969.7 1935.49  4978.7 1931.83
  5008.7 1931.22    5009 1930.72  5012.7 1931.22    5027 1939.53  5032.1 1939.75
  5041.5 1944.67  5070.2 1956.02  5075.3 1955.98  5082.5 1959.57  5113.2 1969.21
  5118.5 1972.06  5161.7 1983.01  5195.3 1986.33    5226 1992.93    5260 1995.33
#Mann= 3 ,-1 , 0
  4721.7      .1       0  5008.7     .05       0  5012.7      .1       0
Bank Sta=5008.7,5012.7
XS Rating Curve= 0 ,0
Exp/Cntr=0.3,0.1

Type RM Length L Ch R = 1 ,3665    ,443,443,443
BEGIN DESCRIPTION:
Stream0583 8.0
END DESCRIPTION:
XS GIS Cut Line= 3
        1886825.       13903675.        1886925.       13903575.
      1887024.97     13903475.03
#Sta/Elev= 26
  4853.8 1975.82  4857.3 1975.82  4867.9 1973.54  4882.1 1971.46  4896.2 1967.64
  4910.4 1959.21  4938.7 1945.54  4952.8 1937.26  4966.9 1927.21  4979.1 1921.88
  4979.3 1921.38  4982.8 1921.38  4983.1 1921.88  4991.7 1923.73  4998.8 1923.73
  5009.4 1925.17  5023.5 1928.16  5037.6 1935.38  5051.8 1942.52  5065.9 1948.91
  5080.1 1953.27  5094.2 1956.85  5108.4 1961.89  5122.5    1967  5133.1 1970.14
  5136.6 1970.14
#Mann= 3 ,-1 , 0
  4853.8      .1       0  4979.1     .05       0  4983.1      .1       0
Bank Sta=4979.1,4983.1
XS Rating Curve= 0 ,0
Exp/Cntr=0.3,0.1

Type RM Length L Ch R = 1 ,3222    ,465,465,465
BEGIN DESCRIPTION:
Stream0583 7.0
END DESCRIPTION:
XS GIS Cut Line= 3
      1887124.98     13904025.04        1887175.       13903925.
      1887225.01     13903774.96
#Sta/Elev= 30
    4884 1954.59  4886.8 1954.59  4892.4 1953.83  4906.4 1950.81  4920.4 1948.81
  4928.8 1945.07  4942.7 1936.24  4951.1 1933.07  4959.5 1928.34  4973.5 1922.25
  4987.5 1914.07    4993 1909.43  4998.5 1909.43  5004.4 1908.83  5004.6 1908.33
  5008.1 1908.33  5008.4 1908.83  5027.5 1912.04    5038 1915.46  5048.5 1921.31
  5059.1 1925.31  5069.6 1927.68  5080.2 1932.25  5090.7 1934.84  5101.3 1938.47
  5111.8 1943.55  5132.9 1948.39  5143.4 1951.74  5151.3 1953.29    5154 1953.29
#Mann= 3 ,-1 , 0
    4884      .1       0  5004.4     .05       0  5008.4      .1       0
Bank Sta=5004.4,5008.4
XS Rating Curve= 0 ,0
Exp/Cntr=0.3,0.1

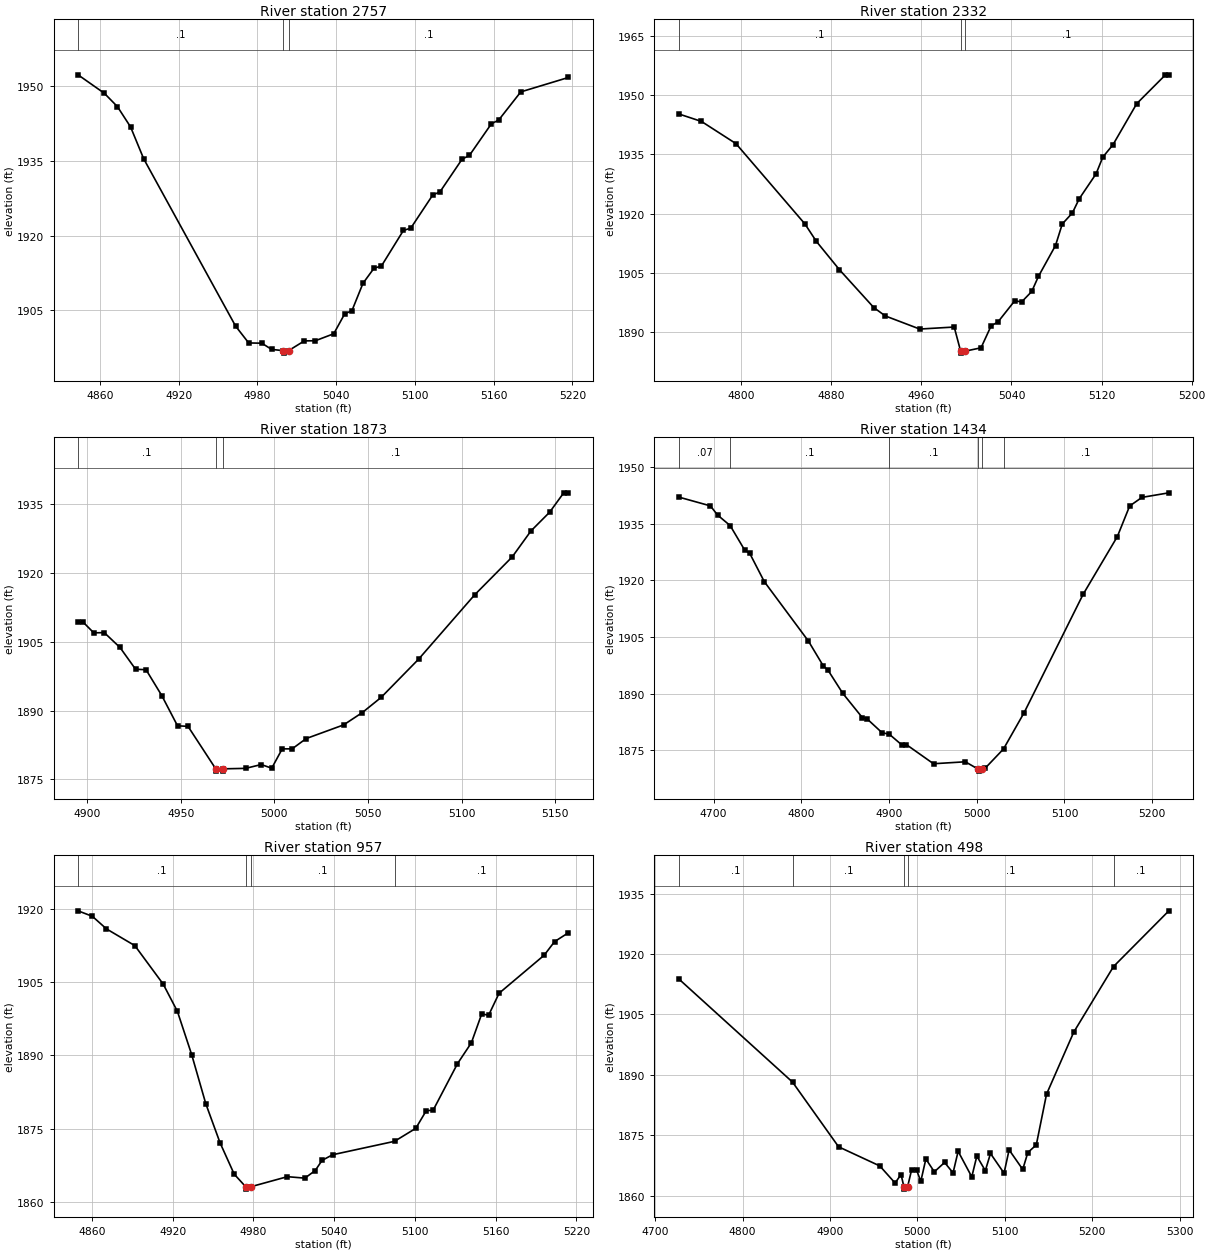
Type RM Length L Ch R = 1 ,2757    ,425,425,425
BEGIN DESCRIPTION:
Stream0583 6.0
END DESCRIPTION:
XS GIS Cut Line= 3
      1887224.96       13904225.        1887375.       13904225.
      1887574.96     13904125.02
#Sta/Elev= 30
  4843.4 1952.19  4863.4  1948.5  4873.4 1945.82  4883.4 1941.76  4893.4 1935.38
  4963.4 1901.88  4973.4  1898.5  4983.4 1898.45  4990.9  1897.2  4999.8 1896.96
  5000.1 1896.46  5003.8 1896.96  5015.8 1898.91  5024.2 1898.94  5038.2 1900.34
  5046.5  1904.3  5052.1 1904.98  5060.5 1910.45  5068.9 1913.47  5074.5 1913.89
  5091.3 1921.03  5096.9 1921.49  5113.6 1928.11  5119.2 1928.77    5136  1935.3
  5141.6 1936.06  5158.3 1942.38  5163.9 1943.14  5180.7 1948.77    5217 1951.66
#Mann= 3 ,-1 , 0
  4843.4      .1       0  4999.8     .05       0  5003.8      .1       0
Bank Sta=4999.8,5003.8
XS Rating Curve= 0 ,0
Exp/Cntr=0.3,0.1

Type RM Length L Ch R = 1 ,2332    ,459,459,459
BEGIN DESCRIPTION:
Stream0583 5.0
END DESCRIPTION:
XS GIS Cut Line= 3
      1887375.02       13904575.        1887625.       13904525.
      1887774.99     13904425.01
#Sta/Elev= 30
  4744.5  1945.3  4764.9 1943.37  4795.5 1937.74  4856.7 1917.36  4866.9 1912.92
  4887.3 1905.76  4917.8 1896.15    4928 1894.02  4958.6 1890.69  4989.2  1891.2
  4994.9 1885.08  4995.1 1884.58  4998.9 1885.08    5013 1885.93    5022 1891.52
    5028 1892.48    5043 1897.89    5049 1897.56    5058 1900.22    5064 1904.08
  5079.1 1911.89  5085.1 1917.35  5094.1 1920.16  5100.1 1923.73  5115.1 1930.08
  5121.1 1934.33  5130.1 1937.46  5151.2 1947.89  5176.7  1955.2  5179.7  1955.2
#Mann= 3 ,-1 , 0
  4744.5      .1       0  4994.9     .05       0  4998.9      .1       0
Bank Sta=4994.9,4998.9
XS Rating Curve= 0 ,0
Exp/Cntr=0.3,0.1

Type RM Length L Ch R = 1 ,1873    ,439,439,439
BEGIN DESCRIPTION:
Stream0583 4.0
END DESCRIPTION:
XS GIS Cut Line= 3
        1887525.       13904875.        1887625.       13904925.
        1887775.       13904925.
#Sta/Elev= 30
  4895.2  1909.2    4898  1909.2  4903.6 1906.91  4909.2 1906.96  4917.6 1903.72
  4925.9 1898.99  4931.5 1898.88  4939.9 1893.25  4948.3 1886.67  4953.9 1886.55
  4968.7  1877.3  4968.9  1876.8  4972.4  1876.8  4972.7  1877.3  4984.6  1877.4
    4993 1878.23  4998.6 1877.44  5004.2 1881.65  5009.5 1881.65    5017 1883.89
    5037 1886.87    5047 1889.56    5057 1892.85    5077 1901.17    5107 1915.21
    5127 1923.45    5137  1929.1    5147 1933.19  5154.5  1937.4    5157  1937.4
#Mann= 3 ,-1 , 0
  4895.2      .1       0  4968.7     .05       0  4972.7      .1       0
Bank Sta=4968.7,4972.7
XS Rating Curve= 0 ,0
Exp/Cntr=0.3,0.1

Type RM Length L Ch R = 1 ,1434    ,477,477,477
BEGIN DESCRIPTION:
Stream0583 3.0
END DESCRIPTION:
XS GIS Cut Line= 3
      1887425.01       13905475.        1887725.       13905325.
      1887924.99       13905225.
#Sta/Elev= 30
    4660 1942.16  4696.3 1939.81  4704.7 1937.34  4718.9 1934.57  4735.5 1928.05
    4741 1927.29  4757.8  1919.7  4808.1 1903.92  4824.9 1897.39  4830.5 1896.17
  4847.3 1890.04  4869.6  1883.6  4875.2 1883.22    4892 1879.61  4900.4 1879.18
  4914.3 1876.41  4919.9 1876.42  4950.7 1871.36    4987 1871.88  5001.8  1869.9
    5002  1869.4  5005.8  1869.9  5009.4 1870.13  5030.5 1875.28  5054.1 1884.96
  5121.2  1916.3  5160.3 1931.67  5174.3 1939.77  5188.3 1942.06    5219 1943.27
#Mann= 6 ,-1 , 0
    4660     .07       0  4718.9      .1       0  4900.4      .1       0
  5001.8     .05       0  5005.8      .1       0  5030.5      .1       0
Bank Sta=5001.8,5005.8
XS Rating Curve= 0 ,0
Exp/Cntr=0.3,0.1

Type RM Length L Ch R = 1 ,957     ,459,459,459
BEGIN DESCRIPTION:
Stream0583 2.0
END DESCRIPTION:
XS GIS Cut Line= 3
      1887874.99     13905875.04        1887925.       13905725.
        1887975.     13905525.01
#Sta/Elev= 30
  4849.7 1919.59  4860.3 1918.47  4870.8 1915.89  4891.9 1912.46    4913 1904.56
  4923.5    1899  4934.1 1890.15  4944.6 1880.08  4955.2 1872.07  4965.7 1865.66
  4974.2 1863.09  4974.5 1862.59  4978.2 1863.09  5005.2 1865.14  5018.2 1864.84
  5025.9  1866.4    5031 1868.48  5038.8 1869.63  5084.8 1872.38  5100.6 1875.04
  5108.4 1878.66  5113.5 1878.75  5131.6 1888.29  5141.9 1892.56  5149.6 1898.49
  5154.7  1898.2  5162.5 1902.71    5196  1910.5  5203.7 1913.28    5214  1915.1
#Mann= 4 ,-1 , 0
  4849.7      .1       0  4974.2     .05       0  4978.2      .1       0
  5084.8      .1       0
Bank Sta=4974.2,4978.2
XS Rating Curve= 0 ,0
Exp/Cntr=0.3,0.1

Type RM Length L Ch R = 1 ,498     ,251,251,251
BEGIN DESCRIPTION:
Stream0583 1.0
END DESCRIPTION:
XS GIS Cut Line= 3
      1888024.97     13906075.01        1888275.       13905975.
      1888424.98     13905725.03
#Sta/Elev= 30
  4726.8 1913.88  4857.2  1888.2  4909.9 1872.13    4957 1867.38  4974.5 1863.14
  4981.3 1865.25  4984.7 1862.12  4984.9 1861.62  4988.7 1862.12  4993.4 1866.41
    4999 1866.41  5003.9 1863.55  5009.7  1869.1  5019.4 1865.92  5031.1 1868.24
  5040.8 1865.66  5046.6 1871.01  5062.2 1864.67    5068 1869.82  5077.7  1866.2
  5083.6 1870.47  5099.1 1865.58  5104.9 1871.37  5120.5 1866.51  5126.3  1870.7
    5136 1872.61  5147.7  1885.2  5178.8 1900.59  5224.3 1916.89  5287.6 1930.73
#Mann= 5 ,-1 , 0
  4726.8      .1       0  4857.2      .1       0  4984.7     .05       0
  4988.7      .1       0  5224.3      .1       0
Bank Sta=4984.7,4988.7
XS Rating Curve= 0 ,0
Exp/Cntr=0.3,0.1

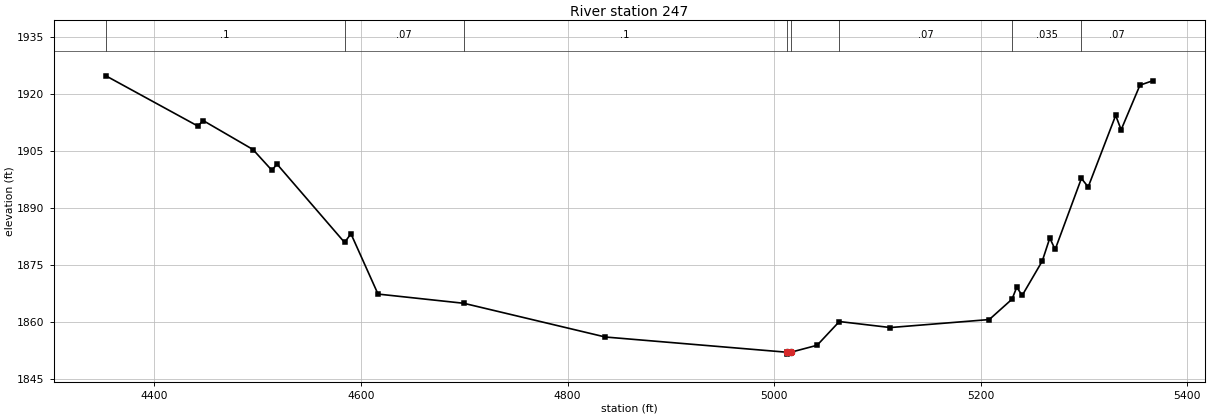
Type RM Length L Ch R = 1 ,247     ,0,0,0
BEGIN DESCRIPTION:
Stream0583 0.0
END DESCRIPTION:
XS GIS Cut Line= 4
      1887913.99     13906192.61      1888382.43     13906127.33
      1888586.17     13905951.51      1888670.34     13905692.94
#Sta/Elev= 30
    4353 1924.74  4442.1 1911.52  4447.1 1912.99  4495.4 1905.37  4513.7 1899.91
  4518.7 1901.52  4584.1 1880.94  4590.3 1883.21  4616.5 1867.36  4699.5 1864.94
  4836.6 1856.07  5012.3 1852.07  5012.5 1851.57  5016.3 1852.07  5041.7  1853.9
  5063.2 1860.14  5112.6 1858.56  5208.4 1860.66  5230.4 1866.01    5235 1869.14
  5240.3 1867.01  5259.7 1876.03    5267 1882.08  5272.2 1879.08  5297.6 1897.76
  5304.2 1895.53  5330.8 1914.33  5336.1 1910.56  5354.3 1922.28    5367 1923.48
#Mann= 8 ,-1 , 0
    4353      .1       0  4584.1     .07       0  4699.5      .1       0
  5012.3     .05       0  5016.3      .1       0  5063.2     .07       0
  5230.4    .035       0  5297.6     .07       0
Bank Sta=5012.3,5016.3
XS Rating Curve= 0 ,0
Exp/Cntr=0.3,0.1

Chan Stop Cuts=-1
Use User Specified Reach Order=0
Composite Channel Slope=5