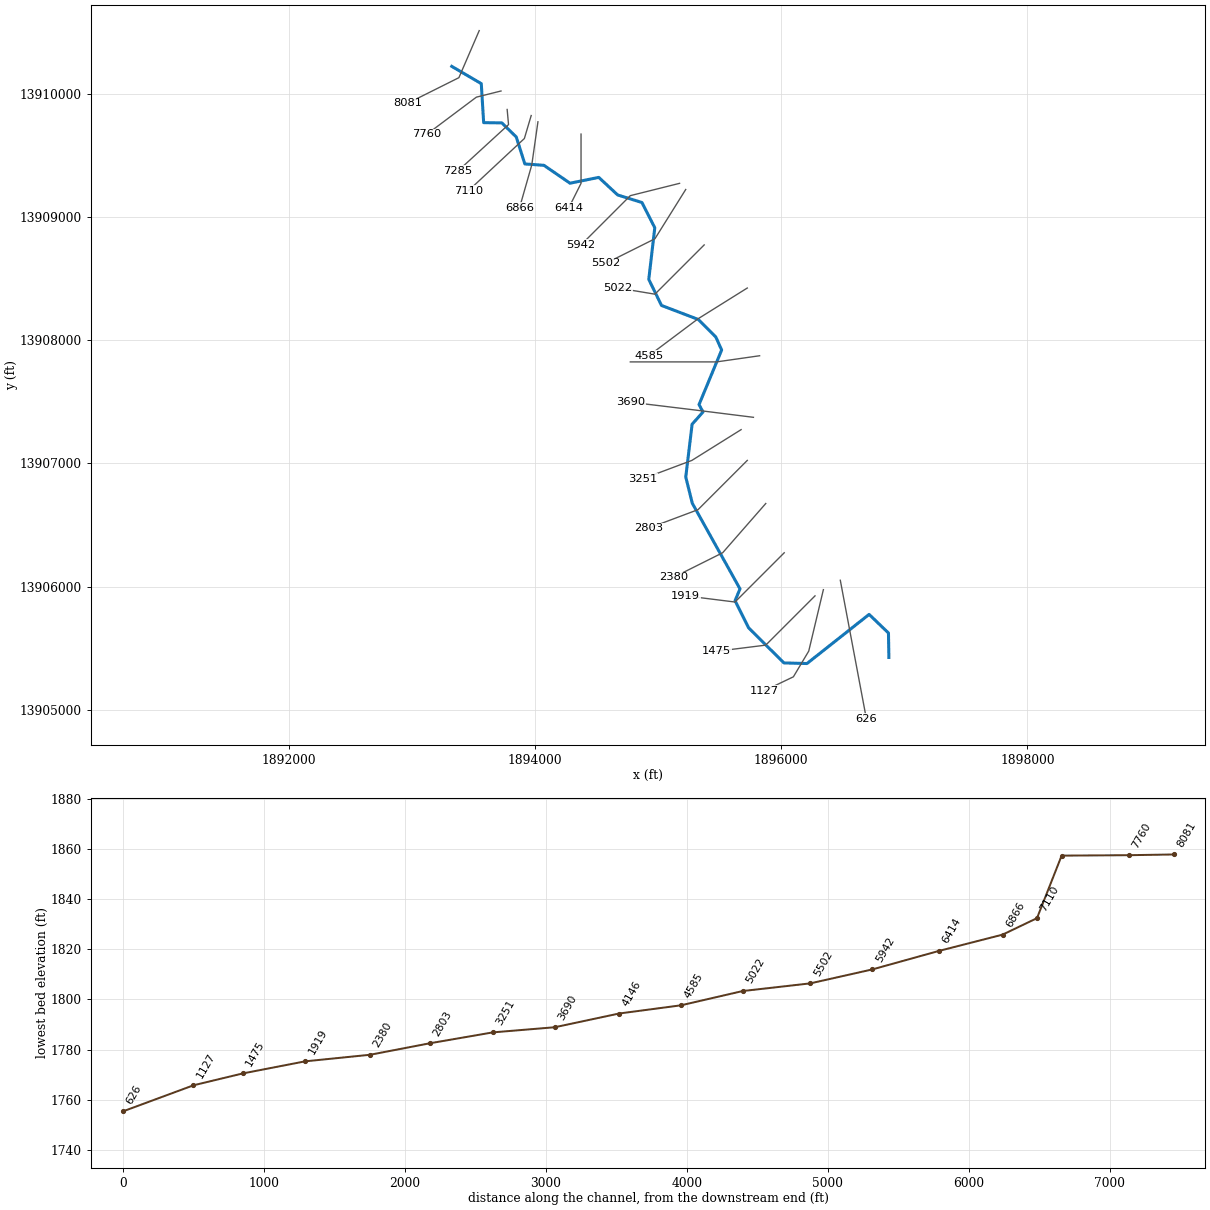
--- Stream0584.prj (project) ---

Proj Title=Stream0584 Base Level Engineering
Current Plan=p01
Default Exp/Contr=0.3,0.1
English Units
Geom File=g01
Flow File=f01
Plan File=p01
BEGIN DESCRIPTION:
Stream0584
END DESCRIPTION:

--- Stream0584.p01 (plan) ---

Plan Title=Multiple Run
Short Identifier=Multiple
Geom File=g01
Flow File=f01
Subcritical Flow
K Sum by GR= 0
Std Step Tol= 0.01
Critical Tol= 0.01
Num of Std Step Trials= 20
Max Error Tol= 0.3
Flow Tol Ratio= 0.001
Split Flow NTrial= 30
Split Flow Tol= 0.02
Split Flow Ratio= 0.02
Log Output Level= 0
Friction Slope Method= 1
Unsteady Friction Slope Method= 2
Unsteady Bridges Friction Slope Method= 1
Parabolic Critical Depth
Global Vel Dist=  1 , 1 , 1
Global Log Level= 0
CheckData=True
Encroach Param= -1, 0, 0, 0
BEGIN DESCRIPTION:
Multiple Run
END DESCRIPTION:

--- Stream0584.f01 (steady flow) ---

Flow Title=Multiple
Number of Profiles=7
Profile Names=10-year,25-year,50-year,1pct_min,100-year,1pct_plu,500-year
River Rch & RM= Stream0584,Reach-1,8081
    2370    4223    6062    4198    8377   16713   15813
River Rch & RM= Stream0584,Reach-1,1919
    2645    4735    6817    4732    9442   18840   17917
Boundary for River Rch & Prof#=Stream0584,Reach-1,1
Up Type=0
Dn Type=3
Dn Slope=0.005
Boundary for River Rch & Prof#=Stream0584,Reach-1,2
Up Type=0
Dn Type=3
Dn Slope=0.005
Boundary for River Rch & Prof#=Stream0584,Reach-1,3
Up Type=0
Dn Type=3
Dn Slope=0.005
Boundary for River Rch & Prof#=Stream0584,Reach-1,4
Up Type=0
Dn Type=3
Dn Slope=0.005
Boundary for River Rch & Prof#=Stream0584,Reach-1,5
Up Type=0
Dn Type=3
Dn Slope=0.005
Boundary for River Rch & Prof#=Stream0584,Reach-1,6
Up Type=0
Dn Type=3
Dn Slope=0.005
Boundary for River Rch & Prof#=Stream0584,Reach-1,7
Up Type=0
Dn Type=3
Dn Slope=0.005

--- Stream0584.g01 (geometry) ---

Geom Title=Existing Conditions

River Reach=Stream0584,Reach-1
Reach XY= 30
      1893325.00     13910225.00      1893564.80     13910084.70
      1893584.18     13909767.95      1893731.73     13909765.85
      1893848.83     13909651.88      1893918.48     13909432.68
      1894073.53     13909421.45      1894285.50     13909276.19
      1894518.97     13909323.38      1894672.57     13909180.52
      1894869.42     13909119.42      1894973.81     13908914.50
      1894925.06     13908495.03      1895028.50     13908283.46
      1895327.43     13908169.48      1895469.19     13908027.29
      1895516.94     13907921.71      1895333.25     13907478.23
      1895365.68     13907418.34      1895277.07     13907319.15
      1895225.38     13906890.27      1895278.55     13906676.47
      1895665.83     13905981.72      1895625.80     13905885.70
      1895735.76     13905665.32      1896022.55     13905380.46
      1896209.79     13905375.50      1896714.36     13905774.45
      1896871.47     13905623.54      1896875.00     13905425.00

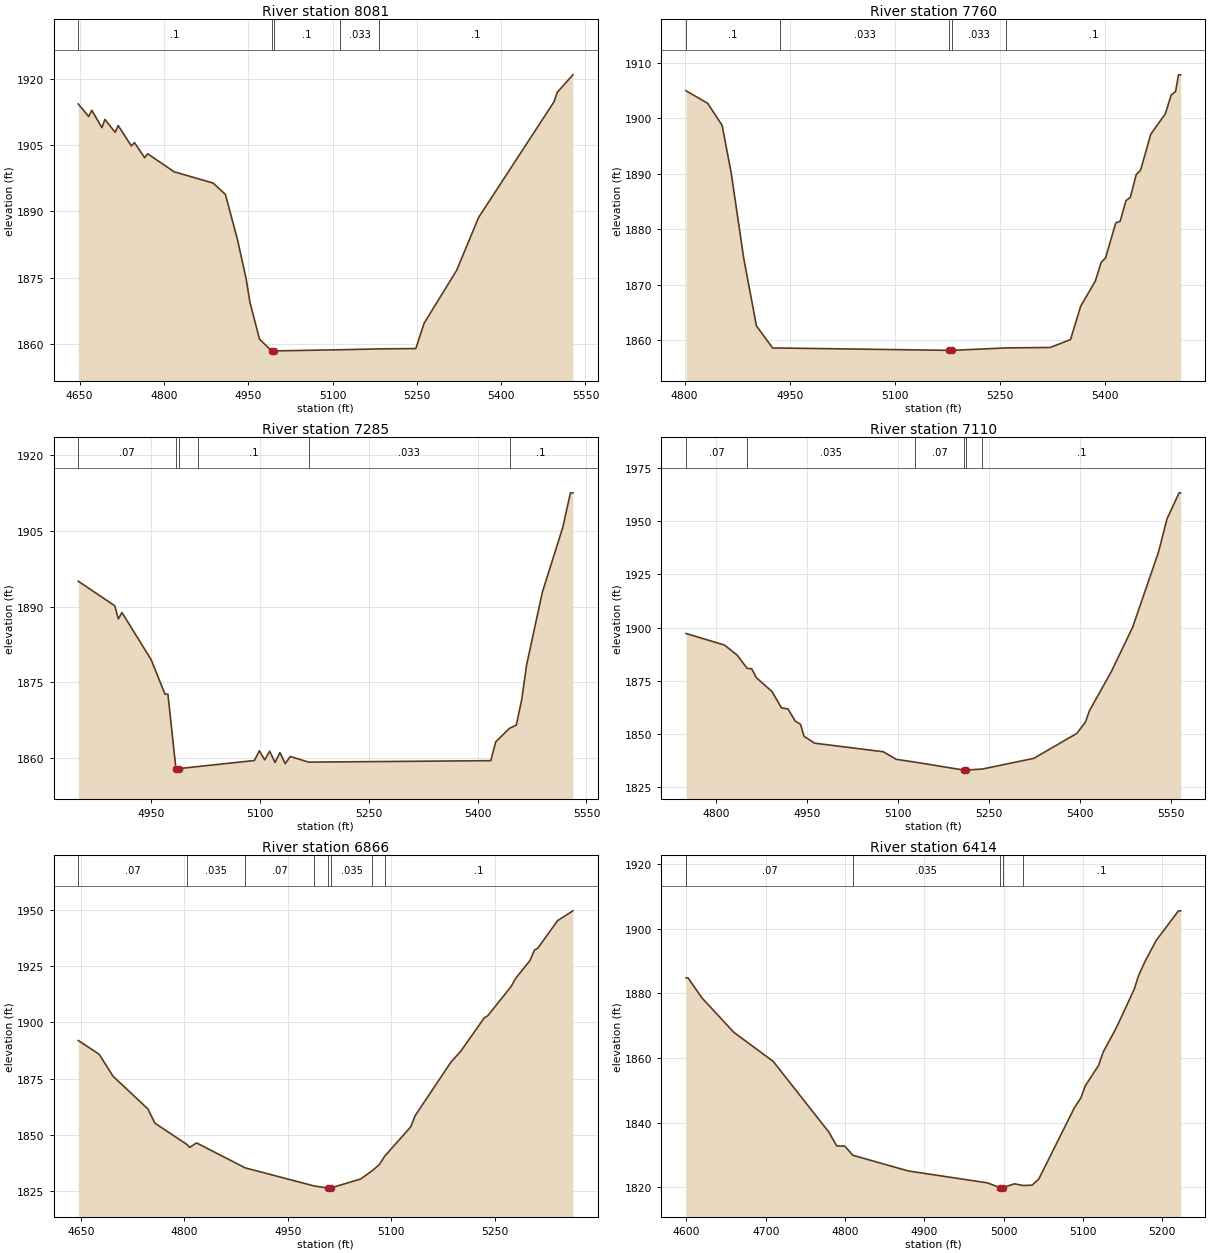
Type RM Length L Ch R = 1,8081,321,321,321
BEGIN DESCRIPTION:
Stream0584 16.0
END DESCRIPTION:
XS GIS Cut Line= 3
      1893548.13     13910515.31      1893383.19     13910133.34
      1892968.23     13909925.86
#Sta/Elev= 30
  4647.6 1914.30  4666.2 1911.45  4671.6 1912.86  4689.7 1908.94  4695.1 1910.80
  4713.2 1907.88  4718.6 1909.41  4742.2 1904.79  4747.6 1905.56  4765.7 1902.14
  4771.1 1903.03  4818.1 1898.96  4887.6 1896.39  4909.4 1893.82  4931.1 1883.48
  4946.5 1874.57  4952.9 1869.50  4970.0 1861.10  4991.5 1858.42  4991.8 1857.92
  4995.5 1858.42  5113.6 1858.68  5183.1 1858.88  5248.1 1858.95  5262.9 1864.69
  5320.7 1876.64  5359.9 1888.63  5494.0 1914.79  5499.6 1916.90  5527.6 1920.89
#Mann=5,-1,0
  4647.6     0.1       0  4991.5    0.05       0  4995.5     0.1       0
  5113.6   0.033       0  5183.1     0.1       0
Bank Sta=4991.5,4995.5
Exp/Cntr=0.3,0.1

Type RM Length L Ch R = 1,7760,475,475,475
BEGIN DESCRIPTION:
Stream0584 15.0
END DESCRIPTION:
XS GIS Cut Line= 3
      1893724.97     13910024.99      1893525.00     13909975.00
      1893125.02     13909675.01
#Sta/Elev= 30
  4802.0 1904.98  4832.9 1902.72  4853.5 1898.74  4866.4 1890.18  4884.4 1874.71
  4902.5 1862.54  4925.7 1858.54  4936.1 1858.55  5177.9 1858.13  5178.2 1857.63
  5182.0 1858.13  5258.6 1858.57  5321.7 1858.65  5350.8 1860.07  5365.4 1866.11
  5386.2 1870.62  5394.6 1874.02  5400.8 1874.79  5415.4 1881.13  5421.7 1881.42
  5430.0 1885.16  5436.2 1885.74  5444.6 1889.85  5450.8 1890.64  5465.4 1897.14
  5486.2 1900.83  5494.6 1904.23  5500.8 1904.85  5505.0 1907.86  5508.1 1907.86
#Mann=5,-1,0
  4802.0     0.1       0  4936.1   0.033       0  5177.9   0.033       0
  5182.0   0.033       0  5258.6     0.1       0
Bank Sta=5177.9,5182
Exp/Cntr=0.3,0.1

Type RM Length L Ch R = 1,7285,175,175,175
BEGIN DESCRIPTION:
Stream0584 14.0
END DESCRIPTION:
XS GIS Cut Line= 3
      1893775.00     13909874.98      1893786.17     13909752.03
      1893375.02     13909375.02
#Sta/Elev= 30
  4850.0 1895.01  4900.2 1890.16  4905.2 1887.55  4910.2 1888.81  4950.4 1879.49
  4969.5 1872.67  4973.5 1872.67  4984.5 1857.96  4984.7 1857.46  4988.6 1857.96
  5015.3 1858.37  5092.6 1859.56  5099.4 1861.48  5106.8 1859.69  5113.6 1861.41
  5121.0 1859.18  5127.8 1861.14  5135.1 1858.93  5141.9 1860.36  5167.4 1859.24
  5418.2 1859.53  5425.0 1863.26  5444.0 1865.93  5453.3 1866.54  5460.7 1871.52
  5467.5 1878.43  5489.1 1892.77  5517.4 1905.68  5527.9 1912.48  5531.3 1912.48
#Mann=6,-1,0
  4850.0    0.07       0  4984.5    0.05       0  4988.6    0.07       0
  5015.3     0.1       0  5167.4   0.033       0  5444.0     0.1       0
Bank Sta=4984.5,4988.6
Exp/Cntr=0.3,0.1

Type RM Length L Ch R = 1,7110,244,244,244
BEGIN DESCRIPTION:
Mapping XS f5cb67c3
END DESCRIPTION:
XS GIS Cut Line= 3
      1893970.19     13909825.73      1893914.76     13909639.03
      1893461.78     13909216.36
#Sta/Elev= 30
  4751.1 1897.19  4814.4 1891.76  4835.3 1887.01  4851.6 1880.80  4859.3 1880.60
  4866.6 1876.48  4892.5 1869.94  4908.3 1862.19  4918.8 1861.75  4930.9 1856.02
  4939.6 1854.46  4945.3 1848.88  4962.6 1845.63  5075.9 1841.59  5096.9 1838.04
  5128.3 1836.71  5208.2 1832.98  5208.5 1832.48  5212.3 1832.98  5239.0 1833.47
  5323.6 1838.49  5394.4 1850.21  5408.6 1855.55  5415.4 1860.99  5451.1 1879.18
  5486.3 1900.11  5528.8 1935.39  5542.9 1951.10  5562.8 1963.32  5565.4 1963.32
#Mann=6,-1,0
  4751.1    0.07       0  4851.6   0.035       0  5128.3    0.07       0
  5208.2   0.035       0  5212.3    0.07       0  5239.0     0.1       0
Bank Sta=5208.2,5212.3
Exp/Cntr=0.3,0.1

Type RM Length L Ch R = 1,6866,452,452,452
BEGIN DESCRIPTION:
Stream0584 13.0
END DESCRIPTION:
XS GIS Cut Line= 3
      1894025.00     13909775.00      1893975.00     13909425.00
      1893874.99     13909074.96
#Sta/Elev= 30
  4646.1 1891.90  4676.4 1885.80  4696.6 1876.00  4747.1 1861.53  4757.2 1855.21
  4803.5 1845.79  4807.7 1844.45  4817.8 1846.41  4888.2 1835.35  4988.0 1827.33
  5008.0 1826.40  5008.3 1825.90  5012.2 1826.40  5055.6 1830.38  5072.6 1834.09
  5082.9 1836.80  5090.8 1840.57  5128.4 1853.56  5134.9 1858.56  5186.9 1882.37
  5201.2 1887.22  5235.0 1901.91  5240.2 1902.91  5274.0 1915.84  5280.5 1919.44
  5301.3 1927.35  5307.8 1931.97  5313.0 1932.98  5341.6 1945.15  5363.7 1949.48
#Mann=8,-1,0
  4646.1    0.07       0  4803.5   0.035       0  4888.2    0.07       0
  4988.0   0.035       0  5008.0   0.035       0  5012.2   0.035       0
  5072.6    0.07       0  5090.8     0.1       0
Bank Sta=5008,5012.2
Exp/Cntr=0.3,0.1

Type RM Length L Ch R = 1,6414,472,472,472
BEGIN DESCRIPTION:
Stream0584 12.0
END DESCRIPTION:
XS GIS Cut Line= 3
      1894375.00     13909674.98      1894375.00     13909275.00
      1894274.99     13909074.99
#Sta/Elev= 30
  4599.5 1884.82  4602.0 1884.82  4619.5 1878.62  4659.5 1868.00  4709.5 1858.92
  4779.5 1837.07  4789.5 1832.75  4799.5 1832.72  4809.8 1829.88  4879.5 1825.02
  4979.5 1821.33  4994.9 1819.89  4995.2 1819.39  4999.1 1819.89  5013.5 1821.03
  5024.8 1820.51  5035.8 1820.62  5044.2 1822.52  5088.9 1844.51  5097.3 1847.65
  5102.9 1851.41  5119.7 1857.75  5125.3 1861.80  5142.0 1869.36  5164.4 1881.23
  5170.0 1885.52  5178.4 1890.03  5192.3 1896.43  5220.3 1905.57  5223.1 1905.57
#Mann=5,-1,0
  4599.5    0.07       0  4809.8   0.035       0  4994.9   0.035       0
  4999.1   0.035       0  5024.8     0.1       0
Bank Sta=4994.9,4999.1
Exp/Cntr=0.3,0.1

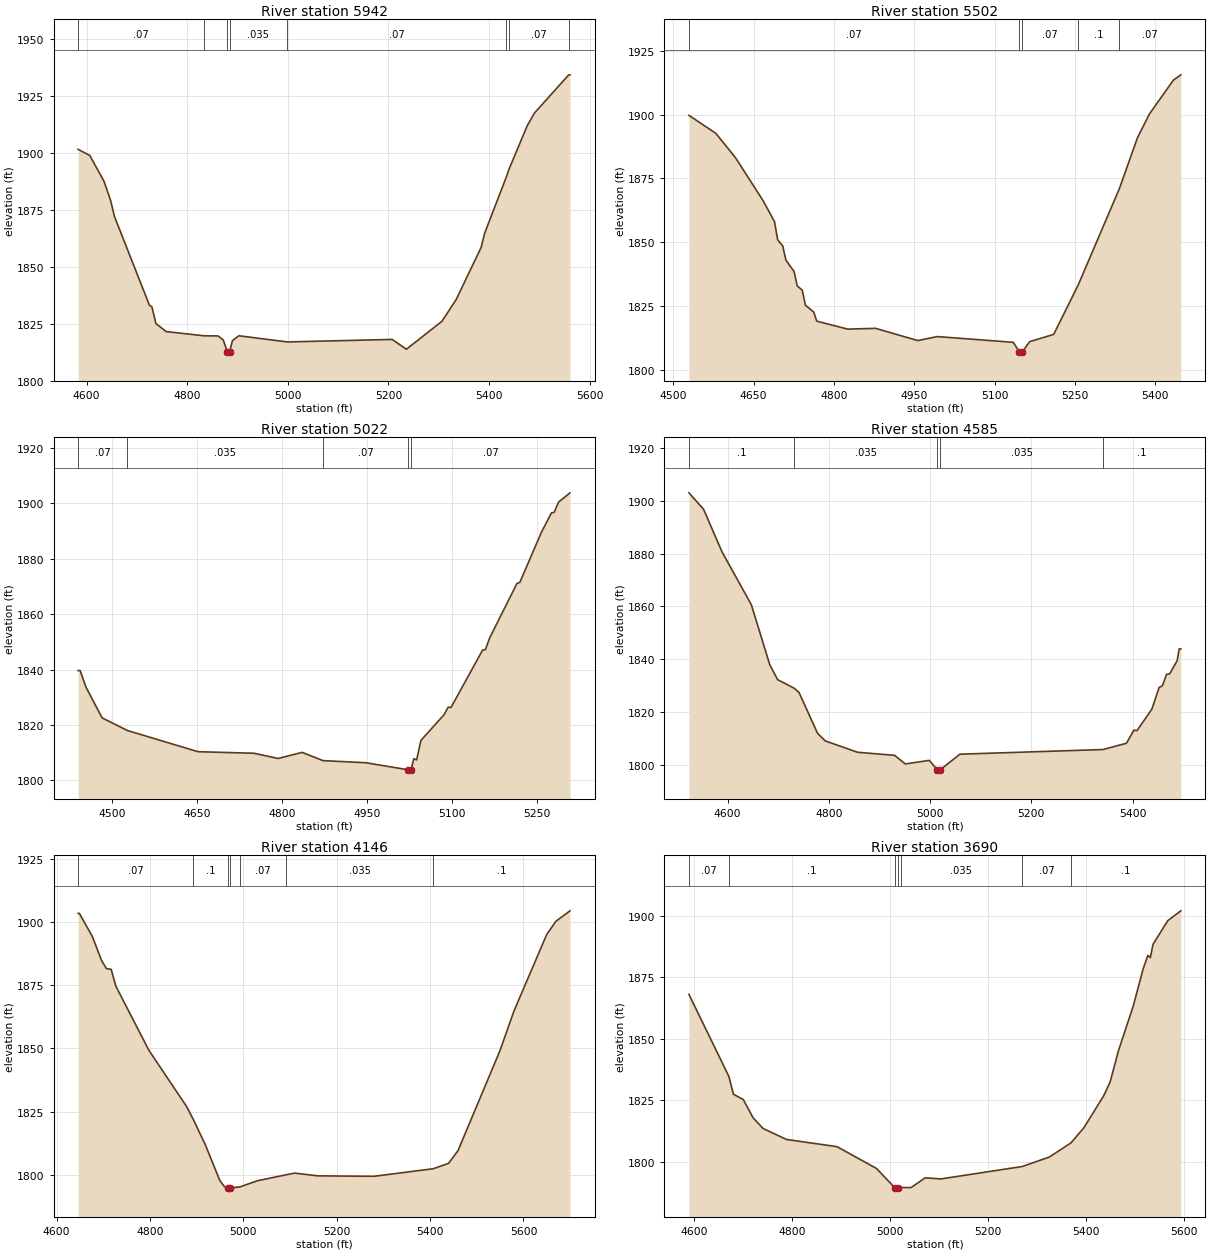
Type RM Length L Ch R = 1,5942,440,440,440
BEGIN DESCRIPTION:
Stream0584 11.0
END DESCRIPTION:
XS GIS Cut Line= 3
      1895175.00     13909275.00      1894775.00     13909175.00
      1894375.00     13908775.00
#Sta/Elev= 30
  4583.1 1901.40  4606.3 1898.71  4634.6 1887.36  4647.5 1879.15  4655.3 1871.96
  4724.8 1833.07  4730.0 1832.19  4737.7 1824.99  4758.3 1821.45  4833.2 1819.62
  4861.4 1819.55  4871.7 1817.78  4879.9 1812.51  4880.2 1812.01  4884.1 1812.51
  4889.8 1817.42  4902.6 1819.63  4999.1 1816.92  5207.5 1818.02  5235.8 1813.71
  5306.5 1825.98  5334.8 1835.52  5384.3 1858.32  5391.4 1864.59  5434.7 1889.38
  5439.7 1892.59  5476.2 1911.83  5490.4 1917.32  5558.6 1934.09  5561.1 1934.09
#Mann=8,-1,0
  4583.1    0.07       0  4833.2   0.035       0  4879.9    0.05       0
  4884.1   0.035       0  4999.1    0.07       0  5434.7     0.1       0
  5439.7    0.07       0  5558.6     0.1       0
Bank Sta=4879.9,4884.1
Exp/Cntr=0.3,0.1

Type RM Length L Ch R = 1,5502,480,480,480
BEGIN DESCRIPTION:
Stream0584 10.0
END DESCRIPTION:
XS GIS Cut Line= 3
      1895225.02     13909225.03      1894975.00     13908825.00
      1894575.04     13908625.02
#Sta/Elev= 30
  4529.1 1899.79  4579.3 1892.73  4615.8 1883.24  4667.7 1866.27  4688.9 1858.08
  4694.8 1850.94  4704.3 1848.53  4710.2 1842.94  4725.5 1838.49  4731.4 1832.83
  4740.8 1831.13  4746.7 1825.21  4762.0 1822.62  4767.9 1818.99  4825.7 1815.87
  4877.6 1816.17  4956.6 1811.37  4993.2 1812.94  5135.0 1810.68  5146.2 1806.94
  5146.6 1806.44  5151.8 1806.94  5165.7 1810.94  5210.5 1813.80  5256.4 1833.24
  5333.2 1871.00  5367.0 1891.00  5389.4 1900.35  5434.1 1913.61  5448.0 1915.70
#Mann=5,-1,0
  4529.1    0.07       0  5146.2    0.05       0  5151.8    0.07       0
  5256.4     0.1       0  5333.2    0.07       0
Bank Sta=5146.2,5151.8
Exp/Cntr=0.3,0.1

Type RM Length L Ch R = 1,5022,437,437,437
BEGIN DESCRIPTION:
Stream0584 9.0
END DESCRIPTION:
XS GIS Cut Line= 3
      1895375.00     13908775.00      1894975.00     13908375.00
      1894675.03     13908425.00
#Sta/Elev= 30
  4439.3 1839.65  4442.8 1839.65  4453.4 1833.60  4481.7 1822.59  4526.5 1818.03
  4651.4 1810.38  4750.4 1809.82  4792.9 1807.93  4835.3 1810.14  4872.3 1807.16
  4948.4 1806.39  5022.5 1803.87  5022.9 1803.37  5028.1 1803.87  5032.9 1807.86
  5037.9 1807.43  5045.5 1814.47  5086.1 1823.66  5093.7 1826.43  5098.8 1826.37
  5154.5 1847.04  5159.6 1847.24  5167.2 1851.50  5215.4 1871.13  5220.4 1871.48
  5258.4 1889.50  5276.2 1896.54  5281.2 1896.79  5288.9 1900.48  5309.1 1903.81
#Mann=5,-1,0
  4439.3    0.07       0  4526.5   0.035       0  4872.3    0.07       0
  5022.5    0.05       0  5028.1    0.07       0
Bank Sta=5022.5,5028.1
Exp/Cntr=0.3,0.1

Type RM Length L Ch R = 1,4585,439,439,439
BEGIN DESCRIPTION:
Stream0584 8.0
END DESCRIPTION:
XS GIS Cut Line= 3
      1895724.96     13908424.98      1895325.00     13908175.00
      1894924.96     13907874.97
#Sta/Elev= 30
  4523.6 1903.02  4552.4 1896.82  4589.0 1880.65  4646.8 1860.70  4683.3 1837.92
  4698.7 1832.32  4731.6 1829.04  4741.1 1827.43  4777.7 1811.97  4793.0 1809.11
  4856.7 1804.82  4929.8 1803.66  4951.0 1800.40  4998.4 1801.75  5014.2 1798.18
  5014.7 1797.68  5020.0 1798.18  5058.8 1804.09  5341.5 1805.85  5388.0 1808.24
  5402.5 1813.16  5408.8 1813.04  5438.0 1821.09  5452.5 1829.39  5458.8 1829.94
  5467.1 1834.30  5473.4 1834.52  5488.0 1839.47  5492.1 1843.95  5495.3 1843.95
#Mann=5,-1,0
  4523.6     0.1       0  4731.6   0.035       0  5014.2   0.035       0
  5020.0   0.035       0  5341.5     0.1       0
Bank Sta=5014.2,5020
Exp/Cntr=0.3,0.1

Type RM Length L Ch R = 1,4146,456,456,456
BEGIN DESCRIPTION:
Stream0584 7.0
END DESCRIPTION:
XS GIS Cut Line= 3
      1895825.05     13907875.01      1895475.00     13907825.00
      1894775.00     13907825.00
#Sta/Elev= 30
  4646.1 1903.35  4648.7 1903.35  4676.5 1894.23  4696.7 1884.55  4706.8 1881.53
  4716.9 1881.23  4727.0 1874.56  4797.7 1849.24  4878.5 1827.03  4892.9 1821.91
  4918.9 1811.79  4949.2 1797.98  4959.3 1795.40  4966.5 1794.90  4966.9 1794.40
  4972.3 1794.90  4992.1 1795.24  5029.7 1797.69  5090.7 1800.02  5109.7 1800.73
  5159.7 1799.64  5279.7 1799.47  5406.8 1802.46  5439.7 1804.59  5459.7 1809.56
  5549.7 1849.10  5579.7 1864.78  5649.7 1894.94  5669.7 1900.26  5699.7 1904.36
#Mann=7,-1,0
  4646.1    0.07       0  4892.9     0.1       0  4966.5    0.05       0
  4972.3     0.1       0  4992.1    0.07       0  5090.7   0.035       0
  5406.8     0.1       0
Bank Sta=4966.5,4972.3
Exp/Cntr=0.3,0.1

Type RM Length L Ch R = 1,3690,439,439,439
BEGIN DESCRIPTION:
Stream0584 6.0
END DESCRIPTION:
XS GIS Cut Line= 3
      1895774.98     13907375.00      1895293.27     13907435.25
      1894778.59     13907497.52
#Sta/Elev= 30
  4589.1 1868.09  4670.8 1834.65  4679.8 1827.52  4699.9 1825.36  4720.1 1817.90
  4740.3 1813.59  4788.1 1809.12  4891.4 1806.18  4972.0 1797.30  5009.4 1789.42
  5009.9 1788.92  5015.3 1789.42  5021.1 1789.57  5042.6 1789.57  5071.2 1793.52
  5103.0 1793.06  5269.2 1798.11  5324.6 1801.96  5368.8 1807.72  5395.2 1813.89
  5435.4 1826.80  5448.8 1832.56  5465.7 1845.18  5495.9 1863.39  5516.0 1878.40
  5525.7 1883.95  5530.8 1883.08  5536.2 1888.44  5566.4 1898.08  5593.0 1902.08
#Mann=7,-1,0
  4589.1    0.07       0  4670.8     0.1       0  5009.4    0.05       0
  5015.3     0.1       0  5021.1   0.035       0  5269.2    0.07       0
  5368.8     0.1       0
Bank Sta=5009.4,5015.3
Exp/Cntr=0.3,0.1

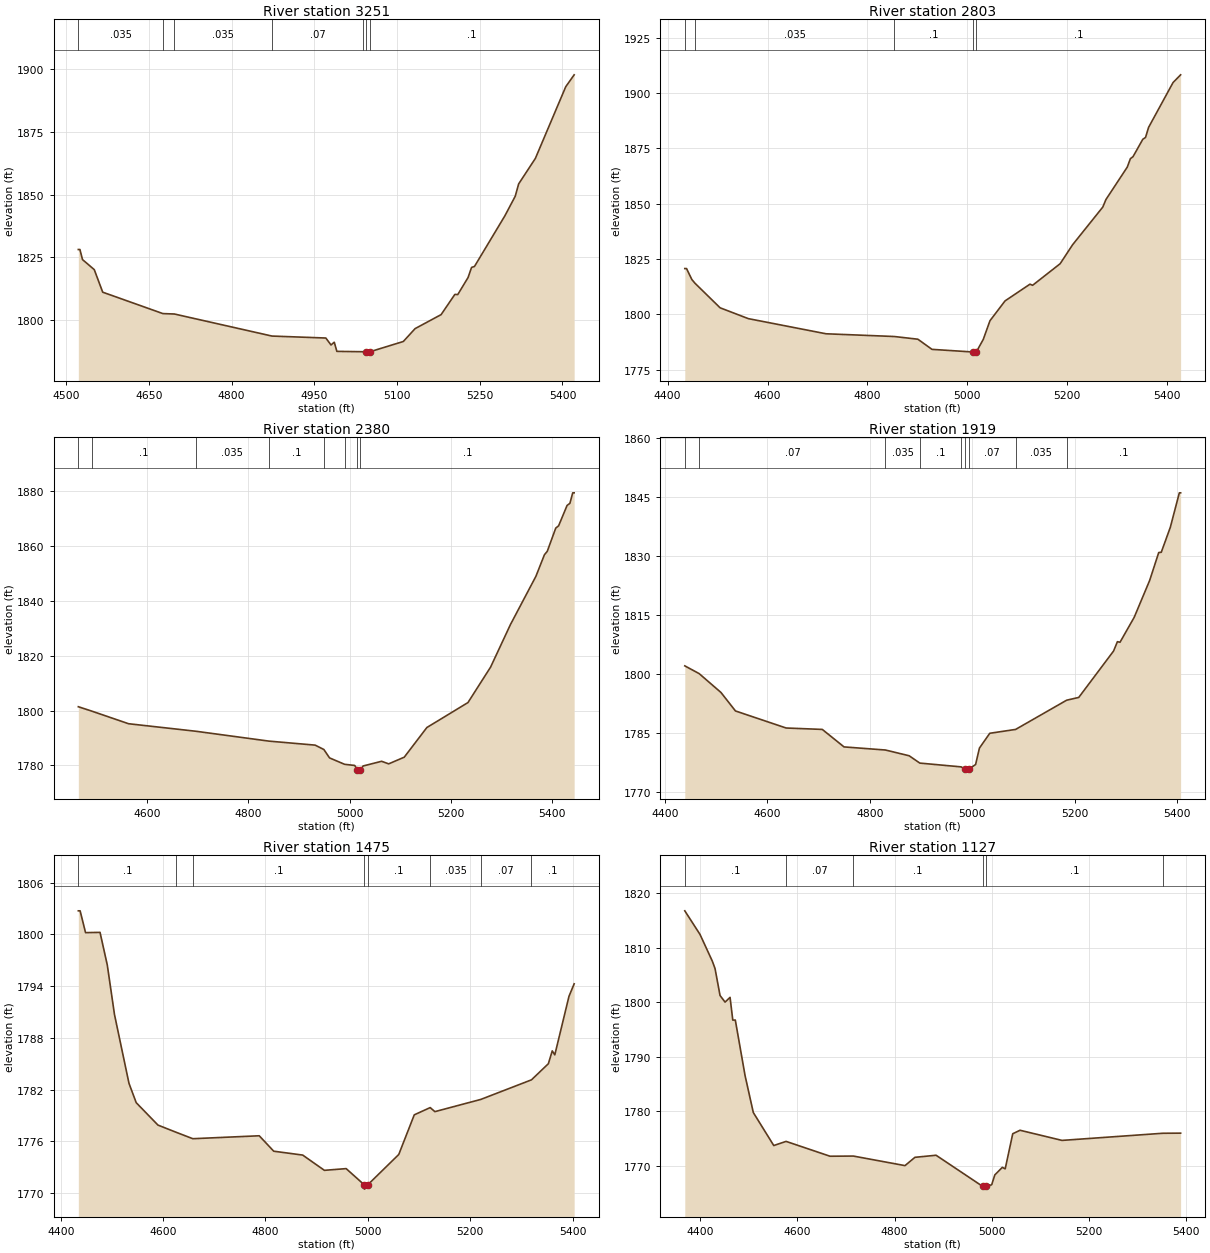
Type RM Length L Ch R = 1,3251,448,448,448
BEGIN DESCRIPTION:
Stream0584 5.0
END DESCRIPTION:
XS GIS Cut Line= 3
      1895674.98     13907274.99      1895275.00     13907025.00
      1894874.98     13906874.99
#Sta/Elev= 30
  4522.3 1828.17  4525.2 1828.17  4529.9 1824.15  4551.2 1820.15  4566.5 1811.16
  4675.6 1802.63  4696.5 1802.46  4873.4 1793.67  4971.0 1792.89  4980.4 1790.12
  4986.3 1791.22  4991.0 1787.57  5038.0 1787.43  5044.4 1787.37  5044.9 1786.87
  5050.3 1787.37  5111.5 1791.51  5132.8 1796.63  5180.0 1802.22  5204.9 1810.27
  5210.2 1810.22  5228.9 1817.02  5235.2 1821.04  5240.5 1821.42  5295.7 1841.64
  5314.4 1849.42  5320.6 1854.32  5350.9 1864.49  5406.0 1893.08  5421.2 1897.80
#Mann=7,-1,0
  4522.3   0.035       0  4675.6     0.1       0  4696.5   0.035       0
  4873.4    0.07       0  5038.0     0.1       0  5044.4    0.05       0
  5050.3     0.1       0
Bank Sta=5044.4,5050.3
Exp/Cntr=0.3,0.1

Type RM Length L Ch R = 1,2803,423,423,423
BEGIN DESCRIPTION:
Stream0584 4.0
END DESCRIPTION:
XS GIS Cut Line= 3
      1895724.99     13907024.99      1895325.00     13906625.00
      1894924.97     13906474.99
#Sta/Elev= 30
  4434.3 1820.72  4437.8 1820.72  4448.4 1815.77  4454.9 1814.04  4505.0 1802.99
  4561.6 1798.09  4717.1 1791.25  4853.6 1790.02  4901.0 1788.80  4929.3 1784.21
  5012.1 1783.01  5012.6 1782.51  5018.0 1783.01  5032.0 1788.71  5045.4 1797.14
  5075.6 1806.10  5125.5 1813.66  5130.8 1813.16  5186.0 1822.92  5210.9 1831.48
  5271.4 1848.52  5277.6 1851.89  5320.4 1866.57  5326.6 1870.35  5331.9 1871.29
  5351.5 1879.14  5356.9 1879.95  5363.1 1884.53  5412.0 1904.75  5427.2 1908.25
#Mann=5,-1,0
  4434.3    0.07       0  4454.9   0.035       0  4853.6     0.1       0
  5012.1    0.05       0  5018.0     0.1       0
Bank Sta=5012.1,5018
Exp/Cntr=0.3,0.1

Type RM Length L Ch R = 1,2380,461,461,461
BEGIN DESCRIPTION:
Stream0584 3.0
END DESCRIPTION:
XS GIS Cut Line= 3
      1895874.99     13906674.99      1895525.00     13906275.00
      1895125.01     13906075.01
#Sta/Elev= 30
  4464.3 1801.41  4490.5 1799.83  4563.5 1795.21  4696.2 1792.47  4840.6 1788.87
  4931.7 1787.41  4948.9 1785.82  4960.2 1782.75  4989.8 1780.42  5009.8 1780.00
  5015.2 1778.43  5015.7 1777.93  5021.2 1778.43  5026.5 1779.81  5062.9 1781.52
  5076.9 1780.58  5107.6 1783.01  5152.3 1793.83  5233.4 1802.93  5278.1 1815.87
  5317.2 1831.35  5367.5 1848.96  5384.3 1856.82  5389.9 1858.07  5406.7 1866.55
  5412.3 1867.37  5429.0 1874.79  5434.6 1875.57  5440.2 1879.40  5443.0 1879.40
#Mann=8,-1,0
  4464.3   0.035       0  4490.5     0.1       0  4696.2   0.035       0
  4840.6     0.1       0  4948.9   0.035       0  4989.8     0.1       0
  5015.2    0.05       0  5021.2     0.1       0
Bank Sta=5015.2,5021.2
Exp/Cntr=0.3,0.1

Type RM Length L Ch R = 1,1919,444,444,444
BEGIN DESCRIPTION:
Stream0584 2.0
END DESCRIPTION:
XS GIS Cut Line= 3
      1896024.99     13906274.99      1895625.00     13905875.00
      1895224.98     13905925.00
#Sta/Elev= 30
  4438.5 1802.03  4466.6 1800.06  4509.2 1795.27  4537.5 1790.58  4636.5 1786.25
  4707.2 1785.89  4749.6 1781.45  4830.6 1780.66  4876.9 1779.20  4897.7 1777.34
  4978.4 1776.38  4986.6 1775.80  4987.1 1775.30  4993.4 1775.80  5006.7 1776.98
  5014.2 1781.15  5034.4 1784.91  5084.9 1785.89  5184.6 1793.31  5208.2 1794.01
  5276.3 1805.80  5283.8 1808.17  5288.9 1808.03  5316.6 1814.36  5346.8 1823.72
  5364.5 1830.80  5369.5 1830.88  5387.1 1837.19  5404.8 1845.97  5407.3 1845.97
#Mann=9,-1,0
  4438.5     0.1       0  4466.6    0.07       0  4830.6   0.035       0
  4897.7     0.1       0  4978.4    0.07       0  4986.6    0.05       0
  4993.4    0.07       0  5084.9   0.035       0  5184.6     0.1       0
Bank Sta=4986.6,4993.4
Exp/Cntr=0.3,0.1

Type RM Length L Ch R = 1,1475,348,348,348
BEGIN DESCRIPTION:
Stream0584 1.0
END DESCRIPTION:
XS GIS Cut Line= 3
      1896274.99     13905924.99      1895875.00     13905525.00
      1895474.99     13905475.00
#Sta/Elev= 30
  4434.3 1802.74  4437.8 1802.74  4448.4 1800.21  4476.7 1800.24  4490.9 1796.45
  4505.0 1790.69  4533.3 1782.72  4547.4 1780.48  4589.9 1777.88  4626.1 1777.03
  4658.0 1776.30  4787.8 1776.64  4816.1 1774.85  4872.7 1774.40  4915.1 1772.63
  4957.6 1772.83  4993.0 1770.95  4993.5 1770.45  4999.8 1770.95  5060.4 1774.47
  5090.7 1779.07  5121.8 1779.91  5131.0 1779.44  5220.8 1780.86  5319.7 1783.13
  5352.7 1785.00  5360.3 1786.49  5365.3 1786.03  5393.0 1792.82  5403.1 1794.27
#Mann=8,-1,0
  4434.3     0.1       0  4626.1    0.07       0  4658.0     0.1       0
  4993.0    0.05       0  4999.8     0.1       0  5121.8   0.035       0
  5220.8    0.07       0  5319.7     0.1       0
Bank Sta=4993,4999.8
Exp/Cntr=0.3,0.1

Type RM Length L Ch R = 1,1127,501,501,501
BEGIN DESCRIPTION:
Stream0584 0.0
END DESCRIPTION:
XS GIS Cut Line= 4
      1896343.00     13905975.53      1896224.11     13905476.44
      1896099.45     13905267.76      1895861.64     13905153.89
#Sta/Elev= 30
  4368.4 1816.74  4399.8 1812.40  4425.0 1807.52  4430.6 1806.16  4440.9 1801.22
  4451.2 1800.01  4461.5 1800.88  4467.1 1796.71  4472.3 1796.72  4492.3 1786.57
  4509.3 1779.77  4551.4 1773.72  4576.7 1774.48  4667.1 1771.76  4715.1 1771.79
  4821.3 1770.04  4841.8 1771.56  4885.2 1771.94  4981.1 1766.23  4981.6 1765.73
  4988.0 1766.23  4999.6 1766.53  5006.0 1768.33  5021.5 1769.72  5027.4 1769.45
  5042.9 1775.88  5057.9 1776.52  5144.3 1774.66  5351.6 1775.97  5388.2 1775.99
#Mann=6,-1,0
  4368.4     0.1       0  4576.7    0.07       0  4715.1     0.1       0
  4981.1    0.05       0  4988.0     0.1       0  5351.6   0.035       0
Bank Sta=4981.1,4988
Exp/Cntr=0.3,0.1

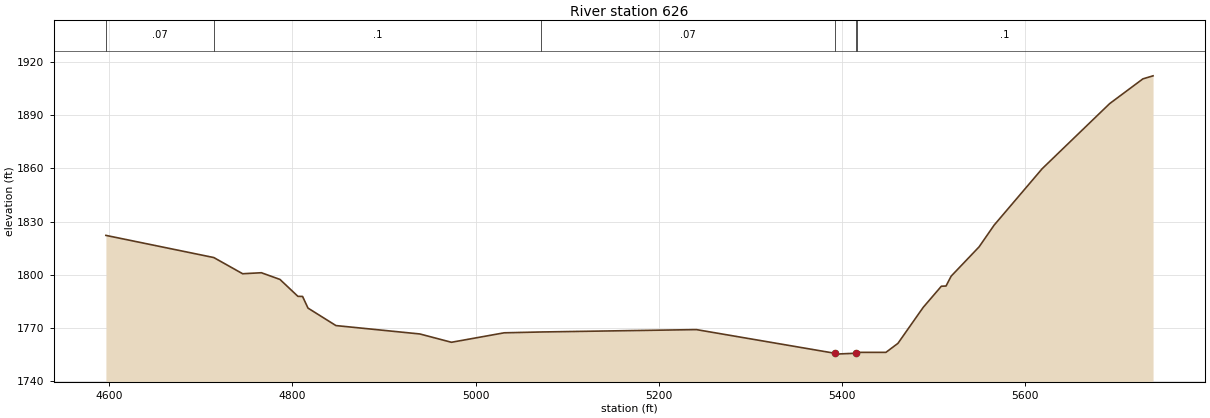
Type RM Length L Ch R = 1,626,0,0,0
BEGIN DESCRIPTION:
Stream0584 0.1
END DESCRIPTION:
XS GIS Cut Line= 2
      1896480.41     13906051.76      1896691.91     13904928.40
#Sta/Elev= 30
  4596.4 1822.25  4714.2 1809.75  4745.7 1800.62  4766.1 1801.19  4786.4 1797.42
  4806.0 1787.88  4811.1 1787.82  4817.0 1781.26  4847.5 1771.40  4939.1 1766.67
  4973.6 1761.98  5031.2 1767.32  5071.9 1767.79  5241.0 1769.13  5391.9 1755.80
  5392.4 1755.30  5415.1 1755.80  5416.2 1756.28  5447.9 1756.30  5461.0 1761.37
  5488.6 1781.67  5508.4 1793.58  5513.5 1793.70  5519.1 1799.26  5549.6 1815.78
  5566.0 1828.01  5618.4 1859.81  5692.1 1896.53  5728.4 1910.49  5739.5 1912.21
#Mann=6,-1,0
  4596.4    0.07       0  4714.2     0.1       0  5071.9    0.07       0
  5391.9    0.05       0  5415.1    0.07       0  5416.2     0.1       0
Bank Sta=5391.9,5415.1
Exp/Cntr=0.3,0.1

Chan Stop Cuts=-1