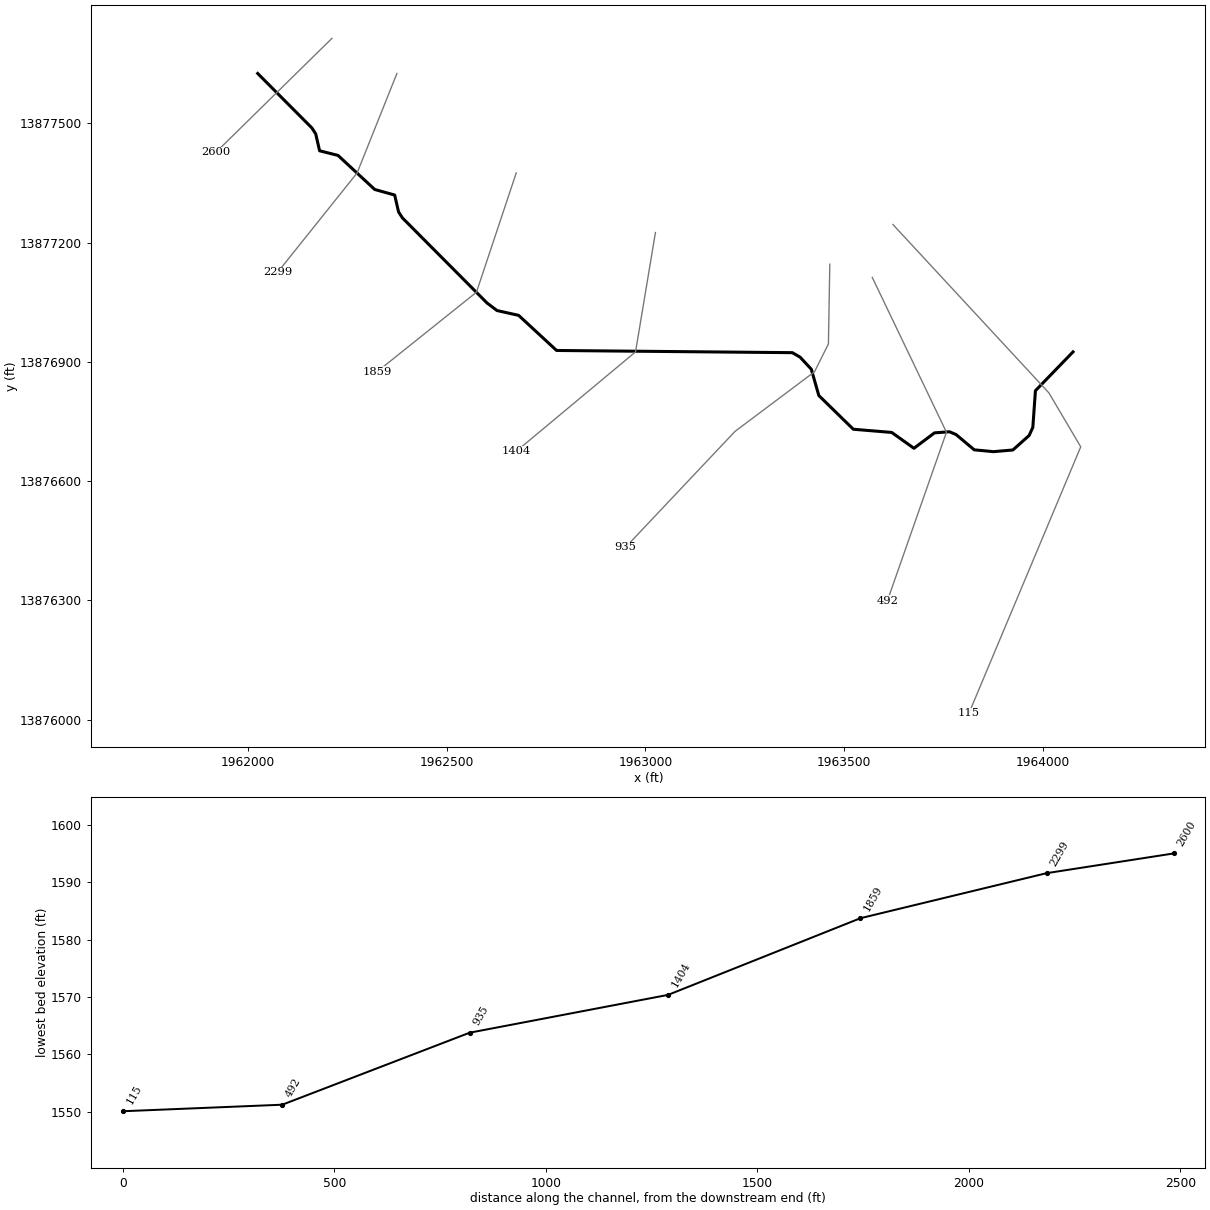
--- Stream0586.prj (project) ---

Proj Title=Stream0586 Base Level Engineering
Current Plan=p01
Default Exp/Contr=0.3,0.1
English Units
Geom File=g01
Flow File=f01
Plan File=p01
BEGIN DESCRIPTION:
Stream0586
END DESCRIPTION:

--- Stream0586.p01 (plan) ---

Plan Title=Multiple Run
Short Identifier=Multiple
Geom File=g01
Flow File=f01
Subcritical Flow
K Sum by GR= 0
Std Step Tol= 0.01
Critical Tol= 0.01
Num of Std Step Trials= 20
Max Error Tol= 0.3
Flow Tol Ratio= 0.001
Split Flow NTrial= 30
Split Flow Tol= 0.02
Split Flow Ratio= 0.02
Log Output Level= 0
Friction Slope Method= 1
Unsteady Friction Slope Method= 2
Unsteady Bridges Friction Slope Method= 1
Parabolic Critical Depth
Global Vel Dist=  1 , 1 , 1
Global Log Level= 0
CheckData=True
Encroach Param= -1, 0, 0, 0
BEGIN DESCRIPTION:
Multiple Run
END DESCRIPTION:

--- Stream0586.f01 (steady flow) ---

Flow Title=Multiple
Number of Profiles=7
Profile Names=10-year,25-year,50-year,1pct_min,100-year,1pct_plu,500-year
River Rch & RM= Stream0586,Reach-1,2600
    1333    2307    3250    2216    4422    8824    8079
Boundary for River Rch & Prof#=Stream0586,Reach-1,1
Up Type=0
Dn Type=3
Dn Slope=0.005
Boundary for River Rch & Prof#=Stream0586,Reach-1,2
Up Type=0
Dn Type=3
Dn Slope=0.005
Boundary for River Rch & Prof#=Stream0586,Reach-1,3
Up Type=0
Dn Type=3
Dn Slope=0.005
Boundary for River Rch & Prof#=Stream0586,Reach-1,4
Up Type=0
Dn Type=3
Dn Slope=0.005
Boundary for River Rch & Prof#=Stream0586,Reach-1,5
Up Type=0
Dn Type=3
Dn Slope=0.005
Boundary for River Rch & Prof#=Stream0586,Reach-1,6
Up Type=0
Dn Type=3
Dn Slope=0.005
Boundary for River Rch & Prof#=Stream0586,Reach-1,7
Up Type=0
Dn Type=3
Dn Slope=0.005

--- Stream0586.g01 (geometry) ---

Geom Title=Existing Conditions

River Reach=Stream0586,Reach-1
Reach XY= 30
      1962025.00     13877625.00      1962161.28     13877487.98
      1962170.88     13877472.99      1962180.62     13877430.62
      1962226.95     13877418.99      1962319.25     13877333.30
      1962369.38     13877319.38      1962379.13     13877277.01
      1962388.73     13877262.02      1962601.53     13877048.01
      1962626.65     13877028.97      1962681.04     13877016.82
      1962776.47     13876928.55      1963369.33     13876923.02
      1963388.67     13876911.77      1963416.98     13876881.38
      1963435.78     13876815.32      1963522.56     13876730.51
      1963619.10     13876722.45      1963675.01     13876682.59
      1963726.64     13876721.39      1963764.29     13876724.18
      1963780.91     13876717.16      1963826.59     13876678.73
      1963875.04     13876674.14      1963923.75     13876678.36
      1963964.64     13876714.83      1963973.91     13876735.31
      1963980.46     13876827.45      1964075.00     13876925.00

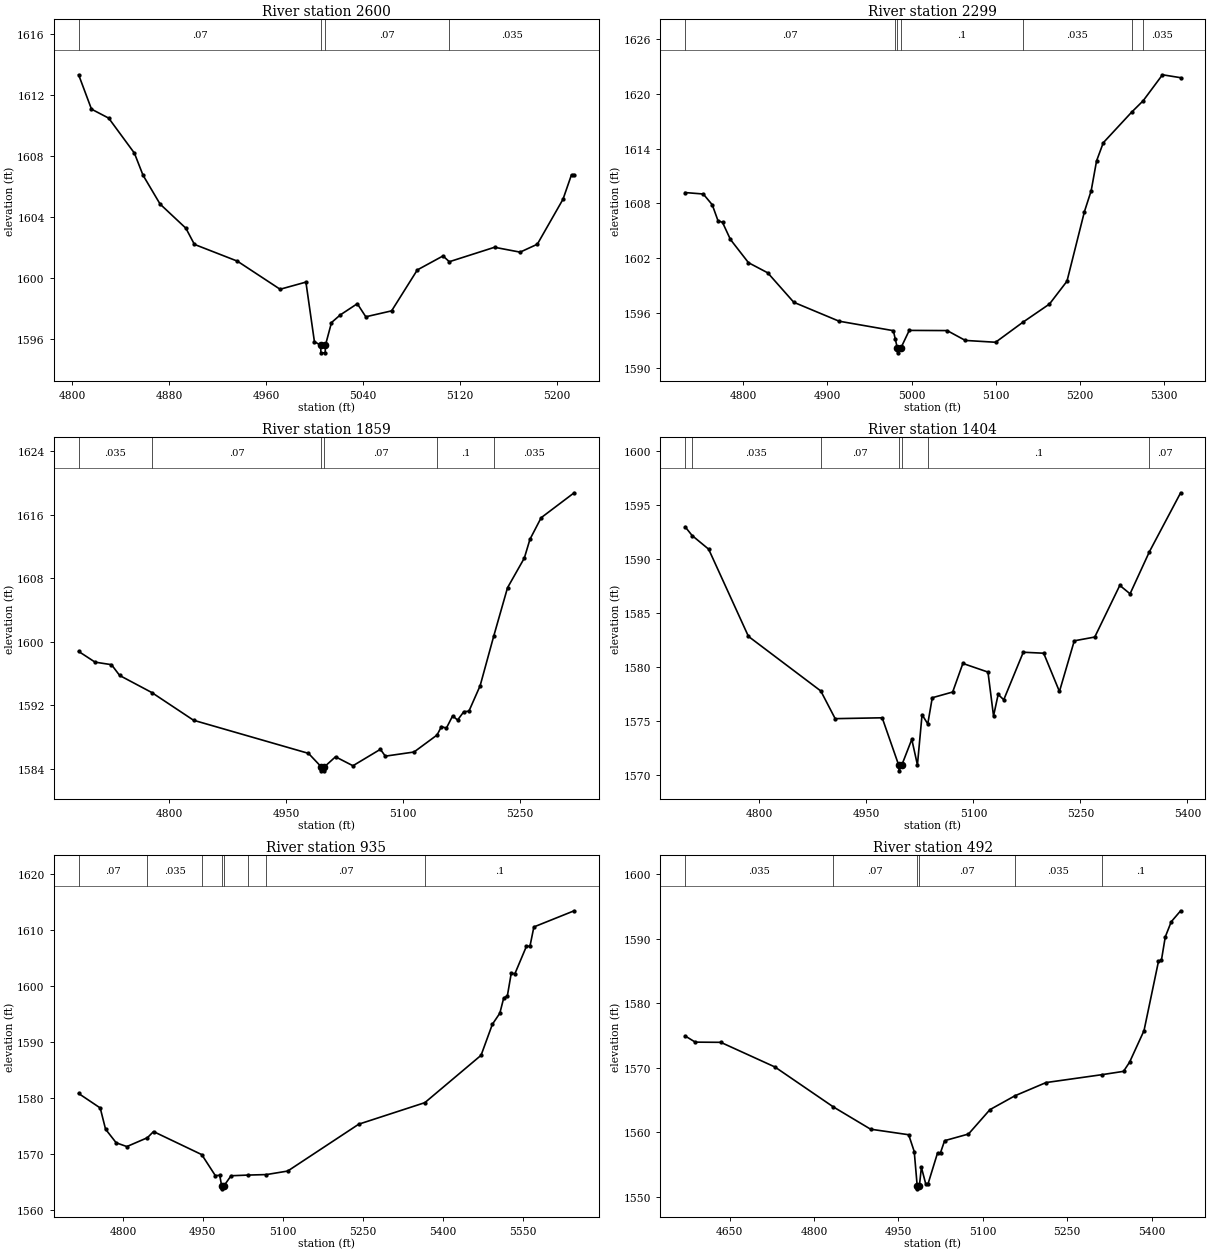
Type RM Length L Ch R = 1,2600,301,301,301
BEGIN DESCRIPTION:
Stream0586 6.0
END DESCRIPTION:
XS GIS Cut Line= 2
      1962211.73     13877713.36      1961920.07     13877426.91
#Sta/Elev= 30
  4805.5 1613.34  4816.1 1611.08  4830.3 1610.49  4851.5 1608.19  4858.6 1606.74
  4872.7 1604.84  4894.0 1603.25  4901.0 1602.19  4936.4 1601.09  4971.7 1599.24
  4993.0 1599.71  5000.0 1595.80  5005.1 1595.56  5005.4 1595.06  5008.9 1595.06
  5009.1 1595.56  5014.1 1597.05  5021.3 1597.55  5035.4 1598.29  5042.4 1597.43
  5063.7 1597.82  5084.9 1600.51  5106.1 1601.43  5111.3 1601.05  5148.6 1602.00
  5169.7 1601.68  5183.9 1602.20  5205.1 1605.16  5212.1 1606.77  5214.3 1606.77
#Mann=4,-1,0
  4805.5    0.07       0  5005.1    0.05       0  5009.1    0.07       0
  5111.3   0.035       0
Bank Sta=5005.1,5009.1
Exp/Cntr=0.3,0.1

Type RM Length L Ch R = 1,2299,440,440,440
BEGIN DESCRIPTION:
Stream0586 5.0
END DESCRIPTION:
XS GIS Cut Line= 3
      1962375.01     13877625.03      1962275.00     13877375.00
      1962075.03     13877125.04
#Sta/Elev= 30
  4730.7 1609.18  4752.3 1609.02  4763.0 1607.84  4769.8 1606.10  4775.2 1605.91
  4784.6 1604.04  4806.1 1601.49  4829.0 1600.38  4860.0 1597.15  4913.8 1595.08
  4978.4 1594.04  4980.6 1593.16  4983.2 1592.11  4983.4 1591.61  4987.2 1592.11
  4997.3 1594.07  5042.4 1594.05  5064.0 1592.97  5100.0 1592.77  5132.4 1594.96
  5164.1 1596.96  5184.9 1599.46  5205.7 1607.10  5213.7 1609.38  5220.1 1612.65
  5228.1 1614.64  5261.7 1617.98  5275.5 1619.24  5298.5 1622.09  5320.1 1621.77
#Mann=7,-1,0
  4730.7    0.07       0  4980.6     0.1       0  4983.2    0.05       0
  4987.2     0.1       0  5132.4   0.035       0  5261.7    0.07       0
  5275.5   0.035       0
Bank Sta=4983.2,4987.2
Exp/Cntr=0.3,0.1

Type RM Length L Ch R = 1,1859,455,455,455
BEGIN DESCRIPTION:
Stream0586 4.0
END DESCRIPTION:
XS GIS Cut Line= 3
      1962675.01     13877375.03      1962575.00     13877075.00
      1962325.01     13876875.01
#Sta/Elev= 30
  4683.5 1598.79  4704.6 1597.44  4725.7 1597.12  4736.2 1595.76  4777.5 1593.61
  4831.1 1590.12  4978.7 1585.95  4995.1 1584.25  4995.4 1583.75  4998.9 1583.75
  4999.1 1584.25  5013.4 1585.52  5035.8 1584.39  5071.0 1586.46  5077.4 1585.60
  5114.2 1586.12  5143.8 1588.26  5149.4 1589.32  5155.8 1589.13  5163.8 1590.67
  5170.2 1590.15  5178.2 1591.20  5184.7 1591.26  5199.1 1594.46  5216.8 1600.79
  5234.3 1606.81  5255.9 1610.55  5263.1 1612.91  5277.5 1615.63  5319.9 1618.77
#Mann=6,-1,0
  4683.5   0.035       0  4777.5    0.07       0  4995.1    0.05       0
  4999.1    0.07       0  5143.8     0.1       0  5216.8   0.035       0
Bank Sta=4995.1,4999.1
Exp/Cntr=0.3,0.1

Type RM Length L Ch R = 1,1404,469,469,469
BEGIN DESCRIPTION:
Stream0586 3.0
END DESCRIPTION:
XS GIS Cut Line= 3
      1963025.01     13877225.04      1962975.00     13876925.00
      1962675.00     13876675.00
#Sta/Elev= 30
  4695.8 1593.00  4705.7 1592.18  4728.8 1590.92  4784.6 1582.83  4886.0 1577.77
  4906.2 1575.20  4972.1 1575.28  4995.4 1570.86  4995.7 1570.36  4999.4 1570.86
  5013.6 1573.28  5021.5 1570.91  5028.0 1575.57  5036.0 1574.71  5042.3 1577.14
  5070.9 1577.67  5085.2 1580.32  5120.4 1579.52  5128.2 1575.45  5134.7 1577.45
  5142.5 1576.95  5169.9 1581.36  5198.5 1581.27  5220.6 1577.72  5241.4 1582.42
  5270.1 1582.77  5305.2 1587.56  5319.6 1586.78  5346.7 1590.68  5390.5 1596.15
#Mann=7,-1,0
  4695.8    0.07       0  4705.7   0.035       0  4886.0    0.07       0
  4995.4    0.05       0  4999.4    0.07       0  5036.0     0.1       0
  5346.7    0.07       0
Bank Sta=4995.4,4999.4
Exp/Cntr=0.3,0.1

Type RM Length L Ch R = 1,935,443,443,443
BEGIN DESCRIPTION:
Stream0586 2.0
END DESCRIPTION:
XS GIS Cut Line= 5
      1963463.46     13877145.46      1963459.94     13876944.88
      1963425.00     13876875.00      1963225.00     13876725.00
      1962949.66     13876433.40
#Sta/Elev= 30
  4716.9 1580.81  4757.4 1578.22  4767.4 1574.43  4787.4 1571.99  4807.4 1571.32
  4845.9 1572.90  4857.4 1574.00  4947.9 1569.88  4973.3 1566.14  4981.7 1566.17
  4985.3 1564.26  4985.5 1563.76  4989.3 1564.26  5002.9 1566.10  5034.6 1566.22
  5069.2 1566.31  5109.2 1566.94  5242.5 1575.32  5366.5 1579.17  5472.0 1587.64
  5493.2 1593.18  5507.2 1595.16  5514.5 1597.89  5521.3 1598.24  5528.6 1602.30
  5535.5 1602.23  5557.0 1607.10  5563.8 1607.17  5571.1 1610.59  5646.7 1613.48
#Mann=8,-1,0
  4716.9    0.07       0  4845.9   0.035       0  4947.9    0.07       0
  4985.3    0.05       0  4989.3    0.07       0  5034.6   0.035       0
  5069.2    0.07       0  5366.5     0.1       0
Bank Sta=4985.3,4989.3
Exp/Cntr=0.3,0.1

Type RM Length L Ch R = 1,492,377,377,377
BEGIN DESCRIPTION:
Stream0586 1.0
END DESCRIPTION:
XS GIS Cut Line= 3
      1963570.23     13877112.20      1963756.73     13876723.00
      1963608.22     13876299.24
#Sta/Elev= 30
  4570.8 1574.90  4588.9 1573.94  4634.2 1573.91  4730.4 1570.09  4834.3 1563.89
  4900.4 1560.44  4968.1 1559.58  4978.0 1556.97  4983.2 1551.69  4983.4 1551.19
  4987.2 1551.69  4990.7 1554.52  4998.5 1551.93  5002.4 1551.93  5019.4 1556.75
  5024.7 1556.80  5032.0 1558.66  5074.4 1559.69  5112.5 1563.47  5156.9 1565.62
  5212.2 1567.67  5311.3 1568.89  5349.9 1569.41  5360.6 1570.82  5386.3 1575.72
  5412.0 1586.46  5417.3 1586.67  5424.1 1590.26  5434.7 1592.61  5451.4 1594.31
#Mann=6,-1,0
  4570.8   0.035       0  4834.3    0.07       0  4983.2    0.05       0
  4987.2    0.07       0  5156.9   0.035       0  5311.3     0.1       0
Bank Sta=4983.2,4987.2
Exp/Cntr=0.3,0.1

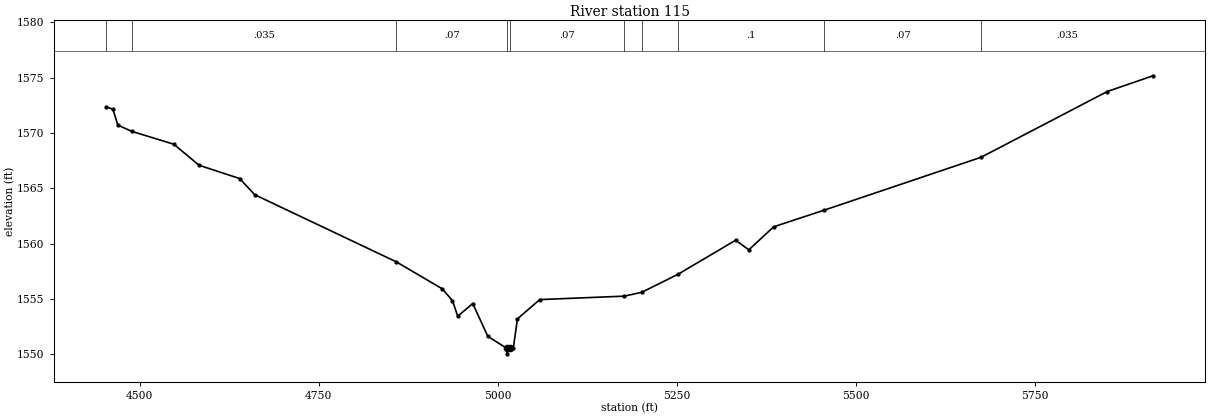
Type RM Length L Ch R = 1,115,0,0,0
BEGIN DESCRIPTION:
Stream0586 0.0
END DESCRIPTION:
XS GIS Cut Line= 4
      1963622.14     13877245.29      1964014.49     13876821.68
      1964094.36     13876686.27      1963813.09     13876016.10
#Sta/Elev= 30
  4453.3 1572.36  4462.7 1572.14  4469.5 1570.71  4489.0 1570.14  4547.7 1568.98
  4582.9 1567.08  4639.6 1565.88  4660.6 1564.42  4858.2 1558.36  4922.5 1555.92
  4936.7 1554.85  4944.0 1553.45  4965.0 1554.59  4986.0 1551.63  5012.4 1550.55
  5012.6 1550.05  5016.4 1550.55  5021.7 1550.61  5027.4 1553.21  5058.5 1554.95
  5176.6 1555.26  5201.0 1555.61  5251.4 1557.23  5332.0 1560.31  5350.4 1559.44
  5385.0 1561.52  5455.8 1563.03  5674.6 1567.80  5850.8 1573.74  5914.7 1575.16
#Mann=10,-1,0
  4453.3    0.07       0  4489.0   0.035       0  4858.2    0.07       0
  5012.4    0.05       0  5016.4    0.07       0  5176.6     0.1       0
  5201.0    0.07       0  5251.4     0.1       0  5455.8    0.07       0
  5674.6   0.035       0
Bank Sta=5012.4,5016.4
Exp/Cntr=0.3,0.1

Chan Stop Cuts=-1