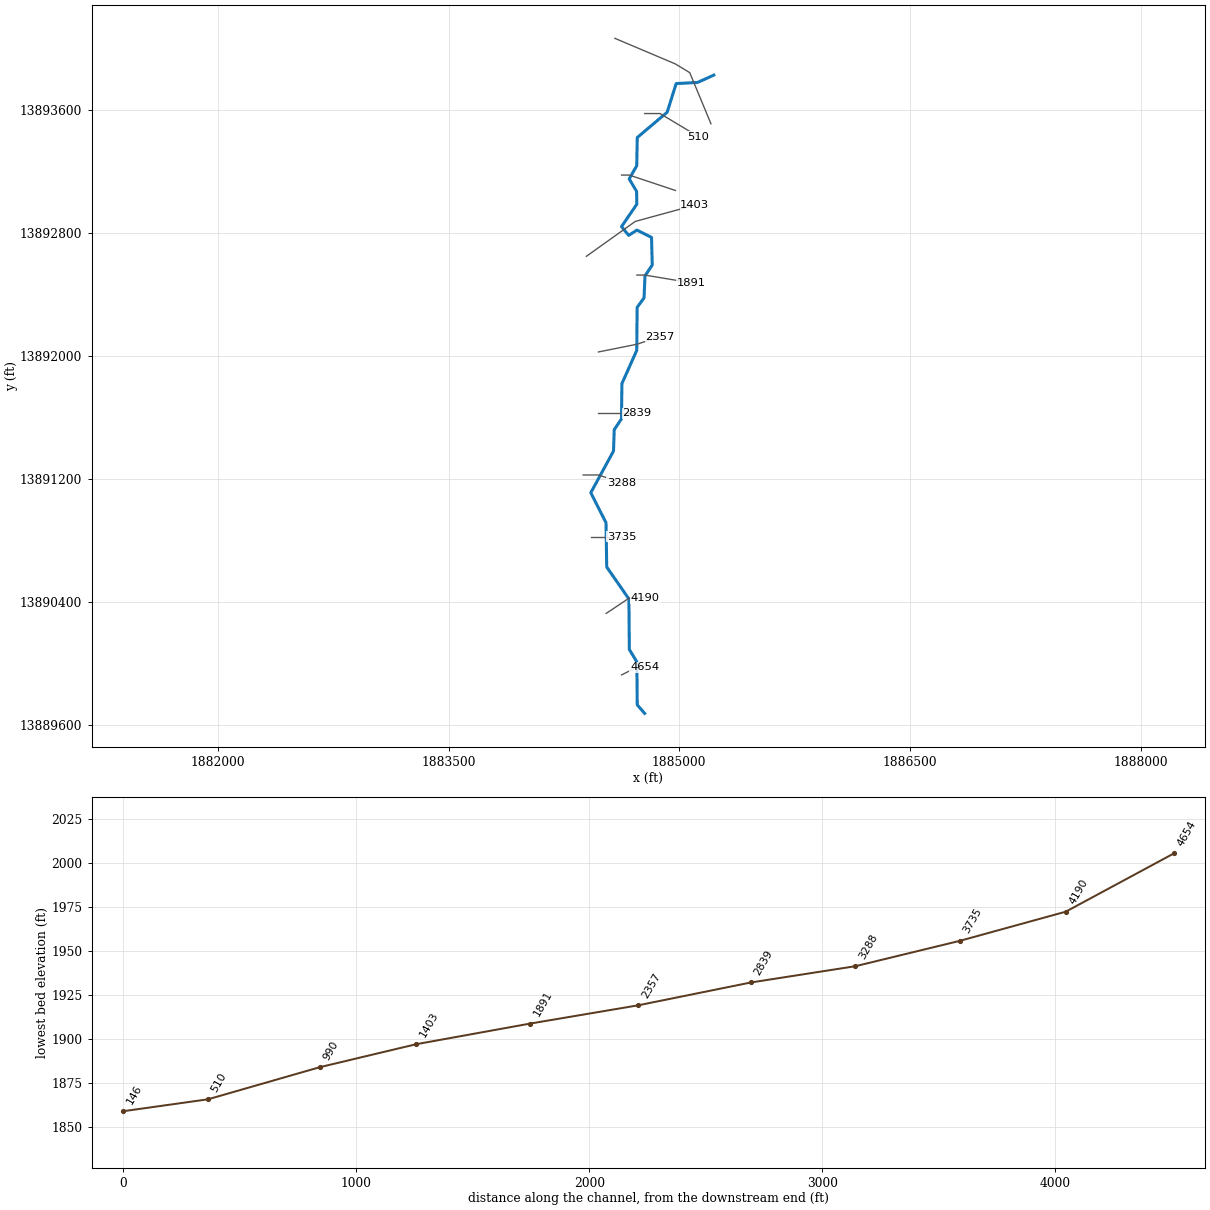
--- Stream0587.prj (project) ---

Proj Title=Stream0587 Base Level Engineering
Current Plan=p01
Default Exp/Contr=0.3,0.1
English Units
Geom File=g01
Flow File=f01
Plan File=p01
BEGIN DESCRIPTION:
Stream0587
END DESCRIPTION:

--- Stream0587.p01 (plan) ---

Plan Title=Multiple Run
Short Identifier=Multiple
Geom File=g01
Flow File=f01
Subcritical Flow
K Sum by GR= 0
Std Step Tol= 0.01
Critical Tol= 0.01
Num of Std Step Trials= 20
Max Error Tol= 0.3
Flow Tol Ratio= 0.001
Split Flow NTrial= 30
Split Flow Tol= 0.02
Split Flow Ratio= 0.02
Log Output Level= 0
Friction Slope Method= 1
Unsteady Friction Slope Method= 2
Unsteady Bridges Friction Slope Method= 1
Parabolic Critical Depth
Global Vel Dist=  1 , 1 , 1
Global Log Level= 0
CheckData=True
Encroach Param= -1, 0, 0, 0
BEGIN DESCRIPTION:
Multiple Run
END DESCRIPTION:

--- Stream0587.f01 (steady flow) ---

Flow Title=Multiple
Number of Profiles=7
Profile Names=10-year,25-year,50-year,1pct_min,100-year,1pct_plu,500-year
River Rch & RM= Stream0587,Reach-1,4654
     320     502     662     425     849    1693    1369
River Rch & RM= Stream0587,Reach-1,3735
     837    1403    1936    1295    2584    5155    4535
Boundary for River Rch & Prof#=Stream0587,Reach-1,1
Up Type=0
Dn Type=3
Dn Slope=0.005
Boundary for River Rch & Prof#=Stream0587,Reach-1,2
Up Type=0
Dn Type=3
Dn Slope=0.005
Boundary for River Rch & Prof#=Stream0587,Reach-1,3
Up Type=0
Dn Type=3
Dn Slope=0.005
Boundary for River Rch & Prof#=Stream0587,Reach-1,4
Up Type=0
Dn Type=3
Dn Slope=0.005
Boundary for River Rch & Prof#=Stream0587,Reach-1,5
Up Type=0
Dn Type=3
Dn Slope=0.005
Boundary for River Rch & Prof#=Stream0587,Reach-1,6
Up Type=0
Dn Type=3
Dn Slope=0.005
Boundary for River Rch & Prof#=Stream0587,Reach-1,7
Up Type=0
Dn Type=3
Dn Slope=0.005

--- Stream0587.g01 (geometry) ---

Geom Title=Existing Conditions

River Reach=Stream0587,Reach-1
Reach XY= 30
      1884775.00     13889675.00      1884726.89     13889730.78
      1884724.48     13890009.78      1884675.52     13890090.22
      1884672.76     13890419.07      1884528.55     13890626.47
      1884523.80     13890914.50      1884425.07     13891109.61
      1884572.75     13891380.93      1884577.27     13891519.06
      1884624.48     13891590.22      1884627.26     13891819.06
      1884723.78     13892035.50      1884726.22     13892314.50
      1884771.21     13892376.57      1884777.27     13892519.06
      1884824.48     13892590.22      1884819.82     13892769.62
      1884724.93     13892817.23      1884671.34     13892782.89
      1884624.89     13892840.09      1884724.06     13892985.48
      1884722.81     13893069.03      1884674.60     13893150.00
      1884723.76     13893235.50      1884727.06     13893419.15
      1884921.49     13893583.48      1884980.08     13893769.96
      1885119.10     13893777.14      1885225.00     13893825.00

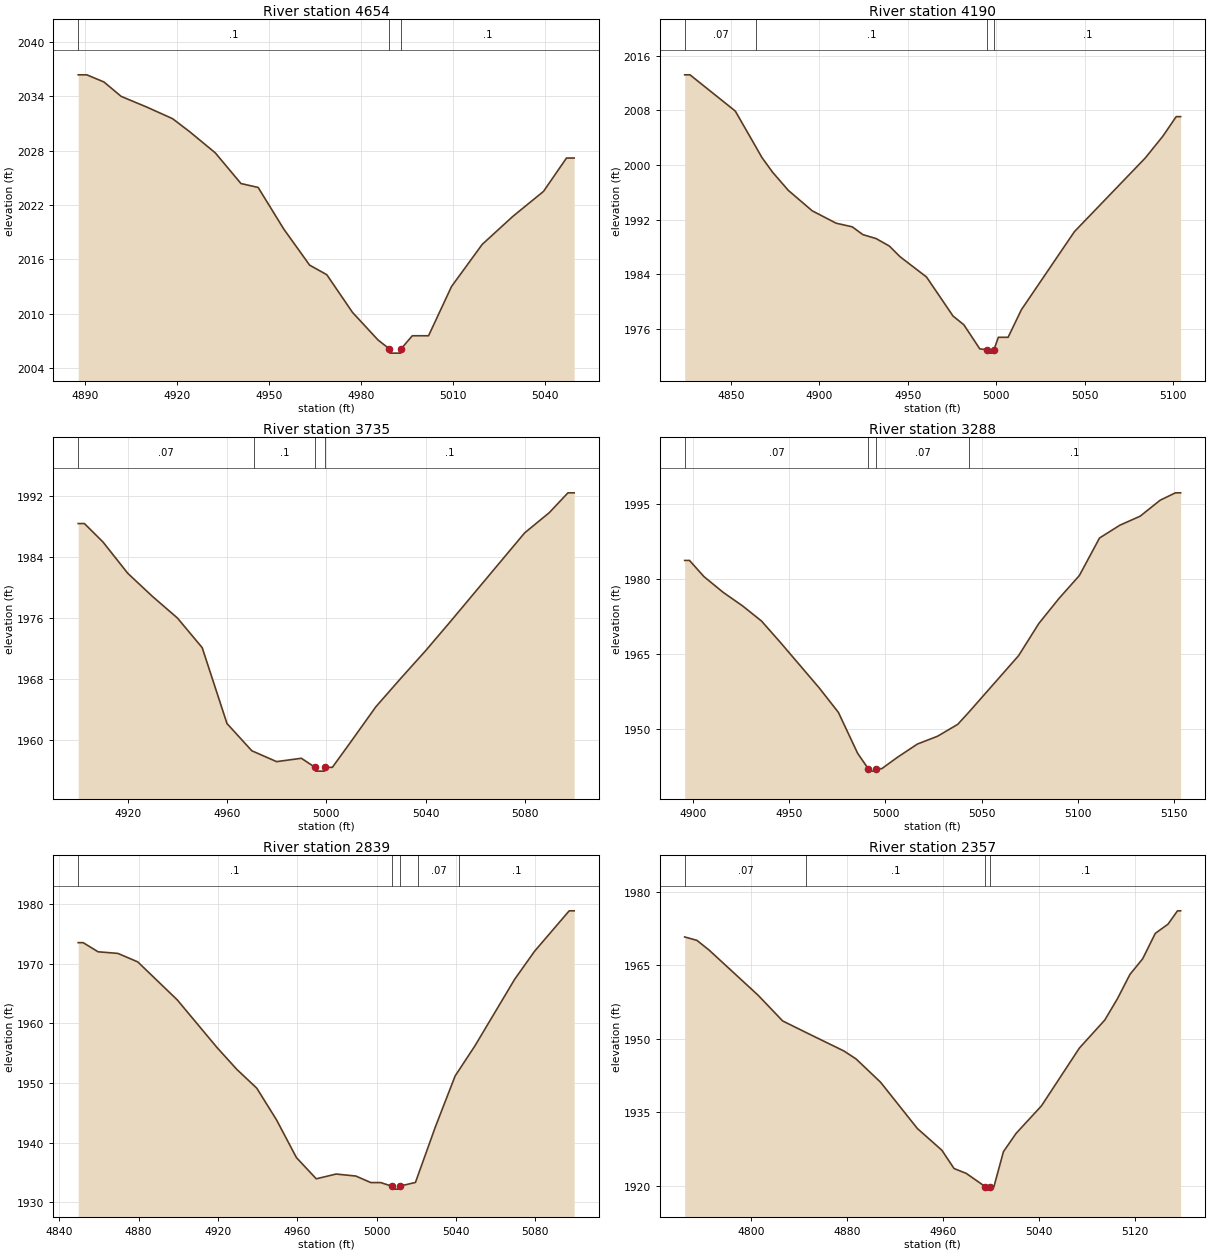
Type RM Length L Ch R = 1,4654,464,464,464
BEGIN DESCRIPTION:
Stream0587 9.0
END DESCRIPTION:
XS GIS Cut Line= 3
      1884624.99     13889924.99      1884725.00     13889975.00
      1884774.98     13889975.00
#Sta/Elev= 28
  4887.8 2036.39  4890.6 2036.39  4896.2 2035.60  4901.8 2034.01  4910.2 2032.82
  4918.6 2031.54  4924.1 2030.12  4932.5 2027.77  4940.9 2024.37  4946.5 2023.94
  4954.9 2019.32  4963.3 2015.35  4968.9 2014.29  4977.3 2010.12  4985.6 2007.08
  4989.2 2006.12  4989.5 2005.62  4993.0 2005.62  4993.2 2006.12  4996.8 2007.54
  4999.6 2007.54  5002.1 2007.54  5009.6 2012.99  5019.6 2017.64  5029.6 2020.74
  5039.6 2023.50  5047.1 2027.19  5049.6 2027.19
#Mann=3,-1,0
  4887.8     0.1       0  4989.2    0.05       0  4993.2     0.1       0
Bank Sta=4989.2,4993.2
Exp/Cntr=0.3,0.1

Type RM Length L Ch R = 1,4190,455,455,455
BEGIN DESCRIPTION:
Stream0587 8.0
END DESCRIPTION:
XS GIS Cut Line= 3
      1884524.99     13890325.00      1884675.00     13890425.00
      1884775.01     13890425.00
#Sta/Elev= 30
  4823.9 2013.21  4826.9 2013.21  4852.5 2007.91  4864.3 2002.59  4867.5 2001.13
  4873.5 1998.98  4882.5 1996.29  4896.0 1993.30  4909.5 1991.49  4918.6 1990.96
  4924.6 1989.82  4932.1 1989.24  4939.6 1988.14  4945.6 1986.59  4960.6 1983.61
  4975.6 1977.89  4981.7 1976.62  4990.7 1973.09  4994.7 1972.97  4994.9 1972.47
  4998.4 1972.47  4998.7 1972.97  5001.2 1974.79  5006.7 1974.79  5014.2 1978.82
  5044.2 1990.26  5084.2 2001.03  5094.2 2004.24  5101.7 2007.09  5104.2 2007.09
#Mann=4,-1,0
  4823.9    0.07       0  4864.3     0.1       0  4994.7    0.05       0
  4998.7     0.1       0
Bank Sta=4994.7,4998.7
Exp/Cntr=0.3,0.1

Type RM Length L Ch R = 1,3735,447,447,447
BEGIN DESCRIPTION:
Stream0587 7.0
END DESCRIPTION:
XS GIS Cut Line= 3
      1884424.99     13890825.00      1884525.00     13890825.00
      1884624.99     13890825.00
#Sta/Elev= 27
  4899.9 1988.43  4902.4 1988.43  4909.9 1986.00  4919.9 1981.88  4929.9 1978.83
  4939.9 1976.01  4949.9 1972.11  4959.9 1962.13  4969.9 1958.55  4970.6 1958.45
  4979.9 1957.12  4989.9 1957.56  4995.4 1956.37  4995.7 1955.87  4999.2 1955.87
  4999.4 1956.37  4999.9 1956.37  5002.4 1956.37  5009.9 1959.75  5019.9 1964.32
  5029.9 1968.04  5039.9 1971.67  5049.9 1975.50  5079.9 1987.19  5089.9 1989.87
  5097.4 1992.47  5099.9 1992.47
#Mann=4,-1,0
  4899.9    0.07       0  4970.6     0.1       0  4995.4    0.05       0
  4999.4     0.1       0
Bank Sta=4995.4,4999.4
Exp/Cntr=0.3,0.1

Type RM Length L Ch R = 1,3288,449,449,449
BEGIN DESCRIPTION:
Stream0587 6.0
END DESCRIPTION:
XS GIS Cut Line= 3
      1884375.03     13891225.00      1884475.00     13891225.00
      1884625.02     13891174.99
#Sta/Elev= 30
  4895.5 1983.69  4898.0 1983.69  4905.5 1980.46  4915.5 1977.30  4925.5 1974.62
  4935.5 1971.54  4945.5 1967.18  4965.5 1958.16  4975.5 1953.25  4985.5 1945.06
  4991.0 1941.98  4991.2 1941.48  4994.7 1941.48  4995.0 1941.98  4998.1 1941.98
  5006.0 1944.19  5016.6 1946.90  5027.1 1948.47  5037.6 1950.85  5043.5 1953.33
  5069.3 1964.62  5079.8 1971.05  5090.3 1976.07  5100.9 1980.66  5111.4 1988.18
  5122.0 1990.75  5132.5 1992.54  5143.0 1995.76  5150.9 1997.23  5153.6 1997.23
#Mann=4,-1,0
  4895.5    0.07       0  4991.0    0.05       0  4995.0    0.07       0
  5043.5     0.1       0
Bank Sta=4991,4995
Exp/Cntr=0.3,0.1

Type RM Length L Ch R = 1,2839,482,482,482
BEGIN DESCRIPTION:
Stream0587 5.0
END DESCRIPTION:
XS GIS Cut Line= 3
      1884474.98     13891625.00      1884625.00     13891625.00
      1884724.98     13891625.00
#Sta/Elev= 30
  4849.6 1973.55  4852.1 1973.55  4859.6 1972.02  4869.6 1971.75  4879.6 1970.33
  4899.6 1963.93  4919.6 1955.95  4929.6 1952.28  4939.6 1949.15  4949.6 1943.81
  4959.6 1937.50  4969.6 1933.94  4979.6 1934.74  4989.6 1934.40  4997.1 1933.31
  5002.1 1933.31  5007.6 1932.71  5007.9 1932.21  5011.4 1932.21  5011.6 1932.71
  5019.6 1933.33  5020.9 1934.54  5029.6 1942.61  5039.6 1951.19  5041.5 1952.15
  5049.6 1956.25  5069.6 1967.40  5079.6 1972.09  5097.1 1978.89  5099.6 1978.89
#Mann=5,-1,0
  4849.6     0.1       0  5007.6    0.05       0  5011.6     0.1       0
  5020.9    0.07       0  5041.5     0.1       0
Bank Sta=5007.6,5011.6
Exp/Cntr=0.3,0.1

Type RM Length L Ch R = 1,2357,466,466,466
BEGIN DESCRIPTION:
Stream0587 4.0
END DESCRIPTION:
XS GIS Cut Line= 3
      1884474.96     13892024.99      1884725.00     13892075.00
      1884874.99     13892125.00
#Sta/Elev= 30
  4744.6 1970.82  4754.8 1970.12  4765.0 1968.12  4805.8 1958.90  4826.2 1953.65
  4845.8 1951.27  4877.2 1947.51  4887.4 1945.87  4907.8 1941.11  4938.4 1931.66
  4958.8 1927.22  4969.0 1923.47  4979.2 1922.47  4995.0 1919.76  4995.3 1919.26
  4998.8 1919.26  4999.0 1919.76  5002.2 1919.76  5010.1 1926.91  5020.7 1930.67
  5041.8 1936.29  5073.4 1948.11  5094.5 1953.82  5105.0 1958.16  5115.5 1963.16
  5126.1 1966.36  5136.6 1971.55  5147.2 1973.43  5155.1 1976.16  5157.7 1976.16
#Mann=4,-1,0
  4744.6    0.07       0  4845.8     0.1       0  4995.0    0.05       0
  4999.0     0.1       0
Bank Sta=4995,4999
Exp/Cntr=0.3,0.1

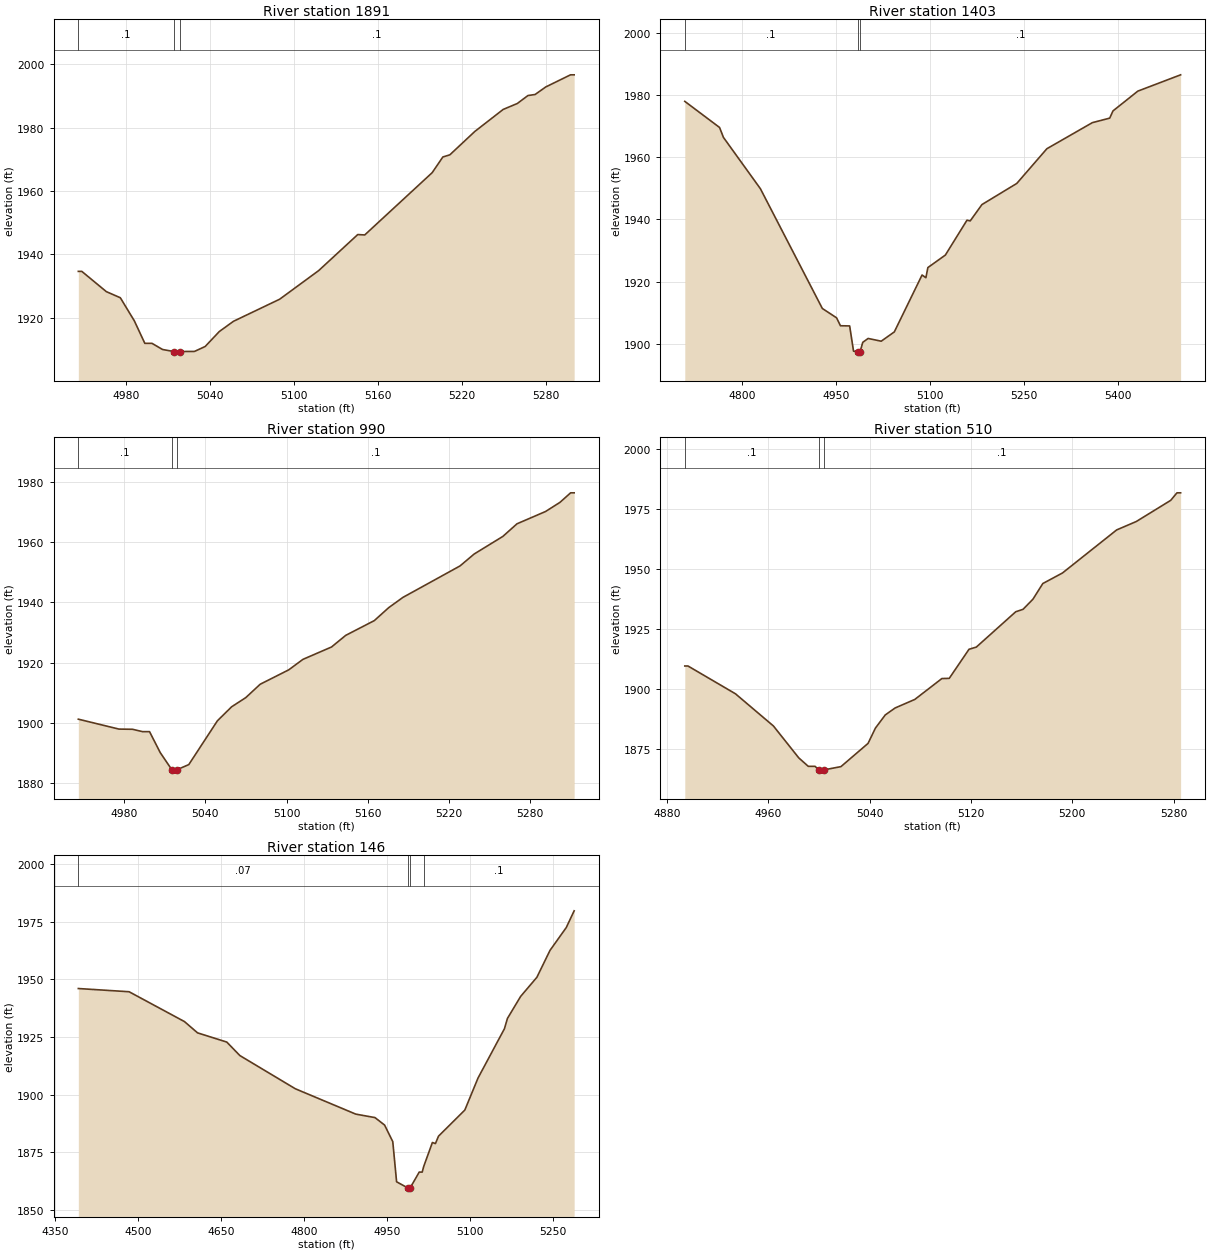
Type RM Length L Ch R = 1,1891,488,488,488
BEGIN DESCRIPTION:
Stream0587 3.0
END DESCRIPTION:
XS GIS Cut Line= 3
      1884724.98     13892525.00      1884775.00     13892525.00
      1885075.04     13892474.99
#Sta/Elev= 30
  4945.7 1934.61  4948.2 1934.61  4965.7 1928.22  4975.7 1926.29  4985.7 1919.01
  4993.2 1911.90  4998.3 1911.90  5005.9 1909.95  5014.0 1909.31  5014.2 1908.81
  5018.0 1909.31  5028.7 1909.35  5036.3 1910.90  5046.4 1915.62  5056.5 1918.85
  5089.5 1925.82  5117.4 1934.86  5145.3 1946.23  5150.3 1946.11  5198.5 1965.78
  5206.1 1970.72  5211.1 1971.40  5228.9 1978.76  5249.2 1985.73  5259.3 1987.60
  5266.9 1990.11  5272.0 1990.44  5279.6 1992.82  5297.3 1996.65  5299.9 1996.65
#Mann=3,-1,0
  4945.7     0.1       0  5014.0    0.05       0  5018.0     0.1       0
Bank Sta=5014,5018
Exp/Cntr=0.3,0.1

Type RM Length L Ch R = 1,1403,413,413,413
BEGIN DESCRIPTION:
Mapping XS 9ad84224
END DESCRIPTION:
XS GIS Cut Line= 3
      1884396.26     13892646.68      1884714.14     13892873.66
      1885100.96     13892979.36
#Sta/Elev= 30
  4708.0 1977.91  4763.5 1969.53  4769.7 1966.34  4828.7 1949.87  4927.6 1911.42
  4950.3 1908.43  4956.5 1905.88  4971.2 1905.82  4977.4 1897.72  4984.0 1897.59
  4984.2 1897.09  4988.0 1897.59  4992.1 1900.55  5000.7 1901.80  5021.6 1900.92
  5042.5 1903.90  5086.8 1922.17  5092.9 1921.30  5096.1 1924.56  5124.0 1928.57
  5158.5 1939.76  5163.7 1939.54  5182.4 1944.78  5238.0 1951.56  5286.1 1962.71
  5358.7 1971.08  5386.4 1972.53  5391.6 1974.84  5431.3 1981.20  5499.6 1986.43
#Mann=3,-1,0
  4708.0     0.1       0  4984.0    0.05       0  4988.0     0.1       0
Bank Sta=4984,4988
Exp/Cntr=0.3,0.1

Type RM Length L Ch R = 1,990,480,480,480
BEGIN DESCRIPTION:
Stream0587 2.0
END DESCRIPTION:
XS GIS Cut Line= 3
      1884625.04     13893175.00      1884675.00     13893175.00
      1884975.01     13893075.00
#Sta/Elev= 30
  4946.2 1901.27  4976.2 1897.98  4986.2 1897.92  4993.7 1897.13  4998.8 1897.13
  5006.7 1890.18  5015.2 1884.54  5015.5 1884.04  5019.0 1884.04  5019.2 1884.54
  5027.8 1886.21  5048.9 1900.72  5059.4 1905.37  5069.9 1908.43  5080.5 1912.85
  5101.6 1917.63  5112.1 1921.11  5133.2 1925.21  5143.7 1929.07  5164.8 1933.96
  5175.4 1938.24  5185.9 1941.65  5228.1 1952.09  5238.6 1956.06  5259.7 1961.87
  5270.2 1966.07  5291.3 1970.15  5301.9 1973.17  5309.8 1976.34  5312.4 1976.34
#Mann=3,-1,0
  4946.2     0.1       0  5015.2    0.05       0  5019.2     0.1       0
Bank Sta=5015.2,5019.2
Exp/Cntr=0.3,0.1

Type RM Length L Ch R = 1,510,364,364,364
BEGIN DESCRIPTION:
Stream0587 1.0
END DESCRIPTION:
XS GIS Cut Line= 3
      1884775.03     13893575.00      1884875.00     13893575.00
      1885124.99     13893425.01
#Sta/Elev= 30
  4894.0 1909.64  4896.5 1909.64  4934.0 1898.04  4964.0 1884.60  4984.0 1871.29
  4991.5 1867.77  4996.9 1867.77  4999.7 1866.27  5000.0 1865.77  5003.7 1866.27
  5017.3 1867.65  5038.7 1877.34  5044.5 1883.71  5052.3 1889.22  5060.1 1892.13
  5075.6 1895.68  5097.0 1904.40  5102.8 1904.47  5118.4 1916.60  5124.2 1917.53
  5155.3 1932.26  5161.1 1933.29  5168.9 1937.51  5176.7 1944.05  5192.2 1948.44
  5235.0 1966.41  5250.5 1969.92  5277.7 1978.76  5282.6 1981.89  5285.5 1981.89
#Mann=3,-1,0
  4894.0     0.1       0  4999.7    0.05       0  5003.7     0.1       0
Bank Sta=4999.7,5003.7
Exp/Cntr=0.3,0.1

Type RM Length L Ch R = 1,146,0,0,0
BEGIN DESCRIPTION:
Stream0587 0.0
END DESCRIPTION:
XS GIS Cut Line= 4
      1884581.63     13894064.05      1884974.26     13893897.86
      1885068.17     13893841.12      1885206.22     13893508.61
#Sta/Elev= 30
  4392.0 1945.96  4483.7 1944.57  4583.8 1931.63  4607.5 1926.74  4660.3 1922.75
  4684.0 1916.89  4784.2 1902.50  4893.4 1891.51  4928.1 1890.01  4945.5 1886.77
  4960.3 1879.57  4967.2 1862.17  4987.6 1859.49  4987.9 1858.99  4991.6 1859.49
  5008.1 1866.37  5013.5 1866.37  5016.2 1868.81  5031.9 1879.21  5037.4 1878.74
  5043.0 1881.96  5090.5 1893.27  5114.4 1907.17  5162.1 1928.54  5167.5 1932.98
  5191.4 1942.55  5220.7 1950.82  5244.5 1962.52  5273.8 1972.38  5288.1 1979.65
#Mann=4,-1,0
  4392.0    0.07       0  4987.6    0.05       0  4991.6    0.07       0
  5016.2     0.1       0
Bank Sta=4987.6,4991.6
Exp/Cntr=0.3,0.1

Chan Stop Cuts=-1