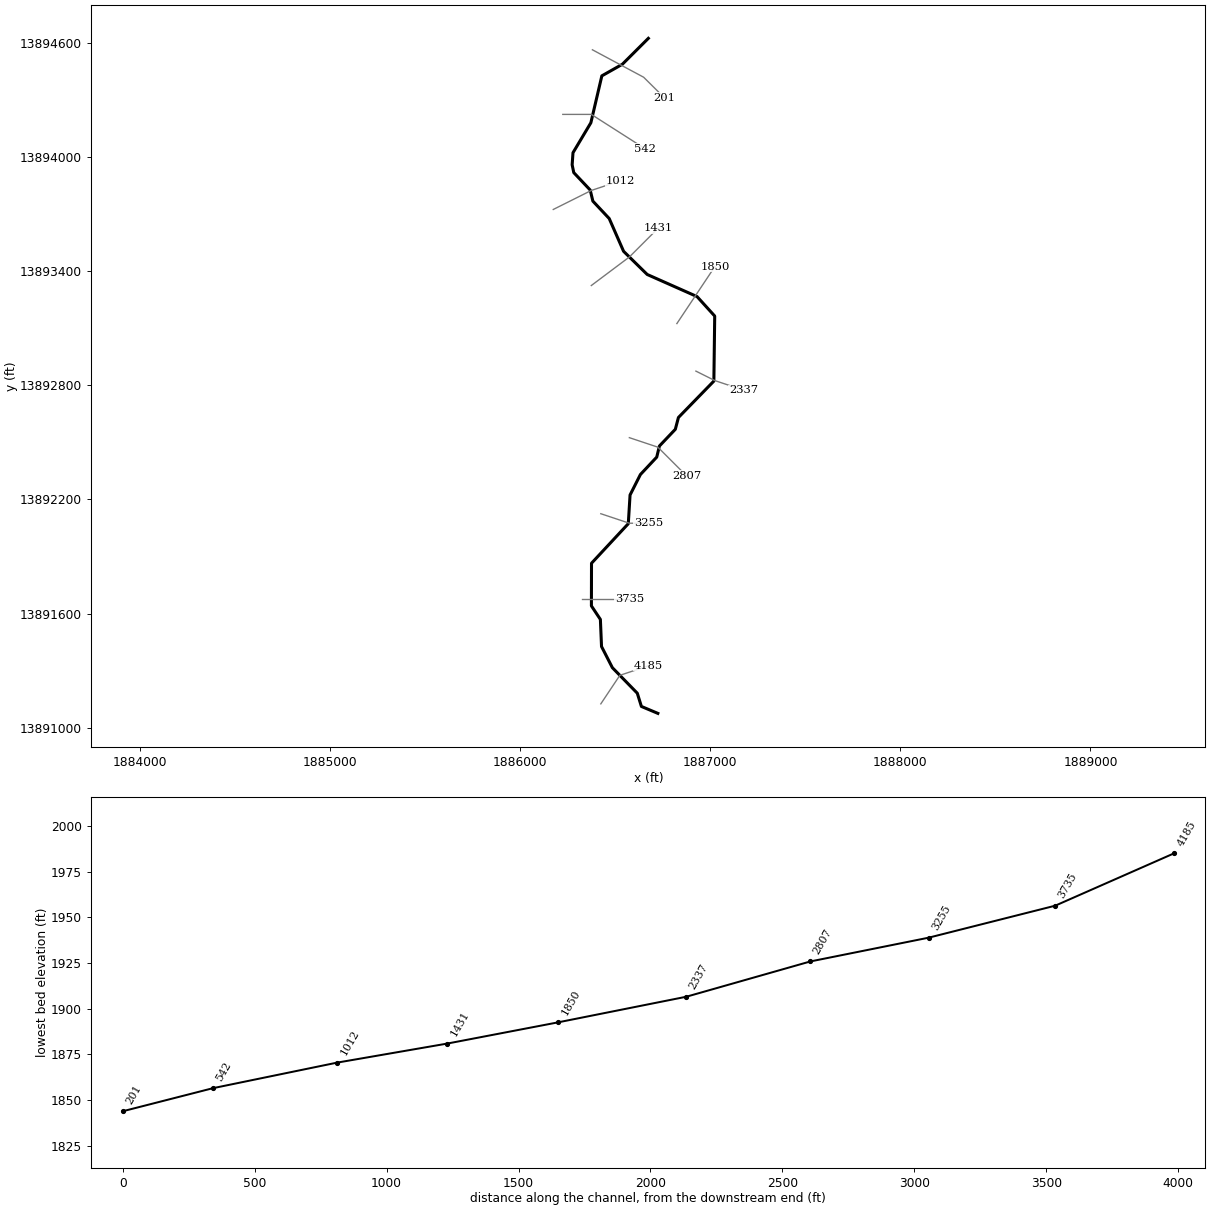
--- Stream0588.prj (project) ---

Proj Title=Stream0588 Base Level Engineering
Current Plan=p01
Default Exp/Contr=0.3,0.1
English Units
Geom File=g01
Flow File=f01
Plan File=p01
Y Axis Title=Elevation
X Axis Title(PF)=Main Channel Distance
X Axis Title(XS)=Station
BEGIN DESCRIPTION:
Stream0588
END DESCRIPTION:
DSS Export Rating Curves= 0
DSS Export Rating Curve Sorted= 0
DSS Export Volume Flow Curves= 0
DXF OffsetX= 0
DXF OffsetY= 0
DXF ScaleX= 1
DXF ScaleY= 10

--- Stream0588.p01 (plan) ---

Plan Title=Multiple Run
Short Identifier=Multiple
Geom File=g01
Flow File=f01
Subcritical Flow
K Sum by GR= 0
Std Step Tol= 0.01
Critical Tol= 0.01
Num of Std Step Trials= 20
Max Error Tol= 0.3
Flow Tol Ratio= 0.001
Split Flow NTrial= 30
Split Flow Tol= 0.02
Split Flow Ratio= 0.02
Log Output Level= 0
Friction Slope Method= 1
Unsteady Friction Slope Method= 2
Unsteady Bridges Friction Slope Method= 1
Parabolic Critical Depth
Global Vel Dist=  1 , 1 , 1
Global Log Level= 0
CheckData=True
Encroach Param= -1, 0, 0, 0
BEGIN DESCRIPTION:
Multiple Run
END DESCRIPTION:

--- Stream0588.f01 (steady flow) ---

Flow Title=Multiple
Program Version=4.10
Number of Profiles= 7
Profile Names=10-year,25-year,50-year,1pct_min,100-year,1pct_plu,500-year
River Rch & RM=Stream0588,Reach-1         ,4185
     263     406     529     337     673    1342    1064
River Rch & RM=Stream0588,Reach-1         ,3255
     634    1044    1423     941    1878    3747    3222
Boundary for River Rch & Prof#=Stream0588,Reach-1         , 1
Up Type= 0
Dn Type= 3
Dn Slope=0.008
Boundary for River Rch & Prof#=Stream0588,Reach-1         , 2
Up Type= 0
Dn Type= 3
Dn Slope=0.008
Boundary for River Rch & Prof#=Stream0588,Reach-1         , 3
Up Type= 0
Dn Type= 3
Dn Slope=0.008
Boundary for River Rch & Prof#=Stream0588,Reach-1         , 4
Up Type= 0
Dn Type= 3
Dn Slope=0.008
Boundary for River Rch & Prof#=Stream0588,Reach-1         , 5
Up Type= 0
Dn Type= 3
Dn Slope=0.008
Boundary for River Rch & Prof#=Stream0588,Reach-1         , 6
Up Type= 0
Dn Type= 3
Dn Slope=0.008
Boundary for River Rch & Prof#=Stream0588,Reach-1         , 7
Up Type= 0
Dn Type= 3
Dn Slope=0.008
DSS Import GetInterval= 0
DSS Import GetPeak= 0
DSS Import FillOption= 0

--- Stream0588.g01 (geometry) ---

Geom Title=Existing Conditions
Program Version=4.10

River Reach=Stream0588      ,Reach-1
Reach XY= 30
        1886725.       13891075.      1886638.39     13891111.46
      1886616.85     13891181.04      1886485.76     13891315.32
      1886428.76     13891426.56      1886422.73     13891569.06
      1886375.52     13891640.22      1886376.05     13891864.57
      1886569.53     13892072.55      1886578.76     13892223.44
      1886633.16     13892331.05      1886719.13     13892422.72
      1886733.18     13892481.04      1886816.82     13892568.96
      1886833.16     13892631.05      1887019.54     13892822.55
      1887023.96     13893164.57      1886931.07     13893266.87
      1886668.94     13893383.14      1886544.78     13893504.91
      1886469.15     13893677.29      1886383.18     13893768.96
      1886369.13     13893827.28      1886282.78     13893918.84
      1886274.23     13893959.91      1886278.67     13894023.41
      1886372.67     13894180.97      1886430.42     13894427.67
       1886538.2     13894488.63        1886675.       13894625.

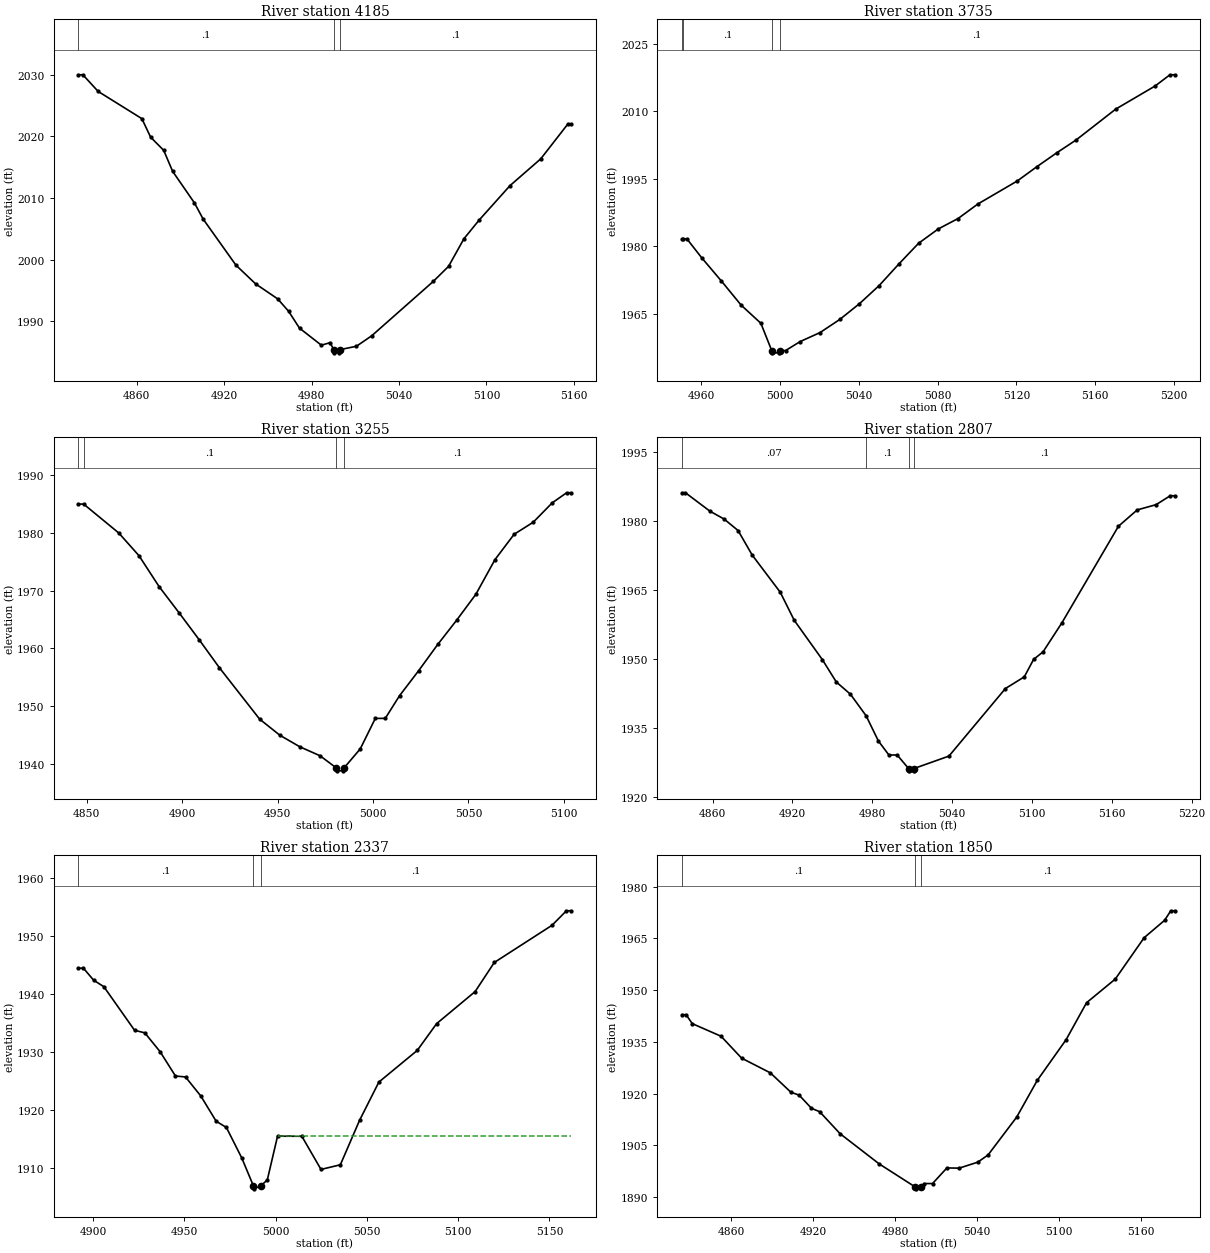
Type RM Length L Ch R = 1 ,4185    ,450,450,450
BEGIN DESCRIPTION:
Stream0588 9.0
END DESCRIPTION:
XS GIS Cut Line= 3
      1886425.03     13891125.04        1886525.       13891275.
      1886674.96     13891324.99
#Sta/Elev= 30
    4820 2029.97    4823 2029.97  4833.5 2027.27  4863.5 2022.86  4869.5 2019.86
  4878.5 2017.72  4884.6 2014.33  4899.6  2009.2  4905.6 2006.57  4928.1 1999.11
  4941.6 1996.08  4956.7 1993.66  4964.2 1991.65  4971.7 1988.91  4986.7 1986.15
  4992.7 1986.56  4995.2 1985.41  4995.5 1984.91    4999 1984.91  4999.2 1985.41
  5010.8 1985.98  5021.3 1987.68  5063.5 1996.48    5074 1998.92  5084.6 2003.41
  5095.1 2006.45  5116.2 2012.01  5137.3 2016.35  5155.7 2021.93  5158.3 2021.93
#Mann= 3 ,-1 , 0
    4820      .1       0  4995.2     .05       0  4999.2      .1       0
Bank Sta=4995.2,4999.2
XS Rating Curve= 0 ,0
Exp/Cntr=0.3,0.1

Type RM Length L Ch R = 1 ,3735    ,480,480,480
BEGIN DESCRIPTION:
Stream0588 8.0
END DESCRIPTION:
XS GIS Cut Line= 3
        1886325.       13891675.        1886375.       13891675.
        1886575.       13891675.
#Sta/Elev= 30
  4950.4  1981.6    4951  1981.6  4952.9  1981.6  4960.4  1977.4  4970.4 1972.23
  4980.4 1966.88  4990.4 1962.85  4995.9 1956.78  4996.2 1956.28  4999.7 1956.28
  4999.9 1956.78  5002.9 1956.78  5010.4  1958.8  5020.4 1960.78  5030.4 1963.69
  5040.4  1967.2  5050.4 1971.23  5060.4 1976.03  5070.4 1980.63  5080.4 1983.82
  5090.4 1986.12  5100.4 1989.34  5120.4 1994.46  5130.4 1997.65  5140.4 2000.71
  5150.4 2003.62  5170.4 2010.45  5190.4 2015.59  5197.9 2018.08  5200.4 2018.08
#Mann= 4 ,-1 , 0
  4950.4     .07       0    4951      .1       0  4995.9     .05       0
  4999.9      .1       0
Bank Sta=4995.9,4999.9
XS Rating Curve= 0 ,0
Exp/Cntr=0.3,0.1

Type RM Length L Ch R = 1 ,3255    ,448,448,448
BEGIN DESCRIPTION:
Stream0588 7.0
END DESCRIPTION:
XS GIS Cut Line= 3
      1886424.95     13892125.02        1886575.       13892075.
      1886675.04       13892075.
#Sta/Elev= 30
  4845.7    1985  4848.4    1985  4866.8 1979.99  4877.4 1976.05  4887.9 1970.71
  4898.5 1966.11    4909 1961.45  4919.5 1956.64  4940.6 1947.72  4951.2 1944.93
  4961.7 1942.92  4972.2 1941.38  4980.8 1939.26    4981 1938.76  4984.5 1938.76
  4984.8 1939.26  4993.3 1942.56  5001.2 1947.85  5006.4 1947.85  5013.9 1951.79
  5023.9 1956.12  5033.9 1960.67  5043.9 1964.91  5053.9 1969.38  5063.9 1975.38
  5073.9 1979.76  5083.9 1981.85  5093.9 1985.22  5101.4 1986.96  5103.9 1986.96
#Mann= 4 ,-1 , 0
  4845.7     .07       0  4848.4      .1       0  4980.8     .05       0
  4984.8      .1       0
Bank Sta=4980.8,4984.8
XS Rating Curve= 0 ,0
Exp/Cntr=0.3,0.1

Type RM Length L Ch R = 1 ,2807    ,470,470,470
BEGIN DESCRIPTION:
Stream0588 6.0
END DESCRIPTION:
XS GIS Cut Line= 3
      1886575.03     13892524.99        1886725.       13892475.
      1886874.99     13892325.01
#Sta/Elev= 30
  4837.1 1986.11  4839.7 1986.11  4858.1 1982.11  4868.7 1980.41  4879.2 1977.92
  4889.8  1972.6  4910.9 1964.52  4921.4 1958.43  4942.5  1949.9    4953 1945.04
  4963.6 1942.39  4975.4  1937.7  4984.6 1932.24  4992.5  1929.2  4998.7  1929.2
  5007.3 1926.26  5007.6 1925.76  5011.1 1925.76  5011.3 1926.26  5037.6 1928.96
    5080 1943.62  5094.2 1946.16  5101.2 1949.95  5108.3 1951.59  5122.5 1957.91
  5164.9 1978.84    5179 1982.39  5193.2 1983.53  5203.8 1985.46  5207.3 1985.46
#Mann= 4 ,-1 , 0
  4837.1     .07       0  4975.4      .1       0  5007.3     .05       0
  5011.3      .1       0
Bank Sta=5007.3,5011.3
XS Rating Curve= 0 ,0
Exp/Cntr=0.3,0.1

Type RM Length L Ch R = 1 ,2337    ,487,487,487
BEGIN DESCRIPTION:
Stream0588 5.0
END DESCRIPTION:
XS GIS Cut Line= 3
      1886925.04     13892874.98        1887025.       13892825.
      1887175.03     13892774.99
#Sta/Elev= 30
  4892.1 1944.43  4894.8 1944.43  4900.4 1942.36    4906 1941.24  4922.8 1933.74
  4928.4  1933.3  4936.8 1930.05  4945.2 1925.87  4950.7 1925.71  4959.1 1922.42
  4967.5 1918.08  4973.1 1917.01  4981.5 1911.77  4987.9 1906.95  4988.1 1906.45
  4991.9 1906.95  4995.5 1907.99  5001.1 1915.51  5014.4  1915.5  5024.9 1909.79
  5035.5 1910.59    5046 1918.23  5056.6 1924.83  5077.6 1930.27  5088.2 1934.88
  5109.3  1940.4  5119.8 1945.41  5151.4 1951.81  5159.3 1954.31    5162 1954.31
#Mann= 3 ,-1 , 0
  4892.1      .1       0  4987.9     .05       0  4991.9      .1       0
#XS Ineff= 2 , 0
                         5001.35         1915.62
Permanent Ineff=
       F       F
Bank Sta=4987.9,4991.9
XS Rating Curve= 0 ,0
Exp/Cntr=0.3,0.1

Type RM Length L Ch R = 1 ,1850    ,419,419,419
BEGIN DESCRIPTION:
Stream0588 4.0
END DESCRIPTION:
XS GIS Cut Line= 3
      1886824.98     13893124.97        1886925.       13893275.
      1887025.01     13893425.01
#Sta/Elev= 30
  4824.1 1942.87  4827.1 1942.87  4831.6 1940.28  4852.7 1936.62  4867.7 1930.28
  4888.7 1926.02  4903.8 1920.39  4909.8 1919.56  4918.8 1915.75  4924.8 1914.76
  4939.8 1908.36  4968.4 1899.62  4994.9  1892.9  4995.2  1892.4  4998.9  1892.9
  5001.4 1893.93  5007.4 1893.93  5017.9 1898.46  5026.9  1898.4  5040.5 1900.13
    5048 1902.21    5069 1913.21    5084 1923.82  5105.1 1935.62  5120.1 1946.35
  5141.1  1953.2  5162.2 1965.18  5177.2 1970.23  5181.7 1972.99  5184.7 1972.99
#Mann= 3 ,-1 , 0
  4824.1      .1       0  4994.9     .05       0  4998.9      .1       0
Bank Sta=4994.9,4998.9
XS Rating Curve= 0 ,0
Exp/Cntr=0.3,0.1

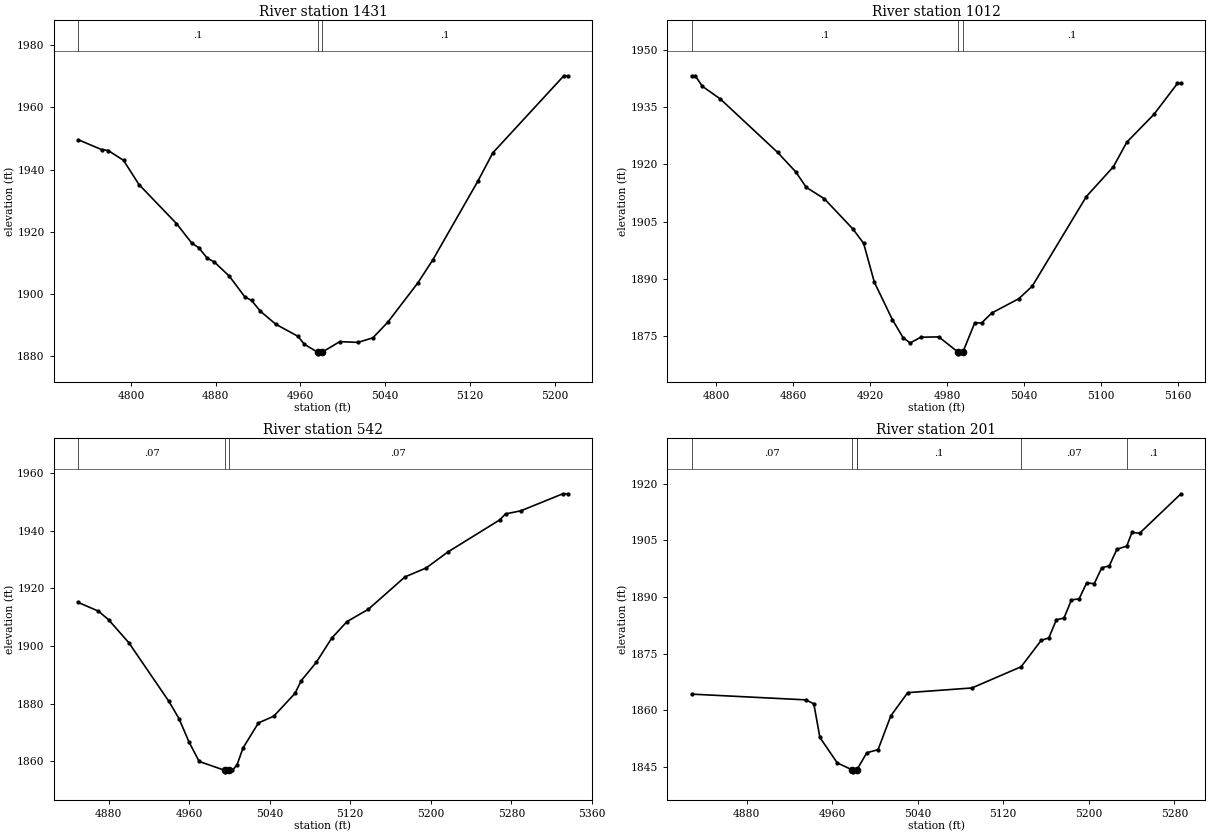
Type RM Length L Ch R = 1 ,1431    ,419,419,419
BEGIN DESCRIPTION:
Stream0588 3.0
END DESCRIPTION:
XS GIS Cut Line= 3
      1886374.97     13893324.98        1886575.       13893475.
      1886725.02     13893625.02
#Sta/Elev= 30
  4750.2 1949.62  4772.1 1946.48  4778.4 1946.17  4792.9 1943.01  4807.5 1935.23
  4842.9 1922.69  4857.5 1916.35  4863.8 1914.98  4872.1 1911.51  4878.4 1910.42
  4892.9 1905.75  4907.5 1899.12  4913.8 1897.97  4922.1 1894.54  4936.7 1890.33
  4957.5 1886.48  4963.8 1883.86  4976.4 1881.31  4976.6 1880.81  4980.4 1881.31
  4997.1 1884.73  5014.4 1884.49  5028.5 1885.97  5042.7 1891.06  5070.9 1903.62
  5085.1 1911.05  5127.5 1936.27  5141.7 1945.41  5208.8 1970.19  5212.4 1970.19
#Mann= 3 ,-1 , 0
  4750.2      .1       0  4976.4     .05       0  4980.4      .1       0
Bank Sta=4976.4,4980.4
XS Rating Curve= 0 ,0
Exp/Cntr=0.3,0.1

Type RM Length L Ch R = 1 ,1012    ,470,470,470
BEGIN DESCRIPTION:
Stream0588 2.0
END DESCRIPTION:
XS GIS Cut Line= 3
      1886174.96     13893724.98        1886375.       13893825.
      1886525.03     13893875.01
#Sta/Elev= 30
  4780.7 1943.25  4783.5 1943.25  4789.1 1940.49  4803.1 1937.17  4847.8 1923.16
  4861.8 1918.11  4870.2 1913.99  4884.2 1911.02  4906.5  1903.1  4914.9 1899.32
  4923.3  1889.1  4937.3 1879.34  4945.7 1874.58  4951.2  1873.2  4959.6  1874.7
  4973.6 1874.78  4988.4 1870.84  4988.6 1870.34  4992.4 1870.84  5001.6 1878.45
    5007 1878.45  5014.9 1881.05    5036  1884.8  5046.5 1888.09  5088.7 1911.59
  5109.8 1919.41  5120.3 1925.86  5141.4 1933.12  5159.8 1941.26  5162.5 1941.26
#Mann= 3 ,-1 , 0
  4780.7      .1       0  4988.4     .05       0  4992.4      .1       0
Bank Sta=4988.4,4992.4
XS Rating Curve= 0 ,0
Exp/Cntr=0.3,0.1

Type RM Length L Ch R = 1 ,542     ,341,341,341
BEGIN DESCRIPTION:
Stream0588 1.0
END DESCRIPTION:
XS GIS Cut Line= 3
        1886225.       13894225.        1886375.       13894225.
      1886658.04     13894044.29
#Sta/Elev= 30
    4850 1915.11    4870  1912.1    4880 1909.14    4900 1901.22    4940 1880.77
    4950 1874.79    4960 1866.62    4970 1859.96  4995.5 1856.86  4995.7 1856.36
  4999.5 1856.86    5003 1856.86  5007.6 1858.81  5013.5 1864.63  5028.8 1873.33
    5044 1875.65  5065.1 1883.57  5071.2 1887.93  5086.3 1894.36  5101.5 1902.71
  5116.7 1908.48  5137.9 1912.74  5174.3 1923.99  5195.4 1927.09  5216.6 1932.57
  5268.2 1943.72  5274.1 1945.83  5289.4 1946.92    5331 1952.82  5335.8 1952.82
#Mann= 3 ,-1 , 0
    4850     .07       0  4995.5     .05       0  4999.5     .07       0
Bank Sta=4995.5,4999.5
XS Rating Curve= 0 ,0
Exp/Cntr=0.3,0.1

Type RM Length L Ch R = 1 ,201     ,0,0,0
BEGIN DESCRIPTION:
Stream0588 0.0
END DESCRIPTION:
XS GIS Cut Line= 3
      1886380.75     13894564.78      1886650.23     13894420.48
      1886758.26     13894313.53
#Sta/Elev= 30
  4828.5 1864.32  4935.4  1862.8  4942.8 1861.75  4948.5 1852.85  4964.7 1846.13
  4978.8 1844.26    4979 1843.76  4982.8 1844.26  4983.5 1844.52  4992.4 1848.82
  5002.9 1849.63  5014.8 1858.56  5030.6 1864.71  5090.7 1865.95  5136.7 1871.56
  5155.5 1878.54  5162.6 1879.19  5169.7    1884  5176.8 1884.44  5183.8 1889.27
  5190.9  1889.5    5198 1893.74  5205.1 1893.54  5212.1 1897.73  5219.2 1898.27
  5226.3 1902.65  5235.5 1903.48  5240.4 1907.11  5247.5 1906.87  5286.2 1917.32
#Mann= 6 ,-1 , 0
  4828.5     .07       0  4978.8     .05       0  4982.8     .07       0
  4983.5      .1       0  5136.7     .07       0  5235.5      .1       0
Bank Sta=4978.8,4982.8
XS Rating Curve= 0 ,0
Exp/Cntr=0.3,0.1

Chan Stop Cuts=-1
Use User Specified Reach Order=0
Composite Channel Slope=5