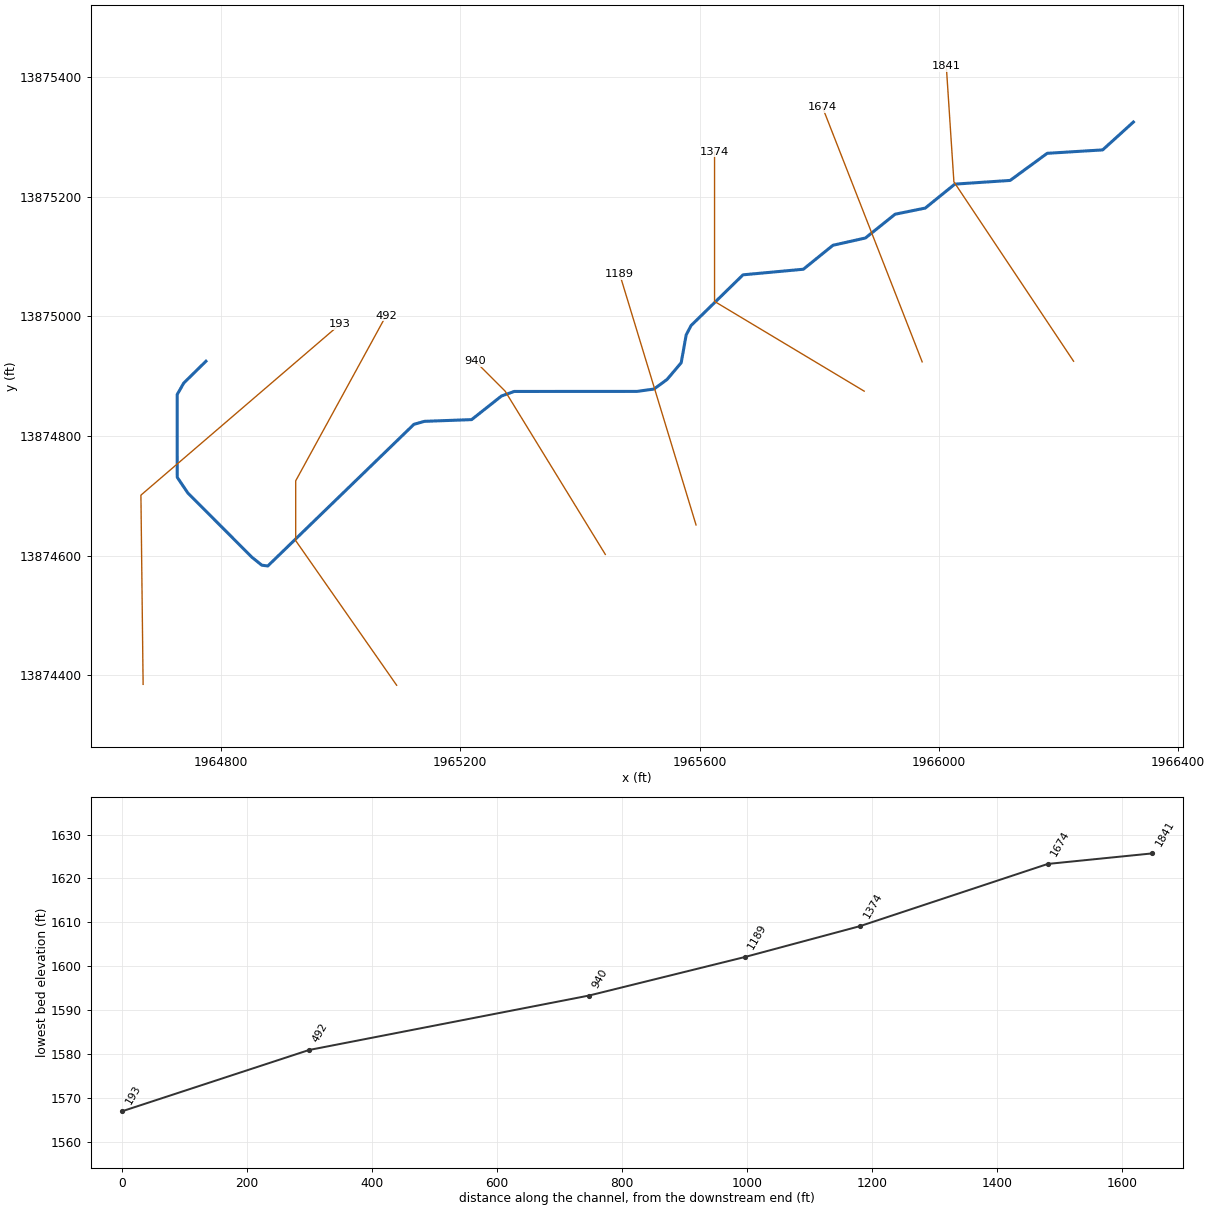
--- Stream0589.prj (project) ---

Proj Title=Stream0589 Base Level Engineering
Current Plan=p01
Default Exp/Contr=0.3,0.1
English Units
Geom File=g01
Flow File=f01
Plan File=p01
BEGIN DESCRIPTION:
Stream0589
END DESCRIPTION:

--- Stream0589.p01 (plan) ---

Plan Title=Multiple Run
Short Identifier=Multiple
Geom File=g01
Flow File=f01
Subcritical Flow
K Sum by GR= 0
Std Step Tol= 0.01
Critical Tol= 0.01
Num of Std Step Trials= 20
Max Error Tol= 0.3
Flow Tol Ratio= 0.001
Split Flow NTrial= 30
Split Flow Tol= 0.02
Split Flow Ratio= 0.02
Log Output Level= 0
Friction Slope Method= 1
Unsteady Friction Slope Method= 2
Unsteady Bridges Friction Slope Method= 1
Parabolic Critical Depth
Global Vel Dist=  1 , 1 , 1
Global Log Level= 0
CheckData=True
Encroach Param= -1, 0, 0, 0
BEGIN DESCRIPTION:
Multiple Run
END DESCRIPTION:

--- Stream0589.f01 (steady flow) ---

Flow Title=Multiple
Number of Profiles=7
Profile Names=10-year,25-year,50-year,1pct_min,100-year,1pct_plu,500-year
River Rch & RM= Stream0589,Reach-1,1841
     594     975    1326     876    1747    3486    2987
Boundary for River Rch & Prof#=Stream0589,Reach-1,1
Up Type=0
Dn Type=3
Dn Slope=0.005
Boundary for River Rch & Prof#=Stream0589,Reach-1,2
Up Type=0
Dn Type=3
Dn Slope=0.005
Boundary for River Rch & Prof#=Stream0589,Reach-1,3
Up Type=0
Dn Type=3
Dn Slope=0.005
Boundary for River Rch & Prof#=Stream0589,Reach-1,4
Up Type=0
Dn Type=3
Dn Slope=0.005
Boundary for River Rch & Prof#=Stream0589,Reach-1,5
Up Type=0
Dn Type=3
Dn Slope=0.005
Boundary for River Rch & Prof#=Stream0589,Reach-1,6
Up Type=0
Dn Type=3
Dn Slope=0.005
Boundary for River Rch & Prof#=Stream0589,Reach-1,7
Up Type=0
Dn Type=3
Dn Slope=0.005

--- Stream0589.g01 (geometry) ---

Geom Title=Existing Conditions

River Reach=Stream0589,Reach-1
Reach XY= 30
      1966325.00     13875325.00      1966273.60     13875278.39
      1966180.96     13875272.68      1966119.03     13875227.35
      1966026.58     13875221.17      1965977.18     13875181.12
      1965926.72     13875170.84      1965877.20     13875131.08
      1965822.82     13875118.88      1965773.41     13875078.83
      1965672.56     13875069.48      1965585.78     13874984.68
      1965577.55     13874968.92      1965569.26     13874922.43
      1965545.55     13874894.44      1965523.75     13874878.45
      1965495.25     13874874.54      1965290.22     13874874.48
      1965268.94     13874866.86      1965219.02     13874827.36
      1965140.22     13874824.48      1965122.57     13874819.48
      1964878.33     13874582.59      1964868.33     13874583.95
      1964851.66     13874597.38      1964744.60     13874704.83
      1964727.04     13874730.85      1964726.88     13874869.21
      1964737.91     13874888.50      1964775.00     13874925.00

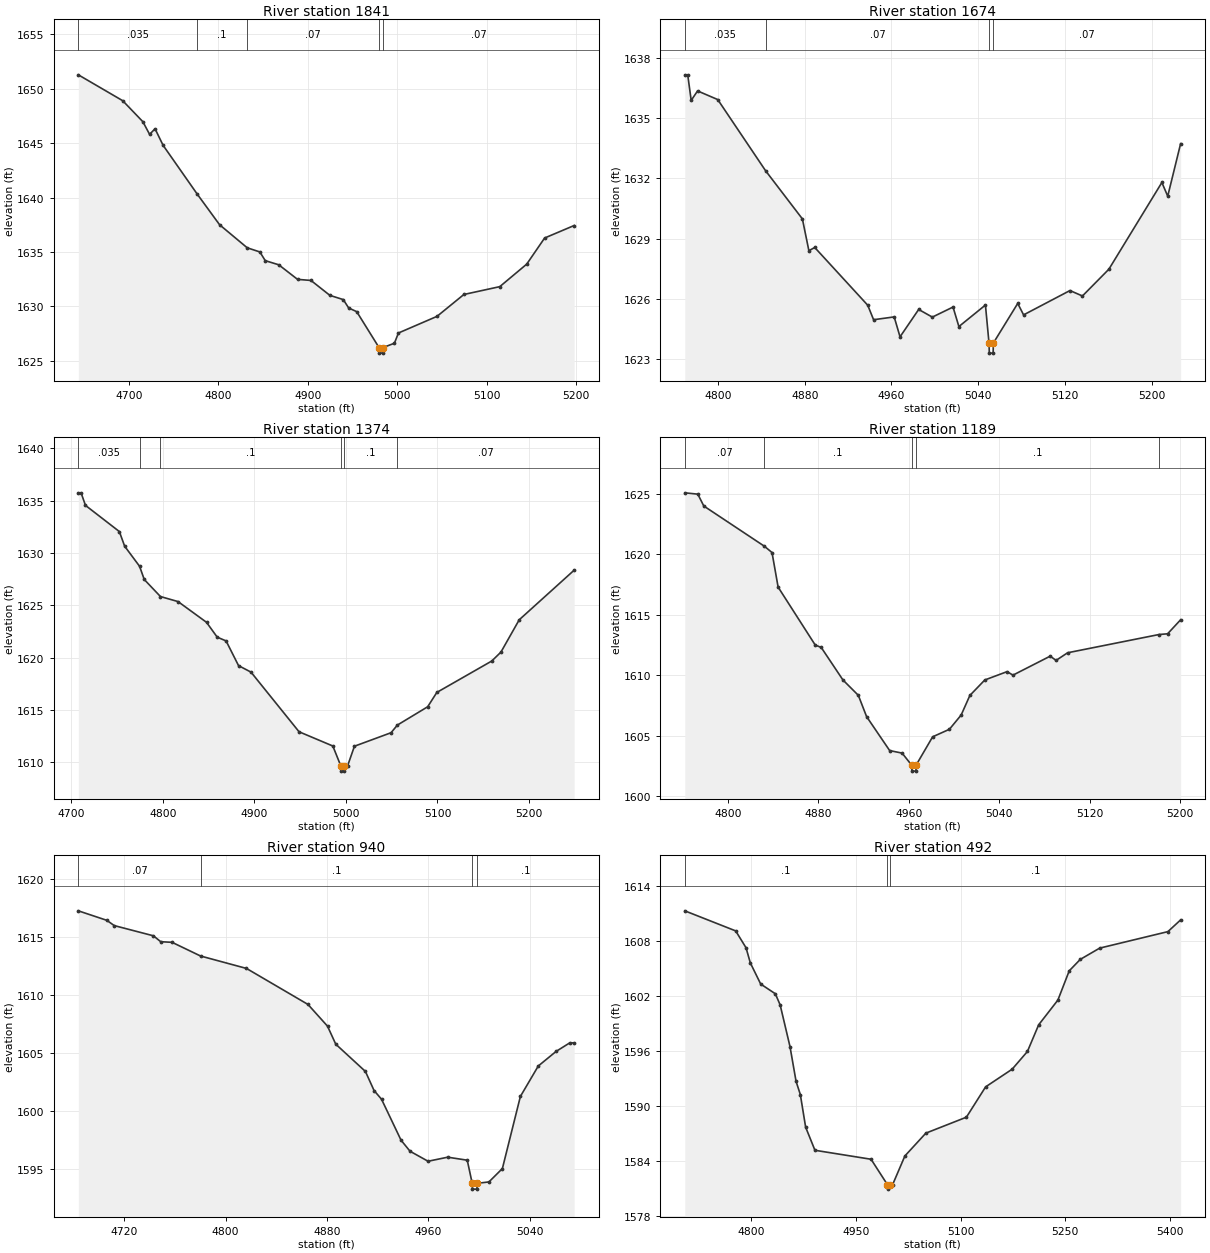
Type RM Length L Ch R = 1,1841,167,167,167
BEGIN DESCRIPTION:
Stream0589 4.0
END DESCRIPTION:
XS GIS Cut Line= 3
      1966225.01     13874924.98      1966025.00     13875225.00
      1966012.33     13875417.91
#Sta/Elev= 30
  4643.7 1651.29  4693.3 1648.91  4715.8 1646.98  4723.3 1645.82  4729.4 1646.33
  4738.4 1644.81  4776.4 1640.34  4801.5 1637.51  4832.4 1635.39  4846.5 1635.01
  4852.5 1634.21  4867.6 1633.83  4888.6 1632.49  4903.6 1632.39  4924.7 1631.02
  4939.7 1630.63  4945.7 1629.86  4954.7 1629.52  4979.7 1626.21  4980.0 1625.71
  4983.5 1625.71  4983.7 1626.21  4996.8 1626.62  5001.3 1627.56  5044.4 1629.09
  5074.4 1631.10  5114.5 1631.82  5144.6 1633.89  5164.6 1636.29  5197.6 1637.44
#Mann=5,-1,0
  4643.7   0.035       0  4776.4     0.1       0  4832.4    0.07       0
  4979.7    0.05       0  4983.7    0.07       0
Bank Sta=4979.7,4983.7
Exp/Cntr=0.3,0.1

Type RM Length L Ch R = 1,1674,300,300,300
BEGIN DESCRIPTION:
Mapping XS 514b3bca
END DESCRIPTION:
XS GIS Cut Line= 2
      1965971.96     13874923.99      1965805.26     13875350.04
#Sta/Elev= 30
  4769.3 1637.14  4772.0 1637.14  4775.2 1635.87  4781.1 1636.34  4799.7 1635.91
  4843.9 1632.37  4877.8 1629.98  4883.8 1628.40  4889.2 1628.56  4938.1 1625.69
  4943.5 1624.97  4962.5 1625.11  4967.9 1624.12  4985.1 1625.48  4997.7 1625.10
  5016.8 1625.60  5022.2 1624.63  5046.7 1625.70  5050.0 1623.81  5050.3 1623.31
  5053.8 1623.31  5054.0 1623.81  5076.5 1625.78  5081.9 1625.21  5124.7 1626.42
  5136.2 1626.15  5160.6 1627.48  5209.5 1631.79  5214.9 1631.11  5226.8 1633.72
#Mann=4,-1,0
  4769.3   0.035       0  4843.9    0.07       0  5050.0    0.05       0
  5054.0    0.07       0
Bank Sta=5050,5054
Exp/Cntr=0.3,0.1

Type RM Length L Ch R = 1,1374,185,185,185
BEGIN DESCRIPTION:
Stream0589 3.0
END DESCRIPTION:
XS GIS Cut Line= 3
      1965875.04     13874874.98      1965625.00     13875025.00
      1965625.00     13875275.01
#Sta/Elev= 30
  4707.7 1635.74  4710.7 1635.74  4715.5 1634.54  4752.5 1632.04  4758.3 1630.64
  4774.6 1628.72  4779.7 1627.46  4797.4 1625.83  4816.6 1625.35  4847.7 1623.37
  4859.4 1621.95  4869.1 1621.59  4882.7 1619.23  4896.3 1618.61  4948.8 1612.91
  4985.7 1611.55  4994.4 1609.65  4994.6 1609.15  4998.1 1609.15  4998.4 1609.65
  5001.8 1609.65  5009.3 1611.53  5049.3 1612.82  5056.2 1613.55  5089.3 1615.30
  5099.3 1616.67  5159.3 1619.67  5169.3 1620.52  5189.3 1623.61  5249.3 1628.35
#Mann=6,-1,0
  4707.7   0.035       0  4774.6    0.07       0  4797.4     0.1       0
  4994.4    0.05       0  4998.4     0.1       0  5056.2    0.07       0
Bank Sta=4994.4,4998.4
Exp/Cntr=0.3,0.1

Type RM Length L Ch R = 1,1189,249,249,249
BEGIN DESCRIPTION:
Mapping XS 735f120e
END DESCRIPTION:
XS GIS Cut Line= 2
      1965594.05     13874651.25      1965466.50     13875070.58
#Sta/Elev= 30
  4762.0 1625.10  4773.5 1624.99  4778.8 1624.01  4832.4 1620.68  4839.1 1620.16
  4844.5 1617.30  4877.3 1612.51  4882.6 1612.31  4901.8 1609.62  4915.4 1608.35
  4922.7 1606.59  4943.1 1603.78  4954.1 1603.57  4962.5 1602.58  4962.8 1602.08
  4966.3 1602.08  4966.5 1602.58  4981.1 1604.92  4995.9 1605.54  5006.3 1606.72
  5014.0 1608.34  5027.2 1609.62  5046.9 1610.31  5052.1 1610.02  5085.0 1611.59
  5090.2 1611.24  5100.4 1611.87  5181.2 1613.38  5188.8 1613.44  5200.3 1614.60
#Mann=5,-1,0
  4762.0    0.07       0  4832.4     0.1       0  4962.5    0.05       0
  4966.5     0.1       0  5181.2    0.07       0
Bank Sta=4962.5,4966.5
Exp/Cntr=0.3,0.1

Type RM Length L Ch R = 1,940,448,448,448
BEGIN DESCRIPTION:
Stream0589 2.0
END DESCRIPTION:
XS GIS Cut Line= 3
      1965442.42     13874601.96      1965275.00     13874875.00
      1965224.99     13874925.01
#Sta/Elev= 30
  4683.9 1617.27  4706.4 1616.45  4712.2 1616.00  4743.1 1615.12  4748.9 1614.61
  4757.8 1614.56  4780.3 1613.38  4816.5 1612.31  4865.0 1609.21  4880.4 1607.34
  4886.9 1605.79  4910.3 1603.44  4917.1 1601.80  4923.0 1601.05  4938.4 1597.52
  4945.5 1596.57  4959.7 1595.71  4975.2 1596.06  4990.6 1595.80  4994.5 1593.81
  4994.7 1593.31  4998.2 1593.31  4998.5 1593.81  5007.7 1593.93  5018.3 1595.08
  5032.5 1601.29  5046.6 1603.91  5060.7 1605.17  5071.4 1605.90  5074.9 1605.90
#Mann=4,-1,0
  4683.9    0.07       0  4780.3     0.1       0  4994.5    0.05       0
  4998.5     0.1       0
Bank Sta=4994.5,4998.5
Exp/Cntr=0.3,0.1

Type RM Length L Ch R = 1,492,299,299,299
BEGIN DESCRIPTION:
Stream0589 1.0
END DESCRIPTION:
XS GIS Cut Line= 4
      1965093.70     13874383.17      1964925.00     13874625.00
      1964925.00     13874725.00      1965075.92     13875000.97
#Sta/Elev= 30
  4705.5 1611.27  4778.3 1609.08  4793.1 1607.24  4799.3 1605.58  4814.1 1603.28
  4835.0 1602.22  4841.9 1601.01  4856.0 1596.46  4864.7 1592.66  4870.8 1591.22
  4878.4 1587.66  4891.7 1585.14  4972.0 1584.16  4995.3 1581.40  4995.6 1580.90
  4999.3 1581.40  5002.9 1581.40  5020.4 1584.52  5050.4 1587.01  5108.4 1588.75
  5135.9 1592.06  5173.9 1593.99  5195.7 1595.92  5211.8 1598.83  5239.3 1601.53
  5255.5 1604.72  5271.3 1605.97  5299.1 1607.20  5396.7 1609.00  5414.9 1610.28
#Mann=3,-1,0
  4705.5     0.1       0  4995.3    0.05       0  4999.3     0.1       0
Bank Sta=4995.3,4999.3
Exp/Cntr=0.3,0.1

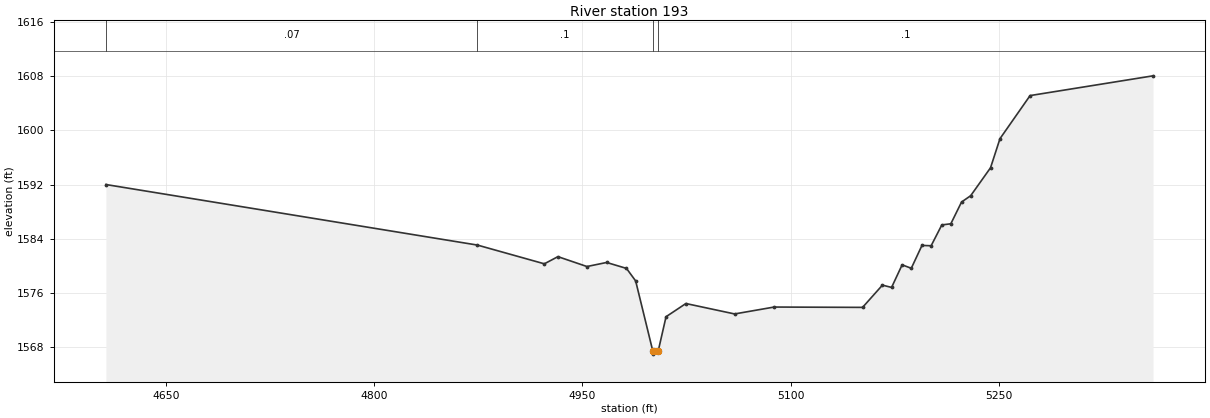
Type RM Length L Ch R = 1,193,0,0,0
BEGIN DESCRIPTION:
Stream0589 0.0
END DESCRIPTION:
XS GIS Cut Line= 3
      1964669.99     13874384.65      1964666.32     13874701.05
      1964998.64     13874986.49
#Sta/Elev= 30
  4606.7 1592.01  4874.4 1583.06  4922.6 1580.29  4932.4 1581.35  4953.3 1579.89
  4967.5 1580.49  4981.8 1579.61  4988.4 1577.76  5000.7 1567.44  5000.9 1566.94
  5004.7 1567.44  5010.3 1572.47  5024.6 1574.42  5059.7 1572.88  5088.2 1573.90
  5151.9 1573.85  5166.2 1577.14  5172.8 1576.80  5180.4 1580.14  5187.0 1579.63
  5194.7 1583.01  5201.3 1582.96  5209.0 1586.04  5215.5 1586.21  5223.2 1589.42
  5229.8 1590.36  5244.1 1594.49  5250.9 1598.79  5272.6 1605.16  5361.2 1608.08
#Mann=4,-1,0
  4606.7    0.07       0  4874.4     0.1       0  5000.7    0.05       0
  5004.7     0.1       0
Bank Sta=5000.7,5004.7
Exp/Cntr=0.3,0.1

Chan Stop Cuts=-1