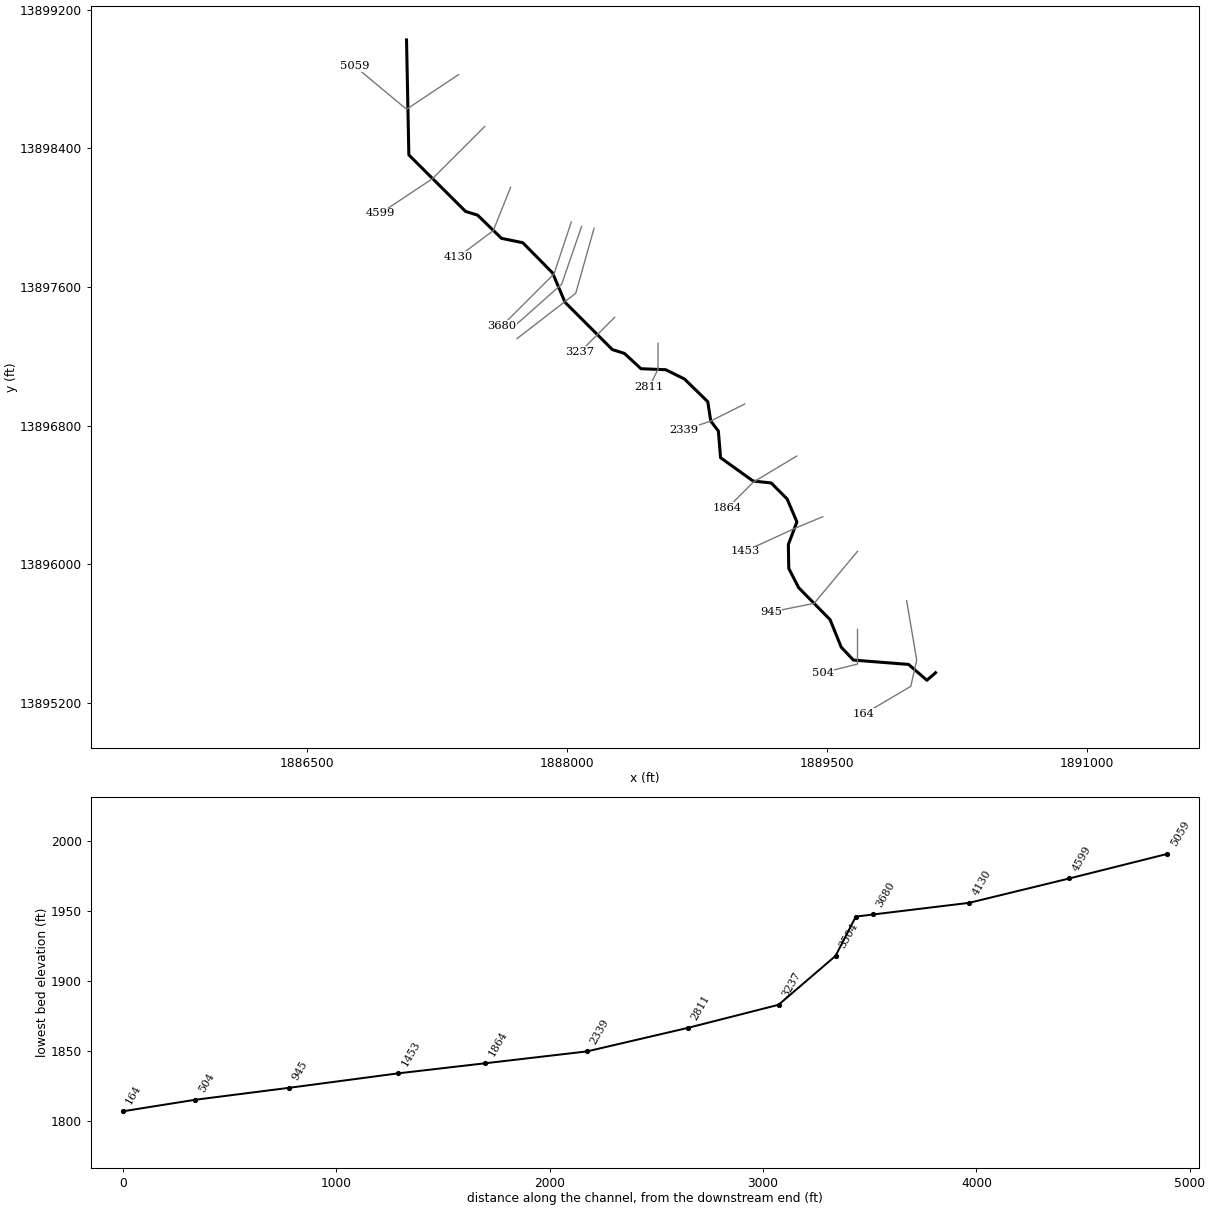
--- Stream0591.prj (project) ---

Proj Title=Stream0591 Base Level Engineering
Current Plan=p01
Default Exp/Contr=0.3,0.1
English Units
Geom File=g01
Flow File=f01
Plan File=p01
BEGIN DESCRIPTION:
Stream0591
END DESCRIPTION:

--- Stream0591.p01 (plan) ---

Plan Title=Multiple Run
Short Identifier=Multiple
Geom File=g01
Flow File=f01
Subcritical Flow
K Sum by GR= 0
Std Step Tol= 0.01
Critical Tol= 0.01
Num of Std Step Trials= 20
Max Error Tol= 0.3
Flow Tol Ratio= 0.001
Split Flow NTrial= 30
Split Flow Tol= 0.02
Split Flow Ratio= 0.02
Log Output Level= 0
Friction Slope Method= 1
Unsteady Friction Slope Method= 2
Unsteady Bridges Friction Slope Method= 1
Parabolic Critical Depth
Global Vel Dist=  1 , 1 , 1
Global Log Level= 0
CheckData=True
Encroach Param= -1, 0, 0, 0
BEGIN DESCRIPTION:
Multiple Run
END DESCRIPTION:

--- Stream0591.f01 (steady flow) ---

Flow Title=Multiple
Number of Profiles=7
Profile Names=10-year,25-year,50-year,1pct_min,100-year,1pct_plu,500-year
River Rch & RM= Stream0591,Reach-1,5059
     718    1199    1648    1100    2195    4379    3833
Boundary for River Rch & Prof#=Stream0591,Reach-1,1
Up Type=0
Dn Type=3
Dn Slope=0.005
Boundary for River Rch & Prof#=Stream0591,Reach-1,2
Up Type=0
Dn Type=3
Dn Slope=0.005
Boundary for River Rch & Prof#=Stream0591,Reach-1,3
Up Type=0
Dn Type=3
Dn Slope=0.005
Boundary for River Rch & Prof#=Stream0591,Reach-1,4
Up Type=0
Dn Type=3
Dn Slope=0.005
Boundary for River Rch & Prof#=Stream0591,Reach-1,5
Up Type=0
Dn Type=3
Dn Slope=0.005
Boundary for River Rch & Prof#=Stream0591,Reach-1,6
Up Type=0
Dn Type=3
Dn Slope=0.005
Boundary for River Rch & Prof#=Stream0591,Reach-1,7
Up Type=0
Dn Type=3
Dn Slope=0.005

--- Stream0591.g01 (geometry) ---

Geom Title=Existing Conditions

River Reach=Stream0591,Reach-1
Reach XY= 30
      1887075.00     13899025.00      1887088.37     13898361.68
      1887415.32     13898035.78      1887484.68     13898014.22
      1887622.57     13897880.52      1887745.15     13897855.37
      1887916.86     13897681.06      1887988.62     13897511.79
      1888261.79     13897238.63      1888331.04     13897216.82
      1888426.47     13897128.55      1888569.07     13897122.75
      1888677.30     13897069.17      1888811.60     13896938.31
      1888828.86     13896826.60      1888872.73     13896769.06
      1888885.47     13896615.18      1889072.68     13896480.77
      1889177.44     13896469.48      1889269.18     13896377.31
      1889325.60     13896245.05      1889276.21     13896114.49
      1889278.74     13895976.56      1889335.76     13895865.32
      1889516.86     13895681.06      1889580.83     13895522.69
      1889651.42     13895447.84      1889969.15     13895422.93
      1890075.01     13895331.59      1890125.00     13895375.00

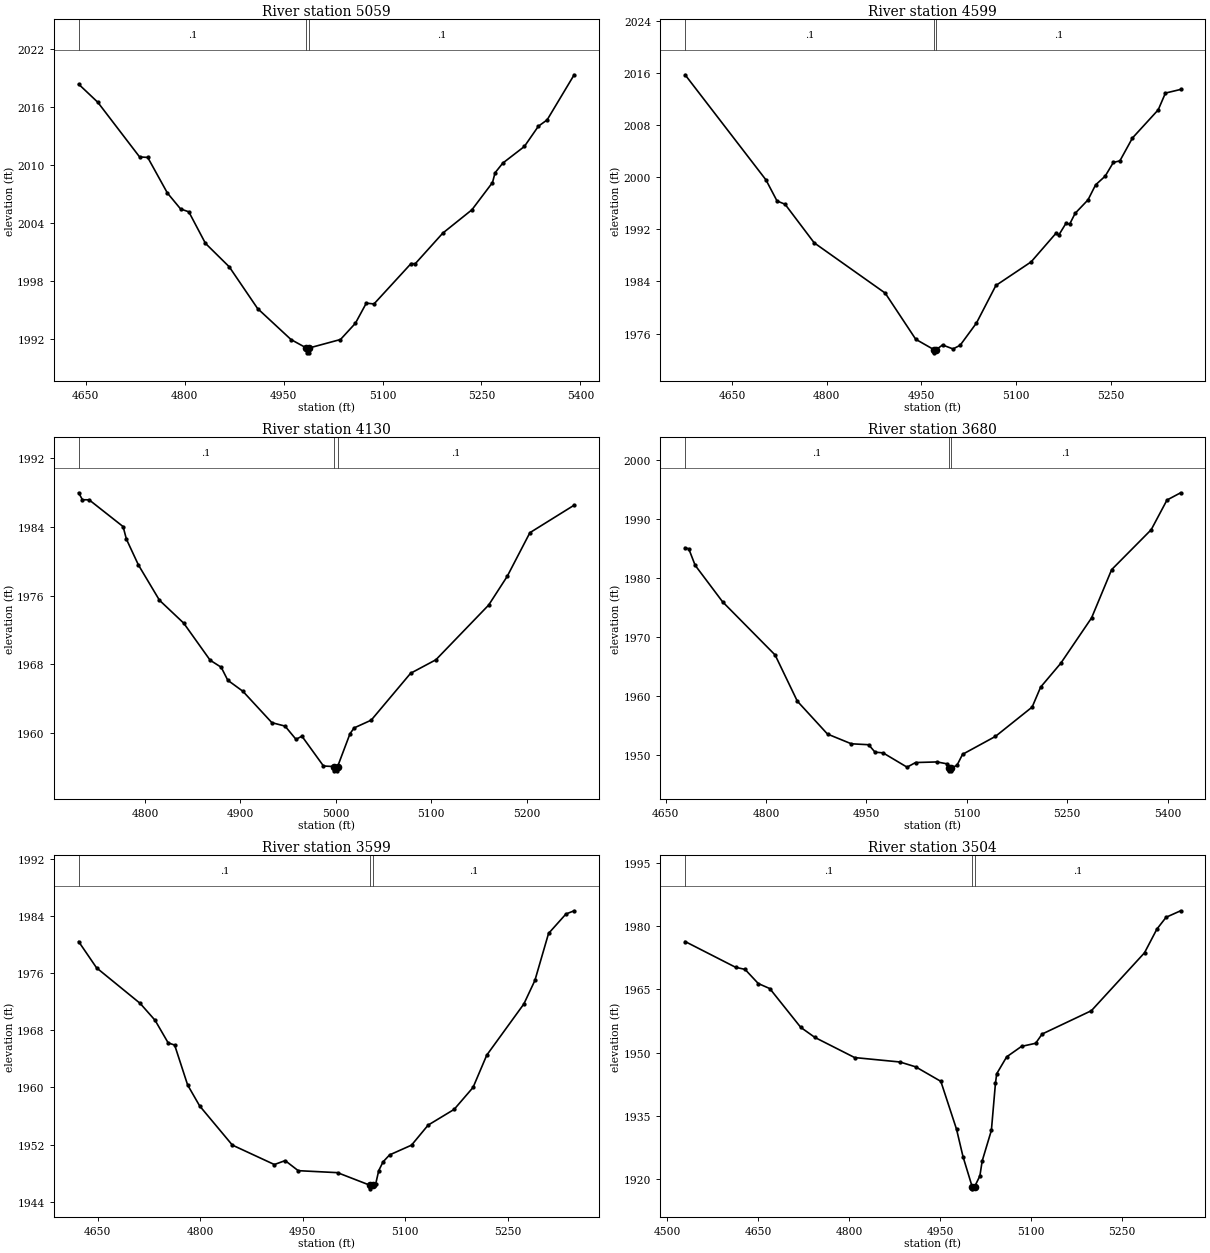
Type RM Length L Ch R = 1,5059,460,460,460
BEGIN DESCRIPTION:
Stream0591 11.0
END DESCRIPTION:
XS GIS Cut Line= 3
      1887375.02     13898825.02      1887075.00     13898625.00
      1886775.00     13898875.00
#Sta/Elev= 30
  4639.4 2018.40  4668.4 2016.53  4731.8 2010.87  4744.1 2010.82  4773.9 2007.14
  4793.9 2005.49  4806.4 2005.19  4831.6 2001.93  4867.7 1999.50  4910.7 1995.18
  4961.4 1991.97  4984.7 1991.10  4984.9 1990.60  4988.4 1990.60  4988.7 1991.10
  5036.3 1991.98  5058.9 1993.66  5075.4 1995.74  5087.1 1995.66  5143.3 1999.84
  5149.6 1999.82  5191.4 2002.99  5235.5 2005.40  5266.7 2008.22  5270.6 2009.23
  5282.3 2010.23  5315.0 2011.95  5336.3 2014.05  5349.5 2014.70  5390.5 2019.37
#Mann=3,-1,0
  4639.4     0.1       0  4984.7    0.05       0  4988.7     0.1       0
Bank Sta=4984.7,4988.7
Exp/Cntr=0.3,0.1

Type RM Length L Ch R = 1,4599,469,469,469
BEGIN DESCRIPTION:
Stream0591 10.0
END DESCRIPTION:
XS GIS Cut Line= 3
      1887525.02     13898525.02      1887225.00     13898225.00
      1886925.04     13898025.02
#Sta/Elev= 30
  4575.7 2015.72  4703.8 1999.58  4721.3 1996.35  4734.0 1995.85  4780.2 1989.92
  4892.6 1982.21  4941.0 1975.12  4969.6 1973.54  4969.8 1973.04  4973.6 1973.54
  4983.4 1974.25  5000.0 1973.64  5011.3 1974.20  5037.1 1977.61  5067.9 1983.38
  5123.7 1987.00  5163.3 1991.42  5167.4 1991.10  5178.9 1992.92  5184.7 1992.79
  5193.4 1994.45  5213.8 1996.52  5225.8 1998.82  5241.0 2000.16  5253.9 2002.26
  5264.3 2002.51  5284.2 2006.02  5325.0 2010.34  5336.4 2012.91  5360.5 2013.47
#Mann=3,-1,0
  4575.7     0.1       0  4969.6    0.05       0  4973.6     0.1       0
Bank Sta=4969.6,4973.6
Exp/Cntr=0.3,0.1

Type RM Length L Ch R = 1,4130,450,450,450
BEGIN DESCRIPTION:
Stream0591 9.0
END DESCRIPTION:
XS GIS Cut Line= 3
      1887675.00     13898174.99      1887575.00     13897925.00
      1887374.96     13897774.97
#Sta/Elev= 30
  4730.5 1987.94  4734.5 1987.13  4741.5 1987.12  4777.1 1984.01  4780.6 1982.54
  4793.2 1979.54  4815.2 1975.45  4840.6 1972.79  4868.3 1968.48  4879.9 1967.66
  4886.8 1966.15  4902.6 1964.87  4933.0 1961.22  4946.8 1960.82  4958.3 1959.28
  4964.5 1959.65  4987.1 1956.18  4997.9 1956.12  4998.1 1955.62  5001.6 1955.62
  5001.9 1956.12  5014.9 1959.94  5019.2 1960.61  5037.1 1961.51  5078.4 1966.96
  5104.9 1968.53  5160.2 1974.89  5179.6 1978.22  5203.4 1983.30  5249.8 1986.50
#Mann=3,-1,0
  4730.5     0.1       0  4997.9    0.05       0  5001.9     0.1       0
Bank Sta=4997.9,5001.9
Exp/Cntr=0.3,0.1

Type RM Length L Ch R = 1,3680,81,81,81
BEGIN DESCRIPTION:
Stream0591 8.0
END DESCRIPTION:
XS GIS Cut Line= 3
      1888025.00     13897975.00      1887925.00     13897675.00
      1887624.99     13897374.99
#Sta/Elev= 30
  4679.0 1985.16  4684.5 1984.98  4694.0 1982.19  4735.1 1975.98  4813.5 1966.97
  4846.7 1959.13  4891.8 1953.55  4927.4 1951.90  4953.3 1951.74  4962.8 1950.48
  4974.8 1950.36  5010.7 1947.93  5023.4 1948.72  5055.5 1948.82  5070.3 1948.50
  5072.8 1947.81  5073.0 1947.31  5076.5 1947.31  5076.8 1947.81  5085.2 1948.23
  5093.6 1950.11  5142.7 1953.15  5197.6 1958.13  5210.3 1961.52  5240.3 1965.55
  5286.4 1973.26  5316.4 1981.45  5375.5 1988.22  5399.1 1993.26  5419.5 1994.49
#Mann=3,-1,0
  4679.0     0.1       0  5072.8    0.05       0  5076.8     0.1       0
Bank Sta=5072.8,5076.8
Exp/Cntr=0.3,0.1

Type RM Length L Ch R = 1,3599,95,95,95
BEGIN DESCRIPTION:
Stream0591 9.1
END DESCRIPTION:
XS GIS Cut Line= 3
      1888084.33     13897949.58      1887969.75     13897616.26
      1887691.10     13897368.85
#Sta/Elev= 30
  4622.0 1980.47  4648.3 1976.78  4712.0 1971.80  4733.9 1969.42  4753.0 1966.26
  4762.5 1965.95  4781.5 1960.35  4799.1 1957.41  4846.9 1951.92  4908.4 1949.19
  4924.2 1949.74  4943.3 1948.33  5000.8 1948.05  5048.4 1946.28  5048.6 1945.78
  5052.4 1946.28  5056.8 1946.52  5061.1 1948.33  5067.4 1949.56  5077.0 1950.54
  5109.1 1951.91  5133.4 1954.72  5171.5 1956.93  5199.1 1960.00  5219.2 1964.54
  5273.5 1971.72  5289.6 1975.01  5309.6 1981.61  5335.1 1984.34  5347.1 1984.79
#Mann=3,-1,0
  4622.0     0.1       0  5048.4    0.05       0  5052.4     0.1       0
Bank Sta=5048.4,5052.4
Exp/Cntr=0.3,0.1

Type RM Length L Ch R = 1,3504,267,267,267
BEGIN DESCRIPTION:
Mapping XS a668a9fc
END DESCRIPTION:
XS GIS Cut Line= 3
      1888156.22     13897938.93      1888050.60     13897563.90
      1887712.11     13897302.16
#Sta/Elev= 30
  4529.4 1976.35  4612.7 1970.24  4628.3 1969.74  4650.1 1966.39  4669.1 1965.19
  4720.2 1955.99  4743.6 1953.60  4809.1 1948.83  4883.9 1947.78  4909.8 1946.63
  4951.3 1943.19  4977.2 1931.83  4987.9 1925.32  5003.0 1918.20  5003.3 1917.70
  5007.0 1918.20  5015.7 1920.76  5019.5 1924.30  5034.7 1931.58  5041.4 1942.75
  5043.5 1945.00  5059.9 1949.00  5084.4 1951.48  5107.7 1952.22  5118.4 1954.41
  5199.7 1959.95  5287.3 1973.68  5307.7 1979.29  5322.9 1982.10  5346.9 1983.64
#Mann=3,-1,0
  4529.4     0.1       0  5003.0    0.05       0  5007.0     0.1       0
Bank Sta=5003,5007
Exp/Cntr=0.3,0.1

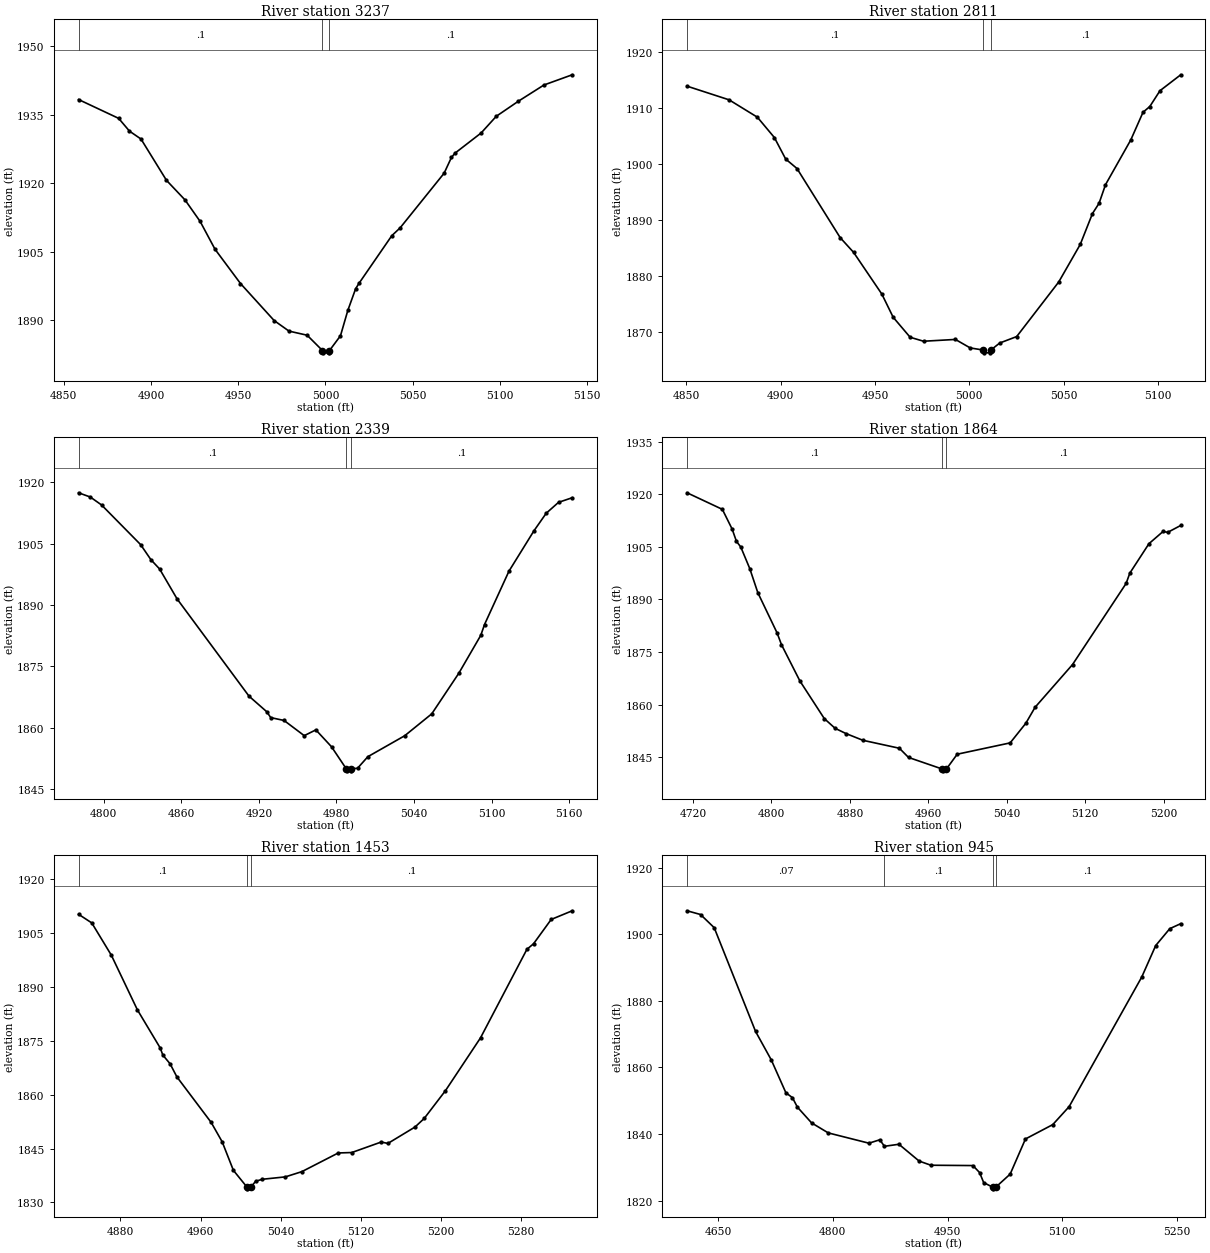
Type RM Length L Ch R = 1,3237,426,426,426
BEGIN DESCRIPTION:
Stream0591 7.0
END DESCRIPTION:
XS GIS Cut Line= 3
      1888275.03     13897425.03      1888175.00     13897325.00
      1888074.99     13897224.99
#Sta/Elev= 30
  4858.5 1938.30  4881.5 1934.17  4887.7 1931.37  4894.3 1929.64  4908.9 1920.59
  4919.5 1916.31  4928.2 1911.58  4936.7 1905.50  4951.3 1897.99  4970.6 1889.87
  4979.1 1887.56  4989.5 1886.66  4998.3 1883.30  4998.6 1882.80  5002.1 1882.80
  5002.3 1883.30  5008.6 1886.54  5012.8 1892.08  5017.3 1896.86  5019.2 1898.02
  5038.0 1908.46  5042.8 1910.19  5068.0 1922.16  5072.2 1925.62  5074.3 1926.57
  5089.2 1930.97  5097.9 1934.63  5110.6 1937.94  5125.2 1941.48  5141.4 1943.72
#Mann=3,-1,0
  4858.5     0.1       0  4998.3    0.05       0  5002.3     0.1       0
Bank Sta=4998.3,5002.3
Exp/Cntr=0.3,0.1

Type RM Length L Ch R = 1,2811,472,472,472
BEGIN DESCRIPTION:
Stream0591 6.0
END DESCRIPTION:
XS GIS Cut Line= 3
      1888525.00     13897275.03      1888525.00     13897125.00
      1888475.02     13897025.03
#Sta/Elev= 30
  4850.3 1913.84  4872.6 1911.40  4887.6 1908.30  4896.6 1904.68  4902.6 1900.84
  4908.6 1899.15  4931.5 1886.82  4938.6 1884.20  4953.6 1876.75  4959.6 1872.62
  4968.6 1869.05  4975.7 1868.34  4992.6 1868.66  5000.5 1867.14  5007.4 1866.77
  5007.7 1866.27  5011.2 1866.27  5011.4 1866.77  5016.1 1868.02  5025.1 1869.17
  5047.4 1878.91  5058.8 1885.60  5065.3 1891.12  5068.8 1892.95  5072.2 1896.26
  5085.6 1904.24  5092.1 1909.18  5095.7 1910.21  5101.1 1913.03  5112.1 1915.87
#Mann=3,-1,0
  4850.3     0.1       0  5007.4    0.05       0  5011.4     0.1       0
Bank Sta=5007.4,5011.4
Exp/Cntr=0.3,0.1

Type RM Length L Ch R = 1,2339,475,475,475
BEGIN DESCRIPTION:
Stream0591 5.0
END DESCRIPTION:
XS GIS Cut Line= 3
      1889025.00     13896925.00      1888825.00     13896825.00
      1888675.02     13896775.01
#Sta/Elev= 30
  4780.6 1917.44  4789.7 1916.40  4798.4 1914.46  4828.6 1904.77  4836.6 1901.07
  4843.3 1898.81  4856.8 1891.50  4912.4 1867.74  4926.1 1863.94  4929.2 1862.50
  4939.5 1861.80  4955.1 1858.09  4964.1 1859.50  4976.2 1855.37  4987.6 1849.99
  4987.8 1849.49  4991.3 1849.49  4991.6 1849.99  4996.3 1850.12  5004.3 1852.95
  5032.8 1858.07  5053.7 1863.42  5074.6 1873.33  5091.6 1882.60  5094.5 1885.25
  5113.4 1898.29  5132.7 1908.14  5142.2 1912.44  5151.7 1915.10  5162.3 1916.23
#Mann=3,-1,0
  4780.6     0.1       0  4987.6    0.05       0  4991.6     0.1       0
Bank Sta=4987.6,4991.6
Exp/Cntr=0.3,0.1

Type RM Length L Ch R = 1,1864,411,411,411
BEGIN DESCRIPTION:
Stream0591 4.0
END DESCRIPTION:
XS GIS Cut Line= 3
      1889324.97     13896624.98      1889075.00     13896475.00
      1888925.03     13896325.03
#Sta/Elev= 30
  4713.9 1920.46  4749.9 1915.73  4759.9 1910.09  4764.3 1906.58  4768.7 1904.98
  4777.9 1898.80  4786.1 1891.93  4805.8 1880.41  4810.2 1877.10  4829.0 1866.73
  4853.9 1855.98  4864.9 1853.21  4875.9 1851.72  4893.3 1849.78  4930.5 1847.51
  4939.8 1844.89  4974.4 1841.56  4974.6 1841.06  4978.4 1841.56  4989.5 1845.81
  5043.5 1849.04  5059.5 1854.65  5068.9 1859.20  5107.1 1871.40  5161.8 1894.58
  5165.6 1897.53  5185.1 1905.93  5199.5 1909.42  5204.2 1909.16  5217.5 1911.13
#Mann=3,-1,0
  4713.9     0.1       0  4974.4    0.05       0  4978.4     0.1       0
Bank Sta=4974.4,4978.4
Exp/Cntr=0.3,0.1

Type RM Length L Ch R = 1,1453,508,508,508
BEGIN DESCRIPTION:
Stream0591 3.0
END DESCRIPTION:
XS GIS Cut Line= 3
      1889474.96     13896274.98      1889317.79     13896209.40
      1889024.97     13896074.99
#Sta/Elev= 30
  4838.3 1910.25  4851.5 1907.84  4871.0 1898.86  4897.0 1883.64  4919.8 1873.01
  4922.4 1871.04  4929.6 1868.62  4936.4 1864.97  4970.6 1852.29  4981.6 1846.88
  4992.8 1838.93  5006.3 1834.29  5006.5 1833.79  5010.3 1834.29  5014.9 1835.88
  5021.5 1836.45  5044.6 1837.12  5061.1 1838.58  5097.4 1843.78  5110.9 1843.90
  5140.3 1846.83  5146.9 1846.43  5174.0 1851.01  5183.1 1853.38  5204.3 1861.11
  5239.3 1875.83  5285.6 1900.49  5292.2 1902.03  5309.8 1908.80  5330.8 1911.22
#Mann=3,-1,0
  4838.3     0.1       0  5006.3    0.05       0  5010.3     0.1       0
Bank Sta=5006.3,5010.3
Exp/Cntr=0.3,0.1

Type RM Length L Ch R = 1,945,441,441,441
BEGIN DESCRIPTION:
Stream0591 2.0
END DESCRIPTION:
XS GIS Cut Line= 3
      1889674.99     13896074.99      1889425.00     13895775.00
      1889175.05     13895725.01
#Sta/Elev= 30
  4609.5 1907.04  4627.1 1905.92  4645.0 1901.96  4699.1 1870.78  4719.6 1862.25
  4738.7 1852.38  4747.3 1850.90  4753.7 1848.08  4772.3 1843.33  4794.1 1840.32
  4847.3 1837.23  4861.4 1838.25  4867.6 1836.30  4886.5 1836.91  4912.9 1831.86
  4928.3 1830.61  4983.2 1830.51  4991.9 1828.42  4997.3 1825.39  5009.1 1824.02
  5009.3 1823.52  5013.1 1824.02  5031.9 1827.94  5051.9 1838.50  5087.6 1842.81
  5109.0 1848.21  5203.9 1887.12  5222.2 1896.60  5240.6 1901.67  5254.9 1903.17
#Mann=4,-1,0
  4609.5    0.07       0  4867.6     0.1       0  5009.1    0.05       0
  5013.1     0.1       0
Bank Sta=5009.1,5013.1
Exp/Cntr=0.3,0.1

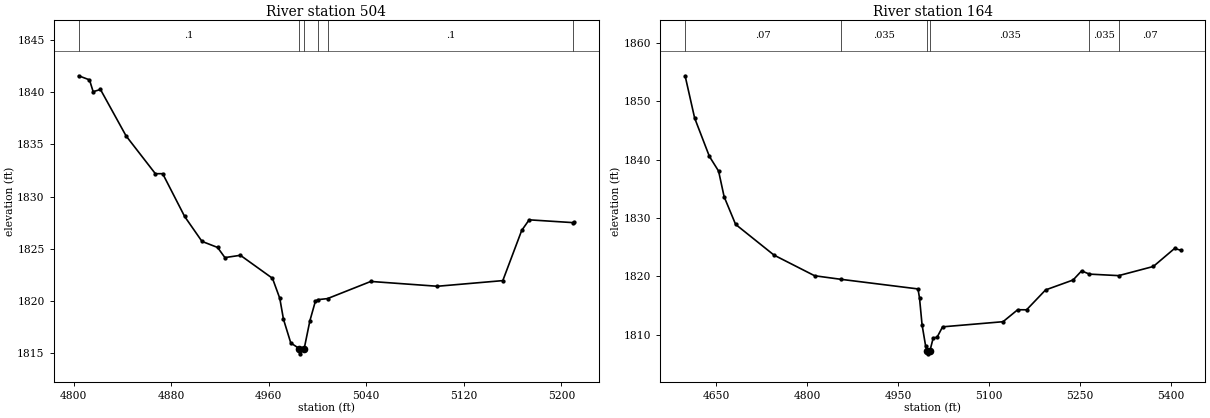
Type RM Length L Ch R = 1,504,340,340,340
BEGIN DESCRIPTION:
Stream0591 1.0
END DESCRIPTION:
XS GIS Cut Line= 3
      1889675.00     13895625.04      1889675.00     13895425.00
      1889475.00     13895375.00
#Sta/Elev= 30
  4804.2 1841.54  4813.1 1841.15  4816.1 1840.02  4822.1 1840.23  4843.1 1835.79
  4867.1 1832.18  4873.1 1832.18  4891.1 1828.09  4905.3 1825.71  4918.1 1825.13
  4924.1 1824.16  4936.8 1824.38  4963.1 1822.18  4969.1 1820.26  4972.1 1818.27
  4978.1 1816.00  4985.1 1815.46  4985.3 1814.96  4989.1 1815.46  4993.8 1818.14
  4998.3 1820.00  5000.4 1820.14  5008.2 1820.24  5043.7 1821.88  5098.3 1821.42
  5151.9 1821.96  5167.4 1826.76  5173.5 1827.77  5209.8 1827.50  5210.4 1827.52
#Mann=6,-1,0
  4804.2     0.1       0  4985.1    0.05       0  4989.1     0.1       0
  5000.4   0.035       0  5008.2     0.1       0  5209.8    0.07       0
Bank Sta=4985.1,4989.1
Exp/Cntr=0.3,0.1

Type RM Length L Ch R = 1,164,0,0,0
BEGIN DESCRIPTION:
Stream0591 0.0
END DESCRIPTION:
XS GIS Cut Line= 4
      1889958.19     13895790.63      1890016.25     13895448.46
      1889982.34     13895296.59      1889712.22     13895137.03
#Sta/Elev= 30
  4599.2 1854.39  4614.9 1847.15  4639.2 1840.57  4654.4 1838.04  4663.5 1833.65
  4682.4 1828.91  4745.7 1823.64  4812.6 1820.10  4855.8 1819.49  4982.9 1817.84
  4985.4 1816.29  4989.6 1811.69  4995.5 1808.03  4998.5 1807.21  4998.8 1806.71
  5002.5 1807.21  5008.0 1809.45  5014.2 1809.53  5023.4 1811.34  5123.0 1812.22
  5147.1 1814.27  5161.8 1814.26  5193.1 1817.67  5238.4 1819.37  5252.4 1820.93
  5265.4 1820.38  5313.5 1820.12  5370.6 1821.69  5405.6 1824.78  5415.6 1824.48
#Mann=6,-1,0
  4599.2    0.07       0  4855.8   0.035       0  4998.5   0.035       0
  5002.5   0.035       0  5265.4   0.035       0  5313.5    0.07       0
Bank Sta=4998.5,5002.5
Exp/Cntr=0.3,0.1

Chan Stop Cuts=-1