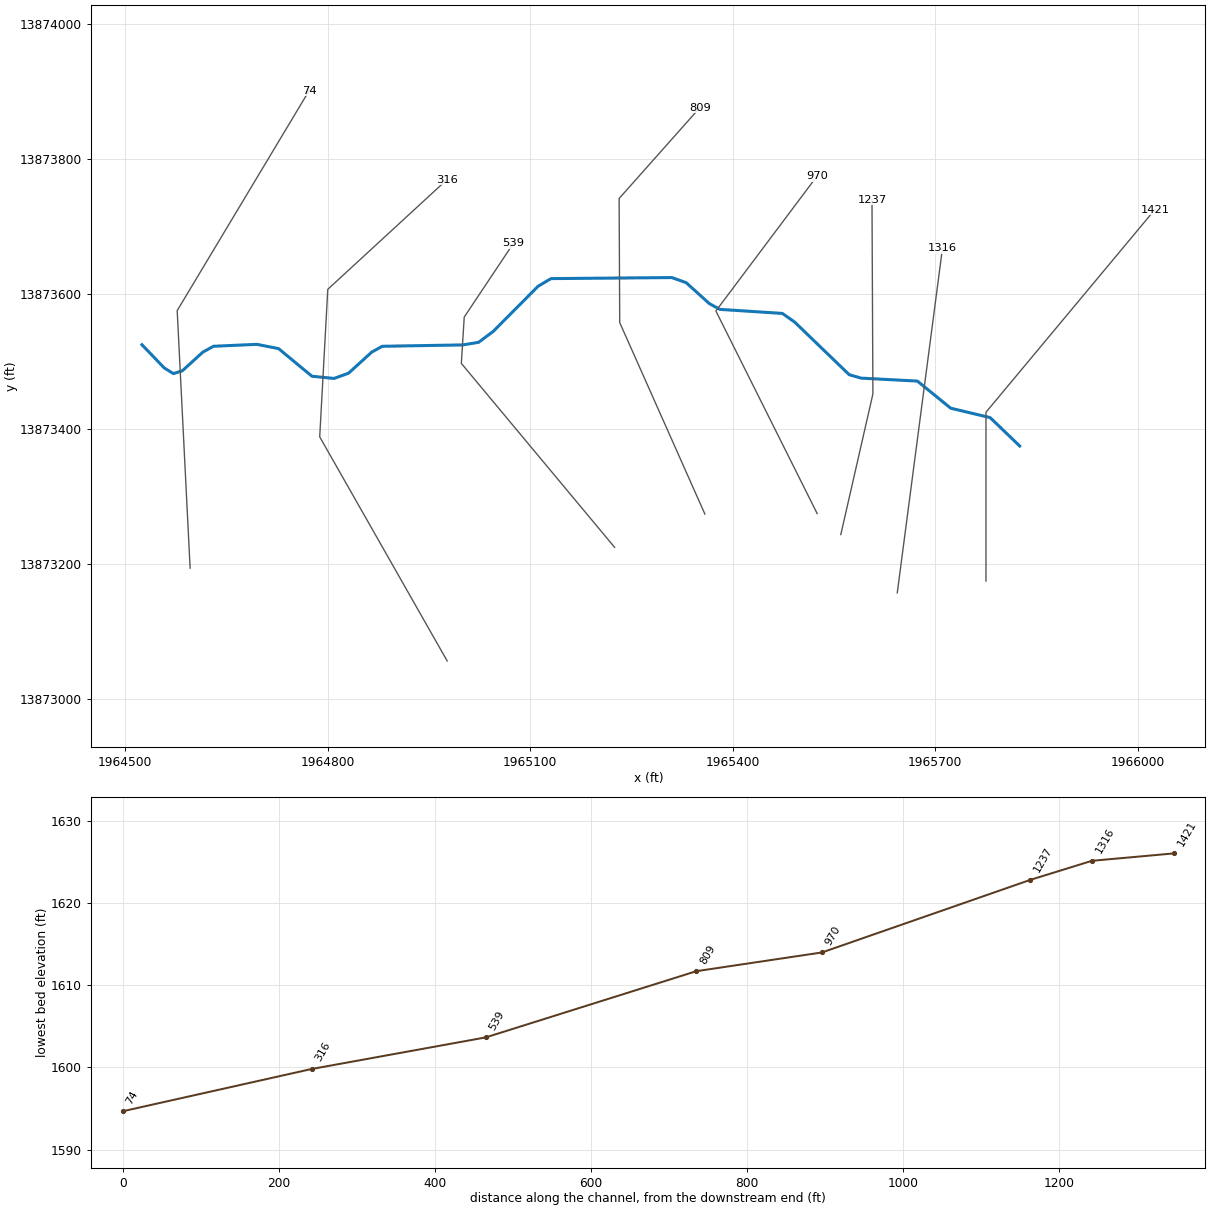
--- Stream0592.prj (project) ---

Proj Title=Stream0592 Base Level Engineering
Current Plan=p01
Default Exp/Contr=0.3,0.1
English Units
Geom File=g01
Flow File=f01
Plan File=p01
BEGIN DESCRIPTION:
Stream0592
END DESCRIPTION:

--- Stream0592.p01 (plan) ---

Plan Title=Multiple Run
Short Identifier=Multiple
Geom File=g01
Flow File=f01
Subcritical Flow
K Sum by GR= 0
Std Step Tol= 0.01
Critical Tol= 0.01
Num of Std Step Trials= 20
Max Error Tol= 0.3
Flow Tol Ratio= 0.001
Split Flow NTrial= 30
Split Flow Tol= 0.02
Split Flow Ratio= 0.02
Log Output Level= 0
Friction Slope Method= 1
Unsteady Friction Slope Method= 2
Unsteady Bridges Friction Slope Method= 1
Parabolic Critical Depth
Global Vel Dist=  1 , 1 , 1
Global Log Level= 0
CheckData=True
Encroach Param= -1, 0, 0, 0
BEGIN DESCRIPTION:
Multiple Run
END DESCRIPTION:

--- Stream0592.f01 (steady flow) ---

Flow Title=Multiple
Number of Profiles=7
Profile Names=10-year,25-year,50-year,1pct_min,100-year,1pct_plu,500-year
River Rch & RM= Stream0592,Reach-1,1421
     800    1341    1849    1238    2470    4928    4340
Boundary for River Rch & Prof#=Stream0592,Reach-1,1
Up Type=0
Dn Type=3
Dn Slope=0.005
Boundary for River Rch & Prof#=Stream0592,Reach-1,2
Up Type=0
Dn Type=3
Dn Slope=0.005
Boundary for River Rch & Prof#=Stream0592,Reach-1,3
Up Type=0
Dn Type=3
Dn Slope=0.005
Boundary for River Rch & Prof#=Stream0592,Reach-1,4
Up Type=0
Dn Type=3
Dn Slope=0.005
Boundary for River Rch & Prof#=Stream0592,Reach-1,5
Up Type=0
Dn Type=3
Dn Slope=0.005
Boundary for River Rch & Prof#=Stream0592,Reach-1,6
Up Type=0
Dn Type=3
Dn Slope=0.005
Boundary for River Rch & Prof#=Stream0592,Reach-1,7
Up Type=0
Dn Type=3
Dn Slope=0.005

--- Stream0592.g01 (geometry) ---

Geom Title=Existing Conditions

River Reach=Stream0592,Reach-1
Reach XY= 30
      1965825.00     13873375.00      1965781.15     13873417.09
      1965722.78     13873431.03      1965673.42     13873471.18
      1965590.22     13873475.53      1965572.58     13873480.54
      1965491.74     13873558.51      1965473.50     13873571.38
      1965380.98     13873577.36      1965365.37     13873585.90
      1965331.06     13873616.86      1965309.78     13873624.48
      1965130.86     13873622.94      1965111.69     13873611.60
      1965045.14     13873544.65      1965023.53     13873528.56
      1965000.11     13873524.73      1964880.93     13873522.70
      1964865.33     13873514.09      1964830.92     13873482.81
      1964809.61     13873475.09      1964776.73     13873478.38
      1964727.32     13873519.28      1964695.05     13873525.58
      1964630.88     13873522.73      1964615.18     13873514.02
      1964584.80     13873486.38      1964571.55     13873482.24
      1964558.16     13873490.54      1964525.00     13873525.00

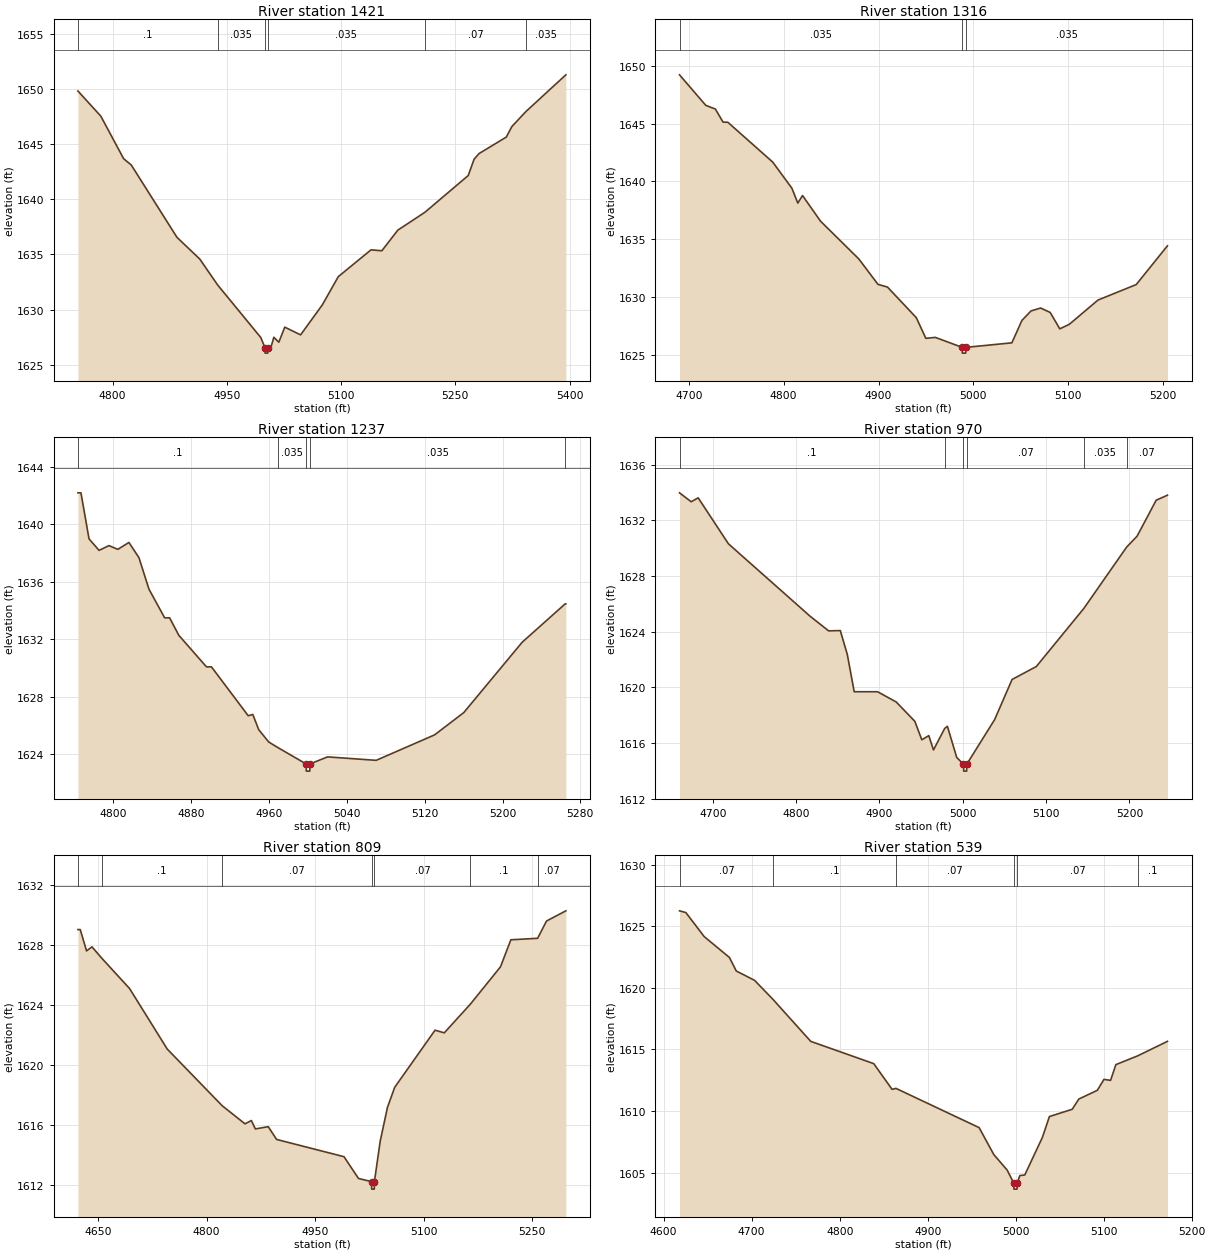
Type RM Length L Ch R = 1,1421,105,105,105
BEGIN DESCRIPTION:
Stream0592 3.0
END DESCRIPTION:
XS GIS Cut Line= 3
      1965775.00     13873175.01      1965775.00     13873425.00
      1966025.00     13873724.99
#Sta/Elev= 30
  4754.6 1649.85  4784.6 1647.57  4814.6 1643.70  4824.6 1643.13  4884.6 1636.56
  4914.6 1634.58  4937.9 1632.24  4994.6 1627.46  5000.1 1626.54  5000.3 1626.04
  5003.8 1626.04  5004.1 1626.54  5007.8 1626.54  5011.8 1627.48  5018.3 1627.03
  5026.1 1628.40  5046.9 1627.70  5075.5 1630.43  5096.4 1632.99  5139.3 1635.42
  5153.6 1635.34  5174.5 1637.21  5210.0 1638.83  5266.9 1642.17  5274.7 1643.66
  5281.2 1644.17  5317.0 1645.67  5324.2 1646.62  5342.9 1648.00  5395.1 1651.32
#Mann=6,-1,0
  4754.6     0.1       0  4937.9   0.035       0  5000.1   0.035       0
  5004.1   0.035       0  5210.0    0.07       0  5342.9   0.035       0
Bank Sta=5000.1,5004.1
Exp/Cntr=0.3,0.1

Type RM Length L Ch R = 1,1316,79,79,79
BEGIN DESCRIPTION:
Mapping XS 5975d26c
END DESCRIPTION:
XS GIS Cut Line= 2
      1965643.63     13873157.56      1965710.55     13873667.58
#Sta/Elev= 30
  4690.2 1649.21  4717.9 1646.57  4728.0 1646.25  4736.1 1645.12  4741.1 1645.11
  4788.5 1641.66  4808.7 1639.40  4814.9 1638.12  4819.9 1638.77  4838.9 1636.55
  4879.3 1633.28  4899.4 1631.09  4909.5 1630.85  4939.8 1628.21  4949.9 1626.42
  4959.9 1626.50  4988.2 1625.64  4988.4 1625.14  4991.9 1625.14  4992.2 1625.64
  5040.6 1626.03  5051.2 1627.97  5060.8 1628.79  5070.9 1629.04  5081.0 1628.66
  5091.1 1627.24  5101.1 1627.63  5131.4 1629.73  5171.7 1631.07  5204.6 1634.42
#Mann=3,-1,0
  4690.2   0.035       0  4988.2   0.035       0  4992.2   0.035       0
Bank Sta=4988.2,4992.2
Exp/Cntr=0.3,0.1

Type RM Length L Ch R = 1,1237,267,267,267
BEGIN DESCRIPTION:
Mapping XS 5a9ec00b
END DESCRIPTION:
XS GIS Cut Line= 3
      1965560.01     13873243.87      1965607.56     13873452.14
      1965606.19     13873739.91
#Sta/Elev= 30
  4763.7 1642.17  4766.8 1642.17  4775.1 1638.97  4785.4 1638.17  4795.6 1638.50
  4804.7 1638.24  4816.1 1638.72  4826.4 1637.66  4836.7 1635.47  4852.8 1633.48
  4857.9 1633.48  4867.4 1632.26  4895.8 1630.07  4900.9 1630.07  4938.7 1626.67
  4943.4 1626.76  4949.5 1625.70  4959.7 1624.85  4969.1 1624.46  4998.2 1623.32
  4998.4 1622.82  5001.9 1622.82  5002.2 1623.32  5020.2 1623.81  5070.2 1623.57
  5130.2 1625.34  5160.2 1626.89  5220.2 1631.78  5264.4 1634.45  5265.1 1634.45
#Mann=5,-1,0
  4763.7     0.1       0  4969.1   0.035       0  4998.2   0.035       0
  5002.2   0.035       0  5264.4    0.07       0
Bank Sta=4998.2,5002.2
Exp/Cntr=0.3,0.1

Type RM Length L Ch R = 1,970,161,161,161
BEGIN DESCRIPTION:
Stream0592 2.0
END DESCRIPTION:
XS GIS Cut Line= 3
      1965525.00     13873274.99      1965375.00     13873575.00
      1965524.99     13873774.99
#Sta/Elev= 30
  4660.2 1633.97  4674.2 1633.33  4682.6 1633.61  4718.9 1630.31  4816.7 1625.12
  4839.1 1624.06  4853.1 1624.08  4861.5 1622.37  4869.8 1619.69  4897.8 1619.69
  4920.1 1618.96  4942.5 1617.57  4950.9 1616.24  4959.3 1616.54  4964.9 1615.51
  4978.3 1617.05  4981.6 1617.21  4992.8 1614.97  5000.9 1614.49  5001.2 1613.99
  5004.7 1613.99  5004.9 1614.49  5038.3 1617.69  5059.2 1620.57  5088.3 1621.50
  5145.3 1625.67  5196.6 1630.07  5209.2 1630.86  5232.1 1633.44  5245.6 1633.80
#Mann=6,-1,0
  4660.2     0.1       0  4978.3    0.07       0  5000.9    0.05       0
  5004.9    0.07       0  5145.3   0.035       0  5196.6    0.07       0
Bank Sta=5000.9,5004.9
Exp/Cntr=0.3,0.1

Type RM Length L Ch R = 1,809,270,270,270
BEGIN DESCRIPTION:
Mapping XS 80e9700b
END DESCRIPTION:
XS GIS Cut Line= 4
      1965358.75     13873274.16      1965232.59     13873557.83
      1965231.72     13873741.59      1965351.22     13873876.04
#Sta/Elev= 30
  4622.2 1629.00  4625.4 1629.00  4634.1 1627.58  4641.6 1627.85  4655.4 1627.08
  4693.6 1625.07  4745.6 1621.04  4821.4 1617.27  4853.0 1616.06  4861.8 1616.28
  4867.3 1615.72  4885.1 1615.87  4896.7 1615.02  4989.8 1613.87  5009.8 1612.42
  5027.8 1612.21  5028.1 1611.71  5031.6 1611.71  5031.8 1612.21  5039.8 1614.90
  5049.8 1617.15  5059.8 1618.49  5115.6 1622.30  5128.3 1622.12  5164.5 1624.04
  5206.0 1626.52  5220.3 1628.32  5257.3 1628.42  5269.6 1629.57  5296.3 1630.25
#Mann=7,-1,0
  4622.2    0.07       0  4655.4     0.1       0  4821.4    0.07       0
  5027.8    0.05       0  5031.8    0.07       0  5164.5     0.1       0
  5257.3    0.07       0
Bank Sta=5027.8,5031.8
Exp/Cntr=0.3,0.1

Type RM Length L Ch R = 1,539,223,223,223
BEGIN DESCRIPTION:
Stream0592 1.0
END DESCRIPTION:
XS GIS Cut Line= 4
      1965225.03     13873224.96      1964998.03     13873497.37
      1965002.32     13873565.98      1965075.02     13873675.03
#Sta/Elev= 30
  4618.0 1626.27  4625.2 1626.13  4646.0 1624.18  4674.7 1622.48  4682.5 1621.38
  4703.3 1620.62  4724.5 1619.05  4767.1 1615.66  4838.7 1613.85  4859.5 1611.76
  4863.9 1611.84  4958.4 1608.65  4975.2 1606.45  4990.3 1605.20  4997.7 1604.15
  4998.0 1603.65  5001.5 1603.65  5001.7 1604.15  5004.7 1604.75  5010.3 1604.80
  5030.3 1607.85  5038.3 1609.55  5064.2 1610.14  5071.7 1610.97  5092.7 1611.68
  5100.3 1612.57  5107.8 1612.49  5113.8 1613.77  5138.5 1614.48  5172.4 1615.66
#Mann=6,-1,0
  4618.0    0.07       0  4724.5     0.1       0  4863.9    0.07       0
  4997.7    0.05       0  5001.7    0.07       0  5138.5     0.1       0
Bank Sta=4997.7,5001.7
Exp/Cntr=0.3,0.1

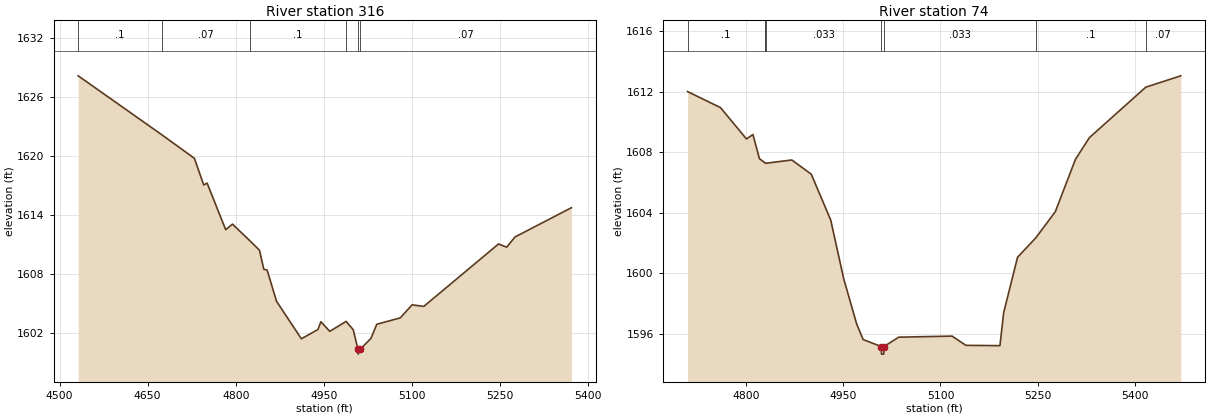
Type RM Length L Ch R = 1,316,242,242,242
BEGIN DESCRIPTION:
Stream0592 0.0
END DESCRIPTION:
XS GIS Cut Line= 4
      1964977.08     13873056.65      1964788.29     13873388.58
      1964800.25     13873607.07      1964976.32     13873769.15
#Sta/Elev= 30
  4531.7 1628.15  4673.6 1622.17  4729.6 1619.75  4745.5 1617.03  4751.2 1617.23
  4782.9 1612.48  4794.4 1613.05  4824.0 1611.36  4840.4 1610.39  4847.8 1608.45
  4853.5 1608.37  4869.4 1605.20  4911.8 1601.37  4940.0 1602.32  4945.0 1603.11
  4960.1 1602.13  4988.0 1603.14  5000.1 1602.30  5008.1 1600.31  5008.4 1599.81
  5012.1 1600.31  5030.2 1601.41  5040.2 1602.85  5080.2 1603.50  5100.3 1604.83
  5120.3 1604.67  5247.6 1611.03  5261.4 1610.70  5275.6 1611.74  5371.7 1614.72
#Mann=6,-1,0
  4531.7     0.1       0  4673.6    0.07       0  4824.0     0.1       0
  4988.0    0.07       0  5008.1    0.05       0  5012.1    0.07       0
Bank Sta=5008.1,5012.1
Exp/Cntr=0.3,0.1

Type RM Length L Ch R = 1,74,0,0,0
BEGIN DESCRIPTION:
Stream0592 0.1
END DESCRIPTION:
XS GIS Cut Line= 3
      1964596.36     13873194.16      1964577.21     13873575.51
      1964772.57     13873901.18
#Sta/Elev= 30
  4709.4 1612.02  4760.3 1610.96  4800.4 1608.89  4810.4 1609.18  4820.4 1607.59
  4828.4 1607.33  4829.1 1607.31  4830.0 1607.28  4870.4 1607.50  4900.5 1606.56
  4930.5 1603.53  4950.5 1599.66  4970.6 1596.66  4980.6 1595.63  5008.6 1595.17
  5008.9 1594.67  5012.4 1594.67  5012.6 1595.17  5035.6 1595.79  5117.9 1595.86
  5139.3 1595.25  5191.8 1595.23  5197.6 1597.42  5219.0 1601.07  5247.3 1602.36
  5277.3 1604.08  5308.4 1607.54  5329.8 1608.97  5417.0 1612.31  5471.0 1613.06
#Mann=8,-1,0
  4709.4     0.1       0  4828.4    0.07       0  4829.1     0.1       0
  4830.0   0.033       0  5008.6   0.033       0  5012.6   0.033       0
  5247.3     0.1       0  5417.0    0.07       0
Bank Sta=5008.6,5012.6
Exp/Cntr=0.3,0.1

Chan Stop Cuts=-1