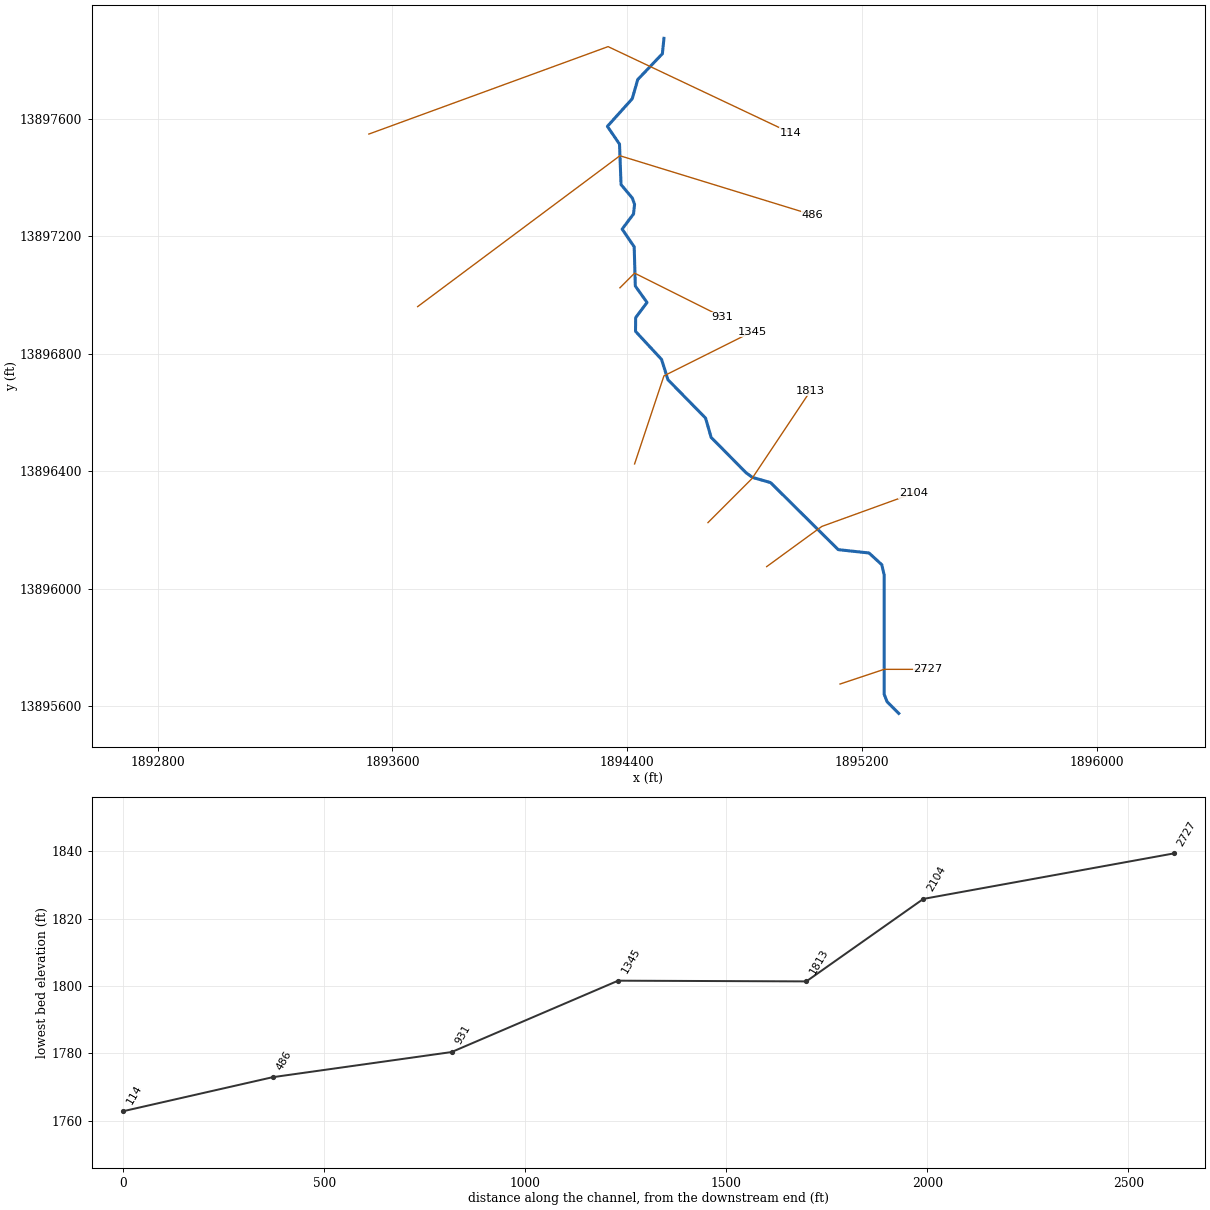
--- Stream0594.prj (project) ---

Proj Title=Stream0594 Base Level Engineering
Current Plan=p01
Default Exp/Contr=0.3,0.1
English Units
Geom File=g01
Flow File=f01
Plan File=p01
BEGIN DESCRIPTION:
Stream0594
END DESCRIPTION:

--- Stream0594.p01 (plan) ---

Plan Title=Multiple Run
Short Identifier=Multiple
Geom File=g01
Flow File=f01
Subcritical Flow
K Sum by GR= 0
Std Step Tol= 0.01
Critical Tol= 0.01
Num of Std Step Trials= 20
Max Error Tol= 0.3
Flow Tol Ratio= 0.001
Split Flow NTrial= 30
Split Flow Tol= 0.02
Split Flow Ratio= 0.02
Log Output Level= 0
Friction Slope Method= 1
Unsteady Friction Slope Method= 2
Unsteady Bridges Friction Slope Method= 1
Parabolic Critical Depth
Global Vel Dist=  1 , 1 , 1
Global Log Level= 0
CheckData=True
Encroach Param= -1, 0, 0, 0
BEGIN DESCRIPTION:
Multiple Run
END DESCRIPTION:

--- Stream0594.f01 (steady flow) ---

Flow Title=Multiple
Number of Profiles=7
Profile Names=10-year,25-year,50-year,1pct_min,100-year,1pct_plu,500-year
River Rch & RM= Stream0594,Reach-1,2727
     422     681     918     603    1203    2400    2026
River Rch & RM= Stream0594,Reach-1,2104
     749    1256    1734    1163    2321    4630    4090
Boundary for River Rch & Prof#=Stream0594,Reach-1,1
Up Type=0
Dn Type=3
Dn Slope=0.005
Boundary for River Rch & Prof#=Stream0594,Reach-1,2
Up Type=0
Dn Type=3
Dn Slope=0.005
Boundary for River Rch & Prof#=Stream0594,Reach-1,3
Up Type=0
Dn Type=3
Dn Slope=0.005
Boundary for River Rch & Prof#=Stream0594,Reach-1,4
Up Type=0
Dn Type=3
Dn Slope=0.005
Boundary for River Rch & Prof#=Stream0594,Reach-1,5
Up Type=0
Dn Type=3
Dn Slope=0.005
Boundary for River Rch & Prof#=Stream0594,Reach-1,6
Up Type=0
Dn Type=3
Dn Slope=0.005
Boundary for River Rch & Prof#=Stream0594,Reach-1,7
Up Type=0
Dn Type=3
Dn Slope=0.005

--- Stream0594.g01 (geometry) ---

Geom Title=Existing Conditions

River Reach=Stream0594,Reach-1
Reach XY= 30
      1895325.00     13895575.00      1895285.05     13895615.02
      1895275.36     13895640.15      1895275.46     13896045.26
      1895267.32     13896081.52      1895223.75     13896121.49
      1895118.83     13896132.86      1894888.21     13896361.37
      1894826.65     13896378.98      1894804.91     13896394.79
      1894685.78     13896515.32      1894666.84     13896581.05
      1894538.63     13896711.79      1894516.82     13896781.04
      1894428.17     13896876.65      1894428.57     13896923.35
      1894467.41     13896974.99      1894427.47     13897030.86
      1894423.61     13897164.56      1894382.59     13897225.01
      1894421.39     13897276.64      1894424.85     13897309.58
      1894417.17     13897330.91      1894378.82     13897376.56
      1894373.60     13897514.56      1894332.33     13897575.10
      1894416.80     13897668.95      1894435.78     13897734.68
      1894519.67     13897822.49      1894525.00     13897875.00

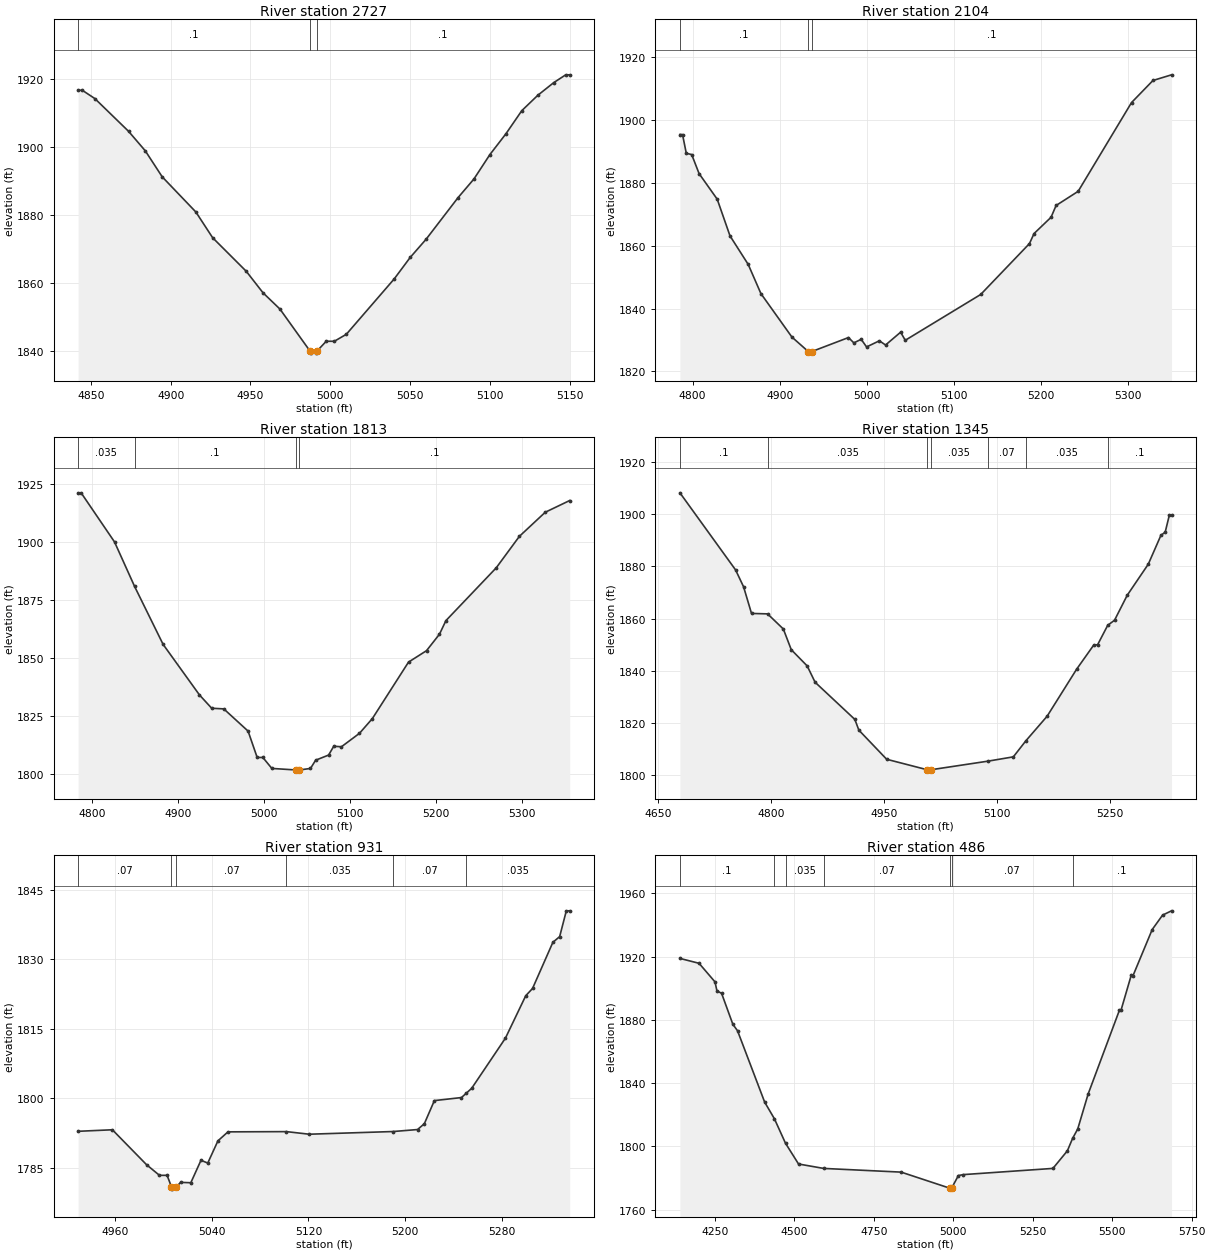
Type RM Length L Ch R = 1,2727,623,623,623
BEGIN DESCRIPTION:
Stream0594 6.0
END DESCRIPTION:
XS GIS Cut Line= 3
      1895125.02     13895675.01      1895275.00     13895725.00
      1895425.01     13895725.00
#Sta/Elev= 30
  4842.0 1916.66  4844.6 1916.66  4852.5 1914.21  4873.6 1904.59  4884.1 1898.84
  4894.7 1891.19  4915.8 1880.84  4926.3 1873.28  4947.4 1863.39  4957.9 1857.06
  4968.5 1852.28  4987.5 1839.82  4987.8 1839.32  4991.3 1839.32  4991.5 1839.82
  4997.5 1842.81  5002.6 1842.81  5010.1 1844.86  5040.1 1861.15  5050.1 1867.46
  5060.1 1872.83  5080.1 1885.06  5090.1 1890.57  5100.1 1897.75  5110.1 1903.84
  5120.1 1910.67  5130.1 1915.18  5140.1 1918.91  5147.6 1921.20  5150.1 1921.20
#Mann=3,-1,0
  4842.0     0.1       0  4987.5    0.05       0  4991.5     0.1       0
Bank Sta=4987.5,4991.5
Exp/Cntr=0.3,0.1

Type RM Length L Ch R = 1,2104,291,291,291
BEGIN DESCRIPTION:
Stream0594 5.0
END DESCRIPTION:
XS GIS Cut Line= 3
      1894875.04     13896075.03      1895062.70     13896211.84
      1895374.99     13896325.00
#Sta/Elev= 30
  4785.4 1895.30  4788.4 1895.30  4792.7 1889.34  4798.9 1888.95  4807.4 1882.89
  4828.2 1874.76  4842.9 1863.09  4863.8 1854.02  4878.4 1844.74  4914.0 1830.92
  4932.8 1826.32  4933.1 1825.82  4936.8 1826.32  4978.9 1830.77  4985.1 1829.08
  4993.5 1830.21  4999.7 1827.79  5014.4 1829.74  5021.5 1828.40  5038.8 1832.48
  5044.1 1829.90  5130.7 1844.46  5186.7 1860.64  5192.0 1863.84  5211.5 1869.01
  5217.3 1872.76  5242.6 1877.25  5303.9 1905.47  5328.5 1912.49  5349.8 1914.29
#Mann=3,-1,0
  4785.4     0.1       0  4932.8    0.05       0  4936.8     0.1       0
Bank Sta=4932.8,4936.8
Exp/Cntr=0.3,0.1

Type RM Length L Ch R = 1,1813,468,468,468
BEGIN DESCRIPTION:
Stream0594 4.0
END DESCRIPTION:
XS GIS Cut Line= 3
      1894674.99     13896224.99      1894825.00     13896375.00
      1895025.00     13896675.00
#Sta/Elev= 30
  4783.4 1921.14  4786.9 1921.14  4825.8 1900.01  4849.2 1880.84  4882.4 1855.91
  4924.8 1834.13  4939.0 1828.42  4953.1 1828.14  4981.4 1818.58  4992.0 1807.23
  4998.6 1807.23  5009.1 1802.51  5037.1 1801.85  5037.4 1801.35  5041.1 1801.85
  5054.1 1802.50  5060.1 1806.05  5075.2 1808.26  5081.2 1812.05  5090.2 1811.84
  5111.2 1817.63  5126.2 1823.97  5168.3 1848.27  5189.3 1853.20  5204.4 1860.30
  5211.9 1866.14  5270.5 1888.86  5297.5 1902.42  5327.6 1912.78  5356.1 1917.83
#Mann=4,-1,0
  4783.4   0.035       0  4849.2     0.1       0  5037.1    0.05       0
  5041.1     0.1       0
Bank Sta=5037.1,5041.1
Exp/Cntr=0.3,0.1

Type RM Length L Ch R = 1,1345,414,414,414
BEGIN DESCRIPTION:
Stream0594 3.0
END DESCRIPTION:
XS GIS Cut Line= 3
      1894424.99     13896424.97      1894525.00     13896725.00
      1894825.02     13896875.01
#Sta/Elev= 30
  4679.4 1908.19  4753.2 1878.65  4763.8 1872.18  4774.3 1861.98  4795.6 1861.81
  4816.5 1856.01  4827.0 1848.09  4848.1 1841.87  4858.6 1835.62  4911.3 1821.37
  4916.6 1817.27  4953.5 1806.10  5007.6 1802.06  5007.9 1801.56  5011.6 1802.06
  5088.0 1805.39  5121.4 1807.03  5138.0 1813.17  5166.2 1822.60  5205.3 1840.61
  5227.7 1849.75  5233.2 1850.03  5246.5 1857.41  5255.6 1859.39  5272.4 1868.95
  5300.3 1880.85  5317.1 1891.94  5322.7 1893.10  5328.3 1899.73  5331.1 1899.73
#Mann=7,-1,0
  4679.4     0.1       0  4795.6   0.035       0  5007.6   0.035       0
  5011.6   0.035       0  5088.0    0.07       0  5138.0   0.035       0
  5246.5     0.1       0
Bank Sta=5007.6,5011.6
Exp/Cntr=0.3,0.1

Type RM Length L Ch R = 1,931,445,445,445
BEGIN DESCRIPTION:
Stream0594 2.0
END DESCRIPTION:
XS GIS Cut Line= 3
      1894374.99     13897024.99      1894425.00     13897075.00
      1894724.96     13896925.02
#Sta/Elev= 30
  4929.7 1792.88  4958.0 1793.21  4986.3 1785.65  4996.9 1783.37  5003.2 1783.37
  5006.8 1780.89  5007.1 1780.39  5010.8 1780.89  5014.4 1781.85  5022.8 1781.77
  5031.2 1786.62  5036.8 1786.02  5045.2 1790.82  5053.5 1792.76  5101.8 1792.81
  5120.6 1792.25  5189.9 1792.83  5210.1 1793.26  5215.7 1794.51  5224.0 1799.51
  5246.4 1800.17  5250.5 1801.14  5254.8 1802.16  5282.7 1813.00  5299.5 1822.17
  5305.1 1823.73  5321.9 1833.70  5327.5 1834.93  5333.0 1840.50  5335.8 1840.50
#Mann=6,-1,0
  4929.7    0.07       0  5006.8    0.05       0  5010.8    0.07       0
  5101.8   0.035       0  5189.9    0.07       0  5250.5   0.035       0
Bank Sta=5006.8,5010.8
Exp/Cntr=0.3,0.1

Type RM Length L Ch R = 1,486,372,372,372
BEGIN DESCRIPTION:
Stream0594 1.0
END DESCRIPTION:
XS GIS Cut Line= 3
      1893685.85     13896960.89      1894375.00     13897475.00
      1895031.60     13897273.21
#Sta/Elev= 30
  4139.9 1918.91  4200.1 1915.82  4250.2 1904.07  4256.4 1898.37  4271.0 1896.82
  4306.5 1877.20  4321.1 1873.16  4406.5 1827.99  4437.2 1817.44  4472.1 1801.96
  4513.1 1788.83  4592.2 1786.03  4836.0 1783.69  4990.4 1773.43  4990.6 1772.93
  4994.4 1773.43  5016.0 1781.51  5031.1 1782.11  5313.5 1786.04  5358.9 1797.16
  5375.3 1804.99  5391.6 1811.03  5424.3 1833.12  5522.4 1885.96  5527.7 1886.10
  5560.4 1908.62  5565.6 1908.05  5625.8 1937.16  5658.5 1946.30  5686.6 1949.02
#Mann=7,-1,0
  4139.9     0.1       0  4437.2    0.07       0  4472.1   0.035       0
  4592.2    0.07       0  4990.4    0.05       0  4994.4    0.07       0
  5375.3     0.1       0
Bank Sta=4990.4,4994.4
Exp/Cntr=0.3,0.1

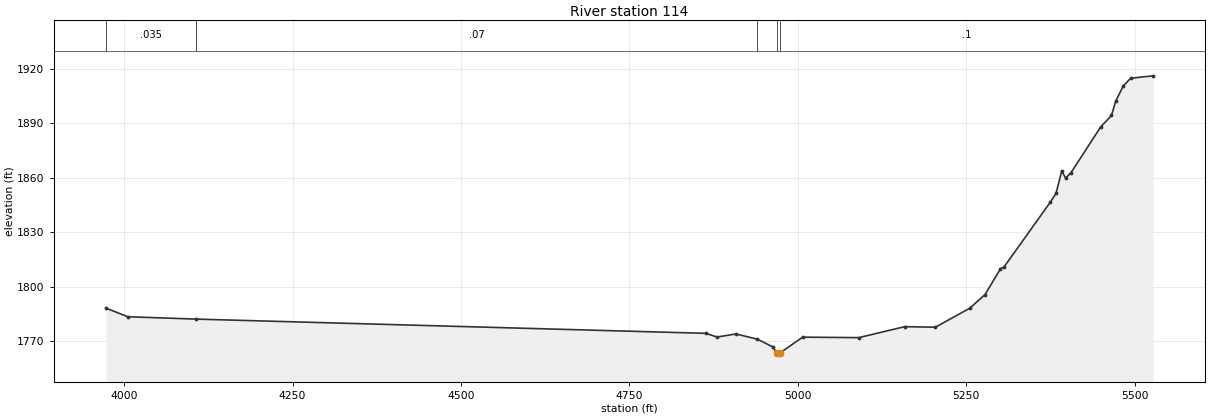
Type RM Length L Ch R = 1,114,0,0,0
BEGIN DESCRIPTION:
Stream0594 0.0
END DESCRIPTION:
XS GIS Cut Line= 3
      1893519.58     13897548.82      1894334.71     13897846.76
      1894955.16     13897553.36
#Sta/Elev= 30
  3972.9 1788.17  4005.4 1783.41  4106.1 1782.12  4863.2 1774.28  4879.9 1772.24
  4908.2 1773.94  4940.0 1771.02  4962.8 1766.81  4968.9 1763.33  4969.2 1762.83
  4972.9 1763.33  5007.0 1772.18  5090.2 1771.91  5158.5 1777.95  5204.0 1777.65
  5255.1 1788.11  5277.8 1795.65  5300.6 1809.83  5306.1 1810.92  5374.4 1846.37
  5383.1 1851.34  5391.6 1863.77  5397.2 1859.73  5405.2 1862.65  5449.5 1887.98
  5465.4 1894.21  5471.6 1902.01  5482.7 1910.34  5493.7 1914.71  5527.1 1916.05
#Mann=5,-1,0
  3972.9   0.035       0  4106.1    0.07       0  4940.0     0.1       0
  4968.9    0.05       0  4972.9     0.1       0
Bank Sta=4968.9,4972.9
Exp/Cntr=0.3,0.1

Chan Stop Cuts=-1