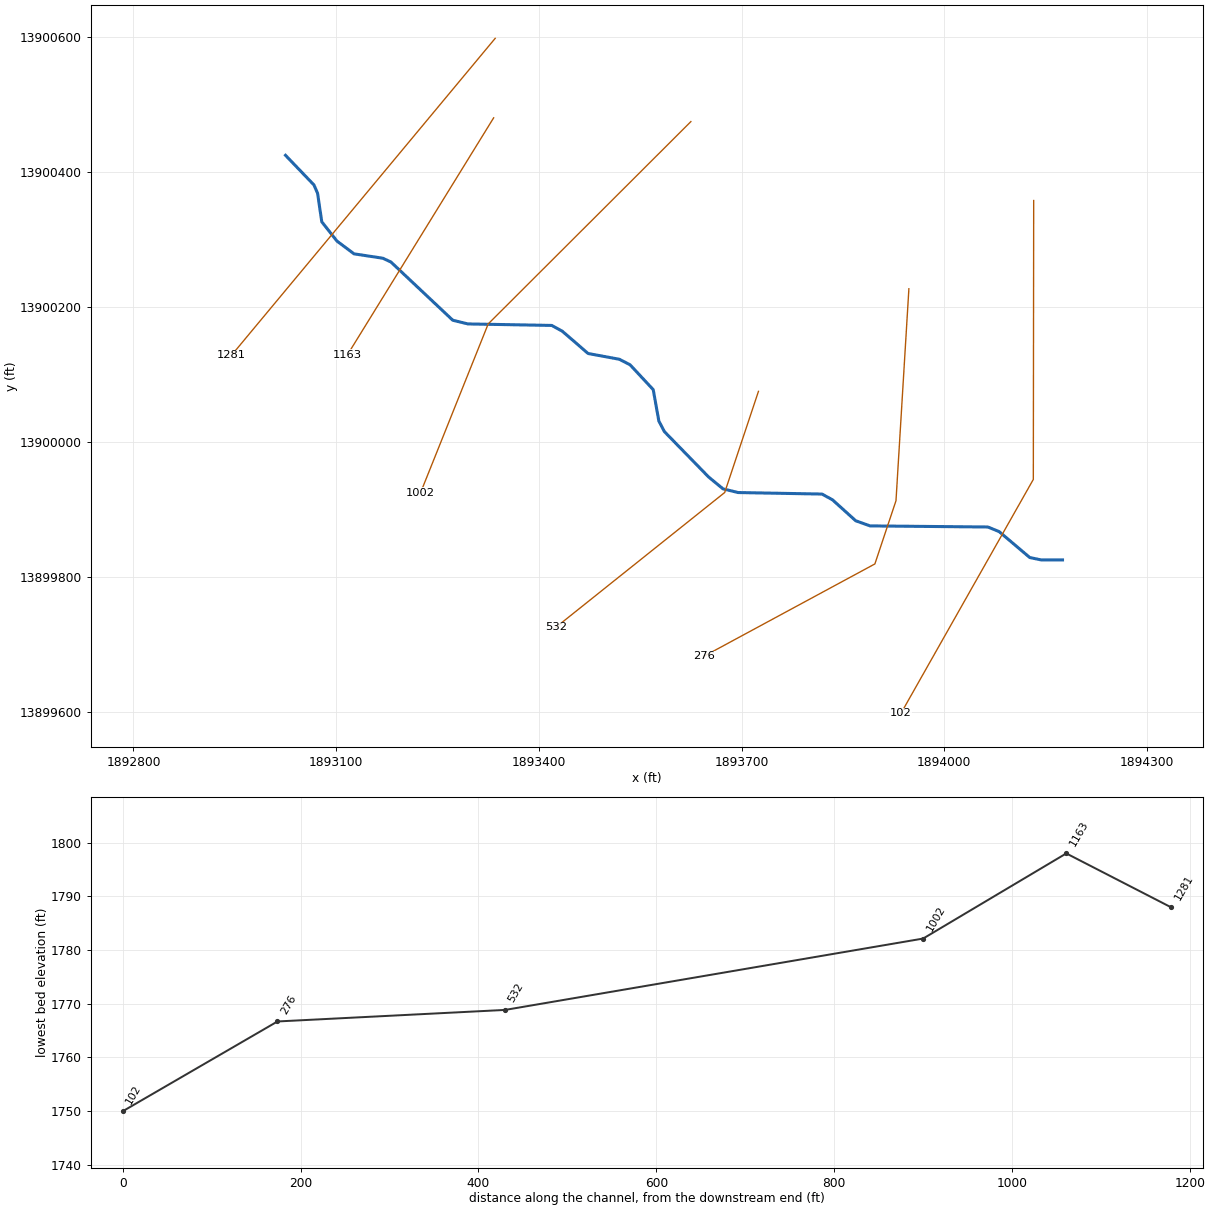
--- Stream0595.prj (project) ---

Proj Title=Stream0595 Base Level Engineering
Current Plan=p01
Default Exp/Contr=0.3,0.1
English Units
Geom File=g01
Flow File=f01
Plan File=p01
BEGIN DESCRIPTION:
Stream0595
END DESCRIPTION:

--- Stream0595.p01 (plan) ---

Plan Title=Multiple Run
Short Identifier=Multiple
Geom File=g01
Flow File=f01
Subcritical Flow
K Sum by GR= 0
Std Step Tol= 0.01
Critical Tol= 0.01
Num of Std Step Trials= 20
Max Error Tol= 0.3
Flow Tol Ratio= 0.001
Split Flow NTrial= 30
Split Flow Tol= 0.02
Split Flow Ratio= 0.02
Log Output Level= 0
Friction Slope Method= 1
Unsteady Friction Slope Method= 2
Unsteady Bridges Friction Slope Method= 1
Parabolic Critical Depth
Global Vel Dist=  1 , 1 , 1
Global Log Level= 0
CheckData=True
Encroach Param= -1, 0, 0, 0
BEGIN DESCRIPTION:
Multiple Run
END DESCRIPTION:

--- Stream0595.f01 (steady flow) ---

Flow Title=Multiple
Number of Profiles=7
Profile Names=10-year,25-year,50-year,1pct_min,100-year,1pct_plu,500-year
River Rch & RM= Stream0595,Reach-1,1281
     518     848    1151     760    1517    3026    2590
Boundary for River Rch & Prof#=Stream0595,Reach-1,1
Up Type=0
Dn Type=3
Dn Slope=0.005
Boundary for River Rch & Prof#=Stream0595,Reach-1,2
Up Type=0
Dn Type=3
Dn Slope=0.005
Boundary for River Rch & Prof#=Stream0595,Reach-1,3
Up Type=0
Dn Type=3
Dn Slope=0.005
Boundary for River Rch & Prof#=Stream0595,Reach-1,4
Up Type=0
Dn Type=3
Dn Slope=0.005
Boundary for River Rch & Prof#=Stream0595,Reach-1,5
Up Type=0
Dn Type=3
Dn Slope=0.005
Boundary for River Rch & Prof#=Stream0595,Reach-1,6
Up Type=0
Dn Type=3
Dn Slope=0.005
Boundary for River Rch & Prof#=Stream0595,Reach-1,7
Up Type=0
Dn Type=3
Dn Slope=0.005

--- Stream0595.g01 (geometry) ---

Geom Title=Existing Conditions

River Reach=Stream0595,Reach-1
Reach XY= 30
      1893025.00     13900425.00      1893067.05     13900381.11
      1893072.42     13900368.89      1893078.71     13900326.34
      1893101.14     13900297.84      1893126.43     13900278.88
      1893168.91     13900272.44      1893181.02     13900266.81
      1893272.56     13900180.48      1893294.99     13900174.98
      1893419.07     13900172.75      1893434.67     13900164.20
      1893472.85     13900131.15      1893519.15     13900122.58
      1893535.00     13900114.37      1893569.25     13900077.54
      1893577.55     13900031.08      1893585.78     13900015.31
      1893651.42     13899947.84      1893672.54     13899930.46
      1893694.99     13899924.98      1893819.06     13899922.73
      1893834.64     13899914.14      1893868.94     13899883.14
      1893890.22     13899875.52      1894064.54     13899873.88
      1894081.16     13899867.11      1894126.51     13899828.65
      1894143.20     13899825.12      1894175.00     13899825.00

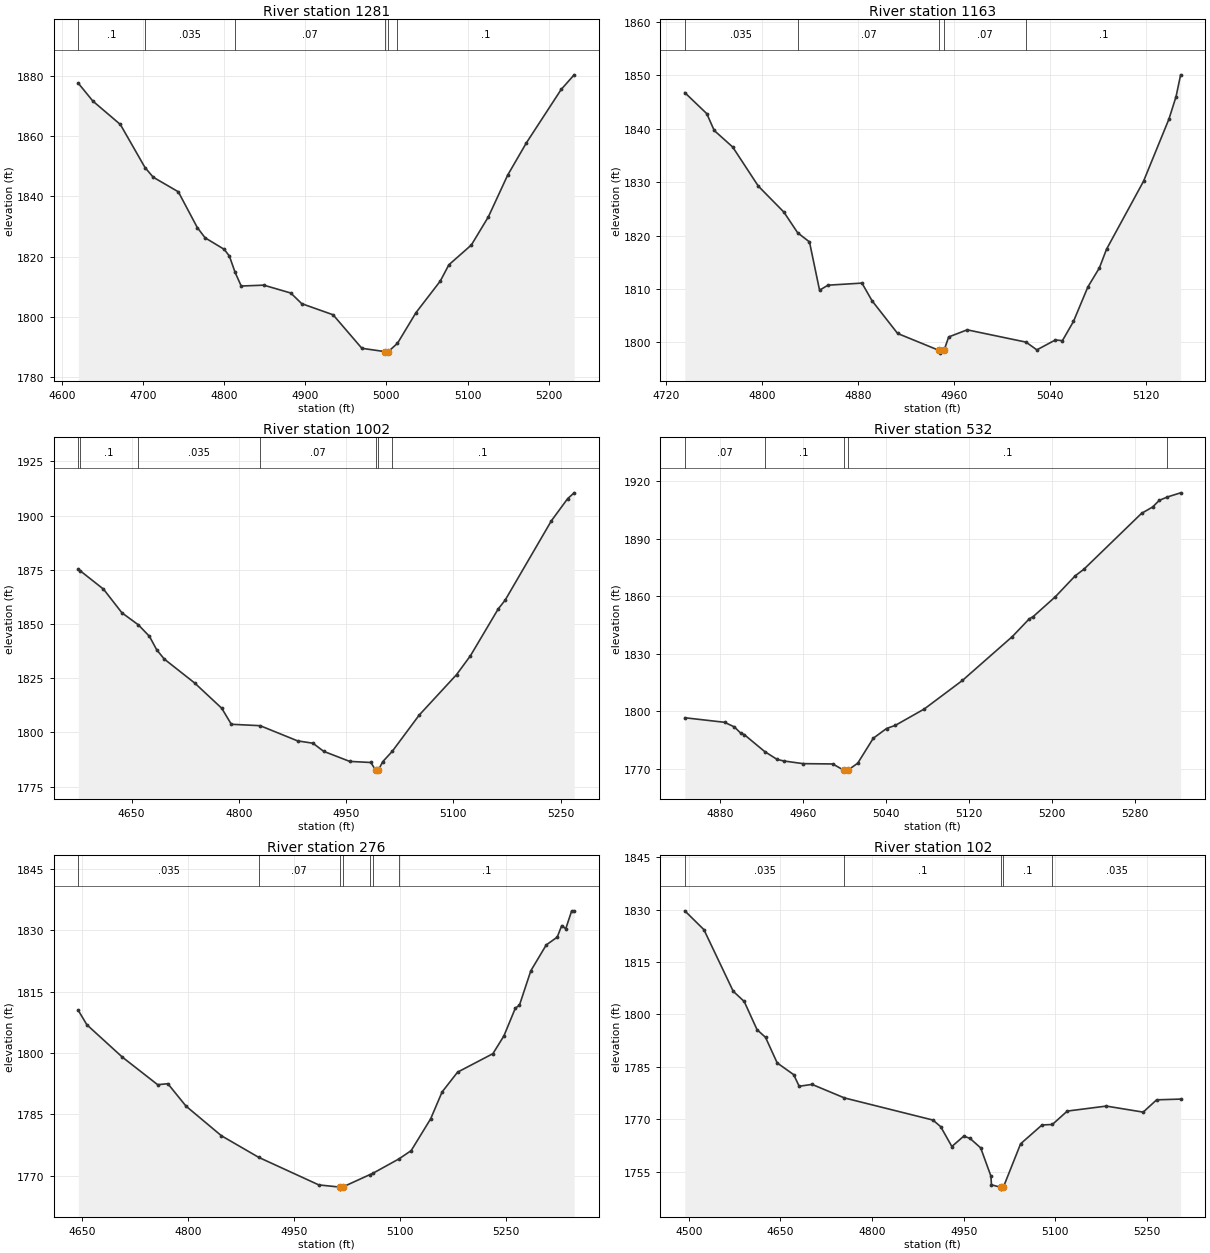
Type RM Length L Ch R = 1,1281,118,118,118
BEGIN DESCRIPTION:
Stream0595 3.0
END DESCRIPTION:
XS GIS Cut Line= 2
      1893335.35     13900598.43      1892945.01     13900128.38
#Sta/Elev= 30
  4620.4 1877.45  4638.3 1871.54  4672.2 1863.77  4702.6 1849.48  4712.7 1846.29
  4743.6 1841.46  4767.0 1829.60  4776.6 1826.20  4800.1 1822.39  4806.5 1820.17
  4813.6 1814.74  4821.1 1810.21  4848.9 1810.50  4882.2 1807.89  4895.7 1804.36
  4934.3 1800.68  4969.8 1789.56  4998.3 1788.46  4998.6 1787.96  5002.3 1788.46
  5013.7 1791.22  5036.5 1801.39  5066.4 1811.85  5077.0 1817.25  5104.7 1823.81
  5125.7 1833.16  5149.4 1846.95  5172.5 1857.67  5215.4 1875.39  5231.4 1880.24
#Mann=6,-1,0
  4620.4     0.1       0  4702.6   0.035       0  4813.6    0.07       0
  4998.3    0.05       0  5002.3    0.07       0  5013.7     0.1       0
Bank Sta=4998.3,5002.3
Exp/Cntr=0.3,0.1

Type RM Length L Ch R = 1,1163,161,161,161
BEGIN DESCRIPTION:
Stream0595 D
END DESCRIPTION:
XS GIS Cut Line= 2
      1893333.06     13900480.57      1893116.61     13900129.07
#Sta/Elev= 30
  4735.8 1846.78  4754.1 1842.84  4760.3 1839.69  4775.7 1836.59  4797.0 1829.28
  4818.3 1824.41  4829.8 1820.53  4839.6 1818.83  4848.0 1809.79  4855.0 1810.73
  4883.3 1811.12  4891.7 1807.81  4913.0 1801.69  4947.6 1798.51  4947.9 1798.01
  4951.6 1798.51  4955.5 1801.04  4970.9 1802.37  5019.9 1800.07  5028.9 1798.62
  5044.3 1800.47  5050.2 1800.35  5059.4 1803.95  5071.4 1810.41  5081.0 1813.98
  5086.9 1817.46  5117.7 1830.18  5138.9 1841.85  5144.8 1846.04  5148.6 1850.11
#Mann=5,-1,0
  4735.8   0.035       0  4829.8    0.07       0  4947.6    0.05       0
  4951.6    0.07       0  5019.9     0.1       0
Bank Sta=4947.6,4951.6
Exp/Cntr=0.3,0.1

Type RM Length L Ch R = 1,1002,470,470,470
BEGIN DESCRIPTION:
Stream0595 2.0
END DESCRIPTION:
XS GIS Cut Line= 3
      1893624.99     13900474.99      1893325.00     13900175.00
      1893225.01     13899925.01
#Sta/Elev= 30
  4575.4 1875.19  4577.6 1874.67  4610.6 1866.09  4636.4 1855.17  4659.3 1849.64
  4674.9 1844.31  4685.1 1838.07  4695.7 1833.82  4738.2 1822.78  4776.0 1811.15
  4789.4 1803.76  4829.7 1803.11  4882.1 1796.10  4903.6 1795.02  4918.5 1791.29
  4954.9 1786.64  4984.6 1786.13  4991.1 1782.65  4991.3 1782.15  4995.1 1782.65
  5001.1 1786.48  5014.5 1791.29  5052.1 1807.98  5104.5 1826.70  5123.9 1835.41
  5162.7 1856.98  5172.3 1860.98  5237.0 1897.60  5259.8 1907.84  5268.9 1910.52
#Mann=7,-1,0
  4575.4    0.07       0  4577.6     0.1       0  4659.3   0.035       0
  4829.7    0.07       0  4991.1    0.05       0  4995.1    0.07       0
  5014.5     0.1       0
Bank Sta=4991.1,4995.1
Exp/Cntr=0.3,0.1

Type RM Length L Ch R = 1,532,256,256,256
BEGIN DESCRIPTION:
Stream0595 1.0
END DESCRIPTION:
XS GIS Cut Line= 3
      1893725.01     13900075.04      1893675.00     13899925.00
      1893425.01     13899725.01
#Sta/Elev= 30
  4845.7 1796.70  4884.0 1794.33  4893.5 1791.92  4899.7 1788.65  4903.0 1787.93
  4922.8 1779.05  4934.6 1775.02  4941.0 1774.17  4959.9 1772.76  4988.4 1772.60
  4999.0 1769.36  4999.3 1768.86  5003.0 1769.36  5012.5 1772.98  5027.5 1786.00
  5040.3 1791.09  5048.8 1792.73  5076.7 1801.26  5113.5 1816.15  5161.7 1839.06
  5178.0 1848.28  5181.8 1849.47  5203.1 1859.77  5222.3 1870.71  5230.8 1874.21
  5286.3 1903.29  5297.0 1906.62  5303.4 1910.07  5311.3 1911.85  5324.0 1914.00
#Mann=5,-1,0
  4845.7    0.07       0  4922.8     0.1       0  4999.0    0.05       0
  5003.0     0.1       0  5311.3   0.035       0
Bank Sta=4999,5003
Exp/Cntr=0.3,0.1

Type RM Length L Ch R = 1,276,174,174,174
BEGIN DESCRIPTION:
Stream0595 H
END DESCRIPTION:
XS GIS Cut Line= 4
      1893947.64     13900227.11      1893928.55     13899912.87
      1893897.30     13899819.12      1893643.86     13899681.99
#Sta/Elev= 30
  4644.8 1810.38  4656.9 1806.88  4707.0 1798.99  4757.1 1792.23  4771.5 1792.48
  4797.2 1787.00  4847.3 1779.76  4900.2 1774.47  4985.2 1767.74  5014.8 1767.21
  5015.1 1766.71  5018.8 1767.21  5057.0 1770.22  5061.3 1770.54  5098.6 1774.10
  5115.9 1776.12  5143.5 1783.90  5159.7 1790.47  5181.6 1795.30  5231.6 1799.82
  5247.2 1804.17  5263.4 1810.96  5269.1 1811.64  5285.3 1820.09  5307.1 1826.40
  5322.6 1828.29  5329.0 1831.12  5334.7 1830.34  5343.1 1834.73  5346.6 1834.73
#Mann=7,-1,0
  4644.8   0.035       0  4900.2    0.07       0  5014.8    0.05       0
  5018.8    0.07       0  5057.0   0.035       0  5061.3    0.07       0
  5098.6     0.1       0
Bank Sta=5014.8,5018.8
Exp/Cntr=0.3,0.1

Type RM Length L Ch R = 1,102,0,0,0
BEGIN DESCRIPTION:
Stream0595 0.0
END DESCRIPTION:
XS GIS Cut Line= 3
      1894132.35     13900357.95      1894131.81     13899944.45
      1893935.88     13899597.56
#Sta/Elev= 30
  4493.4 1829.65  4524.7 1824.26  4572.7 1806.63  4590.7 1803.70  4611.7 1795.63
  4625.6 1793.43  4644.7 1786.11  4671.7 1782.76  4680.7 1779.43  4701.7 1779.97
  4754.9 1776.09  4899.7 1769.76  4912.4 1767.87  4930.7 1762.19  4950.3 1765.17
  4960.6 1764.49  4977.9 1761.79  4994.6 1753.75  4995.6 1751.24  5010.9 1750.49
  5011.1 1749.99  5014.9 1750.49  5043.3 1762.97  5078.3 1768.35  5095.3 1768.50
  5119.7 1772.33  5183.6 1773.76  5244.0 1772.03  5266.0 1775.55  5305.3 1775.76
#Mann=5,-1,0
  4493.4   0.035       0  4754.9     0.1       0  5010.9    0.05       0
  5014.9     0.1       0  5095.3   0.035       0
Bank Sta=5010.9,5014.9
Exp/Cntr=0.3,0.1

Chan Stop Cuts=-1