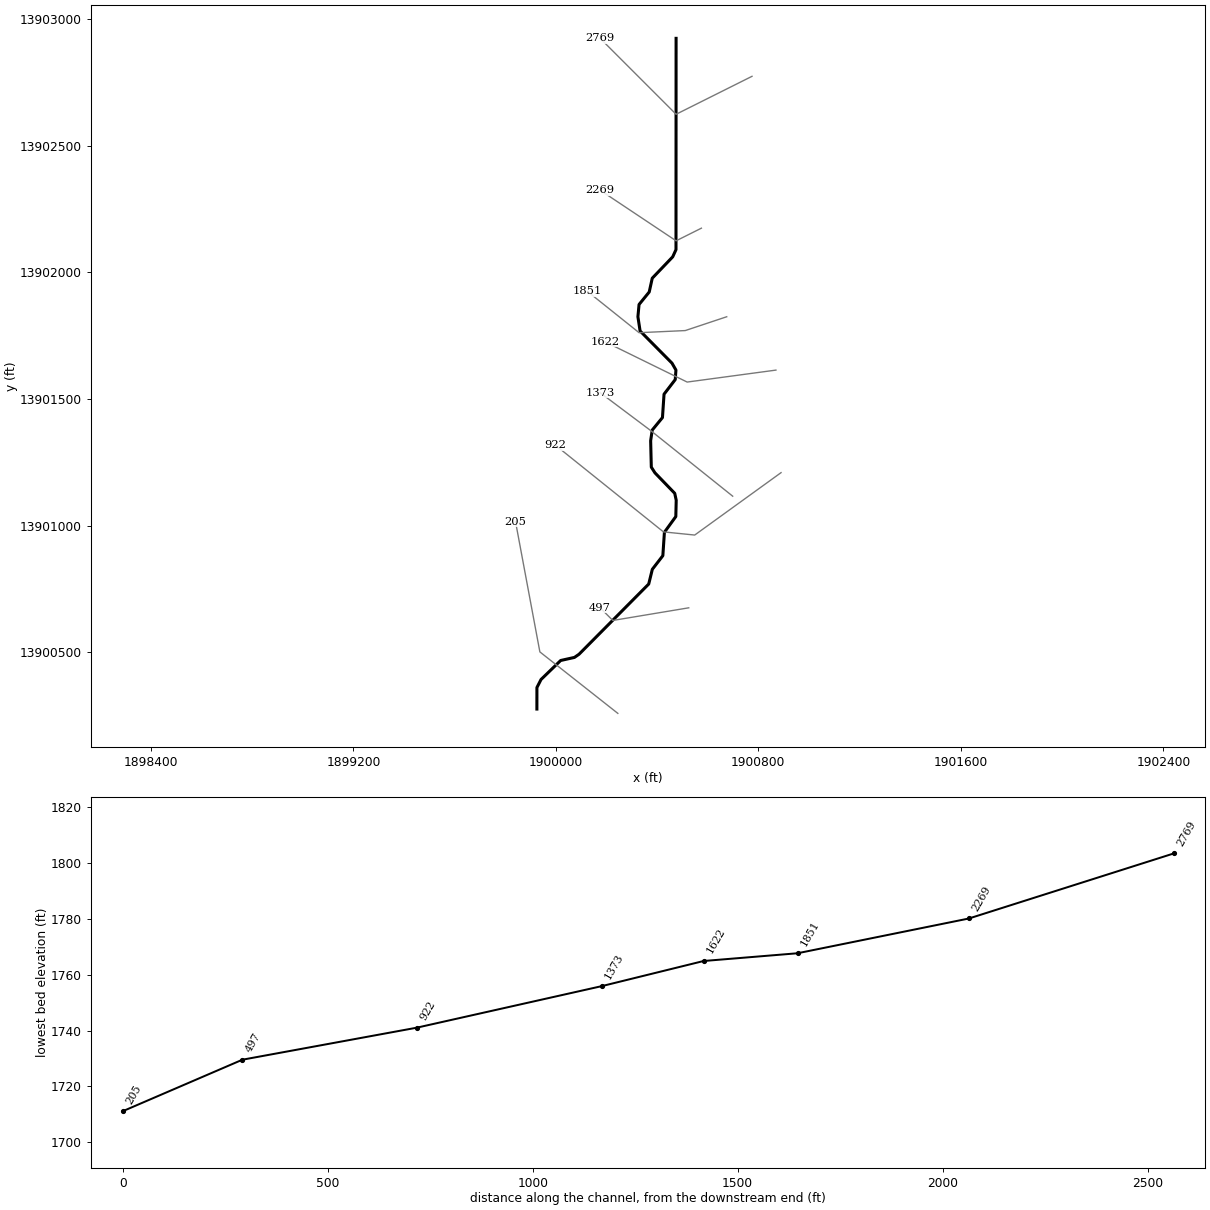
--- Stream0597.prj (project) ---

Proj Title=Stream0597 Base Level Engineering
Current Plan=p01
Default Exp/Contr=0.3,0.1
English Units
Geom File=g01
Flow File=f01
Plan File=p01
BEGIN DESCRIPTION:
Stream0597
END DESCRIPTION:

--- Stream0597.p01 (plan) ---

Plan Title=Multiple Run
Short Identifier=Multiple
Geom File=g01
Flow File=f01
Subcritical Flow
K Sum by GR= 0
Std Step Tol= 0.01
Critical Tol= 0.01
Num of Std Step Trials= 20
Max Error Tol= 0.3
Flow Tol Ratio= 0.001
Split Flow NTrial= 30
Split Flow Tol= 0.02
Split Flow Ratio= 0.02
Log Output Level= 0
Friction Slope Method= 1
Unsteady Friction Slope Method= 2
Unsteady Bridges Friction Slope Method= 1
Parabolic Critical Depth
Global Vel Dist=  1 , 1 , 1
Global Log Level= 0
CheckData=True
Encroach Param= -1, 0, 0, 0
BEGIN DESCRIPTION:
Multiple Run
END DESCRIPTION:

--- Stream0597.f01 (steady flow) ---

Flow Title=Multiple
Number of Profiles=7
Profile Names=10-year,25-year,50-year,1pct_min,100-year,1pct_plu,500-year
River Rch & RM= Stream0597,Reach-1,2769
     494     806    1092     720    1436    2865    2441
Boundary for River Rch & Prof#=Stream0597,Reach-1,1
Up Type=0
Dn Type=3
Dn Slope=0.005
Boundary for River Rch & Prof#=Stream0597,Reach-1,2
Up Type=0
Dn Type=3
Dn Slope=0.005
Boundary for River Rch & Prof#=Stream0597,Reach-1,3
Up Type=0
Dn Type=3
Dn Slope=0.005
Boundary for River Rch & Prof#=Stream0597,Reach-1,4
Up Type=0
Dn Type=3
Dn Slope=0.005
Boundary for River Rch & Prof#=Stream0597,Reach-1,5
Up Type=0
Dn Type=3
Dn Slope=0.005
Boundary for River Rch & Prof#=Stream0597,Reach-1,6
Up Type=0
Dn Type=3
Dn Slope=0.005
Boundary for River Rch & Prof#=Stream0597,Reach-1,7
Up Type=0
Dn Type=3
Dn Slope=0.005

--- Stream0597.g01 (geometry) ---

Geom Title=Existing Conditions

River Reach=Stream0597,Reach-1
Reach XY= 30
      1900475.00     13902925.00      1900474.61     13902090.16
      1900461.60     13902061.69      1900380.85     13901977.29
      1900368.85     13901922.83      1900328.67     13901873.41
      1900324.15     13901824.99      1900332.76     13901768.83
      1900458.78     13901641.68      1900474.40     13901614.38
      1900471.66     13901576.75      1900427.38     13901519.03
      1900421.14     13901426.60      1900380.74     13901377.33
      1900374.50     13901335.17      1900377.06     13901230.86
      1900391.46     13901208.25      1900469.59     13901127.42
      1900475.49     13901100.04      1900473.90     13901035.55
      1900428.86     13900973.40      1900422.67     13900880.97
      1900381.14     13900827.17      1900366.86     13900768.94
      1900091.67     13900491.65      1900073.35     13900478.98
      1900018.93     13900466.85      1899941.42     13900391.80
      1899925.11     13900359.96      1899925.00     13900275.00

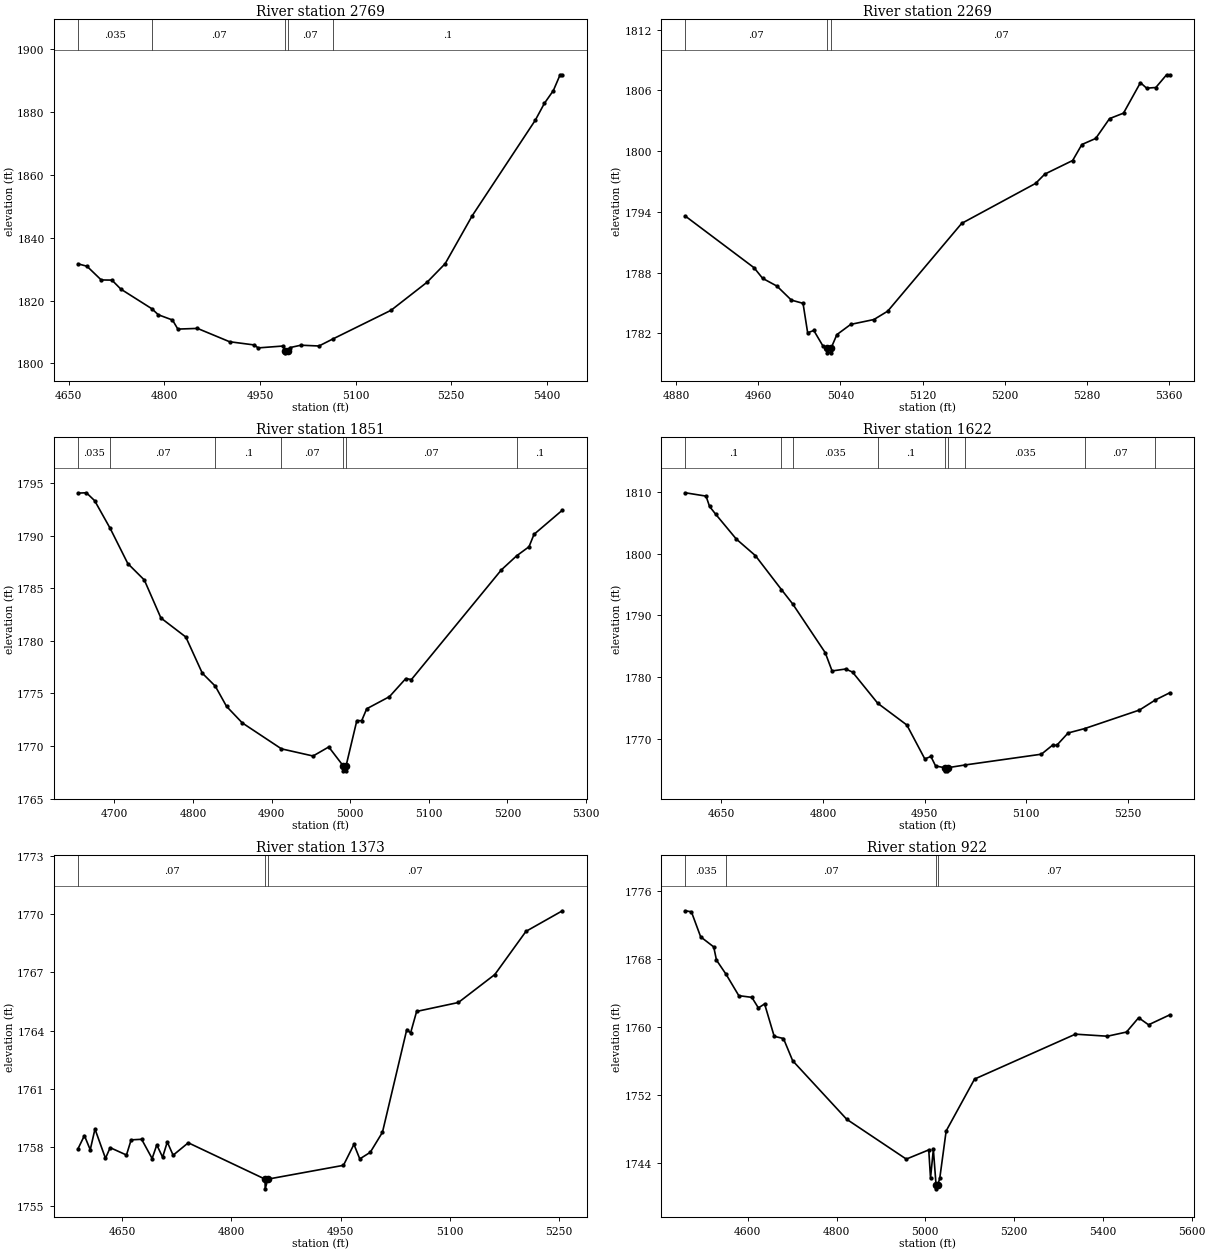
Type RM Length L Ch R = 1,2769,500,500,500
BEGIN DESCRIPTION:
Stream0597 6.0
END DESCRIPTION:
XS GIS Cut Line= 3
      1900775.00     13902775.00      1900475.00     13902625.00
      1900174.98     13902925.02
#Sta/Elev= 30
  4664.6 1831.71  4678.6 1830.94  4700.9 1826.58  4717.7 1826.53  4731.7 1823.66
  4780.4 1817.40  4790.4 1815.50  4812.7 1813.82  4821.1 1810.93  4851.9 1811.15
  4902.2 1806.91  4941.3 1805.87  4946.9 1804.94  4986.0 1805.54  4989.6 1803.87
  4989.9 1803.37  4993.6 1803.87  4997.2 1805.05  5014.1 1805.80  5042.4 1805.55
  5063.9 1807.75  5155.6 1816.93  5212.1 1825.87  5240.4 1831.76  5282.8 1847.01
  5381.8 1877.45  5396.0 1882.80  5410.1 1886.88  5420.7 1891.91  5424.3 1891.91
#Mann=5,-1,0
  4664.6   0.035       0  4780.4    0.07       0  4989.6    0.05       0
  4993.6    0.07       0  5063.9     0.1       0
Bank Sta=4989.6,4993.6
Exp/Cntr=0.3,0.1

Type RM Length L Ch R = 1,2269,418,418,418
BEGIN DESCRIPTION:
Stream0597 5.0
END DESCRIPTION:
XS GIS Cut Line= 3
      1900574.97     13902174.98      1900475.00     13902125.00
      1900175.02     13902324.99
#Sta/Elev= 30
  4888.7 1793.59  4955.7 1788.49  4964.1 1787.44  4978.1 1786.67  4992.1 1785.29
  5003.5 1784.97  5008.0 1782.06  5014.0 1782.29  5023.0 1780.74  5027.0 1780.58
  5027.3 1780.08  5030.8 1780.08  5031.0 1780.58  5036.5 1781.88  5050.0 1782.89
  5072.6 1783.37  5086.1 1784.20  5158.2 1792.87  5230.3 1796.82  5239.3 1797.74
  5266.4 1799.08  5275.4 1800.66  5288.9 1801.26  5302.4 1803.22  5316.0 1803.76
  5332.5 1806.77  5338.5 1806.23  5347.5 1806.29  5358.0 1807.55  5361.0 1807.55
#Mann=3,-1,0
  4888.7    0.07       0  5027.0    0.05       0  5031.0    0.07       0
Bank Sta=5027,5031
Exp/Cntr=0.3,0.1

Type RM Length L Ch R = 1,1851,229,229,229
BEGIN DESCRIPTION:
Stream0597 4.0
END DESCRIPTION:
XS GIS Cut Line= 4
      1900675.02     13901825.01      1900511.17     13901770.39
      1900328.78     13901761.97      1900124.97     13901925.02
#Sta/Elev= 30
  4653.7 1794.04  4664.3 1794.07  4674.8 1793.32  4694.6 1790.68  4717.0 1787.34
  4738.0 1785.78  4759.1 1782.17  4790.8 1780.36  4811.8 1776.92  4828.3 1775.69
  4842.6 1773.77  4862.6 1772.20  4912.5 1769.73  4952.7 1769.05  4972.7 1769.91
  4990.8 1768.14  4991.0 1767.64  4994.5 1767.64  4994.8 1768.14  5008.4 1772.41
  5014.6 1772.41  5021.0 1773.54  5049.9 1774.69  5070.7 1776.41  5077.9 1776.32
  5192.3 1786.74  5211.8 1788.08  5227.5 1788.94  5233.9 1790.12  5270.0 1792.42
#Mann=7,-1,0
  4653.7   0.035       0  4694.6    0.07       0  4828.3     0.1       0
  4912.5    0.07       0  4990.8    0.05       0  4994.8    0.07       0
  5211.8     0.1       0
Bank Sta=4990.8,4994.8
Exp/Cntr=0.3,0.1

Type RM Length L Ch R = 1,1622,249,249,249
BEGIN DESCRIPTION:
Mapping XS 4a159f7a
END DESCRIPTION:
XS GIS Cut Line= 3
      1900869.52     13901614.21      1900518.69     13901566.95
      1900195.02     13901725.70
#Sta/Elev= 30
  4597.0 1809.82  4627.6 1809.28  4632.7 1807.62  4641.9 1806.34  4672.2 1802.34
  4700.4 1799.66  4738.8 1794.17  4755.4 1791.85  4803.4 1783.97  4813.5 1781.02
  4833.6 1781.33  4843.7 1780.83  4880.9 1775.79  4923.8 1772.28  4950.3 1766.80
  4959.3 1767.19  4966.2 1765.66  4979.8 1765.37  4980.0 1764.87  4983.5 1764.87
  4983.8 1765.37  5009.8 1765.82  5122.3 1767.56  5139.2 1769.06  5144.8 1768.98
  5161.7 1770.99  5186.1 1771.70  5267.0 1774.70  5290.6 1776.34  5311.5 1777.48
#Mann=9,-1,0
  4597.0     0.1       0  4738.8    0.07       0  4755.4   0.035       0
  4880.9     0.1       0  4979.8    0.05       0  4983.8     0.1       0
  5009.8   0.035       0  5186.1    0.07       0  5290.6   0.035       0
Bank Sta=4979.8,4983.8
Exp/Cntr=0.3,0.1

Type RM Length L Ch R = 1,1373,451,451,451
BEGIN DESCRIPTION:
Stream0597 3.0
END DESCRIPTION:
XS GIS Cut Line= 3
      1900698.64     13901115.99      1900375.00     13901375.00
      1900175.02     13901524.99
#Sta/Elev= 30
  4589.8 1757.93  4598.5 1758.60  4606.5 1757.87  4613.0 1758.94  4627.4 1757.43
  4633.8 1757.98  4656.2 1757.60  4662.6 1758.38  4677.0 1758.41  4691.4 1757.42
  4697.8 1758.12  4705.8 1757.49  4712.2 1758.27  4720.2 1757.59  4741.0 1758.23
  4846.3 1756.36  4846.5 1755.86  4850.3 1756.36  4953.9 1757.07  4968.3 1758.15
  4976.3 1757.40  4990.7 1757.74  5007.4 1758.77  5040.8 1764.06  5046.0 1763.88
  5054.3 1764.99  5111.6 1765.45  5161.6 1766.89  5204.3 1769.11  5254.3 1770.17
#Mann=3,-1,0
  4589.8    0.07       0  4846.3    0.05       0  4850.3    0.07       0
Bank Sta=4846.3,4850.3
Exp/Cntr=0.3,0.1

Type RM Length L Ch R = 1,922,425,425,425
BEGIN DESCRIPTION:
Stream0597 2.0
END DESCRIPTION:
XS GIS Cut Line= 4
      1900889.74     13901209.06      1900548.52     13900962.46
      1900425.00     13900975.00      1899999.22     13901316.71
#Sta/Elev= 30
  4459.3 1773.63  4473.0 1773.51  4493.9 1770.57  4523.3 1769.39  4529.5 1767.84
  4551.2 1766.17  4579.8 1763.67  4609.2 1763.47  4623.9 1762.23  4637.9 1762.70
  4659.5 1758.90  4680.4 1758.64  4701.2 1756.03  4823.0 1749.16  4957.1 1744.49
  5007.7 1745.57  5011.7 1742.27  5018.1 1745.63  5024.1 1741.50  5024.3 1741.00
  5028.1 1741.50  5032.5 1742.23  5046.9 1747.79  5110.9 1753.88  5338.1 1759.15
  5410.1 1758.91  5453.2 1759.40  5480.5 1761.08  5502.9 1760.25  5550.4 1761.41
#Mann=4,-1,0
  4459.3   0.035       0  4551.2    0.07       0  5024.1    0.05       0
  5028.1    0.07       0
Bank Sta=5024.1,5028.1
Exp/Cntr=0.3,0.1

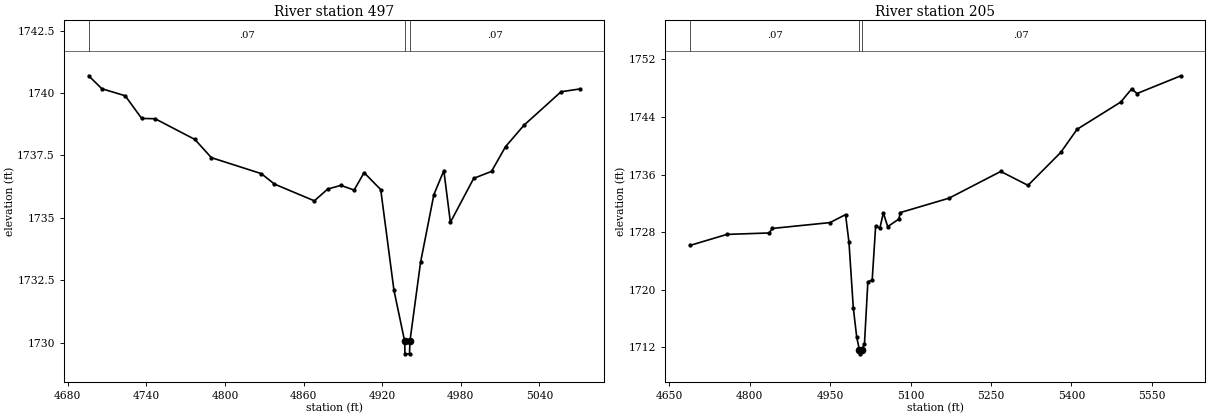
Type RM Length L Ch R = 1,497,292,292,292
BEGIN DESCRIPTION:
Stream0597 1.0
END DESCRIPTION:
XS GIS Cut Line= 3
      1900524.97     13900675.00      1900225.00     13900625.00
      1900175.02     13900674.98
#Sta/Elev= 30
  4695.9 1740.69  4706.0 1740.17  4723.8 1739.89  4736.4 1738.98  4746.6 1738.97
  4777.0 1738.14  4789.6 1737.41  4827.7 1736.77  4837.8 1736.35  4868.2 1735.68
  4878.4 1736.15  4888.5 1736.30  4898.6 1736.11  4906.2 1736.81  4918.9 1736.13
  4929.0 1732.10  4937.2 1730.05  4937.4 1729.55  4940.9 1729.55  4941.2 1730.05
  4949.3 1733.21  4959.5 1735.93  4967.1 1736.89  4972.1 1734.82  4989.9 1736.58
  5003.5 1736.86  5014.2 1737.85  5028.3 1738.71  5056.6 1740.05  5070.7 1740.16
#Mann=3,-1,0
  4695.9    0.07       0  4937.2    0.05       0  4941.2    0.07       0
Bank Sta=4937.2,4941.2
Exp/Cntr=0.3,0.1

Type RM Length L Ch R = 1,205,0,0,0
BEGIN DESCRIPTION:
Stream0597 0.0
END DESCRIPTION:
XS GIS Cut Line= 3
      1900244.83     13900257.90      1899936.78     13900500.80
      1899840.59     13901015.30
#Sta/Elev= 30
  4688.5 1726.16  4757.4 1727.69  4836.0 1727.89  4842.4 1728.52  4949.8 1729.33
  4978.7 1730.44  4985.1 1726.57  4993.1 1717.52  4999.5 1713.43  5004.7 1711.61
  5004.9 1711.11  5008.7 1711.61  5014.0 1712.53  5020.3 1721.10  5028.4 1721.36
  5034.8 1728.85  5042.8 1728.58  5049.2 1730.68  5057.3 1728.77  5078.1 1729.82
  5080.8 1730.72  5171.8 1732.72  5268.2 1736.43  5319.0 1734.50  5380.1 1739.07
  5410.6 1742.28  5492.0 1746.06  5512.3 1747.88  5522.5 1747.25  5604.2 1749.71
#Mann=3,-1,0
  4688.5    0.07       0  5004.7    0.05       0  5008.7    0.07       0
Bank Sta=5004.7,5008.7
Exp/Cntr=0.3,0.1

Chan Stop Cuts=-1