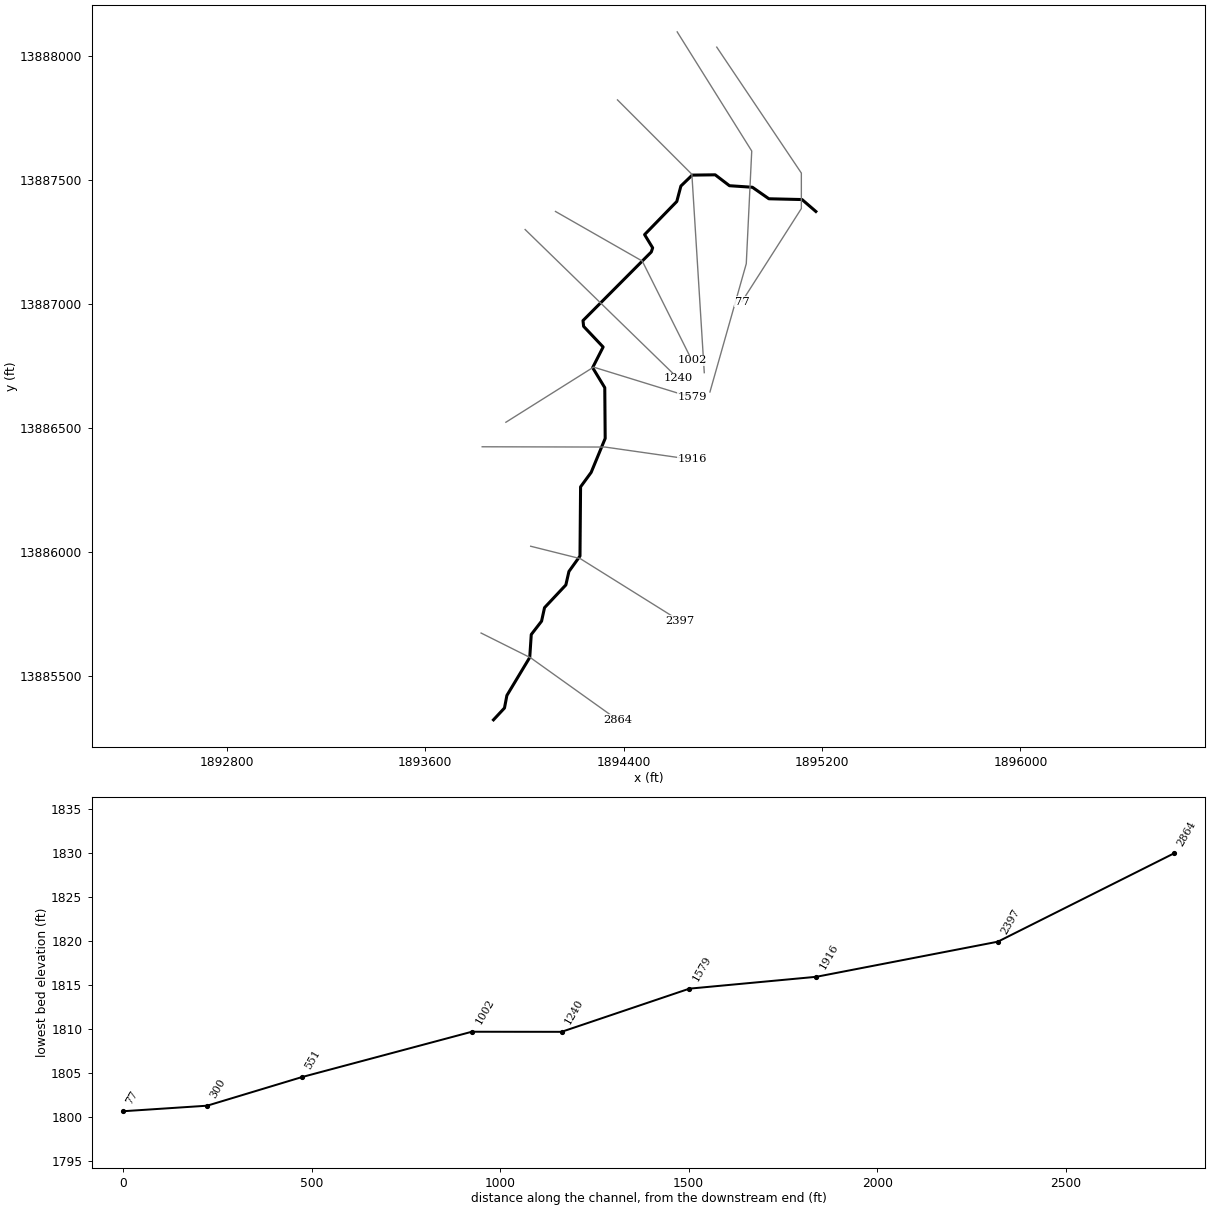
--- Stream0599.prj (project) ---

Proj Title=Stream0599 Base Level Engineering
Current Plan=p01
Default Exp/Contr=0.3,0.1
English Units
Geom File=g01
Flow File=f01
Plan File=p01
BEGIN DESCRIPTION:
Stream0599
END DESCRIPTION:

--- Stream0599.p01 (plan) ---

Plan Title=Multiple Run
Short Identifier=Multiple
Geom File=g01
Flow File=f01
Subcritical Flow
K Sum by GR= 0
Std Step Tol= 0.01
Critical Tol= 0.01
Num of Std Step Trials= 20
Max Error Tol= 0.3
Flow Tol Ratio= 0.001
Split Flow NTrial= 30
Split Flow Tol= 0.02
Split Flow Ratio= 0.02
Log Output Level= 0
Friction Slope Method= 1
Unsteady Friction Slope Method= 2
Unsteady Bridges Friction Slope Method= 1
Parabolic Critical Depth
Global Vel Dist=  1 , 1 , 1
Global Log Level= 0
CheckData=True
Encroach Param= -1, 0, 0, 0
BEGIN DESCRIPTION:
Multiple Run
END DESCRIPTION:

--- Stream0599.f01 (steady flow) ---

Flow Title=Multiple
Number of Profiles=7
Profile Names=10-year,25-year,50-year,1pct_min,100-year,1pct_plu,500-year
River Rch & RM= Stream0599,Reach-1,2864
    2639    4718    6789    4713    9404   18763   17832
Boundary for River Rch & Prof#=Stream0599,Reach-1,1
Up Type=0
Dn Type=3
Dn Slope=0.005
Boundary for River Rch & Prof#=Stream0599,Reach-1,2
Up Type=0
Dn Type=3
Dn Slope=0.005
Boundary for River Rch & Prof#=Stream0599,Reach-1,3
Up Type=0
Dn Type=3
Dn Slope=0.005
Boundary for River Rch & Prof#=Stream0599,Reach-1,4
Up Type=0
Dn Type=3
Dn Slope=0.005
Boundary for River Rch & Prof#=Stream0599,Reach-1,5
Up Type=0
Dn Type=3
Dn Slope=0.005
Boundary for River Rch & Prof#=Stream0599,Reach-1,6
Up Type=0
Dn Type=3
Dn Slope=0.005
Boundary for River Rch & Prof#=Stream0599,Reach-1,7
Up Type=0
Dn Type=3
Dn Slope=0.005

--- Stream0599.g01 (geometry) ---

Geom Title=Existing Conditions

River Reach=Stream0599,Reach-1
Reach XY= 30
      1893875.00     13885325.00      1893919.33     13885372.64
      1893929.04     13885423.33      1894021.17     13885576.58
      1894027.33     13885669.03      1894068.86     13885722.83
      1894080.84     13885777.29      1894166.84     13885868.95
      1894179.22     13885923.25      1894223.80     13885985.50
      1894226.20     13886264.50      1894268.88     13886322.82
      1894325.44     13886459.82      1894323.76     13886664.50
      1894274.79     13886745.21      1894317.15     13886828.41
      1894238.46     13886911.67      1894235.96     13886935.00
      1894511.35     13887211.67      1894516.84     13887228.33
      1894484.30     13887281.67      1894614.21     13887415.34
      1894630.74     13887477.58      1894676.28     13887521.63
      1894769.02     13887522.84      1894826.60     13887478.86
      1894919.02     13887472.65      1894985.51     13887426.22
      1895119.21     13887423.09      1895175.00     13887375.00

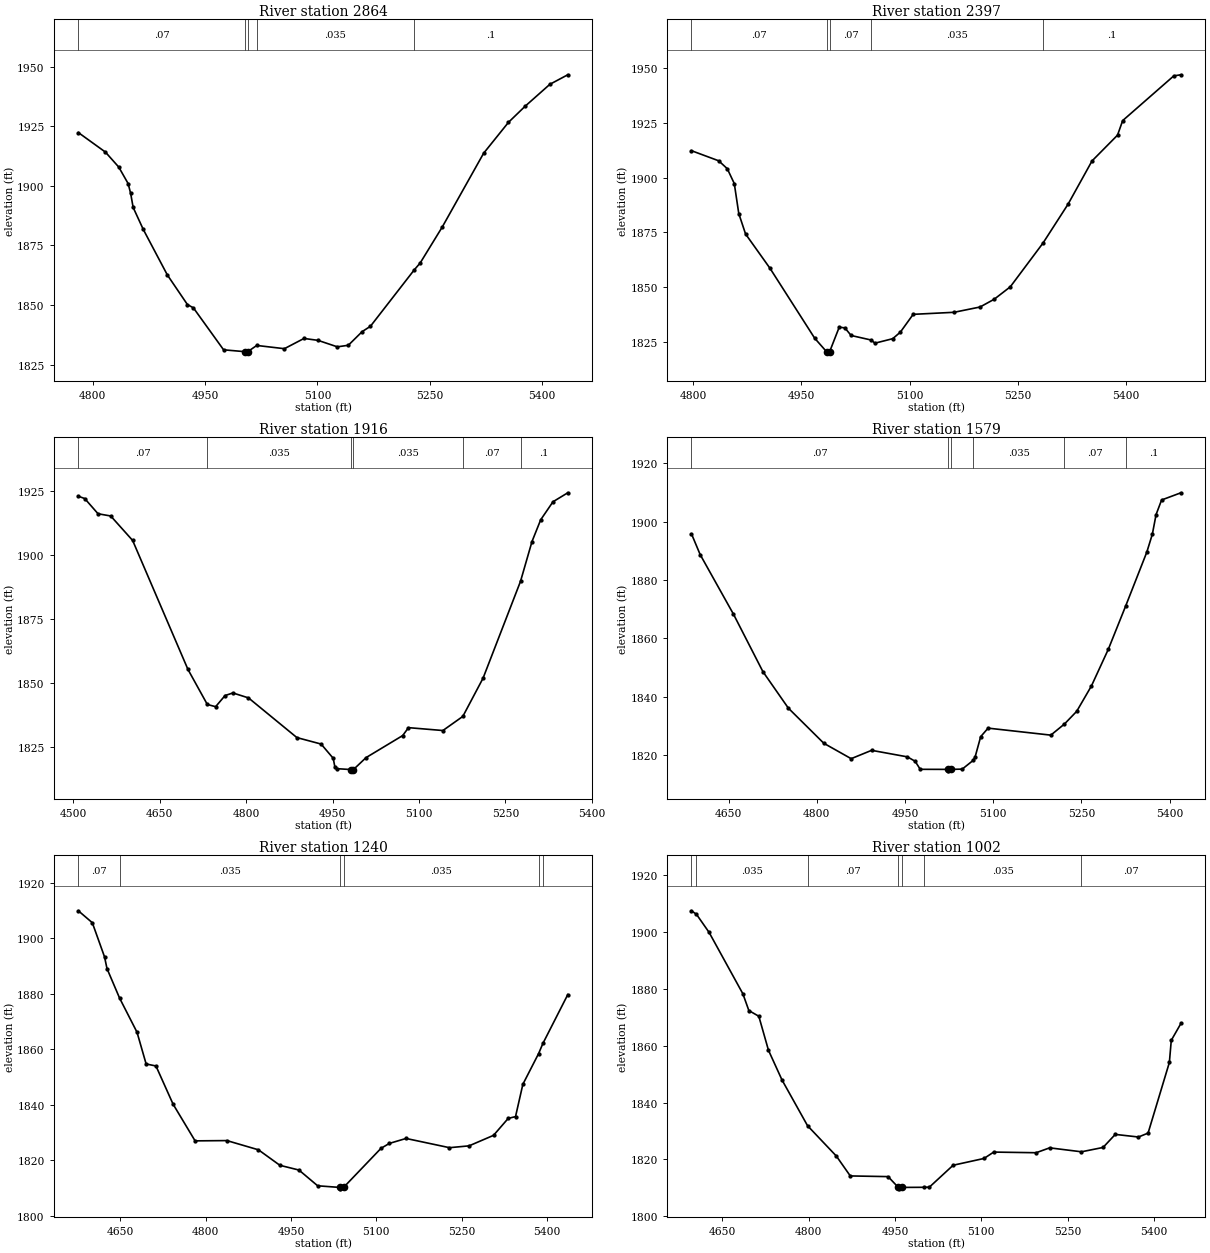
Type RM Length L Ch R = 1,2864,467,467,467
BEGIN DESCRIPTION:
Stream0599 6.0
END DESCRIPTION:
XS GIS Cut Line= 3
      1893825.03     13885674.98      1894025.00     13885575.00
      1894375.01     13885324.99
#Sta/Elev= 30
  4780.6 1922.39  4816.8 1914.19  4834.6 1907.90  4847.1 1900.98  4850.5 1896.84
  4853.8 1890.98  4867.3 1881.75  4899.5 1862.62  4926.3 1850.21  4934.3 1848.81
  4974.6 1831.21  5002.7 1830.44  5003.0 1829.94  5006.9 1830.44  5018.9 1833.04
  5055.8 1831.68  5082.0 1835.98  5100.7 1835.18  5126.5 1832.46  5141.2 1833.12
  5159.7 1838.85  5170.7 1841.08  5229.2 1864.75  5237.1 1867.62  5266.6 1882.73
  5321.9 1913.71  5355.1 1926.69  5377.2 1933.40  5410.4 1942.65  5434.3 1946.64
#Mann=5,-1,0
  4780.6    0.07       0  5002.7    0.05       0  5006.9    0.07       0
  5018.9   0.035       0  5229.2     0.1       0
Bank Sta=5002.7,5006.9
Exp/Cntr=0.3,0.1

Type RM Length L Ch R = 1,2397,481,481,481
BEGIN DESCRIPTION:
Stream0599 5.0
END DESCRIPTION:
XS GIS Cut Line= 3
      1894025.01     13886025.00      1894225.00     13885975.00
      1894624.96     13885725.02
#Sta/Elev= 30
  4798.0 1912.30  4835.7 1907.68  4847.6 1904.06  4857.3 1897.26  4863.5 1883.56
  4872.9 1874.22  4906.8 1858.51  4968.6 1826.59  4985.1 1820.40  4985.3 1819.90
  4989.3 1820.40  5002.6 1831.63  5010.4 1831.31  5019.1 1827.83  5047.0 1825.74
  5052.0 1824.31  5076.7 1826.37  5087.3 1829.38  5105.0 1837.50  5161.6 1838.43
  5197.6 1840.85  5217.2 1844.40  5239.5 1850.08  5284.8 1870.08  5319.5 1887.86
  5352.7 1907.63  5388.0 1919.41  5395.1 1926.05  5465.9 1946.50  5475.8 1947.00
#Mann=5,-1,0
  4798.0    0.07       0  4985.1    0.05       0  4989.3    0.07       0
  5047.0   0.035       0  5284.8     0.1       0
Bank Sta=4985.1,4989.3
Exp/Cntr=0.3,0.1

Type RM Length L Ch R = 1,1916,337,337,337
BEGIN DESCRIPTION:
Stream0599 4.0
END DESCRIPTION:
XS GIS Cut Line= 3
      1893829.38     13886426.11      1894325.00     13886425.00
      1894675.02     13886375.00
#Sta/Elev= 30
  4508.9 1922.86  4520.0 1921.95  4543.1 1916.03  4565.1 1915.16  4603.1 1905.64
  4699.1 1855.40  4732.7 1841.76  4747.1 1840.89  4763.5 1845.24  4777.1 1846.24
  4804.1 1844.32  4888.1 1828.86  4930.1 1826.34  4951.1 1820.80  4954.1 1817.31
  4957.1 1816.76  4981.9 1816.41  4982.2 1815.91  4986.2 1816.41  5008.1 1821.06
  5071.7 1829.66  5081.7 1832.73  5141.4 1831.61  5176.0 1837.11  5211.1 1852.00
  5276.1 1889.73  5296.0 1905.22  5311.1 1913.69  5332.4 1920.70  5358.1 1924.20
#Mann=6,-1,0
  4508.9    0.07       0  4732.7   0.035       0  4981.9   0.035       0
  4986.2   0.035       0  5176.0    0.07       0  5276.1     0.1       0
Bank Sta=4981.9,4986.2
Exp/Cntr=0.3,0.1

Type RM Length L Ch R = 1,1579,339,339,339
BEGIN DESCRIPTION:
Stream0599 3.0
END DESCRIPTION:
XS GIS Cut Line= 3
      1893925.03     13886525.02      1894278.56     13886747.34
      1894674.98     13886625.01
#Sta/Elev= 30
  4586.8 1895.81  4601.6 1888.69  4658.2 1868.28  4708.3 1848.57  4751.6 1836.05
  4811.9 1824.01  4858.4 1818.73  4893.2 1821.59  4954.1 1819.35  4967.2 1817.84
  4975.9 1815.08  5023.2 1815.06  5023.5 1814.56  5027.5 1815.06  5047.3 1815.15
  5066.2 1818.19  5069.3 1819.38  5078.7 1826.28  5091.3 1829.20  5198.0 1826.80
  5221.2 1830.62  5242.0 1834.96  5267.1 1843.68  5295.8 1856.25  5325.4 1871.13
  5361.3 1889.57  5370.7 1895.72  5377.0 1902.41  5386.4 1907.42  5419.3 1909.89
#Mann=6,-1,0
  4586.8    0.07       0  5023.2    0.05       0  5027.5    0.07       0
  5066.2   0.035       0  5221.2    0.07       0  5325.4     0.1       0
Bank Sta=5023.2,5027.5
Exp/Cntr=0.3,0.1

Type RM Length L Ch R = 1,1240,238,238,238
BEGIN DESCRIPTION:
Mapping XS 51c59dc8
END DESCRIPTION:
XS GIS Cut Line= 2
      1894002.60     13887302.15      1894619.31     13886701.91
#Sta/Elev= 30
  4576.1 1909.98  4600.7 1905.67  4622.2 1893.33  4626.5 1889.13  4648.6 1878.49
  4679.3 1866.15  4695.3 1854.71  4712.6 1853.98  4742.7 1840.20  4781.4 1826.96
  4837.3 1827.06  4892.8 1823.73  4930.5 1818.14  4964.0 1816.43  4996.9 1810.75
  5036.5 1810.15  5037.0 1809.65  5042.4 1810.15  5108.3 1824.27  5123.0 1826.04
  5152.3 1827.83  5228.7 1824.50  5263.1 1825.16  5306.1 1828.95  5331.9 1835.06
  5344.8 1835.71  5357.7 1847.37  5385.4 1858.46  5392.9 1862.10  5436.7 1879.74
#Mann=6,-1,0
  4576.1    0.07       0  4648.6   0.035       0  5036.5   0.035       0
  5042.4   0.035       0  5385.4    0.07       0  5392.9     0.1       0
Bank Sta=5036.5,5042.4
Exp/Cntr=0.3,0.1

Type RM Length L Ch R = 1,1002,451,451,451
BEGIN DESCRIPTION:
Stream0599 2.0
END DESCRIPTION:
XS GIS Cut Line= 3
      1894124.97     13887375.02      1894475.00     13887175.00
      1894675.02     13886774.96
#Sta/Elev= 30
  4596.5 1907.47  4605.2 1906.22  4627.1 1899.87  4685.8 1878.27  4696.2 1872.37
  4713.5 1870.37  4730.3 1858.39  4753.8 1847.95  4798.2 1831.85  4848.2 1821.19
  4872.4 1814.20  4938.1 1813.96  4955.9 1810.16  4956.4 1809.66  4961.8 1810.16
  5000.0 1810.20  5009.8 1810.25  5051.1 1817.96  5104.8 1820.35  5121.6 1822.59
  5195.3 1822.36  5218.8 1824.08  5274.1 1822.69  5311.6 1824.22  5332.8 1828.81
  5373.1 1827.89  5389.8 1829.27  5426.8 1854.12  5430.1 1861.90  5446.9 1867.84
#Mann=7,-1,0
  4596.5    0.07       0  4605.2   0.035       0  4798.2    0.07       0
  4955.9   0.035       0  4961.8    0.07       0  5000.0   0.035       0
  5274.1    0.07       0
Bank Sta=4955.9,4961.8
Exp/Cntr=0.3,0.1

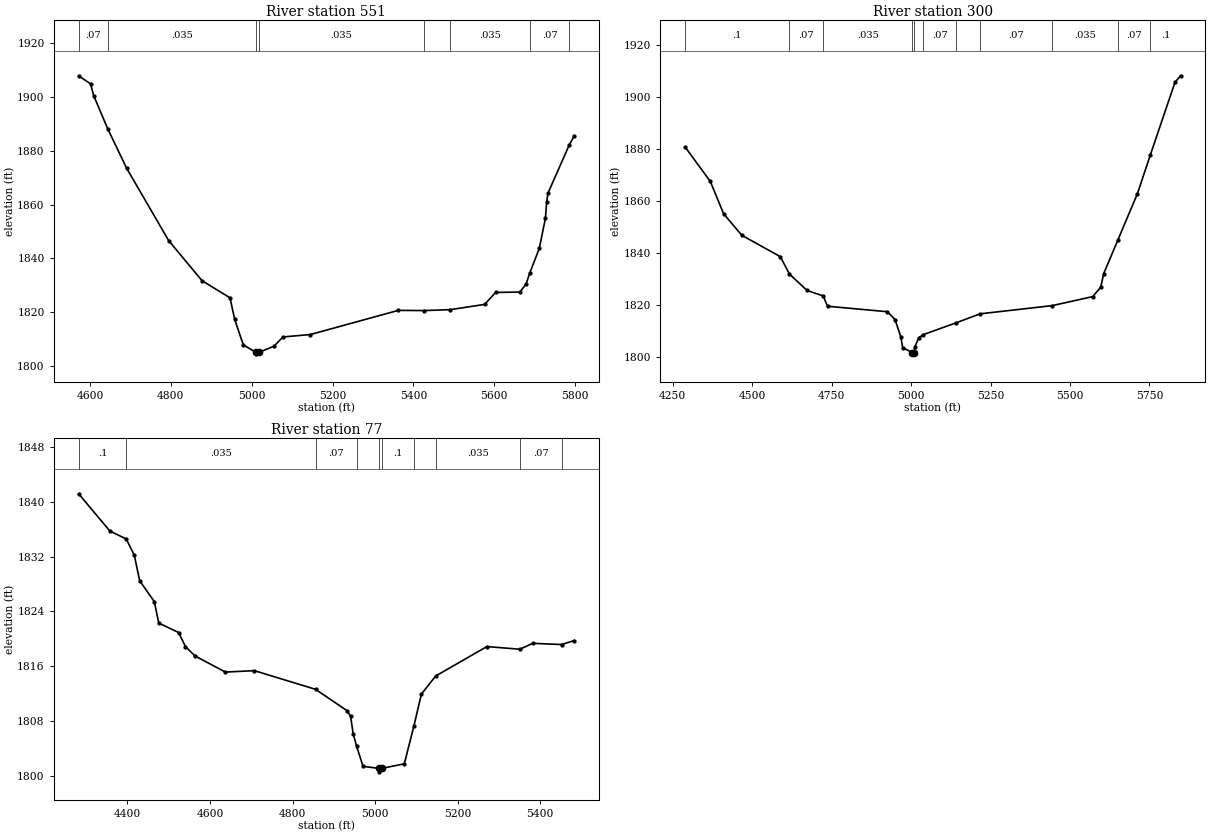
Type RM Length L Ch R = 1,551,251,251,251
BEGIN DESCRIPTION:
Stream0599 1.0
END DESCRIPTION:
XS GIS Cut Line= 3
      1894375.03     13887824.97      1894675.00     13887525.00
      1894725.00     13886724.98
#Sta/Elev= 30
  4571.9 1907.98  4601.6 1904.95  4609.0 1900.64  4644.2 1888.14  4690.7 1873.56
  4794.6 1846.65  4877.3 1831.70  4946.3 1825.36  4958.0 1817.30  4979.2 1807.82
  5011.1 1805.00  5011.6 1804.50  5017.3 1805.00  5055.4 1807.37  5077.3 1810.78
  5145.2 1811.69  5362.8 1820.68  5426.6 1820.60  5490.8 1820.94  5576.3 1822.90
  5603.3 1827.35  5663.4 1827.49  5678.5 1830.41  5687.5 1834.43  5711.5 1843.79
  5726.6 1854.98  5729.6 1860.88  5732.6 1864.20  5785.9 1882.37  5797.7 1885.54
#Mann=8,-1,0
  4571.9    0.07       0  4644.2   0.035       0  5011.1   0.035       0
  5017.3   0.035       0  5426.6    0.07       0  5490.8   0.035       0
  5687.5    0.07       0  5785.9     0.1       0
Bank Sta=5011.1,5017.3
Exp/Cntr=0.3,0.1

Type RM Length L Ch R = 1,300,223,223,223
BEGIN DESCRIPTION:
Stream0599 0.0
END DESCRIPTION:
XS GIS Cut Line= 4
      1894615.82     13888099.22      1894916.40     13887618.77
      1894894.39     13887164.44      1894747.88     13886647.08
#Sta/Elev= 30
  4288.7 1880.92  4368.0 1867.65  4409.8 1855.21  4467.1 1846.90  4588.3 1838.68
  4616.9 1832.00  4672.3 1825.66  4723.3 1823.55  4736.9 1819.58  4925.3 1817.47
  4949.3 1814.46  4967.3 1807.85  4973.4 1803.67  5003.2 1801.75  5003.7 1801.25
  5009.5 1801.75  5010.7 1803.71  5024.4 1807.49  5038.5 1808.66  5141.8 1813.21
  5217.0 1816.66  5443.6 1819.81  5571.6 1823.30  5596.6 1826.94  5605.9 1832.15
  5649.9 1844.91  5711.9 1862.91  5753.1 1878.01  5830.4 1905.90  5848.0 1908.33
#Mann=11,-1,0
  4288.7     0.1       0  4616.9    0.07       0  4723.3   0.035       0
  5003.2   0.035       0  5009.5   0.035       0  5038.5    0.07       0
  5141.8   0.035       0  5217.0    0.07       0  5443.6   0.035       0
  5649.9    0.07       0  5753.1     0.1       0
Bank Sta=5003.2,5009.5
Exp/Cntr=0.3,0.1

Type RM Length L Ch R = 1,77,0,0,0
BEGIN DESCRIPTION:
Stream0599 0.1
END DESCRIPTION:
XS GIS Cut Line= 4
      1894775.35     13888037.70      1895116.47     13887529.91
      1895116.47     13887386.68      1894876.87     13887011.65
#Sta/Elev= 30
  4282.0 1841.15  4357.6 1835.72  4397.1 1834.57  4416.8 1832.21  4429.8 1828.47
  4465.3 1825.43  4476.0 1822.31  4524.4 1820.92  4540.6 1818.88  4563.6 1817.52
  4637.4 1815.16  4707.4 1815.37  4855.6 1812.65  4931.7 1809.55  4940.7 1808.71
  4946.7 1806.20  4955.1 1804.36  4970.7 1801.42  5009.5 1801.12  5010.0 1800.62
  5015.8 1801.12  5070.7 1801.79  5094.0 1807.34  5112.0 1811.94  5146.6 1814.59
  5270.6 1818.88  5350.6 1818.49  5381.4 1819.35  5451.5 1819.18  5482.0 1819.75
#Mann=10,-1,0
  4282.0     0.1       0  4397.1   0.035       0  4855.6    0.07       0
  4955.1     0.1       0  5009.5    0.05       0  5015.8     0.1       0
  5094.0    0.07       0  5146.6   0.035       0  5350.6    0.07       0
  5451.5   0.035       0
Bank Sta=5009.5,5015.8
Exp/Cntr=0.3,0.1

Chan Stop Cuts=-1