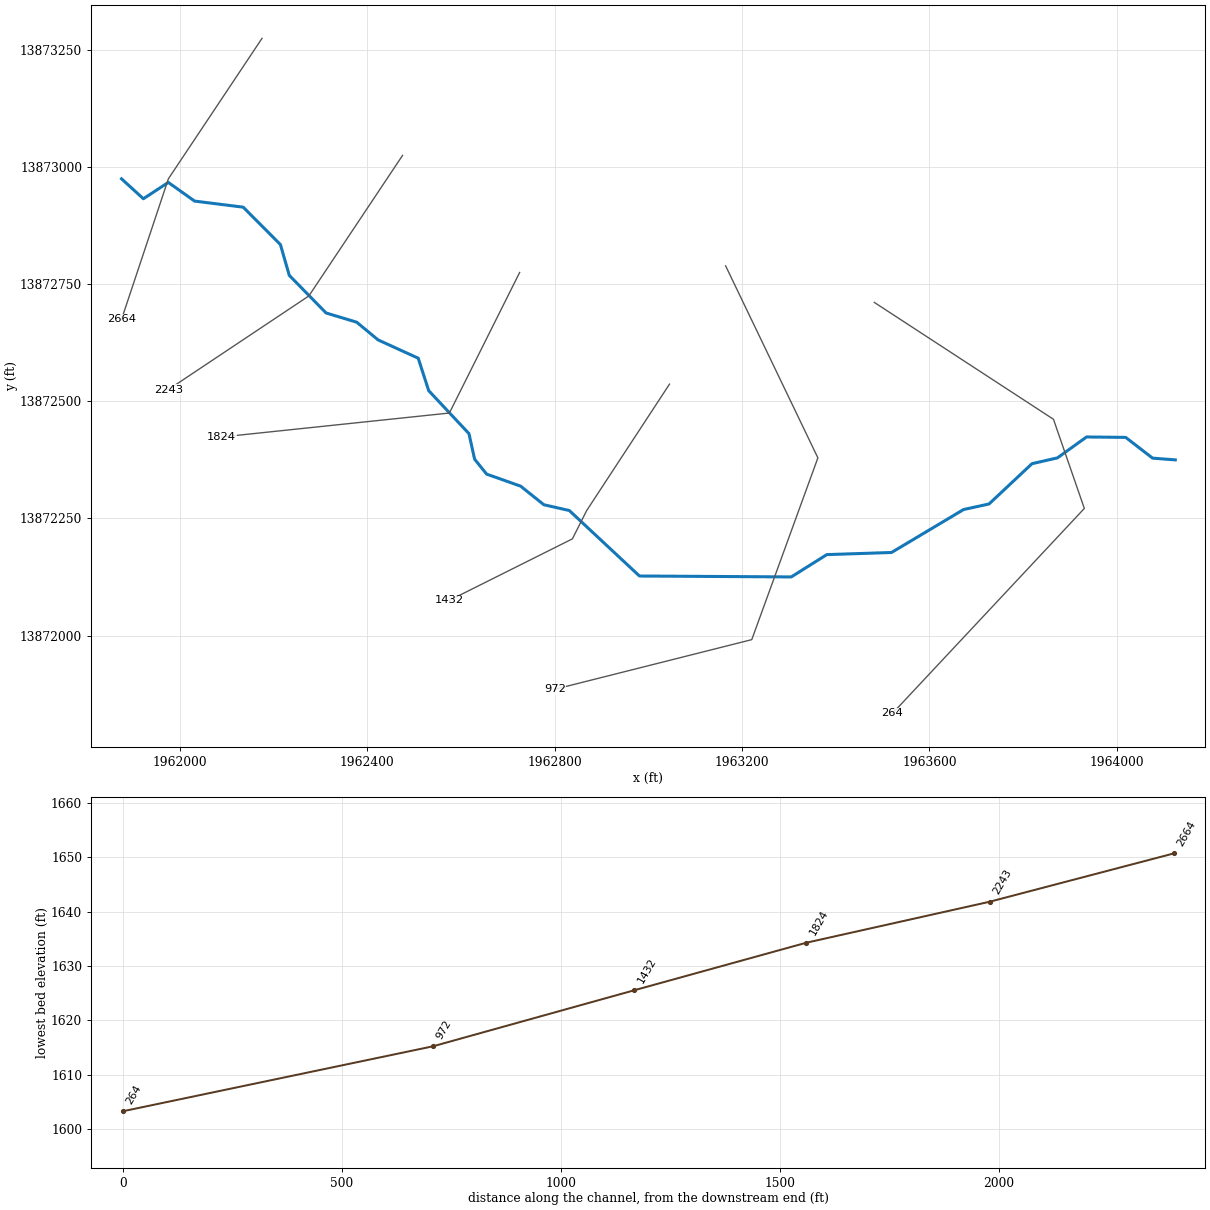
--- Stream0600.prj (project) ---

Proj Title=Stream0600 Base Level Engineering
Current Plan=p01
Default Exp/Contr=0.3,0.1
English Units
Geom File=g01
Flow File=f01
Plan File=p01
BEGIN DESCRIPTION:
Stream0600
END DESCRIPTION:

--- Stream0600.p01 (plan) ---

Plan Title=Multiple Run
Short Identifier=Multiple
Geom File=g01
Flow File=f01
Subcritical Flow
K Sum by GR= 0
Std Step Tol= 0.01
Critical Tol= 0.01
Num of Std Step Trials= 20
Max Error Tol= 0.3
Flow Tol Ratio= 0.001
Split Flow NTrial= 30
Split Flow Tol= 0.02
Split Flow Ratio= 0.02
Log Output Level= 0
Friction Slope Method= 1
Unsteady Friction Slope Method= 2
Unsteady Bridges Friction Slope Method= 1
Parabolic Critical Depth
Global Vel Dist=  1 , 1 , 1
Global Log Level= 0
CheckData=True
Encroach Param= -1, 0, 0, 0
BEGIN DESCRIPTION:
Multiple Run
END DESCRIPTION:

--- Stream0600.f01 (steady flow) ---

Flow Title=Multiple
Number of Profiles=7
Profile Names=10-year,25-year,50-year,1pct_min,100-year,1pct_plu,500-year
River Rch & RM= Stream0600,Reach-1,2664
     845    1420    1962    1315    2624    5236    4624
Boundary for River Rch & Prof#=Stream0600,Reach-1,1
Up Type=0
Dn Type=3
Dn Slope=0.005
Boundary for River Rch & Prof#=Stream0600,Reach-1,2
Up Type=0
Dn Type=3
Dn Slope=0.005
Boundary for River Rch & Prof#=Stream0600,Reach-1,3
Up Type=0
Dn Type=3
Dn Slope=0.005
Boundary for River Rch & Prof#=Stream0600,Reach-1,4
Up Type=0
Dn Type=3
Dn Slope=0.005
Boundary for River Rch & Prof#=Stream0600,Reach-1,5
Up Type=0
Dn Type=3
Dn Slope=0.005
Boundary for River Rch & Prof#=Stream0600,Reach-1,6
Up Type=0
Dn Type=3
Dn Slope=0.005
Boundary for River Rch & Prof#=Stream0600,Reach-1,7
Up Type=0
Dn Type=3
Dn Slope=0.005

--- Stream0600.g01 (geometry) ---

Geom Title=Existing Conditions

River Reach=Stream0600,Reach-1
Reach XY= 30
      1961875.00     13872975.00      1961921.66     13872932.51
      1961974.90     13872967.37      1962030.89     13872927.54
      1962134.81     13872914.49      1962214.23     13872834.70
      1962233.15     13872768.94      1962311.76     13872688.61
      1962377.19     13872668.90      1962422.84     13872631.11
      1962508.51     13872592.05      1962530.88     13872522.74
      1962616.82     13872431.02      1962628.89     13872376.43
      1962654.53     13872344.62      1962727.16     13872318.89
      1962776.73     13872279.19      1962831.06     13872266.86
      1962980.85     13872127.06      1963304.97     13872125.07
      1963380.94     13872172.73      1963519.07     13872177.25
      1963672.81     13872268.90      1963727.29     13872280.85
      1963818.95     13872366.84      1963873.25     13872379.22
      1963935.54     13872423.92      1964019.08     13872422.98
      1964076.51     13872378.65      1964125.00     13872375.00

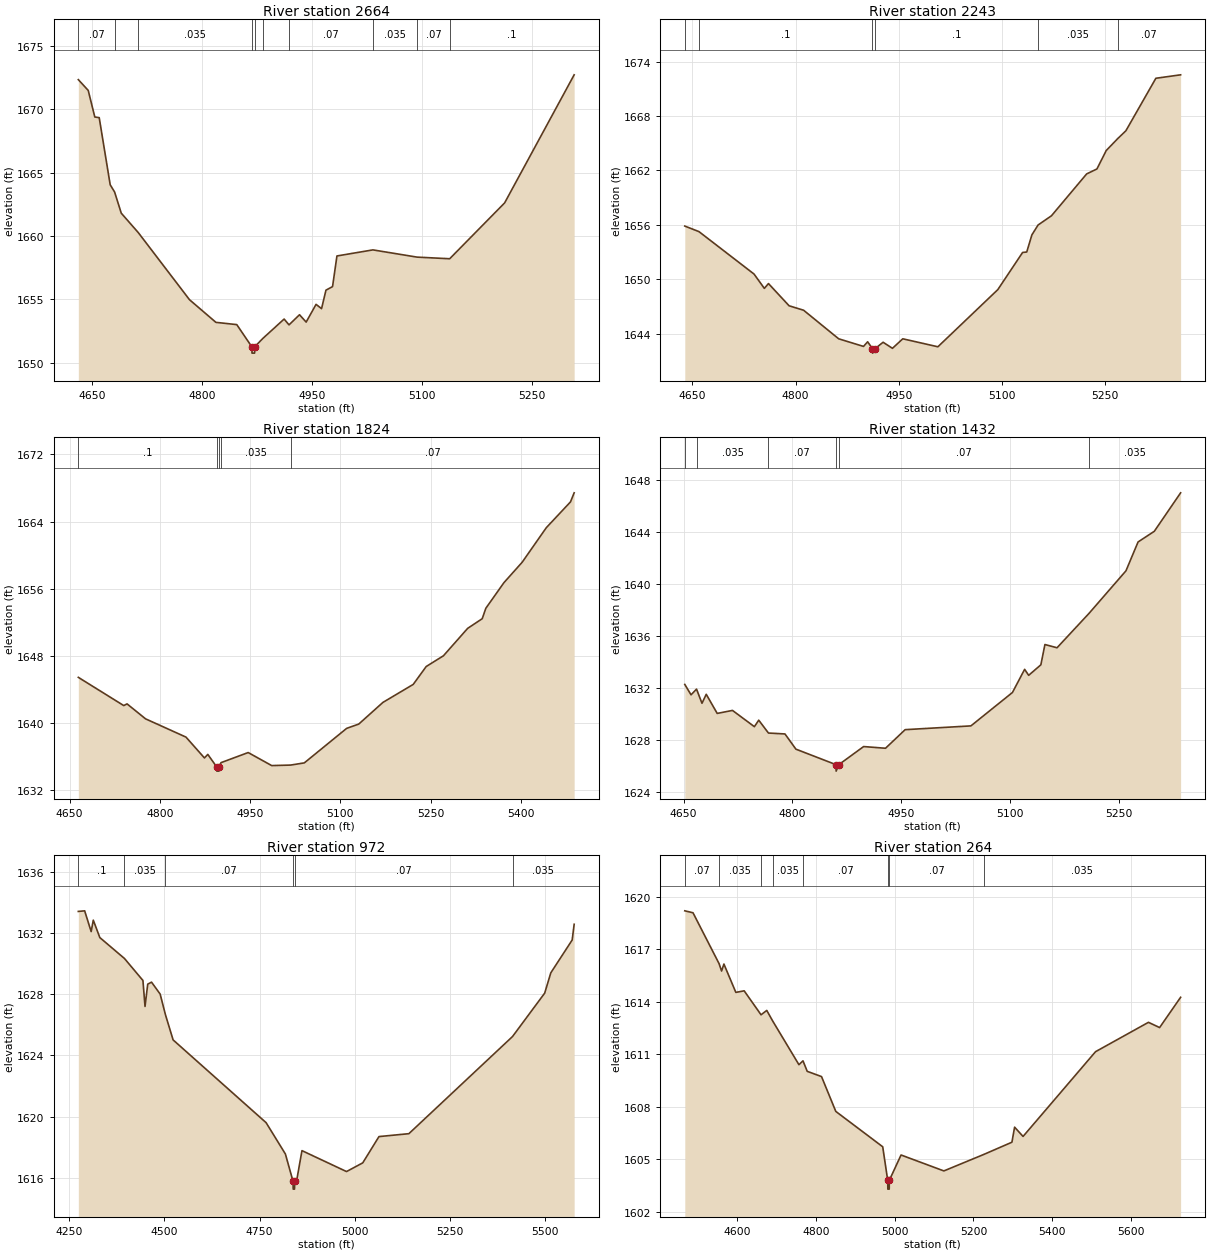
Type RM Length L Ch R = 1,2664,421,421,421
BEGIN DESCRIPTION:
Stream0600 4.0
END DESCRIPTION:
XS GIS Cut Line= 3
      1962174.98     13873274.98      1961975.00     13872975.00
      1961874.99     13872674.96
#Sta/Elev= 30
  4631.0 1672.34  4644.5 1671.49  4653.5 1669.39  4659.5 1669.34  4674.5 1664.04
  4680.5 1663.47  4689.6 1661.80  4712.9 1660.26  4782.7 1654.97  4818.8 1653.18
  4847.3 1653.00  4867.8 1651.25  4868.1 1650.75  4871.6 1650.75  4871.8 1651.25
  4882.5 1651.89  4911.9 1653.44  4918.6 1652.98  4932.9 1653.78  4942.0 1653.20
  4955.5 1654.60  4963.0 1654.26  4969.0 1655.72  4978.0 1656.00  4984.0 1658.42
  5033.1 1658.90  5093.2 1658.33  5137.9 1658.20  5212.9 1662.61  5307.8 1672.72
#Mann=10,-1,0
  4631.0    0.07       0  4680.5     0.1       0  4712.9   0.035       0
  4867.8    0.05       0  4871.8   0.035       0  4882.5     0.1       0
  4918.6    0.07       0  5033.1   0.035       0  5093.2    0.07       0
  5137.9     0.1       0
Bank Sta=4867.8,4871.8
Exp/Cntr=0.3,0.1

Type RM Length L Ch R = 1,2243,419,419,419
BEGIN DESCRIPTION:
Stream0600 3.0
END DESCRIPTION:
XS GIS Cut Line= 3
      1962475.00     13873025.00      1962275.00     13872725.00
      1961975.01     13872525.01
#Sta/Elev= 30
  4639.0 1655.86  4659.6 1655.25  4739.7 1650.57  4754.7 1648.99  4760.7 1649.52
  4790.7 1647.07  4811.8 1646.58  4862.8 1643.43  4898.9 1642.59  4904.9 1643.10
  4911.9 1642.35  4912.2 1641.85  4915.9 1642.35  4927.4 1643.05  4941.0 1642.38
  4956.0 1643.43  5007.1 1642.55  5094.2 1648.85  5130.3 1652.95  5136.3 1653.00
  5143.8 1654.89  5152.8 1655.98  5172.3 1657.00  5223.4 1661.61  5238.4 1662.16
  5251.9 1664.19  5268.8 1665.52  5280.5 1666.37  5324.1 1672.16  5360.1 1672.54
#Mann=6,-1,0
  4639.0    0.07       0  4659.6     0.1       0  4911.9    0.05       0
  4915.9     0.1       0  5152.8   0.035       0  5268.8    0.07       0
Bank Sta=4911.9,4915.9
Exp/Cntr=0.3,0.1

Type RM Length L Ch R = 1,1824,392,392,392
BEGIN DESCRIPTION:
Stream0600 2.0
END DESCRIPTION:
XS GIS Cut Line= 3
      1962725.00     13872774.99      1962575.00     13872475.00
      1962088.98     13872423.92
#Sta/Elev= 30
  4664.6 1645.46  4740.1 1642.10  4745.6 1642.30  4776.4 1640.52  4843.5 1638.35
  4874.2 1635.87  4879.8 1636.29  4894.6 1634.80  4894.8 1634.30  4898.3 1634.30
  4898.6 1634.80  4901.8 1635.31  4946.9 1636.51  4986.0 1634.96  5017.5 1635.02
  5040.2 1635.28  5110.6 1639.39  5130.7 1639.90  5170.9 1642.48  5221.2 1644.62
  5242.8 1646.75  5271.5 1648.03  5311.7 1651.29  5335.9 1652.44  5341.9 1653.68
  5372.0 1656.73  5402.2 1659.15  5442.4 1663.27  5482.6 1666.34  5488.7 1667.42
#Mann=5,-1,0
  4664.6     0.1       0  4894.6   0.035       0  4898.6     0.1       0
  4901.8   0.035       0  5017.5    0.07       0
Bank Sta=4894.6,4898.6
Exp/Cntr=0.3,0.1

Type RM Length L Ch R = 1,1432,460,460,460
BEGIN DESCRIPTION:
Stream0600 1.0
END DESCRIPTION:
XS GIS Cut Line= 4
      1963045.00     13872536.68      1962868.07     13872266.59
      1962837.67     13872206.34      1962575.04     13872075.02
#Sta/Elev= 30
  4651.7 1632.24  4660.3 1631.44  4667.9 1631.88  4675.4 1630.79  4681.3 1631.48
  4696.4 1630.01  4717.5 1630.24  4747.7 1628.99  4753.7 1629.49  4767.1 1628.50
  4789.9 1628.43  4805.0 1627.26  4860.2 1626.07  4860.5 1625.57  4864.2 1626.07
  4898.4 1627.46  4928.6 1627.33  4955.7 1628.76  5046.4 1629.05  5103.7 1631.62
  5120.5 1633.40  5126.1 1632.94  5142.9 1633.75  5148.5 1635.31  5165.2 1635.06
  5209.4 1637.71  5260.3 1640.98  5277.0 1643.20  5299.4 1644.02  5335.7 1646.98
#Mann=6,-1,0
  4651.7     0.1       0  4667.9   0.035       0  4767.1    0.07       0
  4860.2    0.05       0  4864.2    0.07       0  5209.4   0.035       0
Bank Sta=4860.2,4864.2
Exp/Cntr=0.3,0.1

Type RM Length L Ch R = 1,972,708,708,708
BEGIN DESCRIPTION:
Stream0600 0.0
END DESCRIPTION:
XS GIS Cut Line= 4
      1963164.84     13872789.25      1963361.84     13872379.31
      1963220.67     13871991.18      1962799.95     13871885.16
#Sta/Elev= 30
  4274.2 1633.43  4290.8 1633.47  4307.9 1632.11  4313.5 1632.86  4330.6 1631.72
  4395.3 1630.35  4443.8 1628.91  4449.3 1627.21  4456.4 1628.67  4466.4 1628.80
  4489.0 1628.02  4502.9 1626.67  4523.0 1625.02  4767.2 1619.60  4817.8 1617.55
  4838.0 1615.75  4838.3 1615.25  4841.8 1615.25  4842.0 1615.75  4848.4 1615.95
  4861.3 1617.77  4978.3 1616.40  5020.9 1616.97  5063.5 1618.69  5142.0 1618.88
  5414.1 1625.24  5498.5 1628.08  5514.6 1629.41  5570.7 1631.56  5575.9 1632.59
#Mann=6,-1,0
  4274.2     0.1       0  4395.3   0.035       0  4502.9    0.07       0
  4838.0    0.05       0  4842.0    0.07       0  5414.1   0.035       0
Bank Sta=4838,4842
Exp/Cntr=0.3,0.1

Type RM Length L Ch R = 1,264,0,0,0
BEGIN DESCRIPTION:
Stream0600 0.1
END DESCRIPTION:
XS GIS Cut Line= 4
      1963482.27     13872711.21      1963864.84     13872461.67
      1963930.76     13872271.28      1963521.12     13871833.76
#Sta/Elev= 30
  4467.8 1619.20  4488.6 1619.09  4554.8 1616.18  4561.1 1615.76  4567.0 1616.16
  4597.3 1614.54  4618.4 1614.63  4661.2 1613.26  4675.7 1613.51  4690.6 1612.91
  4757.3 1610.41  4767.6 1610.63  4778.3 1610.03  4814.6 1609.73  4850.8 1607.74
  4969.8 1605.72  4982.5 1603.80  4982.8 1603.30  4986.3 1603.30  4986.5 1603.80
  5016.3 1605.25  5124.9 1604.34  5226.0 1605.28  5297.5 1605.98  5304.3 1606.84
  5325.8 1606.31  5509.5 1611.15  5643.8 1612.83  5672.1 1612.53  5725.4 1614.26
#Mann=8,-1,0
  4467.8    0.07       0  4554.8   0.035       0  4661.2    0.07       0
  4690.6   0.035       0  4767.6    0.07       0  4982.5    0.05       0
  4986.5    0.07       0  5226.0   0.035       0
Bank Sta=4982.5,4986.5
Exp/Cntr=0.3,0.1

Chan Stop Cuts=-1