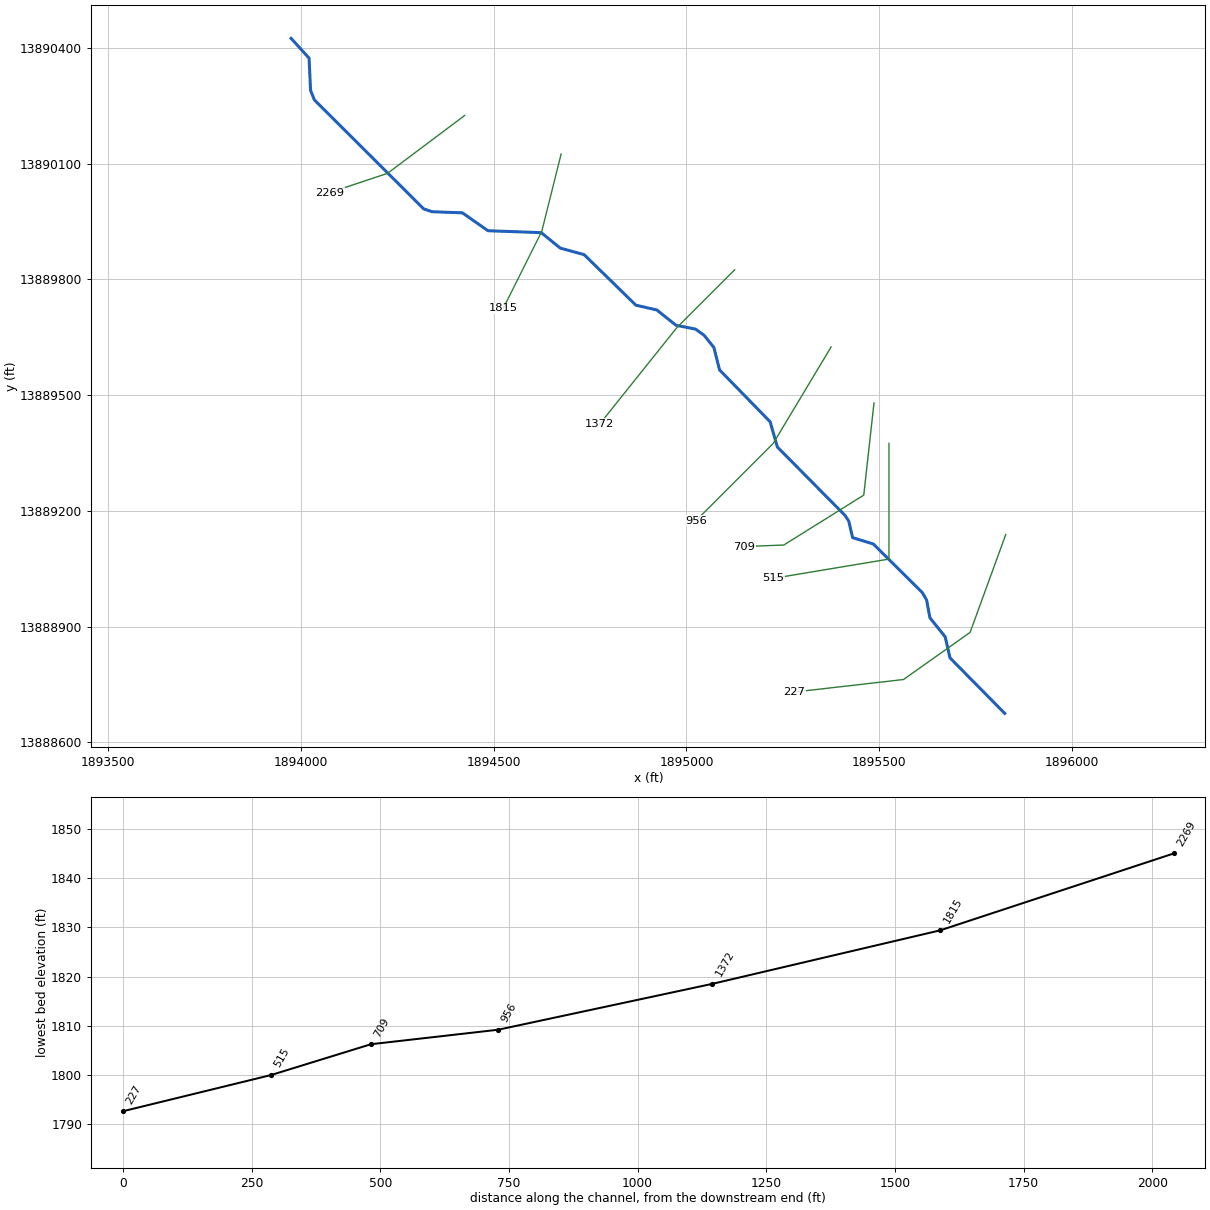
--- Stream0601.prj (project) ---

Proj Title=Stream0601 Base Level Engineering
Current Plan=p01
Default Exp/Contr=0.3,0.1
English Units
Geom File=g01
Flow File=f01
Plan File=p01
BEGIN DESCRIPTION:
Stream0601
END DESCRIPTION:

--- Stream0601.p01 (plan) ---

Plan Title=Multiple Run
Short Identifier=Multiple
Geom File=g01
Flow File=f01
Subcritical Flow
K Sum by GR= 0
Std Step Tol= 0.01
Critical Tol= 0.01
Num of Std Step Trials= 20
Max Error Tol= 0.3
Flow Tol Ratio= 0.001
Split Flow NTrial= 30
Split Flow Tol= 0.02
Split Flow Ratio= 0.02
Log Output Level= 0
Friction Slope Method= 1
Unsteady Friction Slope Method= 2
Unsteady Bridges Friction Slope Method= 1
Parabolic Critical Depth
Global Vel Dist=  1 , 1 , 1
Global Log Level= 0
CheckData=True
Encroach Param= -1, 0, 0, 0
BEGIN DESCRIPTION:
Multiple Run
END DESCRIPTION:

--- Stream0601.f01 (steady flow) ---

Flow Title=Multiple
Number of Profiles=7
Profile Names=10-year,25-year,50-year,1pct_min,100-year,1pct_plu,500-year
River Rch & RM= Stream0601,Reach-1,2269
     493     805    1093     723    1443    2879    2468
River Rch & RM= Stream0601,Reach-1,1815
     546     894    1215     803    1602    3197    2739
Boundary for River Rch & Prof#=Stream0601,Reach-1,1
Up Type=0
Dn Type=3
Dn Slope=0.005
Boundary for River Rch & Prof#=Stream0601,Reach-1,2
Up Type=0
Dn Type=3
Dn Slope=0.005
Boundary for River Rch & Prof#=Stream0601,Reach-1,3
Up Type=0
Dn Type=3
Dn Slope=0.005
Boundary for River Rch & Prof#=Stream0601,Reach-1,4
Up Type=0
Dn Type=3
Dn Slope=0.005
Boundary for River Rch & Prof#=Stream0601,Reach-1,5
Up Type=0
Dn Type=3
Dn Slope=0.005
Boundary for River Rch & Prof#=Stream0601,Reach-1,6
Up Type=0
Dn Type=3
Dn Slope=0.005
Boundary for River Rch & Prof#=Stream0601,Reach-1,7
Up Type=0
Dn Type=3
Dn Slope=0.005

--- Stream0601.g01 (geometry) ---

Geom Title=Existing Conditions

River Reach=Stream0601,Reach-1
Reach XY= 30
      1893975.00     13890425.00      1894021.61     13890373.59
      1894025.47     13890290.19      1894035.51     13890265.21
      1894318.83     13889982.86      1894340.22     13889975.52
      1894419.02     13889972.64      1894485.51     13889926.23
      1894623.44     13889921.24      1894672.83     13889881.14
      1894734.68     13889864.24      1894868.94     13889733.14
      1894923.27     13889720.81      1894972.84     13889681.11
      1895023.58     13889671.14      1895045.47     13889655.38
      1895071.11     13889623.57      1895085.79     13889565.34
      1895216.84     13889431.05      1895235.78     13889365.32
      1895411.27     13889187.98      1895420.87     13889172.99
      1895430.62     13889130.62      1895484.42     13889114.11
      1895611.38     13888988.22      1895622.50     13888968.97
      1895631.10     13888922.81      1895670.81     13888873.27
      1895683.14     13888818.94      1895825.00     13888675.00

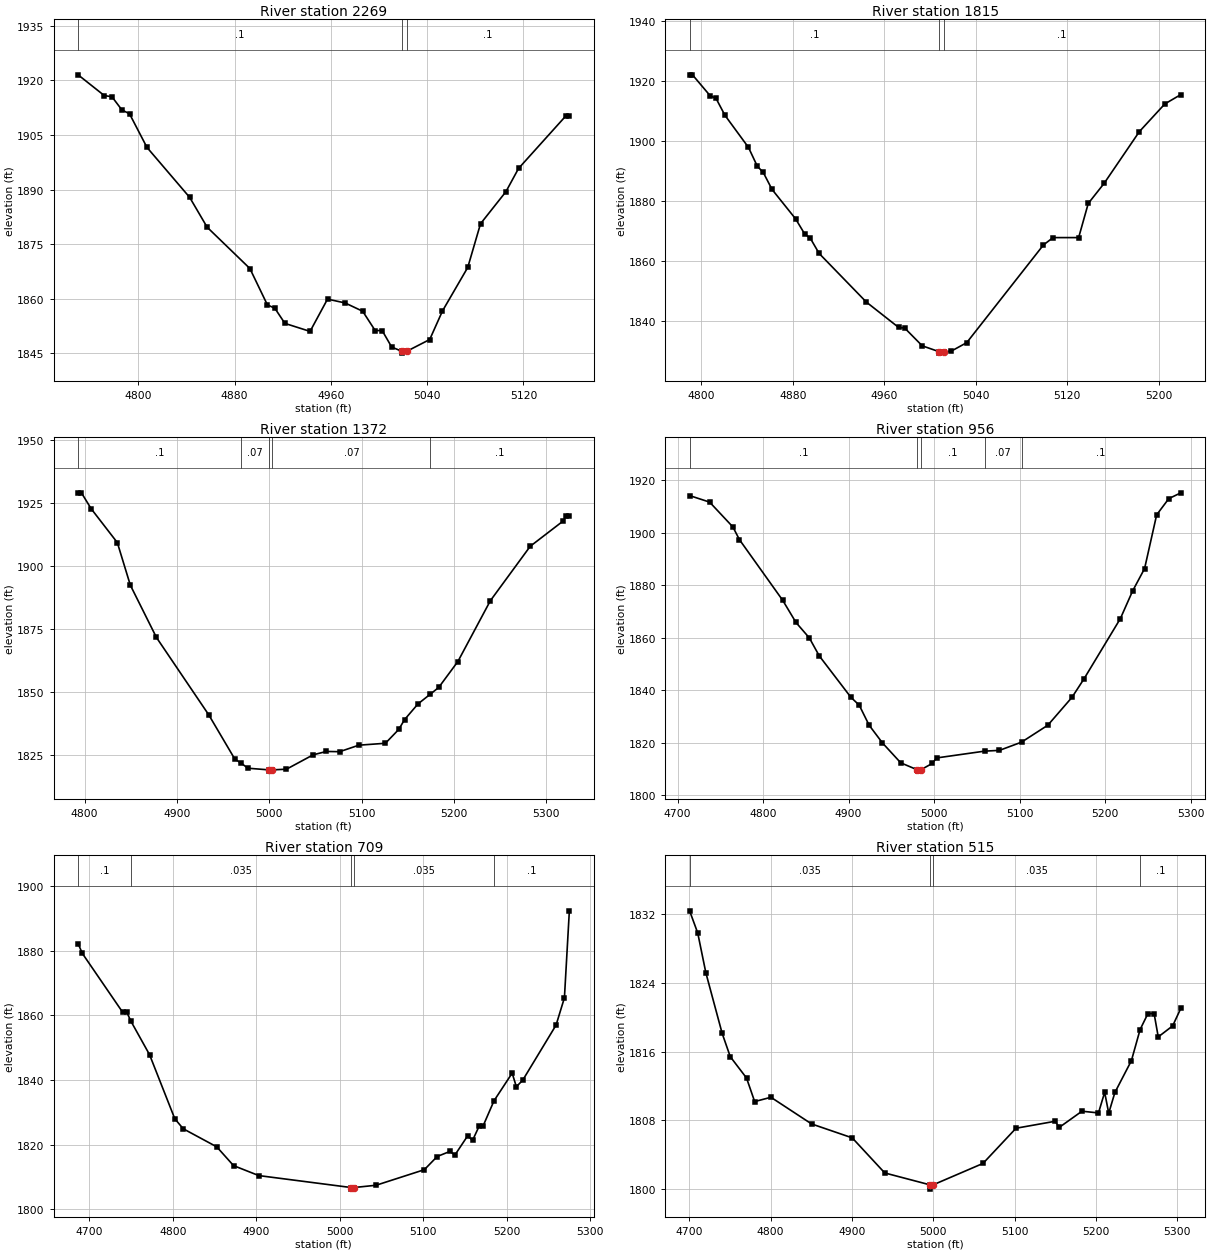
Type RM Length L Ch R = 1,2269,454,454,454
BEGIN DESCRIPTION:
Stream0601 5.0
END DESCRIPTION:
XS GIS Cut Line= 3
      1894424.96     13890224.97      1894225.00     13890075.00
      1894074.97     13890024.99
#Sta/Elev= 30
  4750.0 1921.51  4771.8 1915.80  4778.1 1915.49  4786.4 1911.86  4792.7 1910.81
  4807.2 1901.57  4842.7 1887.83  4857.2 1879.64  4892.7 1868.29  4907.2 1858.33
  4913.5 1857.34  4921.8 1853.21  4942.7 1851.01  4957.2 1859.88  4971.8 1858.83
  4986.4 1856.55  4996.8 1851.24  5002.6 1851.24  5010.5 1846.71  5019.0 1845.54
  5019.3 1845.04  5023.0 1845.54  5042.1 1848.78  5052.7 1856.63  5073.7 1868.59
  5084.3 1880.59  5105.4 1889.40  5115.9 1895.79  5155.4 1910.30  5158.1 1910.30
#Mann=3,-1,0
  4750.0     0.1       0  5019.0    0.05       0  5023.0     0.1       0
Bank Sta=5019,5023
Exp/Cntr=0.3,0.1

Type RM Length L Ch R = 1,1815,443,443,443
BEGIN DESCRIPTION:
Stream0601 4.0
END DESCRIPTION:
XS GIS Cut Line= 3
      1894674.99     13890124.95      1894625.00     13889925.00
      1894525.01     13889725.01
#Sta/Elev= 30
  4789.8 1922.13  4792.3 1922.13  4807.8 1915.15  4812.9 1914.29  4820.7 1908.65
  4841.3 1897.94  4849.0 1891.69  4854.2 1889.62  4861.9 1883.95  4882.5 1874.15
  4890.3 1869.21  4895.4 1867.67  4903.1 1862.62  4944.4 1846.42  4972.7 1837.95
  4977.9 1837.78  4993.3 1831.84  5007.9 1829.91  5008.1 1829.41  5011.9 1829.91
  5018.3 1830.00  5032.2 1832.90  5099.3 1865.45  5107.7 1867.90  5130.1 1867.90
  5138.5 1879.28  5152.4 1885.98  5183.2 1903.21  5205.5 1912.44  5219.5 1915.55
#Mann=3,-1,0
  4789.8     0.1       0  5007.9    0.05       0  5011.9     0.1       0
Bank Sta=5007.9,5011.9
Exp/Cntr=0.3,0.1

Type RM Length L Ch R = 1,1372,416,416,416
BEGIN DESCRIPTION:
Stream0601 3.0
END DESCRIPTION:
XS GIS Cut Line= 3
      1895125.03     13889825.03      1894975.00     13889675.00
      1894775.02     13889425.03
#Sta/Elev= 30
  4792.9 1929.03  4796.5 1929.03  4807.1 1922.69  4835.4 1909.27  4849.5 1892.36
  4877.8 1871.59  4934.4 1840.92  4962.7 1823.32  4969.8 1821.65  4976.8 1819.69
  4999.5 1819.03  4999.8 1818.53  5003.5 1819.03  5018.7 1819.30  5047.5 1824.99
  5061.9 1826.34  5076.3 1826.25  5097.1 1828.83  5125.9 1829.59  5140.3 1835.07
  5146.7 1839.01  5161.2 1845.22  5174.6 1849.11  5183.6 1851.74  5204.4 1862.05
  5239.6 1886.19  5282.8 1907.80  5318.0 1917.70  5322.0 1919.85  5325.2 1919.85
#Mann=5,-1,0
  4792.9     0.1       0  4969.8    0.07       0  4999.5    0.05       0
  5003.5    0.07       0  5174.6     0.1       0
Bank Sta=4999.5,5003.5
Exp/Cntr=0.3,0.1

Type RM Length L Ch R = 1,956,247,247,247
BEGIN DESCRIPTION:
Stream0601 2.0
END DESCRIPTION:
XS GIS Cut Line= 3
      1895375.02     13889625.03      1895225.00     13889375.00
      1895025.01     13889175.01
#Sta/Elev= 30
  4714.1 1914.21  4737.5 1911.72  4764.7 1902.26  4772.4 1897.40  4823.0 1874.28
  4838.5 1865.85  4854.1 1859.97  4865.7 1853.13  4902.7 1837.34  4912.4 1834.36
  4924.0 1826.71  4939.6 1819.95  4961.0 1812.37  4980.4 1809.71  4980.6 1809.21
  4984.4 1809.71  4997.9 1812.16  5002.8 1814.23  5059.1 1816.83  5076.4 1817.12
  5102.2 1820.25  5133.0 1826.72  5161.2 1837.33  5175.4 1844.45  5217.8 1867.35
  5232.0 1877.80  5246.1 1886.41  5260.2 1906.87  5274.4 1913.05  5288.5 1915.26
#Mann=5,-1,0
  4714.1     0.1       0  4980.4    0.05       0  4984.4     0.1       0
  5059.1    0.07       0  5102.2     0.1       0
Bank Sta=4980.4,4984.4
Exp/Cntr=0.3,0.1

Type RM Length L Ch R = 1,709,194,194,194
BEGIN DESCRIPTION:
Mapping XS dfcddc54
END DESCRIPTION:
XS GIS Cut Line= 4
      1895486.17     13889480.08      1895459.63     13889240.75
      1895252.23     13889111.42      1895149.13     13889107.47
#Sta/Elev= 30
  4686.6 1882.19  4691.7 1879.16  4739.8 1861.03  4744.8 1861.04  4749.9 1858.18
  4772.2 1847.84  4802.4 1828.04  4812.5 1824.94  4852.7 1819.34  4872.8 1813.54
  4903.0 1810.46  5013.4 1806.77  5013.6 1806.27  5017.4 1806.77  5043.5 1807.47
  5101.3 1812.28  5116.7 1816.36  5132.0 1817.94  5137.9 1816.81  5153.2 1822.75
  5159.1 1821.37  5167.2 1825.88  5171.8 1825.88  5184.8 1833.61  5206.5 1842.15
  5211.5 1837.95  5219.1 1839.94  5259.1 1857.01  5269.1 1865.46  5275.0 1892.34
#Mann=5,-1,0
  4686.6     0.1       0  4749.9   0.035       0  5013.4   0.035       0
  5017.4   0.035       0  5184.8     0.1       0
Bank Sta=5013.4,5017.4
Exp/Cntr=0.3,0.1

Type RM Length L Ch R = 1,515,288,288,288
BEGIN DESCRIPTION:
Stream0601 1.0
END DESCRIPTION:
XS GIS Cut Line= 3
      1895525.00     13889375.00      1895525.00     13889075.00
      1895225.04     13889025.01
#Sta/Elev= 30
  4700.3 1832.37  4710.3 1829.79  4720.3 1825.16  4740.3 1818.13  4750.3 1815.41
  4770.3 1812.93  4780.3 1810.19  4800.3 1810.69  4850.3 1807.59  4900.3 1805.97
  4940.3 1801.89  4995.8 1800.51  4996.0 1800.01  4999.8 1800.51  5061.1 1803.00
  5101.7 1807.09  5149.8 1807.90  5154.9 1807.19  5182.8 1809.07  5203.1 1808.87
  5210.7 1811.27  5215.7 1808.84  5223.3 1811.25  5243.6 1814.95  5254.3 1818.57
  5263.9 1820.42  5271.5 1820.43  5276.6 1817.71  5294.3 1818.99  5304.4 1821.04
#Mann=4,-1,0
  4700.3   0.035       0  4995.8   0.035       0  4999.8   0.035       0
  5254.3     0.1       0
Bank Sta=4995.8,4999.8
Exp/Cntr=0.3,0.1

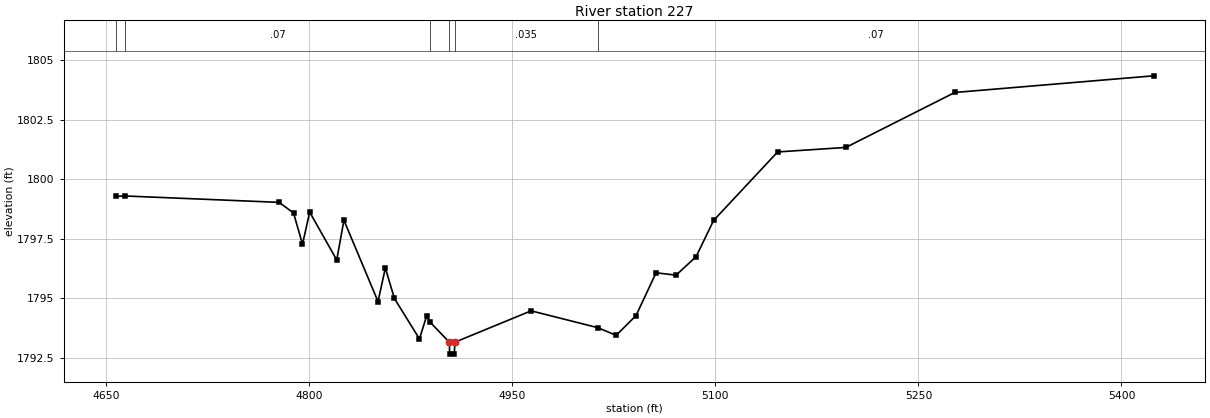
Type RM Length L Ch R = 1,227,0,0,0
BEGIN DESCRIPTION:
Stream0601 0.0
END DESCRIPTION:
XS GIS Cut Line= 4
      1895827.69     13889138.59      1895735.33     13888884.98
      1895562.57     13888762.76      1895279.15     13888730.23
#Sta/Elev= 30
  4656.9 1799.28  4663.6 1799.30  4777.8 1799.03  4788.4 1798.58  4795.0 1797.27
  4800.3 1798.62  4820.3 1796.61  4825.6 1798.28  4850.8 1794.86  4856.2 1796.27
  4862.9 1794.99  4881.4 1793.29  4886.7 1794.25  4889.5 1793.98  4903.5 1793.15
  4903.7 1792.65  4907.2 1792.65  4907.5 1793.15  4963.9 1794.47  5013.3 1793.76
  5026.7 1793.44  5041.4 1794.27  5056.2 1796.07  5071.0 1795.97  5085.8 1796.75
  5098.7 1798.27  5146.0 1801.15  5196.4 1801.34  5276.9 1803.65  5423.7 1804.35
#Mann=6,-1,0
  4656.9   0.035       0  4663.6    0.07       0  4889.5   0.035       0
  4903.5   0.035       0  4907.5   0.035       0  5013.3    0.07       0
Bank Sta=4903.5,4907.5
Exp/Cntr=0.3,0.1

Chan Stop Cuts=-1