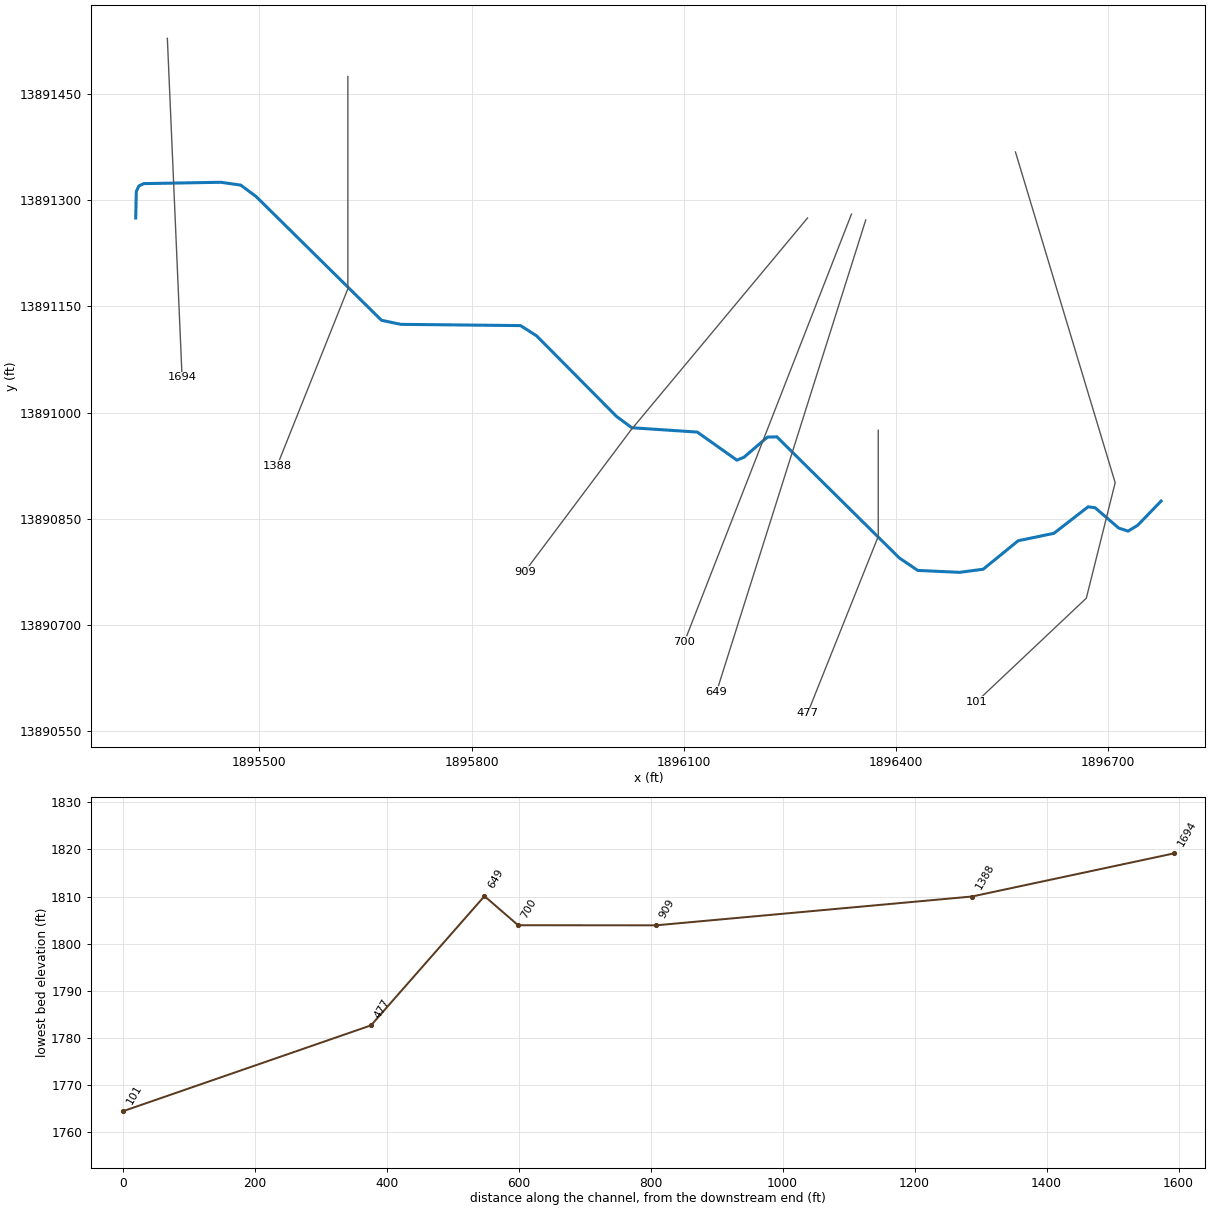
--- Stream0602.prj (project) ---

Proj Title=Stream0602 Base Level Engineering
Current Plan=p01
Default Exp/Contr=0.3,0.1
English Units
Geom File=g01
Flow File=f01
Plan File=p01
BEGIN DESCRIPTION:
Stream0602
END DESCRIPTION:

--- Stream0602.p01 (plan) ---

Plan Title=Multiple Run
Short Identifier=Multiple
Geom File=g01
Flow File=f01
Subcritical Flow
K Sum by GR= 0
Std Step Tol= 0.01
Critical Tol= 0.01
Num of Std Step Trials= 20
Max Error Tol= 0.3
Flow Tol Ratio= 0.001
Split Flow NTrial= 30
Split Flow Tol= 0.02
Split Flow Ratio= 0.02
Log Output Level= 0
Friction Slope Method= 1
Unsteady Friction Slope Method= 2
Unsteady Bridges Friction Slope Method= 1
Parabolic Critical Depth
Global Vel Dist=  1 , 1 , 1
Global Log Level= 0
CheckData=True
Encroach Param= -1, 0, 0, 0
BEGIN DESCRIPTION:
Multiple Run
END DESCRIPTION:

--- Stream0602.f01 (steady flow) ---

Flow Title=Multiple
Number of Profiles=7
Profile Names=10-year,25-year,50-year,1pct_min,100-year,1pct_plu,500-year
River Rch & RM= Stream0602,Reach-1,1694
     521     850    1153     761    1518    3028    2587
Boundary for River Rch & Prof#=Stream0602,Reach-1,1
Up Type=0
Dn Type=3
Dn Slope=0.005
Boundary for River Rch & Prof#=Stream0602,Reach-1,2
Up Type=0
Dn Type=3
Dn Slope=0.005
Boundary for River Rch & Prof#=Stream0602,Reach-1,3
Up Type=0
Dn Type=3
Dn Slope=0.005
Boundary for River Rch & Prof#=Stream0602,Reach-1,4
Up Type=0
Dn Type=3
Dn Slope=0.005
Boundary for River Rch & Prof#=Stream0602,Reach-1,5
Up Type=0
Dn Type=3
Dn Slope=0.005
Boundary for River Rch & Prof#=Stream0602,Reach-1,6
Up Type=0
Dn Type=3
Dn Slope=0.005
Boundary for River Rch & Prof#=Stream0602,Reach-1,7
Up Type=0
Dn Type=3
Dn Slope=0.005

--- Stream0602.g01 (geometry) ---

Geom Title=Existing Conditions

River Reach=Stream0602,Reach-1
Reach XY= 30
      1895325.00     13891275.00      1895325.84     13891312.57
      1895329.63     13891320.38      1895336.44     13891323.59
      1895445.15     13891325.48      1895473.53     13891321.48
      1895495.16     13891305.40      1895672.55     13891130.46
      1895699.88     13891124.71      1895869.15     13891122.94
      1895891.76     13891108.57      1896004.85     13890994.63
      1896026.50     13890978.61      1896119.11     13890972.45
      1896175.10     13890932.80      1896185.06     13890936.85
      1896218.34     13890965.40      1896231.67     13890965.70
      1896404.84     13890794.58      1896430.89     13890776.96
      1896490.06     13890774.27      1896523.41     13890778.67
      1896572.83     13890818.90      1896623.37     13890829.41
      1896671.77     13890866.88      1896681.73     13890865.48
      1896715.01     13890836.83      1896728.34     13890832.51
      1896741.78     13890840.69      1896775.00     13890875.00

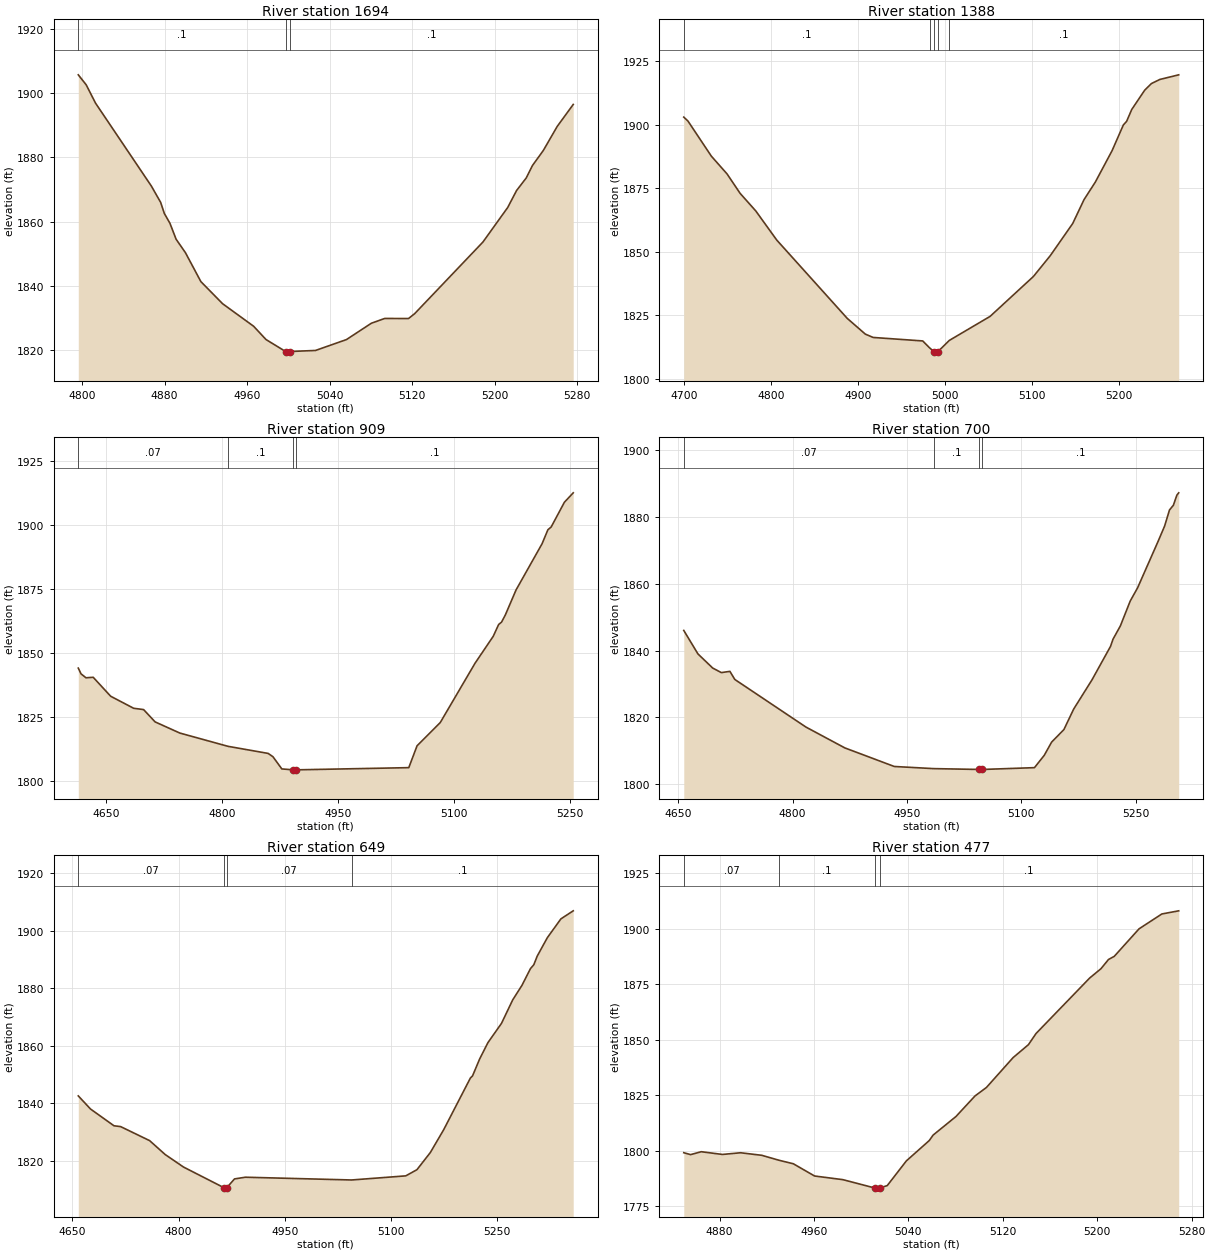
Type RM Length L Ch R = 1,1694,306,306,306
BEGIN DESCRIPTION:
Stream0602 4.0
END DESCRIPTION:
XS GIS Cut Line= 2
      1895369.74     13891528.89      1895390.57     13891049.74
#Sta/Elev= 30
  4796.4 1905.71  4804.1 1902.59  4813.1 1896.91  4867.2 1871.12  4876.2 1866.05
  4879.8 1862.58  4885.2 1859.55  4891.2 1854.57  4900.2 1850.41  4915.2 1841.39
  4936.2 1834.53  4966.3 1827.51  4978.3 1823.38  4997.3 1819.65  4997.5 1819.15
  5001.3 1819.65  5026.3 1819.98  5056.3 1823.37  5080.4 1828.45  5093.3 1829.93
  5116.4 1829.91  5122.4 1831.44  5188.5 1853.70  5212.5 1864.44  5221.1 1869.72
  5230.5 1873.65  5236.5 1877.50  5247.0 1882.17  5260.5 1889.67  5276.0 1896.49
#Mann=3,-1,0
  4796.4     0.1       0  4997.3    0.05       0  5001.3     0.1       0
Bank Sta=4997.3,5001.3
Exp/Cntr=0.3,0.1

Type RM Length L Ch R = 1,1388,479,479,479
BEGIN DESCRIPTION:
Stream0602 3.0
END DESCRIPTION:
XS GIS Cut Line= 3
      1895625.00     13891474.99      1895625.00     13891175.00
      1895525.02     13890925.04
#Sta/Elev= 30
  4699.7 1902.93  4704.5 1901.39  4731.5 1887.52  4749.5 1880.55  4764.5 1872.91
  4782.5 1865.99  4806.7 1854.49  4887.7 1823.68  4908.5 1817.48  4917.5 1816.17
  4974.5 1814.80  4982.3 1812.11  4987.7 1810.50  4988.0 1810.00  4991.7 1810.50
  5005.1 1815.01  5052.0 1824.47  5101.8 1840.18  5121.2 1848.38  5147.0 1861.04
  5160.0 1870.43  5172.9 1877.29  5192.3 1889.74  5205.2 1899.82  5209.0 1901.27
  5214.9 1905.95  5229.8 1913.54  5237.5 1916.14  5247.2 1917.76  5268.9 1919.58
#Mann=5,-1,0
  4699.7     0.1       0  4982.3    0.07       0  4987.7    0.05       0
  4991.7    0.07       0  5005.1     0.1       0
Bank Sta=4987.7,4991.7
Exp/Cntr=0.3,0.1

Type RM Length L Ch R = 1,909,209,209,209
BEGIN DESCRIPTION:
Stream0602 2.0
END DESCRIPTION:
XS GIS Cut Line= 3
      1896274.98     13891274.98      1896025.00     13890975.00
      1895874.99     13890774.99
#Sta/Elev= 30
  4613.7 1844.11  4617.3 1841.86  4623.7 1840.33  4633.0 1840.53  4655.6 1833.13
  4685.4 1828.42  4698.2 1827.92  4713.1 1823.11  4745.1 1818.75  4807.4 1813.57
  4859.4 1810.80  4865.6 1809.51  4877.1 1804.74  4891.7 1804.38  4891.9 1803.88
  4895.7 1804.38  5041.4 1805.24  5052.1 1813.77  5082.1 1822.84  5127.1 1846.00
  5150.7 1856.55  5157.7 1861.15  5161.4 1862.05  5166.3 1864.84  5180.2 1874.63
  5213.9 1892.69  5221.4 1898.13  5225.7 1899.25  5242.8 1908.90  5254.2 1912.57
#Mann=4,-1,0
  4613.7    0.07       0  4807.4     0.1       0  4891.7    0.05       0
  4895.7     0.1       0
Bank Sta=4891.7,4895.7
Exp/Cntr=0.3,0.1

Type RM Length L Ch R = 1,700,51,51,51
BEGIN DESCRIPTION:
Mapping XS a17adcd1
END DESCRIPTION:
XS GIS Cut Line= 2
      1896337.14     13891280.51      1896100.87     13890675.94
#Sta/Elev= 30
  4657.3 1846.05  4675.9 1839.01  4695.2 1834.79  4706.5 1833.42  4717.8 1833.79
  4724.2 1831.37  4817.6 1817.09  4868.6 1810.85  4933.4 1805.29  4985.1 1804.65
  5044.9 1804.40  5045.2 1803.90  5048.9 1804.40  5117.2 1804.94  5130.1 1808.65
  5139.7 1812.59  5155.8 1816.34  5168.7 1822.51  5192.8 1831.30  5217.0 1841.29
  5220.2 1843.41  5229.9 1847.42  5242.8 1854.86  5252.5 1858.83  5279.3 1872.71
  5287.9 1877.32  5294.3 1882.14  5299.4 1883.56  5304.0 1886.60  5306.4 1887.28
#Mann=4,-1,0
  4657.3    0.07       0  4985.1     0.1       0  5044.9    0.05       0
  5048.9     0.1       0
Bank Sta=5044.9,5048.9
Exp/Cntr=0.3,0.1

Type RM Length L Ch R = 1,649,172,172,172
BEGIN DESCRIPTION:
Stream0602 1.1
END DESCRIPTION:
XS GIS Cut Line= 2
      1896357.34     13891272.28      1896146.41     13890605.65
#Sta/Elev= 30
  4658.4 1842.49  4675.7 1837.93  4708.8 1832.11  4718.3 1831.81  4759.2 1826.94
  4781.2 1822.10  4807.1 1817.75  4864.2 1810.58  4864.4 1810.08  4868.2 1810.58
  4879.1 1813.63  4894.5 1814.22  5044.6 1813.26  5121.0 1814.69  5136.8 1816.83
  5155.7 1822.79  5174.5 1830.69  5212.3 1848.69  5215.4 1849.47  5225.4 1855.33
  5237.1 1861.01  5256.3 1867.73  5272.1 1875.87  5285.2 1880.94  5297.2 1886.75
  5301.9 1888.08  5306.7 1891.07  5321.0 1897.49  5340.2 1904.04  5357.6 1906.84
#Mann=4,-1,0
  4658.4    0.07       0  4864.2    0.05       0  4868.2    0.07       0
  5044.6     0.1       0
Bank Sta=4864.2,4868.2
Exp/Cntr=0.3,0.1

Type RM Length L Ch R = 1,477,376,376,376
BEGIN DESCRIPTION:
Stream0602 1.0
END DESCRIPTION:
XS GIS Cut Line= 3
      1896375.00     13890975.00      1896375.00     13890825.00
      1896274.98     13890574.96
#Sta/Elev= 30
  4849.7 1799.06  4855.5 1798.20  4864.5 1799.51  4882.5 1798.28  4897.8 1799.04
  4915.8 1797.89  4930.5 1795.64  4942.5 1794.08  4960.5 1788.56  4984.5 1786.91
  5011.6 1783.14  5011.8 1782.64  5015.6 1783.14  5022.1 1784.25  5038.3 1795.39
  5057.7 1804.56  5060.9 1806.99  5080.3 1815.39  5096.4 1824.64  5106.1 1828.48
  5128.7 1841.95  5141.7 1847.79  5148.1 1852.80  5193.6 1877.85  5203.1 1882.02
  5209.5 1886.19  5214.4 1887.61  5235.4 1900.02  5254.7 1906.72  5269.0 1908.14
#Mann=4,-1,0
  4849.7    0.07       0  4930.5     0.1       0  5011.6    0.05       0
  5015.6     0.1       0
Bank Sta=5011.6,5015.6
Exp/Cntr=0.3,0.1

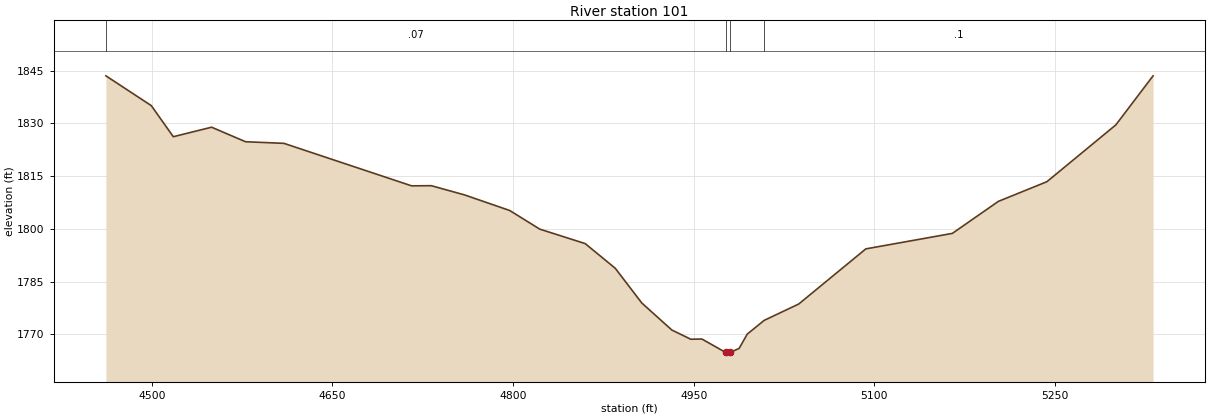
Type RM Length L Ch R = 1,101,0,0,0
BEGIN DESCRIPTION:
Stream0602 0.0
END DESCRIPTION:
XS GIS Cut Line= 4
      1896569.02     13891368.27      1896710.03     13890900.92
      1896669.23     13890737.75      1896513.92     13890591.34
#Sta/Elev= 30
  4461.8 1843.54  4499.5 1835.07  4517.8 1826.23  4549.6 1828.93  4577.8 1824.80
  4609.7 1824.34  4715.7 1812.26  4732.1 1812.30  4759.6 1809.69  4797.2 1805.25
  4822.2 1799.95  4859.9 1795.84  4884.9 1788.82  4906.9 1778.96  4931.9 1771.26
  4947.6 1768.65  4956.9 1768.70  4976.5 1764.91  4976.8 1764.41  4980.5 1764.91
  4987.8 1766.04  4994.5 1770.09  5008.6 1774.01  5037.3 1778.66  5093.0 1794.33
  5164.9 1798.74  5203.1 1807.84  5243.4 1813.43  5300.7 1829.59  5331.6 1843.53
#Mann=4,-1,0
  4461.8    0.07       0  4976.5    0.05       0  4980.5    0.07       0
  5008.6     0.1       0
Bank Sta=4976.5,4980.5
Exp/Cntr=0.3,0.1

Chan Stop Cuts=-1