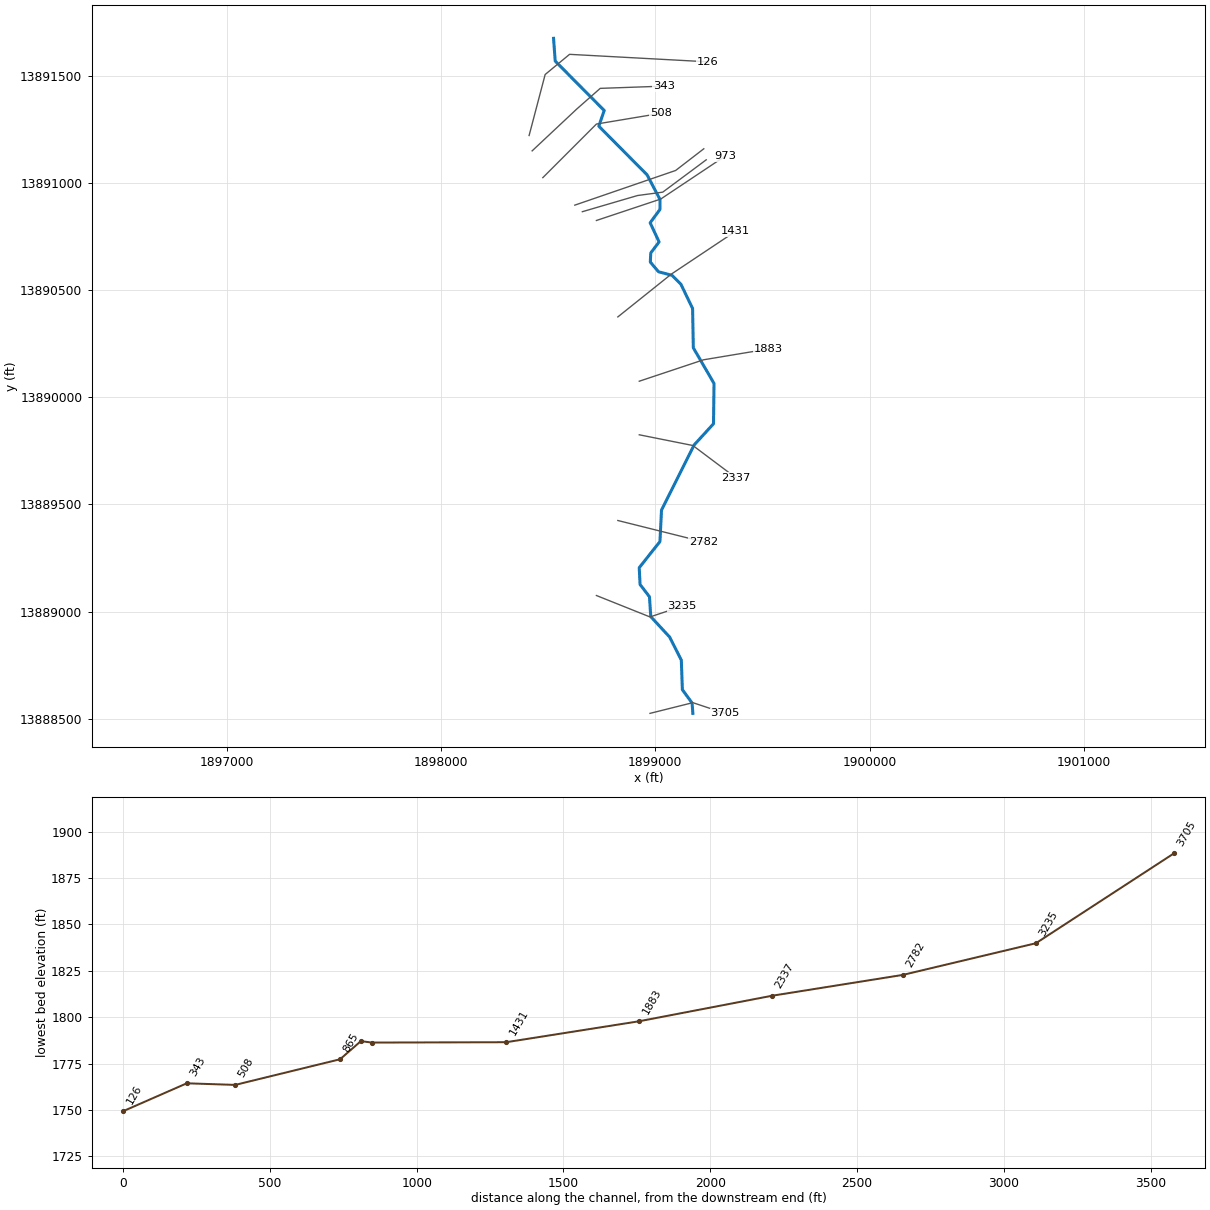
--- Stream0603.prj (project) ---

Proj Title=Stream0603 Base Level Engineering
Current Plan=p01
Default Exp/Contr=0.3,0.1
English Units
Geom File=g01
Flow File=f01
Plan File=p01
BEGIN DESCRIPTION:
Stream0603
END DESCRIPTION:

--- Stream0603.p01 (plan) ---

Plan Title=Multiple Run
Short Identifier=Multiple
Geom File=g01
Flow File=f01
Subcritical Flow
K Sum by GR= 0
Std Step Tol= 0.01
Critical Tol= 0.01
Num of Std Step Trials= 20
Max Error Tol= 0.3
Flow Tol Ratio= 0.001
Split Flow NTrial= 30
Split Flow Tol= 0.02
Split Flow Ratio= 0.02
Log Output Level= 0
Friction Slope Method= 1
Unsteady Friction Slope Method= 2
Unsteady Bridges Friction Slope Method= 1
Parabolic Critical Depth
Global Vel Dist=  1 , 1 , 1
Global Log Level= 0
CheckData=True
Encroach Param= -1, 0, 0, 0
BEGIN DESCRIPTION:
Multiple Run
END DESCRIPTION:

--- Stream0603.f01 (steady flow) ---

Flow Title=Multiple
Number of Profiles=7
Profile Names=10-year,25-year,50-year,1pct_min,100-year,1pct_plu,500-year
River Rch & RM= Stream0603,Reach-1,3705
     339     537     716     465     929    1853    1532
River Rch & RM= Stream0603,Reach-1,2782
     698    1164    1600    1069    2132    4255    3727
Boundary for River Rch & Prof#=Stream0603,Reach-1,1
Up Type=0
Dn Type=3
Dn Slope=0.005
Boundary for River Rch & Prof#=Stream0603,Reach-1,2
Up Type=0
Dn Type=3
Dn Slope=0.005
Boundary for River Rch & Prof#=Stream0603,Reach-1,3
Up Type=0
Dn Type=3
Dn Slope=0.005
Boundary for River Rch & Prof#=Stream0603,Reach-1,4
Up Type=0
Dn Type=3
Dn Slope=0.005
Boundary for River Rch & Prof#=Stream0603,Reach-1,5
Up Type=0
Dn Type=3
Dn Slope=0.005
Boundary for River Rch & Prof#=Stream0603,Reach-1,6
Up Type=0
Dn Type=3
Dn Slope=0.005
Boundary for River Rch & Prof#=Stream0603,Reach-1,7
Up Type=0
Dn Type=3
Dn Slope=0.005

--- Stream0603.g01 (geometry) ---

Geom Title=Existing Conditions

River Reach=Stream0603,Reach-1
Reach XY= 30
      1899175.00     13888525.00      1899171.35     13888573.49
      1899126.13     13888635.47      1899121.24     13888773.44
      1899066.84     13888881.05      1898978.62     13888976.50
      1898972.64     13889069.02      1898928.70     13889126.60
      1898924.79     13889204.95      1899021.44     13889326.47
      1899028.76     13889473.44      1899180.85     13889777.29
      1899271.45     13889876.47      1899273.80     13890064.50
      1899177.24     13890230.93      1899173.80     13890414.50
      1899119.27     13890527.55      1899077.51     13890569.24
      1899014.90     13890585.65      1898976.58     13890630.87
      1898978.56     13890673.32      1899017.38     13890725.00
      1898975.84     13890814.30      1899021.60     13890876.72
      1899021.66     13890923.28      1898961.38     13891038.21
      1898736.24     13891265.00      1898761.35     13891338.33
      1898532.74     13891568.78      1898525.00     13891675.00

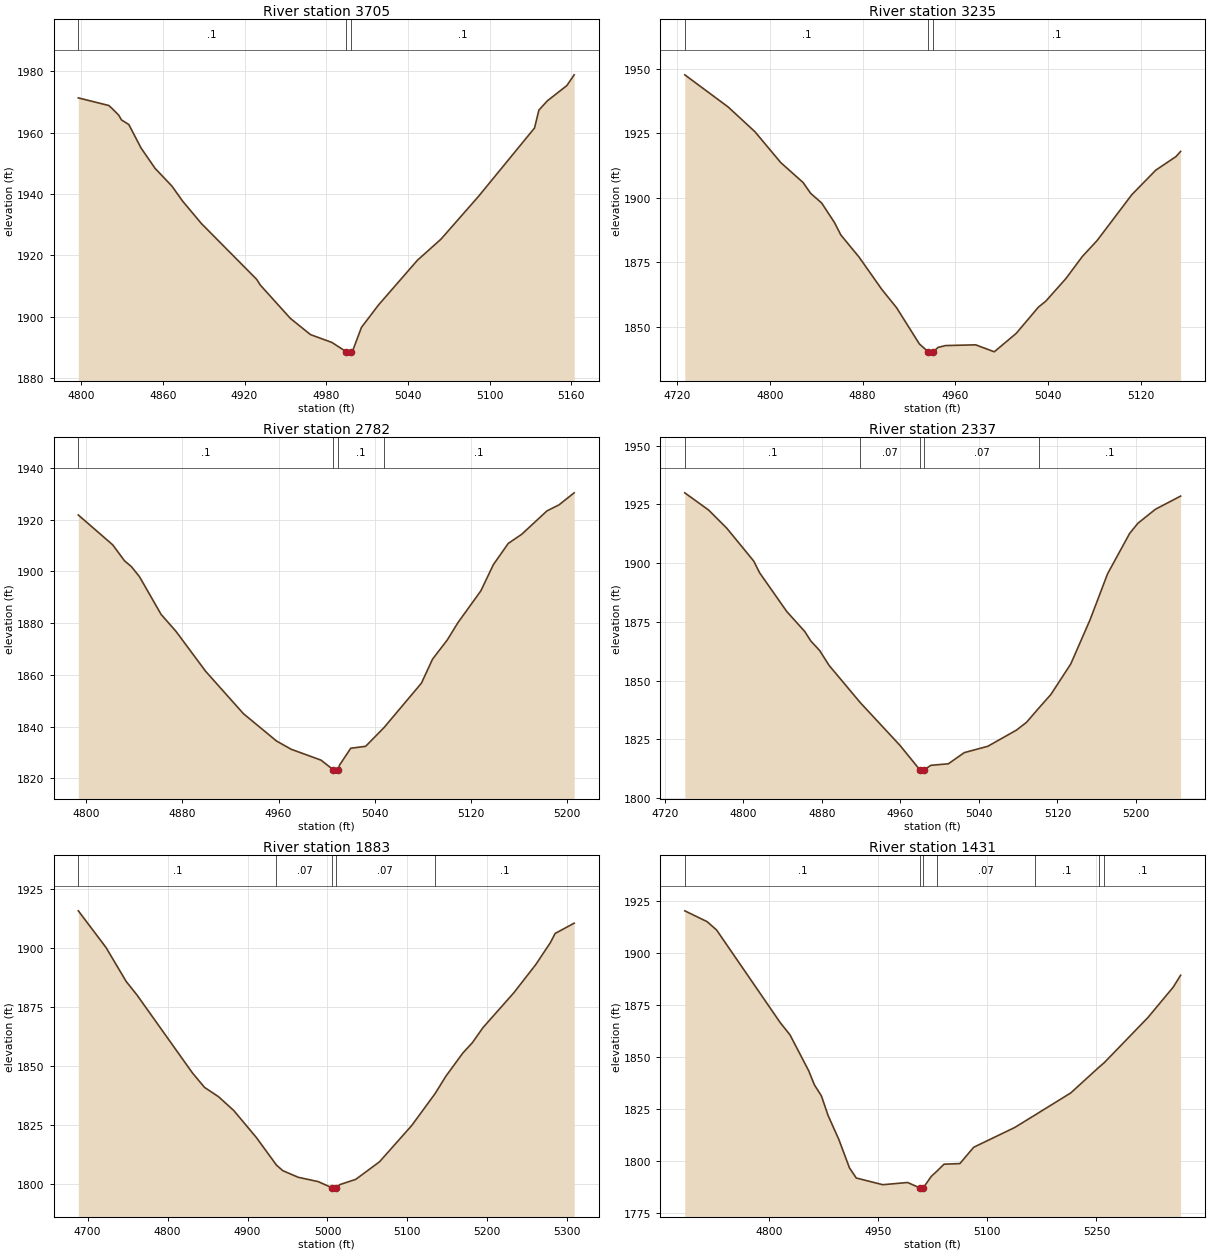
Type RM Length L Ch R = 1,3705,470,470,470
BEGIN DESCRIPTION:
Stream0603 8.0
END DESCRIPTION:
XS GIS Cut Line= 3
      1898975.00     13888525.00      1899175.00     13888575.00
      1899325.03     13888524.99
#Sta/Elev= 30
  4797.9 1971.27  4820.3 1968.79  4822.6 1967.86  4827.5 1965.70  4829.6 1964.10
  4835.0 1962.60  4844.0 1954.95  4854.3 1948.34  4866.7 1942.55  4874.5 1937.69
  4888.3 1930.40  4929.0 1912.19  4931.6 1910.37  4953.7 1899.52  4968.5 1894.24
  4984.2 1891.70  4994.6 1888.72  4994.8 1888.22  4998.6 1888.72  4999.7 1889.24
  5005.9 1896.58  5018.5 1903.92  5047.0 1918.42  5064.3 1925.28  5092.0 1939.26
  5133.1 1961.48  5136.3 1967.30  5142.6 1970.34  5156.8 1975.26  5162.2 1978.77
#Mann=3,-1,0
  4797.9     0.1       0  4994.6    0.05       0  4998.6     0.1       0
Bank Sta=4994.6,4998.6
Exp/Cntr=0.3,0.1

Type RM Length L Ch R = 1,3235,453,453,453
BEGIN DESCRIPTION:
Stream0603 7.0
END DESCRIPTION:
XS GIS Cut Line= 3
      1898725.01     13889075.00      1898975.00     13888975.00
      1899125.03     13889025.01
#Sta/Elev= 30
  4726.8 1947.58  4764.2 1935.13  4787.2 1925.58  4809.5 1913.61  4828.8 1905.87
  4835.3 1901.69  4844.8 1897.94  4855.9 1890.33  4861.3 1885.58  4877.1 1876.96
  4896.7 1864.45  4909.4 1857.38  4929.0 1843.38  4936.7 1840.32  4936.9 1839.82
  4940.7 1840.32  4945.2 1842.05  4951.6 1842.75  4977.5 1843.03  4993.6 1840.34
  5012.5 1847.48  5031.6 1857.62  5038.0 1859.95  5055.3 1868.68  5069.5 1877.25
  5082.2 1883.41  5112.2 1901.21  5132.8 1910.67  5150.2 1915.93  5154.2 1917.92
#Mann=3,-1,0
  4726.8     0.1       0  4936.7    0.05       0  4940.7     0.1       0
Bank Sta=4936.7,4940.7
Exp/Cntr=0.3,0.1

Type RM Length L Ch R = 1,2782,445,445,445
BEGIN DESCRIPTION:
Stream0603 6.0
END DESCRIPTION:
XS GIS Cut Line= 3
      1898825.01     13889425.00      1899025.00     13889375.00
      1899225.00     13889325.00
#Sta/Elev= 30
  4793.5 1921.74  4822.1 1910.21  4831.9 1904.04  4837.6 1901.81  4844.3 1897.94
  4862.3 1883.35  4874.7 1876.78  4899.4 1861.32  4930.8 1844.96  4958.3 1834.40
  4970.5 1831.21  4995.3 1827.01  5005.6 1823.26  5005.9 1822.76  5009.6 1823.26
  5010.7 1825.07  5020.0 1831.60  5032.4 1832.35  5047.6 1839.54  5078.8 1856.76
  5088.0 1866.00  5100.4 1873.52  5109.0 1880.03  5128.2 1892.42  5138.6 1902.54
  5151.0 1910.76  5162.2 1914.29  5183.2 1923.33  5193.2 1925.66  5205.8 1930.31
#Mann=4,-1,0
  4793.5     0.1       0  5005.6    0.05       0  5009.6     0.1       0
  5047.6     0.1       0
Bank Sta=5005.6,5009.6
Exp/Cntr=0.3,0.1

Type RM Length L Ch R = 1,2337,454,454,454
BEGIN DESCRIPTION:
Stream0603 5.0
END DESCRIPTION:
XS GIS Cut Line= 3
      1898924.96     13889825.01      1899175.00     13889775.00
      1899375.01     13889624.99
#Sta/Elev= 30
  4740.5 1929.96  4764.8 1922.63  4783.1 1914.99  4810.6 1900.98  4816.8 1895.88
  4844.3 1879.49  4862.7 1870.94  4868.8 1866.95  4878.0 1862.78  4887.4 1856.56
  4919.3 1840.66  4959.7 1822.48  4980.0 1812.04  4980.2 1811.54  4984.0 1812.04
  4991.2 1814.01  5008.9 1814.66  5025.2 1819.42  5049.1 1822.11  5078.3 1828.99
  5088.6 1832.33  5101.1 1838.38  5113.3 1844.12  5133.6 1857.14  5153.3 1875.97
  5171.1 1895.51  5193.6 1912.70  5202.0 1917.01  5219.8 1922.96  5245.5 1928.57
#Mann=5,-1,0
  4740.5     0.1       0  4919.3    0.07       0  4980.0    0.05       0
  4984.0    0.07       0  5101.1     0.1       0
Bank Sta=4980,4984
Exp/Cntr=0.3,0.1

Type RM Length L Ch R = 1,1883,452,452,452
BEGIN DESCRIPTION:
Stream0603 4.0
END DESCRIPTION:
XS GIS Cut Line= 3
      1898924.96     13890074.99      1899225.00     13890175.00
      1899525.00     13890225.00
#Sta/Elev= 30
  4688.3 1915.66  4722.9 1900.15  4748.2 1885.73  4761.8 1879.96  4831.2 1846.93
  4846.2 1840.86  4863.8 1836.90  4882.8 1831.05  4911.2 1819.57  4936.2 1807.95
  4944.2 1805.57  4963.4 1802.78  4988.5 1800.94  5006.1 1798.26  5006.3 1797.76
  5010.1 1798.26  5015.7 1799.70  5035.5 1801.91  5065.2 1809.36  5105.4 1824.69
  5134.7 1838.23  5148.0 1845.50  5169.3 1855.37  5181.4 1859.82  5194.5 1866.14
  5233.1 1880.90  5260.5 1892.81  5279.0 1902.22  5284.9 1906.07  5308.7 1910.43
#Mann=5,-1,0
  4688.3     0.1       0  4936.2    0.07       0  5006.1    0.05       0
  5010.1    0.07       0  5134.7     0.1       0
Bank Sta=5006.1,5010.1
Exp/Cntr=0.3,0.1

Type RM Length L Ch R = 1,1431,458,458,458
BEGIN DESCRIPTION:
Stream0603 3.0
END DESCRIPTION:
XS GIS Cut Line= 3
      1898824.97     13890374.98      1899075.00     13890575.00
      1899374.96     13890774.97
#Sta/Elev= 30
  4684.8 1920.10  4715.4 1914.91  4728.4 1910.93  4815.7 1866.48  4829.2 1860.57
  4854.8 1843.38  4862.8 1836.52  4872.4 1831.21  4881.7 1821.70  4896.4 1810.24
  4910.9 1796.68  4920.2 1791.83  4956.6 1788.61  4990.7 1789.67  5008.0 1786.99
  5008.2 1786.49  5012.0 1786.99  5023.0 1792.54  5031.0 1795.14  5040.7 1798.47
  5062.4 1798.74  5081.4 1806.59  5137.6 1816.05  5165.0 1821.94  5214.7 1832.68
  5253.9 1845.19  5260.6 1847.18  5320.7 1868.91  5355.3 1883.45  5365.5 1889.17
#Mann=7,-1,0
  4684.8     0.1       0  5008.0    0.05       0  5012.0     0.1       0
  5031.0    0.07       0  5165.0     0.1       0  5253.9    0.07       0
  5260.6     0.1       0
Bank Sta=5008,5012
Exp/Cntr=0.3,0.1

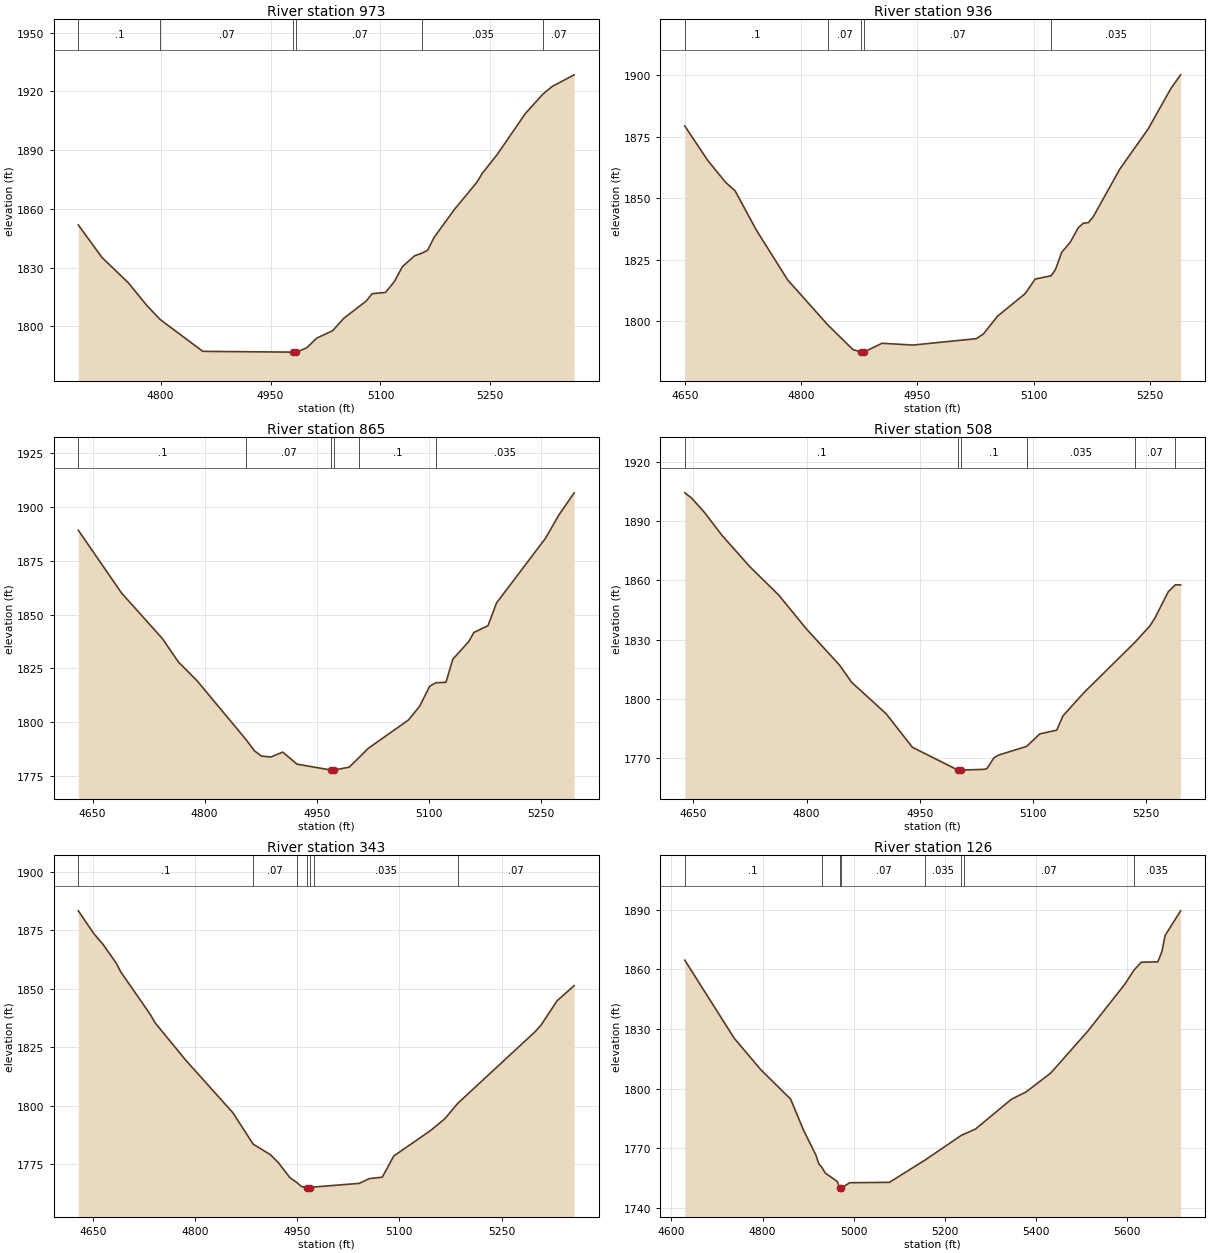
Type RM Length L Ch R = 1,973,37,37,37
BEGIN DESCRIPTION:
Stream0603 2.0
END DESCRIPTION:
XS GIS Cut Line= 3
      1898725.02     13890825.01      1899025.00     13890925.00
      1899325.03     13891125.02
#Sta/Elev= 30
  4687.6 1851.80  4719.9 1835.15  4755.8 1822.26  4781.1 1810.65  4799.4 1803.44
  4857.5 1787.21  4981.2 1786.80  4981.5 1786.30  4985.2 1786.80  4999.3 1788.99
  5013.1 1793.99  5034.7 1797.75  5049.9 1804.07  5080.2 1812.79  5088.8 1816.69
  5106.9 1817.31  5119.1 1822.93  5130.0 1830.49  5146.5 1836.02  5157.1 1837.44
  5164.5 1838.92  5173.2 1845.41  5201.3 1859.88  5231.6 1873.57  5238.7 1878.02
  5259.2 1887.69  5297.9 1908.75  5321.8 1918.66  5334.6 1922.59  5364.4 1928.48
#Mann=6,-1,0
  4687.6     0.1       0  4799.4    0.07       0  4981.2    0.05       0
  4985.2    0.07       0  5157.1   0.035       0  5321.8    0.07       0
Bank Sta=4981.2,4985.2
Exp/Cntr=0.3,0.1

Type RM Length L Ch R = 1,936,71,71,71
BEGIN DESCRIPTION:
Stream0603 4.1
END DESCRIPTION:
XS GIS Cut Line= 4
      1898659.38     13890866.01      1898917.23     13890941.55
      1899034.42     13890957.17      1899237.44     13891108.13
#Sta/Elev= 30
  4649.8 1879.43  4679.4 1865.44  4702.6 1856.46  4714.7 1853.09  4741.9 1837.24
  4782.5 1816.87  4834.2 1798.61  4866.9 1788.49  4877.4 1787.58  4877.7 1787.08
  4881.4 1787.58  4904.4 1791.09  4944.2 1790.36  5025.9 1792.96  5035.2 1794.87
  5053.3 1802.07  5089.1 1811.28  5101.9 1817.18  5122.7 1818.55  5128.1 1821.02
  5136.3 1828.10  5147.3 1832.18  5157.7 1838.12  5164.2 1839.92  5170.6 1840.14
  5176.7 1842.40  5211.3 1861.95  5247.9 1878.26  5277.0 1894.61  5289.7 1900.23
#Mann=5,-1,0
  4649.8     0.1       0  4834.2    0.07       0  4877.4    0.05       0
  4881.4    0.07       0  5122.7   0.035       0
Bank Sta=4877.4,4881.4
Exp/Cntr=0.3,0.1

Type RM Length L Ch R = 1,865,357,357,357
BEGIN DESCRIPTION:
Mapping XS b0f729f9
END DESCRIPTION:
XS GIS Cut Line= 3
      1898624.08     13890896.59      1899094.82     13891058.42
      1899226.06     13891159.61
#Sta/Elev= 30
  4631.0 1889.11  4688.8 1860.01  4743.6 1838.79  4764.9 1827.97  4790.2 1819.13
  4855.6 1791.87  4866.5 1786.80  4876.0 1784.27  4888.7 1783.87  4904.5 1786.14
  4923.6 1780.56  4969.1 1777.80  4969.4 1777.30  4973.1 1777.80  4993.4 1779.14
  5006.3 1783.47  5018.7 1787.80  5072.7 1801.02  5087.6 1807.36  5101.2 1816.72
  5109.3 1818.31  5123.0 1818.55  5132.1 1829.24  5153.5 1837.47  5160.3 1841.66
  5179.2 1844.82  5190.6 1855.36  5256.2 1885.42  5273.9 1896.14  5294.5 1906.50
#Mann=6,-1,0
  4631.0     0.1       0  4855.6    0.07       0  4969.1    0.05       0
  4973.1    0.07       0  5006.3     0.1       0  5109.3   0.035       0
Bank Sta=4969.1,4973.1
Exp/Cntr=0.3,0.1

Type RM Length L Ch R = 1,508,165,165,165
BEGIN DESCRIPTION:
Stream0603 1.0
END DESCRIPTION:
XS GIS Cut Line= 3
      1898474.97     13891024.97      1898725.00     13891275.00
      1899024.96     13891324.99
#Sta/Elev= 30
  4638.5 1904.18  4647.7 1901.47  4664.7 1894.23  4688.0 1882.60  4725.1 1866.72
  4763.3 1852.42  4799.4 1835.55  4843.9 1817.03  4859.8 1808.40  4905.5 1792.53
  4940.4 1775.55  5001.0 1763.99  5001.2 1763.49  5005.0 1763.99  5036.5 1764.42
  5039.5 1764.90  5048.5 1770.21  5054.7 1771.60  5091.9 1775.99  5109.4 1782.31
  5131.9 1784.22  5139.9 1791.25  5142.4 1792.40  5168.4 1803.34  5235.9 1828.74
  5255.4 1836.91  5262.3 1841.01  5279.8 1854.16  5289.2 1857.71  5296.2 1857.61
#Mann=6,-1,0
  4638.5     0.1       0  5001.0    0.05       0  5005.0     0.1       0
  5091.9   0.035       0  5235.9    0.07       0  5289.2   0.035       0
Bank Sta=5001,5005
Exp/Cntr=0.3,0.1

Type RM Length L Ch R = 1,343,217,217,217
BEGIN DESCRIPTION:
Stream0603 0.1
END DESCRIPTION:
XS GIS Cut Line= 4
      1898425.04     13891149.87      1898633.38     13891345.19
      1898742.75     13891441.55      1899039.63     13891451.96
#Sta/Elev= 30
  4628.3 1883.26  4651.2 1873.47  4665.1 1868.74  4684.1 1860.86  4690.6 1857.18
  4733.5 1839.20  4741.3 1835.32  4786.1 1819.44  4855.4 1796.98  4885.1 1783.58
  4910.3 1779.10  4922.4 1775.58  4938.9 1769.32  4949.9 1767.04  4955.9 1765.53
  4964.6 1764.85  4964.8 1764.35  4968.6 1764.85  4973.9 1765.24  5041.0 1766.81
  5055.8 1768.84  5074.8 1769.45  5091.7 1778.50  5145.7 1789.37  5166.7 1794.43
  5185.6 1800.97  5298.8 1831.47  5307.8 1834.33  5331.8 1844.89  5356.7 1851.30
#Mann=7,-1,0
  4628.3     0.1       0  4885.1    0.07       0  4949.9     0.1       0
  4964.6   0.035       0  4968.6     0.1       0  4973.9   0.035       0
  5185.6    0.07       0
Bank Sta=4964.6,4968.6
Exp/Cntr=0.3,0.1

Type RM Length L Ch R = 1,126,0,0,0
BEGIN DESCRIPTION:
Stream0603 0.0
END DESCRIPTION:
XS GIS Cut Line= 4
      1898410.94     13891221.49      1898485.80     13891506.16
      1898599.75     13891600.34      1899244.82     13891565.41
#Sta/Elev= 30
  4629.3 1864.67  4737.6 1825.38  4796.5 1809.38  4861.6 1794.65  4889.6 1779.16
  4917.5 1766.22  4923.6 1761.97  4929.4 1760.52  4937.8 1757.35  4963.8 1753.19
  4969.2 1749.80  4969.5 1749.30  4973.2 1749.80  4991.0 1752.52  5078.5 1752.73
  5157.0 1764.02  5236.5 1776.44  5242.4 1777.02  5267.3 1779.57  5345.9 1794.55
  5378.9 1798.36  5432.6 1807.83  5514.1 1828.98  5595.2 1852.62  5615.1 1859.66
  5631.3 1863.65  5667.4 1863.81  5676.4 1868.94  5683.4 1877.09  5717.5 1889.53
#Mann=8,-1,0
  4629.3     0.1       0  4929.4    0.07       0  4969.2    0.05       0
  4973.2    0.07       0  5157.0   0.035       0  5236.5     0.1       0
  5242.4    0.07       0  5615.1   0.035       0
Bank Sta=4969.2,4973.2
Exp/Cntr=0.3,0.1

Chan Stop Cuts=-1