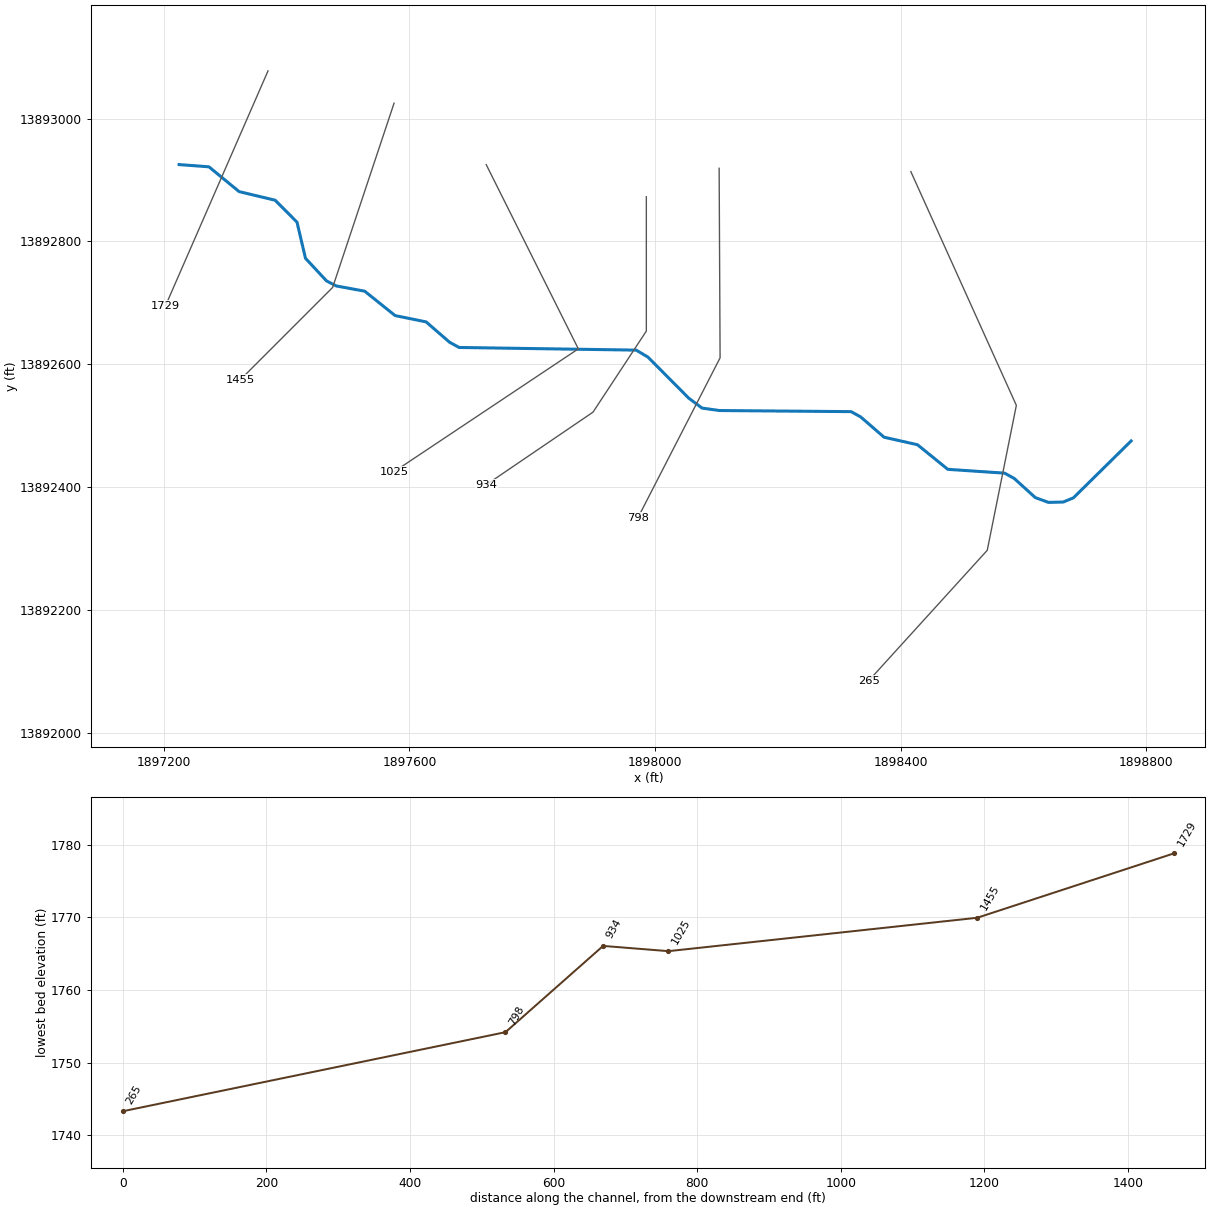
--- Stream0604.prj (project) ---

Proj Title=Stream0604 Base Level Engineering
Current Plan=p01
Default Exp/Contr=0.3,0.1
English Units
Geom File=g01
Flow File=f01
Plan File=p01
BEGIN DESCRIPTION:
Stream0604
END DESCRIPTION:

--- Stream0604.p01 (plan) ---

Plan Title=Multiple Run
Short Identifier=Multiple
Geom File=g01
Flow File=f01
Subcritical Flow
K Sum by GR= 0
Std Step Tol= 0.01
Critical Tol= 0.01
Num of Std Step Trials= 20
Max Error Tol= 0.3
Flow Tol Ratio= 0.001
Split Flow NTrial= 30
Split Flow Tol= 0.02
Split Flow Ratio= 0.02
Log Output Level= 0
Friction Slope Method= 1
Unsteady Friction Slope Method= 2
Unsteady Bridges Friction Slope Method= 1
Parabolic Critical Depth
Global Vel Dist=  1 , 1 , 1
Global Log Level= 0
CheckData=True
Encroach Param= -1, 0, 0, 0
BEGIN DESCRIPTION:
Multiple Run
END DESCRIPTION:

--- Stream0604.f01 (steady flow) ---

Flow Title=Multiple
Number of Profiles=7
Profile Names=10-year,25-year,50-year,1pct_min,100-year,1pct_plu,500-year
River Rch & RM= Stream0604,Reach-1,1729
     780    1304    1795    1199    2392    4773    4185
Boundary for River Rch & Prof#=Stream0604,Reach-1,1
Up Type=0
Dn Type=3
Dn Slope=0.005
Boundary for River Rch & Prof#=Stream0604,Reach-1,2
Up Type=0
Dn Type=3
Dn Slope=0.005
Boundary for River Rch & Prof#=Stream0604,Reach-1,3
Up Type=0
Dn Type=3
Dn Slope=0.005
Boundary for River Rch & Prof#=Stream0604,Reach-1,4
Up Type=0
Dn Type=3
Dn Slope=0.005
Boundary for River Rch & Prof#=Stream0604,Reach-1,5
Up Type=0
Dn Type=3
Dn Slope=0.005
Boundary for River Rch & Prof#=Stream0604,Reach-1,6
Up Type=0
Dn Type=3
Dn Slope=0.005
Boundary for River Rch & Prof#=Stream0604,Reach-1,7
Up Type=0
Dn Type=3
Dn Slope=0.005

--- Stream0604.g01 (geometry) ---

Geom Title=Existing Conditions

River Reach=Stream0604,Reach-1
Reach XY= 30
      1897225.00     13892925.00      1897273.51     13892921.40
      1897322.79     13892880.99      1897381.35     13892866.99
      1897416.95     13892831.31      1897430.76     13892772.49
      1897465.00     13892735.63      1897480.85     13892727.42
      1897527.16     13892718.89      1897576.72     13892679.16
      1897627.18     13892668.88      1897665.33     13892635.80
      1897680.93     13892627.24      1897969.14     13892622.93
      1897988.31     13892611.60      1898054.85     13892544.65
      1898076.47     13892528.55      1898104.82     13892524.57
      1898319.07     13892522.76      1898334.67     13892514.20
      1898372.82     13892481.12      1898427.18     13892468.89
      1898476.58     13892428.83      1898569.03     13892422.62
      1898584.65     13892414.05      1898619.08     13892382.79
      1898640.41     13892375.02      1898664.38     13892375.55
      1898681.08     13892382.38      1898775.00     13892475.00

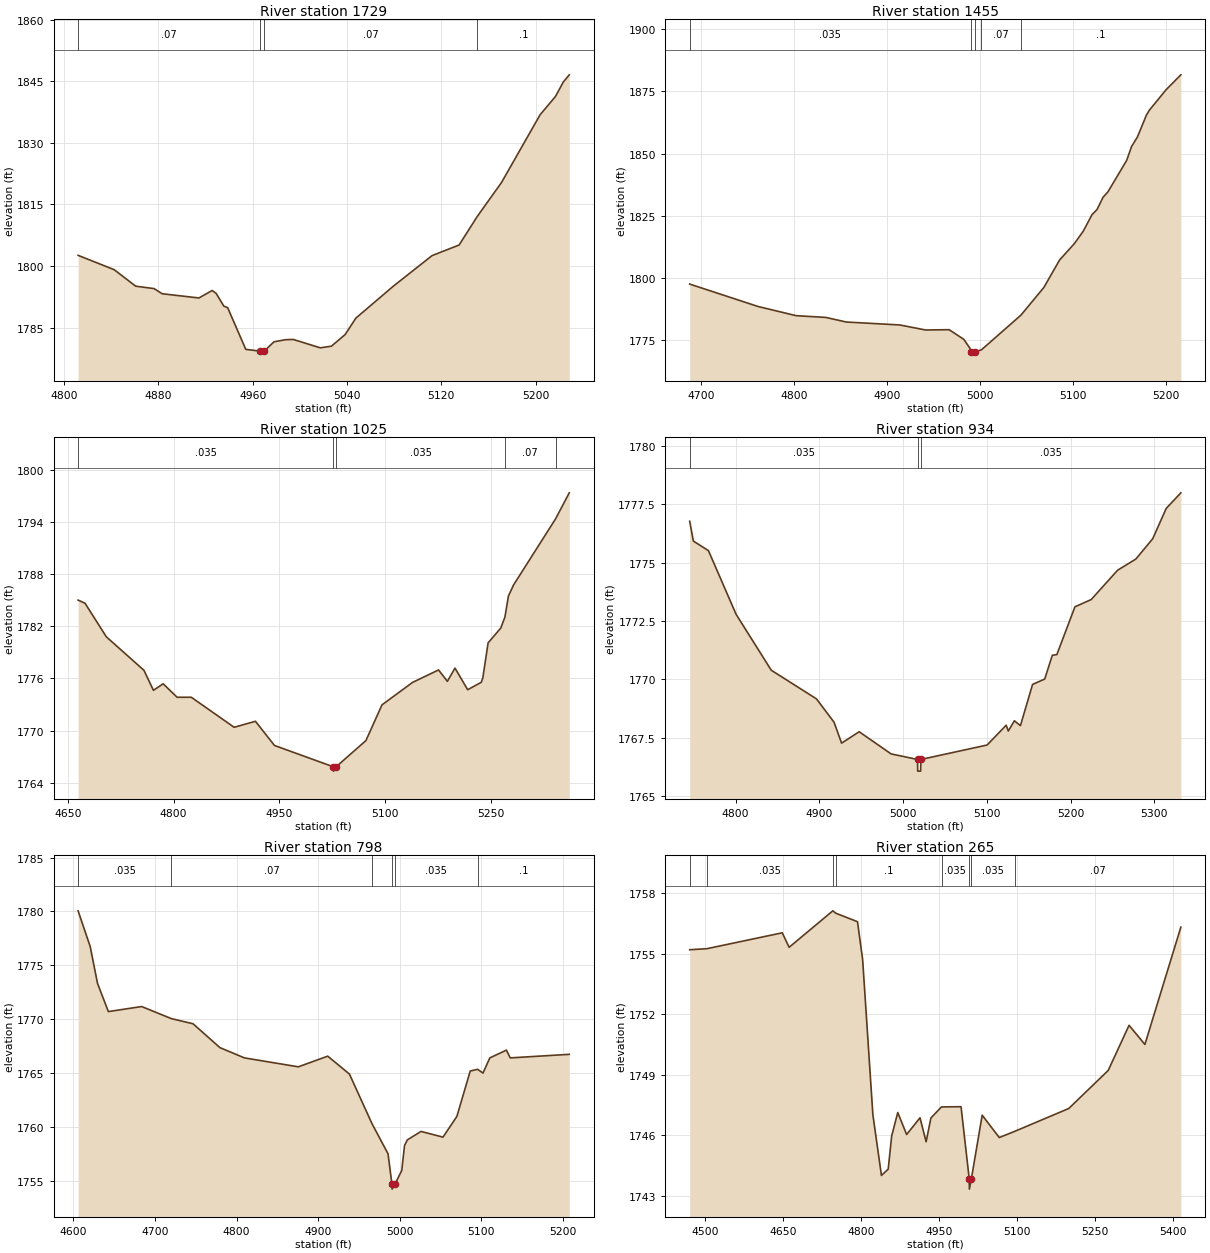
Type RM Length L Ch R = 1,1729,274,274,274
BEGIN DESCRIPTION:
Stream0604 3.0
END DESCRIPTION:
XS GIS Cut Line= 2
      1897369.75     13893077.52      1897203.05     13892695.51
#Sta/Elev= 30
  4811.8 1802.59  4842.4 1799.10  4860.7 1795.08  4876.3 1794.49  4883.1 1793.24
  4914.3 1792.21  4925.6 1794.03  4928.9 1793.34  4935.5 1790.22  4938.7 1789.86
  4954.1 1779.70  4965.8 1779.28  4966.0 1778.78  4969.8 1779.28  4978.0 1781.53
  4987.8 1782.05  4994.4 1782.11  5017.3 1780.07  5026.8 1780.48  5038.4 1783.30
  5047.5 1787.30  5079.3 1795.08  5112.2 1802.53  5135.1 1805.10  5150.6 1812.08
  5171.1 1820.32  5203.9 1836.84  5216.9 1841.27  5223.5 1844.77  5228.6 1846.54
#Mann=4,-1,0
  4811.8    0.07       0  4965.8    0.05       0  4969.8    0.07       0
  5150.6     0.1       0
Bank Sta=4965.8,4969.8
Exp/Cntr=0.3,0.1

Type RM Length L Ch R = 1,1455,430,430,430
BEGIN DESCRIPTION:
Stream0604 2.0
END DESCRIPTION:
XS GIS Cut Line= 3
      1897575.00     13893025.00      1897475.00     13892725.00
      1897324.97     13892574.97
#Sta/Elev= 30
  4687.9 1797.63  4761.5 1788.63  4802.5 1784.95  4834.2 1784.26  4856.4 1782.41
  4914.0 1781.23  4941.7 1779.21  4967.0 1779.33  4982.8 1775.46  4989.2 1771.99
  4990.3 1770.43  4990.5 1769.93  4994.3 1770.43  5001.8 1771.26  5044.2 1785.15
  5068.9 1796.26  5085.9 1807.32  5101.7 1813.84  5111.3 1818.85  5120.8 1825.52
  5126.1 1827.52  5132.6 1832.46  5137.8 1834.60  5158.0 1847.24  5163.3 1852.83
  5169.6 1856.64  5179.2 1865.37  5182.4 1867.37  5200.4 1875.58  5216.3 1881.57
#Mann=5,-1,0
  4687.9   0.035       0  4990.3   0.035       0  4994.3   0.035       0
  5001.8    0.07       0  5044.2     0.1       0
Bank Sta=4990.3,4994.3
Exp/Cntr=0.3,0.1

Type RM Length L Ch R = 1,1025,91,91,91
BEGIN DESCRIPTION:
Stream0604 1.0
END DESCRIPTION:
XS GIS Cut Line= 3
      1897725.01     13892924.98      1897875.00     13892625.00
      1897575.04     13892425.02
#Sta/Elev= 30
  4664.7 1785.00  4674.5 1784.64  4704.7 1780.78  4758.0 1776.93  4771.4 1774.63
  4785.2 1775.38  4805.0 1773.83  4825.1 1773.83  4885.8 1770.38  4916.0 1771.07
  4942.9 1768.29  5026.3 1765.84  5026.5 1765.34  5030.3 1765.84  5072.5 1768.85
  5095.3 1772.96  5138.6 1775.54  5175.4 1776.97  5187.9 1775.66  5198.7 1777.18
  5216.7 1774.70  5235.9 1775.55  5238.1 1776.05  5245.6 1780.08  5263.6 1781.79
  5269.4 1783.04  5274.4 1785.46  5281.6 1786.73  5341.3 1794.35  5360.6 1797.33
#Mann=5,-1,0
  4664.7   0.035       0  5026.3   0.035       0  5030.3   0.035       0
  5269.4    0.07       0  5341.3   0.035       0
Bank Sta=5026.3,5030.3
Exp/Cntr=0.3,0.1

Type RM Length L Ch R = 1,934,136,136,136
BEGIN DESCRIPTION:
Stream0605 0.3
END DESCRIPTION:
XS GIS Cut Line= 4
      1897985.74     13892872.60      1897985.74     13892653.90
      1897898.94     13892521.96      1897725.32     13892403.89
#Sta/Elev= 30
  4745.1 1776.78  4749.5 1775.93  4767.5 1775.52  4800.5 1772.79  4842.5 1770.39
  4896.5 1769.16  4917.5 1768.16  4926.5 1767.26  4947.5 1767.75  4985.6 1766.80
  5017.2 1766.56  5017.4 1766.06  5020.9 1766.06  5021.2 1766.56  5100.3 1767.18
  5123.1 1768.03  5125.6 1767.78  5132.9 1768.22  5140.1 1768.01  5154.6 1769.78
  5169.1 1770.01  5178.2 1771.03  5183.6 1771.06  5205.2 1773.11  5224.6 1773.42
  5256.2 1774.68  5278.0 1775.16  5298.1 1776.03  5314.2 1777.33  5331.7 1778.00
#Mann=3,-1,0
  4745.1   0.035       0  5017.2   0.035       0  5021.2   0.035       0
Bank Sta=5017.2,5021.2
Exp/Cntr=0.3,0.1

Type RM Length L Ch R = 1,798,533,533,533
BEGIN DESCRIPTION:
Mapping XS b0052607
END DESCRIPTION:
XS GIS Cut Line= 3
      1898104.29     13892919.00      1898105.82     13892610.37
      1897971.91     13892349.68
#Sta/Elev= 30
  4605.9 1780.05  4620.7 1776.74  4629.7 1773.31  4643.0 1770.69  4683.7 1771.16
  4720.1 1770.04  4746.7 1769.56  4779.7 1767.34  4809.7 1766.39  4875.7 1765.56
  4911.7 1766.55  4938.3 1764.89  4965.8 1760.30  4985.6 1757.48  4990.3 1754.70
  4990.6 1754.20  4994.3 1754.70  5002.4 1755.93  5005.8 1758.25  5009.2 1758.77
  5026.0 1759.56  5052.9 1759.03  5069.9 1760.95  5086.3 1765.17  5095.3 1765.33
  5101.9 1764.98  5110.3 1766.39  5130.6 1767.11  5135.3 1766.39  5207.6 1766.72
#Mann=6,-1,0
  4605.9   0.035       0  4720.1    0.07       0  4965.8   0.035       0
  4990.3   0.035       0  4994.3   0.035       0  5095.3     0.1       0
Bank Sta=4990.3,4994.3
Exp/Cntr=0.3,0.1

Type RM Length L Ch R = 1,265,0,0,0
BEGIN DESCRIPTION:
Stream0604 0.0
END DESCRIPTION:
XS GIS Cut Line= 4
      1898416.38     13892913.60      1898588.18     13892533.02
      1898540.81     13892297.00      1898347.69     13892084.53
#Sta/Elev= 30
  4470.5 1755.21  4503.5 1755.26  4648.7 1756.05  4661.9 1755.33  4746.0 1757.14
  4751.9 1757.02  4793.5 1756.60  4803.4 1754.72  4823.1 1747.02  4839.6 1744.01
  4852.6 1744.32  4859.3 1745.97  4871.0 1747.13  4888.1 1746.04  4913.8 1746.87
  4925.6 1745.68  4934.8 1746.86  4955.2 1747.41  4992.8 1747.42  5008.6 1743.83
  5008.8 1743.33  5012.6 1743.83  5033.5 1747.00  5066.4 1745.89  5096.4 1746.20
  5200.1 1747.33  5276.1 1749.22  5316.2 1751.46  5346.7 1750.51  5415.9 1756.33
#Mann=8,-1,0
  4470.5    0.07       0  4503.5   0.035       0  4746.0    0.07       0
  4751.9     0.1       0  4955.2   0.035       0  5008.6   0.035       0
  5012.6   0.035       0  5096.4    0.07       0
Bank Sta=5008.6,5012.6
Exp/Cntr=0.3,0.1

Chan Stop Cuts=-1