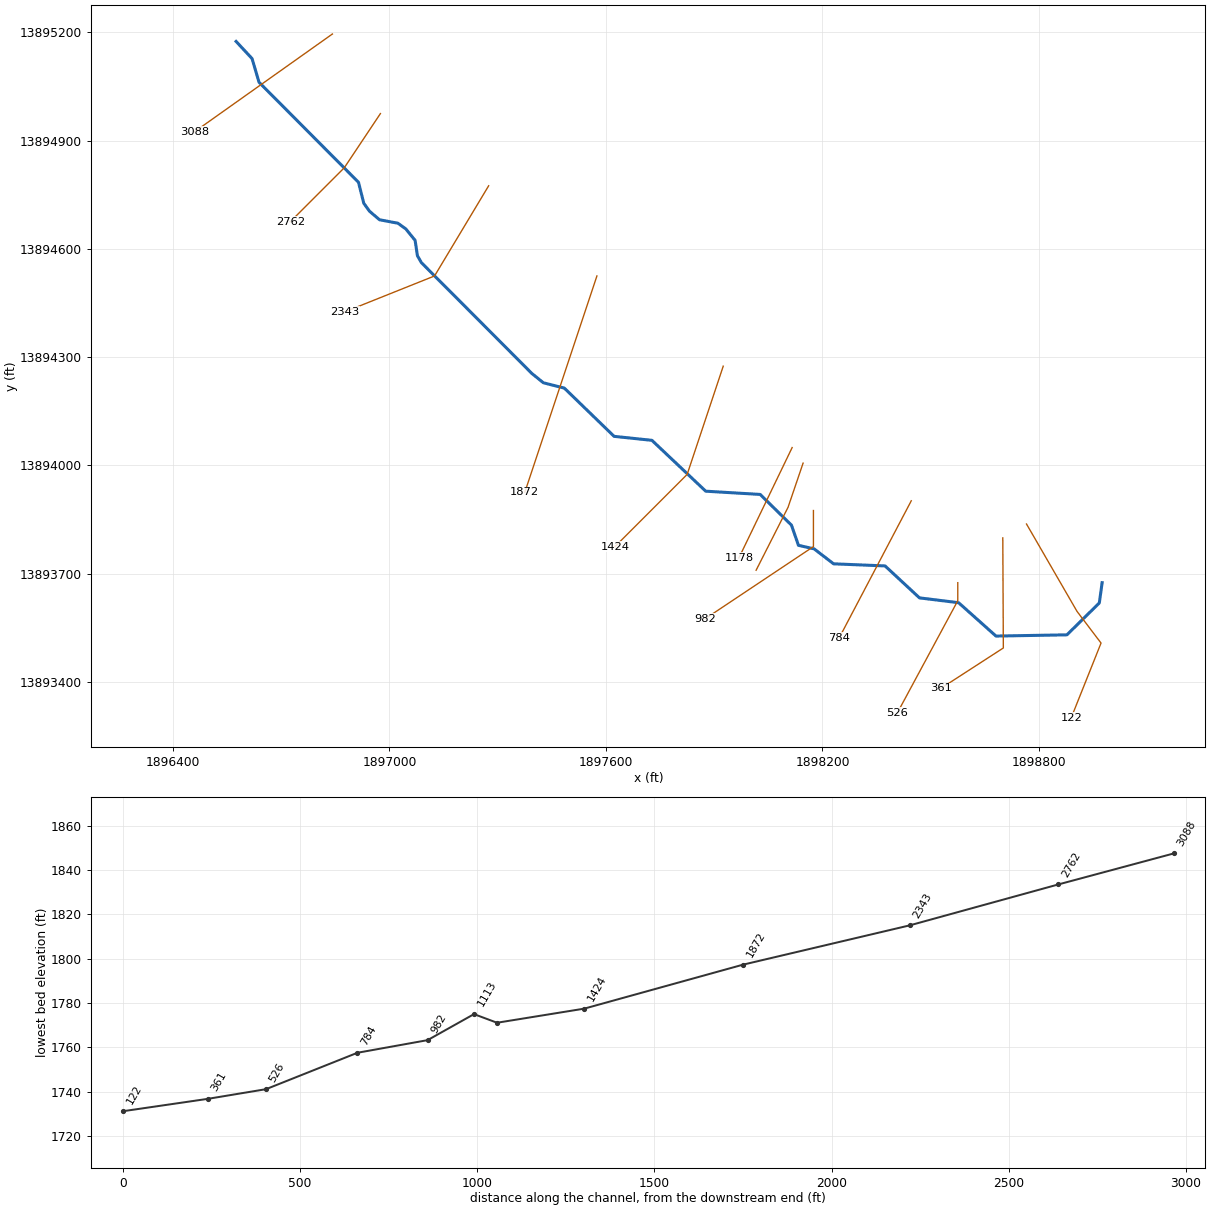
--- Stream0605.prj (project) ---

Proj Title=Stream0605 Base Level Engineering
Current Plan=p01
Default Exp/Contr=0.3,0.1
English Units
Geom File=g01
Flow File=f01
Plan File=p01
Y Axis Title=Elevation
X Axis Title(PF)=Main Channel Distance
X Axis Title(XS)=Station
BEGIN DESCRIPTION:
Stream0605
END DESCRIPTION:
DSS Export Rating Curves= 0
DSS Export Rating Curve Sorted= 0
DSS Export Volume Flow Curves= 0
DXF OffsetX= 0
DXF OffsetY= 0
DXF ScaleX= 1
DXF ScaleY= 10

--- Stream0605.p01 (plan) ---

Plan Title=Multiple Run
Short Identifier=Multiple
Geom File=g01
Flow File=f01
Subcritical Flow
K Sum by GR= 0
Std Step Tol= 0.01
Critical Tol= 0.01
Num of Std Step Trials= 20
Max Error Tol= 0.3
Flow Tol Ratio= 0.001
Split Flow NTrial= 30
Split Flow Tol= 0.02
Split Flow Ratio= 0.02
Log Output Level= 0
Friction Slope Method= 1
Unsteady Friction Slope Method= 2
Unsteady Bridges Friction Slope Method= 1
Parabolic Critical Depth
Global Vel Dist=  1 , 1 , 1
Global Log Level= 0
CheckData=True
Encroach Param= -1, 0, 0, 0
BEGIN DESCRIPTION:
Multiple Run
END DESCRIPTION:

--- Stream0605.f01 (steady flow) ---

Flow Title=Multiple
Number of Profiles=7
Profile Names=10-year,25-year,50-year,1pct_min,100-year,1pct_plu,500-year
River Rch & RM= Stream0605,Reach-1,3088
     226     347     451     287     572    1141     900
River Rch & RM= Stream0605,Reach-1,2343
     462     748    1008     661    1319    2632    2221
Boundary for River Rch & Prof#=Stream0605,Reach-1,1
Up Type=0
Dn Type=3
Dn Slope=0.005
Boundary for River Rch & Prof#=Stream0605,Reach-1,2
Up Type=0
Dn Type=3
Dn Slope=0.005
Boundary for River Rch & Prof#=Stream0605,Reach-1,3
Up Type=0
Dn Type=3
Dn Slope=0.005
Boundary for River Rch & Prof#=Stream0605,Reach-1,4
Up Type=0
Dn Type=3
Dn Slope=0.005
Boundary for River Rch & Prof#=Stream0605,Reach-1,5
Up Type=0
Dn Type=3
Dn Slope=0.005
Boundary for River Rch & Prof#=Stream0605,Reach-1,6
Up Type=0
Dn Type=3
Dn Slope=0.005
Boundary for River Rch & Prof#=Stream0605,Reach-1,7
Up Type=0
Dn Type=3
Dn Slope=0.005

--- Stream0605.g01 (geometry) ---

Geom Title=Existing Conditions
Program Version=4.10

River Reach=Stream0605      ,Reach-1
Reach XY= 30
        1896575.       13895175.      1896619.29     13895127.35
      1896638.57     13895061.77      1896914.21     13894784.66
      1896928.89     13894726.43      1896944.64     13894704.53
      1896972.49     13894680.76      1897023.54      13894671.1
      1897045.46     13894655.36      1897071.11     13894623.57
      1897077.55     13894581.09      1897088.64      13894561.8
      1897394.84     13894254.62      1897426.65     13894228.98
      1897484.68     13894214.22      1897622.57     13894080.52
      1897727.43     13894069.48      1897876.47     13893928.54
      1898027.46     13893919.54      1898114.12     13893834.44
      1898133.48     13893778.51      1898176.84     13893768.72
      1898230.91     13893727.24      1898373.53     13893721.44
      1898468.84     13893632.88      1898577.42     13893619.46
      1898680.86     13893527.06      1898877.47     13893530.44
      1898967.25     13893618.76        1898975.       13893675.

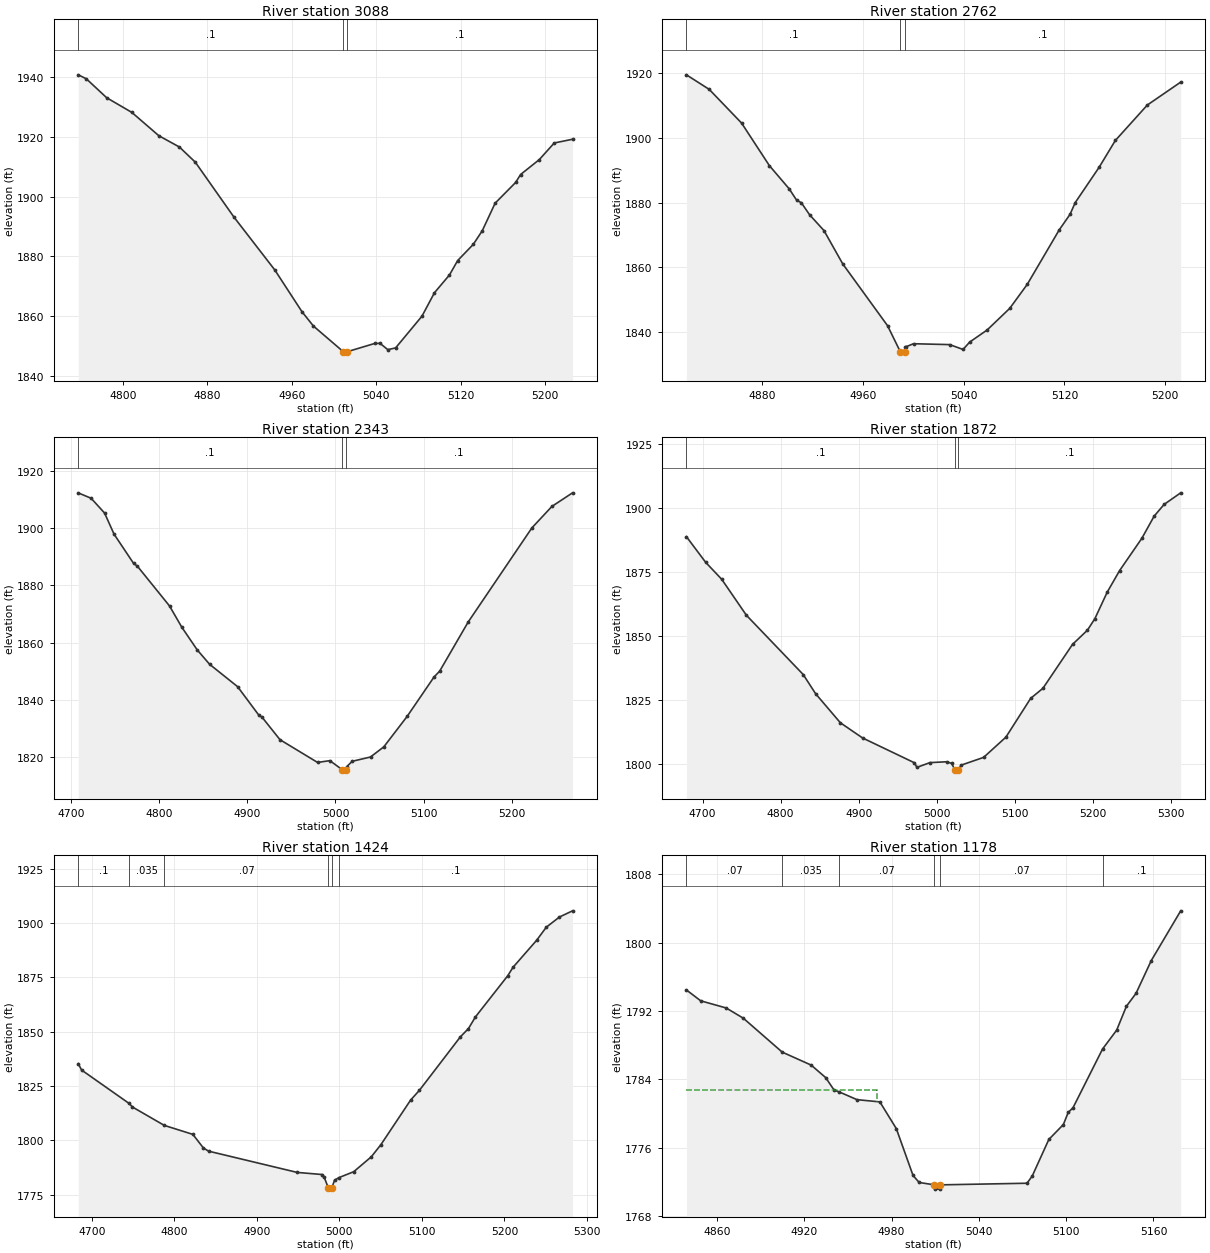
Type RM Length L Ch R = 1 ,3088    ,326,326,326
BEGIN DESCRIPTION:
Stream0605 7.0
END DESCRIPTION:
XS GIS Cut Line= 2
      1896841.96     13895195.55      1896460.03     13894924.73
#Sta/Elev= 30
  4757.7 1940.77  4765.3 1939.45  4784.6  1933.1  4808.5 1928.17    4834 1920.38
  4853.5 1916.59  4868.6  1911.5  4905.1 1893.15  4943.9 1875.39  4969.7 1861.37
  4980.5  1856.6  5008.7 1848.04    5009 1847.54  5012.7 1848.04  5038.6 1850.79
  5043.6 1850.81  5050.9 1848.71  5058.3 1849.28  5083.3 1859.93  5095.1 1867.77
  5109.3 1873.71  5117.1 1878.55  5131.9 1883.98  5140.4 1888.54  5152.6 1897.78
    5172 1904.71  5176.7 1907.37  5194.4 1912.37  5208.6 1917.94  5225.9 1919.19
#Mann= 3 ,-1 , 0
  4757.7      .1       0  5008.7     .05       0  5012.7      .1       0
Bank Sta=5008.7,5012.7
XS Rating Curve= 0 ,0
Exp/Cntr=0.3,0.1

Type RM Length L Ch R = 1 ,2762    ,419,419,419
BEGIN DESCRIPTION:
Stream0605 6.0
END DESCRIPTION:
XS GIS Cut Line= 3
      1896975.02     13894975.03        1896875.       13894825.
      1896725.03     13894675.03
#Sta/Elev= 30
  4819.9 1919.41    4838 1914.92  4863.7 1904.52  4885.8 1891.37  4901.5 1884.23
  4907.4 1880.72  4911.1 1879.96  4917.7 1876.22  4929.1 1871.36    4944 1861.07
  4979.6 1841.99  4989.6 1834.04  4989.9 1833.54  4993.6 1834.04  4993.8 1835.35
    4994 1835.47  5000.2 1836.44  5028.9 1836.17  5039.5 1834.67  5044.8 1836.96
  5058.6 1840.67  5076.6 1847.36  5090.5 1854.77  5115.9 1871.59  5124.4 1876.33
  5128.6 1880.01  5147.6 1890.92  5160.4 1899.15  5185.8 1910.09  5212.3 1917.16
#Mann= 3 ,-1 , 0
  4819.9      .1       0  4989.6     .05       0  4993.6      .1       0
Bank Sta=4989.6,4993.6
XS Rating Curve= 0 ,0
Exp/Cntr=0.3,0.1

Type RM Length L Ch R = 1 ,2343    ,471,471,471
BEGIN DESCRIPTION:
Stream0605 5.0
END DESCRIPTION:
XS GIS Cut Line= 3
      1897274.99     13894774.99        1897125.       13894525.
      1896874.99       13894425.
#Sta/Elev= 30
  4708.2 1912.31  4722.8 1910.43  4738.1 1905.25  4748.8  1897.9  4770.9 1887.71
  4775.3  1886.7  4811.8 1872.78  4825.7 1865.37  4843.2 1857.44  4857.2 1852.43
    4889  1844.6    4913 1834.68  4916.7 1833.95  4937.1 1826.07  4979.7 1818.13
  4993.7 1818.75  5007.7 1815.59  5007.9 1815.09  5011.7 1815.59  5012.9 1816.68
    5019 1818.52  5039.8 1820.03  5054.9 1823.58  5081.3 1834.19  5111.8 1847.95
  5118.3 1850.05  5150.6 1867.19  5222.9 1900.08  5245.6 1907.58    5269 1912.33
#Mann= 3 ,-1 , 0
  4708.2      .1       0  5007.7     .05       0  5011.7      .1       0
Bank Sta=5007.7,5011.7
XS Rating Curve= 0 ,0
Exp/Cntr=0.3,0.1

Type RM Length L Ch R = 1 ,1872    ,448,448,448
BEGIN DESCRIPTION:
Stream0605 4.0
END DESCRIPTION:
XS GIS Cut Line= 3
      1897575.01     13894525.04        1897475.       13894225.
        1897375.       13893925.
#Sta/Elev= 30
  4679.4 1888.79    4704 1878.79  4724.6 1872.15  4756.1 1858.15  4828.9 1834.99
  4844.7 1827.53  4876.4 1816.19  4904.8 1810.27  4971.2 1800.58  4974.3 1798.79
    4991 1800.65  5012.3 1800.98  5018.7 1800.37    5023 1797.83  5023.2 1797.33
    5027 1797.83  5031.2 1799.69  5059.7 1802.69  5088.2 1810.58  5119.9 1825.71
  5135.6 1829.64  5173.5 1846.78  5192.5  1852.3    5202 1856.76  5217.9 1867.16
  5233.7 1875.55  5262.2 1888.16  5277.9 1896.78  5290.6 1901.35  5311.9 1905.89
#Mann= 3 ,-1 , 0
  4679.4      .1       0    5023     .05       0    5027      .1       0
Bank Sta=5023,5027
XS Rating Curve= 0 ,0
Exp/Cntr=0.3,0.1

Type RM Length L Ch R = 1 ,1424    ,246,246,246
BEGIN DESCRIPTION:
Stream0605 3.0
END DESCRIPTION:
XS GIS Cut Line= 3
        1897925.       13894275.        1897825.       13893975.
      1897624.98     13893774.98
#Sta/Elev= 30
  4683.5 1835.23  4687.5 1832.31  4745.2 1816.91  4749.2 1815.28  4787.8 1806.82
  4822.4 1802.69  4835.1 1796.46  4841.4 1794.97  4948.9 1785.18  4979.2 1784.21
  4981.6 1782.94  4986.7 1777.99    4987 1777.49  4990.7 1777.99  4994.2 1781.59
  4999.4 1782.78  5017.4 1785.51  5038.7 1792.37  5050.4 1797.99  5086.3 1818.45
    5097 1822.96  5146.8 1847.64  5156.4 1851.34  5164.9 1856.74  5204.1  1875.7
  5210.5  1879.6  5239.1 1892.01  5250.8 1898.03  5266.7 1902.71  5282.6 1905.57
#Mann= 6 ,-1 , 0
  4683.5      .1       0  4745.2    .035       0  4787.8     .07       0
  4986.7     .05       0  4990.7     .07       0  4999.4      .1       0
Bank Sta=4986.7,4990.7
XS Rating Curve= 0 ,0
Exp/Cntr=0.3,0.1

Type RM Length L Ch R = 1 ,1178    ,65,65,65
BEGIN DESCRIPTION:
Mapping XS 06190309
END DESCRIPTION:
XS GIS Cut Line= 2
      1898116.01     13894049.43      1897968.44     13893743.57
#Sta/Elev= 30
  4839.1 1794.46  4848.9 1793.19  4866.4 1792.35  4878.2 1791.15  4904.9 1787.18
  4924.8 1785.66  4934.8 1784.19  4940.6 1782.72  4943.9 1782.53  4956.3 1781.61
    4972 1781.35  4983.3 1778.22  4994.8 1772.73    4999 1771.91  5009.5 1771.63
  5009.7 1771.13  5013.2 1771.13  5013.5 1771.63  5073.1 1771.82  5076.7 1772.67
  5088.1 1776.95  5098.1  1778.7  5101.4 1780.11  5104.7 1780.66    5125 1787.54
  5134.7 1789.75  5141.4 1792.55    5148 1794.06  5158.5 1797.91  5178.7 1803.73
#Mann= 6 ,-1 , 0
  4839.1     .07       0  4904.9    .035       0  4943.9     .07       0
  5009.5     .05       0  5013.5     .07       0    5125      .1       0
#XS Ineff= 2 , 0
         4970.23 1782.71
Permanent Ineff=
       F       F
Bank Sta=5009.5,5013.5
XS Rating Curve= 0 ,0
Exp/Cntr=0.3,0.1

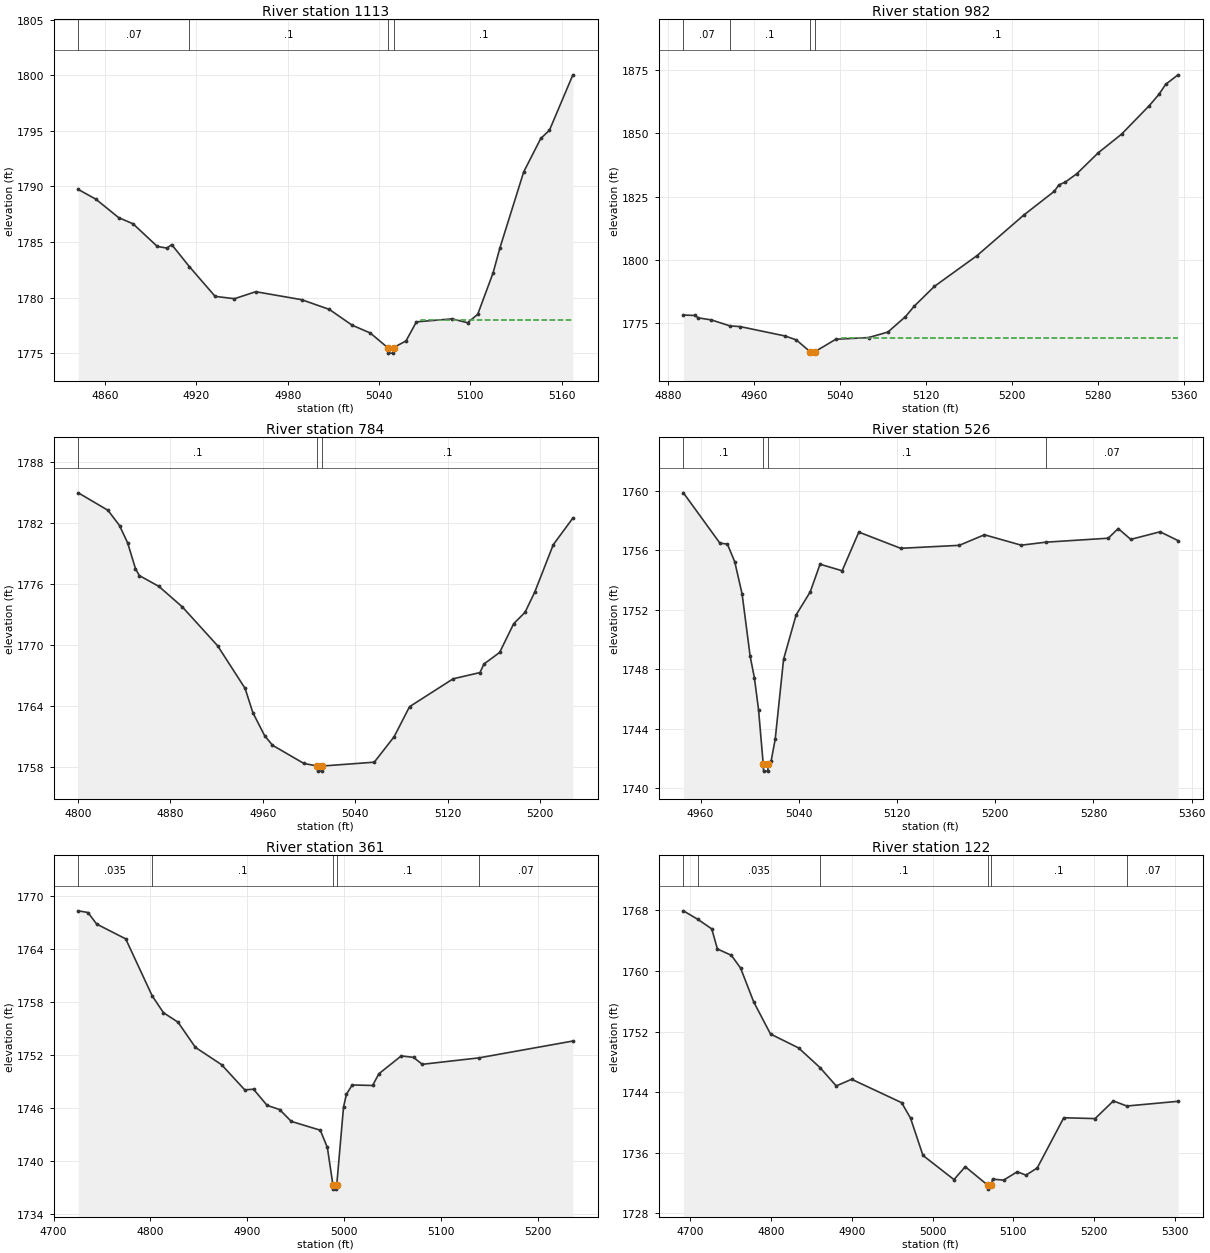
Type RM Length L Ch R = 1 ,1113    ,131,131,131
BEGIN DESCRIPTION:
Stream0605 3.1
END DESCRIPTION:
XS GIS Cut Line= 3
      1898146.32      13894006.3      1898104.67     13893883.94
      1898016.14     13893709.47
#Sta/Elev= 30
  4842.4 1789.73    4854 1788.85  4868.9  1787.2  4878.4 1786.64  4894.3 1784.61
  4900.6 1784.46  4903.8 1784.77  4915.4 1782.79  4932.3 1780.12    4945 1779.91
    4959 1780.54  4989.2 1779.82  5007.3 1778.95  5022.3 1777.53  5034.2 1776.83
  5045.6 1775.52  5045.9 1775.02  5049.4 1775.02  5049.6 1775.52  5057.7 1776.12
  5064.5 1777.83    5088  1778.1  5098.1 1777.75  5104.8 1778.51  5114.9 1782.24
  5119.4 1784.49    5135 1791.31  5146.2 1794.31  5151.9 1795.05  5167.3 1800.03
#Mann= 4 ,-1 , 0
  4842.4     .07       0  4915.4      .1       0  5045.6     .05       0
  5049.6      .1       0
#XS Ineff= 2 , 0
                         5067.53         1777.97
Permanent Ineff=
       F       F
Bank Sta=5045.6,5049.6
XS Rating Curve= 0 ,0
Exp/Cntr=0.3,0.1

Type RM Length L Ch R = 1 ,982     ,198,198,198
BEGIN DESCRIPTION:
Stream0605 2.0
END DESCRIPTION:
XS GIS Cut Line= 3
        1898175.       13893875.        1898175.       13893775.
      1897874.97     13893574.98
#Sta/Elev= 30
  4893.9  1778.3  4904.7 1778.14  4907.7 1777.19    4920 1776.37  4937.3 1774.01
  4946.7 1773.75  4988.7 1770.03    4999  1768.5  5012.1 1763.78  5012.4 1763.28
  5015.9 1763.28  5016.1 1763.78  5035.8 1768.75  5066.3 1769.41  5084.3 1771.58
  5100.7 1777.67  5108.9 1781.82  5127.6 1789.59  5167.3 1801.73    5211 1817.77
  5239.4 1827.14  5243.5 1829.62  5249.6 1830.74  5260.4  1834.1  5280.2 1842.28
  5301.9 1849.63  5327.8 1860.91  5336.7 1865.32    5343 1869.29  5354.5 1873.04
#Mann= 4 ,-1 , 0
  4893.9     .07       0  4937.3      .1       0  5012.1     .05       0
  5016.1      .1       0
#XS Ineff= 2 , 0
                         5041.19         1769.24
Permanent Ineff=
       F       F
Bank Sta=5012.1,5016.1
XS Rating Curve= 0 ,0
Exp/Cntr=0.3,0.1

Type RM Length L Ch R = 1 ,784     ,258,258,258
BEGIN DESCRIPTION:
Mapping XS dbc92c5f
END DESCRIPTION:
XS GIS Cut Line= 2
      1898446.15     13893901.96      1898246.93     13893523.04
#Sta/Elev= 30
  4800.2 1784.97  4825.9 1783.25  4835.9 1781.75  4842.9 1780.05  4849.7 1777.52
    4853 1776.83    4870 1775.76  4890.3 1773.74  4920.8 1769.92  4944.6 1765.72
  4951.3 1763.34  4961.5 1761.07  4968.3 1760.13  4995.4 1758.34  5007.1 1758.08
  5007.4 1757.58  5010.9 1757.58  5011.1 1758.08  5056.4 1758.46  5073.6 1760.97
  5086.9 1763.92  5124.7 1766.67  5147.9 1767.28  5151.3 1768.12  5164.9 1769.26
  5177.1  1772.1  5186.9 1773.21  5195.4 1775.23  5211.3 1779.86  5228.3 1782.49
#Mann= 3 ,-1 , 0
  4800.2      .1       0  5007.1     .05       0  5011.1      .1       0
Bank Sta=5007.1,5011.1
XS Rating Curve= 0 ,0
Exp/Cntr=0.3,0.1

Type RM Length L Ch R = 1 ,526     ,165,165,165
BEGIN DESCRIPTION:
Stream0605 1.0
END DESCRIPTION:
XS GIS Cut Line= 3
        1898575.     13893675.03        1898575.       13893625.
      1898407.66     13893314.33
#Sta/Elev= 30
    4946 1759.86  4975.8 1756.47  4981.8 1756.42  4987.8 1755.23  4993.8 1753.07
  5000.4 1748.86  5003.8 1747.44  5007.2 1745.29    5011 1741.65  5011.3 1741.15
  5014.8 1741.15    5015 1741.65  5017.4  1741.8  5020.8 1743.31  5027.6 1748.67
  5037.8 1751.65  5049.3  1753.2  5057.3 1755.06  5075.3 1754.62  5088.9 1757.22
    5123 1756.13  5170.7 1756.33  5191.2 1757.04  5221.2 1756.34    5241 1756.54
  5292.1 1756.81  5300.2 1757.46  5310.4 1756.73  5334.3 1757.24  5348.9 1756.65
#Mann= 4 ,-1 , 0
    4946      .1       0    5011     .05       0    5015      .1       0
    5241     .07       0
Bank Sta=5011,5015
XS Rating Curve= 0 ,0
Exp/Cntr=0.3,0.1

Type RM Length L Ch R = 1 ,361     ,239,239,239
BEGIN DESCRIPTION:
Mapping XS 260d8ef2
END DESCRIPTION:
XS GIS Cut Line= 3
      1898699.77     13893799.17      1898701.29     13893494.06
      1898528.51     13893382.27
#Sta/Elev= 30
  4725.5 1768.32  4735.5 1768.13  4744.5 1766.82  4774.5 1765.14  4801.8 1758.69
  4813.5 1756.77  4828.5  1755.7  4846.5 1752.84  4873.5 1750.88  4897.5 1748.02
  4906.5  1748.1  4920.5 1746.27  4933.5 1745.79  4945.5 1744.45  4975.5 1743.45
  4982.8 1741.49  4988.5 1737.27  4988.7 1736.77  4992.2 1736.77  4992.5 1737.27
  4999.5 1746.08  5002.5 1747.53  5008.5 1748.58  5029.5 1748.52    5036 1749.85
  5059.1 1751.87  5071.8 1751.71  5080.8 1750.92  5139.3 1751.65  5236.4 1753.56
#Mann= 5 ,-1 , 0
  4725.5    .035       0  4801.8      .1       0  4988.5     .05       0
  4992.5      .1       0  5139.3     .07       0
Bank Sta=4988.5,4992.5
XS Rating Curve= 0 ,0
Exp/Cntr=0.3,0.1

Type RM Length L Ch R = 1 ,122     ,0,0,0
BEGIN DESCRIPTION:
Stream0605 0.0
END DESCRIPTION:
XS GIS Cut Line= 4
      1898765.49     13893837.62      1898905.37     13893595.63
      1898972.02     13893507.65      1898889.48     13893300.79
#Sta/Elev= 30
  4691.3 1767.93  4709.4 1766.79  4726.4 1765.55  4733.4  1762.9  4750.7 1762.06
  4762.1 1760.38  4778.4  1755.9  4799.2 1751.67  4833.9 1749.84  4860.5 1747.24
  4880.6 1744.82  4899.7  1745.7  4961.6 1742.61  4972.6 1740.57    4988 1735.65
  5026.4 1732.46  5040.4 1734.16  5068.5  1731.7  5068.7  1731.2  5072.5  1731.7
  5074.2 1732.52  5087.9 1732.39  5104.8 1733.49  5115.6 1733.05  5129.5 1733.99
  5162.4 1740.62  5201.2 1740.51  5223.8 1742.84  5240.5 1742.17  5303.9 1742.79
#Mann= 6 ,-1 , 0
  4691.3     .07       0  4709.4    .035       0  4860.5      .1       0
  5068.5     .05       0  5072.5      .1       0  5240.5     .07       0
Bank Sta=5068.5,5072.5
XS Rating Curve= 0 ,0
Exp/Cntr=0.3,0.1

Chan Stop Cuts=-1
Use User Specified Reach Order=0
Composite Channel Slope=5