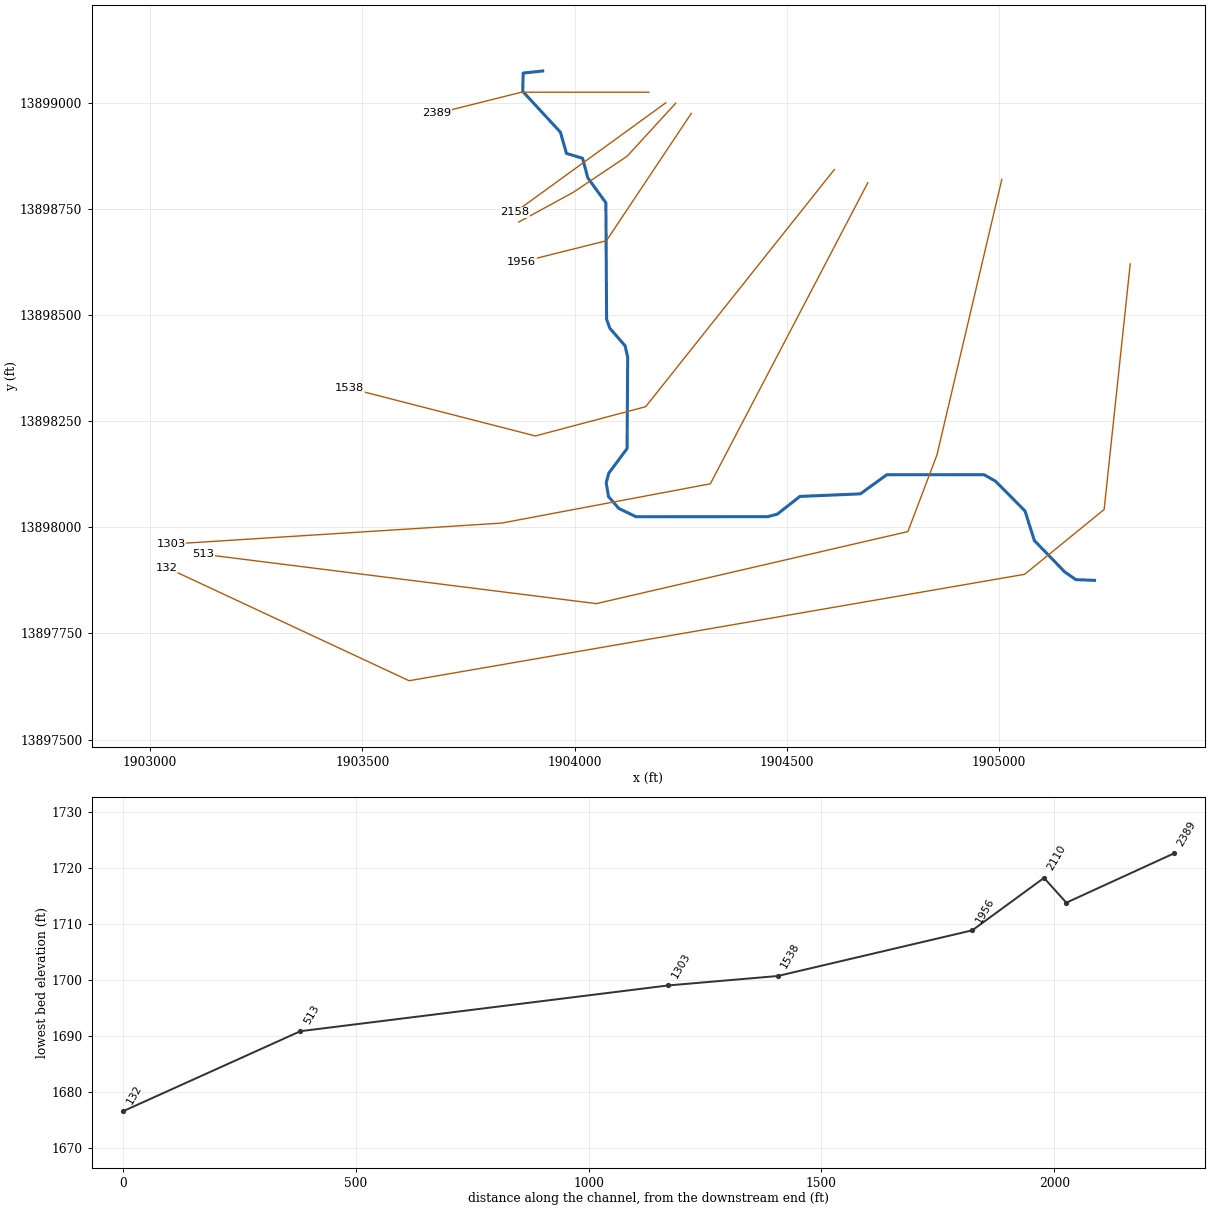
--- Stream0606.prj (project) ---

Proj Title=Stream0606 Base Level Engineering
Current Plan=p01
Default Exp/Contr=0.3,0.1
English Units
Geom File=g01
Flow File=f01
Plan File=p01
Y Axis Title=Elevation
X Axis Title(PF)=Main Channel Distance
X Axis Title(XS)=Station
BEGIN DESCRIPTION:
Stream0606
END DESCRIPTION:
DSS Export Rating Curves= 0
DSS Export Rating Curve Sorted= 0
DSS Export Volume Flow Curves= 0
DXF OffsetX= 0
DXF OffsetY= 0
DXF ScaleX= 1
DXF ScaleY= 10

--- Stream0606.p01 (plan) ---

Plan Title=Multiple Run
Short Identifier=Multiple
Geom File=g01
Flow File=f01
Subcritical Flow
K Sum by GR= 0
Std Step Tol= 0.01
Critical Tol= 0.01
Num of Std Step Trials= 20
Max Error Tol= 0.3
Flow Tol Ratio= 0.001
Split Flow NTrial= 30
Split Flow Tol= 0.02
Split Flow Ratio= 0.02
Log Output Level= 0
Friction Slope Method= 1
Unsteady Friction Slope Method= 2
Unsteady Bridges Friction Slope Method= 1
Parabolic Critical Depth
Global Vel Dist=  1 , 1 , 1
Global Log Level= 0
CheckData=True
Encroach Param= -1, 0, 0, 0
BEGIN DESCRIPTION:
Multiple Run
END DESCRIPTION:

--- Stream0606.f01 (steady flow) ---

Flow Title=Multiple
Number of Profiles=7
Profile Names=10-year,25-year,50-year,1pct_min,100-year,1pct_plu,500-year
River Rch & RM= Stream0606,Reach-1,2389
     674    1117    1528    1015    2026    4043    3506
Boundary for River Rch & Prof#=Stream0606,Reach-1,1
Up Type=0
Dn Type=3
Dn Slope=0.005
Boundary for River Rch & Prof#=Stream0606,Reach-1,2
Up Type=0
Dn Type=3
Dn Slope=0.005
Boundary for River Rch & Prof#=Stream0606,Reach-1,3
Up Type=0
Dn Type=3
Dn Slope=0.005
Boundary for River Rch & Prof#=Stream0606,Reach-1,4
Up Type=0
Dn Type=3
Dn Slope=0.005
Boundary for River Rch & Prof#=Stream0606,Reach-1,5
Up Type=0
Dn Type=3
Dn Slope=0.005
Boundary for River Rch & Prof#=Stream0606,Reach-1,6
Up Type=0
Dn Type=3
Dn Slope=0.005
Boundary for River Rch & Prof#=Stream0606,Reach-1,7
Up Type=0
Dn Type=3
Dn Slope=0.005

--- Stream0606.g01 (geometry) ---

Geom Title=Existing Conditions
Program Version=4.10

River Reach=Stream0606      ,Reach-1
Reach XY= 30
        1903925.       13899075.      1903878.93     13899070.08
      1903877.99     13899026.81      1903966.75     13898930.77
      1903980.99     13898880.77      1904019.05     13898869.24
      1904031.22     13898823.14      1904073.81     13898764.52
      1904075.52     13898490.22      1904083.14     13898468.94
      1904119.25     13898427.33       1904125.2     13898400.08
      1904123.76      13898185.5      1904080.34     13898127.14
      1904074.61     13898104.71      1904079.97     13898072.41
      1904104.24     13898044.44      1904144.85     13898024.91
      1904454.97     13898025.07      1904477.33     13898030.75
      1904530.94     13898072.73      1904673.43     13898078.79
       1904735.5     13898123.78      1904964.57     13898123.96
       1904991.8     13898108.58      1905061.38     13898038.24
      1905083.15     13897968.94      1905154.86     13897894.76
      1905181.13     13897876.67        1905225.       13897875.

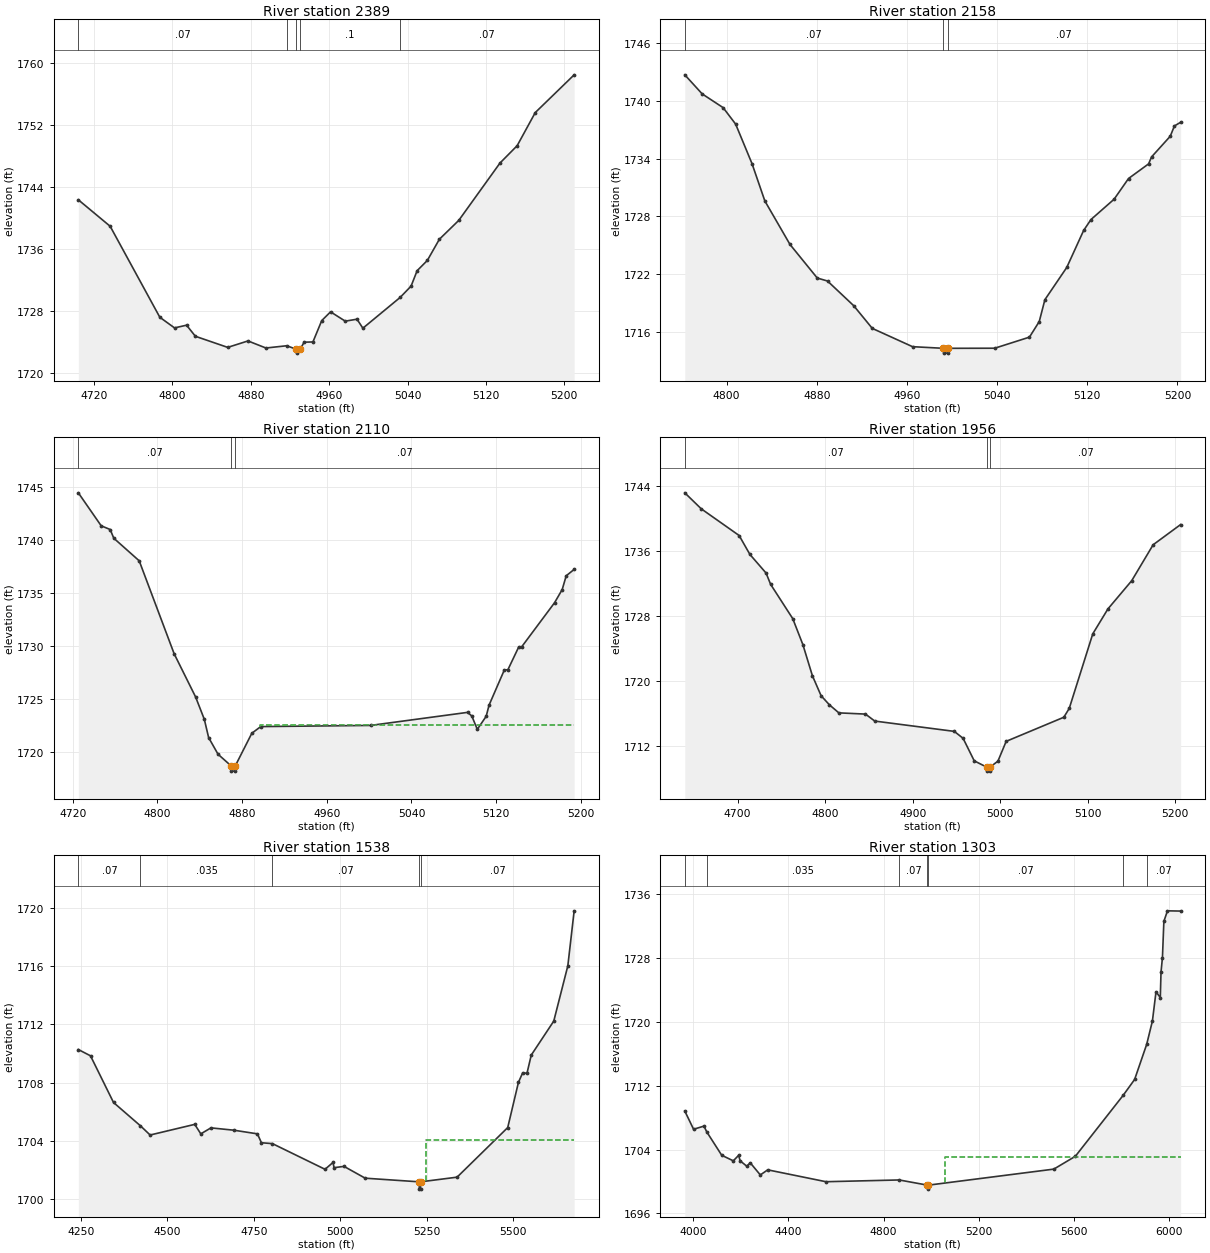
Type RM Length L Ch R = 1 ,2389    ,231,231,231
BEGIN DESCRIPTION:
Stream0606 3.0
END DESCRIPTION:
XS GIS Cut Line= 3
      1904175.01       13899025.        1903875.       13899025.
      1903674.97     13898974.99
#Sta/Elev= 30
  4703.9 1742.33  4736.4 1738.92  4787.1  1727.2  4802.1 1725.83  4814.4 1726.18
  4823.4 1724.75  4856.4 1723.32  4877.1 1724.15  4895.4 1723.24  4916.7 1723.53
  4926.4 1723.08  4926.7 1722.58  4930.4 1723.08  4934.4 1723.99  4943.4 1724.02
  4952.4 1726.77  4961.4  1727.9  4976.4  1726.7  4988.4 1726.95  4994.4 1725.79
  5032.4 1729.75  5043.6 1731.21  5049.8  1733.2  5060.2 1734.52  5072.5 1737.25
  5092.3 1739.68  5134.4 1747.07  5151.9  1749.3  5170.4 1753.57  5210.1 1758.43
#Mann= 5 ,-1 , 0
  4703.9     .07       0  4916.7      .1       0  4926.4     .05       0
  4930.4      .1       0  5032.4     .07       0
Bank Sta=4926.4,4930.4
XS Rating Curve= 0 ,0
Exp/Cntr=0.3,0.1

Type RM Length L Ch R = 1 ,2158    ,48,48,48
BEGIN DESCRIPTION:
Mapping XS 948f9701
END DESCRIPTION:
XS GIS Cut Line= 2
      1904214.95     13899000.02      1903859.05     13898741.64
#Sta/Elev= 30
    4763  1742.7  4778.4 1740.72    4797 1739.29  4808.1 1737.58  4822.6 1733.48
    4834  1729.6  4856.3 1725.08  4880.5 1721.59  4889.6 1721.28  4912.8 1718.72
  4929.3 1716.36    4965 1714.46  4992.4 1714.29  4992.6 1713.79  4996.1 1713.79
  4996.4 1714.29  5037.9  1714.3  5068.7 1715.45  5077.4 1717.07  5082.4 1719.34
  5101.8 1722.69  5116.8 1726.54  5123.3 1727.67  5143.8 1729.78  5156.6 1731.93
  5174.4 1733.45    5177 1734.17  5193.6 1736.32  5197.3 1737.39  5202.8 1737.77
#Mann= 3 ,-1 , 0
    4763     .07       0  4992.4     .05       0  4996.4     .07       0
Bank Sta=4992.4,4996.4
XS Rating Curve= 0 ,0
Exp/Cntr=0.3,0.1

Type RM Length L Ch R = 1 ,2110    ,154,154,154
BEGIN DESCRIPTION:
Stream0606 2.1
END DESCRIPTION:
XS GIS Cut Line= 4
      1904238.32     13898999.04      1904123.76     13898874.07
      1903997.46     13898789.43      1903868.56     13898719.12
#Sta/Elev= 30
  4725.3 1744.45  4746.9 1741.34  4755.4 1740.99  4758.8 1740.17  4782.8 1738.04
  4815.8 1729.28  4836.1  1725.2  4844.3  1723.1  4848.4 1721.37  4857.3  1719.8
  4869.6 1718.71  4869.8 1718.21  4873.3 1718.21  4873.6 1718.71  4889.2 1721.78
  4897.6 1722.41  5001.5 1722.52    5093 1723.75    5097 1723.41  5102.2 1722.15
  5110.6 1723.38  5113.3 1724.43  5127.7 1727.74  5131.1 1727.77  5141.4 1729.93
  5144.2 1729.94  5175.2 1734.09  5182.4 1735.33  5186.2 1736.63  5193.7 1737.23
#Mann= 3 ,-1 , 0
  4725.3     .07       0  4869.6     .05       0  4873.6     .07       0
#XS Ineff= 2 , 0
                          4897.3         1722.54
Permanent Ineff=
       F       F
Bank Sta=4869.6,4873.6
XS Rating Curve= 0 ,0
Exp/Cntr=0.3,0.1

Type RM Length L Ch R = 1 ,1956    ,418,418,418
BEGIN DESCRIPTION:
Stream0606 2.0
END DESCRIPTION:
XS GIS Cut Line= 3
      1904274.99     13898974.99        1904075.       13898675.
      1903874.99       13898625.
#Sta/Elev= 30
  4639.6 1743.16  4658.4 1741.19  4701.7  1737.9    4714 1735.57  4732.5 1733.27
  4737.7 1731.88    4763 1727.65  4774.6 1724.44  4785.4 1720.63  4795.4 1718.15
  4804.9 1717.03  4815.7 1716.04  4846.1 1715.89  4856.7 1715.03  4947.6 1713.76
  4957.7  1712.9  4970.4 1710.13  4984.5 1709.36  4984.8 1708.86  4988.3 1708.86
  4988.5 1709.36  4997.5 1710.09  5006.9 1712.53  5072.8  1715.5    5079 1716.59
  5105.9 1725.78  5123.2 1728.85  5150.4 1732.33  5174.9 1736.76  5206.3 1739.25
#Mann= 3 ,-1 , 0
  4639.6     .07       0  4984.5     .05       0  4988.5     .07       0
Bank Sta=4984.5,4988.5
XS Rating Curve= 0 ,0
Exp/Cntr=0.3,0.1

Type RM Length L Ch R = 1 ,1538    ,235,235,235
BEGIN DESCRIPTION:
Stream0606 1.0
END DESCRIPTION:
XS GIS Cut Line= 4
      1904612.06     13898842.84      1904167.51     13898284.08
      1903907.79     13898215.17       1903470.3     13898327.44
#Sta/Elev= 30
  4242.1 1710.28  4277.3 1709.85  4343.9 1706.65  4421.8 1705.05  4449.8 1704.42
  4578.8 1705.15  4596.4  1704.5  4625.8 1704.91    4692 1704.75  4760.2  1704.5
  4771.8 1703.89  4803.6 1703.83  4955.8 1702.07  4978.9 1702.54    4982 1702.18
  5010.7 1702.27    5072 1701.46  5228.3 1701.21  5228.6 1700.71  5232.1 1700.71
  5232.3 1701.21  5337.8 1701.53  5484.3 1704.93  5515.3 1708.03  5527.7 1708.69
    5540 1708.65  5552.4  1709.9  5617.5 1712.23  5658.2 1716.02  5676.5 1719.79
#Mann= 5 ,-1 , 0
  4242.1     .07       0  4421.8    .035       0  4803.6     .07       0
  5228.3     .05       0  5232.3     .07       0
#XS Ineff= 2 , 0
                         5246.95         1704.07
Permanent Ineff=
       F       F
Bank Sta=5228.3,5232.3
XS Rating Curve= 0 ,0
Exp/Cntr=0.3,0.1

Type RM Length L Ch R = 1 ,1303    ,790,790,790
BEGIN DESCRIPTION:
Mapping XS 60362073
END DESCRIPTION:
XS GIS Cut Line= 4
      1904690.94     13898811.68      1904319.97     13898102.47
      1903828.04     13898009.87      1903049.35     13897960.49
#Sta/Elev= 30
  3965.5 1708.83  4002.4 1706.54    4046 1706.94  4057.7 1706.21  4120.5 1703.28
  4169.1 1702.58  4191.4 1703.27    4198 1702.58  4225.5 1701.91  4240.3 1702.33
  4282.5 1700.81  4313.6 1701.45  4558.1 1699.96  4865.4 1700.18  4984.2 1699.53
  4984.4 1699.03  4988.2 1699.53  5514.4 1701.54  5604.8 1703.15  5805.8 1710.81
  5853.6 1712.79  5904.3  1717.2  5928.3 1720.13  5943.4  1723.8  5961.4 1723.06
  5964.4 1726.26  5970.4 1728.09  5976.4 1732.63  5991.5 1733.95  6046.7 1733.92
#Mann= 7 ,-1 , 0
  3965.5     .07       0  4057.7    .035       0  4865.4     .07       0
  4984.2     .05       0  4988.2     .07       0  5805.8    .035       0
  5904.3     .07       0
#XS Ineff= 2 , 0
                         5058.44         1703.06
Permanent Ineff=
       F       F
Bank Sta=4984.2,4988.2
XS Rating Curve= 0 ,0
Exp/Cntr=0.3,0.1

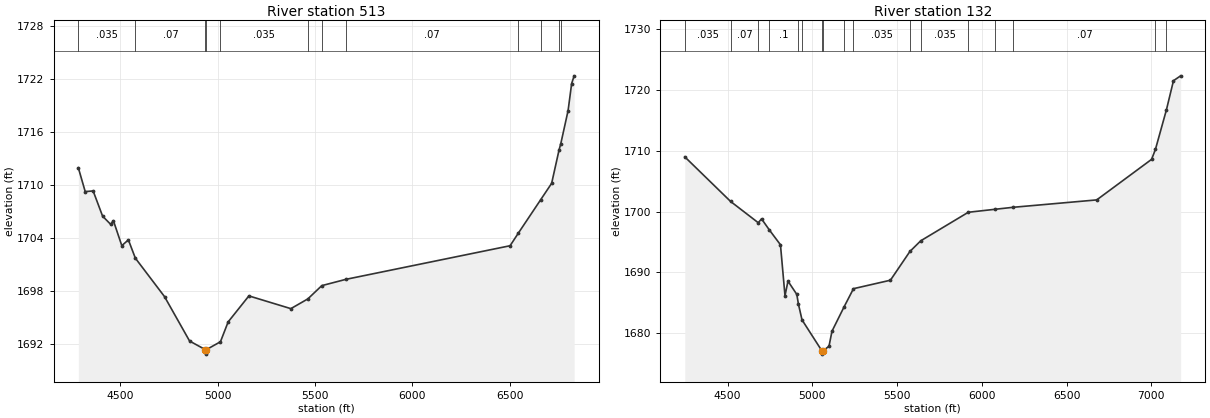
Type RM Length L Ch R = 1 ,513     ,381,381,381
BEGIN DESCRIPTION:
Stream0606 0.3
END DESCRIPTION:
XS GIS Cut Line= 5
       1905006.6     13898819.68      1904853.79     13898170.55
      1904785.34      13897989.9      1904051.42     13897820.17
      1903124.65     13897936.59
#Sta/Elev= 30
  4284.5 1711.93  4319.8 1709.24  4360.6 1709.31  4409.2 1706.46  4450.4 1705.54
  4464.7 1705.95  4507.8 1703.13  4541.7 1703.78  4577.3 1701.72  4727.3 1697.37
  4856.1 1692.35  4937.7 1691.37    4938 1690.87  4941.7 1691.37  5014.7 1692.27
  5054.2 1694.51  5160.8 1697.45  5376.4 1696.01  5463.6 1697.11  5535.3 1698.61
  5658.9 1699.32  6502.8 1703.12  6545.3 1704.55  6659.3  1708.3  6716.2 1710.17
  6754.6 1713.97  6763.2 1714.65  6800.8  1718.4    6819 1721.45  6831.9 1722.32
#Mann= 12 ,-1 , 0
  4284.5    .035       0  4577.3     .07       0  4937.7     .05       0
  4941.7     .07       0  5014.7    .035       0  5463.6     .07       0
  5535.3    .035       0  5658.9     .07       0  6545.3    .035       0
  6659.3     .07       0  6754.6    .035       0  6763.2     .07       0
Bank Sta=4937.7,4941.7
XS Rating Curve= 0 ,0
Exp/Cntr=0.3,0.1

Type RM Length L Ch R = 1 ,132     ,0,0,0
BEGIN DESCRIPTION:
Stream0606 0.0
END DESCRIPTION:
XS GIS Cut Line= 5
       1905309.1     13898620.53      1905247.63     13898041.89
      1905060.28     13897889.26      1903610.22     13897638.54
      1903039.24     13897904.96
#Sta/Elev= 30
  4247.4 1708.99  4517.5 1701.67  4680.9 1698.17  4700.1 1698.81  4746.5 1696.98
  4811.8 1694.55  4838.5 1686.18  4856.1 1688.58  4908.2  1686.4  4917.8  1684.8
  4938.9 1682.22  5057.1 1677.09  5057.3 1676.59  5061.1 1677.09  5098.2 1677.89
  5115.7 1680.35  5187.6 1684.38  5242.5 1687.34  5460.5 1688.73  5575.4 1693.45
  5639.2  1695.2  5919.9 1699.89  6077.8 1700.38  6185.7 1700.71  6677.6 1701.92
  7001.3 1708.58    7024 1710.22  7088.7  1716.7  7130.4  1721.5  7172.6  1722.3
#Mann= 17 ,-1 , 0
  4247.4    .035       0  4517.5     .07       0  4680.9    .035       0
  4746.5      .1       0  4917.8     .07       0  4938.9     .07       0
  5057.1     .05       0  5061.1     .07       0  5187.6     .07       0
  5242.5    .035       0  5575.4     .07       0  5639.2    .035       0
  5919.9     .07       0  6077.8    .035       0  6185.7     .07       0
    7024    .035       0  7088.7     .07       0
Bank Sta=5057.1,5061.1
XS Rating Curve= 0 ,0
Exp/Cntr=0.3,0.1

Chan Stop Cuts=-1
Use User Specified Reach Order=0
Composite Channel Slope=5