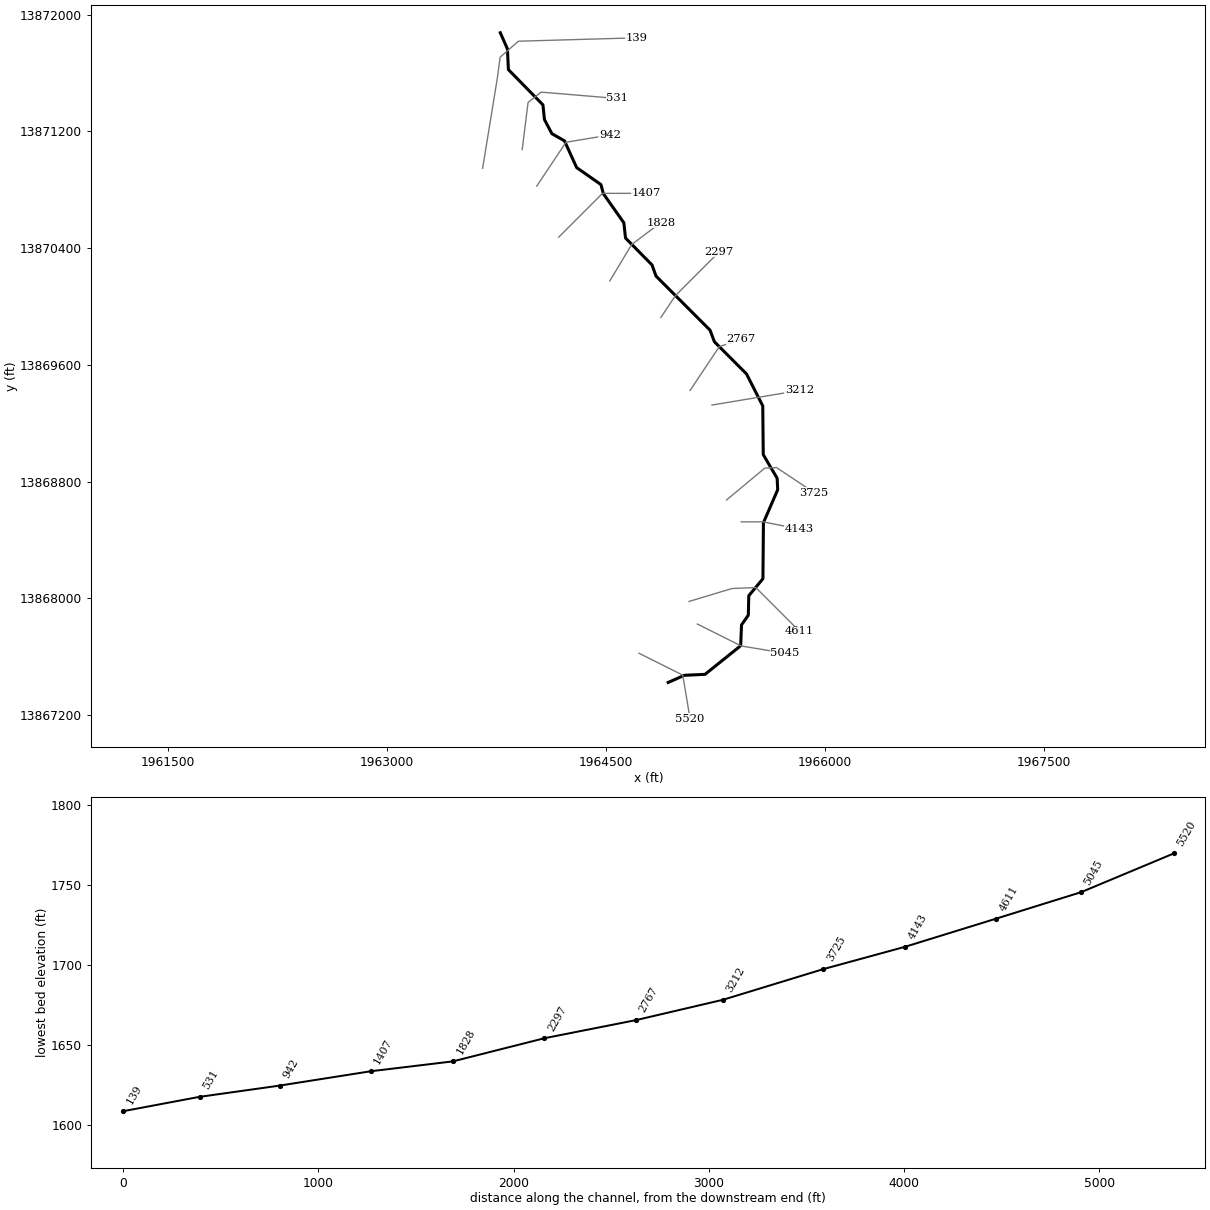
--- Stream0607.prj (project) ---

Proj Title=Stream0607 Base Level Engineering
Current Plan=p01
Default Exp/Contr=0.3,0.1
English Units
Geom File=g01
Flow File=f01
Plan File=p01
BEGIN DESCRIPTION:
Stream0607
END DESCRIPTION:

--- Stream0607.p01 (plan) ---

Plan Title=Multiple Run
Short Identifier=Multiple
Geom File=g01
Flow File=f01
Subcritical Flow
K Sum by GR= 0
Std Step Tol= 0.01
Critical Tol= 0.01
Num of Std Step Trials= 20
Max Error Tol= 0.3
Flow Tol Ratio= 0.001
Split Flow NTrial= 30
Split Flow Tol= 0.02
Split Flow Ratio= 0.02
Log Output Level= 0
Friction Slope Method= 1
Unsteady Friction Slope Method= 2
Unsteady Bridges Friction Slope Method= 1
Parabolic Critical Depth
Global Vel Dist=  1 , 1 , 1
Global Log Level= 0
CheckData=True
Encroach Param= -1, 0, 0, 0
BEGIN DESCRIPTION:
Multiple Run
END DESCRIPTION:

--- Stream0607.f01 (steady flow) ---

Flow Title=Multiple
Number of Profiles=7
Profile Names=10-year,25-year,50-year,1pct_min,100-year,1pct_plu,500-year
River Rch & RM= Stream0607,Reach-1,5520
    1075    1832    2556    1728    3448    6880    6187
Boundary for River Rch & Prof#=Stream0607,Reach-1,1
Up Type=0
Dn Type=3
Dn Slope=0.005
Boundary for River Rch & Prof#=Stream0607,Reach-1,2
Up Type=0
Dn Type=3
Dn Slope=0.005
Boundary for River Rch & Prof#=Stream0607,Reach-1,3
Up Type=0
Dn Type=3
Dn Slope=0.005
Boundary for River Rch & Prof#=Stream0607,Reach-1,4
Up Type=0
Dn Type=3
Dn Slope=0.005
Boundary for River Rch & Prof#=Stream0607,Reach-1,5
Up Type=0
Dn Type=3
Dn Slope=0.005
Boundary for River Rch & Prof#=Stream0607,Reach-1,6
Up Type=0
Dn Type=3
Dn Slope=0.005
Boundary for River Rch & Prof#=Stream0607,Reach-1,7
Up Type=0
Dn Type=3
Dn Slope=0.005

--- Stream0607.g01 (geometry) ---

Geom Title=Existing Conditions

River Reach=Stream0607,Reach-1
Reach XY= 30
      1964925.00     13867425.00      1965035.47     13867473.87
      1965177.44     13867480.48      1965421.46     13867676.46
      1965427.27     13867819.06      1965473.77     13867885.51
      1965477.08     13868019.14      1965573.94     13868135.44
      1965577.26     13868519.06      1965675.10     13868745.10
      1965671.33     13868823.42      1965576.20     13868985.50
      1965572.76     13869319.07      1965461.38     13869538.21
      1965241.65     13869758.33      1965211.37     13869838.21
      1964841.65     13870208.33      1964814.22     13870284.68
      1964632.86     13870468.83      1964621.17     13870573.41
      1964480.88     13870772.74      1964464.35     13870835.00
      1964297.99     13870951.48      1964214.31     13871134.98
      1964128.53     13871183.49      1964077.32     13871280.94
      1964067.14     13871381.17      1963830.47     13871622.55
      1963823.87     13871764.53      1963775.00     13871875.00

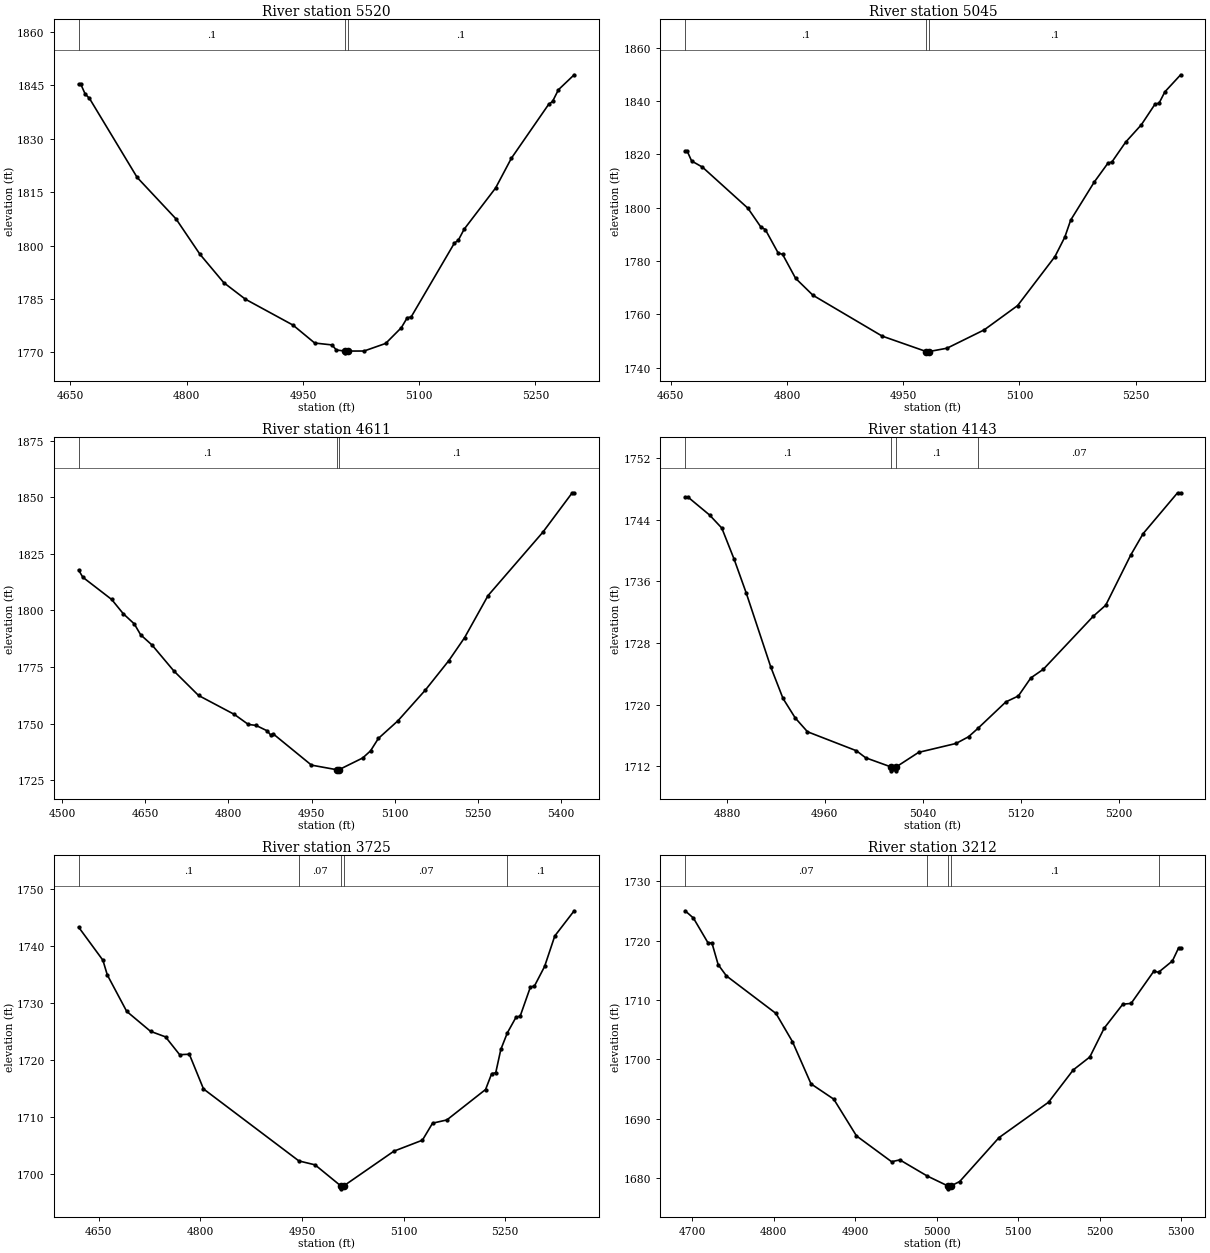
Type RM Length L Ch R = 1,5520,475,475,475
BEGIN DESCRIPTION:
Stream0607 12.0
END DESCRIPTION:
XS GIS Cut Line= 3
      1964724.99     13867625.01      1965025.00     13867475.00
      1965075.01     13867174.96
#Sta/Elev= 30
  4660.5 1845.23  4663.3 1845.23  4668.9 1842.51  4674.5 1841.26  4736.0 1819.11
  4786.3 1807.44  4817.0 1797.57  4847.8 1789.59  4875.7 1784.95  4937.2 1777.68
  4965.2 1772.65  4987.5 1772.12  4993.1 1770.70  5004.1 1770.40  5004.3 1769.90
  5008.1 1770.40  5028.9 1770.41  5056.8 1772.54  5077.0 1776.95  5084.6 1779.74
  5089.7 1779.97  5145.5 1800.68  5150.5 1801.47  5158.1 1804.58  5198.7 1816.14
  5219.0 1824.46  5267.1 1839.58  5272.2 1840.42  5279.8 1843.70  5300.1 1847.89
#Mann=3,-1,0
  4660.5     0.1       0  5004.1    0.05       0  5008.1     0.1       0
Bank Sta=5004.1,5008.1
Exp/Cntr=0.3,0.1

Type RM Length L Ch R = 1,5045,434,434,434
BEGIN DESCRIPTION:
Stream0607 11.0
END DESCRIPTION:
XS GIS Cut Line= 3
      1965124.96     13867825.02      1965425.00     13867675.00
      1965725.01     13867625.00
#Sta/Elev= 30
  4668.4 1821.20  4671.2 1821.20  4676.8 1817.57  4690.8 1815.26  4749.5 1799.84
  4766.3 1792.75  4771.9 1791.87  4788.6 1783.02  4794.2 1782.57  4811.0 1773.57
  4833.4 1767.22  4922.8 1751.89  4979.5 1746.12  4979.7 1745.62  4983.5 1746.12
  5006.4 1747.35  5054.5 1754.24  5097.6 1763.35  5145.8 1781.74  5158.5 1789.01
  5166.1 1795.41  5196.5 1809.67  5214.2 1816.76  5219.3 1817.20  5237.0 1824.63
  5257.3 1831.15  5275.0 1838.91  5280.1 1839.23  5287.7 1843.51  5308.0 1849.89
#Mann=3,-1,0
  4668.4     0.1       0  4979.5    0.05       0  4983.5     0.1       0
Bank Sta=4979.5,4983.5
Exp/Cntr=0.3,0.1

Type RM Length L Ch R = 1,4611,468,468,468
BEGIN DESCRIPTION:
Stream0607 10.0
END DESCRIPTION:
XS GIS Cut Line= 4
      1965067.79     13867979.80      1965362.10     13868068.36
      1965525.00     13868075.00      1965824.97     13867775.03
#Sta/Elev= 30
  4529.6 1817.86  4537.1 1814.68  4589.3 1804.83  4610.2 1798.54  4630.1 1794.04
  4641.6 1789.21  4662.4 1784.63  4701.4 1773.27  4746.0 1762.42  4810.9 1754.00
  4835.9 1749.60  4849.9 1749.16  4869.9 1746.78  4876.1 1744.98  4881.1 1745.37
  4949.9 1731.61  4995.5 1729.58  4995.7 1729.08  4999.5 1729.58  5042.4 1734.76
  5056.6 1737.92  5070.7 1743.40  5106.0 1751.20  5155.5 1764.78  5198.0 1777.84
  5226.3 1787.93  5268.7 1806.56  5367.7 1834.59  5420.7 1852.01  5424.2 1852.01
#Mann=3,-1,0
  4529.6     0.1       0  4995.5    0.05       0  4999.5     0.1       0
Bank Sta=4995.5,4999.5
Exp/Cntr=0.3,0.1

Type RM Length L Ch R = 1,4143,418,418,418
BEGIN DESCRIPTION:
Stream0607 9.0
END DESCRIPTION:
XS GIS Cut Line= 3
      1965425.03     13868525.00      1965575.00     13868525.00
      1965824.98     13868475.00
#Sta/Elev= 30
  4845.8 1746.95  4848.3 1746.95  4865.8 1744.64  4875.8 1742.94  4885.8 1738.92
  4895.8 1734.48  4915.8 1724.89  4925.8 1720.80  4935.8 1718.26  4945.8 1716.47
  4985.8 1714.00  4993.3 1713.09  5014.2 1711.89  5014.4 1711.39  5017.9 1711.39
  5018.2 1711.89  5036.6 1713.79  5067.2 1714.95  5077.4 1715.82  5085.0 1716.90
  5107.9 1720.35  5118.1 1721.12  5128.3 1723.47  5138.5 1724.59  5179.3 1731.48
  5189.5 1732.92  5209.9 1739.43  5220.1 1742.23  5248.2 1747.53  5250.7 1747.53
#Mann=4,-1,0
  4845.8     0.1       0  5014.2    0.05       0  5018.2     0.1       0
  5085.0    0.07       0
Bank Sta=5014.2,5018.2
Exp/Cntr=0.3,0.1

Type RM Length L Ch R = 1,3725,513,513,513
BEGIN DESCRIPTION:
Stream0607 8.0
END DESCRIPTION:
XS GIS Cut Line= 4
      1965325.03     13868675.02      1965586.42     13868892.85
      1965667.22     13868896.85      1965925.03     13868724.98
#Sta/Elev= 30
  4620.6 1743.27  4656.4 1737.48  4662.9 1734.90  4691.5 1728.52  4726.7 1725.02
  4748.8 1724.05  4769.6 1720.93  4783.9 1721.01  4804.8 1714.93  4945.5 1702.32
  4969.4 1701.63  5007.5 1697.93  5007.7 1697.43  5011.5 1697.93  5085.7 1704.03
  5127.7 1705.95  5142.7 1708.93  5163.8 1709.50  5220.9 1714.83  5229.9 1717.61
  5235.9 1717.77  5243.4 1721.85  5253.0 1724.75  5265.9 1727.51  5271.9 1727.67
  5287.0 1732.77  5293.0 1732.96  5308.0 1736.39  5323.0 1741.73  5351.6 1746.14
#Mann=5,-1,0
  4620.6     0.1       0  4945.5    0.07       0  5007.5    0.05       0
  5011.5    0.07       0  5253.0     0.1       0
Bank Sta=5007.5,5011.5
Exp/Cntr=0.3,0.1

Type RM Length L Ch R = 1,3212,445,445,445
BEGIN DESCRIPTION:
Stream0607 7.0
END DESCRIPTION:
XS GIS Cut Line= 3
      1965224.97     13869324.99      1965525.00     13869375.00
      1965824.99     13869425.00
#Sta/Elev= 30
  4691.1 1725.00  4701.3 1723.78  4719.0 1719.66  4724.1 1719.56  4731.7 1715.94
  4741.8 1714.05  4802.7 1707.73  4822.9 1702.99  4845.7 1695.89  4873.6 1693.32
  4901.5 1687.14  4944.6 1682.80  4954.7 1683.11  4988.3 1680.40  5013.5 1678.74
  5013.8 1678.24  5017.5 1678.74  5028.2 1679.47  5076.4 1686.85  5137.2 1692.80
  5167.6 1698.24  5187.9 1700.41  5205.6 1705.27  5228.4 1709.29  5238.6 1709.42
  5266.5 1714.84  5272.3 1714.66  5289.3 1716.56  5296.9 1718.76  5299.4 1718.76
#Mann=5,-1,0
  4691.1    0.07       0  4988.3     0.1       0  5013.5    0.05       0
  5017.5     0.1       0  5272.3    0.07       0
Bank Sta=5013.5,5017.5
Exp/Cntr=0.3,0.1

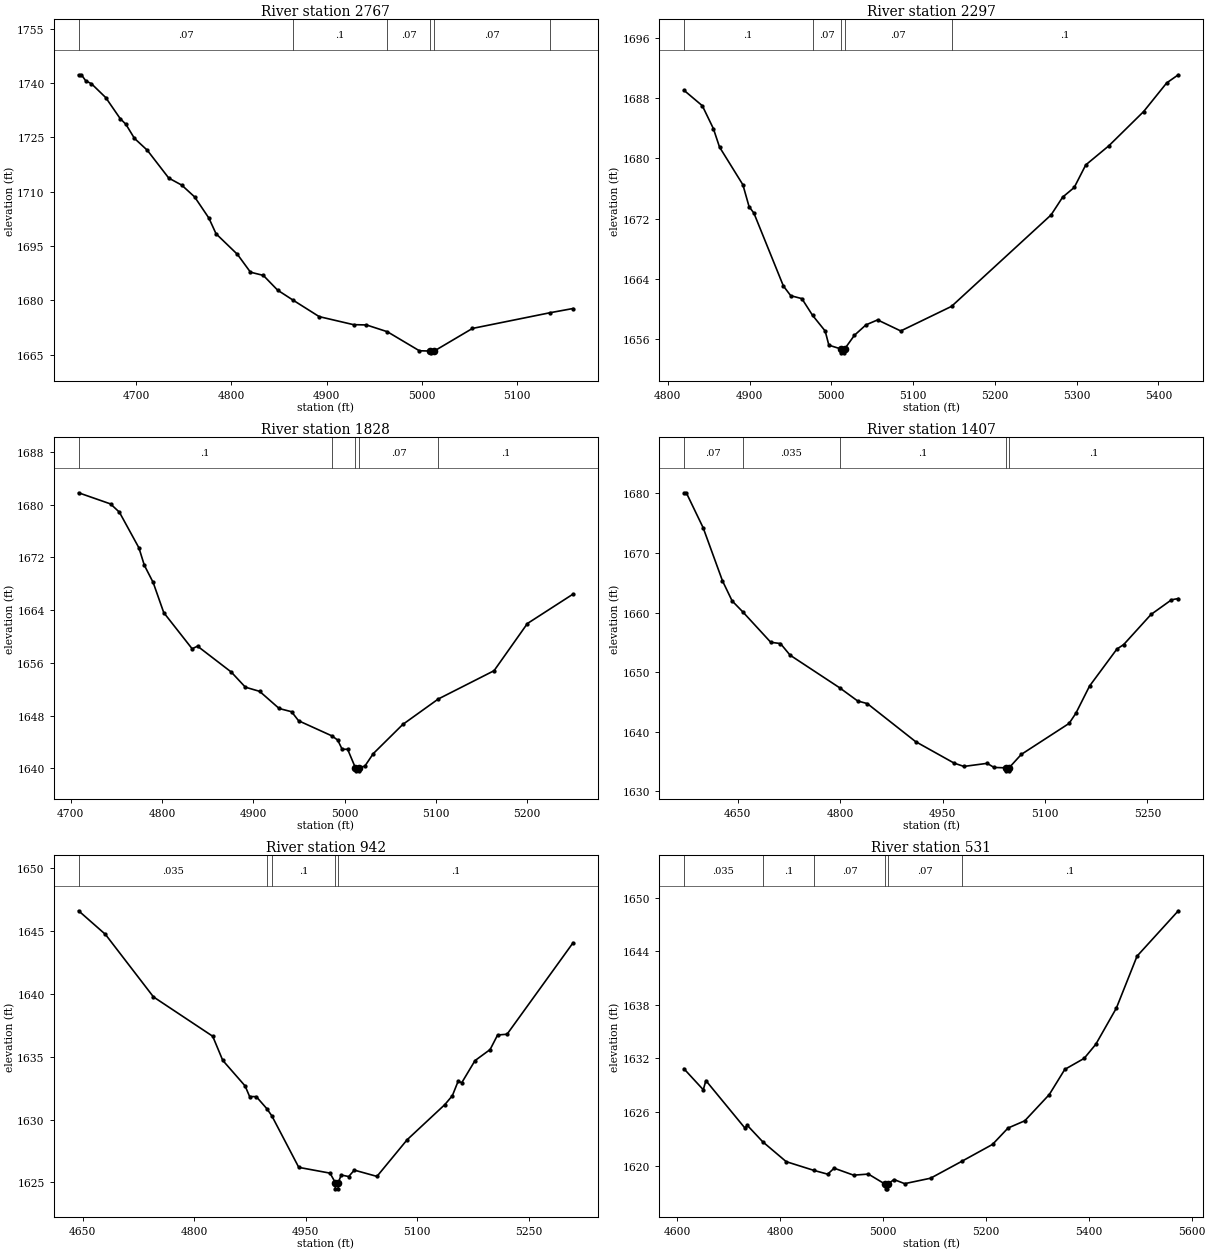
Type RM Length L Ch R = 1,2767,470,470,470
BEGIN DESCRIPTION:
Stream0607 6.0
END DESCRIPTION:
XS GIS Cut Line= 3
      1965075.01     13869425.01      1965275.00     13869725.00
      1965425.04     13869775.01
#Sta/Elev= 30
  4639.7 1742.28  4642.7 1742.28  4647.2 1740.61  4653.2 1739.81  4668.2 1735.98
  4683.3 1730.20  4689.3 1728.62  4698.3 1724.73  4711.8 1721.44  4734.3 1713.76
  4747.9 1711.82  4761.4 1708.57  4776.4 1702.71  4783.9 1698.39  4806.4 1692.68
  4820.0 1687.78  4833.5 1686.89  4848.5 1682.82  4864.7 1680.06  4892.1 1675.51
  4928.1 1673.29  4941.7 1673.21  4963.6 1671.34  4997.2 1666.08  5008.8 1666.01
  5009.0 1665.51  5012.8 1666.01  5052.9 1672.25  5134.2 1676.58  5158.4 1677.75
#Mann=6,-1,0
  4639.7    0.07       0  4864.7     0.1       0  4963.6    0.07       0
  5008.8    0.05       0  5012.8    0.07       0  5134.2     0.1       0
Bank Sta=5008.8,5012.8
Exp/Cntr=0.3,0.1

Type RM Length L Ch R = 1,2297,469,469,469
BEGIN DESCRIPTION:
Stream0607 5.0
END DESCRIPTION:
XS GIS Cut Line= 3
      1964874.98     13869924.97      1964975.00     13870075.00
      1965275.01     13870375.01
#Sta/Elev= 30
  4819.7 1689.07  4842.3 1687.00  4855.8 1683.96  4863.3 1681.51  4891.9 1676.49
  4899.4 1673.60  4905.4 1672.71  4941.4 1663.03  4950.4 1661.74  4964.0 1661.35
  4977.0 1659.14  4992.5 1657.04  4997.0 1655.16  5012.2 1654.64  5012.4 1654.14
  5015.9 1654.14  5016.2 1654.64  5028.3 1656.48  5042.4 1657.86  5056.6 1658.52
  5084.9 1657.05  5147.0 1660.32  5268.7 1672.48  5282.9 1674.85  5297.0 1676.13
  5311.1 1679.13  5339.4 1681.68  5381.9 1686.23  5410.1 1690.04  5424.3 1691.12
#Mann=5,-1,0
  4819.7     0.1       0  4977.0    0.07       0  5012.2    0.05       0
  5016.2    0.07       0  5147.0     0.1       0
Bank Sta=5012.2,5016.2
Exp/Cntr=0.3,0.1

Type RM Length L Ch R = 1,1828,421,421,421
BEGIN DESCRIPTION:
Stream0607 4.0
END DESCRIPTION:
XS GIS Cut Line= 3
      1964524.98     13870174.97      1964675.00     13870425.00
      1964875.01     13870575.01
#Sta/Elev= 30
  4708.7 1681.78  4743.7 1680.09  4753.4 1678.84  4774.8 1673.43  4780.7 1670.80
  4790.4 1668.18  4802.0 1663.61  4833.1 1658.13  4839.0 1658.53  4875.9 1654.61
  4891.4 1652.31  4907.0 1651.68  4928.4 1649.08  4942.0 1648.59  4949.7 1647.22
  4986.0 1644.94  4992.5 1644.30  4997.4 1642.90  5003.4 1642.90  5011.8 1640.13
  5012.1 1639.63  5015.6 1639.63  5015.8 1640.13  5022.2 1640.33  5031.5 1642.24
  5063.8 1646.66  5102.7 1650.52  5163.8 1654.81  5200.3 1661.96  5250.3 1666.42
#Mann=5,-1,0
  4708.7     0.1       0  4986.0    0.07       0  5011.8    0.05       0
  5015.8    0.07       0  5102.7     0.1       0
Bank Sta=5011.8,5015.8
Exp/Cntr=0.3,0.1

Type RM Length L Ch R = 1,1407,465,465,465
BEGIN DESCRIPTION:
Stream0607 3.0
END DESCRIPTION:
XS GIS Cut Line= 3
      1964174.98     13870474.98      1964475.00     13870775.00
      1964775.00     13870775.00
#Sta/Elev= 30
  4570.9 1680.12  4574.5 1680.12  4599.2 1674.24  4627.5 1665.33  4641.6 1661.97
  4657.3 1660.12  4698.2 1655.02  4712.4 1654.81  4726.5 1652.86  4799.0 1647.39
  4825.5 1645.17  4839.6 1644.73  4910.3 1638.35  4966.9 1634.73  4981.1 1634.18
  5015.2 1634.70  5025.2 1634.01  5043.2 1633.94  5043.4 1633.44  5046.9 1633.44
  5047.2 1633.94  5065.2 1636.20  5135.2 1641.40  5145.2 1643.12  5165.2 1647.68
  5205.2 1653.88  5215.2 1654.64  5255.2 1659.69  5285.2 1662.15  5295.2 1662.37
#Mann=5,-1,0
  4570.9    0.07       0  4657.3   0.035       0  4799.0     0.1       0
  5043.2    0.05       0  5047.2     0.1       0
Bank Sta=5043.2,5047.2
Exp/Cntr=0.3,0.1

Type RM Length L Ch R = 1,942,411,411,411
BEGIN DESCRIPTION:
Stream0607 2.0
END DESCRIPTION:
XS GIS Cut Line= 3
      1964024.99     13870824.98      1964225.00     13871125.00
      1964524.99     13871175.00
#Sta/Elev= 30
  4644.7 1646.62  4680.8 1644.74  4745.4 1639.76  4825.0 1636.63  4838.5 1634.71
  4868.6 1632.67  4874.6 1631.83  4883.6 1631.82  4897.8 1630.86  4904.5 1630.29
  4940.7 1626.19  4982.7 1625.73  4989.8 1624.98  4990.0 1624.48  4993.5 1624.48
  4993.8 1624.98  4997.8 1625.58  5007.8 1625.46  5015.4 1625.97  5045.8 1625.47
  5086.4 1628.39  5137.1 1631.19  5147.2 1631.90  5154.8 1633.03  5159.9 1632.94
  5177.6 1634.69  5197.9 1635.57  5208.0 1636.73  5220.7 1636.79  5309.4 1644.07
#Mann=5,-1,0
  4644.7   0.035       0  4897.8    0.07       0  4904.5     0.1       0
  4989.8    0.05       0  4993.8     0.1       0
Bank Sta=4989.8,4993.8
Exp/Cntr=0.3,0.1

Type RM Length L Ch R = 1,531,392,392,392
BEGIN DESCRIPTION:
Stream0607 1.0
END DESCRIPTION:
XS GIS Cut Line= 4
      1963925.00     13871075.02      1963965.32     13871397.55
      1964054.09     13871468.41      1964574.96     13871425.00
#Sta/Elev= 30
  4612.8 1630.86  4650.6 1628.50  4655.6 1629.53  4731.2 1624.24  4736.2 1624.52
  4766.2 1622.68  4811.8 1620.46  4865.8 1619.48  4892.4 1619.06  4905.0 1619.73
  4942.8 1618.95  4971.6 1619.07  5004.8 1617.92  5005.1 1617.42  5008.6 1617.42
  5008.8 1617.92  5021.3 1618.46  5042.1 1618.00  5092.5 1618.61  5153.5 1620.51
  5212.9 1622.39  5243.0 1624.22  5275.6 1625.03  5323.3 1627.97  5353.4 1630.78
  5391.0 1632.01  5413.6 1633.58  5453.7 1637.64  5493.9 1643.45  5574.1 1648.52
#Mann=6,-1,0
  4612.8   0.035       0  4766.2     0.1       0  4865.8    0.07       0
  5004.8    0.05       0  5008.8    0.07       0  5153.5     0.1       0
Bank Sta=5004.8,5008.8
Exp/Cntr=0.3,0.1

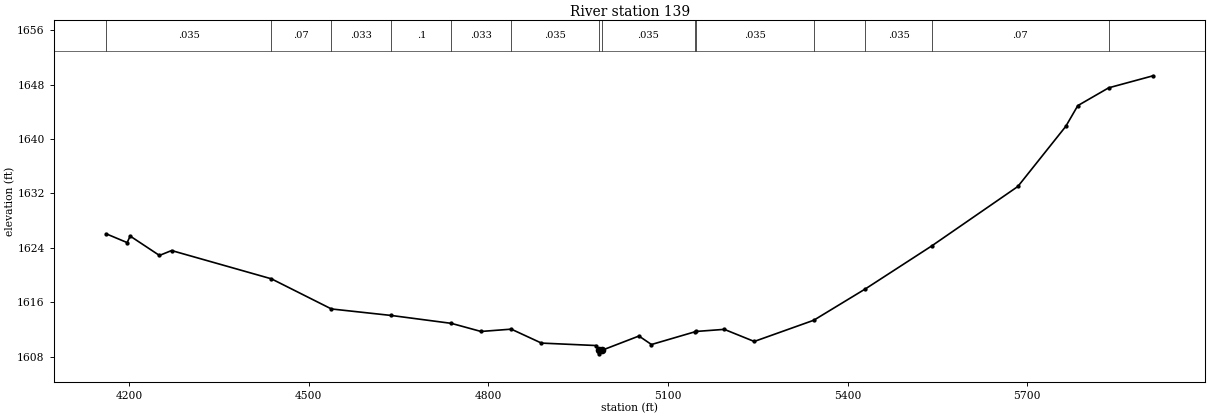
Type RM Length L Ch R = 1,139,0,0,0
BEGIN DESCRIPTION:
Stream0607 0.0
END DESCRIPTION:
XS GIS Cut Line= 5
      1963654.08     13870947.24      1963755.65     13871569.65
      1963773.88     13871707.67      1963898.88     13871817.04
      1964710.69     13871840.46
#Sta/Elev= 30
  4162.1 1626.06  4197.1 1624.77  4202.1 1625.73  4251.0 1622.88  4271.3 1623.60
  4438.0 1619.44  4538.2 1615.01  4638.4 1614.05  4738.6 1612.89  4787.9 1611.70
  4838.5 1612.04  4888.9 1609.99  4980.5 1609.63  4985.2 1608.91  4985.4 1608.41
  4989.2 1608.91  5051.7 1611.03  5072.6 1609.78  5145.5 1611.66  5146.9 1611.70
  5194.2 1612.01  5244.2 1610.23  5343.6 1613.35  5429.8 1617.96  5540.6 1624.28
  5684.4 1633.02  5764.5 1641.87  5784.5 1644.91  5836.1 1647.53  5910.2 1649.30
#Mann=14,-1,0
  4162.1   0.035       0  4438.0    0.07       0  4538.2   0.033       0
  4638.4     0.1       0  4738.6   0.033       0  4838.5   0.035       0
  4985.2   0.035       0  4989.2   0.035       0  5145.5    0.07       0
  5146.9   0.035       0  5343.6    0.07       0  5429.8   0.035       0
  5540.6    0.07       0  5836.1     0.1       0
Bank Sta=4985.2,4989.2
Exp/Cntr=0.3,0.1

Chan Stop Cuts=-1