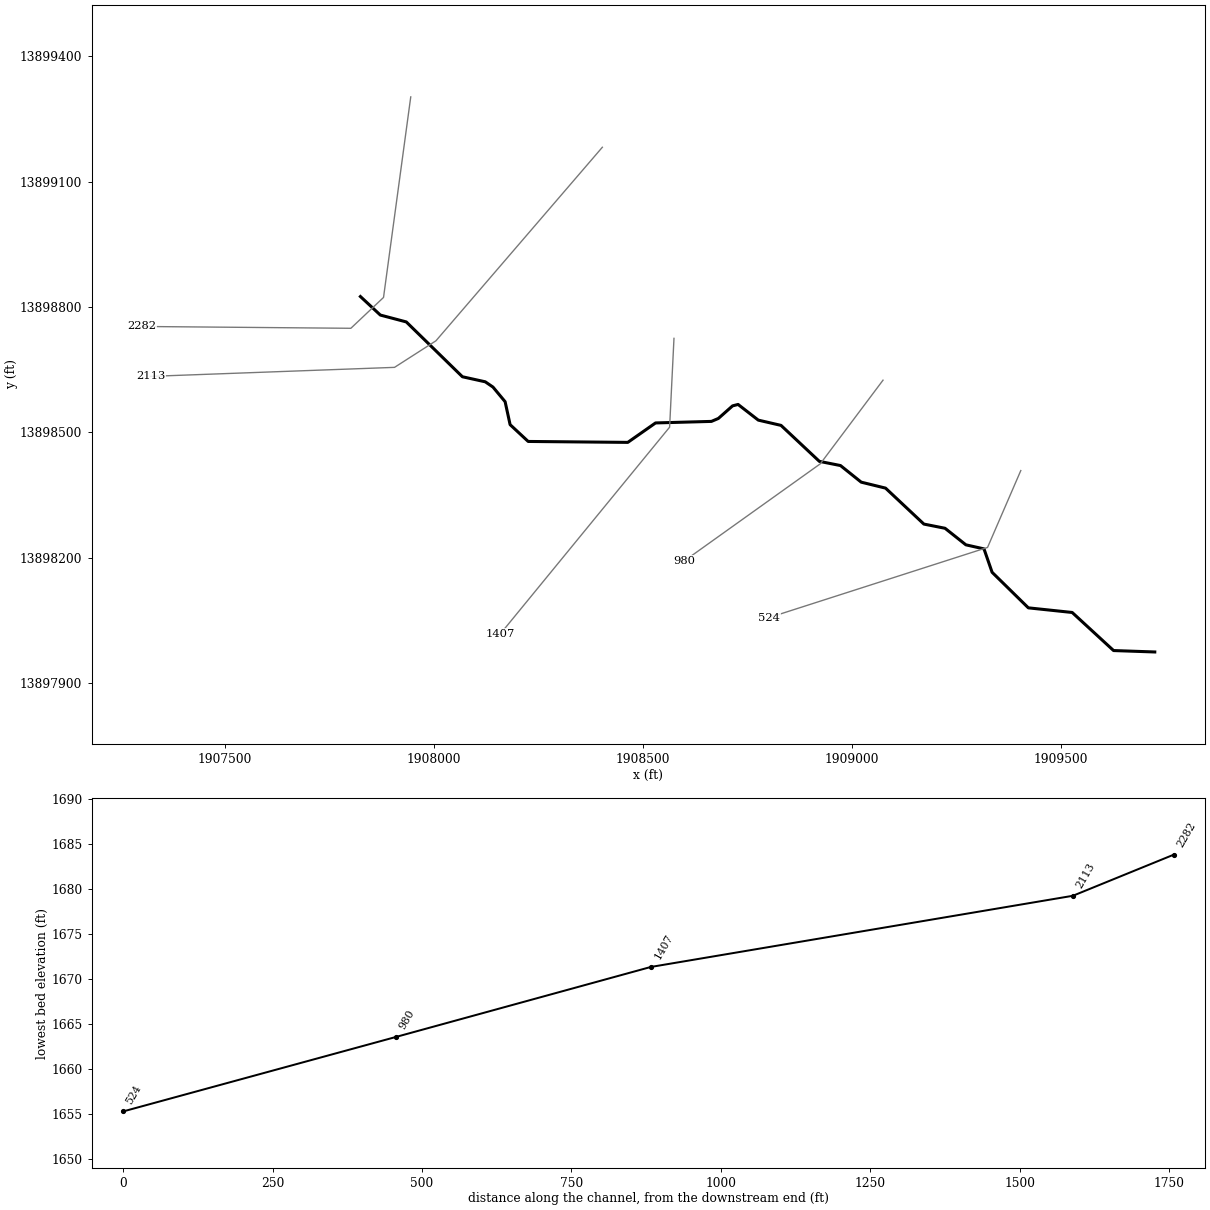
--- Stream0608.prj (project) ---

Proj Title=Stream0608 Base Level Engineering
Current Plan=p01
Default Exp/Contr=0.3,0.1
English Units
Geom File=g01
Flow File=f01
Plan File=p01
BEGIN DESCRIPTION:
Stream0608
END DESCRIPTION:

--- Stream0608.p01 (plan) ---

Plan Title=Multiple Run
Short Identifier=Multiple
Geom File=g01
Flow File=f01
Subcritical Flow
K Sum by GR= 0
Std Step Tol= 0.01
Critical Tol= 0.01
Num of Std Step Trials= 20
Max Error Tol= 0.3
Flow Tol Ratio= 0.001
Split Flow NTrial= 30
Split Flow Tol= 0.02
Split Flow Ratio= 0.02
Log Output Level= 0
Friction Slope Method= 1
Unsteady Friction Slope Method= 2
Unsteady Bridges Friction Slope Method= 1
Parabolic Critical Depth
Global Vel Dist=  1 , 1 , 1
Global Log Level= 0
CheckData=True
Encroach Param= -1, 0, 0, 0
BEGIN DESCRIPTION:
Multiple Run
END DESCRIPTION:

--- Stream0608.f01 (steady flow) ---

Flow Title=Multiple
Number of Profiles=7
Profile Names=10-year,25-year,50-year,1pct_min,100-year,1pct_plu,500-year
River Rch & RM= Stream0608,Reach-1,2282
    1365    2364    3330    2269    4527    9033    8263
Boundary for River Rch & Prof#=Stream0608,Reach-1,1
Up Type=0
Dn Type=3
Dn Slope=0.005
Boundary for River Rch & Prof#=Stream0608,Reach-1,2
Up Type=0
Dn Type=3
Dn Slope=0.005
Boundary for River Rch & Prof#=Stream0608,Reach-1,3
Up Type=0
Dn Type=3
Dn Slope=0.005
Boundary for River Rch & Prof#=Stream0608,Reach-1,4
Up Type=0
Dn Type=3
Dn Slope=0.005
Boundary for River Rch & Prof#=Stream0608,Reach-1,5
Up Type=0
Dn Type=3
Dn Slope=0.005
Boundary for River Rch & Prof#=Stream0608,Reach-1,6
Up Type=0
Dn Type=3
Dn Slope=0.005
Boundary for River Rch & Prof#=Stream0608,Reach-1,7
Up Type=0
Dn Type=3
Dn Slope=0.005

--- Stream0608.g01 (geometry) ---

Geom Title=Existing Conditions

River Reach=Stream0608,Reach-1
Reach XY= 30
      1907825.00     13898825.00      1907872.65     13898780.71
      1907934.71     13898764.30      1908068.97     13898633.17
      1908123.57     13898621.11      1908142.05     13898608.50
      1908171.10     13898573.53      1908183.03     13898518.64
      1908226.25     13898478.45      1908464.50     13898476.22
      1908530.94     13898522.73      1908664.56     13898526.40
      1908681.18     13898533.46      1908715.10     13898563.54
      1908728.32     13898566.96      1908776.65     13898529.45
      1908831.04     13898516.86      1908922.71     13898430.85
      1908973.27     13898420.81      1909022.81     13898381.10
      1909081.05     13898366.84      1909172.71     13898280.85
      1909223.29     13898270.82      1909273.15     13898231.24
      1909316.52     13898221.49      1909335.88     13898165.56
      1909422.56     13898080.52      1909527.42     13898069.46
      1909626.41     13897978.39      1909725.00     13897975.00

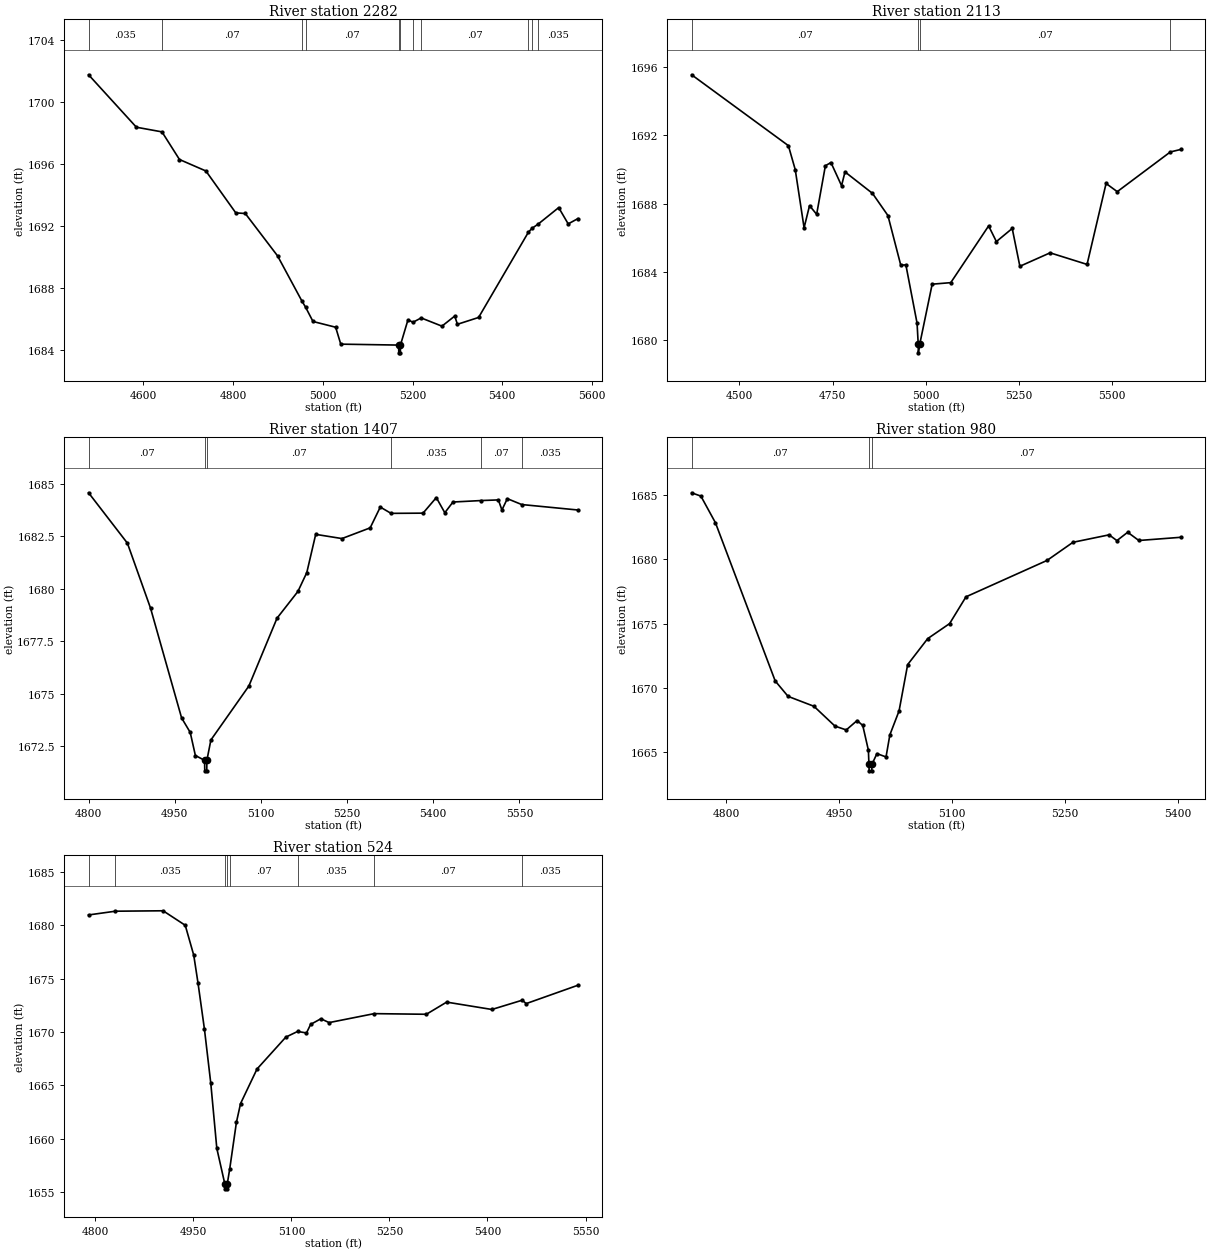
Type RM Length L Ch R = 1,2282,169,169,169
BEGIN DESCRIPTION:
Stream0608 6.0
END DESCRIPTION:
XS GIS Cut Line= 4
      1907945.38     13899302.43      1907880.28     13898822.85
      1907802.15     13898749.07      1907303.00     13898753.41
#Sta/Elev= 30
  4477.9 1701.73  4584.5 1698.35  4641.5 1698.05  4680.5 1696.27  4739.4 1695.53
  4806.0 1692.83  4827.2 1692.79  4899.1 1690.06  4952.8 1687.18  4961.8 1686.74
  4978.1 1685.83  5028.6 1685.46  5040.0 1684.37  5169.0 1684.31  5169.3 1683.81
  5172.8 1683.81  5173.0 1684.31  5189.8 1685.94  5200.9 1685.78  5219.2 1686.06
  5265.5 1685.53  5294.0 1686.18  5300.0 1685.65  5347.2 1686.09  5457.9 1691.57
  5466.0 1691.83  5480.1 1692.11  5525.7 1693.17  5546.9 1692.12  5568.5 1692.46
#Mann=11,-1,0
  4477.9   0.035       0  4641.5    0.07       0  4952.8   0.035       0
  4961.8    0.07       0  5169.0    0.05       0  5173.0    0.07       0
  5200.9   0.035       0  5219.2    0.07       0  5457.9   0.035       0
  5466.0    0.07       0  5480.1   0.035       0
Bank Sta=5169,5173
Exp/Cntr=0.3,0.1

Type RM Length L Ch R = 1,2113,706,706,706
BEGIN DESCRIPTION:
Stream0608 4.0
END DESCRIPTION:
XS GIS Cut Line= 4
      1908403.66     13899182.00      1908005.68     13898719.18
      1907906.62     13898655.64      1907322.81     13898634.07
#Sta/Elev= 30
  4371.7 1695.56  4631.2 1691.40  4649.6 1689.99  4673.3 1686.58  4687.9 1687.88
  4707.0 1687.37  4730.4 1690.22  4745.3 1690.41  4773.8 1689.05  4783.0 1689.86
  4856.7 1688.60  4898.1 1687.30  4932.5 1684.39  4946.3 1684.40  4976.3 1680.98
  4979.4 1679.74  4979.7 1679.24  4983.4 1679.74  5016.8 1683.27  5066.7 1683.36
  5168.2 1686.69  5189.0 1685.77  5231.5 1686.54  5252.0 1684.32  5333.1 1685.11
  5432.2 1684.43  5483.2 1689.18  5513.2 1688.70  5655.5 1691.03  5684.0 1691.18
#Mann=4,-1,0
  4371.7    0.07       0  4979.4    0.05       0  4983.4    0.07       0
  5655.5   0.035       0
Bank Sta=4979.4,4983.4
Exp/Cntr=0.3,0.1

Type RM Length L Ch R = 1,1407,427,427,427
BEGIN DESCRIPTION:
Stream0608 3.0
END DESCRIPTION:
XS GIS Cut Line= 3
      1908575.00     13898725.02      1908564.53     13898512.59
      1908159.73     13898018.28
#Sta/Elev= 30
  4800.1 1684.58  4867.7 1682.18  4907.9 1679.09  4962.0 1673.86  4977.0 1673.17
  4986.0 1672.07  5002.0 1671.84  5002.3 1671.34  5005.8 1671.34  5006.0 1671.84
  5013.0 1672.81  5079.1 1675.38  5128.1 1678.61  5164.4 1679.88  5179.9 1680.78
  5195.4 1682.60  5241.1 1682.40  5290.2 1682.91  5307.8 1683.90  5326.5 1683.60
  5382.2 1683.61  5405.3 1684.35  5420.1 1683.63  5434.3 1684.14  5483.3 1684.21
  5513.3 1684.24  5519.5 1683.76  5528.9 1684.30  5553.9 1684.02  5651.7 1683.76
#Mann=6,-1,0
  4800.1    0.07       0  5002.0    0.05       0  5006.0    0.07       0
  5326.5   0.035       0  5483.3    0.07       0  5553.9   0.035       0
Bank Sta=5002,5006
Exp/Cntr=0.3,0.1

Type RM Length L Ch R = 1,980,456,456,456
BEGIN DESCRIPTION:
Stream0608 2.0
END DESCRIPTION:
XS GIS Cut Line= 3
      1909075.00     13898625.01      1908925.00     13898425.00
      1908599.96     13898192.92
#Sta/Elev= 30
  4754.5 1685.18  4766.8 1684.92  4786.1 1682.85  4865.4 1670.55  4882.5 1669.35
  4916.8 1668.58  4944.7 1667.04  4959.7 1666.74  4974.1 1667.47  4981.6 1667.09
  4989.1 1665.16  4989.8 1664.06  4990.1 1663.56  4993.6 1663.56  4993.8 1664.06
  5000.4 1664.90  5012.5 1664.64  5017.6 1666.36  5029.8 1668.22  5041.2 1671.82
  5067.8 1673.84  5096.9 1675.01  5118.6 1677.09  5226.2 1679.92  5260.6 1681.33
  5308.6 1681.91  5318.9 1681.46  5333.2 1682.11  5348.0 1681.47  5403.9 1681.72
#Mann=3,-1,0
  4754.5    0.07       0  4989.8    0.05       0  4993.8    0.07       0
Bank Sta=4989.8,4993.8
Exp/Cntr=0.3,0.1

Type RM Length L Ch R = 1,524,0,0,0
BEGIN DESCRIPTION:
Stream0608 1.0
END DESCRIPTION:
XS GIS Cut Line= 3
      1909404.51     13898408.79      1909325.00     13898225.00
      1908802.90     13898057.36
#Sta/Elev= 30
  4789.7 1680.97  4830.7 1681.32  4903.7 1681.36  4937.6 1680.00  4950.6 1677.20
  4957.2 1674.56  4967.0 1670.25  4976.7 1665.18  4985.9 1659.09  4998.0 1655.80
  4998.2 1655.30  5001.7 1655.30  5002.0 1655.80  5005.7 1657.19  5015.9 1661.54
  5022.2 1663.29  5047.4 1666.53  5091.5 1669.52  5109.5 1670.05  5123.1 1669.91
  5129.4 1670.71  5145.1 1671.24  5157.7 1670.88  5226.7 1671.72  5306.5 1671.66
  5337.5 1672.80  5406.7 1672.11  5453.2 1672.98  5459.2 1672.66  5538.3 1674.38
#Mann=8,-1,0
  4789.7    0.07       0  4830.7   0.035       0  4998.0   0.035       0
  5002.0   0.035       0  5005.7    0.07       0  5109.5   0.035       0
  5226.7    0.07       0  5453.2   0.035       0
Bank Sta=4998,5002
Exp/Cntr=0.3,0.1

Chan Stop Cuts=-1