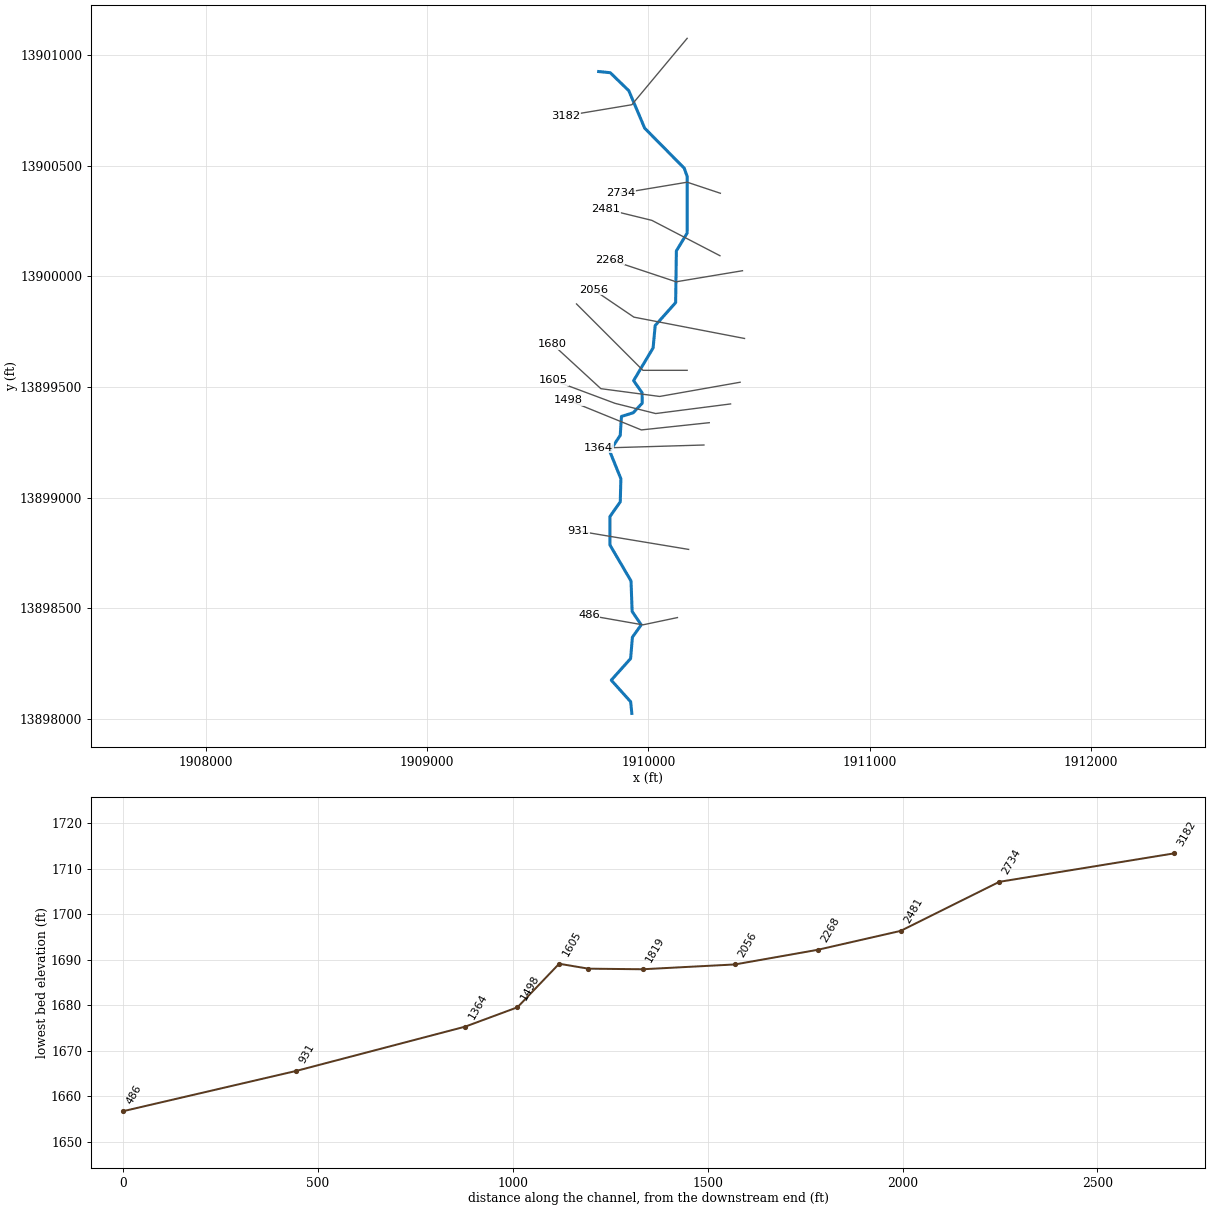
--- Stream0609.prj (project) ---

Proj Title=Stream0609 Base Level Engineering
Current Plan=p01
Default Exp/Contr=0.3,0.1
English Units
Geom File=g01
Flow File=f01
Plan File=p01
BEGIN DESCRIPTION:
Stream0609
END DESCRIPTION:

--- Stream0609.p01 (plan) ---

Plan Title=Multiple Run
Short Identifier=Multiple
Geom File=g01
Flow File=f01
Subcritical Flow
K Sum by GR= 0
Std Step Tol= 0.01
Critical Tol= 0.01
Num of Std Step Trials= 20
Max Error Tol= 0.3
Flow Tol Ratio= 0.001
Split Flow NTrial= 30
Split Flow Tol= 0.02
Split Flow Ratio= 0.02
Log Output Level= 0
Friction Slope Method= 1
Unsteady Friction Slope Method= 2
Unsteady Bridges Friction Slope Method= 1
Parabolic Critical Depth
Global Vel Dist=  1 , 1 , 1
Global Log Level= 0
CheckData=True
Encroach Param= -1, 0, 0, 0
BEGIN DESCRIPTION:
Multiple Run
END DESCRIPTION:

--- Stream0609.f01 (steady flow) ---

Flow Title=Multiple
Number of Profiles=7
Profile Names=10-year,25-year,50-year,1pct_min,100-year,1pct_plu,500-year
River Rch & RM= Stream0609,Reach-1,3182
     925    1563    2166    1454    2902    5789    5136
Boundary for River Rch & Prof#=Stream0609,Reach-1,1
Up Type=0
Dn Type=3
Dn Slope=0.005
Boundary for River Rch & Prof#=Stream0609,Reach-1,2
Up Type=0
Dn Type=3
Dn Slope=0.005
Boundary for River Rch & Prof#=Stream0609,Reach-1,3
Up Type=0
Dn Type=3
Dn Slope=0.005
Boundary for River Rch & Prof#=Stream0609,Reach-1,4
Up Type=0
Dn Type=3
Dn Slope=0.005
Boundary for River Rch & Prof#=Stream0609,Reach-1,5
Up Type=0
Dn Type=3
Dn Slope=0.005
Boundary for River Rch & Prof#=Stream0609,Reach-1,6
Up Type=0
Dn Type=3
Dn Slope=0.005
Boundary for River Rch & Prof#=Stream0609,Reach-1,7
Up Type=0
Dn Type=3
Dn Slope=0.005

--- Stream0609.g01 (geometry) ---

Geom Title=Existing Conditions

River Reach=Stream0609,Reach-1
Reach XY= 30
      1909775.00     13900925.00      1909827.54     13900919.70
      1909911.40     13900838.24      1909983.14     13900668.94
      1910161.63     13900488.32      1910175.30     13900450.12
      1910174.93     13900195.03      1910126.22     13900114.50
      1910122.93     13899880.86      1910030.54     13899777.42
      1910021.17     13899676.59      1909933.07     13899528.31
      1909971.43     13899473.32      1909971.90     13899426.45
      1909931.08     13899383.19      1909878.19     13899366.65
      1909872.58     13899281.05      1909825.09     13899209.61
      1909875.50     13899085.17      1909872.75     13898980.94
      1909826.21     13898914.49      1909826.19     13898785.50
      1909921.24     13898623.44      1909926.40     13898485.44
      1909967.44     13898425.00      1909927.56     13898369.10
      1909919.45     13898272.57      1909832.07     13898175.00
      1909919.65     13898077.52      1909925.00     13898025.00

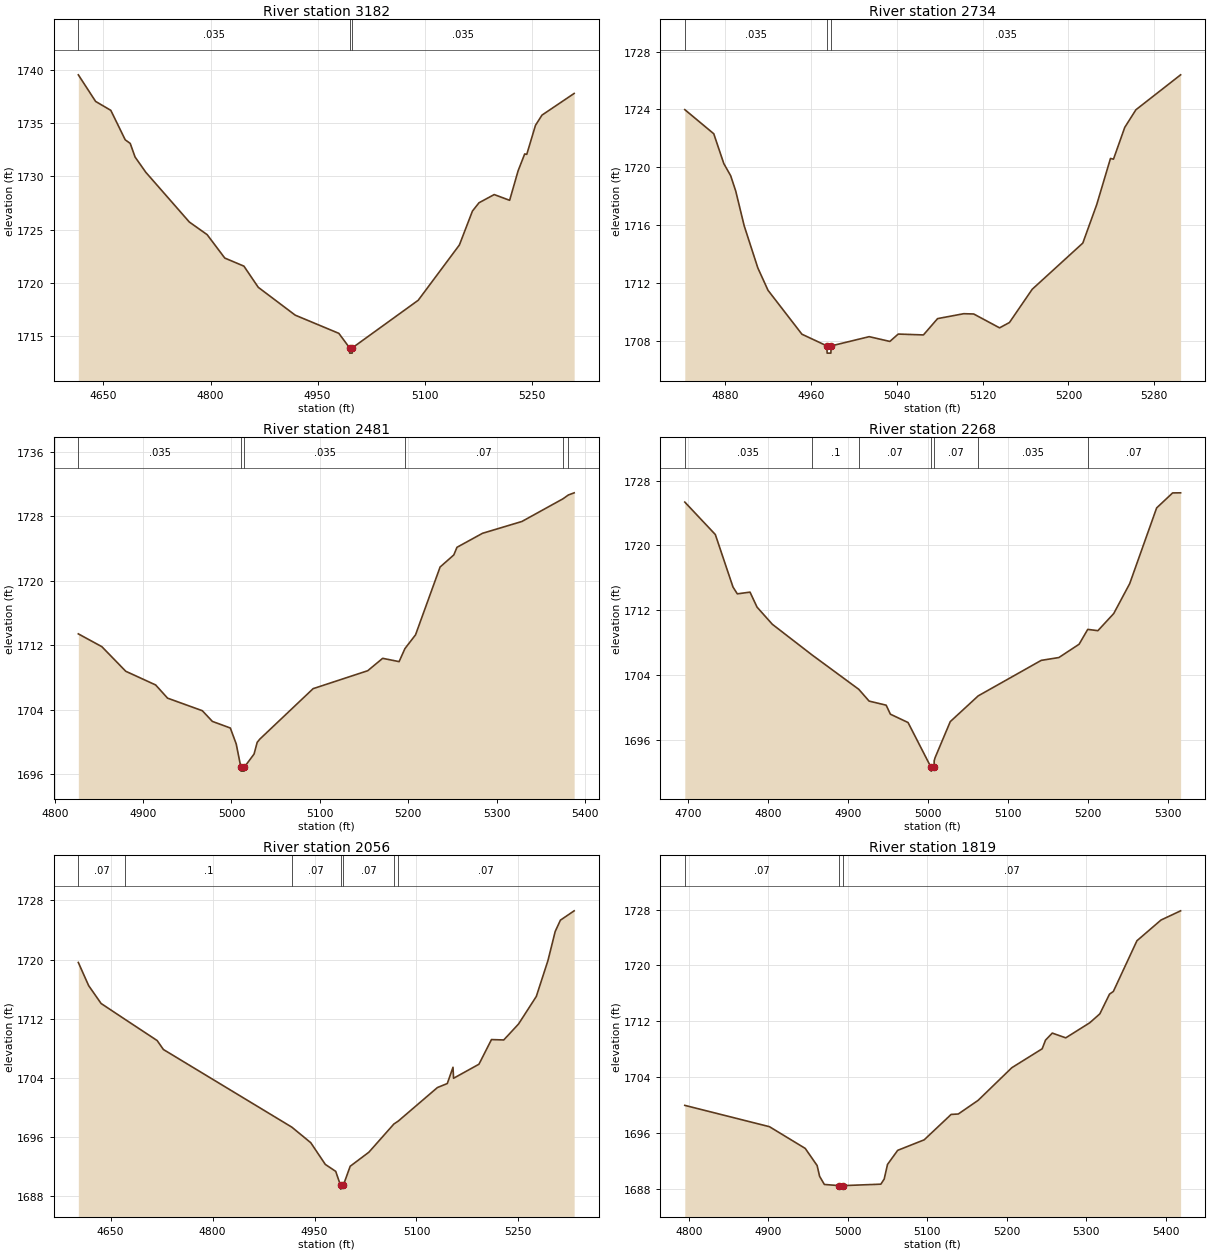
Type RM Length L Ch R = 1,3182,448,448,448
BEGIN DESCRIPTION:
Stream0609 7.0
END DESCRIPTION:
XS GIS Cut Line= 3
      1910175.00     13901075.00      1909925.00     13900775.00
      1909624.95     13900724.99
#Sta/Elev= 30
  4614.8 1739.55  4639.0 1737.05  4660.3 1736.21  4680.5 1733.44  4687.5 1733.10
  4694.3 1731.82  4709.3 1730.39  4770.3 1725.71  4795.3 1724.52  4820.0 1722.32
  4846.8 1721.56  4866.9 1719.57  4918.7 1716.95  4979.8 1715.24  4994.8 1713.88
  4995.0 1713.38  4998.5 1713.38  4998.8 1713.88  5091.0 1718.35  5148.7 1723.55
  5167.0 1726.74  5176.2 1727.52  5197.5 1728.29  5219.1 1727.75  5230.9 1730.51
  5240.2 1732.11  5243.1 1732.07  5255.3 1734.80  5264.4 1735.76  5309.5 1737.80
#Mann=3,-1,0
  4614.8   0.035       0  4994.8   0.035       0  4998.8   0.035       0
Bank Sta=4994.8,4998.8
Exp/Cntr=0.3,0.1

Type RM Length L Ch R = 1,2734,253,253,253
BEGIN DESCRIPTION:
Stream0609 6.0
END DESCRIPTION:
XS GIS Cut Line= 3
      1910325.03     13900374.99      1910175.00     13900425.00
      1909874.99     13900375.00
#Sta/Elev= 30
  4842.3 1723.99  4869.3 1722.32  4878.7 1720.25  4885.1 1719.41  4889.8 1718.35
  4897.7 1715.94  4910.4 1713.03  4919.9 1711.48  4951.5 1708.44  4974.8 1707.63
  4975.0 1707.13  4978.5 1707.13  4978.8 1707.63  5014.2 1708.27  5033.5 1707.94
  5041.3 1708.45  5064.8 1708.39  5078.0 1709.52  5102.4 1709.86  5111.7 1709.84
  5135.8 1708.88  5145.0 1709.25  5166.2 1711.55  5213.4 1714.75  5226.4 1717.42
  5239.2 1720.61  5242.0 1720.56  5252.5 1722.76  5262.9 1723.98  5304.6 1726.40
#Mann=3,-1,0
  4842.3   0.035       0  4974.8   0.035       0  4978.8   0.035       0
Bank Sta=4974.8,4978.8
Exp/Cntr=0.3,0.1

Type RM Length L Ch R = 1,2481,213,213,213
BEGIN DESCRIPTION:
Mapping XS 4092250f
END DESCRIPTION:
XS GIS Cut Line= 3
      1910323.08     13900092.86      1910015.44     13900252.57
      1909807.12     13900303.56
#Sta/Elev= 30
  4826.7 1713.41  4853.3 1711.82  4880.4 1708.76  4914.2 1707.06  4927.7 1705.42
  4967.0 1703.86  4978.4 1702.53  4998.7 1701.71  5005.4 1699.72  5010.6 1696.85
  5010.8 1696.35  5014.3 1696.35  5014.6 1696.85  5025.6 1698.48  5029.1 1699.93
  5032.1 1700.33  5092.4 1706.60  5154.2 1708.83  5171.1 1710.37  5189.7 1709.96
  5196.3 1711.58  5208.3 1713.29  5236.1 1721.72  5251.6 1723.22  5255.2 1724.17
  5284.1 1725.91  5328.7 1727.38  5375.2 1730.20  5381.2 1730.67  5387.8 1730.94
#Mann=6,-1,0
  4826.7   0.035       0  5010.6   0.035       0  5014.6   0.035       0
  5196.3    0.07       0  5375.2     0.1       0  5381.2    0.07       0
Bank Sta=5010.6,5014.6
Exp/Cntr=0.3,0.1

Type RM Length L Ch R = 1,2268,212,212,212
BEGIN DESCRIPTION:
Stream0609 5.0
END DESCRIPTION:
XS GIS Cut Line= 3
      1910424.95     13900024.99      1910125.00     13899975.00
      1909825.02     13900074.99
#Sta/Elev= 30
  4696.0 1725.35  4734.2 1721.35  4756.3 1714.88  4761.7 1714.04  4777.6 1714.25
  4786.4 1712.40  4805.5 1710.29  4855.2 1706.51  4913.7 1702.27  4926.6 1700.82
  4947.9 1700.32  4953.2 1699.21  4975.3 1698.18  5003.9 1692.69  5004.2 1692.19
  5007.9 1692.69  5008.0 1693.47  5009.1 1693.84  5028.1 1698.29  5063.0 1701.46
  5141.9 1705.84  5164.0 1706.19  5189.3 1707.83  5200.1 1709.66  5212.8 1709.50
  5232.6 1711.61  5252.6 1715.30  5286.3 1724.63  5306.3 1726.48  5316.3 1726.49
#Mann=7,-1,0
  4696.0   0.035       0  4855.2     0.1       0  4913.7    0.07       0
  5003.9    0.05       0  5007.9    0.07       0  5063.0   0.035       0
  5200.1    0.07       0
Bank Sta=5003.9,5007.9
Exp/Cntr=0.3,0.1

Type RM Length L Ch R = 1,2056,237,237,237
BEGIN DESCRIPTION:
Mapping XS fd34ee69
END DESCRIPTION:
XS GIS Cut Line= 3
      1910434.18     13899718.91      1909934.38     13899815.27
      1909751.75     13899939.17
#Sta/Elev= 30
  4602.4 1719.61  4617.6 1716.48  4635.9 1714.07  4670.5 1711.96  4718.4 1709.06
  4727.6 1707.85  4916.7 1697.35  4944.5 1695.25  4965.9 1692.32  4981.2 1691.38
  4988.3 1689.48  4988.6 1688.98  4992.3 1689.48  5002.5 1692.07  5030.0 1693.97
  5066.8 1697.78  5073.3 1698.18  5130.9 1702.71  5145.4 1703.25  5153.8 1705.45
  5154.6 1703.96  5192.0 1705.86  5210.4 1709.19  5228.5 1709.14  5250.3 1711.30
  5276.4 1715.02  5293.5 1719.86  5304.2 1723.80  5311.9 1725.33  5332.1 1726.59
#Mann=7,-1,0
  4602.4    0.07       0  4670.5     0.1       0  4916.7    0.07       0
  4988.3    0.05       0  4992.3    0.07       0  5066.8   0.035       0
  5073.3    0.07       0
Bank Sta=4988.3,4992.3
Exp/Cntr=0.3,0.1

Type RM Length L Ch R = 1,1819,139,139,139
BEGIN DESCRIPTION:
Stream0609 4.0
END DESCRIPTION:
XS GIS Cut Line= 3
      1910174.96     13899575.00      1909975.00     13899575.00
      1909675.02     13899874.98
#Sta/Elev= 30
  4794.8 1699.93  4901.4 1696.87  4946.4 1693.76  4961.4 1691.30  4964.5 1689.76
  4970.5 1688.59  4989.5 1688.42  4989.7 1687.92  4993.2 1687.92  4993.5 1688.42
  5041.6 1688.63  5045.8 1689.36  5050.0 1691.46  5062.8 1693.48  5096.2 1694.99
  5130.1 1698.63  5139.1 1698.69  5164.1 1700.65  5206.5 1705.33  5244.7 1708.04
  5248.9 1709.28  5257.4 1710.29  5274.4 1709.61  5304.6 1711.77  5317.3 1713.05
  5329.5 1715.88  5334.3 1716.26  5364.0 1723.53  5394.3 1726.50  5419.0 1727.82
#Mann=3,-1,0
  4794.8    0.07       0  4989.5    0.05       0  4993.5    0.07       0
Bank Sta=4989.5,4993.5
Exp/Cntr=0.3,0.1

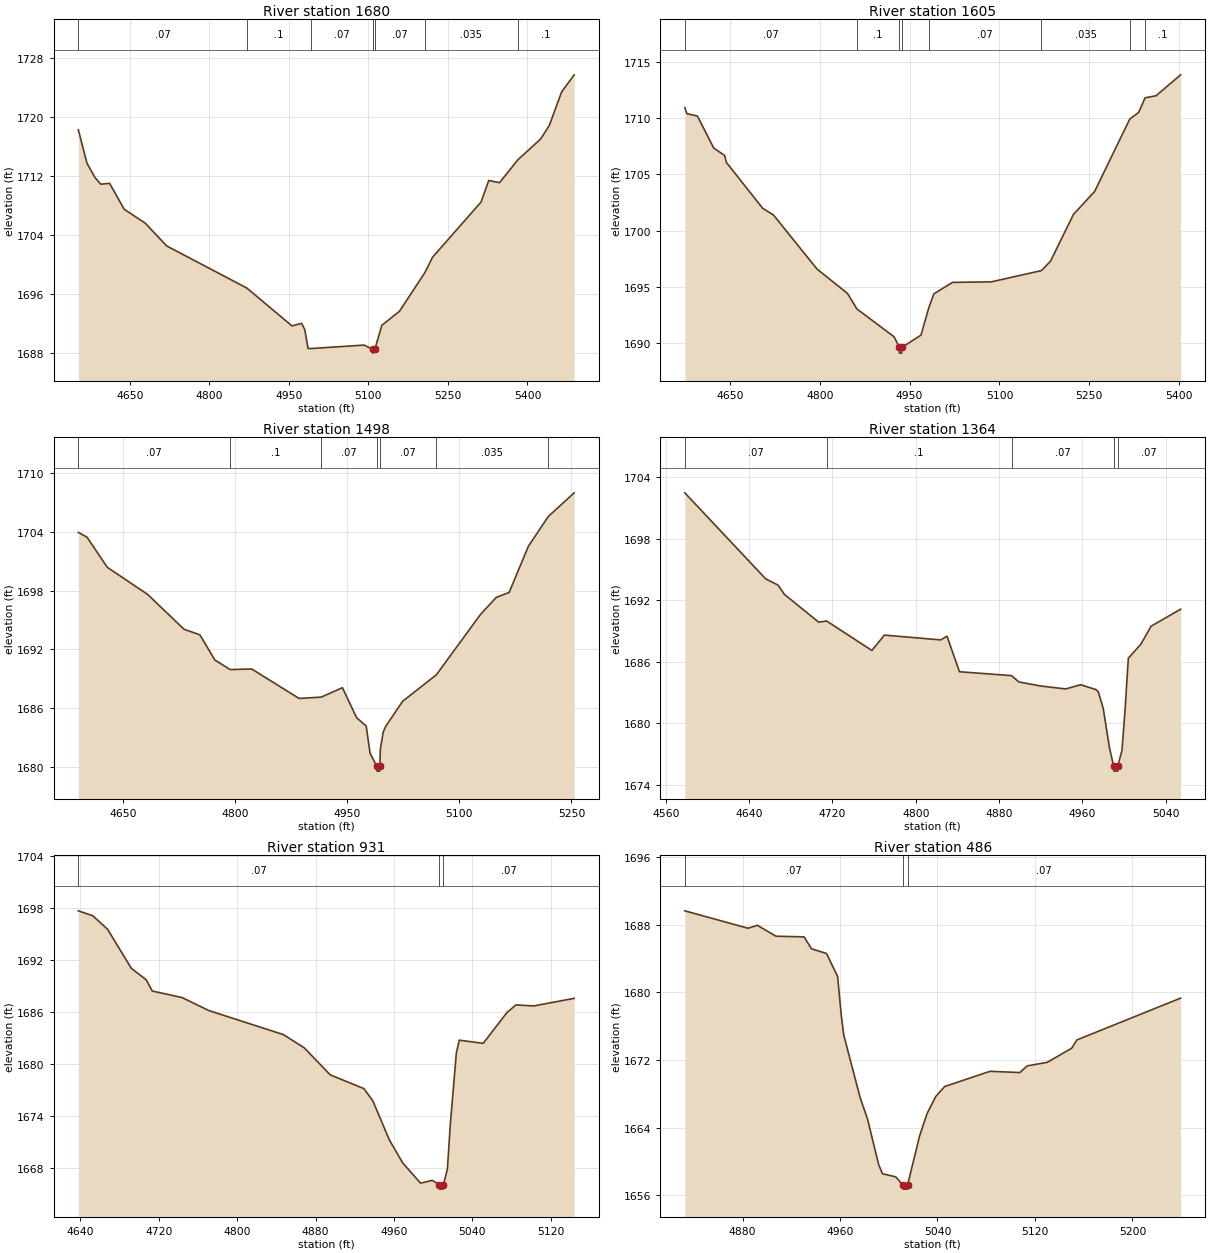
Type RM Length L Ch R = 1,1680,75,75,75
BEGIN DESCRIPTION:
Mapping XS 70deefb4
END DESCRIPTION:
XS GIS Cut Line= 4
      1910414.36     13899521.17      1910050.57     13899456.96
      1909785.14     13899492.05      1909565.66     13899693.85
#Sta/Elev= 30
  4552.8 1718.31  4569.1 1713.78  4584.4 1711.82  4595.2 1710.93  4611.8 1711.05
  4639.3 1707.54  4678.8 1705.67  4719.5 1702.57  4870.6 1696.87  4955.8 1691.74
  4974.0 1692.08  4980.0 1691.23  4986.1 1688.69  4991.6 1688.67  5092.0 1689.14
  5108.1 1688.55  5108.4 1688.05  5112.1 1688.55  5125.3 1691.82  5158.5 1693.71
  5206.3 1698.93  5221.0 1701.04  5312.6 1708.53  5327.0 1711.44  5347.4 1711.14
  5381.8 1714.23  5424.8 1717.05  5441.1 1718.87  5464.5 1723.44  5488.1 1725.75
#Mann=7,-1,0
  4552.8    0.07       0  4870.6     0.1       0  4991.6    0.07       0
  5108.1    0.05       0  5112.1    0.07       0  5206.3   0.035       0
  5381.8     0.1       0
Bank Sta=5108.1,5112.1
Exp/Cntr=0.3,0.1

Type RM Length L Ch R = 1,1605,107,107,107
BEGIN DESCRIPTION:
Stream0609 4.1
END DESCRIPTION:
XS GIS Cut Line= 4
      1910371.18     13899423.12      1910032.62     13899379.71
      1909849.46     13899425.72      1909570.78     13899529.90
#Sta/Elev= 30
  4574.7 1710.93  4578.2 1710.39  4595.8 1710.18  4623.0 1707.34  4641.2 1706.68
  4644.2 1706.06  4704.7 1701.99  4722.8 1701.39  4795.4 1696.60  4846.3 1694.43
  4861.9 1693.06  4924.1 1690.58  4933.0 1689.63  4933.2 1689.13  4936.7 1689.13
  4937.0 1689.63  4969.0 1690.73  4982.0 1693.16  4990.6 1694.40  5021.6 1695.41
  5086.5 1695.46  5170.1 1696.46  5185.2 1697.29  5223.4 1701.44  5258.8 1703.48
  5317.5 1709.91  5332.5 1710.51  5343.0 1711.80  5361.3 1711.98  5402.4 1713.84
#Mann=8,-1,0
  4574.7    0.07       0  4861.9     0.1       0  4933.0    0.05       0
  4937.0     0.1       0  4982.0    0.07       0  5170.1   0.035       0
  5317.5    0.07       0  5343.0     0.1       0
Bank Sta=4933,4937
Exp/Cntr=0.3,0.1

Type RM Length L Ch R = 1,1498,134,134,134
BEGIN DESCRIPTION:
Mapping XS b535ae1f
END DESCRIPTION:
XS GIS Cut Line= 3
      1910274.81     13899338.43      1909968.10     13899305.71
      1909639.79     13899439.31
#Sta/Elev= 30
  4590.7 1703.94  4602.3 1703.45  4629.5 1700.37  4683.3 1697.61  4732.0 1694.05
  4753.2 1693.48  4773.2 1690.91  4793.7 1689.93  4822.5 1689.99  4885.9 1686.98
  4915.5 1687.12  4943.8 1688.08  4962.7 1685.02  4975.6 1684.16  4980.7 1681.40
  4989.8 1680.06  4990.1 1679.56  4993.6 1679.56  4993.8 1680.06  4994.5 1681.82
  4998.3 1683.54  5001.5 1684.11  5024.2 1686.69  5069.4 1689.40  5128.3 1695.55
  5149.4 1697.30  5166.7 1697.81  5192.4 1702.52  5219.0 1705.56  5253.6 1707.98
#Mann=7,-1,0
  4590.7    0.07       0  4793.7     0.1       0  4915.5    0.07       0
  4989.8    0.05       0  4993.8    0.07       0  5069.4   0.035       0
  5219.0    0.07       0
Bank Sta=4989.8,4993.8
Exp/Cntr=0.3,0.1

Type RM Length L Ch R = 1,1364,433,433,433
BEGIN DESCRIPTION:
Stream0609 3.0
END DESCRIPTION:
XS GIS Cut Line= 3
      1910250.84     13899237.56      1909825.00     13899225.00
      1909775.02     13899225.00
#Sta/Elev= 30
  4578.3 1702.50  4655.9 1694.10  4667.9 1693.48  4673.9 1692.58  4706.9 1689.86
  4714.4 1689.98  4757.9 1687.10  4769.9 1688.60  4824.0 1688.13  4830.0 1688.49
  4842.0 1685.02  4892.0 1684.64  4899.0 1684.02  4920.4 1683.62  4944.0 1683.34
  4958.3 1683.75  4972.9 1683.28  4975.3 1683.05  4980.0 1681.44  4986.0 1677.59
  4990.0 1675.81  4990.3 1675.31  4993.8 1675.31  4994.0 1675.81  4998.0 1677.34
  5001.0 1681.35  5004.1 1686.34  5016.1 1687.71  5026.0 1689.47  5054.3 1691.13
#Mann=5,-1,0
  4578.3    0.07       0  4714.4     0.1       0  4892.0    0.07       0
  4990.0    0.05       0  4994.0    0.07       0
Bank Sta=4990,4994
Exp/Cntr=0.3,0.1

Type RM Length L Ch R = 1,931,445,445,445
BEGIN DESCRIPTION:
Stream0609 2.0
END DESCRIPTION:
XS GIS Cut Line= 3
      1910181.65     13898765.85      1909825.00     13898825.00
      1909682.73     13898849.00
#Sta/Elev= 30
  4638.0 1697.70  4652.6 1697.14  4667.8 1695.58  4692.1 1691.06  4707.2 1689.75
  4713.4 1688.45  4743.9 1687.69  4771.2 1686.19  4847.2 1683.42  4868.5 1681.89
  4895.0 1678.77  4929.3 1677.19  4938.4 1675.78  4955.3 1671.27  4968.8 1668.63
  4987.1 1666.28  4999.1 1666.60  5006.4 1666.09  5006.6 1665.59  5010.1 1665.59
  5010.4 1666.09  5014.5 1667.91  5017.5 1673.11  5023.6 1681.27  5026.6 1682.78
  5051.0 1682.41  5075.3 1685.97  5084.4 1686.84  5102.7 1686.73  5143.8 1687.60
#Mann=3,-1,0
  4638.0    0.07       0  5006.4    0.05       0  5010.4    0.07       0
Bank Sta=5006.4,5010.4
Exp/Cntr=0.3,0.1

Type RM Length L Ch R = 1,486,0,0,0
BEGIN DESCRIPTION:
Stream0609 1.0
END DESCRIPTION:
XS GIS Cut Line= 3
      1910131.08     13898457.87      1909975.00     13898425.00
      1909731.24     13898467.81
#Sta/Elev= 30
  4832.6 1689.62  4884.5 1687.56  4892.2 1687.91  4907.4 1686.62  4930.5 1686.54
  4936.6 1685.13  4948.9 1684.58  4958.0 1681.88  4961.2 1677.06  4963.1 1674.93
  4976.5 1667.55  4982.6 1665.00  4991.8 1659.58  4994.9 1658.54  5005.8 1658.17
  5011.5 1657.22  5011.8 1656.72  5015.3 1656.72  5015.5 1657.22  5025.3 1662.99
  5031.4 1665.62  5038.5 1667.65  5045.9 1668.85  5083.2 1670.65  5107.6 1670.50
  5113.7 1671.29  5130.1 1671.71  5150.2 1673.38  5154.5 1674.36  5239.6 1679.30
#Mann=3,-1,0
  4832.6    0.07       0  5011.5    0.05       0  5015.5    0.07       0
Bank Sta=5011.5,5015.5
Exp/Cntr=0.3,0.1

Chan Stop Cuts=-1