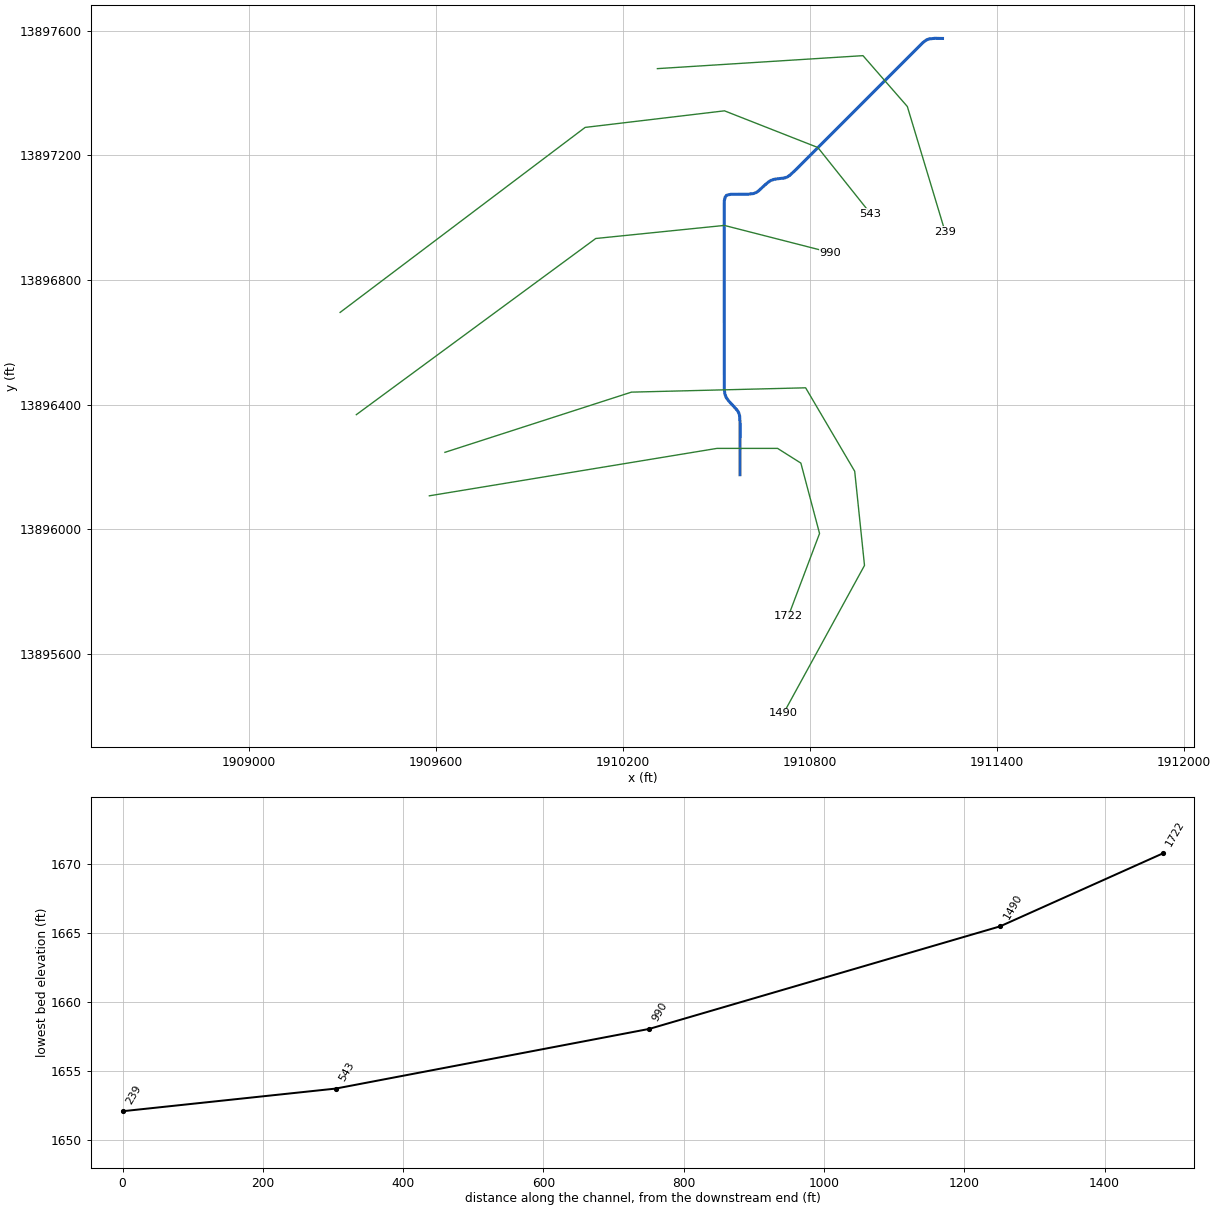
--- Stream0610.prj (project) ---

Proj Title=Stream0610 Base Level Engineering
Current Plan=p01
Default Exp/Contr=0.3,0.1
English Units
Geom File=g01
Flow File=f01
Plan File=p01
Y Axis Title=Elevation
X Axis Title(PF)=Main Channel Distance
X Axis Title(XS)=Station
BEGIN DESCRIPTION:
Stream0610
END DESCRIPTION:
DSS Export Rating Curves= 0
DSS Export Rating Curve Sorted= 0
DSS Export Volume Flow Curves= 0
DXF OffsetX= 0
DXF OffsetY= 0
DXF ScaleX= 1
DXF ScaleY= 10

--- Stream0610.p01 (plan) ---

Plan Title=Multiple Run
Short Identifier=Multiple
Geom File=g01
Flow File=f01
Subcritical Flow
K Sum by GR= 0
Std Step Tol= 0.01
Critical Tol= 0.01
Num of Std Step Trials= 20
Max Error Tol= 0.3
Flow Tol Ratio= 0.001
Split Flow NTrial= 30
Split Flow Tol= 0.02
Split Flow Ratio= 0.02
Log Output Level= 0
Friction Slope Method= 1
Unsteady Friction Slope Method= 2
Unsteady Bridges Friction Slope Method= 1
Parabolic Critical Depth
Global Vel Dist=  1 , 1 , 1
Global Log Level= 0
CheckData=True
Encroach Param= -1, 0, 0, 0
BEGIN DESCRIPTION:
Multiple Run
END DESCRIPTION:

--- Stream0610.f01 (steady flow) ---

Flow Title=Multiple
Program Version=4.10
Number of Profiles= 7
Profile Names=10-year,25-year,50-year,1pct_min,100-year,1pct_plu,500-year
River Rch & RM=Stream0610,Reach-1         ,1722
    1154    1977    2766    1875    3740    7463    6745
Boundary for River Rch & Prof#=Stream0610,Reach-1         , 1
Up Type= 0
Dn Type= 3
Dn Slope=0.009
Boundary for River Rch & Prof#=Stream0610,Reach-1         , 2
Up Type= 0
Dn Type= 3
Dn Slope=0.009
Boundary for River Rch & Prof#=Stream0610,Reach-1         , 3
Up Type= 0
Dn Type= 3
Dn Slope=0.009
Boundary for River Rch & Prof#=Stream0610,Reach-1         , 4
Up Type= 0
Dn Type= 3
Dn Slope=0.009
Boundary for River Rch & Prof#=Stream0610,Reach-1         , 5
Up Type= 0
Dn Type= 3
Dn Slope=0.009
Boundary for River Rch & Prof#=Stream0610,Reach-1         , 6
Up Type= 0
Dn Type= 3
Dn Slope=0.009
Boundary for River Rch & Prof#=Stream0610,Reach-1         , 7
Up Type= 0
Dn Type= 3
Dn Slope=0.009
DSS Import GetInterval= 0
DSS Import GetPeak= 0
DSS Import FillOption= 0

--- Stream0610.g01 (geometry) ---

Geom Title=Existing Conditions
Program Version=4.10

River Reach=Stream0610      ,Reach-1
Reach XY= 30
        1910575.       13896175.      1910575.44     13896340.18
      1910573.79      13896364.5      1910571.22     13896373.44
      1910566.86     13896381.06      1910538.79     13896411.86
      1910530.75     13896422.67      1910526.22      13896435.5
       1910524.8     13896449.92      1910524.31     13897040.68
      1910524.95     13897055.03      1910527.93     13897067.03
      1910532.95       13897072.      1910545.01     13897074.89
      1910599.79     13897075.09      1910618.94     13897077.37
      1910627.26      13897080.8      1910634.61     13897085.85
      1910661.96     13897110.96      1910672.83     13897118.86
      1910685.71     13897123.28      1910718.97      13897127.5
       1910727.3     13897130.83      1910734.68     13897135.76
      1910755.16     13897154.61      1911161.73     13897561.53
      1911172.48     13897569.69      1911181.14     13897573.32
      1911199.63     13897575.41        1911225.       13897575.

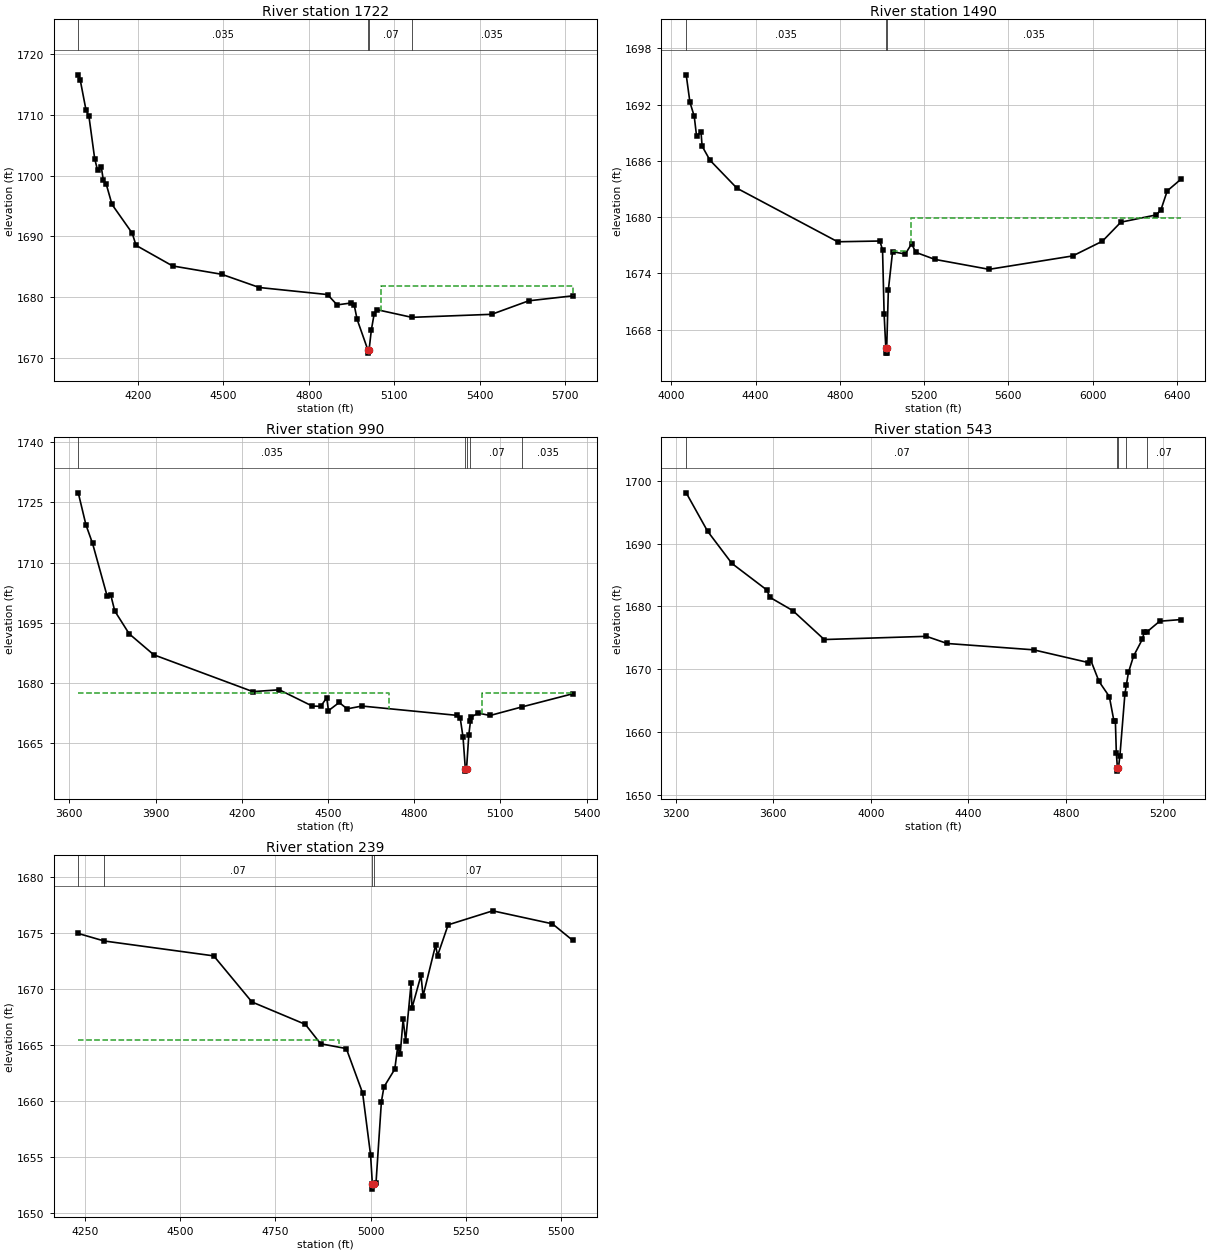
Type RM Length L Ch R = 1 ,1722    ,232,232,232
BEGIN DESCRIPTION:
Stream0610 4.0
END DESCRIPTION:
XS GIS Cut Line= 6
      1909578.13     13896107.25      1910501.01     13896259.42
      1910695.76     13896259.42      1910770.47     13896212.23
      1910830.39     13895986.36      1910729.95     13895720.12
#Sta/Elev= 30
  3990.6 1716.58  3997.6  1715.7  4017.8 1710.78    4028 1709.78  4048.2  1702.8
  4058.4 1700.86  4071.3 1701.46  4078.6 1699.24  4088.8 1698.59  4109.1 1695.24
    4180 1690.52  4193.5 1688.51  4321.9 1685.12  4494.2 1683.75  4626.6 1681.57
  4866.1 1680.41  4899.6 1678.71  4949.9 1679.03  4959.9 1678.65  4969.9 1676.33
  5007.9 1671.27  5008.2 1670.77  5011.9 1671.27  5019.9 1674.57  5029.9 1677.26
  5039.9 1677.92  5162.1 1676.66  5442.7 1677.16  5572.5 1679.38  5727.3  1680.2
#Mann= 4 ,-1 , 0
  3990.6    .035       0  5007.9     .05       0  5011.9     .07       0
  5162.1    .035       0
#XS Ineff= 2 , 0
                         5053.23         1681.81
Permanent Ineff=
       F       F
Bank Sta=5007.9,5011.9
XS Rating Curve= 0 ,0
Exp/Cntr=0.3,0.1

Type RM Length L Ch R = 1 ,1490    ,500,500,500
BEGIN DESCRIPTION:
Stream0610 3.0
END DESCRIPTION:
XS GIS Cut Line= 6
      1909628.17     13896246.79      1910226.71     13896439.97
      1910785.73     13896453.86      1910943.23     13896186.01
      1910974.66     13895883.77      1910714.76     13895409.03
#Sta/Elev= 30
  4071.1 1695.18  4088.8 1692.26  4109.3 1690.75  4120.3 1688.64  4141.3  1689.1
  4146.6 1687.57  4183.9 1686.07  4312.1 1683.08    4790 1677.37  4990.3 1677.45
  5002.9  1676.5  5010.4 1669.64  5018.5 1665.99  5018.7 1665.49  5022.2 1665.49
  5022.5 1665.99  5030.5 1672.24  5050.5 1676.31  5110.7 1676.06  5140.8 1677.15
  5160.9 1676.24  5251.2 1675.49  5508.6 1674.43  5905.4 1675.86  6046.2 1677.43
  6133.9 1679.46  6302.7 1680.24  6324.5 1680.81    6354  1682.8  6417.8 1684.02
#Mann= 3 ,-1 , 0
  4071.1    .035       0  5018.5     .05       0  5022.5    .035       0
#XS Ineff= 2 ,-1
 5052.97 5124.03 1676.34 5140.18  6417.8 1679.93
Permanent Ineff=
       F       F
Bank Sta=5018.5,5022.5
XS Rating Curve= 0 ,0
Exp/Cntr=0.3,0.1

Type RM Length L Ch R = 1 ,990     ,447,447,447
BEGIN DESCRIPTION:
Stream0610 2.0
END DESCRIPTION:
XS GIS Cut Line= 4
      1909343.78     13896367.66      1910112.12     13896933.03
        1910525.       13896975.       1910865.6     13896887.89
#Sta/Elev= 30
  3631.2 1727.35  3657.9 1719.38    3681 1714.74  3731.1 1701.79  3744.5 1701.85
  3758.2 1697.93  3808.3 1692.26  3893.9 1687.03  4238.7 1677.86  4330.6 1678.32
  4445.5 1674.26  4474.8  1674.2  4495.6 1676.32  4501.8 1673.12    4539 1675.16
  4566.6 1673.57  4618.2 1674.27  4947.8 1671.96  4959.9 1671.41    4970 1666.46
    4978 1658.57  4978.3 1658.07    4982 1658.57  4990.1 1667.15  4995.8 1670.48
  4997.6 1671.53  5023.1 1672.51    5064 1671.92  5176.8 1674.09  5351.7 1677.33
#Mann= 5 ,-1 , 0
  3631.2    .035       0    4978     .05       0    4982     .07       0
  4995.8     .07       0  5176.8    .035       0
#XS Ineff= 2 ,-1
  3631.2 4713.95 1677.49 5037.21  5351.7 1677.49
Permanent Ineff=
       F       F
Bank Sta=4978,4982
XS Rating Curve= 0 ,0
Exp/Cntr=0.3,0.1

Type RM Length L Ch R = 1 ,543     ,304,304,304
BEGIN DESCRIPTION:
Stream0610 1.0
END DESCRIPTION:
XS GIS Cut Line= 5
      1909291.74     13896695.82      1910078.17     13897289.55
      1910525.32     13897342.75        1910825.       13897225.
      1910994.05     13897012.91
#Sta/Elev= 30
  3242.3 1698.12    3330    1692  3429.9 1686.86  3572.2 1682.66  3586.1 1681.45
  3679.7 1679.34  3808.7 1674.73  4227.7 1675.24  4313.1  1674.1  4667.6 1673.09
  4892.5 1671.06  4901.1 1671.53  4936.2 1668.04  4978.5 1665.63  4997.3 1661.74
  5003.2 1661.74  5007.2 1656.57  5011.6 1654.25  5011.8 1653.75  5015.6 1654.25
  5021.6  1656.1  5042.4 1666.11  5048.1 1667.44  5056.8 1669.48  5077.6 1672.07
  5114.5 1674.82  5120.9 1675.86    5131 1675.89  5184.9 1677.65  5271.2 1677.91
#Mann= 5 ,-1 , 0
  3242.3     .07       0  5011.6     .05       0  5015.6     .07       0
  5048.1      .1       0    5131     .07       0
Bank Sta=5011.6,5015.6
XS Rating Curve= 0 ,0
Exp/Cntr=0.3,0.1

Type RM Length L Ch R = 1 ,239     ,0,0,0
BEGIN DESCRIPTION:
Stream0610 0.0
END DESCRIPTION:
XS GIS Cut Line= 4
      1910310.03     13897478.17      1910969.76     13897519.84
      1911112.12     13897356.64      1911233.64     13896953.88
#Sta/Elev= 30
  4232.6 1674.92  4300.5 1674.25  4588.3 1672.92  4688.5 1668.81  4828.8 1666.81
  4868.8 1665.08  4936.4 1664.65  4979.2 1660.68    5000 1655.18  5004.7 1652.61
  5004.9 1652.11  5008.7 1652.61  5014.3 1652.65  5028.5 1659.92  5035.2 1661.23
  5063.6 1662.81  5071.2 1664.79  5077.9 1664.15  5085.5 1667.27  5092.1 1665.33
  5106.4 1670.46  5108.6 1668.25  5132.5 1671.19  5137.8 1669.34  5170.7 1673.87
    5176 1672.95  5203.7 1675.69  5320.8 1676.94  5477.5 1675.78  5530.9  1674.3
#Mann= 4 ,-1 , 0
  4232.6    .035       0  4300.5     .07       0  5004.7     .05       0
  5008.7     .07       0
#XS Ineff= 2 , 0
         4916.28 1665.44
Permanent Ineff=
       F       F
Bank Sta=5004.7,5008.7
XS Rating Curve= 0 ,0
Exp/Cntr=0.3,0.1

Chan Stop Cuts=-1
Use User Specified Reach Order=0
Composite Channel Slope=5