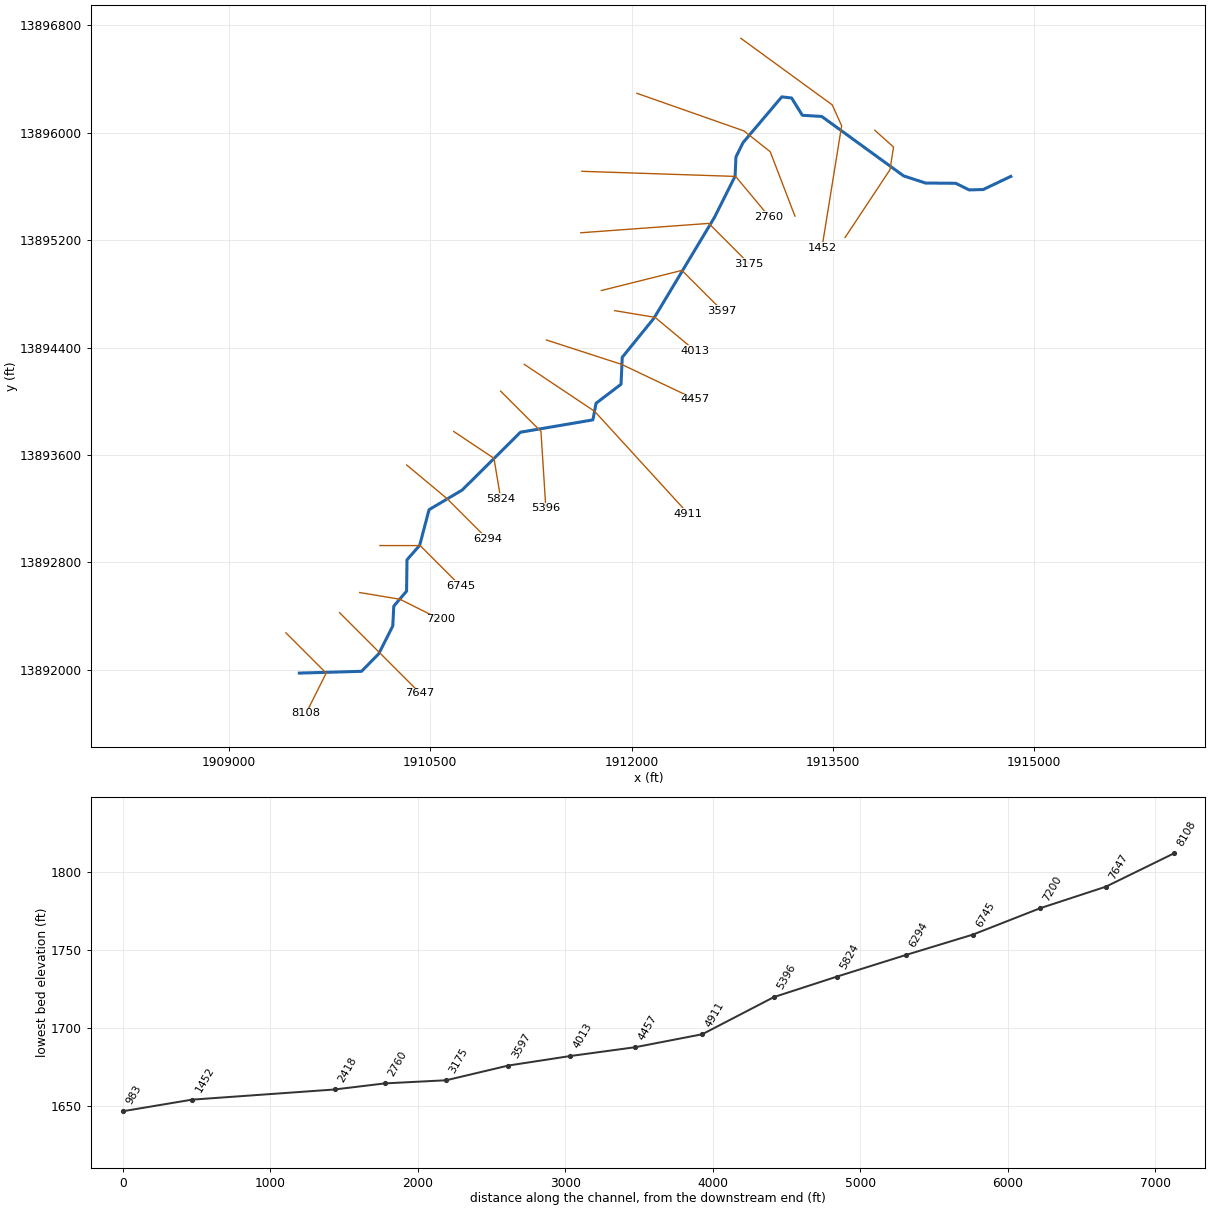
--- Stream0612.prj (project) ---

Proj Title=Stream0612 Base Level Engineering
Current Plan=p01
Default Exp/Contr=0.3,0.1
English Units
Geom File=g01
Flow File=f01
Plan File=p01
BEGIN DESCRIPTION:
Stream0612
END DESCRIPTION:

--- Stream0612.p01 (plan) ---

Plan Title=Multiple Run
Short Identifier=Multiple
Geom File=g01
Flow File=f01
Subcritical Flow
K Sum by GR= 0
Std Step Tol= 0.01
Critical Tol= 0.01
Num of Std Step Trials= 20
Max Error Tol= 0.3
Flow Tol Ratio= 0.001
Split Flow NTrial= 30
Split Flow Tol= 0.02
Split Flow Ratio= 0.02
Log Output Level= 0
Friction Slope Method= 1
Unsteady Friction Slope Method= 2
Unsteady Bridges Friction Slope Method= 1
Parabolic Critical Depth
Global Vel Dist=  1 , 1 , 1
Global Log Level= 0
CheckData=True
Encroach Param= -1, 0, 0, 0
BEGIN DESCRIPTION:
Multiple Run
END DESCRIPTION:

--- Stream0612.f01 (steady flow) ---

Flow Title=Multiple
Number of Profiles=7
Profile Names=10-year,25-year,50-year,1pct_min,100-year,1pct_plu,500-year
River Rch & RM= Stream0612,Reach-1,8108
    1295    2229    3129    2126    4241    8462    7689
Boundary for River Rch & Prof#=Stream0612,Reach-1,1
Up Type=0
Dn Type=3
Dn Slope=0.005
Boundary for River Rch & Prof#=Stream0612,Reach-1,2
Up Type=0
Dn Type=3
Dn Slope=0.005
Boundary for River Rch & Prof#=Stream0612,Reach-1,3
Up Type=0
Dn Type=3
Dn Slope=0.005
Boundary for River Rch & Prof#=Stream0612,Reach-1,4
Up Type=0
Dn Type=3
Dn Slope=0.005
Boundary for River Rch & Prof#=Stream0612,Reach-1,5
Up Type=0
Dn Type=3
Dn Slope=0.005
Boundary for River Rch & Prof#=Stream0612,Reach-1,6
Up Type=0
Dn Type=3
Dn Slope=0.005
Boundary for River Rch & Prof#=Stream0612,Reach-1,7
Up Type=0
Dn Type=3
Dn Slope=0.005

--- Stream0612.g01 (geometry) ---

Geom Title=Existing Conditions

River Reach=Stream0612,Reach-1
Reach XY= 30
      1909525.00     13891975.00      1909988.32     13891988.37
      1910116.86     13892118.94      1910221.24     13892326.56
      1910228.56     13892473.53      1910323.94     13892585.44
      1910327.07     13892819.14      1910421.38     13892926.50
      1910491.30     13893192.13      1910738.21     13893338.63
      1911172.55     13893769.53      1911711.77     13893861.27
      1911735.39     13893985.10      1911921.47     13894126.45
      1911930.46     13894327.45      1912166.84     13894618.95
      1912619.15     13895372.71      1912771.24     13895676.56
      1912777.25     13895819.07      1912830.84     13895927.29
      1913118.97     13896267.55      1913192.05     13896258.94
      1913272.31     13896130.37      1913416.56     13896121.59
      1914026.58     13895678.82      1914190.22     13895625.52
      1914414.50     13895623.78      1914514.83     13895574.50
      1914619.06     13895577.25      1914825.00     13895675.00

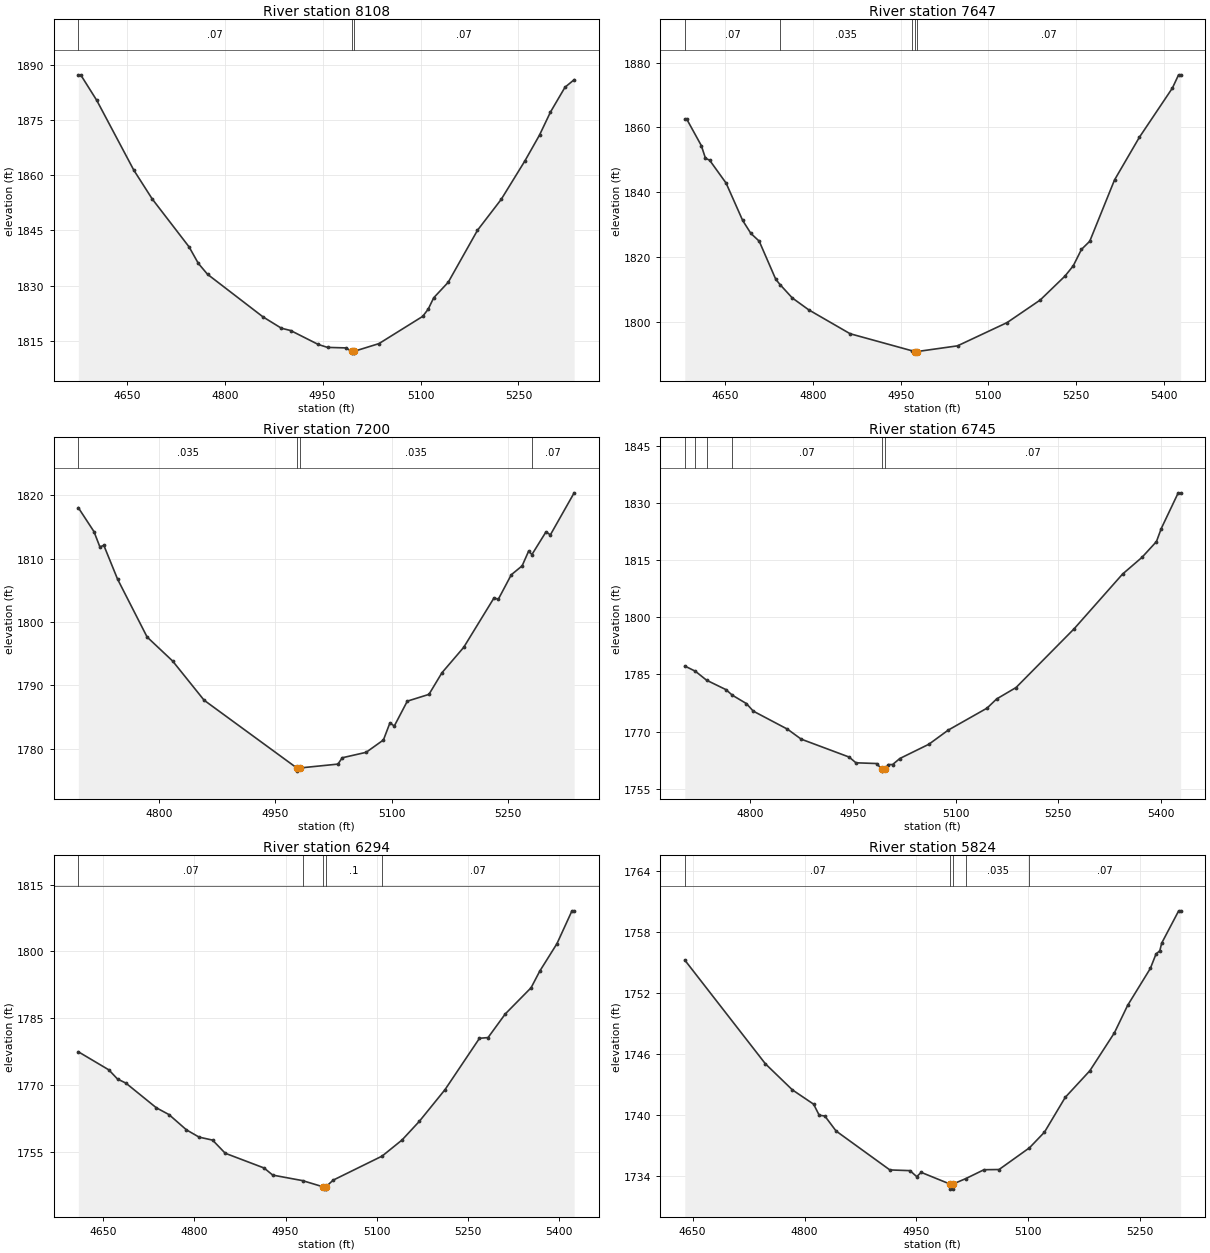
Type RM Length L Ch R = 1,8108,461,461,461
BEGIN DESCRIPTION:
Stream0612 14.0
END DESCRIPTION:
XS GIS Cut Line= 3
      1909424.99     13892275.01      1909725.00     13891975.00
      1909575.00     13891674.99
#Sta/Elev= 30
  4575.7 1887.34  4579.3 1887.34  4604.0 1880.37  4660.6 1861.43  4688.9 1853.56
  4745.4 1840.51  4759.6 1836.01  4773.7 1833.05  4858.6 1821.47  4886.8 1818.38
  4901.0 1817.75  4943.4 1813.95  4957.6 1813.16  4985.8 1813.02  4994.4 1812.10
  4994.7 1811.60  4998.2 1811.60  4998.4 1812.10  5036.3 1814.19  5103.4 1821.61
  5111.8 1823.58  5120.2 1826.66  5142.5 1830.90  5187.3 1845.04  5223.6 1853.44
  5259.9 1863.91  5282.3 1870.94  5299.1 1877.21  5321.4 1883.97  5335.4 1886.01
#Mann=3,-1,0
  4575.7    0.07       0  4994.4    0.05       0  4998.4    0.07       0
Bank Sta=4994.4,4998.4
Exp/Cntr=0.3,0.1

Type RM Length L Ch R = 1,7647,447,447,447
BEGIN DESCRIPTION:
Stream0612 13.0
END DESCRIPTION:
XS GIS Cut Line= 3
      1909824.99     13892425.01      1910125.00     13892125.00
      1910424.97     13891825.03
#Sta/Elev= 30
  4580.5 1862.51  4584.0 1862.51  4608.8 1854.38  4615.9 1850.46  4622.9 1849.90
  4651.2 1842.80  4679.5 1831.28  4693.6 1827.26  4707.8 1824.88  4736.1 1813.12
  4743.4 1811.48  4764.4 1807.34  4792.6 1803.66  4863.4 1796.28  4969.4 1791.01
  4974.5 1790.79  4974.7 1790.29  4978.5 1790.79  5047.2 1792.54  5132.1 1799.73
  5188.6 1806.68  5231.0 1814.07  5245.2 1817.24  5259.3 1822.33  5273.5 1824.85
  5315.9 1843.79  5358.3 1856.93  5414.9 1872.16  5425.5 1876.25  5429.0 1876.25
#Mann=5,-1,0
  4580.5    0.07       0  4743.4   0.035       0  4969.4    0.07       0
  4974.5    0.05       0  4978.5    0.07       0
Bank Sta=4974.5,4978.5
Exp/Cntr=0.3,0.1

Type RM Length L Ch R = 1,7200,455,455,455
BEGIN DESCRIPTION:
Stream0612 12.0
END DESCRIPTION:
XS GIS Cut Line= 3
      1909975.04     13892574.99      1910275.00     13892525.00
      1910575.00     13892375.00
#Sta/Elev= 30
  4695.9 1818.04  4716.1 1814.26  4723.7 1811.85  4728.8 1812.09  4746.5 1806.76
  4784.6 1797.62  4817.5 1793.83  4858.1 1787.64  4977.7 1776.94  4978.0 1776.44
  4981.7 1776.94  5030.7 1777.55  5036.3 1778.55  5067.1 1779.41  5089.4 1781.36
  5097.8 1784.06  5103.4 1783.56  5120.2 1787.49  5148.1 1788.56  5164.9 1791.98
  5192.9 1795.98  5232.0 1803.79  5237.6 1803.59  5254.3 1807.45  5268.3 1808.86
  5276.7 1811.19  5280.9 1810.64  5299.1 1814.23  5304.7 1813.75  5335.4 1820.39
#Mann=4,-1,0
  4695.9   0.035       0  4977.7   0.035       0  4981.7   0.035       0
  5280.9    0.07       0
Bank Sta=4977.7,4981.7
Exp/Cntr=0.3,0.1

Type RM Length L Ch R = 1,6745,451,451,451
BEGIN DESCRIPTION:
Stream0612 11.0
END DESCRIPTION:
XS GIS Cut Line= 3
      1910125.04     13892925.00      1910425.00     13892925.00
      1910724.99     13892625.01
#Sta/Elev= 30
  4704.4 1787.22  4719.8 1785.85  4736.2 1783.49  4764.4 1781.02  4773.9 1779.54
  4794.4 1777.34  4804.4 1775.36  4854.4 1770.61  4874.4 1767.99  4944.4 1763.28
  4954.4 1761.77  4984.4 1761.58  4992.4 1760.08  4992.6 1759.58  4996.4 1760.08
  5001.9 1761.31  5007.9 1761.31  5018.5 1762.90  5060.9 1766.65  5089.2 1770.37
  5145.8 1776.14  5159.9 1778.56  5188.2 1781.56  5273.1 1797.02  5343.8 1811.40
  5372.1 1815.78  5393.3 1819.94  5400.3 1823.37  5425.1 1832.76  5428.6 1832.76
#Mann=6,-1,0
  4704.4   0.035       0  4719.8    0.07       0  4736.2   0.035       0
  4773.9    0.07       0  4992.4    0.05       0  4996.4    0.07       0
Bank Sta=4992.4,4996.4
Exp/Cntr=0.3,0.1

Type RM Length L Ch R = 1,6294,470,470,470
BEGIN DESCRIPTION:
Stream0612 10.0
END DESCRIPTION:
XS GIS Cut Line= 3
      1910325.02     13893524.98      1910625.00     13893275.00
      1910925.03     13892974.97
#Sta/Elev= 30
  4609.5 1777.47  4659.6 1773.41  4673.9 1771.35  4687.6 1770.44  4737.7 1764.89
  4758.5 1763.36  4787.2 1759.93  4808.0 1758.30  4830.1 1757.63  4850.9 1754.68
  4914.7 1751.37  4929.0 1749.77  4978.0 1748.53  5012.1 1747.12  5012.4 1746.62
  5015.9 1746.62  5016.1 1747.12  5028.3 1748.64  5108.7 1754.04  5141.4 1757.65
  5169.7 1761.82  5212.1 1768.97  5268.7 1780.50  5282.8 1780.66  5311.1 1785.97
  5353.5 1791.85  5367.7 1795.57  5396.0 1801.75  5420.7 1809.13  5424.3 1809.13
#Mann=5,-1,0
  4609.5    0.07       0  4978.0     0.1       0  5012.1    0.05       0
  5016.1     0.1       0  5108.7    0.07       0
Bank Sta=5012.1,5016.1
Exp/Cntr=0.3,0.1

Type RM Length L Ch R = 1,5824,428,428,428
BEGIN DESCRIPTION:
Stream0612 9.0
END DESCRIPTION:
XS GIS Cut Line= 3
      1910675.03     13893774.98      1910975.00     13893575.00
      1911025.01     13893274.95
#Sta/Elev= 30
  4639.5 1755.23  4747.6 1745.02  4783.7 1742.46  4812.2 1741.05  4819.7 1739.96
  4827.2 1739.89  4842.3 1738.41  4914.4 1734.58  4941.4 1734.51  4950.4 1733.92
  4956.4 1734.34  4995.0 1733.19  4995.3 1732.69  4998.8 1732.69  4999.0 1733.19
  5016.0 1733.72  5040.6 1734.60  5060.8 1734.62  5101.6 1736.76  5121.7 1738.30
  5149.5 1741.72  5182.5 1744.34  5215.4 1748.07  5233.2 1750.78  5263.6 1754.41
  5271.2 1755.83  5276.3 1756.15  5278.8 1756.90  5301.6 1760.08  5304.2 1760.08
#Mann=5,-1,0
  4639.5    0.07       0  4995.0    0.05       0  4999.0    0.07       0
  5016.0   0.035       0  5101.6    0.07       0
Bank Sta=4995,4999
Exp/Cntr=0.3,0.1

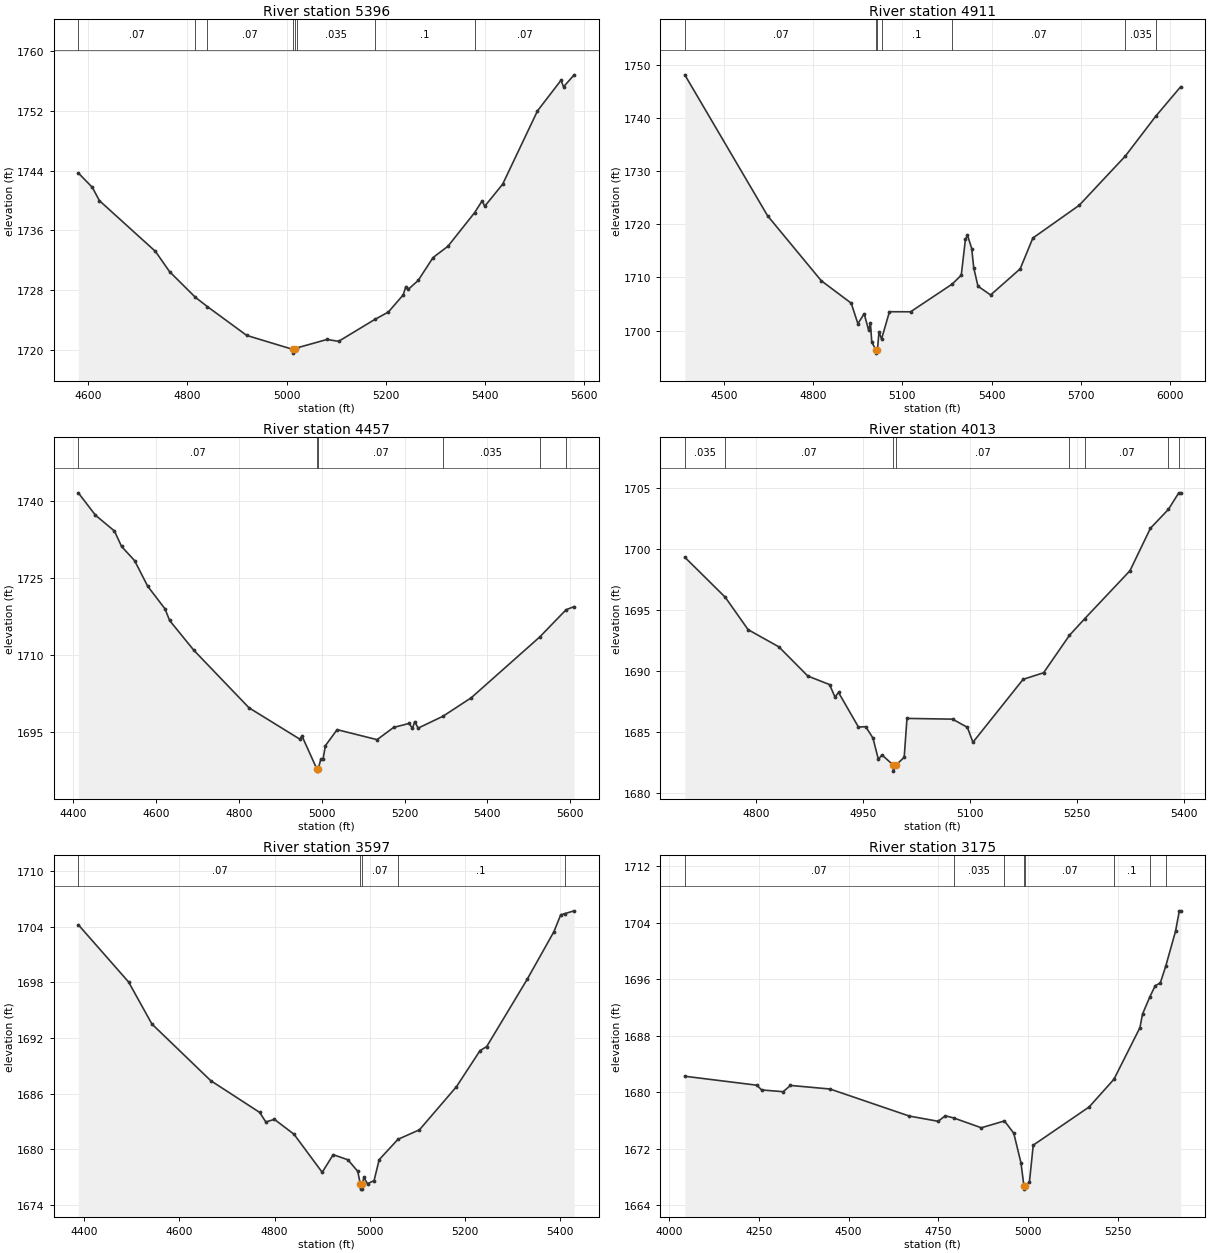
Type RM Length L Ch R = 1,5396,485,485,485
BEGIN DESCRIPTION:
Stream0612 8.0
END DESCRIPTION:
XS GIS Cut Line= 3
      1911025.01     13894074.99      1911325.00     13893775.00
      1911361.52     13893201.21
#Sta/Elev= 30
  4580.3 1743.68  4608.6 1741.75  4622.7 1739.98  4735.8 1733.17  4764.1 1730.47
  4816.0 1727.04  4840.4 1725.78  4919.7 1721.92  5012.6 1720.05  5012.8 1719.55
  5016.6 1720.05  5020.2 1720.24  5081.5 1721.38  5104.8 1721.13  5178.2 1724.08
  5205.0 1725.05  5235.0 1727.35  5240.3 1728.46  5245.4 1728.11  5265.1 1729.28
  5295.1 1732.35  5325.2 1733.87  5378.8 1738.36  5394.2 1739.96  5399.2 1739.22
  5435.4 1742.18  5505.6 1752.00  5553.1 1756.11  5558.1 1755.22  5579.5 1756.83
#Mann=8,-1,0
  4580.3    0.07       0  4816.0     0.1       0  4840.4    0.07       0
  5012.6    0.05       0  5016.6    0.07       0  5020.2   0.035       0
  5178.2     0.1       0  5378.8    0.07       0
Bank Sta=5012.6,5016.6
Exp/Cntr=0.3,0.1

Type RM Length L Ch R = 1,4911,454,454,454
BEGIN DESCRIPTION:
Stream0612 7.0
END DESCRIPTION:
XS GIS Cut Line= 3
      1911200.16     13894275.32      1911725.00     13893925.00
      1912422.73     13893161.38
#Sta/Elev= 30
  4369.0 1748.07  4647.1 1721.58  4827.3 1709.38  4927.9 1705.16  4950.4 1701.30
  4971.5 1703.17  4986.5 1700.07  4992.5 1701.45  4997.0 1697.85  5011.9 1696.27
  5012.1 1695.77  5015.9 1696.27  5021.3 1699.77  5029.8 1698.42  5056.4 1703.55
  5127.4 1703.54  5267.5 1708.76  5297.6 1710.42  5311.6 1717.17  5318.5 1717.94
  5332.7 1715.43  5339.5 1711.81  5353.7 1708.35  5396.2 1706.70  5495.5 1711.61
  5538.1 1717.40  5693.5 1723.54  5848.6 1732.80  5950.8 1740.29  6034.4 1745.82
#Mann=7,-1,0
  4369.0    0.07       0  5011.9    0.05       0  5015.9    0.07       0
  5029.8     0.1       0  5267.5    0.07       0  5848.6   0.035       0
  5950.8    0.07       0
Bank Sta=5011.9,5015.9
Exp/Cntr=0.3,0.1

Type RM Length L Ch R = 1,4457,444,444,444
BEGIN DESCRIPTION:
Stream0612 6.0
END DESCRIPTION:
XS GIS Cut Line= 3
      1911365.74     13894456.42      1911925.00     13894275.00
      1912475.31     13894013.80
#Sta/Elev= 30
  4412.5 1741.49  4453.8 1737.15  4499.6 1734.09  4516.9 1731.08  4548.4 1728.33
  4579.9 1723.37  4622.0 1718.94  4632.8 1716.72  4691.4 1710.93  4824.6 1699.76
  4947.2 1693.68  4952.5 1694.28  4987.9 1687.97  4988.2 1687.47  4991.9 1687.97
  4997.8 1689.73  5003.2 1689.73  5009.0 1692.41  5037.3 1695.52  5133.8 1693.58
  5173.7 1695.95  5210.8 1696.72  5219.2 1695.79  5224.7 1697.08  5232.9 1695.82
  5292.8 1698.12  5361.1 1701.71  5526.6 1713.52  5590.0 1718.79  5609.6 1719.41
#Mann=6,-1,0
  4412.5    0.07       0  4987.9    0.05       0  4991.9    0.07       0
  5292.8   0.035       0  5526.6    0.07       0  5590.0   0.035       0
Bank Sta=4987.9,4991.9
Exp/Cntr=0.3,0.1

Type RM Length L Ch R = 1,4013,416,416,416
BEGIN DESCRIPTION:
Stream0612 5.0
END DESCRIPTION:
XS GIS Cut Line= 3
      1911874.98     13894675.00      1912175.00     13894625.00
      1912475.03     13894374.98
#Sta/Elev= 30
  4700.3 1699.34  4756.9 1696.06  4789.0 1693.39  4832.1 1691.98  4872.7 1689.58
  4903.1 1688.88  4910.7 1687.86  4915.7 1688.23  4943.6 1685.39  4953.8 1685.42
  4963.9 1684.49  4971.5 1682.74  4976.6 1683.10  4992.3 1682.27  4992.6 1681.77
  4996.3 1682.27  5007.7 1682.91  5011.6 1686.10  5075.4 1686.04  5096.2 1685.37
  5104.0 1684.14  5174.3 1689.31  5203.0 1689.85  5239.3 1692.93  5260.6 1694.29
  5324.0 1698.23  5352.7 1701.72  5378.0 1703.28  5392.4 1704.63  5395.0 1704.63
#Mann=8,-1,0
  4700.3   0.035       0  4756.9    0.07       0  4992.3    0.05       0
  4996.3    0.07       0  5239.3     0.1       0  5260.6    0.07       0
  5378.0     0.1       0  5392.4    0.07       0
Bank Sta=4992.3,4996.3
Exp/Cntr=0.3,0.1

Type RM Length L Ch R = 1,3597,422,422,422
BEGIN DESCRIPTION:
Stream0612 4.0
END DESCRIPTION:
XS GIS Cut Line= 3
      1911774.96     13894824.99      1912375.00     13894975.00
      1912675.02     13894674.98
#Sta/Elev= 30
  4387.4 1704.19  4493.1 1698.03  4542.1 1693.51  4665.8 1687.41  4768.8 1683.99
  4781.7 1682.96  4799.8 1683.24  4841.0 1681.64  4900.3 1677.54  4923.4 1679.44
  4954.4 1678.89  4975.0 1677.65  4980.7 1676.23  4981.0 1675.73  4984.5 1675.73
  4984.7 1676.23  4987.9 1677.00  4995.6 1676.31  5009.4 1676.65  5020.1 1678.90
  5059.6 1681.09  5104.9 1682.12  5182.7 1686.76  5232.2 1690.64  5246.3 1691.08
  5331.2 1698.30  5387.7 1703.45  5401.9 1705.26  5409.9 1705.38  5430.2 1705.69
#Mann=5,-1,0
  4387.4    0.07       0  4980.7    0.05       0  4984.7    0.07       0
  5059.6     0.1       0  5409.9   0.035       0
Bank Sta=4980.7,4984.7
Exp/Cntr=0.3,0.1

Type RM Length L Ch R = 1,3175,415,415,415
BEGIN DESCRIPTION:
Stream0612 3.0
END DESCRIPTION:
XS GIS Cut Line= 3
      1911621.87     13895255.20      1912575.00     13895325.00
      1912875.04     13895024.96
#Sta/Elev= 30
  4044.3 1682.28  4245.0 1681.01  4258.0 1680.34  4318.2 1680.09  4338.2 1680.98
  4448.5 1680.47  4669.1 1676.64  4749.3 1675.90  4769.4 1676.68  4792.9 1676.37
  4869.6 1674.98  4934.0 1675.95  4959.9 1674.21  4979.9 1670.03  4988.0 1666.79
  4988.2 1666.29  4992.0 1666.79  5003.5 1667.29  5014.1 1672.52  5169.7 1677.93
  5238.7 1681.85  5311.1 1689.17  5318.2 1691.08  5338.5 1693.51  5353.5 1695.10
  5367.7 1695.49  5382.7 1697.84  5410.1 1702.81  5420.7 1705.71  5424.3 1705.71
#Mann=8,-1,0
  4044.3    0.07       0  4792.9   0.035       0  4934.0    0.07       0
  4988.0    0.05       0  4992.0    0.07       0  5238.7     0.1       0
  5338.5   0.035       0  5382.7     0.1       0
Bank Sta=4988,4992
Exp/Cntr=0.3,0.1

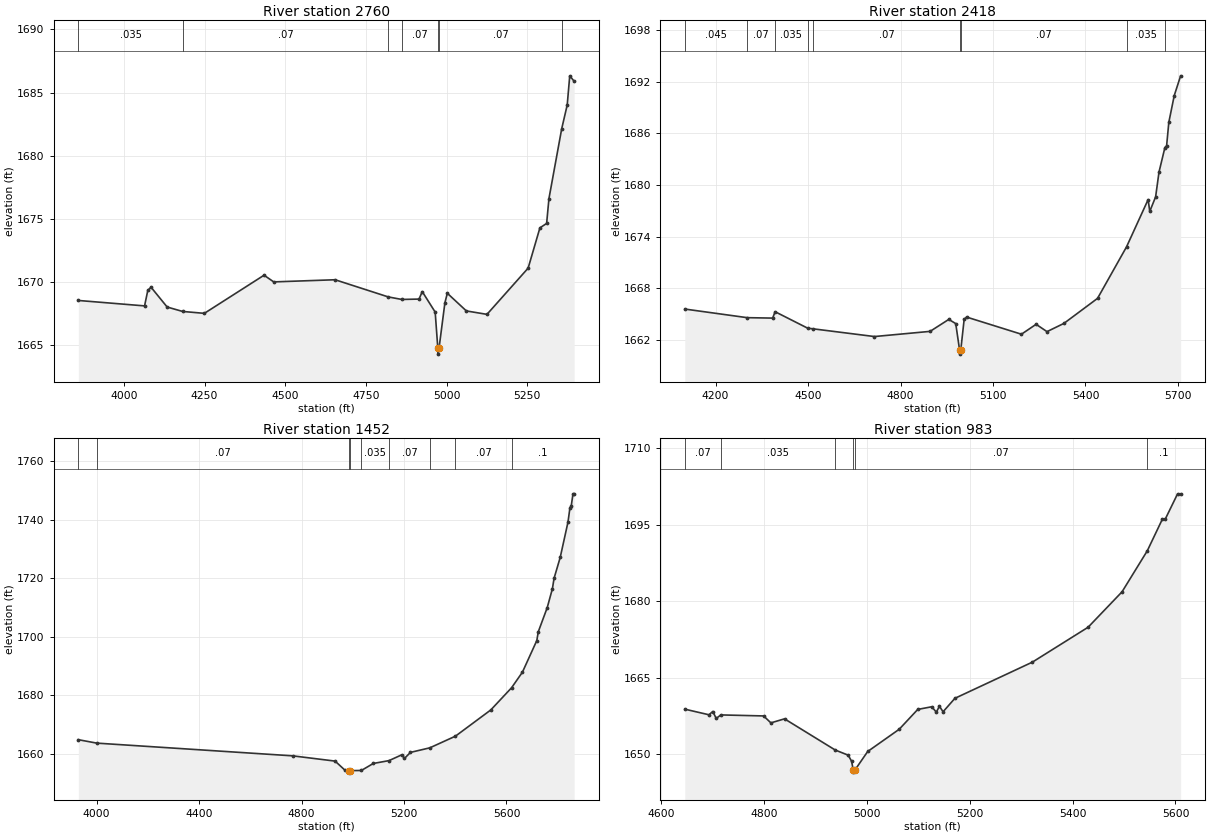
Type RM Length L Ch R = 1,2760,342,342,342
BEGIN DESCRIPTION:
Stream0612 2.0
END DESCRIPTION:
XS GIS Cut Line= 3
      1911629.96     13895712.94      1912775.00     13895675.00
      1913025.01     13895374.98
#Sta/Elev= 30
  3858.8 1668.54  4064.0 1668.11  4074.0 1669.33  4084.0 1669.59  4134.0 1668.02
  4181.9 1667.67  4249.3 1667.52  4434.2 1670.54  4464.2 1670.01  4654.3 1670.18
  4819.1 1668.82  4861.0 1668.62  4914.4 1668.65  4924.4 1669.24  4964.4 1667.62
  4972.5 1664.79  4972.7 1664.29  4976.5 1664.79  4994.5 1668.35  5002.0 1669.11
  5061.1 1667.71  5124.9 1667.44  5252.4 1671.10  5288.9 1674.29  5309.7 1674.64
  5316.9 1676.61  5356.5 1682.15  5373.5 1684.02  5381.3 1686.33  5395.0 1685.90
#Mann=7,-1,0
  3858.8   0.035       0  4181.9    0.07       0  4819.1   0.035       0
  4861.0    0.07       0  4972.5    0.05       0  4976.5    0.07       0
  5356.5   0.035       0
Bank Sta=4972.5,4976.5
Exp/Cntr=0.3,0.1

Type RM Length L Ch R = 1,2418,966,966,966
BEGIN DESCRIPTION:
Stream0612 1.1
END DESCRIPTION:
XS GIS Cut Line= 4
      1912039.79     13896294.02      1912836.95     13896013.87
      1913032.76     13895858.80      1913216.91     13895379.27
#Sta/Elev= 30
  4100.2 1665.61  4302.7 1664.61  4385.2 1664.56  4393.2 1665.30  4498.8 1663.39
  4517.6 1663.31  4715.4 1662.42  4895.9 1663.02  4956.6 1664.41  4979.1 1663.92
  4991.5 1660.88  4991.8 1660.38  4995.5 1660.88  5006.4 1664.41  5014.3 1664.68
  5192.2 1662.69  5239.8 1663.84  5275.1 1662.99  5329.8 1663.94  5439.1 1666.85
  5533.2 1672.83  5603.2 1678.31  5608.5 1676.94  5627.5 1678.63  5638.5 1681.51
  5657.6 1684.35  5663.2 1684.57  5670.3 1687.27  5687.9 1690.38  5708.6 1692.67
#Mann=9,-1,0
  4100.2   0.045       0  4302.7    0.07       0  4393.2   0.035       0
  4498.8   0.045       0  4517.6    0.07       0  4991.5    0.05       0
  4995.5    0.07       0  5533.2   0.035       0  5657.6    0.07       0
Bank Sta=4991.5,4995.5
Exp/Cntr=0.3,0.1

Type RM Length L Ch R = 1,1452,469,469,469
BEGIN DESCRIPTION:
Stream0612 1.2
END DESCRIPTION:
XS GIS Cut Line= 4
      1912814.46     13896703.54      1913494.81     13896207.83
      1913564.93     13896052.14      1913417.72     13895141.20
#Sta/Elev= 30
  3928.8 1664.93  4000.8 1663.76  4765.8 1659.42  4931.0 1657.63  4968.0 1654.65
  4987.1 1654.37  4987.3 1653.87  4991.1 1654.37  5033.6 1654.44  5080.3 1656.83
  5141.2 1657.79  5191.7 1659.79  5201.8 1658.54  5225.1 1660.60  5300.6 1662.15
  5400.7 1666.13  5538.8 1675.08  5619.9 1682.65  5662.2 1687.96  5718.4 1698.75
  5724.0 1701.71  5759.0 1709.97  5779.2 1716.42  5785.7 1719.97  5809.6 1727.06
  5840.0 1739.13  5847.4 1743.83  5852.5 1744.54  5859.6 1748.77  5864.1 1748.77
#Mann=9,-1,0
  3928.8   0.035       0  4000.8    0.07       0  4987.1    0.05       0
  4991.1    0.07       0  5033.6   0.035       0  5141.2    0.07       0
  5300.6   0.035       0  5400.7    0.07       0  5619.9     0.1       0
Bank Sta=4987.1,4991.1
Exp/Cntr=0.3,0.1

Type RM Length L Ch R = 1,983,0,0,0
BEGIN DESCRIPTION:
Stream0612 1.0
END DESCRIPTION:
XS GIS Cut Line= 4
      1913812.12     13896018.71      1913951.47     13895893.67
      1913925.00     13895725.00      1913590.71     13895220.08
#Sta/Elev= 30
  4646.5 1658.81  4693.4 1657.71  4700.9 1658.35  4707.6 1656.99  4716.5 1657.68
  4799.6 1657.48  4813.8 1656.12  4840.3 1656.91  4938.8 1650.79  4964.0 1649.78
  4970.6 1648.59  4973.7 1646.95  4973.9 1646.45  4977.7 1646.95  5001.9 1650.50
  5063.1 1654.86  5099.2 1658.76  5126.3 1659.28  5135.3 1658.23  5141.3 1659.38
  5148.4 1658.30  5171.4 1660.94  5321.9 1668.04  5430.2 1674.89  5496.2 1681.85
  5545.2 1689.89  5574.6 1696.12  5580.6 1696.21  5604.1 1701.08  5610.0 1701.08
#Mann=6,-1,0
  4646.5    0.07       0  4716.5   0.035       0  4938.8    0.07       0
  4973.7    0.05       0  4977.7    0.07       0  5545.2     0.1       0
Bank Sta=4973.7,4977.7
Exp/Cntr=0.3,0.1

Chan Stop Cuts=-1