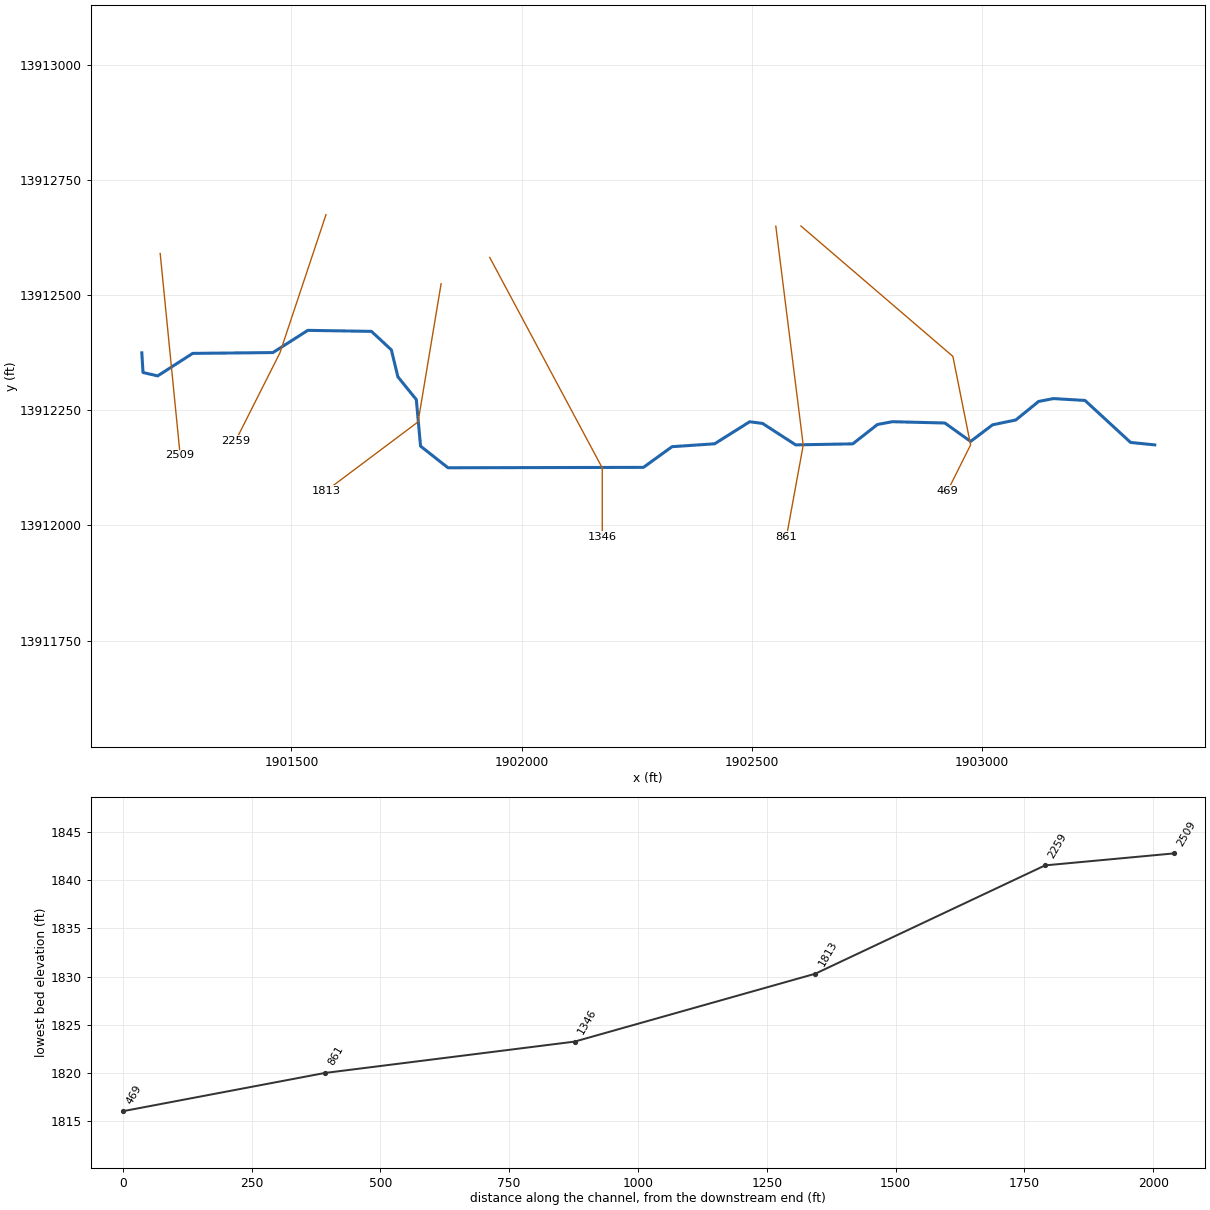
--- Stream0614.prj (project) ---

Proj Title=Stream0614 Base Level Engineering
Current Plan=p01
Default Exp/Contr=0.3,0.1
English Units
Geom File=g01
Flow File=f01
Plan File=p01
Y Axis Title=Elevation
X Axis Title(PF)=Main Channel Distance
X Axis Title(XS)=Station
BEGIN DESCRIPTION:
Stream0614
END DESCRIPTION:
DSS Export Rating Curves= 0
DSS Export Rating Curve Sorted= 0
DSS Export Volume Flow Curves= 0
DXF OffsetX= 0
DXF OffsetY= 0
DXF ScaleX= 1
DXF ScaleY= 10

--- Stream0614.p01 (plan) ---

Plan Title=Multiple Run
Short Identifier=Multiple
Geom File=g01
Flow File=f01
Subcritical Flow
K Sum by GR= 0
Std Step Tol= 0.01
Critical Tol= 0.01
Num of Std Step Trials= 20
Max Error Tol= 0.3
Flow Tol Ratio= 0.001
Split Flow NTrial= 30
Split Flow Tol= 0.02
Split Flow Ratio= 0.02
Log Output Level= 0
Friction Slope Method= 1
Unsteady Friction Slope Method= 2
Unsteady Bridges Friction Slope Method= 1
Parabolic Critical Depth
Global Vel Dist=  1 , 1 , 1
Global Log Level= 0
CheckData=True
Encroach Param= -1, 0, 0, 0
BEGIN DESCRIPTION:
Multiple Run
END DESCRIPTION:

--- Stream0614.f01 (steady flow) ---

Flow Title=Multiple
Program Version=4.10
Number of Profiles= 7
Profile Names=10-year,25-year,50-year,1pct_min,100-year,1pct_plu,500-year
River Rch & RM=Stream0614,Reach-1         ,2509
    1235    2129    2991    2033    4056    8093    7363
Boundary for River Rch & Prof#=Stream0614,Reach-1         , 1
Up Type= 0
Dn Type= 3
Dn Slope=0.008
Boundary for River Rch & Prof#=Stream0614,Reach-1         , 2
Up Type= 0
Dn Type= 3
Dn Slope=0.008
Boundary for River Rch & Prof#=Stream0614,Reach-1         , 3
Up Type= 0
Dn Type= 3
Dn Slope=0.008
Boundary for River Rch & Prof#=Stream0614,Reach-1         , 4
Up Type= 0
Dn Type= 3
Dn Slope=0.008
Boundary for River Rch & Prof#=Stream0614,Reach-1         , 5
Up Type= 0
Dn Type= 3
Dn Slope=0.008
Boundary for River Rch & Prof#=Stream0614,Reach-1         , 6
Up Type= 0
Dn Type= 3
Dn Slope=0.008
Boundary for River Rch & Prof#=Stream0614,Reach-1         , 7
Up Type= 0
Dn Type= 3
Dn Slope=0.008
DSS Import GetInterval= 0
DSS Import GetPeak= 0
DSS Import FillOption= 0

--- Stream0614.g01 (geometry) ---

Geom Title=Existing Conditions
Program Version=4.10

River Reach=Stream0614      ,Reach-1
Reach XY= 30
        1901175.       13912375.      1901177.61     13912332.24
      1901209.45     13912324.86      1901285.48     13912373.78
      1901459.78     13912375.52      1901535.51     13912423.79
      1901673.75     13912421.56        1901717.     13912381.39
      1901731.15     13912322.85      1901771.17     13912273.41
       1901780.4     13912172.29      1901840.02     13912125.32
       1902264.5     13912126.22       1902326.6     13912171.14
      1902419.03     13912177.38      1902495.18     13912225.28
      1902523.26     13912221.63      1902595.03     13912175.07
      1902719.06     13912177.25      1902772.67     13912219.26
      1902804.87     13912225.39      1902919.14     13912222.55
      1902975.01     13912182.53      1903022.71     13912218.61
      1903073.25     13912229.16      1903122.68     13912269.35
      1903154.95     13912275.61       1903223.5     13912271.54
      1903322.49     13912180.33        1903375.       13912175.

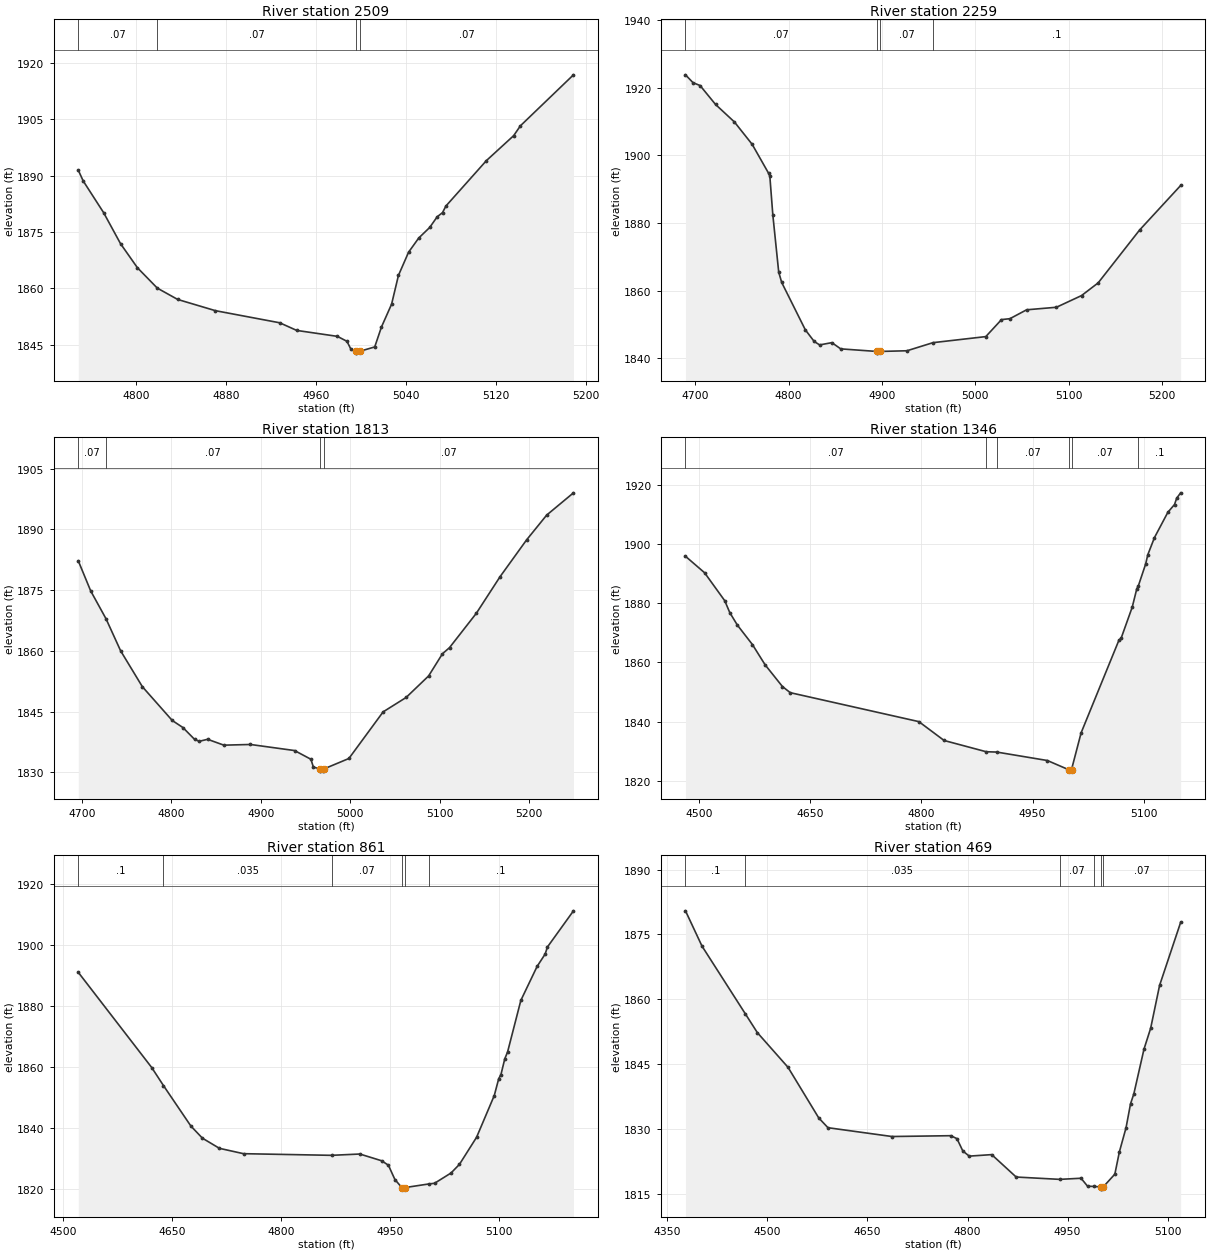
Type RM Length L Ch R = 1 ,2509    ,250,250,250
BEGIN DESCRIPTION:
Stream0614 6.0
END DESCRIPTION:
XS GIS Cut Line= 2
      1901214.91     13912590.64      1901258.31     13912152.29
#Sta/Elev= 30
  4748.4  1891.4  4752.8 1888.53  4770.9 1880.13    4786 1871.85    4801 1865.46
  4818.7 1860.04  4836.8 1857.03  4870.4 1854.04  4927.6 1850.82  4942.7 1848.79
  4978.9 1847.21  4987.4 1845.89    4991 1843.74    4995 1843.25  4995.2 1842.75
    4999 1843.25  5012.1  1844.4  5018.1 1849.71  5027.1 1855.77  5033.2 1863.43
  5042.2 1869.59  5051.2 1873.35    5061 1876.18  5067.7 1879.03  5072.4 1880.12
  5075.4 1881.87  5111.5 1893.98  5135.7  1900.6  5141.7 1903.22  5188.9 1916.78
#Mann= 4 ,-1 , 0
  4748.4     .07       0  4818.7     .07       0    4995     .05       0
    4999     .07       0
Bank Sta=4995,4999
XS Rating Curve= 0 ,0
Exp/Cntr=0.3,0.1

Type RM Length L Ch R = 1 ,2259    ,446,446,446
BEGIN DESCRIPTION:
Stream0614 5.0
END DESCRIPTION:
XS GIS Cut Line= 3
      1901574.99     13912674.97        1901475.       13912375.
      1901378.71     13912183.99
#Sta/Elev= 30
  4689.6 1923.85  4697.7 1921.52  4705.2 1920.69  4721.8 1915.08    4742  1909.9
    4761 1903.28  4778.7 1894.66  4779.9 1893.86  4783.1 1882.42  4789.4 1865.48
  4792.6 1862.42  4817.9  1848.4  4827.4 1844.96  4833.2 1843.94  4846.3 1844.61
  4855.8 1842.77  4894.3 1842.01  4894.5 1841.51  4898.3 1842.01  4926.7 1842.21
  4954.6 1844.61  5011.1  1846.4  5027.9 1851.43  5036.9  1851.7  5054.8 1854.33
  5086.7 1855.08  5113.6 1858.54  5131.4  1862.3  5175.7 1877.92  5219.7 1891.11
#Mann= 4 ,-1 , 0
  4689.6     .07       0  4894.3     .05       0  4898.3     .07       0
  4954.6      .1       0
Bank Sta=4894.3,4898.3
XS Rating Curve= 0 ,0
Exp/Cntr=0.3,0.1

Type RM Length L Ch R = 1 ,1813    ,467,467,467
BEGIN DESCRIPTION:
Stream0614 4.0
END DESCRIPTION:
XS GIS Cut Line= 3
        1901825.     13912524.98        1901775.       13912225.
      1901575.02     13912075.01
#Sta/Elev= 30
  4695.8  1882.2  4709.7 1874.77  4726.8 1867.91  4743.2 1859.98  4767.5 1851.13
  4800.9  1842.8  4812.8 1841.06  4825.9 1838.14  4831.1 1837.65  4840.5 1838.15
  4858.7  1836.7  4888.4 1836.87  4937.8 1835.37  4956.1 1833.22  4958.8 1831.32
  4966.2 1830.79  4966.5 1830.29    4970 1830.29  4970.2 1830.79  4998.6 1833.41
  5036.9 1844.92  5062.6 1848.47  5087.8 1853.79  5103.3 1859.27  5111.2 1860.78
  5141.2 1869.26  5167.8 1878.31  5197.4 1887.37  5219.9  1893.5  5249.9    1899
#Mann= 4 ,-1 , 0
  4695.8     .07       0  4726.8     .07       0  4966.2     .05       0
  4970.2     .07       0
Bank Sta=4966.2,4970.2
XS Rating Curve= 0 ,0
Exp/Cntr=0.3,0.1

Type RM Length L Ch R = 1 ,1346    ,485,485,485
BEGIN DESCRIPTION:
Stream0614 3.0
END DESCRIPTION:
XS GIS Cut Line= 3
      1901930.71     13912582.02        1902175.       13912125.
        1902175.     13911975.01
#Sta/Elev= 30
  4481.7 1895.83  4507.5 1890.26  4534.7 1880.81  4541.5 1876.79  4551.7 1872.59
  4572.1 1865.99  4589.1 1859.19  4612.5 1851.84  4623.1 1849.76  4796.6 1839.98
  4830.7 1833.61  4887.5 1829.81  4901.7  1829.7  4970.1 1826.84  4998.6 1823.76
  4998.9 1823.26  5002.6 1823.76  5015.6 1836.21  5066.6 1867.48  5069.6 1868.17
  5084.6 1878.68  5090.6 1884.74  5092.8 1885.84  5102.6 1893.16  5105.6 1896.37
  5114.6 1902.17  5132.6 1910.67  5141.6 1913.31  5144.6 1915.47  5149.9 1917.26
#Mann= 6 ,-1 , 0
  4481.7     .07       0  4887.5    .035       0  4901.7     .07       0
  4998.6     .05       0  5002.6     .07       0  5092.8      .1       0
Bank Sta=4998.6,5002.6
XS Rating Curve= 0 ,0
Exp/Cntr=0.3,0.1

Type RM Length L Ch R = 1 ,861     ,392,392,392
BEGIN DESCRIPTION:
Stream0614 2.0
END DESCRIPTION:
XS GIS Cut Line= 3
      1902551.93     13912650.13       1902611.5     13912174.51
      1902574.99     13911974.96
#Sta/Elev= 30
  4520.7 1891.14  4621.9 1859.89    4638    1854  4675.8 1840.71  4691.7 1836.73
  4715.1  1833.4  4748.3 1831.64  4869.6  1831.1  4908.6 1831.53  4938.7 1829.31
  4947.9 1827.86  4956.9 1823.16  4966.5 1820.51  4966.7 1820.01  4970.5 1820.51
  5003.4  1821.7  5011.5 1821.93  5034.2  1825.3  5045.8 1828.14  5069.4 1837.02
  5093.8 1850.73  5099.9 1856.24    5103 1857.62  5108.3  1862.8  5112.1    1865
  5130.4 1881.94  5152.8 1893.09  5163.9 1897.15    5167 1899.45  5202.9 1911.33
#Mann= 6 ,-1 , 0
  4520.7      .1       0    4638    .035       0  4869.6     .07       0
  4966.5     .05       0  4970.5     .07       0  5003.4      .1       0
Bank Sta=4966.5,4970.5
XS Rating Curve= 0 ,0
Exp/Cntr=0.3,0.1

Type RM Length L Ch R = 1 ,469     ,0,0,0
BEGIN DESCRIPTION:
Stream0614 1.0
END DESCRIPTION:
XS GIS Cut Line= 4
      1902606.51     13912650.44      1902936.55     13912367.24
        1902975.       13912175.      1902925.02     13912075.03
#Sta/Elev= 30
    4377 1880.48  4401.8  1872.3  4466.5  1856.7  4484.8 1852.28  4530.8 1844.25
  4576.9 1832.53  4590.7 1830.27  4686.7 1828.23    4775 1828.42  4784.2 1827.73
    4793 1824.88  4802.6 1823.69  4836.3 1824.04    4873 1818.85  4938.3 1818.31
  4970.3 1818.57  4980.1 1816.72  4990.4 1816.67  4999.5 1816.55  4999.8 1816.05
  5003.5 1816.55    5021 1819.52  5027.8 1824.68  5037.8 1830.27  5044.5 1835.79
  5049.5 1838.12  5064.7 1848.46  5074.7 1853.29  5088.1 1863.22  5119.7 1877.82
#Mann= 6 ,-1 , 0
    4377      .1       0  4466.5    .035       0  4938.3     .07       0
  4990.4     .07       0  4999.5     .05       0  5003.5     .07       0
Bank Sta=4999.5,5003.5
XS Rating Curve= 0 ,0
Exp/Cntr=0.3,0.1

Chan Stop Cuts=-1
Use User Specified Reach Order=0
Composite Channel Slope=5