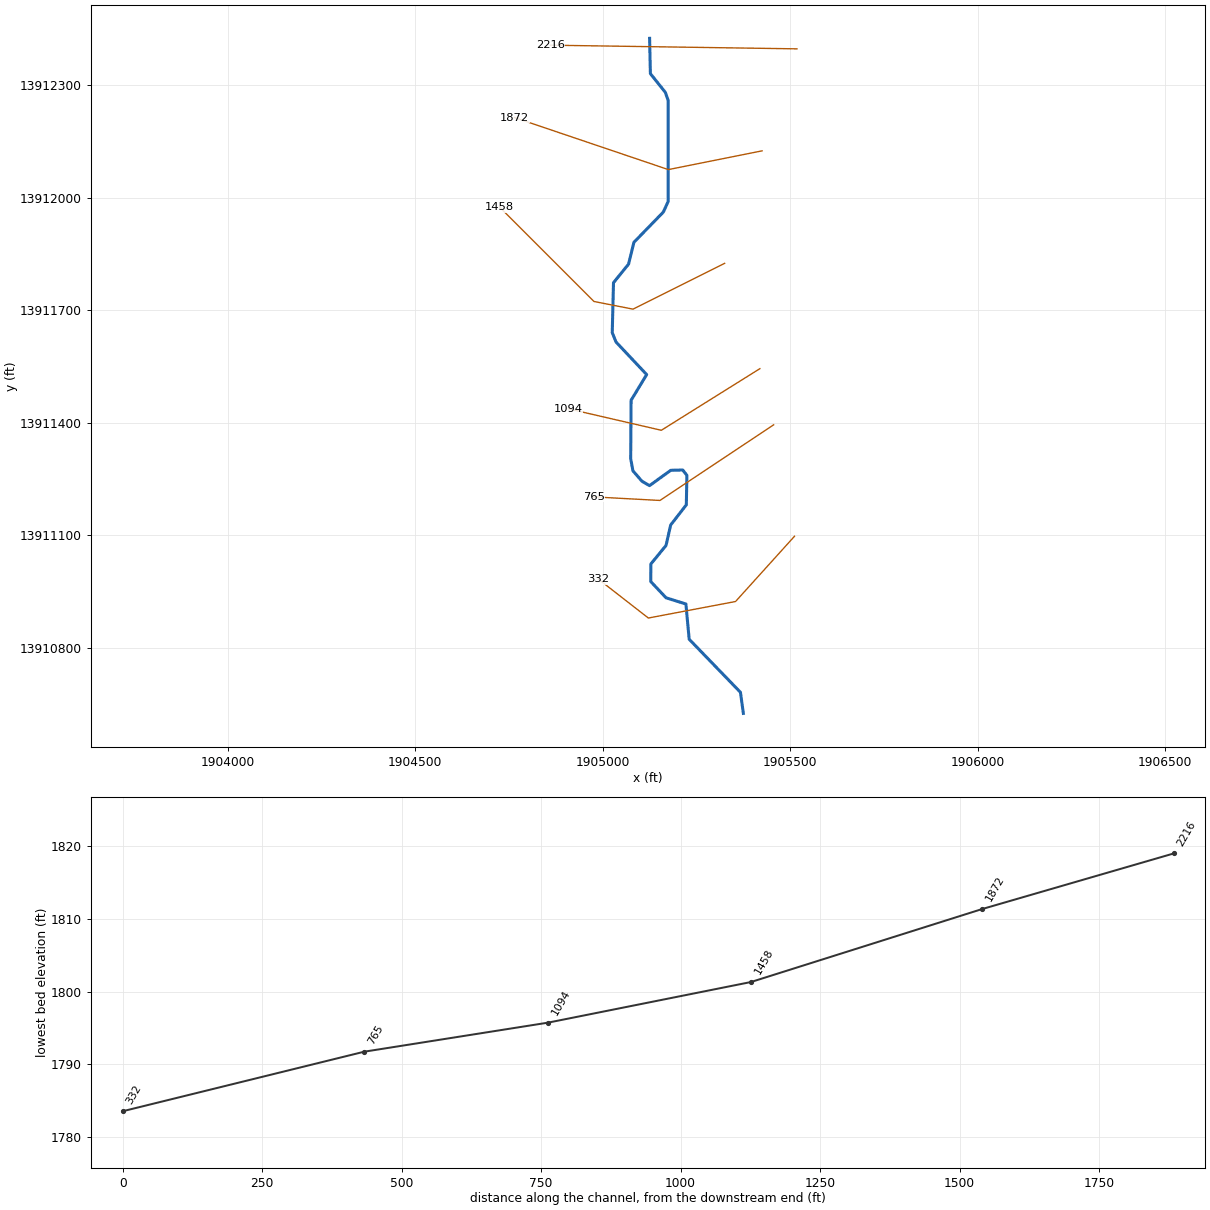
--- Stream0616.prj (project) ---

Proj Title=Stream0616 Base Level Engineering
Current Plan=p01
Default Exp/Contr=0.3,0.1
English Units
Geom File=g01
Flow File=f01
Plan File=p01
BEGIN DESCRIPTION:
Stream0616
END DESCRIPTION:

--- Stream0616.p01 (plan) ---

Plan Title=Multiple Run
Short Identifier=Multiple
Geom File=g01
Flow File=f01
Subcritical Flow
K Sum by GR= 0
Std Step Tol= 0.01
Critical Tol= 0.01
Num of Std Step Trials= 20
Max Error Tol= 0.3
Flow Tol Ratio= 0.001
Split Flow NTrial= 30
Split Flow Tol= 0.02
Split Flow Ratio= 0.02
Log Output Level= 0
Friction Slope Method= 1
Unsteady Friction Slope Method= 2
Unsteady Bridges Friction Slope Method= 1
Parabolic Critical Depth
Global Vel Dist=  1 , 1 , 1
Global Log Level= 0
CheckData=True
Encroach Param= -1, 0, 0, 0
BEGIN DESCRIPTION:
Multiple Run
END DESCRIPTION:

--- Stream0616.f01 (steady flow) ---

Flow Title=Multiple
Number of Profiles=7
Profile Names=10-year,25-year,50-year,1pct_min,100-year,1pct_plu,500-year
River Rch & RM= Stream0616,Reach-1,2216
     599     982    1335     881    1757    3506    2996
Boundary for River Rch & Prof#=Stream0616,Reach-1,1
Up Type=0
Dn Type=3
Dn Slope=0.005
Boundary for River Rch & Prof#=Stream0616,Reach-1,2
Up Type=0
Dn Type=3
Dn Slope=0.005
Boundary for River Rch & Prof#=Stream0616,Reach-1,3
Up Type=0
Dn Type=3
Dn Slope=0.005
Boundary for River Rch & Prof#=Stream0616,Reach-1,4
Up Type=0
Dn Type=3
Dn Slope=0.005
Boundary for River Rch & Prof#=Stream0616,Reach-1,5
Up Type=0
Dn Type=3
Dn Slope=0.005
Boundary for River Rch & Prof#=Stream0616,Reach-1,6
Up Type=0
Dn Type=3
Dn Slope=0.005
Boundary for River Rch & Prof#=Stream0616,Reach-1,7
Up Type=0
Dn Type=3
Dn Slope=0.005

--- Stream0616.g01 (geometry) ---

Geom Title=Existing Conditions

River Reach=Stream0616,Reach-1
Reach XY= 30
      1905125.00     13912425.00      1905127.10     13912330.87
      1905166.90     13912281.07      1905174.49     13912259.79
      1905174.61     13911990.16      1905161.60     13911961.69
      1905083.16     13911881.05      1905068.86     13911822.83
      1905028.74     13911773.44      1905025.38     13911640.16
      1905035.52     13911615.20      1905117.19     13911528.41
      1905075.66     13911459.84      1905074.56     13911304.67
      1905080.45     13911271.99      1905104.49     13911244.10
      1905124.70     13911232.26      1905181.53     13911273.20
      1905213.36     13911273.90      1905224.48     13911259.67
      1905222.90     13911181.07      1905181.12     13911127.18
      1905168.84     13911072.80      1905128.30     13911023.24
      1905128.07     13910976.43      1905168.92     13910933.18
      1905221.80     13910916.65      1905230.55     13910822.63
      1905367.24     13910681.21      1905375.00     13910625.00

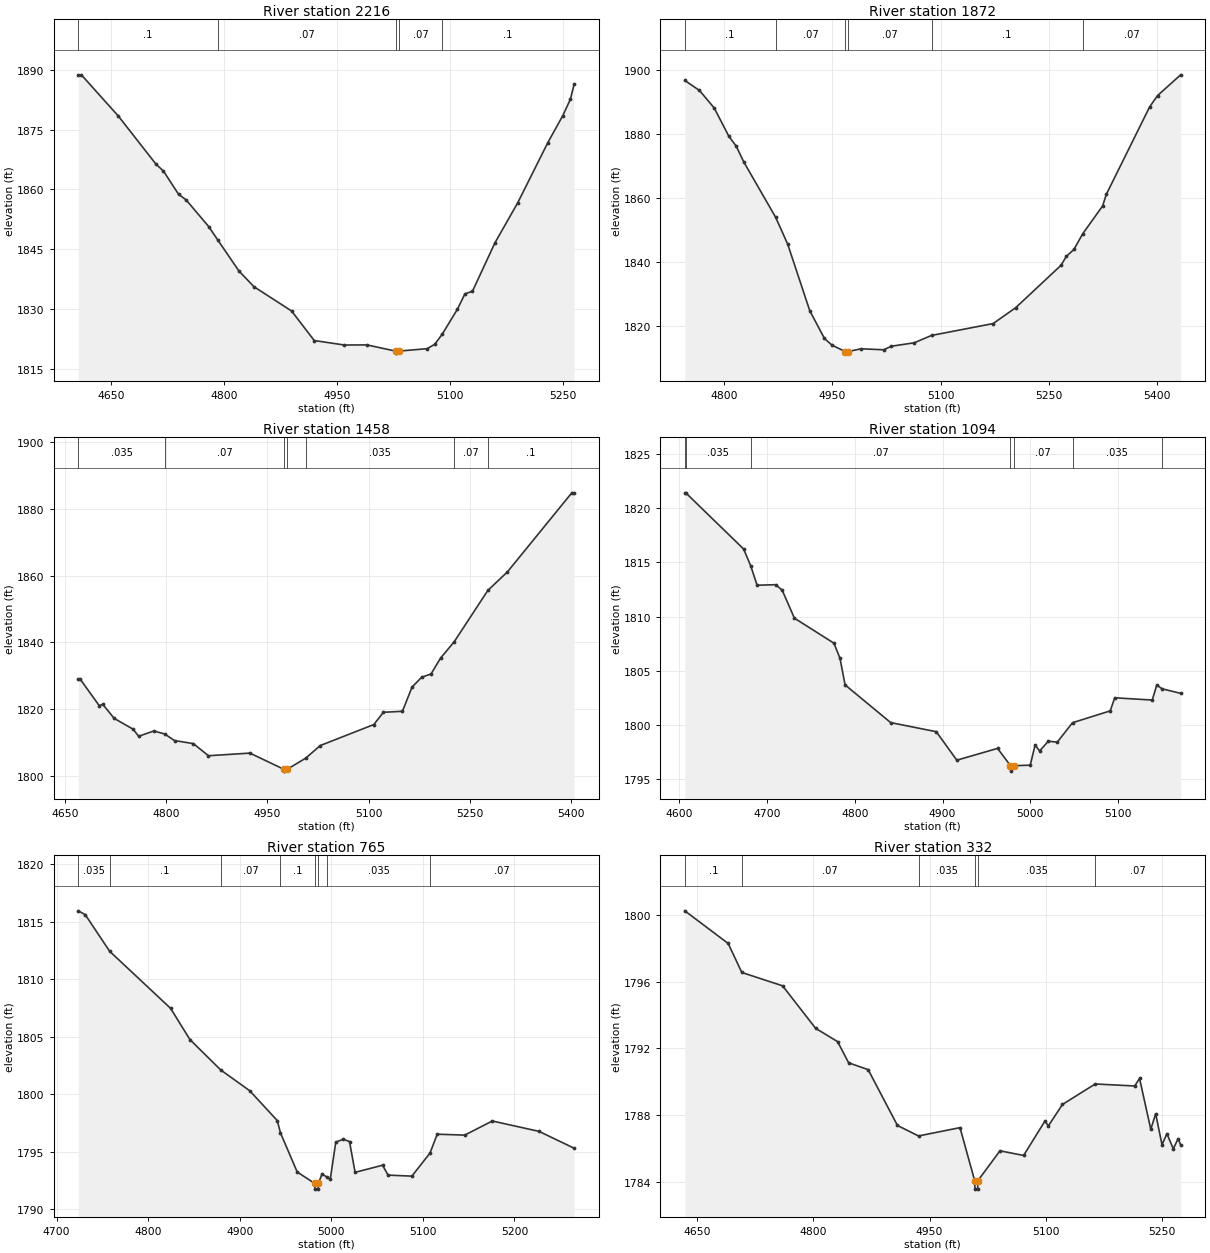
Type RM Length L Ch R = 1,2216,344,344,344
BEGIN DESCRIPTION:
Stream0616 3.0
END DESCRIPTION:
XS GIS Cut Line= 2
      1905518.02     13912396.98      1904859.99     13912406.72
#Sta/Elev= 30
  4606.7 1888.69  4610.7 1888.69  4659.7 1878.39  4709.7 1866.34  4719.7 1864.59
  4739.7 1858.79  4749.7 1857.39  4779.7 1850.70  4791.8 1847.33  4819.7 1839.62
  4839.7 1835.65  4889.7 1829.57  4919.8 1822.17  4959.8 1821.04  4989.8 1821.07
  5027.8 1819.51  5028.0 1819.01  5031.8 1819.51  5069.8 1820.13  5079.8 1821.23
  5089.7 1823.75  5109.8 1829.99  5119.8 1833.84  5129.8 1834.50  5159.8 1846.68
  5189.8 1856.62  5229.8 1871.70  5249.8 1878.50  5259.8 1882.58  5264.8 1886.38
#Mann=5,-1,0
  4606.7     0.1       0  4791.8    0.07       0  5027.8    0.05       0
  5031.8    0.07       0  5089.7     0.1       0
Bank Sta=5027.8,5031.8
Exp/Cntr=0.3,0.1

Type RM Length L Ch R = 1,1872,414,414,414
BEGIN DESCRIPTION:
Stream0616 2.0
END DESCRIPTION:
XS GIS Cut Line= 3
      1905425.04     13912125.01      1905175.00     13912075.00
      1904764.73     13912213.79
#Sta/Elev= 30
  4745.1 1896.87  4765.5 1893.73  4785.9 1888.24  4806.3 1879.34  4816.5 1876.26
  4826.7 1871.41  4871.2 1853.95  4887.9 1845.53  4918.5 1824.67  4938.9 1815.95
  4949.1 1813.90  4967.5 1811.85  4967.7 1811.35  4971.5 1811.85  4989.9 1812.71
  5021.2 1812.40  5031.8 1813.52  5063.4 1814.59  5087.7 1816.91  5173.0 1820.62
  5204.4 1825.62  5267.3 1838.92  5274.6 1841.70  5285.1 1843.86  5297.3 1848.78
  5324.9 1857.50  5330.2 1861.21  5390.2 1888.59  5401.2 1892.13  5433.2 1898.64
#Mann=6,-1,0
  4745.1     0.1       0  4871.2    0.07       0  4967.5    0.05       0
  4971.5    0.07       0  5087.7     0.1       0  5297.3    0.07       0
Bank Sta=4967.5,4971.5
Exp/Cntr=0.3,0.1

Type RM Length L Ch R = 1,1458,364,364,364
BEGIN DESCRIPTION:
Stream0616 1.0
END DESCRIPTION:
XS GIS Cut Line= 4
      1905325.04     13911825.02      1905080.78     13911702.89
      1904976.66     13911723.34      1904725.01     13911974.99
#Sta/Elev= 30
  4669.6 1828.91  4672.4 1828.91  4700.4 1821.01  4706.0 1821.33  4722.8 1817.14
  4750.7 1813.92  4759.1 1811.78  4781.5 1813.37  4797.6 1812.47  4812.2 1810.49
  4840.1 1809.58  4862.5 1805.94  4924.0 1806.73  4974.8 1801.82  4975.1 1801.32
  4978.8 1801.82  5006.7 1805.21  5028.3 1809.00  5107.7 1815.30  5121.9 1818.98
  5150.1 1819.27  5164.3 1826.52  5178.4 1829.46  5192.6 1830.51  5206.7 1835.26
  5226.8 1840.12  5276.8 1855.56  5305.7 1861.09  5401.2 1884.83  5404.7 1884.83
#Mann=7,-1,0
  4669.6   0.035       0  4797.6    0.07       0  4974.8    0.05       0
  4978.8    0.07       0  5006.7   0.035       0  5226.8    0.07       0
  5276.8     0.1       0
Bank Sta=4974.8,4978.8
Exp/Cntr=0.3,0.1

Type RM Length L Ch R = 1,1094,329,329,329
BEGIN DESCRIPTION:
Stream0616 0.1
END DESCRIPTION:
XS GIS Cut Line= 3
      1905419.01     13911544.13      1905156.33     13911379.88
      1904908.17     13911437.18
#Sta/Elev= 30
  4606.5 1821.42  4607.6 1821.42  4673.5 1816.23  4681.6 1814.67  4688.8 1812.89
  4710.0 1812.94  4717.4 1812.43  4731.3 1809.85  4776.3 1807.54  4783.2 1806.14
  4789.0 1803.69  4840.9 1800.21  4892.8 1799.37  4916.2 1796.74  4962.6 1797.83
  4977.3 1796.23  4977.5 1795.73  4981.3 1796.23  4999.8 1796.28  5005.3 1798.14
  5010.5 1797.59  5020.3 1798.49  5030.6 1798.41  5047.9 1800.20  5090.8 1801.29
  5096.0 1802.50  5138.7 1802.29  5143.9 1803.69  5149.8 1803.33  5171.0 1802.91
#Mann=7,-1,0
  4606.5     0.1       0  4607.6   0.035       0  4681.6    0.07       0
  4977.3    0.05       0  4981.3    0.07       0  5047.9   0.035       0
  5149.8    0.07       0
Bank Sta=4977.3,4981.3
Exp/Cntr=0.3,0.1

Type RM Length L Ch R = 1,765,433,433,433
BEGIN DESCRIPTION:
Stream0616 0.2
END DESCRIPTION:
XS GIS Cut Line= 3
      1905455.86     13911394.51      1905152.60     13911192.77
      1904975.69     13911202.29
#Sta/Elev= 30
  4723.8 1815.96  4731.4 1815.62  4758.0 1812.44  4824.6 1807.47  4845.6 1804.76
  4879.3 1802.11  4911.0 1800.30  4941.0 1797.71  4944.5 1796.64  4962.8 1793.23
  4981.9 1792.24  4982.1 1791.74  4985.6 1791.74  4985.9 1792.24  4989.9 1793.06
  4995.2 1792.79  4998.9 1792.60  5004.9 1795.83  5013.1 1796.08  5019.9 1795.88
  5026.0 1793.20  5056.0 1793.82  5062.0 1792.96  5088.0 1792.87  5107.8 1794.88
  5115.7 1796.52  5145.7 1796.44  5175.8 1797.67  5226.7 1796.77  5265.2 1795.30
#Mann=8,-1,0
  4723.8   0.035       0  4758.0     0.1       0  4879.3    0.07       0
  4944.5     0.1       0  4981.9   0.035       0  4985.9     0.1       0
  4995.2   0.035       0  5107.8    0.07       0
Bank Sta=4981.9,4985.9
Exp/Cntr=0.3,0.1

Type RM Length L Ch R = 1,332,0,0,0
BEGIN DESCRIPTION:
Stream0616 0.0
END DESCRIPTION:
XS GIS Cut Line= 4
      1905511.39     13911097.26      1905354.19     13910923.29
      1905121.64     13910879.23      1904988.56     13910982.82
#Sta/Elev= 30
  4634.2 1800.25  4690.2 1798.29  4707.8 1796.55  4760.4 1795.75  4803.0 1793.20
  4831.4 1792.40  4845.6 1791.13  4870.8 1790.72  4908.6 1787.37  4935.8 1786.74
  4989.3 1787.24  5008.3 1784.05  5008.6 1783.55  5012.1 1783.55  5012.3 1784.05
  5040.9 1785.85  5071.4 1785.57  5099.0 1787.64  5103.3 1787.34  5121.5 1788.63
  5163.8 1789.86  5214.7 1789.74  5221.0 1790.19  5235.5 1787.14  5241.8 1788.07
  5250.0 1786.21  5256.3 1786.88  5264.5 1785.97  5270.8 1786.58  5274.0 1786.21
#Mann=6,-1,0
  4634.2     0.1       0  4707.8    0.07       0  4935.8   0.035       0
  5008.3   0.035       0  5012.3   0.035       0  5163.8    0.07       0
Bank Sta=5008.3,5012.3
Exp/Cntr=0.3,0.1

Chan Stop Cuts=-1