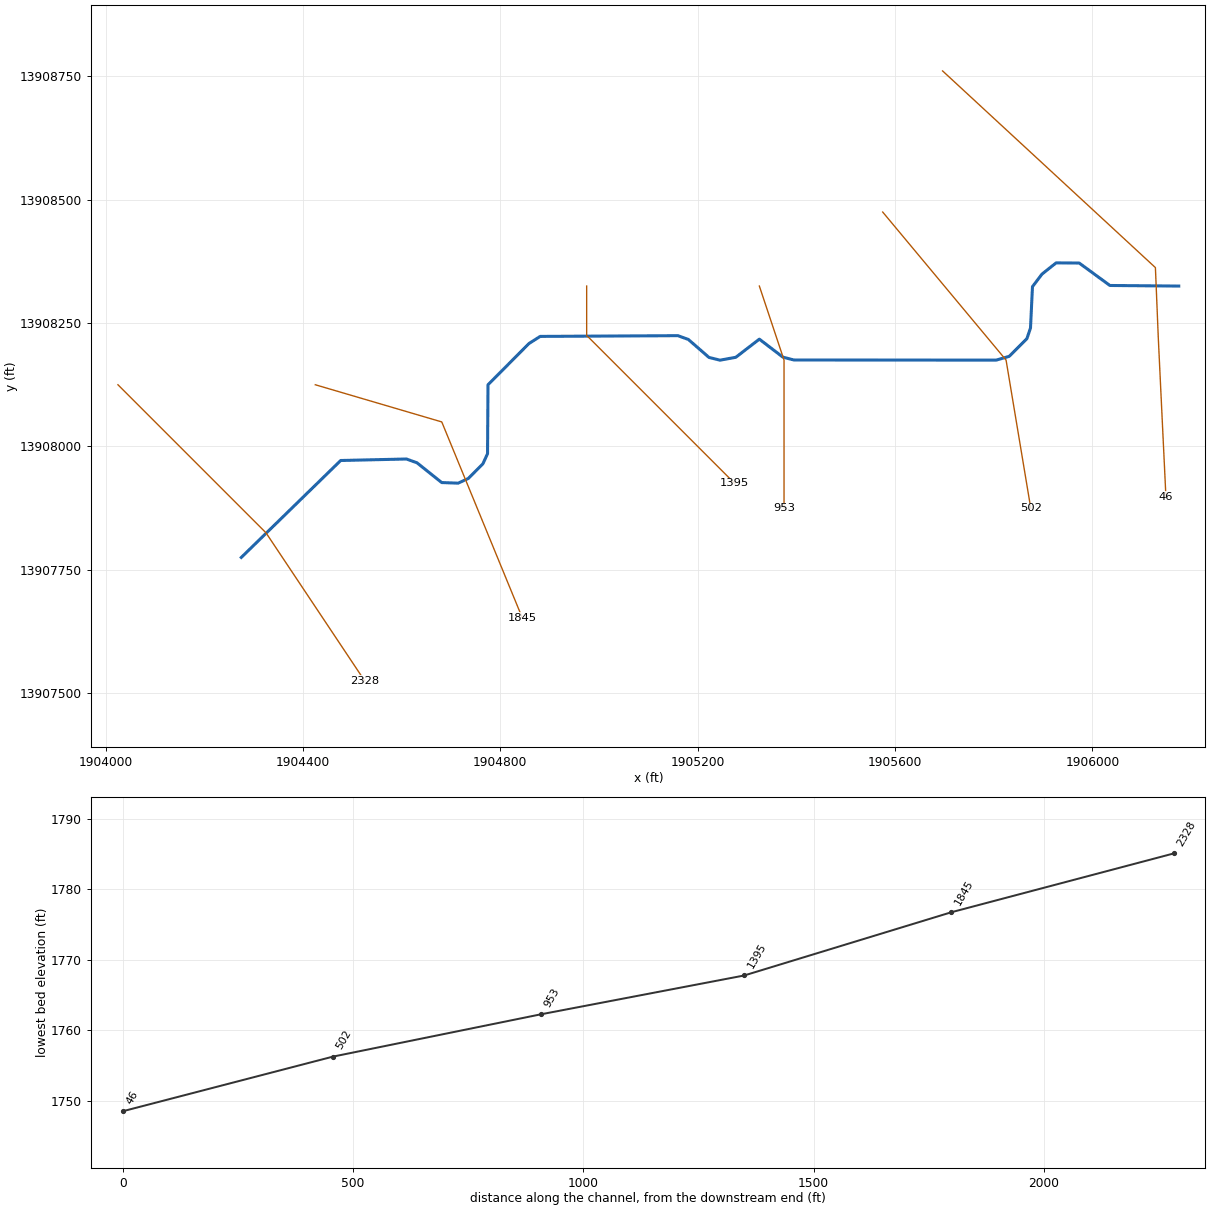
--- Stream0617.prj (project) ---

Proj Title=Stream0617 Base Level Engineering
Current Plan=p01
Default Exp/Contr=0.3,0.1
English Units
Geom File=g01
Flow File=f01
Plan File=p01
Y Axis Title=Elevation
X Axis Title(PF)=Main Channel Distance
X Axis Title(XS)=Station
BEGIN DESCRIPTION:
Stream0617
END DESCRIPTION:
DSS Export Rating Curves= 0
DSS Export Rating Curve Sorted= 0
DSS Export Volume Flow Curves= 0
DXF OffsetX= 0
DXF OffsetY= 0
DXF ScaleX= 1
DXF ScaleY= 10

--- Stream0617.p01 (plan) ---

Plan Title=Multiple Run
Short Identifier=Multiple
Geom File=g01
Flow File=f01
Subcritical Flow
K Sum by GR= 0
Std Step Tol= 0.01
Critical Tol= 0.01
Num of Std Step Trials= 20
Max Error Tol= 0.3
Flow Tol Ratio= 0.001
Split Flow NTrial= 30
Split Flow Tol= 0.02
Split Flow Ratio= 0.02
Log Output Level= 0
Friction Slope Method= 1
Unsteady Friction Slope Method= 2
Unsteady Bridges Friction Slope Method= 1
Parabolic Critical Depth
Global Vel Dist=  1 , 1 , 1
Global Log Level= 0
CheckData=True
Encroach Param= -1, 0, 0, 0
BEGIN DESCRIPTION:
Multiple Run
END DESCRIPTION:

--- Stream0617.f01 (steady flow) ---

Flow Title=Multiple
Program Version=4.10
Number of Profiles= 7
Profile Names=10-year,25-year,50-year,1pct_min,100-year,1pct_plu,500-year
River Rch & RM=Stream0617,Reach-1         ,2328
    1342    2329    3287    2244    4476    8932    8200
Boundary for River Rch & Prof#=Stream0617,Reach-1         , 1
Up Type= 0
Dn Type= 3
Dn Slope=0.008
Boundary for River Rch & Prof#=Stream0617,Reach-1         , 2
Up Type= 0
Dn Type= 3
Dn Slope=0.008
Boundary for River Rch & Prof#=Stream0617,Reach-1         , 3
Up Type= 0
Dn Type= 3
Dn Slope=0.008
Boundary for River Rch & Prof#=Stream0617,Reach-1         , 4
Up Type= 0
Dn Type= 3
Dn Slope=0.008
Boundary for River Rch & Prof#=Stream0617,Reach-1         , 5
Up Type= 0
Dn Type= 3
Dn Slope=0.008
Boundary for River Rch & Prof#=Stream0617,Reach-1         , 6
Up Type= 0
Dn Type= 3
Dn Slope=0.008
Boundary for River Rch & Prof#=Stream0617,Reach-1         , 7
Up Type= 0
Dn Type= 3
Dn Slope=0.008
DSS Import GetInterval= 0
DSS Import GetPeak= 0
DSS Import FillOption= 0

--- Stream0617.g01 (geometry) ---

Geom Title=Existing Conditions
Program Version=4.10

River Reach=Stream0617      ,Reach-1
Reach XY= 30
        1904275.       13907775.      1904476.47     13907971.47
      1904609.78     13907974.48      1904631.08     13907966.81
      1904681.17     13907926.77      1904714.55     13907925.52
      1904735.06     13907935.03      1904764.67     13907964.75
      1904774.08     13907985.21        1904775.       13908125.
      1904858.19     13908208.67      1904880.84     13908222.98
      1905159.79     13908224.46      1905181.08     13908216.81
      1905222.83      13908180.4      1905245.21     13908174.79
      1905277.29     13908180.65      1905324.99     13908217.41
      1905372.55     13908181.02      1905394.98     13908175.18
      1905805.13     13908174.91      1905831.52     13908182.68
      1905867.27      13908218.5      1905874.53     13908240.08
      1905878.53     13908323.78      1905897.72     13908349.15
      1905926.39     13908371.97      1905973.22     13908371.68
      1906035.47     13908326.19        1906175.       13908325.

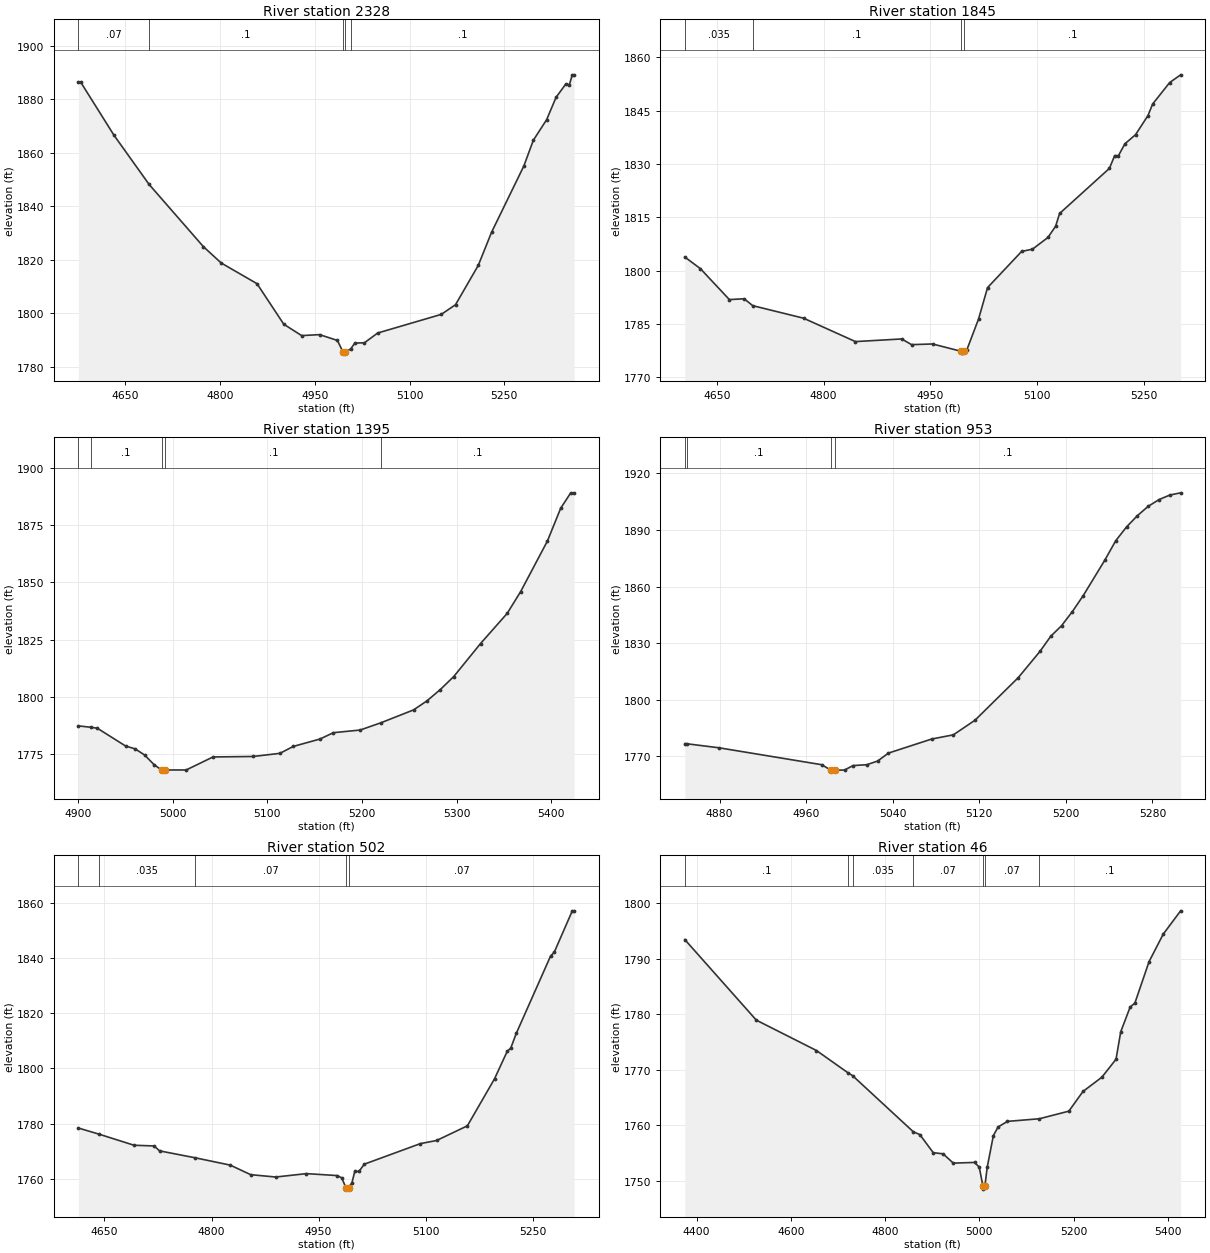
Type RM Length L Ch R = 1 ,2328    ,483,483,483
BEGIN DESCRIPTION:
Stream0617 5.0
END DESCRIPTION:
XS GIS Cut Line= 3
      1904025.03     13908124.97        1904325.       13907825.
      1904525.01     13907524.98
#Sta/Elev= 30
  4575.8 1886.48  4579.3 1886.48  4632.3 1866.52  4687.8 1848.16  4773.7  1824.9
    4802 1818.77  4858.6 1811.05    4901 1795.88  4929.3 1791.63  4957.6    1792
  4985.9 1789.82  4994.5 1785.58  4994.7 1785.08  4998.5 1785.58  5006.7  1786.6
  5013.5 1788.84  5028.6 1788.94  5049.6  1792.6  5150.3 1799.57  5172.8 1803.18
  5208.8 1817.88  5229.9 1830.28    5281 1855.06    5296 1864.68    5317 1872.34
    5332 1880.74  5347.1 1885.59  5353.1 1885.47  5357.6 1889.13  5360.6 1889.13
#Mann= 5 ,-1 , 0
  4575.8     .07       0  4687.8      .1       0  4994.5     .05       0
  4998.5      .1       0  5006.7      .1       0
Bank Sta=4994.5,4998.5
XS Rating Curve= 0 ,0
Exp/Cntr=0.3,0.1

Type RM Length L Ch R = 1 ,1845    ,450,450,450
BEGIN DESCRIPTION:
Stream0617 4.0
END DESCRIPTION:
XS GIS Cut Line= 3
      1904424.99       13908125.      1904681.31     13908049.65
      1904844.52     13907652.55
#Sta/Elev= 30
    4605  1803.8  4626.9 1800.52  4667.6 1791.81  4688.4 1792.04  4700.4  1790.1
  4771.8 1786.57  4844.7 1779.98  4909.6 1780.72  4923.6 1779.12    4953 1779.31
  4993.5 1777.23  4993.7 1776.73  4997.5 1777.23  5000.9  1777.5  5017.7 1786.37
  5030.3 1795.19  5078.2 1805.38  5093.4 1806.01  5115.1  1809.3  5125.9 1812.47
  5131.5 1816.06  5201.5 1828.77  5208.8 1832.33  5214.2 1832.36  5223.2 1835.68
  5238.2 1838.26  5255.6 1843.63  5262.2 1846.89  5286.1 1852.93  5301.5 1855.11
#Mann= 4 ,-1 , 0
    4605    .035       0  4700.4      .1       0  4993.5     .05       0
  4997.5      .1       0
Bank Sta=4993.5,4997.5
XS Rating Curve= 0 ,0
Exp/Cntr=0.3,0.1

Type RM Length L Ch R = 1 ,1395    ,442,442,442
BEGIN DESCRIPTION:
Stream0617 3.0
END DESCRIPTION:
XS GIS Cut Line= 3
        1904975.     13908324.99        1904975.       13908225.
      1905275.03     13907924.97
#Sta/Elev= 30
  4900.1 1787.48    4913 1786.88  4920.1 1786.47  4950.1 1778.69  4960.1 1777.47
  4970.1  1774.8  4980.1 1770.61  4988.1 1768.25  4988.3 1767.75  4992.1 1768.25
  5014.2 1768.26  5042.5 1773.93  5084.9 1774.13  5113.2  1775.5  5127.4 1778.52
  5155.7 1781.75  5169.8 1784.51  5198.1 1785.66  5220.4 1788.88  5254.6 1794.44
  5268.8 1798.39  5282.9 1803.33  5297.1 1808.99  5325.4 1823.36  5353.6 1836.52
  5367.8 1845.99  5396.1 1868.03  5410.2 1882.38  5420.8 1889.06  5424.4 1889.06
#Mann= 5 ,-1 , 0
  4900.1     .07       0    4913      .1       0  4988.1     .05       0
  4992.1      .1       0  5220.4      .1       0
Bank Sta=4988.1,4992.1
XS Rating Curve= 0 ,0
Exp/Cntr=0.3,0.1

Type RM Length L Ch R = 1 ,953     ,451,451,451
BEGIN DESCRIPTION:
Stream0617 2.0
END DESCRIPTION:
XS GIS Cut Line= 3
      1905324.99     13908325.04        1905375.       13908175.
        1905375.     13907874.96
#Sta/Elev= 30
  4847.9 1776.72  4849.8 1776.72  4879.6 1774.58  4974.4 1765.63    4983 1762.73
  4983.2 1762.23  4986.7 1762.23    4987 1762.73  4995.5 1762.81  5003.4 1765.18
  5016.1 1765.62  5026.1 1767.58  5036.1 1771.78  5076.1 1779.24  5096.1 1781.45
  5116.1  1789.2  5156.1 1811.77  5176.1 1825.63  5186.1 1833.66  5196.1 1839.27
  5206.1 1846.75  5216.1 1855.19  5236.1 1874.01  5246.1 1884.22  5256.1 1891.54
  5266.1 1897.48  5276.1 1902.45  5286.1 1906.02  5296.1 1908.43  5306.1 1909.61
#Mann= 4 ,-1 , 0
  4847.9     .07       0  4849.8      .1       0    4983     .05       0
    4987      .1       0
Bank Sta=4983,4987
XS Rating Curve= 0 ,0
Exp/Cntr=0.3,0.1

Type RM Length L Ch R = 1 ,502     ,456,456,456
BEGIN DESCRIPTION:
Stream0617 1.0
END DESCRIPTION:
XS GIS Cut Line= 3
        1905575.       13908475.        1905825.       13908175.
      1905875.01     13907874.96
#Sta/Elev= 30
  4613.4 1778.39  4641.8 1776.21  4691.5 1772.14  4719.5 1771.89  4727.3  1770.1
  4777.2 1767.59  4826.2 1764.94  4854.9 1761.47    4890 1760.62    4933 1761.85
  4975.9 1761.15  4982.4 1760.34  4988.3 1756.73  4988.5 1756.23  4992.3 1756.73
  4996.8 1758.57  5000.7 1762.63  5006.5 1762.63  5014.1 1765.28  5092.6 1772.73
  5115.4 1773.87  5158.5 1779.19  5196.5 1796.22  5214.3 1806.19  5219.3 1807.38
    5227 1812.71  5275.1 1840.77  5280.2 1842.13  5305.5 1857.15  5308.1 1857.15
#Mann= 5 ,-1 , 0
  4613.4      .1       0  4641.8    .035       0  4777.2     .07       0
  4988.3     .05       0  4992.3     .07       0
Bank Sta=4988.3,4992.3
XS Rating Curve= 0 ,0
Exp/Cntr=0.3,0.1

Type RM Length L Ch R = 1 ,46      ,0,0,0
BEGIN DESCRIPTION:
Stream0617 0.0
END DESCRIPTION:
XS GIS Cut Line= 4
      1905696.35     13908761.06      1906127.69     13908362.42
       1906133.6     13908218.55      1906148.98     13907898.05
#Sta/Elev= 30
  4375.1 1793.45  4526.9 1778.93  4654.5 1773.46  4721.3 1769.45    4731 1768.94
  4860.2  1758.8  4873.9 1758.31  4902.3 1755.05  4923.3 1754.84  4944.8 1753.17
  4989.9 1753.29  4999.9 1752.45  5007.9 1748.98  5008.2 1748.48  5011.9 1748.98
  5016.8  1752.4  5029.9 1758.12  5039.9 1759.68  5059.9 1760.69  5127.4 1761.16
  5190.1 1762.53  5220.1 1766.08  5260.2 1768.65  5290.2 1771.88  5300.2 1776.83
  5320.2 1781.29  5330.2    1782  5360.3 1789.47  5390.3 1794.42  5427.3 1798.63
#Mann= 7 ,-1 , 0
  4375.1      .1       0  4721.3     .07       0    4731    .035       0
  4860.2     .07       0  5007.9     .05       0  5011.9     .07       0
  5127.4      .1       0
Bank Sta=5007.9,5011.9
XS Rating Curve= 0 ,0
Exp/Cntr=0.3,0.1

Chan Stop Cuts=-1
Use User Specified Reach Order=0
Composite Channel Slope=5