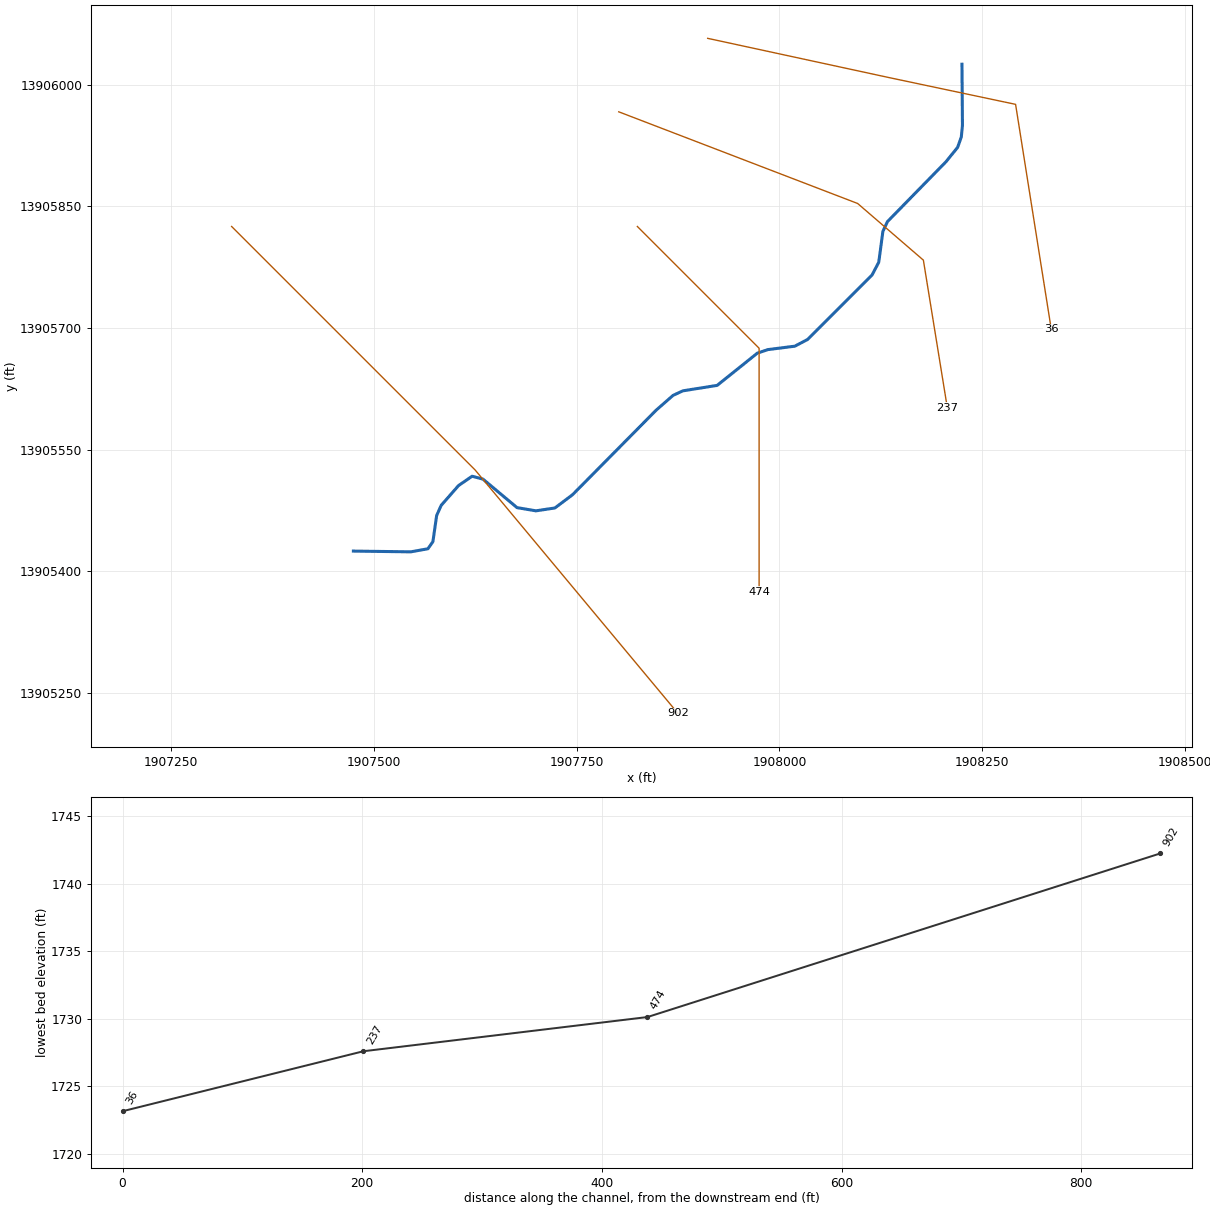
--- Stream0620.prj (project) ---

Proj Title=Stream0620 Base Level Engineering
Current Plan=p01
Default Exp/Contr=0.3,0.1
English Units
Geom File=g01
Flow File=f01
Plan File=p01
Y Axis Title=Elevation
X Axis Title(PF)=Main Channel Distance
X Axis Title(XS)=Station
BEGIN DESCRIPTION:
Stream0620
END DESCRIPTION:
DSS Export Rating Curves= 0
DSS Export Rating Curve Sorted= 0
DSS Export Volume Flow Curves= 0
DXF OffsetX= 0
DXF OffsetY= 0
DXF ScaleX= 1
DXF ScaleY= 10

--- Stream0620.p01 (plan) ---

Plan Title=Multiple Run
Short Identifier=Multiple
Geom File=g01
Flow File=f01
Subcritical Flow
K Sum by GR= 0
Std Step Tol= 0.01
Critical Tol= 0.01
Num of Std Step Trials= 20
Max Error Tol= 0.3
Flow Tol Ratio= 0.001
Split Flow NTrial= 30
Split Flow Tol= 0.02
Split Flow Ratio= 0.02
Log Output Level= 0
Friction Slope Method= 1
Unsteady Friction Slope Method= 2
Unsteady Bridges Friction Slope Method= 1
Parabolic Critical Depth
Global Vel Dist=  1 , 1 , 1
Global Log Level= 0
CheckData=True
Encroach Param= -1, 0, 0, 0
BEGIN DESCRIPTION:
Multiple Run
END DESCRIPTION:

--- Stream0620.f01 (steady flow) ---

Flow Title=Multiple
Program Version=4.10
Number of Profiles= 7
Profile Names=10-year,25-year,50-year,1pct_min,100-year,1pct_plu,500-year
River Rch & RM=Stream0620,Reach-1         ,902
     795    1330    1832    1223    2440    4867    4266
Boundary for River Rch & Prof#=Stream0620,Reach-1         , 1
Up Type= 0
Dn Type= 3
Dn Slope=0.01
Boundary for River Rch & Prof#=Stream0620,Reach-1         , 2
Up Type= 0
Dn Type= 3
Dn Slope=0.01
Boundary for River Rch & Prof#=Stream0620,Reach-1         , 3
Up Type= 0
Dn Type= 3
Dn Slope=0.01
Boundary for River Rch & Prof#=Stream0620,Reach-1         , 4
Up Type= 0
Dn Type= 3
Dn Slope=0.01
Boundary for River Rch & Prof#=Stream0620,Reach-1         , 5
Up Type= 0
Dn Type= 3
Dn Slope=0.01
Boundary for River Rch & Prof#=Stream0620,Reach-1         , 6
Up Type= 0
Dn Type= 3
Dn Slope=0.01
Boundary for River Rch & Prof#=Stream0620,Reach-1         , 7
Up Type= 0
Dn Type= 3
Dn Slope=0.01
DSS Import GetInterval= 0
DSS Import GetPeak= 0
DSS Import FillOption= 0

--- Stream0620.g01 (geometry) ---

Geom Title=Existing Conditions
Program Version=4.10

River Reach=Stream0620      ,Reach-1
Reach XY= 30
        1907475.       13905425.       1907545.8     13905424.08
      1907566.89     13905427.88      1907573.03     13905436.74
      1907577.65     13905468.94      1907583.25     13905481.39
      1907604.62     13905505.77      1907621.36     13905517.25
      1907634.75     13905513.65      1907676.64     13905478.59
        1907700.      13905474.6      1907723.35     13905478.16
      1907745.09     13905494.44      1907848.18     13905598.71
      1907868.94     13905616.86      1907881.04      13905622.5
      1907923.26     13905629.19      1907972.81      13905668.9
      1907985.71      13905673.3      1908018.97      13905677.5
       1908034.7     13905685.76      1908114.23      13905765.3
      1908122.47     13905781.04      1908127.54     13905818.95
      1908133.18     13905831.04      1908205.34     13905904.86
      1908219.64     13905922.51      1908224.18     13905935.34
      1908225.59     13905949.76        1908225.       13906025.

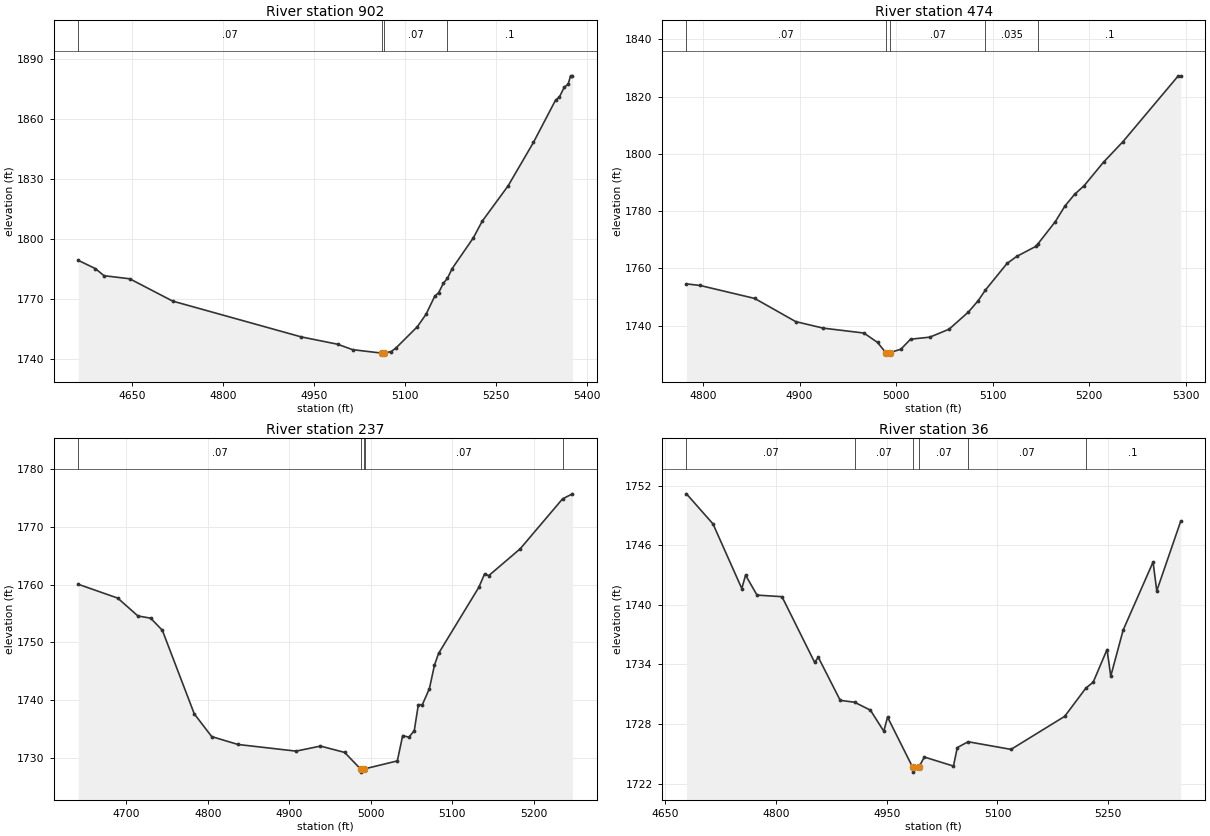
Type RM Length L Ch R = 1 ,902     ,428,428,428
BEGIN DESCRIPTION:
Stream0620 2.0
END DESCRIPTION:
XS GIS Cut Line= 3
      1907324.97     13905825.03        1907625.       13905525.
      1907874.99     13905225.01
#Sta/Elev= 30
  4561.4 1789.12  4589.7 1784.98  4603.9 1781.44  4646.3  1779.9    4717 1768.75
  4929.1 1750.84    4989 1747.18  5013.7 1744.46  5061.8 1742.73  5062.1 1742.23
  5065.8 1742.73  5077.5 1743.54  5085.3 1745.34  5120.4 1755.93  5134.7 1762.13
  5149.1 1771.18  5155.6 1772.99  5163.4 1777.68    5170 1780.13  5177.7 1784.95
  5212.8  1800.4  5227.2 1808.62  5270.1 1826.39  5311.8 1848.08  5348.2 1869.18
  5354.7 1870.85  5362.5 1875.59  5369.1 1877.26    5373 1881.38  5376.2 1881.38
#Mann= 4 ,-1 , 0
  4561.4     .07       0  5061.8     .05       0  5065.8     .07       0
    5170      .1       0
Bank Sta=5061.8,5065.8
XS Rating Curve= 0 ,0
Exp/Cntr=0.3,0.1

Type RM Length L Ch R = 1 ,474     ,237,237,237
BEGIN DESCRIPTION:
Stream0620 1.0
END DESCRIPTION:
XS GIS Cut Line= 3
      1907824.98     13905825.02        1907975.       13905675.
        1907975.     13905374.96
#Sta/Elev= 30
  4782.8 1754.63    4797 1754.07  4853.5 1749.55    4896 1741.47  4924.3  1739.2
  4966.7 1737.48  4980.8 1734.21  4989.4 1730.62  4989.7 1730.12  4993.2 1730.12
  4993.4 1730.62    5005 1731.84    5015 1735.33    5035 1736.04    5055 1738.83
    5075 1744.82    5085 1748.72  5092.6 1752.47    5115 1761.76    5125  1764.2
    5145 1767.74  5147.1 1768.62    5165 1776.33    5175 1781.78    5185 1785.86
    5195 1788.92    5215 1797.09    5235  1804.2  5292.5 1827.22    5295 1827.22
#Mann= 5 ,-1 , 0
  4782.8     .07       0  4989.4     .05       0  4993.4     .07       0
  5092.6    .035       0  5147.1      .1       0
Bank Sta=4989.4,4993.4
XS Rating Curve= 0 ,0
Exp/Cntr=0.3,0.1

Type RM Length L Ch R = 1 ,237     ,201,201,201
BEGIN DESCRIPTION:
Stream0620 0.0
END DESCRIPTION:
XS GIS Cut Line= 4
      1907802.03     13905966.35      1908096.47     13905853.37
      1908177.44     13905783.56      1908206.95     13905601.62
#Sta/Elev= 30
  4640.8 1760.05  4689.3 1757.66    4714 1754.58  4729.7 1754.19    4744  1752.1
  4783.2 1737.66  4804.6 1733.73  4836.8 1732.37  4908.1 1731.22  4938.1 1732.09
  4967.7    1731  4987.6 1728.09  4987.9 1727.59  4991.6 1728.09  4992.8 1728.17
  5032.4 1729.53    5039 1733.91  5046.6 1733.62  5053.2 1734.75  5058.2 1739.24
  5063.1 1739.24  5071.8 1742.03    5078 1746.08    5083  1748.1  5132.5 1759.54
  5139.6 1761.87  5144.6 1761.54  5183.2 1766.18  5235.2 1774.81  5247.4 1775.68
#Mann= 5 ,-1 , 0
  4640.8     .07       0  4987.6     .05       0  4991.6     .07       0
  4992.8     .07       0  5235.2     .07       0
Bank Sta=4987.6,4991.6
XS Rating Curve= 0 ,0
Exp/Cntr=0.3,0.1

Type RM Length L Ch R = 1 ,36      ,0,0,0
BEGIN DESCRIPTION:
Stream0620 0.1
END DESCRIPTION:
XS GIS Cut Line= 4
      1907911.63      13906056.9      1908134.88     13906008.59
      1908291.08     13905975.55      1908335.08      13905698.1
#Sta/Elev= 30
    4679 1751.18  4714.9 1748.15  4753.9 1741.64    4759 1742.99  4774.5 1740.98
  4808.3 1740.82  4852.4 1734.22  4857.5 1734.71  4887.1 1730.38  4906.5 1730.19
    4928 1729.39  4946.1 1727.27  4951.2 1728.69  4985.1 1723.65  4985.6 1723.15
  4993.5 1723.65    5001 1724.67  5040.4 1723.76  5045.6 1725.62  5060.2 1726.21
  5118.3 1725.44    5191 1728.77  5219.5  1731.6  5229.6 1732.22  5248.3  1735.5
  5253.3 1732.81  5270.1 1737.46  5310.6 1744.31  5315.6 1741.41    5348 1748.42
#Mann= 6 ,-1 , 0
    4679     .07       0  4906.5     .07       0  4985.1     .05       0
  4993.5     .07       0  5060.2     .07       0  5219.5      .1       0
Bank Sta=4985.1,4993.5
XS Rating Curve= 0 ,0
Exp/Cntr=0.3,0.1

Chan Stop Cuts=-1
Use User Specified Reach Order=0
Composite Channel Slope=5