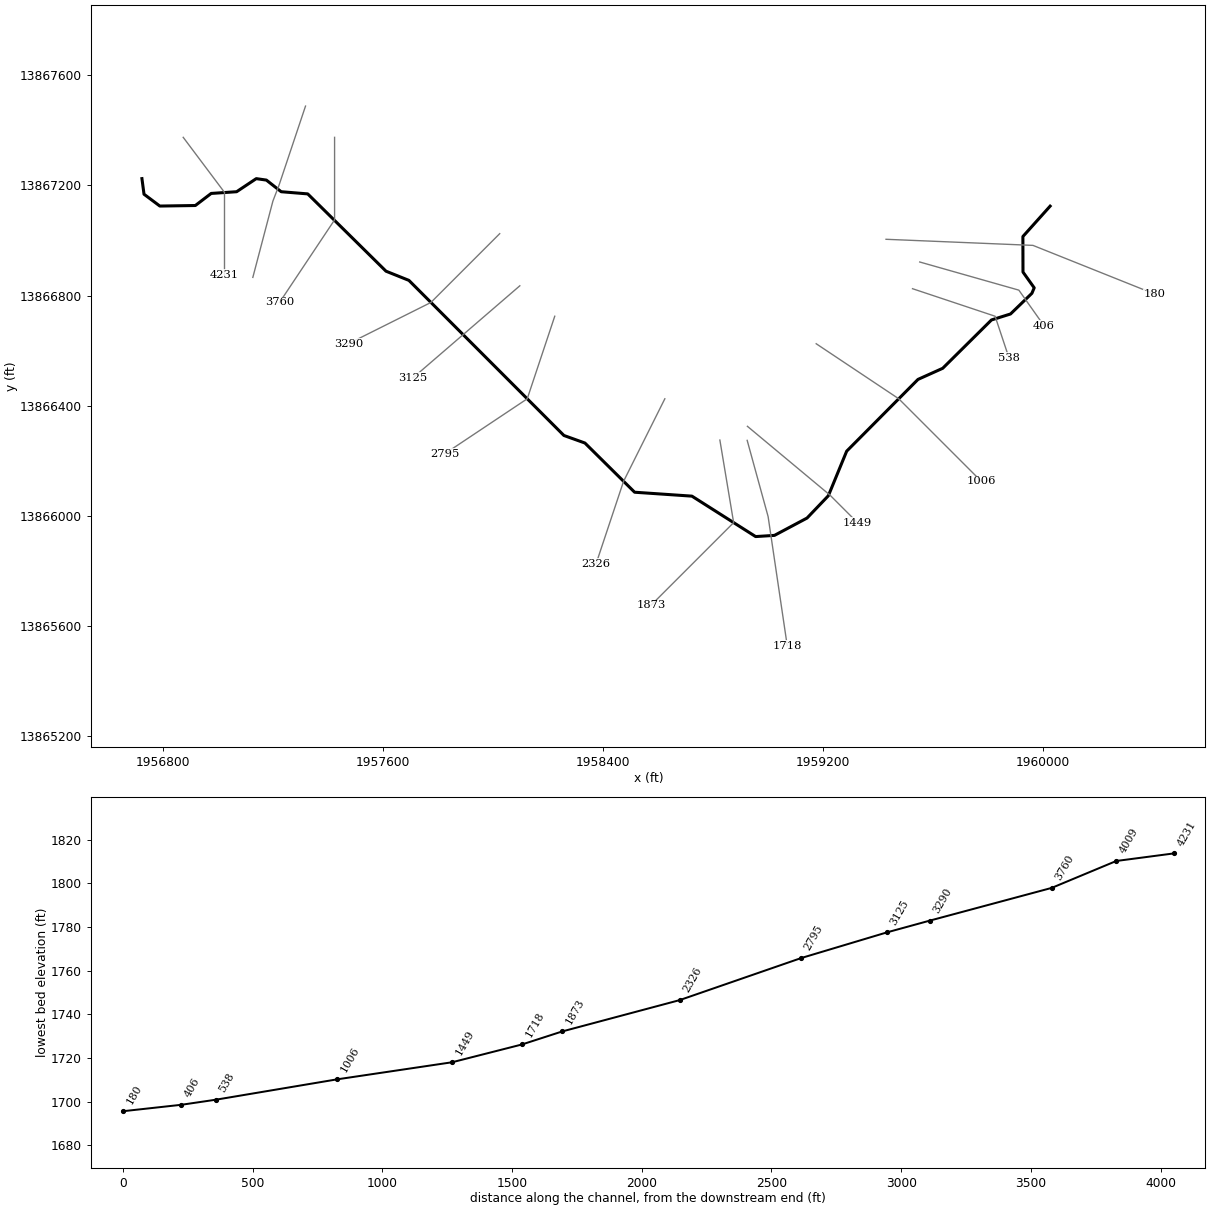
--- Stream0621.prj (project) ---

Proj Title=Stream0621 Base Level Engineering
Current Plan=p01
Default Exp/Contr=0.3,0.1
English Units
Geom File=g01
Flow File=f01
Plan File=p01
BEGIN DESCRIPTION:
Stream0621
END DESCRIPTION:

--- Stream0621.p01 (plan) ---

Plan Title=Multiple Run
Short Identifier=Multiple
Geom File=g01
Flow File=f01
Subcritical Flow
K Sum by GR= 0
Std Step Tol= 0.01
Critical Tol= 0.01
Num of Std Step Trials= 20
Max Error Tol= 0.3
Flow Tol Ratio= 0.001
Split Flow NTrial= 30
Split Flow Tol= 0.02
Split Flow Ratio= 0.02
Log Output Level= 0
Friction Slope Method= 1
Unsteady Friction Slope Method= 2
Unsteady Bridges Friction Slope Method= 1
Parabolic Critical Depth
Global Vel Dist=  1 , 1 , 1
Global Log Level= 0
CheckData=True
Encroach Param= -1, 0, 0, 0
BEGIN DESCRIPTION:
Multiple Run
END DESCRIPTION:

--- Stream0621.f01 (steady flow) ---

Flow Title=Multiple
Number of Profiles=7
Profile Names=10-year,25-year,50-year,1pct_min,100-year,1pct_plu,500-year
River Rch & RM= Stream0621,Reach-1,4231
     640    1056    1442     956    1907    3805    3284
Boundary for River Rch & Prof#=Stream0621,Reach-1,1
Up Type=0
Dn Type=3
Dn Slope=0.005
Boundary for River Rch & Prof#=Stream0621,Reach-1,2
Up Type=0
Dn Type=3
Dn Slope=0.005
Boundary for River Rch & Prof#=Stream0621,Reach-1,3
Up Type=0
Dn Type=3
Dn Slope=0.005
Boundary for River Rch & Prof#=Stream0621,Reach-1,4
Up Type=0
Dn Type=3
Dn Slope=0.005
Boundary for River Rch & Prof#=Stream0621,Reach-1,5
Up Type=0
Dn Type=3
Dn Slope=0.005
Boundary for River Rch & Prof#=Stream0621,Reach-1,6
Up Type=0
Dn Type=3
Dn Slope=0.005
Boundary for River Rch & Prof#=Stream0621,Reach-1,7
Up Type=0
Dn Type=3
Dn Slope=0.005

--- Stream0621.g01 (geometry) ---

Geom Title=Existing Conditions

River Reach=Stream0621,Reach-1
Reach XY= 30
      1956725.00     13867225.00      1956732.56     13867168.30
      1956790.06     13867125.30      1956919.06     13867127.25
      1956976.60     13867171.14      1957069.03     13867177.38
      1957140.39     13867224.91      1957177.18     13867219.63
      1957230.97     13867177.38      1957327.43     13867169.48
      1957611.79     13866888.63      1957695.09     13866855.21
      1958258.33     13866291.65      1958334.68     13866264.22
      1958515.20     13866085.48      1958723.45     13866071.25
      1958954.92     13865924.33      1959023.41     13865928.67
      1959141.71     13865991.63      1959219.17     13866072.69
      1959285.76     13866234.68      1959544.84     13866495.38
      1959634.68     13866535.78      1959811.79     13866711.37
      1959881.09     13866733.16      1959958.72     13866808.26
      1959967.13     13866828.21      1959926.38     13866885.44
      1959926.01     13867014.57      1960025.00     13867125.00

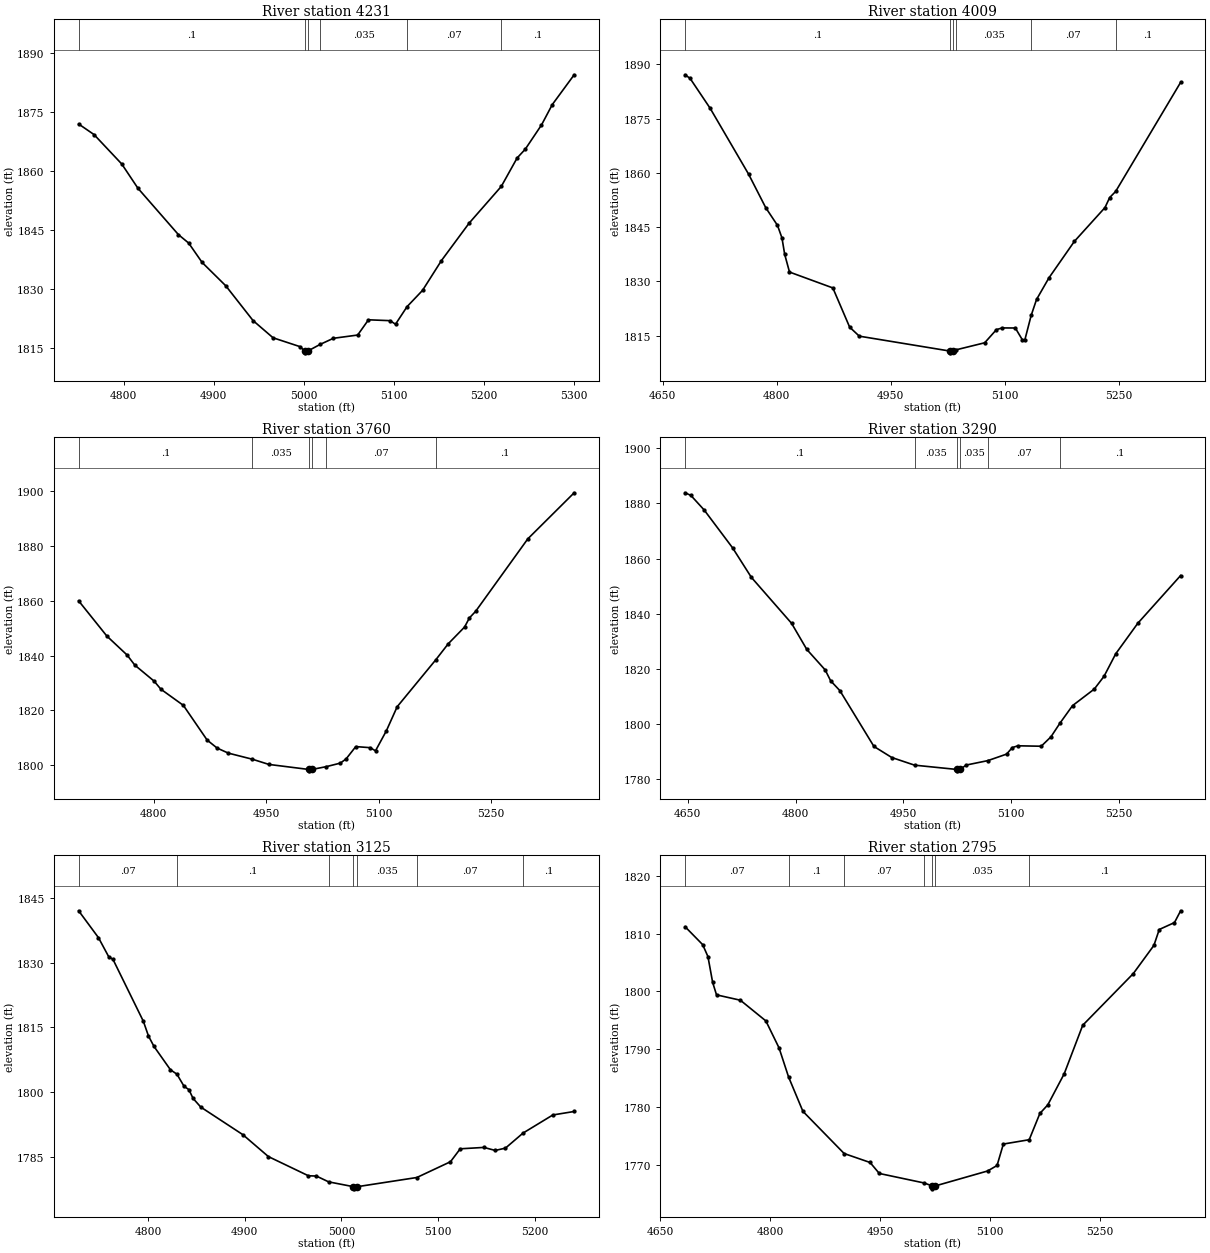
Type RM Length L Ch R = 1,4231,222,222,222
BEGIN DESCRIPTION:
Stream0621 9.0
END DESCRIPTION:
XS GIS Cut Line= 3
      1956875.00     13867375.00      1957025.00     13867175.00
      1957025.00     13866875.00
#Sta/Elev= 30
  4750.0 1871.98  4767.1 1869.29  4797.9 1861.79  4815.8 1855.63  4860.8 1843.81
  4872.1 1841.68  4887.1 1836.73  4913.3 1830.80  4943.6 1821.94  4965.8 1817.56
  4995.8 1815.30  5000.7 1814.23  5000.9 1813.73  5004.7 1814.23  5017.9 1815.86
  5032.7 1817.43  5059.7 1818.26  5071.7 1822.14  5095.7 1821.92  5101.7 1821.01
  5114.5 1825.48  5131.7 1829.63  5152.7 1837.22  5183.4 1846.74  5219.1 1856.09
  5236.7 1863.34  5245.7 1865.56  5263.7 1871.72  5275.7 1876.92  5300.0 1884.51
#Mann=6,-1,0
  4750.0     0.1       0  5000.7    0.05       0  5004.7     0.1       0
  5017.9   0.035       0  5114.5    0.07       0  5219.1     0.1       0
Bank Sta=5000.7,5004.7
Exp/Cntr=0.3,0.1

Type RM Length L Ch R = 1,4009,249,249,249
BEGIN DESCRIPTION:
Stream0621 8.1
END DESCRIPTION:
XS GIS Cut Line= 4
      1957319.41     13867488.54      1957223.05     13867200.77
      1957200.92     13867143.48      1957127.99     13866866.10
#Sta/Elev= 30
  4679.4 1887.15  4686.0 1886.14  4712.3 1877.90  4762.9 1859.67  4785.5 1850.38
  4800.9 1845.51  4806.8 1842.03  4810.4 1837.47  4816.7 1832.60  4873.7 1828.21
  4895.8 1817.37  4908.5 1814.87  5027.4 1810.76  5027.7 1810.26  5031.4 1810.76
  5036.3 1811.12  5073.4 1813.04  5088.9 1816.69  5096.5 1817.15  5113.7 1817.13
  5123.0 1813.84  5126.1 1813.74  5134.5 1820.59  5141.6 1825.02  5157.9 1830.99
  5191.3 1841.07  5231.6 1850.43  5237.8 1853.21  5245.6 1854.88  5331.1 1885.06
#Mann=6,-1,0
  4679.4     0.1       0  5027.4    0.05       0  5031.4     0.1       0
  5036.3   0.035       0  5134.5    0.07       0  5245.6     0.1       0
Bank Sta=5027.4,5031.4
Exp/Cntr=0.3,0.1

Type RM Length L Ch R = 1,3760,470,470,470
BEGIN DESCRIPTION:
Stream0621 8.0
END DESCRIPTION:
XS GIS Cut Line= 3
      1957425.00     13867374.96      1957425.00     13867075.00
      1957225.01     13866775.01
#Sta/Elev= 30
  4700.1 1859.99  4737.7 1847.14  4764.7 1840.21  4775.0 1836.52  4800.7 1830.68
  4809.7 1827.74  4839.7 1821.83  4871.4 1809.16  4884.7 1806.24  4899.7 1804.39
  4931.8 1802.16  4953.7 1800.27  5007.0 1798.43  5007.2 1797.93  5011.0 1798.43
  5030.2 1799.46  5048.9 1800.75  5056.6 1802.28  5069.5 1806.78  5088.6 1806.39
  5095.8 1805.24  5110.2 1812.50  5124.7 1821.34  5176.1 1838.45  5192.8 1844.33
  5214.5 1850.42  5221.0 1853.77  5229.2 1856.14  5298.8 1882.62  5360.6 1899.44
#Mann=6,-1,0
  4700.1     0.1       0  4931.8   0.035       0  5007.0   0.035       0
  5011.0   0.035       0  5030.2    0.07       0  5176.1     0.1       0
Bank Sta=5007,5011
Exp/Cntr=0.3,0.1

Type RM Length L Ch R = 1,3290,165,165,165
BEGIN DESCRIPTION:
Stream0621 7.0
END DESCRIPTION:
XS GIS Cut Line= 3
      1958024.97     13867024.97      1957775.00     13866775.00
      1957475.02     13866625.01
#Sta/Elev= 30
  4646.5 1883.86  4654.5 1882.91  4672.9 1877.65  4712.5 1863.88  4738.6 1853.17
  4794.5 1836.49  4815.7 1827.00  4841.2 1819.58  4848.9 1815.60  4861.7 1812.04
  4909.0 1791.80  4933.8 1787.78  4965.5 1785.00  5024.4 1783.44  5024.6 1782.94
  5028.4 1783.44  5037.5 1785.05  5067.4 1786.65  5093.4 1789.01  5101.4 1791.38
  5109.1 1792.03  5141.6 1791.87  5155.1 1795.28  5167.6 1800.23  5185.1 1806.60
  5215.4 1812.63  5228.9 1817.25  5245.2 1825.44  5275.8 1836.48  5335.4 1853.83
#Mann=6,-1,0
  4646.5     0.1       0  4965.5   0.035       0  5024.4   0.035       0
  5028.4   0.035       0  5067.4    0.07       0  5167.6     0.1       0
Bank Sta=5024.4,5028.4
Exp/Cntr=0.3,0.1

Type RM Length L Ch R = 1,3125,330,330,330
BEGIN DESCRIPTION:
Mapping XS 138a1e8f
END DESCRIPTION:
XS GIS Cut Line= 2
      1958098.07     13866835.54      1957709.59     13866500.81
#Sta/Elev= 30
  4728.0 1842.08  4748.5 1835.85  4759.0 1831.47  4763.6 1830.78  4795.0 1816.43
  4800.3 1813.01  4806.0 1810.60  4823.0 1805.19  4829.7 1804.17  4837.1 1801.35
  4842.1 1800.58  4846.4 1798.55  4854.4 1796.53  4898.0 1790.12  4924.4 1785.04
  4965.8 1780.59  4974.0 1780.53  4986.7 1779.18  5012.4 1778.06  5012.7 1777.56
  5016.4 1778.06  5078.0 1780.19  5112.8 1783.85  5122.9 1786.85  5147.4 1787.17
  5159.1 1786.47  5169.7 1787.01  5187.9 1790.50  5218.7 1794.70  5240.8 1795.51
#Mann=7,-1,0
  4728.0    0.07       0  4829.7     0.1       0  4986.7   0.035       0
  5012.4   0.035       0  5016.4   0.035       0  5078.0    0.07       0
  5187.9     0.1       0
Bank Sta=5012.4,5016.4
Exp/Cntr=0.3,0.1

Type RM Length L Ch R = 1,2795,469,469,469
BEGIN DESCRIPTION:
Stream0621 6.0
END DESCRIPTION:
XS GIS Cut Line= 3
      1958224.99     13866724.96      1958125.00     13866425.00
      1957825.03     13866225.02
#Sta/Elev= 30
  4683.8 1811.18  4707.8 1808.08  4715.0 1806.01  4721.4 1801.56  4726.7 1799.39
  4759.3 1798.46  4794.1 1794.88  4812.1 1790.21  4825.1 1785.18  4844.7 1779.23
  4901.0 1771.93  4936.4 1770.38  4949.0 1768.48  5010.4 1766.83  5021.3 1766.32
  5021.6 1765.82  5025.3 1766.32  5096.9 1768.91  5109.8 1769.86  5118.4 1773.57
  5153.7 1774.32  5168.3 1778.87  5179.1 1780.35  5201.5 1785.73  5226.8 1794.13
  5295.9 1803.08  5324.0 1807.95  5331.3 1810.70  5352.1 1811.90  5360.5 1813.94
#Mann=7,-1,0
  4683.8    0.07       0  4825.1     0.1       0  4901.0    0.07       0
  5010.4   0.035       0  5021.3    0.05       0  5025.3   0.035       0
  5153.7     0.1       0
Bank Sta=5021.3,5025.3
Exp/Cntr=0.3,0.1

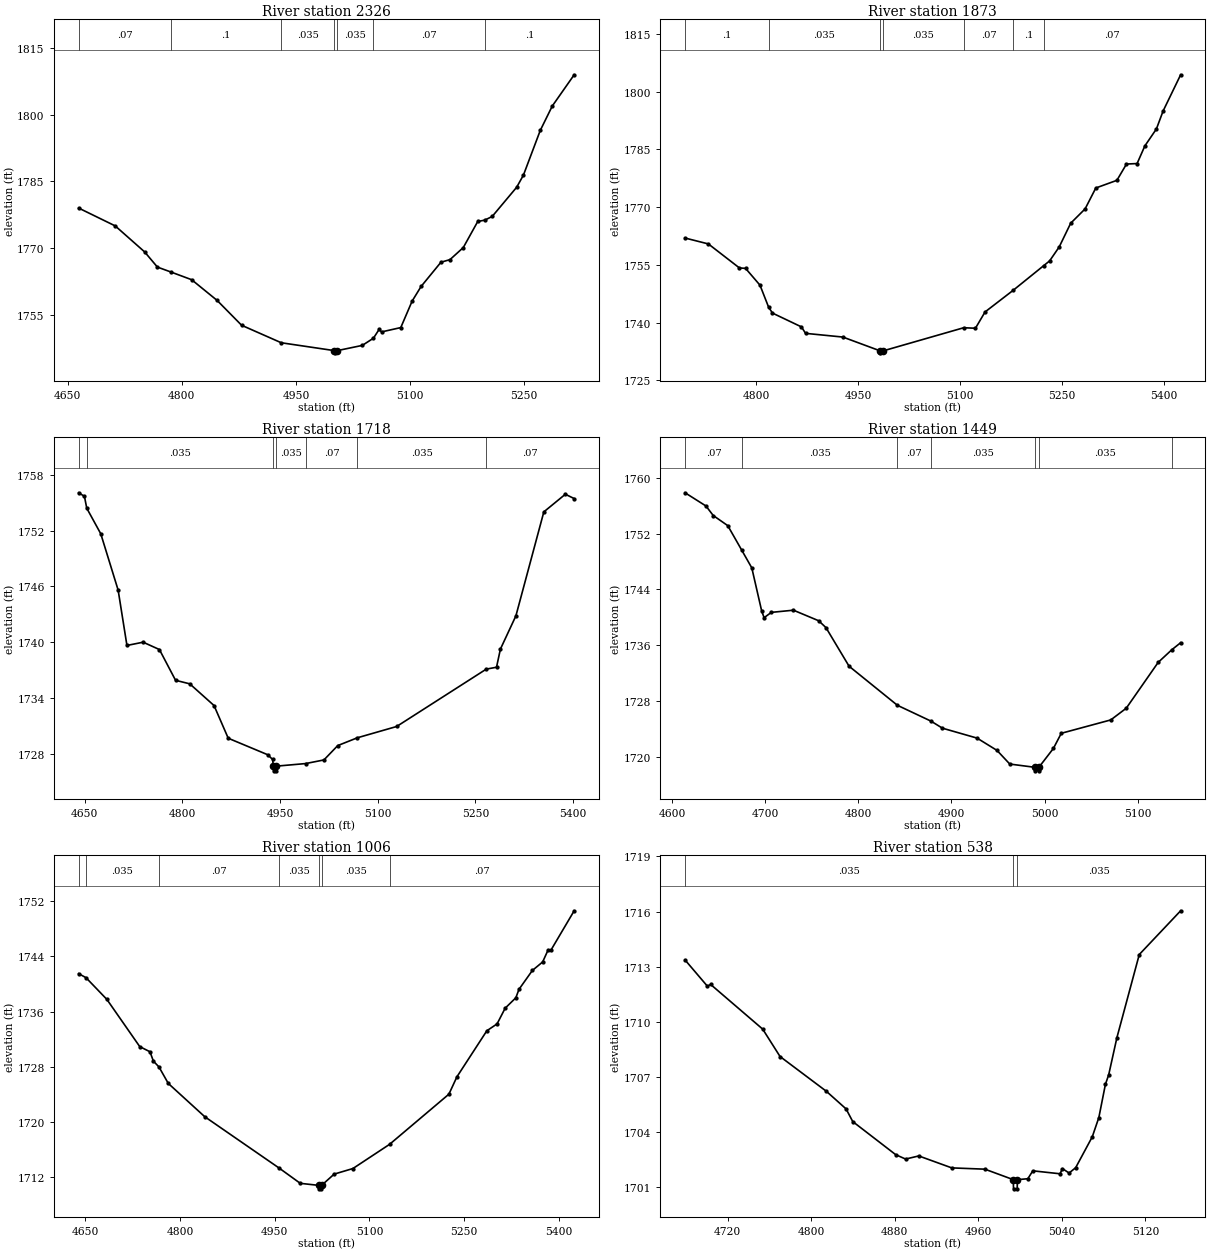
Type RM Length L Ch R = 1,2326,453,453,453
BEGIN DESCRIPTION:
Stream0621 5.0
END DESCRIPTION:
XS GIS Cut Line= 3
      1958625.00     13866424.99      1958475.00     13866125.00
      1958375.01     13865825.03
#Sta/Elev= 30
  4664.3 1779.04  4712.4 1775.03  4751.1 1769.19  4767.9 1765.78  4785.8 1764.67
  4812.9 1762.95  4846.4 1758.30  4878.6 1752.72  4930.8 1748.79  5000.5 1747.03
  5000.8 1746.53  5004.5 1747.03  5037.3 1748.20  5051.9 1749.81  5059.4 1751.78
  5062.6 1751.23  5087.9 1752.20  5102.8 1758.14  5114.6 1761.43  5140.7 1766.87
  5152.6 1767.46  5170.1 1770.17  5189.1 1776.02  5198.2 1776.32  5208.1 1777.15
  5240.3 1783.71  5249.2 1786.44  5271.3 1796.46  5287.1 1801.94  5315.9 1808.96
#Mann=7,-1,0
  4664.3    0.07       0  4785.8     0.1       0  4930.8   0.035       0
  5000.5   0.035       0  5004.5   0.035       0  5051.9    0.07       0
  5198.2     0.1       0
Bank Sta=5000.5,5004.5
Exp/Cntr=0.3,0.1

Type RM Length L Ch R = 1,1873,155,155,155
BEGIN DESCRIPTION:
Stream0621 4.0
END DESCRIPTION:
XS GIS Cut Line= 3
      1958825.00     13866275.01      1958875.00     13865975.00
      1958575.01     13865675.01
#Sta/Elev= 30
  4695.8 1761.99  4730.0 1760.46  4775.6 1754.23  4784.7 1754.11  4805.9 1749.74
  4818.5 1744.06  4824.2 1742.50  4866.8 1738.91  4872.9 1737.23  4927.7 1736.27
  4982.7 1732.67  4983.0 1732.17  4986.7 1732.67  5105.3 1738.69  5122.6 1738.56
  5136.7 1742.79  5178.3 1748.45  5222.8 1754.80  5231.6 1756.05  5245.7 1759.68
  5262.6 1765.84  5283.8 1769.57  5299.5 1774.99  5330.5 1776.98  5344.6 1781.21
  5360.2 1781.34  5371.6 1785.92  5388.6 1790.33  5398.4 1794.98  5424.2 1804.40
#Mann=7,-1,0
  4695.8     0.1       0  4818.5   0.035       0  4982.7   0.035       0
  4986.7   0.035       0  5105.3    0.07       0  5178.3     0.1       0
  5222.8    0.07       0
Bank Sta=4982.7,4986.7
Exp/Cntr=0.3,0.1

Type RM Length L Ch R = 1,1718,269,269,269
BEGIN DESCRIPTION:
Mapping XS c73b3098
END DESCRIPTION:
XS GIS Cut Line= 3
      1958924.20     13866273.89      1959000.28     13865996.90
      1959069.71     13865528.07
#Sta/Elev= 30
  4640.6 1756.06  4649.5 1755.68  4653.1 1754.40  4674.6 1751.66  4701.3 1745.61
  4714.8 1739.67  4739.7 1740.02  4764.7 1739.23  4789.5 1735.93  4811.3 1735.55
  4848.6 1733.22  4870.4 1729.71  4931.0 1727.94  4938.6 1727.43  4939.7 1726.71
  4940.0 1726.21  4943.5 1726.21  4943.7 1726.71  4989.2 1726.99  5017.4 1727.38
  5038.6 1728.92  5068.8 1729.76  5129.1 1730.97  5266.8 1737.13  5282.5 1737.33
  5288.5 1739.28  5312.3 1742.85  5355.2 1754.01  5388.2 1755.90  5401.8 1755.44
#Mann=7,-1,0
  4640.6    0.07       0  4653.1   0.035       0  4939.7    0.05       0
  4943.7   0.035       0  4989.2    0.07       0  5068.8   0.035       0
  5266.8    0.07       0
Bank Sta=4939.7,4943.7
Exp/Cntr=0.3,0.1

Type RM Length L Ch R = 1,1449,443,443,443
BEGIN DESCRIPTION:
Stream0621 3.0
END DESCRIPTION:
XS GIS Cut Line= 3
      1958925.03     13866324.98      1959225.00     13866075.00
      1959325.00     13865975.00
#Sta/Elev= 30
  4614.1 1757.83  4636.5 1755.94  4644.3 1754.58  4659.9 1753.13  4675.0 1749.60
  4685.7 1747.09  4696.3 1740.93  4698.9 1739.97  4706.7 1740.73  4730.4 1741.04
  4757.5 1739.53  4765.3 1738.55  4790.1 1733.03  4842.0 1727.44  4878.0 1725.18
  4890.3 1724.17  4927.5 1722.75  4948.9 1720.99  4962.6 1719.04  4989.8 1718.57
  4990.1 1718.07  4993.6 1718.07  4993.8 1718.57  5009.4 1721.27  5017.9 1723.44
  5071.0 1725.35  5087.6 1727.02  5121.9 1733.58  5136.4 1735.37  5146.0 1736.39
#Mann=7,-1,0
  4614.1    0.07       0  4675.0   0.035       0  4842.0    0.07       0
  4878.0   0.035       0  4989.8   0.035       0  4993.8   0.035       0
  5136.4    0.07       0
Bank Sta=4989.8,4993.8
Exp/Cntr=0.3,0.1

Type RM Length L Ch R = 1,1006,468,468,468
BEGIN DESCRIPTION:
Stream0621 2.0
END DESCRIPTION:
XS GIS Cut Line= 3
      1959175.01     13866624.99      1959475.00     13866425.00
      1959775.00     13866125.00
#Sta/Elev= 30
  4639.5 1741.51  4651.2 1740.92  4684.2 1737.77  4736.3 1730.91  4752.5 1730.16
  4757.9 1728.80  4766.7 1727.96  4781.5 1725.56  4839.2 1720.73  4957.0 1713.27
  4990.5 1711.05  5020.2 1710.75  5020.5 1710.25  5024.0 1710.25  5024.2 1710.75
  5044.2 1712.39  5073.9 1713.20  5131.9 1716.71  5225.9 1724.00  5238.6 1726.52
  5286.0 1733.21  5302.2 1734.21  5315.0 1736.49  5331.9 1738.00  5336.9 1739.23
  5358.1 1741.97  5374.4 1743.21  5382.9 1744.93  5387.5 1744.92  5424.3 1750.64
#Mann=7,-1,0
  4639.5    0.07       0  4651.2   0.035       0  4766.7    0.07       0
  4957.0   0.035       0  5020.2   0.035       0  5024.2   0.035       0
  5131.9    0.07       0
Bank Sta=5020.2,5024.2
Exp/Cntr=0.3,0.1

Type RM Length L Ch R = 1,538,132,132,132
BEGIN DESCRIPTION:
Stream0621 1.0
END DESCRIPTION:
XS GIS Cut Line= 3
      1959524.96     13866825.01      1959825.00     13866725.00
      1959875.01     13866574.98
#Sta/Elev= 30
  4679.4 1713.36  4700.7 1711.94  4703.9 1712.03  4753.7 1709.60  4770.3 1708.11
  4814.6 1706.22  4833.5 1705.26  4839.9 1704.57  4881.0 1702.77  4890.5 1702.53
  4903.1 1702.70  4934.7 1702.05  4966.4 1701.98  4993.6 1701.41  4993.8 1700.91
  4997.3 1700.91  4997.6 1701.41  5007.5 1701.46  5012.3 1701.89  5038.3 1701.73
  5040.7 1702.01  5047.0 1701.77  5053.3 1702.06  5069.2 1703.74  5075.5 1704.79
  5081.8 1706.60  5084.9 1707.11  5092.8 1709.14  5114.2 1713.66  5153.8 1716.04
#Mann=3,-1,0
  4679.4   0.035       0  4993.6   0.035       0  4997.6   0.035       0
Bank Sta=4993.6,4997.6
Exp/Cntr=0.3,0.1

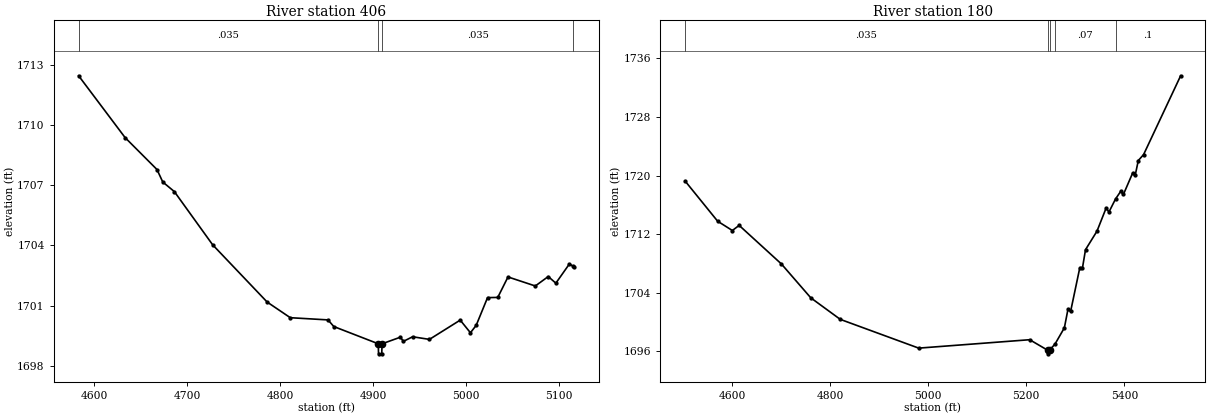
Type RM Length L Ch R = 1,406,226,226,226
BEGIN DESCRIPTION:
Stream0621 0.0
END DESCRIPTION:
XS GIS Cut Line= 3
      1959551.15     13866922.04      1959911.31     13866819.76
      1960002.94     13866690.19
#Sta/Elev= 30
  4583.0 1712.45  4633.0 1709.37  4667.3 1707.78  4673.5 1707.16  4686.0 1706.68
  4727.2 1704.03  4785.8 1701.18  4810.7 1700.40  4851.3 1700.29  4857.5 1699.96
  4905.4 1699.10  4905.6 1698.60  4909.1 1698.60  4909.4 1699.10  4929.2 1699.43
  4932.3 1699.22  4942.3 1699.45  4960.4 1699.32  4993.5 1700.28  5004.5 1699.65
  5010.7 1700.02  5022.9 1701.40  5033.9 1701.41  5044.9 1702.43  5074.3 1701.98
  5088.2 1702.45  5096.4 1702.12  5111.0 1703.08  5115.0 1702.96  5116.1 1702.93
#Mann=4,-1,0
  4583.0   0.035       0  4905.4   0.035       0  4909.4   0.035       0
  5115.0    0.07       0
Bank Sta=4905.4,4909.4
Exp/Cntr=0.3,0.1

Type RM Length L Ch R = 1,180,0,0,0
BEGIN DESCRIPTION:
Stream0621 T
END DESCRIPTION:
XS GIS Cut Line= 3
      1959428.69     13867004.53      1959962.55     13866982.39
      1960405.23     13866805.32
#Sta/Elev= 30
  4503.8 1719.25  4570.2 1713.76  4600.2 1712.49  4614.1 1713.19  4700.3 1707.92
  4760.3 1703.29  4820.4 1700.35  4980.5 1696.42  5206.9 1697.57  5243.4 1696.14
  5243.6 1695.64  5247.4 1696.14  5258.7 1696.99  5277.7 1699.20  5285.0 1701.73
  5290.4 1701.43  5309.2 1707.42  5314.6 1707.38  5320.8 1709.87  5344.2 1712.40
  5363.1 1715.60  5368.5 1715.00  5382.0 1716.79  5392.7 1717.85  5398.1 1717.41
  5416.9 1720.33  5422.3 1720.07  5428.5 1722.05  5439.3 1722.86  5514.9 1733.63
#Mann=5,-1,0
  4503.8   0.035       0  5243.4   0.035       0  5247.4   0.035       0
  5258.7    0.07       0  5382.0     0.1       0
Bank Sta=5243.4,5247.4
Exp/Cntr=0.3,0.1

Chan Stop Cuts=-1