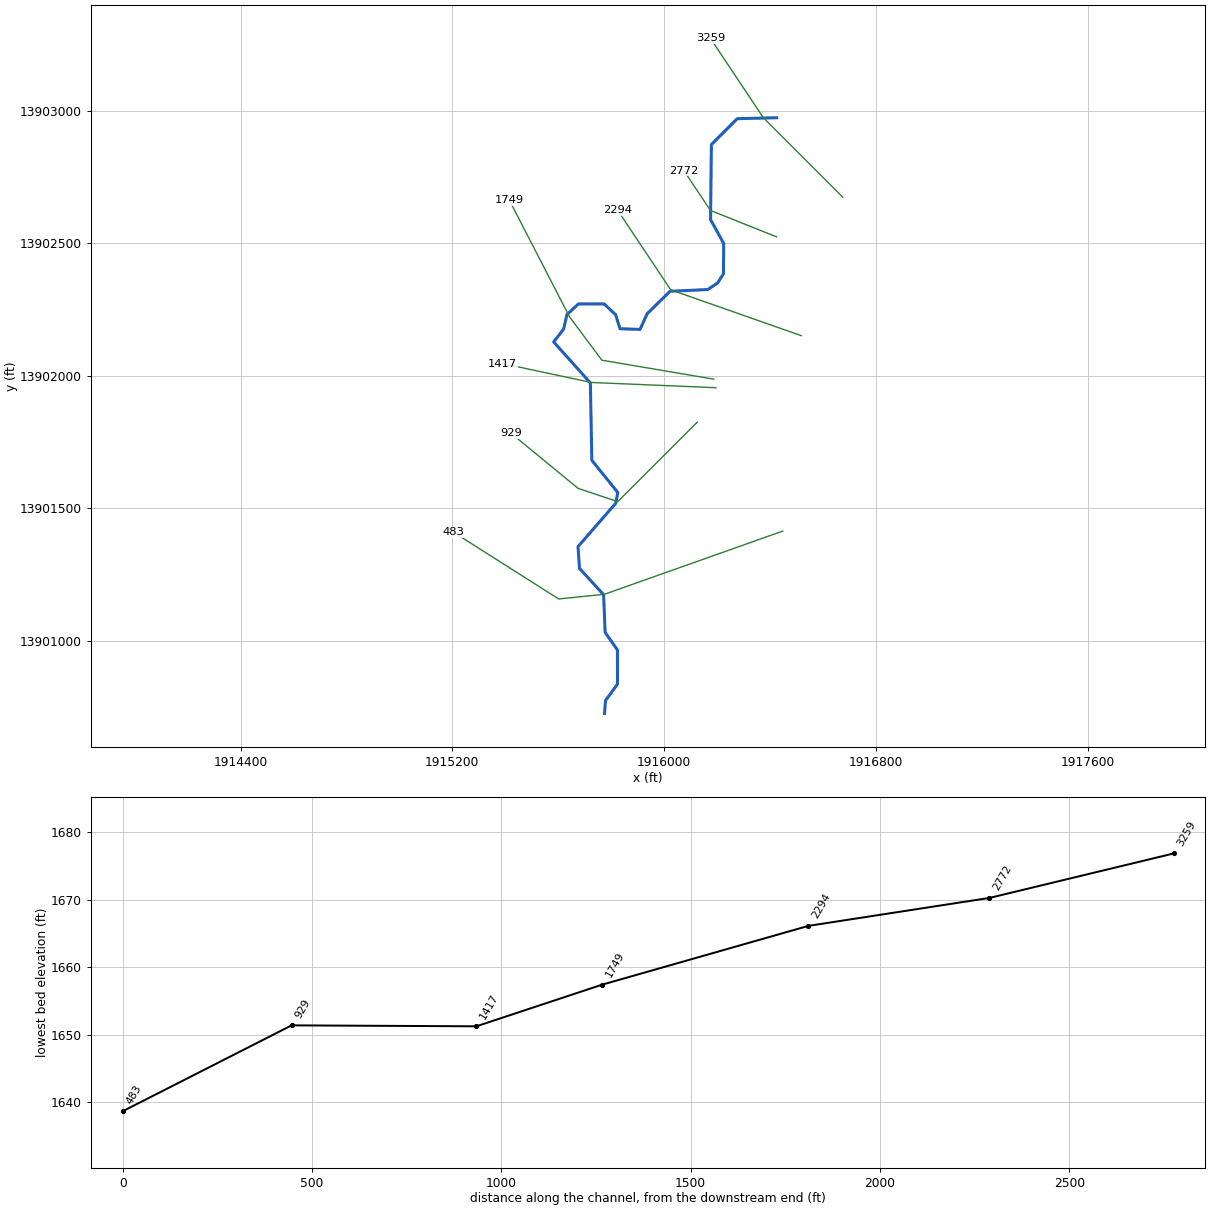
--- Stream0623.prj (project) ---

Proj Title=Stream0623 Base Level Engineering
Current Plan=p01
Default Exp/Contr=0.3,0.1
English Units
Geom File=g01
Flow File=f01
Plan File=p01
Y Axis Title=Elevation
X Axis Title(PF)=Main Channel Distance
X Axis Title(XS)=Station
BEGIN DESCRIPTION:
Stream0623
END DESCRIPTION:
DSS Export Rating Curves= 0
DSS Export Rating Curve Sorted= 0
DSS Export Volume Flow Curves= 0
DXF OffsetX= 0
DXF OffsetY= 0
DXF ScaleX= 1
DXF ScaleY= 10

--- Stream0623.p01 (plan) ---

Plan Title=Multiple Run
Short Identifier=Multiple
Geom File=g01
Flow File=f01
Subcritical Flow
K Sum by GR= 0
Std Step Tol= 0.01
Critical Tol= 0.01
Num of Std Step Trials= 20
Max Error Tol= 0.3
Flow Tol Ratio= 0.001
Split Flow NTrial= 30
Split Flow Tol= 0.02
Split Flow Ratio= 0.02
Log Output Level= 0
Friction Slope Method= 1
Unsteady Friction Slope Method= 2
Unsteady Bridges Friction Slope Method= 1
Parabolic Critical Depth
Global Vel Dist=  1 , 1 , 1
Global Log Level= 0
CheckData=True
Encroach Param= -1, 0, 0, 0
BEGIN DESCRIPTION:
Multiple Run
END DESCRIPTION:

--- Stream0623.f01 (steady flow) ---

Flow Title=Multiple
Program Version=4.10
Number of Profiles= 7
Profile Names=10-year,25-year,50-year,1pct_min,100-year,1pct_plu,500-year
River Rch & RM=Stream0623,Reach-1         ,3259
    1359    2347    3300    2243    4475    8929    8131
Boundary for River Rch & Prof#=Stream0623,Reach-1         , 1
Up Type= 0
Dn Type= 3
Dn Slope=0.008
Boundary for River Rch & Prof#=Stream0623,Reach-1         , 2
Up Type= 0
Dn Type= 3
Dn Slope=0.008
Boundary for River Rch & Prof#=Stream0623,Reach-1         , 3
Up Type= 0
Dn Type= 3
Dn Slope=0.008
Boundary for River Rch & Prof#=Stream0623,Reach-1         , 4
Up Type= 0
Dn Type= 3
Dn Slope=0.008
Boundary for River Rch & Prof#=Stream0623,Reach-1         , 5
Up Type= 0
Dn Type= 3
Dn Slope=0.008
Boundary for River Rch & Prof#=Stream0623,Reach-1         , 6
Up Type= 0
Dn Type= 3
Dn Slope=0.008
Boundary for River Rch & Prof#=Stream0623,Reach-1         , 7
Up Type= 0
Dn Type= 3
Dn Slope=0.008
DSS Import GetInterval= 0
DSS Import GetPeak= 0
DSS Import FillOption= 0

--- Stream0623.g01 (geometry) ---

Geom Title=Existing Conditions
Program Version=4.10

River Reach=Stream0623      ,Reach-1
Reach XY= 30
        1916425.       13902975.      1916276.44     13902971.51
      1916178.53     13902873.55      1916175.52     13902590.22
      1916225.23     13902500.07      1916224.04     13902385.27
      1916202.35     13902350.97      1916164.73     13902325.99
      1916022.54     13902319.54      1915935.89     13902234.39
      1915908.98     13902175.46      1915833.44     13902177.96
      1915816.84     13902231.03       1915773.7      13902271.6
      1915676.28     13902271.63      1915632.98     13902231.38
      1915620.52     13902176.68      1915582.83     13902128.23
      1915721.46     13901973.54      1915727.07     13901680.86
       1915825.1     13901559.64      1915817.54     13901518.95
      1915674.78     13901354.94      1915680.41     13901272.58
      1915771.44     13901173.53      1915777.27     13901030.94
      1915823.79     13900964.49       1915823.9     13900835.47
      1915778.65     13900773.49        1915775.       13900725.

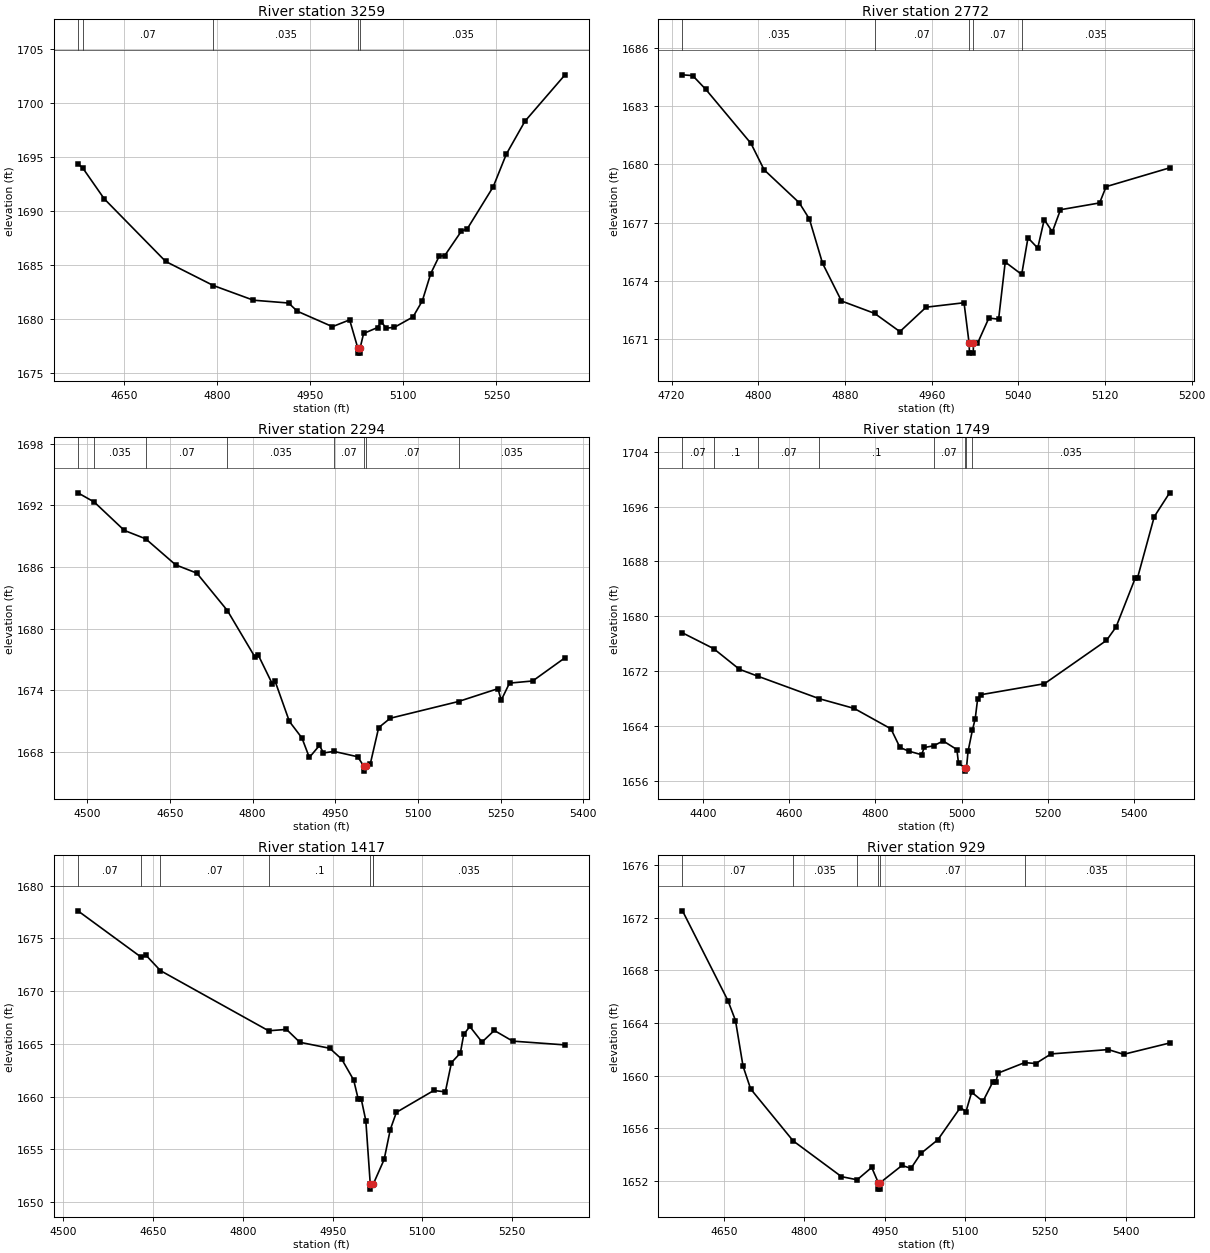
Type RM Length L Ch R = 1 ,3259    ,487,487,487
BEGIN DESCRIPTION:
Stream0623 7.0
END DESCRIPTION:
XS GIS Cut Line= 3
      1916674.99     13902675.01        1916375.       13902975.
        1916175.       13903275.
#Sta/Elev= 30
  4575.6 1694.38  4583.1 1694.03    4618 1691.15    4717 1685.35  4793.8 1683.12
  4858.4 1681.76    4915  1681.5  4929.1 1680.74  4985.7 1679.31  5013.4 1679.94
  5026.4 1677.36  5026.6 1676.86  5030.1 1676.86  5030.4 1677.36  5035.9 1678.68
  5058.4 1679.23  5064.4 1679.78    5072 1679.17  5085.5 1679.25  5115.5 1680.21
  5130.5  1681.7  5144.1 1684.23  5157.6 1685.83  5166.6 1685.89  5193.6 1688.17
  5202.7 1688.35  5244.7 1692.26  5265.8 1695.28  5295.8 1698.33  5360.4 1702.63
#Mann= 5 ,-1 , 0
  4575.6      .1       0  4583.1     .07       0  4793.8    .035       0
  5026.4    .035       0  5030.4    .035       0
Bank Sta=5026.4,5030.4
XS Rating Curve= 0 ,0
Exp/Cntr=0.3,0.1

Type RM Length L Ch R = 1 ,2772    ,478,478,478
BEGIN DESCRIPTION:
Stream0623 6.0
END DESCRIPTION:
XS GIS Cut Line= 3
      1916424.96     13902525.02        1916175.       13902625.
      1916074.99     13902775.01
#Sta/Elev= 30
  4730.1 1684.62  4739.5 1684.58  4751.6 1683.87  4793.3 1681.08  4805.4 1679.72
  4837.8 1678.02  4847.2 1677.18  4859.3  1674.9  4876.8 1672.95  4907.4 1672.31
  4930.7 1671.37  4954.9 1672.63  4989.9 1672.86  4994.6 1670.76  4994.9 1670.26
  4998.4 1670.26  4998.6 1670.76  5002.3 1670.76  5012.8 1672.07  5021.8 1672.01
  5027.9 1674.96  5043.1 1674.32  5048.9 1676.21  5057.9 1675.68  5063.9 1677.15
  5071.4 1676.52  5078.9 1677.66    5115 1678.01    5121 1678.85  5179.6 1679.82
#Mann= 5 ,-1 , 0
  4730.1    .035       0  4907.4     .07       0  4994.6     .05       0
  4998.6     .07       0  5043.1    .035       0
Bank Sta=4994.6,4998.6
XS Rating Curve= 0 ,0
Exp/Cntr=0.3,0.1

Type RM Length L Ch R = 1 ,2294    ,545,545,545
BEGIN DESCRIPTION:
Stream0623 5.0
END DESCRIPTION:
XS GIS Cut Line= 3
      1916518.49     13902151.76        1916025.       13902325.
      1915824.98     13902625.02
#Sta/Elev= 30
  4483.2 1693.22  4512.9 1692.32  4567.4 1689.56  4606.2 1688.74  4660.4 1686.21
  4698.9  1685.4  4754.3 1681.76  4804.8 1677.19  4810.1 1677.45  4835.8 1674.62
  4841.1 1674.85  4866.8 1670.96  4889.6 1669.35    4903 1667.45  4921.4 1668.62
  4928.7 1667.89  4947.8 1668.04  4990.7 1667.52  5001.6 1666.62  5001.8 1666.12
  5005.6 1666.62  5013.7 1666.85  5028.8 1670.36  5049.8 1671.27  5173.6  1672.9
  5245.1 1674.15  5251.1 1673.03  5266.1 1674.69  5308.2  1674.9  5366.8 1677.16
#Mann= 8 ,-1 , 0
  4483.2     .07       0  4512.9    .035       0  4606.2     .07       0
  4754.3    .035       0  4947.8     .07       0  5001.6     .05       0
  5005.6     .07       0  5173.6    .035       0
Bank Sta=5001.6,5005.6
XS Rating Curve= 0 ,0
Exp/Cntr=0.3,0.1

Type RM Length L Ch R = 1 ,1749    ,332,332,332
BEGIN DESCRIPTION:
Stream0623 4.0
END DESCRIPTION:
XS GIS Cut Line= 4
      1916187.72     13901987.59      1915764.79     13902059.19
      1915642.62     13902223.29      1915415.05      13902664.3
#Sta/Elev= 30
  4352.4 1677.58  4424.6 1675.28  4484.3 1672.27  4527.8 1671.24  4669.7 1667.97
  4750.7 1666.55  4835.9 1663.57  4856.8 1660.85  4877.6 1660.31  4906.8  1659.8
  4913.3 1660.85  4934.8 1661.09  4956.9 1661.81  4988.8 1660.55  4992.6 1658.54
  5007.1  1657.9  5007.3  1657.4  5011.1  1657.9  5014.7 1660.29  5024.7 1663.35
  5031.3 1665.04  5036.9 1667.93  5044.1 1668.55    5192 1670.16  5335.8 1676.48
    5358 1678.44  5402.3 1685.54  5407.9 1685.64  5446.6 1694.54  5482.2 1698.02
#Mann= 8 ,-1 , 0
  4352.4     .07       0  4424.6      .1       0  4527.8     .07       0
  4669.7      .1       0  4934.8     .07       0  5007.1     .05       0
  5011.1     .07       0  5024.7    .035       0
Bank Sta=5007.1,5011.1
XS Rating Curve= 0 ,0
Exp/Cntr=0.3,0.1

Type RM Length L Ch R = 1 ,1417    ,488,488,488
BEGIN DESCRIPTION:
Stream0623 3.0
END DESCRIPTION:
XS GIS Cut Line= 3
      1916195.53     13901955.29        1915725.       13901975.
      1915389.38     13902046.56
#Sta/Elev= 30
  4524.2 1677.61  4630.1 1673.21  4638.3 1673.38  4662.2 1671.94  4842.9 1666.24
  4872.8 1666.37  4895.1 1665.15  4945.1 1664.58  4965.1 1663.55  4985.1 1661.57
  4992.6 1659.78  4997.7 1659.78  5005.4 1657.72  5012.8 1651.73    5013 1651.23
  5016.8 1651.73    5018 1651.73    5036 1654.04  5046.3 1656.88  5056.5 1658.51
    5119 1660.58  5138.3 1660.45  5148.5 1663.22  5163.4 1664.13    5169 1665.89
  5179.2 1666.65  5199.6 1665.17  5220.1 1666.27  5250.8 1665.26  5338.3  1664.9
#Mann= 7 ,-1 , 0
  4524.2     .07       0  4630.1      .1       0  4662.2     .07       0
  4842.9      .1       0  5012.8     .05       0  5016.8      .1       0
    5018    .035       0
Bank Sta=5012.8,5016.8
XS Rating Curve= 0 ,0
Exp/Cntr=0.3,0.1

Type RM Length L Ch R = 1 ,929     ,446,446,446
BEGIN DESCRIPTION:
Stream0623 2.0
END DESCRIPTION:
XS GIS Cut Line= 4
        1916125.       13901825.        1915825.       13901525.
        1915675.       13901575.       1915421.8     13901783.07
#Sta/Elev= 30
  4572.2 1672.53    4657 1665.71  4671.2 1664.19  4685.3 1660.72  4699.5 1658.99
  4778.9 1655.04  4869.2 1652.32  4898.5 1652.08  4925.7 1653.02  4937.9 1651.87
  4938.1 1651.37  4941.6 1651.37  4941.9 1651.87  4982.3 1653.17  4999.1 1652.95
  5017.5 1654.08  5049.2 1655.12  5091.3 1657.57  5101.9 1657.27  5112.4 1658.74
  5133.5 1658.04  5151.9 1659.51  5157.8 1659.51  5161.7 1660.19  5211.5 1660.99
  5232.2 1660.92  5260.8 1661.65  5367.7 1661.98  5396.4 1661.62  5482.3 1662.48
#Mann= 6 ,-1 , 0
  4572.2     .07       0  4778.9    .035       0  4898.5     .07       0
  4937.9     .05       0  4941.9     .07       0  5211.5    .035       0
Bank Sta=4937.9,4941.9
XS Rating Curve= 0 ,0
Exp/Cntr=0.3,0.1

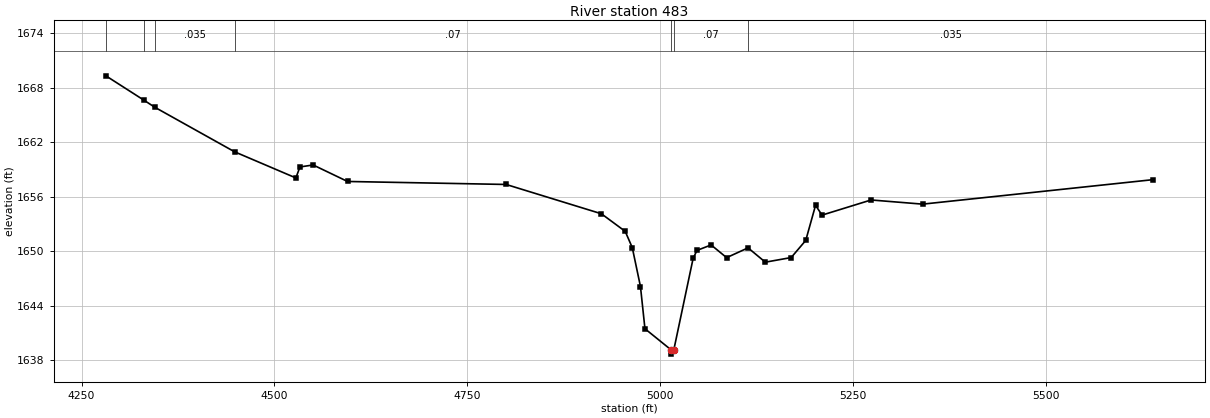
Type RM Length L Ch R = 1 ,483     ,0,0,0
BEGIN DESCRIPTION:
Stream0623 1.0
END DESCRIPTION:
XS GIS Cut Line= 4
      1916448.26     13901413.63        1915775.       13901175.
      1915601.72      13901157.2      1915205.57     13901408.64
#Sta/Elev= 30
  4281.6 1669.33  4330.8 1666.65  4345.1 1665.86  4448.5 1660.95  4527.9 1658.07
  4533.2 1659.28  4550.3  1659.5  4594.9 1657.68  4800.5 1657.35    4924 1654.12
  4954.9 1652.18  4964.1 1650.38  4974.7 1646.09  4980.5 1641.44    5014 1639.14
  5014.3 1638.64    5018 1639.14    5043 1649.21    5048 1650.08  5066.3 1650.68
  5086.4 1649.28  5114.2 1650.36  5136.6 1648.78  5170.1 1649.29    5189 1651.18
  5201.7 1655.05  5210.1 1653.97  5273.7 1655.64  5340.6 1655.18  5639.3 1657.88
#Mann= 7 ,-1 , 0
  4281.6     .07       0  4330.8      .1       0  4345.1    .035       0
  4448.5     .07       0    5014     .05       0    5018     .07       0
  5114.2    .035       0
Bank Sta=5014,5018
XS Rating Curve= 0 ,0
Exp/Cntr=0.3,0.1

Chan Stop Cuts=-1
Use User Specified Reach Order=0
Composite Channel Slope=5