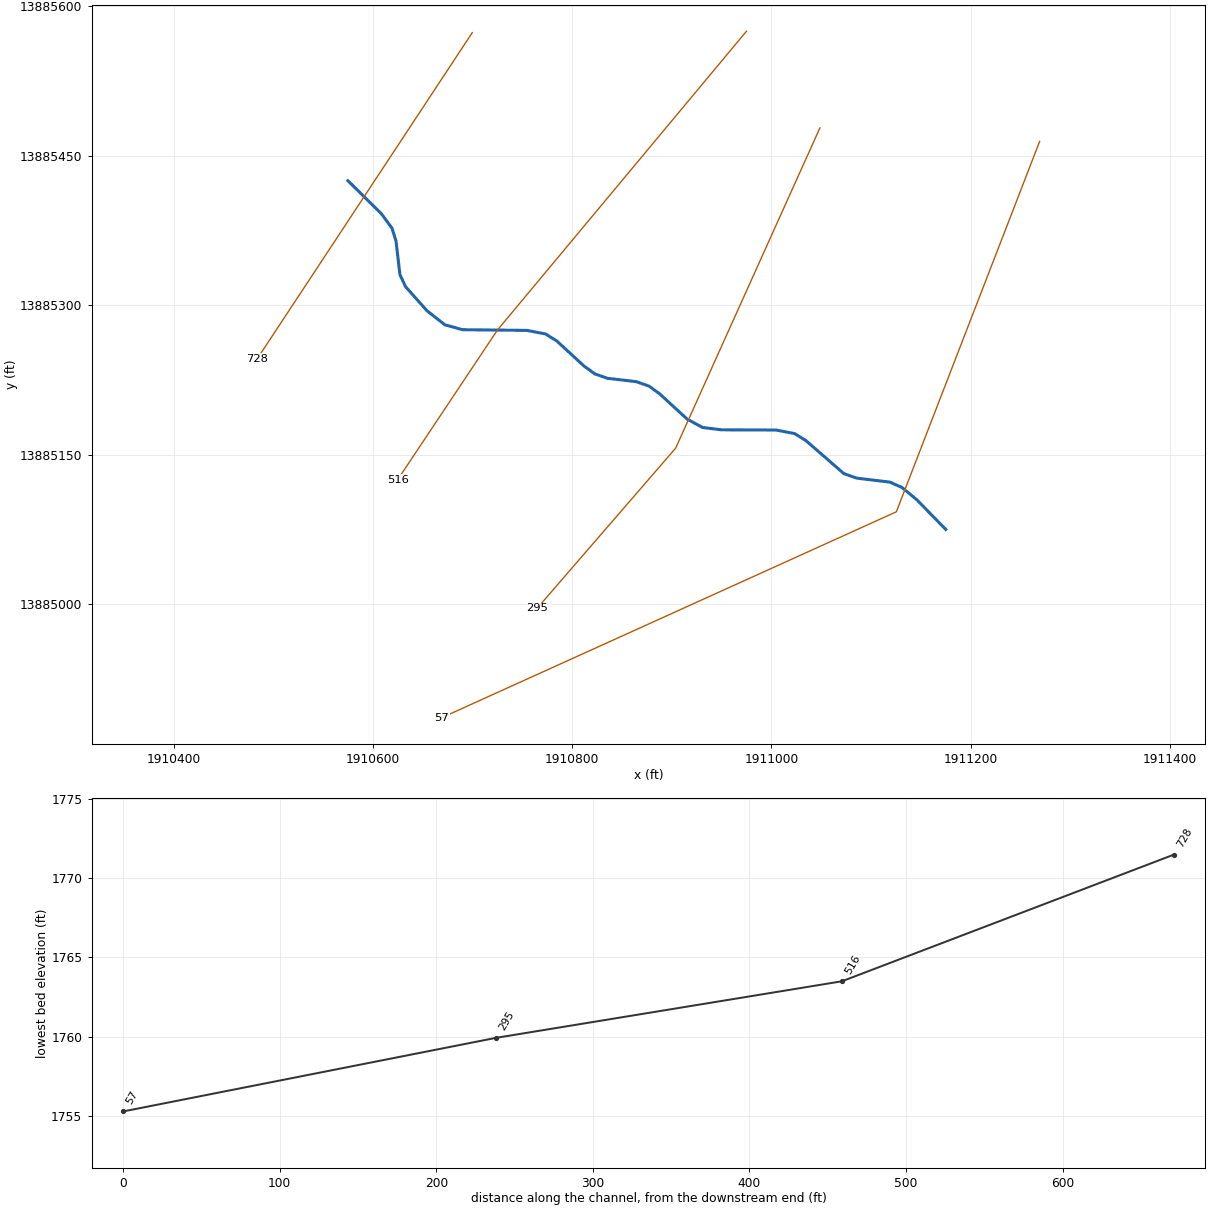
--- Stream0627.prj (project) ---

Proj Title=Stream0627 Base Level Engineering
Current Plan=p01
Default Exp/Contr=0.3,0.1
English Units
Geom File=g01
Flow File=f01
Plan File=p01
BEGIN DESCRIPTION:
Stream0627
END DESCRIPTION:

--- Stream0627.p01 (plan) ---

Plan Title=Multiple Run
Short Identifier=Multiple
Geom File=g01
Flow File=f01
Subcritical Flow
K Sum by GR= 0
Std Step Tol= 0.01
Critical Tol= 0.01
Num of Std Step Trials= 20
Max Error Tol= 0.3
Flow Tol Ratio= 0.001
Split Flow NTrial= 30
Split Flow Tol= 0.02
Split Flow Ratio= 0.02
Log Output Level= 0
Friction Slope Method= 1
Unsteady Friction Slope Method= 2
Unsteady Bridges Friction Slope Method= 1
Parabolic Critical Depth
Global Vel Dist=  1 , 1 , 1
Global Log Level= 0
CheckData=True
Encroach Param= -1, 0, 0, 0
BEGIN DESCRIPTION:
Multiple Run
END DESCRIPTION:

--- Stream0627.f01 (steady flow) ---

Flow Title=Multiple
Number of Profiles=7
Profile Names=10-year,25-year,50-year,1pct_min,100-year,1pct_plu,500-year
River Rch & RM= Stream0627,Reach-1,728
     907    1523    2103    1408    2809    5604    4936
Boundary for River Rch & Prof#=Stream0627,Reach-1,1
Up Type=0
Dn Type=3
Dn Slope=0.005
Boundary for River Rch & Prof#=Stream0627,Reach-1,2
Up Type=0
Dn Type=3
Dn Slope=0.005
Boundary for River Rch & Prof#=Stream0627,Reach-1,3
Up Type=0
Dn Type=3
Dn Slope=0.005
Boundary for River Rch & Prof#=Stream0627,Reach-1,4
Up Type=0
Dn Type=3
Dn Slope=0.005
Boundary for River Rch & Prof#=Stream0627,Reach-1,5
Up Type=0
Dn Type=3
Dn Slope=0.005
Boundary for River Rch & Prof#=Stream0627,Reach-1,6
Up Type=0
Dn Type=3
Dn Slope=0.005
Boundary for River Rch & Prof#=Stream0627,Reach-1,7
Up Type=0
Dn Type=3
Dn Slope=0.005

--- Stream0627.g01 (geometry) ---

Geom Title=Existing Conditions

River Reach=Stream0627,Reach-1
Reach XY= 30
      1910575.00     13885425.00      1910608.57     13885391.91
      1910619.28     13885377.32      1910623.32     13885364.25
      1910627.24     13885330.74      1910632.91     13885318.56
      1910654.44     13885294.44      1910672.32     13885280.41
      1910690.09     13885275.47      1910754.90     13885274.76
      1910773.41     13885271.17      1910784.65     13885264.16
      1910811.96     13885239.03      1910822.82     13885231.11
      1910835.69     13885226.67      1910864.31     13885223.33
      1910877.18     13885218.89      1910888.04     13885210.97
      1910915.35     13885185.84      1910930.97     13885177.33
      1910950.00     13885174.99      1911004.91     13885174.77
      1911023.42     13885171.18      1911034.66     13885164.18
      1911072.78     13885131.03      1911085.63     13885126.51
      1911118.96     13885122.49      1911131.15     13885117.09
      1911145.92     13885104.86      1911175.00     13885075.00

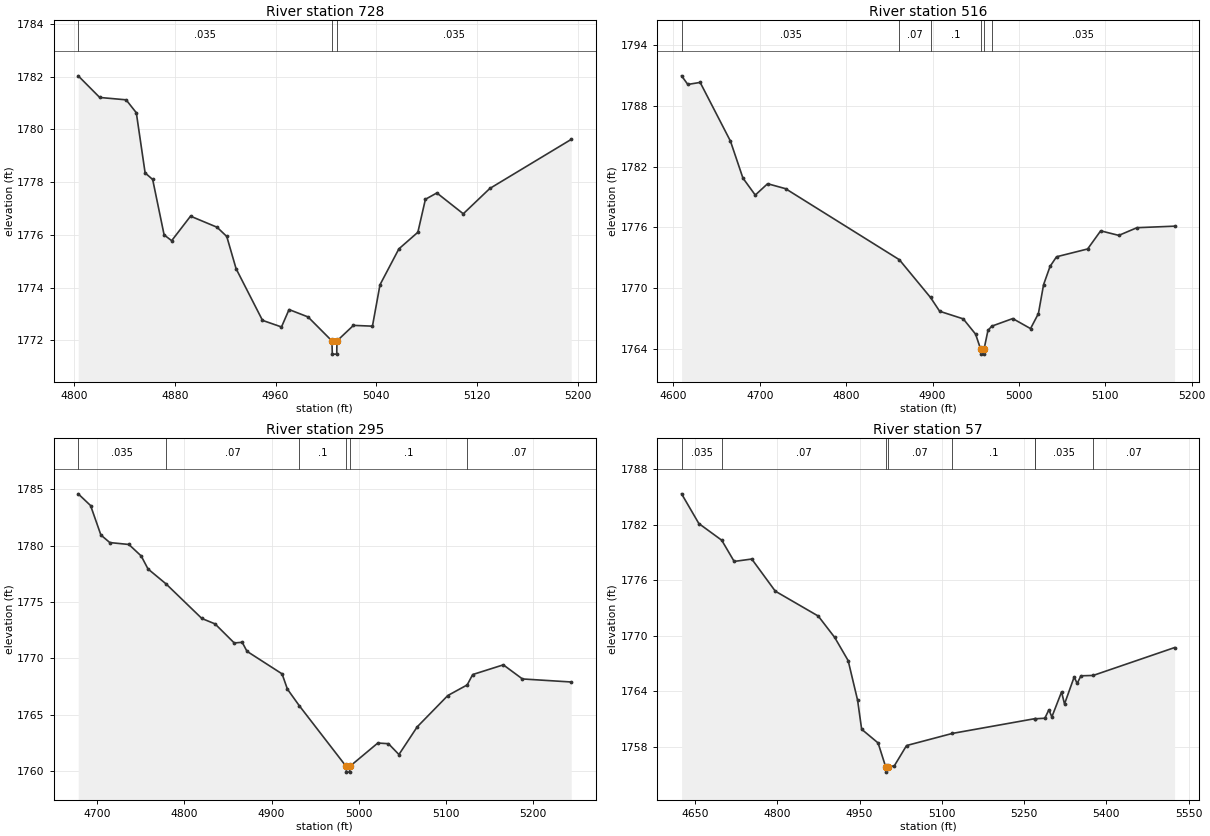
Type RM Length L Ch R = 1,728,212,212,212
BEGIN DESCRIPTION:
Stream0627 2.0
END DESCRIPTION:
XS GIS Cut Line= 2
      1910699.83     13885573.60      1910484.12     13885246.41
#Sta/Elev= 30
  4803.1 1782.03  4820.2 1781.21  4841.2 1781.12  4849.3 1780.63  4856.3 1778.35
  4862.3 1778.10  4871.4 1776.00  4877.4 1775.78  4892.4 1776.71  4913.5 1776.29
  4921.2 1775.94  4928.6 1774.72  4949.6 1772.76  4964.7 1772.51  4970.7 1773.17
  4985.8 1772.89  5004.8 1771.98  5005.1 1771.48  5008.6 1771.48  5008.8 1771.98
  5021.9 1772.57  5037.0 1772.54  5043.0 1774.11  5058.0 1775.47  5073.1 1776.10
  5079.1 1777.35  5088.2 1777.59  5109.2 1776.80  5130.3 1777.76  5195.0 1779.62
#Mann=3,-1,0
  4803.1   0.035       0  5004.8   0.035       0  5008.8   0.035       0
Bank Sta=5004.8,5008.8
Exp/Cntr=0.3,0.1

Type RM Length L Ch R = 1,516,221,221,221
BEGIN DESCRIPTION:
Stream0627 1.0
END DESCRIPTION:
XS GIS Cut Line= 3
      1910975.01     13885575.01      1910725.00     13885275.00
      1910625.00     13885125.00
#Sta/Elev= 30
  4609.4 1790.96  4616.6 1790.11  4630.9 1790.31  4666.0 1784.51  4680.4 1780.87
  4694.7 1779.19  4709.0 1780.31  4729.8 1779.82  4861.5 1772.81  4897.6 1769.08
  4908.2 1767.72  4935.5 1766.97  4949.8 1765.46  4955.6 1763.99  4955.9 1763.49
  4959.4 1763.49  4959.6 1763.99  4964.1 1765.83  4968.5 1766.25  4992.8 1767.00
  5013.4 1766.01  5022.5 1767.49  5028.5 1770.35  5036.0 1772.15  5043.5 1773.10
  5079.5 1773.87  5094.6 1775.66  5115.6 1775.21  5136.6 1775.97  5180.2 1776.12
#Mann=6,-1,0
  4609.4   0.035       0  4861.5    0.07       0  4897.6     0.1       0
  4955.6   0.035       0  4959.6     0.1       0  4968.5   0.035       0
Bank Sta=4955.6,4959.6
Exp/Cntr=0.3,0.1

Type RM Length L Ch R = 1,295,238,238,238
BEGIN DESCRIPTION:
Stream0627 0.0
END DESCRIPTION:
XS GIS Cut Line= 3
      1911048.71     13885477.98      1910903.96     13885156.62
      1910764.99     13884995.94
#Sta/Elev= 30
  4678.5 1784.59  4692.7 1783.55  4704.5 1780.94  4714.7 1780.27  4736.6 1780.10
  4750.7 1779.08  4758.5 1777.93  4779.1 1776.61  4820.2 1773.54  4835.3 1773.06
  4857.3 1771.37  4866.4 1771.43  4871.9 1770.63  4912.1 1768.63  4918.2 1767.28
  4931.7 1765.82  4985.6 1760.42  4985.9 1759.92  4989.4 1759.92  4989.6 1760.42
  5021.8 1762.50  5034.0 1762.44  5046.0 1761.48  5066.9 1763.93  5102.0 1766.71
  5124.2 1767.65  5130.5 1768.57  5165.6 1769.43  5187.5 1768.18  5243.4 1767.91
#Mann=6,-1,0
  4678.5   0.035       0  4779.1    0.07       0  4931.7     0.1       0
  4985.6    0.05       0  4989.6     0.1       0  5124.2    0.07       0
Bank Sta=4985.6,4989.6
Exp/Cntr=0.3,0.1

Type RM Length L Ch R = 1,57,0,0,0
BEGIN DESCRIPTION:
Stream0627 0.1
END DESCRIPTION:
XS GIS Cut Line= 3
      1911269.22     13885464.41      1911125.43     13885092.71
      1910669.36     13884886.16
#Sta/Elev= 30
  4625.4 1785.33  4656.9 1782.12  4698.6 1780.32  4721.3 1778.03  4753.4 1778.29
  4796.3 1774.82  4874.7 1772.13  4904.7 1769.82  4929.2 1767.32  4946.4 1763.05
  4953.8 1759.91  4983.8 1758.43  4998.0 1755.78  4998.3 1755.28  5002.0 1755.78
  5013.7 1755.99  5035.7 1758.15  5119.3 1759.46  5269.5 1761.05  5270.4 1761.04
  5287.9 1761.10  5295.3 1762.01  5300.7 1761.24  5318.4 1763.94  5323.8 1762.64
  5341.4 1765.55  5346.9 1764.85  5353.7 1765.68  5376.1 1765.72  5524.6 1768.73
#Mann=8,-1,0
  4625.4   0.035       0  4698.6    0.07       0  4998.0    0.05       0
  5002.0    0.07       0  5119.3     0.1       0  5269.5    0.07       0
  5270.4   0.035       0  5376.1    0.07       0
Bank Sta=4998,5002
Exp/Cntr=0.3,0.1

Chan Stop Cuts=-1