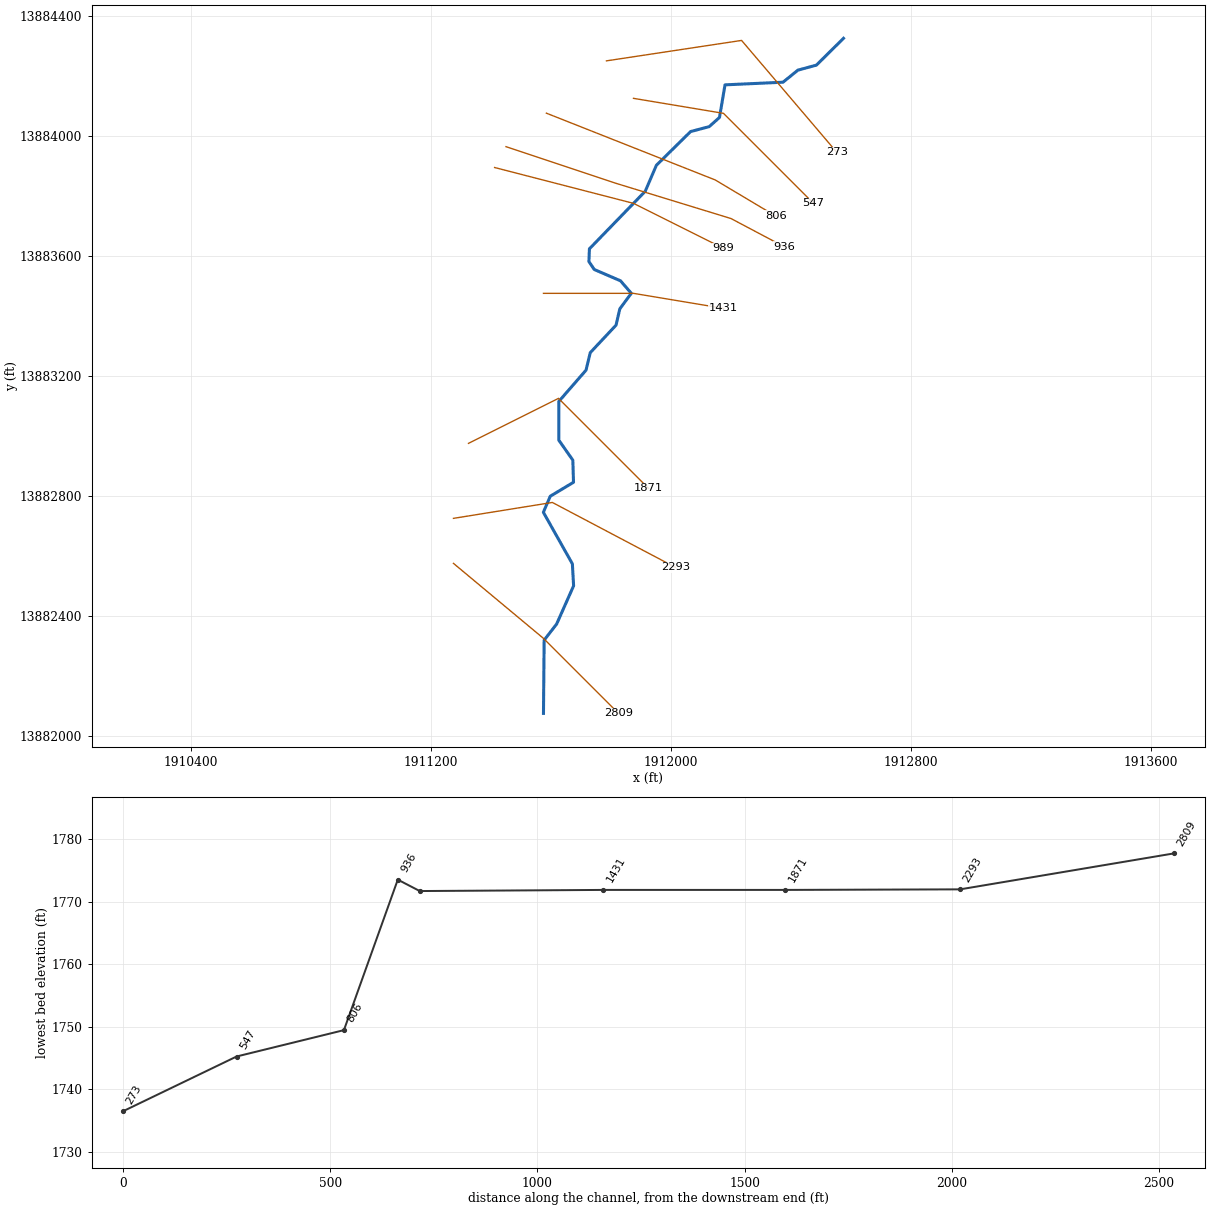
--- Stream0628.prj (project) ---

Proj Title=Stream0628 Base Level Engineering
Current Plan=p01
Default Exp/Contr=0.3,0.1
English Units
Geom File=g01
Flow File=f01
Plan File=p01
BEGIN DESCRIPTION:
Stream0628
END DESCRIPTION:

--- Stream0628.p01 (plan) ---

Plan Title=Multiple Run
Short Identifier=Multiple
Geom File=g01
Flow File=f01
Subcritical Flow
K Sum by GR= 0
Std Step Tol= 0.01
Critical Tol= 0.01
Num of Std Step Trials= 20
Max Error Tol= 0.3
Flow Tol Ratio= 0.001
Split Flow NTrial= 30
Split Flow Tol= 0.02
Split Flow Ratio= 0.02
Log Output Level= 0
Friction Slope Method= 1
Unsteady Friction Slope Method= 2
Unsteady Bridges Friction Slope Method= 1
Parabolic Critical Depth
Global Vel Dist=  1 , 1 , 1
Global Log Level= 0
CheckData=True
Encroach Param= -1, 0, 0, 0
BEGIN DESCRIPTION:
Multiple Run
END DESCRIPTION:

--- Stream0628.f01 (steady flow) ---

Flow Title=Multiple
Number of Profiles=7
Profile Names=10-year,25-year,50-year,1pct_min,100-year,1pct_plu,500-year
River Rch & RM= Stream0628,Reach-1,2809
    1354    2330    3271    2223    4435    8849    8042
Boundary for River Rch & Prof#=Stream0628,Reach-1,1
Up Type=0
Dn Type=3
Dn Slope=0.005
Boundary for River Rch & Prof#=Stream0628,Reach-1,2
Up Type=0
Dn Type=3
Dn Slope=0.005
Boundary for River Rch & Prof#=Stream0628,Reach-1,3
Up Type=0
Dn Type=3
Dn Slope=0.005
Boundary for River Rch & Prof#=Stream0628,Reach-1,4
Up Type=0
Dn Type=3
Dn Slope=0.005
Boundary for River Rch & Prof#=Stream0628,Reach-1,5
Up Type=0
Dn Type=3
Dn Slope=0.005
Boundary for River Rch & Prof#=Stream0628,Reach-1,6
Up Type=0
Dn Type=3
Dn Slope=0.005
Boundary for River Rch & Prof#=Stream0628,Reach-1,7
Up Type=0
Dn Type=3
Dn Slope=0.005

--- Stream0628.g01 (geometry) ---

Geom Title=Existing Conditions

River Reach=Stream0628,Reach-1
Reach XY= 30
      1911575.00     13882075.00      1911577.24     13882319.07
      1911618.88     13882372.82      1911675.41     13882500.00
      1911671.33     13882573.42      1911574.61     13882745.27
      1911597.69     13882798.78      1911675.11     13882845.27
      1911672.87     13882918.94      1911626.21     13882985.51
      1911626.04     13883114.56      1911716.82     13883218.96
      1911730.87     13883277.28      1911816.86     13883368.96
      1911829.47     13883423.36      1911867.80     13883475.30
      1911831.67     13883516.84      1911744.27     13883554.53
      1911726.50     13883580.87      1911728.08     13883623.32
      1911914.22     13883815.32      1911951.30     13883901.82
      1912065.34     13884014.21      1912127.57     13884030.74
      1912161.73     13884061.38      1912180.08     13884169.96
      1912373.45     13884178.75      1912422.83     13884218.87
      1912484.71     13884235.70      1912575.00     13884325.00

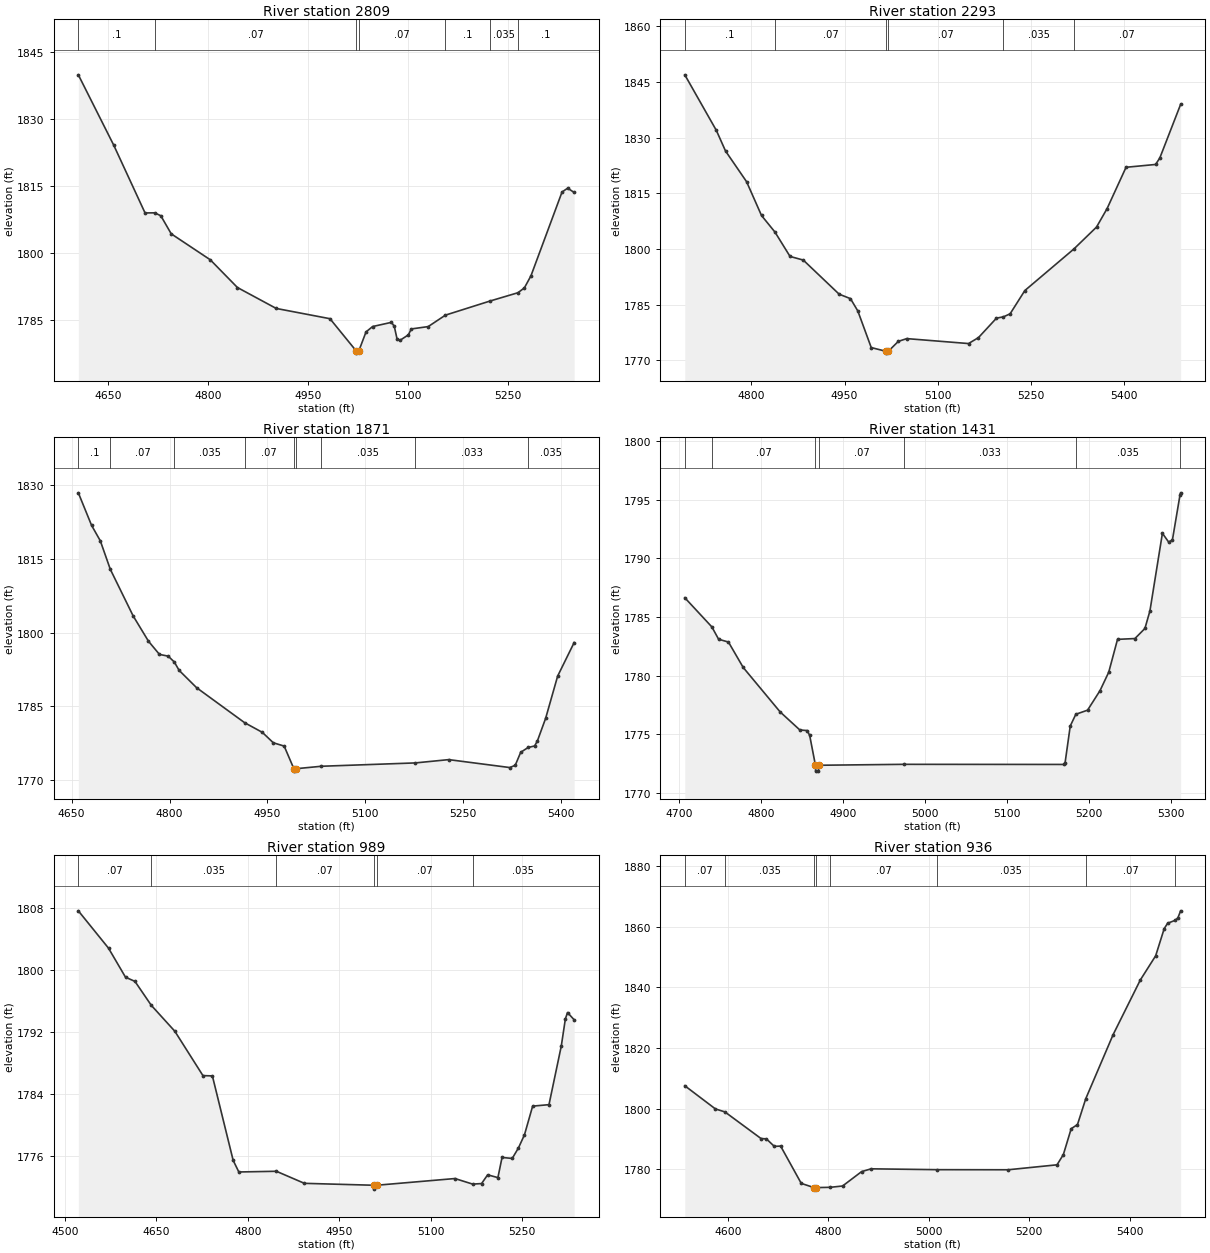
Type RM Length L Ch R = 1,2809,516,516,516
BEGIN DESCRIPTION:
Stream0628 6.0
END DESCRIPTION:
XS GIS Cut Line= 3
      1911275.01     13882574.99      1911575.00     13882325.00
      1911824.97     13882075.03
#Sta/Elev= 30
  4605.0 1839.85  4658.3 1824.08  4705.1 1809.00  4719.7 1809.02  4728.8 1808.36
  4744.4 1804.33  4803.0 1798.53  4843.7 1792.34  4902.0 1787.66  4982.6 1785.37
  5021.9 1778.18  5022.2 1777.68  5025.9 1778.18  5036.7 1782.42  5046.6 1783.62
  5074.9 1784.56  5079.1 1783.67  5083.3 1780.81  5087.6 1780.53  5100.3 1781.77
  5104.6 1783.08  5130.0 1783.61  5155.9 1786.17  5222.8 1789.32  5264.6 1791.17
  5274.3 1792.25  5284.2 1794.96  5330.8 1813.67  5339.3 1814.53  5349.0 1813.57
#Mann=7,-1,0
  4605.0     0.1       0  4719.7    0.07       0  5021.9    0.05       0
  5025.9    0.07       0  5155.9     0.1       0  5222.8   0.035       0
  5264.6     0.1       0
Bank Sta=5021.9,5025.9
Exp/Cntr=0.3,0.1

Type RM Length L Ch R = 1,2293,422,422,422
BEGIN DESCRIPTION:
Stream0628 5.0
END DESCRIPTION:
XS GIS Cut Line= 3
      1911274.99     13882725.00      1911604.58     13882778.05
      1912014.76     13882561.65
#Sta/Elev= 30
  4692.9 1846.92  4743.7 1831.93  4758.4 1826.40  4792.3 1818.12  4816.3 1809.02
  4838.0 1804.54  4862.2 1797.99  4883.5 1797.01  4941.2 1787.82  4959.4 1786.62
  4971.2 1783.31  4992.8 1773.44  5016.3 1772.44  5016.6 1771.94  5020.3 1772.44
  5036.4 1775.11  5050.0 1775.85  5149.3 1774.52  5165.3 1776.12  5194.3 1781.37
  5205.4 1781.71  5216.2 1782.53  5239.9 1788.80  5318.8 1800.00  5355.2 1805.90
  5372.2 1810.88  5402.7 1822.01  5450.2 1822.77  5457.0 1824.51  5490.5 1838.96
#Mann=6,-1,0
  4692.9     0.1       0  4838.0    0.07       0  5016.3    0.05       0
  5020.3    0.07       0  5205.4   0.035       0  5318.8    0.07       0
Bank Sta=5016.3,5020.3
Exp/Cntr=0.3,0.1

Type RM Length L Ch R = 1,1871,440,440,440
BEGIN DESCRIPTION:
Stream0628 4.0
END DESCRIPTION:
XS GIS Cut Line= 3
      1911324.98     13882974.99      1911625.00     13883125.00
      1911925.00     13882825.00
#Sta/Elev= 30
  4660.3 1828.46  4680.6 1821.84  4694.0 1818.69  4709.3 1812.90  4744.3 1803.42
  4767.8 1798.27  4784.6 1795.59  4798.0 1795.24  4807.4 1794.04  4814.7 1792.35
  4841.6 1788.81  4915.1 1781.70  4942.2 1779.74  4959.0 1777.62  4975.7 1776.94
  4990.5 1772.35  4990.8 1771.85  4994.5 1772.35  5032.7 1772.84  5176.7 1773.52
  5227.8 1774.19  5321.2 1772.58  5329.7 1773.03  5338.1 1775.68  5349.5 1776.66
  5359.4 1776.97  5363.6 1777.97  5376.3 1782.59  5394.7 1791.18  5420.0 1798.01
#Mann=9,-1,0
  4660.3     0.1       0  4709.3    0.07       0  4807.4   0.035       0
  4915.1    0.07       0  4990.5    0.05       0  4994.5    0.07       0
  5032.7   0.035       0  5176.7   0.033       0  5349.5   0.035       0
Bank Sta=4990.5,4994.5
Exp/Cntr=0.3,0.1

Type RM Length L Ch R = 1,1431,442,442,442
BEGIN DESCRIPTION:
Stream0628 3.0
END DESCRIPTION:
XS GIS Cut Line= 3
      1911574.95     13883475.00      1911875.00     13883475.00
      1912175.01     13883425.00
#Sta/Elev= 30
  4707.2 1786.64  4740.2 1784.15  4748.4 1783.10  4760.4 1782.86  4778.4 1780.69
  4823.4 1776.90  4847.4 1775.36  4856.4 1775.31  4859.4 1774.89  4866.4 1772.35
  4866.6 1771.85  4870.1 1771.85  4870.4 1772.35  4974.2 1772.43  5169.1 1772.42
  5170.6 1772.56  5176.9 1775.70  5183.7 1776.70  5198.0 1777.05  5213.2 1778.72
  5223.8 1780.29  5234.5 1783.09  5255.7 1783.16  5267.9 1784.02  5274.0 1785.52
  5289.2 1792.14  5296.8 1791.39  5301.4 1791.57  5310.6 1795.39  5311.4 1795.59
#Mann=7,-1,0
  4707.2   0.035       0  4740.2    0.07       0  4866.4   0.033       0
  4870.4    0.07       0  4974.2   0.033       0  5183.7   0.035       0
  5310.6    0.07       0
Bank Sta=4866.4,4870.4
Exp/Cntr=0.3,0.1

Type RM Length L Ch R = 1,989,53,53,53
BEGIN DESCRIPTION:
Stream0628 2.0
END DESCRIPTION:
XS GIS Cut Line= 3
      1911412.20     13883894.43      1911875.00     13883775.00
      1912175.03     13883624.99
#Sta/Elev= 30
  4521.8 1807.68  4571.3 1802.85  4599.2 1799.09  4614.7 1798.55  4641.5 1795.45
  4680.1 1792.10  4726.2 1786.36  4741.7 1786.32  4775.8 1775.39  4785.1 1773.89
  4846.7 1773.98  4892.6 1772.42  5007.0 1772.17  5007.2 1771.67  5011.0 1772.17
  5139.6 1773.04  5168.7 1772.32  5183.3 1772.39  5193.3 1773.52  5210.1 1773.16
  5216.9 1775.77  5233.6 1775.64  5243.8 1777.00  5253.7 1778.70  5267.1 1782.41
  5293.9 1782.60  5314.1 1790.19  5320.8 1793.70  5324.3 1794.52  5335.2 1793.58
#Mann=6,-1,0
  4521.8    0.07       0  4641.5   0.035       0  4846.7    0.07       0
  5007.0    0.05       0  5011.0    0.07       0  5168.7   0.035       0
Bank Sta=5007,5011
Exp/Cntr=0.3,0.1

Type RM Length L Ch R = 1,936,130,130,130
BEGIN DESCRIPTION:
Stream0628 1.1
END DESCRIPTION:
XS GIS Cut Line= 4
      1911450.00     13883963.95      1911814.56     13883842.43
      1912199.98     13883724.37      1912377.02     13883630.65
#Sta/Elev= 30
  4513.8 1807.55  4574.8 1799.91  4593.6 1798.94  4665.7 1790.15  4676.3 1790.05
  4692.1 1787.58  4704.7 1787.67  4745.8 1775.38  4771.3 1773.99  4771.6 1773.49
  4775.3 1773.99  4803.6 1774.09  4828.1 1774.52  4866.0 1779.26  4885.0 1780.18
  5015.9 1779.90  5158.0 1779.87  5255.3 1781.50  5267.9 1784.87  5283.5 1793.40
  5296.0 1794.75  5312.6 1803.31  5367.0 1824.38  5421.3 1842.42  5451.8 1850.37
  5468.8 1859.32  5475.6 1861.08  5490.4 1862.04  5496.0 1862.83  5501.5 1865.18
#Mann=8,-1,0
  4513.8    0.07       0  4593.6   0.035       0  4771.3    0.05       0
  4775.3   0.035       0  4803.6    0.07       0  5015.9   0.035       0
  5312.6    0.07       0  5490.4     0.1       0
Bank Sta=4771.3,4775.3
Exp/Cntr=0.3,0.1

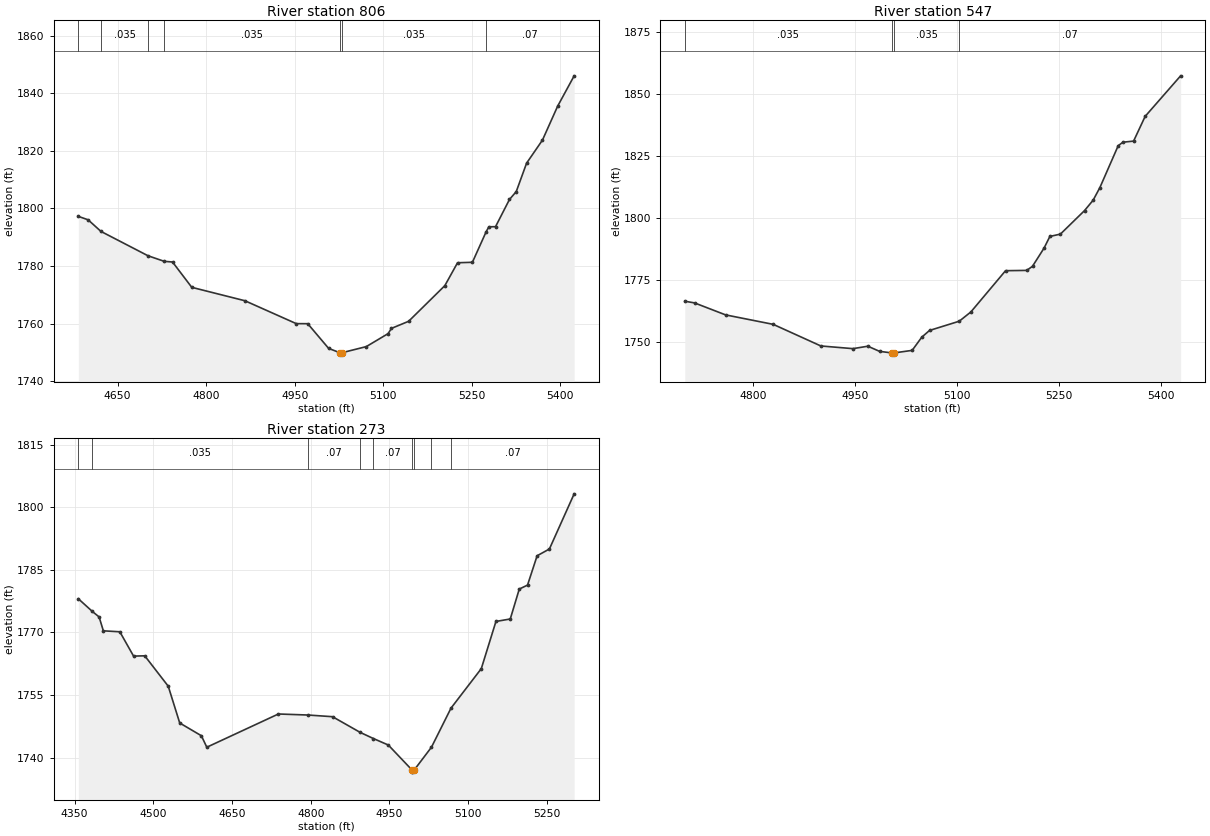
Type RM Length L Ch R = 1,806,259,259,259
BEGIN DESCRIPTION:
Mapping XS d783e3c7
END DESCRIPTION:
XS GIS Cut Line= 3
      1911584.71     13884075.57      1912147.48     13883852.98
      1912349.20     13883732.60
#Sta/Elev= 30
  4583.5 1797.27  4600.1 1796.07  4621.8 1792.05  4701.6 1783.59  4729.1 1781.66
  4743.1 1781.43  4775.7 1772.64  4865.7 1767.99  4952.8 1760.04  4972.2 1760.02
  5007.6 1751.45  5026.5 1749.96  5026.8 1749.46  5030.5 1749.96  5071.4 1752.07
  5108.3 1756.57  5114.1 1758.40  5143.1 1760.85  5204.5 1773.23  5226.0 1781.17
  5251.2 1781.33  5274.4 1791.89  5279.1 1793.65  5290.4 1793.69  5314.0 1803.14
  5325.5 1805.87  5343.0 1815.73  5369.9 1823.74  5395.7 1835.54  5423.6 1846.04
#Mann=7,-1,0
  4583.5    0.07       0  4621.8   0.035       0  4701.6    0.07       0
  4729.1   0.035       0  5026.5   0.035       0  5030.5   0.035       0
  5274.4    0.07       0
Bank Sta=5026.5,5030.5
Exp/Cntr=0.3,0.1

Type RM Length L Ch R = 1,547,274,274,274
BEGIN DESCRIPTION:
Stream0628 1.0
END DESCRIPTION:
XS GIS Cut Line= 3
      1911874.99     13884125.00      1912175.00     13884075.00
      1912474.99     13883775.01
#Sta/Elev= 30
  4699.8 1766.58  4714.1 1765.90  4759.7 1761.07  4829.7 1757.25  4899.7 1748.54
  4946.8 1747.46  4968.7 1748.44  4985.9 1746.37  5003.5 1745.75  5003.8 1745.25
  5007.5 1745.75  5033.8 1746.76  5048.0 1752.10  5059.3 1754.79  5103.0 1758.52
  5120.1 1762.26  5171.0 1778.88  5202.1 1779.00  5210.6 1780.66  5227.6 1788.00
  5236.1 1792.69  5251.6 1793.63  5287.0 1803.10  5299.7 1807.31  5309.6 1812.39
  5336.5 1829.27  5343.5 1830.68  5359.1 1831.12  5376.1 1841.09  5428.2 1857.43
#Mann=4,-1,0
  4699.8   0.035       0  5003.5   0.035       0  5007.5   0.035       0
  5103.0    0.07       0
Bank Sta=5003.5,5007.5
Exp/Cntr=0.3,0.1

Type RM Length L Ch R = 1,273,0,0,0
BEGIN DESCRIPTION:
Stream0628 0.0
END DESCRIPTION:
XS GIS Cut Line= 3
      1911784.97     13884249.94      1912235.33     13884318.04
      1912552.73     13883945.10
#Sta/Elev= 30
  4357.0 1778.08  4383.6 1775.05  4396.6 1773.72  4404.7 1770.39  4436.1 1770.16
  4462.3 1764.33  4483.6 1764.40  4528.4 1757.11  4550.3 1748.29  4591.6 1745.23
  4601.9 1742.48  4738.4 1750.45  4795.1 1750.20  4841.6 1749.80  4894.4 1746.03
  4919.4 1744.57  4947.9 1743.01  4993.2 1737.01  4993.5 1736.51  4997.2 1737.01
  5030.2 1742.49  5067.4 1751.85  5125.2 1761.33  5153.1 1772.64  5180.4 1773.23
  5197.6 1780.41  5213.3 1781.35  5231.6 1788.39  5255.0 1790.01  5302.2 1803.24
#Mann=9,-1,0
  4357.0    0.07       0  4383.6   0.035       0  4795.1    0.07       0
  4894.4   0.035       0  4919.4    0.07       0  4993.2    0.05       0
  4997.2    0.07       0  5030.2     0.1       0  5067.4    0.07       0
Bank Sta=4993.2,4997.2
Exp/Cntr=0.3,0.1

Chan Stop Cuts=-1