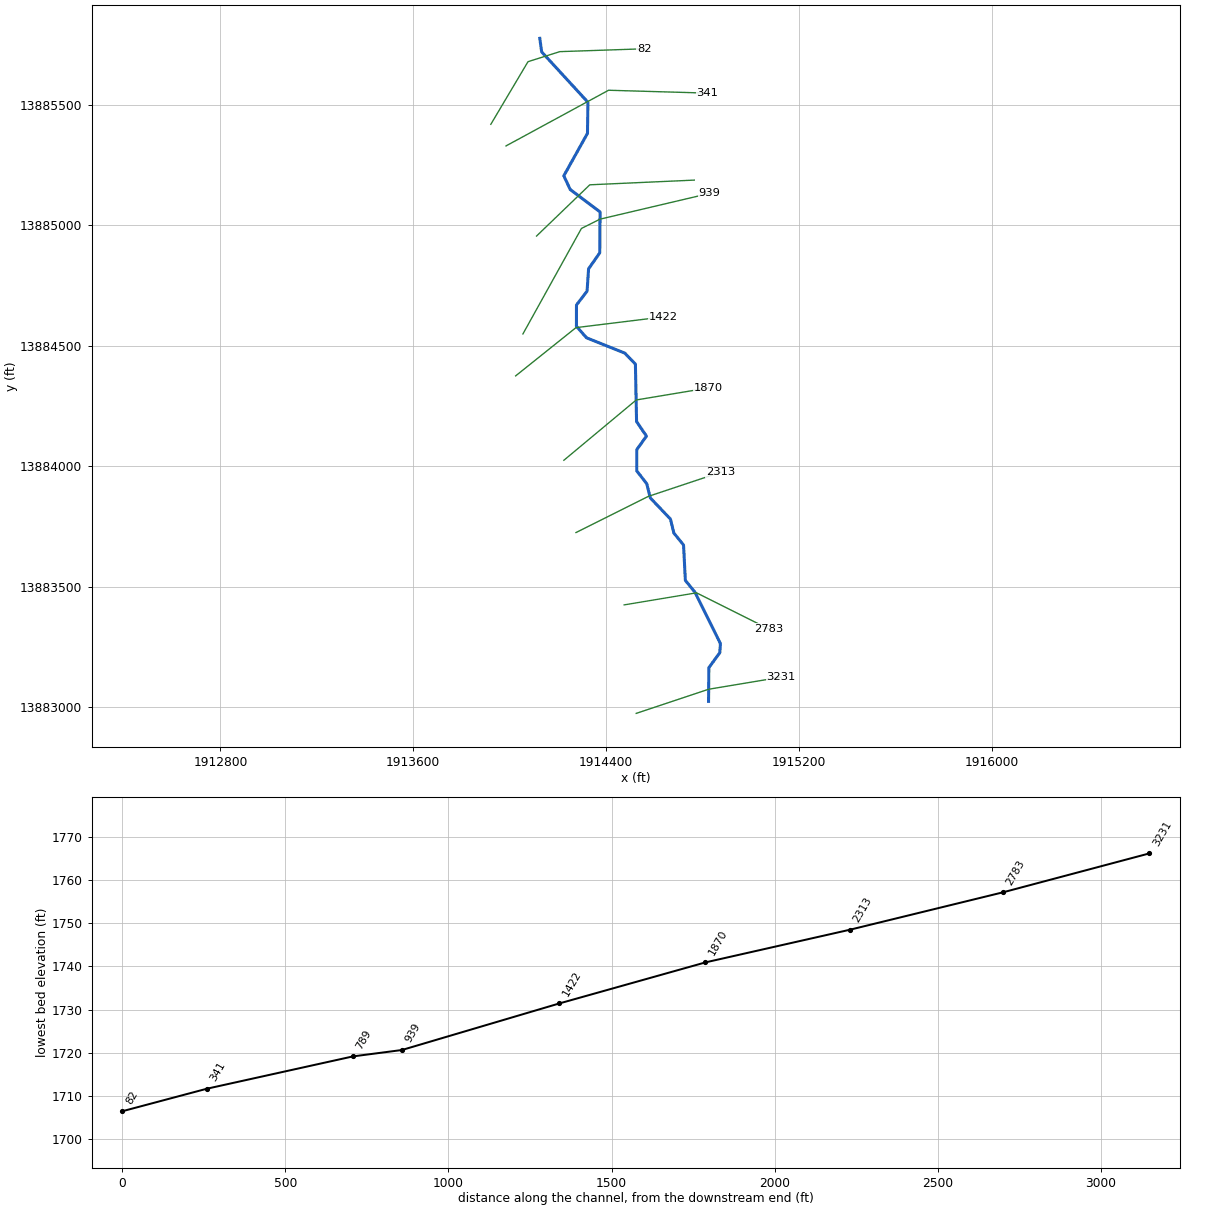
--- Stream0629.prj (project) ---

Proj Title=Stream0629 Base Level Engineering
Current Plan=p01
Default Exp/Contr=0.3,0.1
English Units
Geom File=g01
Flow File=f01
Plan File=p01
BEGIN DESCRIPTION:
Stream0629
END DESCRIPTION:

--- Stream0629.p01 (plan) ---

Plan Title=Multiple Run
Short Identifier=Multiple
Geom File=g01
Flow File=f01
Subcritical Flow
K Sum by GR= 0
Std Step Tol= 0.01
Critical Tol= 0.01
Num of Std Step Trials= 20
Max Error Tol= 0.3
Flow Tol Ratio= 0.001
Split Flow NTrial= 30
Split Flow Tol= 0.02
Split Flow Ratio= 0.02
Log Output Level= 0
Friction Slope Method= 1
Unsteady Friction Slope Method= 2
Unsteady Bridges Friction Slope Method= 1
Parabolic Critical Depth
Global Vel Dist=  1 , 1 , 1
Global Log Level= 0
CheckData=True
Encroach Param= -1, 0, 0, 0
BEGIN DESCRIPTION:
Multiple Run
END DESCRIPTION:

--- Stream0629.f01 (steady flow) ---

Flow Title=Multiple
Number of Profiles=7
Profile Names=10-year,25-year,50-year,1pct_min,100-year,1pct_plu,500-year
River Rch & RM= Stream0629,Reach-1,3231
    1016    1718    2384    1603    3198    6381    5675
Boundary for River Rch & Prof#=Stream0629,Reach-1,1
Up Type=0
Dn Type=3
Dn Slope=0.005
Boundary for River Rch & Prof#=Stream0629,Reach-1,2
Up Type=0
Dn Type=3
Dn Slope=0.005
Boundary for River Rch & Prof#=Stream0629,Reach-1,3
Up Type=0
Dn Type=3
Dn Slope=0.005
Boundary for River Rch & Prof#=Stream0629,Reach-1,4
Up Type=0
Dn Type=3
Dn Slope=0.005
Boundary for River Rch & Prof#=Stream0629,Reach-1,5
Up Type=0
Dn Type=3
Dn Slope=0.005
Boundary for River Rch & Prof#=Stream0629,Reach-1,6
Up Type=0
Dn Type=3
Dn Slope=0.005
Boundary for River Rch & Prof#=Stream0629,Reach-1,7
Up Type=0
Dn Type=3
Dn Slope=0.005

--- Stream0629.g01 (geometry) ---

Geom Title=Existing Conditions

River Reach=Stream0629,Reach-1
Reach XY= 30
      1914825.00     13883025.00      1914826.19     13883164.52
      1914871.64     13883226.74      1914874.25     13883264.32
      1914768.88     13883477.18      1914728.76     13883526.56
      1914721.24     13883673.44      1914681.14     13883722.83
      1914666.84     13883781.05      1914583.16     13883868.95
      1914568.85     13883927.17      1914527.15     13883980.97
      1914527.36     13884069.11      1914567.44     13884125.00
      1914526.38     13884185.44      1914521.55     13884423.75
      1914477.58     13884469.29      1914318.61     13884533.01
      1914276.89     13884580.71      1914277.16     13884669.02
      1914321.14     13884726.60      1914327.36     13884819.02
      1914373.78     13884885.51      1914374.96     13885054.81
      1914251.02     13885148.12      1914224.63     13885204.79
      1914322.77     13885380.93      1914324.64     13885509.84
      1914132.76     13885718.79      1914125.00     13885775.00

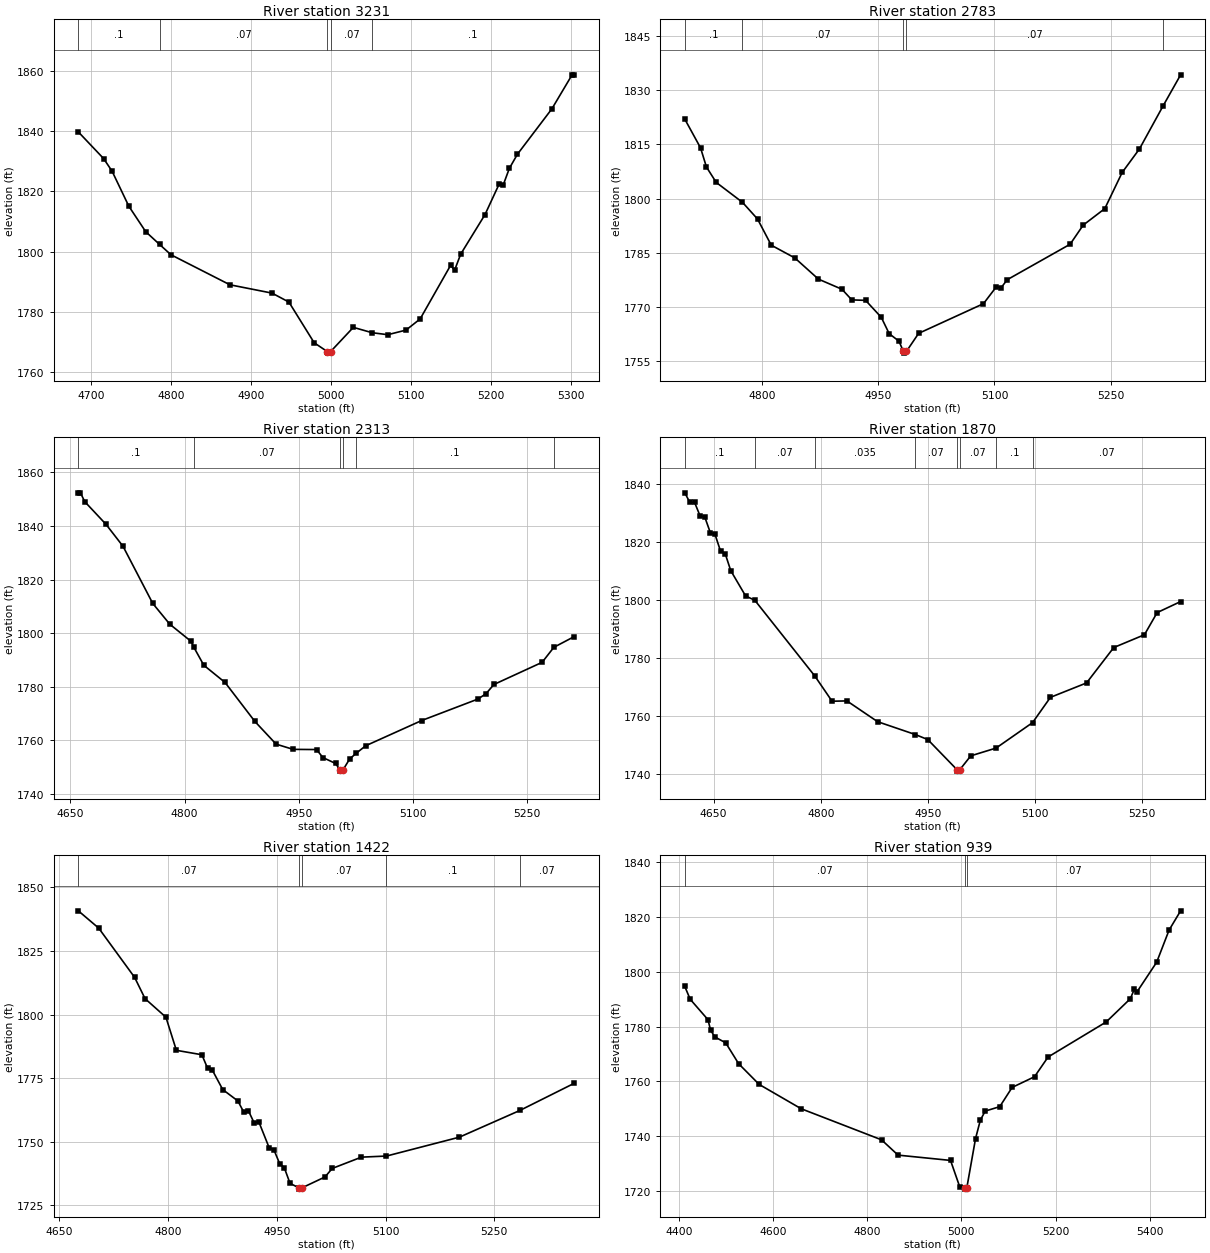
Type RM Length L Ch R = 1,3231,448,448,448
BEGIN DESCRIPTION:
Stream0629 7.0
END DESCRIPTION:
XS GIS Cut Line= 3
      1914525.01     13882975.00      1914825.00     13883075.00
      1915125.04     13883125.01
#Sta/Elev= 30
  4683.9 1839.81  4715.5 1830.95  4726.1 1826.76  4747.1 1815.09  4768.2 1806.63
  4785.5 1802.40  4799.8 1798.95  4873.6 1788.96  4926.3 1786.19  4947.4 1783.21
  4979.0 1769.68  4995.5 1766.73  4995.7 1766.23  4999.5 1766.73  5028.0 1774.80
  5051.5 1773.02  5071.1 1772.36  5093.9 1773.89  5111.6 1777.60  5149.7 1795.43
  5154.7 1793.81  5162.3 1799.14  5192.7 1812.29  5210.5 1822.50  5215.6 1822.20
  5223.2 1827.68  5233.3 1832.38  5276.4 1847.48  5301.7 1858.80  5304.3 1858.80
#Mann=5,-1,0
  4683.9     0.1       0  4785.5    0.07       0  4995.5    0.05       0
  4999.5    0.07       0  5051.5     0.1       0
Bank Sta=4995.5,4999.5
Exp/Cntr=0.3,0.1

Type RM Length L Ch R = 1,2783,470,470,470
BEGIN DESCRIPTION:
Stream0629 6.0
END DESCRIPTION:
XS GIS Cut Line= 3
      1914475.01     13883425.00      1914775.00     13883475.00
      1915074.97     13883325.02
#Sta/Elev= 30
  4700.6 1821.96  4720.9 1814.02  4728.5 1808.72  4741.1 1804.46  4775.0 1798.94
  4794.4 1794.33  4812.1 1787.09  4842.5 1783.56  4872.9 1777.70  4903.3 1774.89
  4916.0 1771.95  4933.8 1771.82  4954.0 1767.13  4964.2 1762.61  4976.8 1760.53
  4982.5 1757.72  4982.7 1757.22  4986.5 1757.72  5002.2 1762.69  5085.8 1770.90
  5102.6 1775.62  5108.1 1775.19  5116.5 1777.54  5197.6 1787.35  5214.4 1792.63
  5242.3 1797.20  5264.7 1807.20  5287.0 1813.72  5317.6 1825.67  5340.1 1834.22
#Mann=5,-1,0
  4700.6     0.1       0  4775.0    0.07       0  4982.5    0.05       0
  4986.5    0.07       0  5317.6     0.1       0
Bank Sta=4982.5,4986.5
Exp/Cntr=0.3,0.1

Type RM Length L Ch R = 1,2313,443,443,443
BEGIN DESCRIPTION:
Stream0629 5.0
END DESCRIPTION:
XS GIS Cut Line= 3
      1914275.02     13883725.01      1914575.00     13883875.00
      1914874.98     13883974.99
#Sta/Elev= 30
  4660.3 1852.38  4663.1 1852.38  4668.7 1849.10  4696.6 1840.64  4719.0 1832.44
  4758.1 1811.11  4780.5 1803.35  4808.4 1796.97  4812.1 1794.76  4825.2 1788.04
  4853.1 1781.62  4892.3 1767.07  4920.2 1758.60  4942.6 1756.65  4973.3 1756.58
  4981.7 1753.60  4998.3 1751.39  5004.2 1749.03  5004.5 1748.53  5008.2 1749.03
  5016.8 1753.03  5025.1 1755.11  5037.9 1757.99  5111.6 1767.42  5185.4 1775.42
  5196.0 1777.41  5206.5 1780.87  5269.8 1789.13  5285.2 1794.73  5311.9 1798.72
#Mann=6,-1,0
  4660.3     0.1       0  4812.1    0.07       0  5004.2    0.05       0
  5008.2    0.07       0  5025.1     0.1       0  5285.2    0.07       0
Bank Sta=5004.2,5008.2
Exp/Cntr=0.3,0.1

Type RM Length L Ch R = 1,1870,448,448,448
BEGIN DESCRIPTION:
Stream0629 4.0
END DESCRIPTION:
XS GIS Cut Line= 3
      1914225.01     13884025.01      1914525.00     13884275.00
      1914824.97     13884324.99
#Sta/Elev= 30
  4609.6 1836.98  4616.7 1833.67  4623.3 1833.68  4631.1 1828.96  4637.6 1828.62
  4645.4 1823.21  4651.9 1822.64  4659.7 1816.85  4666.2 1815.97  4674.0 1810.12
  4694.8 1801.39  4707.7 1799.90  4791.8 1773.75  4815.9 1765.07  4836.7 1765.18
  4879.7 1758.01  4932.5 1753.58  4950.0 1751.84  4990.9 1741.45  4991.2 1740.95
  4994.9 1741.45  5010.2 1746.22  5045.7 1748.91  5096.8 1757.69  5121.8 1766.41
  5172.4 1771.38  5210.5 1783.59  5253.5 1788.01  5271.3 1795.65  5304.2 1799.46
#Mann=8,-1,0
  4609.6     0.1       0  4707.7    0.07       0  4791.8   0.035       0
  4932.5    0.07       0  4990.9    0.05       0  4994.9    0.07       0
  5045.7     0.1       0  5096.8    0.07       0
Bank Sta=4990.9,4994.9
Exp/Cntr=0.3,0.1

Type RM Length L Ch R = 1,1422,483,483,483
BEGIN DESCRIPTION:
Stream0629 3.0
END DESCRIPTION:
XS GIS Cut Line= 3
      1914024.96     13884374.97      1914275.00     13884575.00
      1914636.38     13884619.41
#Sta/Elev= 30
  4676.0 1840.80  4704.1 1834.01  4753.7 1814.64  4768.1 1806.28  4796.9 1798.99
  4811.3 1785.98  4846.5 1784.24  4854.5 1778.85  4860.9 1778.22  4875.3 1770.55
  4896.2 1766.08  4904.2 1761.74  4910.6 1762.31  4918.6 1757.48  4925.0 1757.95
  4939.4 1747.67  4945.8 1746.96  4953.8 1741.49  4960.2 1739.88  4968.2 1733.68
  4980.6 1731.93  4980.8 1731.43  4984.6 1731.93  5016.4 1736.21  5026.4 1739.56
  5066.7 1744.00  5101.3 1744.43  5201.9 1751.85  5285.4 1762.35  5360.3 1773.01
#Mann=5,-1,0
  4676.0    0.07       0  4980.6    0.05       0  4984.6    0.07       0
  5101.3     0.1       0  5285.4    0.07       0
Bank Sta=4980.6,4984.6
Exp/Cntr=0.3,0.1

Type RM Length L Ch R = 1,939,150,150,150
BEGIN DESCRIPTION:
Stream0629 2.0
END DESCRIPTION:
XS GIS Cut Line= 4
      1914055.06     13884548.95      1914297.66     13884986.33
      1914375.00     13885025.00      1914828.88     13885131.79
#Sta/Elev= 30
  4412.8 1794.66  4424.2 1790.00  4462.0 1782.53  4467.7 1778.61  4476.9 1776.20
  4499.7 1774.06  4527.2 1766.43  4570.7 1758.88  4659.9 1749.99  4830.5 1738.64
  4865.7 1733.04  4977.1 1731.11  4996.6 1721.47  5007.7 1721.12  5007.9 1720.62
  5011.7 1721.12  5030.2 1739.09  5040.5 1745.87  5050.8 1749.14  5081.6 1750.75
  5107.9 1757.78  5155.4 1761.68  5184.3 1768.90  5307.6 1781.69  5359.0 1790.20
  5367.3 1793.64  5372.5 1792.55  5414.8 1803.51  5441.2 1815.27  5465.7 1822.30
#Mann=3,-1,0
  4412.8    0.07       0  5007.7    0.05       0  5011.7    0.07       0
Bank Sta=5007.7,5011.7
Exp/Cntr=0.3,0.1

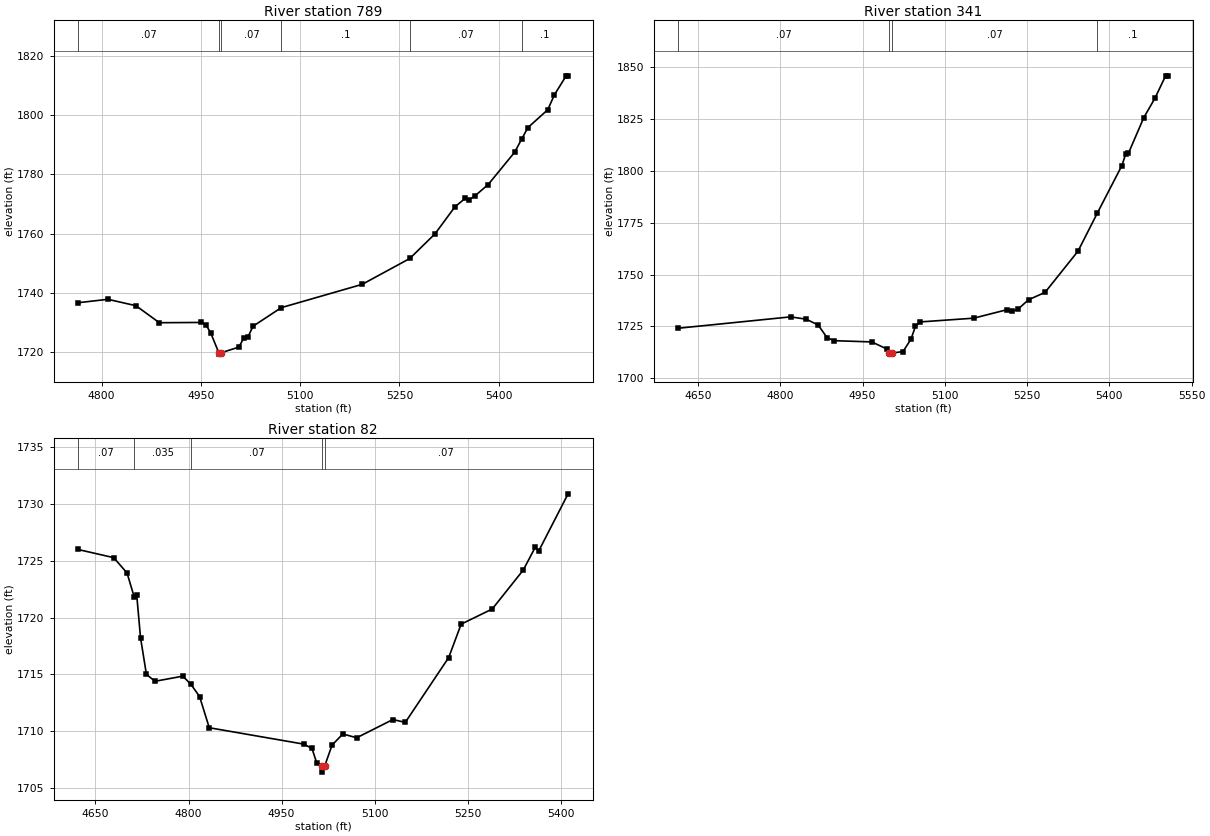
Type RM Length L Ch R = 1,789,448,448,448
BEGIN DESCRIPTION:
Mapping XS fc5a99a3
END DESCRIPTION:
XS GIS Cut Line= 3
      1914111.52     13884954.90      1914332.36     13885167.47
      1914765.70     13885186.94
#Sta/Elev= 30
  4764.5 1736.55  4809.6 1737.71  4852.0 1735.54  4887.3 1729.78  4950.8 1729.87
  4958.0 1728.98  4964.9 1726.32  4977.1 1719.64  4977.3 1719.14  4981.1 1719.64
  5007.4 1721.51  5014.6 1724.47  5021.5 1725.10  5028.8 1728.58  5071.5 1734.88
  5193.8 1742.78  5265.7 1751.54  5303.9 1759.92  5333.9 1769.05  5349.6 1771.94
  5354.6 1771.36  5364.0 1772.73  5384.0 1776.57  5424.0 1787.51  5434.5 1791.89
  5444.0 1795.85  5474.1 1801.93  5484.1 1806.96  5501.9 1813.41  5504.8 1813.41
#Mann=6,-1,0
  4764.5    0.07       0  4977.1    0.05       0  4981.1    0.07       0
  5071.5     0.1       0  5265.7    0.07       0  5434.5     0.1       0
Bank Sta=4977.1,4981.1
Exp/Cntr=0.3,0.1

Type RM Length L Ch R = 1,341,259,259,259
BEGIN DESCRIPTION:
Stream0629 0.0
END DESCRIPTION:
XS GIS Cut Line= 3
      1913984.79     13885328.70      1914410.17     13885559.66
      1914819.36     13885547.81
#Sta/Elev= 30
  4613.8 1724.13  4818.9 1729.61  4847.2 1728.49  4869.0 1725.71  4885.2 1719.61
  4898.5 1718.12  4966.8 1717.53  4994.5 1714.09  4998.9 1712.14  4999.2 1711.64
  5002.9 1712.14  5023.7 1712.87  5038.2 1718.81  5046.4 1725.02  5054.4 1727.16
  5152.7 1728.98  5212.7 1733.03  5222.7 1732.33  5232.7 1733.17  5252.7 1737.88
  5282.7 1741.42  5342.8 1761.31  5377.9 1779.61  5422.8 1802.59  5429.6 1808.03
  5434.6 1808.44  5462.8 1825.76  5482.8 1834.93  5502.5 1845.86  5507.2 1845.86
#Mann=4,-1,0
  4613.8    0.07       0  4998.9    0.05       0  5002.9    0.07       0
  5377.9     0.1       0
Bank Sta=4998.9,5002.9
Exp/Cntr=0.3,0.1

Type RM Length L Ch R = 1,82,0,0,0
BEGIN DESCRIPTION:
Stream0629 0.1
END DESCRIPTION:
XS GIS Cut Line= 4
      1913921.88     13885418.39      1914076.07     13885678.15
      1914208.01     13885719.81      1914557.28     13885731.62
#Sta/Elev= 30
  4621.9 1725.98  4679.5 1725.26  4700.9 1723.91  4712.5 1721.80  4716.5 1721.97
  4722.6 1718.24  4732.1 1715.01  4745.9 1714.40  4790.6 1714.85  4803.4 1714.17
  4817.8 1713.06  4833.4 1710.32  4985.8 1708.88  4999.0 1708.50  5006.7 1707.21
  5015.2 1706.92  5015.5 1706.42  5019.2 1706.92  5031.4 1708.80  5048.7 1709.77
  5071.1 1709.44  5129.4 1711.04  5149.4 1710.79  5219.4 1716.49  5239.4 1719.42
  5289.5 1720.75  5339.5 1724.17  5359.2 1726.21  5364.2 1725.82  5411.8 1730.87
#Mann=5,-1,0
  4621.9    0.07       0  4712.5   0.035       0  4803.4    0.07       0
  5015.2    0.05       0  5019.2    0.07       0
Bank Sta=5015.2,5019.2
Exp/Cntr=0.3,0.1

Chan Stop Cuts=-1