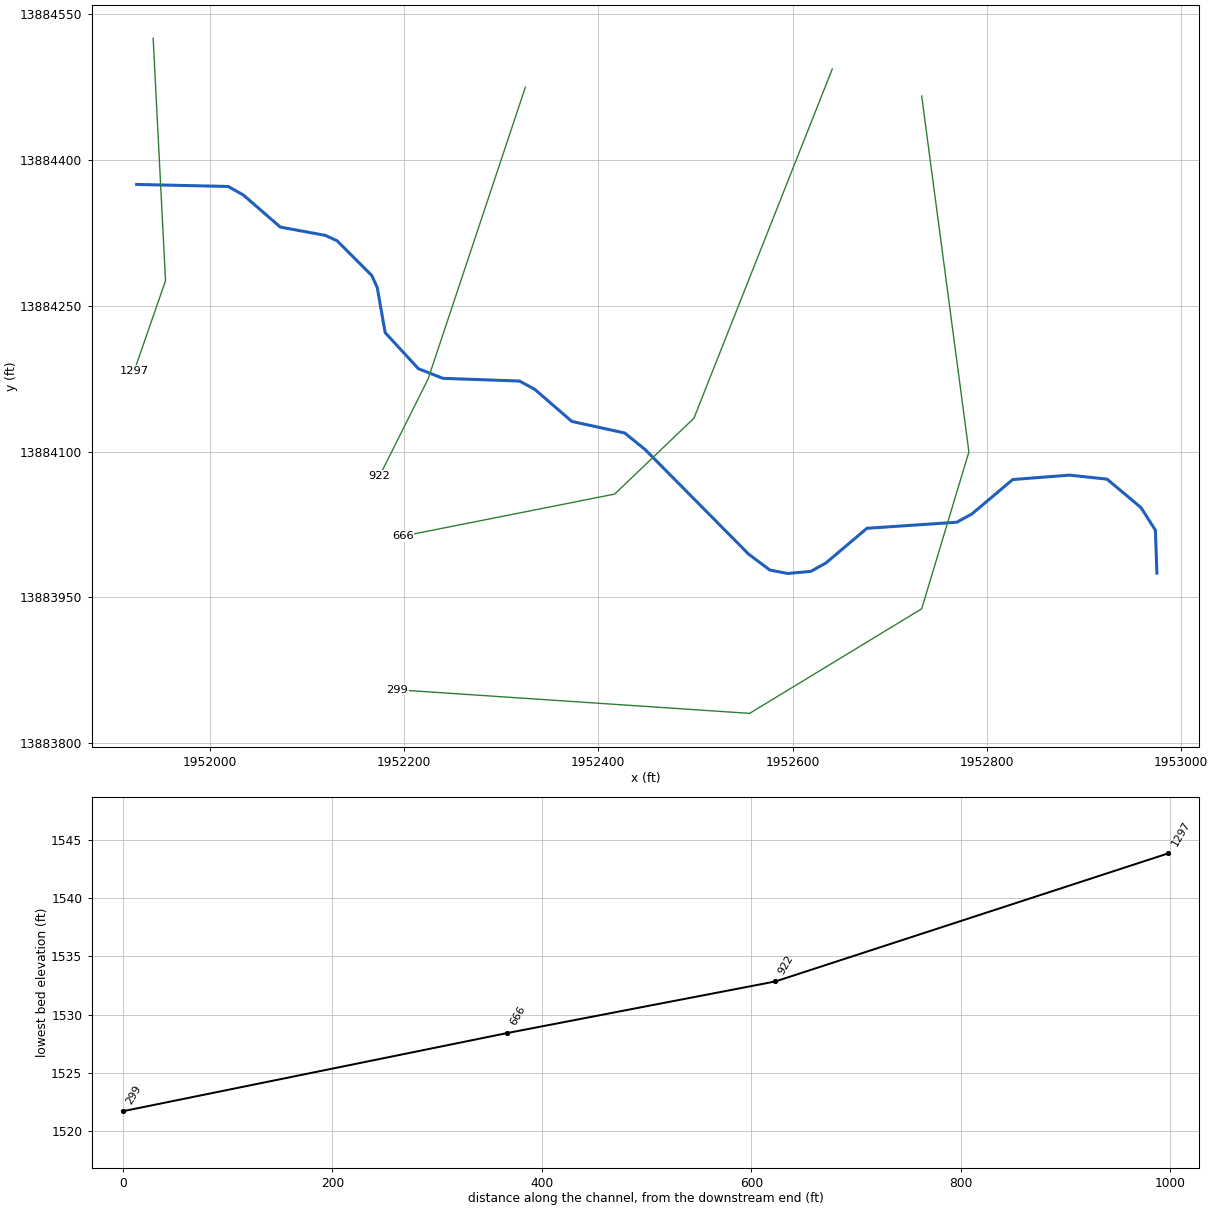
--- Stream0630.prj (project) ---

Proj Title=Stream0630 Base Level Engineering
Current Plan=p01
Default Exp/Contr=0.3,0.1
English Units
Geom File=g01
Flow File=f01
Plan File=p01
BEGIN DESCRIPTION:
Stream0630
END DESCRIPTION:

--- Stream0630.p01 (plan) ---

Plan Title=Multiple Run
Short Identifier=Multiple
Geom File=g01
Flow File=f01
Subcritical Flow
K Sum by GR= 0
Std Step Tol= 0.01
Critical Tol= 0.01
Num of Std Step Trials= 20
Max Error Tol= 0.3
Flow Tol Ratio= 0.001
Split Flow NTrial= 30
Split Flow Tol= 0.02
Split Flow Ratio= 0.02
Log Output Level= 0
Friction Slope Method= 1
Unsteady Friction Slope Method= 2
Unsteady Bridges Friction Slope Method= 1
Parabolic Critical Depth
Global Vel Dist=  1 , 1 , 1
Global Log Level= 0
CheckData=True
Encroach Param= -1, 0, 0, 0
BEGIN DESCRIPTION:
Multiple Run
END DESCRIPTION:

--- Stream0630.f01 (steady flow) ---

Flow Title=Multiple
Number of Profiles=7
Profile Names=10-year,25-year,50-year,1pct_min,100-year,1pct_plu,500-year
River Rch & RM= Stream0630,Reach-1,1297
     580     946    1283     844    1684    3361    2858
Boundary for River Rch & Prof#=Stream0630,Reach-1,1
Up Type=0
Dn Type=3
Dn Slope=0.005
Boundary for River Rch & Prof#=Stream0630,Reach-1,2
Up Type=0
Dn Type=3
Dn Slope=0.005
Boundary for River Rch & Prof#=Stream0630,Reach-1,3
Up Type=0
Dn Type=3
Dn Slope=0.005
Boundary for River Rch & Prof#=Stream0630,Reach-1,4
Up Type=0
Dn Type=3
Dn Slope=0.005
Boundary for River Rch & Prof#=Stream0630,Reach-1,5
Up Type=0
Dn Type=3
Dn Slope=0.005
Boundary for River Rch & Prof#=Stream0630,Reach-1,6
Up Type=0
Dn Type=3
Dn Slope=0.005
Boundary for River Rch & Prof#=Stream0630,Reach-1,7
Up Type=0
Dn Type=3
Dn Slope=0.005

--- Stream0630.g01 (geometry) ---

Geom Title=Existing Conditions

River Reach=Stream0630,Reach-1
Reach XY= 30
      1951925.00     13884375.00      1952019.14     13884372.93
      1952034.67     13884364.21      1952072.84     13884331.12
      1952119.15     13884322.58      1952131.34     13884316.98
      1952166.95     13884281.31      1952172.52     13884269.09
      1952180.75     13884222.45      1952214.90     13884185.39
      1952240.09     13884175.47      1952319.03     13884172.66
      1952334.65     13884164.16      1952372.83     13884131.14
      1952427.30     13884119.17      1952448.47     13884101.99
      1952554.91     13883994.43      1952576.63     13883978.13
      1952595.13     13883974.60      1952618.87     13883976.78
      1952634.52     13883985.54      1952676.58     13884021.11
      1952769.03     13884027.36      1952784.63     13884035.90
      1952826.60     13884071.30      1952885.10     13884075.84
      1952923.70     13884071.71      1952958.69     13884042.36
      1952973.45     13884019.17      1952975.00     13883975.00

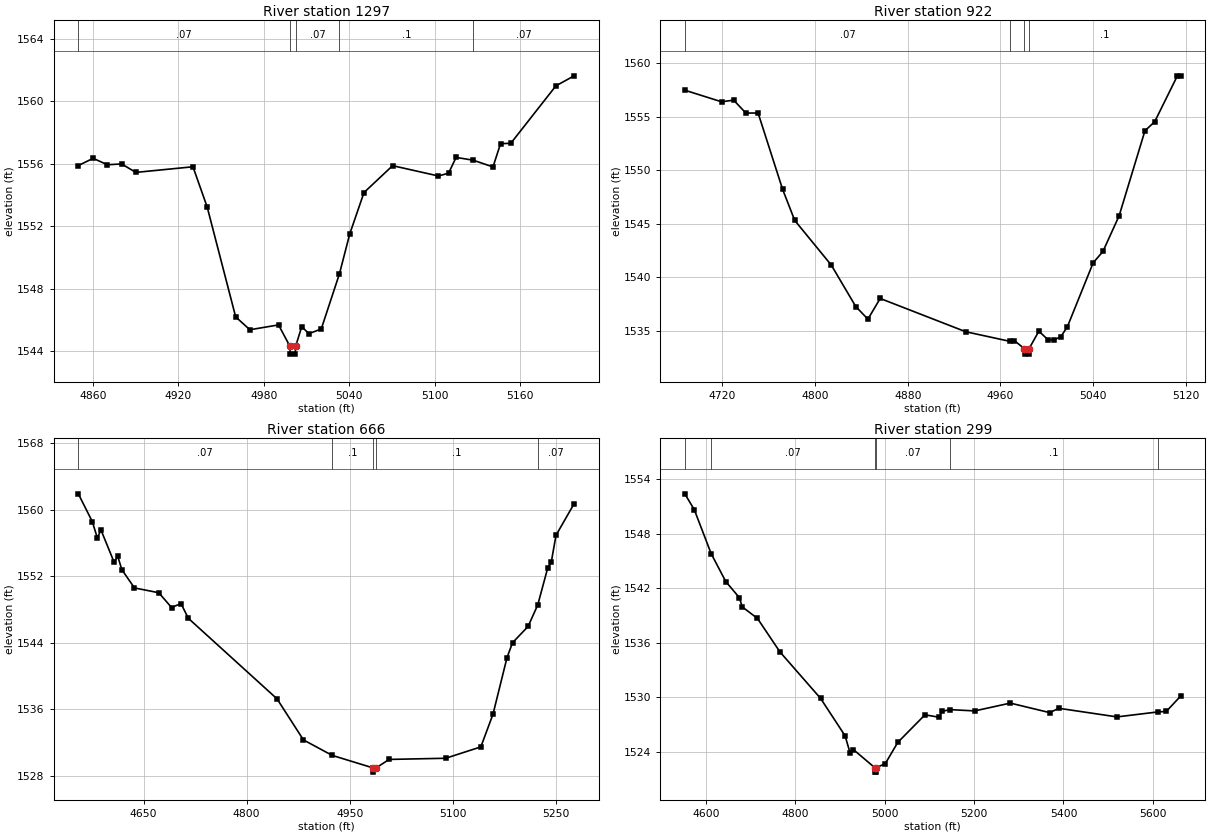
Type RM Length L Ch R = 1,1297,375,375,375
BEGIN DESCRIPTION:
Stream0630 2.0
END DESCRIPTION:
XS GIS Cut Line= 3
      1951941.95     13884525.38      1951954.67     13884275.89
      1951922.38     13884182.95
#Sta/Elev= 30
  4849.7 1555.89  4860.1 1556.35  4870.1 1555.94  4880.1 1555.99  4890.1 1555.45
  4930.2 1555.81  4940.2 1553.23  4960.2 1546.20  4970.2 1545.38  4990.3 1545.69
  4998.3 1544.32  4998.5 1543.82  5002.0 1543.82  5002.3 1544.32  5006.6 1545.58
  5011.6 1545.13  5020.3 1545.43  5033.1 1548.97  5040.3 1551.51  5050.3 1554.16
  5070.4 1555.88  5102.6 1555.22  5109.7 1555.40  5115.0 1556.41  5127.0 1556.23
  5140.9 1555.80  5146.2 1557.29  5153.4 1557.31  5185.1 1560.99  5197.9 1561.63
#Mann=5,-1,0
  4849.7    0.07       0  4998.3    0.05       0  5002.3    0.07       0
  5033.1     0.1       0  5127.0    0.07       0
Bank Sta=4998.3,5002.3
Exp/Cntr=0.3,0.1

Type RM Length L Ch R = 1,922,256,256,256
BEGIN DESCRIPTION:
Stream0630 1.0
END DESCRIPTION:
XS GIS Cut Line= 3
      1952325.01     13884475.03      1952225.00     13884175.00
      1952174.98     13884074.97
#Sta/Elev= 30
  4687.5 1557.46  4719.2 1556.38  4729.7 1556.53  4740.2 1555.33  4750.8 1555.33
  4771.9 1548.23  4782.4 1545.32  4814.0 1541.15  4835.1 1537.29  4845.6 1536.11
  4856.2 1538.04  4930.0 1534.94  4968.3 1534.04  4972.1 1534.11  4980.7 1533.35
  4980.9 1532.85  4984.4 1532.85  4984.7 1533.35  4993.2 1534.99  5001.1 1534.19
  5006.6 1534.19  5012.1 1534.47  5017.7 1535.37  5040.1 1541.37  5048.5 1542.42
  5062.5 1545.75  5084.8 1553.68  5093.2 1554.52  5112.8 1558.80  5115.6 1558.80
#Mann=4,-1,0
  4687.5    0.07       0  4968.3     0.1       0  4980.7    0.05       0
  4984.7     0.1       0
Bank Sta=4980.7,4984.7
Exp/Cntr=0.3,0.1

Type RM Length L Ch R = 1,666,367,367,367
BEGIN DESCRIPTION:
Stream0630 3.0
END DESCRIPTION:
XS GIS Cut Line= 4
      1952640.91     13884493.86      1952498.54     13884134.44
      1952416.94     13884056.32      1952199.14     13884013.11
#Sta/Elev= 30
  4555.1 1561.94  4575.4 1558.60  4582.7 1556.64  4588.1 1557.58  4607.1 1553.72
  4612.5 1554.41  4618.4 1552.81  4636.8 1550.61  4672.2 1550.03  4690.8 1548.25
  4704.5 1548.73  4715.2 1546.95  4844.3 1537.25  4882.7 1532.31  4924.4 1530.45
  4984.3 1528.93  4984.6 1528.43  4988.3 1528.93  5007.4 1529.96  5089.7 1530.10
  5140.9 1531.47  5158.6 1535.41  5179.0 1542.23  5187.0 1544.01  5209.6 1545.97
  5223.7 1548.56  5238.2 1553.01  5243.3 1553.68  5250.3 1556.95  5276.7 1560.76
#Mann=5,-1,0
  4555.1    0.07       0  4924.4     0.1       0  4984.3    0.05       0
  4988.3     0.1       0  5223.7    0.07       0
Bank Sta=4984.3,4988.3
Exp/Cntr=0.3,0.1

Type RM Length L Ch R = 1,299,0,0,0
BEGIN DESCRIPTION:
Stream0630 4.0
END DESCRIPTION:
XS GIS Cut Line= 5
      1952732.92     13884466.02      1952781.52     13884099.72
      1952732.91     13883938.26      1952555.83     13883830.63
      1952193.00     13883854.93
#Sta/Elev= 30
  4553.1 1552.37  4574.3 1550.63  4612.0 1545.79  4644.9 1542.70  4675.2 1540.94
  4681.6 1539.92  4715.5 1538.66  4766.0 1534.96  4856.8 1529.85  4911.6 1525.73
  4922.5 1523.89  4930.3 1524.21  4977.8 1522.23  4978.0 1521.73  4981.5 1521.73
  4981.8 1522.23  5001.6 1522.67  5029.4 1525.00  5090.3 1528.04  5122.2 1527.77
  5128.1 1528.42  5146.5 1528.61  5201.7 1528.47  5281.1 1529.33  5369.4 1528.28
  5389.5 1528.76  5519.8 1527.81  5611.6 1528.36  5630.0 1528.41  5662.1 1530.10
#Mann=6,-1,0
  4553.1   0.035       0  4612.0    0.07       0  4977.8    0.05       0
  4981.8    0.07       0  5146.5     0.1       0  5611.6    0.07       0
Bank Sta=4977.8,4981.8
Exp/Cntr=0.3,0.1

Chan Stop Cuts=-1