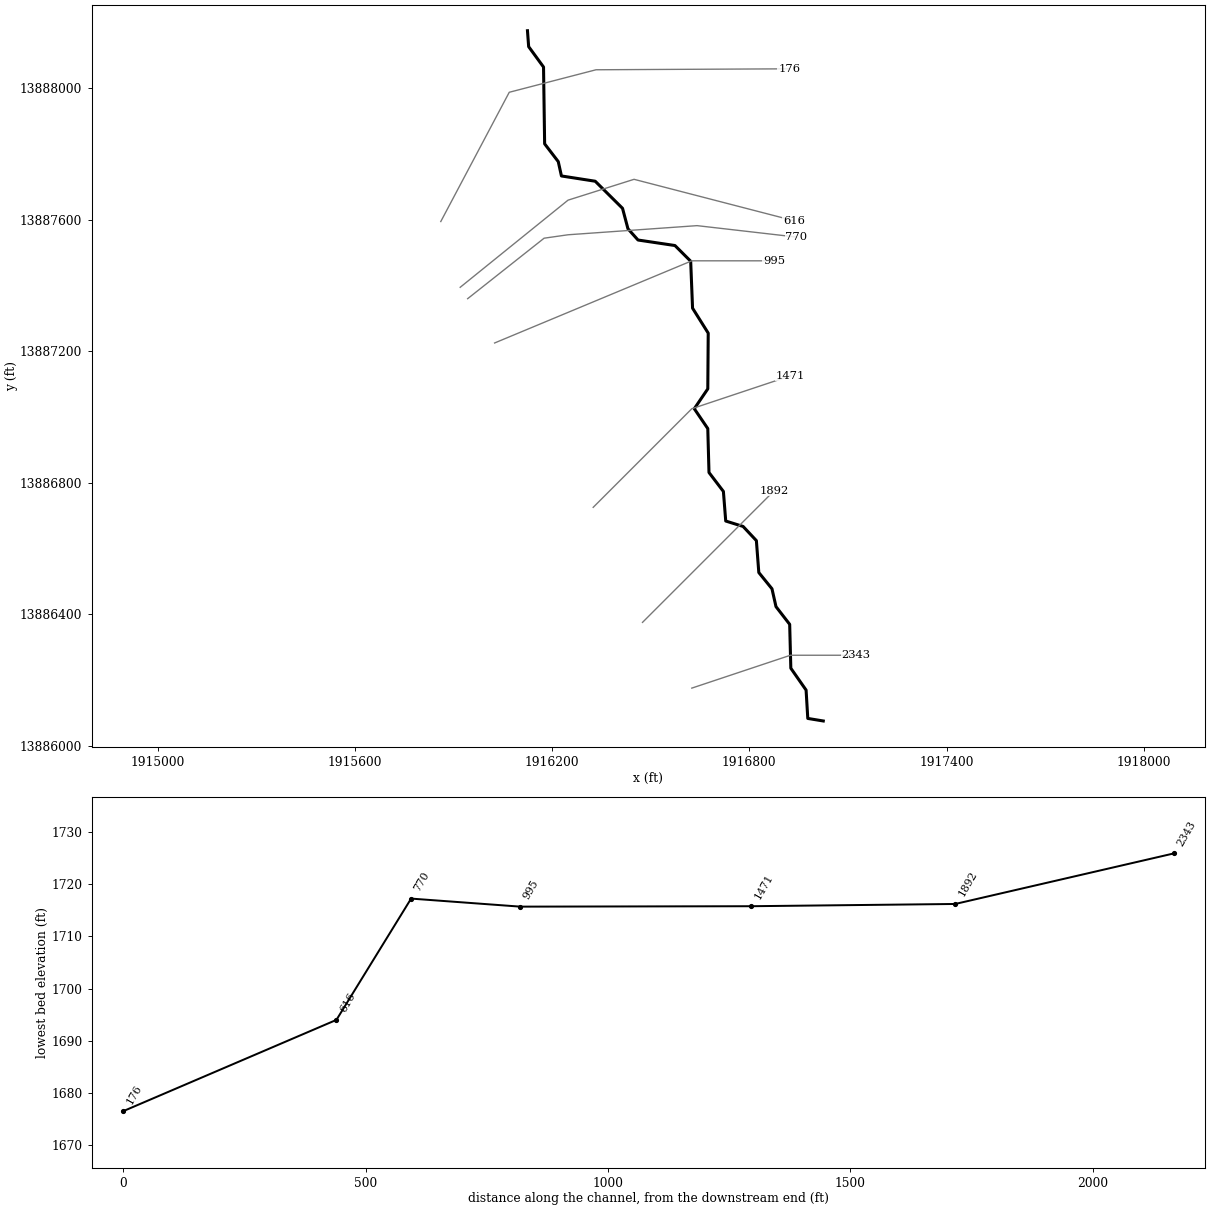
--- Stream0631.prj (project) ---

Proj Title=Stream0631 Base Level Engineering
Current Plan=p01
Default Exp/Contr=0.3,0.1
English Units
Geom File=g01
Flow File=f01
Plan File=p01
BEGIN DESCRIPTION:
Stream0631
END DESCRIPTION:

--- Stream0631.p01 (plan) ---

Plan Title=Multiple Run
Short Identifier=Multiple
Geom File=g01
Flow File=f01
Subcritical Flow
K Sum by GR= 0
Std Step Tol= 0.01
Critical Tol= 0.01
Num of Std Step Trials= 20
Max Error Tol= 0.3
Flow Tol Ratio= 0.001
Split Flow NTrial= 30
Split Flow Tol= 0.02
Split Flow Ratio= 0.02
Log Output Level= 0
Friction Slope Method= 1
Unsteady Friction Slope Method= 2
Unsteady Bridges Friction Slope Method= 1
Parabolic Critical Depth
Global Vel Dist=  1 , 1 , 1
Global Log Level= 0
CheckData=True
Encroach Param= -1, 0, 0, 0
BEGIN DESCRIPTION:
Multiple Run
END DESCRIPTION:

--- Stream0631.f01 (steady flow) ---

Flow Title=Multiple
Number of Profiles=7
Profile Names=10-year,25-year,50-year,1pct_min,100-year,1pct_plu,500-year
River Rch & RM= Stream0631,Reach-1,2343
    1264    2172    3046    2069    4127    8235    7474
Boundary for River Rch & Prof#=Stream0631,Reach-1,1
Up Type=0
Dn Type=3
Dn Slope=0.005
Boundary for River Rch & Prof#=Stream0631,Reach-1,2
Up Type=0
Dn Type=3
Dn Slope=0.005
Boundary for River Rch & Prof#=Stream0631,Reach-1,3
Up Type=0
Dn Type=3
Dn Slope=0.005
Boundary for River Rch & Prof#=Stream0631,Reach-1,4
Up Type=0
Dn Type=3
Dn Slope=0.005
Boundary for River Rch & Prof#=Stream0631,Reach-1,5
Up Type=0
Dn Type=3
Dn Slope=0.005
Boundary for River Rch & Prof#=Stream0631,Reach-1,6
Up Type=0
Dn Type=3
Dn Slope=0.005
Boundary for River Rch & Prof#=Stream0631,Reach-1,7
Up Type=0
Dn Type=3
Dn Slope=0.005

--- Stream0631.g01 (geometry) ---

Geom Title=Existing Conditions

River Reach=Stream0631,Reach-1
Reach XY= 30
      1917025.00     13886075.00      1916977.84     13886082.76
      1916972.69     13886168.99      1916926.23     13886235.51
      1916922.75     13886369.07      1916881.12     13886422.82
      1916868.89     13886477.18      1916828.83     13886526.59
      1916821.45     13886623.70      1916781.03     13886666.83
      1916728.19     13886683.35      1916721.11     13886773.33
      1916677.27     13886830.94      1916673.60     13886964.56
      1916632.56     13887025.00      1916673.62     13887085.44
      1916674.93     13887254.97      1916627.27     13887330.94
      1916621.56     13887473.77      1916573.75     13887521.49
      1916461.35     13887538.26      1916430.74     13887572.43
      1916414.22     13887634.68      1916331.14     13887717.12
      1916228.37     13887733.15      1916218.70     13887776.78
      1916177.23     13887830.90      1916173.88     13888064.54
      1916128.65     13888126.51      1916125.00     13888175.00

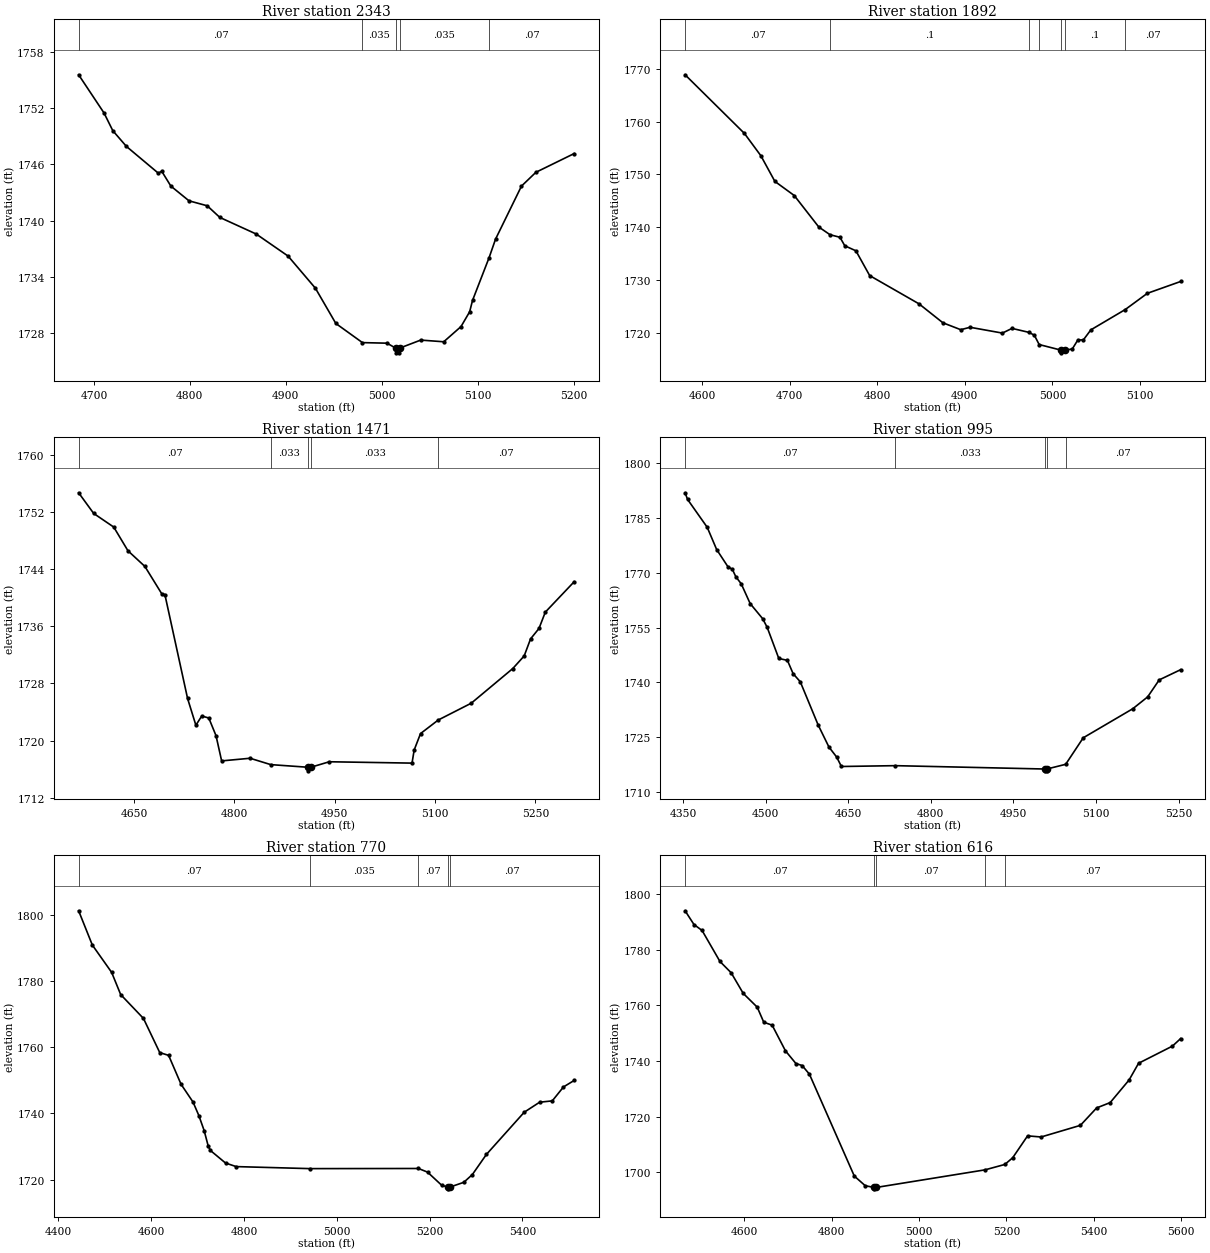
Type RM Length L Ch R = 1,2343,451,451,451
BEGIN DESCRIPTION:
Stream0631 4.0
END DESCRIPTION:
XS GIS Cut Line= 3
      1916624.98     13886174.99      1916925.00     13886275.00
      1917125.05     13886275.00
#Sta/Elev= 30
  4684.1 1755.54  4710.6 1751.46  4719.7 1749.58  4733.9 1747.90  4767.1 1745.05
  4770.7 1745.25  4780.2 1743.67  4799.1 1742.10  4818.1 1741.57  4831.2 1740.33
  4869.1 1738.56  4902.3 1736.21  4930.8 1732.78  4952.1 1729.02  4979.8 1726.98
  5005.4 1726.92  5014.5 1726.39  5014.7 1725.89  5018.2 1725.89  5018.5 1726.39
  5040.5 1727.25  5064.5 1727.07  5082.5 1728.69  5091.5 1730.27  5094.5 1731.48
  5111.8 1736.05  5118.5 1738.02  5145.5 1743.67  5160.5 1745.14  5200.4 1747.14
#Mann=5,-1,0
  4684.1    0.07       0  4979.8   0.035       0  5014.5   0.035       0
  5018.5   0.035       0  5111.8    0.07       0
Bank Sta=5014.5,5018.5
Exp/Cntr=0.3,0.1

Type RM Length L Ch R = 1,1892,421,421,421
BEGIN DESCRIPTION:
Stream0631 3.0
END DESCRIPTION:
XS GIS Cut Line= 3
      1916474.99     13886374.99      1916775.00     13886675.00
      1916875.00     13886775.00
#Sta/Elev= 30
  4580.7 1768.86  4648.4 1757.76  4667.2 1753.53  4683.2 1748.67  4705.3 1746.00
  4733.3 1740.04  4746.1 1738.58  4757.5 1738.09  4763.0 1736.48  4775.7 1735.53
  4791.4 1730.84  4847.8 1725.48  4875.0 1721.90  4895.4 1720.59  4906.0 1721.05
  4942.9 1719.95  4953.9 1720.84  4973.4 1720.08  4979.4 1719.54  4984.9 1717.78
  5010.1 1716.71  5010.3 1716.21  5014.1 1716.71  5022.7 1716.94  5029.0 1718.63
  5035.4 1718.67  5043.9 1720.56  5083.1 1724.40  5108.4 1727.48  5146.4 1729.72
#Mann=7,-1,0
  4580.7    0.07       0  4746.1     0.1       0  4973.4   0.033       0
  4984.9     0.1       0  5010.1    0.05       0  5014.1     0.1       0
  5083.1    0.07       0
Bank Sta=5010.1,5014.1
Exp/Cntr=0.3,0.1

Type RM Length L Ch R = 1,1471,476,476,476
BEGIN DESCRIPTION:
Stream0631 2.0
END DESCRIPTION:
XS GIS Cut Line= 3
      1916324.98     13886724.98      1916625.00     13887025.00
      1916924.98     13887124.99
#Sta/Elev= 30
  4567.3 1754.67  4589.8 1751.78  4619.8 1749.87  4641.0 1746.56  4666.3 1744.37
  4691.8 1740.50  4696.2 1740.43  4730.1 1725.90  4742.5 1722.16  4751.3 1723.45
  4761.8 1723.17  4772.6 1720.70  4781.0 1717.17  4823.5 1717.54  4854.4 1716.65
  4910.2 1716.28  4910.5 1715.78  4914.2 1716.28  4941.9 1717.05  5065.5 1716.86
  5068.7 1718.69  5078.2 1720.99  5104.7 1722.89  5154.0 1725.24  5216.1 1730.09
  5233.1 1731.85  5242.6 1734.23  5255.2 1735.69  5264.7 1737.98  5307.8 1742.23
#Mann=5,-1,0
  4567.3    0.07       0  4854.4   0.033       0  4910.2   0.033       0
  4914.2   0.033       0  5104.7    0.07       0
Bank Sta=4910.2,4914.2
Exp/Cntr=0.3,0.1

Type RM Length L Ch R = 1,995,225,225,225
BEGIN DESCRIPTION:
Stream0631 1.0
END DESCRIPTION:
XS GIS Cut Line= 3
      1916025.03     13887225.01      1916625.00     13887475.00
      1916875.04     13887475.00
#Sta/Elev= 30
  4353.7 1791.95  4358.1 1790.15  4393.9 1782.48  4411.0 1776.39  4431.7 1771.62
  4439.4 1770.99  4445.9 1768.91  4455.6 1767.00  4471.9 1761.56  4494.6 1757.42
  4502.8 1755.04  4523.9 1746.51  4539.5 1746.00  4549.9 1742.34  4562.9 1740.12
  4595.4 1728.26  4614.9 1722.24  4629.0 1719.47  4637.6 1716.89  4735.5 1717.12
  5006.7 1716.20  5006.9 1715.70  5010.4 1715.70  5010.7 1716.20  5044.9 1717.49
  5076.8 1724.76  5166.8 1732.73  5193.8 1735.98  5214.8 1740.64  5253.7 1743.44
#Mann=5,-1,0
  4353.7    0.07       0  4735.5   0.033       0  5006.7   0.033       0
  5010.7   0.033       0  5044.9    0.07       0
Bank Sta=5006.7,5010.7
Exp/Cntr=0.3,0.1

Type RM Length L Ch R = 1,770,154,154,154
BEGIN DESCRIPTION:
Stream0631 0.3
END DESCRIPTION:
XS GIS Cut Line= 5
      1915943.02     13887359.78      1916175.67     13887543.82
      1916248.59     13887554.23      1916640.95     13887582.01
      1916943.02     13887547.29
#Sta/Elev= 30
  4443.9 1801.14  4473.4 1790.81  4515.0 1782.56  4534.5 1775.86  4583.6 1768.65
  4618.7 1758.35  4637.8 1757.51  4664.6 1748.79  4690.4 1743.42  4702.9 1739.36
  4714.3 1734.84  4722.9 1730.26  4727.8 1728.82  4760.4 1725.03  4783.4 1723.95
  4942.3 1723.34  5176.1 1723.38  5195.7 1722.28  5225.8 1718.36  5239.2 1717.74
  5239.5 1717.24  5243.2 1717.74  5273.7 1719.20  5292.3 1721.56  5322.5 1727.62
  5404.0 1740.36  5437.2 1743.38  5464.4 1743.78  5488.6 1747.99  5511.6 1749.95
#Mann=5,-1,0
  4443.9    0.07       0  4942.3   0.035       0  5176.1    0.07       0
  5239.2   0.035       0  5243.2    0.07       0
Bank Sta=5239.2,5243.2
Exp/Cntr=0.3,0.1

Type RM Length L Ch R = 1,616,440,440,440
BEGIN DESCRIPTION:
Stream0631 0.0
END DESCRIPTION:
XS GIS Cut Line= 4
      1915920.36     13887394.42      1916248.45     13887659.55
      1916449.24     13887722.95      1916935.31     13887597.04
#Sta/Elev= 30
  4464.4 1794.02  4484.7 1789.08  4503.3 1786.93  4544.2 1775.79  4569.8 1771.74
  4597.5 1764.31  4629.5 1759.36  4644.5 1753.94  4663.7 1752.88  4694.2 1743.64
  4718.1 1739.09  4732.4 1738.36  4749.0 1735.26  4851.8 1698.61  4877.0 1695.12
  4897.8 1694.52  4898.0 1694.02  4901.8 1694.52  5151.1 1700.85  5196.4 1702.79
  5214.4 1705.20  5248.5 1713.07  5279.5 1712.67  5369.4 1716.85  5406.6 1723.12
  5437.6 1725.04  5480.9 1733.17  5502.6 1739.18  5580.1 1745.35  5598.9 1748.06
#Mann=5,-1,0
  4464.4    0.07       0  4897.8    0.05       0  4901.8    0.07       0
  5151.1   0.035       0  5196.4    0.07       0
Bank Sta=4897.8,4901.8
Exp/Cntr=0.3,0.1

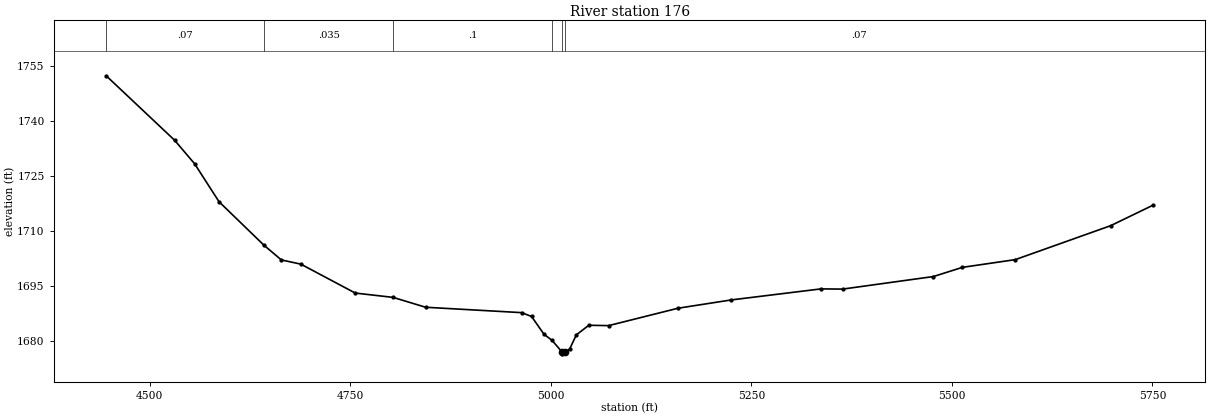
Type RM Length L Ch R = 1,176,0,0,0
BEGIN DESCRIPTION:
Stream0631 0.1
END DESCRIPTION:
XS GIS Cut Line= 4
      1915861.29     13887594.46      1916069.58     13887987.76
      1916333.63     13888056.24      1916920.89     13888059.13
#Sta/Elev= 30
  4445.7 1752.39  4531.0 1734.80  4555.9 1728.39  4586.4 1718.02  4642.3 1706.18
  4664.1 1702.14  4688.3 1701.01  4756.2 1693.11  4803.4 1691.93  4843.9 1689.24
  4963.6 1687.77  4976.0 1686.72  4991.5 1681.87  5001.6 1680.19  5014.0 1677.03
  5014.2 1676.53  5018.0 1677.03  5023.4 1677.81  5031.8 1681.70  5047.3 1684.32
  5072.1 1684.23  5158.7 1688.98  5225.0 1691.24  5336.8 1694.25  5363.7 1694.19
  5477.0 1697.62  5513.0 1700.12  5579.0 1702.23  5698.0 1711.50  5750.8 1717.09
#Mann=6,-1,0
  4445.7    0.07       0  4642.3   0.035       0  4803.4     0.1       0
  5001.6    0.07       0  5014.0    0.05       0  5018.0    0.07       0
Bank Sta=5014,5018
Exp/Cntr=0.3,0.1

Chan Stop Cuts=-1