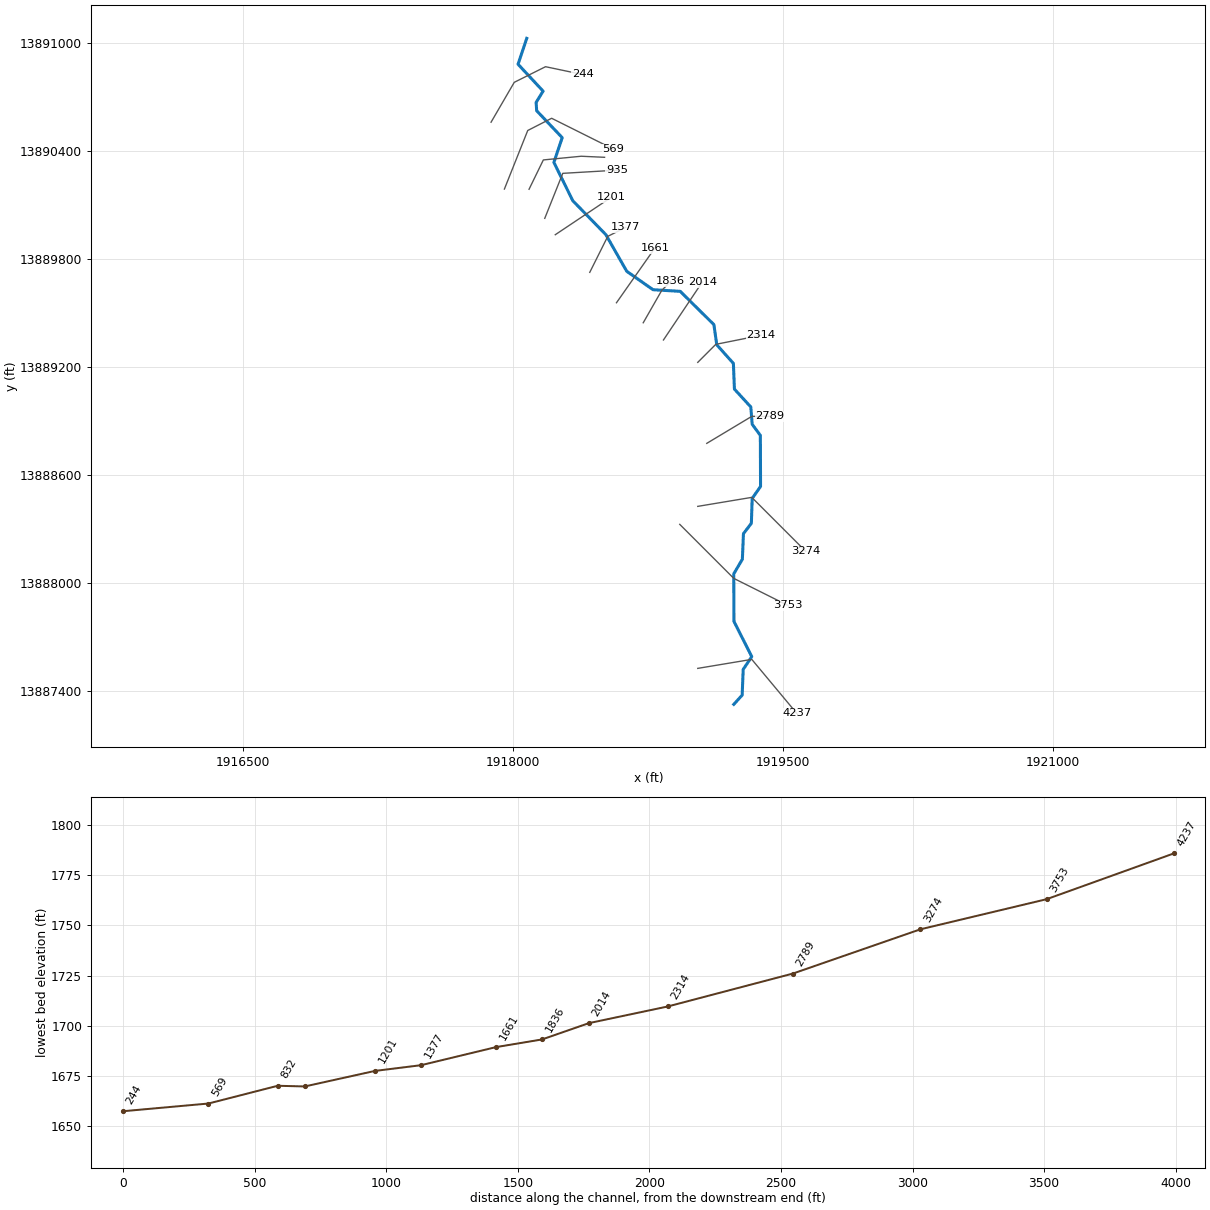
--- Stream0632.prj (project) ---

Proj Title=Stream0632 Base Level Engineering
Current Plan=p01
Default Exp/Contr=0.3,0.1
English Units
Geom File=g01
Flow File=f01
Plan File=p01
BEGIN DESCRIPTION:
Stream0632
END DESCRIPTION:

--- Stream0632.p01 (plan) ---

Plan Title=Multiple Run
Short Identifier=Multiple
Geom File=g01
Flow File=f01
Subcritical Flow
K Sum by GR= 0
Std Step Tol= 0.01
Critical Tol= 0.01
Num of Std Step Trials= 20
Max Error Tol= 0.3
Flow Tol Ratio= 0.001
Split Flow NTrial= 30
Split Flow Tol= 0.02
Split Flow Ratio= 0.02
Log Output Level= 0
Friction Slope Method= 1
Unsteady Friction Slope Method= 2
Unsteady Bridges Friction Slope Method= 1
Parabolic Critical Depth
Global Vel Dist=  1 , 1 , 1
Global Log Level= 0
CheckData=True
Encroach Param= -1, 0, 0, 0
BEGIN DESCRIPTION:
Multiple Run
END DESCRIPTION:

--- Stream0632.f01 (steady flow) ---

Flow Title=Multiple
Number of Profiles=7
Profile Names=10-year,25-year,50-year,1pct_min,100-year,1pct_plu,500-year
River Rch & RM= Stream0632,Reach-1,4237
     715    1189    1632    1088    2170    4330    3778
Boundary for River Rch & Prof#=Stream0632,Reach-1,1
Up Type=0
Dn Type=3
Dn Slope=0.005
Boundary for River Rch & Prof#=Stream0632,Reach-1,2
Up Type=0
Dn Type=3
Dn Slope=0.005
Boundary for River Rch & Prof#=Stream0632,Reach-1,3
Up Type=0
Dn Type=3
Dn Slope=0.005
Boundary for River Rch & Prof#=Stream0632,Reach-1,4
Up Type=0
Dn Type=3
Dn Slope=0.005
Boundary for River Rch & Prof#=Stream0632,Reach-1,5
Up Type=0
Dn Type=3
Dn Slope=0.005
Boundary for River Rch & Prof#=Stream0632,Reach-1,6
Up Type=0
Dn Type=3
Dn Slope=0.005
Boundary for River Rch & Prof#=Stream0632,Reach-1,7
Up Type=0
Dn Type=3
Dn Slope=0.005

--- Stream0632.g01 (geometry) ---

Geom Title=Existing Conditions

River Reach=Stream0632,Reach-1
Reach XY= 30
      1919225.00     13887325.00      1919271.70     13887376.37
      1919277.29     13887519.07      1919324.91     13887590.40
      1919226.20     13887785.50      1919224.80     13888050.08
      1919272.73     13888130.94      1919278.79     13888273.43
      1919322.73     13888330.94      1919327.27     13888469.06
      1919373.78     13888535.50      1919372.74     13888819.06
      1919327.36     13888880.98      1919319.46     13888977.42
      1919228.56     13889076.47      1919222.92     13889219.14
      1919130.54     13889322.58      1919114.48     13889434.79
      1918927.45     13889619.53      1918776.47     13889628.55
      1918630.62     13889730.62      1918514.22     13889934.68
      1918330.83     13890122.70      1918225.75     13890335.69
      1918271.87     13890473.37      1918130.12     13890622.71
      1918126.99     13890668.95      1918165.85     13890731.73
      1918026.59     13890881.02      1918075.00     13891025.00

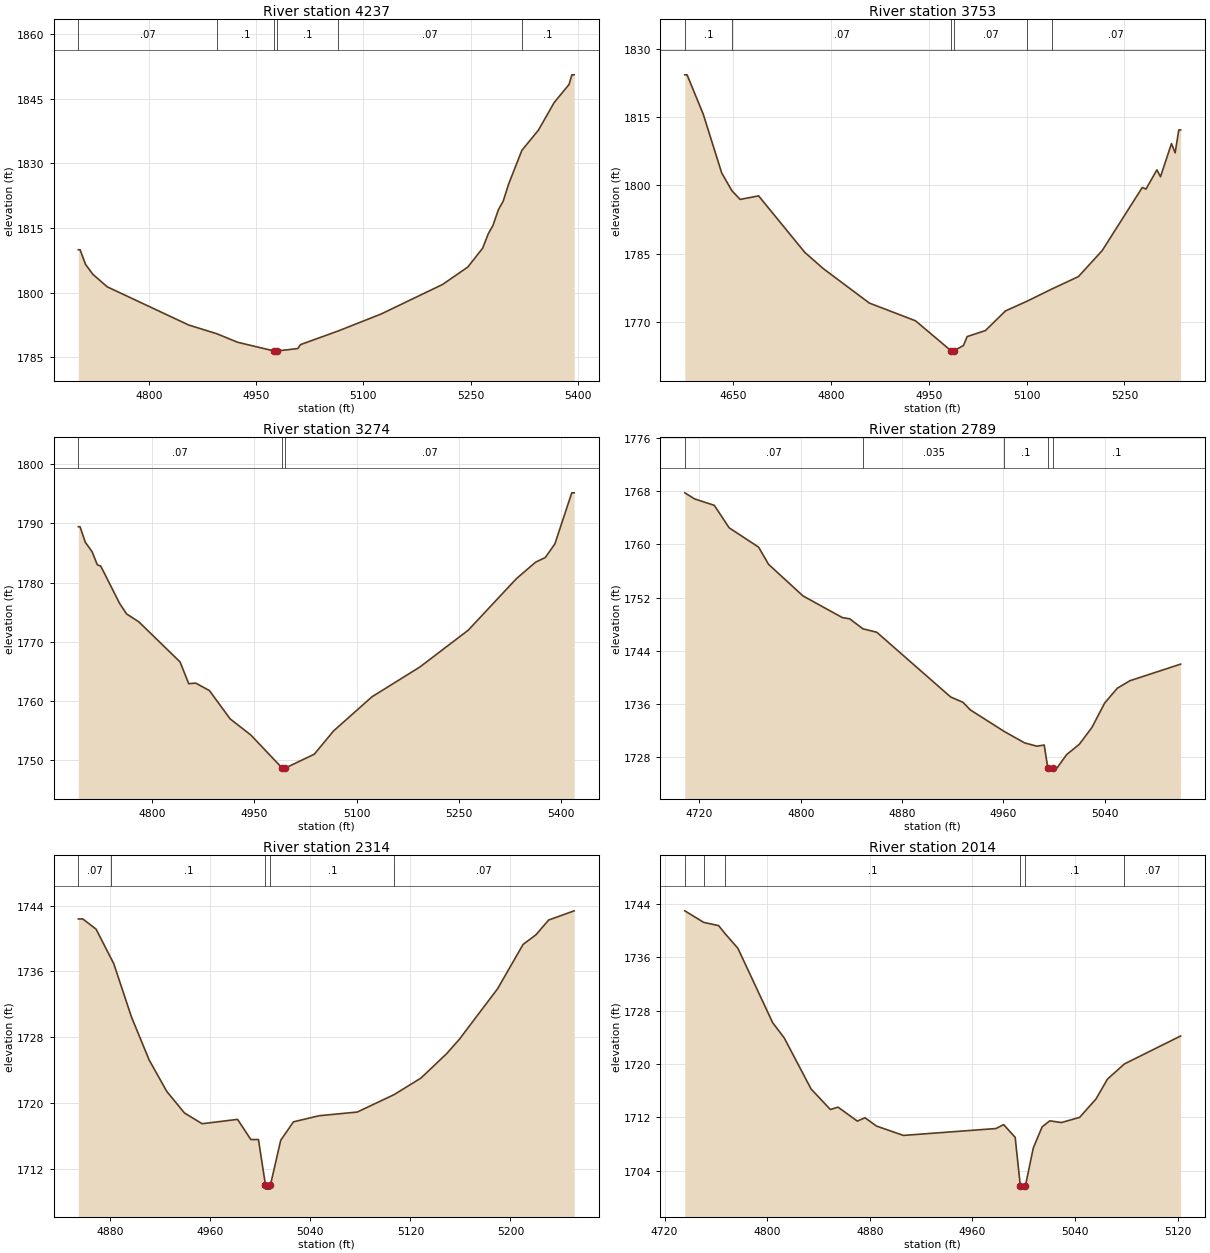
Type RM Length L Ch R = 1,4237,484,484,484
BEGIN DESCRIPTION:
Stream0632 9.0
END DESCRIPTION:
XS GIS Cut Line= 3
      1919025.02     13887525.00      1919325.00     13887575.00
      1919574.98     13887275.02
#Sta/Elev= 30
  4700.6 1809.95  4703.1 1809.95  4710.7 1806.56  4720.9 1804.25  4741.1 1801.34
  4855.2 1792.47  4894.5 1790.45  4923.6 1788.47  4974.8 1786.44  4975.1 1785.94
  4978.6 1785.94  4978.8 1786.44  5008.0 1787.00  5011.9 1787.92  5064.7 1791.09
  5125.1 1795.05  5211.0 1801.90  5246.2 1805.93  5267.0 1810.31  5274.8 1813.63
  5281.3 1815.54  5289.1 1819.27  5295.7 1821.19  5303.5 1825.25  5322.0 1833.05
  5345.1 1837.72  5367.2 1844.14  5388.1 1848.35  5392.0 1850.58  5395.2 1850.58
#Mann=6,-1,0
  4700.6    0.07       0  4894.5     0.1       0  4974.8    0.05       0
  4978.8     0.1       0  5064.7    0.07       0  5322.0     0.1       0
Bank Sta=4974.8,4978.8
Exp/Cntr=0.3,0.1

Type RM Length L Ch R = 1,3753,479,479,479
BEGIN DESCRIPTION:
Stream0632 8.0
END DESCRIPTION:
XS GIS Cut Line= 3
      1918925.01     13888324.99      1919225.00     13888025.00
      1919525.03     13887874.98
#Sta/Elev= 30
  4576.3 1824.34  4579.8 1824.34  4604.6 1815.66  4632.9 1802.72  4648.5 1798.82
  4661.1 1796.91  4689.4 1797.69  4760.1 1785.26  4788.4 1781.69  4859.1 1774.09
  4929.8 1770.19  4984.4 1763.57  4984.7 1763.07  4988.4 1763.57  5003.3 1764.75
  5008.9 1766.71  5036.9 1768.04  5067.6 1772.36  5100.5 1774.49  5138.5 1777.17
  5179.4 1779.92  5215.8 1785.64  5277.3 1799.55  5282.9 1799.18  5299.6 1803.41
  5305.2 1801.91  5322.0 1809.21  5327.6 1807.16  5333.2 1812.20  5336.0 1812.20
#Mann=6,-1,0
  4576.3     0.1       0  4648.5    0.07       0  4984.4    0.05       0
  4988.4    0.07       0  5100.5     0.1       0  5138.5    0.07       0
Bank Sta=4984.4,4988.4
Exp/Cntr=0.3,0.1

Type RM Length L Ch R = 1,3274,485,485,485
BEGIN DESCRIPTION:
Stream0632 7.0
END DESCRIPTION:
XS GIS Cut Line= 3
      1919024.99     13888425.00      1919325.00     13888475.00
      1919624.99     13888175.01
#Sta/Elev= 30
  4691.3 1789.45  4693.8 1789.45  4701.5 1786.84  4711.6 1785.20  4719.2 1783.00
  4724.3 1782.77  4752.1 1776.43  4762.3 1774.67  4780.0 1773.36  4840.8 1766.55
  4853.5 1762.86  4863.7 1762.97  4883.9 1761.70  4914.3 1756.91  4944.8 1754.17
  4990.9 1748.56  4991.2 1748.06  4994.7 1748.06  4994.9 1748.56  5037.9 1750.92
  5066.2 1754.86  5122.7 1760.65  5193.4 1765.72  5264.2 1771.94  5334.9 1780.66
  5363.1 1783.45  5377.3 1784.23  5391.4 1786.55  5416.2 1795.19  5419.7 1795.19
#Mann=3,-1,0
  4691.3    0.07       0  4990.9    0.05       0  4994.9    0.07       0
Bank Sta=4990.9,4994.9
Exp/Cntr=0.3,0.1

Type RM Length L Ch R = 1,2789,475,475,475
BEGIN DESCRIPTION:
Stream0632 6.0
END DESCRIPTION:
XS GIS Cut Line= 3
      1919075.00     13888775.00      1919325.00     13888925.00
      1919424.95     13888925.00
#Sta/Elev= 30
  4708.4 1767.75  4716.2 1766.83  4731.7 1765.87  4743.4 1762.50  4766.7 1759.59
  4774.5 1757.02  4801.7 1752.27  4832.8 1749.01  4838.6 1748.83  4849.0 1747.33
  4860.0 1746.81  4918.3 1737.09  4928.0 1736.29  4933.9 1735.14  4960.7 1731.90
  4976.6 1730.20  4986.3 1729.70  4992.2 1729.87  4995.0 1726.45  4995.3 1725.95
  4998.8 1725.95  4999.0 1726.45  5002.4 1726.45  5009.9 1728.43  5019.9 1729.98
  5029.9 1732.52  5039.9 1736.17  5049.9 1738.40  5059.9 1739.53  5099.9 1742.02
#Mann=5,-1,0
  4708.4    0.07       0  4849.0   0.035       0  4960.7     0.1       0
  4995.0    0.05       0  4999.0     0.1       0
Bank Sta=4995,4999
Exp/Cntr=0.3,0.1

Type RM Length L Ch R = 1,2314,300,300,300
BEGIN DESCRIPTION:
Stream0632 5.0
END DESCRIPTION:
XS GIS Cut Line= 3
      1919024.98     13889224.98      1919125.00     13889325.00
      1919375.00     13889375.00
#Sta/Elev= 30
  4854.5 1742.38  4858.1 1742.38  4868.7 1741.14  4880.9 1737.52  4882.8 1736.96
  4897.0 1730.46  4911.1 1725.25  4925.2 1721.42  4939.4 1718.79  4953.5 1717.49
  4981.8 1718.02  4992.4 1715.57  4998.5 1715.57  5004.1 1710.04  5004.4 1709.54
  5007.9 1709.54  5008.1 1710.04  5016.3 1715.48  5026.5 1717.72  5046.9 1718.46
  5077.5 1718.91  5107.1 1721.04  5128.5 1723.05  5148.9 1726.00  5159.1 1727.75
  5189.7 1733.90  5210.1 1739.29  5220.3 1740.45  5230.5 1742.25  5250.9 1743.37
#Mann=5,-1,0
  4854.5    0.07       0  4880.9     0.1       0  5004.1    0.05       0
  5008.1     0.1       0  5107.1    0.07       0
Bank Sta=5004.1,5008.1
Exp/Cntr=0.3,0.1

Type RM Length L Ch R = 1,2014,178,178,178
BEGIN DESCRIPTION:
Mapping XS 61935abf
END DESCRIPTION:
XS GIS Cut Line= 2
      1918834.42     13889349.32      1919049.67     13889670.45
#Sta/Elev= 30
  4735.8 1742.97  4750.5 1741.24  4762.2 1740.75  4767.2 1739.55  4777.2 1737.35
  4804.3 1726.19  4813.3 1723.91  4834.3 1716.23  4849.3 1713.16  4855.3 1713.51
  4870.3 1711.42  4876.3 1711.92  4885.3 1710.67  4906.3 1709.27  4978.4 1710.30
  4984.4 1710.89  4993.4 1708.98  4997.4 1701.71  4997.6 1701.21  5001.1 1701.21
  5001.4 1701.71  5007.5 1707.37  5014.4 1710.55  5020.4 1711.46  5029.4 1711.20
  5043.6 1711.97  5056.4 1714.73  5065.4 1717.73  5078.6 1720.00  5122.4 1724.19
#Mann=6,-1,0
  4735.8   0.035       0  4750.5    0.07       0  4767.2     0.1       0
  4997.4    0.05       0  5001.4     0.1       0  5078.6    0.07       0
Bank Sta=4997.4,5001.4
Exp/Cntr=0.3,0.1

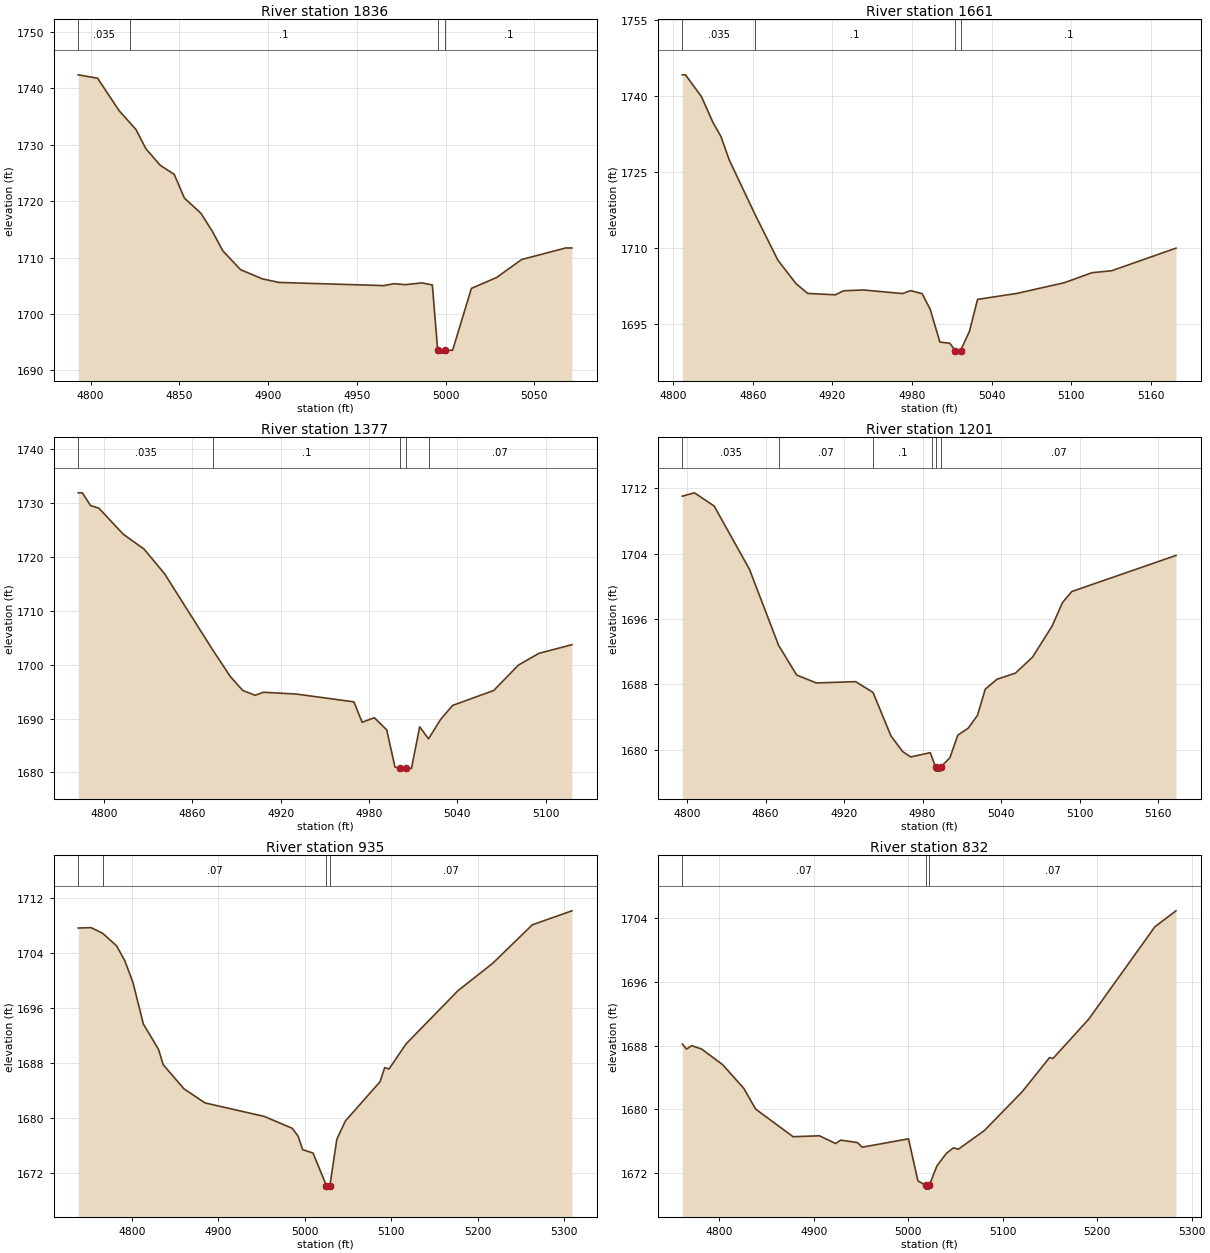
Type RM Length L Ch R = 1,1836,175,175,175
BEGIN DESCRIPTION:
Stream0632 4.0
END DESCRIPTION:
XS GIS Cut Line= 3
      1918722.09     13889444.93      1918825.00     13889625.00
      1918874.99     13889674.99
#Sta/Elev= 30
  4793.0 1742.40  4803.9 1741.80  4816.1 1736.02  4822.2 1733.88  4825.5 1732.72
  4831.2 1729.26  4839.2 1726.37  4847.1 1724.75  4852.8 1720.56  4862.2 1717.83
  4868.7 1714.58  4874.4 1711.23  4884.5 1707.85  4896.7 1706.24  4906.1 1705.60
  4965.1 1705.04  4970.9 1705.37  4977.4 1705.21  4986.7 1705.52  4992.5 1705.15
  4995.5 1693.57  4995.8 1693.07  4999.3 1693.07  4999.5 1693.57  5003.9 1693.57
  5014.5 1704.54  5028.7 1706.48  5042.8 1709.66  5067.6 1711.71  5071.1 1711.71
#Mann=4,-1,0
  4793.0   0.035       0  4822.2     0.1       0  4995.5    0.05       0
  4999.5     0.1       0
Bank Sta=4995.5,4999.5
Exp/Cntr=0.3,0.1

Type RM Length L Ch R = 1,1661,284,284,284
BEGIN DESCRIPTION:
Mapping XS 0c14ebcd
END DESCRIPTION:
XS GIS Cut Line= 2
      1918573.31     13889556.02      1918787.17     13889860.65
#Sta/Elev= 30
  4806.8 1744.23  4809.2 1744.23  4821.2 1739.93  4829.9 1734.83  4836.0 1732.01
  4842.2 1727.40  4861.4 1716.77  4878.9 1707.59  4892.6 1702.96  4901.3 1701.04
  4922.2 1700.76  4928.4 1701.56  4943.2 1701.72  4972.8 1701.01  4978.9 1701.59
  4987.6 1700.99  4993.7 1697.91  5001.0 1691.42  5008.5 1691.19  5012.6 1689.74
  5012.9 1689.24  5016.4 1689.24  5016.6 1689.74  5023.3 1693.55  5029.4 1699.86
  5059.1 1701.04  5094.8 1703.15  5115.7 1705.13  5130.5 1705.52  5179.0 1709.98
#Mann=4,-1,0
  4806.8   0.035       0  4861.4     0.1       0  5012.6    0.05       0
  5016.6     0.1       0
Bank Sta=5012.6,5016.6
Exp/Cntr=0.3,0.1

Type RM Length L Ch R = 1,1377,176,176,176
BEGIN DESCRIPTION:
Stream0632 3.0
END DESCRIPTION:
XS GIS Cut Line= 3
      1918425.00     13889725.01      1918525.00     13889925.00
      1918625.00     13889975.00
#Sta/Elev= 30
  4782.5 1731.90  4785.3 1731.90  4790.9 1729.53  4796.5 1729.06  4813.2 1724.19
  4827.2 1721.47  4841.2 1716.86  4874.3 1702.56  4885.9 1697.78  4894.3 1695.21
  4902.7 1694.32  4908.3 1694.88  4930.6 1694.55  4969.8 1693.10  4975.4 1689.31
  4983.7 1690.15  4992.1 1687.90  4997.7 1681.01  5001.3 1680.74  5001.6 1680.24
  5005.3 1680.74  5008.9 1680.74  5014.5 1688.47  5020.5 1686.23  5028.5 1689.75
  5036.8 1692.43  5064.8 1695.21  5081.6 1699.93  5095.5 1702.10  5117.9 1703.71
#Mann=5,-1,0
  4782.5   0.035       0  4874.3     0.1       0  5001.3    0.05       0
  5005.3     0.1       0  5020.5    0.07       0
Bank Sta=5001.3,5005.3
Exp/Cntr=0.3,0.1

Type RM Length L Ch R = 1,1201,266,266,266
BEGIN DESCRIPTION:
Mapping XS 7b124dc5
END DESCRIPTION:
XS GIS Cut Line= 2
      1918233.44     13889934.08      1918547.06     13890143.66
#Sta/Elev= 30
  4796.4 1711.04  4805.7 1711.45  4820.7 1709.84  4847.7 1702.09  4870.0 1692.76
  4883.8 1689.13  4898.8 1688.16  4928.8 1688.32  4942.1 1687.01  4955.8 1681.68
  4964.8 1679.75  4970.9 1679.10  4985.9 1679.62  4987.3 1679.00  4989.9 1677.86
  4990.1 1677.36  4993.6 1677.36  4993.9 1677.86  5000.9 1679.01  5006.9 1681.77
  5014.8 1682.61  5021.9 1684.18  5027.9 1687.40  5036.9 1688.62  5050.9 1689.36
  5064.0 1691.32  5079.0 1695.14  5086.9 1698.01  5094.0 1699.36  5173.6 1703.78
#Mann=6,-1,0
  4796.4   0.035       0  4870.0    0.07       0  4942.1     0.1       0
  4987.3    0.07       0  4989.9    0.05       0  4993.9    0.07       0
Bank Sta=4989.9,4993.9
Exp/Cntr=0.3,0.1

Type RM Length L Ch R = 1,935,103,103,103
BEGIN DESCRIPTION:
Stream0632 2.0
END DESCRIPTION:
XS GIS Cut Line= 3
      1918175.00     13890024.99      1918275.00     13890275.00
      1918576.61     13890292.63
#Sta/Elev= 30
  4737.8 1707.69  4752.6 1707.75  4766.1 1706.92  4782.2 1705.10  4791.7 1702.93
  4801.1 1699.78  4813.2 1693.70  4830.7 1690.01  4836.1 1687.78  4860.3 1684.23
  4884.6 1682.19  4953.2 1680.22  4985.5 1678.49  4992.3 1677.34  4997.6 1675.37
  5009.6 1674.88  5025.1 1670.12  5025.4 1669.62  5028.9 1669.62  5029.1 1670.12
  5037.1 1676.88  5047.1 1679.57  5087.2 1685.29  5092.5 1687.34  5097.5 1687.13
  5117.3 1690.80  5177.4 1698.56  5217.4 1702.53  5263.4 1708.16  5309.2 1710.20
#Mann=4,-1,0
  4737.8   0.035       0  4766.1    0.07       0  5025.1    0.05       0
  5029.1    0.07       0
Bank Sta=5025.1,5029.1
Exp/Cntr=0.3,0.1

Type RM Length L Ch R = 1,832,263,263,263
BEGIN DESCRIPTION:
Stream0632 1.1
END DESCRIPTION:
XS GIS Cut Line= 4
      1918087.76     13890186.56      1918167.13     13890349.47
      1918377.24     13890370.00      1918507.29     13890364.14
#Sta/Elev= 30
  4760.9 1688.19  4765.4 1687.56  4770.9 1687.99  4781.4 1687.56  4803.7 1685.59
  4825.9 1682.63  4838.6 1680.01  4878.1 1676.55  4906.2 1676.66  4923.1 1675.69
  4928.7 1676.12  4946.3 1675.81  4951.3 1675.23  5000.3 1676.28  5010.3 1670.99
  5018.4 1670.46  5018.6 1669.96  5022.1 1669.96  5022.4 1670.46  5030.4 1672.88
  5040.4 1674.46  5047.9 1675.15  5053.0 1674.97  5080.6 1677.32  5120.8 1682.22
  5149.6 1686.49  5153.2 1686.37  5191.0 1691.31  5261.1 1702.93  5283.4 1704.93
#Mann=3,-1,0
  4760.9    0.07       0  5018.4    0.05       0  5022.4    0.07       0
Bank Sta=5018.4,5022.4
Exp/Cntr=0.3,0.1

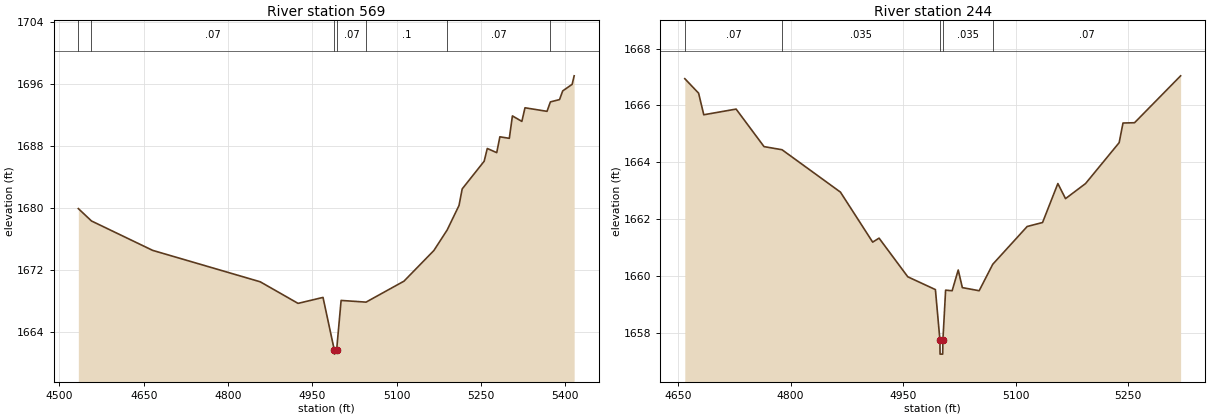
Type RM Length L Ch R = 1,569,325,325,325
BEGIN DESCRIPTION:
Stream0632 1.0
END DESCRIPTION:
XS GIS Cut Line= 4
      1917950.79     13890187.72      1918080.40     13890513.05
      1918213.24     13890580.94      1918556.00     13890409.79
#Sta/Elev= 30
  4533.6 1679.91  4557.0 1678.31  4665.9 1674.51  4857.3 1670.45  4924.7 1667.66
  4969.1 1668.43  4989.3 1661.60  4989.6 1661.10  4993.3 1661.60  5001.3 1668.04
  5045.7 1667.82  5113.2 1670.53  5166.4 1674.49  5190.1 1677.15  5211.2 1680.32
  5216.8 1682.45  5255.9 1686.03  5261.5 1687.68  5278.3 1687.14  5283.9 1689.19
  5300.7 1688.99  5306.2 1691.89  5323.0 1691.18  5328.6 1692.94  5367.8 1692.48
  5373.8 1693.70  5390.1 1694.00  5395.7 1695.12  5412.5 1695.97  5416.1 1697.07
#Mann=7,-1,0
  4533.6   0.035       0  4557.0    0.07       0  4989.3    0.05       0
  4993.3    0.07       0  5045.7     0.1       0  5190.1    0.07       0
  5373.8     0.1       0
Bank Sta=4989.3,4993.3
Exp/Cntr=0.3,0.1

Type RM Length L Ch R = 1,244,0,0,0
BEGIN DESCRIPTION:
Stream0632 0.0
END DESCRIPTION:
XS GIS Cut Line= 4
      1917876.68     13890559.08      1918005.60     13890780.72
      1918179.41     13890867.40      1918385.09     13890824.19
#Sta/Elev= 30
  4659.0 1666.94  4677.4 1666.43  4684.3 1665.67  4727.4 1665.87  4764.6 1664.55
  4788.6 1664.44  4866.4 1662.95  4909.4 1661.19  4917.9 1661.33  4956.2 1659.97
  4993.0 1659.52  4999.0 1657.75  4999.2 1657.25  5002.7 1657.25  5003.0 1657.75
  5006.6 1659.50  5015.3 1659.48  5023.4 1660.21  5028.9 1659.59  5051.3 1659.48
  5069.4 1660.41  5115.3 1661.74  5135.8 1661.88  5156.2 1663.25  5166.4 1662.72
  5193.1 1663.25  5237.9 1664.69  5243.0 1665.38  5258.4 1665.39  5319.8 1667.04
#Mann=5,-1,0
  4659.0    0.07       0  4788.6   0.035       0  4999.0   0.035       0
  5003.0   0.035       0  5069.4    0.07       0
Bank Sta=4999,5003
Exp/Cntr=0.3,0.1

Chan Stop Cuts=-1