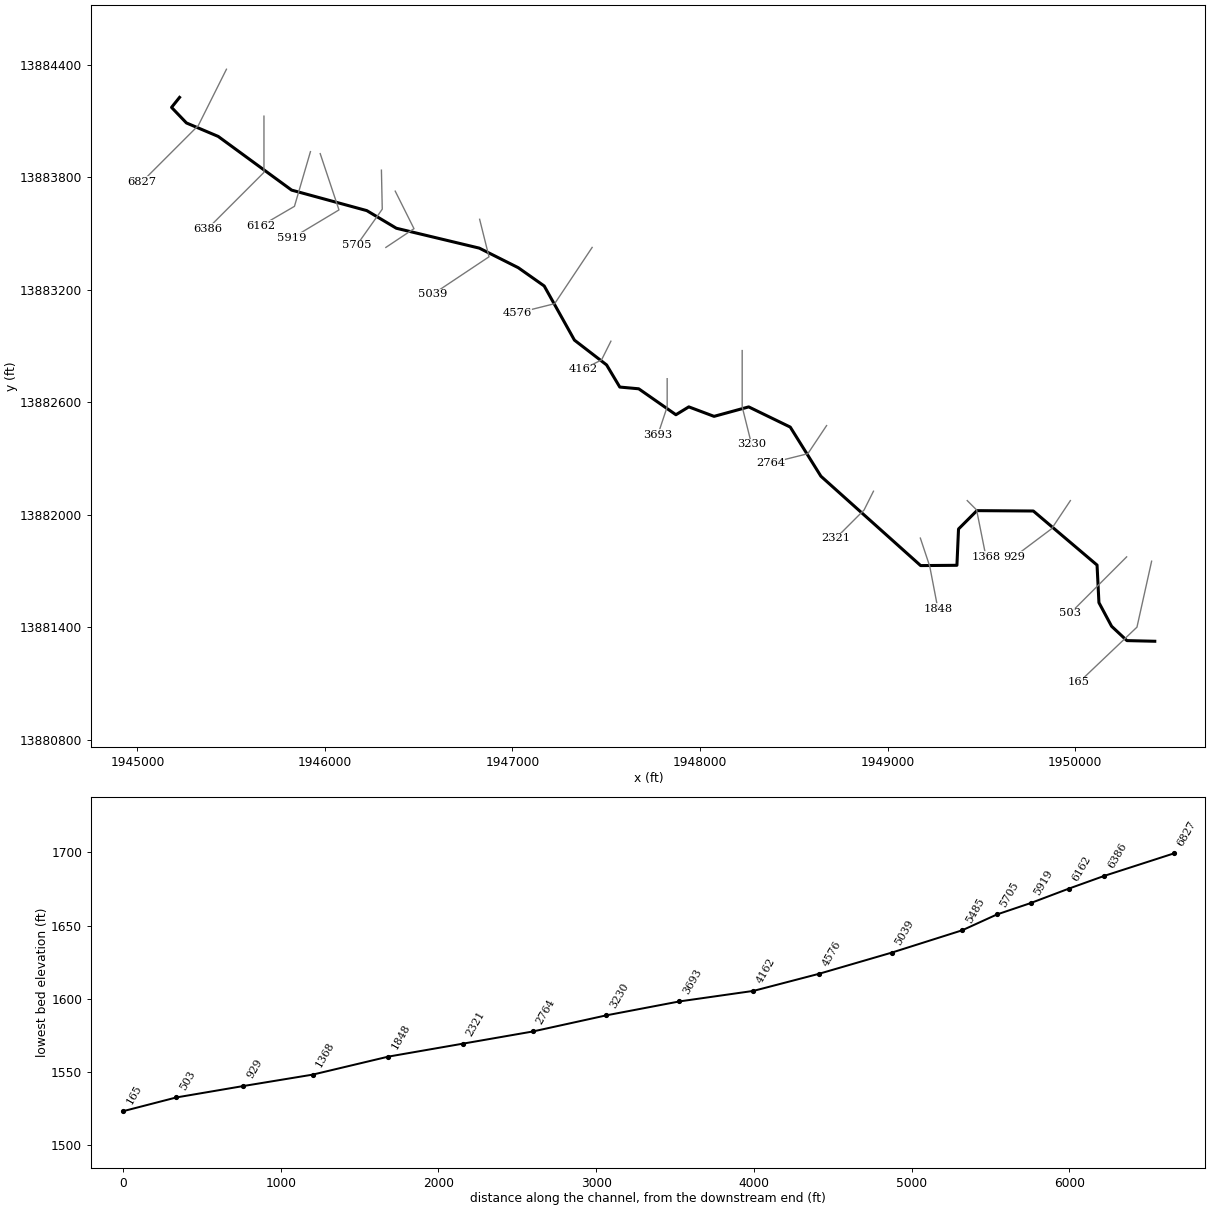
--- Stream0634.prj (project) ---

Proj Title=Stream0634 Base Level Engineering
Current Plan=p01
Default Exp/Contr=0.3,0.1
English Units
Geom File=g01
Flow File=f01
Plan File=p01
BEGIN DESCRIPTION:
Stream0634
END DESCRIPTION:

--- Stream0634.p01 (plan) ---

Plan Title=Multiple Run
Short Identifier=Multiple
Geom File=g01
Flow File=f01
Subcritical Flow
K Sum by GR= 0
Std Step Tol= 0.01
Critical Tol= 0.01
Num of Std Step Trials= 20
Max Error Tol= 0.3
Flow Tol Ratio= 0.001
Split Flow NTrial= 30
Split Flow Tol= 0.02
Split Flow Ratio= 0.02
Log Output Level= 0
Friction Slope Method= 1
Unsteady Friction Slope Method= 2
Unsteady Bridges Friction Slope Method= 1
Parabolic Critical Depth
Global Vel Dist=  1 , 1 , 1
Global Log Level= 0
CheckData=True
Encroach Param= -1, 0, 0, 0
BEGIN DESCRIPTION:
Multiple Run
END DESCRIPTION:

--- Stream0634.f01 (steady flow) ---

Flow Title=Multiple
Number of Profiles=7
Profile Names=10-year,25-year,50-year,1pct_min,100-year,1pct_plu,500-year
River Rch & RM= Stream0634,Reach-1,6827
     927    1564    2168    1456    2905    5797    5144
Boundary for River Rch & Prof#=Stream0634,Reach-1,1
Up Type=0
Dn Type=3
Dn Slope=0.005
Boundary for River Rch & Prof#=Stream0634,Reach-1,2
Up Type=0
Dn Type=3
Dn Slope=0.005
Boundary for River Rch & Prof#=Stream0634,Reach-1,3
Up Type=0
Dn Type=3
Dn Slope=0.005
Boundary for River Rch & Prof#=Stream0634,Reach-1,4
Up Type=0
Dn Type=3
Dn Slope=0.005
Boundary for River Rch & Prof#=Stream0634,Reach-1,5
Up Type=0
Dn Type=3
Dn Slope=0.005
Boundary for River Rch & Prof#=Stream0634,Reach-1,6
Up Type=0
Dn Type=3
Dn Slope=0.005
Boundary for River Rch & Prof#=Stream0634,Reach-1,7
Up Type=0
Dn Type=3
Dn Slope=0.005

--- Stream0634.g01 (geometry) ---

Geom Title=Existing Conditions

River Reach=Stream0634,Reach-1
Reach XY= 30
      1945225.00     13884225.00      1945182.24     13884171.65
      1945261.73     13884088.61      1945431.05     13884016.84
      1945822.58     13883730.54      1946223.44     13883621.24
      1946380.93     13883527.25      1946823.42     13883421.17
      1947031.05     13883316.84      1947169.38     13883219.38
      1947330.59     13882930.61      1947501.98     13882798.46
      1947572.33     13882680.42      1947673.41     13882671.17
      1947871.60     13882532.83      1947940.34     13882574.77
      1948075.00     13882524.19      1948259.73     13882574.63
      1948481.34     13882466.98      1948644.79     13882204.91
      1949176.47     13881728.53      1949370.00     13881730.00
      1949378.53     13881923.55      1949476.45     13882021.47
      1949777.45     13882019.53      1950117.19     13881731.19
      1950127.24     13881530.93      1950194.76     13881404.87
      1950276.44     13881328.49      1950425.00     13881325.00

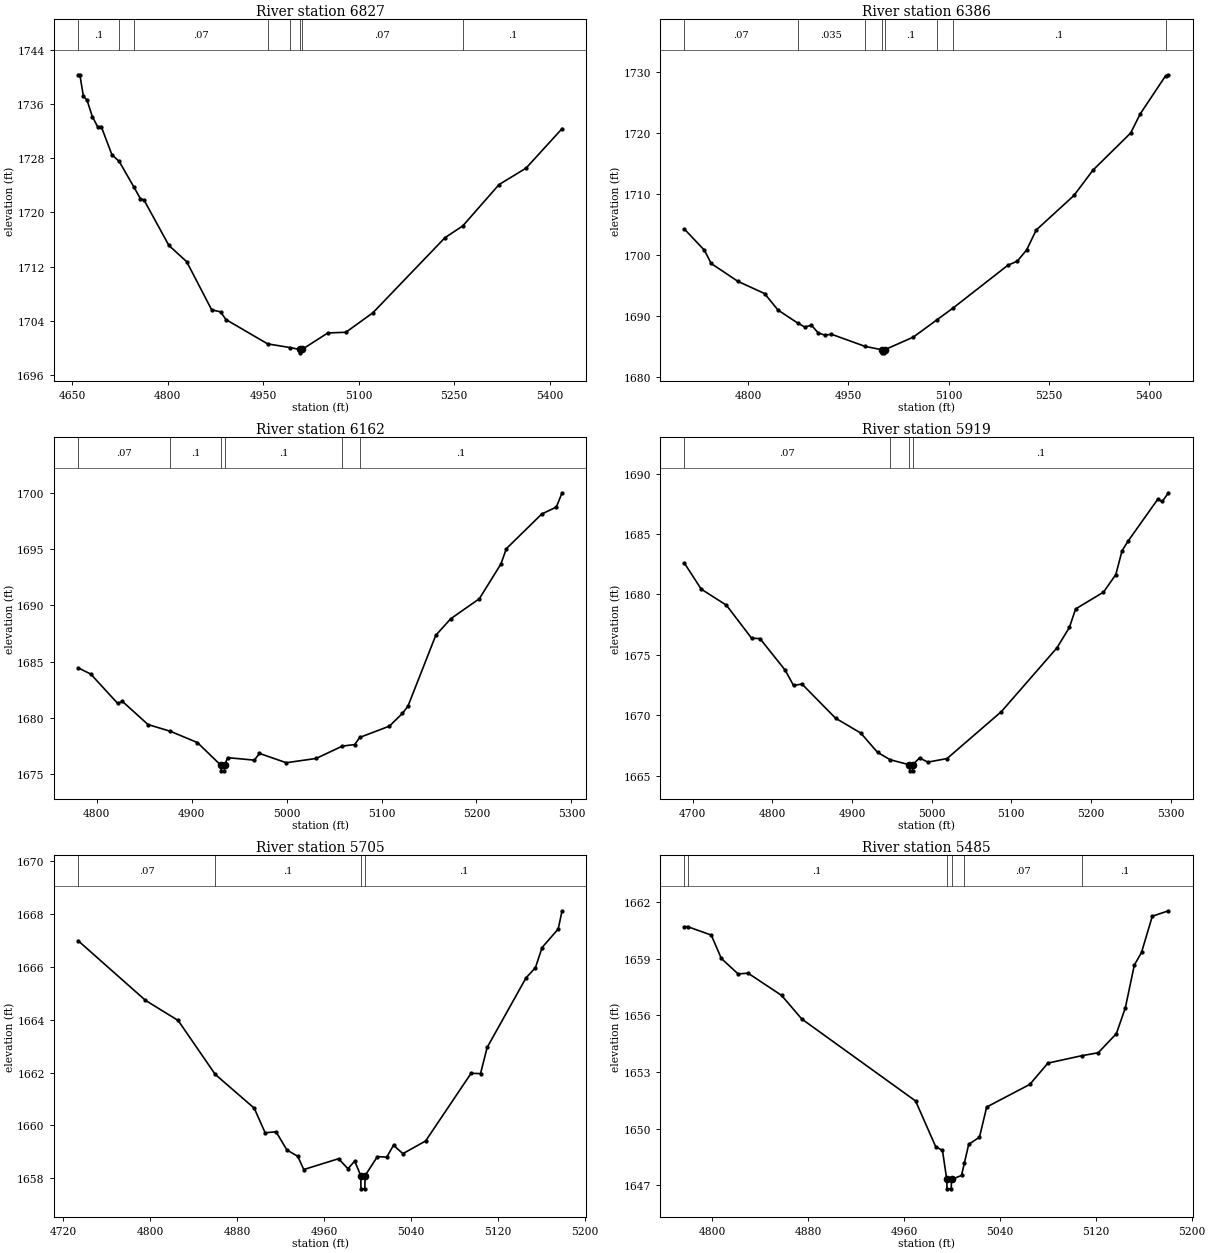
Type RM Length L Ch R = 1,6827,441,441,441
BEGIN DESCRIPTION:
Stream0634 15.0
END DESCRIPTION:
XS GIS Cut Line= 3
      1945475.02     13884375.03      1945325.00     13884075.00
      1945025.01     13883775.01
#Sta/Elev= 30
  4659.5 1740.29  4662.3 1740.29  4667.9 1737.13  4673.5 1736.57  4681.9 1734.14
  4690.3 1732.62  4695.9 1732.66  4712.6 1728.52  4724.1 1727.52  4747.5 1723.69
  4757.4 1722.03  4763.0 1721.84  4802.1 1715.14  4830.0 1712.75  4869.2 1705.66
  4883.1 1705.36  4891.5 1704.23  4957.0 1700.64  4992.1 1700.10  5007.1 1699.82
  5007.3 1699.32  5011.1 1699.82  5051.5 1702.25  5079.8 1702.35  5122.2 1705.22
  5235.4 1716.29  5263.3 1718.02  5320.2 1724.11  5362.6 1726.53  5419.2 1732.36
#Mann=8,-1,0
  4659.5     0.1       0  4724.1   0.035       0  4747.5    0.07       0
  4957.0   0.035       0  4992.1    0.07       0  5007.1    0.05       0
  5011.1    0.07       0  5263.3     0.1       0
Bank Sta=5007.1,5011.1
Exp/Cntr=0.3,0.1

Type RM Length L Ch R = 1,6386,224,224,224
BEGIN DESCRIPTION:
Stream0634 14.0
END DESCRIPTION:
XS GIS Cut Line= 3
      1945675.00     13884124.98      1945675.00     13883825.00
      1945375.03     13883525.03
#Sta/Elev= 30
  4704.8 1704.28  4734.8 1700.80  4744.8 1698.64  4784.8 1695.71  4824.8 1693.70
  4844.8 1691.00  4874.1 1688.88  4884.8 1688.21  4894.8 1688.52  4904.8 1687.27
  4914.8 1686.88  4924.8 1687.03  4974.8 1685.05  5000.3 1684.48  5000.5 1683.98
  5004.0 1683.98  5004.3 1684.48  5047.2 1686.56  5082.2 1689.37  5106.6 1691.32
  5188.6 1698.34  5202.8 1699.02  5216.9 1700.88  5231.1 1704.13  5287.6 1709.80
  5315.9 1713.94  5372.5 1720.05  5386.6 1723.16  5424.6 1729.42  5429.0 1729.60
#Mann=8,-1,0
  4704.8    0.07       0  4874.1   0.035       0  4974.8     0.1       0
  5000.3    0.05       0  5004.3     0.1       0  5082.2   0.035       0
  5106.6     0.1       0  5424.6    0.07       0
Bank Sta=5000.3,5004.3
Exp/Cntr=0.3,0.1

Type RM Length L Ch R = 1,6162,243,243,243
BEGIN DESCRIPTION:
Mapping XS b0c066f0
END DESCRIPTION:
XS GIS Cut Line= 3
      1945922.93     13883935.69      1945837.66     13883644.04
      1945659.70     13883540.22
#Sta/Elev= 30
  4780.3 1684.45  4793.7 1683.89  4821.9 1681.30  4827.1 1681.46  4854.0 1679.41
  4877.6 1678.81  4906.0 1677.81  4930.7 1675.80  4930.9 1675.30  4934.4 1675.30
  4934.7 1675.80  4937.9 1676.47  4966.1 1676.25  4971.3 1676.85  4999.6 1676.02
  5031.1 1676.40  5058.8 1677.50  5071.7 1677.63  5077.1 1678.27  5108.3 1679.27
  5122.0 1680.40  5127.8 1681.04  5157.1 1687.33  5172.8 1688.80  5203.0 1690.58
  5225.7 1693.66  5231.5 1695.03  5268.7 1698.10  5284.1 1698.72  5290.2 1699.99
#Mann=6,-1,0
  4780.3    0.07       0  4877.6     0.1       0  4930.7    0.05       0
  4934.7     0.1       0  5058.8    0.07       0  5077.1     0.1       0
Bank Sta=4930.7,4934.7
Exp/Cntr=0.3,0.1

Type RM Length L Ch R = 1,5919,214,214,214
BEGIN DESCRIPTION:
Stream0634 13.0
END DESCRIPTION:
XS GIS Cut Line= 3
      1945974.99     13883925.02      1946075.00     13883625.00
      1945824.99     13883475.00
#Sta/Elev= 30
  4689.5 1682.59  4710.6 1680.44  4742.2 1679.11  4773.8 1676.38  4784.4 1676.34
  4816.0 1673.73  4826.5 1672.46  4837.1 1672.58  4879.3 1669.75  4910.9 1668.52
  4932.0 1666.92  4947.8 1666.31  4972.1 1665.89  4972.4 1665.39  4975.9 1665.39
  4976.1 1665.89  4984.7 1666.46  4995.2 1666.11  5019.3 1666.41  5087.4 1670.29
  5157.3 1675.58  5172.9 1677.27  5180.7 1678.80  5215.7 1680.19  5231.2 1681.65
  5239.0 1683.62  5246.8 1684.44  5283.7 1687.87  5289.5 1687.71  5297.3 1688.42
#Mann=4,-1,0
  4689.5    0.07       0  4947.8     0.1       0  4972.1    0.05       0
  4976.1     0.1       0
Bank Sta=4972.1,4976.1
Exp/Cntr=0.3,0.1

Type RM Length L Ch R = 1,5705,220,220,220
BEGIN DESCRIPTION:
Mapping XS f946b9b8
END DESCRIPTION:
XS GIS Cut Line= 3
      1946301.35     13883836.96      1946305.83     13883628.96
      1946169.03     13883435.48
#Sta/Elev= 30
  4733.8 1666.99  4795.8 1664.73  4825.8 1663.97  4859.9 1661.93  4895.8 1660.65
  4905.8 1659.72  4915.8 1659.76  4925.8 1659.07  4935.8 1658.83  4941.3 1658.33
  4973.3 1658.74  4981.9 1658.36  4988.1 1658.65  4993.7 1658.10  4993.9 1657.60
  4997.4 1657.60  4997.7 1658.10  5009.0 1658.82  5017.6 1658.80  5023.8 1659.25
  5032.4 1658.93  5053.3 1659.41  5095.1 1661.97  5103.8 1661.96  5109.9 1662.95
  5145.6 1665.58  5154.3 1665.97  5160.4 1666.73  5175.2 1667.43  5178.8 1668.12
#Mann=4,-1,0
  4733.8    0.07       0  4859.9     0.1       0  4993.7    0.05       0
  4997.7     0.1       0
Bank Sta=4993.7,4997.7
Exp/Cntr=0.3,0.1

Type RM Length L Ch R = 1,5485,446,446,446
BEGIN DESCRIPTION:
Stream0634 12.0
END DESCRIPTION:
XS GIS Cut Line= 3
      1946374.98     13883725.03      1946475.00     13883525.00
      1946325.02     13883425.01
#Sta/Elev= 30
  4776.7 1660.71  4779.3 1660.71  4799.1 1660.26  4807.5 1659.02  4821.5 1658.20
  4829.8 1658.24  4857.8 1657.06  4874.6 1655.81  4969.6 1651.46  4986.4 1649.03
  4992.0 1648.84  4995.6 1647.30  4995.8 1646.80  4999.3 1646.80  4999.6 1647.30
  5007.9 1647.51  5010.3 1648.17  5013.9 1649.16  5022.9 1649.54  5028.9 1651.14
  5064.9 1652.34  5080.0 1653.47  5108.1 1653.86  5122.0 1654.02  5137.1 1655.03
  5144.6 1656.40  5152.1 1658.67  5158.1 1659.34  5167.1 1661.26  5180.6 1661.55
#Mann=6,-1,0
  4776.7    0.07       0  4779.3     0.1       0  4995.6    0.05       0
  4999.6     0.1       0  5010.3    0.07       0  5108.1     0.1       0
Bank Sta=4995.6,4999.6
Exp/Cntr=0.3,0.1

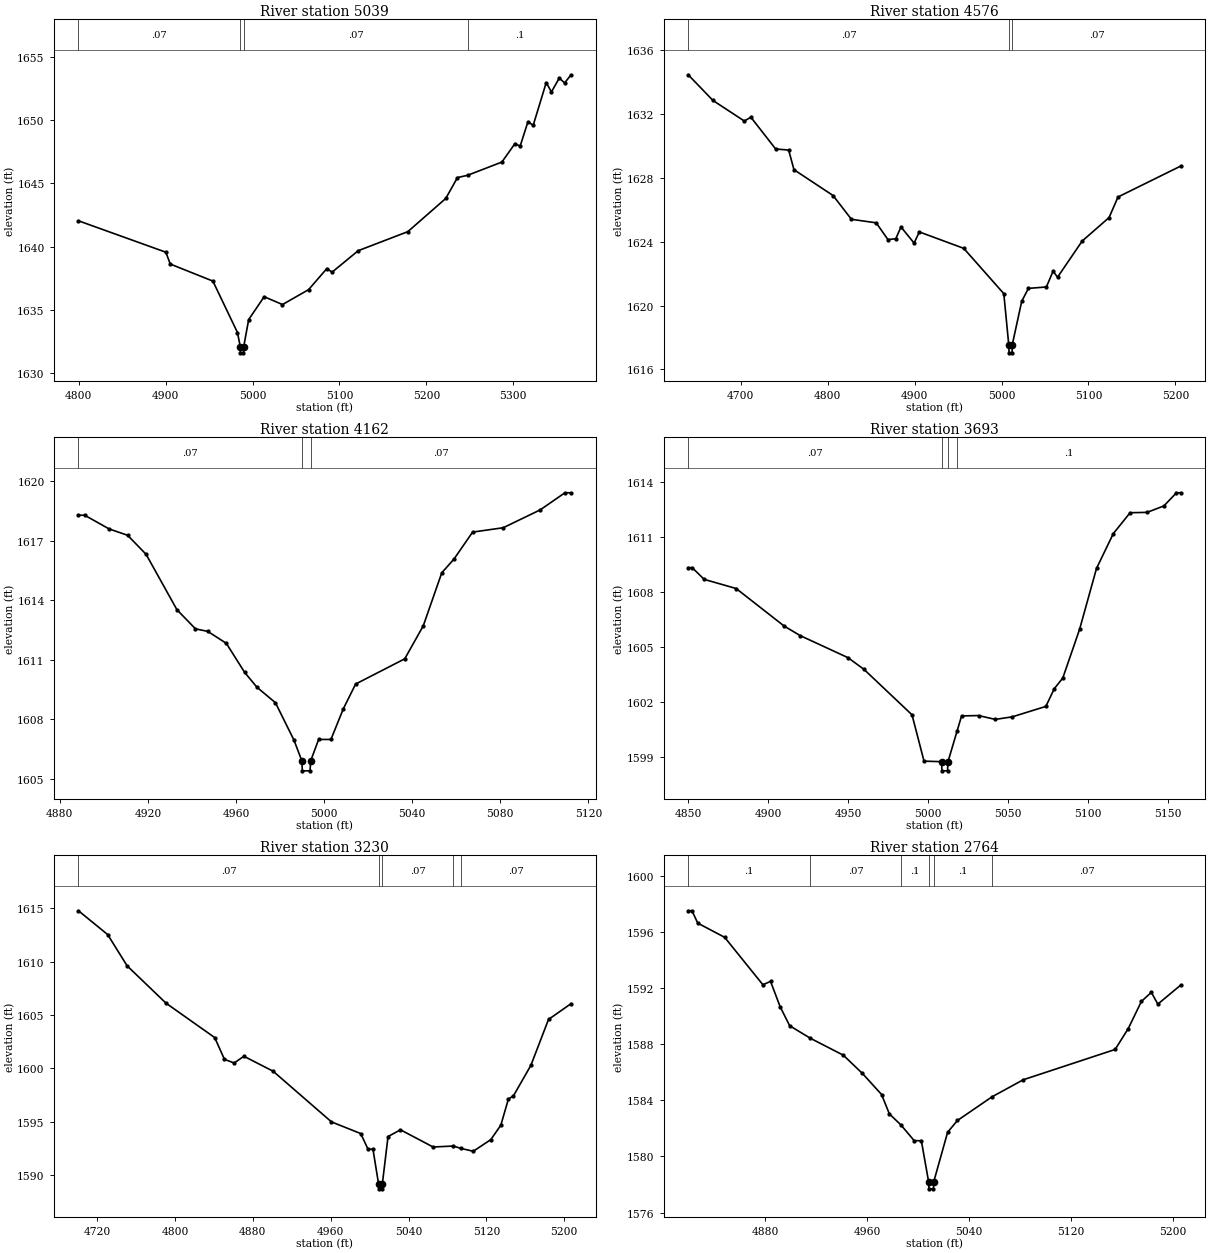
Type RM Length L Ch R = 1,5039,463,463,463
BEGIN DESCRIPTION:
Stream0634 11.0
END DESCRIPTION:
XS GIS Cut Line= 3
      1946825.01     13883574.97      1946875.00     13883375.00
      1946574.99     13883174.99
#Sta/Elev= 30
  4799.8 1642.04  4900.3 1639.55  4905.4 1638.61  4954.4 1637.26  4982.7 1633.18
  4985.9 1632.07  4986.1 1631.57  4989.6 1631.57  4989.9 1632.07  4995.6 1634.21
  5013.4 1636.02  5034.5 1635.40  5064.5 1636.58  5085.5 1638.25  5091.6 1637.97
  5121.6 1639.67  5178.7 1641.18  5222.3 1643.81  5235.8 1645.47  5247.5 1645.65
  5286.9 1646.70  5301.9 1648.16  5307.9 1647.96  5316.9 1649.90  5322.9 1649.61
  5337.9 1653.00  5343.9 1652.26  5353.0 1653.37  5359.0 1652.97  5366.5 1653.62
#Mann=4,-1,0
  4799.8    0.07       0  4985.9    0.05       0  4989.9    0.07       0
  5247.5     0.1       0
Bank Sta=4985.9,4989.9
Exp/Cntr=0.3,0.1

Type RM Length L Ch R = 1,4576,414,414,414
BEGIN DESCRIPTION:
Stream0634 10.0
END DESCRIPTION:
XS GIS Cut Line= 3
      1947424.98     13883424.97      1947225.00     13883125.00
      1947024.98     13883074.99
#Sta/Elev= 30
  4639.5 1634.47  4668.0 1632.86  4704.1 1631.57  4711.6 1631.81  4740.1 1629.82
  4755.1 1629.75  4761.2 1628.52  4806.2 1626.90  4827.3 1625.41  4855.8 1625.19
  4869.3 1624.14  4878.3 1624.19  4884.3 1624.93  4899.4 1623.92  4905.4 1624.62
  4956.5 1623.59  5002.6 1620.75  5008.3 1617.54  5008.6 1617.04  5012.1 1617.04
  5012.3 1617.54  5023.2 1620.27  5030.9 1621.08  5051.6 1621.17  5059.3 1622.16
  5064.4 1621.78  5092.8 1624.05  5123.7 1625.52  5134.0 1626.81  5206.2 1628.75
#Mann=3,-1,0
  4639.5    0.07       0  5008.3    0.05       0  5012.3    0.07       0
Bank Sta=5008.3,5012.3
Exp/Cntr=0.3,0.1

Type RM Length L Ch R = 1,4162,469,469,469
BEGIN DESCRIPTION:
Stream0634 9.0
END DESCRIPTION:
XS GIS Cut Line= 3
      1947524.99     13882924.98      1947475.00     13882825.00
      1947374.98     13882774.99
#Sta/Elev= 30
  4888.5 1618.28  4891.3 1618.28  4902.4 1617.59  4910.8 1617.27  4919.2 1616.31
  4933.2 1613.52  4941.6 1612.56  4947.2 1612.43  4955.6 1611.83  4963.9 1610.37
  4969.5 1609.62  4977.9 1608.84  4986.3 1606.96  4989.9 1605.91  4990.1 1605.41
  4993.6 1605.41  4993.9 1605.91  4997.5 1606.99  5003.1 1606.99  5008.7 1608.53
  5014.3 1609.78  5036.6 1611.05  5045.0 1612.71  5053.4 1615.38  5059.0 1616.08
  5067.4 1617.43  5081.3 1617.65  5098.1 1618.55  5109.3 1619.41  5112.1 1619.41
#Mann=3,-1,0
  4888.5    0.07       0  4989.9    0.05       0  4993.9    0.07       0
Bank Sta=4989.9,4993.9
Exp/Cntr=0.3,0.1

Type RM Length L Ch R = 1,3693,463,463,463
BEGIN DESCRIPTION:
Stream0634 8.0
END DESCRIPTION:
XS GIS Cut Line= 3
      1947825.00     13882724.96      1947825.00     13882575.00
      1947774.99     13882424.97
#Sta/Elev= 30
  4849.9 1609.32  4852.4 1609.32  4859.9 1608.68  4879.9 1608.18  4909.9 1606.13
  4919.9 1605.61  4949.9 1604.40  4959.9 1603.76  4989.9 1601.28  4997.4 1598.75
  5008.4 1598.72  5008.6 1598.22  5012.1 1598.22  5012.4 1598.72  5018.0 1600.37
  5020.9 1601.22  5031.5 1601.24  5042.0 1601.03  5052.6 1601.17  5073.6 1601.74
  5078.9 1602.71  5084.2 1603.29  5094.7 1605.95  5105.3 1609.28  5115.8 1611.18
  5126.3 1612.32  5136.9 1612.34  5147.4 1612.69  5155.3 1613.41  5158.0 1613.41
#Mann=4,-1,0
  4849.9    0.07       0  5008.4    0.05       0  5012.4    0.07       0
  5018.0     0.1       0
Bank Sta=5008.4,5012.4
Exp/Cntr=0.3,0.1

Type RM Length L Ch R = 1,3230,466,466,466
BEGIN DESCRIPTION:
Stream0634 7.0
END DESCRIPTION:
XS GIS Cut Line= 3
      1948225.00     13882875.02      1948225.00     13882575.00
      1948275.01     13882374.98
#Sta/Elev= 30
  4700.8 1614.77  4730.8 1612.54  4750.8 1609.61  4790.8 1606.11  4840.8 1602.89
  4850.8 1600.85  4860.8 1600.51  4870.8 1601.14  4900.8 1599.74  4960.8 1594.99
  4990.8 1593.90  4998.3 1592.44  5003.4 1592.44  5009.1 1589.22  5009.4 1588.72
  5012.9 1588.72  5013.1 1589.22  5018.9 1593.62  5031.7 1594.25  5065.2 1592.64
  5086.0 1592.73  5093.7 1592.51  5106.5 1592.24  5124.5 1593.33  5134.8 1594.68
  5142.6 1597.14  5147.7 1597.42  5165.7 1600.29  5183.8 1604.59  5207.0 1606.07
#Mann=5,-1,0
  4700.8    0.07       0  5009.1    0.05       0  5013.1    0.07       0
  5086.0     0.1       0  5093.7    0.07       0
Bank Sta=5009.1,5013.1
Exp/Cntr=0.3,0.1

Type RM Length L Ch R = 1,2764,443,443,443
BEGIN DESCRIPTION:
Stream0634 6.0
END DESCRIPTION:
XS GIS Cut Line= 3
      1948675.01     13882475.01      1948575.00     13882325.00
      1948375.05     13882275.01
#Sta/Elev= 30
  4819.7 1597.50  4822.7 1597.50  4827.2 1596.62  4848.3 1595.61  4878.3 1592.23
  4884.3 1592.47  4891.8 1590.67  4899.3 1589.31  4915.5 1588.42  4941.4 1587.21
  4956.4 1585.91  4971.4 1584.41  4977.5 1583.03  4986.5 1582.25  4997.0 1581.12
  5002.6 1581.12  5008.3 1578.19  5008.6 1577.69  5012.1 1577.69  5012.3 1578.19
  5023.2 1581.72  5030.9 1582.56  5058.1 1584.25  5082.5 1585.46  5154.6 1587.62
  5164.9 1589.11  5175.2 1591.04  5183.0 1591.69  5188.1 1590.85  5206.1 1592.21
#Mann=6,-1,0
  4819.7     0.1       0  4915.5    0.07       0  4986.5     0.1       0
  5008.3    0.05       0  5012.3     0.1       0  5058.1    0.07       0
Bank Sta=5008.3,5012.3
Exp/Cntr=0.3,0.1

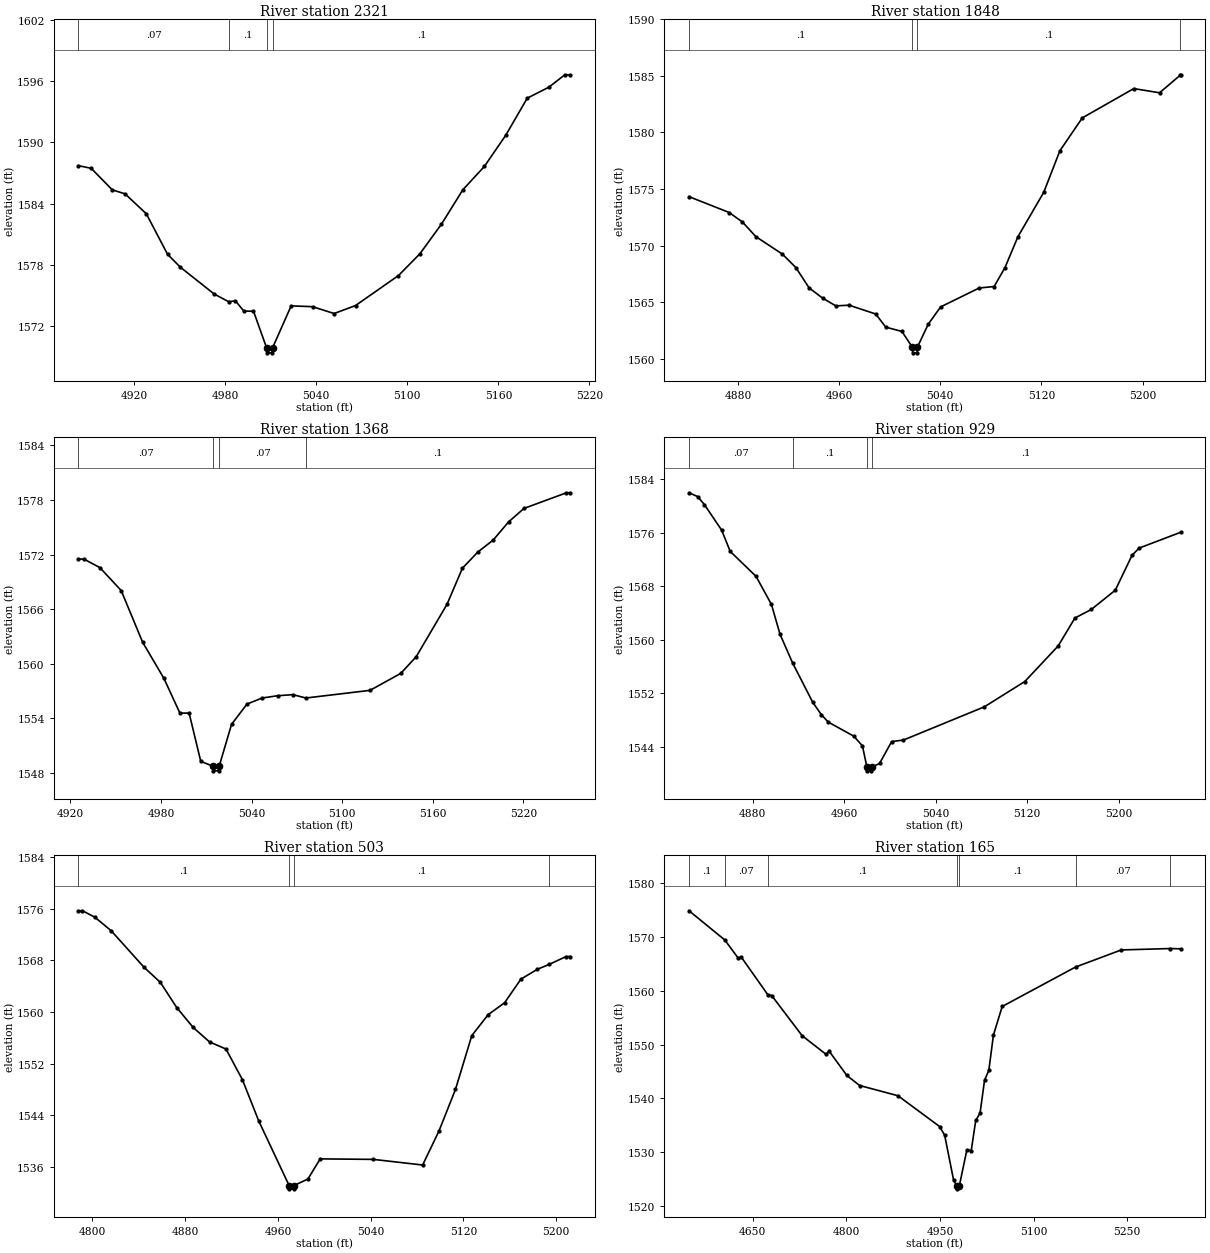
Type RM Length L Ch R = 1,2321,473,473,473
BEGIN DESCRIPTION:
Stream0634 5.0
END DESCRIPTION:
XS GIS Cut Line= 3
      1948924.99     13882124.99      1948875.00     13882025.00
      1948725.02     13881875.02
#Sta/Elev= 30
  4883.4 1587.71  4891.8 1587.45  4905.7 1585.34  4914.1 1584.95  4928.1 1583.00
  4942.1 1579.03  4950.5 1577.77  4972.8 1575.14  4982.3 1574.39  4986.8 1574.47
  4992.4 1573.46  4998.7 1573.46  5007.3 1569.88  5007.6 1569.38  5011.1 1569.38
  5011.3 1569.88  5023.5 1573.98  5037.6 1573.90  5051.8 1573.23  5065.9 1574.01
  5094.2 1576.95  5108.3 1579.08  5122.5 1581.98  5136.6 1585.35  5150.8 1587.64
  5164.9 1590.70  5179.0 1594.32  5193.2 1595.39  5203.8 1596.61  5207.3 1596.61
#Mann=4,-1,0
  4883.4    0.07       0  4982.3     0.1       0  5007.3    0.05       0
  5011.3     0.1       0
Bank Sta=5007.3,5011.3
Exp/Cntr=0.3,0.1

Type RM Length L Ch R = 1,1848,480,480,480
BEGIN DESCRIPTION:
Stream0634 4.0
END DESCRIPTION:
XS GIS Cut Line= 3
      1949174.99     13881875.04      1949225.00     13881725.00
      1949268.50     13881498.50
#Sta/Elev= 30
  4841.4 1574.32  4873.1 1572.92  4883.6 1572.08  4894.2 1570.79  4915.2 1569.24
  4925.8 1568.06  4936.3 1566.26  4946.9 1565.36  4957.4 1564.67  4967.9 1564.73
  4989.0 1563.95  4996.9 1562.79  5009.7 1562.41  5017.9 1561.02  5018.2 1560.52
  5021.7 1560.52  5021.9 1561.02  5030.6 1563.07  5040.3 1564.58  5070.8 1566.25
  5082.6 1566.38  5091.2 1568.06  5101.4 1570.78  5121.8 1574.70  5134.6 1578.38
  5152.3 1581.28  5193.0 1583.87  5213.4 1583.50  5229.8 1585.06  5230.2 1585.09
#Mann=4,-1,0
  4841.4     0.1       0  5017.9    0.05       0  5021.9     0.1       0
  5229.8    0.07       0
Bank Sta=5017.9,5021.9
Exp/Cntr=0.3,0.1

Type RM Length L Ch R = 1,1368,439,439,439
BEGIN DESCRIPTION:
Stream0634 3.0
END DESCRIPTION:
XS GIS Cut Line= 3
      1949424.97     13882075.03      1949475.00     13882025.00
      1949525.00     13881775.01
#Sta/Elev= 30
  4925.3 1571.50  4928.9 1571.50  4939.5 1570.56  4953.6 1568.04  4967.8 1562.36
  4981.9 1558.38  4992.5 1554.56  4998.6 1554.56  5006.3 1549.26  5014.5 1548.71
  5014.7 1548.21  5018.2 1548.21  5018.5 1548.71  5026.7 1553.32  5036.9 1555.55
  5047.0 1556.22  5057.2 1556.47  5067.4 1556.59  5075.9 1556.22  5118.4 1557.06
  5138.8 1558.93  5149.0 1560.76  5169.4 1566.52  5179.6 1570.49  5189.8 1572.27
  5200.0 1573.59  5210.2 1575.59  5220.4 1577.07  5248.5 1578.79  5251.0 1578.79
#Mann=4,-1,0
  4925.3    0.07       0  5014.5    0.05       0  5018.5    0.07       0
  5075.9     0.1       0
Bank Sta=5014.5,5018.5
Exp/Cntr=0.3,0.1

Type RM Length L Ch R = 1,929,426,426,426
BEGIN DESCRIPTION:
Stream0634 2.0
END DESCRIPTION:
XS GIS Cut Line= 3
      1949974.99     13882074.99      1949875.00     13881925.00
      1949674.97     13881774.98
#Sta/Elev= 30
  4824.2 1581.95  4831.7 1581.38  4837.7 1580.17  4852.7 1576.37  4860.2 1573.20
  4882.8 1569.47  4896.3 1565.27  4903.8 1560.82  4914.8 1556.53  4932.4 1550.67
  4939.9 1548.83  4945.9 1547.72  4968.4 1545.60  4975.9 1544.15  4979.9 1540.93
  4980.2 1540.43  4983.7 1540.43  4983.9 1540.93  4990.9 1541.54  5001.5 1544.80
  5011.8 1545.03  5082.6 1549.99  5118.0 1553.77  5147.2 1559.08  5161.8 1563.25
  5176.3 1564.54  5197.2 1567.41  5211.8 1572.61  5218.0 1573.69  5254.5 1576.06
#Mann=4,-1,0
  4824.2    0.07       0  4914.8     0.1       0  4979.9    0.05       0
  4983.9     0.1       0
Bank Sta=4979.9,4983.9
Exp/Cntr=0.3,0.1

Type RM Length L Ch R = 1,503,338,338,338
BEGIN DESCRIPTION:
Stream0634 1.0
END DESCRIPTION:
XS GIS Cut Line= 3
      1950274.99     13881774.99      1950125.00     13881625.00
      1949974.97     13881474.97
#Sta/Elev= 30
  4787.9 1575.67  4791.4 1575.67  4802.0 1574.68  4816.2 1572.57  4844.5 1566.92
  4858.6 1564.58  4872.7 1560.68  4886.9 1557.60  4901.0 1555.36  4915.2 1554.26
  4929.3 1549.54  4943.5 1543.11  4969.7 1533.11  4970.0 1532.61  4973.5 1532.61
  4973.7 1533.11  4985.9 1534.13  4996.5 1537.25  5042.4 1537.17  5084.9 1536.30
  5099.0 1541.58  5113.2 1548.00  5127.3 1556.34  5141.4 1559.58  5155.6 1561.43
  5169.7 1565.09  5183.9 1566.61  5194.0 1567.36  5208.6 1568.58  5212.2 1568.58
#Mann=4,-1,0
  4787.9     0.1       0  4969.7    0.05       0  4973.7     0.1       0
  5194.0    0.07       0
Bank Sta=4969.7,4973.7
Exp/Cntr=0.3,0.1

Type RM Length L Ch R = 1,165,0,0,0
BEGIN DESCRIPTION:
Stream0634 0.0
END DESCRIPTION:
XS GIS Cut Line= 3
      1950408.15     13881751.86      1950330.02     13881400.28
      1950019.85     13881105.29
#Sta/Elev= 30
  4547.9 1574.89  4605.2 1569.46  4626.5 1566.11  4631.7 1566.26  4674.2 1559.27
  4680.3 1559.14  4729.1 1551.67  4767.4 1548.21  4772.5 1548.79  4800.8 1544.27
  4821.3 1542.41  4882.7 1540.51  4949.5 1534.78  4957.6 1533.15  4971.8 1524.87
  4977.0 1523.70  4977.3 1523.20  4981.0 1523.70  4993.2 1530.47  5000.1 1530.28
  5007.4 1535.92  5014.3 1537.27  5021.5 1543.40  5028.4 1545.24  5035.7 1551.77
  5049.8 1557.10  5167.3 1564.43  5240.7 1567.61  5318.8 1567.87  5336.1 1567.82
#Mann=7,-1,0
  4547.9     0.1       0  4605.2    0.07       0  4674.2     0.1       0
  4977.0    0.05       0  4981.0     0.1       0  5167.3    0.07       0
  5318.8   0.035       0
Bank Sta=4977,4981
Exp/Cntr=0.3,0.1

Chan Stop Cuts=-1