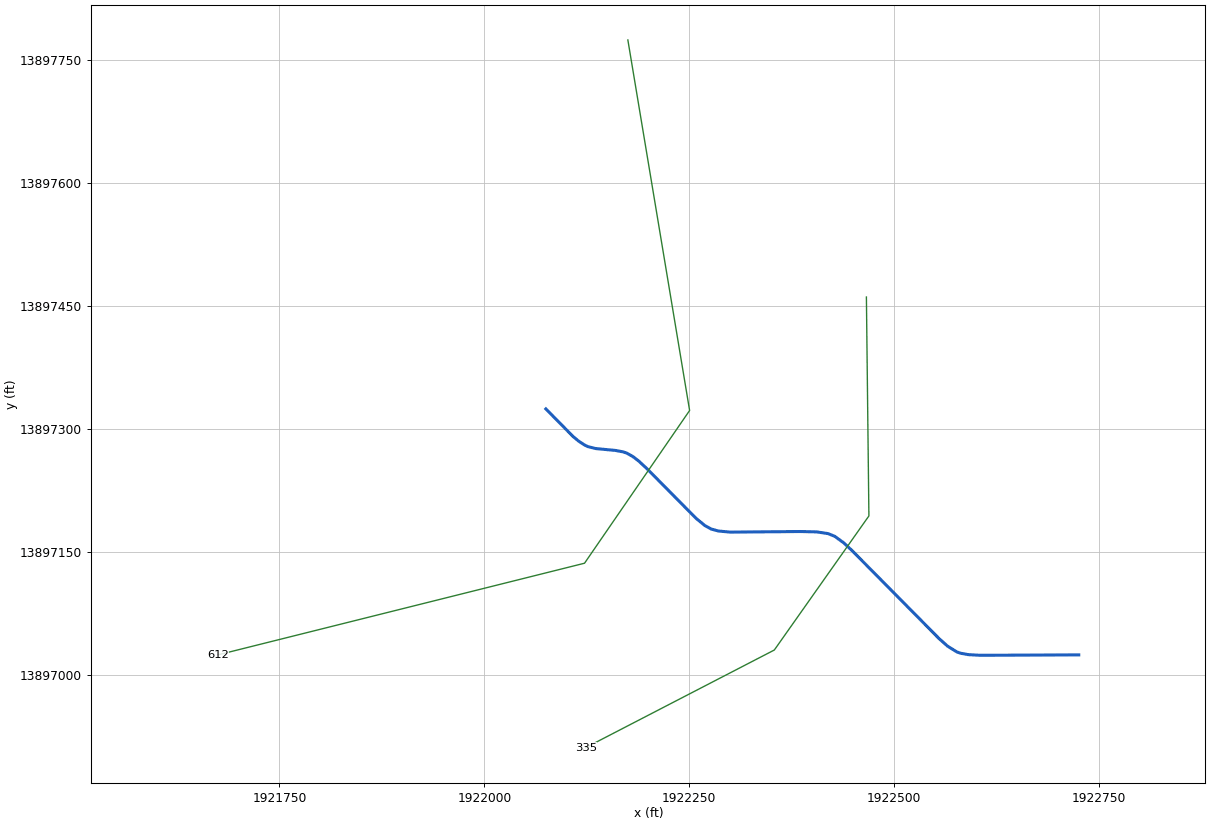
--- Stream0635.prj (project) ---

Proj Title=Stream0635 Base Level Engineering
Current Plan=p01
Default Exp/Contr=0.3,0.1
English Units
Geom File=g01
Flow File=f01
Plan File=p01
BEGIN DESCRIPTION:
Stream0635
END DESCRIPTION:

--- Stream0635.p01 (plan) ---

Plan Title=Multiple Run
Short Identifier=Multiple
Geom File=g01
Flow File=f01
Subcritical Flow
K Sum by GR= 0
Std Step Tol= 0.01
Critical Tol= 0.01
Num of Std Step Trials= 20
Max Error Tol= 0.3
Flow Tol Ratio= 0.001
Split Flow NTrial= 30
Split Flow Tol= 0.02
Split Flow Ratio= 0.02
Log Output Level= 0
Friction Slope Method= 1
Unsteady Friction Slope Method= 2
Unsteady Bridges Friction Slope Method= 1
Parabolic Critical Depth
Global Vel Dist=  1 , 1 , 1
Global Log Level= 0
CheckData=True
Encroach Param= -1, 0, 0, 0
BEGIN DESCRIPTION:
Multiple Run
END DESCRIPTION:

--- Stream0635.f01 (steady flow) ---

Flow Title=Multiple
Number of Profiles=7
Profile Names=10-year,25-year,50-year,1pct_min,100-year,1pct_plu,500-year
River Rch & RM= Stream0635,Reach-1,612
     260     398     517     327     652    1302    1019
Boundary for River Rch & Prof#=Stream0635,Reach-1,1
Up Type=0
Dn Type=3
Dn Slope=0.005
Boundary for River Rch & Prof#=Stream0635,Reach-1,2
Up Type=0
Dn Type=3
Dn Slope=0.005
Boundary for River Rch & Prof#=Stream0635,Reach-1,3
Up Type=0
Dn Type=3
Dn Slope=0.005
Boundary for River Rch & Prof#=Stream0635,Reach-1,4
Up Type=0
Dn Type=3
Dn Slope=0.005
Boundary for River Rch & Prof#=Stream0635,Reach-1,5
Up Type=0
Dn Type=3
Dn Slope=0.005
Boundary for River Rch & Prof#=Stream0635,Reach-1,6
Up Type=0
Dn Type=3
Dn Slope=0.005
Boundary for River Rch & Prof#=Stream0635,Reach-1,7
Up Type=0
Dn Type=3
Dn Slope=0.005

--- Stream0635.g01 (geometry) ---

Geom Title=Existing Conditions

River Reach=Stream0635,Reach-1
Reach XY= 30
      1922075.00     13897325.00      1922108.08     13897291.42
      1922115.21     13897285.50      1922122.65     13897280.70
      1922126.62     13897278.91      1922135.68     13897276.65
      1922159.74     13897274.36      1922169.03     13897272.65
      1922173.42     13897271.18      1922181.08     13897266.93
      1922188.22     13897261.40      1922198.45     13897251.95
      1922258.25     13897191.46      1922268.82     13897182.83
      1922276.47     13897178.55      1922285.44     13897176.07
      1922299.89     13897174.73      1922385.19     13897175.45
      1922405.01     13897175.02      1922419.14     13897172.93
      1922427.45     13897169.53      1922438.32     13897161.63
      1922448.53     13897152.14      1922554.84     13897044.60
      1922565.19     13897035.46      1922576.45     13897028.50
      1922580.83     13897027.01      1922590.13     13897025.31
      1922604.79     13897024.48      1922725.00     13897025.00

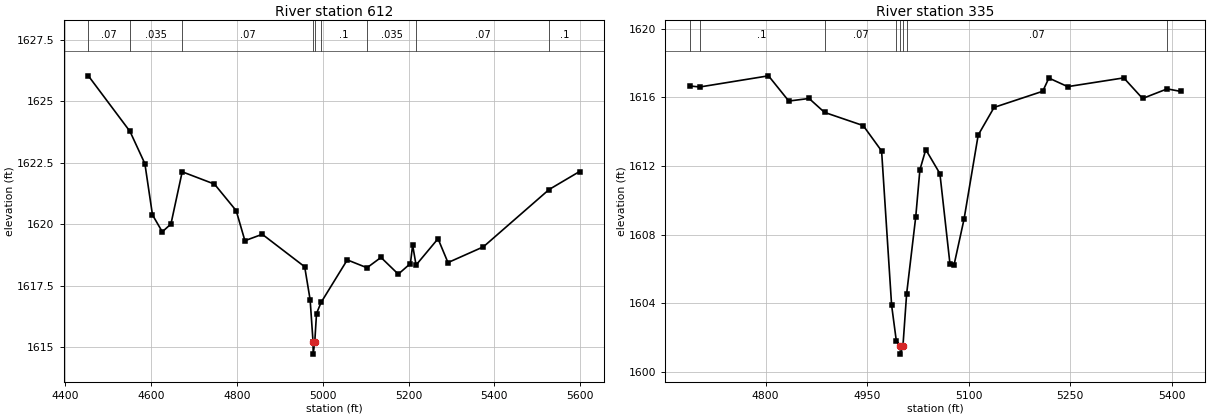
Type RM Length L Ch R = 1,612,277,277,277
BEGIN DESCRIPTION:
Stream0635 1.0
END DESCRIPTION:
XS GIS Cut Line= 4
      1922175.00     13897775.01      1922250.32     13897323.08
      1922122.15     13897136.79      1921674.99     13897025.00
#Sta/Elev= 30
  4453.4 1626.03  4550.5 1623.77  4585.2 1622.46  4602.9 1620.38  4625.8 1619.69
  4646.0 1620.01  4672.2 1622.13  4747.4 1621.63  4798.1 1620.55  4818.4 1619.33
  4858.9 1619.59  4957.8 1618.27  4970.5 1616.93  4977.3 1615.22  4977.6 1614.72
  4981.3 1615.22  4985.4 1616.37  4996.0 1616.82  5057.1 1618.55  5103.1 1618.23
  5135.7 1618.65  5176.0 1617.97  5204.3 1618.40  5209.5 1619.15  5217.5 1618.34
  5268.7 1619.41  5291.9 1618.44  5374.4 1619.08  5527.7 1621.41  5598.6 1622.14
#Mann=9,-1,0
  4453.4    0.07       0  4550.5   0.035       0  4672.2    0.07       0
  4977.3    0.05       0  4981.3    0.07       0  4996.0     0.1       0
  5103.1   0.035       0  5217.5    0.07       0  5527.7     0.1       0
Bank Sta=4977.3,4981.3
Exp/Cntr=0.3,0.1

Type RM Length L Ch R = 1,335,0,0,0
BEGIN DESCRIPTION:
Stream0635 0.0
END DESCRIPTION:
XS GIS Cut Line= 4
      1922465.95     13897461.49      1922469.00     13897194.47
      1922353.64     13897030.93      1922123.67     13896911.93
#Sta/Elev= 30
  4687.7 1616.67  4702.6 1616.61  4804.2 1617.26  4834.2 1615.79  4864.2 1615.94
  4887.0 1615.13  4944.2 1614.36  4971.4 1612.88  4986.2 1603.89  4993.1 1601.83
  4999.0 1601.54  4999.2 1601.04  5003.0 1601.54  5008.4 1604.55  5021.9 1609.05
  5028.0 1611.78  5036.7 1612.96  5057.6 1611.56  5072.4 1606.32  5078.5 1606.24
  5093.3 1608.91  5114.2 1613.81  5137.7 1615.42  5209.6 1616.36  5218.7 1617.13
  5246.5 1616.63  5329.4 1617.14  5357.2 1615.94  5393.6 1616.50  5413.8 1616.35
#Mann=8,-1,0
  4687.7    0.07       0  4702.6     0.1       0  4887.0    0.07       0
  4993.1     0.1       0  4999.0    0.05       0  5003.0     0.1       0
  5008.4    0.07       0  5393.6   0.035       0
Bank Sta=4999,5003
Exp/Cntr=0.3,0.1

Chan Stop Cuts=-1