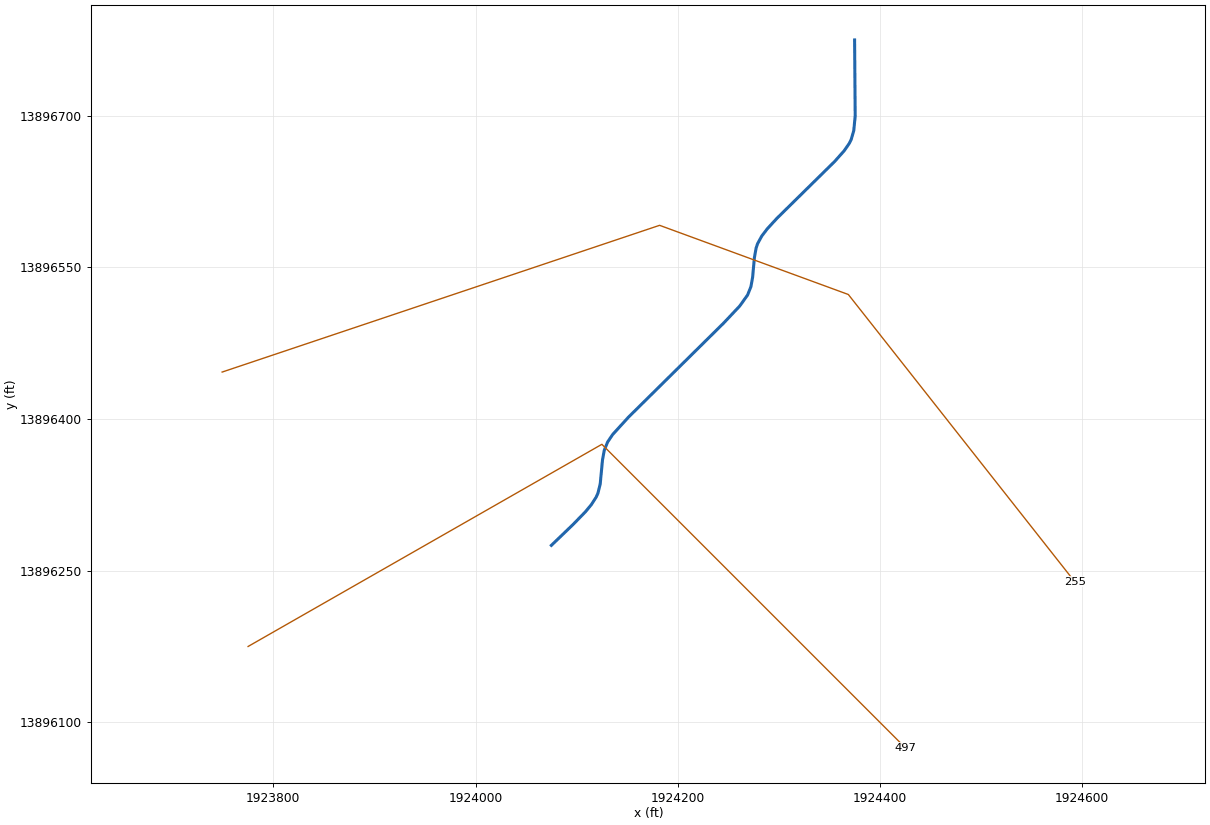
--- Stream0636.prj (project) ---

Proj Title=Stream0636 Base Level Engineering
Current Plan=p01
Default Exp/Contr=0.3,0.1
English Units
Geom File=g01
Flow File=f01
Plan File=p01
BEGIN DESCRIPTION:
Stream0636
END DESCRIPTION:

--- Stream0636.p01 (plan) ---

Plan Title=Multiple Run
Short Identifier=Multiple
Geom File=g01
Flow File=f01
Subcritical Flow
K Sum by GR= 0
Std Step Tol= 0.01
Critical Tol= 0.01
Num of Std Step Trials= 20
Max Error Tol= 0.3
Flow Tol Ratio= 0.001
Split Flow NTrial= 30
Split Flow Tol= 0.02
Split Flow Ratio= 0.02
Log Output Level= 0
Friction Slope Method= 1
Unsteady Friction Slope Method= 2
Unsteady Bridges Friction Slope Method= 1
Parabolic Critical Depth
Global Vel Dist=  1 , 1 , 1
Global Log Level= 0
CheckData=True
Encroach Param= -1, 0, 0, 0
BEGIN DESCRIPTION:
Multiple Run
END DESCRIPTION:

--- Stream0636.f01 (steady flow) ---

Flow Title=Multiple
Number of Profiles=7
Profile Names=10-year,25-year,50-year,1pct_min,100-year,1pct_plu,500-year
River Rch & RM= Stream0636,Reach-1,497
     384     609     810     524    1046    2087    1713
Boundary for River Rch & Prof#=Stream0636,Reach-1,1
Up Type=0
Dn Type=3
Dn Slope=0.005
Boundary for River Rch & Prof#=Stream0636,Reach-1,2
Up Type=0
Dn Type=3
Dn Slope=0.005
Boundary for River Rch & Prof#=Stream0636,Reach-1,3
Up Type=0
Dn Type=3
Dn Slope=0.005
Boundary for River Rch & Prof#=Stream0636,Reach-1,4
Up Type=0
Dn Type=3
Dn Slope=0.005
Boundary for River Rch & Prof#=Stream0636,Reach-1,5
Up Type=0
Dn Type=3
Dn Slope=0.005
Boundary for River Rch & Prof#=Stream0636,Reach-1,6
Up Type=0
Dn Type=3
Dn Slope=0.005
Boundary for River Rch & Prof#=Stream0636,Reach-1,7
Up Type=0
Dn Type=3
Dn Slope=0.005

--- Stream0636.g01 (geometry) ---

Geom Title=Existing Conditions

River Reach=Stream0636,Reach-1
Reach XY= 30
      1924075.00     13896275.00      1924096.22     13896295.39
      1924108.58     13896308.08      1924114.50     13896315.21
      1924119.29     13896322.65      1924121.09     13896326.62
      1924123.34     13896335.69      1924125.63     13896359.74
      1924127.34     13896369.03      1924130.72     13896377.34
      1924135.70     13896384.71      1924151.29     13896401.82
      1924245.38     13896494.84      1924261.37     13896511.79
      1924269.14     13896522.71      1924272.47     13896531.05
      1924274.13     13896540.36      1924275.88     13896559.64
      1924277.54     13896568.95      1924278.99     13896573.35
      1924283.18     13896581.04      1924288.66     13896588.20
      1924298.06     13896598.44      1924355.34     13896654.86
      1924364.54     13896665.19      1924369.64     13896672.51
      1924371.61     13896676.41      1924374.18     13896685.34
      1924375.59     13896699.76      1924375.00     13896775.00

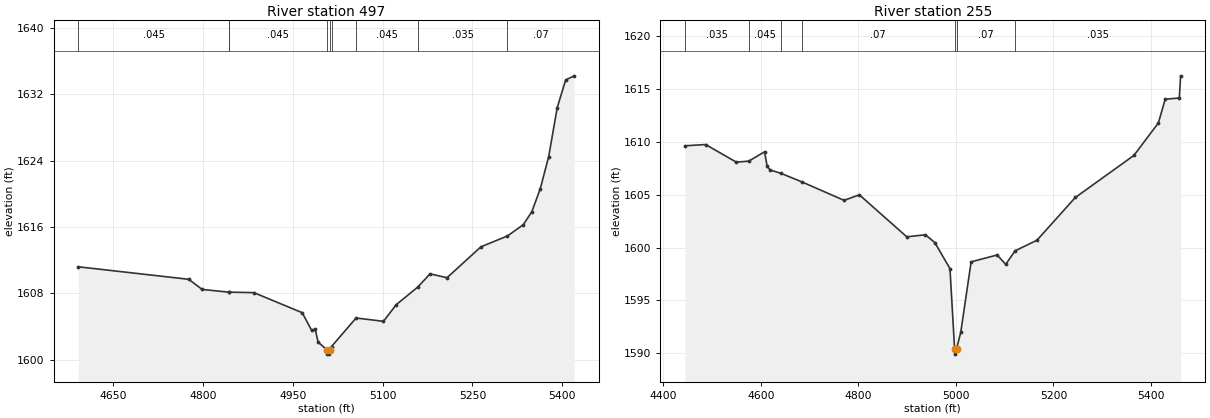
Type RM Length L Ch R = 1,497,242,242,242
BEGIN DESCRIPTION:
Stream0636 1.0
END DESCRIPTION:
XS GIS Cut Line= 3
      1923775.01     13896175.00      1924125.00     13896375.00
      1924425.02     13896074.98
#Sta/Elev= 30
  4592.3 1611.20  4776.6 1609.69  4798.9 1608.47  4843.1 1608.14  4843.4 1608.14
  4885.3 1608.08  4965.9 1605.66  4981.7 1603.52  4987.5 1603.67  4992.5 1602.10
  5007.5 1601.16  5007.8 1600.66  5011.3 1600.66  5011.5 1601.16  5014.8 1601.58
  5055.8 1605.02  5101.5 1604.62  5122.7 1606.62  5158.8 1608.76  5179.3 1610.35
  5207.5 1609.88  5264.1 1613.61  5308.3 1614.92  5334.8 1616.28  5349.0 1617.84
  5363.1 1620.61  5377.2 1624.50  5391.4 1630.39  5405.5 1633.75  5419.7 1634.25
#Mann=9,-1,0
  4592.3   0.045       0  4843.1    0.07       0  4843.4   0.045       0
  5007.5   0.045       0  5011.5   0.045       0  5014.8    0.07       0
  5055.8   0.045       0  5158.8   0.035       0  5308.3    0.07       0
Bank Sta=5007.5,5011.5
Exp/Cntr=0.3,0.1

Type RM Length L Ch R = 1,255,0,0,0
BEGIN DESCRIPTION:
Stream0636 0.0
END DESCRIPTION:
XS GIS Cut Line= 4
      1923749.35     13896446.47      1924182.10     13896591.63
      1924368.81     13896523.20      1924592.72     13896239.13
#Sta/Elev= 30
  4443.9 1609.63  4486.6 1609.75  4549.7 1608.08  4575.1 1608.18  4607.5 1609.06
  4612.8 1607.71  4618.6 1607.35  4640.9 1607.03  4683.8 1606.22  4770.5 1604.47
  4802.0 1604.99  4899.2 1601.02  4937.4 1601.21  4956.7 1600.48  4987.8 1598.01
  4997.3 1590.42  4997.5 1589.92  5001.3 1590.42  5009.9 1591.98  5031.2 1598.65
  5084.6 1599.30  5102.2 1598.41  5121.3 1599.69  5166.3 1600.70  5244.9 1604.74
  5365.1 1608.72  5415.2 1611.79  5429.3 1614.04  5458.2 1614.15  5460.9 1616.25
#Mann=7,-1,0
  4443.9   0.035       0  4575.1   0.045       0  4640.9   0.035       0
  4683.8    0.07       0  4997.3    0.05       0  5001.3    0.07       0
  5121.3   0.035       0
Bank Sta=4997.3,5001.3
Exp/Cntr=0.3,0.1

Chan Stop Cuts=-1