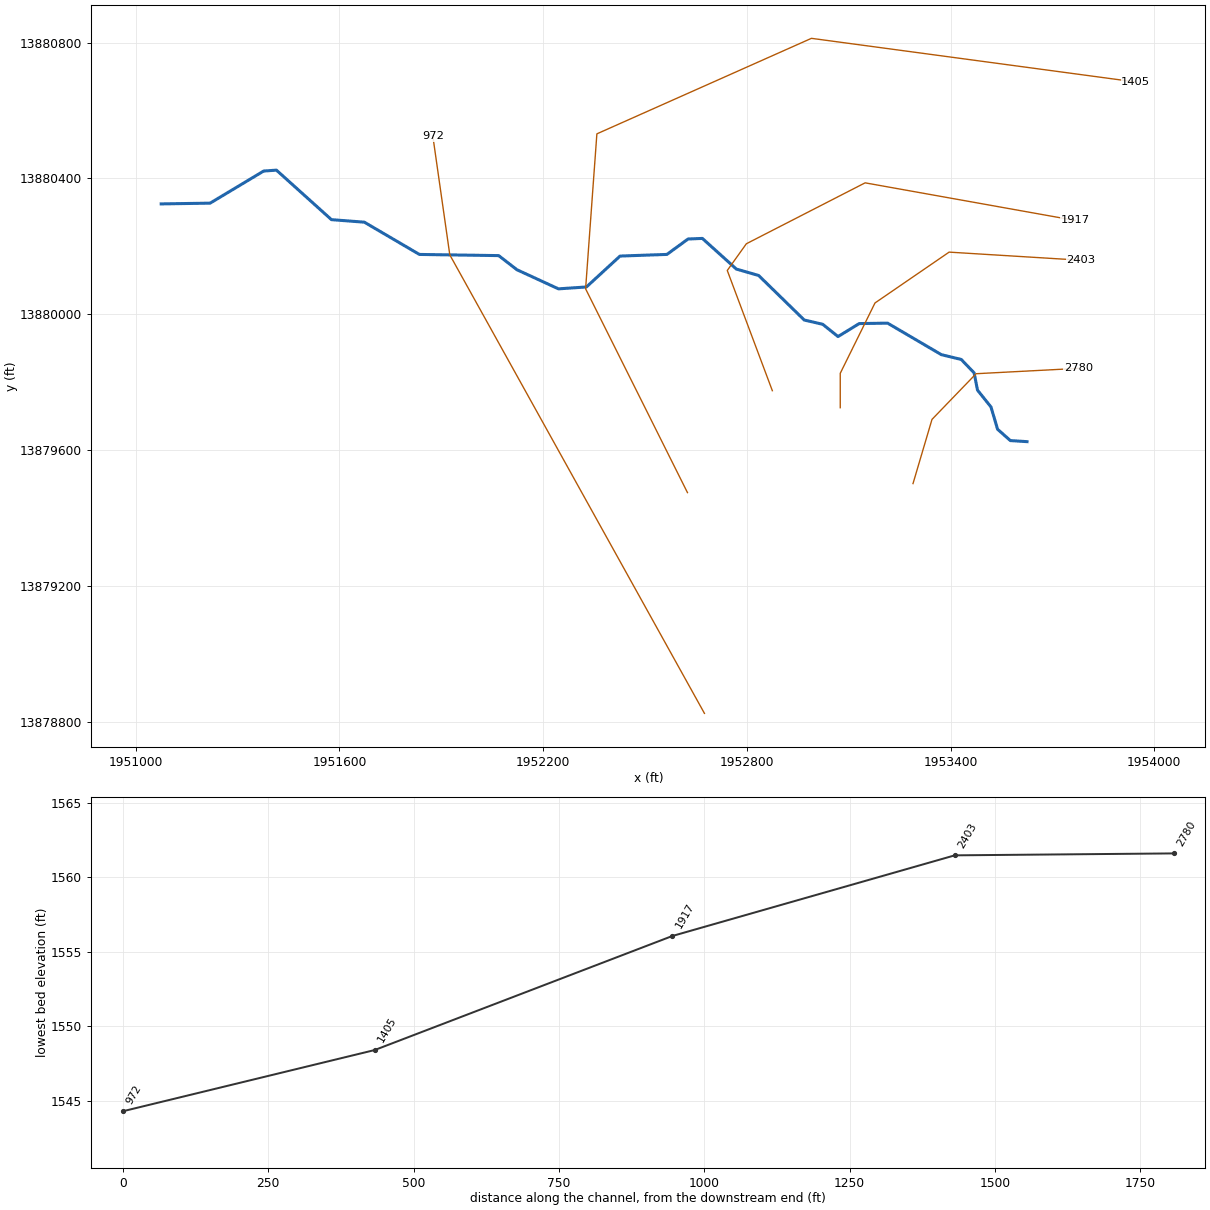
--- Stream0637.prj (project) ---

Proj Title=Stream0637 Base Level Engineering
Current Plan=p01
Default Exp/Contr=0.3,0.1
English Units
Geom File=g01
Flow File=f01
Plan File=p01
BEGIN DESCRIPTION:
Stream0637
END DESCRIPTION:

--- Stream0637.p01 (plan) ---

Plan Title=Multiple Run
Short Identifier=Multiple
Geom File=g01
Flow File=f01
Subcritical Flow
K Sum by GR= 0
Std Step Tol= 0.01
Critical Tol= 0.01
Num of Std Step Trials= 20
Max Error Tol= 0.3
Flow Tol Ratio= 0.001
Split Flow NTrial= 30
Split Flow Tol= 0.02
Split Flow Ratio= 0.02
Log Output Level= 0
Friction Slope Method= 1
Unsteady Friction Slope Method= 2
Unsteady Bridges Friction Slope Method= 1
Parabolic Critical Depth
Global Vel Dist=  1 , 1 , 1
Global Log Level= 0
CheckData=True
Encroach Param= -1, 0, 0, 0
BEGIN DESCRIPTION:
Multiple Run
END DESCRIPTION:

--- Stream0637.f01 (steady flow) ---

Flow Title=Multiple
Number of Profiles=7
Profile Names=10-year,25-year,50-year,1pct_min,100-year,1pct_plu,500-year
River Rch & RM= Stream0637,Reach-1,2780
    1146    1968    2759    1873    3738    7458    6768
Boundary for River Rch & Prof#=Stream0637,Reach-1,1
Up Type=0
Dn Type=3
Dn Slope=0.005
Boundary for River Rch & Prof#=Stream0637,Reach-1,2
Up Type=0
Dn Type=3
Dn Slope=0.005
Boundary for River Rch & Prof#=Stream0637,Reach-1,3
Up Type=0
Dn Type=3
Dn Slope=0.005
Boundary for River Rch & Prof#=Stream0637,Reach-1,4
Up Type=0
Dn Type=3
Dn Slope=0.005
Boundary for River Rch & Prof#=Stream0637,Reach-1,5
Up Type=0
Dn Type=3
Dn Slope=0.005
Boundary for River Rch & Prof#=Stream0637,Reach-1,6
Up Type=0
Dn Type=3
Dn Slope=0.005
Boundary for River Rch & Prof#=Stream0637,Reach-1,7
Up Type=0
Dn Type=3
Dn Slope=0.005

--- Stream0637.g01 (geometry) ---

Geom Title=Existing Conditions

River Reach=Stream0637,Reach-1
Reach XY= 30
      1953625.00     13879625.00      1953576.03     13879628.14
      1953538.37     13879661.45      1953518.91     13879727.18
      1953479.20     13879776.76      1953469.27     13879827.55
      1953431.34     13879866.98      1953372.84     13879881.11
      1953214.45     13879973.91      1953130.89     13879972.63
      1953068.38     13879934.41      1953023.35     13879970.55
      1952968.95     13879983.12      1952834.68     13880114.22
      1952768.96     13880133.18      1952668.96     13880223.37
      1952626.75     13880221.66      1952564.50     13880176.25
      1952426.47     13880171.44      1952327.42     13880080.41
      1952245.10     13880074.89      1952122.82     13880131.12
      1952069.07     13880172.76      1951835.50     13880176.20
      1951673.41     13880271.17      1951576.50     13880278.61
      1951414.38     13880424.41      1951376.74     13880421.69
      1951219.09     13880327.20      1951075.00     13880325.00

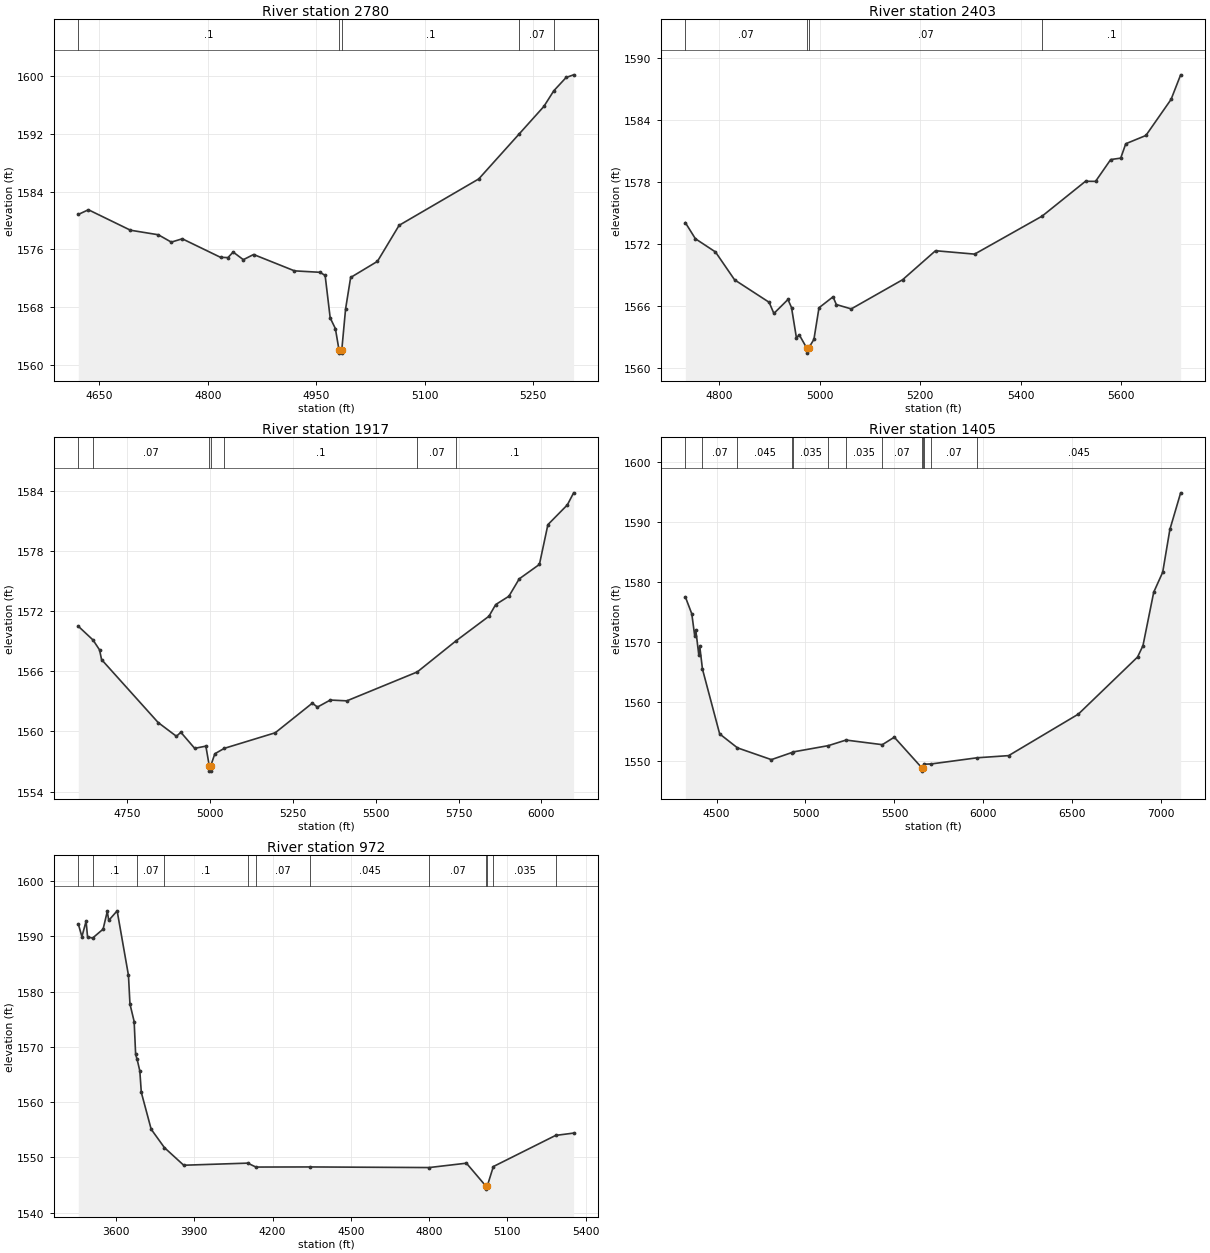
Type RM Length L Ch R = 1,2780,377,377,377
BEGIN DESCRIPTION:
Stream0637 5.0
END DESCRIPTION:
XS GIS Cut Line= 4
      1953289.29     13879501.56      1953345.18     13879690.47
      1953475.00     13879825.00      1953776.13     13879840.77
#Sta/Elev= 30
  4620.7 1580.85  4634.7 1581.50  4692.9 1578.66  4731.4 1578.03  4749.4 1577.01
  4764.6 1577.47  4817.5 1574.90  4827.8 1574.86  4835.0 1575.63  4849.1 1574.57
  4863.3 1575.29  4919.9 1573.02  4955.1 1572.82  4962.3 1572.39  4969.3 1566.49
  4976.5 1565.00  4981.4 1562.10  4981.7 1561.60  4985.2 1561.60  4985.4 1562.10
  4990.6 1567.73  4997.6 1572.10  5034.7 1574.34  5064.7 1579.34  5174.9 1585.78
  5230.9 1592.03  5265.0 1595.84  5278.8 1598.02  5295.8 1599.86  5306.2 1600.23
#Mann=5,-1,0
  4620.7     0.1       0  4981.4    0.05       0  4985.4     0.1       0
  5230.9    0.07       0  5278.8     0.1       0
Bank Sta=4981.4,4985.4
Exp/Cntr=0.3,0.1

Type RM Length L Ch R = 1,2403,486,486,486
BEGIN DESCRIPTION:
Stream0637 4.0
END DESCRIPTION:
XS GIS Cut Line= 5
      1953075.00     13879725.01      1953075.00     13879826.24
      1953177.29     13880033.31      1953395.64     13880183.02
      1953784.07     13880159.15
#Sta/Elev= 30
  4732.6 1574.10  4752.6 1572.54  4792.6 1571.26  4830.7 1568.56  4899.4 1566.39
  4908.9 1565.31  4936.9 1566.66  4944.0 1565.88  4953.8 1562.94  4959.4 1563.24
  4974.2 1561.97  4974.5 1561.47  4978.2 1561.97  4988.6 1562.80  4998.7 1565.86
  5026.7 1566.92  5033.2 1566.17  5062.9 1565.75  5165.1 1568.57  5230.7 1571.38
  5308.5 1571.05  5443.0 1574.73  5529.3 1578.10  5549.3 1578.09  5579.4 1580.20
  5599.4 1580.34  5609.4 1581.73  5649.5 1582.53  5699.6 1586.02  5718.7 1588.40
#Mann=4,-1,0
  4732.6    0.07       0  4974.2    0.05       0  4978.2    0.07       0
  5443.0     0.1       0
Bank Sta=4974.2,4978.2
Exp/Cntr=0.3,0.1

Type RM Length L Ch R = 1,1917,512,512,512
BEGIN DESCRIPTION:
Stream0637 3.0
END DESCRIPTION:
XS GIS Cut Line= 5
      1952875.00     13879775.01      1952742.26     13880128.98
      1952798.47     13880207.65      1953148.24     13880387.01
      1953766.71     13880276.34
#Sta/Elev= 30
  4601.5 1570.48  4646.0 1569.11  4665.6 1568.13  4671.8 1567.16  4842.7 1560.89
  4897.9 1559.52  4911.2 1559.92  4953.0 1558.32  4986.8 1558.54  4997.2 1556.55
  4997.5 1556.05  5001.0 1556.05  5001.2 1556.55  5013.9 1557.78  5042.5 1558.32
  5196.3 1559.87  5308.3 1562.82  5323.8 1562.43  5362.6 1563.13  5412.6 1563.05
  5625.4 1565.93  5741.8 1569.01  5841.9 1571.48  5862.2 1572.64  5902.1 1573.47
  5933.3 1575.20  5994.3 1576.64  6019.9 1580.60  6078.7 1582.57  6097.6 1583.77
#Mann=7,-1,0
  4601.5     0.1       0  4646.0    0.07       0  4997.2    0.05       0
  5001.2    0.07       0  5042.5     0.1       0  5625.4    0.07       0
  5741.8     0.1       0
Bank Sta=4997.2,5001.2
Exp/Cntr=0.3,0.1

Type RM Length L Ch R = 1,1405,433,433,433
BEGIN DESCRIPTION:
Stream0637 2.0
END DESCRIPTION:
XS GIS Cut Line= 5
      1952625.00     13879475.00      1952325.00     13880075.00
      1952358.20     13880531.22      1952990.15     13880812.47
      1953945.00     13880684.00
#Sta/Elev= 30
  4324.8 1577.51  4361.1 1574.67  4377.9 1570.90  4383.5 1571.96  4400.3 1567.84
  4405.9 1569.23  4421.0 1565.44  4517.7 1554.61  4617.6 1552.28  4808.3 1550.31
  4923.7 1551.50  4930.9 1551.60  5128.5 1552.65  5227.7 1553.58  5431.8 1552.81
  5499.0 1554.06  5655.5 1548.89  5655.8 1548.39  5659.5 1548.89  5665.4 1549.55
  5706.6 1549.59  5964.4 1550.62  6141.6 1550.98  6533.1 1557.91  6866.0 1567.45
  6896.3 1569.34  6956.9 1578.29  7007.3 1581.62  7047.7 1588.77  7108.2 1594.89
#Mann=13,-1,0
  4324.8     0.1       0  4421.0    0.07       0  4617.6   0.045       0
  4923.7    0.07       0  4930.9   0.035       0  5128.5    0.07       0
  5227.7   0.035       0  5431.8    0.07       0  5655.5   0.035       0
  5659.5    0.07       0  5665.4     0.1       0  5706.6    0.07       0
  5964.4   0.045       0
Bank Sta=5655.5,5659.5
Exp/Cntr=0.3,0.1

Type RM Length L Ch R = 1,972,0,0,0
BEGIN DESCRIPTION:
Stream0637 1.0
END DESCRIPTION:
XS GIS Cut Line= 3
      1952675.02     13878824.97      1951925.00     13880175.00
      1951875.01     13880524.96
#Sta/Elev= 30
  3455.7 1592.21  3469.5 1589.92  3485.5 1592.71  3491.2 1589.86  3510.3 1589.66
  3550.7 1591.28  3566.7 1594.48  3572.4 1592.86  3604.5 1594.59  3647.9 1582.92
  3653.6 1577.75  3669.7 1574.58  3675.4 1568.62  3681.0 1567.75  3691.4 1565.65
  3697.1 1561.77  3734.9 1555.11  3785.7 1551.78  3859.6 1548.60  4104.7 1548.98
  4136.3 1548.27  4343.3 1548.29  4799.9 1548.18  4942.9 1548.97  5018.3 1544.78
  5018.5 1544.28  5022.3 1544.78  5046.0 1548.36  5284.6 1553.99  5353.6 1554.41
#Mann=12,-1,0
  3455.7    0.07       0  3510.3     0.1       0  3681.0    0.07       0
  3785.7     0.1       0  4104.7   0.045       0  4136.3    0.07       0
  4343.3   0.045       0  4799.9    0.07       0  5018.3    0.05       0
  5022.3    0.07       0  5046.0   0.035       0  5284.6    0.07       0
Bank Sta=5018.3,5022.3
Exp/Cntr=0.3,0.1

Chan Stop Cuts=-1