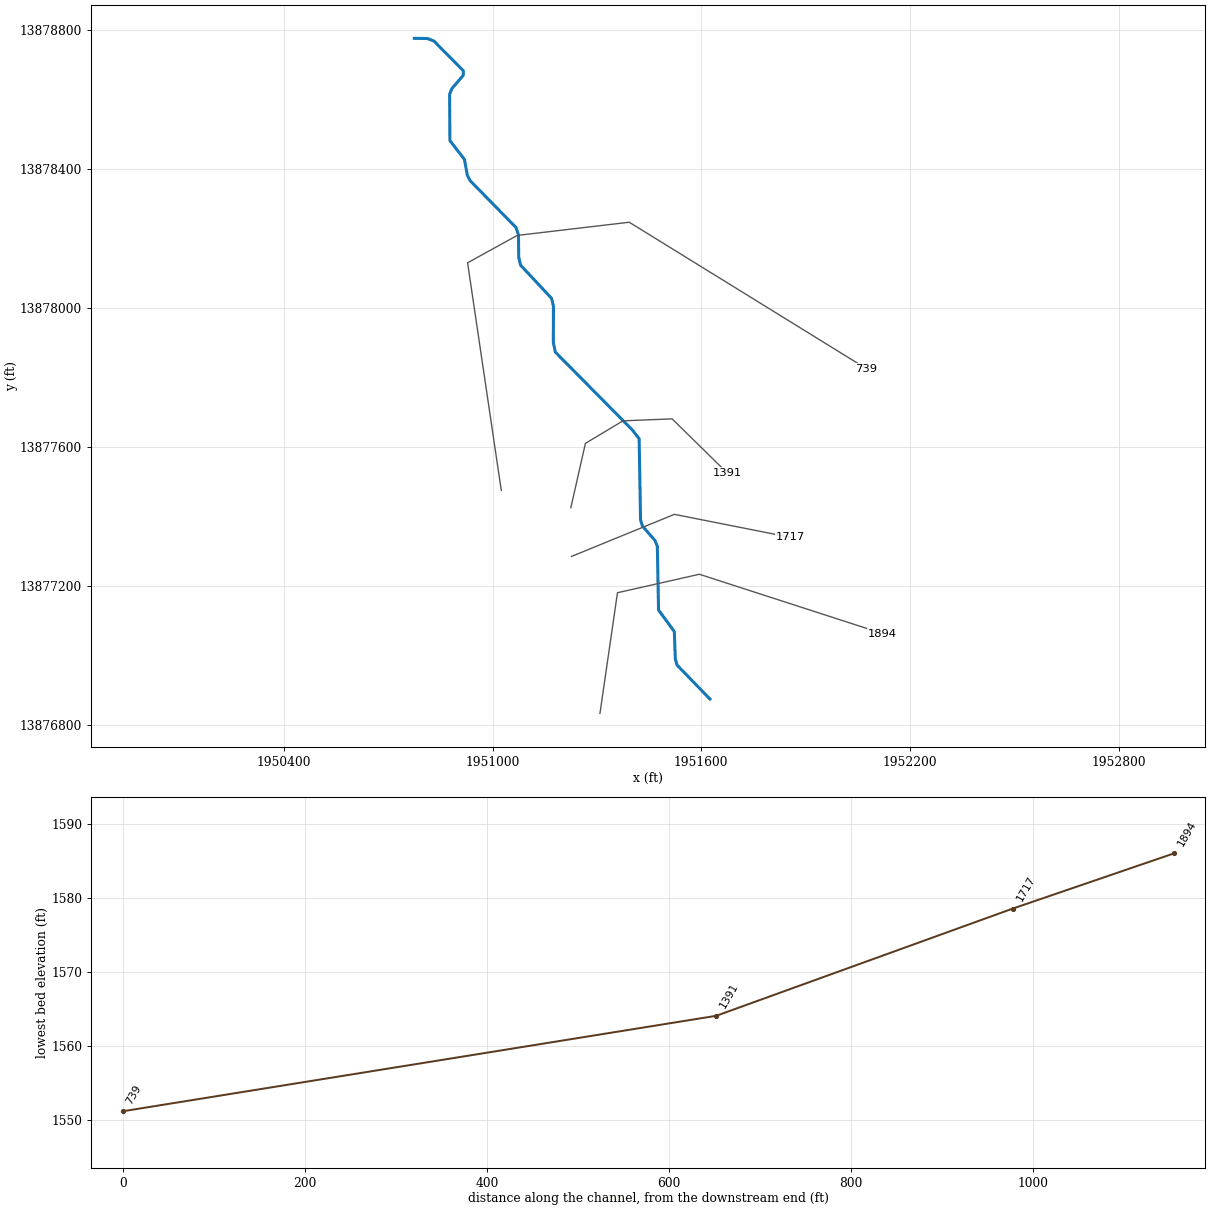
--- Stream0638.prj (project) ---

Proj Title=Stream0638 Base Level Engineering
Current Plan=p01
Default Exp/Contr=0.3,0.1
English Units
Geom File=g01
Flow File=f01
Plan File=p01
BEGIN DESCRIPTION:
Stream0638
END DESCRIPTION:

--- Stream0638.p01 (plan) ---

Plan Title=Multiple Run
Short Identifier=Multiple
Geom File=g01
Flow File=f01
Subcritical Flow
K Sum by GR= 0
Std Step Tol= 0.01
Critical Tol= 0.01
Num of Std Step Trials= 20
Max Error Tol= 0.3
Flow Tol Ratio= 0.001
Split Flow NTrial= 30
Split Flow Tol= 0.02
Split Flow Ratio= 0.02
Log Output Level= 0
Friction Slope Method= 1
Unsteady Friction Slope Method= 2
Unsteady Bridges Friction Slope Method= 1
Parabolic Critical Depth
Global Vel Dist=  1 , 1 , 1
Global Log Level= 0
CheckData=True
Encroach Param= -1, 0, 0, 0
BEGIN DESCRIPTION:
Multiple Run
END DESCRIPTION:

--- Stream0638.f01 (steady flow) ---

Flow Title=Multiple
Number of Profiles=7
Profile Names=10-year,25-year,50-year,1pct_min,100-year,1pct_plu,500-year
River Rch & RM= Stream0638,Reach-1,1894
     302     471     619     397     792    1579    1269
Boundary for River Rch & Prof#=Stream0638,Reach-1,1
Up Type=0
Dn Type=3
Dn Slope=0.005
Boundary for River Rch & Prof#=Stream0638,Reach-1,2
Up Type=0
Dn Type=3
Dn Slope=0.005
Boundary for River Rch & Prof#=Stream0638,Reach-1,3
Up Type=0
Dn Type=3
Dn Slope=0.005
Boundary for River Rch & Prof#=Stream0638,Reach-1,4
Up Type=0
Dn Type=3
Dn Slope=0.005
Boundary for River Rch & Prof#=Stream0638,Reach-1,5
Up Type=0
Dn Type=3
Dn Slope=0.005
Boundary for River Rch & Prof#=Stream0638,Reach-1,6
Up Type=0
Dn Type=3
Dn Slope=0.005
Boundary for River Rch & Prof#=Stream0638,Reach-1,7
Up Type=0
Dn Type=3
Dn Slope=0.005

--- Stream0638.g01 (geometry) ---

Geom Title=Existing Conditions

River Reach=Stream0638,Reach-1
Reach XY= 30
      1951625.00     13876875.00      1951530.46     13876972.55
      1951525.51     13876990.21      1951522.64     13877069.02
      1951477.26     13877130.94      1951473.78     13877314.49
      1951466.86     13877331.06      1951430.75     13877372.67
      1951425.52     13877390.22      1951421.46     13877623.54
      1951402.14     13877648.53      1951180.47     13877872.55
      1951174.73     13877899.89      1951175.02     13878005.01
      1951169.52     13878027.44      1951080.54     13878122.58
      1951075.14     13878145.06      1951074.47     13878209.78
      1951067.14     13878231.17      1950935.76     13878365.32
      1950927.50     13878381.03      1950918.86     13878427.17
      1950877.23     13878480.93      1950876.38     13878614.56
      1950883.47     13878631.19      1950915.72     13878668.48
      1950915.90     13878681.75      1950831.27     13878767.24
      1950813.18     13878774.41      1950775.00     13878775.00

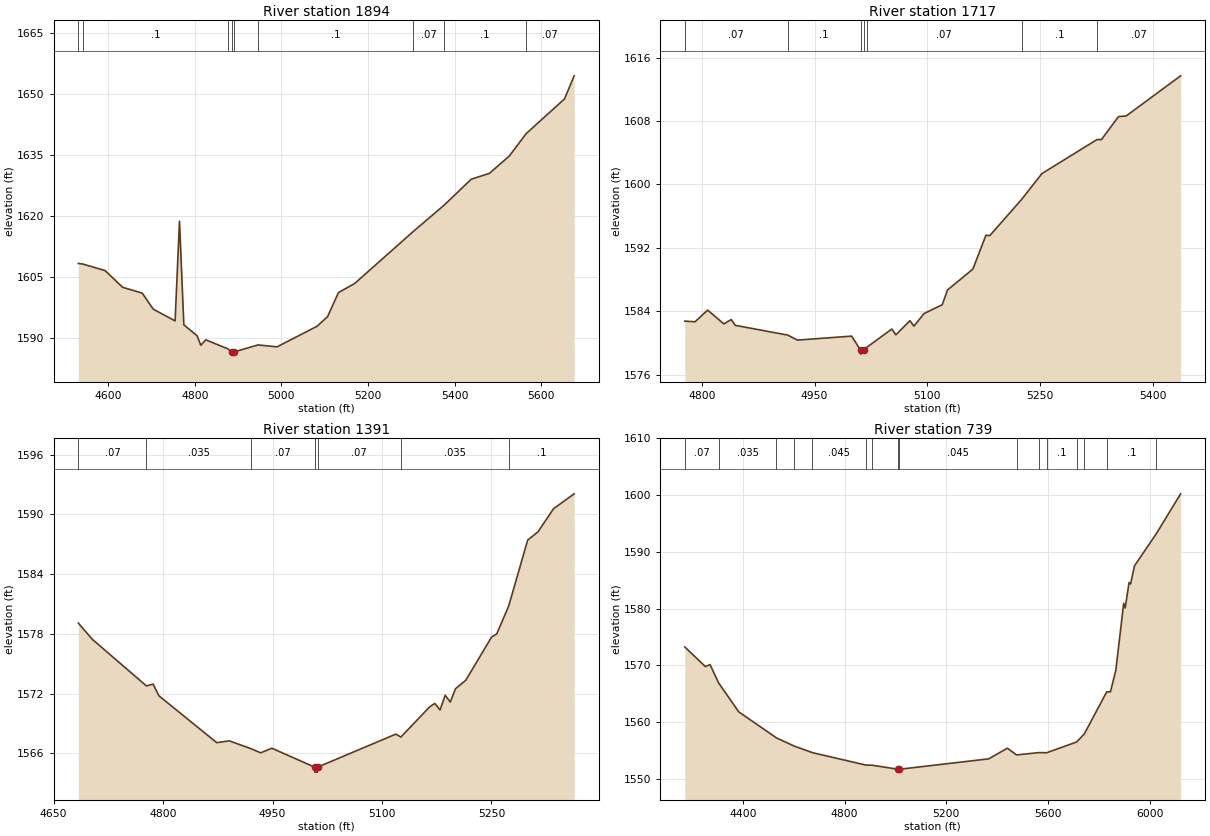
Type RM Length L Ch R = 1,1894,177,177,177
BEGIN DESCRIPTION:
Stream0638 3.0
END DESCRIPTION:
XS GIS Cut Line= 4
      1951308.80     13876833.74      1951359.13     13877180.67
      1951594.65     13877233.81      1952121.26     13877063.39
#Sta/Elev= 30
  4530.8 1608.35  4541.5 1608.20  4592.7 1606.60  4633.1 1602.49  4678.5 1601.05
  4703.9 1597.11  4754.4 1594.22  4764.5 1618.75  4774.6 1593.24  4804.9 1590.60
  4813.9 1588.22  4825.1 1589.57  4876.3 1587.35  4885.4 1586.55  4885.6 1586.05
  4889.4 1586.55  4945.8 1588.31  4989.9 1587.84  5082.2 1592.90  5106.6 1595.26
  5131.8 1601.20  5169.1 1603.41  5304.2 1616.18  5376.2 1622.72  5438.5 1629.07
  5480.5 1630.51  5526.4 1634.77  5565.5 1640.29  5654.0 1648.82  5676.3 1654.50
#Mann=9,-1,0
  4530.8    0.07       0  4541.5     0.1       0  4876.3    0.07       0
  4885.4    0.05       0  4889.4    0.07       0  4945.8     0.1       0
  5304.2    0.07       0  5376.2     0.1       0  5565.5    0.07       0
Bank Sta=4885.4,4889.4
Exp/Cntr=0.3,0.1

Type RM Length L Ch R = 1,1717,326,326,326
BEGIN DESCRIPTION:
Mapping XS dc08395e
END DESCRIPTION:
XS GIS Cut Line= 3
      1951226.87     13877285.04      1951522.79     13877406.10
      1951855.99     13877340.09
#Sta/Elev= 30
  4777.4 1582.76  4791.0 1582.68  4807.8 1584.15  4829.4 1582.41  4839.1 1582.96
  4844.5 1582.23  4914.3 1581.00  4927.3 1580.37  4999.3 1580.87  5011.1 1579.10
  5011.3 1578.60  5015.1 1579.10  5019.4 1579.45  5052.7 1581.77  5058.1 1581.03
  5076.8 1582.82  5082.2 1582.13  5095.6 1583.72  5119.8 1584.83  5126.7 1586.68
  5160.5 1589.32  5177.9 1593.59  5183.0 1593.54  5225.3 1598.10  5252.3 1601.36
  5325.7 1605.66  5331.5 1605.65  5354.2 1608.55  5364.4 1608.63  5436.8 1613.69
#Mann=7,-1,0
  4777.4    0.07       0  4914.3     0.1       0  5011.1    0.05       0
  5015.1     0.1       0  5019.4    0.07       0  5225.3     0.1       0
  5325.7    0.07       0
Bank Sta=5011.1,5015.1
Exp/Cntr=0.3,0.1

Type RM Length L Ch R = 1,1391,652,652,652
BEGIN DESCRIPTION:
Stream0638 2.0
END DESCRIPTION:
XS GIS Cut Line= 5
      1951225.01     13877425.04      1951266.91     13877610.17
      1951375.00     13877675.00      1951516.22     13877680.71
      1951675.02     13877524.98
#Sta/Elev= 30
  4683.8 1579.08  4702.8 1577.46  4777.1 1572.77  4786.3 1572.95  4794.2 1571.78
  4873.5 1567.07  4890.8 1567.25  4920.6 1566.46  4933.6 1566.05  4949.1 1566.51
  5007.7 1564.61  5007.9 1564.11  5011.4 1564.11  5011.7 1564.61  5119.1 1567.93
  5125.9 1567.63  5165.4 1570.67  5172.4 1571.01  5179.6 1570.36  5186.6 1571.83
  5193.7 1571.15  5200.7 1572.48  5214.9 1573.34  5250.3 1577.68  5257.3 1577.99
  5273.7 1580.80  5299.7 1587.41  5313.9 1588.25  5335.2 1590.57  5363.4 1592.06
#Mann=7,-1,0
  4683.8    0.07       0  4777.1   0.035       0  4920.6    0.07       0
  5007.7    0.05       0  5011.7    0.07       0  5125.9   0.035       0
  5273.7     0.1       0
Bank Sta=5007.7,5011.7
Exp/Cntr=0.3,0.1

Type RM Length L Ch R = 1,739,0,0,0
BEGIN DESCRIPTION:
Stream0638 1.0
END DESCRIPTION:
XS GIS Cut Line= 5
      1951025.00     13877475.00      1950928.09     13878129.49
      1951070.74     13878208.19      1951393.01     13878246.15
      1952075.01     13877825.00
#Sta/Elev= 30
  4171.6 1573.26  4252.5 1569.81  4270.8 1570.16  4304.8 1566.93  4383.9 1561.83
  4532.3 1557.25  4601.8 1555.81  4673.8 1554.65  4884.4 1552.46  4908.0 1552.44
  5011.6 1551.72  5011.8 1551.22  5015.6 1551.72  5367.3 1553.56  5440.5 1555.43
  5476.9 1554.25  5565.4 1554.66  5595.0 1554.63  5713.2 1556.53  5743.5 1557.96
  5831.3 1565.35  5846.1 1565.36  5867.4 1569.19  5898.2 1580.96  5904.0 1580.12
  5919.4 1584.60  5925.3 1584.35  5940.7 1587.55  6025.6 1593.14  6122.2 1600.23
#Mann=16,-1,0
  4171.6    0.07       0  4304.8   0.035       0  4532.3   0.045       0
  4601.8   0.035       0  4673.8   0.045       0  4884.4   0.035       0
  4908.0   0.045       0  5011.6   0.045       0  5015.6   0.045       0
  5476.9    0.07       0  5565.4   0.045       0  5595.0     0.1       0
  5713.2   0.035       0  5743.5    0.07       0  5831.3     0.1       0
  6025.6    0.07       0
Bank Sta=5011.6,5015.6
Exp/Cntr=0.3,0.1

Chan Stop Cuts=-1