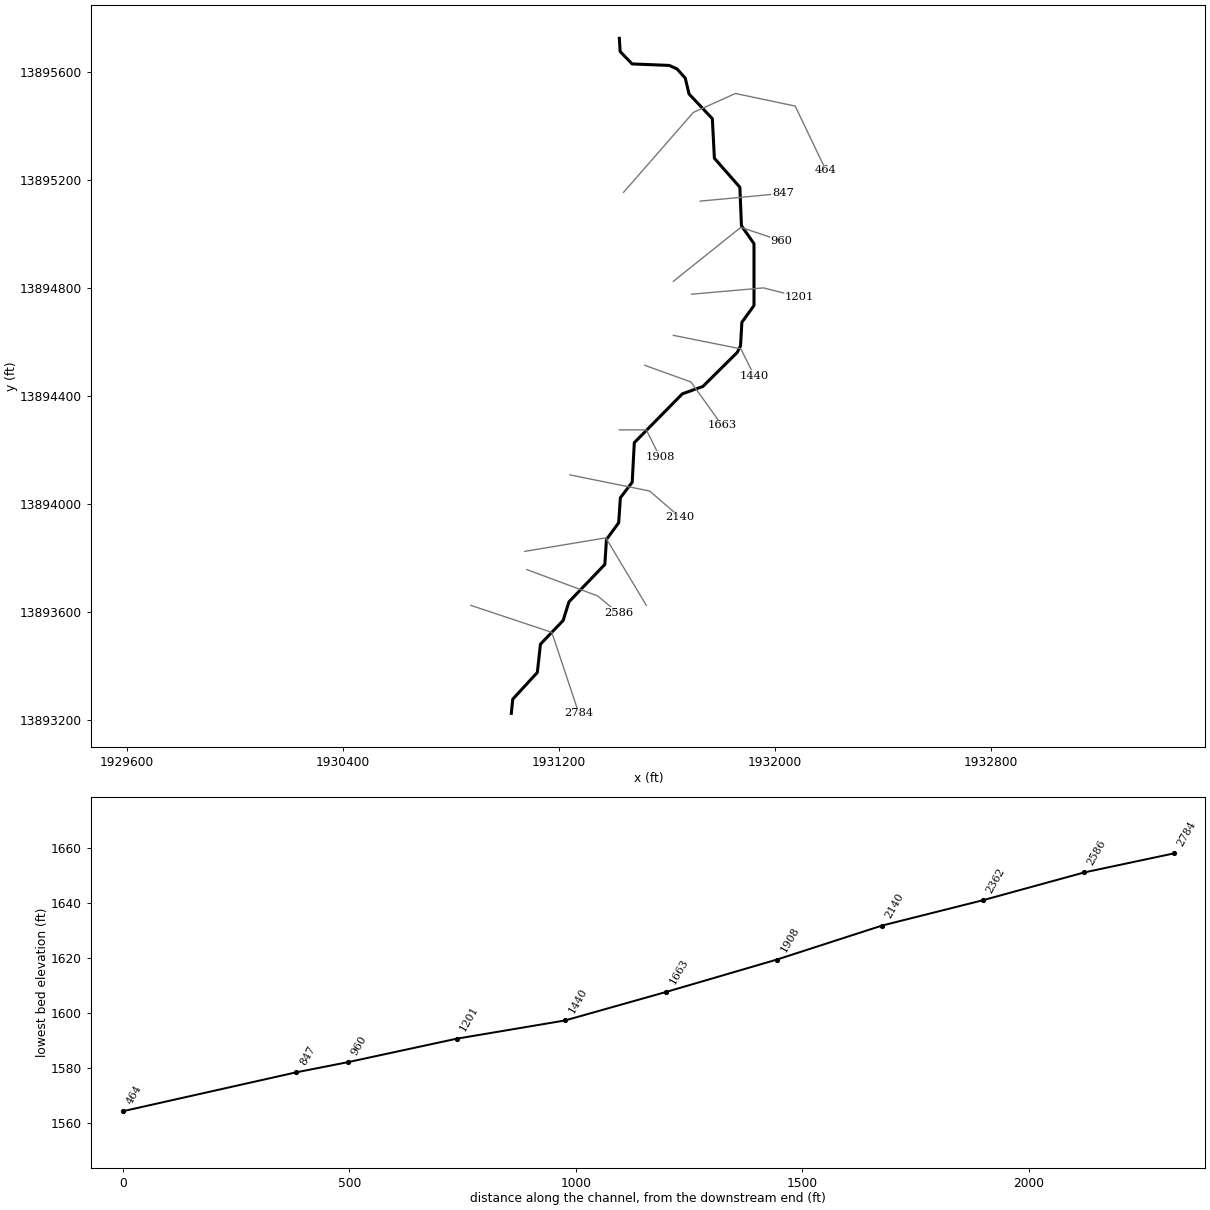
--- Stream0639.prj (project) ---

Proj Title=Stream0639 Base Level Engineering
Current Plan=p01
Default Exp/Contr=0.3,0.1
English Units
Geom File=g01
Flow File=f01
Plan File=p01
Y Axis Title=Elevation
X Axis Title(PF)=Main Channel Distance
X Axis Title(XS)=Station
BEGIN DESCRIPTION:
Stream0639
END DESCRIPTION:
DSS Export Rating Curves= 0
DSS Export Rating Curve Sorted= 0
DSS Export Volume Flow Curves= 0
DXF OffsetX= 0
DXF OffsetY= 0
DXF ScaleX= 1
DXF ScaleY= 10

--- Stream0639.p01 (plan) ---

Plan Title=Multiple Run
Short Identifier=Multiple
Geom File=g01
Flow File=f01
Subcritical Flow
K Sum by GR= 0
Std Step Tol= 0.01
Critical Tol= 0.01
Num of Std Step Trials= 20
Max Error Tol= 0.3
Flow Tol Ratio= 0.001
Split Flow NTrial= 30
Split Flow Tol= 0.02
Split Flow Ratio= 0.02
Log Output Level= 0
Friction Slope Method= 1
Unsteady Friction Slope Method= 2
Unsteady Bridges Friction Slope Method= 1
Parabolic Critical Depth
Global Vel Dist=  1 , 1 , 1
Global Log Level= 0
CheckData=True
Encroach Param= -1, 0, 0, 0
BEGIN DESCRIPTION:
Multiple Run
END DESCRIPTION:

--- Stream0639.f01 (steady flow) ---

Flow Title=Multiple
Number of Profiles=7
Profile Names=10-year,25-year,50-year,1pct_min,100-year,1pct_plu,500-year
River Rch & RM= Stream0639,Reach-1,2784
     311     485     638     409     816    1628    1309
Boundary for River Rch & Prof#=Stream0639,Reach-1,1
Up Type=0
Dn Type=3
Dn Slope=0.005
Boundary for River Rch & Prof#=Stream0639,Reach-1,2
Up Type=0
Dn Type=3
Dn Slope=0.005
Boundary for River Rch & Prof#=Stream0639,Reach-1,3
Up Type=0
Dn Type=3
Dn Slope=0.005
Boundary for River Rch & Prof#=Stream0639,Reach-1,4
Up Type=0
Dn Type=3
Dn Slope=0.005
Boundary for River Rch & Prof#=Stream0639,Reach-1,5
Up Type=0
Dn Type=3
Dn Slope=0.005
Boundary for River Rch & Prof#=Stream0639,Reach-1,6
Up Type=0
Dn Type=3
Dn Slope=0.005
Boundary for River Rch & Prof#=Stream0639,Reach-1,7
Up Type=0
Dn Type=3
Dn Slope=0.005

--- Stream0639.g01 (geometry) ---

Geom Title=Existing Conditions
Program Version=4.10

River Reach=Stream0639      ,Reach-1
Reach XY= 30
        1931025.       13893225.      1931030.33     13893277.51
      1931121.39      13893376.5      1931132.88     13893481.16
      1931216.82     13893568.96      1931238.63     13893638.21
      1931371.39      13893776.5      1931377.36     13893869.02
      1931422.65     13893930.97      1931428.86      13894023.4
      1931472.73     13894080.94      1931480.47     13894227.45
      1931658.33     13894408.35      1931734.68     13894435.78
       1931861.6     13894561.69      1931873.84     13894585.48
      1931878.86      13894673.4      1931923.78      13894735.5
      1931923.78      13894964.5      1931877.27     13895030.94
      1931871.44     13895173.53      1931777.08     13895280.86
      1931769.52     13895427.44      1931683.19     13895518.98
      1931669.26     13895577.58      1931638.67     13895611.77
      1931609.96     13895624.66      1931472.31     13895630.27
      1931428.12     13895675.98        1931425.       13895725.

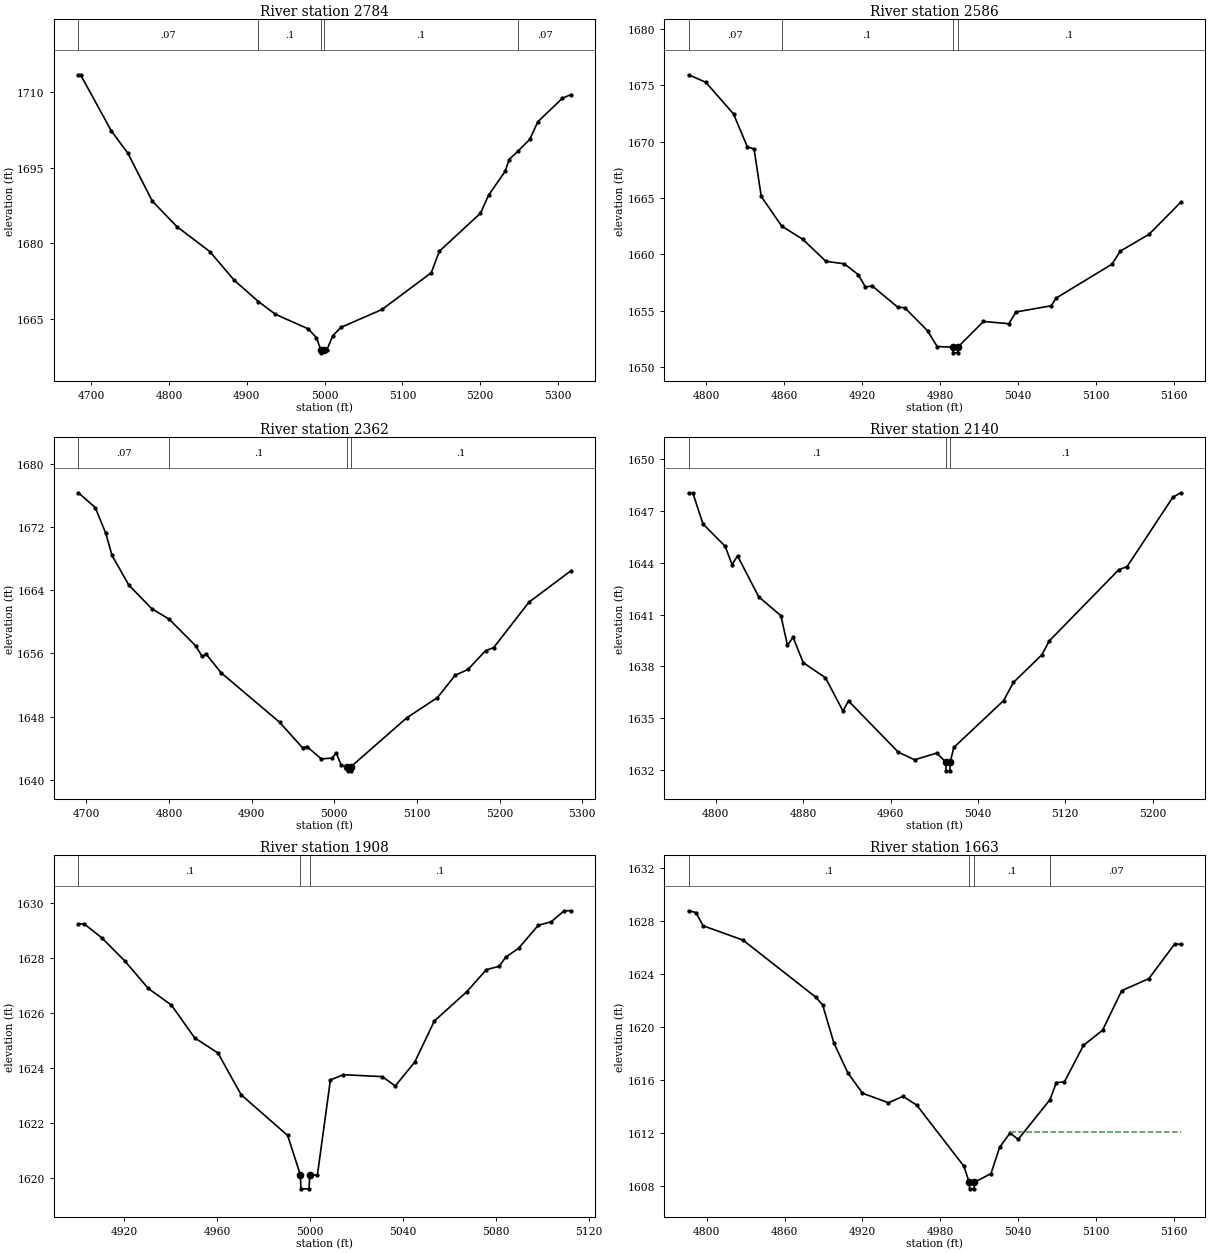
Type RM Length L Ch R = 1 ,2784    ,198,198,198
BEGIN DESCRIPTION:
Stream0639 5.0
END DESCRIPTION:
XS GIS Cut Line= 3
      1930874.98     13893625.01        1931175.       13893525.
      1931275.01     13893224.98
#Sta/Elev= 30
  4683.8 1713.51  4686.5 1713.51    4726 1702.35  4747.1 1697.95  4778.7 1688.38
  4810.3 1683.31  4852.5 1678.36  4884.1 1672.63  4914.9 1668.42  4936.8 1665.88
    4979 1662.98  4989.5 1661.23  4995.4 1658.71  4995.7 1658.21  4999.4 1658.71
  5002.7 1658.71  5010.6 1661.62  5021.1 1663.28  5073.8 1666.83  5137.1 1674.14
  5147.6 1678.43  5200.3 1685.97  5210.9  1689.6    5232  1694.3  5237.2 1696.66
  5248.9 1698.39  5263.6 1700.65  5274.1 1704.18  5305.7 1708.86  5316.3 1709.55
#Mann= 5 ,-1 , 0
  4683.8     .07       0  4914.9      .1       0  4995.4     .05       0
  4999.4      .1       0  5248.9     .07       0
Bank Sta=4995.4,4999.4
XS Rating Curve= 0 ,0
Exp/Cntr=0.3,0.1

Type RM Length L Ch R = 1 ,2586    ,224,224,224
BEGIN DESCRIPTION:
Mapping XS 2d6afc85
END DESCRIPTION:
XS GIS Cut Line= 3
      1931082.52     13893757.58      1931344.37     13893660.03
      1931421.32     13893596.53
#Sta/Elev= 30
  4786.3 1675.92  4799.6 1675.26    4821 1672.44  4831.5 1669.56  4836.8 1669.33
  4842.3 1665.14    4858 1662.52  4874.3 1661.34  4892.1 1659.39  4906.3 1659.17
    4917 1658.21  4922.5 1657.12  4927.8 1657.21  4947.5 1655.32  4952.8 1655.28
  4970.4 1653.24  4977.8 1651.84  4989.7 1651.78    4990 1651.28  4993.5 1651.28
  4993.7 1651.78  5013.5 1654.06  5033.1 1653.86  5038.5  1654.9  5065.7 1655.45
  5069.4 1656.13  5112.4 1659.13  5118.9 1660.29  5141.1 1661.79  5165.5 1664.63
#Mann= 4 ,-1 , 0
  4786.3     .07       0    4858      .1       0  4989.7     .05       0
  4993.7      .1       0
Bank Sta=4989.7,4993.7
XS Rating Curve= 0 ,0
Exp/Cntr=0.3,0.1

Type RM Length L Ch R = 1 ,2362    ,222,222,222
BEGIN DESCRIPTION:
Stream0639 4.0
END DESCRIPTION:
XS GIS Cut Line= 3
      1931074.99       13893825.        1931375.       13893875.
        1931525.       13893625.
#Sta/Elev= 30
  4690.4 1676.34  4710.7 1674.47  4723.4 1671.23    4731 1668.41  4751.2 1664.68
  4779.1 1661.67  4800.2 1660.34  4832.3 1656.97  4839.9 1655.64    4845 1655.92
  4862.8 1653.58  4933.7 1647.31  4961.6 1644.06  4966.7 1644.23  4984.4 1642.66
  4997.5 1642.77  5002.3 1643.44  5008.2 1641.88  5015.9 1641.65  5016.1 1641.15
  5019.6 1641.15  5019.9 1641.65  5087.8 1647.87  5124.8 1650.42  5146.2 1653.24
  5161.7 1653.98  5183.1 1656.36  5192.8 1656.74  5235.6  1662.5  5286.1 1666.45
#Mann= 4 ,-1 , 0
  4690.4     .07       0  4800.2      .1       0  5015.9     .05       0
  5019.9      .1       0
Bank Sta=5015.9,5019.9
XS Rating Curve= 0 ,0
Exp/Cntr=0.3,0.1

Type RM Length L Ch R = 1 ,2140    ,232,232,232
BEGIN DESCRIPTION:
Mapping XS d7e6f516
END DESCRIPTION:
XS GIS Cut Line= 3
      1931242.11     13894108.12      1931537.52     13894048.46
      1931650.53      13893950.7
#Sta/Elev= 30
    4775 1648.02    4779 1648.02  4788.2 1646.24  4808.6 1644.94  4814.8 1643.89
  4819.9 1644.39  4839.2 1642.03  4859.6 1640.93  4865.6 1639.22  4870.7 1639.69
    4880 1638.22  4900.4 1637.34  4916.4 1635.42  4921.5    1636  4967.1 1633.04
    4982  1632.6  5002.4 1632.99  5010.6 1632.46  5010.8 1631.96  5014.3 1631.96
  5014.6 1632.46  5017.9 1633.31  5063.5 1636.02  5072.5 1637.07  5098.7 1638.68
  5105.3 1639.47    5169 1643.59  5176.6 1643.77  5218.5 1647.78  5225.8 1648.04
#Mann= 3 ,-1 , 0
    4775      .1       0  5010.6     .05       0  5014.6      .1       0
Bank Sta=5010.6,5014.6
XS Rating Curve= 0 ,0
Exp/Cntr=0.3,0.1

Type RM Length L Ch R = 1 ,1908    ,245,245,245
BEGIN DESCRIPTION:
Stream0639 3.0
END DESCRIPTION:
XS GIS Cut Line= 3
      1931425.01       13894275.        1931525.       13894275.
        1931575.     13894174.99
#Sta/Elev= 30
  4900.4 1629.22  4902.9 1629.22  4910.4 1628.72  4920.4 1627.87  4930.4 1626.88
  4940.4 1626.27  4950.4 1625.08  4960.4 1624.53  4970.4 1623.01  4990.4 1621.53
  4995.9 1620.09  4996.1 1619.59  4999.6 1619.59  4999.9 1620.09  5003.2 1620.09
  5008.8 1623.55  5014.4 1623.74  5031.1 1623.67  5036.7 1623.33  5045.1  1624.2
  5053.5 1625.69  5067.5 1626.76  5075.9 1627.56  5081.4 1627.68  5084.2 1628.01
  5089.8 1628.34  5098.2 1629.17  5103.8  1629.3  5109.4  1629.7  5112.2  1629.7
#Mann= 3 ,-1 , 0
  4900.4      .1       0  4995.9     .05       0  4999.9      .1       0
#XS Ineff= 2 , 0
                         5014.39          1623.7
Permanent Ineff=
       F       F
Bank Sta=4995.9,4999.9
XS Rating Curve= 0 ,0
Exp/Cntr=0.3,0.1

Type RM Length L Ch R = 1 ,1663    ,223,223,223
BEGIN DESCRIPTION:
Mapping XS cb0c2011
END DESCRIPTION:
XS GIS Cut Line= 3
      1931519.61     13894513.89      1931690.29     13894452.29
      1931805.52     13894291.58
#Sta/Elev= 30
    4786 1628.77  4791.7 1628.64  4797.2 1627.64  4827.9 1626.56    4884 1622.25
  4889.3 1621.66    4898 1618.78  4908.7 1616.54    4920    1615    4940 1614.28
  4951.2 1614.76  4961.8  1614.1  4998.1 1609.49  5002.2 1608.28  5002.5 1607.78
    5006 1607.78  5006.2 1608.28    5019 1608.93  5025.6 1610.91  5033.7    1612
  5039.9 1611.51  5064.5 1614.52  5069.3  1615.8  5075.5 1615.85  5090.2 1618.61
  5104.9 1619.75  5119.7 1622.74  5140.6 1623.65  5160.4 1626.25  5165.2 1626.25
#Mann= 4 ,-1 , 0
    4786      .1       0  5002.2     .05       0  5006.2      .1       0
  5064.5     .07       0
#XS Ineff= 2 , 0
                         5034.17         1612.04
Permanent Ineff=
       F       F
Bank Sta=5002.2,5006.2
XS Rating Curve= 0 ,0
Exp/Cntr=0.3,0.1

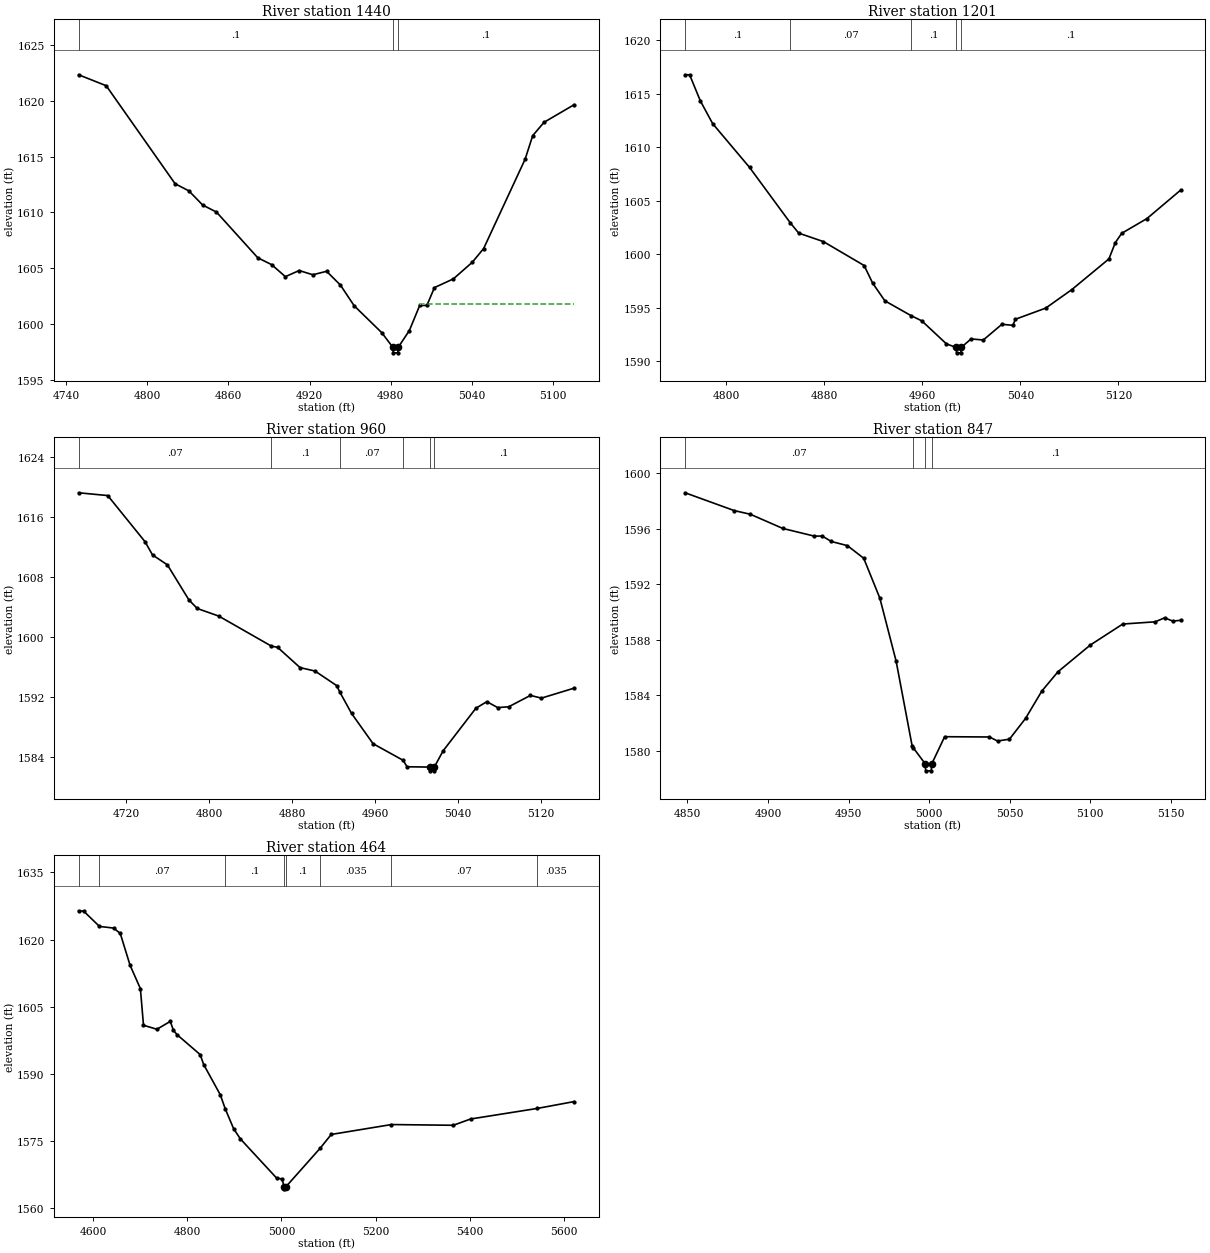
Type RM Length L Ch R = 1 ,1440    ,239,239,239
BEGIN DESCRIPTION:
Stream0639 2.0
END DESCRIPTION:
XS GIS Cut Line= 3
      1931625.02       13894625.        1931875.       13894575.
      1931924.98     13894475.03
#Sta/Elev= 30
  4749.1 1622.34  4769.5 1621.36  4820.5 1612.57  4830.7 1611.93  4840.9 1610.66
  4851.1 1610.03  4881.7 1605.93  4891.9 1605.32  4902.1 1604.24  4912.3 1604.79
  4922.4 1604.41  4932.6 1604.72  4942.8 1603.49    4953 1601.63  4973.4 1599.22
  4981.6 1597.91  4981.9 1597.41  4985.4 1597.41  4985.6 1597.91  4993.8  1599.4
  5001.5 1601.66  5006.8 1601.66  5012.4 1603.26  5026.4 1604.04  5040.4 1605.53
  5048.8 1606.76  5079.5 1614.77  5085.1 1616.88  5093.5 1618.08  5115.8 1619.66
#Mann= 3 ,-1 , 0
  4749.1      .1       0  4981.6     .05       0  4985.6      .1       0
#XS Ineff= 2 , 0
                         5001.65         1601.83
Permanent Ineff=
       F       F
Bank Sta=4981.6,4985.6
XS Rating Curve= 0 ,0
Exp/Cntr=0.3,0.1

Type RM Length L Ch R = 1 ,1201    ,241,241,241
BEGIN DESCRIPTION:
Mapping XS cac19555
END DESCRIPTION:
XS GIS Cut Line= 3
      1931692.64     13894777.38      1931959.05     13894800.78
      1932091.61     13894766.72
#Sta/Elev= 30
  4766.5 1616.77  4770.2 1616.77  4778.9 1614.34    4789  1612.2  4819.1 1608.11
  4852.4 1602.92  4859.2 1601.97  4879.3 1601.18  4912.6 1598.94  4919.5  1597.3
  4929.5 1595.64    4951 1594.25  4959.6 1593.77  4979.7 1591.62  4987.7 1591.28
    4988 1590.78  4991.5 1590.78  4991.7 1591.28  4999.8 1592.08  5009.8 1591.98
    5025 1593.45  5033.9 1593.35    5036 1593.92  5060.7 1594.96  5081.9 1596.68
  5112.3 1599.56  5117.5 1601.08  5122.7 1601.95  5143.3 1603.33  5170.8 1605.99
#Mann= 5 ,-1 , 0
  4766.5      .1       0  4852.4     .07       0    4951      .1       0
  4987.7     .05       0  4991.7      .1       0
Bank Sta=4987.7,4991.7
XS Rating Curve= 0 ,0
Exp/Cntr=0.3,0.1

Type RM Length L Ch R = 1 ,960     ,113,113,113
BEGIN DESCRIPTION:
Stream0639 1.0
END DESCRIPTION:
XS GIS Cut Line= 3
      1931624.97     13894824.97        1931875.       13895025.
      1932024.99       13894975.
#Sta/Elev= 30
    4674 1619.19  4702.1 1618.82  4738.1 1612.68  4745.3 1610.93  4759.7  1609.6
  4780.5 1604.93  4788.5  1603.8  4809.3 1602.79    4860  1598.8  4866.1 1598.63
  4887.7 1595.94  4902.2 1595.48    4923 1593.55  4926.2 1592.66  4937.4 1589.85
  4958.2 1585.82  4987.2 1583.61    4991 1582.75  5013.3 1582.71  5013.5 1582.21
    5017 1582.21  5017.3 1582.71  5025.8 1584.87  5057.4 1590.53    5068 1591.41
  5078.5 1590.62  5089.1 1590.73  5110.1 1592.24  5120.7 1591.88  5152.3 1593.21
#Mann= 6 ,-1 , 0
    4674     .07       0    4860      .1       0  4926.2     .07       0
  4987.2      .1       0  5013.3     .05       0  5017.3      .1       0
Bank Sta=5013.3,5017.3
XS Rating Curve= 0 ,0
Exp/Cntr=0.3,0.1

Type RM Length L Ch R = 1 ,847     ,383,383,383
BEGIN DESCRIPTION:
Mapping XS 4b3b7613
END DESCRIPTION:
XS GIS Cut Line= 2
      1931724.71     13895122.11      1932030.76     13895150.84
#Sta/Elev= 30
  4848.6 1598.59    4879 1597.31  4889.1 1597.04  4909.2 1596.02  4928.6 1595.47
  4933.7 1595.47  4939.3 1595.08  4949.3 1594.78  4959.4 1593.87  4969.4    1591
  4979.5 1586.46  4989.5 1580.31  4990.2  1580.2  4997.6 1579.05  4997.8 1578.55
  5001.3 1578.55  5001.6 1579.05  5009.6 1581.01  5037.4 1580.99  5042.4  1580.7
  5049.8 1580.83  5059.8 1582.33  5069.9  1584.3  5079.9 1585.69    5100 1587.62
  5120.1 1589.13  5140.2 1589.29  5146.1 1589.58  5151.1 1589.34    5156  1589.4
#Mann= 4 ,-1 , 0
  4848.6     .07       0  4990.2      .1       0  4997.6     .05       0
  5001.6      .1       0
Bank Sta=4997.6,5001.6
XS Rating Curve= 0 ,0
Exp/Cntr=0.3,0.1

Type RM Length L Ch R = 1 ,464     ,0,0,0
BEGIN DESCRIPTION:
Stream0639 0.0
END DESCRIPTION:
XS GIS Cut Line= 5
      1931440.63      13895154.6      1931699.28     13895450.63
      1931854.97     13895520.74      1932076.25     13895474.14
      1932190.07     13895236.37
#Sta/Elev= 30
  4568.8 1626.45  4579.5 1626.37  4613.1 1622.96  4643.1 1622.59  4657.3 1621.39
  4678.2 1614.28  4700.1 1609.07  4706.7  1600.9  4735.2    1600  4763.7 1601.76
  4770.3 1599.79  4777.9 1598.81  4827.2 1594.35  4834.8  1592.1    4870 1585.38
  4880.4 1582.27  4898.4 1577.79  4912.7 1575.53  4990.2 1566.73  5001.1  1566.6
  5005.8 1564.88  5006.1 1564.38  5009.8 1564.88  5082.2 1573.43  5105.9 1576.52
  5233.8 1578.73  5365.4 1578.57  5402.2 1579.97  5543.4 1582.32  5622.4 1583.86
#Mann= 8 ,-1 , 0
  4568.8      .1       0  4613.1     .07       0  4880.4      .1       0
  5005.8     .05       0  5009.8      .1       0  5082.2    .035       0
  5233.8     .07       0  5543.4    .035       0
Bank Sta=5005.8,5009.8
XS Rating Curve= 0 ,0
Exp/Cntr=0.3,0.1

Chan Stop Cuts=-1
Use User Specified Reach Order=0
Composite Channel Slope=5