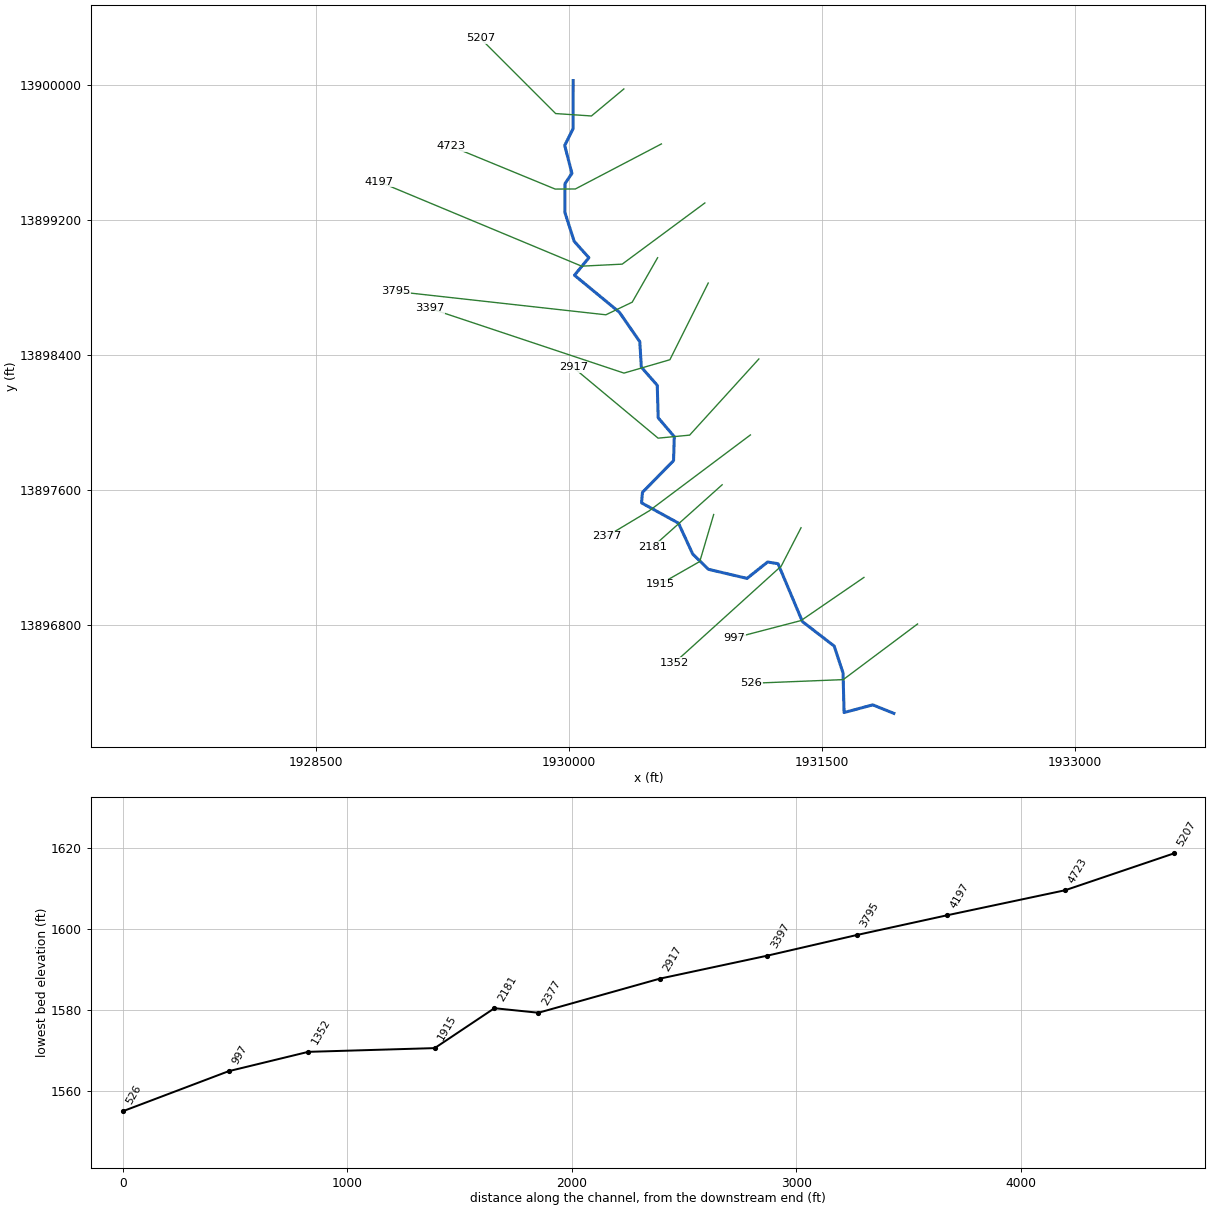
--- Stream0640.prj (project) ---

Proj Title=Stream0640 Base Level Engineering
Current Plan=p01
Default Exp/Contr=0.3,0.1
English Units
Geom File=g01
Flow File=f01
Plan File=p01
BEGIN DESCRIPTION:
Stream0640
END DESCRIPTION:

--- Stream0640.p01 (plan) ---

Plan Title=Multiple Run
Short Identifier=Multiple
Geom File=g01
Flow File=f01
Subcritical Flow
K Sum by GR= 0
Std Step Tol= 0.01
Critical Tol= 0.01
Num of Std Step Trials= 20
Max Error Tol= 0.3
Flow Tol Ratio= 0.001
Split Flow NTrial= 30
Split Flow Tol= 0.02
Split Flow Ratio= 0.02
Log Output Level= 0
Friction Slope Method= 1
Unsteady Friction Slope Method= 2
Unsteady Bridges Friction Slope Method= 1
Parabolic Critical Depth
Global Vel Dist=  1 , 1 , 1
Global Log Level= 0
CheckData=True
Encroach Param= -1, 0, 0, 0
BEGIN DESCRIPTION:
Multiple Run
END DESCRIPTION:

--- Stream0640.f01 (steady flow) ---

Flow Title=Multiple
Number of Profiles=7
Profile Names=10-year,25-year,50-year,1pct_min,100-year,1pct_plu,500-year
River Rch & RM= Stream0640,Reach-1,5207
    1213    2062    2868    1928    3847    7676    6835
Boundary for River Rch & Prof#=Stream0640,Reach-1,1
Up Type=0
Dn Type=3
Dn Slope=0.005
Boundary for River Rch & Prof#=Stream0640,Reach-1,2
Up Type=0
Dn Type=3
Dn Slope=0.005
Boundary for River Rch & Prof#=Stream0640,Reach-1,3
Up Type=0
Dn Type=3
Dn Slope=0.005
Boundary for River Rch & Prof#=Stream0640,Reach-1,4
Up Type=0
Dn Type=3
Dn Slope=0.005
Boundary for River Rch & Prof#=Stream0640,Reach-1,5
Up Type=0
Dn Type=3
Dn Slope=0.005
Boundary for River Rch & Prof#=Stream0640,Reach-1,6
Up Type=0
Dn Type=3
Dn Slope=0.005
Boundary for River Rch & Prof#=Stream0640,Reach-1,7
Up Type=0
Dn Type=3
Dn Slope=0.005

--- Stream0640.g01 (geometry) ---

Geom Title=Existing Conditions

River Reach=Stream0640,Reach-1
Reach XY= 30
      1930025.00     13900025.00      1930024.48     13899740.22
      1929974.53     13899640.16      1930017.44     13899475.00
      1929976.38     13899414.56      1929975.07     13899245.03
      1930030.55     13899072.57      1930117.89     13898974.99
      1930032.50     13898871.42      1930298.70     13898651.82
      1930419.52     13898477.44      1930428.56     13898326.47
      1930522.93     13898219.14      1930528.55     13898026.47
      1930623.96     13897914.56      1930619.55     13897772.55
      1930435.17     13897584.66      1930429.96     13897522.46
      1930648.84     13897402.15      1930733.13     13897218.93
      1930826.48     13897128.61      1931054.95     13897074.79
      1931176.68     13897171.90      1931238.56     13897162.04
      1931383.13     13896818.93      1931571.48     13896673.72
      1931623.78     13896514.50      1931630.03     13896279.92
      1931800.00     13896325.47      1931925.00     13896275.00

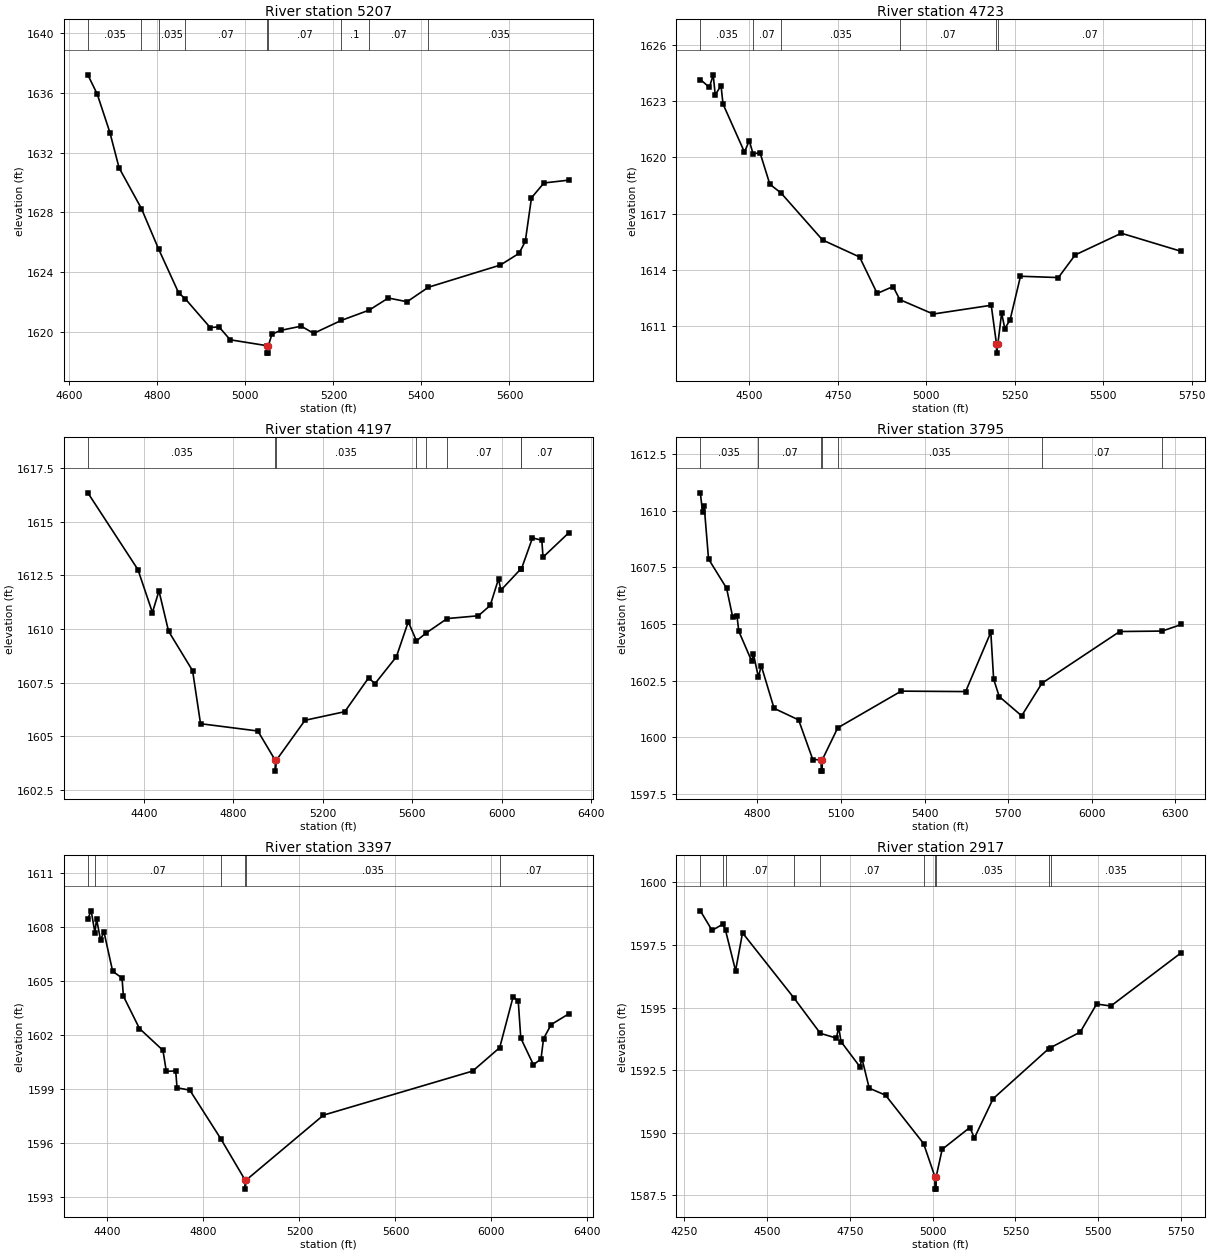
Type RM Length L Ch R = 1,5207,484,484,484
BEGIN DESCRIPTION:
Stream0640 11.0
END DESCRIPTION:
XS GIS Cut Line= 4
      1930325.04     13899975.03      1930133.07     13899815.06
      1929920.71     13899829.29      1929474.96     13900275.04
#Sta/Elev= 30
  4641.9 1637.19  4663.4 1635.89  4692.1 1633.33  4712.9 1630.98  4763.7 1628.26
  4802.7 1625.56  4848.3 1622.63  4862.9 1622.25  4919.9 1620.32  4940.0 1620.36
  4965.4 1619.50  5048.2 1619.11  5048.5 1618.61  5052.0 1618.61  5052.2 1619.11
  5060.2 1619.87  5080.3 1620.13  5126.8 1620.41  5155.1 1619.93  5217.5 1620.79
  5281.1 1621.48  5324.8 1622.29  5367.3 1622.04  5415.9 1623.01  5579.4 1624.49
  5621.8 1625.27  5636.0 1626.07  5650.1 1628.98  5678.4 1629.97  5735.0 1630.16
#Mann=9,-1,0
  4641.9   0.035       0  4763.7    0.07       0  4802.7   0.035       0
  4862.9    0.07       0  5048.2    0.05       0  5052.2    0.07       0
  5217.5     0.1       0  5281.1    0.07       0  5415.9   0.035       0
Bank Sta=5048.2,5052.2
Exp/Cntr=0.3,0.1

Type RM Length L Ch R = 1,4723,526,526,526
BEGIN DESCRIPTION:
Stream0640 10.0
END DESCRIPTION:
XS GIS Cut Line= 4
      1930547.57     13899649.35      1930037.67     13899382.45
      1929918.13     13899381.87      1929303.64     13899634.60
#Sta/Elev= 30
  4361.4 1624.17  4387.0 1623.75  4397.8 1624.42  4403.5 1623.35  4419.9 1623.84
  4425.5 1622.86  4486.1 1620.29  4499.7 1620.90  4510.4 1620.20  4530.2 1620.25
  4557.9 1618.57  4589.6 1618.10  4706.8 1615.59  4811.5 1614.68  4861.3 1612.73
  4906.1 1613.10  4925.3 1612.40  5019.6 1611.63  5183.6 1612.10  5198.4 1610.04
  5198.7 1609.54  5202.4 1610.04  5213.0 1611.69  5222.0 1610.85  5236.9 1611.32
  5266.3 1613.65  5373.4 1613.58  5420.8 1614.79  5551.4 1615.95  5720.9 1614.98
#Mann=6,-1,0
  4361.4   0.035       0  4510.4    0.07       0  4589.6   0.035       0
  4925.3    0.07       0  5198.4    0.05       0  5202.4    0.07       0
Bank Sta=5198.4,5202.4
Exp/Cntr=0.3,0.1

Type RM Length L Ch R = 1,4197,402,402,402
BEGIN DESCRIPTION:
Stream0640 9.0
END DESCRIPTION:
XS GIS Cut Line= 4
      1930805.02     13899299.53      1930315.22     13898936.99
      1930075.00     13898925.00      1928875.00     13899425.00
#Sta/Elev= 30
  4150.1 1616.34  4374.1 1612.76  4438.8 1610.76  4468.0 1611.77  4510.9 1609.89
  4618.3 1608.05  4653.8 1605.58  4909.9 1605.24  4988.0 1603.87  4988.2 1603.37
  4992.0 1603.87  5120.8 1605.74  5298.5 1606.14  5404.6 1607.71  5433.9 1607.45
  5529.2 1608.70  5582.3 1610.33  5618.9 1609.44  5662.6 1609.81  5756.2 1610.48
  5895.4 1610.61  5948.5 1611.09  5985.8 1612.33  5996.1 1611.80  6085.1 1612.79
  6088.3 1612.80  6137.5 1614.24  6179.2 1614.13  6184.6 1613.34  6300.0 1614.48
#Mann=8,-1,0
  4150.1   0.035       0  4988.0   0.035       0  4992.0   0.035       0
  5618.9    0.07       0  5662.6   0.035       0  5756.2    0.07       0
  6085.1     0.1       0  6088.3    0.07       0
Bank Sta=4988,4992
Exp/Cntr=0.3,0.1

Type RM Length L Ch R = 1,3795,398,398,398
BEGIN DESCRIPTION:
Stream0640 8.0
END DESCRIPTION:
XS GIS Cut Line= 4
      1930525.00     13898975.01      1930374.44     13898711.52
      1930218.39     13898636.85      1928975.01     13898775.00
#Sta/Elev= 30
  4594.9 1610.79  4602.8 1609.95  4608.6 1610.23  4624.4 1607.87  4689.2 1606.58
  4710.8 1605.33  4726.6 1605.35  4733.1 1604.68  4779.2 1603.37  4785.7 1603.67
  4803.4 1602.66  4813.7 1603.16  4859.8 1601.28  4947.9 1600.77  4998.8 1599.02
  5028.8 1599.01  5029.0 1598.51  5032.5 1598.51  5032.8 1599.01  5088.4 1600.42
  5316.3 1602.04  5547.7 1602.02  5638.2 1604.64  5648.3 1602.57  5668.4 1601.80
  5748.9 1600.95  5821.9 1602.39  6101.1 1604.67  6253.5 1604.69  6322.4 1604.98
#Mann=7,-1,0
  4594.9   0.035       0  4803.4    0.07       0  5028.8    0.05       0
  5032.8    0.07       0  5088.4   0.035       0  5821.9    0.07       0
  6253.5   0.035       0
Bank Sta=5028.8,5032.8
Exp/Cntr=0.3,0.1

Type RM Length L Ch R = 1,3397,480,480,480
BEGIN DESCRIPTION:
Stream0640 7.0
END DESCRIPTION:
XS GIS Cut Line= 4
      1930824.98     13898824.96      1930597.75     13898370.50
      1930325.86     13898291.38      1929174.98     13898675.01
#Sta/Elev= 30
  4318.1 1608.45  4332.0 1608.89  4347.6 1607.68  4354.4 1608.43  4371.2 1607.27
  4385.1 1607.73  4421.5 1605.53  4460.6 1605.16  4466.2 1604.15  4533.3 1602.35
  4631.1 1601.14  4645.1 1599.97  4684.2 1600.00  4689.8 1599.06  4742.9 1598.93
  4871.5 1596.24  4973.6 1593.93  4973.9 1593.43  4977.6 1593.93  5300.0 1597.54
  5921.9 1599.99  6034.4 1601.29  6090.6 1604.13  6111.7 1603.87  6122.2 1601.82
  6174.9 1600.34  6206.5 1600.66  6217.1 1601.79  6248.7 1602.57  6322.5 1603.17
#Mann=6,-1,0
  4318.1   0.035       0  4347.6    0.07       0  4871.5   0.035       0
  4973.6   0.035       0  4977.6   0.035       0  6034.4    0.07       0
Bank Sta=4973.6,4977.6
Exp/Cntr=0.3,0.1

Type RM Length L Ch R = 1,2917,540,540,540
BEGIN DESCRIPTION:
Stream0640 6.0
END DESCRIPTION:
XS GIS Cut Line= 4
      1931125.01     13898375.01      1930714.77     13897923.75
      1930527.98     13897905.85      1930025.03     13898324.97
#Sta/Elev= 30
  4298.8 1598.86  4334.3 1598.08  4367.2 1598.33  4374.9 1598.08  4405.2 1596.47
  4426.2 1597.98  4581.5 1595.38  4661.1 1593.97  4709.3 1593.78  4716.8 1594.20
  4723.5 1593.64  4780.3 1592.64  4787.0 1592.95  4808.7 1591.78  4858.0 1591.50
  4972.8 1589.57  5006.9 1588.25  5007.1 1587.75  5010.6 1587.75  5010.9 1588.25
  5029.0 1589.34  5112.6 1590.21  5126.2 1589.79  5182.8 1591.36  5350.0 1593.35
  5356.4 1593.40  5445.8 1594.02  5495.3 1595.14  5538.2 1595.06  5751.0 1597.19
#Mann=10,-1,0
  4298.8    0.07       0  4367.2   0.035       0  4374.9    0.07       0
  4581.5     0.1       0  4661.1    0.07       0  4972.8   0.035       0
  5006.9   0.035       0  5010.9   0.035       0  5350.0    0.07       0
  5356.4   0.035       0
Bank Sta=5006.9,5010.9
Exp/Cntr=0.3,0.1

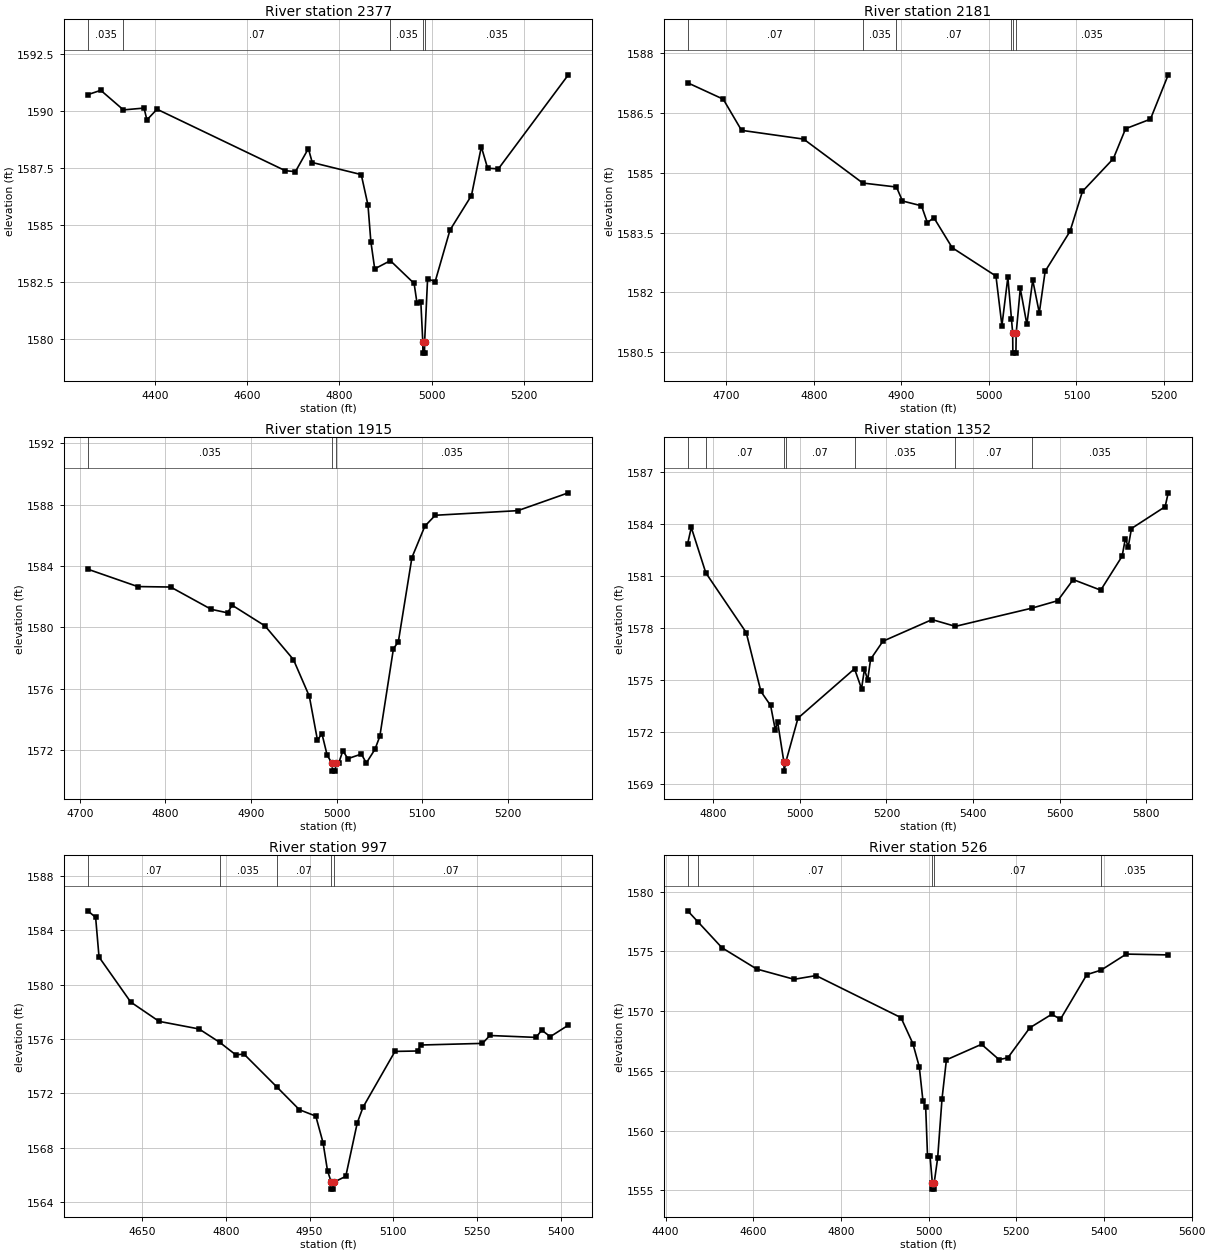
Type RM Length L Ch R = 1,2377,196,196,196
BEGIN DESCRIPTION:
Stream0640 5.0
END DESCRIPTION:
XS GIS Cut Line= 3
      1931075.01     13897925.00      1930475.00     13897475.00
      1930224.96     13897324.98
#Sta/Elev= 30
  4255.0 1590.71  4283.1 1590.90  4332.2 1590.04  4376.9 1590.12  4383.1 1589.60
  4405.0 1590.07  4683.1 1587.37  4705.0 1587.33  4733.1 1588.34  4741.5 1587.73
  4847.7 1587.20  4862.3 1585.86  4868.5 1584.26  4876.9 1583.06  4910.8 1583.42
  4962.3 1582.42  4968.5 1581.57  4976.9 1581.59  4981.1 1579.86  4981.4 1579.36
  4984.9 1579.36  4985.1 1579.86  4991.5 1582.62  5007.9 1582.50  5040.0 1584.76
  5086.6 1586.28  5108.0 1588.42  5121.6 1587.48  5144.9 1587.45  5296.6 1591.58
#Mann=5,-1,0
  4255.0   0.035       0  4332.2    0.07       0  4910.8   0.035       0
  4981.1   0.035       0  4985.1   0.035       0
Bank Sta=4981.1,4985.1
Exp/Cntr=0.3,0.1

Type RM Length L Ch R = 1,2181,266,266,266
BEGIN DESCRIPTION:
Mapping XS 432c10ed
END DESCRIPTION:
XS GIS Cut Line= 2
      1930907.43     13897629.54      1930498.31     13897263.45
#Sta/Elev= 30
  4655.8 1587.25  4696.4 1586.84  4717.3 1586.06  4788.3 1585.84  4855.8 1584.74
  4894.3 1584.64  4901.2 1584.29  4922.9 1584.17  4929.6 1583.75  4937.1 1583.87
  4958.0 1583.12  5008.0 1582.41  5014.8 1581.17  5021.6 1582.38  5025.7 1581.34
  5027.1 1580.98  5027.3 1580.48  5030.8 1580.48  5031.1 1580.98  5035.8 1582.10
  5043.3 1581.20  5050.0 1582.31  5057.5 1581.49  5064.2 1582.53  5092.6 1583.53
  5106.8 1584.53  5142.1 1585.35  5156.1 1586.10  5184.5 1586.34  5204.8 1587.45
#Mann=6,-1,0
  4655.8    0.07       0  4855.8   0.035       0  4894.3    0.07       0
  5025.7   0.035       0  5027.1    0.05       0  5031.1   0.035       0
Bank Sta=5027.1,5031.1
Exp/Cntr=0.3,0.1

Type RM Length L Ch R = 1,1915,563,563,563
BEGIN DESCRIPTION:
Stream0640 4.0
END DESCRIPTION:
XS GIS Cut Line= 3
      1930857.32     13897453.31      1930775.00     13897175.00
      1930539.34     13897040.43
#Sta/Elev= 30
  4709.3 1583.79  4767.6 1582.66  4806.1 1582.63  4853.5 1581.18  4872.7 1580.95
  4877.9 1581.45  4916.4 1580.10  4949.6 1577.91  4968.2 1575.52  4977.7 1572.66
  4982.9 1573.09  4989.1 1571.67  4994.9 1571.15  4995.2 1570.65  4998.7 1570.65
  4998.9 1571.15  5002.4 1571.15  5007.4 1571.98  5013.2 1571.46  5029.0 1571.76
  5034.8 1571.18  5044.9 1572.07  5050.6 1572.92  5066.5 1578.62  5072.2 1579.06
  5088.1 1584.55  5103.2 1586.59  5115.4 1587.30  5211.9 1587.60  5270.9 1588.76
#Mann=3,-1,0
  4709.3   0.035       0  4994.9   0.035       0  4998.9   0.035       0
Bank Sta=4994.9,4998.9
Exp/Cntr=0.3,0.1

Type RM Length L Ch R = 1,1352,355,355,355
BEGIN DESCRIPTION:
Stream0640 3.0
END DESCRIPTION:
XS GIS Cut Line= 3
      1931375.02     13897375.04      1931257.57     13897147.54
      1930625.02     13896575.02
#Sta/Elev= 30
  4741.1 1582.87  4749.4 1583.80  4782.9 1581.18  4876.2 1577.73  4910.1 1574.33
  4932.5 1573.52  4943.2 1572.13  4948.8 1572.56  4963.3 1570.23  4963.6 1569.73
  4967.3 1570.23  4995.7 1572.79  5126.2 1575.64  5142.4 1574.49  5149.1 1575.62
  5156.5 1574.99  5163.3 1576.19  5191.7 1577.23  5305.2 1578.48  5359.0 1578.09
  5535.4 1579.14  5595.2 1579.57  5631.0 1580.79  5694.5 1580.18  5743.9 1582.14
  5751.3 1583.15  5758.1 1582.70  5765.5 1583.74  5843.2 1585.00  5850.3 1585.80
#Mann=7,-1,0
  4741.1   0.035       0  4782.9    0.07       0  4963.3    0.05       0
  4967.3    0.07       0  5126.2   0.035       0  5359.0    0.07       0
  5535.4   0.035       0
Bank Sta=4963.3,4967.3
Exp/Cntr=0.3,0.1

Type RM Length L Ch R = 1,997,471,471,471
BEGIN DESCRIPTION:
Stream0640 2.0
END DESCRIPTION:
XS GIS Cut Line= 3
      1931747.70     13897080.59      1931375.00     13896825.00
      1930978.98     13896721.69
#Sta/Elev= 30
  4552.5 1585.43  4566.5 1584.95  4572.6 1582.03  4629.4 1578.72  4680.2 1577.30
  4751.9 1576.74  4789.1 1575.75  4817.6 1574.84  4832.5 1574.89  4890.9 1572.49
  4931.7 1570.80  4961.1 1570.33  4974.1 1568.37  4982.1 1566.31  4988.9 1565.46
  4989.2 1564.96  4992.7 1564.96  4992.9 1565.46  5014.8 1565.90  5035.4 1569.83
  5045.8 1570.99  5103.0 1575.09  5143.5 1575.12  5149.1 1575.56  5259.8 1575.68
  5273.1 1576.26  5355.8 1576.12  5366.1 1576.66  5381.2 1576.17  5413.7 1577.02
#Mann=5,-1,0
  4552.5    0.07       0  4789.1   0.035       0  4890.9    0.07       0
  4988.9    0.05       0  4992.9    0.07       0
Bank Sta=4988.9,4992.9
Exp/Cntr=0.3,0.1

Type RM Length L Ch R = 1,526,0,0,0
BEGIN DESCRIPTION:
Stream0640 1.0
END DESCRIPTION:
XS GIS Cut Line= 3
      1932065.43     13896804.73      1931625.00     13896475.00
      1931079.41     13896453.19
#Sta/Elev= 30
  4450.3 1578.39  4474.9 1577.42  4528.5 1575.30  4607.7 1573.52  4693.1 1572.66
  4743.1 1572.97  4936.9 1569.45  4964.0 1567.28  4978.6 1565.34  4986.9 1562.51
  4993.2 1561.96  4997.4 1557.90  5003.0 1557.90  5008.5 1555.60  5008.7 1555.10
  5012.2 1555.10  5012.5 1555.60  5020.5 1557.69  5030.5 1562.67  5040.5 1565.92
  5120.6 1567.22  5160.6 1565.94  5180.6 1566.09  5230.7 1568.60  5280.7 1569.73
  5300.7 1569.32  5360.8 1573.05  5393.5 1573.43  5450.8 1574.77  5546.5 1574.70
#Mann=5,-1,0
  4450.3   0.035       0  4474.9    0.07       0  5008.5    0.05       0
  5012.5    0.07       0  5393.5   0.035       0
Bank Sta=5008.5,5012.5
Exp/Cntr=0.3,0.1

Chan Stop Cuts=-1