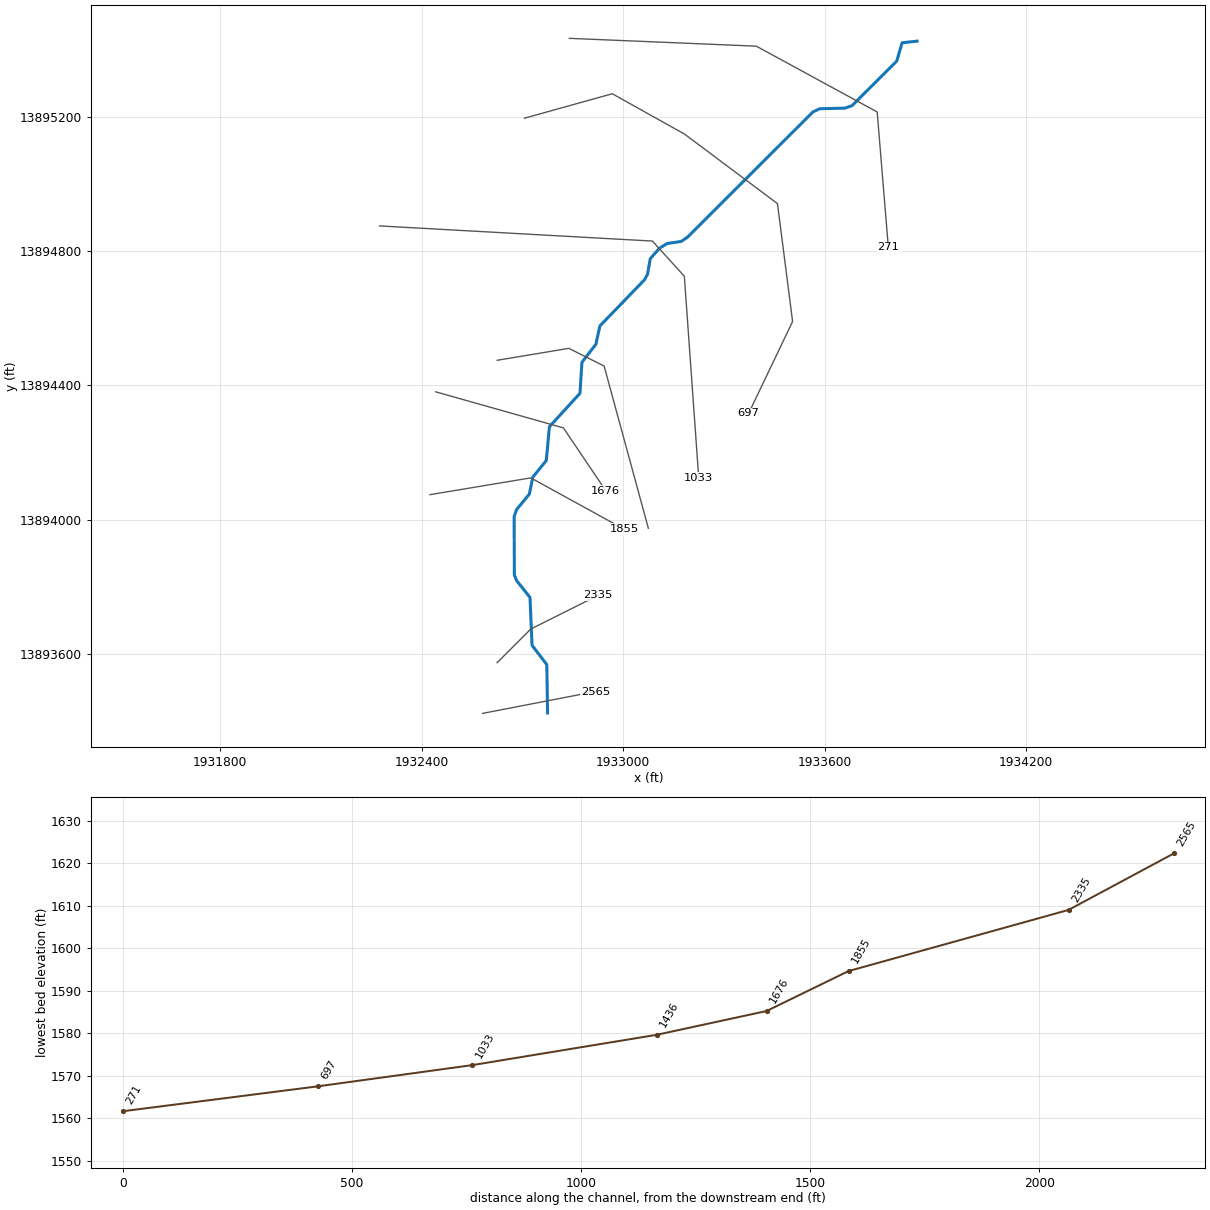
--- Stream0641.prj (project) ---

Proj Title=Stream0641 Base Level Engineering
Current Plan=p01
Default Exp/Contr=0.3,0.1
English Units
Geom File=g01
Flow File=f01
Plan File=p01
Y Axis Title=Elevation
X Axis Title(PF)=Main Channel Distance
X Axis Title(XS)=Station
BEGIN DESCRIPTION:
Stream0641
END DESCRIPTION:
DSS Export Rating Curves= 0
DSS Export Rating Curve Sorted= 0
DSS Export Volume Flow Curves= 0
DXF OffsetX= 0
DXF OffsetY= 0
DXF ScaleX= 1
DXF ScaleY= 10

--- Stream0641.p01 (plan) ---

Plan Title=Multiple Run
Short Identifier=Multiple
Geom File=g01
Flow File=f01
Subcritical Flow
K Sum by GR= 0
Std Step Tol= 0.01
Critical Tol= 0.01
Num of Std Step Trials= 20
Max Error Tol= 0.3
Flow Tol Ratio= 0.001
Split Flow NTrial= 30
Split Flow Tol= 0.02
Split Flow Ratio= 0.02
Log Output Level= 0
Friction Slope Method= 1
Unsteady Friction Slope Method= 2
Unsteady Bridges Friction Slope Method= 1
Parabolic Critical Depth
Global Vel Dist=  1 , 1 , 1
Global Log Level= 0
CheckData=True
Encroach Param= -1, 0, 0, 0
BEGIN DESCRIPTION:
Multiple Run
END DESCRIPTION:

--- Stream0641.f01 (steady flow) ---

Flow Title=Multiple
Program Version=4.10
Number of Profiles= 7
Profile Names=10-year,25-year,50-year,1pct_min,100-year,1pct_plu,500-year
River Rch & RM=Stream0641,Reach-1         ,2565
     267     412     538     342     682    1361    1077
Boundary for River Rch & Prof#=Stream0641,Reach-1         , 1
Up Type= 0
Dn Type= 3
Dn Slope=0.008
Boundary for River Rch & Prof#=Stream0641,Reach-1         , 2
Up Type= 0
Dn Type= 3
Dn Slope=0.008
Boundary for River Rch & Prof#=Stream0641,Reach-1         , 3
Up Type= 0
Dn Type= 3
Dn Slope=0.008
Boundary for River Rch & Prof#=Stream0641,Reach-1         , 4
Up Type= 0
Dn Type= 3
Dn Slope=0.008
Boundary for River Rch & Prof#=Stream0641,Reach-1         , 5
Up Type= 0
Dn Type= 3
Dn Slope=0.008
Boundary for River Rch & Prof#=Stream0641,Reach-1         , 6
Up Type= 0
Dn Type= 3
Dn Slope=0.008
Boundary for River Rch & Prof#=Stream0641,Reach-1         , 7
Up Type= 0
Dn Type= 3
Dn Slope=0.008
DSS Import GetInterval= 0
DSS Import GetPeak= 0
DSS Import FillOption= 0

--- Stream0641.g01 (geometry) ---

Geom Title=Existing Conditions
Program Version=4.10

River Reach=Stream0641      ,Reach-1
Reach XY= 30
        1932775.       13893425.      1932772.78     13893569.08
      1932728.78     13893626.57      1932722.73     13893769.06
      1932683.14     13893818.94      1932676.22     13893835.51
      1932675.51     13894009.79      1932683.09     13894031.07
      1932720.81     13894076.74      1932731.11     13894127.18
      1932771.17     13894176.59      1932780.54     13894277.42
      1932871.38      13894376.5      1932877.33     13894469.03
      1932918.86     13894522.83      1932930.83      13894577.3
      1933064.21     13894715.34      1933072.45     13894731.09
      1933080.75     13894777.54      1933107.95      13894808.5
      1933130.87     13894822.54      1933173.32     13894828.99
      1933191.66     13894841.66      1933565.21     13895214.48
      1933585.48     13895223.83      1933659.78     13895225.53
      1933681.17     13895232.86      1933814.28     13895365.46
      1933830.33     13895420.08        1933875.       13895425.

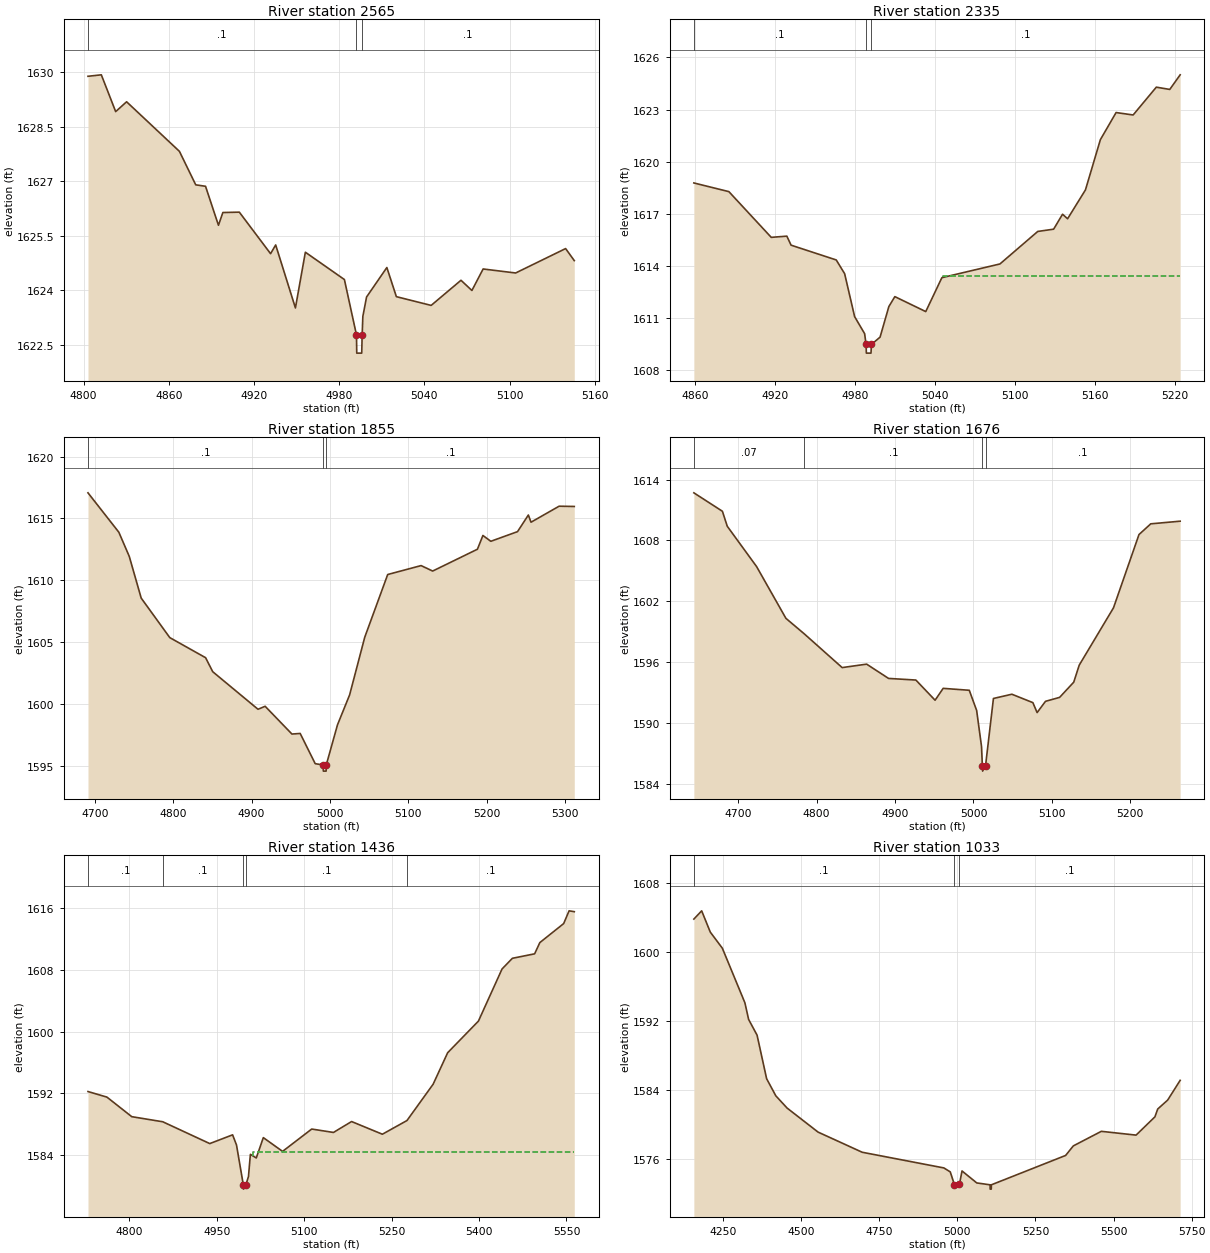
Type RM Length L Ch R = 1 ,2565    ,230,230,230
BEGIN DESCRIPTION:
Stream0641 5.0
END DESCRIPTION:
XS GIS Cut Line= 2
      1932581.77     13893423.98      1932918.03     13893489.06
#Sta/Elev= 30
  4803.1 1629.88  4812.5 1629.92  4822.6 1628.91  4830.3 1629.18  4867.5 1627.82
    4879  1626.9  4885.9 1626.86    4895 1625.79  4898.1 1626.14  4909.7 1626.15
  4931.7 1625.01  4935.3 1625.25  4949.2 1623.52  4956.2 1625.05  4983.7  1624.3
  4992.2 1622.78  4992.4 1622.28  4995.9 1622.28  4996.2 1622.78  4996.7 1623.29
  4999.3 1623.82  5013.6 1624.63  5020.3 1623.83  5044.8 1623.59  5065.8 1624.28
  5073.5    1624  5081.4 1624.59  5104.3 1624.48  5139.5 1625.15  5145.6 1624.82
#Mann= 3 ,-1 , 0
  4803.1      .1       0  4992.2     .05       0  4996.2      .1       0
Bank Sta=4992.2,4996.2
XS Rating Curve= 0 ,0
Exp/Cntr=0.3,0.1

Type RM Length L Ch R = 1 ,2335    ,480,480,480
BEGIN DESCRIPTION:
Stream0641 4.0
END DESCRIPTION:
XS GIS Cut Line= 3
      1932624.98     13893574.98        1932725.       13893675.
      1932925.04     13893775.02
#Sta/Elev= 30
    4859 1618.78  4885.3 1618.28  4917.1 1615.65  4928.8 1615.72    4932  1615.2
  4965.9 1614.35  4972.2 1613.56  4979.7 1611.09  4987.2 1610.11  4988.3 1609.49
  4988.5 1608.99    4992 1608.99  4992.3 1609.49  4998.8 1609.91  5005.4 1611.67
  5009.9 1612.24  5033.1 1611.38  5045.2 1613.33  5088.8 1614.12  5117.2 1615.99
  5129.1 1616.12  5135.8 1616.98  5139.6 1616.72    5153 1618.38  5164.2 1621.27
    5176 1622.83  5188.8 1622.69  5206.2 1624.29  5216.3 1624.16  5224.1    1625
#Mann= 3 ,-1 , 0
    4859      .1       0  4988.3     .05       0  4992.3      .1       0
#XS Ineff= 2 , 0
                         5046.24         1613.42
Permanent Ineff=
       F       F
Bank Sta=4988.3,4992.3
XS Rating Curve= 0 ,0
Exp/Cntr=0.3,0.1

Type RM Length L Ch R = 1 ,1855    ,179,179,179
BEGIN DESCRIPTION:
Stream0641 3.0
END DESCRIPTION:
XS GIS Cut Line= 3
      1932425.03       13894075.        1932725.       13894125.
       1933002.4     13893972.64
#Sta/Elev= 30
  4691.3 1617.07  4730.7 1613.89    4744 1611.94  4759.2 1608.58  4795.7 1605.39
  4841.4 1603.77  4850.5 1602.64  4908.3 1599.61  4917.4 1599.85  4951.6 1597.61
  4962.1 1597.66  4981.3 1595.22  4991.4 1595.12  4991.7 1594.62  4995.2 1594.62
  4995.4 1595.12  5009.7 1598.35  5025.2 1600.77  5044.5 1605.42  5073.8 1610.48
  5116.4  1611.2  5131.2 1610.76  5188.3 1612.52  5195.3 1613.63  5205.4 1613.16
  5239.5 1613.94  5253.3 1615.28  5256.7  1614.7  5292.5 1615.99  5311.9 1615.97
#Mann= 3 ,-1 , 0
  4691.3      .1       0  4991.4     .05       0  4995.4      .1       0
Bank Sta=4991.4,4995.4
XS Rating Curve= 0 ,0
Exp/Cntr=0.3,0.1

Type RM Length L Ch R = 1 ,1676    ,240,240,240
BEGIN DESCRIPTION:
Mapping XS 2dab32ac
END DESCRIPTION:
XS GIS Cut Line= 3
      1932442.04      13894381.1      1932822.23     13894273.73
      1932947.97      13894087.1
#Sta/Elev= 30
  4643.5  1612.7  4679.9 1610.88  4686.1  1609.4  4723.5 1605.42  4760.9 1600.31
  4784.3 1598.78  4832.6 1595.45  4863.8 1595.79  4891.8 1594.38  4926.6 1594.22
  4951.1 1592.23  4961.4  1593.4  4994.7 1593.21  5004.1 1591.22  5010.3 1587.67
  5011.4 1585.73  5011.7 1585.23  5015.4 1585.73  5025.5  1592.4    5049 1592.82
  5075.8 1591.99  5081.2 1591.01  5091.9 1592.12  5109.9 1592.51  5127.9 1594.01
  5134.9 1595.69  5178.6 1601.35  5211.1 1608.58  5226.1 1609.64  5263.6  1609.9
#Mann= 4 ,-1 , 0
  4643.5     .07       0  4784.3      .1       0  5011.4     .05       0
  5015.4      .1       0
#XS Ineff= 2 , 0
                         5053.05         1592.48
Permanent Ineff=
       F       F
Bank Sta=5011.4,5015.4
XS Rating Curve= 0 ,0
Exp/Cntr=0.3,0.1

Type RM Length L Ch R = 1 ,1436    ,403,403,403
BEGIN DESCRIPTION:
Stream0641 2.0
END DESCRIPTION:
XS GIS Cut Line= 4
      1932624.99       13894475.      1932838.39     13894510.56
      1932943.33     13894457.78      1933074.99     13893975.03
#Sta/Elev= 30
  4729.2 1592.25  4761.7 1591.53  4804.3    1589  4857.5 1588.34  4938.1 1585.52
  4977.3 1586.65    4984 1585.33  4995.8 1580.13    4996 1579.63  4999.8 1580.13
  5004.5 1581.25  5007.8 1584.13  5017.9 1583.66    5030 1586.29    5063 1584.51
    5113  1587.4  5150.3 1586.96  5181.4 1588.37  5234.2 1586.73  5276.4  1588.5
  5321.3  1593.2  5346.2 1597.27    5399 1601.36  5439.5  1608.1  5457.2 1609.48
  5495.4 1610.06  5504.3 1611.51  5545.2 1613.97  5554.5 1615.62  5563.4 1615.51
#Mann= 5 ,-1 , 0
  4729.2      .1       0  4857.5      .1       0  4995.8     .05       0
  4999.8      .1       0  5276.4      .1       0
#XS Ineff= 2 , 0
                         5012.32         1584.47
Permanent Ineff=
       F       F
Bank Sta=4995.8,4999.8
XS Rating Curve= 0 ,0
Exp/Cntr=0.3,0.1

Type RM Length L Ch R = 1 ,1033    ,336,336,336
BEGIN DESCRIPTION:
Stream0641 1.0
END DESCRIPTION:
XS GIS Cut Line= 4
      1932275.02       13894875.      1933087.15     13894829.88
      1933182.13     13894725.17        1933225.     13894124.96
#Sta/Elev= 30
  4156.8 1603.85  4181.8 1604.81  4209.4 1602.34    4248 1600.47  4320.1 1594.14
  4332.1  1592.2  4359.1 1590.38  4389.7 1585.32  4419.2 1583.33  4455.3 1581.91
  4554.4 1579.12  4695.7 1576.78  4957.1 1574.96  4977.5  1574.5  4990.8 1573.01
    5007 1573.08  5015.1 1574.61  5062.3 1573.22    5105    1573  5105.2  1572.5
  5108.7  1572.5    5109    1573  5346.7 1576.41  5371.4 1577.52    5461 1579.21
  5572.2 1578.77  5632.5 1580.89  5641.5  1581.8  5673.4 1582.84  5713.3 1585.13
#Mann= 3 ,-1 , 0
  4156.8      .1       0  4990.8     .05       0    5007      .1       0
Bank Sta=4990.8,5007
XS Rating Curve= 0 ,0
Exp/Cntr=0.3,0.1

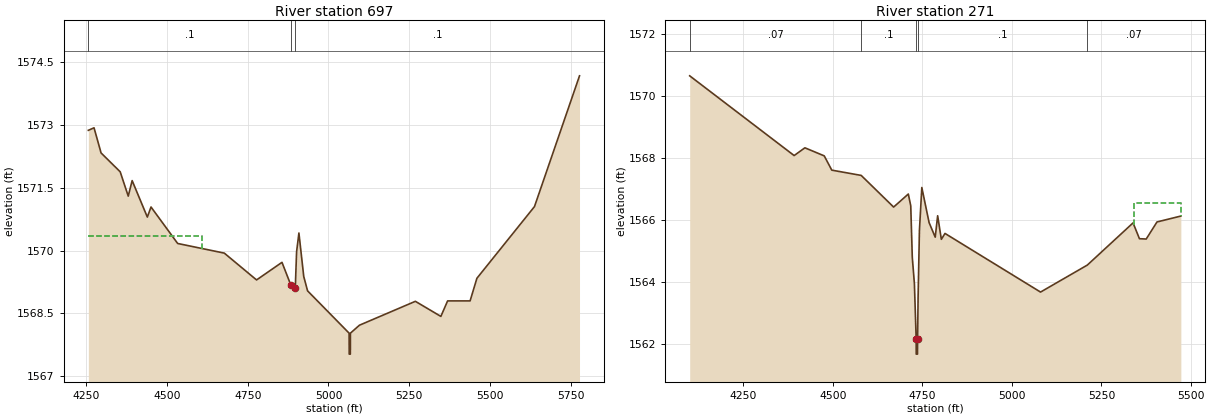
Type RM Length L Ch R = 1 ,697     ,426,426,426
BEGIN DESCRIPTION:
Stream0641 0.0
END DESCRIPTION:
XS GIS Cut Line= 6
      1932706.08     13895195.62      1932967.67     13895268.41
      1933183.08      13895148.1      1933459.32      13894941.4
      1933504.37     13894590.54       1933373.5     13894316.83
#Sta/Elev= 30
  4256.7 1572.87  4274.3 1572.93  4296.1 1572.33  4355.3 1571.88  4380.2  1571.3
  4392.3 1571.67  4439.3  1570.8  4450.7 1571.04  4533.2 1570.17  4677.5 1569.94
  4777.4  1569.3  4856.1 1569.72 4883.43 1569.18  4897.3 1569.11  4901.3 1569.97
  4908.5 1570.42  4923.5 1569.38  4935.3 1569.04  5063.9 1568.03  5064.2 1567.53
  5067.7 1567.53  5067.9 1568.03  5095.9 1568.22    5269 1568.79  5347.9 1568.43
  5368.8  1568.8  5438.4  1568.8  5459.5 1569.34  5637.7 1571.05  5777.1 1574.17
#Mann= 3 ,-1 , 0
  4256.7      .1       0 4883.43     .05       0  4897.3      .1       0
#XS Ineff= 2 , 0
         4608.82 1570.34
Permanent Ineff=
       F       F
#Block Obstruct= 2 , 0
                         4909.73         1568.84
Bank Sta=4883.43,4897.3
XS Rating Curve= 0 ,0
Exp/Cntr=0.3,0.1

Type RM Length L Ch R = 1 ,271     ,0,0,0
BEGIN DESCRIPTION:
Stream0641 0.1
END DESCRIPTION:
XS GIS Cut Line= 4
      1932839.73     13895433.36      1933396.36     13895410.06
      1933756.19     13895214.17      1933789.36     13894811.25
#Sta/Elev= 30
  4100.6 1570.64  4392.2 1568.07  4422.2 1568.32  4476.2 1568.06  4497.3  1567.6
  4579.4 1567.43  4669.9 1566.41  4710.9 1566.83  4717.7 1566.45    4722 1564.79
  4727.9 1563.94  4732.8 1562.17    4733 1561.67  4736.5 1561.67  4736.8 1562.17
  4738.2  1563.5  4741.9 1565.65  4748.6 1567.04  4768.9 1565.91    4786 1565.44
  4792.8 1566.13  4803.1 1565.37  4813.3 1565.56    5080 1563.67  5210.6 1564.54
  5338.3  1565.9  5356.1 1565.39    5375 1565.38  5405.1 1565.93  5471.7 1566.12
#Mann= 5 ,-1 , 0
  4100.6     .07       0  4579.4      .1       0  4732.8     .05       0
  4736.8      .1       0  5210.6     .07       0
#XS Ineff= 2 , 0
                          5340.6         1566.53
Permanent Ineff=
       F       F
Bank Sta=4732.8,4736.8
XS Rating Curve= 0 ,0
Exp/Cntr=0.3,0.1

Chan Stop Cuts=-1
Use User Specified Reach Order=0
Composite Channel Slope=5