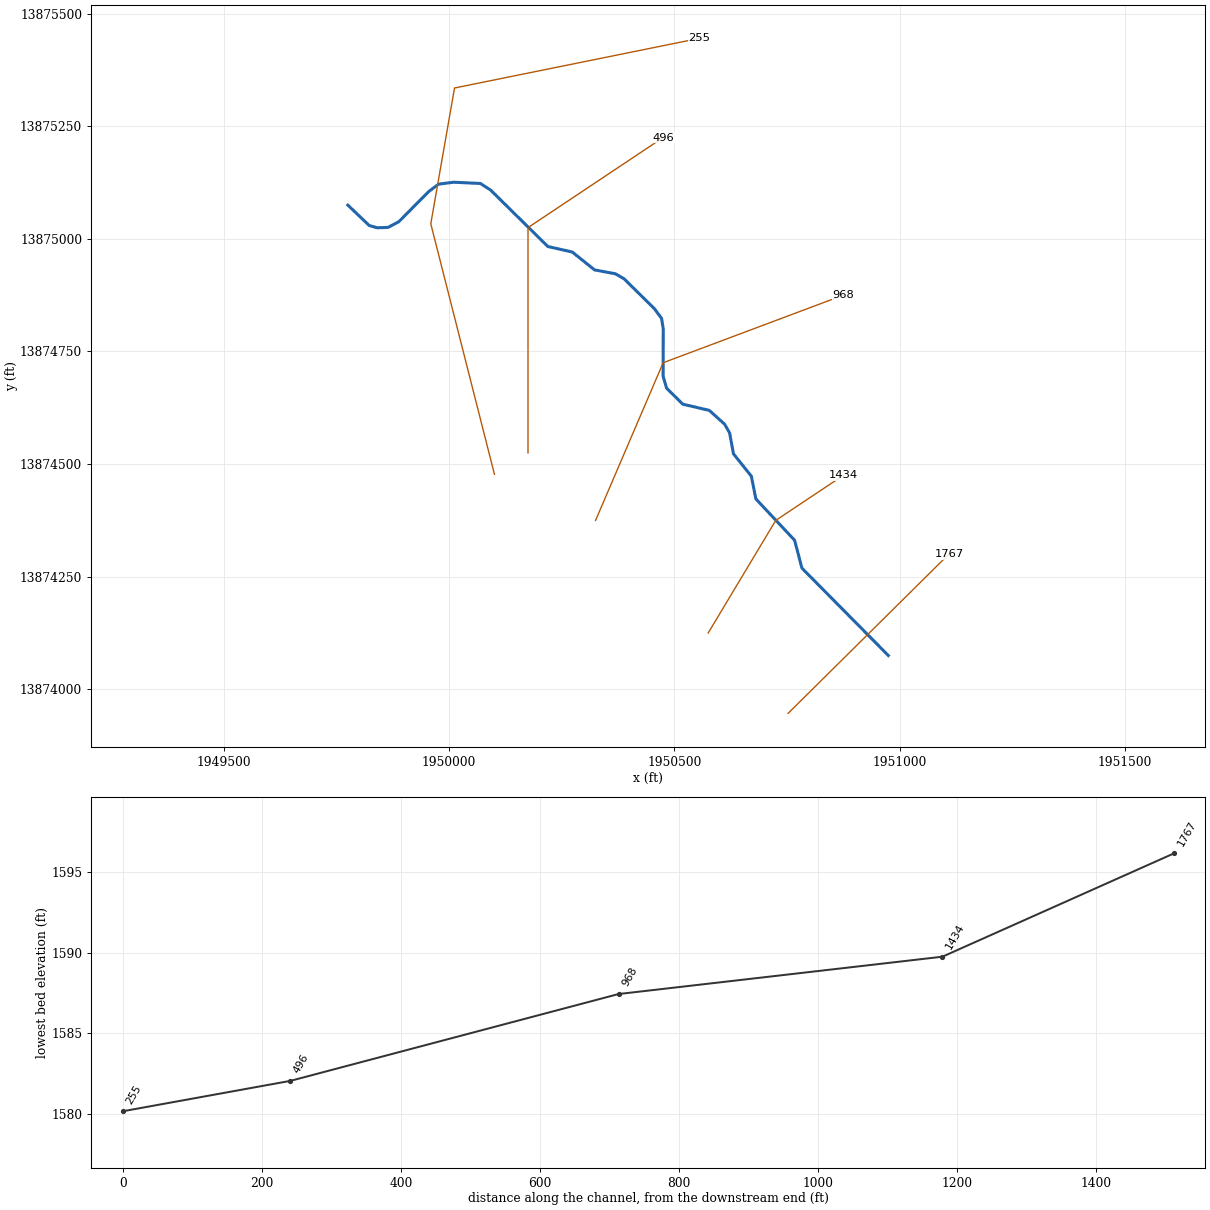
--- Stream0642.prj (project) ---

Proj Title=Stream0642 Base Level Engineering
Current Plan=p01
Default Exp/Contr=0.3,0.1
English Units
Geom File=g01
Flow File=f01
Plan File=p01
Y Axis Title=Elevation
X Axis Title(PF)=Main Channel Distance
X Axis Title(XS)=Station
BEGIN DESCRIPTION:
Stream0642
END DESCRIPTION:
DSS Export Rating Curves= 0
DSS Export Rating Curve Sorted= 0
DSS Export Volume Flow Curves= 0
DXF OffsetX= 0
DXF OffsetY= 0
DXF ScaleX= 1
DXF ScaleY= 10

--- Stream0642.p01 (plan) ---

Plan Title=Multiple Run
Short Identifier=Multiple
Geom File=g01
Flow File=f01
Subcritical Flow
K Sum by GR= 0
Std Step Tol= 0.01
Critical Tol= 0.01
Num of Std Step Trials= 20
Max Error Tol= 0.3
Flow Tol Ratio= 0.001
Split Flow NTrial= 30
Split Flow Tol= 0.02
Split Flow Ratio= 0.02
Log Output Level= 0
Friction Slope Method= 1
Unsteady Friction Slope Method= 2
Unsteady Bridges Friction Slope Method= 1
Parabolic Critical Depth
Global Vel Dist=  1 , 1 , 1
Global Log Level= 0
CheckData=True
Encroach Param= -1, 0, 0, 0
BEGIN DESCRIPTION:
Multiple Run
END DESCRIPTION:

--- Stream0642.f01 (steady flow) ---

Flow Title=Multiple
Program Version=4.10
Number of Profiles= 7
Profile Names=10-year,25-year,50-year,1pct_min,100-year,1pct_plu,500-year
River Rch & RM=Stream0642,Reach-1         ,1767
    1726    3027    4302    2956    5899   11770   10950
Boundary for River Rch & Prof#=Stream0642,Reach-1         , 1
Up Type= 0
Dn Type= 3
Dn Slope=0.008
Boundary for River Rch & Prof#=Stream0642,Reach-1         , 2
Up Type= 0
Dn Type= 3
Dn Slope=0.008
Boundary for River Rch & Prof#=Stream0642,Reach-1         , 3
Up Type= 0
Dn Type= 3
Dn Slope=0.008
Boundary for River Rch & Prof#=Stream0642,Reach-1         , 4
Up Type= 0
Dn Type= 3
Dn Slope=0.008
Boundary for River Rch & Prof#=Stream0642,Reach-1         , 5
Up Type= 0
Dn Type= 3
Dn Slope=0.008
Boundary for River Rch & Prof#=Stream0642,Reach-1         , 6
Up Type= 0
Dn Type= 3
Dn Slope=0.008
Boundary for River Rch & Prof#=Stream0642,Reach-1         , 7
Up Type= 0
Dn Type= 3
Dn Slope=0.008
DSS Import GetInterval= 0
DSS Import GetPeak= 0
DSS Import FillOption= 0

--- Stream0642.g01 (geometry) ---

Geom Title=Existing Conditions
Program Version=4.10

River Reach=Stream0642      ,Reach-1
Reach XY= 30
        1950975.       13874075.      1950783.16     13874268.95
      1950766.82     13874331.04      1950680.85     13874422.71
      1950670.81     13874473.27      1950631.11     13874522.84
      1950622.58     13874569.15      1950611.52     13874588.56
      1950577.51     13874619.24      1950518.64     13874633.03
       1950482.7     13874668.53      1950474.94     13874694.89
      1950475.27     13874800.11      1950471.46     13874823.54
      1950455.41      13874845.2      1950388.24     13874911.39
      1950368.97     13874922.51      1950322.81      13874931.1
      1950273.26     13874970.81      1950218.94     13874983.14
      1950091.75      13875108.6      1950069.11     13875123.04
      1950009.92     13875125.79       1949976.5     13875121.53
      1949954.86     13875105.37      1949888.22     13875038.17
      1949864.45      13875025.5      1949840.43     13875024.68
      1949822.65     13875029.57        1949775.       13875075.

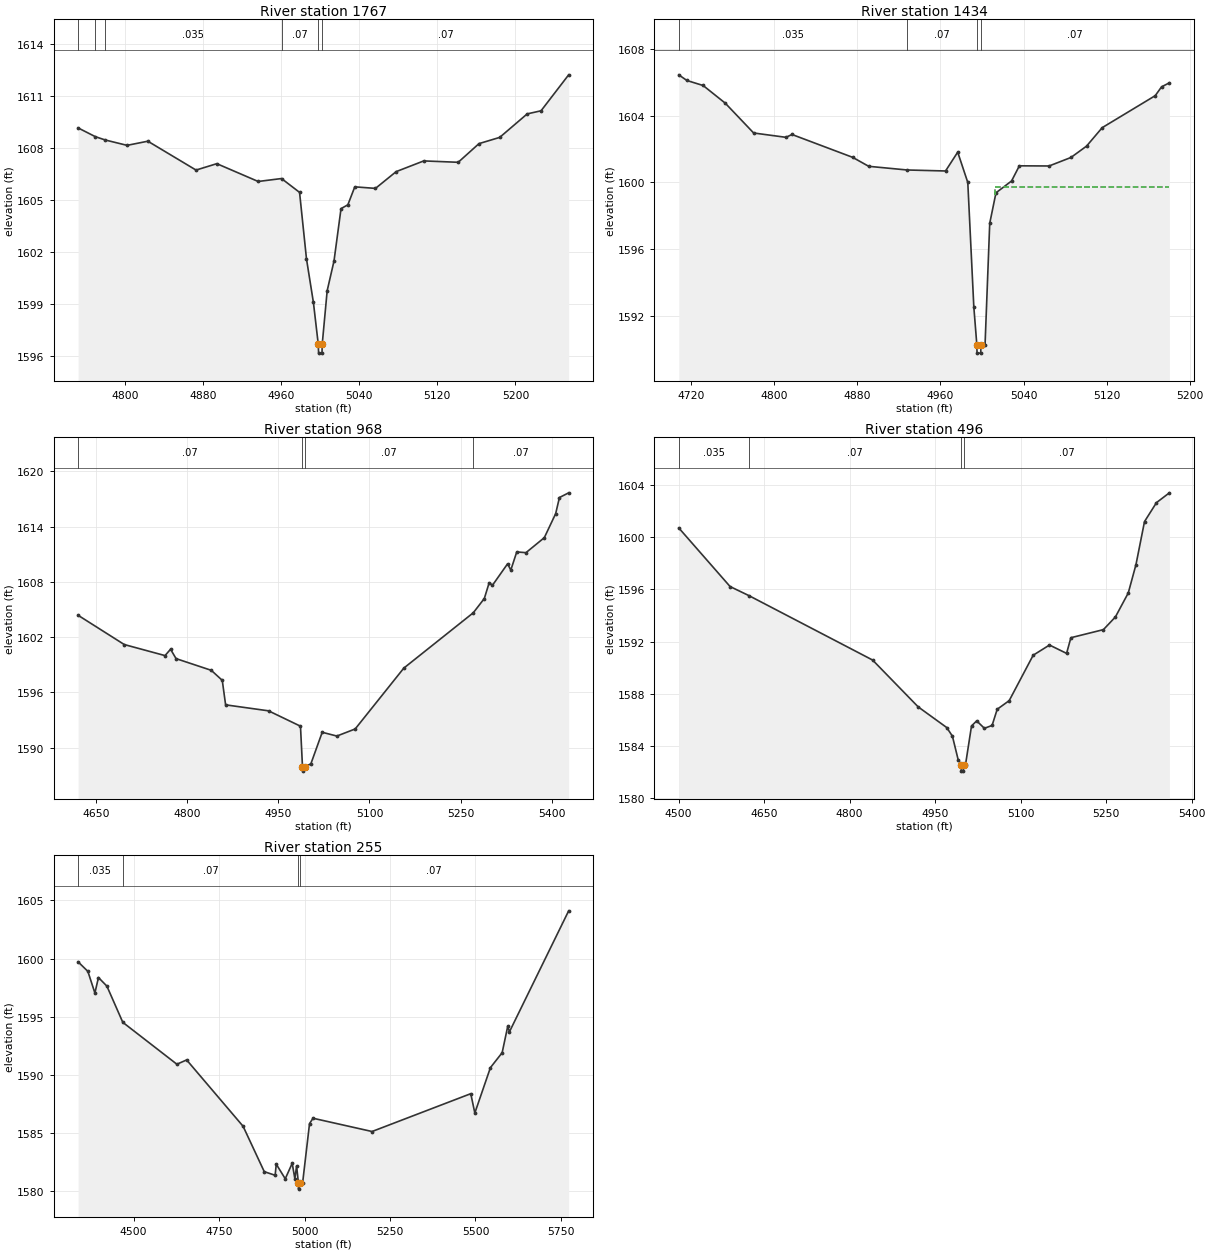
Type RM Length L Ch R = 1 ,1767    ,333,333,333
BEGIN DESCRIPTION:
Stream0642 4.0
END DESCRIPTION:
XS GIS Cut Line= 2
      1950752.38      13873946.6      1951109.65     13874300.39
#Sta/Elev= 30
  4751.8 1609.17  4769.6 1608.66  4779.7 1608.47    4802 1608.16  4823.3  1608.4
  4872.7 1606.73    4894  1607.1  4936.4 1606.07  4960.3 1606.24  4978.8 1605.44
  4985.9 1601.59    4993 1599.07    4998 1596.64  4998.3 1596.14  5001.8 1596.14
    5002 1596.64  5007.1 1599.75  5014.1 1601.47  5021.3  1604.5  5028.3 1604.72
  5035.4 1605.76  5056.6 1605.67  5077.8 1606.64  5106.1 1607.26  5141.4 1607.18
  5162.7 1608.26  5183.9 1608.62  5212.1 1609.98  5226.3 1610.16  5254.6 1612.24
#Mann= 6 ,-1 , 0
  4751.8    .035       0  4769.6     .07       0  4779.7    .035       0
  4960.3     .07       0    4998     .05       0    5002     .07       0
Bank Sta=4998,5002
XS Rating Curve= 0 ,0
Exp/Cntr=0.3,0.1

Type RM Length L Ch R = 1 ,1434    ,466,466,466
BEGIN DESCRIPTION:
Stream0642 3.0
END DESCRIPTION:
XS GIS Cut Line= 3
      1950574.98     13874124.97        1950725.       13874375.
      1950875.03     13874475.02
#Sta/Elev= 30
  4708.4 1606.45  4716.2 1606.11  4731.8 1605.81  4753.1 1604.75  4780.4 1602.96
  4811.5  1602.7  4817.3 1602.87  4875.6  1601.5  4891.1 1600.96    4928 1600.74
    4965 1600.68  4976.7 1601.81  4986.4 1599.99  4992.2 1592.52  4995.1 1590.25
  4995.3 1589.75  4998.8 1589.75  4999.1 1590.25    5003 1590.25  5007.5 1597.54
  5013.5 1599.37  5028.5 1600.08    5036 1600.99  5064.6 1600.98  5085.6 1601.49
  5100.6 1602.17  5115.7 1603.28  5166.7  1605.2  5172.8 1605.73  5180.3 1605.97
#Mann= 4 ,-1 , 0
  4708.4    .035       0    4928     .07       0  4995.1     .05       0
  4999.1     .07       0
#XS Ineff= 2 , 0
                         5012.99         1599.71
Permanent Ineff=
       F       F
Bank Sta=4995.1,4999.1
XS Rating Curve= 0 ,0
Exp/Cntr=0.3,0.1

Type RM Length L Ch R = 1 ,968     ,472,472,472
BEGIN DESCRIPTION:
Stream0642 2.0
END DESCRIPTION:
XS GIS Cut Line= 3
      1950325.01     13874375.02        1950475.       13874725.
      1950875.03     13874875.01
#Sta/Elev= 30
  4620.1 1604.37  4696.2 1601.19  4763.3 1599.99  4772.4 1600.68  4781.5 1599.66
  4839.5 1598.39  4857.6  1597.3  4863.1 1594.64  4933.8 1593.99  4986.4 1592.32
  4989.7 1587.94    4990 1587.44  4993.8 1587.94  5003.5 1588.23  5022.2 1591.66
  5046.3 1591.25  5076.5 1592.02  5156.6 1598.63    5271 1604.64  5289.2 1606.19
  5297.2 1607.91  5302.6 1607.63  5327.5 1609.96  5332.8 1609.28  5342.6 1611.25
  5357.8 1611.17    5388  1612.8  5406.7 1615.41  5412.9 1617.16  5428.1 1617.67
#Mann= 4 ,-1 , 0
  4620.1     .07       0  4989.7     .05       0  4993.8     .07       0
    5271     .07       0
Bank Sta=4989.7,4993.8
XS Rating Curve= 0 ,0
Exp/Cntr=0.3,0.1

Type RM Length L Ch R = 1 ,496     ,241,241,241
BEGIN DESCRIPTION:
Stream0642 1.0
END DESCRIPTION:
XS GIS Cut Line= 3
        1950175.     13874524.97        1950175.       13875025.
      1950475.02     13875225.01
#Sta/Elev= 30
  4500.3  1600.7  4590.3 1596.21  4623.6 1595.51  4840.3 1590.58  4920.3 1586.99
  4970.3 1585.41  4980.3 1584.75  4990.3 1582.96  4995.8 1582.57    4996 1582.07
  4999.6 1582.07  4999.9 1582.57  5003.3 1582.57  5013.8 1585.53  5022.9 1585.92
  5036.4 1585.35  5049.9 1585.57  5058.9 1586.81  5079.9 1587.47    5122 1590.95
  5150.6 1591.73  5180.6 1591.09  5188.1 1592.29  5245.2 1592.91  5266.2 1593.88
  5288.8 1595.72  5302.3 1597.89  5317.3 1601.19  5338.3 1602.64  5360.9 1603.39
#Mann= 4 ,-1 , 0
  4500.3    .035       0  4623.6     .07       0  4995.8     .05       0
  4999.9     .07       0
#XS Ineff= 2 , 0
                         5152.52         1591.68
Permanent Ineff=
       F       F
Bank Sta=4995.8,4999.9
XS Rating Curve= 0 ,0
Exp/Cntr=0.3,0.1

Type RM Length L Ch R = 1 ,255     ,0,0,0
BEGIN DESCRIPTION:
Stream0642 0.0
END DESCRIPTION:
XS GIS Cut Line= 4
      1950100.53     13874477.28      1949959.17     13875033.49
      1950011.89     13875334.96      1950555.59     13875445.22
#Sta/Elev= 30
  4337.8 1599.72  4366.4  1598.9    4387 1597.04  4397.4 1598.37  4422.1 1597.63
  4468.6 1594.52  4626.8 1590.92  4655.3 1591.29  4820.4 1585.59  4882.3 1581.69
  4914.1 1581.38  4917.4 1582.33  4943.7 1581.08    4964 1582.41  4971.8 1581.08
  4976.9 1582.19  4982.2 1580.69  4982.5 1580.19  4986.3 1580.69  4994.4 1580.71
  5014.7 1585.82  5024.9 1586.28  5197.5 1585.14  5486.2 1588.39  5498.1 1586.73
  5543.7 1590.63    5578 1591.91  5594.3 1594.18  5599.4 1593.71  5772.5  1604.1
#Mann= 4 ,-1 , 0
  4337.8    .035       0  4468.6     .07       0  4982.2     .05       0
  4986.3     .07       0
#XS Ineff= 2 , 0
                         5027.77          1586.1
Permanent Ineff=
       F       F
Bank Sta=4982.2,4986.3
XS Rating Curve= 0 ,0
Exp/Cntr=0.3,0.1

Chan Stop Cuts=-1
Use User Specified Reach Order=0
Composite Channel Slope=5