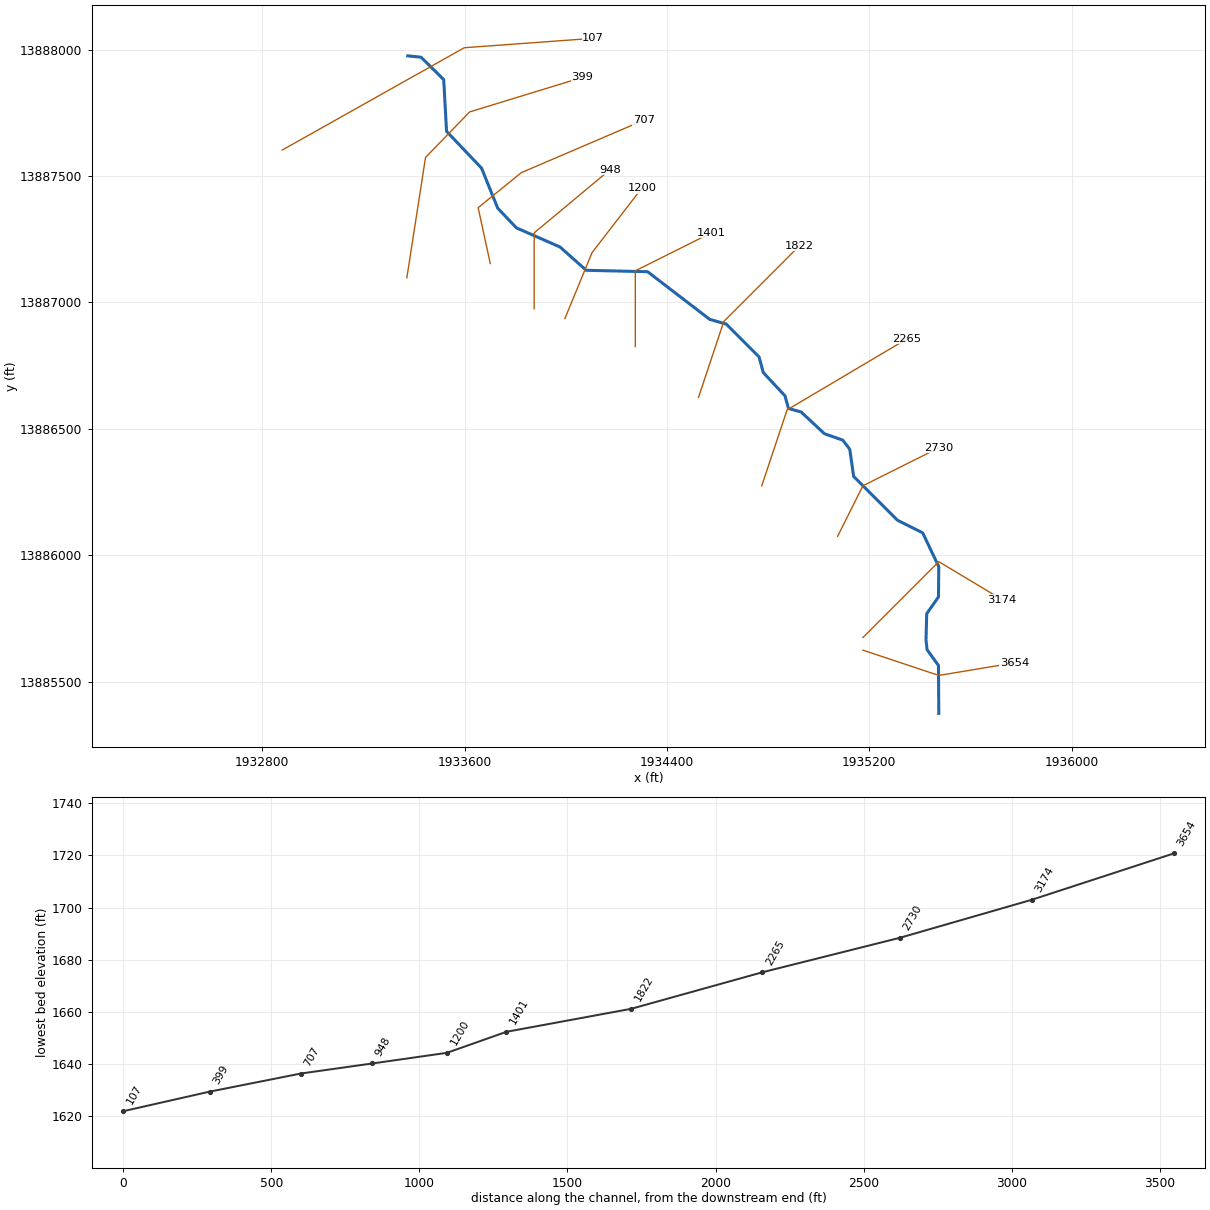
--- Stream0643.prj (project) ---

Proj Title=Stream0643 Base Level Engineering
Current Plan=p01
Default Exp/Contr=0.3,0.1
English Units
Geom File=g01
Flow File=f01
Plan File=p01
BEGIN DESCRIPTION:
Stream0643
END DESCRIPTION:

--- Stream0643.p01 (plan) ---

Plan Title=Multiple Run
Short Identifier=Multiple
Geom File=g01
Flow File=f01
Subcritical Flow
K Sum by GR= 0
Std Step Tol= 0.01
Critical Tol= 0.01
Num of Std Step Trials= 20
Max Error Tol= 0.3
Flow Tol Ratio= 0.001
Split Flow NTrial= 30
Split Flow Tol= 0.02
Split Flow Ratio= 0.02
Log Output Level= 0
Friction Slope Method= 1
Unsteady Friction Slope Method= 2
Unsteady Bridges Friction Slope Method= 1
Parabolic Critical Depth
Global Vel Dist=  1 , 1 , 1
Global Log Level= 0
CheckData=True
Encroach Param= -1, 0, 0, 0
BEGIN DESCRIPTION:
Multiple Run
END DESCRIPTION:

--- Stream0643.f01 (steady flow) ---

Flow Title=Multiple
Number of Profiles=7
Profile Names=10-year,25-year,50-year,1pct_min,100-year,1pct_plu,500-year
River Rch & RM= Stream0643,Reach-1,3654
     715    1188    1630    1085    2165    4319    3763
River Rch & RM= Stream0643,Reach-1,107
    2300    4066    5807    4001    7982   15927   14908
Boundary for River Rch & Prof#=Stream0643,Reach-1,1
Up Type=0
Dn Type=3
Dn Slope=0.005
Boundary for River Rch & Prof#=Stream0643,Reach-1,2
Up Type=0
Dn Type=3
Dn Slope=0.005
Boundary for River Rch & Prof#=Stream0643,Reach-1,3
Up Type=0
Dn Type=3
Dn Slope=0.005
Boundary for River Rch & Prof#=Stream0643,Reach-1,4
Up Type=0
Dn Type=3
Dn Slope=0.005
Boundary for River Rch & Prof#=Stream0643,Reach-1,5
Up Type=0
Dn Type=3
Dn Slope=0.005
Boundary for River Rch & Prof#=Stream0643,Reach-1,6
Up Type=0
Dn Type=3
Dn Slope=0.005
Boundary for River Rch & Prof#=Stream0643,Reach-1,7
Up Type=0
Dn Type=3
Dn Slope=0.005

--- Stream0643.g01 (geometry) ---

Geom Title=Existing Conditions

River Reach=Stream0643,Reach-1
Reach XY= 30
      1935475.00     13885375.00      1935473.79     13885564.50
      1935428.77     13885626.57      1935424.50     13885664.83
      1935427.25     13885769.06      1935473.79     13885835.51
      1935474.96     13885954.97      1935411.53     13886088.57
      1935311.80     13886138.64      1935138.41     13886311.70
      1935122.92     13886419.29      1935095.57     13886455.41
      1935022.74     13886480.88      1934930.74     13886566.70
      1934880.62     13886580.62      1934866.70     13886630.74
      1934780.87     13886722.72      1934764.22     13886784.68
      1934634.68     13886914.22      1934568.96     13886933.18
      1934323.53     13887121.45      1934080.86     13887127.06
      1933977.29     13887219.15      1933804.87     13887294.77
      1933730.83     13887372.69      1933666.86     13887531.06
      1933528.54     13887676.46      1933517.21     13887881.21
      1933427.54     13887969.70      1933375.00     13887975.00

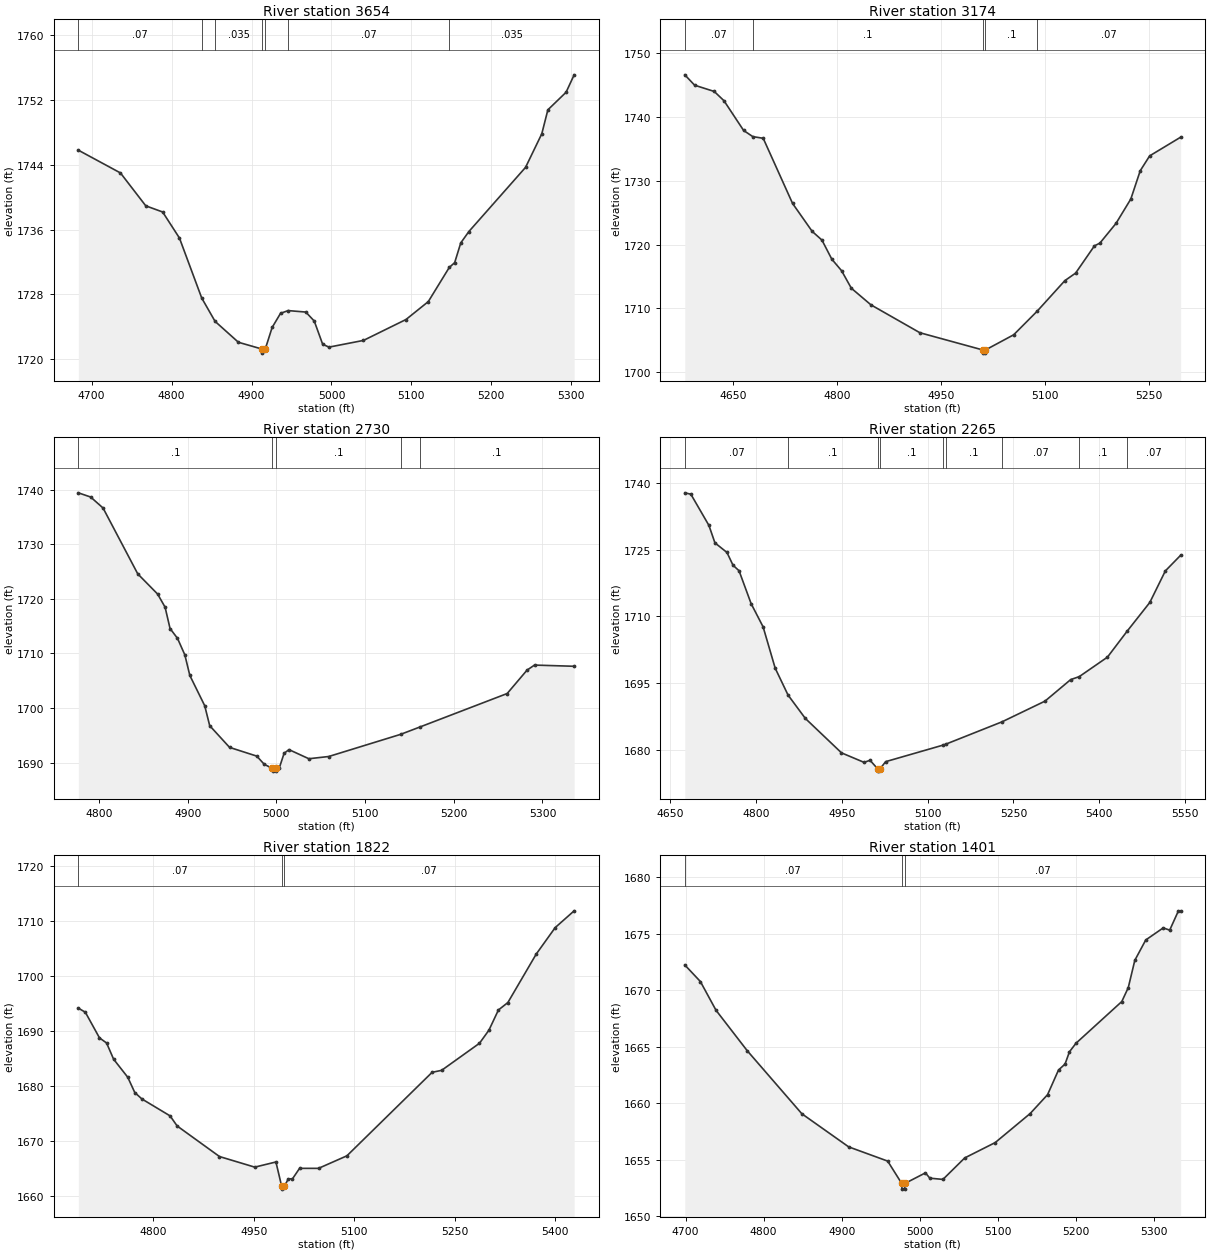
Type RM Length L Ch R = 1,3654,480,480,480
BEGIN DESCRIPTION:
Stream0643 7.0
END DESCRIPTION:
XS GIS Cut Line= 3
      1935174.96     13885625.01      1935475.00     13885525.00
      1935774.99     13885575.00
#Sta/Elev= 30
  4683.3 1745.80  4736.0 1742.99  4767.7 1738.93  4788.8 1738.17  4809.8 1734.96
  4837.7 1727.55  4854.4 1724.67  4883.6 1722.09  4913.2 1721.25  4913.5 1720.75
  4917.2 1721.25  4925.8 1723.92  4936.3 1725.66  4945.8 1726.00  4967.9 1725.82
  4978.5 1724.71  4989.0 1721.85  4996.9 1721.49  5040.1 1722.32  5093.3 1724.90
  5121.2 1727.11  5147.4 1731.32  5154.2 1731.92  5161.8 1734.35  5171.9 1735.75
  5242.9 1743.68  5263.2 1747.82  5270.8 1750.78  5293.6 1752.95  5303.7 1755.10
#Mann=7,-1,0
  4683.3    0.07       0  4837.7     0.1       0  4854.4   0.035       0
  4913.2    0.05       0  4917.2   0.035       0  4945.8    0.07       0
  5147.4   0.035       0
Bank Sta=4913.2,4917.2
Exp/Cntr=0.3,0.1

Type RM Length L Ch R = 1,3174,444,444,444
BEGIN DESCRIPTION:
Stream0643 6.0
END DESCRIPTION:
XS GIS Cut Line= 3
      1935174.98     13885674.98      1935475.00     13885975.00
      1935724.96     13885825.02
#Sta/Elev= 30
  4580.2 1746.65  4594.4 1745.02  4622.7 1744.04  4636.8 1742.58  4665.1 1737.92
  4678.4 1736.95  4693.4 1736.69  4735.8 1726.46  4764.1 1722.08  4778.2 1720.71
  4792.4 1717.72  4806.5 1715.91  4820.6 1713.16  4848.9 1710.55  4919.6 1706.17
  5010.3 1703.47  5010.5 1702.97  5014.0 1702.97  5014.3 1703.47  5055.0 1705.85
  5088.7 1709.53  5128.9 1714.35  5144.4 1715.53  5171.6 1719.81  5179.4 1720.23
  5202.7 1723.33  5224.1 1727.16  5237.7 1731.60  5251.3 1733.93  5296.0 1736.86
#Mann=5,-1,0
  4580.2    0.07       0  4678.4     0.1       0  5010.3    0.05       0
  5014.3     0.1       0  5088.7    0.07       0
Bank Sta=5010.3,5014.3
Exp/Cntr=0.3,0.1

Type RM Length L Ch R = 1,2730,465,465,465
BEGIN DESCRIPTION:
Stream0643 5.0
END DESCRIPTION:
XS GIS Cut Line= 3
      1935075.02     13886075.04      1935175.00     13886275.00
      1935475.02     13886425.01
#Sta/Elev= 30
  4776.7 1739.43  4790.6 1738.66  4804.6 1736.64  4843.7 1724.58  4866.1 1720.88
  4874.5 1718.48  4880.1 1714.57  4888.5 1712.77  4896.8 1709.73  4902.4 1705.97
  4919.2 1700.42  4924.8 1696.77  4947.2 1692.79  4977.9 1691.19  4986.3 1689.69
  4995.5 1688.94  4995.7 1688.44  4999.2 1688.44  4999.5 1688.94  5003.1 1688.94
  5008.7 1691.71  5014.2 1692.38  5036.6 1690.71  5059.0 1691.12  5140.1 1695.18
  5162.2 1696.55  5260.2 1702.66  5282.6 1706.95  5291.0 1707.87  5335.7 1707.65
#Mann=5,-1,0
  4776.7     0.1       0  4995.5    0.05       0  4999.5     0.1       0
  5140.1    0.07       0  5162.2     0.1       0
Bank Sta=4995.5,4999.5
Exp/Cntr=0.3,0.1

Type RM Length L Ch R = 1,2265,443,443,443
BEGIN DESCRIPTION:
Stream0643 4.0
END DESCRIPTION:
XS GIS Cut Line= 3
      1934775.00     13886274.99      1934875.00     13886575.00
      1935349.13     13886855.83
#Sta/Elev= 30
  4675.2 1737.80  4685.8 1737.49  4717.4 1730.47  4727.9 1726.55  4749.0 1724.38
  4759.5 1721.52  4770.1 1720.27  4791.2 1712.88  4812.2 1707.64  4833.3 1698.36
  4855.8 1692.31  4886.0 1687.06  4949.3 1679.31  4988.8 1677.17  4999.2 1677.64
  5012.7 1675.70  5012.9 1675.20  5016.7 1675.70  5026.5 1677.33  5126.4 1681.03
  5131.5 1681.25  5230.1 1686.29  5305.2 1690.94  5350.2 1695.79  5365.1 1696.45
  5414.5 1700.84  5448.6 1706.62  5488.6 1713.14  5515.8 1720.24  5542.5 1723.75
#Mann=9,-1,0
  4675.2    0.07       0  4855.8     0.1       0  5012.7    0.05       0
  5016.7     0.1       0  5126.4    0.07       0  5131.5     0.1       0
  5230.1    0.07       0  5365.1     0.1       0  5448.6    0.07       0
Bank Sta=5012.7,5016.7
Exp/Cntr=0.3,0.1

Type RM Length L Ch R = 1,1822,421,421,421
BEGIN DESCRIPTION:
Stream0643 3.0
END DESCRIPTION:
XS GIS Cut Line= 3
      1934525.00     13886625.00      1934625.00     13886925.00
      1934925.00     13887225.00
#Sta/Elev= 30
  4688.1 1694.13  4698.6 1693.37  4719.7 1688.71  4730.3 1687.78  4740.8 1684.83
  4761.9 1681.55  4772.4 1678.77  4783.0 1677.60  4825.1 1674.52  4835.7 1672.68
  4898.9 1667.12  4951.6 1665.19  4983.2 1666.13  4991.8 1661.69  4992.0 1661.19
  4995.8 1661.69  5001.7 1663.06  5007.9 1663.06  5018.5 1664.97  5046.8 1664.97
  5089.2 1667.25  5216.5 1682.45  5230.6 1682.80  5287.2 1687.73  5301.3 1690.11
  5315.5 1693.79  5329.6 1695.14  5372.0 1703.97  5400.3 1708.78  5428.6 1711.83
#Mann=3,-1,0
  4688.1    0.07       0  4991.8    0.05       0  4995.8    0.07       0
Bank Sta=4991.8,4995.8
Exp/Cntr=0.3,0.1

Type RM Length L Ch R = 1,1401,201,201,201
BEGIN DESCRIPTION:
Stream0643 2.0
END DESCRIPTION:
XS GIS Cut Line= 3
      1934275.00     13886824.99      1934275.00     13887125.00
      1934574.98     13887274.99
#Sta/Elev= 30
  4699.0 1672.22  4719.0 1670.75  4739.0 1668.21  4779.0 1664.63  4849.0 1659.05
  4909.0 1656.12  4959.0 1654.86  4977.0 1652.88  4977.3 1652.38  4980.8 1652.38
  4981.0 1652.88  5007.4 1653.82  5013.0 1653.35  5029.8 1653.24  5057.7 1655.14
  5096.8 1656.50  5141.6 1659.07  5163.9 1660.74  5177.9 1662.92  5186.3 1663.45
  5191.9 1664.53  5200.3 1665.29  5259.0 1668.98  5267.3 1670.21  5275.7 1672.63
  5289.7 1674.43  5312.1 1675.50  5320.4 1675.30  5331.6 1677.01  5334.4 1677.01
#Mann=3,-1,0
  4699.0    0.07       0  4977.0    0.05       0  4981.0    0.07       0
Bank Sta=4977,4981
Exp/Cntr=0.3,0.1

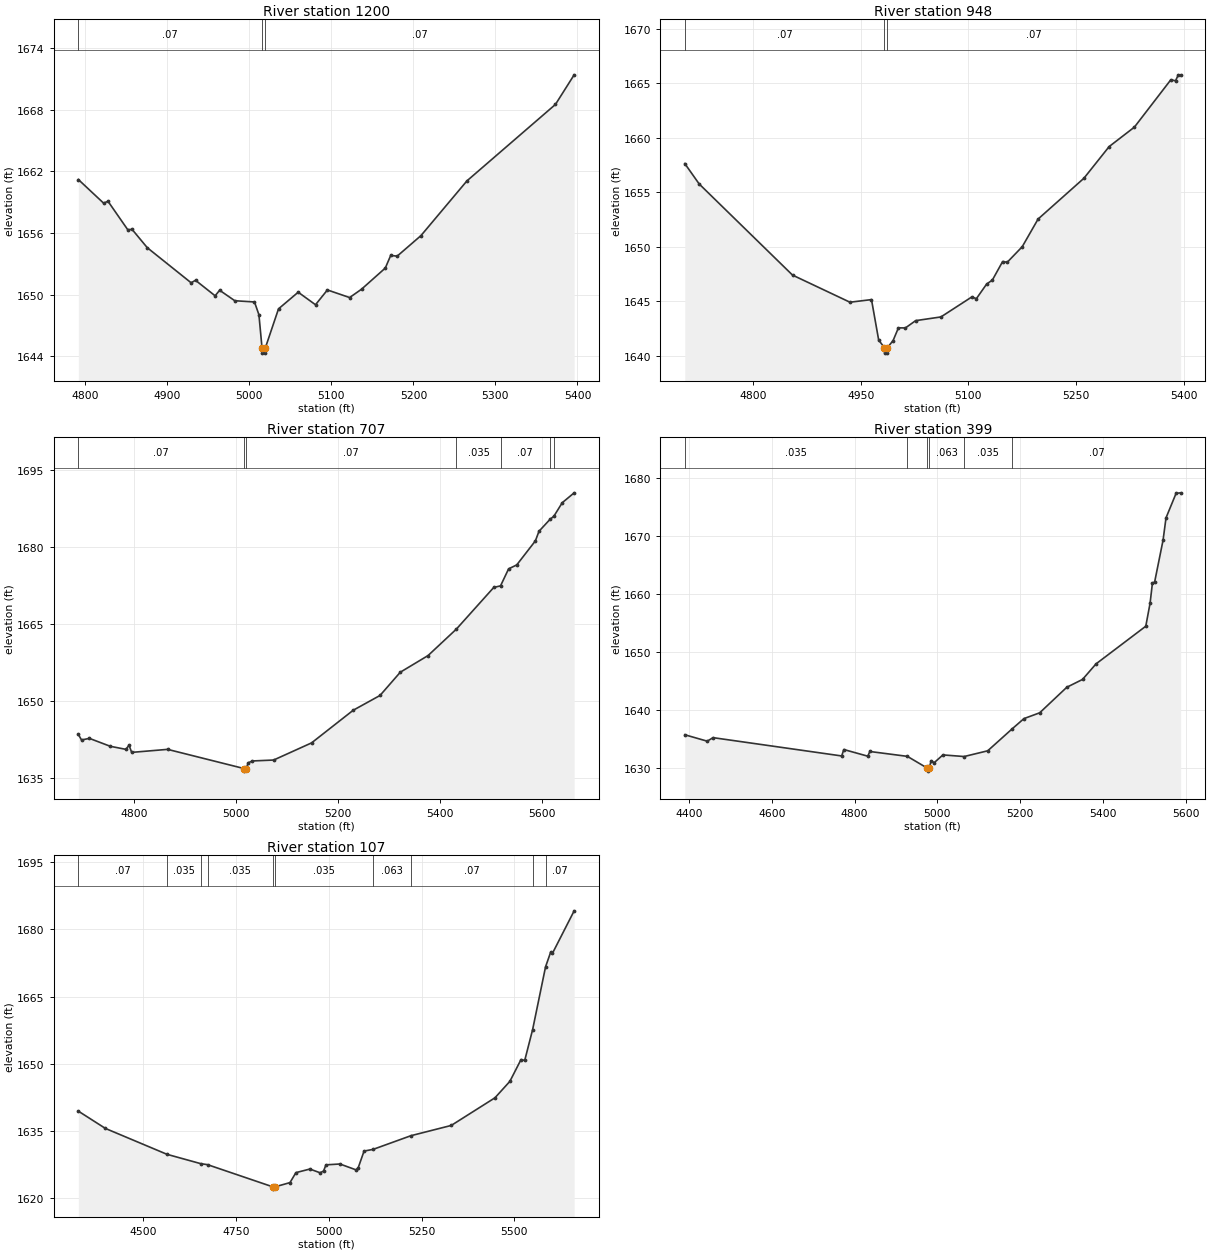
Type RM Length L Ch R = 1,1200,252,252,252
BEGIN DESCRIPTION:
Mapping XS 041c038b
END DESCRIPTION:
XS GIS Cut Line= 3
      1933996.46     13886935.96      1934103.54     13887196.50
      1934300.84     13887452.12
#Sta/Elev= 30
  4791.4 1661.22  4822.2 1658.92  4827.6 1659.10  4851.6 1656.34  4857.0 1656.36
  4875.5 1654.58  4928.9 1651.17  4934.3 1651.41  4958.2 1649.90  4963.7 1650.44
  4982.2 1649.42  5006.2 1649.30  5011.6 1648.06  5015.4 1644.82  5015.7 1644.32
  5019.2 1644.32  5019.4 1644.82  5035.5 1648.63  5059.5 1650.25  5080.6 1649.03
  5095.1 1650.47  5122.2 1649.73  5136.7 1650.54  5165.7 1652.60  5172.3 1653.83
  5180.2 1653.76  5209.2 1655.76  5265.3 1661.09  5373.2 1668.53  5396.0 1671.41
#Mann=3,-1,0
  4791.4    0.07       0  5015.4    0.05       0  5019.4    0.07       0
Bank Sta=5015.4,5019.4
Exp/Cntr=0.3,0.1

Type RM Length L Ch R = 1,948,241,241,241
BEGIN DESCRIPTION:
Stream0643 1.0
END DESCRIPTION:
XS GIS Cut Line= 3
      1933875.00     13886974.96      1933875.00     13887275.00
      1934174.96     13887524.97
#Sta/Elev= 30
  4705.0 1657.63  4725.0 1655.76  4855.0 1647.40  4935.0 1644.91  4965.0 1645.15
  4975.0 1641.44  4983.0 1640.74  4983.3 1640.24  4986.8 1640.24  4987.0 1640.74
  4995.0 1641.38  5002.5 1642.56  5012.2 1642.55  5026.5 1643.22  5061.7 1643.56
  5104.6 1645.39  5111.1 1645.24  5125.4 1646.58  5133.3 1646.94  5147.6 1648.64
  5154.1 1648.58  5174.9 1650.00  5197.0 1652.54  5260.8 1656.28  5296.0 1659.19
  5331.1 1660.97  5381.9 1665.32  5388.4 1665.22  5392.3 1665.77  5395.5 1665.77
#Mann=3,-1,0
  4705.0    0.07       0  4983.0    0.05       0  4987.0    0.07       0
Bank Sta=4983,4987
Exp/Cntr=0.3,0.1

Type RM Length L Ch R = 1,707,308,308,308
BEGIN DESCRIPTION:
Stream0643 0.0
END DESCRIPTION:
XS GIS Cut Line= 4
      1933701.32     13887153.84      1933653.45     13887374.61
      1933824.41     13887513.27      1934308.47     13887720.55
#Sta/Elev= 30
  4690.1 1643.53  4696.4 1642.46  4711.8 1642.77  4752.7 1641.23  4783.4 1640.63
  4789.6 1641.44  4794.7 1640.04  4865.2 1640.63  5015.2 1636.89  5015.4 1636.39
  5019.2 1636.89  5023.6 1638.02  5031.6 1638.37  5073.2 1638.55  5147.6 1641.89
  5229.3 1648.25  5281.9 1651.13  5321.7 1655.66  5376.1 1658.90  5431.7 1664.06
  5505.0 1672.17  5518.3 1672.48  5534.1 1675.79  5550.1 1676.56  5586.7 1681.25
  5593.7 1683.11  5615.4 1685.44  5622.9 1686.04  5639.3 1688.67  5662.7 1690.60
#Mann=7,-1,0
  4690.1    0.07       0  5015.2    0.05       0  5019.2    0.07       0
  5431.7   0.035       0  5518.3    0.07       0  5615.4   0.035       0
  5622.9    0.07       0
Bank Sta=5015.2,5019.2
Exp/Cntr=0.3,0.1

Type RM Length L Ch R = 1,399,292,292,292
BEGIN DESCRIPTION:
Stream0643 0.1
END DESCRIPTION:
XS GIS Cut Line= 4
      1933371.52     13887097.51      1933445.31     13887573.13
      1933619.73     13887753.26      1934065.54     13887889.80
#Sta/Elev= 30
  4389.7 1635.72  4443.9 1634.61  4458.0 1635.22  4768.9 1632.06  4774.0 1633.17
  4831.9 1632.02  4836.9 1632.83  4927.6 1631.99  4976.2 1629.94  4976.5 1629.44
  4980.2 1629.94  4985.2 1631.25  4992.3 1630.89  5013.5 1632.24  5064.8 1631.96
  5121.8 1632.95  5181.2 1636.76  5209.4 1638.51  5247.4 1639.51  5312.9 1643.92
  5350.9 1645.27  5383.6 1647.96  5503.8 1654.46  5514.2 1658.44  5519.9 1661.94
  5525.1 1662.06  5545.6 1669.33  5552.7 1673.17  5577.0 1677.40  5588.0 1677.49
#Mann=6,-1,0
  4389.7   0.035       0  4927.6   0.063       0  4976.2    0.05       0
  4980.2   0.063       0  5064.8   0.035       0  5181.2    0.07       0
Bank Sta=4976.2,4980.2
Exp/Cntr=0.3,0.1

Type RM Length L Ch R = 1,107,0,0,0
BEGIN DESCRIPTION:
Stream0643 0.2
END DESCRIPTION:
XS GIS Cut Line= 3
      1932879.02     13887602.71      1933598.71     13888007.13
      1934107.82     13888044.29
#Sta/Elev= 30
  4325.2 1639.38  4398.2 1635.51  4564.2 1629.72  4655.3 1627.63  4673.4 1627.41
  4849.6 1622.44  4850.0 1621.94  4854.8 1622.44  4895.5 1623.40  4911.5 1625.63
  4949.1 1626.43  4976.5 1625.60  4985.9 1625.98  4992.5 1627.37  5030.1 1627.56
  5073.4 1626.25  5079.2 1626.69  5095.1 1630.45  5119.5 1630.83  5221.5 1633.89
  5330.0 1636.18  5447.8 1642.36  5487.9 1646.03  5518.0 1650.91  5528.0 1650.72
  5549.3 1657.62  5584.2 1671.67  5597.8 1674.90  5602.8 1674.68  5661.2 1684.17
#Mann=10,-1,0
  4325.2    0.07       0  4564.2   0.035       0  4655.3    0.07       0
  4673.4   0.035       0  4849.6   0.035       0  4854.8   0.035       0
  5119.5   0.063       0  5221.5    0.07       0  5549.3   0.035       0
  5584.2    0.07       0
Bank Sta=4849.6,4854.8
Exp/Cntr=0.3,0.1

Chan Stop Cuts=-1