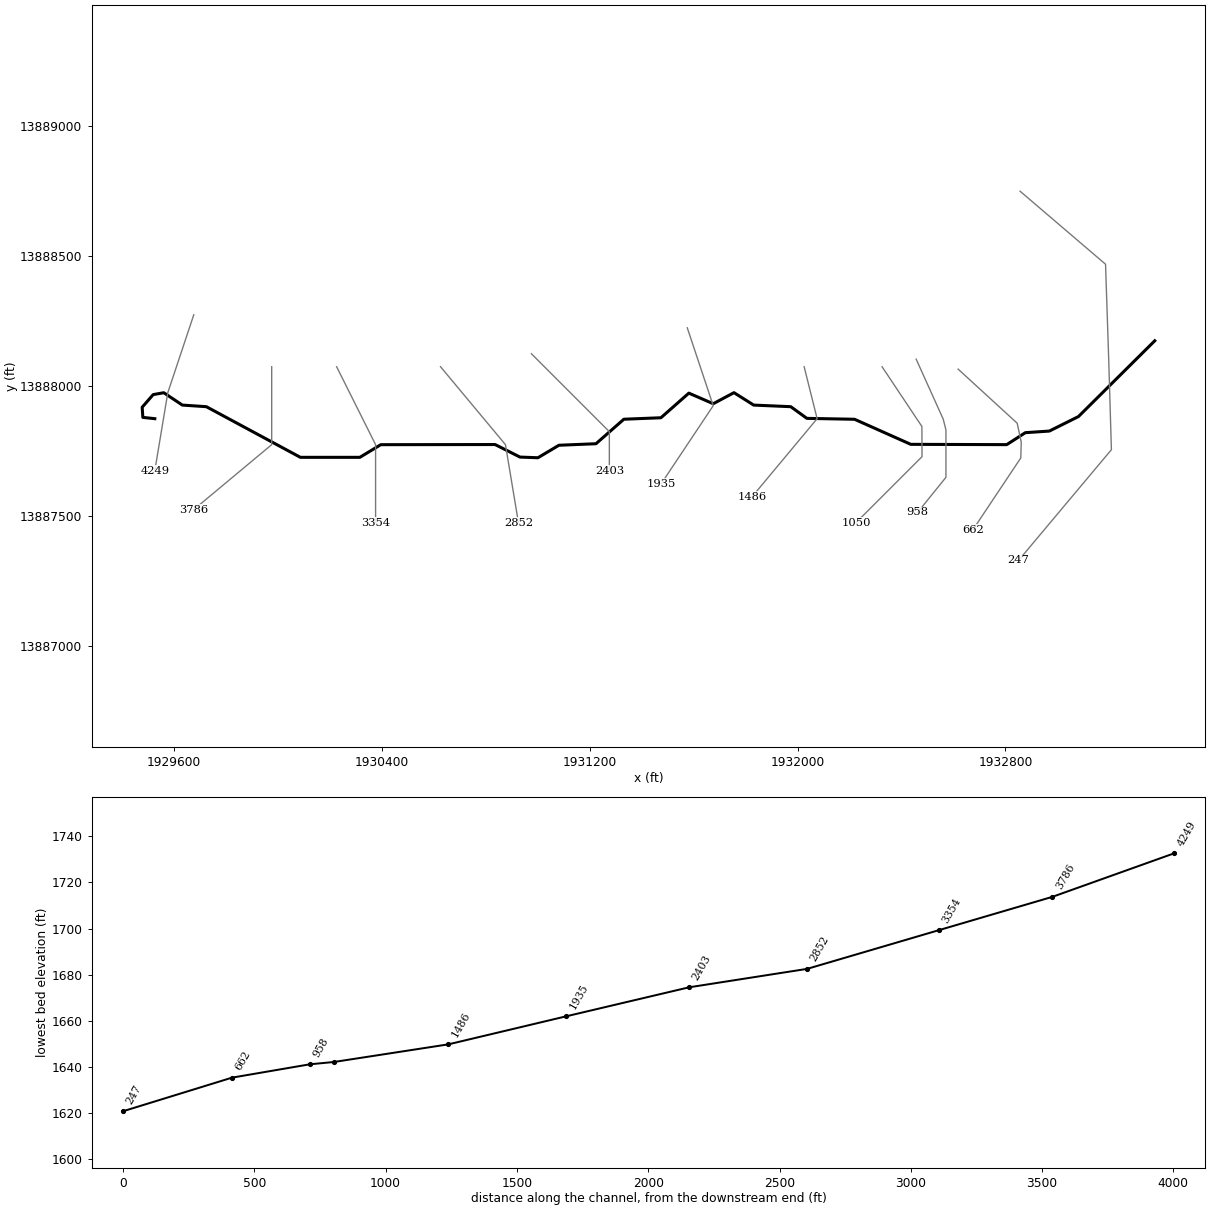
--- Stream0644.prj (project) ---

Proj Title=Stream0644 Base Level Engineering
Current Plan=p01
Default Exp/Contr=0.3,0.1
English Units
Geom File=g01
Flow File=f01
Plan File=p01
BEGIN DESCRIPTION:
Stream0644
END DESCRIPTION:

--- Stream0644.p01 (plan) ---

Plan Title=Multiple Run
Short Identifier=Multiple
Geom File=g01
Flow File=f01
Subcritical Flow
K Sum by GR= 0
Std Step Tol= 0.01
Critical Tol= 0.01
Num of Std Step Trials= 20
Max Error Tol= 0.3
Flow Tol Ratio= 0.001
Split Flow NTrial= 30
Split Flow Tol= 0.02
Split Flow Ratio= 0.02
Log Output Level= 0
Friction Slope Method= 1
Unsteady Friction Slope Method= 2
Unsteady Bridges Friction Slope Method= 1
Parabolic Critical Depth
Global Vel Dist=  1 , 1 , 1
Global Log Level= 0
CheckData=True
Encroach Param= -1, 0, 0, 0
BEGIN DESCRIPTION:
Multiple Run
END DESCRIPTION:

--- Stream0644.f01 (steady flow) ---

Flow Title=Multiple
Number of Profiles=7
Profile Names=10-year,25-year,50-year,1pct_min,100-year,1pct_plu,500-year
River Rch & RM= Stream0644,Reach-1,4249
     808    1351    1862    1244    2482    4952    4347
Boundary for River Rch & Prof#=Stream0644,Reach-1,1
Up Type=0
Dn Type=3
Dn Slope=0.005
Boundary for River Rch & Prof#=Stream0644,Reach-1,2
Up Type=0
Dn Type=3
Dn Slope=0.005
Boundary for River Rch & Prof#=Stream0644,Reach-1,3
Up Type=0
Dn Type=3
Dn Slope=0.005
Boundary for River Rch & Prof#=Stream0644,Reach-1,4
Up Type=0
Dn Type=3
Dn Slope=0.005
Boundary for River Rch & Prof#=Stream0644,Reach-1,5
Up Type=0
Dn Type=3
Dn Slope=0.005
Boundary for River Rch & Prof#=Stream0644,Reach-1,6
Up Type=0
Dn Type=3
Dn Slope=0.005
Boundary for River Rch & Prof#=Stream0644,Reach-1,7
Up Type=0
Dn Type=3
Dn Slope=0.005

--- Stream0644.g01 (geometry) ---

Geom Title=Existing Conditions

River Reach=Stream0644,Reach-1
Reach XY= 30
      1929525.00     13887875.00      1929478.91     13887879.97
      1929476.33     13887919.07      1929518.57     13887967.64
      1929559.52     13887974.99      1929630.96     13887927.38
      1929723.42     13887921.17      1930085.50     13887726.20
      1930314.50     13887726.22      1930395.03     13887774.93
      1930835.19     13887775.45      1930930.98     13887727.17
      1931000.00     13887724.60      1931080.94     13887772.73
      1931223.53     13887778.56      1931330.86     13887872.92
      1931473.53     13887878.56      1931581.05     13887973.33
      1931675.00     13887932.62      1931754.79     13887975.21
      1931830.93     13887927.30      1931973.43     13887921.21
      1932035.51     13887876.22      1932219.06     13887872.74
      1932435.50     13887776.22      1932804.97     13887775.07
      1932876.60     13887821.14      1932969.03     13887827.33
      1933081.06     13887883.14      1933375.00     13888175.00

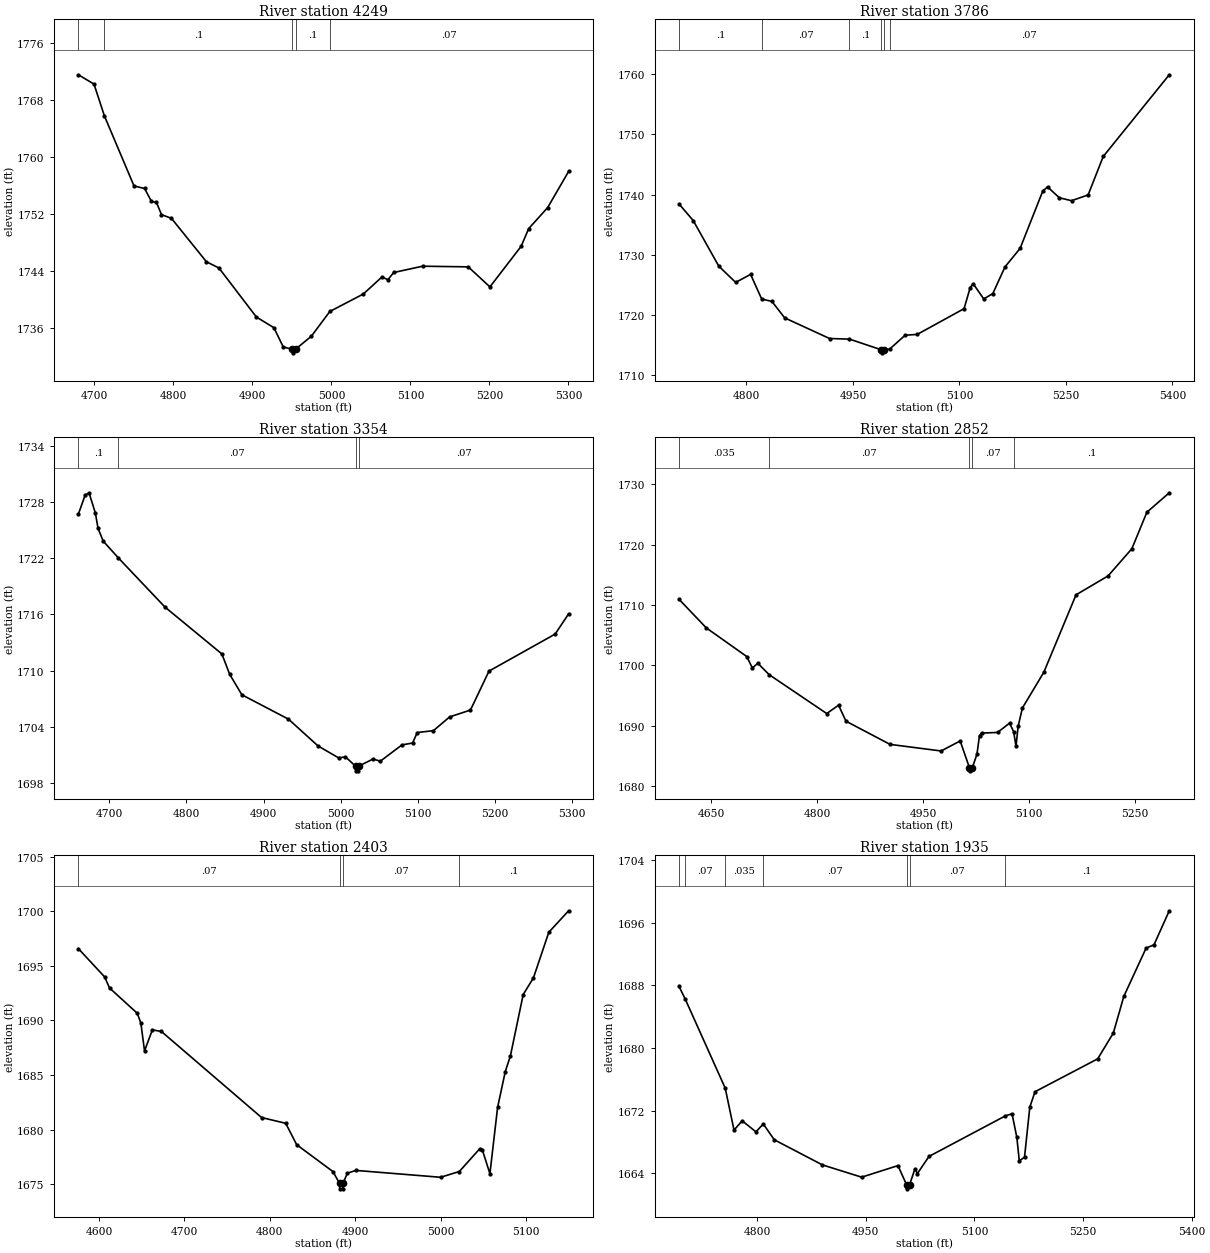
Type RM Length L Ch R = 1,4249,463,463,463
BEGIN DESCRIPTION:
Stream0644 8.0
END DESCRIPTION:
XS GIS Cut Line= 3
      1929675.00     13888275.01      1929575.00     13887975.00
      1929525.00     13887674.98
#Sta/Elev= 30
  4679.8 1771.54  4699.6 1770.23  4712.8 1765.76  4750.2 1755.95  4763.6 1755.59
  4772.3 1753.78  4778.6 1753.64  4785.0 1751.93  4797.6 1751.40  4841.9 1745.31
  4857.7 1744.44  4905.1 1737.56  4927.3 1736.06  4939.1 1733.36  4950.6 1733.04
  4950.8 1732.54  4954.6 1733.04  4974.7 1734.88  4998.0 1738.34  5040.4 1740.79
  5063.8 1743.16  5071.6 1742.81  5078.9 1743.81  5115.4 1744.69  5173.2 1744.60
  5200.6 1741.79  5240.1 1747.48  5249.7 1749.97  5273.6 1752.90  5300.2 1757.98
#Mann=5,-1,0
  4679.8   0.035       0  4712.8     0.1       0  4950.6    0.05       0
  4954.6     0.1       0  4998.0    0.07       0
Bank Sta=4950.6,4954.6
Exp/Cntr=0.3,0.1

Type RM Length L Ch R = 1,3786,432,432,432
BEGIN DESCRIPTION:
Stream0644 7.0
END DESCRIPTION:
XS GIS Cut Line= 3
      1929975.00     13888075.00      1929975.00     13887775.00
      1929675.01     13887525.01
#Sta/Elev= 30
  4705.0 1738.45  4725.0 1735.70  4761.0 1728.12  4784.8 1725.42  4805.8 1726.75
  4821.5 1722.64  4835.8 1722.27  4853.8 1719.53  4917.0 1716.10  4945.1 1716.00
  4990.0 1714.22  4990.3 1713.72  4994.0 1714.22  5001.6 1714.33  5023.5 1716.65
  5040.5 1716.78  5106.5 1721.06  5115.1 1724.56  5119.3 1725.21  5134.2 1722.67
  5147.0 1723.57  5164.1 1727.99  5185.4 1731.07  5217.3 1740.58  5224.0 1741.29
  5240.7 1739.48  5257.8 1738.99  5281.2 1739.95  5302.5 1746.34  5395.5 1759.91
#Mann=6,-1,0
  4705.0     0.1       0  4821.5    0.07       0  4945.1     0.1       0
  4990.0    0.05       0  4994.0     0.1       0  5001.6    0.07       0
Bank Sta=4990,4994
Exp/Cntr=0.3,0.1

Type RM Length L Ch R = 1,3354,502,502,502
BEGIN DESCRIPTION:
Stream0644 6.0
END DESCRIPTION:
XS GIS Cut Line= 3
      1930224.99     13888075.02      1930375.00     13887775.00
      1930375.00     13887475.03
#Sta/Elev= 30
  4660.0 1726.71  4668.7 1728.72  4673.8 1728.99  4682.1 1726.81  4685.5 1725.19
  4692.2 1723.83  4712.0 1722.02  4772.2 1716.79  4846.0 1711.78  4856.1 1709.61
  4871.9 1707.42  4932.3 1704.82  4970.6 1701.96  4997.2 1700.69  5006.2 1700.79
  5019.2 1699.80  5019.4 1699.30  5022.9 1699.30  5023.2 1699.80  5042.2 1700.57
  5051.2 1700.32  5079.4 1702.07  5093.2 1702.27  5099.2 1703.39  5120.2 1703.59
  5141.2 1705.06  5168.2 1705.79  5192.2 1709.95  5277.9 1713.90  5295.4 1716.06
#Mann=4,-1,0
  4660.0     0.1       0  4712.0    0.07       0  5019.2    0.05       0
  5023.2    0.07       0
Bank Sta=5019.2,5023.2
Exp/Cntr=0.3,0.1

Type RM Length L Ch R = 1,2852,449,449,449
BEGIN DESCRIPTION:
Stream0644 5.0
END DESCRIPTION:
XS GIS Cut Line= 3
      1930624.98     13888075.02      1930875.00     13887775.00
      1930925.00     13887474.98
#Sta/Elev= 30
  4604.4 1710.94  4643.1 1706.20  4700.4 1701.46  4708.3 1699.57  4716.1 1700.34
  4732.1 1698.46  4813.7 1692.02  4830.5 1693.40  4841.0 1690.75  4903.5 1686.91
  4975.8 1685.82  5002.8 1687.48  5016.0 1683.03  5016.3 1682.53  5020.0 1683.03
  5026.6 1685.30  5030.2 1688.38  5033.2 1688.78  5055.8 1688.89  5072.8 1690.43
  5078.7 1688.98  5081.9 1686.58  5084.9 1689.88  5091.0 1692.94  5121.4 1698.87
  5167.0 1711.68  5212.4 1714.81  5246.1 1719.32  5267.4 1725.36  5299.1 1728.58
#Mann=5,-1,0
  4604.4   0.035       0  4732.1    0.07       0  5016.0    0.05       0
  5020.0    0.07       0  5078.7     0.1       0
Bank Sta=5016,5020
Exp/Cntr=0.3,0.1

Type RM Length L Ch R = 1,2403,468,468,468
BEGIN DESCRIPTION:
Stream0644 4.0
END DESCRIPTION:
XS GIS Cut Line= 3
      1930974.97     13888125.03      1931275.00     13887825.00
      1931275.00     13887675.01
#Sta/Elev= 30
  4575.7 1696.59  4606.5 1693.99  4612.2 1692.98  4644.7 1690.66  4648.9 1689.77
  4653.2 1687.21  4662.4 1689.14  4673.0 1688.99  4790.3 1681.10  4818.6 1680.57
  4831.4 1678.61  4873.8 1676.15  4881.7 1675.06  4881.9 1674.56  4885.4 1674.56
  4885.7 1675.06  4890.8 1675.99  4900.7 1676.25  5000.0 1675.62  5022.0 1676.15
  5045.8 1678.23  5048.8 1678.16  5057.8 1675.95  5066.8 1682.03  5075.8 1685.31
  5081.8 1686.75  5096.8 1692.38  5108.8 1693.91  5126.8 1698.09  5150.0 1700.06
#Mann=4,-1,0
  4575.7    0.07       0  4881.7    0.05       0  4885.7    0.07       0
  5022.0     0.1       0
Bank Sta=4881.7,4885.7
Exp/Cntr=0.3,0.1

Type RM Length L Ch R = 1,1935,449,449,449
BEGIN DESCRIPTION:
Stream0644 3.0
END DESCRIPTION:
XS GIS Cut Line= 3
      1931575.01     13888224.96      1931675.00     13887925.00
      1931475.02     13887625.03
#Sta/Elev= 30
  4692.3 1687.87  4701.1 1686.20  4756.1 1674.86  4768.2 1669.51  4779.5 1670.69
  4798.5 1669.28  4808.6 1670.29  4823.8 1668.27  4890.2 1665.06  4944.4 1663.49
  4994.5 1664.97  5006.5 1662.50  5006.7 1662.00  5010.5 1662.50  5017.8 1664.53
  5021.4 1663.96  5037.3 1666.14  5142.7 1671.32  5152.0 1671.59  5158.6 1668.57
  5162.0 1665.58  5169.2 1666.04  5176.5 1672.44  5183.7 1674.41  5270.2 1678.61
  5291.8 1681.91  5306.3 1686.60  5337.0 1692.76  5347.9 1693.18  5369.0 1697.53
#Mann=7,-1,0
  4692.3     0.1       0  4701.1    0.07       0  4756.1   0.035       0
  4808.6    0.07       0  5006.5    0.05       0  5010.5    0.07       0
  5142.7     0.1       0
Bank Sta=5006.5,5010.5
Exp/Cntr=0.3,0.1

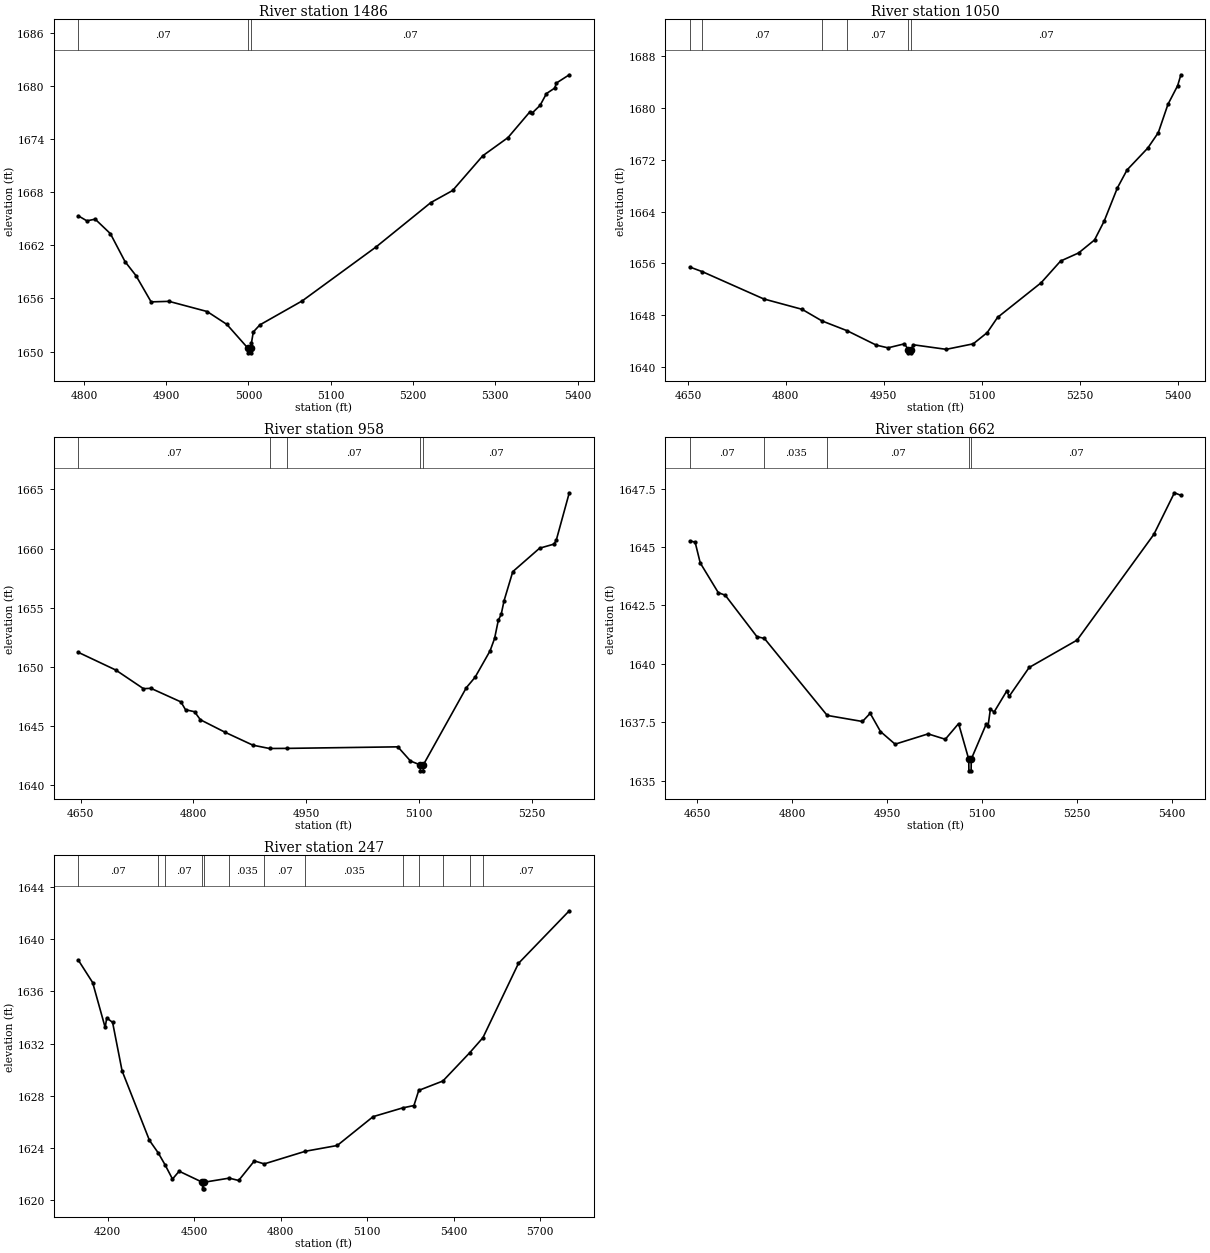
Type RM Length L Ch R = 1,1486,436,436,436
BEGIN DESCRIPTION:
Stream0644 2.0
END DESCRIPTION:
XS GIS Cut Line= 3
      1932024.99     13888075.02      1932075.00     13887875.00
      1931824.99     13887574.99
#Sta/Elev= 30
  4793.3 1665.33  4803.6 1664.77  4813.7 1664.96  4832.2 1663.32  4850.0 1660.16
  4863.2 1658.59  4881.7 1655.61  4903.4 1655.67  4949.8 1654.52  4973.7 1653.07
  4999.6 1650.35  4999.9 1649.85  5003.4 1649.85  5003.6 1650.35  5003.7 1650.99
  5005.9 1652.21  5013.9 1653.01  5065.5 1655.73  5155.0 1661.81  5221.8 1666.84
  5248.2 1668.20  5284.9 1672.13  5315.5 1674.18  5342.0 1677.08  5344.6 1676.93
  5354.5 1677.82  5362.3 1679.16  5372.2 1679.77  5374.4 1680.35  5390.0 1681.28
#Mann=3,-1,0
  4793.3    0.07       0  4999.6    0.05       0  5003.6    0.07       0
Bank Sta=4999.6,5003.6
Exp/Cntr=0.3,0.1

Type RM Length L Ch R = 1,1050,92,92,92
BEGIN DESCRIPTION:
Stream0644 1.0
END DESCRIPTION:
XS GIS Cut Line= 4
      1932324.99     13888075.01      1932478.32     13887845.02
      1932478.88     13887728.88      1932225.00     13887475.00
#Sta/Elev= 30
  4653.2 1655.43  4672.2 1654.72  4766.1 1650.52  4824.8 1648.92  4855.3 1647.13
  4893.8 1645.62  4938.4 1643.40  4956.4 1642.98  4981.6 1643.60  4987.4 1642.71
  4987.6 1642.21  4991.1 1642.21  4991.4 1642.71  4995.4 1643.45  5045.5 1642.75
  5086.9 1643.60  5108.2 1645.32  5124.1 1647.67  5190.9 1653.02  5220.6 1656.36
  5248.2 1657.61  5272.6 1659.61  5287.4 1662.53  5307.6 1667.64  5322.4 1670.41
  5354.2 1673.79  5370.2 1676.15  5385.0 1680.52  5399.9 1683.41  5404.8 1685.08
#Mann=6,-1,0
  4653.2   0.035       0  4672.2    0.07       0  4855.3   0.035       0
  4893.8    0.07       0  4987.4    0.05       0  4991.4    0.07       0
Bank Sta=4987.4,4991.4
Exp/Cntr=0.3,0.1

Type RM Length L Ch R = 1,958,296,296,296
BEGIN DESCRIPTION:
Stream0644 0.1
END DESCRIPTION:
XS GIS Cut Line= 5
      1932456.34     13888104.07      1932560.52     13887873.15
      1932570.93     13887831.49      1932570.93     13887649.19
      1932461.59     13887513.81
#Sta/Elev= 30
  4647.2 1651.22  4696.8 1649.73  4733.7 1648.15  4743.6 1648.18  4783.5 1647.03
  4789.6 1646.37  4801.6 1646.20  4809.4 1645.52  4842.3 1644.46  4879.2 1643.37
  4901.3 1643.09  4925.1 1643.10  5071.9 1643.23  5088.7 1642.03  5101.7 1641.70
  5102.0 1641.20  5105.5 1641.20  5105.7 1641.70  5163.0 1648.24  5174.6 1649.12
  5194.5 1651.35  5200.5 1652.40  5205.4 1653.92  5209.3 1654.44  5213.1 1655.59
  5224.7 1658.05  5260.3 1660.03  5279.5 1660.38  5282.5 1660.71  5299.8 1664.72
#Mann=5,-1,0
  4647.2    0.07       0  4901.3   0.035       0  4925.1    0.07       0
  5101.7    0.05       0  5105.7    0.07       0
Bank Sta=5101.7,5105.7
Exp/Cntr=0.3,0.1

Type RM Length L Ch R = 1,662,415,415,415
BEGIN DESCRIPTION:
Stream0644 0.2
END DESCRIPTION:
XS GIS Cut Line= 5
      1932617.80     13888065.87      1932845.24     13887857.53
      1932860.87     13887784.61      1932859.13     13887723.85
      1932675.08     13887447.77
#Sta/Elev= 30
  4638.9 1645.26  4647.0 1645.21  4655.1 1644.32  4683.6 1643.05  4694.6 1642.94
  4744.6 1641.17  4756.5 1641.09  4855.7 1637.80  4911.4 1637.54  4923.6 1637.89
  4939.9 1637.11  4963.0 1636.57  5015.1 1637.01  5042.3 1636.78  5063.3 1637.45
  5079.3 1635.93  5079.6 1635.43  5083.1 1635.43  5083.3 1635.93  5106.8 1637.42
  5109.9 1637.36  5113.5 1638.06  5119.5 1637.95  5139.3 1638.84  5143.3 1638.62
  5174.8 1639.85  5250.5 1641.02  5371.8 1645.54  5404.3 1647.32  5414.5 1647.21
#Mann=5,-1,0
  4638.9    0.07       0  4756.5   0.035       0  4855.7    0.07       0
  5079.3    0.05       0  5083.3    0.07       0
Bank Sta=5079.3,5083.3
Exp/Cntr=0.3,0.1

Type RM Length L Ch R = 1,247,0,0,0
BEGIN DESCRIPTION:
Stream0644 0.0
END DESCRIPTION:
XS GIS Cut Line= 5
      1932856.42     13888750.72      1933185.41     13888469.71
      1933197.62     13888102.28      1933207.97     13887755.59
      1932850.28     13887329.07
#Sta/Elev= 30
  4098.0 1638.39  4147.5 1636.68  4190.9 1633.24  4196.4 1633.97  4216.7 1633.63
  4249.6 1629.92  4344.7 1624.59  4374.9 1623.64  4398.3 1622.74  4424.6 1621.63
  4447.7 1622.23  4528.7 1621.38  4528.9 1620.88  4532.4 1620.88  4532.7 1621.38
  4621.4 1621.70  4654.2 1621.52  4708.8 1623.02  4743.1 1622.79  4886.1 1623.76
  4996.4 1624.20  5120.9 1626.41  5223.4 1627.08  5262.6 1627.26  5279.3 1628.42
  5363.1 1629.14  5456.4 1631.31  5502.1 1632.46  5625.4 1638.15  5801.8 1642.18
#Mann=13,-1,0
  4098.0    0.07       0  4374.9   0.035       0  4398.3    0.07       0
  4528.7   0.035       0  4532.7    0.07       0  4621.4   0.035       0
  4743.1    0.07       0  4886.1   0.035       0  5223.4    0.07       0
  5279.3   0.035       0  5363.1    0.07       0  5456.4   0.035       0
  5502.1    0.07       0
Bank Sta=4528.7,4532.7
Exp/Cntr=0.3,0.1

Chan Stop Cuts=-1