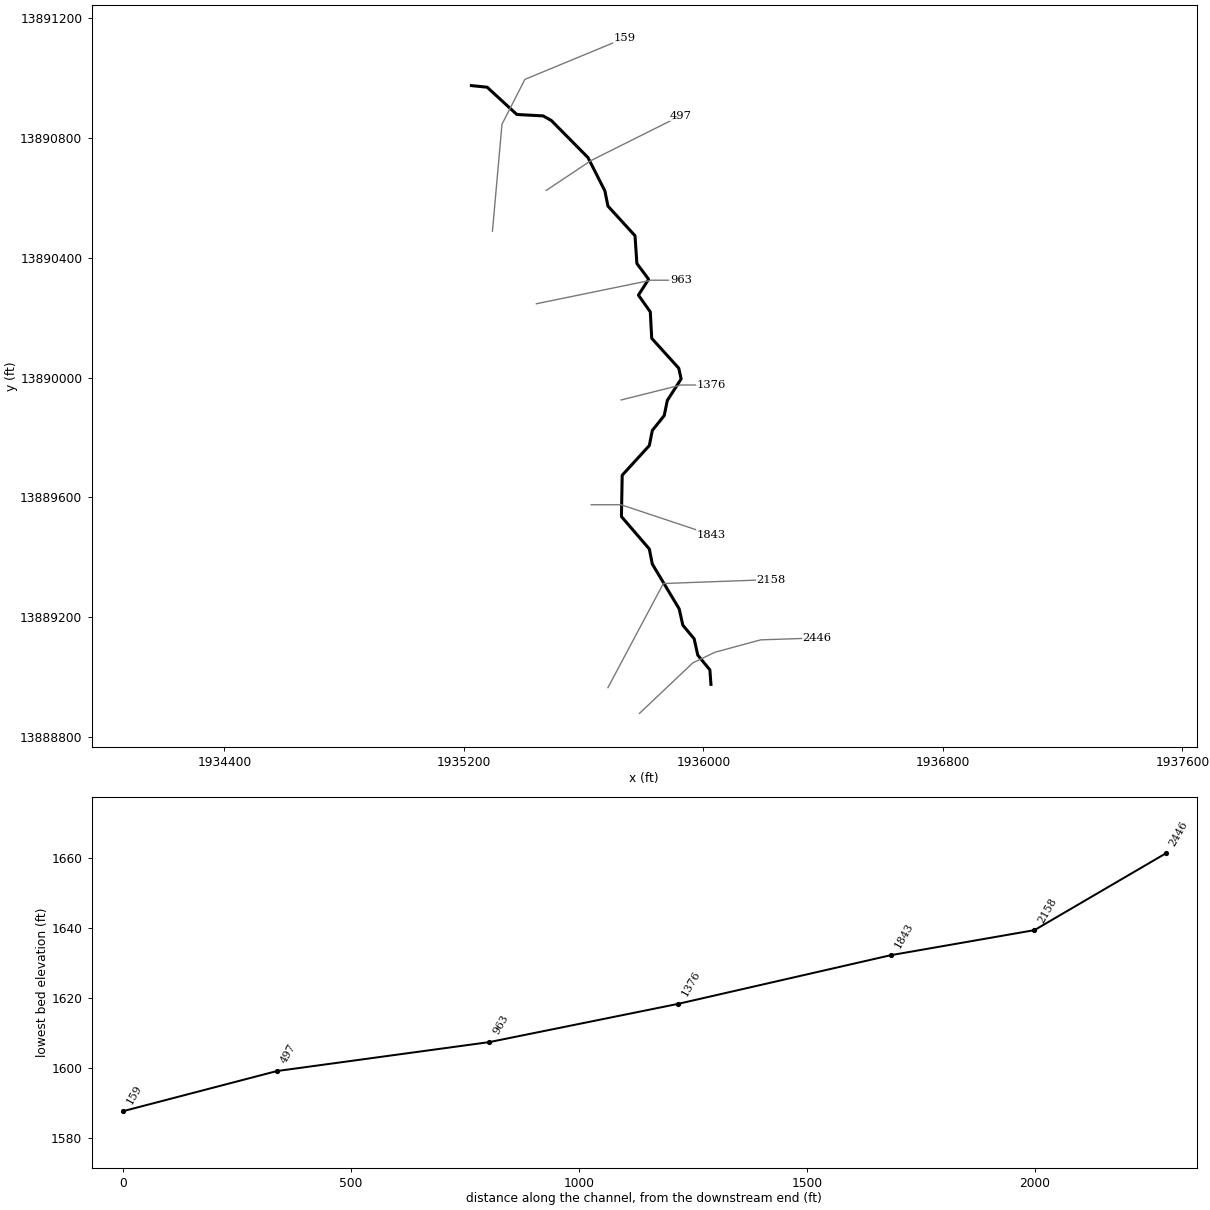
--- Stream0647.prj (project) ---

Proj Title=Stream0647 Base Level Engineering
Current Plan=p01
Default Exp/Contr=0.3,0.1
English Units
Geom File=g01
Flow File=f01
Plan File=p01
Y Axis Title=Elevation
X Axis Title(PF)=Main Channel Distance
X Axis Title(XS)=Station
BEGIN DESCRIPTION:
Stream0647
END DESCRIPTION:
DSS Export Rating Curves= 0
DSS Export Rating Curve Sorted= 0
DSS Export Volume Flow Curves= 0
DXF OffsetX= 0
DXF OffsetY= 0
DXF ScaleX= 1
DXF ScaleY= 10

--- Stream0647.p01 (plan) ---

Plan Title=Multiple Run
Short Identifier=Multiple
Geom File=g01
Flow File=f01
Subcritical Flow
K Sum by GR= 0
Std Step Tol= 0.01
Critical Tol= 0.01
Num of Std Step Trials= 20
Max Error Tol= 0.3
Flow Tol Ratio= 0.001
Split Flow NTrial= 30
Split Flow Tol= 0.02
Split Flow Ratio= 0.02
Log Output Level= 0
Friction Slope Method= 1
Unsteady Friction Slope Method= 2
Unsteady Bridges Friction Slope Method= 1
Parabolic Critical Depth
Global Vel Dist=  1 , 1 , 1
Global Log Level= 0
CheckData=True
Encroach Param= -1, 0, 0, 0
BEGIN DESCRIPTION:
Multiple Run
END DESCRIPTION:

--- Stream0647.f01 (steady flow) ---

Flow Title=Multiple
Program Version=4.10
Number of Profiles= 7
Profile Names=10-year,25-year,50-year,1pct_min,100-year,1pct_plu,500-year
River Rch & RM=Stream0647,Reach-1         ,2446
     703    1166    1598    1062    2119    4229    3672
Boundary for River Rch & Prof#=Stream0647,Reach-1         , 1
Up Type= 0
Dn Type= 3
Dn Slope=0.008
Boundary for River Rch & Prof#=Stream0647,Reach-1         , 2
Up Type= 0
Dn Type= 3
Dn Slope=0.008
Boundary for River Rch & Prof#=Stream0647,Reach-1         , 3
Up Type= 0
Dn Type= 3
Dn Slope=0.008
Boundary for River Rch & Prof#=Stream0647,Reach-1         , 4
Up Type= 0
Dn Type= 3
Dn Slope=0.008
Boundary for River Rch & Prof#=Stream0647,Reach-1         , 5
Up Type= 0
Dn Type= 3
Dn Slope=0.008
Boundary for River Rch & Prof#=Stream0647,Reach-1         , 6
Up Type= 0
Dn Type= 3
Dn Slope=0.008
Boundary for River Rch & Prof#=Stream0647,Reach-1         , 7
Up Type= 0
Dn Type= 3
Dn Slope=0.008
DSS Import GetInterval= 0
DSS Import GetPeak= 0
DSS Import FillOption= 0

--- Stream0647.g01 (geometry) ---

Geom Title=Existing Conditions
Program Version=4.10

River Reach=Stream0647      ,Reach-1
Reach XY= 30
        1936025.       13888975.       1936021.4     13889023.51
      1935980.95     13889072.75      1935968.93      13889127.2
      1935931.08      13889172.8      1935918.92      13889227.2
      1935829.19     13889376.74      1935819.15     13889427.29
      1935726.04     13889535.44      1935728.54     13889673.53
      1935819.15     13889772.71      1935829.19     13889823.26
      1935868.92      13889872.8      1935879.22     13889923.28
      1935925.37      13889995.2       1935917.5     13890031.05
      1935827.16      13890130.9      1935822.45     13890219.11
      1935782.79      13890275.1      1935816.72     13890328.22
      1935777.55     13890380.89      1935771.38      13890473.5
      1935680.85     13890572.71      1935670.81     13890623.27
      1935614.24     13890734.68      1935491.75     13890858.54
      1935464.52     13890873.83       1935376.5     13890878.61
      1935277.51     13890969.67        1935225.       13890975.

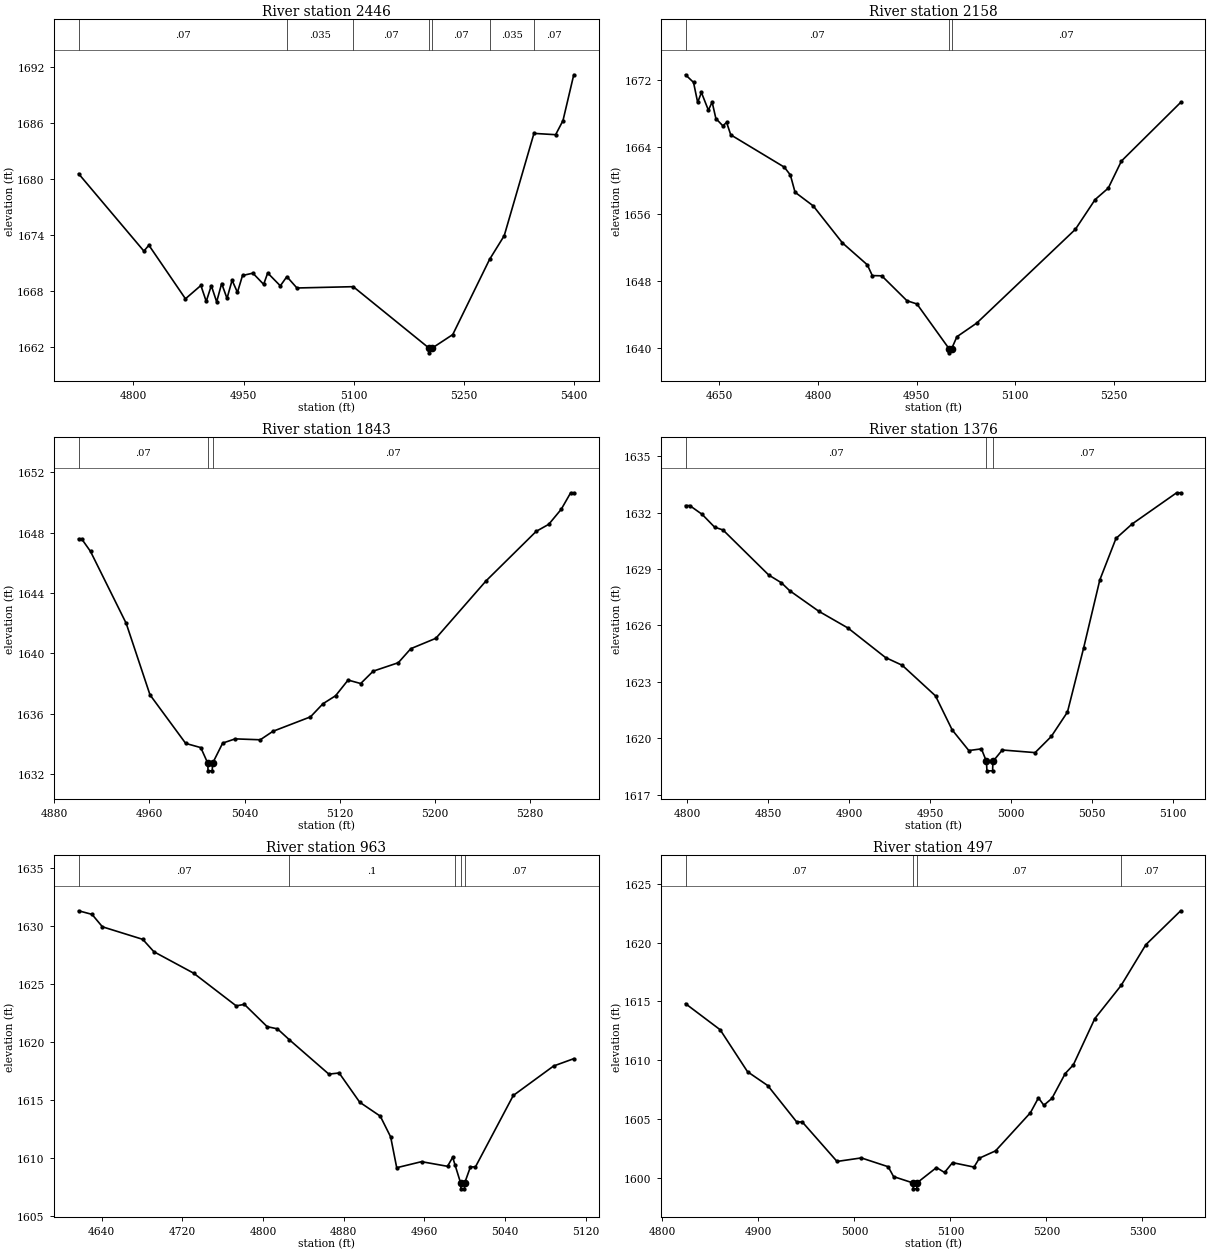
Type RM Length L Ch R = 1 ,2446    ,288,288,288
BEGIN DESCRIPTION:
Stream0647 6.0
END DESCRIPTION:
XS GIS Cut Line= 5
      1935786.27     13888878.17      1935964.86     13889047.19
      1936038.21     13889082.27      1936191.29     13889123.73
      1936379.69     13889130.01
#Sta/Elev= 30
  4725.4 1680.57  4814.3 1672.27  4821.1  1672.9  4870.9 1667.15  4891.9 1668.58
  4899.2 1666.87  4906.1 1668.56  4913.4 1666.82  4920.2 1668.79  4927.5 1667.19
  4934.4 1669.14  4941.7 1667.84  4948.6 1669.65  4962.7  1669.9  4977.4  1668.7
  4982.9 1669.92  5000.1 1668.54    5009 1669.53  5022.7 1668.31  5099.4 1668.45
  5202.7 1661.85  5202.9 1661.35  5206.7 1661.85  5234.9 1663.31    5285 1671.37
    5305 1673.92  5345.5  1684.9    5375 1684.76    5385 1686.27  5399.7 1691.19
#Mann= 7 ,-1 , 0
  4725.4     .07       0    5009    .035       0  5099.4     .07       0
  5202.7     .05       0  5206.7     .07       0    5285    .035       0
  5345.5     .07       0
Bank Sta=5202.7,5206.7
XS Rating Curve= 0 ,0
Exp/Cntr=0.3,0.1

Type RM Length L Ch R = 1 ,2158    ,315,315,315
BEGIN DESCRIPTION:
Stream0647 5.0
END DESCRIPTION:
XS GIS Cut Line= 3
        1935681.     13888964.23      1935865.99      13889311.9
      1936225.04       13889325.
#Sta/Elev= 30
  4598.5 1672.67  4610.7 1671.76    4617 1669.36  4622.7 1670.55  4633.3 1668.43
    4639  1669.4  4644.7 1667.43  4655.3 1666.56    4661 1666.97  4667.3 1665.48
  4748.8 1661.61    4758 1660.67  4765.1 1658.61  4792.8 1656.97  4837.2 1652.54
    4875 1649.92  4882.6 1648.63    4897  1648.6  4935.3 1645.62  4950.5 1645.23
  4999.3 1639.88  4999.6 1639.38  5003.3 1639.88  5011.3 1641.31  5041.4 1642.94
  5191.5 1654.17  5221.5 1657.73  5241.5  1659.1  5261.5 1662.34  5351.6 1669.36
#Mann= 3 ,-1 , 0
  4598.5     .07       0  4999.3     .05       0  5003.3     .07       0
Bank Sta=4999.3,5003.3
XS Rating Curve= 0 ,0
Exp/Cntr=0.3,0.1

Type RM Length L Ch R = 1 ,1843    ,467,467,467
BEGIN DESCRIPTION:
Stream0647 4.0
END DESCRIPTION:
XS GIS Cut Line= 3
      1935624.98       13889575.        1935725.       13889575.
      1936024.96     13889475.01
#Sta/Elev= 30
  4900.5  1647.6    4903  1647.6  4910.5 1646.76  4940.5 1641.99  4960.5 1637.25
  4990.5 1634.03  5003.2 1633.75  5009.1 1632.71  5009.3 1632.21  5012.8 1632.21
  5013.1 1632.71  5021.6 1634.05  5032.1 1634.33  5053.2 1634.27  5063.8 1634.83
  5095.4 1635.79  5105.9 1636.66  5116.5 1637.19    5127 1638.23  5137.6    1638
  5148.1 1638.82  5169.2 1639.38  5179.7 1640.31  5200.8    1641    5243 1644.81
  5285.1 1648.09  5295.7 1648.56  5306.2 1649.56  5314.1 1650.65  5316.7 1650.65
#Mann= 3 ,-1 , 0
  4900.5     .07       0  5009.1     .05       0  5013.1     .07       0
Bank Sta=5009.1,5013.1
XS Rating Curve= 0 ,0
Exp/Cntr=0.3,0.1

Type RM Length L Ch R = 1 ,1376    ,413,413,413
BEGIN DESCRIPTION:
Stream0647 3.0
END DESCRIPTION:
XS GIS Cut Line= 3
        1935725.       13889925.        1935925.       13889975.
      1936025.04       13889975.
#Sta/Elev= 30
  4798.8 1632.38  4801.4 1632.38  4809.1 1631.91  4816.8 1631.23    4822 1631.08
  4850.3 1628.68  4858.1 1628.27  4863.2 1627.85  4881.3 1626.75  4899.3 1625.86
  4922.5 1624.29  4932.8 1623.88  4953.4 1622.25  4963.7 1620.44    4974 1619.34
  4981.8 1619.43  4984.9 1618.76  4985.2 1618.26  4988.7 1618.26  4988.9 1618.76
  4994.7 1619.37    5015 1619.23    5025 1620.09    5035 1621.39    5045  1624.8
    5055 1628.42    5065 1630.63    5075  1631.4  5102.5 1633.06    5105 1633.06
#Mann= 3 ,-1 , 0
  4798.8     .07       0  4984.9     .05       0  4988.9     .07       0
Bank Sta=4984.9,4988.9
XS Rating Curve= 0 ,0
Exp/Cntr=0.3,0.1

Type RM Length L Ch R = 1 ,963     ,466,466,466
BEGIN DESCRIPTION:
Stream0647 2.0
END DESCRIPTION:
XS GIS Cut Line= 3
      1935441.87     13890246.34        1935825.       13890325.
      1935924.98       13890325.
#Sta/Elev= 30
  4617.1 1631.29  4630.4 1630.98  4640.7 1629.91  4680.7 1628.83  4691.8 1627.76
  4731.1 1625.92  4773.4  1623.1  4781.5 1623.23  4804.1 1621.31  4814.3 1621.12
    4826 1620.19  4865.3 1617.22  4875.5 1617.32  4895.9  1614.8  4916.3  1613.6
  4926.6 1611.81  4932.6 1609.16  4957.2 1609.68    4983 1609.28  4988.1 1610.06
  4990.4 1609.41    4996 1607.84  4996.3 1607.34  4999.8 1607.34    5000 1607.84
  5005.7 1609.23  5010.7 1609.23  5048.2 1615.38  5088.2 1617.92  5108.2 1618.55
#Mann= 5 ,-1 , 0
  4617.1     .07       0    4826      .1       0  4990.4     .07       0
    4996     .05       0    5000     .07       0
Bank Sta=4996,5000
XS Rating Curve= 0 ,0
Exp/Cntr=0.3,0.1

Type RM Length L Ch R = 1 ,497     ,338,338,338
BEGIN DESCRIPTION:
Stream0647 1.0
END DESCRIPTION:
XS GIS Cut Line= 3
      1935474.96     13890624.98        1935625.       13890725.
      1935924.97     13890874.99
#Sta/Elev= 30
  4824.1  1614.8  4860.2 1612.58  4888.7 1609.01  4909.8 1607.83  4939.8 1604.75
  4945.8 1604.73  4981.9 1601.38  5007.2 1601.68  5035.2 1600.93  5040.8 1600.09
  5061.1 1599.55  5061.4 1599.05  5064.9 1599.05  5065.1 1599.55  5085.5 1600.86
  5093.9 1600.44  5102.2 1601.28  5124.6  1600.9  5130.2 1601.66    5147 1602.28
  5183.3 1605.52  5191.7 1606.79  5197.3 1606.16  5205.7 1606.74  5219.6 1608.86
    5228 1609.59  5250.4 1613.53  5277.8 1616.35  5303.5 1619.81  5339.8  1622.7
#Mann= 4 ,-1 , 0
  4824.1     .07       0  5061.1     .05       0  5065.1     .07       0
  5277.8     .07       0
Bank Sta=5061.1,5065.1
XS Rating Curve= 0 ,0
Exp/Cntr=0.3,0.1

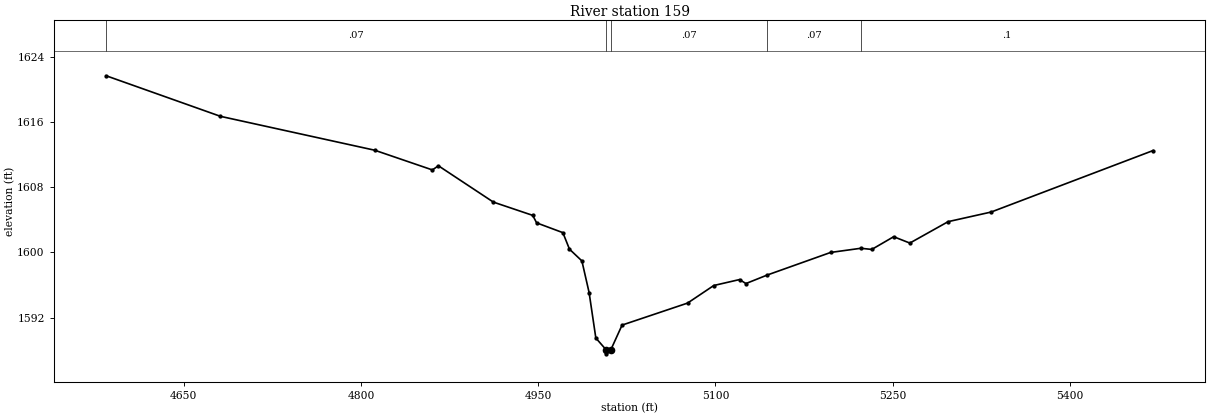
Type RM Length L Ch R = 1 ,159     ,0,0,0
BEGIN DESCRIPTION:
Stream0647 0.0
END DESCRIPTION:
XS GIS Cut Line= 4
      1935295.13      13890488.7      1935327.02      13890845.9
      1935403.56     13890995.79      1935735.21     13891132.91
#Sta/Elev= 30
  4584.5 1621.68  4681.2  1616.7  4811.7 1612.54  4860.5 1610.12  4865.6 1610.63
  4912.1 1606.17  4945.4 1604.54  4948.7 1603.62  4970.9 1602.42  4976.5 1600.39
    4987 1598.95  4993.1 1595.07  4998.8 1589.48  5007.5 1588.04  5007.7 1587.54
  5011.5 1588.04    5021 1591.07  5076.4 1593.77  5098.6 1595.93  5120.4 1596.66
  5125.8 1596.17  5143.9 1597.22  5197.5 1599.99    5223  1600.5  5232.3 1600.36
  5250.8 1601.92  5264.5 1601.14  5296.9 1603.77  5333.3 1604.95  5470.3  1612.5
#Mann= 5 ,-1 , 0
  4584.5     .07       0  5007.5     .05       0  5011.5     .07       0
  5143.9     .07       0    5223      .1       0
Bank Sta=5007.5,5011.5
XS Rating Curve= 0 ,0
Exp/Cntr=0.3,0.1

Chan Stop Cuts=-1
Use User Specified Reach Order=0
Composite Channel Slope=5