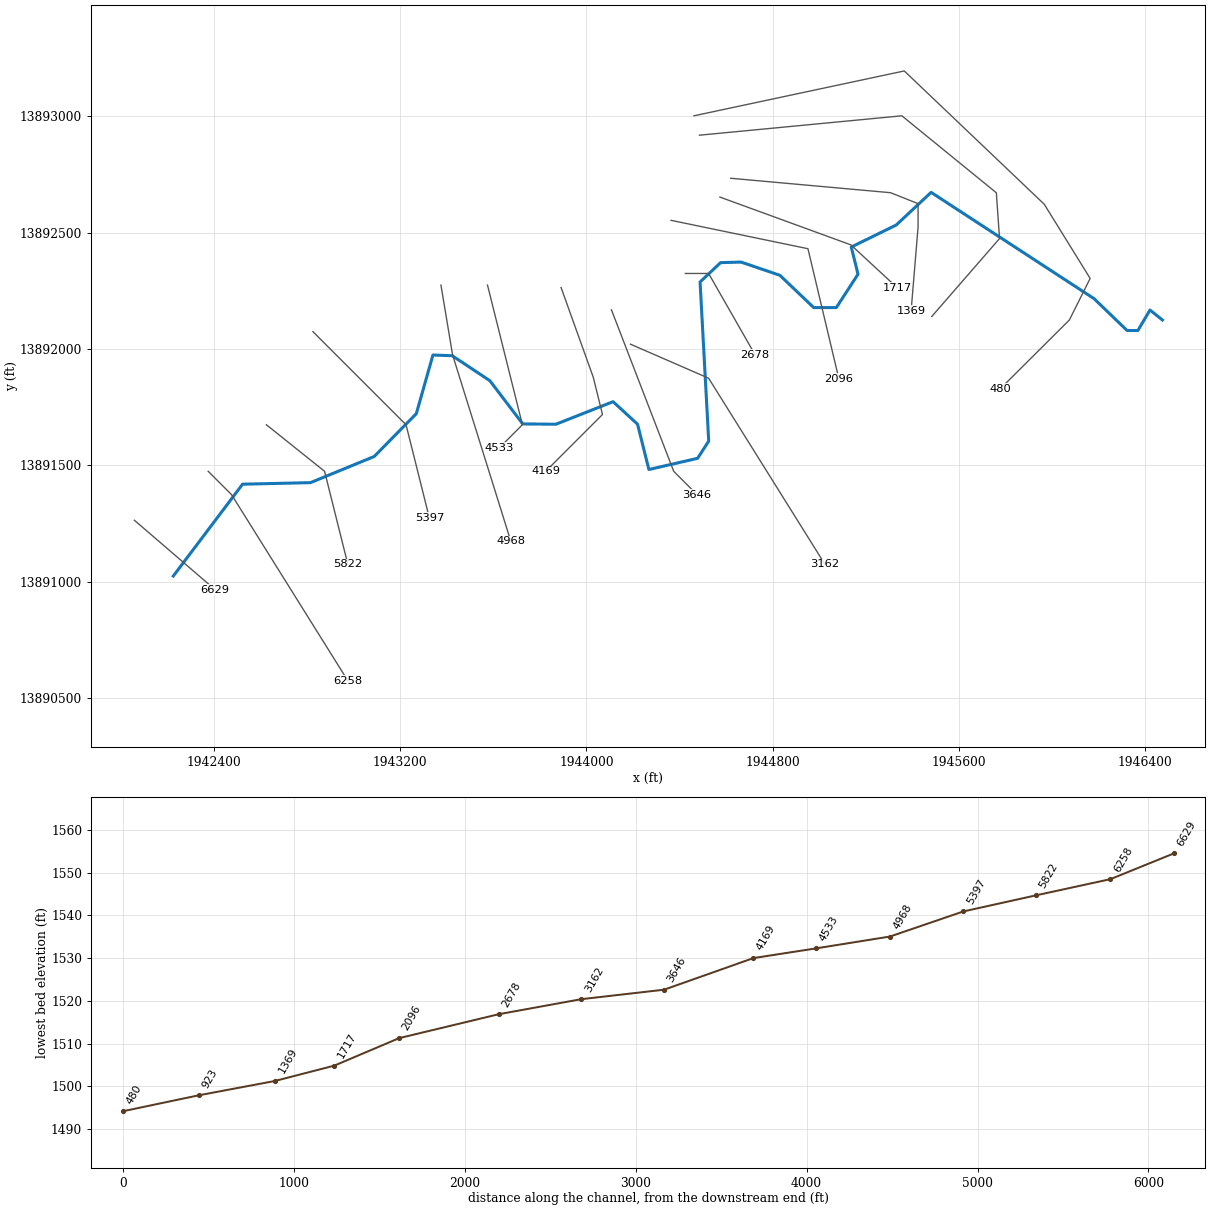
--- Stream0649.prj (project) ---

Proj Title=Stream0649 Base Level Engineering
Current Plan=p01
Default Exp/Contr=0.3,0.1
English Units
Geom File=g01
Flow File=f01
Plan File=p01
Y Axis Title=Elevation
X Axis Title(PF)=Main Channel Distance
X Axis Title(XS)=Station
BEGIN DESCRIPTION:
Stream0649
END DESCRIPTION:
DSS Export Rating Curves= 0
DSS Export Rating Curve Sorted= 0
DSS Export Volume Flow Curves= 0
DXF OffsetX= 0
DXF OffsetY= 0
DXF ScaleX= 1
DXF ScaleY= 10

--- Stream0649.p01 (plan) ---

Plan Title=Multiple Run
Short Identifier=Multiple
Geom File=g01
Flow File=f01
Subcritical Flow
K Sum by GR= 0
Std Step Tol= 0.01
Critical Tol= 0.01
Num of Std Step Trials= 20
Max Error Tol= 0.3
Flow Tol Ratio= 0.001
Split Flow NTrial= 30
Split Flow Tol= 0.02
Split Flow Ratio= 0.02
Log Output Level= 0
Friction Slope Method= 1
Unsteady Friction Slope Method= 2
Unsteady Bridges Friction Slope Method= 1
Parabolic Critical Depth
Global Vel Dist=  1 , 1 , 1
Global Log Level= 0
CheckData=True
Encroach Param= -1, 0, 0, 0
BEGIN DESCRIPTION:
Multiple Run
END DESCRIPTION:

--- Stream0649.f01 (steady flow) ---

Flow Title=Multiple
Program Version=4.10
Number of Profiles= 7
Profile Names=10-year,25-year,50-year,1pct_min,100-year,1pct_plu,500-year
River Rch & RM=Stream0649,Reach-1         ,6629
    2214    3913    5587    3850    7682   15327   14350
Boundary for River Rch & Prof#=Stream0649,Reach-1         , 1
Up Type= 0
Dn Type= 3
Dn Slope=0.009
Boundary for River Rch & Prof#=Stream0649,Reach-1         , 2
Up Type= 0
Dn Type= 3
Dn Slope=0.009
Boundary for River Rch & Prof#=Stream0649,Reach-1         , 3
Up Type= 0
Dn Type= 3
Dn Slope=0.009
Boundary for River Rch & Prof#=Stream0649,Reach-1         , 4
Up Type= 0
Dn Type= 3
Dn Slope=0.009
Boundary for River Rch & Prof#=Stream0649,Reach-1         , 5
Up Type= 0
Dn Type= 3
Dn Slope=0.009
Boundary for River Rch & Prof#=Stream0649,Reach-1         , 6
Up Type= 0
Dn Type= 3
Dn Slope=0.009
Boundary for River Rch & Prof#=Stream0649,Reach-1         , 7
Up Type= 0
Dn Type= 3
Dn Slope=0.009
DSS Import GetInterval= 0
DSS Import GetPeak= 0
DSS Import FillOption= 0

--- Stream0649.g01 (geometry) ---

Geom Title=Existing Conditions
Program Version=4.10

River Reach=Stream0649      ,Reach-1
Reach XY= 30
        1942225.       13891025.      1942522.53     13891419.55
       1942814.5     13891426.22      1943088.22     13891538.62
      1943269.17      13891722.7       1943340.6      13891974.6
      1943423.42     13891971.56        1943585.     13891864.35
      1943726.46     13891678.52      1943869.07     13891677.23
      1944114.53     13891774.07      1944219.54     13891677.46
       1944268.5     13891482.62      1944477.59     13891530.71
      1944525.46     13891604.75      1944488.32     13892288.33
      1944576.48     13892371.55      1944664.45      13892373.9
      1944831.17     13892317.14       1944976.5     13892178.46
      1945073.72     13892178.37      1945166.93     13892321.69
      1945137.99     13892438.56      1945331.06     13892533.14
      1945481.05     13892673.42      1946181.05     13892216.84
      1946323.04     13892079.93      1946369.39     13892079.78
      1946421.36     13892167.83        1946475.       13892125.

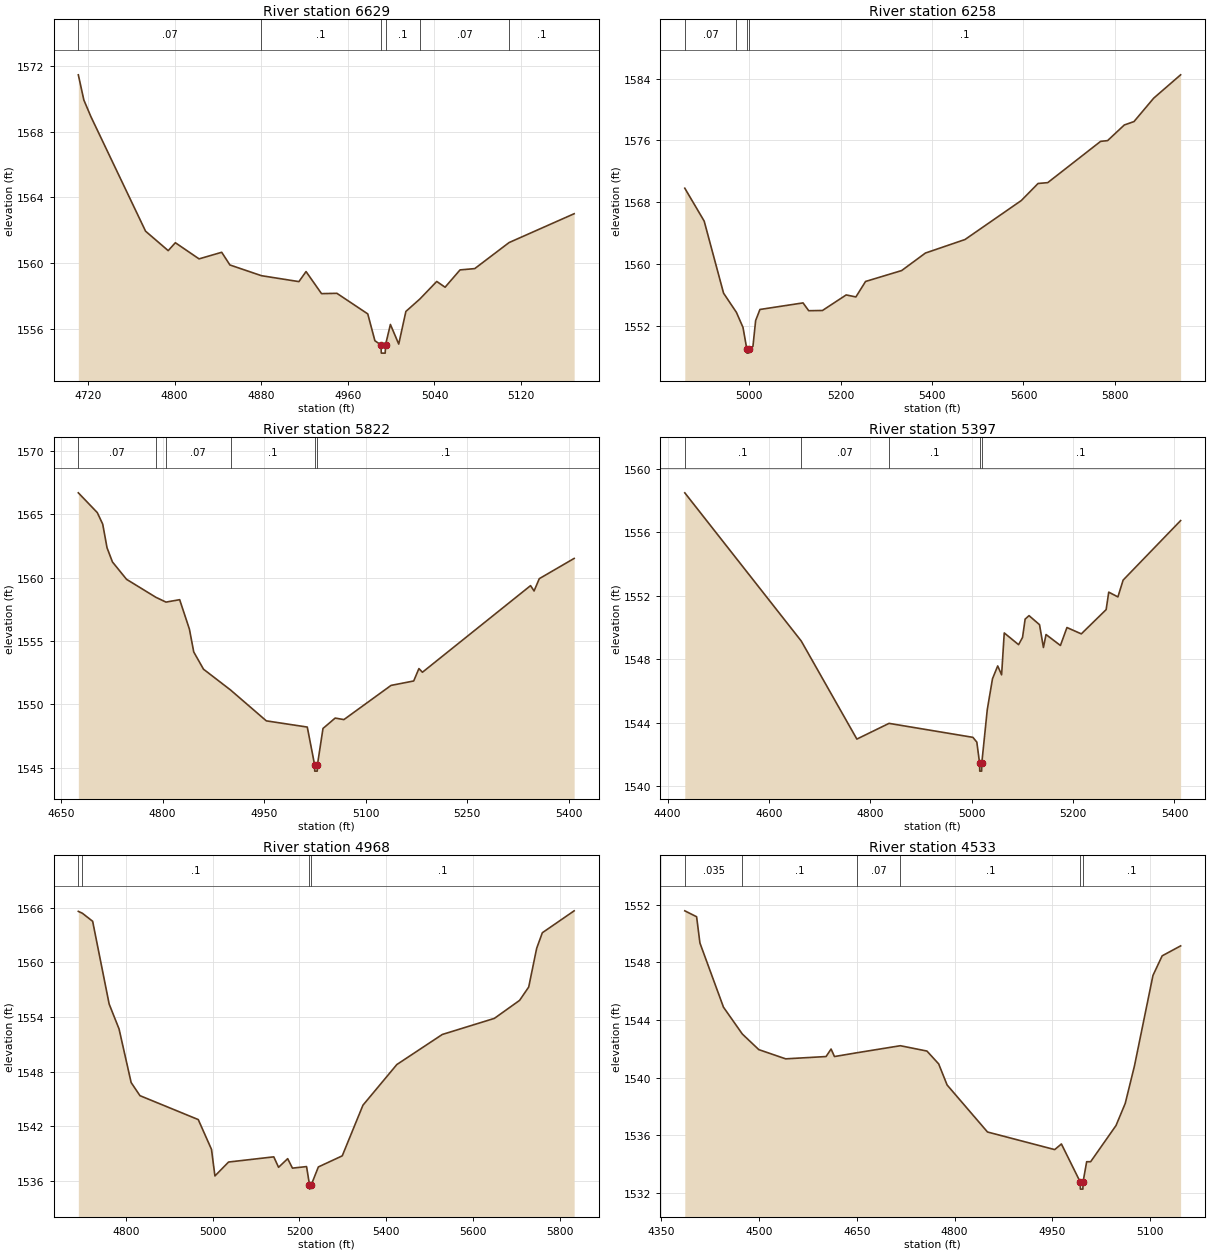
Type RM Length L Ch R = 1 ,6629    ,371,371,371
BEGIN DESCRIPTION:
Stream0649 15.0
END DESCRIPTION:
XS GIS Cut Line= 2
      1942057.75      13891264.7      1942404.92     13890966.13
#Sta/Elev= 30
  4711.1 1571.44  4716.2 1569.91  4722.8 1568.89  4773.2 1561.95  4794.1 1560.77
  4800.7 1561.25  4822.6 1560.27  4843.5 1560.67  4851.1  1559.9  4880.2 1559.25
  4914.8 1558.89  4921.4  1559.5  4935.7 1558.16  4949.9 1558.18  4978.4 1556.93
    4985  1555.3  4990.6 1555.05  4990.9 1554.55  4994.5 1554.55  4994.8 1555.05
  4999.3 1556.29    5007  1555.1  5013.6 1557.08  5026.6 1557.84  5042.1  1558.9
  5049.8 1558.55  5063.6  1559.6  5077.2 1559.68  5108.9 1561.26    5169 1563.01
#Mann= 6 ,-1 , 0
  4711.1     .07       0  4880.2      .1       0  4990.6     .05       0
  4994.8      .1       0  5026.6     .07       0  5108.9      .1       0
Bank Sta=4990.6,4994.8
XS Rating Curve= 0 ,0
Exp/Cntr=0.3,0.1

Type RM Length L Ch R = 1 ,6258    ,436,436,436
BEGIN DESCRIPTION:
Stream0649 14.0
END DESCRIPTION:
XS GIS Cut Line= 3
      1942375.01     13891474.99        1942475.       13891375.
        1942975.       13890575.
#Sta/Elev= 30
  4859.1 1569.83  4901.5 1565.58  4943.9 1556.27    4972 1553.79  4986.4 1551.85
  4994.9 1549.02  4995.1 1548.52  4998.8 1548.52  4999.1 1549.02  5008.2 1549.39
  5014.1 1552.73  5023.5 1554.16  5117.8 1555.01  5130.2    1554  5160.3 1554.03
  5212.2 1556.04  5233.4 1555.78  5254.6 1557.78  5333.6 1559.19  5385.5 1561.45
  5472.2  1563.2  5595.4 1568.24    5632 1570.44  5653.2 1570.55  5768.8 1575.88
  5784.1 1575.98  5820.7    1578  5841.9 1578.44  5884.9 1581.46  5943.9 1584.48
#Mann= 4 ,-1 , 0
  4859.1     .07       0    4972      .1       0  4994.9     .05       0
  4999.1      .1       0
Bank Sta=4994.9,4999.1
XS Rating Curve= 0 ,0
Exp/Cntr=0.3,0.1

Type RM Length L Ch R = 1 ,5822    ,425,425,425
BEGIN DESCRIPTION:
Stream0649 13.0
END DESCRIPTION:
XS GIS Cut Line= 3
      1942625.02     13891674.99        1942875.       13891475.
      1942974.99     13891075.04
#Sta/Elev= 30
  4675.6  1566.7  4703.6 1565.14  4711.6 1564.23    4718 1562.36    4726 1561.24
  4746.8 1559.87  4790.1 1558.45  4805.1 1558.07  4825.3 1558.26  4839.7 1555.93
  4846.1 1554.13  4860.5 1552.77  4900.4 1551.13  4953.3 1548.69  5013.8  1548.2
  5024.6 1545.22  5024.8 1544.72  5028.5 1544.72  5028.8 1545.22    5037 1548.09
    5055 1548.91  5067.9 1548.79  5137.5 1551.49    5171 1551.84  5178.7 1552.82
  5183.9 1552.53  5343.6 1559.37  5348.8 1558.95  5356.5 1559.92    5408 1561.52
#Mann= 6 ,-1 , 0
  4675.6     .07       0  4790.1      .1       0  4805.1     .07       0
  4900.4      .1       0  5024.6     .05       0  5028.8      .1       0
Bank Sta=5024.6,5028.8
XS Rating Curve= 0 ,0
Exp/Cntr=0.3,0.1

Type RM Length L Ch R = 1 ,5397    ,429,429,429
BEGIN DESCRIPTION:
Stream0649 12.0
END DESCRIPTION:
XS GIS Cut Line= 3
      1942825.02     13892074.98        1943225.       13891675.
      1943325.01     13891274.97
#Sta/Elev= 30
  4434.1 1558.49  4663.8 1549.15  4773.5 1542.97    4837 1543.96  5002.3 1543.08
  5010.1 1542.78  5015.6 1541.45  5015.9 1540.95  5019.6 1540.95  5019.9 1541.45
  5030.7 1544.82    5041 1546.77  5051.3 1547.58    5059 1547.02  5064.2 1549.66
  5092.5 1548.92  5100.3 1549.38  5105.4 1550.53  5113.1 1550.75  5133.8 1550.18
  5141.5 1548.74  5146.6 1549.56    5175 1548.87  5187.9    1550  5216.2  1549.6
  5265.2 1551.13  5270.3 1552.23  5288.4 1551.93  5298.7 1552.99  5412.1 1556.74
#Mann= 5 ,-1 , 0
  4434.1      .1       0  4663.8     .07       0    4837      .1       0
  5015.6     .05       0  5019.9      .1       0
Bank Sta=5015.6,5019.9
XS Rating Curve= 0 ,0
Exp/Cntr=0.3,0.1

Type RM Length L Ch R = 1 ,4968    ,435,435,435
BEGIN DESCRIPTION:
Stream0649 11.0
END DESCRIPTION:
XS GIS Cut Line= 3
      1943374.99     13892275.04        1943425.       13891975.
      1943674.99     13891175.03
#Sta/Elev= 30
  4690.6 1565.62  4699.7 1565.42  4723.6 1564.53  4761.6 1555.43  4784.4 1552.69
  4812.3 1546.79  4832.6 1545.35  4966.9 1542.72  4997.4 1539.44  5005.3 1536.52
  5036.7 1538.05  5140.9 1538.62  5151.9 1537.47  5172.9 1538.42  5183.9 1537.38
  5216.4 1537.55  5223.1 1535.57  5223.4 1535.07  5227.5 1535.57  5243.6 1537.51
  5298.6 1538.73  5346.3  1544.3  5424.3 1548.77  5529.1 1552.08  5649.1 1553.85
  5707.2 1555.83  5728.2  1557.3  5746.5 1561.55  5759.6 1563.27  5832.9 1565.68
#Mann= 4 ,-1 , 0
  4690.6    .035       0  4699.7      .1       0  5223.1     .05       0
  5227.5      .1       0
Bank Sta=5223.1,5227.5
XS Rating Curve= 0 ,0
Exp/Cntr=0.3,0.1

Type RM Length L Ch R = 1 ,4533    ,364,364,364
BEGIN DESCRIPTION:
Stream0649 10.0
END DESCRIPTION:
XS GIS Cut Line= 3
        1943575.     13892275.01        1943725.       13891675.
        1943625.       13891575.
#Sta/Elev= 30
  4386.5 1551.57  4404.6 1551.16  4409.7 1549.34  4445.8 1544.89  4474.7 1543.03
  4499.9 1541.95  4541.1 1541.31    4603 1541.47  4610.7 1541.99  4615.9 1541.47
    4650 1541.73  4716.9 1542.22  4757.6 1541.85  4775.6 1540.96  4788.5  1539.5
  4850.4 1536.24  4953.4 1535.02  4963.7 1535.41  4992.5 1532.78  4992.8 1532.28
  4996.6 1532.28  4996.9 1532.78  5002.4 1534.18  5008.5 1534.18  5047.4 1536.69
  5061.5 1538.22  5075.7 1540.83    5104 1547.09  5118.1 1548.45  5146.4 1549.14
#Mann= 6 ,-1 , 0
  4386.5    .035       0  4474.7      .1       0    4650     .07       0
  4716.9      .1       0  4992.5     .05       0  4996.9      .1       0
Bank Sta=4992.5,4996.9
XS Rating Curve= 0 ,0
Exp/Cntr=0.3,0.1

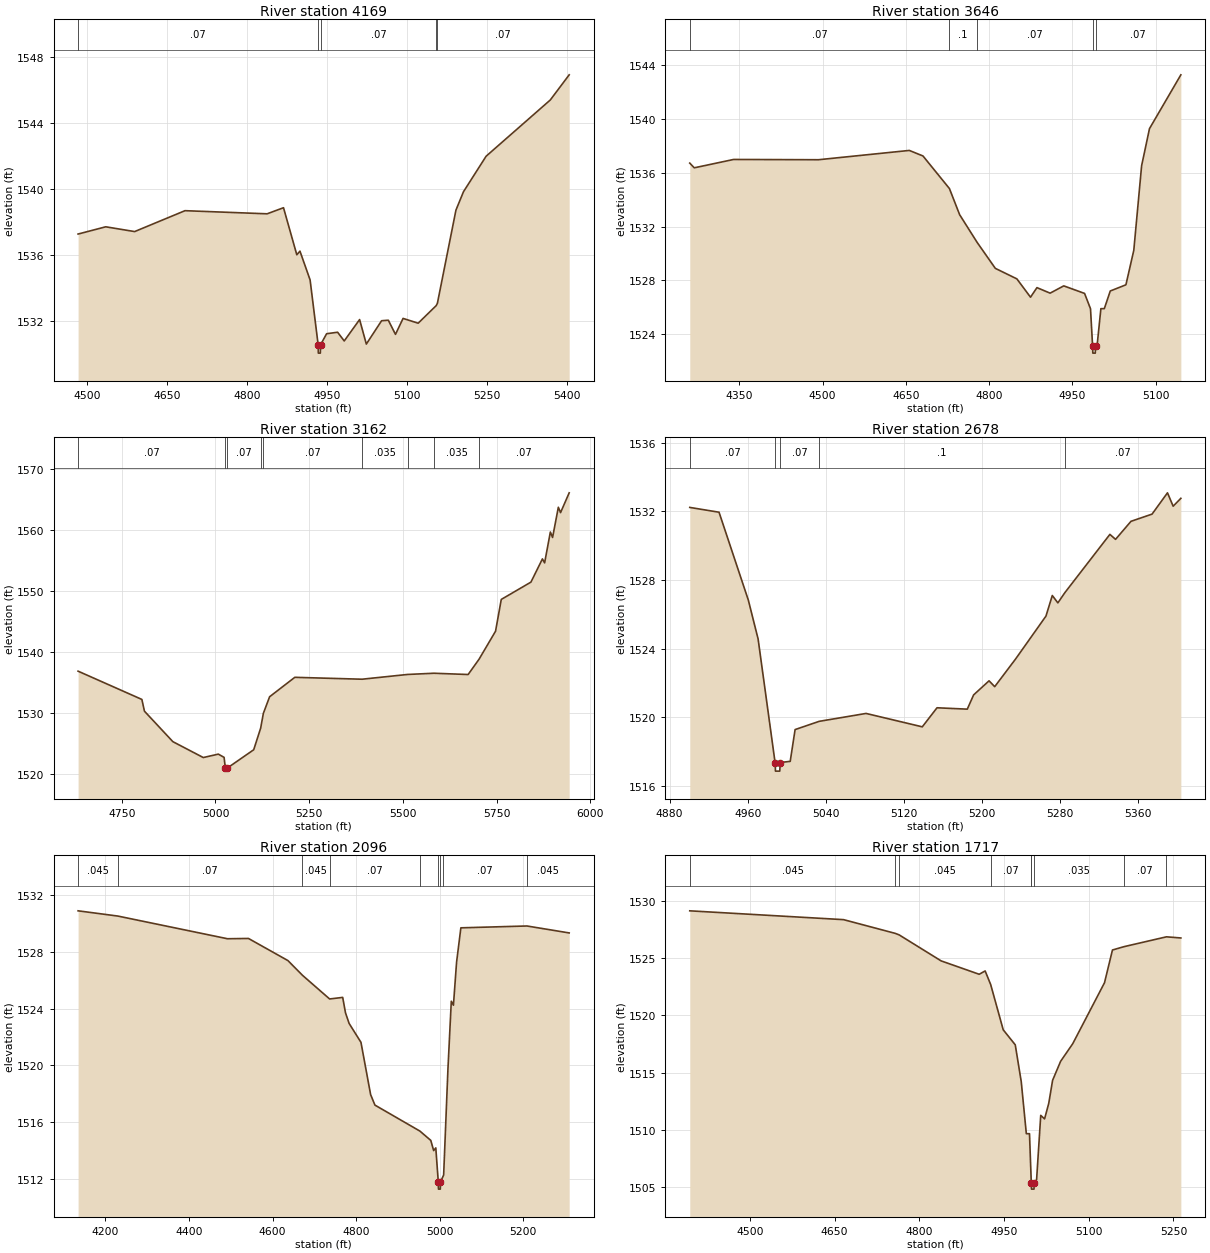
Type RM Length L Ch R = 1 ,4169    ,523,523,523
BEGIN DESCRIPTION:
Stream0649 9.0
END DESCRIPTION:
XS GIS Cut Line= 4
      1943891.06     13892264.72      1944029.66     13891878.28
      1944069.03     13891719.03        1943825.       13891475.
#Sta/Elev= 30
  4483.7 1537.26  4535.5  1537.7  4589.6 1537.41  4683.9 1538.68  4837.7 1538.49
  4868.4 1538.86  4893.3    1536  4899.2 1536.22  4918.2 1534.47  4933.3 1530.52
  4933.6 1530.02  4937.4 1530.02  4937.7 1530.52  4949.1  1531.2  4969.7 1531.29
  4982.1 1530.76  5010.9 1532.06  5023.5 1530.57  5052.1 1531.99  5064.7 1532.02
  5078.1 1531.16  5092.3 1532.13  5120.6 1531.84  5154.4 1532.91  5156.6 1533.05
  5191.3 1538.71  5205.4 1539.83  5247.8 1541.99    5368 1545.41  5403.4 1546.94
#Mann= 5 ,-1 , 0
  4483.7     .07       0  4933.3     .05       0  4937.7     .07       0
  5154.4      .1       0  5156.6     .07       0
Bank Sta=4933.3,4937.7
XS Rating Curve= 0 ,0
Exp/Cntr=0.3,0.1

Type RM Length L Ch R = 1 ,3646    ,484,484,484
BEGIN DESCRIPTION:
Stream0649 8.0
END DESCRIPTION:
XS GIS Cut Line= 3
      1944107.51     13892168.73        1944375.       13891475.
      1944474.98     13891375.02
#Sta/Elev= 30
  4260.5 1536.71  4268.6 1536.36  4339.5 1536.98  4492.4 1536.96  4656.1 1537.65
  4680.7 1537.24  4728.4 1534.82  4746.8 1532.88  4778.1 1530.84  4811.1  1528.9
  4849.9 1528.12  4874.5 1526.76  4886.1 1527.47  4909.8 1527.06  4934.4  1527.6
  4971.9 1527.04  4982.6  1525.9  4986.4 1523.11  4986.8 1522.61  4991.2 1522.61
  4991.6 1523.11  4994.4 1523.14  5001.3 1525.91  5007.5 1525.91  5018.2 1527.22
  5046.4 1527.68  5060.6 1530.24  5074.7 1536.52  5088.9 1539.27  5145.4 1543.26
#Mann= 5 ,-1 , 0
  4260.5     .07       0  4728.4      .1       0  4778.1     .07       0
  4986.4     .05       0  4991.6     .07       0
Bank Sta=4986.4,4991.6
XS Rating Curve= 0 ,0
Exp/Cntr=0.3,0.1

Type RM Length L Ch R = 1 ,3162    ,484,484,484
BEGIN DESCRIPTION:
Stream0649 7.0
END DESCRIPTION:
XS GIS Cut Line= 3
      1944189.07      13892021.2        1944525.       13891875.
      1945025.02     13891074.97
#Sta/Elev= 30
  4633.6  1536.8  4803.7 1532.16  4810.6 1530.23  4886.3 1525.23  4967.5 1522.62
  5007.6 1523.18    5023 1522.65  5026.3 1520.89  5026.7 1520.39  5031.5 1520.89
    5102  1523.9  5120.5 1527.44  5127.7 1529.87  5144.4  1532.6  5211.6 1535.79
  5390.9 1535.48  5512.4 1536.26  5582.7 1536.46  5673.9 1536.25  5703.1 1538.77
    5747 1543.36  5762.3 1548.58  5841.4 1551.42    5872 1555.23  5877.9 1554.58
  5893.2 1559.65  5899.1 1558.75  5914.5 1563.71  5920.4 1562.83  5943.4 1566.08
#Mann= 9 ,-1 , 0
  4633.6     .07       0  5026.3     .05       0  5031.5     .07       0
  5120.5      .1       0  5127.7     .07       0  5390.9    .035       0
  5512.4    .045       0  5582.7    .035       0  5703.1     .07       0
Bank Sta=5026.3,5031.5
XS Rating Curve= 0 ,0
Exp/Cntr=0.3,0.1

Type RM Length L Ch R = 1 ,2678    ,582,582,582
BEGIN DESCRIPTION:
Stream0649 6.0
END DESCRIPTION:
XS GIS Cut Line= 3
        1944425.       13892325.        1944525.       13892325.
      1944724.99     13891975.01
#Sta/Elev= 30
  4900.7 1532.22  4930.7 1531.94  4960.7 1526.82  4970.7 1524.56  4988.1 1517.36
  4988.5 1516.86  4992.9 1516.86  4993.3 1517.36  5003.6 1517.43  5008.6 1519.28
  5033.3 1519.76  5081.3 1520.22  5138.9 1519.44    5154 1520.55    5185 1520.47
  5191.5  1521.3  5207.3 1522.12  5213.1 1521.78  5234.6  1523.4  5265.6 1525.89
  5272.1 1527.09  5277.8 1526.66  5284.9 1527.25  5331.1 1530.65  5336.9 1530.36
  5352.7 1531.41  5374.3 1531.83  5390.1 1533.07  5395.9 1532.29  5403.8 1532.75
#Mann= 5 ,-1 , 0
  4900.7     .07       0  4988.1     .05       0  4993.3     .07       0
  5033.3      .1       0  5284.9     .07       0
Bank Sta=4988.1,4993.3
XS Rating Curve= 0 ,0
Exp/Cntr=0.3,0.1

Type RM Length L Ch R = 1 ,2096    ,379,379,379
BEGIN DESCRIPTION:
Stream0649 5.0
END DESCRIPTION:
XS GIS Cut Line= 3
      1944363.57     13892553.31      1944951.84     13892431.33
      1945084.56     13891872.87
#Sta/Elev= 30
  4134.9  1530.9    4230 1530.53  4492.3 1528.93  4542.5 1528.95  4636.8 1527.39
  4671.7 1526.35  4736.6 1524.68  4767.9 1524.79  4774.6  1523.7  4783.3 1522.95
  4811.6 1521.62  4834.7 1517.93    4845 1517.19  4952.4 1515.36  4978.6  1514.7
  4985.5 1513.98  4990.6 1514.17  4996.6 1511.76    4997 1511.26  5001.4 1511.26
  5001.8 1511.76  5007.9 1512.16  5009.4 1512.26  5019.7 1519.76  5027.7 1524.52
  5032.8 1524.24  5040.3 1527.27  5050.6  1529.7  5208.7 1529.83  5309.7 1529.34
#Mann= 9 ,-1 , 0
  4134.9    .045       0    4230     .07       0  4671.7    .045       0
  4736.6     .07       0  4952.4    .035       0  4996.6    .035       0
  5001.8    .035       0  5007.9     .07       0  5208.7    .045       0
Bank Sta=4996.6,5001.8
XS Rating Curve= 0 ,0
Exp/Cntr=0.3,0.1

Type RM Length L Ch R = 1 ,1717    ,348,348,348
BEGIN DESCRIPTION:
Stream0649 4.0
END DESCRIPTION:
XS GIS Cut Line= 3
      1944573.65     13892653.17       1945136.4     13892447.83
      1945334.92     13892264.16
#Sta/Elev= 30
  4393.6 1529.12  4665.9 1528.35  4757.5 1527.15  4764.3 1527.02  4838.6 1524.75
    4906 1523.58  4916.6 1523.87  4926.4 1522.68  4948.6 1518.73  4969.9 1517.42
  4980.5  1514.2  4989.5 1509.66  4995.1 1509.66  4997.8    1506  4998.3 1505.32
  4998.7 1504.82  5003.1 1504.82  5003.5 1505.32  5007.7 1505.66    5015 1511.26
  5021.8 1510.95  5029.2 1512.31    5036 1514.32  5050.2 1515.98  5071.7 1517.52
  5127.9 1522.84    5142  1525.7  5162.4 1525.99  5237.6 1526.85  5263.1 1526.75
#Mann= 9 ,-1 , 0
  4393.6    .045       0  4757.5     .07       0  4764.3    .045       0
  4926.4     .07       0  4997.8    .035       0  4998.3    .035       0
  5003.5    .035       0  5162.4     .07       0  5237.6    .035       0
Bank Sta=4998.3,5003.5
XS Rating Curve= 0 ,0
Exp/Cntr=0.3,0.1

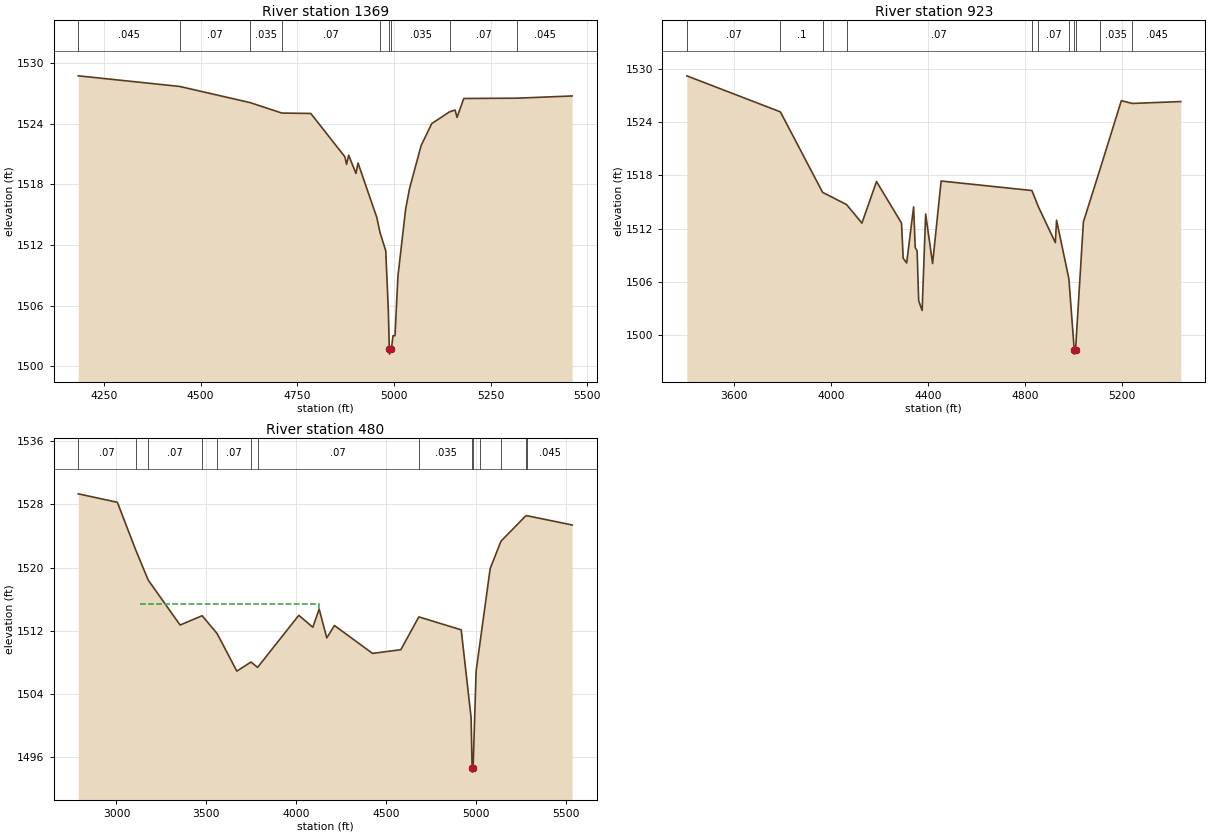
Type RM Length L Ch R = 1 ,1369    ,446,446,446
BEGIN DESCRIPTION:
Stream0649 3.0
END DESCRIPTION:
XS GIS Cut Line= 5
      1944620.11       13892734.      1945306.84       13892672.
        1945425.       13892625.        1945425.       13892525.
      1945395.22     13892165.62
#Sta/Elev= 30
  4183.6 1528.73    4446 1527.68  4628.3 1526.08  4710.1 1525.05    4785 1525.01
  4873.1 1520.73  4877.5 1519.98  4882.9 1520.88  4901.8 1519.08  4907.2 1520.11
  4955.8 1514.72  4963.8 1513.27  4978.8 1511.44  4985.5 1505.57  4988.1 1501.72
  4988.5 1501.22  4993.6 1501.72  4997.6 1503.04  5002.8 1503.04  5010.3  1508.9
  5030.3 1515.56  5040.3 1517.58  5070.3 1521.83  5097.8 1524.01  5143.9 1525.17
  5158.2 1525.35  5163.2 1524.62  5180.6 1526.49  5318.4 1526.52  5460.9 1526.74
#Mann= 9 ,-1 , 0
  4183.6    .045       0    4446     .07       0  4628.3    .035       0
  4710.1     .07       0  4963.8    .035       0  4988.1    .035       0
  4993.6    .035       0  5143.9     .07       0  5318.4    .045       0
Bank Sta=4988.1,4993.6
XS Rating Curve= 0 ,0
Exp/Cntr=0.3,0.1

Type RM Length L Ch R = 1 ,923     ,443,443,443
BEGIN DESCRIPTION:
Stream0649 2.0
END DESCRIPTION:
XS GIS Cut Line= 5
      1944485.55     13892919.09      1945355.31     13893002.42
      1945761.32     13892671.68        1945775.       13892475.
      1945483.79     13892140.07
#Sta/Elev= 30
  3405.2 1529.21  3791.4 1525.15  3965.8 1516.08  4064.5 1514.71  4127.9 1512.62
  4188.2  1517.3  4291.4 1512.62  4298.2 1508.66  4312.6 1508.13  4341.3 1514.45
  4347.8 1509.89  4355.7 1509.47  4362.2 1503.87  4376.5 1502.78  4390.9 1513.64
  4419.6 1508.06  4454.8 1517.36  4829.4 1516.29  4855.7 1514.49  4926.1 1510.42
  4931.2 1512.94    4982 1506.36  5004.1 1498.36  5004.6 1497.86  5009.6 1498.36
    5042 1512.76  5109.7 1518.61  5198.5 1526.41  5243.7  1526.1  5443.6 1526.31
#Mann= 11 ,-1 , 0
  3405.2     .07       0  3791.4      .1       0  3965.8    .035       0
  4064.5     .07       0  4829.4    .035       0  4855.7     .07       0
    4982    .035       0  5004.1    .035       0  5009.6    .035       0
  5109.7    .035       0  5243.7    .045       0
#XS Ineff= 2 , 0
         4794.51 1516.22
Permanent Ineff=
       F       F
Bank Sta=5004.1,5009.6
XS Rating Curve= 0 ,0
Exp/Cntr=0.3,0.1

Type RM Length L Ch R = 1 ,480     ,0,0,0
BEGIN DESCRIPTION:
Stream0649 1.0
END DESCRIPTION:
XS GIS Cut Line= 6
      1944462.03     13893002.42      1945365.72     13893195.13
      1945967.28     13892622.22      1946164.32     13892303.65
        1946075.       13892125.      1945777.48     13891828.77
#Sta/Elev= 30
  2787.1 1529.34  3004.9 1528.27  3106.3 1522.28  3176.5 1518.43  3354.2 1512.74
  3476.8 1513.92  3560.4 1511.65  3669.5 1506.91  3748.7 1508.06  3785.2 1507.38
  4014.7 1513.97  4092.7 1512.46  4127.9 1514.76  4170.4 1511.11  4212.9 1512.68
  4425.2 1509.15  4582.4 1509.62  4682.8 1513.77  4918.5 1512.13  4973.6 1501.02
  4979.2 1494.63  4979.7 1494.13  4984.7 1494.63  5001.6 1506.95  5022.9 1510.45
  5079.8 1519.89    5140 1523.35  5276.8 1526.53    5284 1526.57    5536  1525.4
#Mann= 14 ,-1 , 0
  2787.1     .07       0  3106.3      .1       0  3176.5     .07       0
  3476.8    .035       0  3560.4     .07       0  3748.7    .035       0
  3785.2     .07       0  4682.8    .035       0  4979.2    .035       0
  4984.7    .035       0  5022.9     .07       0    5140    .035       0
  5276.8     .07       0    5284    .045       0
#XS Ineff= 2 ,-1
 3131.73 4124.44 1515.41 4136.96 4666.63 1512.48
Permanent Ineff=
       F       F
Bank Sta=4979.2,4984.7
XS Rating Curve= 0 ,0
Exp/Cntr=0.3,0.1

Chan Stop Cuts=-1
Use User Specified Reach Order=0
Composite Channel Slope=5