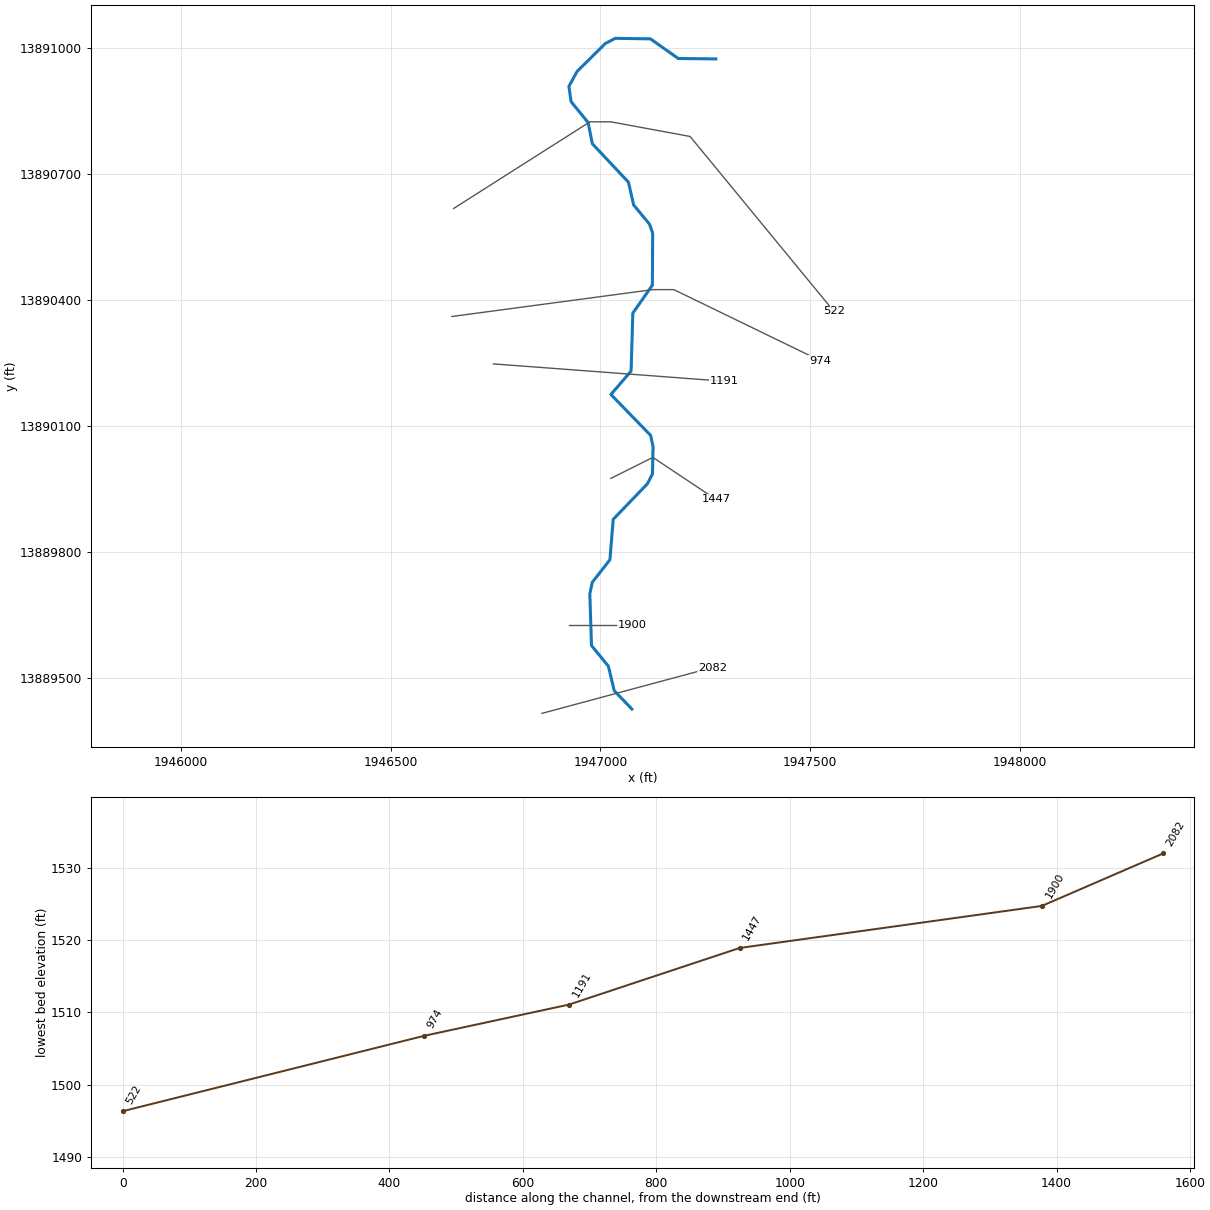
--- Stream0650.prj (project) ---

Proj Title=Stream0650 Base Level Engineering
Current Plan=p01
Default Exp/Contr=0.3,0.1
English Units
Geom File=g01
Flow File=f01
Plan File=p01
BEGIN DESCRIPTION:
Stream0650
END DESCRIPTION:

--- Stream0650.p01 (plan) ---

Plan Title=Multiple Run
Short Identifier=Multiple
Geom File=g01
Flow File=f01
Subcritical Flow
K Sum by GR= 0
Std Step Tol= 0.01
Critical Tol= 0.01
Num of Std Step Trials= 20
Max Error Tol= 0.3
Flow Tol Ratio= 0.001
Split Flow NTrial= 30
Split Flow Tol= 0.02
Split Flow Ratio= 0.02
Log Output Level= 0
Friction Slope Method= 1
Unsteady Friction Slope Method= 2
Unsteady Bridges Friction Slope Method= 1
Parabolic Critical Depth
Global Vel Dist=  1 , 1 , 1
Global Log Level= 0
CheckData=True
Encroach Param= -1, 0, 0, 0
BEGIN DESCRIPTION:
Multiple Run
END DESCRIPTION:

--- Stream0650.f01 (steady flow) ---

Flow Title=Multiple
Number of Profiles=7
Profile Names=10-year,25-year,50-year,1pct_min,100-year,1pct_plu,500-year
River Rch & RM= Stream0650,Reach-1,2082
     799    1333    1833    1222    2439    4866    4254
River Rch & RM= Stream0650,Reach-1,1191
    1175    2011    2812    1903    3798    7578    6835
Boundary for River Rch & Prof#=Stream0650,Reach-1,1
Up Type=0
Dn Type=3
Dn Slope=0.005
Boundary for River Rch & Prof#=Stream0650,Reach-1,2
Up Type=0
Dn Type=3
Dn Slope=0.005
Boundary for River Rch & Prof#=Stream0650,Reach-1,3
Up Type=0
Dn Type=3
Dn Slope=0.005
Boundary for River Rch & Prof#=Stream0650,Reach-1,4
Up Type=0
Dn Type=3
Dn Slope=0.005
Boundary for River Rch & Prof#=Stream0650,Reach-1,5
Up Type=0
Dn Type=3
Dn Slope=0.005
Boundary for River Rch & Prof#=Stream0650,Reach-1,6
Up Type=0
Dn Type=3
Dn Slope=0.005
Boundary for River Rch & Prof#=Stream0650,Reach-1,7
Up Type=0
Dn Type=3
Dn Slope=0.005

--- Stream0650.g01 (geometry) ---

Geom Title=Existing Conditions

River Reach=Stream0650,Reach-1
Reach XY= 30
      1947075.00     13889425.00      1947032.91     13889468.85
      1947018.97     13889527.22      1946978.73     13889576.55
      1946974.77     13889700.07      1946980.74     13889727.33
      1947022.64     13889780.98      1947030.54     13889877.42
      1947111.64     13889961.71      1947124.06     13889985.49
      1947125.51     13890050.04      1947119.67     13890077.45
      1947025.00     13890175.00      1947073.09     13890230.79
      1947077.27     13890369.06      1947123.79     13890435.51
      1947124.51     13890559.78      1947116.91     13890581.07
      1947079.22     13890626.75      1947066.84     13890681.05
      1946980.84     13890772.71      1946970.75     13890823.27
      1946930.31     13890872.81      1946924.94     13890909.67
      1946944.41     13890945.13      1947011.66     13891011.67
      1947035.47     13891024.07      1947119.03     13891022.86
      1947185.42     13890976.02      1947275.00     13890975.00

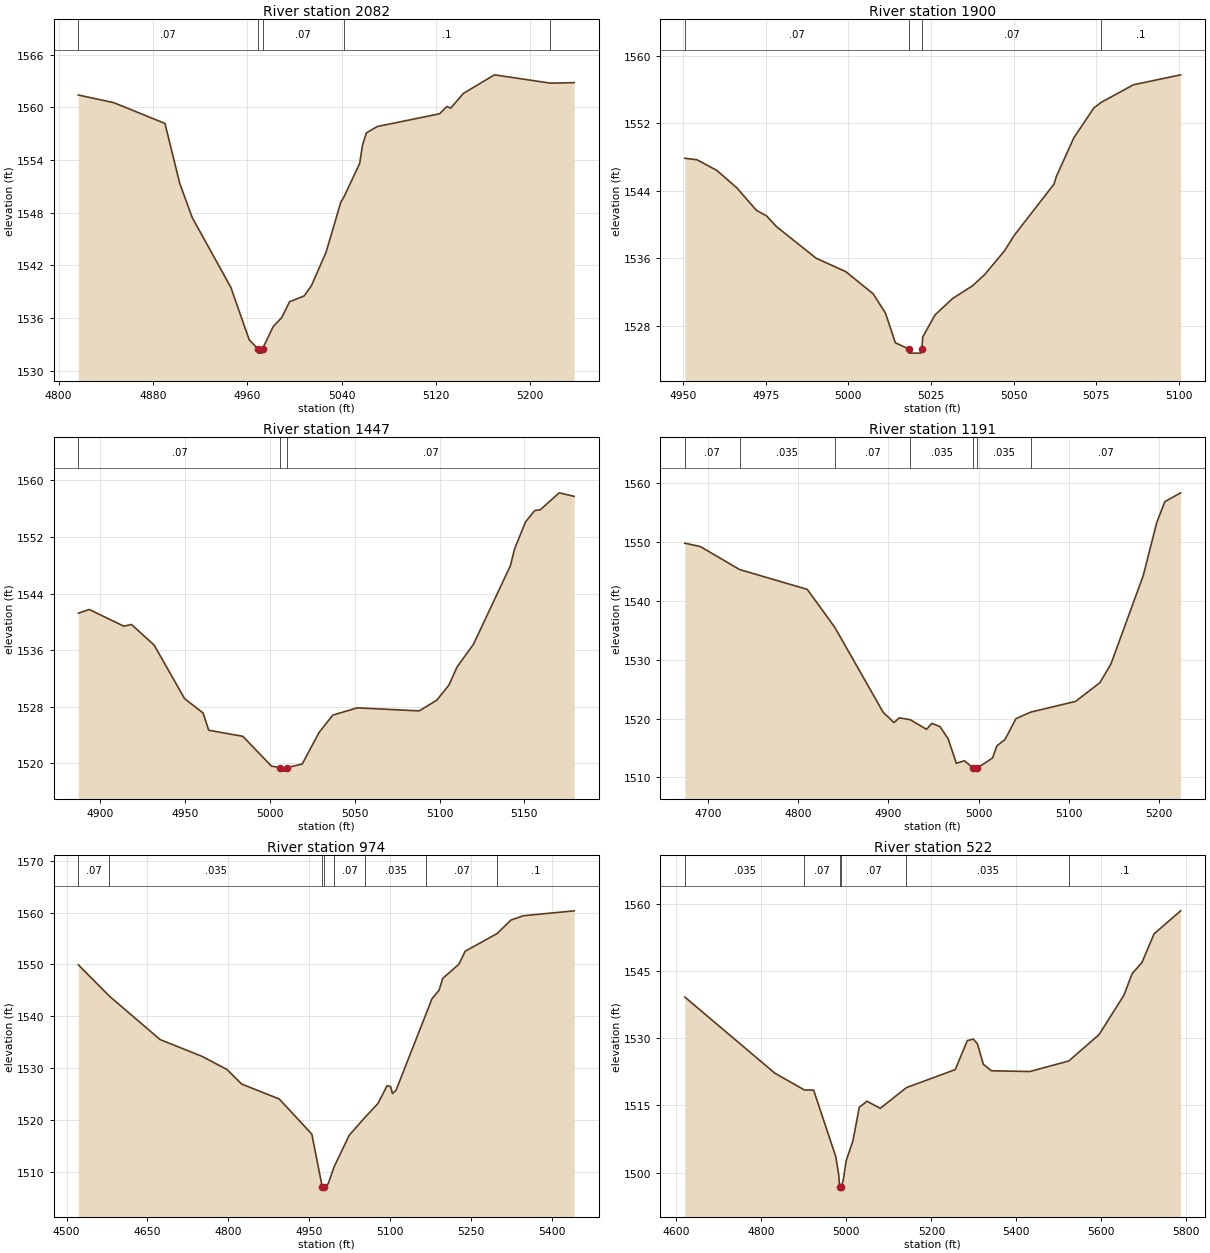
Type RM Length L Ch R = 1,2082,182,182,182
BEGIN DESCRIPTION:
Stream0650 5.0
END DESCRIPTION:
XS GIS Cut Line= 2
      1946860.72     13889414.72      1947266.96     13889524.09
#Sta/Elev= 30
  4816.7 1561.42  4846.7 1560.55  4890.2 1558.18  4902.7 1551.37  4913.4 1547.43
  4946.1 1539.50  4961.7 1533.52  4969.0 1532.50  4969.3 1532.00  4972.8 1532.00
  4973.0 1532.50  4982.0 1535.01  4989.3 1536.06  4995.9 1537.85  5008.3 1538.52
  5014.5 1539.70  5026.9 1543.50  5039.4 1549.20  5042.1 1549.81  5055.4 1553.62
  5057.8 1555.69  5061.1 1557.10  5070.4 1557.83  5123.2 1559.28  5129.4 1560.11
  5132.6 1559.92  5143.5 1561.61  5169.8 1563.72  5217.3 1562.77  5237.4 1562.83
#Mann=5,-1,0
  4816.7    0.07       0  4969.0    0.05       0  4973.0    0.07       0
  5042.1     0.1       0  5217.3    0.07       0
Bank Sta=4969,4973
Exp/Cntr=0.3,0.1

Type RM Length L Ch R = 1,1900,453,453,453
BEGIN DESCRIPTION:
Stream0650 4.0
END DESCRIPTION:
XS GIS Cut Line= 3
      1946925.02     13889625.00      1946975.00     13889625.00
      1947075.02     13889625.00
#Sta/Elev= 30
  4950.5 1547.83  4954.2 1547.65  4960.2 1546.39  4966.2 1544.34  4972.2 1541.65
  4975.2 1541.01  4978.2 1539.74  4990.2 1535.99  4999.2 1534.39  5007.5 1531.76
  5011.2 1529.48  5014.2 1525.96  5018.2 1525.23  5018.4 1524.73  5021.9 1524.73
  5022.2 1525.23  5022.5 1526.66  5026.2 1529.26  5031.5 1531.20  5037.5 1532.70
  5041.2 1534.03  5047.2 1536.85  5050.2 1538.71  5062.2 1544.77  5062.9 1545.67
  5068.2 1550.26  5074.2 1553.77  5076.4 1554.44  5086.2 1556.54  5100.5 1557.72
#Mann=4,-1,0
  4950.5    0.07       0  5018.2    0.05       0  5022.2    0.07       0
  5076.4     0.1       0
Bank Sta=5018.2,5022.2
Exp/Cntr=0.3,0.1

Type RM Length L Ch R = 1,1447,256,256,256
BEGIN DESCRIPTION:
Stream0650 3.0
END DESCRIPTION:
XS GIS Cut Line= 3
      1947025.02     13889975.01      1947125.00     13890025.00
      1947275.03     13889924.98
#Sta/Elev= 30
  4887.2 1541.22  4893.6 1541.75  4914.0 1539.39  4918.5 1539.63  4931.9 1536.71
  4949.8 1529.15  4960.7 1527.13  4964.0 1524.69  4984.1 1523.83  5001.0 1519.62
  5006.3 1519.41  5006.5 1518.91  5010.0 1518.91  5010.3 1519.41  5019.1 1519.92
  5029.1 1524.40  5037.1 1526.82  5051.5 1527.85  5088.0 1527.42  5098.4 1528.94
  5105.6 1531.10  5110.3 1533.62  5120.0 1536.84  5141.7 1547.91  5144.2 1550.31
  5150.7 1554.14  5156.1 1555.73  5159.4 1555.85  5170.5 1558.23  5179.3 1557.73
#Mann=3,-1,0
  4887.2    0.07       0  5006.3    0.05       0  5010.3    0.07       0
Bank Sta=5006.3,5010.3
Exp/Cntr=0.3,0.1

Type RM Length L Ch R = 1,1191,217,217,217
BEGIN DESCRIPTION:
Stream0650 0.0
END DESCRIPTION:
XS GIS Cut Line= 2
      1946745.08     13890247.93      1947294.13     13890206.70
#Sta/Elev= 30
  4673.8 1549.84  4691.1 1549.26  4734.7 1545.35  4809.8 1541.98  4840.4 1535.52
  4894.1 1521.08  4906.1 1519.33  4912.1 1520.14  4924.3 1519.81  4942.2 1518.18
  4948.2 1519.19  4957.2 1518.65  4966.3 1516.55  4975.3 1512.40  4984.3 1512.84
  4994.3 1511.57  4994.6 1511.07  4998.3 1511.57  5015.5 1513.30  5020.4 1515.37
  5029.4 1516.45  5041.5 1519.99  5057.8 1521.10  5107.7 1522.93  5134.7 1526.10
  5147.0 1529.28  5182.9 1544.33  5197.9 1553.36  5206.9 1556.90  5224.4 1558.40
#Mann=7,-1,0
  4673.8    0.07       0  4734.7   0.035       0  4840.4    0.07       0
  4924.3   0.035       0  4994.3   0.035       0  4998.3   0.035       0
  5057.8    0.07       0
Bank Sta=4994.3,4998.3
Exp/Cntr=0.3,0.1

Type RM Length L Ch R = 1,974,452,452,452
BEGIN DESCRIPTION:
Stream0650 2.0
END DESCRIPTION:
XS GIS Cut Line= 4
      1946646.23     13890360.91      1947125.00     13890425.00
      1947175.00     13890425.00      1947523.17     13890255.89
#Sta/Elev= 30
  4521.9 1549.94  4579.5 1543.91  4673.7 1535.54  4751.5 1532.31  4797.8 1529.78
  4825.1 1526.97  4894.7 1524.11  4955.2 1517.34  4974.4 1507.25  4974.7 1506.75
  4978.4 1507.25  4985.5 1507.76  4996.3 1510.99  5024.7 1517.14  5053.8 1520.56
  5078.0 1523.25  5094.9 1526.66  5101.3 1526.52  5104.7 1525.17  5111.3 1525.74
  5167.0 1540.45  5178.0 1543.37  5191.4 1545.05  5198.0 1547.32  5228.1 1550.05
  5239.7 1552.55  5299.3 1555.97  5324.8 1558.56  5348.1 1559.39  5442.0 1560.33
#Mann=8,-1,0
  4521.9    0.07       0  4579.5   0.035       0  4974.4    0.05       0
  4978.4   0.035       0  4996.3    0.07       0  5053.8   0.035       0
  5167.0    0.07       0  5299.3     0.1       0
Bank Sta=4974.4,4978.4
Exp/Cntr=0.3,0.1

Type RM Length L Ch R = 1,522,0,0,0
BEGIN DESCRIPTION:
Stream0650 1.0
END DESCRIPTION:
XS GIS Cut Line= 5
      1946650.22     13890618.40      1946975.00     13890825.00
      1947025.00     13890825.00      1947213.68     13890790.13
      1947556.39     13890373.07
#Sta/Elev= 30
  4619.8 1539.22  4831.6 1522.22  4901.2 1518.46  4922.9 1518.43  4975.0 1503.58
  4981.9 1499.59  4983.9 1496.81  4984.1 1496.31  4987.9 1496.81  4992.4 1498.20
  4999.6 1502.68  5015.4 1507.09  5030.4 1514.61  5048.4 1515.94  5079.7 1514.36
  5141.3 1518.99  5256.1 1523.01  5284.5 1529.49  5298.6 1529.82  5308.1 1528.81
  5322.3 1524.19  5341.2 1522.75  5431.5 1522.58  5523.3 1524.94  5594.6 1530.84
  5652.8 1539.60  5672.2 1544.42  5695.5 1546.96  5723.9 1553.34  5786.4 1558.48
#Mann=6,-1,0
  4619.8   0.035       0  4901.2    0.07       0  4983.9    0.05       0
  4987.9    0.07       0  5141.3   0.035       0  5523.3     0.1       0
Bank Sta=4983.9,4987.9
Exp/Cntr=0.3,0.1

Chan Stop Cuts=-1