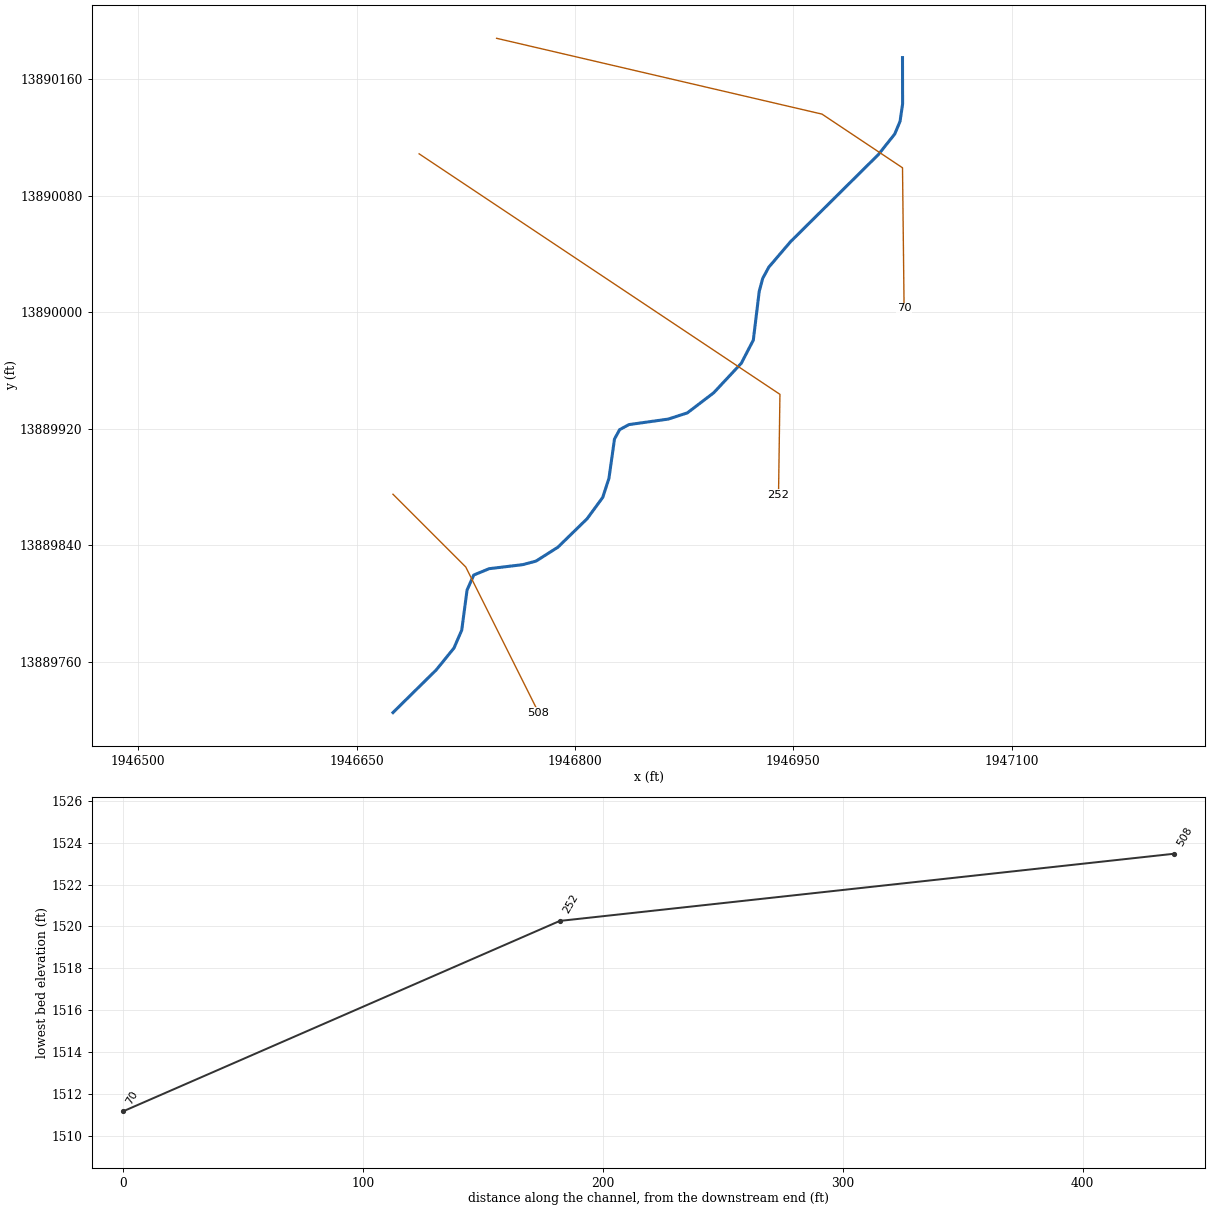
--- Stream0651.prj (project) ---

Proj Title=Stream0651 Base Level Engineering
Current Plan=p01
Default Exp/Contr=0.3,0.1
English Units
Geom File=g01
Flow File=f01
Plan File=p01
BEGIN DESCRIPTION:
Stream0651
END DESCRIPTION:

--- Stream0651.p01 (plan) ---

Plan Title=Multiple Run
Short Identifier=Multiple
Geom File=g01
Flow File=f01
Subcritical Flow
K Sum by GR= 0
Std Step Tol= 0.01
Critical Tol= 0.01
Num of Std Step Trials= 20
Max Error Tol= 0.3
Flow Tol Ratio= 0.001
Split Flow NTrial= 30
Split Flow Tol= 0.02
Split Flow Ratio= 0.02
Log Output Level= 0
Friction Slope Method= 1
Unsteady Friction Slope Method= 2
Unsteady Bridges Friction Slope Method= 1
Parabolic Critical Depth
Global Vel Dist=  1 , 1 , 1
Global Log Level= 0
CheckData=True
Encroach Param= -1, 0, 0, 0
BEGIN DESCRIPTION:
Multiple Run
END DESCRIPTION:

--- Stream0651.f01 (steady flow) ---

Flow Title=Multiple
Number of Profiles=7
Profile Names=10-year,25-year,50-year,1pct_min,100-year,1pct_plu,500-year
River Rch & RM= Stream0651,Reach-1,508
     647    1072    1468     978    1950    3892    3386
Boundary for River Rch & Prof#=Stream0651,Reach-1,1
Up Type=0
Dn Type=3
Dn Slope=0.005
Boundary for River Rch & Prof#=Stream0651,Reach-1,2
Up Type=0
Dn Type=3
Dn Slope=0.005
Boundary for River Rch & Prof#=Stream0651,Reach-1,3
Up Type=0
Dn Type=3
Dn Slope=0.005
Boundary for River Rch & Prof#=Stream0651,Reach-1,4
Up Type=0
Dn Type=3
Dn Slope=0.005
Boundary for River Rch & Prof#=Stream0651,Reach-1,5
Up Type=0
Dn Type=3
Dn Slope=0.005
Boundary for River Rch & Prof#=Stream0651,Reach-1,6
Up Type=0
Dn Type=3
Dn Slope=0.005
Boundary for River Rch & Prof#=Stream0651,Reach-1,7
Up Type=0
Dn Type=3
Dn Slope=0.005

--- Stream0651.g01 (geometry) ---

Geom Title=Existing Conditions

River Reach=Stream0651,Reach-1
Reach XY= 30
      1946675.00     13889725.00      1946704.75     13889754.34
      1946716.88     13889769.30      1946722.22     13889781.60
      1946725.88     13889809.17      1946730.47     13889819.48
      1946741.03     13889823.84      1946764.13     13889826.63
      1946773.21     13889829.04      1946788.31     13889838.63
      1946808.35     13889858.18      1946819.08     13889872.81
      1946823.34     13889885.88      1946827.16     13889912.92
      1946830.66     13889919.34      1946837.08     13889922.84
      1946864.13     13889926.64      1946877.21     13889930.89
      1946895.31     13889944.70      1946914.30     13889965.03
      1946922.52     13889980.88      1946926.57     13890014.31
      1946928.99     13890023.32      1946933.17     13890031.03
      1946948.04     13890048.45      1947008.38     13890108.31
      1947019.67     13890122.49      1947023.31     13890131.15
      1947025.07     13890143.12      1947025.00     13890175.00

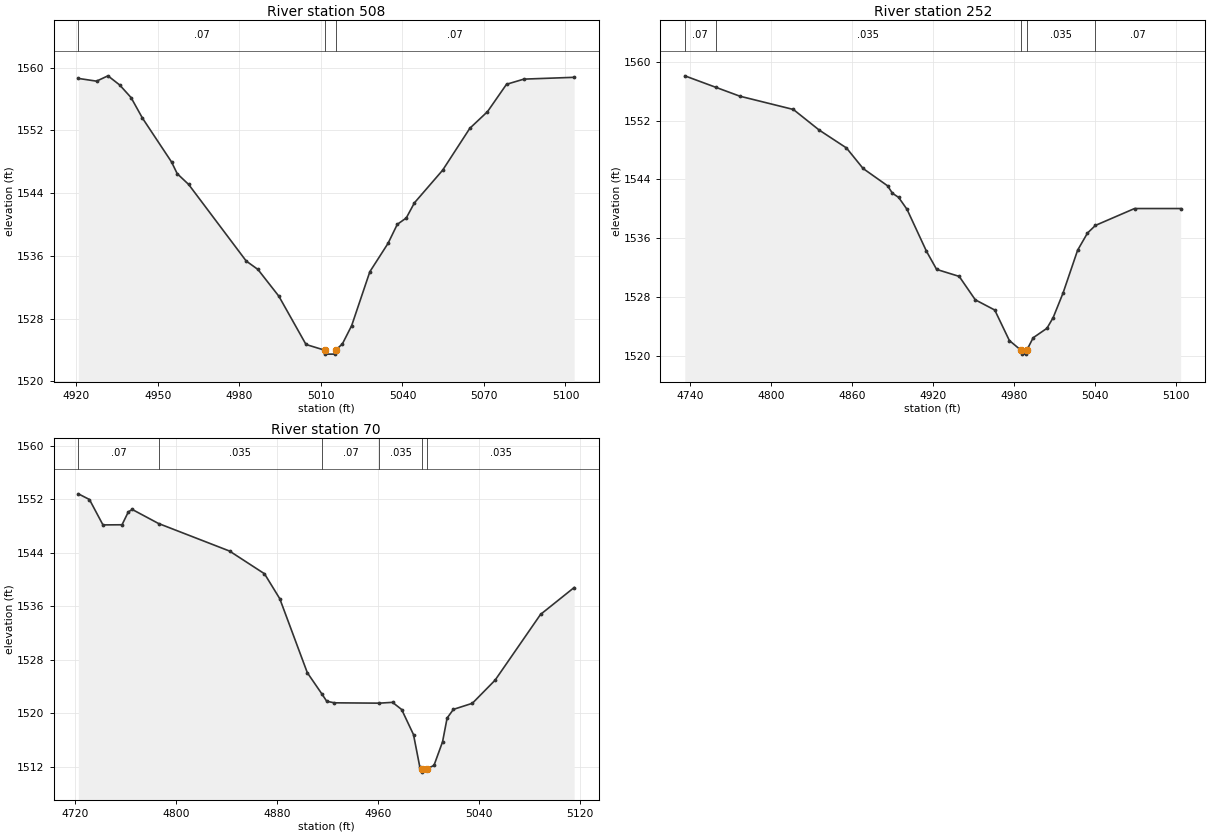
Type RM Length L Ch R = 1,508,256,256,256
BEGIN DESCRIPTION:
Stream0651 1.0
END DESCRIPTION:
XS GIS Cut Line= 3
      1946675.00     13889875.00      1946725.00     13889825.00
      1946775.00     13889725.01
#Sta/Elev= 30
  4920.7 1558.63  4927.4 1558.28  4931.6 1558.96  4935.9 1557.80  4940.1 1556.19
  4944.3 1553.57  4955.0 1547.98  4957.1 1546.48  4961.3 1545.11  4982.5 1535.34
  4986.8 1534.27  4994.5 1530.86  5004.5 1524.70  5011.4 1523.97  5011.6 1523.47
  5015.1 1523.47  5015.4 1523.97  5017.9 1524.78  5021.3 1527.10  5028.0 1533.98
  5034.7 1537.60  5038.1 1540.02  5041.4 1540.83  5044.4 1542.76  5054.8 1546.93
  5064.8 1552.27  5071.3 1554.39  5078.3 1557.88  5084.7 1558.54  5103.2 1558.77
#Mann=3,-1,0
  4920.7    0.07       0  5011.4    0.05       0  5015.4    0.07       0
Bank Sta=5011.4,5015.4
Exp/Cntr=0.3,0.1

Type RM Length L Ch R = 1,252,182,182,182
BEGIN DESCRIPTION:
Stream0651 0.0
END DESCRIPTION:
XS GIS Cut Line= 3
      1946692.95     13890108.88      1946940.81     13889943.64
      1946939.84     13889874.74
#Sta/Elev= 30
  4736.3 1558.07  4759.1 1556.52  4777.1 1555.30  4816.6 1553.50  4835.8 1550.69
  4855.9 1548.27  4868.2 1545.48  4886.3 1543.13  4889.9 1542.12  4894.5 1541.55
  4900.7 1539.93  4915.1 1534.23  4922.6 1531.77  4939.3 1530.82  4951.2 1527.64
  4965.6 1526.25  4976.4 1522.11  4985.2 1520.76  4985.5 1520.26  4989.0 1520.26
  4989.2 1520.76  4994.0 1522.48  5004.2 1523.77  5008.8 1525.22  5016.1 1528.55
  5026.9 1534.38  5034.2 1536.71  5040.1 1537.75  5069.0 1540.04  5103.1 1540.04
#Mann=5,-1,0
  4736.3    0.07       0  4759.1   0.035       0  4985.2   0.035       0
  4989.2   0.035       0  5040.1    0.07       0
Bank Sta=4985.2,4989.2
Exp/Cntr=0.3,0.1

Type RM Length L Ch R = 1,70,0,0,0
BEGIN DESCRIPTION:
Stream0651 0.1
END DESCRIPTION:
XS GIS Cut Line= 4
      1946746.17     13890188.25      1946969.68     13890136.17
      1947025.01     13890099.28      1947026.10     13890002.68
#Sta/Elev= 30
  4722.6 1552.80  4731.4 1551.95  4742.1 1548.15  4757.2 1548.17  4762.2 1550.10
  4765.3 1550.46  4786.1 1548.36  4842.3 1544.24  4870.0 1540.84  4882.1 1537.11
  4903.9 1526.04  4915.4 1522.87  4919.3 1521.76  4925.4 1521.53  4960.9 1521.48
  4971.4 1521.60  4978.6 1520.53  4988.0 1516.77  4993.0 1511.92  4994.6 1511.66
  4994.9 1511.16  4998.6 1511.66  5004.2 1512.16  5011.0 1515.70  5014.6 1519.25
  5019.6 1520.55  5034.6 1521.46  5052.6 1524.92  5088.6 1534.76  5115.2 1538.78
#Mann=6,-1,0
  4722.6    0.07       0  4786.1   0.035       0  4915.4    0.07       0
  4960.9   0.035       0  4994.6   0.035       0  4998.6   0.035       0
Bank Sta=4994.6,4998.6
Exp/Cntr=0.3,0.1

Chan Stop Cuts=-1