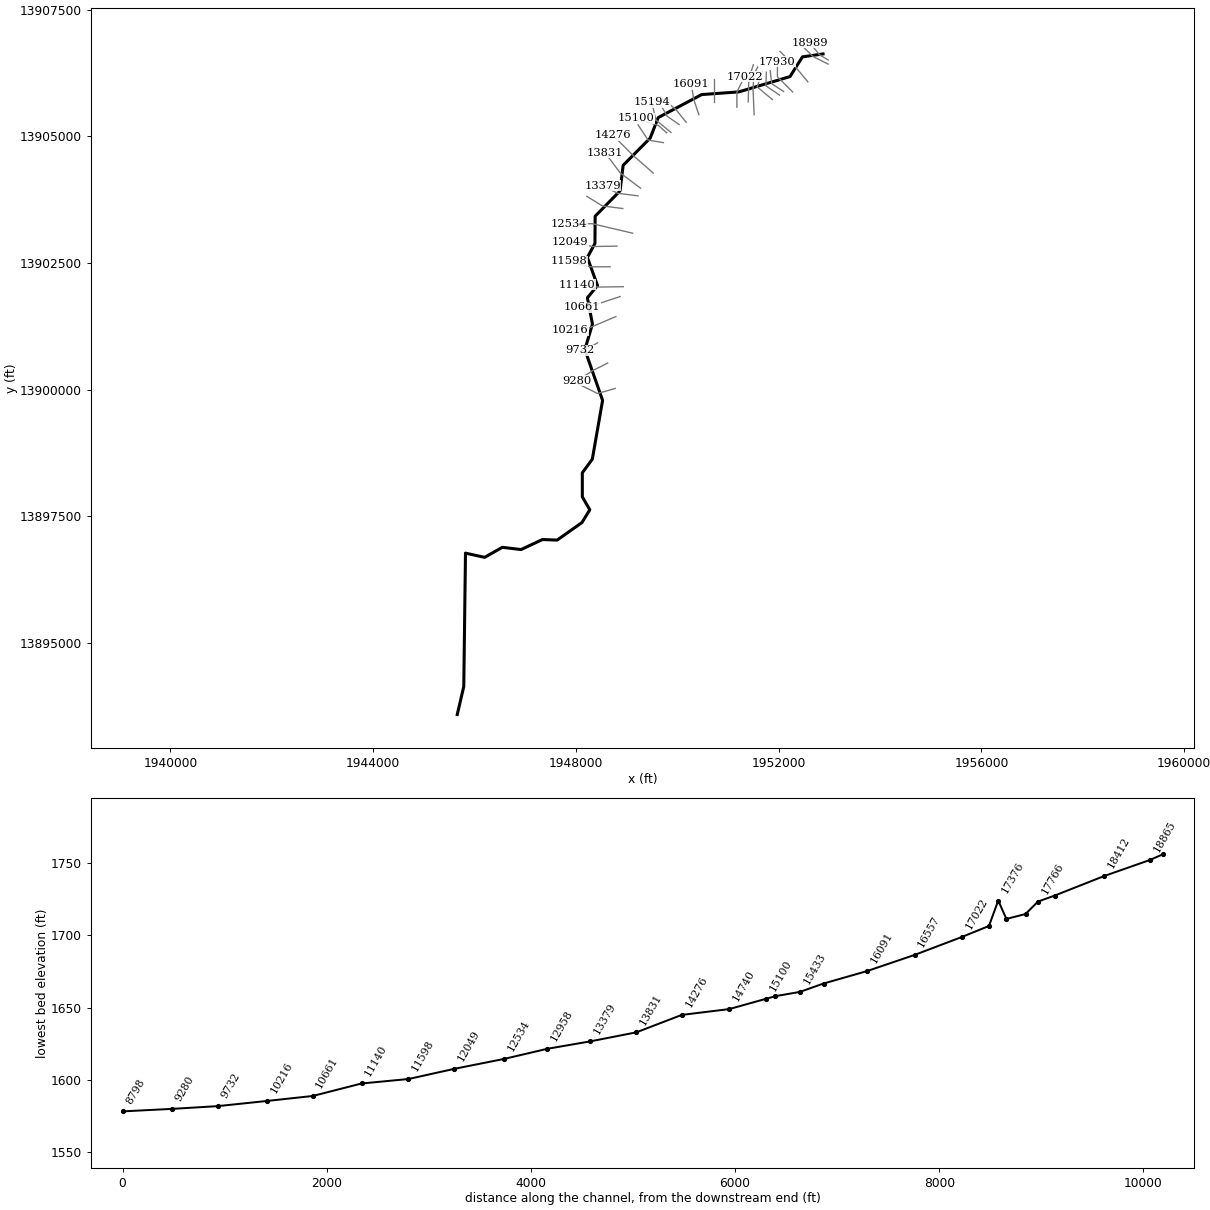
--- Stream0652.prj (project) ---

Proj Title=Stream0652 Base Level Engineering
Current Plan=p01
Default Exp/Contr=0.3,0.1
English Units
Geom File=g01
Flow File=f01
Plan File=p01
BEGIN DESCRIPTION:
Stream0652
END DESCRIPTION:

--- Stream0652.p01 (plan) ---

Plan Title=Multiple Run
Short Identifier=Multiple
Geom File=g01
Flow File=f01
Subcritical Flow
K Sum by GR= 0
Std Step Tol= 0.01
Critical Tol= 0.01
Num of Std Step Trials= 20
Max Error Tol= 0.3
Flow Tol Ratio= 0.001
Split Flow NTrial= 30
Split Flow Tol= 0.02
Split Flow Ratio= 0.02
Log Output Level= 0
Friction Slope Method= 1
Unsteady Friction Slope Method= 2
Unsteady Bridges Friction Slope Method= 1
Parabolic Critical Depth
Global Vel Dist=  1 , 1 , 1
Global Log Level= 0
CheckData=True
Encroach Param= -1, 0, 0, 0
BEGIN DESCRIPTION:
Multiple Run
END DESCRIPTION:

--- Stream0652.f01 (steady flow) ---

Flow Title=Multiple
Number of Profiles=7
Profile Names=10-year,25-year,50-year,1pct_min,100-year,1pct_plu,500-year
River Rch & RM= Stream0652,Reach-1,18989
     741    1236    1699    1134    2263    4514    3952
River Rch & RM= Stream0652,Reach-1,16557
    1031    1756    2449    1655    3302    6589    5921
River Rch & RM= Stream0652,Reach-1,15433
    1488    2595    3675    2519    5027   10029    9280
River Rch & RM= Stream0652,Reach-1,15100
    2418    4304    6176    4277    8534   17027   16101
River Rch & RM= Stream0652,Reach-1,7907
    2630    4660    6665    4594    9166   18289   17140
River Rch & RM= Stream0652,Reach-1,4750
   65003  119563  175708  123476  246366  491566  477083
Boundary for River Rch & Prof#=Stream0652,Reach-1,1
Up Type=0
Dn Type=3
Dn Slope=0.005
Boundary for River Rch & Prof#=Stream0652,Reach-1,2
Up Type=0
Dn Type=3
Dn Slope=0.005
Boundary for River Rch & Prof#=Stream0652,Reach-1,3
Up Type=0
Dn Type=3
Dn Slope=0.005
Boundary for River Rch & Prof#=Stream0652,Reach-1,4
Up Type=0
Dn Type=3
Dn Slope=0.005
Boundary for River Rch & Prof#=Stream0652,Reach-1,5
Up Type=0
Dn Type=3
Dn Slope=0.005
Boundary for River Rch & Prof#=Stream0652,Reach-1,6
Up Type=0
Dn Type=3
Dn Slope=0.005
Boundary for River Rch & Prof#=Stream0652,Reach-1,7
Up Type=0
Dn Type=3
Dn Slope=0.005

--- Stream0652.g01 (geometry) ---

Geom Title=Existing Conditions

River Reach=Stream0652,Reach-1
Reach XY= 30
      1952875.00     13906625.00      1952468.79     13906567.20
      1952223.55     13906178.53      1951214.50     13905876.20
      1950481.11     13905823.20      1949622.48     13905369.32
      1949464.61     13904964.89      1948930.83     13904427.30
      1948869.92     13903922.69      1948378.61     13903423.50
      1948374.40     13902885.62      1948225.09     13902609.61
      1948425.44     13902054.82      1948226.05     13901814.57
      1948325.30     13901295.17      1948175.52     13900790.22
      1948525.49     13899790.20      1948323.02     13898630.67
      1948125.09     13898359.61      1948125.87     13897885.33
      1948272.77     13897630.93      1948119.56     13897380.19
      1947628.41     13897032.82      1947338.52     13897043.97
      1946916.64     13896846.06      1946546.85     13896890.33
      1946197.89     13896692.41      1945820.29     13896775.74
      1945786.43     13894142.93      1945657.77     13893592.31

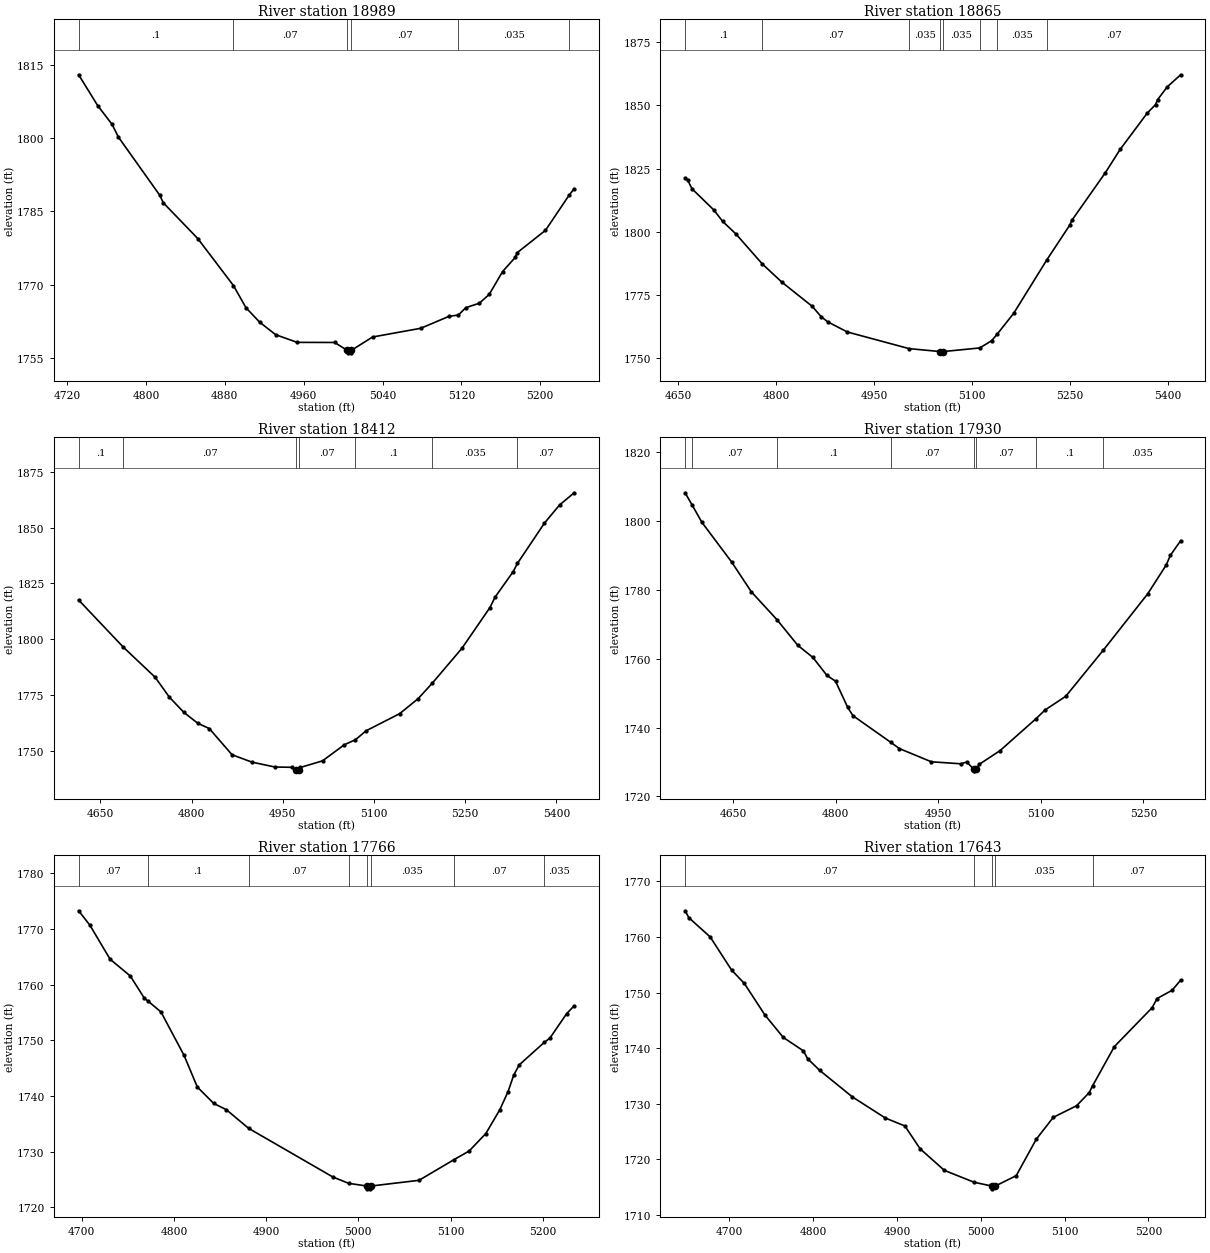
Type RM Length L Ch R = 1,18989,124,124,124
BEGIN DESCRIPTION:
Stream0652 47.0
END DESCRIPTION:
XS GIS Cut Line= 3
      1952976.15     13906505.19      1952806.86     13906606.77
      1952614.13     13906843.77
#Sta/Elev= 30
  4731.6 1813.07  4751.0 1806.73  4765.5 1802.90  4772.0 1800.27  4814.0 1788.32
  4817.5 1786.79  4852.5 1779.45  4888.7 1769.80  4901.4 1765.25  4915.4 1762.26
  4931.6 1759.70  4953.4 1758.13  4991.4 1758.11  5004.3 1756.48  5004.5 1755.98
  5008.0 1755.98  5008.3 1756.48  5029.9 1759.23  5078.8 1761.02  5107.3 1763.46
  5117.0 1763.75  5124.5 1765.25  5138.2 1766.16  5148.3 1767.98  5161.9 1772.68
  5174.7 1775.58  5176.8 1776.56  5205.4 1781.14  5229.3 1788.33  5234.5 1789.68
#Mann=6,-1,0
  4731.6     0.1       0  4888.7    0.07       0  5004.3    0.05       0
  5008.3    0.07       0  5117.0   0.035       0  5229.3    0.07       0
Bank Sta=5004.3,5008.3
Exp/Cntr=0.3,0.1

Type RM Length L Ch R = 1,18865,453,453,453
BEGIN DESCRIPTION:
Stream0652 46.0
END DESCRIPTION:
XS GIS Cut Line= 3
      1952975.00     13906425.00      1952675.00     13906575.00
      1952374.99     13906875.01
#Sta/Elev= 30
  4660.3 1821.31  4664.2 1820.47  4670.9 1816.99  4704.5 1808.58  4717.9 1804.09
  4738.0 1799.19  4778.4 1787.34  4808.4 1780.13  4855.4 1770.46  4868.8 1766.44
  4879.1 1764.35  4909.1 1760.36  5003.8 1753.78  5051.8 1752.62  5052.0 1752.12
  5055.8 1752.62  5112.1 1754.06  5130.2 1756.91  5138.6 1759.46  5164.1 1767.77
  5214.9 1788.90  5250.0 1802.63  5253.2 1804.51  5304.1 1823.17  5327.3 1832.58
  5368.7 1846.89  5381.5 1850.29  5384.7 1852.26  5399.5 1857.30  5420.0 1862.08
#Mann=8,-1,0
  4660.3     0.1       0  4778.4    0.07       0  5003.8   0.035       0
  5051.8    0.05       0  5055.8   0.035       0  5112.1     0.1       0
  5138.6   0.035       0  5214.9    0.07       0
Bank Sta=5051.8,5055.8
Exp/Cntr=0.3,0.1

Type RM Length L Ch R = 1,18412,482,482,482
BEGIN DESCRIPTION:
Stream0652 45.0
END DESCRIPTION:
XS GIS Cut Line= 3
      1952575.02     13906074.98      1952325.00     13906375.00
      1952025.00     13906675.00
#Sta/Elev= 30
  4614.3 1817.53  4687.8 1796.37  4740.1 1782.88  4763.5 1773.95  4787.5 1767.07
  4810.4 1762.19  4829.1 1759.88  4866.6 1748.09  4899.4 1744.79  4936.9 1742.61
  4965.0 1742.47  4972.4 1741.39  4972.6 1740.89  4976.4 1741.39  4979.1 1742.42
  5015.4 1745.38  5051.2 1752.60  5069.3 1754.81  5087.0 1758.86  5142.1 1766.53
  5172.4 1773.24  5195.4 1780.09  5244.5 1795.85  5290.6 1814.15  5299.1 1818.85
  5328.8 1830.26  5335.8 1833.96  5380.3 1852.06  5405.1 1860.18  5429.1 1865.64
#Mann=7,-1,0
  4614.3     0.1       0  4687.8    0.07       0  4972.4    0.05       0
  4976.4    0.07       0  5069.3     0.1       0  5195.4   0.035       0
  5335.8    0.07       0
Bank Sta=4972.4,4976.4
Exp/Cntr=0.3,0.1

Type RM Length L Ch R = 1,17930,164,164,164
BEGIN DESCRIPTION:
Stream0652 44.0
END DESCRIPTION:
XS GIS Cut Line= 3
      1952275.00     13905875.00      1951975.00     13906175.00
      1951975.00     13906475.04
#Sta/Elev= 30
  4580.0 1808.26  4590.5 1804.62  4604.7 1799.63  4648.0 1788.15  4676.9 1779.46
  4714.2 1771.40  4744.7 1763.93  4766.8 1760.40  4787.2 1755.21  4799.9 1753.49
  4817.7 1745.88  4825.3 1743.49  4880.3 1735.78  4893.2 1733.92  4939.9 1730.08
  4983.1 1729.50  4991.6 1730.02  5001.9 1727.95  5002.2 1727.45  5005.9 1727.95
  5009.8 1729.32  5040.3 1733.32  5092.9 1742.60  5106.3 1745.16  5136.3 1749.10
  5191.3 1762.53  5256.3 1778.93  5283.3 1787.30  5289.3 1790.09  5304.3 1794.32
#Mann=8,-1,0
  4580.0     0.1       0  4590.5    0.07       0  4714.2     0.1       0
  4880.3    0.07       0  5001.9    0.05       0  5005.9    0.07       0
  5092.9     0.1       0  5191.3   0.035       0
Bank Sta=5001.9,5005.9
Exp/Cntr=0.3,0.1

Type RM Length L Ch R = 1,17766,123,123,123
BEGIN DESCRIPTION:
Mapping XS 5ee528b2
END DESCRIPTION:
XS GIS Cut Line= 3
      1952098.19     13905883.35      1951861.63     13906038.27
      1951832.67     13906291.25
#Sta/Elev= 30
  4696.7 1773.28  4708.9 1770.69  4730.8 1764.58  4752.7 1761.56  4768.0 1757.56
  4771.6 1757.10  4786.0 1755.09  4811.1 1747.27  4825.4 1741.60  4843.3 1738.64
  4856.8 1737.54  4881.1 1734.17  4972.4 1725.43  4989.5 1724.29  5009.5 1723.80
  5009.7 1723.30  5013.2 1723.30  5013.5 1723.80  5065.8 1724.83  5103.3 1728.50
  5120.2 1730.10  5138.3 1733.24  5153.4 1737.50  5162.4 1740.77  5168.5 1743.72
  5174.5 1745.58  5201.9 1749.66  5207.7 1750.37  5225.9 1754.78  5234.1 1756.20
#Mann=8,-1,0
  4696.7    0.07       0  4771.6     0.1       0  4881.1    0.07       0
  4989.5   0.035       0  5009.5   0.035       0  5013.5   0.035       0
  5103.3    0.07       0  5201.9   0.035       0
Bank Sta=5009.5,5013.5
Exp/Cntr=0.3,0.1

Type RM Length L Ch R = 1,17643,187,187,187
BEGIN DESCRIPTION:
Mapping XS 196cc2c5
END DESCRIPTION:
XS GIS Cut Line= 3
      1952015.25     13905813.64      1951747.40     13905996.11
      1951756.52     13906263.15
#Sta/Elev= 30
  4647.2 1764.71  4651.7 1763.46  4677.1 1760.01  4702.6 1754.06  4717.9 1751.63
  4742.5 1745.95  4764.3 1741.93  4788.3 1739.51  4793.3 1738.12  4807.8 1735.99
  4846.9 1731.21  4886.3 1727.41  4909.5 1725.99  4927.6 1721.89  4956.6 1718.00
  4992.1 1715.86  5013.3 1715.18  5013.5 1714.68  5017.3 1715.18  5042.3 1717.05
  5066.3 1723.62  5086.5 1727.54  5114.3 1729.63  5129.3 1731.97  5133.6 1733.26
  5159.4 1740.27  5204.4 1747.26  5210.4 1748.92  5228.4 1750.41  5238.5 1752.23
#Mann=5,-1,0
  4647.2    0.07       0  4992.1   0.035       0  5013.3   0.035       0
  5017.3   0.035       0  5133.6    0.07       0
Bank Sta=5013.3,5017.3
Exp/Cntr=0.3,0.1

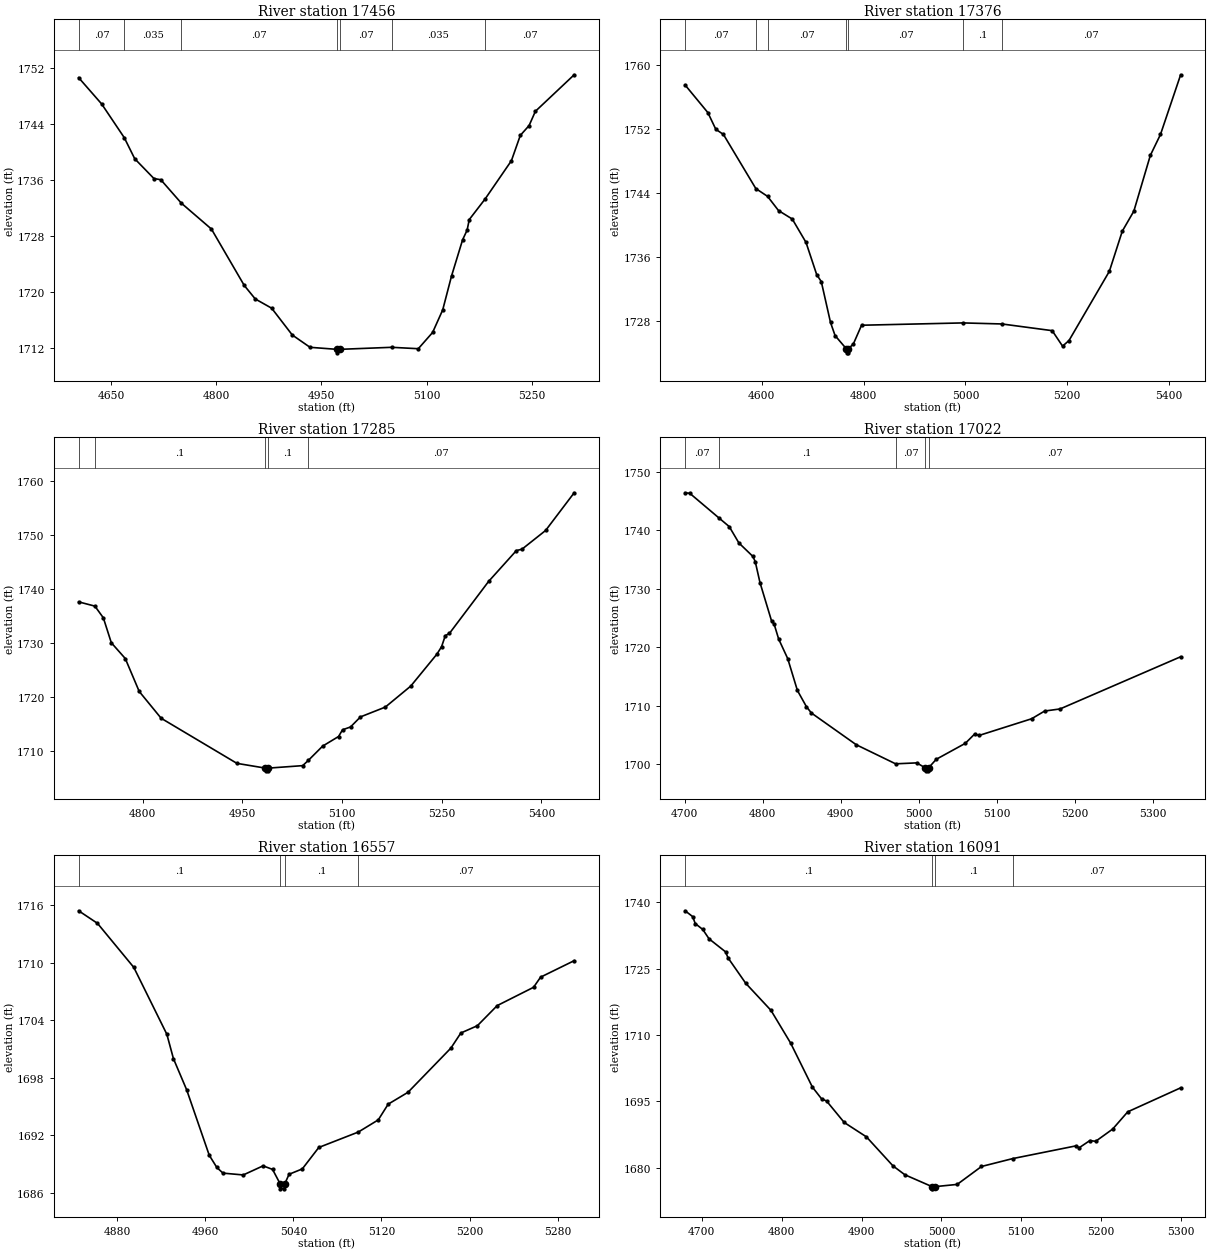
Type RM Length L Ch R = 1,17456,80,80,80
BEGIN DESCRIPTION:
Stream0652 43.0
END DESCRIPTION:
XS GIS Cut Line= 3
      1951875.00     13905725.00      1951575.00     13905975.00
      1951674.99     13906274.97
#Sta/Elev= 30
  4603.7 1750.61  4636.6 1746.84  4668.8 1742.03  4683.7 1739.02  4711.1 1736.19
  4720.9 1736.02  4750.1 1732.68  4793.1 1728.97  4839.9 1720.91  4855.6 1718.98
  4879.0 1717.66  4908.4 1713.83  4933.7 1712.07  4972.0 1711.78  4972.2 1711.28
  4976.0 1711.78  5050.0 1712.07  5088.1 1711.87  5108.5 1714.19  5122.9 1717.41
  5135.5 1722.26  5151.3 1727.44  5157.7 1728.81  5160.8 1730.33  5183.4 1733.27
  5220.9 1738.74  5233.6 1742.36  5246.1 1743.76  5255.1 1745.80  5310.4 1751.02
#Mann=7,-1,0
  4603.7    0.07       0  4668.8   0.035       0  4750.1    0.07       0
  4972.0    0.05       0  4976.0    0.07       0  5050.0   0.035       0
  5183.4    0.07       0
Bank Sta=4972,4976
Exp/Cntr=0.3,0.1

Type RM Length L Ch R = 1,17376,91,91,91
BEGIN DESCRIPTION:
Stream0652 42.1
END DESCRIPTION:
XS GIS Cut Line= 4
      1951516.17     13905424.79      1951494.47     13905904.43
      1951507.49     13906223.44      1951592.12     13906375.35
#Sta/Elev= 30
  4449.4 1757.54  4494.1 1754.08  4509.7 1751.99  4524.7 1751.34  4588.3 1744.56
  4611.4 1743.58  4632.9 1741.80  4659.9 1740.74  4686.9 1737.81  4707.9 1733.77
  4716.9 1732.90  4735.0 1727.78  4744.0 1726.13  4766.2 1724.47  4766.5 1723.97
  4770.0 1723.97  4770.2 1724.47  4780.0 1725.10  4796.0 1727.43  4994.9 1727.72
  5071.6 1727.59  5170.4 1726.75  5190.8 1724.81  5203.4 1725.51  5282.7 1734.19
  5308.1 1739.22  5330.8 1741.73  5363.2 1748.72  5383.1 1751.34  5422.7 1758.82
#Mann=7,-1,0
  4449.4    0.07       0  4588.3   0.035       0  4611.4    0.07       0
  4766.2    0.05       0  4770.2    0.07       0  4994.9     0.1       0
  5071.6    0.07       0
Bank Sta=4766.2,4770.2
Exp/Cntr=0.3,0.1

Type RM Length L Ch R = 1,17285,263,263,263
BEGIN DESCRIPTION:
Mapping XS 792c67b5
END DESCRIPTION:
XS GIS Cut Line= 3
      1951398.70     13905678.87      1951410.40     13906129.72
      1951499.21     13906411.03
#Sta/Elev= 30
  4703.4 1737.61  4727.9 1736.82  4740.6 1734.66  4752.6 1730.06  4773.6 1727.15
  4794.6 1721.07  4827.6 1716.12  4941.7 1707.79  4984.7 1706.91  4984.9 1706.41
  4988.4 1706.41  4988.7 1706.91  5040.7 1707.37  5049.3 1708.35  5070.7 1710.97
  5094.7 1712.75  5100.7 1713.99  5112.7 1714.51  5127.7 1716.37  5165.1 1718.18
  5203.4 1722.06  5242.8 1727.96  5249.8 1729.34  5255.4 1731.37  5261.7 1731.80
  5320.5 1741.37  5362.4 1747.08  5370.8 1747.33  5406.4 1750.79  5449.4 1757.75
#Mann=5,-1,0
  4703.4    0.07       0  4727.9     0.1       0  4984.7    0.05       0
  4988.7     0.1       0  5049.3    0.07       0
Bank Sta=4984.7,4988.7
Exp/Cntr=0.3,0.1

Type RM Length L Ch R = 1,17022,465,465,465
BEGIN DESCRIPTION:
Stream0652 42.0
END DESCRIPTION:
XS GIS Cut Line= 3
      1951175.00     13905575.02      1951175.00     13905875.00
      1951325.00     13906175.01
#Sta/Elev= 30
  4700.4 1746.41  4706.4 1746.32  4743.6 1742.13  4757.0 1740.63  4769.4 1737.83
  4787.4 1735.52  4790.4 1734.61  4796.4 1731.07  4811.4 1724.44  4814.4 1724.03
  4820.4 1721.40  4832.0 1718.06  4844.4 1712.62  4856.0 1709.84  4862.4 1708.76
  4919.9 1703.34  4970.3 1700.08  4997.4 1700.24  5008.5 1699.38  5008.8 1698.88
  5012.3 1698.88  5012.5 1699.38  5022.4 1700.85  5059.7 1703.58  5071.6 1705.16
  5077.6 1704.94  5144.7 1707.78  5161.4 1709.10  5181.2 1709.46  5335.8 1718.38
#Mann=5,-1,0
  4700.4    0.07       0  4743.6     0.1       0  4970.3    0.07       0
  5008.5    0.05       0  5012.5    0.07       0
Bank Sta=5008.5,5012.5
Exp/Cntr=0.3,0.1

Type RM Length L Ch R = 1,16557,466,466,466
BEGIN DESCRIPTION:
Stream0652 41.0
END DESCRIPTION:
XS GIS Cut Line= 3
      1950725.00     13905675.01      1950725.00     13905825.00
      1950725.00     13906125.01
#Sta/Elev= 30
  4845.0 1715.43  4862.1 1714.12  4895.1 1709.52  4925.1 1702.54  4931.1 1699.99
  4943.1 1696.74  4963.6 1689.91  4970.5 1688.63  4976.1 1688.04  4994.5 1687.85
  5012.5 1688.80  5021.1 1688.43  5028.1 1686.90  5028.3 1686.40  5031.8 1686.40
  5032.1 1686.90  5036.1 1687.92  5048.1 1688.48  5063.1 1690.72  5099.0 1692.33
  5117.1 1693.60  5126.1 1695.24  5144.1 1696.48  5183.1 1701.10  5192.1 1702.67
  5207.1 1703.43  5225.1 1705.53  5258.1 1707.44  5264.5 1708.50  5295.0 1710.22
#Mann=4,-1,0
  4845.0     0.1       0  5028.1    0.05       0  5032.1     0.1       0
  5099.0    0.07       0
Bank Sta=5028.1,5032.1
Exp/Cntr=0.3,0.1

Type RM Length L Ch R = 1,16091,426,426,426
BEGIN DESCRIPTION:
Stream0652 40.0
END DESCRIPTION:
XS GIS Cut Line= 3
      1950424.98     13905425.05      1950325.00     13905725.00
      1950275.00     13906024.98
#Sta/Elev= 30
  4679.1 1738.06  4688.6 1736.74  4691.8 1735.17  4701.2 1733.84  4709.1 1731.72
  4729.7 1728.79  4732.9 1727.41  4755.0 1721.68  4786.6 1715.56  4811.2 1708.17
  4838.4 1698.24  4849.9 1695.58  4856.2 1695.08  4878.3 1690.23  4906.1 1686.98
  4939.3 1680.43  4954.2 1678.42  4988.2 1675.74  4988.4 1675.24  4992.2 1675.74
  5019.7 1676.24  5050.1 1680.29  5089.1 1682.07  5168.7 1684.96  5172.2 1684.50
  5185.8 1686.15  5193.0 1685.97  5214.3 1688.74  5233.2 1692.64  5299.4 1698.06
#Mann=4,-1,0
  4679.1     0.1       0  4988.2    0.05       0  4992.2     0.1       0
  5089.1    0.07       0
Bank Sta=4988.2,4992.2
Exp/Cntr=0.3,0.1

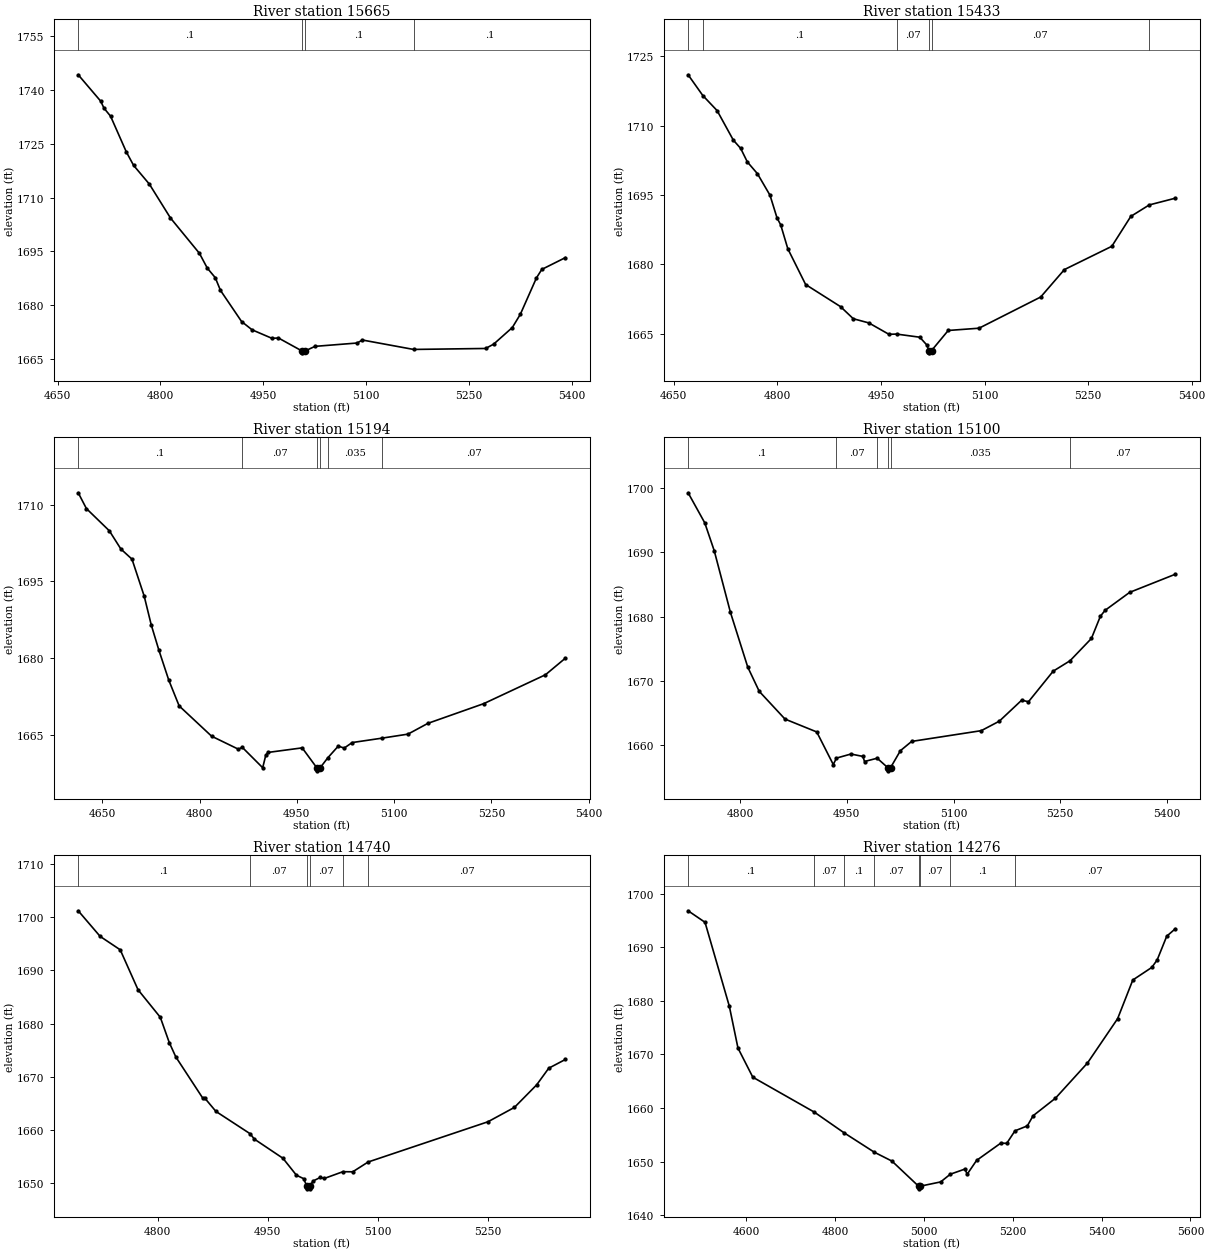
Type RM Length L Ch R = 1,15665,232,232,232
BEGIN DESCRIPTION:
Stream0652 39.0
END DESCRIPTION:
XS GIS Cut Line= 3
      1950175.00     13905275.00      1949975.00     13905525.00
      1949674.98     13905775.02
#Sta/Elev= 30
  4680.1 1744.29  4712.9 1736.92  4717.7 1734.96  4727.3 1732.72  4750.2 1722.78
  4760.9 1718.98  4783.9 1713.75  4814.6 1704.31  4856.9 1694.43  4868.4 1690.29
  4880.0 1687.63  4887.6 1684.08  4918.4 1675.38  4933.7 1673.07  4962.6 1670.70
  4972.2 1670.78  5006.7 1667.14  5007.0 1666.64  5010.7 1667.14  5025.5 1668.45
  5086.8 1669.38  5094.6 1670.22  5169.3 1667.59  5274.3 1667.86  5286.0 1669.06
  5313.3 1673.71  5325.0 1677.41  5348.5 1687.57  5356.3 1689.94  5390.8 1693.24
#Mann=4,-1,0
  4680.1     0.1       0  5006.7    0.05       0  5010.7     0.1       0
  5169.3     0.1       0
Bank Sta=5006.7,5010.7
Exp/Cntr=0.3,0.1

Type RM Length L Ch R = 1,15433,239,239,239
BEGIN DESCRIPTION:
Stream0652 38.1
END DESCRIPTION:
XS GIS Cut Line= 3
      1950036.05     13905231.75      1949799.05     13905395.83
      1949595.93     13905760.41
#Sta/Elev= 30
  4670.7 1720.99  4692.0 1716.50  4712.7 1713.24  4736.2 1706.85  4746.8 1705.07
  4756.5 1702.13  4771.1 1699.59  4789.3 1694.93  4799.5 1690.01  4804.8 1688.52
  4815.1 1683.35  4840.9 1675.61  4891.5 1670.82  4909.9 1668.21  4932.5 1667.30
  4961.5 1664.84  4972.6 1664.89  5006.2 1664.21  5016.5 1662.51  5019.3 1661.33
  5019.5 1660.83  5023.3 1661.33  5047.4 1665.67  5092.0 1666.16  5181.3 1672.91
  5215.6 1678.84  5284.3 1683.88  5311.8 1690.35  5338.5 1692.83  5376.3 1694.29
#Mann=6,-1,0
  4670.7    0.07       0  4692.0     0.1       0  4972.6    0.07       0
  5019.3    0.05       0  5023.3    0.07       0  5338.5     0.1       0
Bank Sta=5019.3,5023.3
Exp/Cntr=0.3,0.1

Type RM Length L Ch R = 1,15194,94,94,94
BEGIN DESCRIPTION:
Stream0652 38.0
END DESCRIPTION:
XS GIS Cut Line= 3
      1949875.03     13905074.97      1949575.00     13905325.00
      1949496.96     13905677.10
#Sta/Elev= 30
  4613.0 1712.36  4625.6 1709.27  4661.0 1704.91  4678.8 1701.34  4695.9 1699.36
  4714.7 1692.13  4725.6 1686.48  4737.3 1681.56  4752.6 1675.67  4768.6 1670.62
  4818.6 1664.69  4859.9 1662.14  4865.9 1662.51  4897.4 1658.51  4902.1 1660.91
  4905.3 1661.50  4958.3 1662.40  4981.4 1658.40  4981.6 1657.90  4985.4 1658.40
  4997.7 1660.44  5013.9 1662.74  5023.1 1662.36  5035.4 1663.44  5080.7 1664.29
  5121.4 1665.09  5152.1 1667.20  5238.2 1671.06  5333.4 1676.72  5364.2 1679.98
#Mann=6,-1,0
  4613.0     0.1       0  4865.9    0.07       0  4981.4   0.035       0
  4985.4    0.07       0  4997.7   0.035       0  5080.7    0.07       0
Bank Sta=4981.4,4985.4
Exp/Cntr=0.3,0.1

Type RM Length L Ch R = 1,15100,360,360,360
BEGIN DESCRIPTION:
Stream0652 37.1
END DESCRIPTION:
XS GIS Cut Line= 3
      1949791.22     13905067.72      1949629.78     13905210.93
      1949184.46     13905356.77
#Sta/Elev= 30
  4727.2 1699.24  4750.6 1694.57  4763.9 1690.24  4786.7 1680.65  4811.0 1672.16
  4827.1 1668.40  4863.3 1664.09  4907.9 1662.09  4931.1 1657.03  4935.6 1658.03
  4955.9 1658.66  4972.7 1658.29  4975.0 1657.50  4992.8 1658.01  5007.6 1656.55
  5007.8 1656.05  5011.6 1656.55  5025.4 1659.18  5041.2 1660.62  5139.0 1662.29
  5164.3 1663.76  5195.8 1667.03  5205.3 1666.78  5240.0 1671.53  5263.7 1673.15
  5293.7 1676.61  5306.3 1680.06  5312.9 1680.98  5347.4 1683.77  5411.6 1686.59
#Mann=6,-1,0
  4727.2     0.1       0  4935.6    0.07       0  4992.8   0.035       0
  5007.6   0.035       0  5011.6   0.035       0  5263.7    0.07       0
Bank Sta=5007.6,5011.6
Exp/Cntr=0.3,0.1

Type RM Length L Ch R = 1,14740,464,464,464
BEGIN DESCRIPTION:
Stream0652 37.0
END DESCRIPTION:
XS GIS Cut Line= 3
      1949725.01     13904875.00      1949425.00     13904925.00
      1949225.00     13905224.99
#Sta/Elev= 30
  4691.6 1701.18  4721.5 1696.37  4748.9 1693.85  4773.2 1686.35  4803.6 1681.17
  4815.8 1676.43  4824.7 1673.74  4861.4 1666.01  4864.5 1665.95  4879.5 1663.49
  4926.0 1659.31  4931.9 1658.29  4970.9 1654.69  4989.3 1651.51  4999.0 1650.87
  5003.6 1649.45  5003.9 1648.95  5007.4 1648.95  5007.6 1649.45  5012.0 1650.42
  5021.9 1651.10  5027.3 1650.90  5052.7 1652.17  5066.1 1652.15  5087.1 1653.99
  5250.6 1661.55  5286.7 1664.25  5317.0 1668.48  5333.5 1671.61  5356.3 1673.26
#Mann=6,-1,0
  4691.6     0.1       0  4926.0    0.07       0  5003.6    0.05       0
  5007.6    0.07       0  5052.7   0.035       0  5087.1    0.07       0
Bank Sta=5003.6,5007.6
Exp/Cntr=0.3,0.1

Type RM Length L Ch R = 1,14276,445,445,445
BEGIN DESCRIPTION:
Stream0652 36.0
END DESCRIPTION:
XS GIS Cut Line= 3
      1949525.02     13904274.98      1949125.00     13904625.00
      1948725.02     13905024.98
#Sta/Elev= 30
  4468.7 1696.79  4506.8 1694.64  4561.5 1679.00  4581.0 1671.19  4614.4 1665.76
  4753.0 1659.24  4819.0 1655.44  4887.8 1651.78  4927.8 1650.11  4987.6 1645.44
  4987.9 1644.94  4991.7 1645.44  5037.4 1646.23  5059.2 1647.67  5092.2 1648.63
  5097.1 1647.66  5118.3 1650.24  5172.9 1653.47  5186.2 1653.42  5204.8 1655.76
  5232.6 1656.68  5245.6 1658.57  5295.9 1661.84  5368.0 1668.40  5435.9 1676.67
  5470.1 1683.88  5512.9 1686.23  5525.0 1687.63  5546.5 1692.05  5565.9 1693.44
#Mann=8,-1,0
  4468.7     0.1       0  4753.0    0.07       0  4819.0     0.1       0
  4887.8    0.07       0  4987.6    0.05       0  4991.7    0.07       0
  5059.2     0.1       0  5204.8    0.07       0
Bank Sta=4987.6,4991.7
Exp/Cntr=0.3,0.1

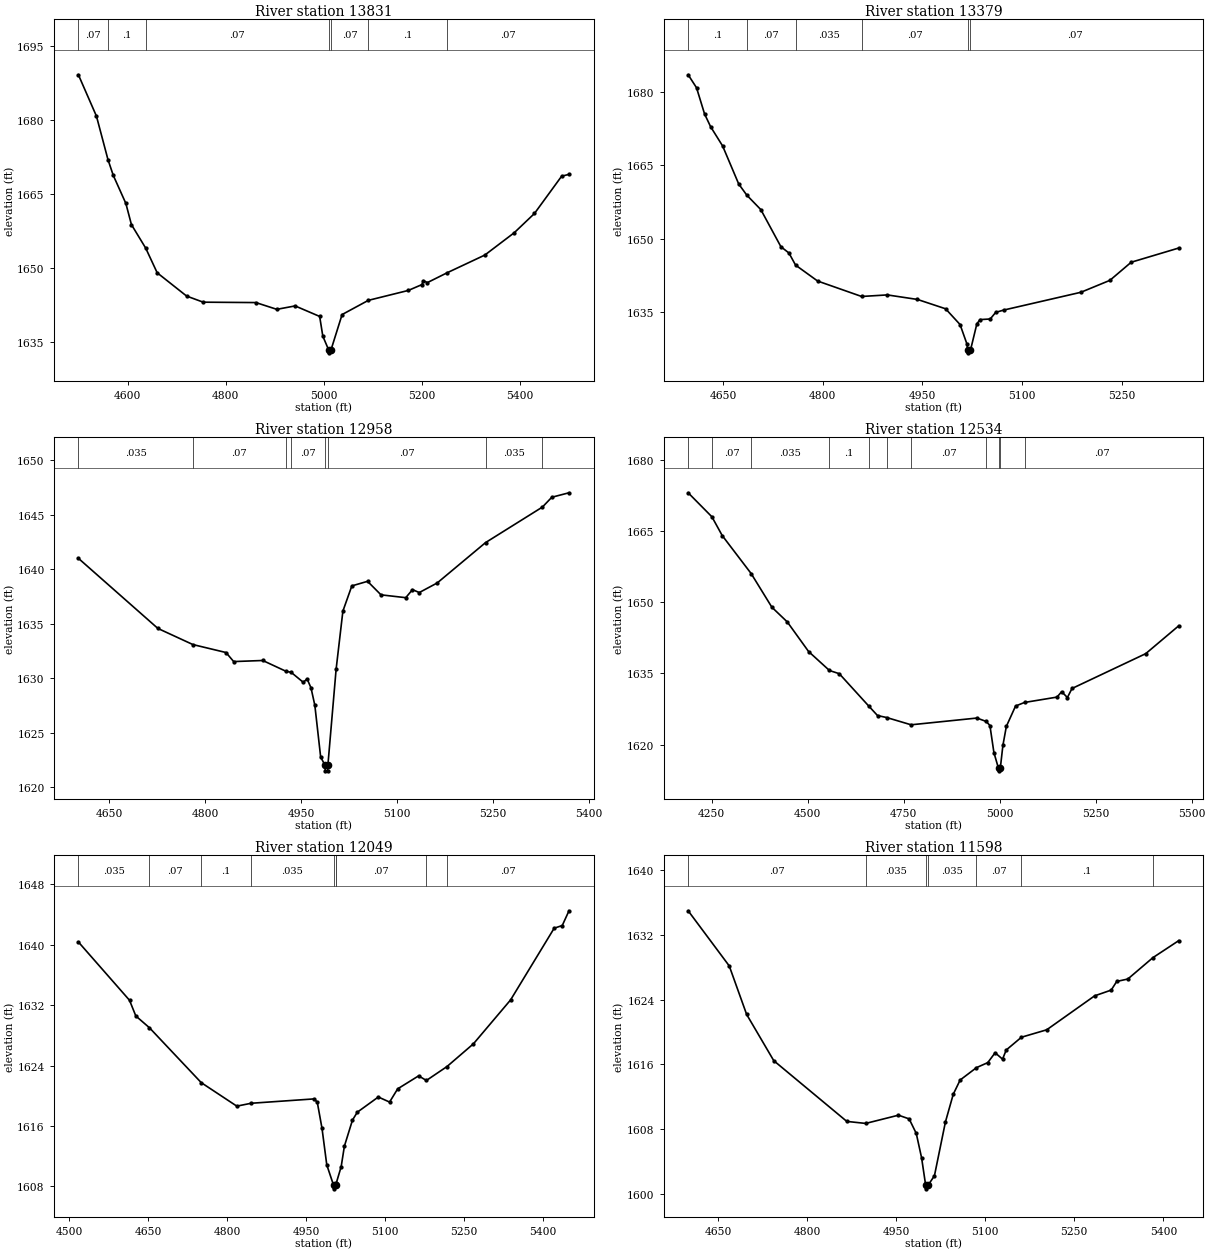
Type RM Length L Ch R = 1,13831,452,452,452
BEGIN DESCRIPTION:
Stream0652 35.0
END DESCRIPTION:
XS GIS Cut Line= 3
      1949275.03     13903974.98      1948875.00     13904275.00
      1948575.02     13904674.97
#Sta/Elev= 30
  4499.4 1689.26  4536.2 1680.88  4559.7 1672.06  4570.5 1668.87  4596.2 1663.17
  4607.5 1658.89  4636.7 1654.10  4660.0 1649.12  4720.0 1644.40  4753.8 1643.16
  4861.2 1643.08  4903.8 1641.71  4941.2 1642.40  4991.2 1640.27  4997.6 1636.28
  5009.9 1633.39  5010.1 1632.89  5014.0 1633.39  5036.9 1640.65  5090.4 1643.53
  5171.9 1645.54  5199.5 1646.72  5202.7 1647.53  5210.8 1647.13  5251.2 1649.13
  5327.8 1652.71  5387.8 1657.24  5429.0 1661.14  5484.4 1668.70  5499.4 1669.07
#Mann=7,-1,0
  4499.4    0.07       0  4559.7     0.1       0  4636.7    0.07       0
  5009.9    0.05       0  5014.0    0.07       0  5090.4     0.1       0
  5251.2    0.07       0
Bank Sta=5009.9,5014
Exp/Cntr=0.3,0.1

Type RM Length L Ch R = 1,13379,421,421,421
BEGIN DESCRIPTION:
Stream0652 34.0
END DESCRIPTION:
XS GIS Cut Line= 3
      1949225.02     13903825.00      1948825.00     13903875.00
      1948525.04     13904024.98
#Sta/Elev= 30
  4597.5 1683.57  4610.1 1680.92  4622.2 1675.55  4631.3 1672.94  4649.4 1668.99
  4673.6 1661.21  4685.8 1658.92  4706.9 1655.96  4737.1 1648.37  4749.2 1647.08
  4759.2 1644.60  4792.4 1641.34  4858.6 1638.18  4897.3 1638.50  4942.7 1637.57
  4985.0 1635.66  5006.8 1632.43  5017.4 1628.35  5018.0 1627.14  5018.3 1626.64
  5022.4 1627.14  5032.1 1632.59  5037.0 1633.45  5052.2 1633.57  5060.4 1634.92
  5072.3 1635.39  5188.7 1639.04  5232.3 1641.48  5264.4 1645.19  5336.0 1648.10
#Mann=6,-1,0
  4597.5     0.1       0  4685.8    0.07       0  4759.2   0.035       0
  4858.6    0.07       0  5018.0    0.05       0  5022.4    0.07       0
Bank Sta=5018,5022.4
Exp/Cntr=0.3,0.1

Type RM Length L Ch R = 1,12958,424,424,424
BEGIN DESCRIPTION:
Stream0652 33.0
END DESCRIPTION:
XS GIS Cut Line= 3
      1948924.97     13903575.00      1948525.00     13903625.00
      1948213.82     13903815.03
#Sta/Elev= 30
  4601.7 1640.99  4726.1 1634.56  4780.9 1633.08  4832.7 1632.35  4844.7 1631.52
  4890.2 1631.62  4925.8 1630.65  4934.7 1630.53  4953.6 1629.62  4959.6 1629.93
  4965.7 1629.11  4971.7 1627.51  4980.8 1622.77  4987.7 1622.00  4988.0 1621.50
  4991.8 1621.50  4992.1 1622.00  5005.0 1630.82  5015.6 1636.15  5029.6 1638.46
  5054.2 1638.88  5075.2 1637.64  5114.0 1637.38  5124.5 1638.12  5135.1 1637.85
  5163.2 1638.73  5238.8 1642.43  5327.8 1645.69  5342.5 1646.59  5369.4 1647.00
#Mann=8,-1,0
  4601.7   0.035       0  4780.9    0.07       0  4925.8   0.035       0
  4934.7    0.07       0  4987.7    0.05       0  4992.1    0.07       0
  5238.8   0.035       0  5327.8    0.07       0
Bank Sta=4987.7,4992.1
Exp/Cntr=0.3,0.1

Type RM Length L Ch R = 1,12534,485,485,485
BEGIN DESCRIPTION:
Stream0652 32.0
END DESCRIPTION:
XS GIS Cut Line= 3
      1949118.81     13903087.77      1948325.00     13903275.00
      1947862.71     13903279.36
#Sta/Elev= 30
  4188.6 1673.01  4250.5 1667.95  4277.3 1664.01  4352.6 1656.02  4406.7 1648.92
  4446.8 1645.83  4502.3 1639.60  4556.6 1635.61  4582.3 1634.93  4658.7 1628.15
  4681.8 1626.13  4705.6 1625.71  4769.3 1624.18  4940.7 1625.60  4964.8 1624.89
  4974.6 1624.03  4985.0 1618.34  4997.0 1614.99  4997.3 1614.49  5001.6 1614.99
  5008.4 1619.84  5017.4 1623.84  5041.4 1628.13  5064.7 1628.88  5149.4 1630.01
  5161.4 1631.15  5176.4 1629.92  5188.4 1631.82  5380.4 1639.15  5466.5 1645.02
#Mann=11,-1,0
  4188.6   0.035       0  4250.5    0.07       0  4352.6   0.035       0
  4556.6     0.1       0  4658.7    0.07       0  4705.6   0.035       0
  4769.3    0.07       0  4964.8   0.035       0  4997.0   0.035       0
  5001.6   0.035       0  5064.7    0.07       0
Bank Sta=4997,5001.6
Exp/Cntr=0.3,0.1

Type RM Length L Ch R = 1,12049,451,451,451
BEGIN DESCRIPTION:
Stream0652 31.0
END DESCRIPTION:
XS GIS Cut Line= 3
      1948807.97     13902833.13      1948325.00     13902825.00
      1947885.24     13902918.84
#Sta/Elev= 30
  4517.0 1640.37  4614.2 1632.65  4626.2 1630.57  4652.1 1629.01  4750.6 1621.74
  4818.2 1618.63  4845.3 1619.01  4965.2 1619.59  4971.2 1619.14  4980.2 1615.67
  4989.2 1610.86  5002.0 1608.18  5002.3 1607.68  5006.6 1608.18  5007.4 1608.47
  5016.6 1610.62  5022.7 1613.33  5038.1 1616.79  5047.3 1617.83  5087.2 1619.84
  5108.6 1619.17  5124.0 1620.92  5163.8 1622.64  5178.6 1622.03  5217.7 1623.87
  5268.1 1626.89  5338.7 1632.70  5421.5 1642.19  5436.9 1642.55  5449.7 1644.50
#Mann=9,-1,0
  4517.0   0.035       0  4652.1    0.07       0  4750.6     0.1       0
  4845.3   0.035       0  5002.0   0.035       0  5006.6   0.035       0
  5007.4    0.07       0  5178.6   0.035       0  5217.7    0.07       0
Bank Sta=5002,5006.6
Exp/Cntr=0.3,0.1

Type RM Length L Ch R = 1,11598,458,458,458
BEGIN DESCRIPTION:
Stream0652 30.0
END DESCRIPTION:
XS GIS Cut Line= 3
      1948674.97     13902425.00      1948275.00     13902425.00
      1947862.80     13902533.84
#Sta/Elev= 30
  4599.7 1635.00  4668.9 1628.18  4698.2 1622.18  4743.9 1616.46  4866.9 1608.95
  4898.7 1608.70  4953.9 1609.72  4971.9 1609.26  4983.9 1607.46  4992.9 1604.43
  4999.6 1601.11  4999.9 1600.61  5004.3 1601.11  5014.5 1602.23  5033.0 1608.88
  5046.2 1612.31  5057.8 1614.07  5085.3 1615.60  5104.3 1616.22  5116.7 1617.44
  5129.2 1616.65  5135.4 1617.78  5161.0 1619.36  5203.6 1620.28  5284.3 1624.48
  5312.2 1625.19  5321.5 1626.26  5340.2 1626.56  5382.4 1629.20  5426.0 1631.31
#Mann=7,-1,0
  4599.7    0.07       0  4898.7   0.035       0  4999.6   0.035       0
  5004.3   0.035       0  5085.3    0.07       0  5161.0     0.1       0
  5382.4    0.07       0
Bank Sta=4999.6,5004.3
Exp/Cntr=0.3,0.1

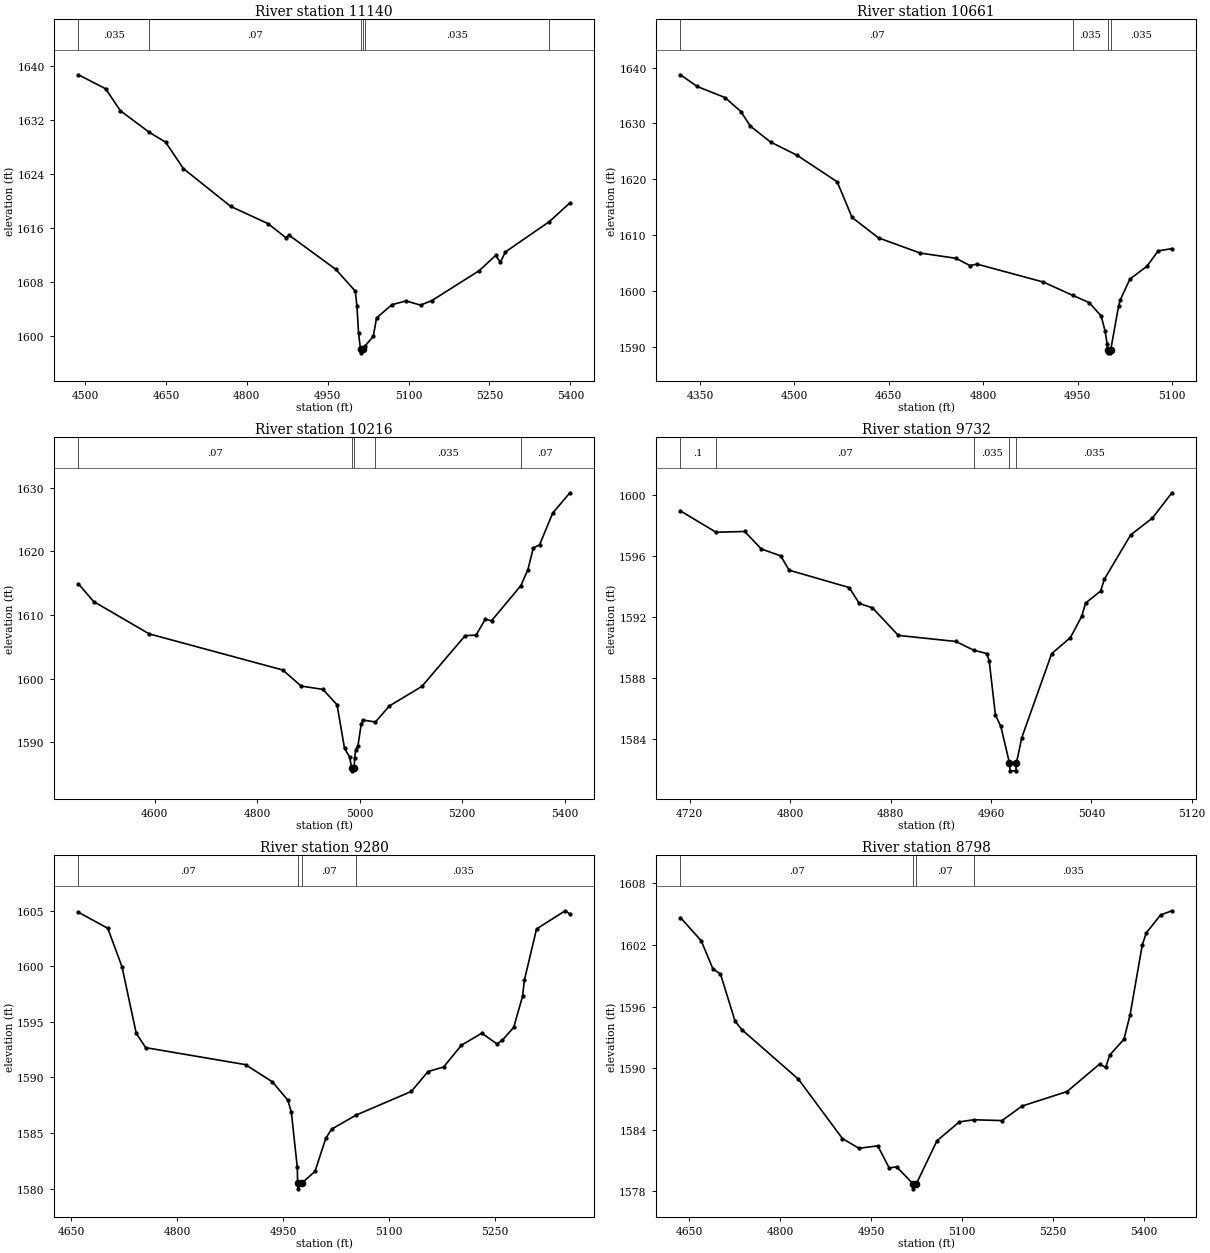
Type RM Length L Ch R = 1,11140,479,479,479
BEGIN DESCRIPTION:
Stream0652 29.0
END DESCRIPTION:
XS GIS Cut Line= 3
      1948933.20     13902032.74      1948425.00     13902025.00
      1948024.97     13902075.00
#Sta/Elev= 30
  4487.7 1638.73  4538.3 1636.65  4565.4 1633.41  4619.4 1630.19  4649.4 1628.75
  4682.4 1624.83  4770.1 1619.23  4839.1 1616.69  4872.3 1614.60  4878.1 1614.98
  4965.2 1609.89  5001.2 1606.67  5004.2 1604.45  5007.2 1600.41  5010.9 1598.04
  5011.2 1597.54  5015.7 1598.04  5018.4 1598.49  5034.5 1599.98  5040.5 1602.71
  5069.1 1604.67  5094.9 1605.23  5122.1 1604.61  5143.3 1605.29  5231.0 1609.72
  5261.2 1611.96  5270.3 1610.96  5279.3 1612.48  5360.7 1616.96  5399.1 1619.75
#Mann=6,-1,0
  4487.7   0.035       0  4619.4    0.07       0  5010.9    0.05       0
  5015.7    0.07       0  5018.4   0.035       0  5360.7    0.07       0
Bank Sta=5010.9,5015.7
Exp/Cntr=0.3,0.1

Type RM Length L Ch R = 1,10661,445,445,445
BEGIN DESCRIPTION:
Stream0652 28.0
END DESCRIPTION:
XS GIS Cut Line= 3
      1948871.76     13901838.27      1948225.00     13901625.00
      1948125.01     13901625.00
#Sta/Elev= 30
  4318.9 1638.73  4345.5 1636.64  4389.8 1634.64  4415.0 1632.14  4430.1 1629.52
  4462.4 1626.66  4504.2 1624.31  4568.0 1619.55  4591.7 1613.16  4633.7 1609.50
  4700.0 1606.78  4756.9 1605.84  4779.0 1604.54  4790.2 1604.80  4895.8 1601.58
  4942.4 1599.19  4968.5 1597.90  4987.5 1595.51  4993.8 1592.77  4997.0 1590.47
  4997.6 1589.40  4998.0 1588.90  5002.2 1588.90  5002.6 1589.40  5015.1 1597.21
  5018.1 1598.45  5033.1 1602.10  5060.4 1604.44  5078.1 1607.17  5099.9 1607.58
#Mann=4,-1,0
  4318.9    0.07       0  4942.4   0.035       0  4997.6   0.035       0
  5002.6   0.035       0
Bank Sta=4997.6,5002.6
Exp/Cntr=0.3,0.1

Type RM Length L Ch R = 1,10216,484,484,484
BEGIN DESCRIPTION:
Stream0652 27.0
END DESCRIPTION:
XS GIS Cut Line= 3
      1948786.95     13901442.56      1948275.00     13901225.00
      1947874.97     13901175.00
#Sta/Elev= 30
  4450.8 1614.90  4480.6 1612.12  4589.0 1607.03  4849.7 1601.35  4885.6 1598.82
  4928.0 1598.30  4955.6 1595.88  4970.3 1589.00  4980.1 1587.67  4984.1 1585.98
  4984.5 1585.48  4989.2 1585.98  4989.9 1587.55  4992.2 1588.82  4996.4 1589.39
  5002.9 1592.87  5006.2 1593.47  5030.6 1593.17  5057.7 1595.69  5121.3 1598.77
  5205.8 1606.76  5227.0 1606.84  5244.9 1609.32  5257.2 1609.10  5314.5 1614.63
  5328.2 1617.13  5338.8 1620.58  5350.9 1621.03  5376.6 1626.04  5410.2 1629.24
#Mann=5,-1,0
  4450.8    0.07       0  4984.1    0.05       0  4989.2    0.07       0
  5030.6   0.035       0  5314.5    0.07       0
Bank Sta=4984.1,4989.2
Exp/Cntr=0.3,0.1

Type RM Length L Ch R = 1,9732,452,452,452
BEGIN DESCRIPTION:
Stream0652 26.0
END DESCRIPTION:
XS GIS Cut Line= 3
      1948425.02     13900925.01      1948175.00     13900775.00
      1948074.97     13900775.00
#Sta/Elev= 30
  4712.6 1598.95  4741.0 1597.55  4763.8 1597.60  4777.1 1596.45  4792.5 1596.00
  4799.2 1595.06  4847.1 1593.92  4855.1 1592.88  4865.6 1592.59  4886.2 1590.78
  4932.1 1590.38  4946.2 1589.81  4956.6 1589.59  4958.6 1589.13  4963.6 1585.55
  4967.9 1584.81  4974.8 1582.39  4975.3 1581.89  4979.9 1581.89  4980.3 1582.39
  4984.6 1584.07  5008.4 1589.58  5023.4 1590.64  5032.4 1592.04  5035.4 1592.90
  5047.4 1593.69  5050.4 1594.47  5071.4 1597.38  5088.7 1598.48  5104.2 1600.14
#Mann=5,-1,0
  4712.6     0.1       0  4741.0    0.07       0  4946.2   0.035       0
  4974.8   0.035       0  4980.3   0.035       0
Bank Sta=4974.8,4980.3
Exp/Cntr=0.3,0.1

Type RM Length L Ch R = 1,9280,482,482,482
BEGIN DESCRIPTION:
Stream0652 25.0
END DESCRIPTION:
XS GIS Cut Line= 3
      1948624.98     13900524.99      1948325.00     13900375.00
      1948025.03     13900175.02
#Sta/Elev= 30
  4660.4 1604.85  4702.0 1603.40  4722.1 1599.94  4742.2 1593.97  4755.6 1592.67
  4897.0 1591.14  4935.1 1589.59  4956.9 1587.95  4961.9 1586.86  4970.3 1581.89
  4970.8 1580.47  4971.3 1579.97  4976.4 1580.47  4995.4 1581.54  5010.6 1584.51
  5018.9 1585.34  5053.8 1586.61  5131.7 1588.73  5155.5 1590.52  5177.5 1590.93
  5202.7 1592.89  5231.6 1593.97  5252.9 1593.01  5260.4 1593.32  5276.7 1594.49
  5289.3 1597.30  5291.8 1598.73  5309.1 1603.35  5349.7 1604.98  5356.3 1604.69
#Mann=4,-1,0
  4660.4    0.07       0  4970.8    0.05       0  4976.4    0.07       0
  5053.8   0.035       0
Bank Sta=4970.8,4976.4
Exp/Cntr=0.3,0.1

Type RM Length L Ch R = 1,8798,440,440,440
BEGIN DESCRIPTION:
Stream0652 24.0
END DESCRIPTION:
XS GIS Cut Line= 3
      1948775.02     13900025.01      1948425.00     13899925.00
      1948025.04     13900124.98
#Sta/Elev= 30
  4635.1 1604.68  4669.4 1602.42  4688.9 1599.66  4701.2 1599.18  4725.3 1594.59
  4736.2 1593.77  4829.8 1588.94  4902.5 1583.15  4929.7 1582.20  4960.9 1582.44
  4979.6 1580.29  4992.1 1580.39  5018.9 1578.75  5019.3 1578.25  5024.6 1578.75
  5058.6 1582.94  5095.5 1584.77  5119.1 1584.98  5165.9 1584.90  5198.8 1586.31
  5273.3 1587.73  5326.9 1590.40  5337.0 1590.08  5343.7 1591.28  5367.2 1592.83
  5377.2 1595.18  5397.4 1602.01  5404.1 1603.19  5427.6 1604.93  5446.3 1605.34
#Mann=4,-1,0
  4635.1    0.07       0  5018.9    0.05       0  5024.6    0.07       0
  5119.1   0.035       0
Bank Sta=5018.9,5024.6
Exp/Cntr=0.3,0.1