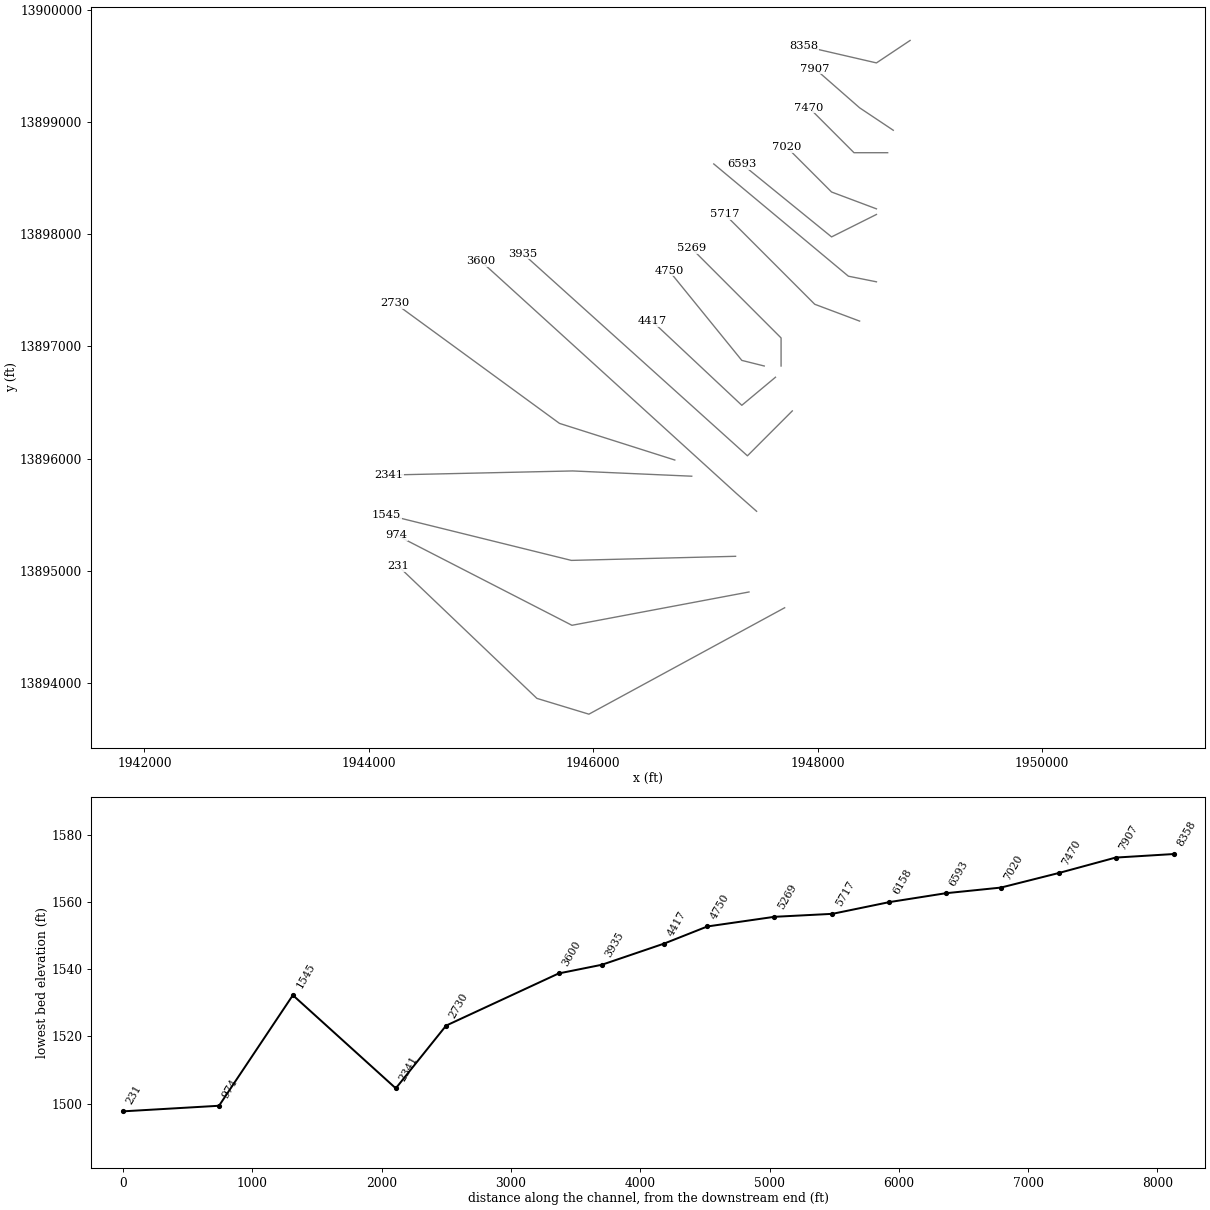
HEC-RAS study Stream0652.prj: Stream0652 Base Level Engineering

--- Stream0652.g01 (geometry) --- (continued)

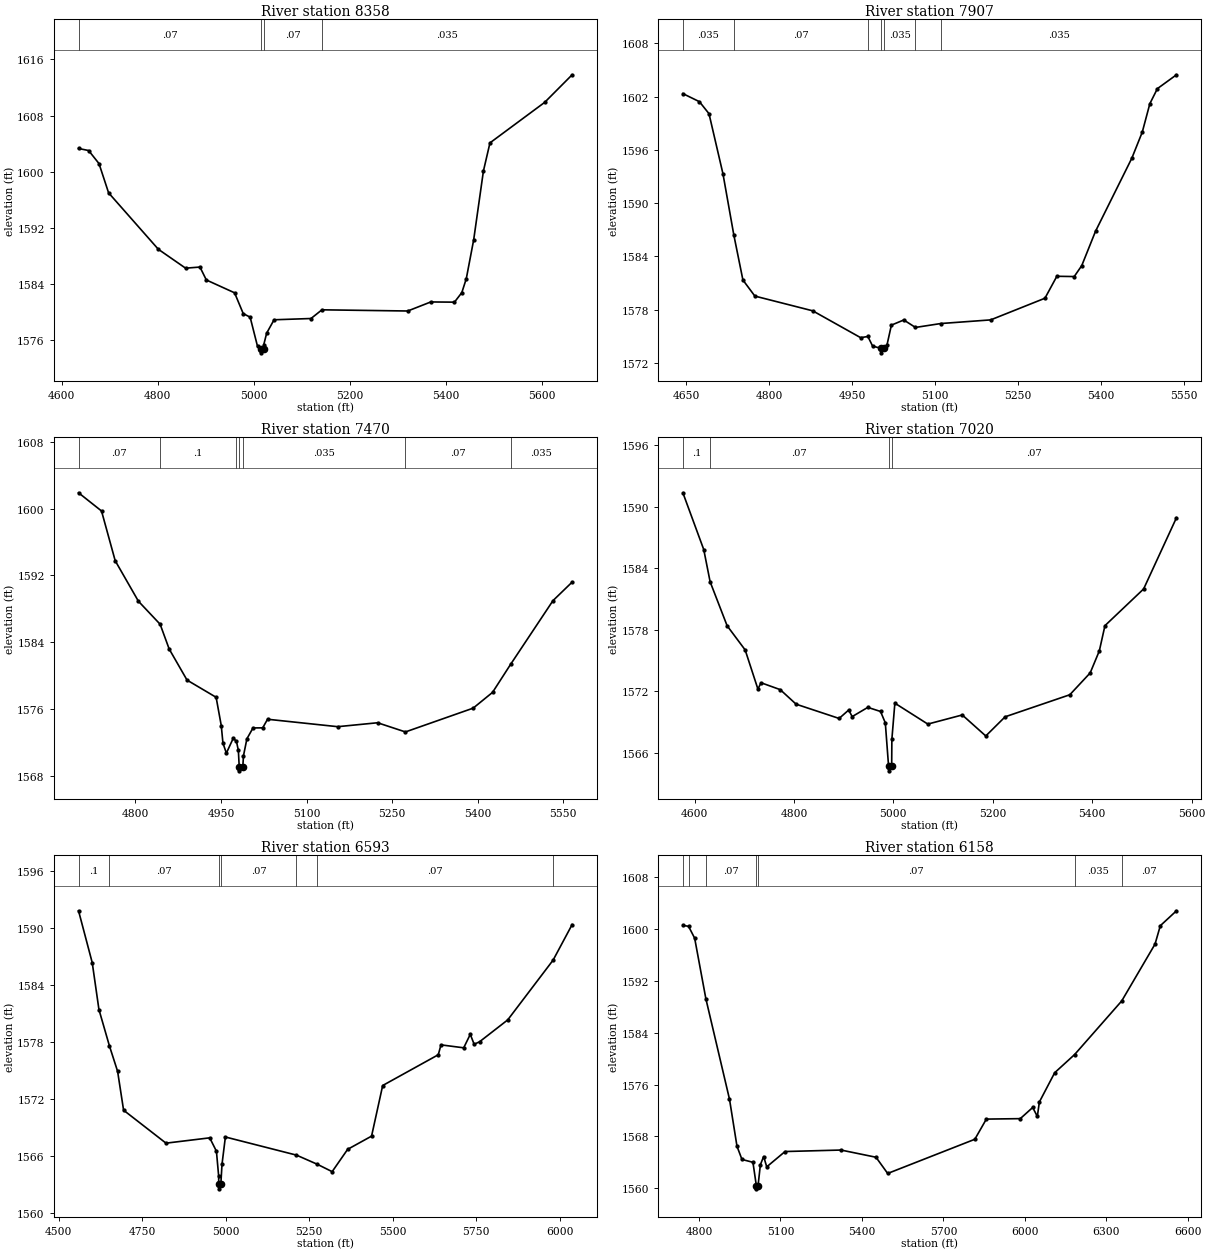
Type RM Length L Ch R = 1,8358,451,451,451
BEGIN DESCRIPTION:
Stream0652 23.0
END DESCRIPTION:
XS GIS Cut Line= 3
      1948825.04     13899725.03      1948525.00     13899525.00
      1947874.99     13899675.00
#Sta/Elev= 30
  4635.2 1603.31  4656.2 1603.02  4677.8 1601.16  4697.8 1596.99  4801.4 1588.95
  4858.1 1586.26  4888.0 1586.42  4901.3 1584.58  4960.1 1582.75  4978.1 1579.79
  4992.5 1579.28  5007.9 1575.11  5014.8 1574.70  5015.2 1574.20  5020.5 1574.70
  5020.7 1575.32  5026.9 1577.01  5042.3 1578.91  5119.2 1579.09  5142.0 1580.33
  5320.6 1580.16  5368.6 1581.45  5417.9 1581.42  5433.2 1582.78  5442.5 1584.76
  5457.9 1590.30  5478.2 1600.11  5491.8 1604.11  5605.7 1609.88  5662.9 1613.81
#Mann=4,-1,0
  4635.2    0.07       0  5014.8    0.05       0  5020.5    0.07       0
  5142.0   0.035       0
Bank Sta=5014.8,5020.5
Exp/Cntr=0.3,0.1

Type RM Length L Ch R = 1,7907,437,437,437
BEGIN DESCRIPTION:
Stream0652 22.0
END DESCRIPTION:
XS GIS Cut Line= 3
      1948674.98     13898925.01      1948375.00     13899125.00
      1947975.03     13899474.97
#Sta/Elev= 30
  4644.1 1602.33  4674.0 1601.42  4691.3 1600.07  4716.5 1593.31  4736.2 1586.40
  4752.6 1581.34  4774.2 1579.53  4878.8 1577.87  4965.3 1574.85  4978.4 1574.98
  4986.9 1573.91  5001.9 1573.64  5002.4 1573.14  5008.2 1573.64  5013.0 1574.04
  5020.9 1576.26  5043.3 1576.84  5064.4 1576.00  5110.2 1576.44  5200.3 1576.85
  5298.4 1579.29  5319.9 1581.76  5351.3 1581.73  5364.9 1582.96  5389.8 1586.83
  5455.5 1595.07  5474.3 1598.00  5488.0 1601.20  5501.6 1602.89  5536.1 1604.45
#Mann=7,-1,0
  4644.1   0.035       0  4736.2    0.07       0  4978.4   0.035       0
  5001.9   0.035       0  5008.2   0.035       0  5064.4    0.07       0
  5110.2   0.035       0
Bank Sta=5001.9,5008.2
Exp/Cntr=0.3,0.1

Type RM Length L Ch R = 1,7470,450,450,450
BEGIN DESCRIPTION:
Stream0652 21.0
END DESCRIPTION:
XS GIS Cut Line= 3
      1948624.99     13898725.00      1948325.00     13898725.00
      1947924.98     13899125.02
#Sta/Elev= 30
  4700.1 1601.89  4740.4 1599.71  4764.4 1593.75  4805.1 1588.90  4843.2 1586.14
  4859.1 1583.17  4890.4 1579.45  4941.4 1577.39  4950.4 1574.01  4953.4 1571.89
  4959.4 1570.70  4971.4 1572.48  4977.0 1572.12  4980.4 1571.04  4981.9 1569.08
  4982.4 1568.58  4988.2 1569.08  4989.4 1570.39  4995.4 1572.42  5006.1 1573.72
  5023.1 1573.73  5031.6 1574.76  5154.6 1573.87  5224.6 1574.34  5273.4 1573.24
  5392.2 1576.09  5426.2 1577.98  5457.9 1581.34  5532.2 1588.97  5565.8 1591.19
#Mann=7,-1,0
  4700.1    0.07       0  4843.2     0.1       0  4977.0   0.035       0
  4981.9   0.035       0  4988.2   0.035       0  5273.4    0.07       0
  5457.9   0.035       0
Bank Sta=4981.9,4988.2
Exp/Cntr=0.3,0.1

Type RM Length L Ch R = 1,7020,427,427,427
BEGIN DESCRIPTION:
Stream0652 20.0
END DESCRIPTION:
XS GIS Cut Line= 3
      1948525.01     13898225.00      1948125.00     13898375.00
      1947725.00     13898775.00
#Sta/Elev= 30
  4576.6 1591.35  4618.6 1585.81  4631.4 1582.67  4665.6 1578.38  4701.9 1576.02
  4727.5 1572.21  4733.9 1572.82  4772.4 1572.15  4804.4 1570.73  4890.9 1569.34
  4910.1 1570.16  4917.2 1569.52  4948.6 1570.42  4974.2 1570.02  4983.8 1568.91
  4990.3 1564.73  4990.8 1564.23  4996.6 1564.73  4997.0 1567.31  5003.0 1570.83
  5069.3 1568.79  5138.6 1569.68  5185.9 1567.63  5224.8 1569.50  5354.9 1571.65
  5395.9 1573.78  5414.3 1575.93  5425.6 1578.39  5503.4 1581.97  5569.5 1588.92
#Mann=4,-1,0
  4576.6     0.1       0  4631.4    0.07       0  4990.3    0.05       0
  4996.6    0.07       0
Bank Sta=4990.3,4996.6
Exp/Cntr=0.3,0.1

Type RM Length L Ch R = 1,6593,435,435,435
BEGIN DESCRIPTION:
Stream0652 19.0
END DESCRIPTION:
XS GIS Cut Line= 3
      1948525.01     13898175.00      1948125.00     13897975.00
      1947325.00     13898625.00
#Sta/Elev= 30
  4559.7 1591.83  4600.7 1586.37  4620.8 1581.43  4652.3 1577.59  4676.7 1574.92
  4694.6 1570.83  4821.6 1567.36  4952.5 1567.92  4972.6 1566.51  4979.3 1563.88
  4979.4 1563.05  4979.9 1562.55  4985.8 1563.05  4989.3 1565.14  4999.4 1568.01
  5212.3 1566.10  5274.4 1565.14  5319.1 1564.36  5365.5 1566.71  5437.1 1568.10
  5470.4 1573.43  5636.9 1576.67  5645.0 1577.71  5713.0 1577.40  5732.7 1578.82
  5744.3 1577.77  5760.6 1578.04  5844.8 1580.34  5980.8 1586.64  6037.7 1590.38
#Mann=7,-1,0
  4559.7     0.1       0  4652.3    0.07       0  4979.4    0.05       0
  4985.8    0.07       0  5212.3   0.035       0  5274.4    0.07       0
  5980.8   0.035       0
Bank Sta=4979.4,4985.8
Exp/Cntr=0.3,0.1

Type RM Length L Ch R = 1,6158,441,441,441
BEGIN DESCRIPTION:
Stream0652 18.0
END DESCRIPTION:
XS GIS Cut Line= 3
      1948525.02     13897575.00      1948275.00     13897625.00
      1947075.02     13898624.98
#Sta/Elev= 30
  4740.7 1600.54  4761.7 1600.38  4784.1 1598.55  4825.4 1589.21  4912.3 1573.74
  4939.9 1566.48  4958.2 1564.45  4998.6 1564.01  5011.1 1560.42  5011.6 1559.92
  5017.5 1560.42  5026.0 1563.64  5038.0 1564.90  5049.4 1563.31  5116.8 1565.67
  5322.8 1565.90  5451.6 1564.79  5494.6 1562.29  5815.4 1567.56  5857.8 1570.67
  5982.7 1570.74  6028.4 1572.46  6045.5 1571.08  6053.0 1573.31  6109.4 1577.82
  6182.7 1580.62  6356.1 1588.88  6478.7 1597.64  6498.2 1600.48  6557.7 1602.78
#Mann=7,-1,0
  4740.7    0.07       0  4761.7     0.1       0  4825.4    0.07       0
  5011.1    0.05       0  5017.5    0.07       0  6182.7   0.035       0
  6356.1    0.07       0
Bank Sta=5011.1,5017.5
Exp/Cntr=0.3,0.1

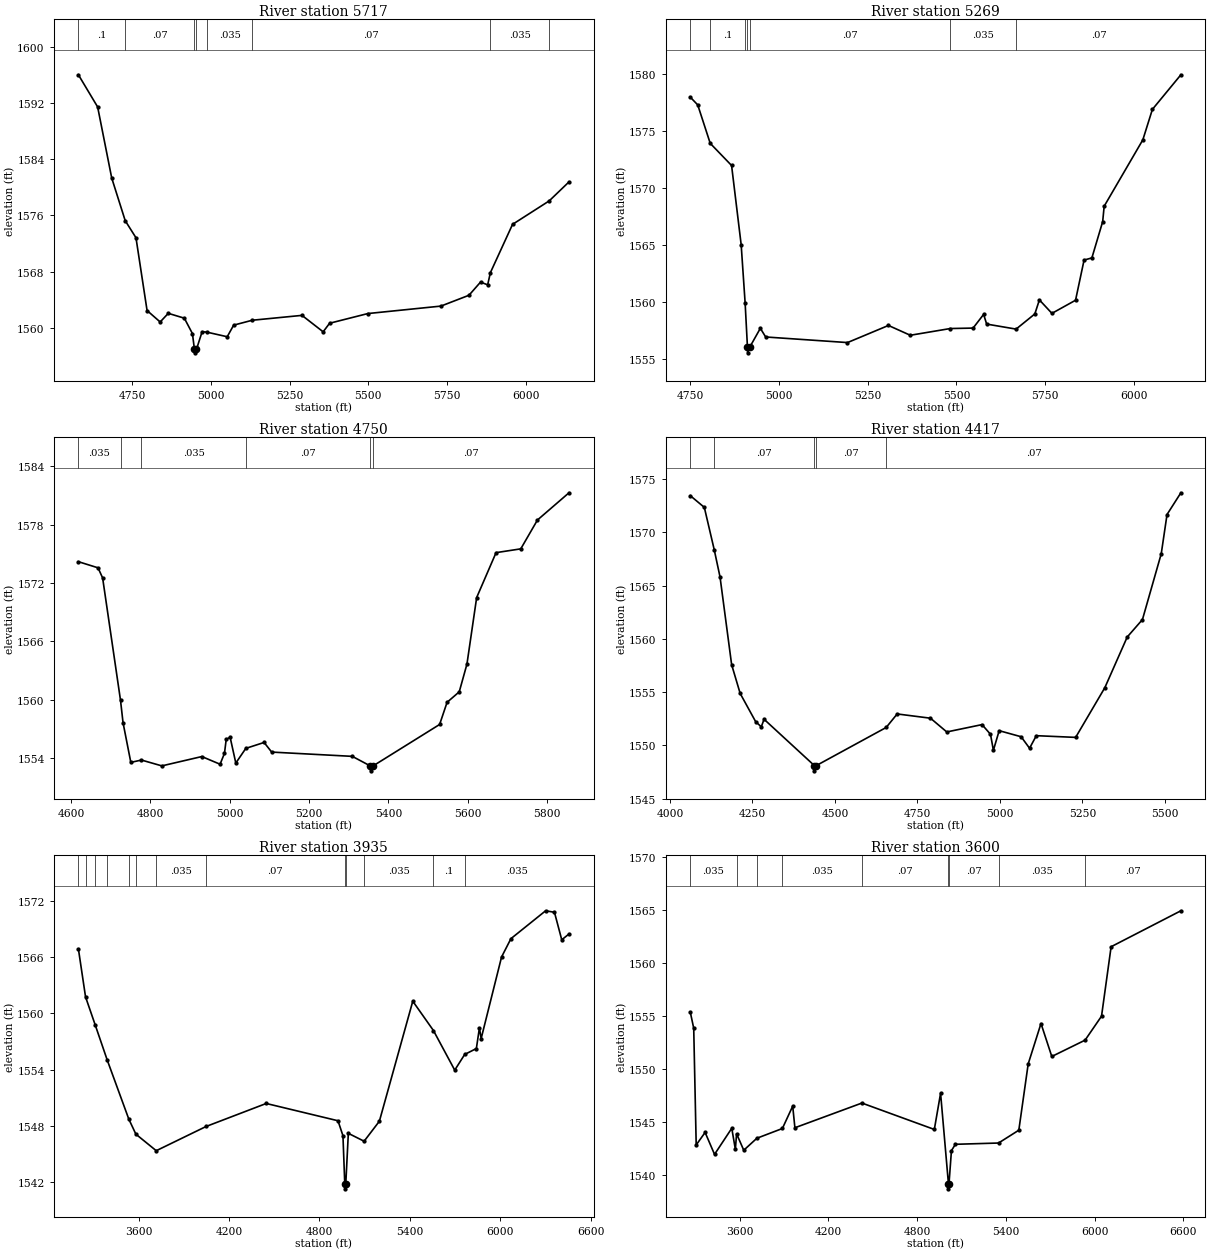
Type RM Length L Ch R = 1,5717,448,448,448
BEGIN DESCRIPTION:
Stream0652 17.0
END DESCRIPTION:
XS GIS Cut Line= 3
      1948374.99     13897225.01      1947975.00     13897375.00
      1947174.97     13898175.03
#Sta/Elev= 30
  4579.2 1595.99  4640.4 1591.41  4685.1 1581.30  4728.0 1575.23  4762.2 1572.80
  4797.4 1562.45  4839.0 1560.82  4864.8 1562.05  4915.8 1561.36  4941.5 1559.17
  4947.9 1556.93  4948.4 1556.43  4954.4 1556.93  4972.2 1559.43  4986.9 1559.38
  5052.0 1558.72  5072.5 1560.37  5131.8 1561.07  5289.6 1561.76  5356.8 1559.42
  5377.3 1560.64  5498.9 1562.02  5730.9 1563.08  5820.0 1564.62  5856.7 1566.49
  5879.4 1566.11  5888.1 1567.84  5958.5 1574.71  6074.7 1578.04  6137.8 1580.75
#Mann=8,-1,0
  4579.2     0.1       0  4728.0    0.07       0  4947.9   0.035       0
  4954.4    0.07       0  4986.9   0.035       0  5131.8    0.07       0
  5888.1   0.035       0  6074.7    0.07       0
Bank Sta=4947.9,4954.4
Exp/Cntr=0.3,0.1

Type RM Length L Ch R = 1,5269,519,519,519
BEGIN DESCRIPTION:
Stream0652 16.0
END DESCRIPTION:
XS GIS Cut Line= 3
      1947675.00     13896824.98      1947675.00     13897075.00
      1946874.99     13897875.01
#Sta/Elev= 30
  4750.5 1577.96  4771.5 1577.28  4806.7 1573.91  4866.8 1571.97  4893.8 1565.03
  4905.0 1559.90  4911.5 1556.05  4912.0 1555.55  4918.0 1556.05  4947.8 1557.70
  4962.8 1556.94  5193.2 1556.45  5308.5 1557.95  5370.0 1557.09  5482.6 1557.68
  5546.8 1557.72  5576.5 1558.92  5585.0 1558.07  5667.9 1557.63  5720.7 1558.96
  5733.5 1560.19  5768.8 1559.01  5835.3 1560.16  5859.3 1563.68  5881.3 1563.87
  5911.7 1567.05  5915.9 1568.40  6024.8 1574.22  6051.7 1576.89  6131.9 1579.92
#Mann=7,-1,0
  4750.5    0.07       0  4806.7     0.1       0  4905.0    0.07       0
  4911.5    0.05       0  4918.0    0.07       0  5482.6   0.035       0
  5667.9    0.07       0
Bank Sta=4911.5,4918
Exp/Cntr=0.3,0.1

Type RM Length L Ch R = 1,4750,333,333,333
BEGIN DESCRIPTION:
Stream0652 15.0
END DESCRIPTION:
XS GIS Cut Line= 3
      1947524.99     13896825.00      1947325.00     13896875.00
      1946675.01     13897674.99
#Sta/Elev= 30
  4618.4 1574.20  4667.9 1573.57  4679.5 1572.53  4724.6 1559.94  4731.0 1557.63
  4750.6 1553.55  4777.4 1553.79  4828.8 1553.19  4929.6 1554.15  4975.6 1553.36
  4986.7 1554.48  4991.1 1555.92  5001.0 1556.13  5015.3 1553.48  5040.5 1554.99
  5086.6 1555.60  5105.7 1554.61  5309.0 1554.17  5354.6 1553.18  5355.1 1552.68
  5361.1 1553.18  5529.1 1557.45  5547.9 1559.73  5578.6 1560.81  5598.0 1563.66
  5622.5 1570.51  5671.4 1575.13  5733.7 1575.52  5775.8 1578.49  5855.3 1581.29
#Mann=6,-1,0
  4618.4   0.035       0  4724.6    0.07       0  4777.4   0.035       0
  5040.5    0.07       0  5354.6   0.035       0  5361.1    0.07       0
Bank Sta=5354.6,5361.1
Exp/Cntr=0.3,0.1

Type RM Length L Ch R = 1,4417,482,482,482
BEGIN DESCRIPTION:
Stream0652 14.0
END DESCRIPTION:
XS GIS Cut Line= 3
      1947625.02     13896725.02      1947325.00     13896475.00
      1946525.02     13897224.98
#Sta/Elev= 30
  4061.5 1573.44  4104.1 1572.34  4134.0 1568.38  4151.7 1565.81  4186.9 1557.57
  4212.8 1554.87  4259.6 1552.23  4276.7 1551.74  4285.2 1552.45  4437.4 1548.11
  4437.9 1547.61  4443.9 1548.11  4655.3 1551.68  4688.7 1552.95  4789.6 1552.55
  4839.0 1551.26  4945.9 1551.95  4971.5 1551.04  4980.3 1549.54  4997.8 1551.38
  5064.4 1550.81  5089.9 1549.73  5110.4 1550.91  5229.6 1550.75  5318.0 1555.41
  5385.9 1560.17  5432.1 1561.81  5489.1 1567.99  5506.6 1571.67  5548.6 1573.71
#Mann=5,-1,0
  4061.5   0.035       0  4134.0    0.07       0  4437.4    0.05       0
  4443.9    0.07       0  4655.3    0.07       0
Bank Sta=4437.4,4443.9
Exp/Cntr=0.3,0.1

Type RM Length L Ch R = 1,3935,335,335,335
BEGIN DESCRIPTION:
Stream0652 13.0
END DESCRIPTION:
XS GIS Cut Line= 3
      1947774.98     13896424.98      1947375.00     13896025.00
      1945374.99     13897825.01
#Sta/Elev= 30
  3200.1 1566.87  3247.6 1561.75  3311.6 1558.77  3391.2 1555.04  3534.9 1548.73
  3581.8 1547.13  3716.9 1545.37  4047.7 1547.95  4446.9 1550.40  4923.2 1548.56
  4956.1 1546.97  4968.3 1541.81  4968.8 1541.31  4974.8 1541.81  4991.9 1547.22
  5096.6 1546.38  5197.9 1548.51  5419.6 1561.29  5556.6 1558.17  5698.1 1553.95
  5764.1 1555.62  5841.6 1556.25  5861.9 1558.44  5873.4 1557.31  6008.9 1566.00
  6071.0 1567.95  6301.4 1570.92  6360.0 1570.76  6408.4 1567.83  6456.5 1568.45
#Mann=13,-1,0
  3200.1     0.1       0  3247.6    0.07       0  3311.6     0.1       0
  3391.2    0.07       0  3534.9   0.035       0  3581.8    0.07       0
  3716.9   0.035       0  4047.7    0.07       0  4968.3    0.05       0
  4974.8    0.07       0  5096.6   0.035       0  5556.6     0.1       0
  5764.1   0.035       0
Bank Sta=4968.3,4974.8
Exp/Cntr=0.3,0.1

Type RM Length L Ch R = 1,3600,870,870,870
BEGIN DESCRIPTION:
Stream0652 12.0
END DESCRIPTION:
XS GIS Cut Line= 3
      1947456.76     13895530.85      1947279.71     13895687.07
      1944998.46     13897759.99
#Sta/Elev= 30
  3265.4 1555.39  3288.7 1553.87  3305.5 1542.86  3365.8 1544.04  3429.5 1541.97
  3546.1 1544.43  3570.4 1542.45  3578.7 1543.91  3627.2 1542.36  3715.8 1543.49
  3888.4 1544.41  3958.3 1546.52  3973.1 1544.48  4426.3 1546.81  4916.2 1544.32
  4958.5 1547.73  5011.5 1539.22  5011.7 1538.72  5015.5 1539.22  5031.9 1542.32
  5058.7 1542.92  5350.5 1543.04  5487.7 1544.25  5551.1 1550.50  5637.7 1554.31
  5710.7 1551.20  5935.9 1552.74  6047.1 1555.00  6112.0 1561.55  6583.9 1564.94
#Mann=9,-1,0
  3265.4   0.035       0  3578.7   0.063       0  3715.8    0.07       0
  3888.4   0.035       0  4426.3    0.07       0  5011.5    0.05       0
  5015.5    0.07       0  5350.5   0.035       0  5935.9    0.07       0
Bank Sta=5011.5,5015.5
Exp/Cntr=0.3,0.1

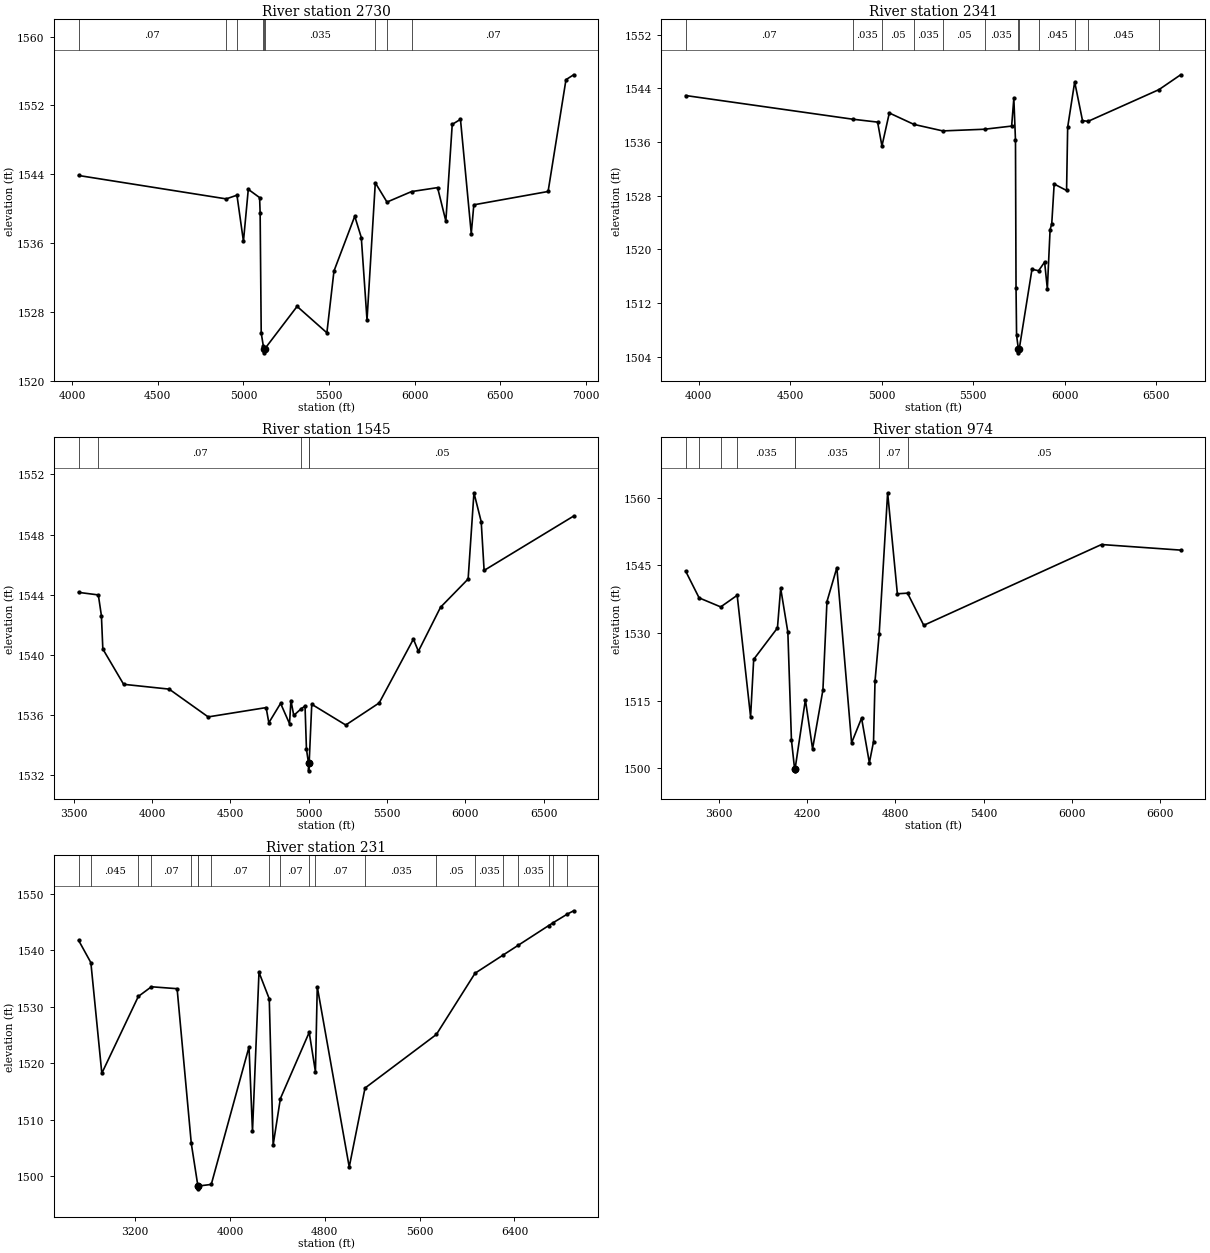
Type RM Length L Ch R = 1,2730,389,389,389
BEGIN DESCRIPTION:
Stream0652 11.1
END DESCRIPTION:
XS GIS Cut Line= 3
      1946727.60     13895987.43      1945699.85     13896313.81
      1944234.55     13897383.27
#Sta/Elev= 30
  4037.1 1543.85  4899.5 1541.13  4962.3 1541.56  5000.2 1536.20  5028.5 1542.24
  5094.6 1541.28  5097.7 1539.52  5104.0 1525.54  5116.4 1524.02  5122.3 1523.73
  5122.5 1523.23  5126.3 1523.73  5313.7 1528.63  5487.7 1525.56  5529.1 1532.74
  5650.5 1539.11  5688.8 1536.64  5722.2 1527.05  5770.6 1543.00  5838.9 1540.76
  5982.3 1541.98  6134.5 1542.44  6182.8 1538.55  6220.1 1549.79  6268.2 1550.38
  6331.3 1537.09  6346.2 1540.44  6780.2 1541.99  6884.7 1554.99  6929.5 1555.56
#Mann=9,-1,0
  4037.1    0.07       0  4899.5   0.035       0  4962.3    0.07       0
  5116.4   0.035       0  5122.3    0.05       0  5126.3   0.035       0
  5770.6    0.07       0  5838.9   0.045       0  5982.3    0.07       0
Bank Sta=5122.3,5126.3
Exp/Cntr=0.3,0.1

Type RM Length L Ch R = 1,2341,796,796,796
BEGIN DESCRIPTION:
Stream0652 11.0
END DESCRIPTION:
XS GIS Cut Line= 3
      1946878.63     13895843.32      1945816.17     13895890.20
      1944175.57     13895853.74
#Sta/Elev= 30
  3928.4 1542.92  4842.4 1539.39  4977.3 1538.96  5000.9 1535.40  5041.2 1540.32
  5175.7 1538.62  5333.3 1537.65  5561.3 1537.90  5709.5 1538.37  5721.5 1542.50
  5730.5 1536.25  5733.5 1514.27  5736.5 1507.21  5746.6 1505.10  5746.9 1504.60
  5750.6 1505.10  5820.6 1517.04  5856.9 1516.83  5889.6 1518.12  5904.6 1514.13
  5919.6 1522.96  5928.6 1523.80  5941.8 1529.74  6009.6 1528.78  6015.6 1538.20
  6053.9 1544.95  6096.6 1539.19  6126.6 1539.07  6514.4 1543.80  6632.9 1546.01
#Mann=12,-1,0
  3928.4    0.07       0  4842.4   0.035       0  5000.9    0.05       0
  5175.7   0.035       0  5333.3    0.05       0  5561.3   0.035       0
  5746.6   0.035       0  5750.6   0.035       0  5856.9   0.045       0
  6053.9    0.05       0  6126.6   0.045       0  6514.4    0.07       0
Bank Sta=5746.6,5750.6
Exp/Cntr=0.3,0.1

Type RM Length L Ch R = 1,1545,571,571,571
BEGIN DESCRIPTION:
Stream0652 10.1
END DESCRIPTION:
XS GIS Cut Line= 3
      1947269.31     13895129.78      1945805.75     13895093.32
      1944159.96     13895499.56
#Sta/Elev= 30
  3531.4 1544.15  3657.3 1543.98  3677.0 1542.59  3686.0 1540.38  3818.7 1538.03
  4109.2 1537.71  4358.2 1535.86  4728.1 1536.48  4745.4 1535.47  4820.4 1536.76
  4877.4 1535.41  4886.4 1536.95  4904.4 1535.96  4952.7 1536.41  4976.4 1536.58
  4985.4 1533.72  4998.6 1532.77  4998.8 1532.27  5002.6 1532.77  5019.3 1536.70
  5236.2 1535.32  5449.6 1536.79  5668.0 1541.04  5699.8 1540.23  5841.1 1543.16
  6017.2 1545.04  6054.3 1550.78  6100.6 1548.86  6119.2 1545.61  6690.6 1549.23
#Mann=5,-1,0
  3531.4   0.035       0  3657.3    0.07       0  4952.7    0.05       0
  4998.6    0.05       0  5002.6    0.05       0
Bank Sta=4998.6,5002.6
Exp/Cntr=0.3,0.1

Type RM Length L Ch R = 1,974,743,743,743
BEGIN DESCRIPTION:
Stream0652 3.0
END DESCRIPTION:
XS GIS Cut Line= 3
      1947389.07     13894812.07      1945810.96     13894515.20
      1944248.50     13895317.26
#Sta/Elev= 30
  3375.7 1543.70  3467.4 1537.76  3614.0 1535.76  3725.9 1538.33  3816.9 1511.40
  3838.0 1524.13  3999.3 1531.09  4021.2 1539.91  4070.0 1530.17  4094.4 1506.25
  4115.5 1499.92  4115.8 1499.42  4119.5 1499.92  4189.1 1515.18  4237.9 1504.29
  4308.1 1517.33  4335.6 1536.94  4402.8 1544.46  4502.9 1505.63  4570.7 1511.11
  4623.7 1501.21  4651.9 1505.89  4662.0 1519.31  4690.2 1529.73  4747.7 1561.06
  4813.8 1538.67  4882.9 1538.81  4993.0 1531.68  6200.2 1549.59  6737.8 1548.35
#Mann=8,-1,0
  3375.7    0.07       0  3467.4   0.035       0  3614.0    0.07       0
  3725.9   0.035       0  4115.5    0.05       0  4119.5   0.035       0
  4690.2    0.07       0  4882.9    0.05       0
Bank Sta=4115.5,4119.5
Exp/Cntr=0.3,0.1

Type RM Length L Ch R = 1,231,0,0,0
BEGIN DESCRIPTION:
Stream0652 2.0
END DESCRIPTION:
XS GIS Cut Line= 4
      1947706.79     13894671.44      1945962.00     13893723.53
      1945498.46     13893864.16      1944264.08     13895041.24
#Sta/Elev= 30
  2723.3 1541.77  2826.7 1537.83  2919.1 1518.23  3227.1 1531.84  3337.3 1533.55
  3554.2 1533.21  3673.8 1505.80  3729.5 1498.26  3729.8 1497.76  3733.5 1498.26
  3842.3 1498.54  4160.7 1522.90  4190.0 1507.93  4244.8 1536.11  4331.4 1531.42
  4364.2 1505.51  4425.2 1513.74  4668.5 1525.48  4721.0 1518.49  4736.4 1533.55
  5006.0 1501.62  5139.1 1515.61  5741.0 1525.10  6067.4 1535.95  6303.3 1539.16
  6430.8 1540.89  6689.3 1544.40  6724.7 1544.88  6844.7 1546.41  6899.0 1547.01
#Mann=20,-1,0
  2723.3   0.035       0  2826.7   0.045       0  3227.1   0.035       0
  3337.3    0.07       0  3673.8   0.035       0  3729.5    0.05       0
  3733.5   0.035       0  3842.3    0.07       0  4331.4   0.035       0
  4425.2    0.07       0  4668.5   0.035       0  4721.0    0.07       0
  5139.1   0.035       0  5741.0    0.05       0  6067.4   0.035       0
  6303.3    0.05       0  6430.8   0.035       0  6689.3    0.05       0
  6724.7   0.035       0  6844.7    0.05       0
Bank Sta=3729.5,3733.5
Exp/Cntr=0.3,0.1

Chan Stop Cuts=-1