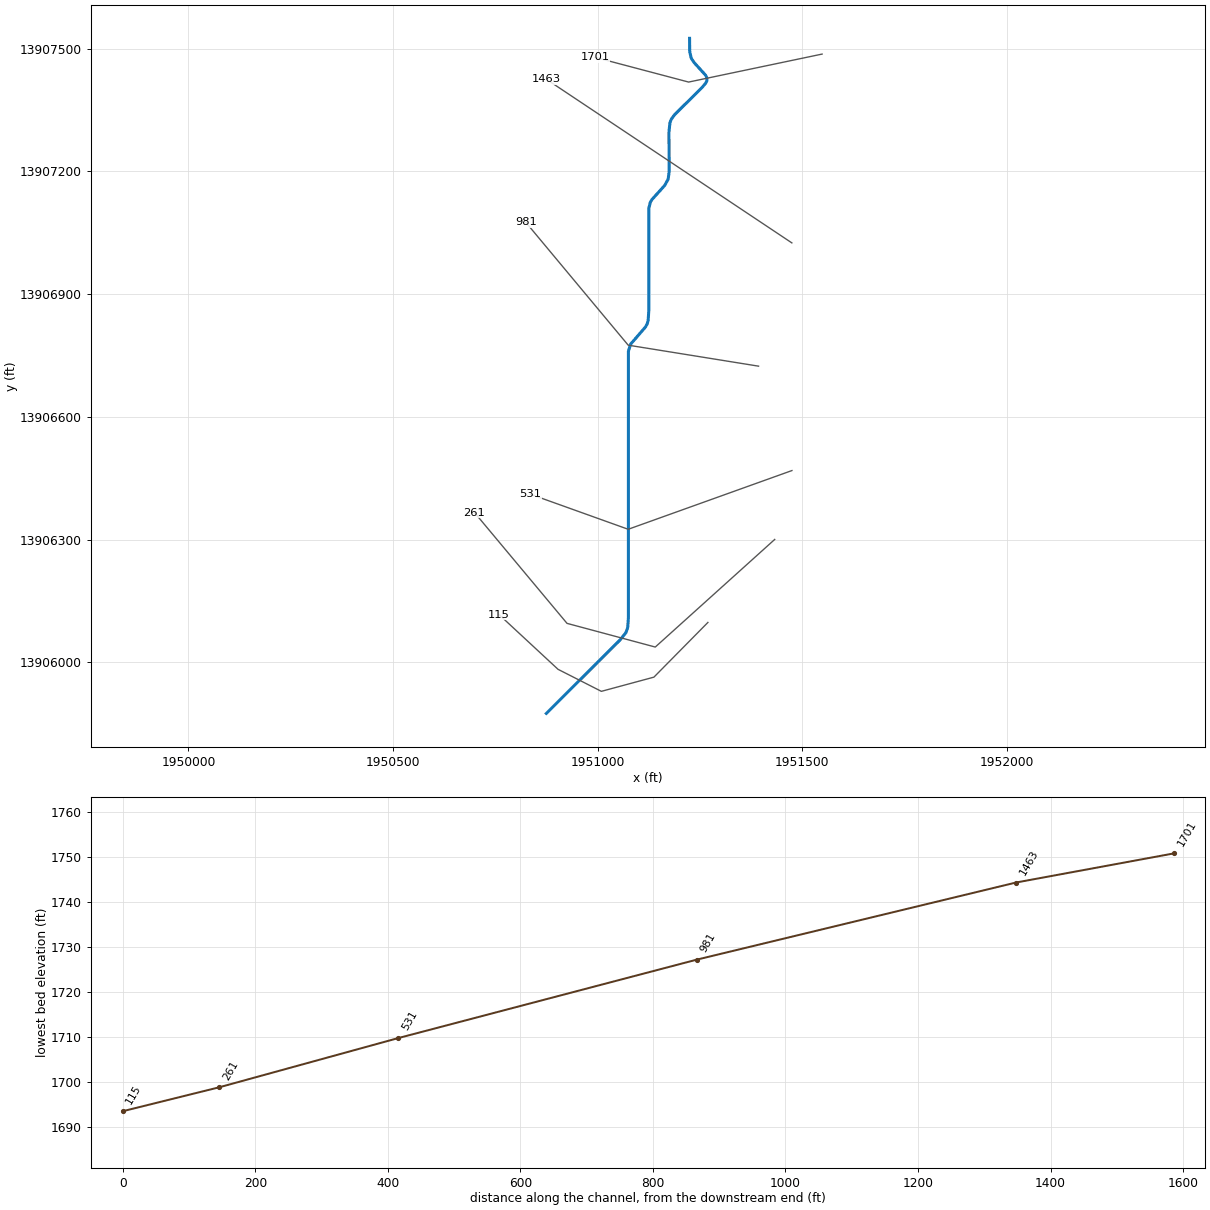
--- Stream0653.prj (project) ---

Proj Title=Stream0653 Base Level Engineering
Current Plan=p01
Default Exp/Contr=0.3,0.1
English Units
Geom File=g01
Flow File=f01
Plan File=p01
BEGIN DESCRIPTION:
Stream0653
END DESCRIPTION:

--- Stream0653.p01 (plan) ---

Plan Title=Multiple Run
Short Identifier=Multiple
Geom File=g01
Flow File=f01
Subcritical Flow
K Sum by GR= 0
Std Step Tol= 0.01
Critical Tol= 0.01
Num of Std Step Trials= 20
Max Error Tol= 0.3
Flow Tol Ratio= 0.001
Split Flow NTrial= 30
Split Flow Tol= 0.02
Split Flow Ratio= 0.02
Log Output Level= 0
Friction Slope Method= 1
Unsteady Friction Slope Method= 2
Unsteady Bridges Friction Slope Method= 1
Parabolic Critical Depth
Global Vel Dist=  1 , 1 , 1
Global Log Level= 0
CheckData=True
Encroach Param= -1, 0, 0, 0
BEGIN DESCRIPTION:
Multiple Run
END DESCRIPTION:

--- Stream0653.f01 (steady flow) ---

Flow Title=Multiple
Number of Profiles=7
Profile Names=10-year,25-year,50-year,1pct_min,100-year,1pct_plu,500-year
River Rch & RM= Stream0653,Reach-1,1701
     375     595     791     513    1023    2042    1680
Boundary for River Rch & Prof#=Stream0653,Reach-1,1
Up Type=0
Dn Type=3
Dn Slope=0.005
Boundary for River Rch & Prof#=Stream0653,Reach-1,2
Up Type=0
Dn Type=3
Dn Slope=0.005
Boundary for River Rch & Prof#=Stream0653,Reach-1,3
Up Type=0
Dn Type=3
Dn Slope=0.005
Boundary for River Rch & Prof#=Stream0653,Reach-1,4
Up Type=0
Dn Type=3
Dn Slope=0.005
Boundary for River Rch & Prof#=Stream0653,Reach-1,5
Up Type=0
Dn Type=3
Dn Slope=0.005
Boundary for River Rch & Prof#=Stream0653,Reach-1,6
Up Type=0
Dn Type=3
Dn Slope=0.005
Boundary for River Rch & Prof#=Stream0653,Reach-1,7
Up Type=0
Dn Type=3
Dn Slope=0.005

--- Stream0653.g01 (geometry) ---

Geom Title=Existing Conditions

River Reach=Stream0653,Reach-1
Reach XY= 30
      1951225.00     13907525.00      1951225.32     13907493.12
      1951229.02     13907476.36      1951236.60     13907465.21
      1951264.11     13907434.90      1951267.45     13907428.26
      1951267.40     13907421.62      1951263.98     13907414.97
      1951255.69     13907405.00      1951188.43     13907338.32
      1951180.50     13907327.45      1951177.08     13907319.14
      1951174.60     13907295.17      1951175.18     13907199.93
      1951172.73     13907180.94      1951164.14     13907165.36
      1951133.14     13907131.06      1951128.78     13907123.43
      1951125.52     13907109.78      1951125.43     13906859.82
      1951123.78     13906835.50      1951121.22     13906826.57
      1951116.86     13906818.94      1951080.75     13906777.33
      1951075.52     13906759.78      1951075.49     13906109.80
      1951073.95     13906085.43      1951069.54     13906072.55
      1951055.40     13906054.84      1950875.00     13905875.00

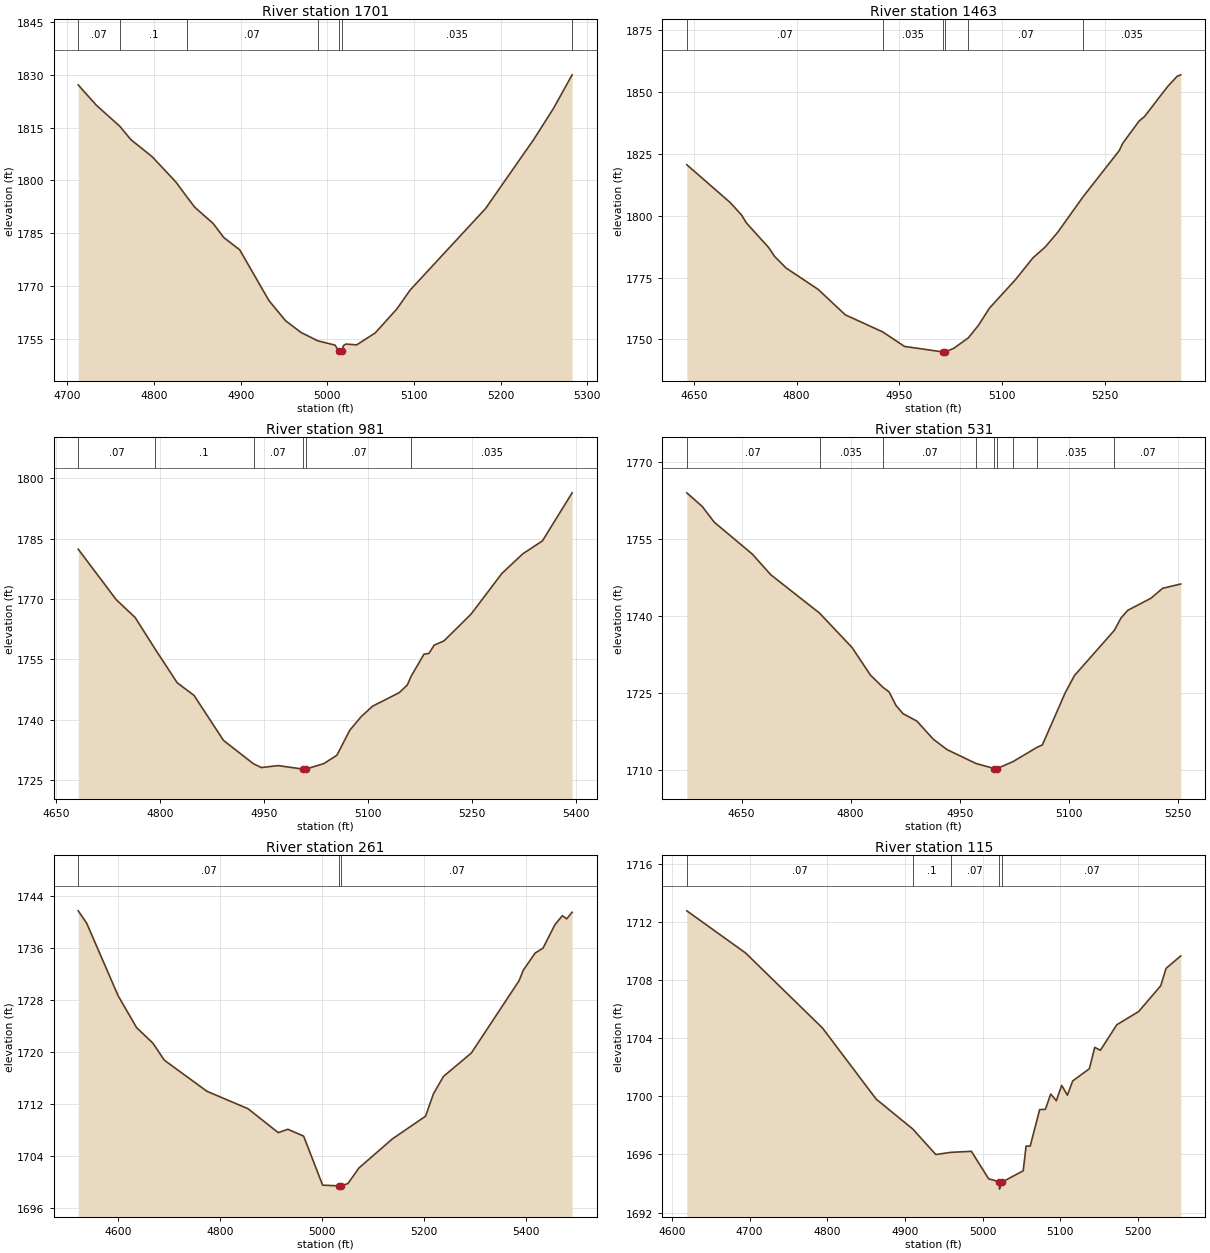
Type RM Length L Ch R = 1,1701,238,238,238
BEGIN DESCRIPTION:
Stream0653 4.0
END DESCRIPTION:
XS GIS Cut Line= 3
      1951548.94     13907486.51      1951222.72     13907418.11
      1950993.89     13907478.60
#Sta/Elev= 30
  4712.5 1827.20  4733.4 1821.43  4760.7 1815.38  4773.2 1811.64  4797.7 1806.80
  4825.3 1799.54  4837.5 1795.46  4846.8 1792.43  4868.2 1787.76  4880.5 1783.76
  4898.9 1780.25  4932.6 1765.81  4951.6 1760.12  4969.4 1756.77  4988.9 1754.36
  5008.9 1753.13  5013.4 1751.35  5013.6 1750.85  5017.4 1751.35  5018.4 1752.95
  5021.5 1753.43  5033.8 1753.20  5055.3 1756.61  5080.2 1763.43  5095.7 1768.85
  5182.6 1792.02  5238.4 1811.76  5261.1 1820.57  5282.4 1830.04  5282.5 1830.08
#Mann=7,-1,0
  4712.5    0.07       0  4760.7     0.1       0  4837.5    0.07       0
  4988.9   0.035       0  5013.4   0.035       0  5017.4   0.035       0
  5282.4    0.07       0
Bank Sta=5013.4,5017.4
Exp/Cntr=0.3,0.1

Type RM Length L Ch R = 1,1463,482,482,482
BEGIN DESCRIPTION:
Stream0653 3.0
END DESCRIPTION:
XS GIS Cut Line= 3
      1951475.02     13907024.99      1951175.00     13907225.00
      1950875.02     13907424.98
#Sta/Elev= 30
  4639.8 1820.64  4703.0 1805.38  4719.7 1800.30  4726.9 1797.05  4759.4 1787.10
  4767.9 1783.55  4784.6 1778.87  4831.5 1770.21  4871.2 1759.89  4925.8 1752.98
  4957.7 1747.10  5013.4 1744.89  5013.6 1744.39  5017.4 1744.89  5029.8 1746.38
  5050.9 1750.60  5065.7 1755.68  5081.6 1762.59  5119.8 1774.19  5145.2 1782.97
  5163.2 1787.37  5181.2 1793.27  5218.2 1807.62  5271.2 1826.40  5276.3 1829.35
  5300.2 1838.35  5308.0 1840.13  5341.2 1852.11  5355.6 1856.44  5360.9 1857.04
#Mann=6,-1,0
  4639.8    0.07       0  4925.8   0.035       0  5013.4   0.035       0
  5017.4   0.035       0  5050.9    0.07       0  5218.2   0.035       0
Bank Sta=5013.4,5017.4
Exp/Cntr=0.3,0.1

Type RM Length L Ch R = 1,981,450,450,450
BEGIN DESCRIPTION:
Stream0653 2.0
END DESCRIPTION:
XS GIS Cut Line= 3
      1951393.68     13906723.68      1951075.00     13906775.00
      1950825.00     13907075.00
#Sta/Elev= 30
  4681.5 1782.39  4736.4 1769.85  4763.7 1765.42  4792.0 1757.74  4824.5 1749.20
  4848.8 1746.06  4891.3 1734.89  4934.7 1729.07  4946.0 1728.15  4970.3 1728.63
  5006.2 1727.76  5006.4 1727.26  5010.2 1727.76  5036.3 1729.14  5055.0 1731.20
  5073.8 1737.45  5090.3 1740.83  5106.6 1743.39  5144.9 1746.73  5156.7 1748.64
  5162.1 1750.76  5180.8 1756.31  5187.9 1756.49  5195.6 1758.55  5209.7 1759.61
  5248.9 1766.27  5293.3 1776.36  5323.5 1781.23  5351.9 1784.45  5394.8 1796.39
#Mann=6,-1,0
  4681.5    0.07       0  4792.0     0.1       0  4934.7    0.07       0
  5006.2    0.05       0  5010.2    0.07       0  5162.1   0.035       0
Bank Sta=5006.2,5010.2
Exp/Cntr=0.3,0.1

Type RM Length L Ch R = 1,531,270,270,270
BEGIN DESCRIPTION:
Stream0653 1.0
END DESCRIPTION:
XS GIS Cut Line= 3
      1951475.26     13906468.53      1951075.00     13906325.00
      1950836.01     13906410.67
#Sta/Elev= 30
  4574.8 1763.99  4596.1 1761.32  4612.5 1758.28  4664.8 1752.08  4690.3 1748.05
  4757.4 1740.58  4801.9 1733.92  4827.4 1728.52  4844.3 1726.18  4852.9 1725.27
  4862.4 1722.64  4872.0 1721.04  4891.1 1719.60  4913.4 1716.11  4932.5 1714.05
  4972.2 1711.36  4997.5 1710.36  4997.7 1709.86  5001.5 1710.36  5023.3 1711.71
  5056.2 1714.48  5063.7 1714.97  5095.1 1725.10  5107.8 1728.45  5162.8 1737.27
  5171.6 1739.61  5181.1 1741.14  5213.0 1743.49  5228.9 1745.41  5253.9 1746.26
#Mann=9,-1,0
  4574.8    0.07       0  4757.4   0.035       0  4844.3    0.07       0
  4972.2   0.035       0  4997.5   0.035       0  5001.5   0.035       0
  5023.3    0.07       0  5056.2   0.035       0  5162.8    0.07       0
Bank Sta=4997.5,5001.5
Exp/Cntr=0.3,0.1

Type RM Length L Ch R = 1,261,146,146,146
BEGIN DESCRIPTION:
Stream0653 0.0
END DESCRIPTION:
XS GIS Cut Line= 4
      1951433.13     13906300.15      1951141.18     13906037.13
      1950925.48     13906095.00      1950699.29     13906365.90
#Sta/Elev= 30
  4522.3 1741.66  4538.9 1739.76  4600.7 1728.61  4636.8 1723.73  4668.7 1721.36
  4691.3 1718.73  4774.9 1713.96  4855.6 1711.28  4914.8 1707.61  4933.6 1708.13
  4964.6 1707.08  5001.9 1699.55  5034.1 1699.44  5034.3 1698.94  5038.1 1699.44
  5051.6 1699.80  5073.3 1702.20  5138.6 1706.64  5203.8 1710.13  5219.4 1713.58
  5239.0 1716.24  5293.7 1719.83  5387.5 1730.95  5395.6 1732.54  5418.8 1735.17
  5434.4 1735.94  5457.8 1739.54  5472.3 1740.91  5480.8 1740.43  5491.5 1741.44
#Mann=3,-1,0
  4522.3    0.07       0  5034.1    0.05       0  5038.1    0.07       0
Bank Sta=5034.1,5038.1
Exp/Cntr=0.3,0.1

Type RM Length L Ch R = 1,115,0,0,0
BEGIN DESCRIPTION:
Stream0653 T
END DESCRIPTION:
XS GIS Cut Line= 5
      1951269.83     13906097.27      1951137.88     13905963.58
      1951009.41     13905928.86      1950903.51     13905982.68
      1950759.68     13906116.11
#Sta/Elev= 30
  4619.2 1712.75  4694.9 1709.85  4793.9 1704.69  4863.0 1699.80  4910.0 1697.75
  4939.8 1695.99  4959.2 1696.14  4985.6 1696.21  5007.8 1694.32  5021.6 1694.11
  5021.8 1693.61  5025.6 1694.11  5052.3 1694.87  5056.0 1696.57  5061.3 1696.57
  5073.5 1699.08  5080.9 1699.10  5087.7 1700.15  5095.0 1699.69  5101.8 1700.75
  5109.2 1700.07  5116.0 1701.05  5137.5 1701.89  5144.4 1703.36  5151.7 1703.16
  5172.7 1704.91  5201.1 1705.83  5229.4 1707.60  5236.2 1708.79  5255.1 1709.65
#Mann=5,-1,0
  4619.2    0.07       0  4910.0     0.1       0  4959.2    0.07       0
  5021.6    0.05       0  5025.6    0.07       0
Bank Sta=5021.6,5025.6
Exp/Cntr=0.3,0.1

Chan Stop Cuts=-1