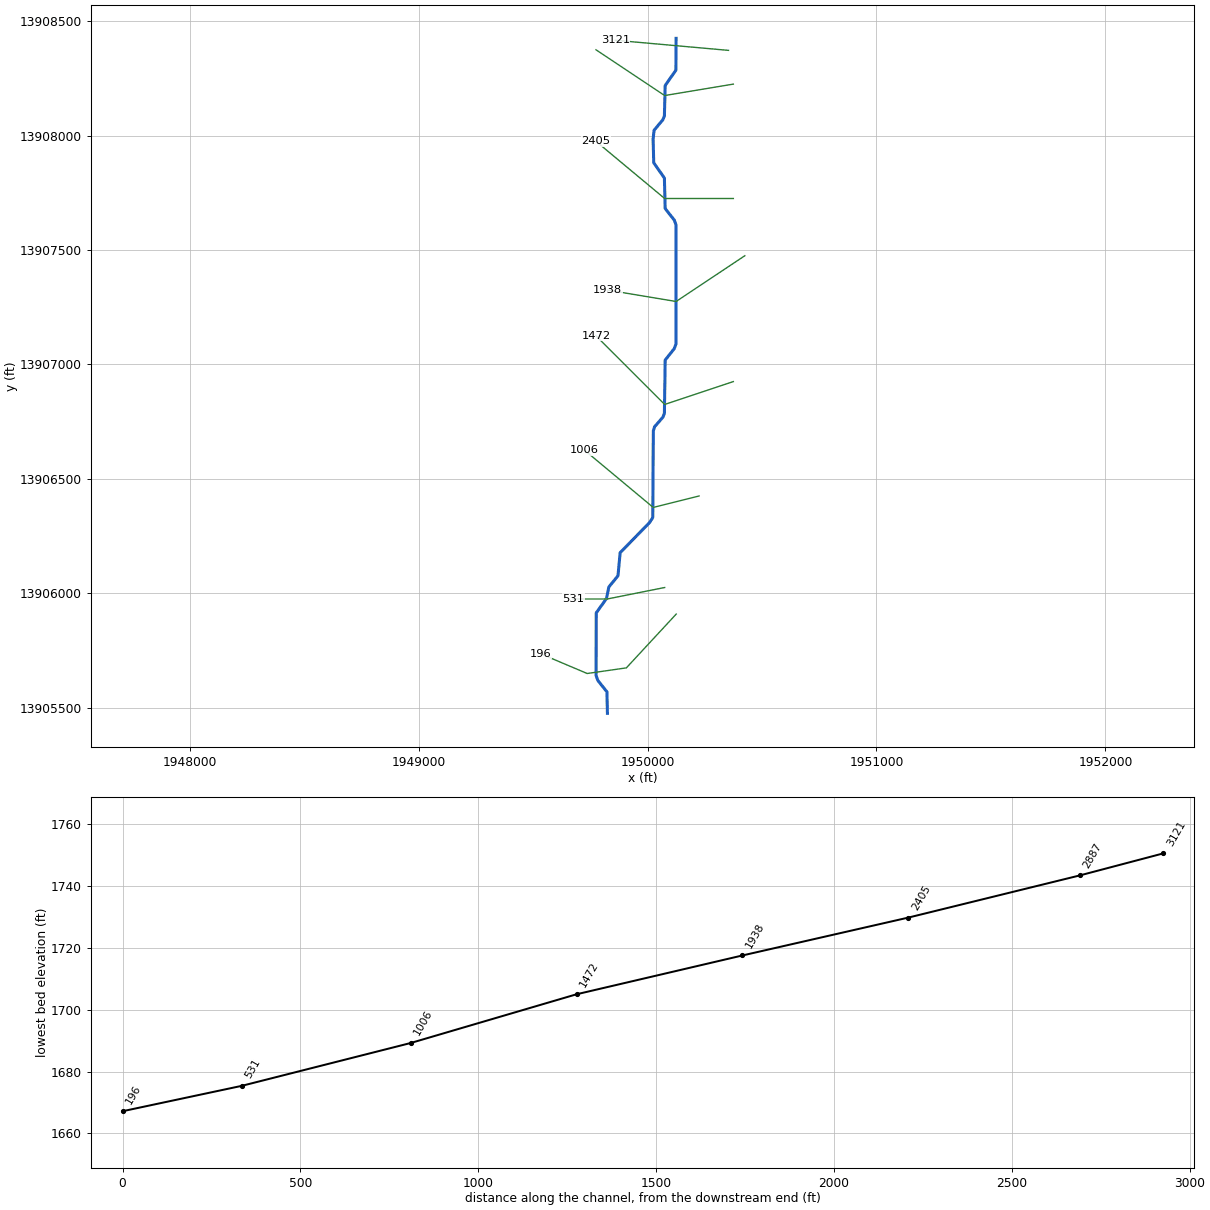
--- Stream0654.prj (project) ---

Proj Title=Stream0654 Base Level Engineering
Current Plan=p01
Default Exp/Contr=0.3,0.1
English Units
Geom File=g01
Flow File=f01
Plan File=p01
Y Axis Title=Elevation
X Axis Title(PF)=Main Channel Distance
X Axis Title(XS)=Station
BEGIN DESCRIPTION:
Stream0654
END DESCRIPTION:
DSS Export Rating Curves= 0
DSS Export Rating Curve Sorted= 0
DSS Export Volume Flow Curves= 0
DXF OffsetX= 0
DXF OffsetY= 0
DXF ScaleX= 1
DXF ScaleY= 10

--- Stream0654.p01 (plan) ---

Plan Title=Multiple Run
Short Identifier=Multiple
Geom File=g01
Flow File=f01
Subcritical Flow
K Sum by GR= 0
Std Step Tol= 0.01
Critical Tol= 0.01
Num of Std Step Trials= 20
Max Error Tol= 0.3
Flow Tol Ratio= 0.001
Split Flow NTrial= 30
Split Flow Tol= 0.02
Split Flow Ratio= 0.02
Log Output Level= 0
Friction Slope Method= 1
Unsteady Friction Slope Method= 2
Unsteady Bridges Friction Slope Method= 1
Parabolic Critical Depth
Global Vel Dist=  1 , 1 , 1
Global Log Level= 0
CheckData=True
Encroach Param= -1, 0, 0, 0
BEGIN DESCRIPTION:
Multiple Run
END DESCRIPTION:

--- Stream0654.f01 (steady flow) ---

Flow Title=Multiple
Program Version=4.10
Number of Profiles= 7
Profile Names=10-year,25-year,50-year,1pct_min,100-year,1pct_plu,500-year
River Rch & RM=Stream0654,Reach-1         ,3121
     664    1096    1498     993    1982    3954    3416
Boundary for River Rch & Prof#=Stream0654,Reach-1         , 1
Up Type= 0
Dn Type= 3
Dn Slope=0.007
Boundary for River Rch & Prof#=Stream0654,Reach-1         , 2
Up Type= 0
Dn Type= 3
Dn Slope=0.007
Boundary for River Rch & Prof#=Stream0654,Reach-1         , 3
Up Type= 0
Dn Type= 3
Dn Slope=0.007
Boundary for River Rch & Prof#=Stream0654,Reach-1         , 4
Up Type= 0
Dn Type= 3
Dn Slope=0.007
Boundary for River Rch & Prof#=Stream0654,Reach-1         , 5
Up Type= 0
Dn Type= 3
Dn Slope=0.007
Boundary for River Rch & Prof#=Stream0654,Reach-1         , 6
Up Type= 0
Dn Type= 3
Dn Slope=0.007
Boundary for River Rch & Prof#=Stream0654,Reach-1         , 7
Up Type= 0
Dn Type= 3
Dn Slope=0.007
DSS Import GetInterval= 0
DSS Import GetPeak= 0
DSS Import FillOption= 0

--- Stream0654.g01 (geometry) ---

Geom Title=Existing Conditions
Program Version=4.10

River Reach=Stream0654      ,Reach-1
Reach XY= 30
        1950125.       13908425.      1950123.83     13908285.48
      1950077.27     13908219.06      1950073.77     13908085.51
      1950066.85     13908068.95      1950028.77     13908023.43
       1950024.5     13907985.17      1950027.25     13907880.94
      1950073.77     13907814.49      1950077.27     13907680.94
      1950116.86     13907631.06      1950124.48     13907609.78
      1950124.48     13907090.22      1950116.86     13907068.94
      1950077.26     13907019.06      1950073.78      13906785.5
      1950066.86     13906768.94      1950030.75     13906727.33
      1950025.52     13906709.78      1950022.94     13906330.85
      1950008.57     13906308.24      1949880.52     13906177.43
      1949871.17     13906076.59      1949831.11     13906027.18
      1949820.81     13905976.74       1949776.2      13905914.5
      1949775.51     13905640.21       1949783.1     13905618.93
       1949822.9     13905569.13        1949825.       13905475.

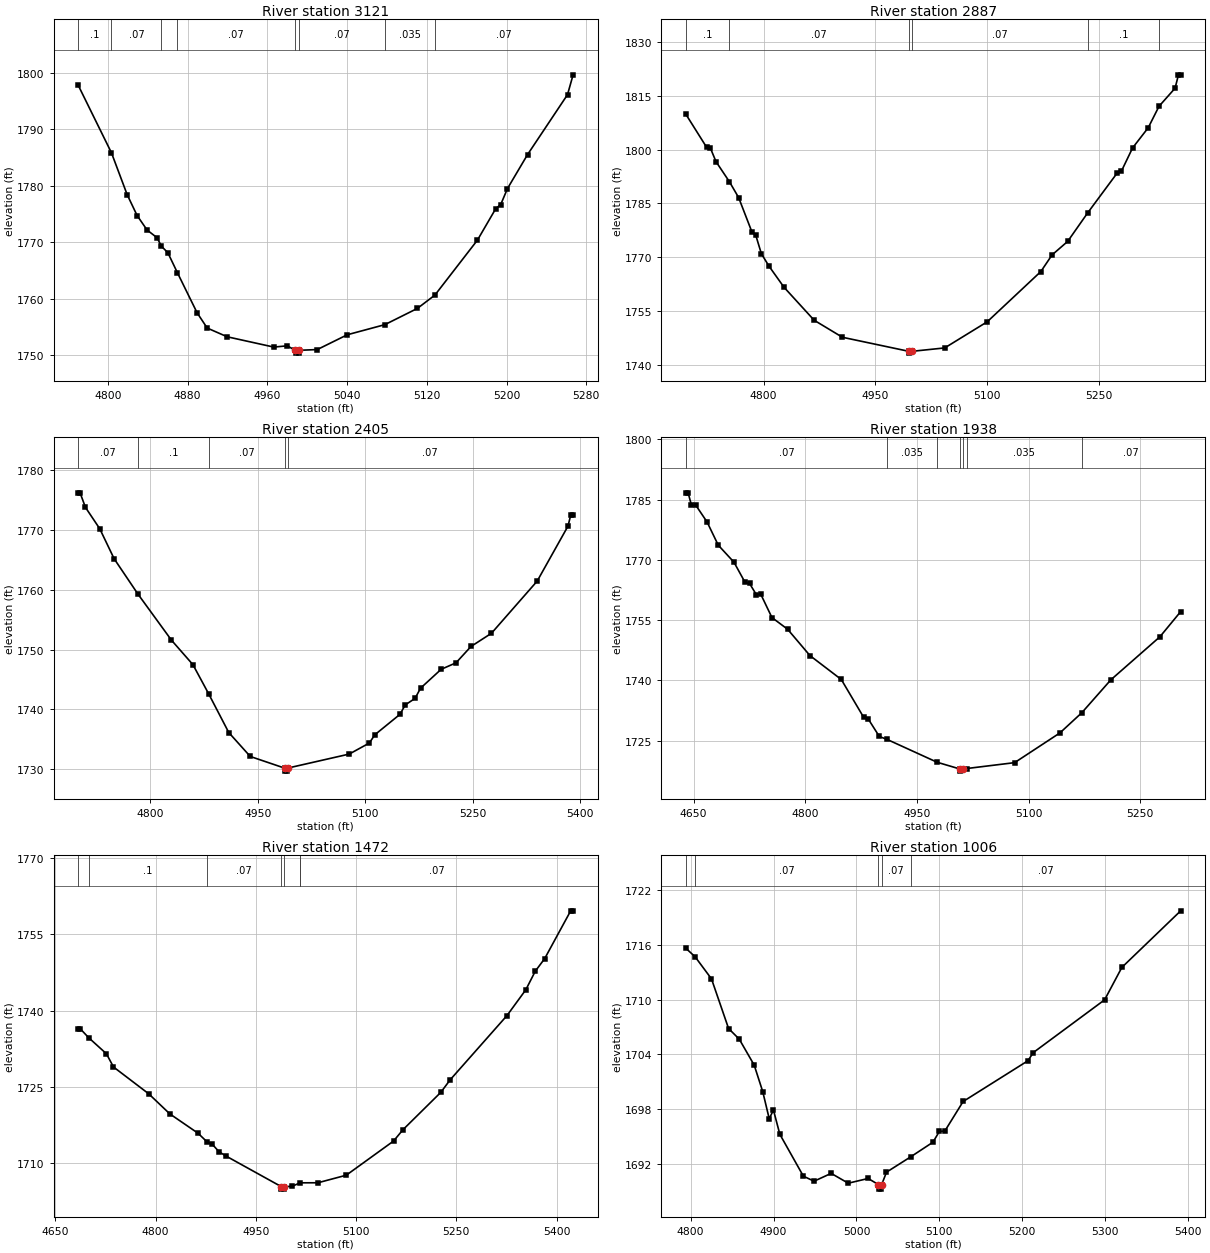
Type RM Length L Ch R = 1 ,3121    ,234,234,234
BEGIN DESCRIPTION:
Stream0654 7.0
END DESCRIPTION:
XS GIS Cut Line= 2
      1950353.76     13908372.39      1949859.43     13908416.62
#Sta/Elev= 30
  4770.4 1797.76  4803.7 1785.82  4819.4 1778.44  4829.4 1774.73  4839.4 1772.17
  4849.5 1770.79  4853.7 1769.31  4860.2 1768.16  4869.8 1764.62  4889.6 1757.51
  4899.7 1754.82  4919.8 1753.27  4966.5 1751.45    4980 1751.67    4988 1750.88
  4988.3 1750.38  4991.8 1750.38    4992 1750.88  5010.1 1751.01  5040.2 1753.63
  5077.9 1755.42  5110.5 1758.29  5128.1 1760.65  5170.8 1770.39  5189.1 1775.94
  5194.1 1776.67  5200.9 1779.51    5221 1785.51  5261.1 1796.12  5266.7 1799.63
#Mann= 8 ,-1 , 0
  4770.4      .1       0  4803.7     .07       0  4853.7    .035       0
  4869.8     .07       0    4988     .05       0    4992     .07       0
  5077.9    .035       0  5128.1     .07       0
Bank Sta=4988,4992
XS Rating Curve= 0 ,0
Exp/Cntr=0.3,0.1

Type RM Length L Ch R = 1 ,2887    ,482,482,482
BEGIN DESCRIPTION:
Stream0654 6.0
END DESCRIPTION:
XS GIS Cut Line= 3
      1950374.98       13908225.        1950075.       13908175.
      1949774.98     13908375.01
#Sta/Elev= 30
  4695.5 1809.87  4723.4 1800.65  4728.4 1800.46    4736 1796.66  4754.1 1791.03
  4766.4 1786.64  4784.2 1777.08  4789.3 1776.22  4796.9 1771.02    4807 1767.58
  4827.3 1761.66  4867.8 1752.46  4905.8 1747.71  4995.1 1743.79  4995.3 1743.29
  4999.1 1743.79  5043.2 1744.74  5100.3 1752.02  5172.4 1766.04  5187.4 1770.66
  5208.4 1774.43  5235.2 1782.36  5274.5 1793.38  5280.6 1794.02  5295.6 1800.49
  5316.6 1806.11  5331.1 1812.09  5352.7 1817.14  5357.2 1820.86  5360.2 1820.86
#Mann= 6 ,-1 , 0
  4695.5      .1       0  4754.1     .07       0  4995.1     .05       0
  4999.1     .07       0  5235.2      .1       0  5331.1     .07       0
Bank Sta=4995.1,4999.1
XS Rating Curve= 0 ,0
Exp/Cntr=0.3,0.1

Type RM Length L Ch R = 1 ,2405    ,467,467,467
BEGIN DESCRIPTION:
Stream0654 5.0
END DESCRIPTION:
XS GIS Cut Line= 3
        1950375.       13907725.        1950075.       13907725.
      1949775.01     13907974.99
#Sta/Elev= 30
  4699.6 1776.19  4702.1 1776.19  4709.6 1773.76  4729.6 1770.18  4749.6 1765.18
  4782.9 1759.26  4829.6 1751.57  4859.6 1747.47  4881.5 1742.61  4909.6 1736.13
  4939.6 1732.13  4987.6 1730.18  4987.8 1729.68  4991.3 1729.68  4991.6 1730.18
  5077.7 1732.53  5105.7 1734.37  5113.5 1735.76  5148.6 1739.18  5155.8 1740.74
  5169.5 1741.83  5177.3 1743.55  5205.9 1746.69  5226.7 1747.78  5247.6 1750.51
  5276.2 1752.72    5340 1761.44    5383 1770.63  5386.9 1772.52  5390.1 1772.52
#Mann= 5 ,-1 , 0
  4699.6     .07       0  4782.9      .1       0  4881.5     .07       0
  4987.6     .05       0  4991.6     .07       0
Bank Sta=4987.6,4991.6
XS Rating Curve= 0 ,0
Exp/Cntr=0.3,0.1

Type RM Length L Ch R = 1 ,1938    ,466,466,466
BEGIN DESCRIPTION:
Stream0654 4.0
END DESCRIPTION:
XS GIS Cut Line= 3
      1950424.97     13907474.98        1950125.       13907275.
      1949824.96     13907325.01
#Sta/Elev= 30
  4639.5 1786.69  4642.5 1786.69    4647 1783.64    4653 1783.56    4668 1779.43
    4683 1773.67  4704.1 1769.43  4719.1 1764.38  4725.1 1764.13  4734.1 1761.36
  4740.1 1761.47  4755.1 1755.66  4776.2 1752.74  4806.2 1746.19  4848.3 1740.24
  4878.3 1730.84  4884.3 1730.47  4899.4 1726.06  4909.8 1725.33    4977 1719.65
  5008.2 1717.94  5008.4 1717.44  5012.2 1717.94  5016.5 1718.08  5081.1 1719.55
    5142 1726.95  5171.5 1731.99  5210.4 1740.16  5276.3 1750.87  5304.2 1757.13
#Mann= 7 ,-1 , 0
  4639.5     .07       0  4909.8    .035       0    4977     .07       0
  5008.2     .05       0  5012.2     .07       0  5016.5    .035       0
  5171.5     .07       0
Bank Sta=5008.2,5012.2
XS Rating Curve= 0 ,0
Exp/Cntr=0.3,0.1

Type RM Length L Ch R = 1 ,1472    ,466,466,466
BEGIN DESCRIPTION:
Stream0654 3.0
END DESCRIPTION:
XS GIS Cut Line= 3
      1950374.97     13906924.99        1950075.       13906825.
      1949774.98     13907125.02
#Sta/Elev= 30
  4684.2 1736.49  4686.8 1736.49  4699.9 1734.67  4726.3 1731.53  4736.9 1728.93
  4789.6 1723.66  4821.2 1719.71  4863.4 1715.91  4877.3 1714.16  4884.5 1713.77
    4895 1712.25  4905.5 1711.41  4987.9 1705.42  4988.1 1704.92  4991.6 1704.92
  4991.9 1705.42  5003.9 1705.46  5016.2 1706.16  5042.8 1706.17  5085.3 1707.66
    5156 1714.37  5170.1  1716.6  5226.7 1723.94  5240.8 1726.42  5325.7 1739.03
    5354 1744.12  5368.1 1747.76  5382.2 1750.24  5421.1 1759.63  5424.7 1759.63
#Mann= 7 ,-1 , 0
  4684.2     .07       0  4699.9      .1       0  4877.3     .07       0
  4987.9     .05       0  4991.9     .07       0  5016.2    .035       0
  5016.2     .07       0
Bank Sta=4987.9,4991.9
XS Rating Curve= 0 ,0
Exp/Cntr=0.3,0.1

Type RM Length L Ch R = 1 ,1006    ,475,475,475
BEGIN DESCRIPTION:
Stream0654 2.0
END DESCRIPTION:
XS GIS Cut Line= 3
      1950224.96     13906424.99        1950025.       13906375.
      1949725.02     13906624.99
#Sta/Elev= 30
  4794.3 1715.64  4805.5  1714.7  4825.2 1712.28  4845.8 1706.83  4858.7 1705.66
  4876.7 1702.81    4887  1699.9  4894.8 1696.93  4899.9 1697.88  4907.6 1695.22
    4936 1690.62  4948.9 1690.07  4969.5 1690.93  4990.1 1689.85  5014.1 1690.37
  5026.4  1689.7  5026.6  1689.2  5030.1  1689.2  5030.4  1689.7  5036.2 1691.06
  5065.3 1692.74  5092.2 1694.35    5100 1695.54  5106.5 1695.57  5128.6 1698.82
  5206.7 1703.29  5213.2 1704.19  5299.2 1709.98    5320 1713.54  5390.9 1719.75
#Mann= 5 ,-1 , 0
  4794.3     .07       0  4805.5     .07       0  5026.4     .05       0
  5030.4     .07       0  5065.3     .07       0
Bank Sta=5026.4,5030.4
XS Rating Curve= 0 ,0
Exp/Cntr=0.3,0.1

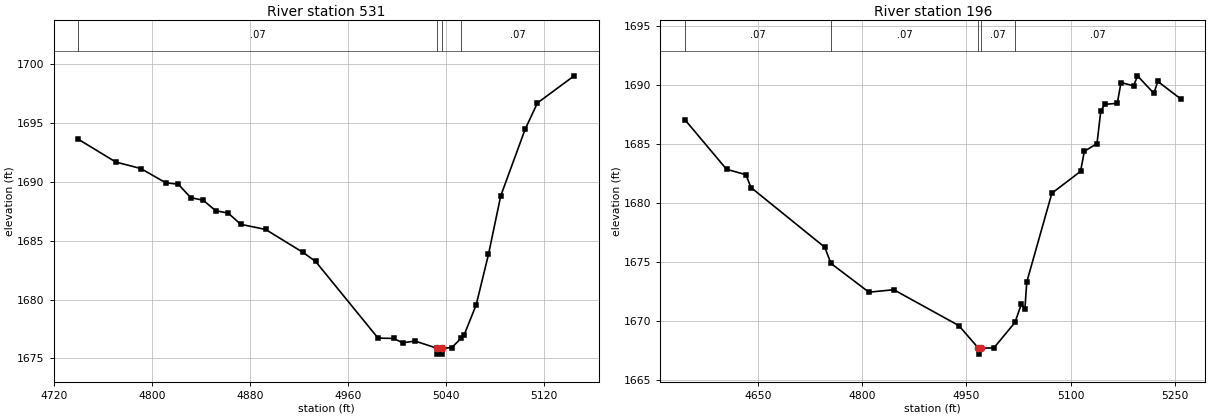
Type RM Length L Ch R = 1 ,531     ,335,335,335
BEGIN DESCRIPTION:
Stream0654 1.0
END DESCRIPTION:
XS GIS Cut Line= 3
      1950075.01       13906025.        1949825.       13905975.
      1949674.96       13905975.
#Sta/Elev= 30
    4740 1693.59  4770.6 1691.66    4791 1691.11  4811.4  1689.9  4821.6 1689.78
  4831.8 1688.64    4842 1688.42  4852.2 1687.53  4862.4 1687.33  4872.6 1686.38
    4893 1685.94  4923.6 1683.99  4933.8 1683.23  4984.8 1676.73  4997.5  1676.7
    5005 1676.33    5015 1676.48    5033 1675.87  5033.2 1675.37  5036.7 1675.37
    5037 1675.87    5045 1675.92  5052.5  1676.7    5055 1676.96    5065 1679.56
    5075 1683.82    5085 1688.78    5105 1694.45    5115 1696.67    5145 1698.97
#Mann= 4 ,-1 , 0
    4740     .07       0    5033     .05       0    5037     .07       0
  5052.5     .07       0
Bank Sta=5033,5037
XS Rating Curve= 0 ,0
Exp/Cntr=0.3,0.1

Type RM Length L Ch R = 1 ,196     ,0,0,0
BEGIN DESCRIPTION:
Stream0654 0.0
END DESCRIPTION:
XS GIS Cut Line= 4
      1950125.46     13905909.01      1949907.68     13905673.87
      1949736.58     13905649.21      1949534.58     13905734.94
#Sta/Elev= 30
  4545.1 1687.06  4605.1 1682.85  4632.9 1682.39  4640.3  1681.3  4746.3 1676.24
  4755.2 1674.87  4809.8 1672.43  4845.5 1672.64    4939  1669.6  4967.3 1667.68
  4967.6 1667.18  4971.3 1667.68  4989.5 1667.71  5019.8 1669.87  5028.9 1671.43
    5034 1670.97  5036.7 1673.29  5072.8 1680.82    5114 1682.67  5119.5 1684.37
  5137.7 1685.03  5143.1 1687.78  5148.8 1688.35  5166.8 1688.44  5172.2  1690.2
  5190.4 1689.92  5195.9 1690.77  5219.5 1689.28    5225  1690.3  5257.9 1688.82
#Mann= 5 ,-1 , 0
  4545.1     .07       0  4755.2     .07       0  4967.3     .05       0
  4971.3     .07       0  5019.8     .07       0
Bank Sta=4967.3,4971.3
XS Rating Curve= 0 ,0
Exp/Cntr=0.3,0.1

Chan Stop Cuts=-1
Use User Specified Reach Order=0
Composite Channel Slope=5