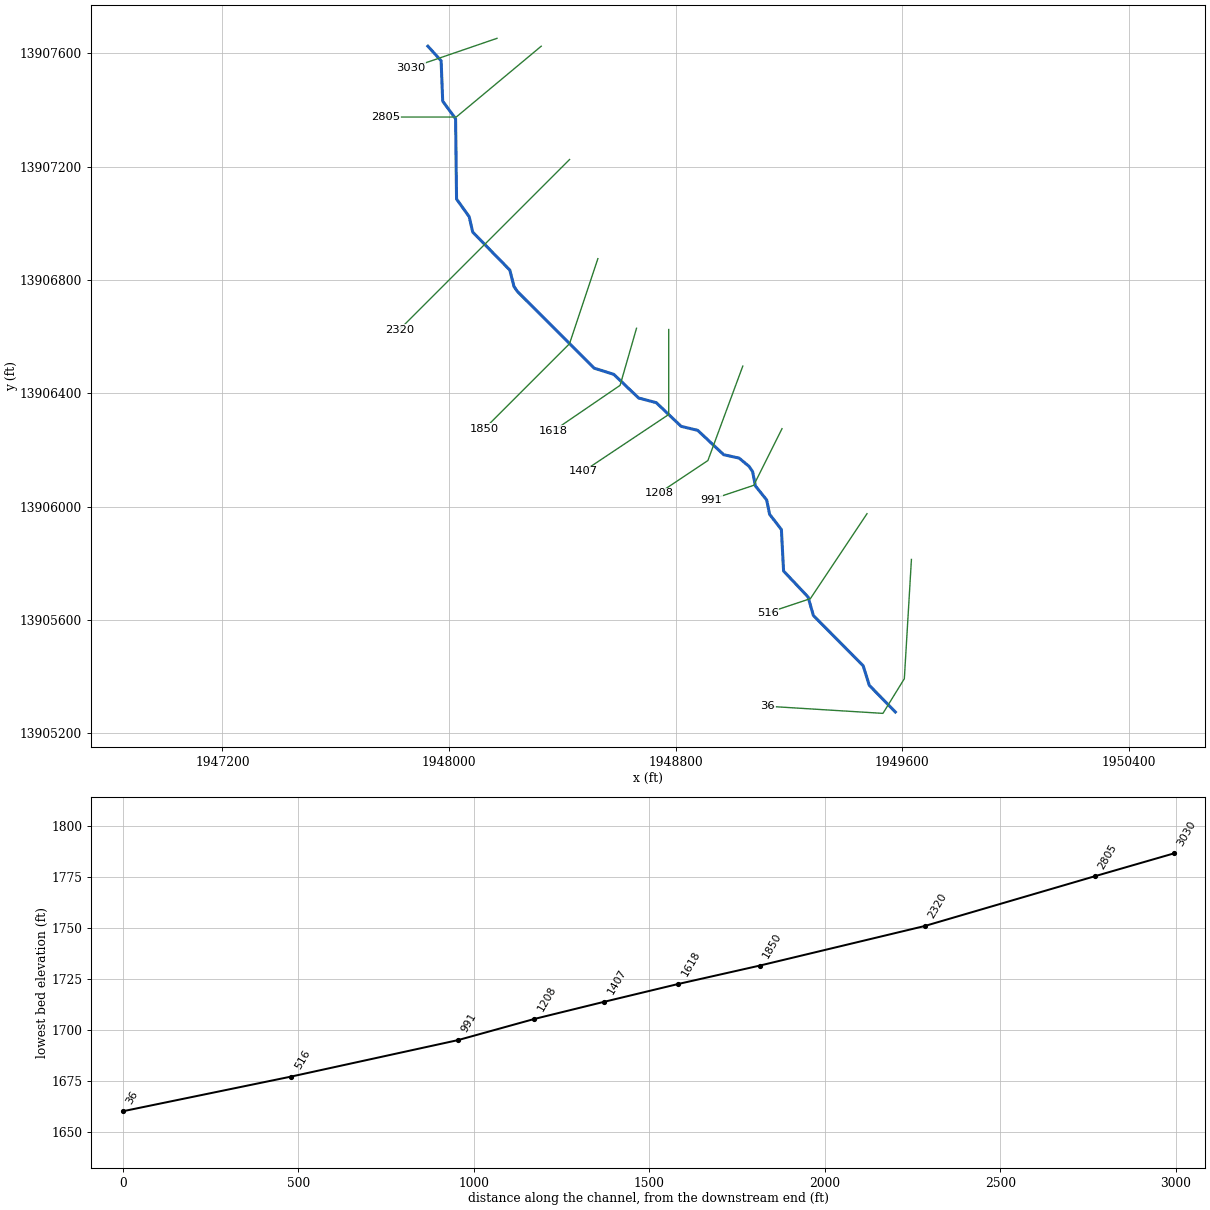
--- Stream0655.prj (project) ---

Proj Title=Stream0655 Base Level Engineering
Current Plan=p01
Default Exp/Contr=0.3,0.1
English Units
Geom File=g01
Flow File=f01
Plan File=p01
Y Axis Title=Elevation
X Axis Title(PF)=Main Channel Distance
X Axis Title(XS)=Station
BEGIN DESCRIPTION:
Stream0655
END DESCRIPTION:
DSS Export Rating Curves= 0
DSS Export Rating Curve Sorted= 0
DSS Export Volume Flow Curves= 0
DXF OffsetX= 0
DXF OffsetY= 0
DXF ScaleX= 1
DXF ScaleY= 10

--- Stream0655.p01 (plan) ---

Plan Title=Multiple Run
Short Identifier=Multiple
Geom File=g01
Flow File=f01
Subcritical Flow
K Sum by GR= 0
Std Step Tol= 0.01
Critical Tol= 0.01
Num of Std Step Trials= 20
Max Error Tol= 0.3
Flow Tol Ratio= 0.001
Split Flow NTrial= 30
Split Flow Tol= 0.02
Split Flow Ratio= 0.02
Log Output Level= 0
Friction Slope Method= 1
Unsteady Friction Slope Method= 2
Unsteady Bridges Friction Slope Method= 1
Parabolic Critical Depth
Global Vel Dist=  1 , 1 , 1
Global Log Level= 0
CheckData=True
Encroach Param= -1, 0, 0, 0
BEGIN DESCRIPTION:
Multiple Run
END DESCRIPTION:

--- Stream0655.f01 (steady flow) ---

Flow Title=Multiple
Program Version=4.10
Number of Profiles= 7
Profile Names=10-year,25-year,50-year,1pct_min,100-year,1pct_plu,500-year
River Rch & RM=Stream0655,Reach-1         ,3030
     429     688     922     602    1201    2395    1999
Boundary for River Rch & Prof#=Stream0655,Reach-1         , 1
Up Type= 0
Dn Type= 3
Dn Slope=0.005
Boundary for River Rch & Prof#=Stream0655,Reach-1         , 2
Up Type= 0
Dn Type= 3
Dn Slope=0.005
Boundary for River Rch & Prof#=Stream0655,Reach-1         , 3
Up Type= 0
Dn Type= 3
Dn Slope=0.005
Boundary for River Rch & Prof#=Stream0655,Reach-1         , 4
Up Type= 0
Dn Type= 3
Dn Slope=0.005
Boundary for River Rch & Prof#=Stream0655,Reach-1         , 5
Up Type= 0
Dn Type= 3
Dn Slope=0.005
Boundary for River Rch & Prof#=Stream0655,Reach-1         , 6
Up Type= 0
Dn Type= 3
Dn Slope=0.005
Boundary for River Rch & Prof#=Stream0655,Reach-1         , 7
Up Type= 0
Dn Type= 3
Dn Slope=0.005
DSS Import GetInterval= 0
DSS Import GetPeak= 0
DSS Import FillOption= 0

--- Stream0655.g01 (geometry) ---

Geom Title=Existing Conditions

River Reach=Stream0655,Reach-1
Reach XY= 30
      1947925.00     13907625.00      1947971.70     13907573.63
      1947977.27     13907430.94      1948022.74     13907369.06
      1948026.20     13907085.50      1948070.78     13907023.25
      1948083.14     13906968.94      1948214.22     13906834.68
      1948228.98     13906776.65      1948241.65     13906758.33
      1948511.79     13906488.63      1948581.04     13906466.82
      1948668.96     13906383.18      1948731.04     13906366.82
      1948818.96     13906283.18      1948877.28     13906269.13
      1948968.98     13906183.18      1949023.57     13906171.11
      1949058.51     13906142.05      1949071.14     13906123.58
      1949081.11     13906072.84      1949120.84     13906023.28
      1949131.12     13905972.82      1949172.75     13905919.07
      1949180.48     13905772.56      1949266.82     13905681.04
      1949285.78     13905615.32      1949461.37     13905438.21
      1949483.11     13905368.93      1949575.00     13905275.00

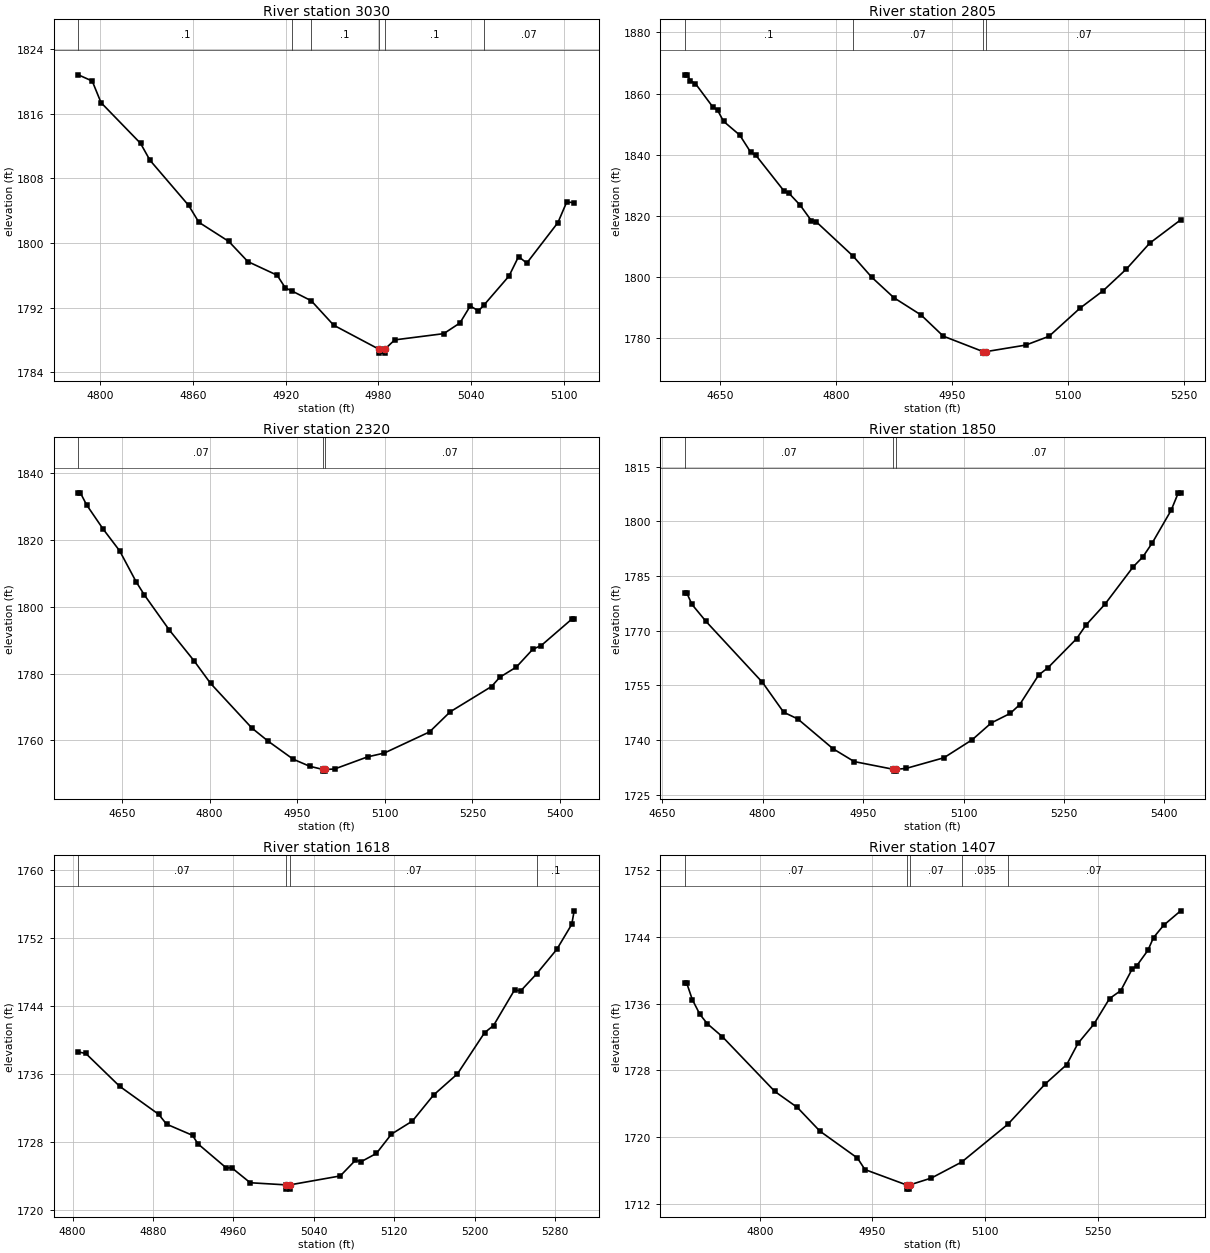
Type RM Length L Ch R = 1,3030,225,225,225
BEGIN DESCRIPTION:
Stream0655 7.0
END DESCRIPTION:
XS GIS Cut Line= 2
      1948168.88     13907652.79      1947865.05     13907548.61
#Sta/Elev= 30
  4785.7 1820.80  4794.7 1820.03  4800.4 1817.36  4826.0 1812.32  4832.1 1810.23
  4857.2 1804.63  4863.8 1802.55  4883.2 1800.18  4895.5 1797.69  4914.5 1796.00
  4919.8 1794.43  4924.3 1794.03  4936.6 1792.84  4951.1 1789.82  4980.3 1786.86
  4980.6 1786.36  4984.1 1786.36  4984.3 1786.86  4990.7 1788.00  5022.4 1788.77
  5032.9 1790.09  5039.6 1792.20  5044.9 1791.58  5048.7 1792.36  5064.7 1795.90
  5070.9 1798.31  5076.2 1797.50  5096.4 1802.52  5102.1 1805.07  5106.9 1804.97
#Mann=6,-1,0
  4785.7     0.1       0  4924.3    0.07       0  4936.6     0.1       0
  4980.3    0.05       0  4984.3     0.1       0  5048.7    0.07       0
Bank Sta=4980.3,4984.3
Exp/Cntr=0.3,0.1

Type RM Length L Ch R = 1,2805,485,485,485
BEGIN DESCRIPTION:
Stream0655 6.0
END DESCRIPTION:
XS GIS Cut Line= 3
      1948325.01     13907625.01      1948025.00     13907375.00
      1947775.03     13907375.00
#Sta/Elev= 30
  4604.9 1866.10  4608.2 1866.10  4612.1 1864.12  4618.6 1863.24  4640.7 1855.73
  4647.2 1854.55  4655.0 1850.91  4675.9 1846.41  4690.2 1840.75  4696.7 1839.83
  4733.1 1828.15  4739.6 1827.39  4754.0 1823.50  4768.3 1818.50  4774.8 1818.07
  4822.2 1806.91  4846.4 1799.98  4875.0 1793.30  4910.2 1787.64  4938.8 1780.75
  4990.2 1775.70  4990.4 1775.20  4994.2 1775.70  5045.4 1777.83  5075.4 1780.70
  5115.4 1789.88  5145.4 1795.60  5175.4 1802.68  5205.4 1811.10  5245.4 1818.72
#Mann=4,-1,0
  4604.9     0.1       0  4822.2    0.07       0  4990.2    0.05       0
  4994.2    0.07       0
Bank Sta=4990.2,4994.2
Exp/Cntr=0.3,0.1

Type RM Length L Ch R = 1,2320,470,470,470
BEGIN DESCRIPTION:
Stream0655 5.0
END DESCRIPTION:
XS GIS Cut Line= 3
      1948425.01     13907225.01      1948125.00     13906925.00
      1947825.03     13906625.03
#Sta/Elev= 30
  4575.5 1834.12  4579.0 1834.12  4589.6 1830.53  4617.9 1823.28  4646.2 1816.76
  4674.5 1807.47  4688.6 1803.53  4731.1 1793.08  4773.5 1783.85  4801.8 1777.08
  4872.5 1763.71  4900.8 1759.72  4943.2 1754.39  4971.5 1752.27  4994.2 1751.32
  4994.5 1750.82  4998.0 1750.82  4998.2 1751.32  5013.9 1751.45  5070.5 1755.09
  5098.8 1756.21  5176.5 1762.56  5211.9 1768.58  5282.6 1776.15  5296.8 1778.93
  5325.0 1781.96  5353.3 1787.31  5367.5 1788.39  5420.5 1796.40  5424.0 1796.40
#Mann=3,-1,0
  4575.5    0.07       0  4994.2    0.05       0  4998.2    0.07       0
Bank Sta=4994.2,4998.2
Exp/Cntr=0.3,0.1

Type RM Length L Ch R = 1,1850,232,232,232
BEGIN DESCRIPTION:
Stream0655 4.0
END DESCRIPTION:
XS GIS Cut Line= 3
      1948525.01     13906875.04      1948425.00     13906575.00
      1948125.02     13906275.02
#Sta/Elev= 30
  4683.7 1780.47  4686.4 1780.47  4694.3 1777.23  4715.4 1772.54  4799.7 1755.81
  4831.3 1747.62  4852.4 1745.78  4905.1 1737.59  4936.7 1734.07  4995.3 1731.95
  4995.6 1731.45  4999.1 1731.45  4999.3 1731.95  5014.1 1732.19  5070.7 1735.12
  5113.1 1740.09  5141.4 1744.68  5169.7 1747.29  5183.8 1749.69  5212.1 1757.82
  5226.2 1759.85  5268.7 1767.77  5282.8 1771.53  5311.1 1777.25  5353.5 1787.56
  5367.7 1790.23  5381.8 1794.08  5410.1 1803.07  5420.7 1807.84  5424.2 1807.84
#Mann=3,-1,0
  4683.7    0.07       0  4995.3    0.05       0  4999.3    0.07       0
Bank Sta=4995.3,4999.3
Exp/Cntr=0.3,0.1

Type RM Length L Ch R = 1,1618,211,211,211
BEGIN DESCRIPTION:
Mapping XS d06d4ccb
END DESCRIPTION:
XS GIS Cut Line= 3
      1948661.39     13906629.37      1948603.42     13906428.00
      1948369.16     13906267.88
#Sta/Elev= 30
  4805.8 1738.57  4813.2 1738.40  4846.9 1734.54  4885.7 1731.25  4893.6 1730.09
  4919.4 1728.78  4924.8 1727.78  4953.1 1724.94  4958.3 1724.98  4976.8 1723.21
  5012.3 1722.96  5012.6 1722.46  5016.1 1722.46  5016.3 1722.96  5066.4 1724.01
  5081.4 1725.84  5087.4 1725.70  5102.3 1726.65  5117.3 1728.92  5138.2 1730.46
  5159.2 1733.51  5183.0 1736.00  5210.0 1740.84  5218.9 1741.68  5239.8 1745.86
  5245.9 1745.74  5261.9 1747.77  5281.8 1750.62  5296.7 1753.56  5299.1 1755.15
#Mann=4,-1,0
  4805.8    0.07       0  5012.3    0.05       0  5016.3    0.07       0
  5261.9     0.1       0
Bank Sta=5012.3,5016.3
Exp/Cntr=0.3,0.1

Type RM Length L Ch R = 1,1407,199,199,199
BEGIN DESCRIPTION:
Stream0655 3.0
END DESCRIPTION:
XS GIS Cut Line= 3
      1948775.00     13906625.00      1948775.00     13906325.00
      1948474.96     13906124.98
#Sta/Elev= 30
  4700.0 1738.48  4702.5 1738.48  4710.0 1736.49  4720.0 1734.73  4730.0 1733.59
  4750.0 1732.04  4820.0 1725.46  4850.0 1723.54  4880.0 1720.70  4930.0 1717.47
  4940.0 1716.09  4995.5 1714.24  4995.7 1713.74  4999.2 1713.74  4999.5 1714.24
  5028.5 1715.07  5068.9 1716.99  5130.5 1721.53  5180.3 1726.37  5208.8 1728.68
  5223.8 1731.23  5244.9 1733.52  5265.9 1736.61  5280.9 1737.57  5296.0 1740.15
  5302.0 1740.53  5317.0 1742.40  5324.5 1743.93  5338.0 1745.41  5360.6 1747.14
#Mann=5,-1,0
  4700.0    0.07       0  4995.5    0.05       0  4999.5    0.07       0
  5068.9   0.035       0  5130.5    0.07       0
Bank Sta=4995.5,4999.5
Exp/Cntr=0.3,0.1

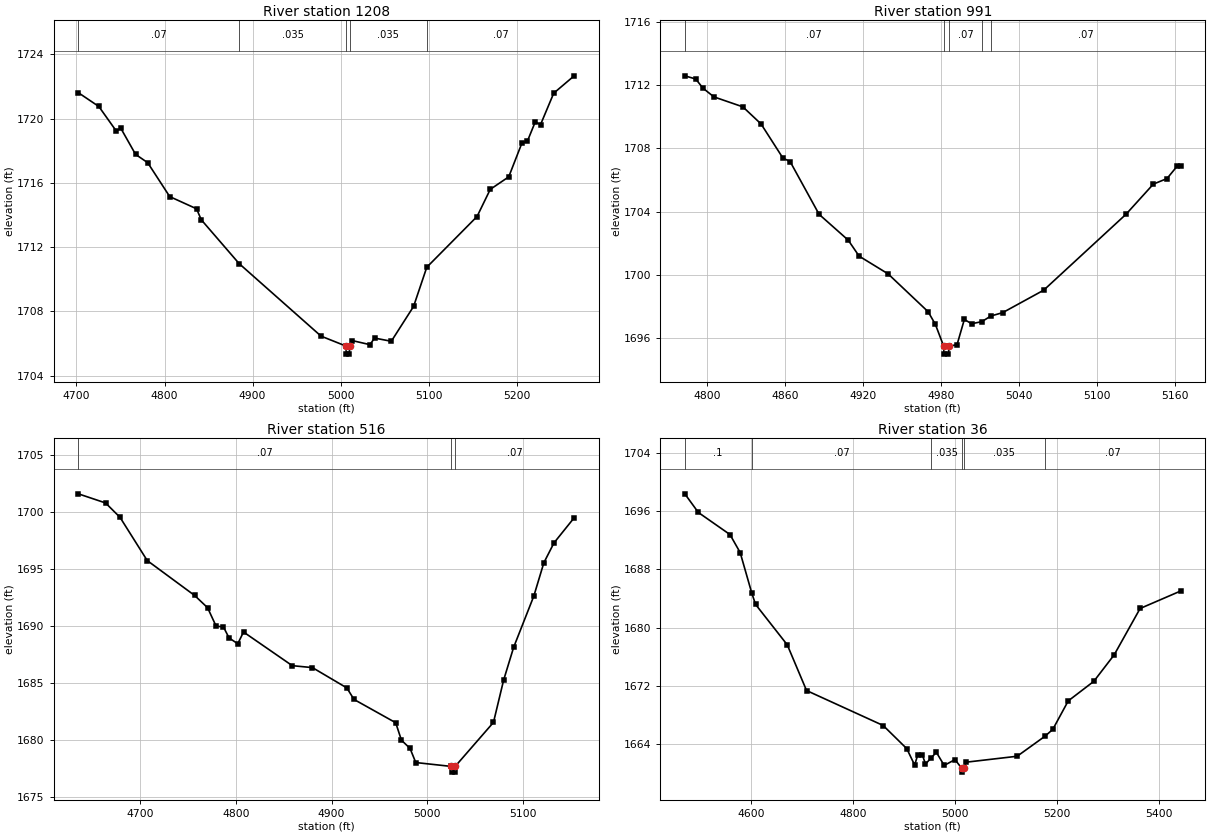
Type RM Length L Ch R = 1,1208,217,217,217
BEGIN DESCRIPTION:
Mapping XS f089f3cf
END DESCRIPTION:
XS GIS Cut Line= 3
      1949036.53     13906495.95      1948913.31     13906162.49
      1948740.52     13906047.24
#Sta/Elev= 30
  4702.1 1721.62  4725.4 1720.76  4745.1 1719.24  4750.4 1719.40  4767.1 1717.78
  4780.9 1717.26  4805.9 1715.15  4836.4 1714.39  4841.7 1713.71  4884.7 1710.98
  4977.8 1706.46  5006.2 1705.84  5006.4 1705.34  5009.9 1705.34  5010.2 1705.84
  5013.5 1706.18  5033.3 1705.93  5038.6 1706.34  5057.6 1706.14  5082.9 1708.31
  5097.9 1710.75  5155.0 1713.91  5170.0 1715.60  5191.0 1716.38  5206.0 1718.49
  5212.1 1718.59  5221.1 1719.80  5227.1 1719.63  5242.1 1721.59  5265.3 1722.67
#Mann=5,-1,0
  4702.1    0.07       0  4884.7   0.035       0  5006.2   0.035       0
  5010.2   0.035       0  5097.9    0.07       0
Bank Sta=5006.2,5010.2
Exp/Cntr=0.3,0.1

Type RM Length L Ch R = 1,991,475,475,475
BEGIN DESCRIPTION:
Stream0655 2.0
END DESCRIPTION:
XS GIS Cut Line= 3
      1949175.01     13906275.01      1949075.00     13906075.00
      1948925.03     13906025.01
#Sta/Elev= 30
  4782.8 1712.59  4791.2 1712.39  4796.8 1711.81  4805.2 1711.26  4827.5 1710.63
  4841.5 1709.55  4858.3 1707.40  4863.9 1707.17  4886.2 1703.84  4908.6 1702.21
  4917.0 1701.20  4939.3 1700.08  4970.1 1697.69  4975.7 1696.89  4982.1 1695.51
  4982.3 1695.01  4985.8 1695.01  4986.1 1695.51  4992.4 1695.61  4998.0 1697.20
  5003.6 1696.93  5011.4 1697.06  5018.5 1697.42  5027.5 1697.63  5059.1 1699.05
  5122.4 1703.84  5143.5 1705.75  5154.0 1706.10  5161.9 1706.89  5164.5 1706.89
#Mann=5,-1,0
  4782.8    0.07       0  4982.1    0.05       0  4986.1    0.07       0
  5011.4   0.035       0  5018.5    0.07       0
Bank Sta=4982.1,4986.1
Exp/Cntr=0.3,0.1

Type RM Length L Ch R = 1,516,480,480,480
BEGIN DESCRIPTION:
Stream0655 1.0
END DESCRIPTION:
XS GIS Cut Line= 3
      1949475.00     13905975.00      1949275.00     13905675.00
      1949124.97     13905624.99
#Sta/Elev= 30
  4635.1 1701.56  4663.6 1700.76  4678.7 1699.50  4707.2 1695.71  4756.8 1692.65
  4770.3 1691.58  4779.3 1689.95  4786.8 1689.91  4792.8 1688.93  4801.9 1688.42
  4807.9 1689.45  4858.9 1686.50  4880.0 1686.33  4916.0 1684.55  4923.5 1683.54
  4967.1 1681.50  4973.1 1679.97  4982.1 1679.25  4988.1 1678.01  5025.3 1677.67
  5025.5 1677.17  5029.0 1677.17  5029.3 1677.67  5069.4 1681.53  5080.0 1685.23
  5090.5 1688.11  5111.6 1692.60  5122.1 1695.52  5132.7 1697.26  5153.8 1699.46
#Mann=3,-1,0
  4635.1    0.07       0  5025.3    0.05       0  5029.3    0.07       0
Bank Sta=5025.3,5029.3
Exp/Cntr=0.3,0.1

Type RM Length L Ch R = 1,36,0,0,0
BEGIN DESCRIPTION:
Stream0655 0.0
END DESCRIPTION:
XS GIS Cut Line= 4
      1949631.77     13905813.41      1949606.74     13905392.48
      1949531.22     13905270.09      1949124.98     13905295.17
#Sta/Elev= 30
  4469.8 1698.38  4496.4 1695.82  4558.4 1692.79  4578.4 1690.32  4600.9 1684.82
  4608.5 1683.21  4670.8 1677.65  4708.6 1671.38  4858.9 1666.58  4905.2 1663.40
  4920.6 1661.15  4926.5 1662.50  4935.5 1662.59  4941.9 1661.29  4952.9 1662.13
  4963.2 1662.90  4978.6 1661.10  4999.8 1661.90  5013.2 1660.68  5013.5 1660.18
  5017.2 1660.68  5021.1 1661.54  5121.7 1662.36  5176.1 1665.10  5191.5 1666.04
  5221.9 1669.96  5272.0 1672.64  5312.0 1676.28  5362.8 1682.64  5442.3 1685.04
#Mann=6,-1,0
  4469.8     0.1       0  4600.9    0.07       0  4952.9   0.035       0
  5013.2   0.035       0  5017.2   0.035       0  5176.1    0.07       0
Bank Sta=5013.2,5017.2
Exp/Cntr=0.3,0.1

Chan Stop Cuts=-1