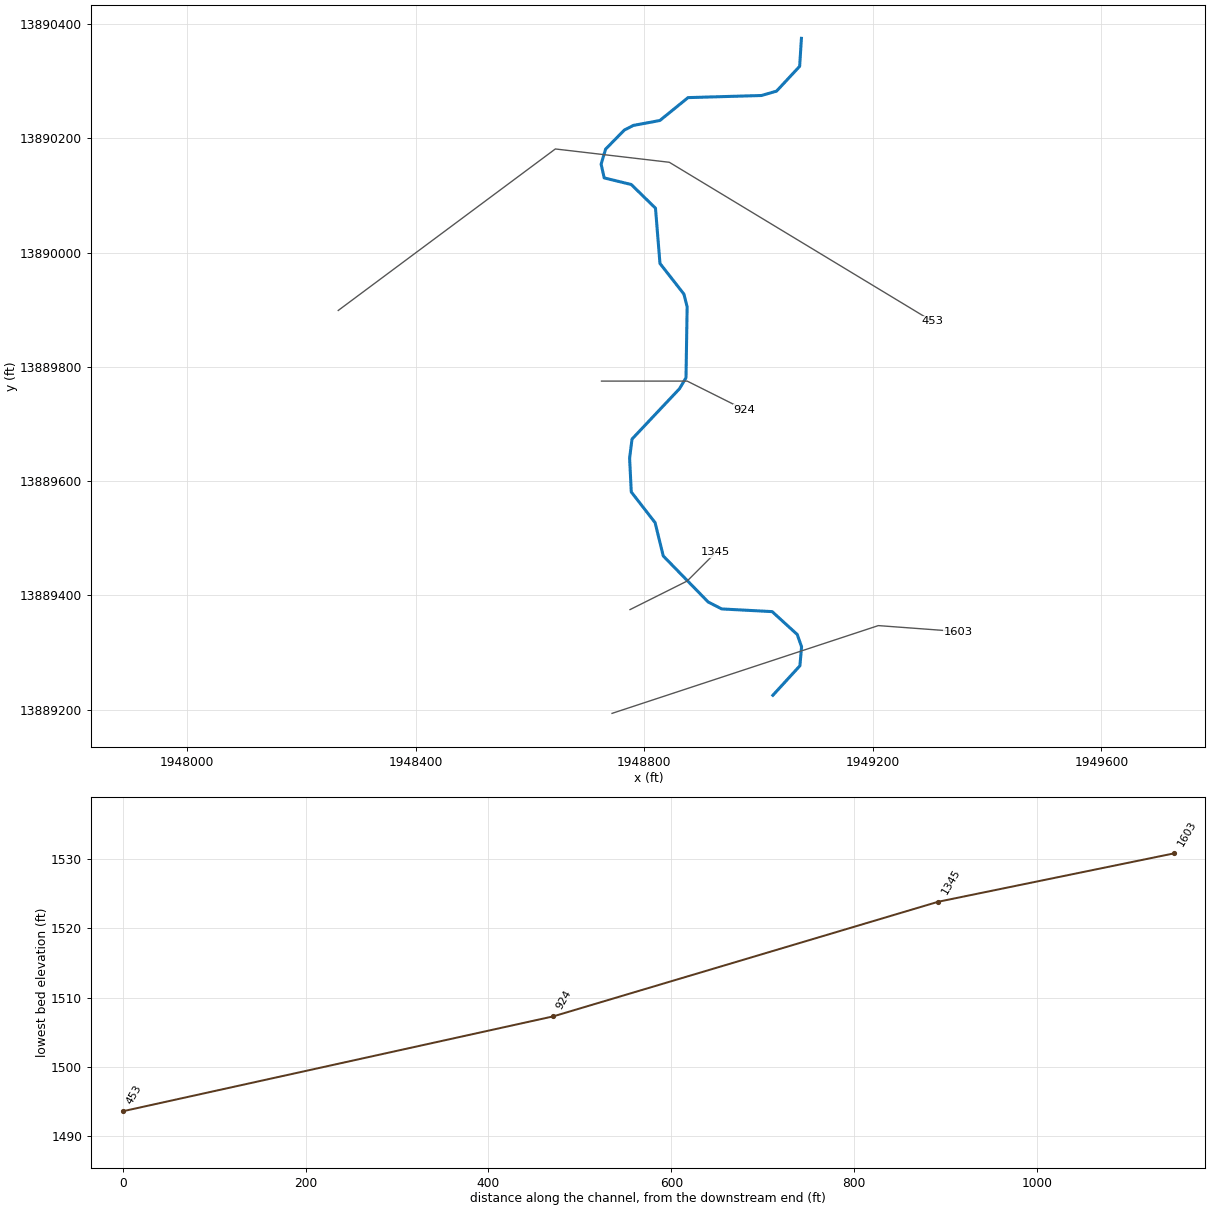
--- Stream0658.prj (project) ---

Proj Title=Stream0658 Base Level Engineering
Current Plan=p01
Default Exp/Contr=0.3,0.1
English Units
Geom File=g01
Flow File=f01
Plan File=p01
Y Axis Title=Elevation
X Axis Title(PF)=Main Channel Distance
X Axis Title(XS)=Station
BEGIN DESCRIPTION:
Stream0658
END DESCRIPTION:
DSS Export Rating Curves= 0
DSS Export Rating Curve Sorted= 0
DSS Export Volume Flow Curves= 0
DXF OffsetX= 0
DXF OffsetY= 0
DXF ScaleX= 1
DXF ScaleY= 10

--- Stream0658.p01 (plan) ---

Plan Title=Multiple Run
Short Identifier=Multiple
Geom File=g01
Flow File=f01
Subcritical Flow
K Sum by GR= 0
Std Step Tol= 0.01
Critical Tol= 0.01
Num of Std Step Trials= 20
Max Error Tol= 0.3
Flow Tol Ratio= 0.001
Split Flow NTrial= 30
Split Flow Tol= 0.02
Split Flow Ratio= 0.02
Log Output Level= 0
Friction Slope Method= 1
Unsteady Friction Slope Method= 2
Unsteady Bridges Friction Slope Method= 1
Parabolic Critical Depth
Global Vel Dist=  1 , 1 , 1
Global Log Level= 0
CheckData=True
Encroach Param= -1, 0, 0, 0
BEGIN DESCRIPTION:
Multiple Run
END DESCRIPTION:

--- Stream0658.f01 (steady flow) ---

Flow Title=Multiple
Number of Profiles=7
Profile Names=10-year,25-year,50-year,1pct_min,100-year,1pct_plu,500-year
River Rch & RM= Stream0658,Reach-1,1603
     599     982    1335     882    1759    3510    3004
Boundary for River Rch & Prof#=Stream0658,Reach-1,1
Up Type=0
Dn Type=3
Dn Slope=0.005
Boundary for River Rch & Prof#=Stream0658,Reach-1,2
Up Type=0
Dn Type=3
Dn Slope=0.005
Boundary for River Rch & Prof#=Stream0658,Reach-1,3
Up Type=0
Dn Type=3
Dn Slope=0.005
Boundary for River Rch & Prof#=Stream0658,Reach-1,4
Up Type=0
Dn Type=3
Dn Slope=0.005
Boundary for River Rch & Prof#=Stream0658,Reach-1,5
Up Type=0
Dn Type=3
Dn Slope=0.005
Boundary for River Rch & Prof#=Stream0658,Reach-1,6
Up Type=0
Dn Type=3
Dn Slope=0.005
Boundary for River Rch & Prof#=Stream0658,Reach-1,7
Up Type=0
Dn Type=3
Dn Slope=0.005

--- Stream0658.g01 (geometry) ---

Geom Title=Existing Conditions
Program Version=4.10

River Reach=Stream0658      ,Reach-1
Reach XY= 30
        1949025.       13889225.      1949072.35     13889276.66
      1949075.25      13889309.9      1949067.67     13889331.44
      1949023.77     13889371.48      1948935.48     13889376.17
      1948911.67     13889388.39      1948833.13     13889468.92
      1948818.85     13889527.17      1948777.14     13889580.97
      1948774.23     13889640.09      1948778.47      13889673.5
       1948861.6      13889761.7      1948872.94     13889780.86
      1948874.95     13889904.96      1948869.26     13889927.33
      1948827.36     13889980.98      1948819.54     13890077.66
      1948777.11     13890119.13      1948729.76     13890130.66
      1948724.38     13890154.69      1948732.22     13890181.04
      1948764.86     13890214.32      1948780.79     13890222.56
      1948827.14     13890231.15      1948876.56     13890271.24
      1949005.09     13890274.93      1949031.47     13890282.59
      1949071.88     13890325.98        1949075.       13890375.

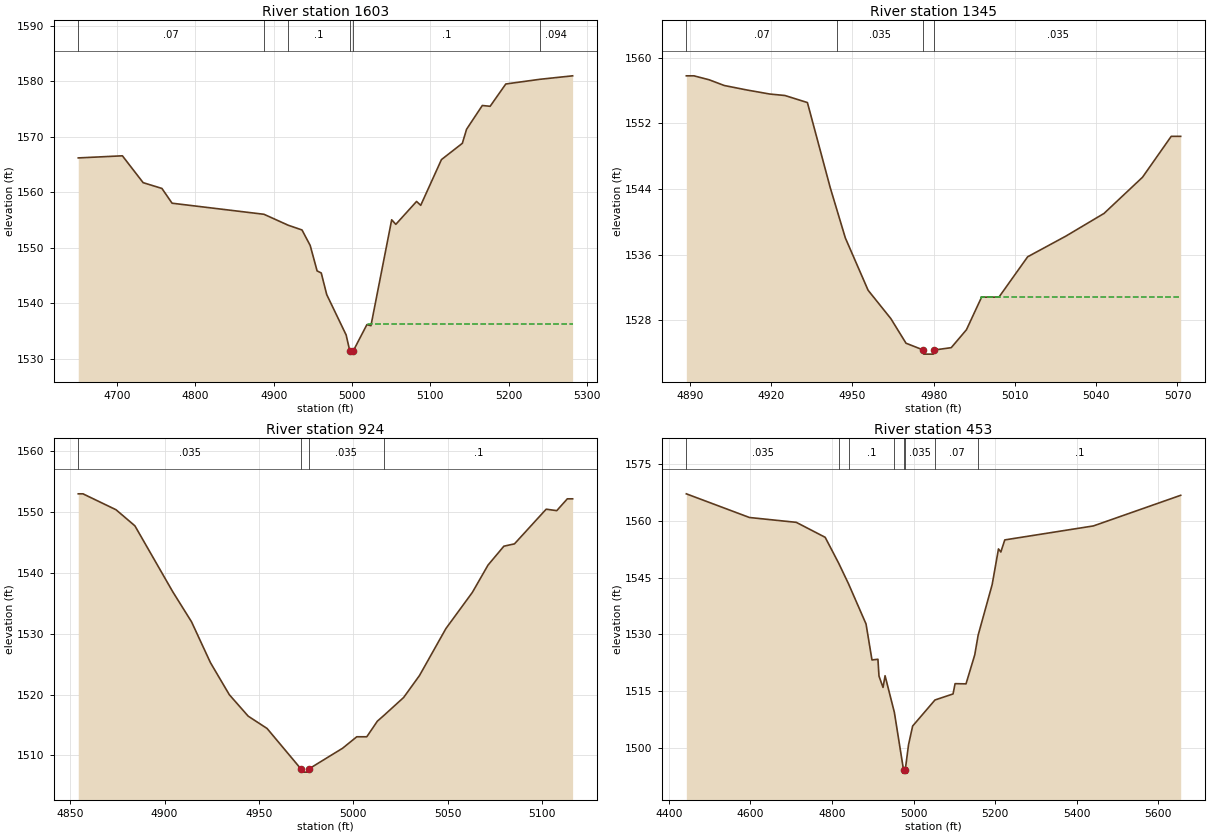
Type RM Length L Ch R = 1 ,1603    ,258,258,258
BEGIN DESCRIPTION:
Stream0658 4.0
END DESCRIPTION:
XS GIS Cut Line= 3
      1948743.47     13889193.35      1949209.64       13889347.
      1949350.12     13889336.59
#Sta/Elev= 30
  4650.2 1566.18  4706.6 1566.56  4733.1 1561.73  4757.1 1560.69  4770.1 1558.03
  4887.5 1556.04  4918.5 1554.07  4936.1 1553.22  4946.6 1550.42  4955.4 1545.85
  4960.7 1545.48  4967.7 1541.59  4992.5 1534.33  4997.3 1531.38  4997.5 1530.88
  5001.3 1531.38    5019 1536.18  5024.2    1536  5050.7 1555.05    5056 1554.23
  5082.5 1558.35  5087.8 1557.65  5114.3 1565.88    5141 1568.81  5146.4 1571.34
  5166.5 1575.61  5176.5 1575.47  5196.5 1579.48  5239.7 1580.32  5281.9 1580.95
#Mann= 6 ,-1 , 0
  4650.2     .07       0  4887.5    .035       0  4918.5      .1       0
  4997.3     .05       0  5001.3      .1       0  5239.7    .094       0
#XS Ineff= 2 , 0
                         5019.86         1536.23
Permanent Ineff=
       F       F
Bank Sta=4997.3,5001.3
XS Rating Curve= 0 ,0
Exp/Cntr=0.3,0.1

Type RM Length L Ch R = 1 ,1345    ,421,421,421
BEGIN DESCRIPTION:
Stream0658 3.0
END DESCRIPTION:
XS GIS Cut Line= 3
      1948774.98     13889374.99        1948875.       13889425.
      1948924.98     13889474.98
#Sta/Elev= 29
  4888.7 1557.81  4891.5 1557.81  4897.1 1557.33  4902.7 1556.63  4911.1 1556.08
  4919.5 1555.59  4925.1 1555.41  4933.4 1554.55  4941.8  1544.2  4944.4 1541.34
  4947.4 1538.04  4955.8 1531.66  4964.2  1528.2  4969.8  1525.2  4976.2 1524.37
  4976.4 1523.87  4979.9 1523.87  4980.2 1524.37  4986.5 1524.66  4992.1 1526.84
  4997.7 1530.82  5000.5 1530.82  5004.1 1530.82  5014.7 1535.74  5028.8 1538.26
  5042.9 1541.03  5057.1 1545.44  5067.7 1550.43  5071.2 1550.43
#Mann= 4 ,-1 , 0
  4888.7     .07       0  4944.4    .035       0  4976.2    .035       0
  4980.2    .035       0
#XS Ineff= 2 , 0
                         4997.46         1530.86
Permanent Ineff=
       F       F
Bank Sta=4976.2,4980.2
XS Rating Curve= 0 ,0
Exp/Cntr=0.3,0.1

Type RM Length L Ch R = 1 ,924     ,471,471,471
BEGIN DESCRIPTION:
Stream0658 2.0
END DESCRIPTION:
XS GIS Cut Line= 3
      1948725.03       13889775.        1948875.       13889775.
      1948975.03     13889724.99
#Sta/Elev= 30
  4854.3 1552.92  4856.8 1552.92  4874.3 1550.31  4884.3 1547.67  4904.3 1536.88
  4914.3 1531.92  4924.3 1525.23  4934.3 1519.97  4944.3 1516.45  4954.3 1514.43
  4972.3 1507.77  4972.5 1507.27    4976 1507.27  4976.3 1507.77  4994.3 1511.19
  5001.8 1513.07  5007.1 1513.07  5012.7 1515.63  5016.2 1516.58  5026.6 1519.51
    5035 1523.11    5049 1530.82    5063 1536.75  5071.3 1541.23  5079.7 1544.33
  5085.3 1544.71  5102.1  1550.4  5107.7 1550.16  5113.3  1552.1  5116.1  1552.1
#Mann= 4 ,-1 , 0
  4854.3    .035       0  4972.3    .035       0  4976.3    .035       0
  5016.2      .1       0
Bank Sta=4972.3,4976.3
XS Rating Curve= 0 ,0
Exp/Cntr=0.3,0.1

Type RM Length L Ch R = 1 ,453     ,0,0,0
BEGIN DESCRIPTION:
Stream0658 1.0
END DESCRIPTION:
XS GIS Cut Line= 4
       1948264.2     13889898.67      1948644.25     13890181.35
      1948843.74     13890158.04      1949304.02      13889879.7
#Sta/Elev= 30
  4442.7  1567.2  4597.6 1560.93  4712.3 1559.65  4783.2 1555.69  4816.4 1548.82
  4840.4 1543.39  4883.4 1532.75    4898 1523.22  4912.6  1523.4  4915.2 1518.94
  4925.1 1515.94  4930.1 1519.04  4952.9 1509.34  4975.5 1494.02  4975.8 1493.52
  4979.5 1494.02  4987.6 1500.76  4997.7 1505.72  5052.5 1512.62  5096.8 1514.22
  5101.8 1516.94  5128.6 1516.89    5150 1524.56  5158.4  1529.8  5192.7 1543.16
  5208.2 1552.61    5214  1551.8  5223.7    1555    5441  1558.7  5655.1 1566.81
#Mann= 8 ,-1 , 0
  4442.7    .035       0  4816.4     .07       0  4840.4      .1       0
  4952.9    .035       0  4975.5    .035       0  4979.5    .035       0
  5052.5     .07       0  5158.4      .1       0
Bank Sta=4975.5,4979.5
XS Rating Curve= 0 ,0
Exp/Cntr=0.3,0.1

Chan Stop Cuts=-1
Use User Specified Reach Order=0
Composite Channel Slope=5