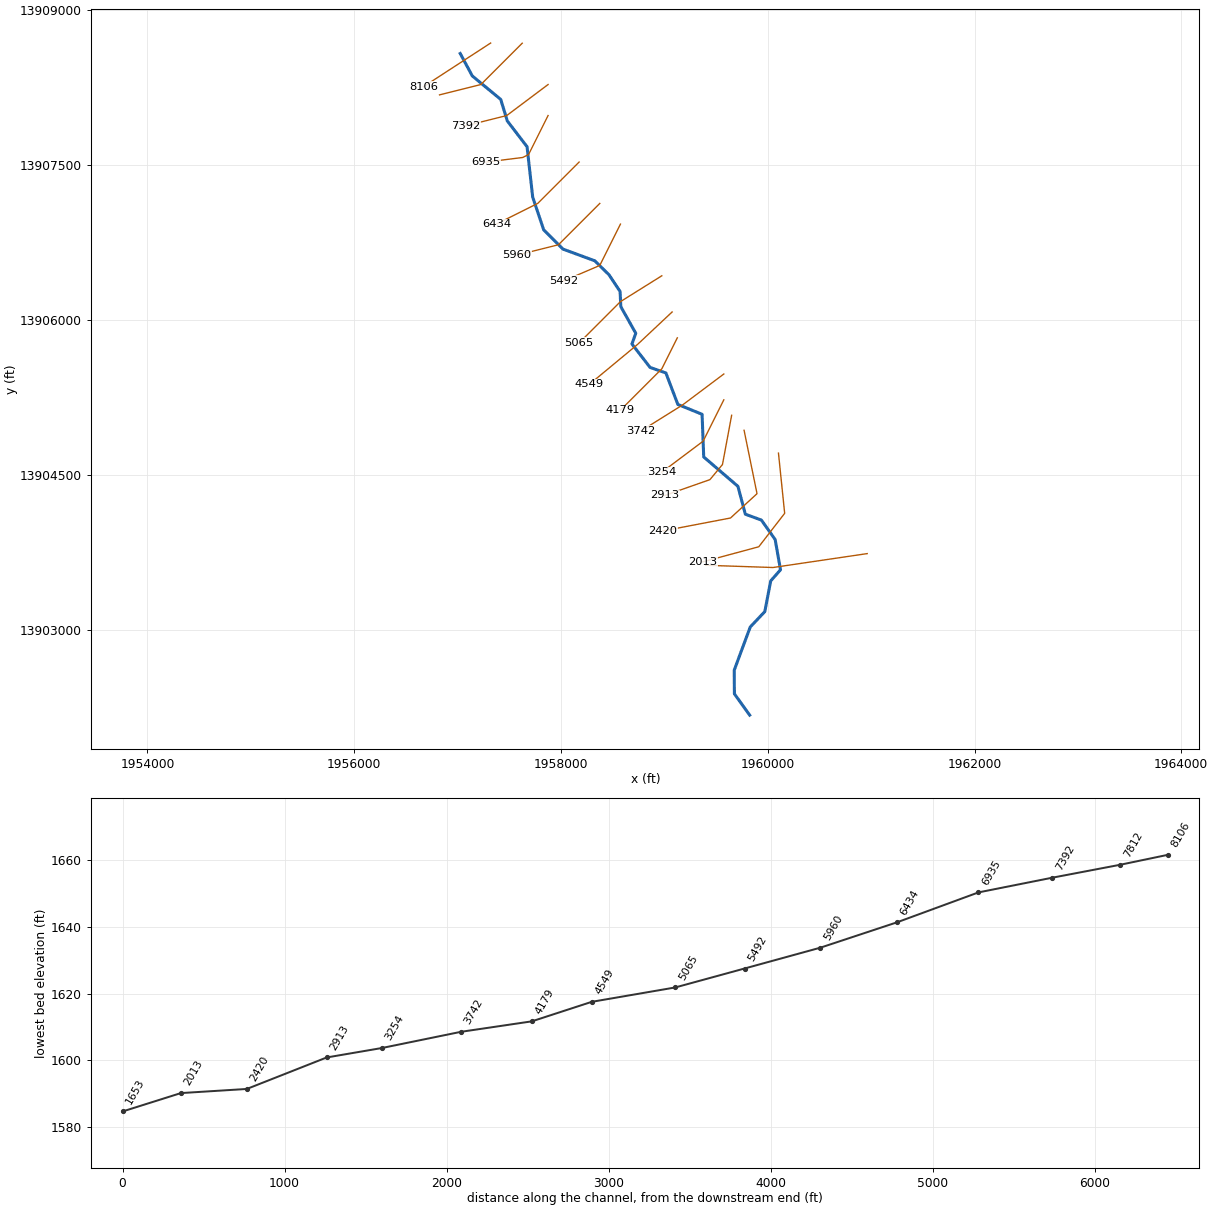
--- Stream0659.prj (project) ---

Proj Title=Stream0659 Base Level Engineering
Current Plan=p01
Default Exp/Contr=0.3,0.1
English Units
Geom File=g01
Flow File=f01
Plan File=p01
BEGIN DESCRIPTION:
Stream0659
END DESCRIPTION:

--- Stream0659.p01 (plan) ---

Plan Title=Multiple Run
Short Identifier=Multiple
Geom File=g01
Flow File=f01
Subcritical Flow
K Sum by GR= 0
Std Step Tol= 0.01
Critical Tol= 0.01
Num of Std Step Trials= 20
Max Error Tol= 0.3
Flow Tol Ratio= 0.001
Split Flow NTrial= 30
Split Flow Tol= 0.02
Split Flow Ratio= 0.02
Log Output Level= 0
Friction Slope Method= 1
Unsteady Friction Slope Method= 2
Unsteady Bridges Friction Slope Method= 1
Parabolic Critical Depth
Global Vel Dist=  1 , 1 , 1
Global Log Level= 0
CheckData=True
Encroach Param= -1, 0, 0, 0
BEGIN DESCRIPTION:
Multiple Run
END DESCRIPTION:

--- Stream0659.f01 (steady flow) ---

Flow Title=Multiple
Number of Profiles=7
Profile Names=10-year,25-year,50-year,1pct_min,100-year,1pct_plu,500-year
River Rch & RM= Stream0659,Reach-1,8106
    2217    3914    5585    3845    7672   15308   14307
Boundary for River Rch & Prof#=Stream0659,Reach-1,1
Up Type=0
Dn Type=3
Dn Slope=0.005
Boundary for River Rch & Prof#=Stream0659,Reach-1,2
Up Type=0
Dn Type=3
Dn Slope=0.005
Boundary for River Rch & Prof#=Stream0659,Reach-1,3
Up Type=0
Dn Type=3
Dn Slope=0.005
Boundary for River Rch & Prof#=Stream0659,Reach-1,4
Up Type=0
Dn Type=3
Dn Slope=0.005
Boundary for River Rch & Prof#=Stream0659,Reach-1,5
Up Type=0
Dn Type=3
Dn Slope=0.005
Boundary for River Rch & Prof#=Stream0659,Reach-1,6
Up Type=0
Dn Type=3
Dn Slope=0.005
Boundary for River Rch & Prof#=Stream0659,Reach-1,7
Up Type=0
Dn Type=3
Dn Slope=0.005

--- Stream0659.g01 (geometry) ---

Geom Title=Existing Conditions

River Reach=Stream0659,Reach-1
Reach XY= 30
      1957025.00     13908575.00      1957141.64     13908358.29
      1957416.86     13908131.06      1957480.54     13907922.58
      1957671.45     13907673.53      1957726.22     13907185.50
      1957832.86     13906868.83      1958018.94     13906683.14
      1958327.43     13906569.48      1958464.22     13906434.68
      1958571.45     13906273.53      1958578.56     13906126.47
      1958723.14     13905868.87      1958686.13     13905764.96
      1958861.67     13905538.39      1959014.39     13905485.06
      1959130.25     13905180.44      1959364.68     13905085.17
      1959380.46     13904672.55      1959711.39     13904388.21
      1959782.98     13904118.63      1959938.65     13904061.74
      1960071.45     13903873.53      1960123.37     13903581.04
      1960028.56     13903473.53      1959971.39     13903176.50
      1959830.52     13903027.43      1959675.52     13902609.78
      1959677.24     13902380.93      1959825.00     13902175.00

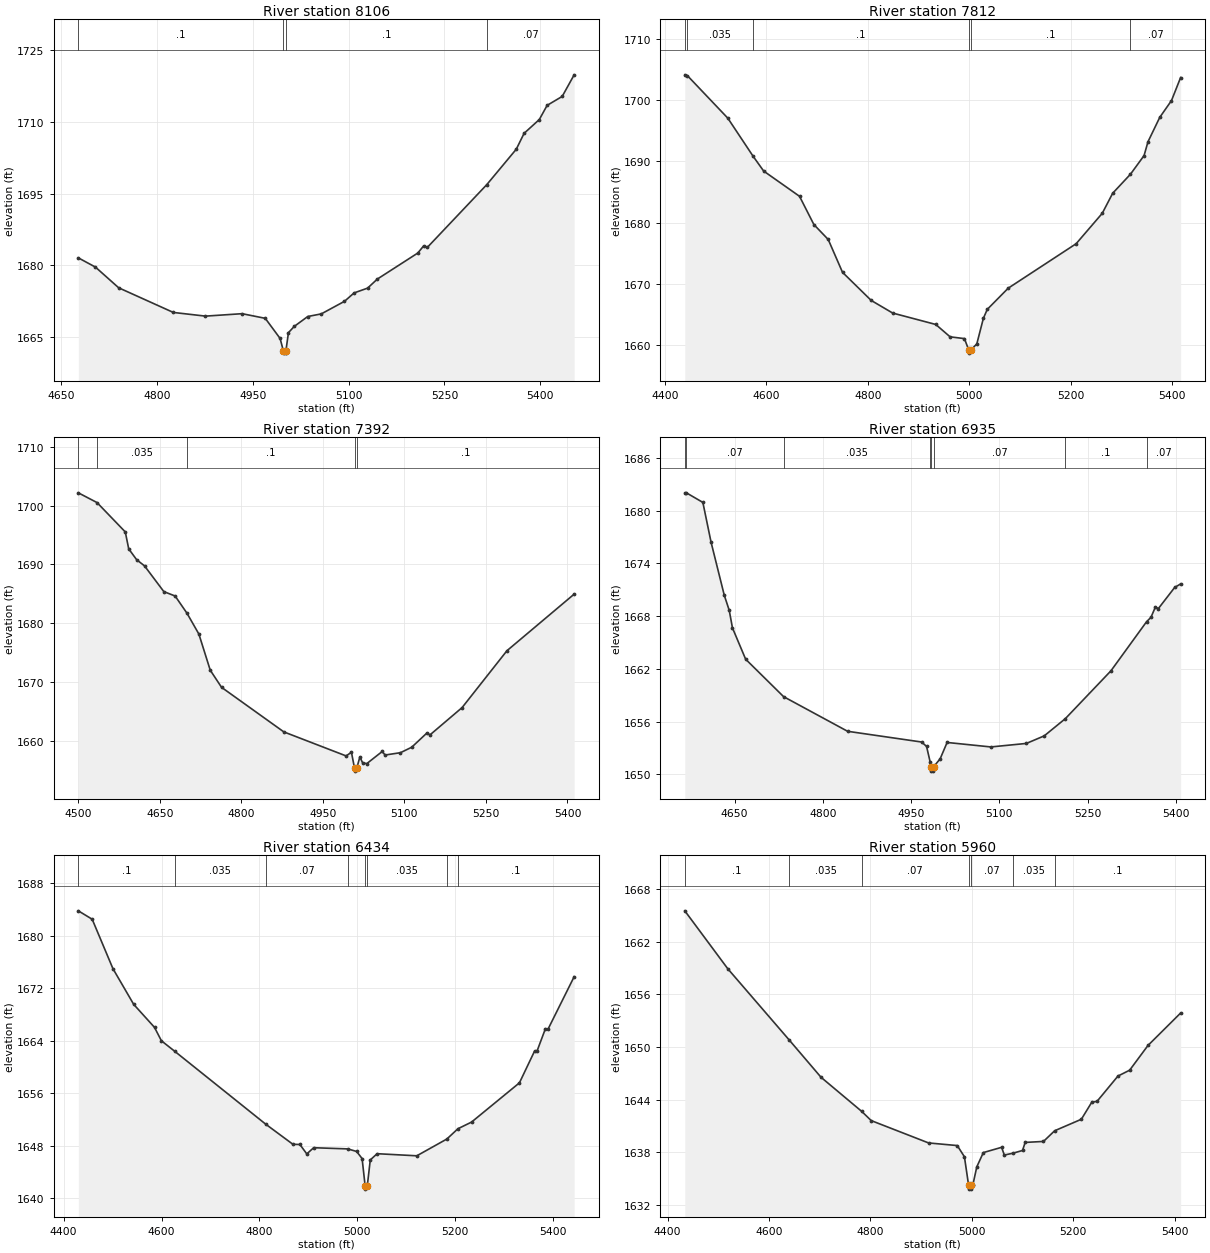
Type RM Length L Ch R = 1,8106,294,294,294
BEGIN DESCRIPTION:
Stream0659 12.0
END DESCRIPTION:
XS GIS Cut Line= 2
      1957319.61     13908676.50      1956669.31     13908253.81
#Sta/Elev= 30
  4677.3 1681.57  4704.1 1679.64  4740.4 1675.32  4825.9 1670.17  4876.2 1669.40
  4933.5 1669.91  4969.7 1668.94  4992.9 1664.74  4998.0 1662.17  4998.3 1661.67
  5001.8 1661.67  5002.0 1662.17  5006.0 1665.95  5015.1 1667.26  5036.2 1669.32
  5057.4 1669.87  5093.6 1672.49  5108.7 1674.25  5129.8 1675.25  5145.0 1677.14
  5208.3 1682.58  5217.4 1684.06  5223.4 1683.78  5316.3 1696.88  5362.4 1704.28
  5374.6 1707.59  5398.4 1710.47  5410.6 1713.43  5434.2 1715.30  5452.9 1719.81
#Mann=4,-1,0
  4677.3     0.1       0  4998.0    0.05       0  5002.0     0.1       0
  5316.3    0.07       0
Bank Sta=4998,5002
Exp/Cntr=0.3,0.1

Type RM Length L Ch R = 1,7812,420,420,420
BEGIN DESCRIPTION:
Stream0659 11.0
END DESCRIPTION:
XS GIS Cut Line= 3
      1957625.01     13908675.01      1957225.00     13908275.00
      1956825.01     13908175.00
#Sta/Elev= 30
  4439.1 1704.12  4444.2 1703.99  4524.0 1697.04  4573.9 1690.82  4594.7 1688.41
  4665.4 1684.29  4693.7 1679.68  4722.0 1677.24  4750.2 1671.88  4806.8 1667.29
  4849.2 1665.23  4934.1 1663.37  4962.4 1661.35  4990.7 1661.06  4999.2 1659.19
  4999.5 1658.69  5003.3 1659.19  5015.1 1660.20  5028.0 1664.36  5035.7 1665.83
  5077.0 1669.29  5211.0 1676.55  5262.5 1681.51  5283.1 1684.79  5318.1 1687.89
  5345.0 1690.94  5352.7 1693.19  5375.9 1697.17  5399.1 1699.92  5417.1 1703.68
#Mann=6,-1,0
  4439.1     0.1       0  4444.2   0.035       0  4573.9     0.1       0
  4999.2    0.05       0  5003.3     0.1       0  5318.1    0.07       0
Bank Sta=4999.2,5003.3
Exp/Cntr=0.3,0.1

Type RM Length L Ch R = 1,7392,457,457,457
BEGIN DESCRIPTION:
Stream0659 10.0
END DESCRIPTION:
XS GIS Cut Line= 3
      1957874.97     13908274.98      1957475.00     13907975.00
      1957074.98     13907874.99
#Sta/Elev= 30
  4500.0 1702.19  4534.4 1700.53  4586.4 1695.53  4592.7 1692.65  4607.3 1690.80
  4621.8 1689.75  4657.3 1685.37  4678.1 1684.62  4699.9 1681.69  4721.8 1678.14
  4742.7 1671.99  4763.5 1669.07  4878.1 1661.48  4992.7 1657.39  5002.5 1658.01
  5008.2 1655.30  5008.5 1654.80  5012.3 1655.30  5018.0 1657.22  5023.2 1656.19
  5030.9 1656.09  5059.2 1658.15  5064.4 1657.54  5092.7 1657.94  5113.4 1658.87
  5141.7 1661.32  5146.9 1660.96  5206.1 1665.62  5288.6 1675.30  5412.3 1684.94
#Mann=5,-1,0
  4500.0     0.1       0  4534.4   0.035       0  4699.9     0.1       0
  5008.2    0.05       0  5012.3     0.1       0
Bank Sta=5008.2,5012.3
Exp/Cntr=0.3,0.1

Type RM Length L Ch R = 1,6935,501,501,501
BEGIN DESCRIPTION:
Stream0659 9.0
END DESCRIPTION:
XS GIS Cut Line= 4
      1957874.99     13907974.99      1957686.16     13907597.31
      1957628.76     13907569.22      1957274.97     13907525.00
#Sta/Elev= 30
  4565.5 1682.02  4568.2 1682.02  4596.2 1680.93  4610.2 1676.39  4632.6 1670.37
  4641.0 1668.66  4646.5 1666.66  4668.9 1663.10  4733.4 1658.84  4842.2 1654.90
  4968.0 1653.68  4976.4 1653.18  4982.7 1651.36  4984.2 1650.87  4984.5 1650.37
  4988.1 1650.37  4988.4 1650.87  4999.5 1651.77  5011.3 1653.63  5085.7 1653.12
  5146.1 1653.52  5176.4 1654.38  5212.3 1656.34  5289.8 1661.78  5350.3 1667.36
  5357.8 1667.86  5365.3 1669.03  5370.4 1668.86  5398.1 1671.26  5408.2 1671.66
#Mann=8,-1,0
  4565.5   0.035       0  4568.2    0.07       0  4733.4   0.035       0
  4982.7    0.07       0  4984.2    0.05       0  4988.4    0.07       0
  5212.3     0.1       0  5350.3    0.07       0
Bank Sta=4984.2,4988.4
Exp/Cntr=0.3,0.1

Type RM Length L Ch R = 1,6434,474,474,474
BEGIN DESCRIPTION:
Stream0659 8.0
END DESCRIPTION:
XS GIS Cut Line= 3
      1958175.01     13907525.01      1957775.00     13907125.00
      1957375.01     13906925.00
#Sta/Elev= 30
  4430.1 1683.76  4458.4 1682.48  4500.8 1674.96  4543.2 1669.53  4585.7 1666.03
  4599.8 1663.99  4626.7 1662.41  4813.1 1651.29  4868.5 1648.24  4882.7 1648.21
  4896.8 1646.78  4910.9 1647.72  4980.5 1647.54  4998.6 1647.15  5009.8 1646.07
  5016.0 1641.92  5016.3 1641.42  5020.4 1641.92  5026.5 1645.86  5040.5 1646.81
  5121.6 1646.49  5182.9 1649.04  5205.6 1650.61  5233.4 1651.62  5331.2 1657.59
  5362.0 1662.40  5367.5 1662.49  5384.3 1665.83  5389.9 1665.80  5443.0 1673.74
#Mann=8,-1,0
  4430.1     0.1       0  4626.7   0.035       0  4813.1    0.07       0
  4980.5   0.035       0  5016.0   0.035       0  5020.4   0.035       0
  5182.9    0.07       0  5205.6     0.1       0
Bank Sta=5016,5020.4
Exp/Cntr=0.3,0.1

Type RM Length L Ch R = 1,5960,468,468,468
BEGIN DESCRIPTION:
Stream0659 7.0
END DESCRIPTION:
XS GIS Cut Line= 3
      1958374.97     13907124.97      1957975.00     13906725.00
      1957575.05     13906625.01
#Sta/Elev= 30
  4434.1 1665.54  4518.9 1658.93  4640.1 1650.80  4702.8 1646.55  4783.2 1642.65
  4801.7 1641.61  4914.9 1639.06  4971.5 1638.76  4985.6 1637.48  4993.7 1634.29
  4994.1 1633.79  4998.3 1633.79  4998.7 1634.29  5002.3 1634.29  5010.0 1636.33
  5022.9 1637.96  5059.0 1638.56  5064.2 1637.68  5080.8 1637.88  5100.2 1638.20
  5105.4 1639.12  5141.5 1639.23  5163.6 1640.45  5216.2 1641.76  5236.8 1643.71
  5247.1 1643.80  5288.4 1646.69  5311.5 1647.36  5347.6 1650.18  5412.0 1653.88
#Mann=7,-1,0
  4434.1     0.1       0  4640.1   0.035       0  4783.2    0.07       0
  4993.7    0.05       0  4998.7    0.07       0  5080.8   0.035       0
  5163.6     0.1       0
Bank Sta=4993.7,4998.7
Exp/Cntr=0.3,0.1

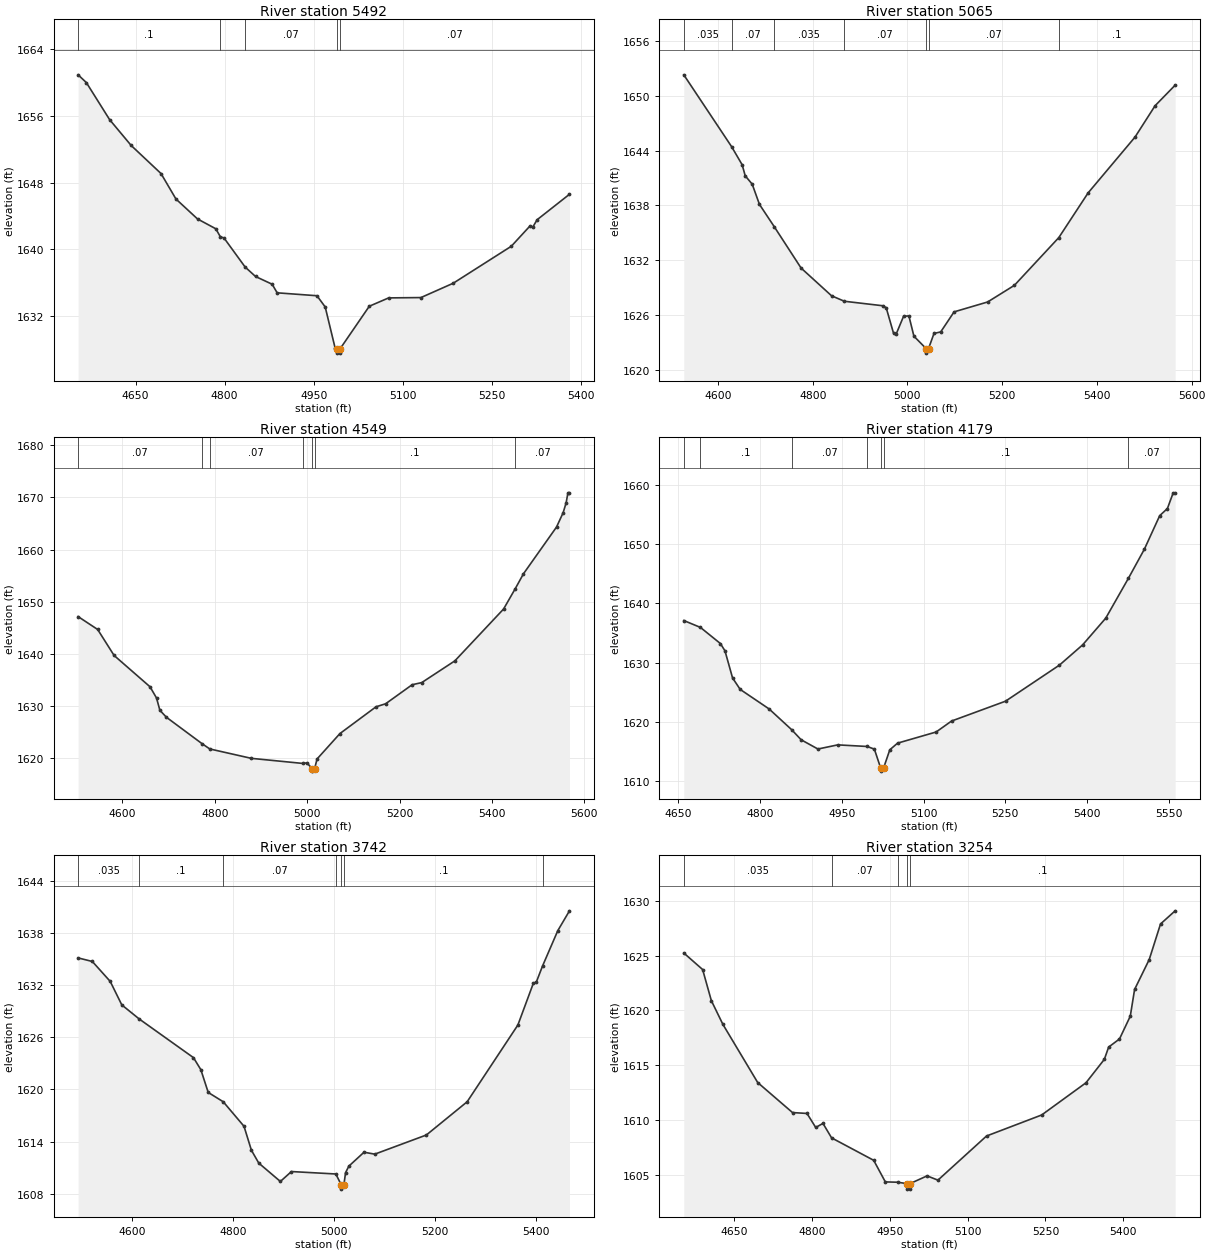
Type RM Length L Ch R = 1,5492,427,427,427
BEGIN DESCRIPTION:
Stream0659 6.0
END DESCRIPTION:
XS GIS Cut Line= 3
      1958574.98     13906924.97      1958375.00     13906525.00
      1958024.97     13906374.99
#Sta/Elev= 30
  4553.1 1660.95  4567.0 1660.02  4606.2 1655.57  4642.5 1652.47  4692.8 1649.10
  4718.0 1646.04  4754.3 1643.65  4785.1 1642.47  4792.8 1641.51  4799.0 1641.36
  4834.5 1637.88  4852.1 1636.74  4880.1 1635.81  4888.5 1634.78  4955.6 1634.43
  4969.5 1633.08  4986.3 1628.12  4989.4 1628.04  4989.8 1627.54  4994.0 1627.54
  4994.4 1628.04  5043.8 1633.17  5076.4 1634.17  5130.8 1634.21  5185.2 1635.93
  5283.1 1640.37  5314.0 1642.76  5319.4 1642.69  5326.7 1643.56  5381.1 1646.61
#Mann=5,-1,0
  4553.1     0.1       0  4792.8   0.035       0  4834.5    0.07       0
  4989.4    0.05       0  4994.4    0.07       0
Bank Sta=4989.4,4994.4
Exp/Cntr=0.3,0.1

Type RM Length L Ch R = 1,5065,516,516,516
BEGIN DESCRIPTION:
Stream0659 5.0
END DESCRIPTION:
XS GIS Cut Line= 3
      1958974.96     13906424.97      1958575.00     13906175.00
      1958175.03     13905775.03
#Sta/Elev= 30
  4527.9 1652.28  4628.8 1644.43  4651.1 1642.45  4657.6 1641.24  4672.3 1640.33
  4687.6 1638.12  4718.6 1635.70  4775.5 1631.16  4839.8 1628.13  4866.8 1627.53
  4949.4 1627.03  4955.3 1626.80  4970.7 1624.03  4976.6 1623.99  4991.9 1625.89
  5003.1 1625.93  5013.7 1623.71  5039.4 1622.36  5039.8 1621.86  5044.6 1622.36
  5056.1 1624.01  5070.3 1624.18  5098.5 1626.37  5169.3 1627.45  5225.8 1629.27
  5319.6 1634.49  5381.4 1639.37  5480.4 1645.47  5522.8 1648.90  5565.2 1651.15
#Mann=7,-1,0
  4527.9   0.035       0  4628.8    0.07       0  4718.6   0.035       0
  4866.8    0.07       0  5039.4    0.05       0  5044.6    0.07       0
  5319.6     0.1       0
Bank Sta=5039.4,5044.6
Exp/Cntr=0.3,0.1

Type RM Length L Ch R = 1,4549,370,370,370
BEGIN DESCRIPTION:
Stream0659 4.0
END DESCRIPTION:
XS GIS Cut Line= 3
      1959074.99     13906074.99      1958739.68     13905760.26
      1958275.00     13905375.00
#Sta/Elev= 30
  4504.2 1647.16  4546.5 1644.69  4582.1 1639.71  4659.8 1633.71  4673.9 1631.56
  4681.2 1629.20  4695.4 1627.86  4772.5 1622.80  4789.2 1621.79  4879.1 1619.99
  4990.0 1619.02  4999.2 1619.12  5011.0 1618.04  5011.4 1617.54  5016.2 1618.04
  5021.4 1619.87  5070.9 1624.74  5149.0 1629.87  5169.8 1630.45  5227.2 1634.10
  5248.0 1634.51  5319.6 1638.67  5425.1 1648.61  5450.5 1652.53  5468.1 1655.36
  5539.7 1664.32  5554.0 1667.07  5560.5 1668.97  5564.4 1670.88  5567.7 1670.88
#Mann=7,-1,0
  4504.2    0.07       0  4772.5   0.035       0  4789.2    0.07       0
  4990.0     0.1       0  5011.0    0.05       0  5016.2     0.1       0
  5450.5    0.07       0
Bank Sta=5011,5016.2
Exp/Cntr=0.3,0.1

Type RM Length L Ch R = 1,4179,437,437,437
BEGIN DESCRIPTION:
Stream0659 3.0
END DESCRIPTION:
XS GIS Cut Line= 3
      1959124.99     13905824.99      1958975.00     13905525.00
      1958574.99     13905124.99
#Sta/Elev= 30
  4660.4 1637.09  4690.9 1635.93  4727.5 1633.21  4735.9 1631.98  4749.8 1627.41
  4763.8 1625.47  4816.9 1622.17  4858.0 1618.69  4875.6 1616.97  4906.4 1615.41
  4942.7 1616.11  4996.7 1615.84  5009.9 1615.39  5021.5 1612.18  5021.9 1611.68
  5026.7 1612.18  5038.2 1615.28  5052.4 1616.40  5123.1 1618.28  5151.4 1620.13
  5250.4 1623.48  5349.3 1629.57  5391.8 1632.98  5434.2 1637.49  5475.8 1644.22
  5504.9 1649.10  5533.2 1654.79  5547.3 1655.99  5557.9 1658.64  5561.5 1658.64
#Mann=7,-1,0
  4660.4    0.07       0  4690.9     0.1       0  4858.0    0.07       0
  4996.7     0.1       0  5021.5    0.05       0  5026.7     0.1       0
  5475.8    0.07       0
Bank Sta=5021.5,5026.7
Exp/Cntr=0.3,0.1

Type RM Length L Ch R = 1,3742,488,488,488
BEGIN DESCRIPTION:
Stream0659 2.0
END DESCRIPTION:
XS GIS Cut Line= 3
      1959574.99     13905474.99      1959175.00     13905175.00
      1958774.99     13904924.99
#Sta/Elev= 30
  4493.7 1635.11  4521.8 1634.70  4557.2 1632.41  4580.1 1629.71  4614.6 1628.09
  4721.8 1623.65  4736.4 1622.27  4751.0 1619.65  4780.7 1618.58  4821.8 1615.76
  4836.4 1613.01  4851.0 1611.53  4893.7 1609.42  4915.6 1610.56  5003.4 1610.28
  5014.0 1609.04  5014.4 1608.54  5019.3 1609.04  5022.6 1610.43  5029.1 1611.18
  5059.1 1612.78  5080.4 1612.56  5182.4 1614.76  5263.1 1618.58  5363.4 1627.40
  5394.0 1632.20  5399.9 1632.34  5412.3 1634.20  5442.4 1638.25  5465.4 1640.52
#Mann=7,-1,0
  4493.7   0.035       0  4614.6     0.1       0  4780.7    0.07       0
  5003.4     0.1       0  5014.0    0.05       0  5019.3     0.1       0
  5412.3    0.07       0
Bank Sta=5014,5019.3
Exp/Cntr=0.3,0.1

Type RM Length L Ch R = 1,3254,341,341,341
BEGIN DESCRIPTION:
Stream0659 1.0
END DESCRIPTION:
XS GIS Cut Line= 3
      1959574.98     13905224.96      1959375.00     13904825.00
      1958974.98     13904524.98
#Sta/Elev= 30
  4552.8 1625.24  4589.1 1623.73  4605.9 1620.89  4628.2 1618.72  4695.3 1613.41
  4762.4 1610.67  4790.3 1610.59  4807.1 1609.31  4821.1 1609.68  4837.7 1608.36
  4918.9 1606.31  4941.3 1604.34  4965.0 1604.31  4983.3 1604.18  4983.7 1603.68
  4988.2 1603.68  4988.7 1604.18  5021.8 1604.89  5042.7 1604.50  5136.4 1608.53
  5242.7 1610.45  5328.1 1613.39  5363.5 1615.53  5371.8 1616.65  5392.7 1617.39
  5413.5 1619.47  5421.8 1621.91  5450.0 1624.64  5471.8 1627.89  5500.0 1629.09
#Mann=5,-1,0
  4552.8   0.035       0  4837.7    0.07       0  4965.0     0.1       0
  4983.3    0.05       0  4988.7     0.1       0
Bank Sta=4983.3,4988.7
Exp/Cntr=0.3,0.1

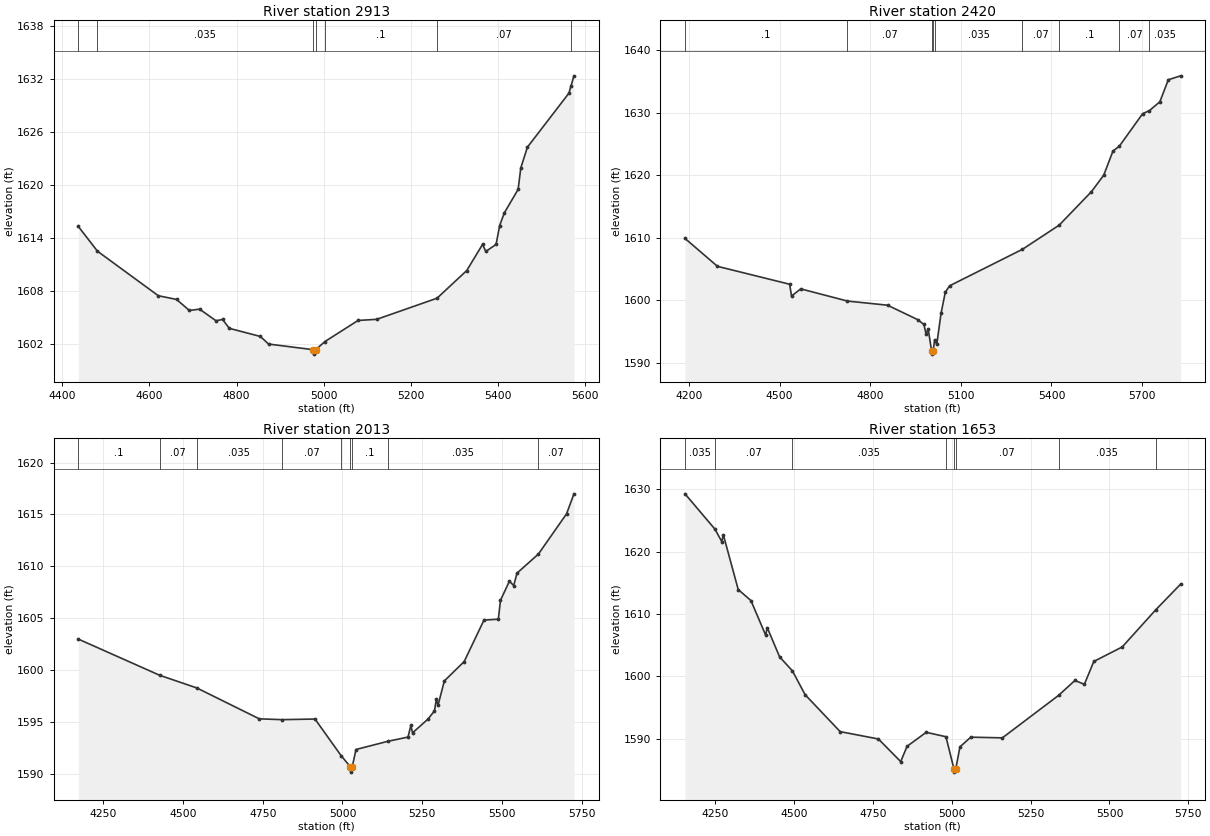
Type RM Length L Ch R = 1,2913,493,493,493
BEGIN DESCRIPTION:
Stream0659 0.1
END DESCRIPTION:
XS GIS Cut Line= 4
      1959650.59     13905075.41      1959561.85     13904599.10
      1959440.32     13904452.88      1959004.18     13904299.97
#Sta/Elev= 30
  4437.0 1615.29  4480.9 1612.49  4620.5 1607.45  4662.4 1607.03  4691.7 1605.78
  4715.2 1605.93  4752.7 1604.62  4767.9 1604.76  4783.3 1603.76  4854.5 1602.84
  4873.4 1601.98  4976.1 1601.34  4976.5 1600.84  4981.5 1601.34  5002.5 1602.26
  5078.6 1604.65  5121.5 1604.78  5259.8 1607.17  5327.9 1610.30  5364.2 1613.26
  5371.6 1612.46  5395.2 1613.26  5403.4 1615.39  5414.0 1616.82  5445.8 1619.49
  5451.9 1621.92  5467.0 1624.26  5562.3 1630.38  5567.2 1631.22  5573.8 1632.34
#Mann=7,-1,0
  4437.0     0.1       0  4480.9   0.035       0  4976.1   0.035       0
  4981.5   0.035       0  5002.5     0.1       0  5259.8    0.07       0
  5567.2   0.035       0
Bank Sta=4976.1,4981.5
Exp/Cntr=0.3,0.1

Type RM Length L Ch R = 1,2420,407,407,407
BEGIN DESCRIPTION:
Stream0659 0.0
END DESCRIPTION:
XS GIS Cut Line= 4
      1959770.93     13904930.35      1959896.09     13904317.23
      1959639.75     13904081.94      1958984.96     13903956.57
#Sta/Elev= 30
  4187.2 1609.88  4294.7 1605.42  4533.6 1602.56  4539.7 1600.68  4570.3 1601.82
  4724.9 1599.87  4857.6 1599.21  4956.9 1596.91  4977.8 1596.14  4985.2 1594.59
  4992.0 1595.42  5003.4 1591.89  5003.9 1591.39  5008.9 1591.89  5013.3 1593.70
  5020.4 1592.93  5034.6 1597.90  5048.7 1601.28  5062.9 1602.31  5303.9 1608.14
  5425.5 1612.00  5532.3 1617.35  5573.0 1619.98  5603.6 1623.84  5625.0 1624.64
  5701.7 1629.81  5724.4 1630.32  5758.8 1631.72  5786.8 1635.24  5827.6 1635.87
#Mann=9,-1,0
  4187.2     0.1       0  4724.9    0.07       0  5003.4    0.05       0
  5008.9    0.07       0  5013.3   0.035       0  5303.9    0.07       0
  5425.5     0.1       0  5625.0    0.07       0  5724.4   0.035       0
Bank Sta=5003.4,5008.9
Exp/Cntr=0.3,0.1

Type RM Length L Ch R = 1,2013,360,360,360
BEGIN DESCRIPTION:
Stream0659 0.2
END DESCRIPTION:
XS GIS Cut Line= 4
      1960103.50     13904709.50      1960163.51     13904127.20
      1959912.79     13903803.51      1959372.58     13903657.90
#Sta/Elev= 30
  4171.6 1602.98  4426.8 1599.49  4543.1 1598.27  4739.1 1595.29  4810.3 1595.21
  4913.8 1595.27  4996.2 1591.72  5025.1 1590.65  5025.6 1590.15  5030.6 1590.65
  5042.3 1592.33  5141.9 1593.12  5205.5 1593.53  5214.5 1594.65  5219.7 1593.94
  5267.7 1595.25  5288.4 1596.05  5294.4 1597.18  5299.6 1596.59  5319.5 1598.95
  5381.6 1600.81  5443.7 1604.81  5488.8 1604.90  5495.5 1606.72  5523.6 1608.57
  5537.0 1608.14  5547.3 1609.34  5614.4 1611.18  5702.7 1615.06  5725.9 1616.99
#Mann=9,-1,0
  4171.6     0.1       0  4426.8    0.07       0  4543.1   0.035       0
  4810.3    0.07       0  4996.2     0.1       0  5025.1    0.05       0
  5030.6     0.1       0  5141.9   0.035       0  5614.4    0.07       0
Bank Sta=5025.1,5030.6
Exp/Cntr=0.3,0.1

Type RM Length L Ch R = 1,1653,0,0,0
BEGIN DESCRIPTION:
Stream0659 0.3
END DESCRIPTION:
XS GIS Cut Line= 3
      1960961.96     13903737.53      1960050.55     13903602.99
      1959399.80     13903624.68
#Sta/Elev= 30
  4153.3 1629.29  4248.3 1623.62  4269.9 1621.63  4275.0 1622.70  4322.1 1613.93
  4362.5 1612.16  4409.1 1606.62  4414.2 1607.82  4453.5 1603.12  4494.1 1600.88
  4534.3 1597.06  4645.5 1591.13  4766.8 1589.95  4837.6 1586.32  4857.8 1588.77
  4918.5 1591.02  4981.1 1590.31  5006.7 1585.13  5007.1 1584.63  5012.2 1585.13
  5025.6 1588.69  5060.0 1590.24  5160.2 1590.13  5338.6 1596.95  5390.3 1599.34
  5420.3 1598.72  5450.3 1602.39  5540.4 1604.72  5647.3 1610.71  5725.7 1614.80
#Mann=8,-1,0
  4153.3   0.035       0  4248.3    0.07       0  4494.1   0.035       0
  4981.1    0.07       0  5006.7    0.05       0  5012.2    0.07       0
  5338.6   0.035       0  5647.3    0.07       0
Bank Sta=5006.7,5012.2
Exp/Cntr=0.3,0.1

Chan Stop Cuts=-1