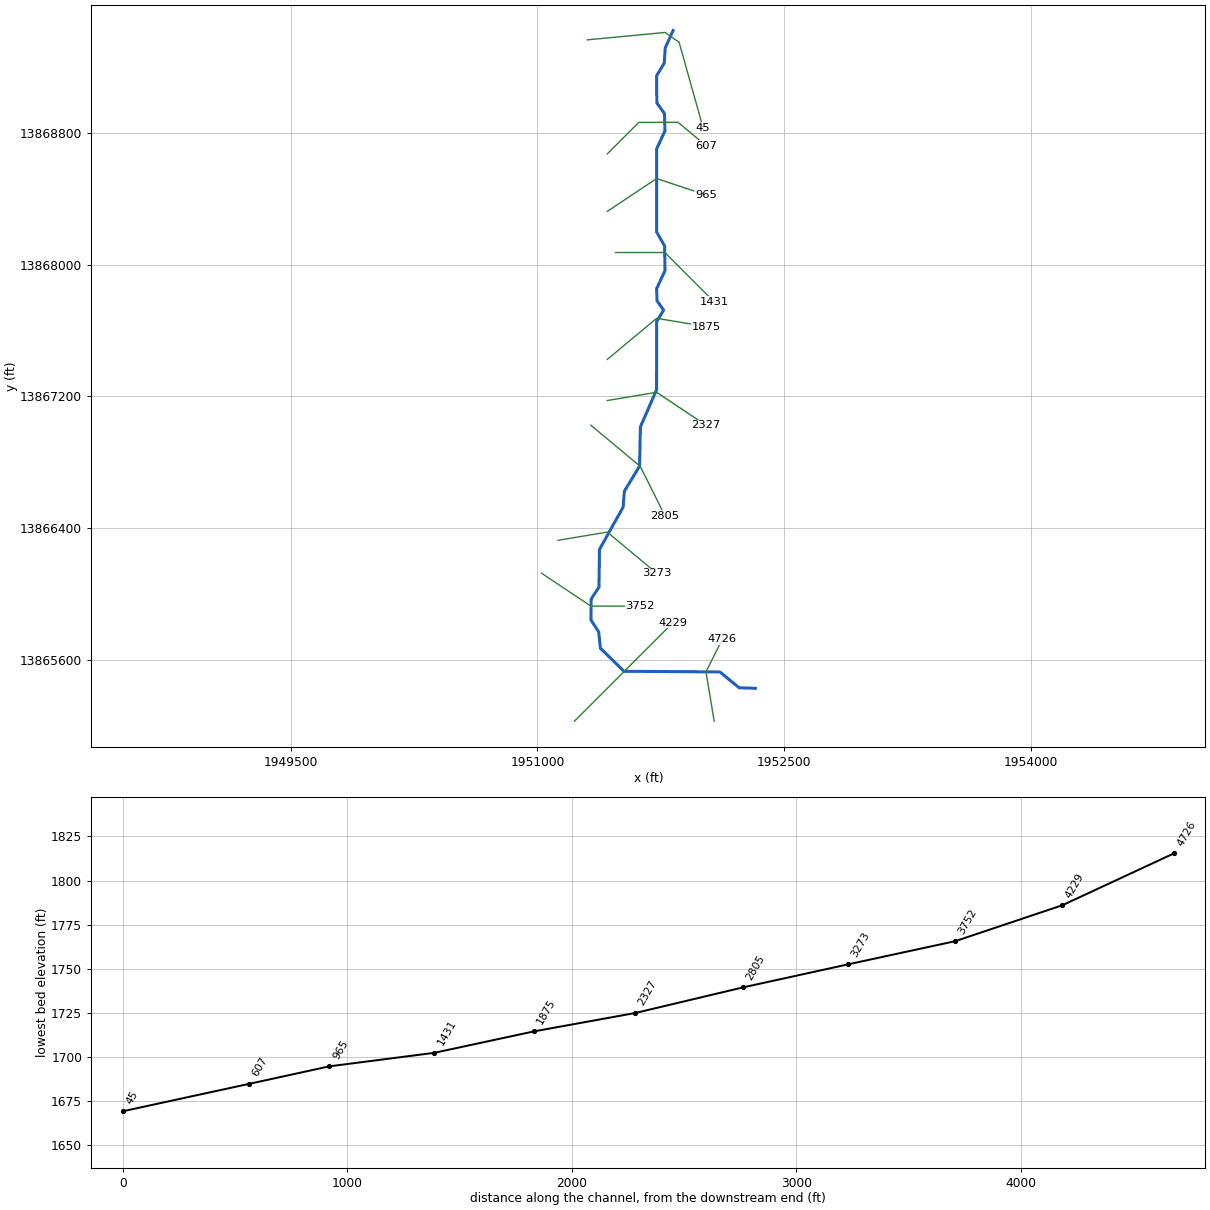
--- Stream0660.prj (project) ---

Proj Title=Stream0660 Base Level Engineering
Current Plan=p01
Default Exp/Contr=0.3,0.1
English Units
Geom File=g01
Flow File=f01
Plan File=p01
Y Axis Title=Elevation
X Axis Title(PF)=Main Channel Distance
X Axis Title(XS)=Station
BEGIN DESCRIPTION:
Stream0660
END DESCRIPTION:
DSS Export Rating Curves= 0
DSS Export Rating Curve Sorted= 0
DSS Export Volume Flow Curves= 0
DXF OffsetX= 0
DXF OffsetY= 0
DXF ScaleX= 1
DXF ScaleY= 10

--- Stream0660.p01 (plan) ---

Plan Title=Multiple Run
Short Identifier=Multiple
Geom File=g01
Flow File=f01
Subcritical Flow
K Sum by GR= 0
Std Step Tol= 0.01
Critical Tol= 0.01
Num of Std Step Trials= 20
Max Error Tol= 0.3
Flow Tol Ratio= 0.001
Split Flow NTrial= 30
Split Flow Tol= 0.02
Split Flow Ratio= 0.02
Log Output Level= 0
Friction Slope Method= 1
Unsteady Friction Slope Method= 2
Unsteady Bridges Friction Slope Method= 1
Parabolic Critical Depth
Global Vel Dist=  1 , 1 , 1
Global Log Level= 0
CheckData=True
Encroach Param= -1, 0, 0, 0
BEGIN DESCRIPTION:
Multiple Run
END DESCRIPTION:

--- Stream0660.f01 (steady flow) ---

Flow Title=Multiple
Program Version=4.10
Number of Profiles= 7
Profile Names=10-year,25-year,50-year,1pct_min,100-year,1pct_plu,500-year
River Rch & RM=Stream0660,Reach-1         ,4726
     621    1027    1403     932    1860    3712    3217
River Rch & RM=Stream0660,Reach-1         ,2327
     821    1379    1905    1277    2547    5082    4486
Boundary for River Rch & Prof#=Stream0660,Reach-1         , 1
Up Type= 0
Dn Type= 3
Dn Slope=0.005
Boundary for River Rch & Prof#=Stream0660,Reach-1         , 2
Up Type= 0
Dn Type= 3
Dn Slope=0.005
Boundary for River Rch & Prof#=Stream0660,Reach-1         , 3
Up Type= 0
Dn Type= 3
Dn Slope=0.005
Boundary for River Rch & Prof#=Stream0660,Reach-1         , 4
Up Type= 0
Dn Type= 3
Dn Slope=0.005
Boundary for River Rch & Prof#=Stream0660,Reach-1         , 5
Up Type= 0
Dn Type= 3
Dn Slope=0.005
Boundary for River Rch & Prof#=Stream0660,Reach-1         , 6
Up Type= 0
Dn Type= 3
Dn Slope=0.005
Boundary for River Rch & Prof#=Stream0660,Reach-1         , 7
Up Type= 0
Dn Type= 3
Dn Slope=0.005
DSS Import GetInterval= 0
DSS Import GetPeak= 0
DSS Import FillOption= 0

--- Stream0660.g01 (geometry) ---

Geom Title=Existing Conditions

River Reach=Stream0660,Reach-1
Reach XY= 30
      1952325.00     13865425.00      1952226.41     13865428.39
      1952109.84     13865524.61      1951526.46     13865528.54
      1951382.86     13865668.83      1951372.64     13865769.02
      1951325.50     13865840.22      1951327.25     13865969.06
      1951374.48     13866040.22      1951377.24     13866269.07
      1951521.17     13866526.58      1951528.83     13866623.42
      1951621.25     13866776.55      1951626.22     13867014.50
      1951724.48     13867240.22      1951725.18     13867655.02
      1951767.44     13867725.00      1951727.36     13867780.89
      1951724.91     13867854.90      1951775.46     13867964.82
      1951773.78     13868114.49      1951724.80     13868199.92
      1951725.07     13868704.97      1951775.50     13868814.83
      1951772.75     13868919.06      1951726.22     13868985.51
      1951724.80     13869150.08      1951771.15     13869226.60
      1951777.23     13869319.08      1951825.00     13869425.00

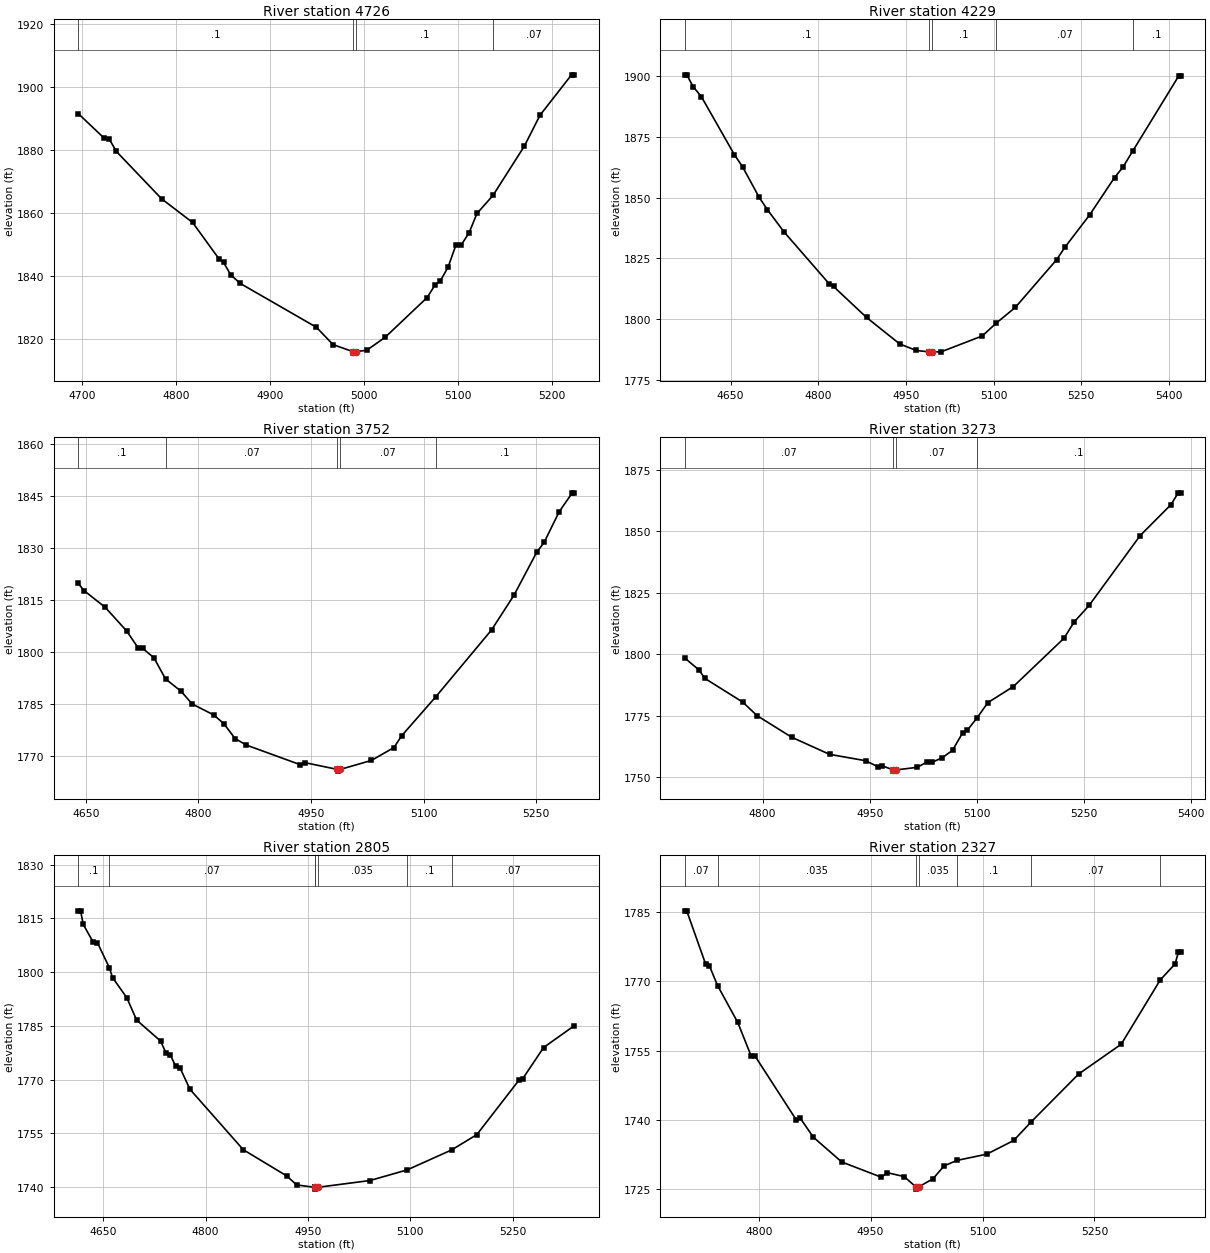
Type RM Length L Ch R = 1,4726,497,497,497
BEGIN DESCRIPTION:
Stream0660 10.0
END DESCRIPTION:
XS GIS Cut Line= 3
      1952074.99     13865225.04      1952025.00     13865525.00
      1952125.00     13865725.00
#Sta/Elev= 30
  4695.8 1891.55  4723.6 1883.67  4728.7 1883.45  4736.3 1879.53  4784.5 1864.44
  4817.4 1856.93  4845.3 1845.44  4850.4 1844.20  4858.0 1840.26  4868.1 1837.54
  4949.2 1823.58  4966.9 1818.07  4987.8 1815.86  4988.0 1815.36  4991.8 1815.86
  5002.7 1816.27  5022.3 1820.38  5067.0 1833.04  5075.4 1837.02  5081.0 1838.30
  5089.3 1842.71  5097.7 1849.77  5103.3 1849.77  5111.7 1853.68  5120.1 1859.81
  5137.1 1865.54  5170.4 1881.17  5187.2 1891.08  5220.7 1903.91  5223.5 1903.91
#Mann=4,-1,0
  4695.8     0.1       0  4987.8    0.05       0  4991.8     0.1       0
  5137.1    0.07       0
Bank Sta=4987.8,4991.8
Exp/Cntr=0.3,0.1

Type RM Length L Ch R = 1,4229,477,477,477
BEGIN DESCRIPTION:
Stream0660 9.0
END DESCRIPTION:
XS GIS Cut Line= 3
      1951225.02     13865225.02      1951525.00     13865525.00
      1951825.00     13865825.00
#Sta/Elev= 30
  4571.5 1900.64  4575.0 1900.64  4585.6 1895.82  4599.8 1891.67  4656.3 1867.78
  4670.5 1862.69  4698.8 1850.16  4712.9 1845.07  4741.2 1835.97  4819.0 1814.44
  4826.0 1813.45  4882.6 1800.68  4939.2 1789.79  4967.5 1787.10  4990.2 1786.50
  4990.5 1786.00  4994.0 1786.00  4994.2 1786.50  5009.9 1786.52  5080.6 1793.08
  5104.5 1798.36  5137.2 1804.85  5207.9 1824.52  5222.0 1829.62  5264.4 1842.97
  5306.9 1858.33  5321.0 1862.51  5337.9 1869.18  5416.5 1900.09  5420.0 1900.09
#Mann=5,-1,0
  4571.5     0.1       0  4990.2    0.05       0  4994.2     0.1       0
  5104.5    0.07       0  5337.9     0.1       0
Bank Sta=4990.2,4994.2
Exp/Cntr=0.3,0.1

Type RM Length L Ch R = 1,3752,479,479,479
BEGIN DESCRIPTION:
Stream0660 8.0
END DESCRIPTION:
XS GIS Cut Line= 3
      1951025.02     13866124.99      1951325.00     13865925.00
      1951624.97     13865925.00
#Sta/Elev= 30
  4640.0 1819.79  4647.5 1817.76  4676.0 1812.88  4704.6 1806.03  4719.6 1801.24
  4725.6 1801.10  4740.6 1798.39  4756.2 1792.25  4776.7 1788.74  4791.7 1785.03
  4820.3 1781.88  4833.8 1779.37  4848.8 1775.06  4863.8 1773.19  4935.9 1767.51
  4941.9 1768.11  4985.0 1766.17  4985.3 1765.67  4989.0 1766.17  5030.5 1768.76
  5060.5 1772.48  5070.5 1775.81  5116.4 1787.17  5190.5 1806.40  5220.5 1816.47
  5250.5 1828.75  5260.5 1831.64  5280.5 1840.47  5298.0 1845.94  5300.5 1845.94
#Mann=5,-1,0
  4640.0     0.1       0  4756.2    0.07       0  4985.0    0.05       0
  4989.0    0.07       0  5116.4     0.1       0
Bank Sta=4985,4989
Exp/Cntr=0.3,0.1

Type RM Length L Ch R = 1,3273,468,468,468
BEGIN DESCRIPTION:
Stream0660 7.0
END DESCRIPTION:
XS GIS Cut Line= 3
      1951124.95     13866324.99      1951425.00     13866375.00
      1951725.00     13866125.00
#Sta/Elev= 30
  4691.0 1798.44  4711.3 1793.50  4718.9 1790.21  4772.2 1780.54  4792.4 1775.01
  4840.6 1766.30  4893.8 1759.32  4944.5 1756.72  4962.2 1754.17  4967.3 1754.68
  4983.0 1753.00  4983.3 1752.50  4987.0 1753.00  5016.7 1754.04  5031.0 1756.33
  5037.5 1756.09  5051.8 1757.95  5066.1 1760.96  5080.4 1768.12  5087.0 1769.19
  5100.5 1774.13  5115.6 1780.33  5151.4 1786.88  5222.3 1806.49  5236.7 1813.17
  5257.5 1819.83  5329.1 1848.24  5372.0 1860.73  5382.4 1865.58  5385.7 1865.58
#Mann=4,-1,0
  4691.0    0.07       0  4983.0    0.05       0  4987.0    0.07       0
  5100.5     0.1       0
Bank Sta=4983,4987
Exp/Cntr=0.3,0.1

Type RM Length L Ch R = 1,2805,478,478,478
BEGIN DESCRIPTION:
Stream0660 6.0
END DESCRIPTION:
XS GIS Cut Line= 3
      1951324.98     13867025.01      1951625.00     13866775.00
      1951774.98     13866475.04
#Sta/Elev= 30
  4613.8 1817.13  4617.1 1817.13  4621.0 1813.34  4635.3 1808.47  4641.8 1808.23
  4659.3 1801.22  4663.9 1798.50  4684.8 1792.86  4699.1 1786.65  4734.2 1780.78
  4742.0 1777.53  4748.5 1776.92  4756.4 1773.69  4762.9 1773.21  4777.2 1767.32
  4855.3 1750.45  4919.1 1743.11  4933.4 1740.62  4959.9 1739.96  4960.0 1739.95
  4960.3 1739.45  4964.0 1739.95  5040.7 1741.85  5095.4 1744.83  5160.3 1750.39
  5197.2 1754.66  5258.7 1769.81  5264.3 1770.25  5295.0 1778.98  5339.7 1785.04
#Mann=7,-1,0
  4613.8     0.1       0  4659.3    0.07       0  4959.9   0.035       0
  4960.0    0.05       0  4964.0   0.035       0  5095.4     0.1       0
  5160.3    0.07       0
Bank Sta=4960,4964
Exp/Cntr=0.3,0.1

Type RM Length L Ch R = 1,2327,452,452,452
BEGIN DESCRIPTION:
Stream0660 5.0
END DESCRIPTION:
XS GIS Cut Line= 3
      1951424.98     13867175.00      1951725.00     13867225.00
      1952024.99     13867025.00
#Sta/Elev= 30
  4700.9 1785.26  4703.5 1785.26  4728.8 1773.74  4733.9 1773.35  4744.8 1769.09
  4771.9 1761.09  4789.6 1753.93  4794.7 1753.90  4850.5 1739.96  4855.5 1740.41
  4873.3 1736.24  4911.3 1730.89  4964.5 1727.58  4972.1 1728.58  4994.9 1727.73
  5010.6 1725.51  5010.8 1725.01  5014.6 1725.51  5033.6 1727.25  5048.6 1730.05
  5065.9 1731.23  5105.7 1732.58  5141.8 1735.54  5165.4 1739.59  5228.9 1749.93
  5286.0 1756.39  5338.3 1770.30  5358.1 1773.75  5362.6 1776.28  5365.6 1776.28
#Mann=7,-1,0
  4700.9    0.07       0  4744.8   0.035       0  5010.6   0.035       0
  5014.6   0.035       0  5065.9     0.1       0  5165.4    0.07       0
  5338.3     0.1       0
Bank Sta=5010.6,5014.6
Exp/Cntr=0.3,0.1

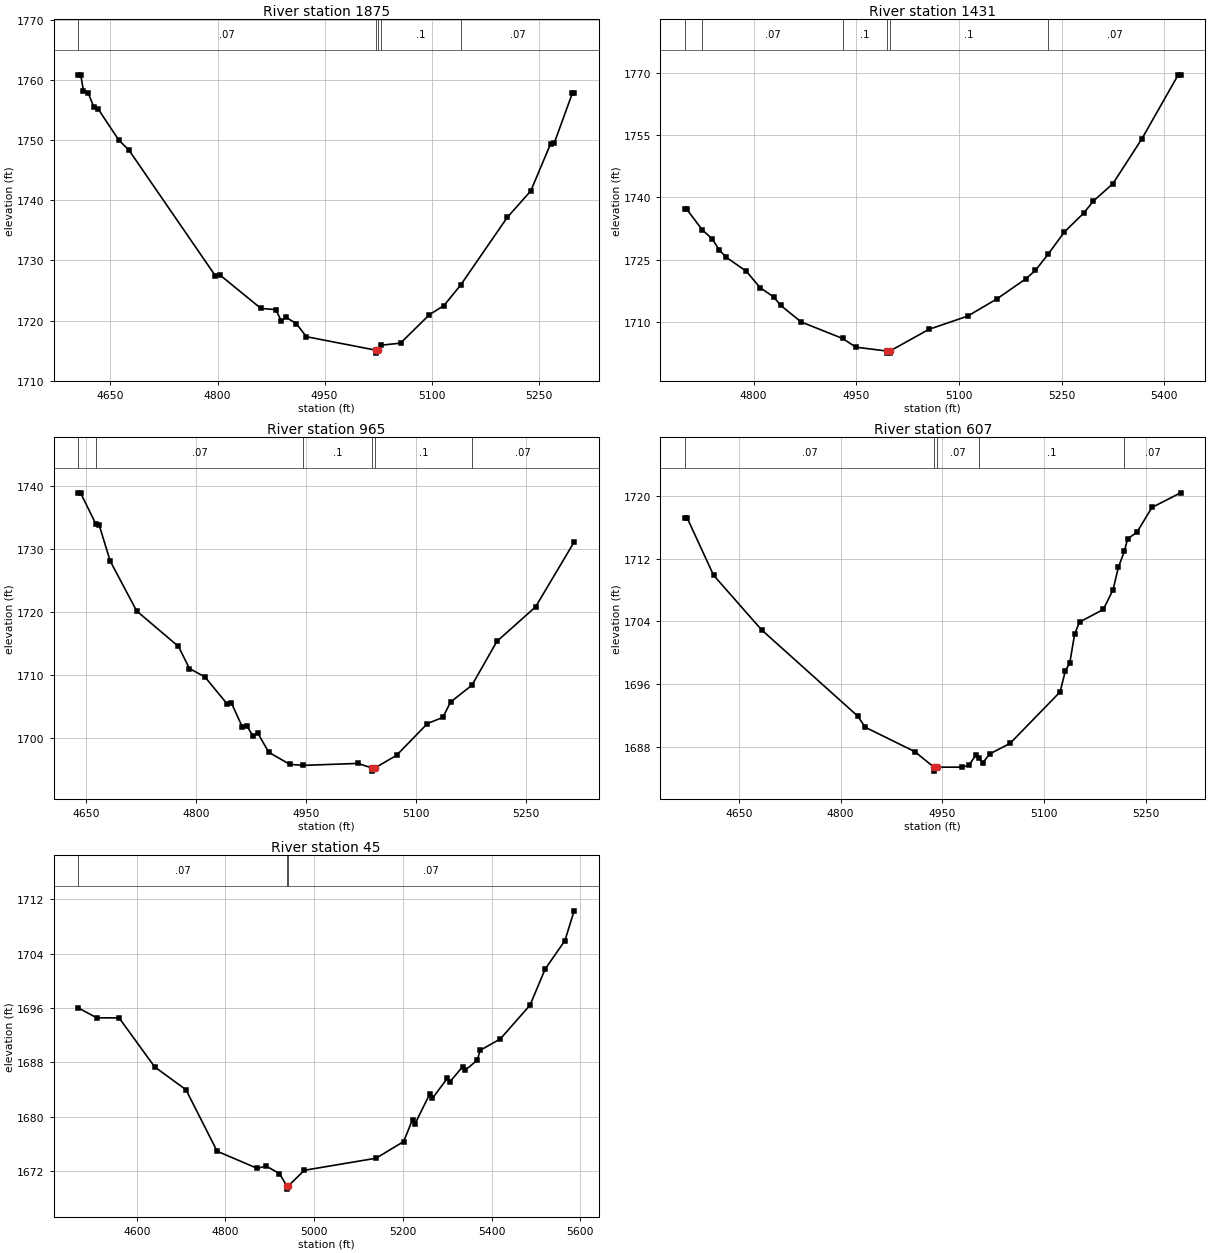
Type RM Length L Ch R = 1,1875,444,444,444
BEGIN DESCRIPTION:
Stream0660 4.0
END DESCRIPTION:
XS GIS Cut Line= 3
      1951424.97     13867424.98      1951725.00     13867675.00
      1952025.01     13867625.00
#Sta/Elev= 30
  4605.0 1760.84  4608.3 1760.84  4612.2 1758.20  4618.7 1757.87  4626.5 1755.54
  4633.0 1755.12  4661.7 1749.99  4676.0 1748.31  4797.0 1727.43  4803.5 1727.56
  4860.8 1722.01  4881.6 1721.81  4889.5 1719.91  4896.0 1720.54  4910.3 1719.49
  4924.6 1717.31  5021.4 1715.08  5021.7 1714.58  5025.4 1715.08  5028.6 1715.89
  5056.4 1716.24  5096.9 1720.97  5117.2 1722.48  5140.5 1725.87  5205.9 1737.13
  5238.9 1741.54  5266.7 1749.37  5271.8 1749.49  5297.2 1757.79  5299.7 1757.79
#Mann=5,-1,0
  4605.0    0.07       0  5021.4    0.05       0  5025.4    0.07       0
  5028.6     0.1       0  5140.5    0.07       0
Bank Sta=5021.4,5025.4
Exp/Cntr=0.3,0.1

Type RM Length L Ch R = 1,1431,466,466,466
BEGIN DESCRIPTION:
Stream0660 3.0
END DESCRIPTION:
XS GIS Cut Line= 3
      1951474.97     13868075.00      1951775.00     13868075.00
      1952075.01     13867774.99
#Sta/Elev= 30
  4699.4 1737.19  4701.9 1737.19  4725.0 1732.13  4739.4 1729.98  4749.4 1727.37
  4759.4 1725.61  4789.4 1722.15  4809.4 1718.21  4829.4 1715.97  4839.4 1713.95
  4869.4 1709.95  4929.8 1705.98  4949.4 1703.87  4994.9 1702.94  4995.2 1702.44
  4998.7 1702.44  4998.9 1702.94  5056.0 1708.17  5112.6 1711.36  5155.0 1715.47
  5197.4 1720.33  5211.6 1722.38  5230.1 1726.27  5254.0 1731.66  5282.3 1736.22
  5296.4 1739.11  5324.7 1743.26  5367.1 1754.09  5420.2 1769.51  5423.7 1769.51
#Mann=6,-1,0
  4699.4     0.1       0  4725.0    0.07       0  4929.8     0.1       0
  4994.9    0.05       0  4998.9     0.1       0  5230.1    0.07       0
Bank Sta=4994.9,4998.9
Exp/Cntr=0.3,0.1

Type RM Length L Ch R = 1,965,358,358,358
BEGIN DESCRIPTION:
Stream0660 2.0
END DESCRIPTION:
XS GIS Cut Line= 3
      1951425.03     13868325.02      1951725.00     13868525.00
      1952024.96     13868425.01
#Sta/Elev= 30
  4639.5 1738.90  4642.5 1738.90  4663.6 1733.92  4668.0 1733.77  4683.0 1728.09
  4719.1 1720.19  4776.2 1714.56  4791.2 1711.06  4812.2 1709.75  4842.3 1705.50
  4848.3 1705.66  4863.3 1701.81  4869.3 1702.01  4878.3 1700.31  4884.3 1700.86
  4899.4 1697.81  4927.9 1695.90  4945.7 1695.73  5021.1 1696.04  5040.2 1695.32
  5040.4 1694.82  5044.2 1695.32  5073.8 1697.32  5116.0 1702.36  5137.0 1703.33
  5147.6 1705.77  5176.7 1708.43  5210.8 1715.38  5263.5 1720.83  5316.2 1731.11
#Mann=6,-1,0
  4639.5     0.1       0  4663.6    0.07       0  4945.7     0.1       0
  5040.2    0.05       0  5044.2     0.1       0  5176.7    0.07       0
Bank Sta=5040.2,5044.2
Exp/Cntr=0.3,0.1

Type RM Length L Ch R = 1,607,562,562,562
BEGIN DESCRIPTION:
Stream0660 1.0
END DESCRIPTION:
XS GIS Cut Line= 4
      1951425.01     13868675.01      1951616.08     13868866.08
      1951854.32     13868867.23      1952024.97     13868725.02
#Sta/Elev= 30
  4570.4 1717.21  4573.9 1717.21  4612.8 1709.90  4683.5 1702.93  4825.0 1691.93
  4836.3 1690.49  4909.5 1687.37  4937.5 1685.39  4937.8 1684.89  4941.5 1685.39
  4979.5 1685.40  4989.5 1685.67  4999.5 1687.00  5003.8 1686.54  5009.5 1685.94
  5019.5 1687.08  5049.5 1688.42  5123.4 1695.00  5131.2 1697.71  5137.7 1698.71
  5144.8 1702.38  5152.0 1703.92  5187.1 1705.53  5201.5 1708.06  5209.3 1710.92
  5218.1 1712.96  5222.9 1714.55  5236.6 1715.38  5258.7 1718.55  5301.0 1720.42
#Mann=5,-1,0
  4570.4    0.07       0  4937.5    0.05       0  4941.5    0.07       0
  5003.8     0.1       0  5218.1    0.07       0
Bank Sta=4937.5,4941.5
Exp/Cntr=0.3,0.1

Type RM Length L Ch R = 1,45,0,0,0
BEGIN DESCRIPTION:
Stream0660 0.0
END DESCRIPTION:
XS GIS Cut Line= 4
      1951303.54     13869368.27      1951776.20     13869413.32
      1951861.78     13869353.41      1952007.00     13868834.83
#Sta/Elev= 30
  4468.3 1696.01  4509.9 1694.56  4560.2 1694.55  4640.5 1687.34  4710.9 1684.00
  4781.2 1674.96  4871.6 1672.44  4891.7 1672.78  4921.8 1671.67  4938.0 1669.89
  4938.2 1669.39  4942.0 1669.89  4978.0 1672.16  5139.4 1673.93  5201.7 1676.38
  5221.8 1679.62  5227.0 1678.95  5261.1 1683.44  5266.3 1682.71  5300.4 1685.69
  5305.6 1685.12  5334.6 1687.37  5339.8 1686.82  5367.8 1688.35  5373.9 1689.77
  5419.8 1691.47  5486.6 1696.42  5520.7 1701.72  5565.2 1705.90  5586.1 1710.28
#Mann=3,-1,0
  4468.3    0.07       0  4938.0    0.05       0  4942.0    0.07       0
Bank Sta=4938,4942
Exp/Cntr=0.3,0.1

Chan Stop Cuts=-1