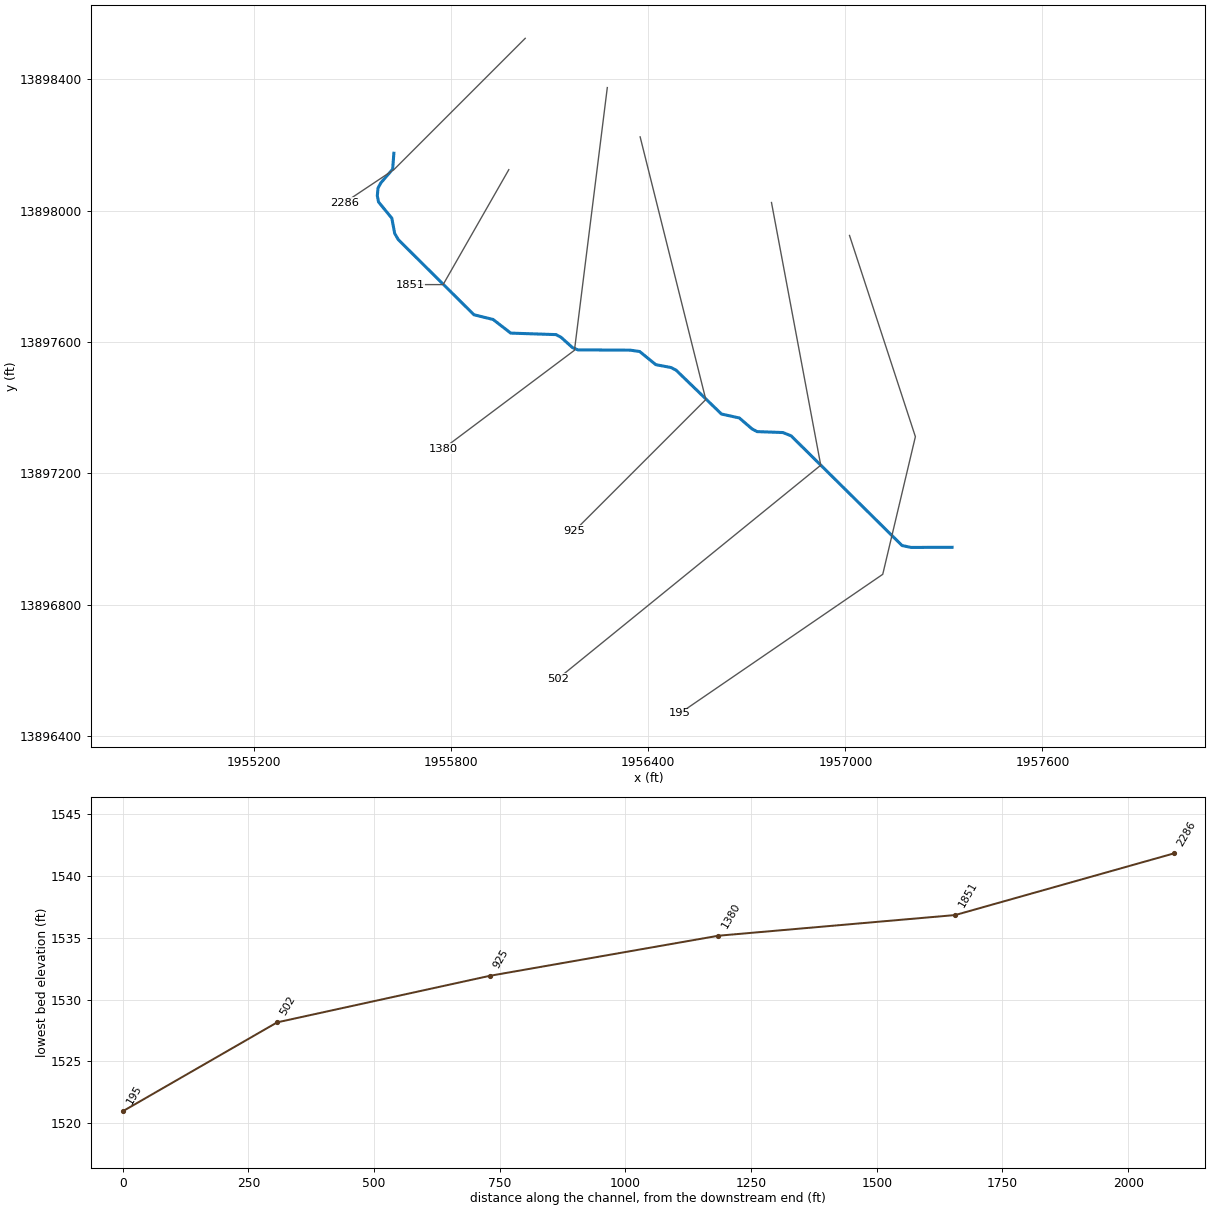
--- Stream0663.prj (project) ---

Proj Title=Stream0663 Base Level Engineering
Current Plan=p01
Default Exp/Contr=0.3,0.1
English Units
Geom File=g01
Flow File=f01
Plan File=p01
Y Axis Title=Elevation
X Axis Title(PF)=Main Channel Distance
X Axis Title(XS)=Station
BEGIN DESCRIPTION:
Stream0663
END DESCRIPTION:
DSS Export Rating Curves= 0
DSS Export Rating Curve Sorted= 0
DSS Export Volume Flow Curves= 0
DXF OffsetX= 0
DXF OffsetY= 0
DXF ScaleX= 1
DXF ScaleY= 10

--- Stream0663.p01 (plan) ---

Plan Title=Multiple Run
Short Identifier=Multiple
Geom File=g01
Flow File=f01
Subcritical Flow
K Sum by GR= 0
Std Step Tol= 0.01
Critical Tol= 0.01
Num of Std Step Trials= 20
Max Error Tol= 0.3
Flow Tol Ratio= 0.001
Split Flow NTrial= 30
Split Flow Tol= 0.02
Split Flow Ratio= 0.02
Log Output Level= 0
Friction Slope Method= 1
Unsteady Friction Slope Method= 2
Unsteady Bridges Friction Slope Method= 1
Parabolic Critical Depth
Global Vel Dist=  1 , 1 , 1
Global Log Level= 0
CheckData=True
Encroach Param= -1, 0, 0, 0
BEGIN DESCRIPTION:
Multiple Run
END DESCRIPTION:

--- Stream0663.f01 (steady flow) ---

Flow Title=Multiple
Program Version=4.10
Number of Profiles= 7
Profile Names=10-year,25-year,50-year,1pct_min,100-year,1pct_plu,500-year
River Rch & RM=Stream0663,Reach-1         ,2286
    1800    3164    4504    3098    6182   12334   11502
Boundary for River Rch & Prof#=Stream0663,Reach-1         , 1
Up Type= 0
Dn Type= 3
Dn Slope=0.008
Boundary for River Rch & Prof#=Stream0663,Reach-1         , 2
Up Type= 0
Dn Type= 3
Dn Slope=0.008
Boundary for River Rch & Prof#=Stream0663,Reach-1         , 3
Up Type= 0
Dn Type= 3
Dn Slope=0.008
Boundary for River Rch & Prof#=Stream0663,Reach-1         , 4
Up Type= 0
Dn Type= 3
Dn Slope=0.008
Boundary for River Rch & Prof#=Stream0663,Reach-1         , 5
Up Type= 0
Dn Type= 3
Dn Slope=0.008
Boundary for River Rch & Prof#=Stream0663,Reach-1         , 6
Up Type= 0
Dn Type= 3
Dn Slope=0.008
Boundary for River Rch & Prof#=Stream0663,Reach-1         , 7
Up Type= 0
Dn Type= 3
Dn Slope=0.008
DSS Import GetInterval= 0
DSS Import GetPeak= 0
DSS Import FillOption= 0

--- Stream0663.g01 (geometry) ---

Geom Title=Existing Conditions
Program Version=4.10

River Reach=Stream0663      ,Reach-1
Reach XY= 30
        1955625.       13898175.      1955621.31     13898126.49
      1955585.24     13898084.63      1955576.64     13898068.92
      1955574.65     13898045.17      1955578.32     13898026.72
      1955618.82     13897977.19      1955627.49     13897931.03
      1955638.62     13897911.79      1955868.94     13897683.14
      1955927.17     13897668.86      1955980.93     13897627.25
      1956119.06     13897622.73      1956134.64     13897614.14
      1956168.94     13897583.14      1956185.51     13897576.22
      1956345.15     13897575.36      1956373.45     13897571.25
      1956422.83     13897531.14      1956468.97      13897522.5
      1956484.68     13897514.24       1956622.7     13897380.83
      1956677.17     13897368.86      1956715.35     13897335.84
      1956730.97     13897327.33      1956809.78     13897324.48
      1956834.79     13897314.48      1957172.54     13896980.43
      1957199.84     13896974.62        1957325.       13896975.

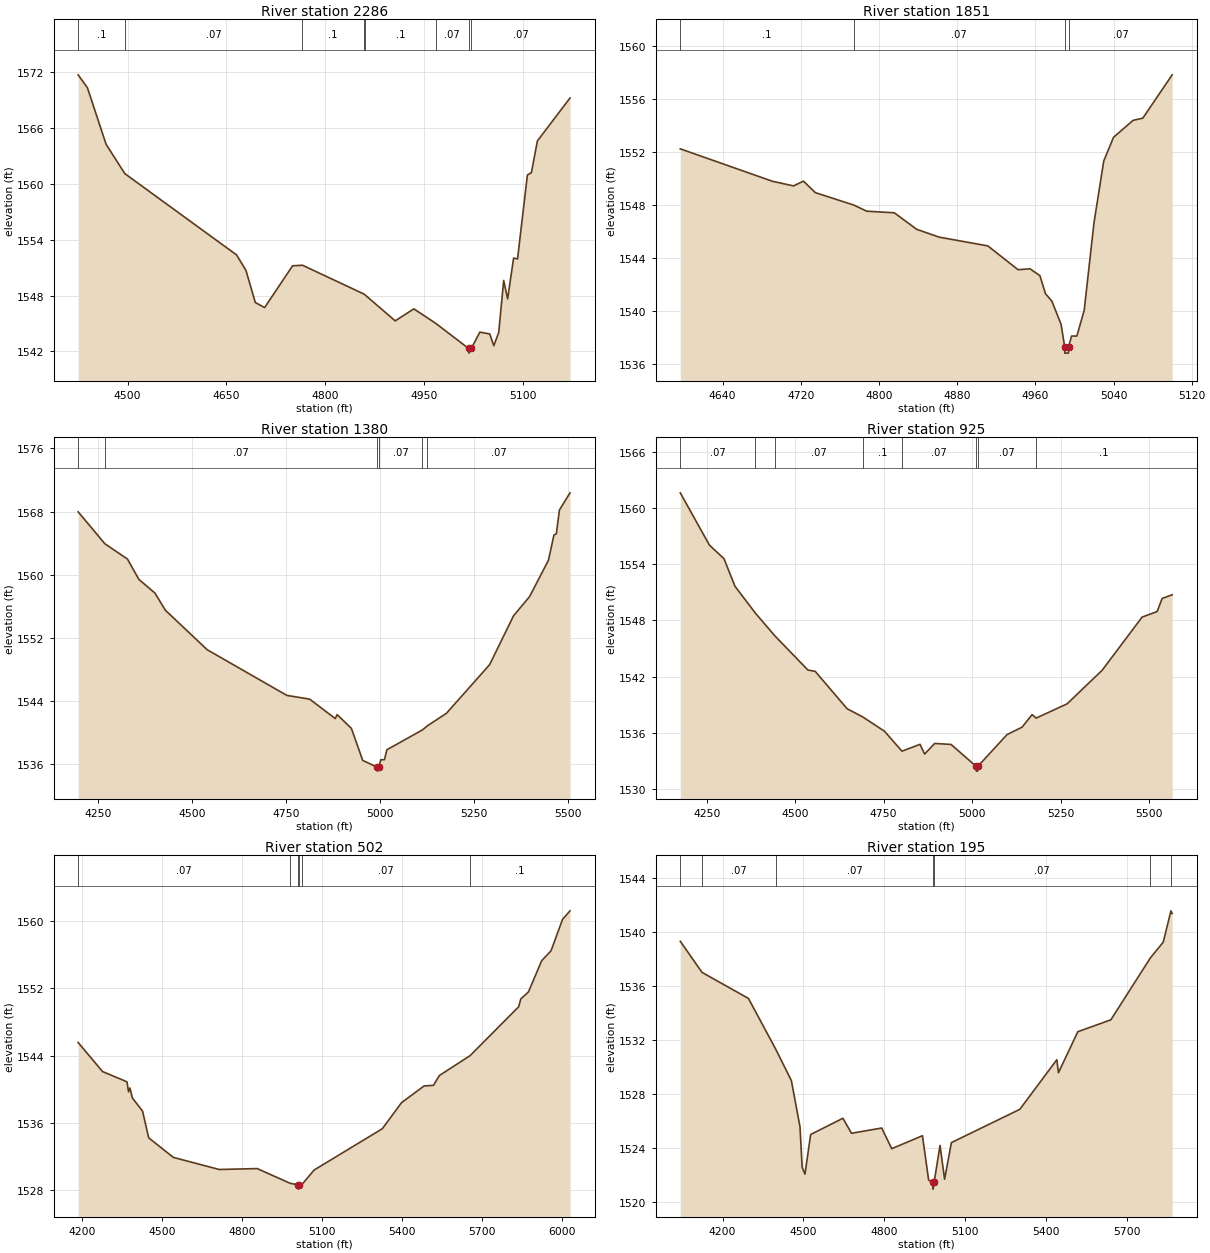
Type RM Length L Ch R = 1 ,2286    ,435,435,435
BEGIN DESCRIPTION:
Stream0663 5.0
END DESCRIPTION:
XS GIS Cut Line= 3
      1956024.98     13898524.98        1955625.       13898125.
      1955475.03     13898025.02
#Sta/Elev= 30
  4425.1 1571.73  4439.2 1570.34  4467.5 1564.26  4495.9 1561.11  4665.5 1552.36
  4679.6  1550.7  4693.8 1547.25  4707.9 1546.71  4750.3  1551.2  4765.3 1551.26
  4858.3 1548.17  4860.8 1548.03  4905.9 1545.28  4934.2 1546.57  4967.6    1545
  5017.2 1542.31  5017.5 1541.81  5021.3 1542.31  5034.3 1544.07  5049.3 1543.87
  5055.4 1542.61  5062.9 1544.04  5070.4 1549.62  5076.4 1547.64  5085.4 1552.02
  5091.4 1551.94  5106.4 1560.97  5112.4 1561.21  5121.5 1564.62    5171 1569.24
#Mann= 8 ,-1 , 0
  4425.1      .1       0  4495.9     .07       0  4765.3      .1       0
  4858.3     .07       0  4860.8      .1       0  4967.6     .07       0
  5017.2     .05       0  5021.3     .07       0
Bank Sta=5017.2,5021.3
XS Rating Curve= 0 ,0
Exp/Cntr=0.3,0.1

Type RM Length L Ch R = 1 ,1851    ,471,471,471
BEGIN DESCRIPTION:
Stream0663 4.0
END DESCRIPTION:
XS GIS Cut Line= 3
      1955975.02     13898125.03        1955775.       13897775.
      1955674.95       13897775.
#Sta/Elev= 30
  4596.8 1552.26  4691.1 1549.81  4712.7 1549.46  4722.8 1549.82    4735 1548.95
  4774.1 1548.02  4787.6 1547.55  4815.7 1547.43  4838.7 1546.18  4861.7 1545.59
  4911.4 1544.93  4942.4 1543.13  4954.6  1543.2  4964.7 1542.68  4970.4 1541.32
  4976.9 1540.76  4986.3 1539.02    4990 1537.33  4990.2 1536.83  4993.8 1536.83
  4994.1 1537.33  4997.1 1538.12  5002.5 1538.12    5010 1540.06    5020 1546.66
    5030 1551.34    5040 1553.13    5060 1554.41    5070 1554.58    5100 1557.85
#Mann= 4 ,-1 , 0
  4596.8      .1       0  4774.1     .07       0    4990     .05       0
  4994.1     .07       0
Bank Sta=4990,4994.1
XS Rating Curve= 0 ,0
Exp/Cntr=0.3,0.1

Type RM Length L Ch R = 1 ,1380    ,455,455,455
BEGIN DESCRIPTION:
Stream0663 3.0
END DESCRIPTION:
XS GIS Cut Line= 3
        1956275.     13898375.01        1956175.       13897575.
      1955775.03     13897275.02
#Sta/Elev= 30
  4198.1 1567.97    4269 1563.93  4329.1 1561.99  4359.4 1559.42  4402.2 1557.68
  4429.9 1555.51  4540.8 1550.52  4752.4 1544.74  4812.9 1544.27  4880.9 1541.81
  4885.9 1542.31  4923.7 1540.57  4953.9 1536.51  4992.2 1535.66  4992.5 1535.16
  4996.4 1535.66  5001.8  1536.6  5011.6 1536.61  5017.9 1537.86  5112.2 1540.37
  5125.5 1540.89  5176.2 1542.48  5290.8 1548.63  5354.3 1554.81    5397 1557.25
    5447 1561.84  5461.6 1565.04  5467.9 1565.18  5476.2  1568.2  5504.3 1570.37
#Mann= 6 ,-1 , 0
  4198.1    .035       0    4269     .07       0  4992.2     .05       0
  4996.4     .07       0  5112.2      .1       0  5125.5     .07       0
Bank Sta=4992.2,4996.4
XS Rating Curve= 0 ,0
Exp/Cntr=0.3,0.1

Type RM Length L Ch R = 1 ,925     ,423,423,423
BEGIN DESCRIPTION:
Stream0663 2.0
END DESCRIPTION:
XS GIS Cut Line= 3
      1956375.01     13898224.96        1956575.       13897425.
      1956174.97     13897024.97
#Sta/Elev= 30
  4175.2 1561.62  4257.6 1556.04  4298.8 1554.59  4329.8 1551.65  4387.8 1548.77
  4442.7 1546.35  4535.9 1542.71  4556.5 1542.57  4646.7 1538.58  4690.6 1537.71
  4752.4 1536.18  4801.7 1534.05  4852.9 1534.78  4865.8 1533.74  4894.1 1534.87
  4940.5 1534.77  5011.8 1532.42  5012.1 1531.92  5015.7 1531.92    5016 1532.42
  5098.8 1535.82  5141.2 1536.61  5169.5 1537.95  5181.1 1537.58  5268.5  1539.1
  5367.5 1542.68  5480.6 1548.36    5523 1548.95  5537.2 1550.35  5565.5 1550.74
#Mann= 8 ,-1 , 0
  4175.2     .07       0  4387.8    .035       0  4442.7     .07       0
  4690.6      .1       0  4801.7     .07       0  5011.8     .05       0
    5016     .07       0  5181.1      .1       0
Bank Sta=5011.8,5016
XS Rating Curve= 0 ,0
Exp/Cntr=0.3,0.1

Type RM Length L Ch R = 1 ,502     ,307,307,307
BEGIN DESCRIPTION:
Stream0663 1.0
END DESCRIPTION:
XS GIS Cut Line= 3
      1956774.99     13898025.04        1956925.       13897225.
      1956124.96     13896574.97
#Sta/Elev= 30
  4186.1 1545.57  4277.7 1542.12  4369.3  1540.9  4375.2 1539.71  4380.3 1540.17
  4389.6 1538.98  4427.8 1537.42  4450.7 1534.25  4543.1 1531.93  4715.2 1530.49
  4857.6  1530.6  4980.6 1528.86  5011.6 1528.66  5011.9 1528.16  5015.8 1528.66
  5026.9 1528.76  5071.2 1530.43  5326.9 1535.33  5398.8 1538.42  5483.5 1540.41
  5518.7 1540.48    5541 1541.65  5656.2 1544.01  5838.3 1549.81  5846.3 1550.74
    5875 1551.57  5924.6 1555.28  5959.7 1556.46  6002.9 1560.19  6030.9  1561.2
#Mann= 6 ,-1 , 0
  4186.1     .07       0  4980.6     .07       0  5011.6     .05       0
  5015.8     .07       0  5026.9     .07       0  5656.2      .1       0
Bank Sta=5011.6,5015.8
XS Rating Curve= 0 ,0
Exp/Cntr=0.3,0.1

Type RM Length L Ch R = 1 ,195     ,0,0,0
BEGIN DESCRIPTION:
Stream0663 0.0
END DESCRIPTION:
XS GIS Cut Line= 4
      1957012.65     13897924.65      1957213.23      13897311.9
      1957113.81     13896892.72      1956495.47     13896469.25
#Sta/Elev= 30
  4043.1 1539.31  4123.7 1537.01  4296.1 1535.08    4398  1531.3  4455.4    1529
  4487.3 1525.58  4495.2 1522.61  4505.7 1522.09  4526.8 1525.02  4646.5 1526.22
  4678.4 1525.11  4790.5  1525.5  4827.6 1523.97  4941.6 1524.93  4964.6 1521.65
  4980.6 1521.48  4980.9 1520.98  4984.9 1521.48  5006.8 1524.21  5023.8 1521.71
    5049 1524.42  5302.8 1526.88  5440.2 1530.55  5446.3 1529.59    5518 1532.62
  5640.6  1533.5  5787.6 1538.09  5834.9 1539.24  5863.6 1541.56  5868.1 1541.36
#Mann= 7 ,-1 , 0
  4043.1    .035       0  4123.7     .07       0    4398     .07       0
  4980.6     .05       0  4984.9     .07       0  5787.6     .07       0
  5863.6      .1       0
Bank Sta=4980.6,4984.9
XS Rating Curve= 0 ,0
Exp/Cntr=0.3,0.1

Chan Stop Cuts=-1
Use User Specified Reach Order=0
Composite Channel Slope=5