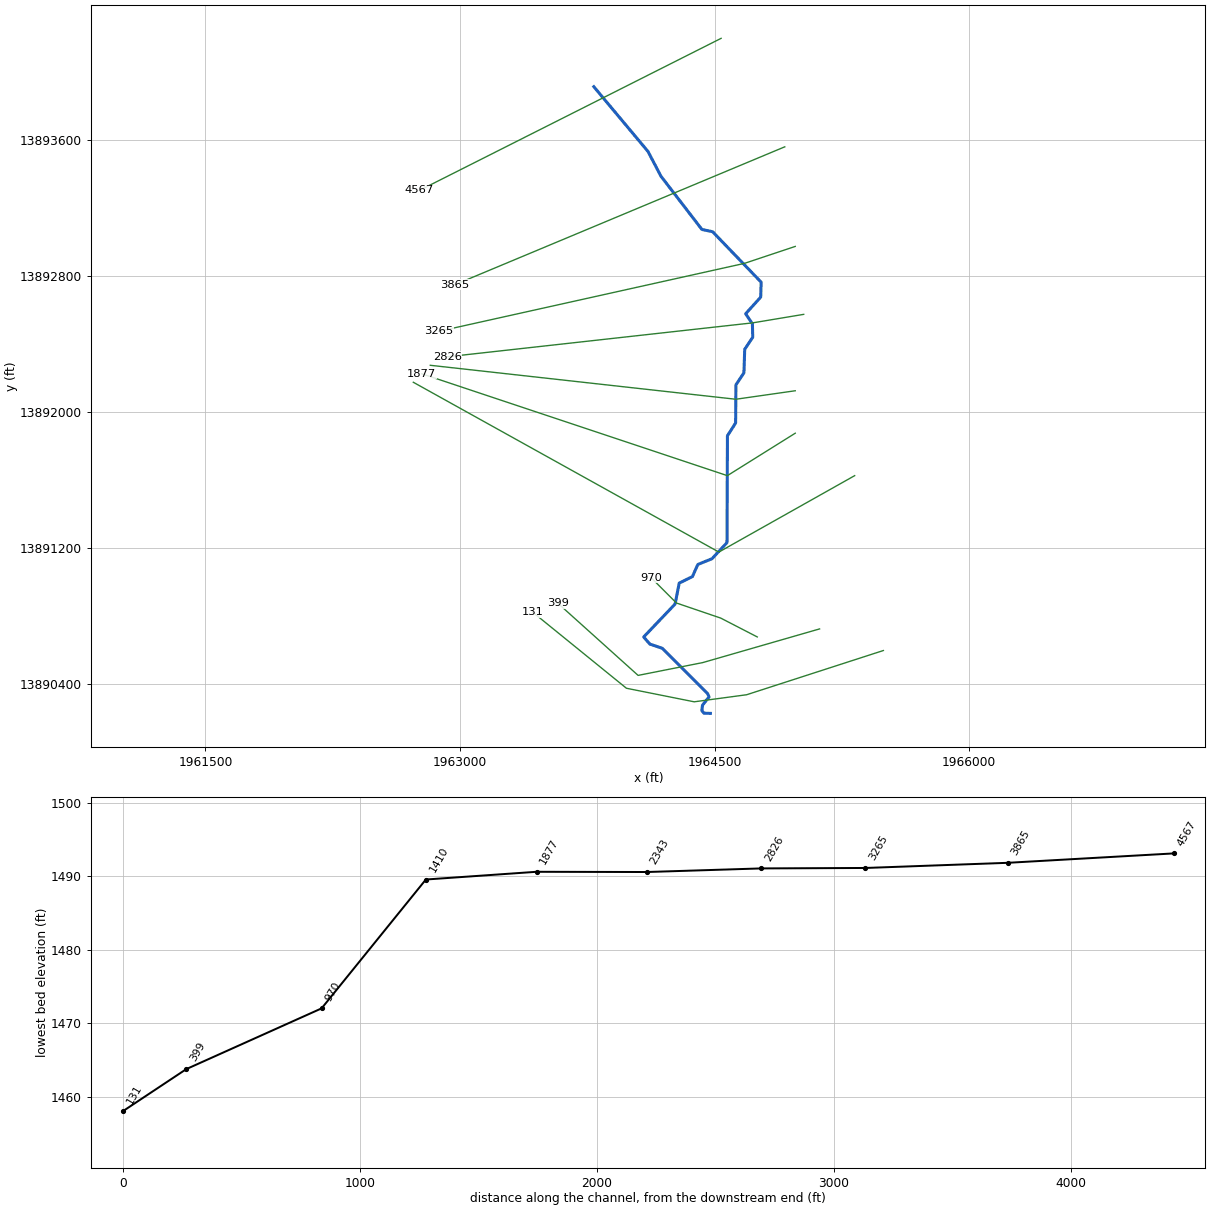
--- Stream0666.prj (project) ---

Proj Title=Stream0666 Base Level Engineering
Current Plan=p01
Default Exp/Contr=0.3,0.1
English Units
Geom File=g01
Flow File=f01
Plan File=p01
Y Axis Title=Elevation
X Axis Title(PF)=Main Channel Distance
X Axis Title(XS)=Station
BEGIN DESCRIPTION:
Stream0666
END DESCRIPTION:
DSS Export Rating Curves= 0
DSS Export Rating Curve Sorted= 0
DSS Export Volume Flow Curves= 0
DXF OffsetX= 0
DXF OffsetY= 0
DXF ScaleX= 1
DXF ScaleY= 10

--- Stream0666.p01 (plan) ---

Plan Title=Multiple Run
Short Identifier=Multiple
Geom File=g01
Flow File=f01
Subcritical Flow
K Sum by GR= 0
Std Step Tol= 0.01
Critical Tol= 0.01
Num of Std Step Trials= 20
Max Error Tol= 0.3
Flow Tol Ratio= 0.001
Split Flow NTrial= 30
Split Flow Tol= 0.02
Split Flow Ratio= 0.02
Log Output Level= 0
Friction Slope Method= 1
Unsteady Friction Slope Method= 2
Unsteady Bridges Friction Slope Method= 1
Parabolic Critical Depth
Global Vel Dist=  1 , 1 , 1
Global Log Level= 0
CheckData=True
Encroach Param= -1, 0, 0, 0
BEGIN DESCRIPTION:
Multiple Run
END DESCRIPTION:

--- Stream0666.f01 (steady flow) ---

Flow Title=Multiple
Program Version=4.10
Number of Profiles= 7
Profile Names=10-year,25-year,50-year,1pct_min,100-year,1pct_plu,500-year
River Rch & RM=Stream0666,Reach-1         ,4567
    1474    2545    3577    2430    4849    9676    8798
River Rch & RM=Stream0666,Reach-1         ,3265
    1668    2893    4080    2778    5542   11059   10105
Boundary for River Rch & Prof#=Stream0666,Reach-1         , 1
Up Type= 0
Dn Type= 3
Dn Slope=0.01
Boundary for River Rch & Prof#=Stream0666,Reach-1         , 2
Up Type= 0
Dn Type= 3
Dn Slope=0.01
Boundary for River Rch & Prof#=Stream0666,Reach-1         , 3
Up Type= 0
Dn Type= 3
Dn Slope=0.01
Boundary for River Rch & Prof#=Stream0666,Reach-1         , 4
Up Type= 0
Dn Type= 3
Dn Slope=0.01
Boundary for River Rch & Prof#=Stream0666,Reach-1         , 5
Up Type= 0
Dn Type= 3
Dn Slope=0.01
Boundary for River Rch & Prof#=Stream0666,Reach-1         , 6
Up Type= 0
Dn Type= 3
Dn Slope=0.01
Boundary for River Rch & Prof#=Stream0666,Reach-1         , 7
Up Type= 0
Dn Type= 3
Dn Slope=0.01
DSS Import GetInterval= 0
DSS Import GetPeak= 0
DSS Import FillOption= 0

--- Stream0666.g01 (geometry) ---

Geom Title=Existing Conditions
Program Version=4.10

River Reach=Stream0666      ,Reach-1
Reach XY= 30
      1963788.29     13893915.81      1964107.74     13893533.87
      1964184.12     13893388.04        1964425.       13893075.
      1964488.27     13893061.53      1964774.07     13892764.52
      1964771.52      13892676.5      1964682.81     13892578.41
      1964722.63     13892519.11      1964724.61     13892440.28
      1964677.27     13892369.06      1964672.73     13892230.94
      1964625.52     13892159.78      1964623.78      13891935.5
      1964575.52     13891859.78      1964572.95     13891230.84
      1964484.69     13891135.77      1964401.21     13891102.02
      1964369.33     13891030.66      1964291.38      13890992.1
      1964267.14     13890868.83      1964081.98     13890674.79
      1964118.29     13890633.16      1964191.65     13890608.35
      1964458.71      13890341.7      1964467.15     13890321.74
      1964428.55     13890273.19      1964424.99     13890240.94
      1964436.97     13890226.05        1964475.       13890225.

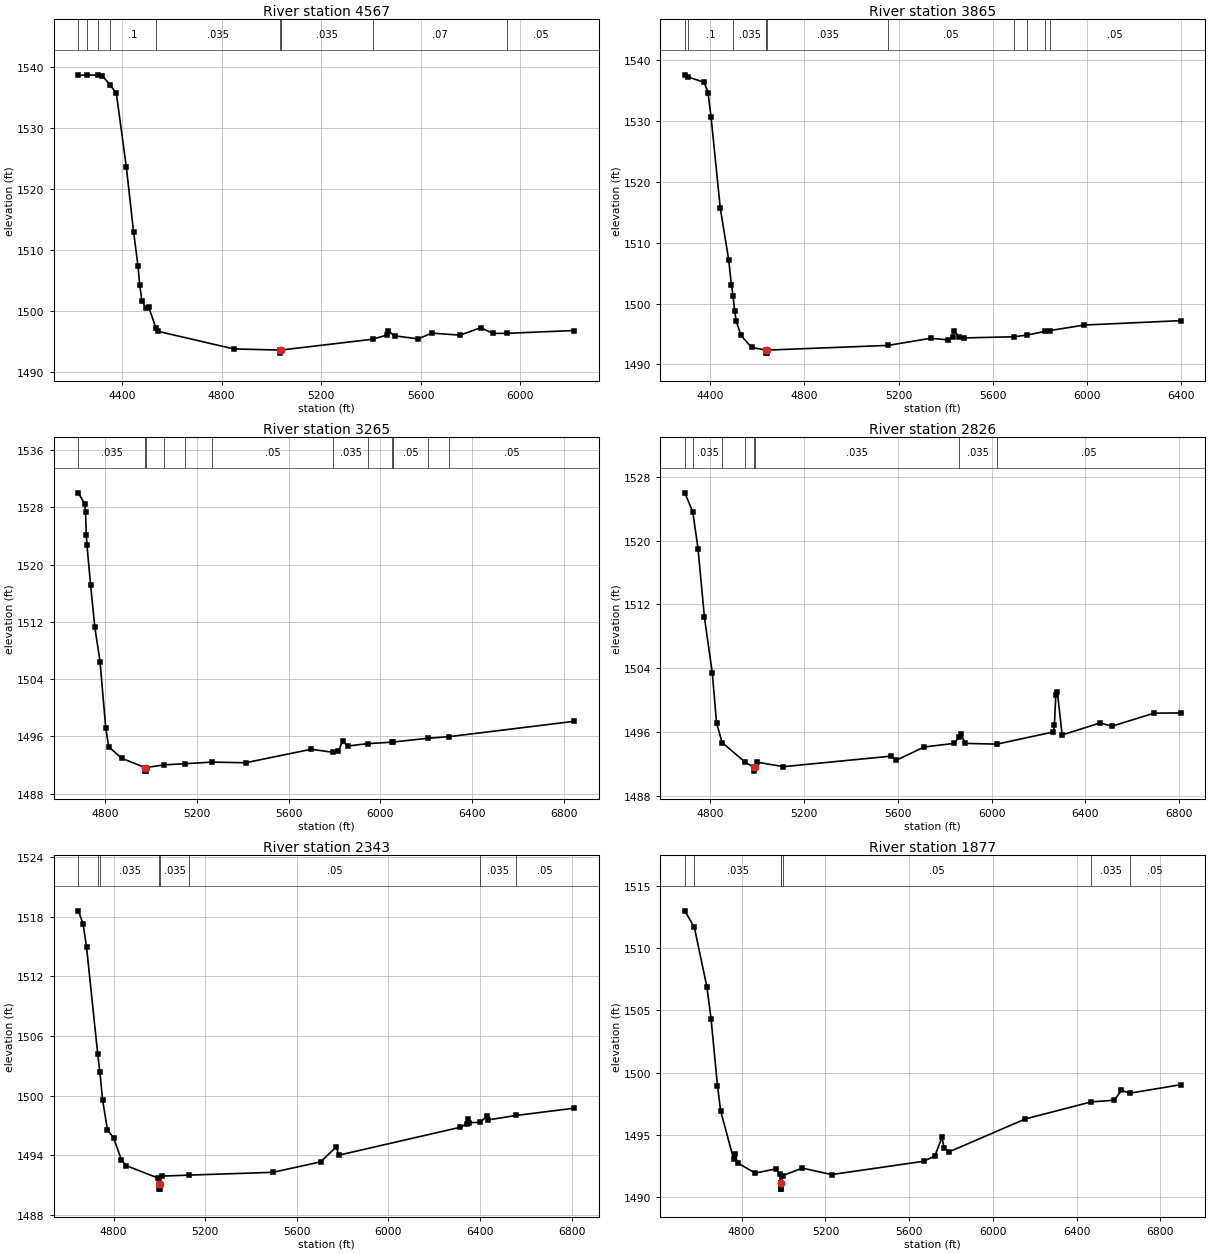
Type RM Length L Ch R = 1 ,4567    ,702,702,702
BEGIN DESCRIPTION:
Stream0666 9.0
END DESCRIPTION:
XS GIS Cut Line= 2
      1964538.28     13894200.53      1962760.53     13893304.71
#Sta/Elev= 30
  4224.8 1538.65  4259.4 1538.76  4302.6 1538.67  4321.5 1538.58  4353.7 1537.03
  4377.4 1535.74  4417.6  1523.6  4446.6    1513  4464.6 1507.34  4471.2 1504.31
  4480.1 1501.69    4498 1500.44  4506.9 1500.72  4535.8 1497.31  4545.1 1496.69
  4848.7 1493.81  5033.5 1493.62  5033.8 1493.12  5037.5 1493.62    5406  1495.4
    5463 1496.07  5469.7 1496.74  5494.2 1495.95  5590.3 1495.46  5643.6  1496.4
  5757.8 1496.07  5840.5  1497.3  5888.8 1496.35  5947.6 1496.37  6215.5 1496.83
#Mann= 9 ,-1 , 0
  4224.8     .07       0  4259.4    .035       0  4302.6     .07       0
  4353.7      .1       0  4535.8    .035       0  5033.5    .035       0
  5037.5    .035       0    5406     .07       0  5947.6     .05       0
#Block Obstruct= 2 , 0
                         5472.56         1496.69
Bank Sta=5033.5,5037.5
XS Rating Curve= 0 ,0
Exp/Cntr=0.3,0.1

Type RM Length L Ch R = 1 ,3865    ,600,600,600
BEGIN DESCRIPTION:
Stream0666 8.0
END DESCRIPTION:
XS GIS Cut Line= 2
      1964913.27     13893561.64       1962968.8     13892749.13
#Sta/Elev= 30
  4291.7  1537.6  4304.9 1537.26  4374.1 1536.38  4390.3 1534.69  4403.3 1530.66
  4442.3 1515.73  4478.4 1507.15  4489.7 1503.09    4497 1501.22  4503.4  1498.8
  4510.6 1497.08  4530.1 1494.79  4575.6 1492.77  4638.7 1492.34  4638.9 1491.84
  4642.4 1491.84  4642.7 1492.34  5155.4 1493.11  5336.5 1494.28  5411.2 1494.02
  5430.8 1494.45  5437.3 1495.51  5456.8 1494.52  5479.5 1494.34  5690.7 1494.53
  5747.8 1494.82  5821.3  1495.4  5843.4 1495.55    5990 1496.46  6399.1 1497.18
#Mann= 10 ,-1 , 0
  4291.7     .07       0  4304.9      .1       0    4497    .035       0
  4638.7    .035       0  4642.7    .035       0  5155.4     .05       0
  5690.7    .035       0  5747.8     .05       0  5821.3    .035       0
  5843.4     .05       0
Bank Sta=4638.7,4642.7
XS Rating Curve= 0 ,0
Exp/Cntr=0.3,0.1

Type RM Length L Ch R = 1 ,3265    ,439,439,439
BEGIN DESCRIPTION:
Stream0666 7.0
END DESCRIPTION:
XS GIS Cut Line= 3
        1964975.       13892975.        1964675.       13892875.
      1962875.03     13892475.01
#Sta/Elev= 30
  4683.8 1530.03    4712 1528.45  4715.1 1527.37  4718.3 1524.16  4721.5 1522.71
  4737.3 1517.11  4755.8 1511.22  4778.4 1506.43  4803.2 1497.15  4816.3 1494.54
  4873.2 1492.92  4974.3 1491.64  4974.5 1491.14  4978.2 1491.14  4978.5 1491.64
    5057 1492.01  5148.6 1492.18  5266.1  1492.4  5412.5 1492.31  5697.4 1494.19
  5794.4 1493.77  5817.2 1494.02  5835.6 1495.29  5857.2 1494.65  5944.2 1494.98
  6050.4 1495.19  6055.4 1495.21    6209 1495.74    6300 1495.96  6843.9  1498.1
#Mann= 12 ,-1 , 0
  4683.8    .035       0  4974.3    .035       0  4978.5    .035       0
    5057     .05       0  5148.6    .035       0  5266.1     .05       0
  5794.4    .035       0  5944.2     .05       0  6050.4    .035       0
  6055.4     .05       0    6209    .035       0    6300     .05       0
Bank Sta=4974.3,4978.5
XS Rating Curve= 0 ,0
Exp/Cntr=0.3,0.1

Type RM Length L Ch R = 1 ,2826    ,483,483,483
BEGIN DESCRIPTION:
Stream0666 6.0
END DESCRIPTION:
XS GIS Cut Line= 3
      1965024.97     13892574.99        1964725.       13892525.
      1962924.98       13892325.
#Sta/Elev= 30
  4691.4 1526.01  4725.4 1523.62  4747.9 1519.01  4775.2 1510.37  4808.7  1503.4
  4826.9 1497.11  4850.6 1494.67    4950 1492.17    4986 1491.58  4986.3 1491.08
  4990.2 1491.58  5000.3  1492.2  5111.9 1491.64  5570.7 1492.96  5593.2 1492.44
  5712.6 1494.11  5840.4 1494.56  5861.8 1495.38  5869.6 1495.71  5887.7 1494.56
    6023 1494.47  6264.2    1496    6268 1496.82    6274 1500.58  6280.5 1501.06
  6301.2 1495.62  6464.2 1497.14  6512.5 1496.71  6693.6 1498.36  6806.6 1498.38
#Mann= 8 ,-1 , 0
  4691.4     .07       0  4725.4    .035       0  4850.6     .07       0
    4950    .035       0    4986    .035       0  4990.2    .035       0
  5861.8    .035       0    6023     .05       0
#Block Obstruct= 2 , 0
                         6280.52          1500.6
Bank Sta=4986,4990.2
XS Rating Curve= 0 ,0
Exp/Cntr=0.3,0.1

Type RM Length L Ch R = 1 ,2343    ,466,466,466
BEGIN DESCRIPTION:
Stream0666 5.0
END DESCRIPTION:
XS GIS Cut Line= 3
      1964974.97       13892125.        1964625.       13892075.
        1962825.       13892275.
#Sta/Elev= 30
  4646.4 1518.58  4667.3 1517.27  4682.4  1514.9  4730.8 1504.22  4740.6 1502.35
  4752.2 1499.58  4773.4 1496.56  4800.6 1495.74    4834 1493.56  4855.2 1492.96
  4994.6  1491.7  4998.5 1491.09  4998.8 1490.59  5002.5 1490.59  5002.8 1491.09
  5009.7  1491.9  5129.9    1492  5495.7 1492.28  5703.9 1493.33  5773.4 1494.86
  5782.4    1494  6313.7 1496.81  6344.1 1497.19  6346.9 1497.63  6349.9 1497.27
  6400.6 1497.31  6431.4 1497.93  6434.4 1497.55  6557.8    1498    6811 1498.73
#Mann= 8 ,-1 , 0
  4646.4    .035       0  4730.8     .07       0  4740.6    .035       0
  4998.5    .035       0  5002.8    .035       0  5129.9     .05       0
  6400.6    .035       0  6557.8     .05       0
Bank Sta=4998.5,5002.8
XS Rating Curve= 0 ,0
Exp/Cntr=0.3,0.1

Type RM Length L Ch R = 1 ,1877    ,467,467,467
BEGIN DESCRIPTION:
Stream0666 4.0
END DESCRIPTION:
XS GIS Cut Line= 3
        1964975.       13891875.        1964575.       13891625.
      1962774.96     13892225.01
#Sta/Elev= 30
  4528.3 1513.01    4574 1511.68  4634.1 1506.87  4653.9 1504.31  4684.4 1498.94
  4699.6 1496.91  4761.5 1493.04  4768.5 1493.47  4780.2 1492.73  4865.1 1491.91
    4963 1492.25  4980.8 1491.84  4985.7 1491.12    4986 1490.62  4989.7 1490.62
    4990 1491.12  4996.8 1491.71  5090.4 1492.31  5229.5 1491.79    5669 1492.86
  5722.8 1493.28  5757.6  1494.8  5767.1 1493.92  5792.4 1493.63    6156 1496.27
  6470.4 1497.64  6579.8 1497.77  6614.6 1498.57  6654.8 1498.34  6897.4 1499.02
#Mann= 7 ,-1 , 0
  4528.3     .07       0    4574    .035       0  4985.7    .035       0
    4990    .035       0  4996.8     .05       0  6470.4    .035       0
  6654.8     .05       0
Bank Sta=4985.7,4990
XS Rating Curve= 0 ,0
Exp/Cntr=0.3,0.1

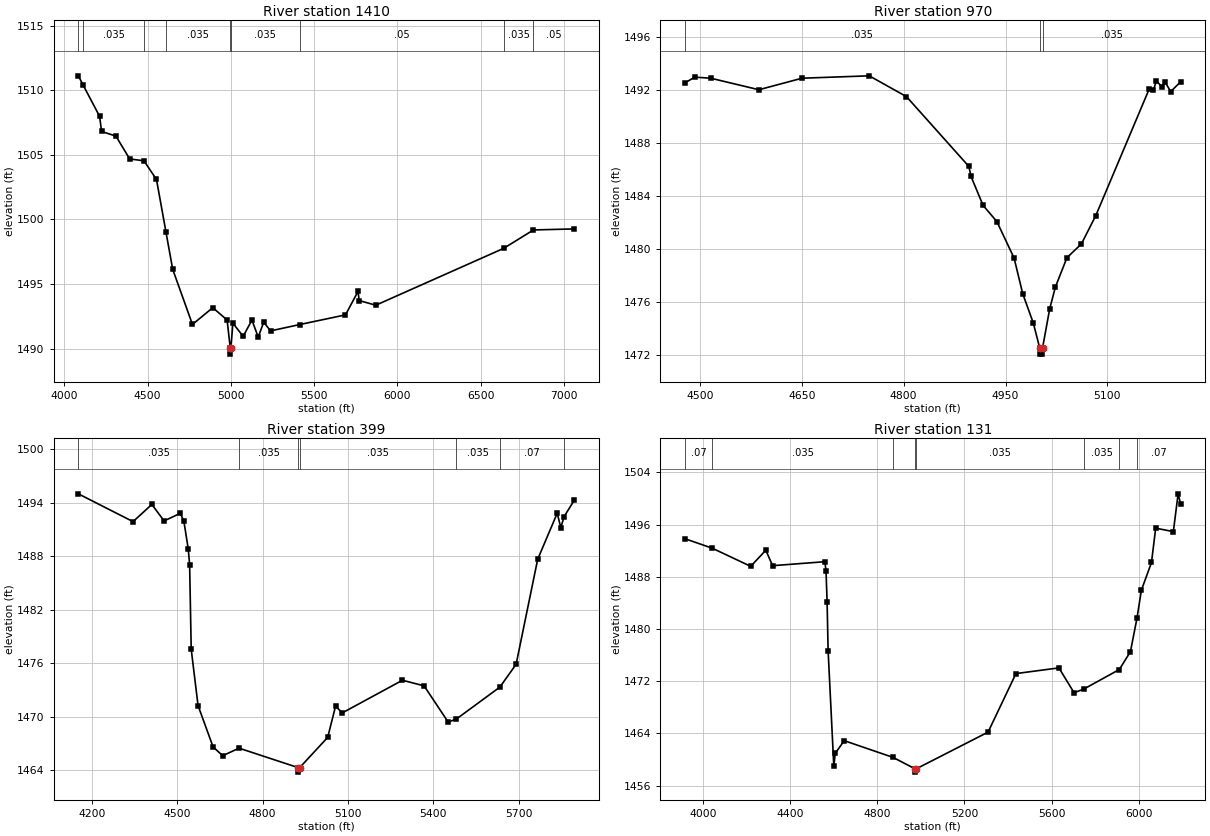
Type RM Length L Ch R = 1 ,1410    ,440,440,440
BEGIN DESCRIPTION:
Stream0666 3.0
END DESCRIPTION:
XS GIS Cut Line= 3
      1965324.98     13891624.99        1964525.       13891175.
      1962724.99     13892175.01
#Sta/Elev= 30
    4084 1511.13  4113.7 1510.39  4211.8 1507.99  4223.6 1506.82  4309.7 1506.46
  4392.4 1504.69  4477.9 1504.55  4553.3  1503.1  4610.6    1499  4650.4 1496.15
  4769.1 1491.87  4891.4 1493.17  4977.4 1492.21  4995.9 1490.07  4996.2 1489.57
  5000.3 1490.07  5011.8 1491.97  5073.6 1490.95  5126.4 1492.21  5163.9 1490.89
  5197.2 1492.04  5238.3 1491.37  5412.6 1491.86  5687.9 1492.61  5763.4 1494.43
  5770.3 1493.72  5870.1 1493.36  6637.1 1497.76  6816.7 1499.19    7061 1499.27
#Mann= 9 ,-1 , 0
    4084     .07       0  4113.7    .035       0  4477.9     .07       0
  4610.6    .035       0  4995.9    .035       0  5000.3    .035       0
  5412.6     .05       0  6637.1    .035       0  6816.7     .05       0
Bank Sta=4995.9,5000.3
XS Rating Curve= 0 ,0
Exp/Cntr=0.3,0.1

Type RM Length L Ch R = 1 ,970     ,571,571,571
BEGIN DESCRIPTION:
Stream0666 2.0
END DESCRIPTION:
XS GIS Cut Line= 4
      1964751.25     13890675.07      1964535.98     13890786.18
        1964275.       13890875.      1964124.98     13891025.02
#Sta/Elev= 30
  4477.7 1492.52  4492.3 1492.96  4515.9 1492.88  4586.8 1492.01  4650.3 1492.88
  4749.3 1493.06  4804.1 1491.49    4896 1486.22  4899.2 1485.46  4916.9 1483.28
  4937.2 1482.06  4962.6  1479.3  4975.3 1476.61    4991 1474.38  5000.1 1472.55
  5000.4 1472.05  5004.3 1472.05  5004.6 1472.55    5015 1475.47  5023.5 1477.13
  5040.4 1479.33  5061.7 1480.37  5082.9 1482.51  5161.4 1492.05  5167.7 1491.96
    5172 1492.68  5180.5 1492.22  5184.7 1492.61  5193.2 1491.87  5207.8 1492.61
#Mann= 3 ,-1 , 0
  4477.7    .035       0  5000.1    .035       0  5004.6    .035       0
Bank Sta=5000.1,5004.6
XS Rating Curve= 0 ,0
Exp/Cntr=0.3,0.1

Type RM Length L Ch R = 1 ,399     ,268,268,268
BEGIN DESCRIPTION:
Stream0666 1.0
END DESCRIPTION:
XS GIS Cut Line= 4
       1965118.5      13890722.5       1964430.3     13890524.17
      1964049.24     13890448.67      1963574.98     13890875.02
#Sta/Elev= 30
  4152.4 1495.02  4344.7  1491.9  4410.7 1493.83  4453.8 1491.98  4510.6 1492.83
  4523.1 1491.98  4538.6 1488.85  4543.5 1487.08  4549.1 1477.58  4573.1 1471.26
  4625.9 1466.62  4659.8 1465.63  4717.2 1466.48  4925.5 1464.29  4925.8 1463.79
  4930.1 1464.29  5028.7 1467.69  5056.2 1471.17  5080.7 1470.45  5291.4  1474.1
  5367.5 1473.47    5452 1469.41  5480.6 1469.74  5633.7 1473.33  5690.8 1475.89
  5766.6 1487.67  5835.2 1492.84  5847.9 1491.23  5859.6 1492.47  5894.8 1494.28
#Mann= 7 ,-1 , 0
  4152.4    .035       0  4717.2    .035       0  4925.5    .035       0
  4930.1    .035       0  5480.6    .035       0  5633.7     .07       0
  5859.6     .05       0
Bank Sta=4925.5,4930.1
XS Rating Curve= 0 ,0
Exp/Cntr=0.3,0.1

Type RM Length L Ch R = 1 ,131     ,0,0,0
BEGIN DESCRIPTION:
Stream0666 0.0
END DESCRIPTION:
XS GIS Cut Line= 5
      1965494.26      13890595.2      1964688.75      13890334.8
      1964379.73     13890293.13      1963980.42     13890372.99
      1963428.36     13890820.89
#Sta/Elev= 30
  3915.9 1493.83  4041.8 1492.37  4218.6 1489.59  4287.9 1492.06    4319 1489.69
  4559.1  1490.3  4564.4  1488.8  4569.2  1484.2  4573.9 1476.68  4600.1 1458.93
  4606.4 1460.92  4647.8 1462.88  4871.8 1460.32  4973.5 1458.56  4973.9 1458.06
  4978.1 1458.56  5308.3 1464.19  5436.3 1473.16  5633.5 1474.03  5703.2 1470.22
  5748.6  1470.8  5910.9 1473.78    5962 1476.52    5992 1481.64  6012.2 1485.93
  6058.6 1490.18  6077.9 1495.44    6159 1494.91  6180.9  1500.7  6192.4 1499.13
#Mann= 8 ,-1 , 0
  3915.9     .07       0  4041.8    .035       0  4871.8    .035       0
  4973.5    .035       0  4978.1    .035       0  5748.6    .035       0
  5910.9     .05       0    5992     .07       0
Bank Sta=4973.5,4978.1
XS Rating Curve= 0 ,0
Exp/Cntr=0.3,0.1

Chan Stop Cuts=-1
Use User Specified Reach Order=0
Composite Channel Slope=5