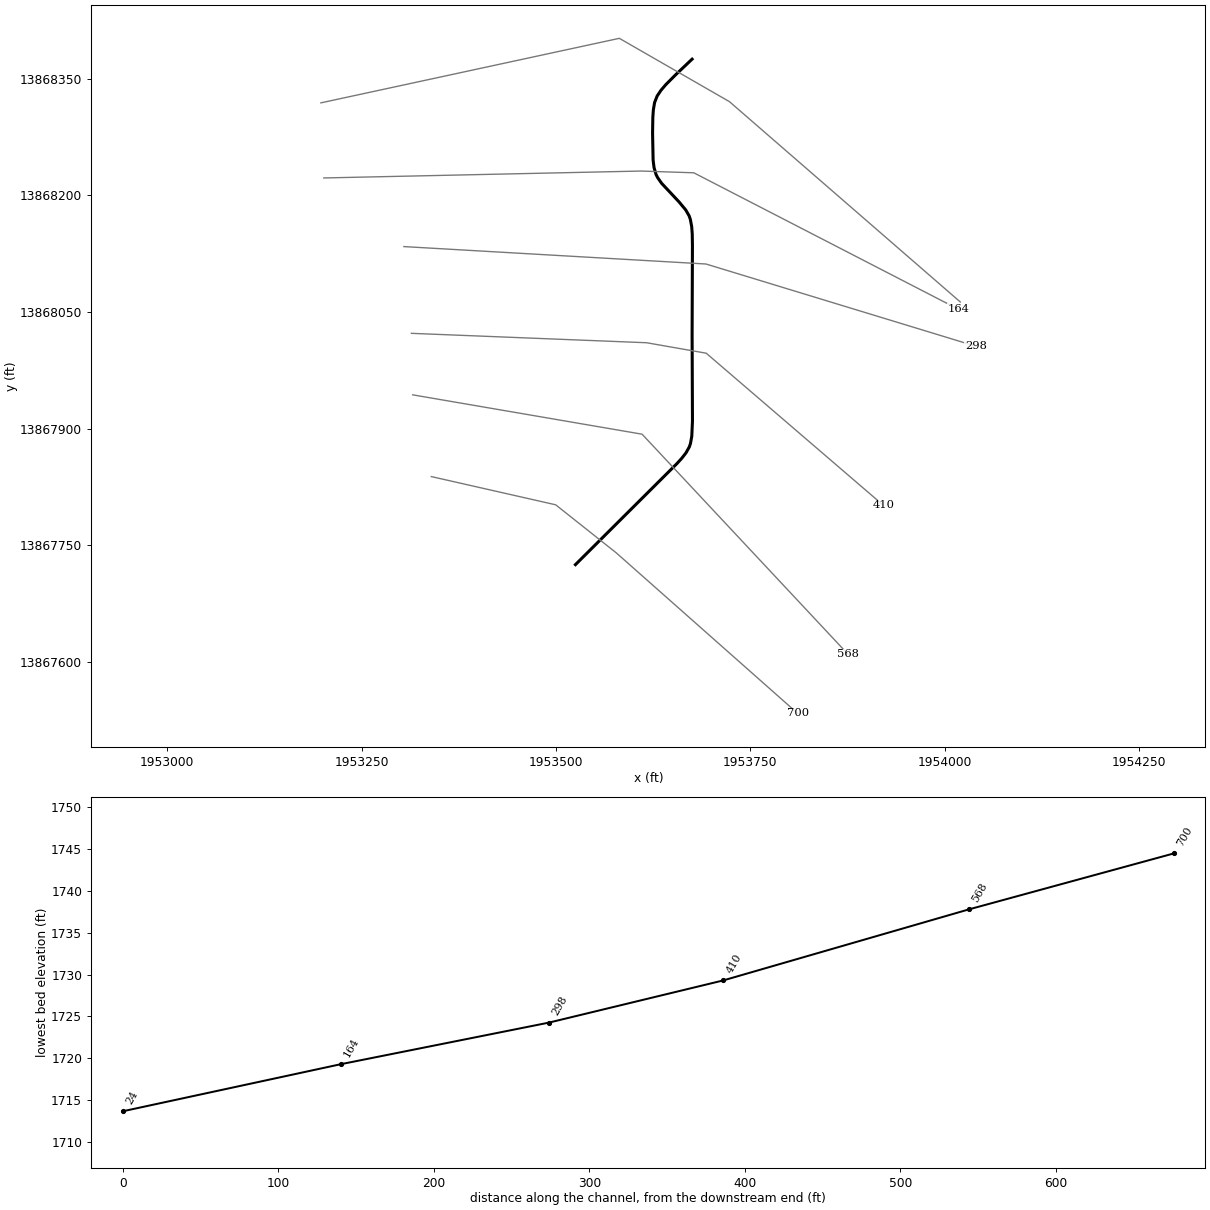
--- Stream0667.prj (project) ---

Proj Title=Stream0667 Base Level Engineering
Current Plan=p01
Default Exp/Contr=0.3,0.1
English Units
Geom File=g01
Flow File=f01
Plan File=p01
Y Axis Title=Elevation
X Axis Title(PF)=Main Channel Distance
X Axis Title(XS)=Station
BEGIN DESCRIPTION:
Stream0667
END DESCRIPTION:
DSS Export Rating Curves= 0
DSS Export Rating Curve Sorted= 0
DSS Export Volume Flow Curves= 0
DXF OffsetX= 0
DXF OffsetY= 0
DXF ScaleX= 1
DXF ScaleY= 10

--- Stream0667.p01 (plan) ---

Plan Title=Multiple Run
Short Identifier=Multiple
Geom File=g01
Flow File=f01
Subcritical Flow
K Sum by GR= 0
Std Step Tol= 0.01
Critical Tol= 0.01
Num of Std Step Trials= 20
Max Error Tol= 0.3
Flow Tol Ratio= 0.001
Split Flow NTrial= 30
Split Flow Tol= 0.02
Split Flow Ratio= 0.02
Log Output Level= 0
Friction Slope Method= 1
Unsteady Friction Slope Method= 2
Unsteady Bridges Friction Slope Method= 1
Parabolic Critical Depth
Global Vel Dist=  1 , 1 , 1
Global Log Level= 0
CheckData=True
Encroach Param= -1, 0, 0, 0
BEGIN DESCRIPTION:
Multiple Run
END DESCRIPTION:

--- Stream0667.f01 (steady flow) ---

Flow Title=Multiple
Program Version=4.10
Number of Profiles= 7
Profile Names=10-year,25-year,50-year,1pct_min,100-year,1pct_plu,500-year
River Rch & RM=Stream0667,Reach-1         ,700
     417     670     899     588    1173    2340    1959
Boundary for River Rch & Prof#=Stream0667,Reach-1         , 1
Up Type= 0
Dn Type= 3
Dn Slope=0.005
Boundary for River Rch & Prof#=Stream0667,Reach-1         , 2
Up Type= 0
Dn Type= 3
Dn Slope=0.005
Boundary for River Rch & Prof#=Stream0667,Reach-1         , 3
Up Type= 0
Dn Type= 3
Dn Slope=0.005
Boundary for River Rch & Prof#=Stream0667,Reach-1         , 4
Up Type= 0
Dn Type= 3
Dn Slope=0.005
Boundary for River Rch & Prof#=Stream0667,Reach-1         , 5
Up Type= 0
Dn Type= 3
Dn Slope=0.005
Boundary for River Rch & Prof#=Stream0667,Reach-1         , 6
Up Type= 0
Dn Type= 3
Dn Slope=0.005
Boundary for River Rch & Prof#=Stream0667,Reach-1         , 7
Up Type= 0
Dn Type= 3
Dn Slope=0.005
DSS Import GetInterval= 0
DSS Import GetPeak= 0
DSS Import FillOption= 0

--- Stream0667.g01 (geometry) ---

Geom Title=Existing Conditions
Program Version=4.10

River Reach=Stream0667      ,Reach-1
Reach XY= 30
        1953525.       13867725.      1953655.41     13867854.83
      1953661.64     13867861.68       1953667.2      13867868.8
      1953671.47     13867876.46      1953672.95     13867880.85
      1953674.62     13867890.16      1953675.49      13867909.8
      1953675.02       13868020.      1953675.45     13868135.19
       1953675.2     13868150.08      1953674.48     13868159.78
      1953672.74     13868169.06      1953671.22     13868173.44
      1953666.86     13868181.06       1953658.1     13868191.58
      1953635.81     13868215.37      1953630.68     13868222.68
       1953628.7     13868226.59      1953626.09     13868235.54
      1953624.89     13868245.08      1953624.19     13868279.99
      1953624.52       13868300.      1953625.19     13868309.78
      1953626.77     13868319.17      1953630.05     13868327.55
      1953634.99     13868334.95      1953641.04     13868342.05
      1953653.59     13868354.67        1953675.       13868375.

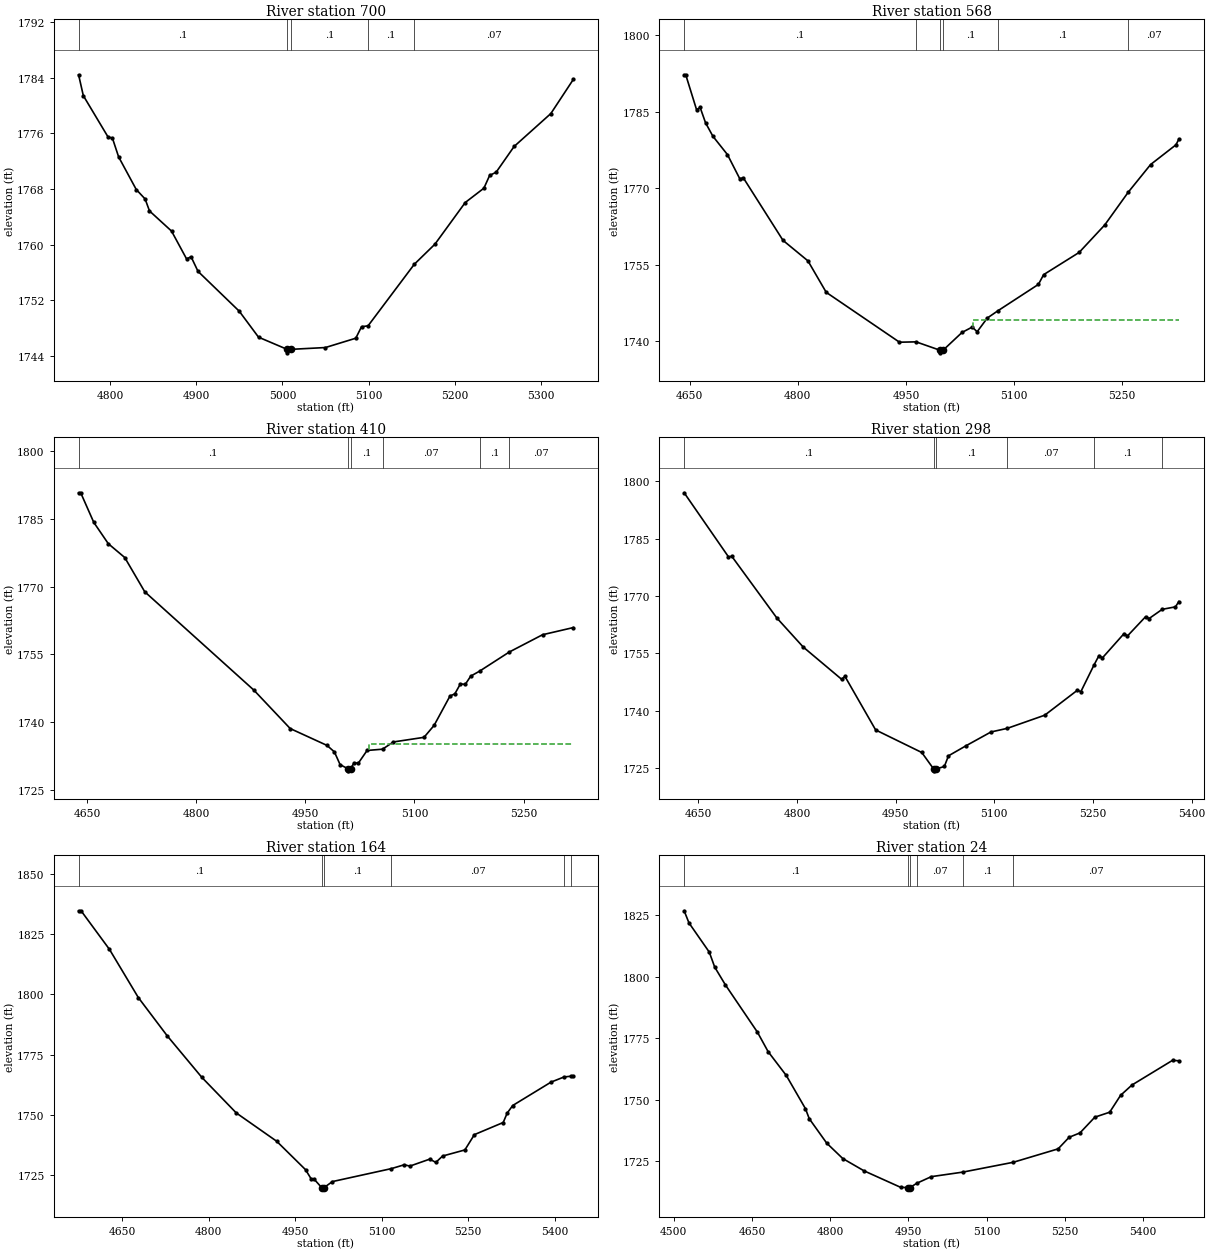
Type RM Length L Ch R = 1 ,700     ,132,132,132
BEGIN DESCRIPTION:
Stream0667 1.0
END DESCRIPTION:
XS GIS Cut Line= 4
      1953339.65     13867838.25      1953499.58     13867801.96
      1953577.55     13867740.12      1953810.73     13867533.75
#Sta/Elev= 30
  4763.1 1784.41  4768.6 1781.41  4797.3 1775.48  4802.4 1775.32  4809.6 1772.62
  4830.1 1767.93  4840.4 1766.57  4845.5 1764.85  4871.1 1761.96  4888.6 1757.96
  4893.8 1758.27  4901.9 1756.17  4949.8 1750.45  4972.2 1746.72  5005.5 1744.97
  5005.7 1744.47  5009.5 1744.97  5049.9 1745.23  5085.2 1746.57  5091.9 1748.22
  5099.5 1748.35  5153.2 1757.19  5177.2 1760.08  5212.4 1766.06  5234.1 1768.12
  5240.8 1769.96  5248.3 1770.41  5269.2 1774.11  5311.9 1778.84    5338 1783.74
#Mann= 5 ,-1 , 0
  4763.1      .1       0  5005.5     .05       0  5009.5      .1       0
  5099.5      .1       0  5153.2     .07       0
Bank Sta=5005.5,5009.5
XS Rating Curve= 0 ,0
Exp/Cntr=0.3,0.1

Type RM Length L Ch R = 1 ,568     ,158,158,158
BEGIN DESCRIPTION:
Mapping XS f2cd382c
END DESCRIPTION:
XS GIS Cut Line= 3
      1953315.72     13867943.35      1953610.71     13867892.75
      1953875.41     13867609.89
#Sta/Elev= 30
  4642.2 1792.19  4644.4 1792.19  4659.4 1785.37  4664.4 1785.79  4671.9 1782.79
  4682.1 1780.16  4702.3 1776.57  4719.4 1771.85  4724.4 1772.01  4779.4 1759.79
    4814 1755.78  4839.4 1749.62  4941.1 1739.86  4964.1 1739.93  4997.5 1738.28
  4997.8 1737.78  5001.5 1738.28  5027.9 1741.77    5042 1742.82  5048.9 1741.91
    5063 1744.59  5077.8 1746.02  5133.9 1751.17  5141.2 1753.08  5190.5 1757.43
    5226  1762.8  5258.6 1769.21  5289.7 1774.63  5324.9 1778.49  5328.9  1779.6
#Mann= 6 ,-1 , 0
  4642.2      .1       0  4964.1      .1       0  4997.5     .05       0
  5001.5      .1       0  5077.8      .1       0  5258.6     .07       0
#XS Ineff= 2 , 0
                         5042.76         1744.11
Permanent Ineff=
       F       F
Bank Sta=4997.5,5001.5
XS Rating Curve= 0 ,0
Exp/Cntr=0.3,0.1

Type RM Length L Ch R = 1 ,410     ,112,112,112
BEGIN DESCRIPTION:
Stream0667 0.5
END DESCRIPTION:
XS GIS Cut Line= 4
      1953314.08     13868022.44      1953616.54     13868010.34
      1953693.17      13867996.9      1953920.84     13867801.37
#Sta/Elev= 30
  4637.9 1790.71  4640.8 1790.71  4658.8 1784.17  4678.8 1779.46  4701.4 1776.41
  4728.9 1768.85    4879 1747.13    4929 1738.64  4979.6 1734.92  4989.8 1733.49
  4997.7 1730.66  5008.1  1729.8  5008.4  1729.3  5012.1  1729.8  5016.8 1731.03
  5022.9 1731.03  5034.8  1733.8    5056 1734.08    5071 1735.68  5113.1  1736.7
    5127 1739.34  5148.9 1745.84  5155.5  1746.3  5163.2 1748.51  5169.8 1748.38
  5177.4 1750.22  5189.6 1751.32  5230.4 1755.54  5276.2 1759.36  5318.5 1760.94
#Mann= 6 ,-1 , 0
  4637.9      .1       0  5008.1     .05       0  5012.1      .1       0
    5056     .07       0  5189.6      .1       0  5230.4     .07       0
#XS Ineff= 2 , 0
                         5037.96         1735.17
Permanent Ineff=
       F       F
Bank Sta=5008.1,5012.1
XS Rating Curve= 0 ,0
Exp/Cntr=0.3,0.1

Type RM Length L Ch R = 1 ,298     ,134,134,134
BEGIN DESCRIPTION:
Mapping XS 10566a79
END DESCRIPTION:
XS GIS Cut Line= 3
      1953304.42     13868133.98      1953692.87     13868111.58
      1954040.01     13868005.79
#Sta/Elev= 30
  4628.5 1797.03  4695.9 1780.26  4700.9 1780.41  4769.3 1764.29  4809.4 1756.68
  4867.9 1748.22  4872.9 1748.99  4919.6 1734.97  4989.7 1729.07  5007.7 1724.77
    5008 1724.27  5011.7 1724.77    5024 1725.41  5030.3  1728.2  5056.9 1730.83
  5094.9 1734.44  5119.7 1735.39  5176.6 1738.83  5226.3 1745.37  5231.5 1744.98
  5251.2 1751.86  5259.1 1754.45  5264.3 1753.83  5297.2 1760.19  5302.4 1759.57
    5330 1764.62  5335.2 1764.12  5355.2 1766.53  5375.3 1767.18  5380.5 1768.58
#Mann= 6 ,-1 , 0
  4628.5      .1       0  5007.7     .05       0  5011.7      .1       0
  5119.7     .07       0  5251.2      .1       0  5355.2     .07       0
Bank Sta=5007.7,5011.7
XS Rating Curve= 0 ,0
Exp/Cntr=0.3,0.1

Type RM Length L Ch R = 1 ,164     ,140,140,140
BEGIN DESCRIPTION:
Stream0667 0.3
END DESCRIPTION:
XS GIS Cut Line= 4
      1953201.42     13868222.24       1953609.6     13868231.13
      1953677.22     13868228.86      1954016.97     13868053.66
#Sta/Elev= 30
    4574 1834.61  4578.3 1834.61  4627.6 1818.59  4677.6 1798.63  4727.6  1782.8
  4787.6 1765.58  4847.6 1750.76  4917.7 1739.02  4967.7 1727.24  4977.5  1723.4
  4982.3  1723.4  4995.7  1719.8  4995.9  1719.3  4999.7  1719.8  5014.3 1722.31
  5116.7 1727.69  5138.9 1729.28  5148.7 1728.73  5183.2 1731.62  5193.7 1730.26
  5205.4  1732.9  5244.1 1735.43  5260.6 1741.78  5310.6 1746.81  5317.5 1750.71
  5327.1 1753.86  5393.6 1763.56  5416.1 1765.69    5428    1766  5432.2 1766.03
#Mann= 6 ,-1 , 0
    4574      .1       0  4995.7     .05       0  4999.7      .1       0
  5116.7     .07       0  5416.1      .1       0    5428     .07       0
Bank Sta=4995.7,4999.7
XS Rating Curve= 0 ,0
Exp/Cntr=0.3,0.1

Type RM Length L Ch R = 1 ,24      ,0,0,0
BEGIN DESCRIPTION:
Stream0667 0.0
END DESCRIPTION:
XS GIS Cut Line= 4
      1953197.68      13868318.8      1953581.46     13868401.77
      1953723.08     13868320.33      1954019.88     13868062.75
#Sta/Elev= 30
  4519.9 1826.83  4529.1 1821.91  4568.1 1810.01  4578.5 1803.92    4599 1796.68
  4660.4 1777.46  4680.9 1769.54  4715.8 1759.82  4752.5 1746.34  4759.9 1742.22
  4793.4 1732.28  4824.1 1726.03    4865 1721.01    4935 1714.32  4948.8 1714.19
  4949.1 1713.69  4952.8 1714.19  4966.4 1715.98    4994 1718.65  5054.3 1720.49
  5151.1 1724.49  5237.3 1729.96  5258.4 1734.67  5279.2 1736.45  5307.7 1742.85
  5336.2 1744.87  5357.1 1751.74    5379 1755.95  5456.8 1765.98  5468.9 1765.79
#Mann= 6 ,-1 , 0
  4519.9      .1       0  4948.8     .05       0  4952.8      .1       0
  4966.4     .07       0  5054.3      .1       0  5151.1     .07       0
Bank Sta=4948.8,4952.8
XS Rating Curve= 0 ,0
Exp/Cntr=0.3,0.1

Chan Stop Cuts=-1
Use User Specified Reach Order=0
Composite Channel Slope=5