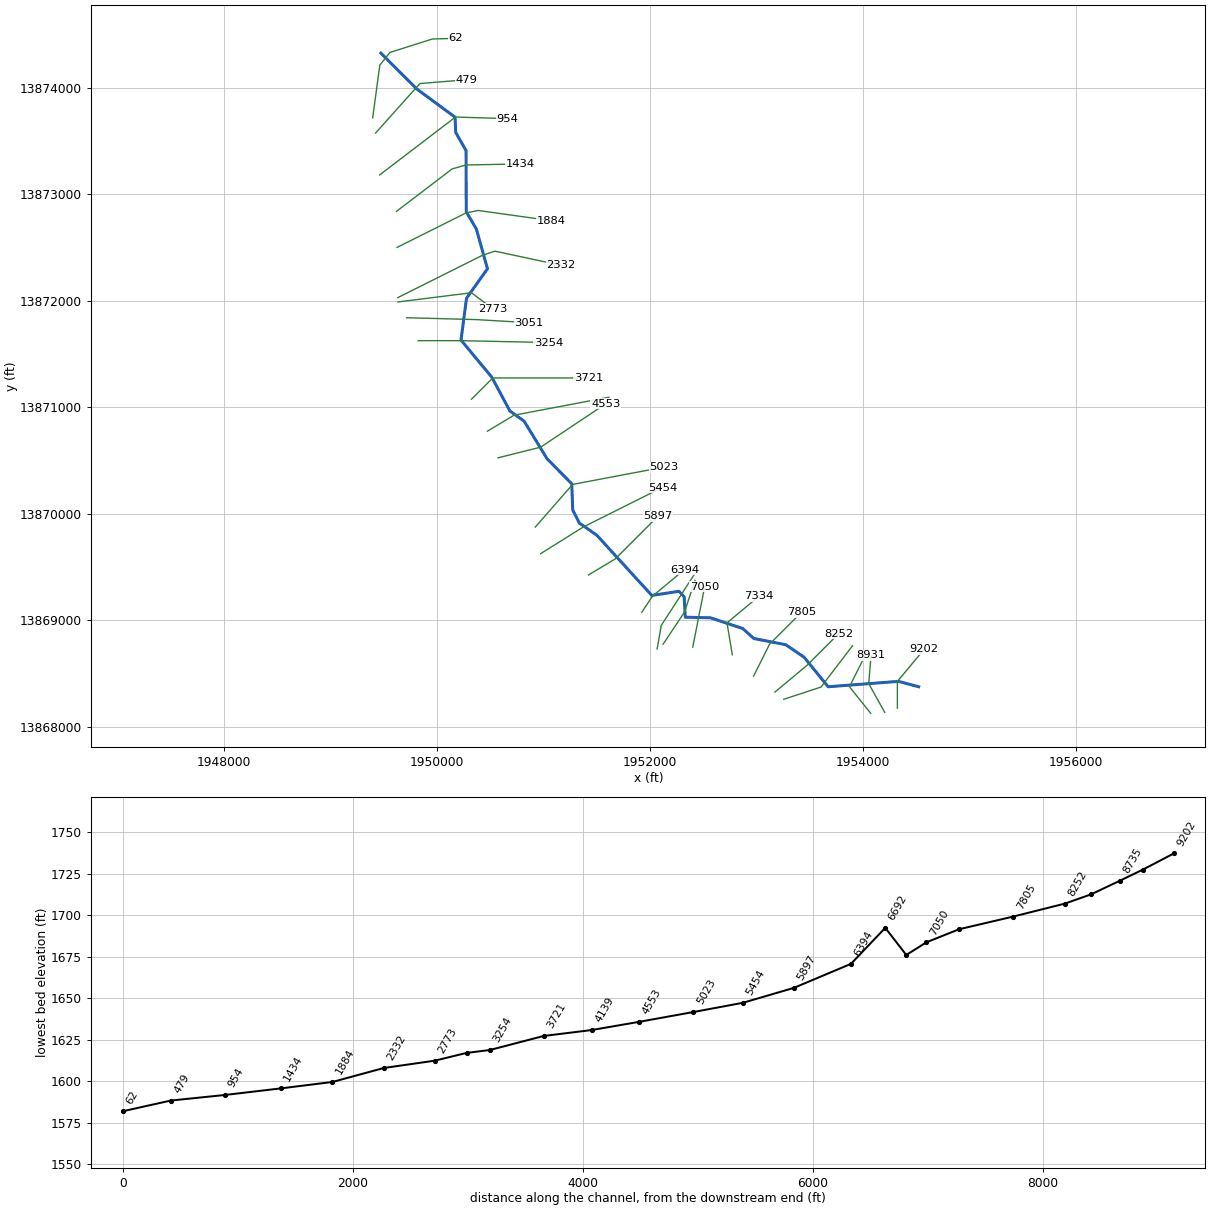
--- Stream0669.prj (project) ---

Proj Title=Stream0669 Base Level Engineering
Current Plan=p01
Default Exp/Contr=0.3,0.1
English Units
Geom File=g01
Flow File=f01
Plan File=p01
Y Axis Title=Elevation
X Axis Title(PF)=Main Channel Distance
X Axis Title(XS)=Station
BEGIN DESCRIPTION:
Stream0669
END DESCRIPTION:
DSS Export Rating Curves= 0
DSS Export Rating Curve Sorted= 0
DSS Export Volume Flow Curves= 0
DXF OffsetX= 0
DXF OffsetY= 0
DXF ScaleX= 1
DXF ScaleY= 10

--- Stream0669.p01 (plan) ---

Plan Title=Multiple Run
Short Identifier=Multiple
Geom File=g01
Flow File=f01
Subcritical Flow
K Sum by GR= 0
Std Step Tol= 0.01
Critical Tol= 0.01
Num of Std Step Trials= 20
Max Error Tol= 0.3
Flow Tol Ratio= 0.001
Split Flow NTrial= 30
Split Flow Tol= 0.02
Split Flow Ratio= 0.02
Log Output Level= 0
Friction Slope Method= 1
Unsteady Friction Slope Method= 2
Unsteady Bridges Friction Slope Method= 1
Parabolic Critical Depth
Global Vel Dist=  1 , 1 , 1
Global Log Level= 0
CheckData=True
Encroach Param= -1, 0, 0, 0
BEGIN DESCRIPTION:
Multiple Run
END DESCRIPTION:

--- Stream0669.f01 (steady flow) ---

Flow Title=Multiple
Number of Profiles=7
Profile Names=10-year,25-year,50-year,1pct_min,100-year,1pct_plu,500-year
River Rch & RM= Stream0669,Reach-1,9202
     776    1303    1800    1207    2409    4807    4249
River Rch & RM= Stream0669,Reach-1,8483
    1198    2063    2898    1972    3935    7851    7154
River Rch & RM= Stream0669,Reach-1,5897
    2139    3792    5427    3751    7485   14934   14065
Boundary for River Rch & Prof#=Stream0669,Reach-1,1
Up Type=0
Dn Type=3
Dn Slope=0.005
Boundary for River Rch & Prof#=Stream0669,Reach-1,2
Up Type=0
Dn Type=3
Dn Slope=0.005
Boundary for River Rch & Prof#=Stream0669,Reach-1,3
Up Type=0
Dn Type=3
Dn Slope=0.005
Boundary for River Rch & Prof#=Stream0669,Reach-1,4
Up Type=0
Dn Type=3
Dn Slope=0.005
Boundary for River Rch & Prof#=Stream0669,Reach-1,5
Up Type=0
Dn Type=3
Dn Slope=0.005
Boundary for River Rch & Prof#=Stream0669,Reach-1,6
Up Type=0
Dn Type=3
Dn Slope=0.005
Boundary for River Rch & Prof#=Stream0669,Reach-1,7
Up Type=0
Dn Type=3
Dn Slope=0.005

--- Stream0669.g01 (geometry) ---

Geom Title=Existing Conditions
Program Version=4.10

River Reach=Stream0669      ,Reach-1
Reach XY= 30
        1954525.       13868375.      1954335.19     13868425.45
        1953675.       13868375.      1953448.84     13868652.14
      1953277.44     13868769.52       1952976.5     13868828.62
       1952873.5     13868921.38      1952569.06     13869022.74
      1952332.91     13869027.91      1952323.03     13869219.35
      1952273.78     13869271.57      1952018.94     13869232.48
      1951501.82      13869798.7      1951338.61     13869911.76
       1951276.2      13870035.5      1951267.19     13870281.19
      1951035.76     13870515.32      1950819.38     13870869.38
      1950685.77      13870965.3      1950516.86     13871281.06
      1950227.06     13871630.85      1950278.76     13872023.44
      1950475.52     13872299.88      1950371.17     13872673.42
       1950276.2      13872835.5      1950274.49     13873409.79
      1950177.25     13873580.93      1950171.46     13873723.54
      1949811.79     13873988.63        1949475.       13874325.

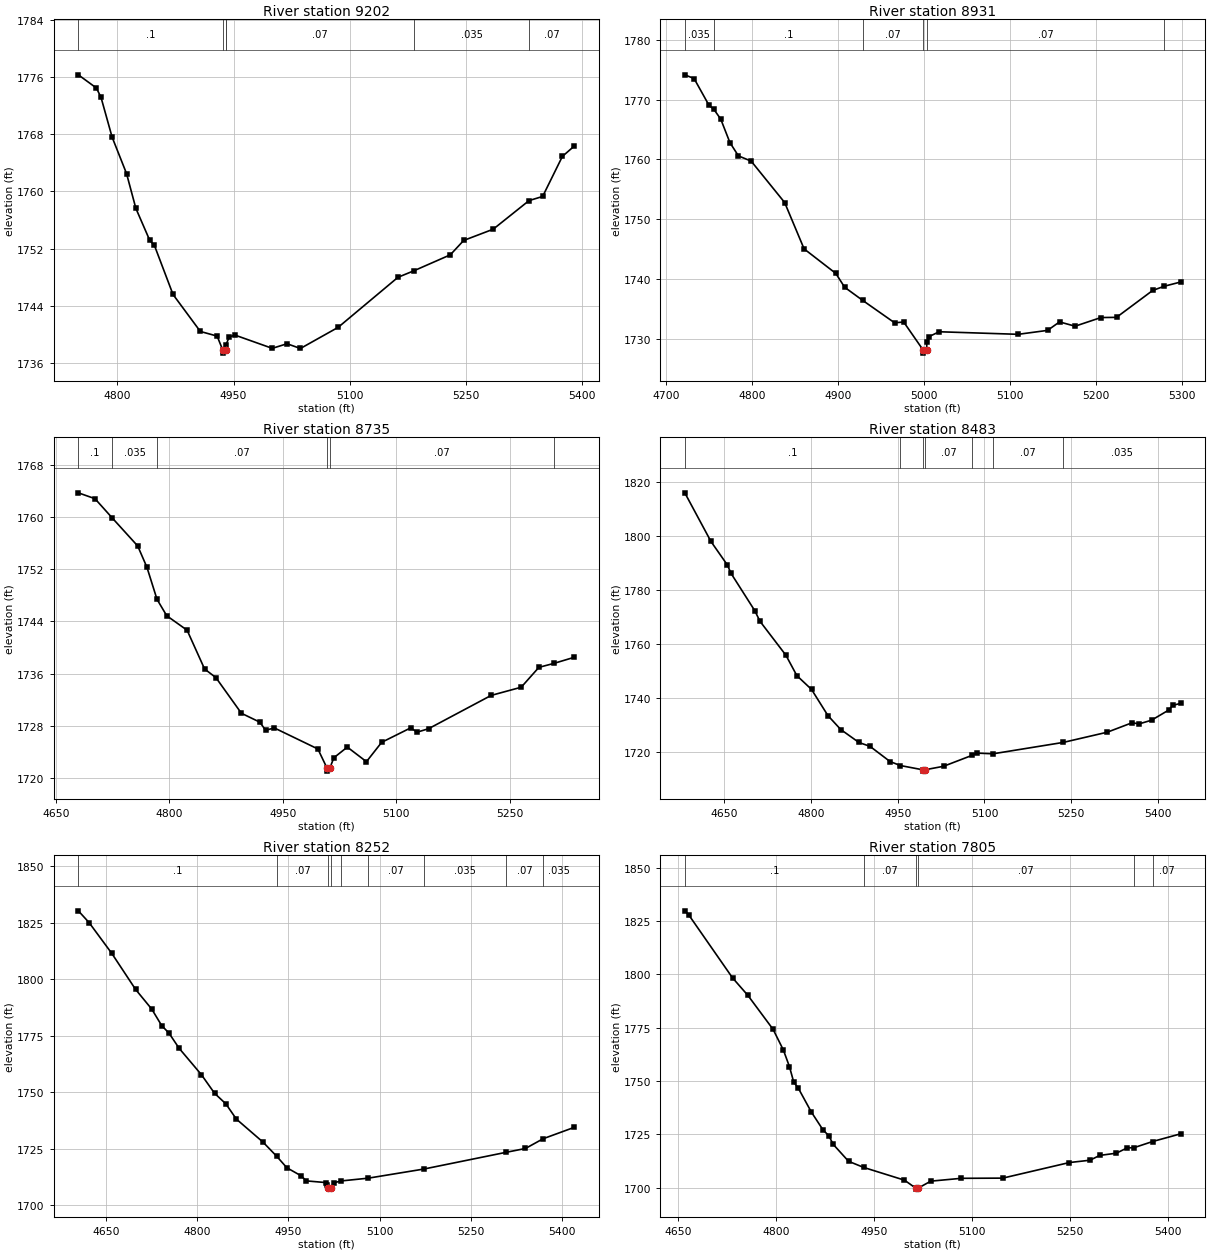
Type RM Length L Ch R = 1 ,9202    ,271,271,271
BEGIN DESCRIPTION:
Stream0669 20.0
END DESCRIPTION:
XS GIS Cut Line= 3
        1954325.       13868175.        1954325.       13868425.
      1954574.99     13868724.99
#Sta/Elev= 30
  4749.5 1776.29  4772.8 1774.45  4778.8 1773.14  4793.1 1767.59  4811.8 1762.48
  4823.8 1757.63  4841.8 1753.14  4847.8 1752.44  4871.8 1745.59  4907.1 1740.42
  4928.8 1739.77  4935.8 1737.89  4936.1 1737.39  4939.8 1737.89    4940 1738.49
  4944.5 1739.67  4952.1  1739.9    5000 1738.06  5019.1  1738.7  5036.4 1738.04
  5085.2    1741  5162.4 1747.99    5183  1748.9    5230 1751.13  5247.3 1753.14
  5285.4 1754.71  5331.7 1758.71  5349.3 1759.29  5374.8 1764.89    5390 1766.32
#Mann= 6 ,-1 , 0
  4749.5      .1       0  4935.8     .05       0  4939.8      .1       0
    4940     .07       0    5183    .035       0  5331.7     .07       0
Bank Sta=4935.8,4939.8
XS Rating Curve= 0 ,0
Exp/Cntr=0.3,0.1

Type RM Length L Ch R = 1 ,8931    ,196,196,196
BEGIN DESCRIPTION:
Mapping XS 593616b9
END DESCRIPTION:
XS GIS Cut Line= 3
       1954205.9     13868134.85      1954055.52     13868404.56
      1954078.51     13868671.68
#Sta/Elev= 30
  4721.9 1774.18  4732.7 1773.56  4749.9 1769.12  4755.8 1768.38  4763.7 1766.77
  4774.4 1762.83  4784.3  1760.6  4799.1 1759.73  4838.1 1752.79  4860.7 1745.03
  4897.6 1740.92  4907.9  1738.6  4928.9  1736.4    4966 1732.65  4976.6 1732.78
  4999.3 1728.07  4999.5 1727.57  5003.3 1728.07  5003.5 1729.36  5006.3 1730.35
  5017.8 1731.15  5109.8 1730.72    5144 1731.38  5157.9  1732.8    5176 1732.08
  5206.1 1733.53  5224.2 1733.56  5266.3 1738.07  5279.9 1738.78  5298.8 1739.48
#Mann= 6 ,-1 , 0
  4721.9    .035       0  4755.8      .1       0  4928.9     .07       0
  4999.3     .05       0  5003.3     .07       0  5279.9    .035       0
Bank Sta=4999.3,5003.3
XS Rating Curve= 0 ,0
Exp/Cntr=0.3,0.1

Type RM Length L Ch R = 1 ,8735    ,252,252,252
BEGIN DESCRIPTION:
Stream0669 19.0
END DESCRIPTION:
XS GIS Cut Line= 3
      1954074.98     13868125.03        1953875.       13868375.
      1954024.98     13868674.97
#Sta/Elev= 30
  4679.9 1763.75  4701.9 1762.85  4724.6 1759.91  4758.4 1755.59  4770.6 1752.32
  4783.9  1747.4  4796.8 1744.88  4823.7 1742.66  4846.8 1736.71  4861.8 1735.38
  4895.5 1729.91  4919.8 1728.55  4927.5  1727.3    4939 1727.66  4996.6 1724.43
  5008.5 1721.53  5008.7 1721.03  5012.5 1721.53  5017.7 1723.08  5035.5 1724.72
  5060.8 1722.48  5080.9 1725.45  5119.3 1727.67  5127.8 1727.01  5142.9 1727.54
  5225.6 1732.65  5265.4 1733.91  5288.8 1736.96  5308.4 1737.56  5335.4  1738.5
#Mann= 6 ,-1 , 0
  4679.9      .1       0  4724.6    .035       0  4783.9     .07       0
  5008.5     .05       0  5012.5     .07       0  5308.4    .035       0
Bank Sta=5008.5,5012.5
XS Rating Curve= 0 ,0
Exp/Cntr=0.3,0.1

Type RM Length L Ch R = 1 ,8483    ,231,231,231
BEGIN DESCRIPTION:
Stream0669 18.1
END DESCRIPTION:
XS GIS Cut Line= 3
      1953258.38     13868257.41      1953607.35       13868372.
      1953904.25     13868760.92
#Sta/Elev= 30
  4582.3 1815.85  4627.5 1797.82  4655.9  1789.1  4662.2    1786  4703.3 1772.15
  4712.1 1768.28    4757 1755.67  4775.9 1748.12  4801.2 1743.02  4829.6 1733.31
  4851.7 1728.16  4883.2 1723.35  4902.2 1721.93  4936.9 1716.29  4954.7 1714.81
  4993.3 1713.24  4993.6 1712.74  4997.3 1713.24  5029.3 1714.53    5078 1718.54
  5086.8 1719.42  5114.8 1719.16  5236.2 1723.38  5312.3 1727.17    5355 1730.66
  5367.2 1730.25  5388.6  1731.6  5418.6  1735.4    5425 1737.07  5438.9 1737.86
#Mann= 7 ,-1 , 0
  4582.3      .1       0  4954.7     .07       0  4993.3     .05       0
  4997.3     .07       0    5078    .035       0  5114.8     .07       0
  5236.2    .035       0
Bank Sta=4993.3,4997.3
XS Rating Curve= 0 ,0
Exp/Cntr=0.3,0.1

Type RM Length L Ch R = 1 ,8252    ,447,447,447
BEGIN DESCRIPTION:
Stream0669 18.0
END DESCRIPTION:
XS GIS Cut Line= 3
      1953175.04     13868325.03        1953475.       13868575.
      1953774.98     13868874.98
#Sta/Elev= 30
  4604.7 1830.33  4622.4 1825.11  4659.7 1811.47  4698.8 1795.52  4725.4 1786.79
  4741.7  1779.5  4753.5 1776.23  4770.5  1769.4  4806.8 1757.82  4828.5 1749.55
  4847.2 1744.83  4864.3 1738.13  4908.2  1727.9  4930.9 1721.57  4947.3 1716.57
  4970.8 1712.99  4979.3 1710.75  5011.2 1710.01    5014 1709.12  5015.5  1707.6
  5015.8  1707.1  5019.5  1707.6  5025.3 1709.97  5037.1 1710.74    5081 1711.95
  5172.2 1715.98  5307.2 1723.38  5339.3 1725.09  5368.4 1729.41  5419.4 1734.44
#Mann= 9 ,-1 , 0
  4604.7      .1       0  4930.9     .07       0  5015.5     .05       0
  5019.5     .07       0  5037.1    .035       0    5081     .07       0
  5172.2    .035       0  5307.2     .07       0  5368.4    .035       0
Bank Sta=5015.5,5019.5
XS Rating Curve= 0 ,0
Exp/Cntr=0.3,0.1

Type RM Length L Ch R = 1 ,7805    ,471,471,471
BEGIN DESCRIPTION:
Stream0669 17.0
END DESCRIPTION:
XS GIS Cut Line= 3
      1952974.98     13868474.96        1953125.       13868775.
      1953424.99     13869074.99
#Sta/Elev= 30
    4660 1829.84    4666 1827.95  4733.1 1798.42  4756.6 1790.21  4795.4  1774.2
  4811.1 1764.52  4820.3 1756.81    4827 1749.41  4833.5  1746.9  4853.8 1735.53
  4871.5 1727.22  4880.7 1724.32  4887.4 1720.32  4910.9 1712.39  4934.2 1709.49
  4996.6 1703.53  5013.7 1699.83    5014 1699.33  5017.7 1699.83  5036.9 1703.07
  5083.6  1704.4  5147.2 1704.49  5249.1 1711.79  5280.9 1712.89  5295.7 1715.14
  5321.2 1716.18  5338.1 1718.72  5347.8 1718.72  5376.8 1721.66  5419.7 1725.26
#Mann= 6 ,-1 , 0
    4660      .1       0  4934.2     .07       0  5013.7     .05       0
  5017.7     .07       0  5347.8    .035       0  5376.8     .07       0
Bank Sta=5013.7,5017.7
XS Rating Curve= 0 ,0
Exp/Cntr=0.3,0.1

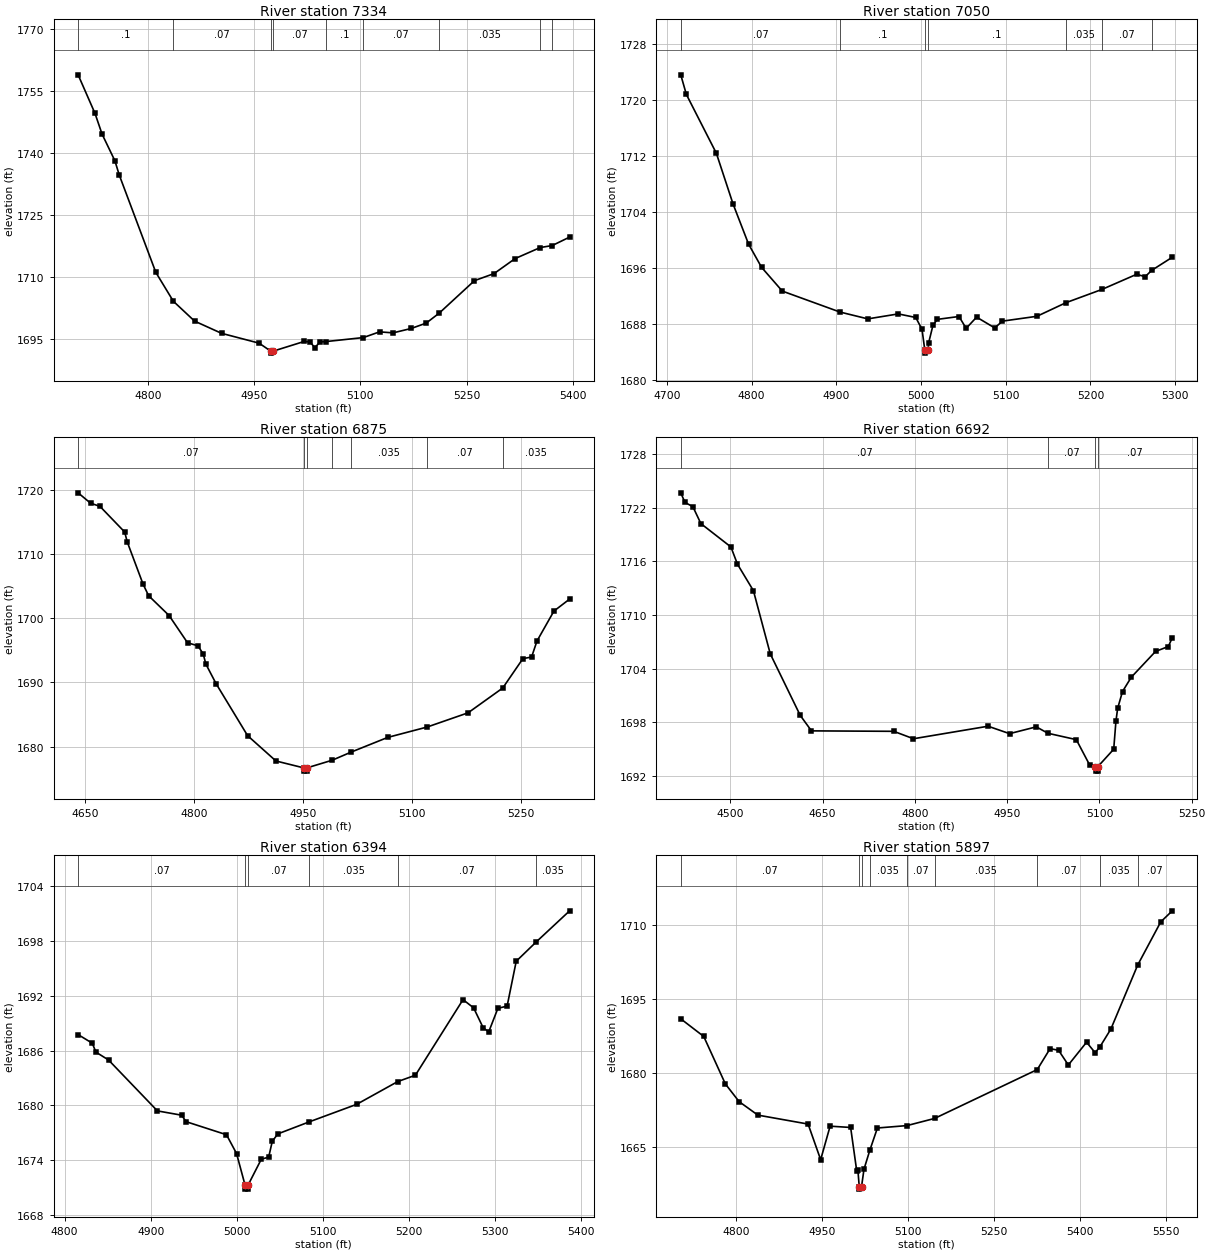
Type RM Length L Ch R = 1 ,7334    ,284,284,284
BEGIN DESCRIPTION:
Stream0669 16.0
END DESCRIPTION:
XS GIS Cut Line= 3
        1952775.     13868674.99        1952725.       13868975.
      1953025.03     13869225.03
#Sta/Elev= 30
    4701 1758.97  4724.9 1749.63  4734.8 1744.66    4753 1738.18  4759.1 1734.77
  4810.8 1711.22  4835.6 1704.23  4865.6 1699.43  4903.7 1696.48  4956.8  1694.1
  4973.1 1692.19  4973.3 1691.69  4977.1 1692.19  5020.5 1694.51    5029  1694.4
  5035.4    1693  5043.1  1694.4  5051.6 1694.49  5104.1 1695.45    5127 1696.83
  5146.1 1696.59  5171.8 1697.65    5193 1698.95  5211.3 1701.35  5261.2 1709.21
  5288.9 1710.92  5318.7 1714.55  5354.1 1717.21  5371.1  1717.7  5395.7 1719.74
#Mann= 9 ,-1 , 0
    4701      .1       0  4835.6     .07       0  4973.1     .05       0
  4977.1     .07       0  5051.6      .1       0  5104.1     .07       0
  5211.3    .035       0  5354.1     .07       0  5371.1      .1       0
Bank Sta=4973.1,4977.1
XS Rating Curve= 0 ,0
Exp/Cntr=0.3,0.1

Type RM Length L Ch R = 1 ,7050    ,175,175,175
BEGIN DESCRIPTION:
Mapping XS 76591673
END DESCRIPTION:
XS GIS Cut Line= 2
       1952403.5     13868746.81      1952515.18     13869315.95
#Sta/Elev= 30
  4716.5 1723.56  4723.1 1720.76  4758.5 1712.36  4778.2 1705.12  4796.5 1699.39
  4811.8 1696.08  4836.3 1692.68  4904.3 1689.69  4937.2 1688.71  4973.2 1689.42
  4993.8 1688.91  5001.2 1687.21  5004.4 1684.32  5004.7 1683.82  5008.4 1684.32
    5009 1685.29  5014.1 1687.79  5019.2 1688.64  5044.8 1689.05  5053.3 1687.36
  5065.6 1688.96    5087 1687.42  5096.1 1688.39  5136.8 1689.08  5171.2 1691.03
  5213.4 1692.91  5254.3 1695.07  5264.6 1694.74  5272.1 1695.63  5296.5 1697.51
#Mann= 7 ,-1 , 0
  4716.5     .07       0  4904.3      .1       0  5004.4     .05       0
  5008.4      .1       0  5171.2    .035       0  5213.4     .07       0
  5272.1    .035       0
Bank Sta=5004.4,5008.4
XS Rating Curve= 0 ,0
Exp/Cntr=0.3,0.1

Type RM Length L Ch R = 1 ,6875    ,183,183,183
BEGIN DESCRIPTION:
Stream0669 15.0
END DESCRIPTION:
XS GIS Cut Line= 3
      1952124.97     13868774.96        1952325.       13869075.
      1952424.99     13869374.97
#Sta/Elev= 30
  4640.5 1719.52  4657.6 1717.91  4670.6 1717.41  4704.6 1713.42  4708.2 1711.86
  4729.9 1705.31  4737.6  1703.5  4765.8 1700.41  4791.2 1696.17  4805.6  1695.7
  4812.8 1694.41  4816.4 1692.86  4830.4 1689.82  4873.9 1681.71  4912.9 1677.77
  4951.4 1676.69  4951.7 1676.19  4955.2 1676.19  4955.4 1676.69  4990.4 1677.89
  5016.4 1679.15  5066.8 1681.44  5121.2 1683.06  5177.5 1685.27  5225.2 1689.13
    5253 1693.71  5264.9 1693.95  5272.4 1696.46  5295.7 1701.11  5317.3 1702.98
#Mann= 7 ,-1 , 0
  4640.5     .07       0  4951.4     .05       0  4955.4     .07       0
  4990.4      .1       0  5016.4    .035       0  5121.2     .07       0
  5225.2    .035       0
Bank Sta=4951.4,4955.4
XS Rating Curve= 0 ,0
Exp/Cntr=0.3,0.1

Type RM Length L Ch R = 1 ,6692    ,298,298,298
BEGIN DESCRIPTION:
Stream0669 0.2
END DESCRIPTION:
XS GIS Cut Line= 3
      1952068.72     13868730.07      1952107.78     13868951.42
      1952420.27     13869433.17
#Sta/Elev= 30
  4419.4 1723.65  4426.2 1722.58  4439.1  1722.1  4452.1 1720.21  4500.9  1717.6
  4511.6 1715.67  4537.5 1712.71  4564.9 1705.65  4613.6 1698.77  4631.9 1697.04
  4765.6 1696.99  4797.7 1696.16    4919 1697.56  4953.9 1696.73  4997.3 1697.49
  5016.4 1696.77  5062.4 1696.06  5084.3  1693.2  5093.4 1693.04  5093.6 1692.54
  5097.1 1692.54  5097.4 1693.04  5123.2 1694.99  5126.8 1698.11  5129.6 1699.56
  5137.5 1701.44  5151.8 1703.04  5191.2 1705.92    5212 1706.47  5218.4 1707.45
#Mann= 4 ,-1 , 0
  4419.4     .07       0  5016.4     .07       0  5093.4     .05       0
  5097.4     .07       0
Bank Sta=5093.4,5097.4
XS Rating Curve= 0 ,0
Exp/Cntr=0.3,0.1

Type RM Length L Ch R = 1 ,6394    ,497,497,497
BEGIN DESCRIPTION:
Stream0669 14.0
END DESCRIPTION:
XS GIS Cut Line= 3
      1951924.98     13869074.96        1952025.       13869225.
      1952324.98     13869474.98
#Sta/Elev= 30
  4815.6 1687.76    4832 1686.82  4836.3 1685.84  4850.9 1684.98  4907.7  1679.4
  4935.8 1678.93    4941 1678.22  4987.9 1676.79  4999.6 1674.73  5009.3 1671.33
  5009.5 1670.83    5013 1670.83  5013.3 1671.33  5028.3  1674.1  5036.9 1674.34
  5041.1 1676.07  5047.5 1676.88    5084  1678.2  5139.1 1680.12  5186.7 1682.61
  5207.3 1683.31  5262.6 1691.59  5274.9 1690.69  5286.1 1688.49  5292.5 1688.07
  5303.1 1690.64  5313.8 1690.88  5324.4  1695.8  5347.7 1697.92  5386.4 1701.32
#Mann= 6 ,-1 , 0
  4815.6     .07       0  5009.3     .05       0  5013.3     .07       0
    5084    .035       0  5186.7     .07       0  5347.7    .035       0
Bank Sta=5009.3,5013.3
XS Rating Curve= 0 ,0
Exp/Cntr=0.3,0.1

Type RM Length L Ch R = 1 ,5897    ,443,443,443
BEGIN DESCRIPTION:
Stream0669 13.0
END DESCRIPTION:
XS GIS Cut Line= 3
      1951424.96     13869424.98        1951675.       13869575.
      1952075.02     13869975.02
#Sta/Elev= 30
  4703.6 1690.97  4743.7 1687.38  4781.4 1677.73  4805.4 1674.13  4838.1 1671.39
  4925.7 1669.57  4947.6 1662.33  4964.1 1669.14  4999.9 1668.88  5010.5 1660.06
  5012.6 1660.14  5014.9 1656.84  5015.1 1656.34  5018.9 1656.84  5023.2 1660.39
  5033.3 1664.22  5046.6 1668.77  5098.2 1669.26  5146.2 1670.71  5325.4 1680.65
  5347.8 1684.91  5362.6 1684.57  5379.6 1681.58  5411.4 1686.21  5426.3 1684.09
  5434.7 1685.27  5453.8 1688.89  5500.6 1701.91  5540.8 1710.68  5560.9 1712.93
#Mann= 9 ,-1 , 0
  4703.6     .07       0  5014.9     .05       0  5018.9     .07       0
  5033.3    .035       0  5098.2     .07       0  5146.2    .035       0
  5325.4     .07       0  5434.7    .035       0  5500.6     .07       0
Bank Sta=5014.9,5018.9
XS Rating Curve= 0 ,0
Exp/Cntr=0.3,0.1

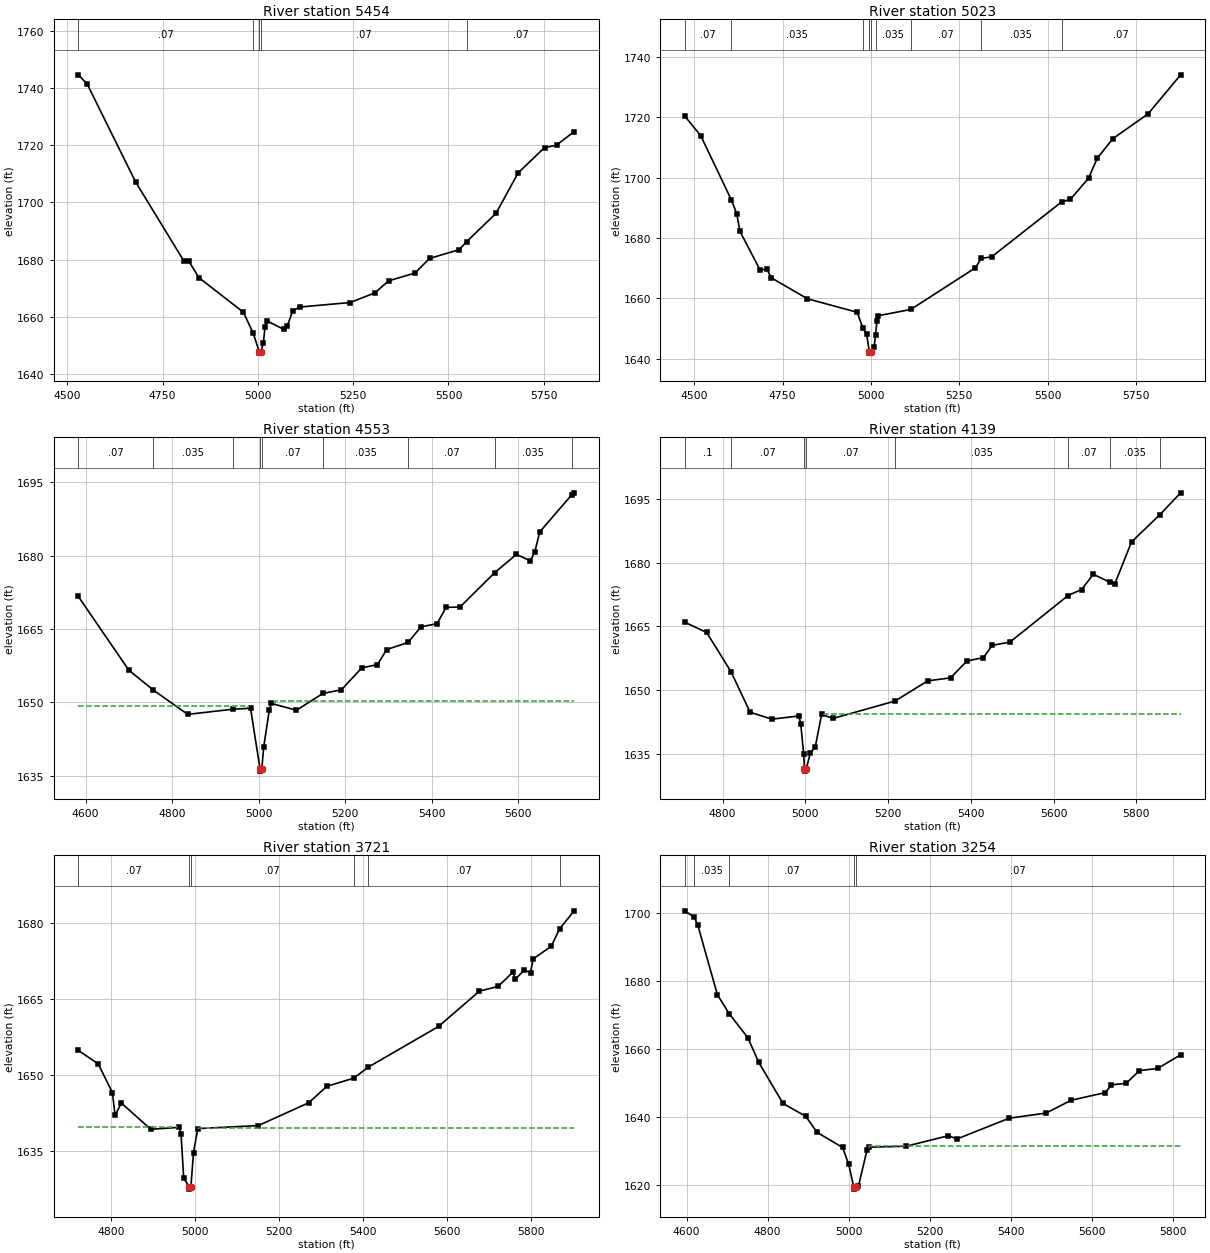
Type RM Length L Ch R = 1 ,5454    ,431,431,431
BEGIN DESCRIPTION:
Stream0669 12.0
END DESCRIPTION:
XS GIS Cut Line= 4
      1950974.96     13869624.98        1951375.       13869875.
        1951575.       13869975.      1952116.89     13870245.94
#Sta/Elev= 30
  4528.7 1744.58  4551.5 1741.46  4678.9 1707.19    4805 1679.68    4818 1679.59
  4845.2 1673.73  4961.9 1661.63  4987.8 1654.27  5003.4 1647.86  5003.6 1647.36
  5007.5 1647.86  5014.2 1650.75  5018.8 1656.66  5023.3 1658.66    5068 1655.64
    5077 1656.74  5091.4  1662.2  5110.5 1663.47  5242.3 1665.04  5307.3 1668.43
  5342.9 1672.61  5412.4 1675.35  5450.4 1680.44  5528.6 1683.52    5548 1686.35
  5624.7 1696.17  5682.9 1710.34  5752.2 1719.16  5783.6 1720.01  5829.9 1724.76
#Mann= 5 ,-1 , 0
  4528.7     .07       0  4987.8     .07       0  5003.4     .05       0
  5007.5     .07       0    5548     .07       0
Bank Sta=5003.4,5007.5
XS Rating Curve= 0 ,0
Exp/Cntr=0.3,0.1

Type RM Length L Ch R = 1 ,5023    ,470,470,470
BEGIN DESCRIPTION:
Stream0669 11.0
END DESCRIPTION:
XS GIS Cut Line= 3
      1950924.99     13869874.99        1951275.       13870275.
      1952131.91     13870437.49
#Sta/Elev= 30
  4472.9 1720.37    4518  1713.9  4604.7 1692.61  4620.1 1687.97  4628.8 1682.21
    4686 1669.37  4705.1 1669.65  4717.9 1666.76  4819.9 1659.82  4960.9 1655.33
    4977 1650.09  4987.6 1648.07  4995.3 1642.29  4995.5 1641.79  4999.4 1642.29
  5008.8 1643.87  5013.1 1647.94  5016.9  1652.5    5021 1654.19  5112.8 1656.28
  5295.8  1670.1  5312.2  1673.2  5341.6 1673.72  5539.4  1691.9  5564.5 1692.78
  5615.9 1699.79  5640.9 1706.48  5685.2 1712.95  5784.4 1721.12  5876.6 1734.07
#Mann= 9 ,-1 , 0
  4472.9     .07       0  4604.7    .035       0    4977     .07       0
  4995.3     .05       0  4999.4     .07       0  5013.1    .035       0
  5112.8     .07       0  5312.2    .035       0  5539.4     .07       0
Bank Sta=4995.3,4999.4
XS Rating Curve= 0 ,0
Exp/Cntr=0.3,0.1

Type RM Length L Ch R = 1 ,4553    ,414,414,414
BEGIN DESCRIPTION:
Stream0669 10.0
END DESCRIPTION:
XS GIS Cut Line= 4
        1950575.       13870525.        1950975.       13870625.
        1951125.       13870725.      1951585.96     13871032.31
#Sta/Elev= 30
    4583 1671.64  4699.8 1656.55  4756.1 1652.51  4835.9 1647.51  4940.3 1648.57
  4981.2 1648.77  5003.1  1636.4  5003.4  1635.9  5007.3  1636.4  5011.6  1640.8
  5024.6 1648.36  5029.4 1649.75  5087.4 1648.36  5148.8 1651.81  5191.2 1652.53
  5238.5 1657.03  5274.5 1657.69  5296.2 1660.78  5345.4 1662.23  5375.5 1665.44
  5412.4 1666.06  5433.5 1669.41  5465.6 1669.48  5545.9 1676.52  5596.2 1680.26
  5628.2 1678.93  5638.7 1680.78  5649.8 1684.83  5723.9 1692.44  5729.6 1692.85
#Mann= 9 ,-1 , 0
    4583     .07       0  4756.1    .035       0  4940.3     .07       0
  5003.1     .05       0  5007.3     .07       0  5148.8    .035       0
  5345.4     .07       0  5545.9    .035       0  5723.9     .07       0
#XS Ineff= 2 , 0
         4974.83 1649.24 5036.69         1650.31
Permanent Ineff=
       F       F
Bank Sta=5003.1,5007.3
XS Rating Curve= 0 ,0
Exp/Cntr=0.3,0.1

Type RM Length L Ch R = 1 ,4139    ,418,418,418
BEGIN DESCRIPTION:
Stream0669 9.0
END DESCRIPTION:
XS GIS Cut Line= 3
      1950475.01     13870775.01        1950725.       13870925.
      1951615.52     13871093.76
#Sta/Elev= 30
  4708.9    1666  4761.7 1663.58  4820.4 1654.36  4866.7 1644.81  4919.3 1643.17
  4984.9 1643.93  4989.1 1641.98  4996.1 1634.94    4998 1631.44  4998.3 1630.94
  5002.3 1631.44    5012 1635.17  5024.2 1636.68  5039.4 1644.28  5066.9 1643.34
  5216.9 1647.44  5295.9  1652.2  5350.9  1652.9  5390.6 1656.88  5430.3 1657.65
  5451.6 1660.55  5494.4 1661.32  5634.9 1672.28  5667.5  1673.7  5695.9 1677.28
  5735.9 1675.41  5747.8 1675.04  5788.2  1684.9  5855.8 1691.23  5906.8 1696.46
#Mann= 8 ,-1 , 0
  4708.9      .1       0  4820.4     .07       0    4998     .05       0
  5002.3     .07       0  5216.9    .035       0  5634.9     .07       0
  5735.9    .035       0  5855.8     .07       0
#XS Ineff= 2 , 0
         4984.37  1643.8 5045.89         1644.43
Permanent Ineff=
       F       F
Bank Sta=4998,5002.3
XS Rating Curve= 0 ,0
Exp/Cntr=0.3,0.1

Type RM Length L Ch R = 1 ,3721    ,467,467,467
BEGIN DESCRIPTION:
Stream0669 8.0
END DESCRIPTION:
XS GIS Cut Line= 4
      1950324.98     13871074.98        1950525.       13871275.
        1950775.       13871275.      1951422.13       13871275.
#Sta/Elev= 30
  4721.9 1654.81  4769.1 1652.17    4803 1646.47  4809.4 1641.95  4824.2 1644.41
  4894.2 1639.21  4962.1 1639.59  4966.3 1638.21  4972.7 1629.53  4985.4 1627.86
  4985.7 1627.36  4989.8 1627.86    4996 1634.56  5006.1 1639.35  5150.1 1639.94
  5270.1 1644.45  5313.4 1647.72  5377.1 1649.32  5412.1 1651.52  5579.1 1659.56
  5676.4 1666.56  5721.4 1667.51  5756.1 1670.32  5762.1 1668.94  5783.1 1670.72
  5798.1 1670.21  5804.1 1672.92  5847.4 1675.44  5867.1 1678.89  5901.9 1682.46
#Mann= 6 ,-1 , 0
  4721.9     .07       0  4985.4     .05       0  4989.8     .07       0
  5377.1    .035       0  5412.1     .07       0  5867.1    .035       0
#XS Ineff= 2 , 0
         4958.64 1639.58 5007.09         1639.55
Permanent Ineff=
       F       F
Bank Sta=4985.4,4989.8
XS Rating Curve= 0 ,0
Exp/Cntr=0.3,0.1

Type RM Length L Ch R = 1 ,3254    ,203,203,203
BEGIN DESCRIPTION:
Stream0669 7.0
END DESCRIPTION:
XS GIS Cut Line= 3
        1949825.       13871625.        1950225.       13871625.
      1951047.92     13871607.65
#Sta/Elev= 30
  4595.7 1700.58    4619 1698.72    4628 1696.28    4676    1676    4705 1670.43
    4751 1663.39    4778 1656.14    4838 1644.05  4894.3 1640.25    4922 1635.57
    4985 1631.13    5000  1626.2  5012.7 1619.41  5013.1 1618.91  5017.3 1619.41
    5024 1619.73    5045  1630.3    5051 1631.24  5141.1 1631.48  5246.1 1634.59
  5267.1 1633.63  5396.1 1639.73  5486.8 1641.23  5549.1    1645  5633.2 1647.24
  5648.2 1649.55  5684.2 1649.92  5717.2 1653.69  5762.2 1654.32  5818.8 1658.34
#Mann= 5 ,-1 , 0
  4595.7     .07       0    4619    .035       0    4705     .07       0
  5012.7     .05       0  5017.3     .07       0
#XS Ineff= 2 , 0
                         5050.13         1631.59
Permanent Ineff=
       F       F
Bank Sta=5012.7,5017.3
XS Rating Curve= 0 ,0
Exp/Cntr=0.3,0.1

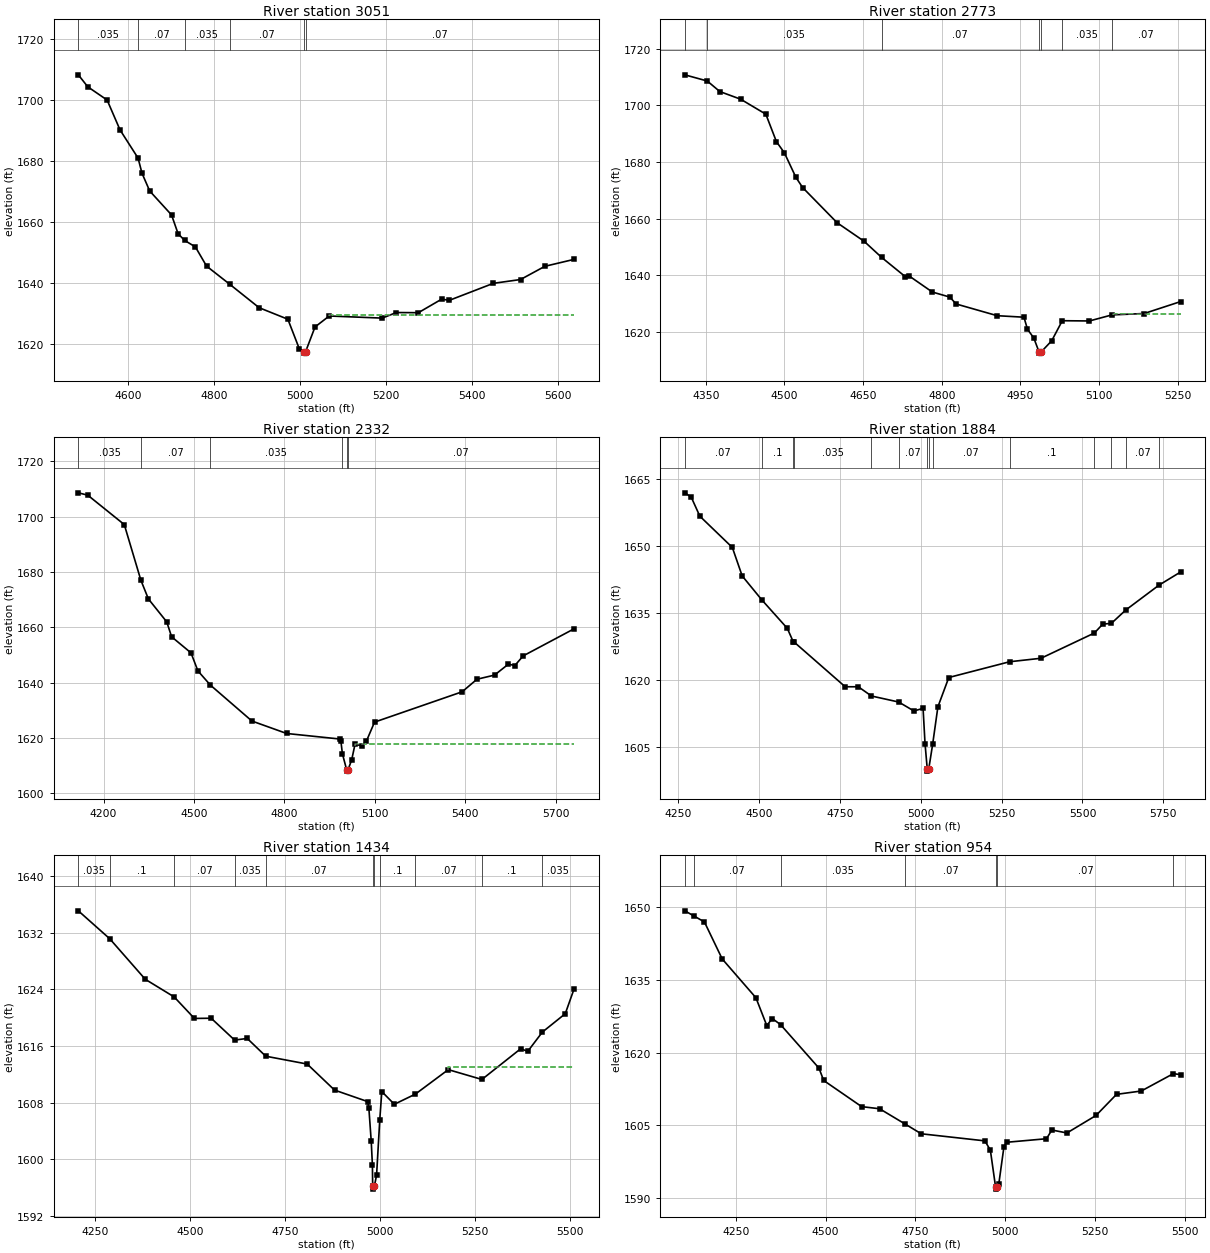
Type RM Length L Ch R = 1 ,3051    ,278,278,278
BEGIN DESCRIPTION:
Mapping XS edc26e75
END DESCRIPTION:
XS GIS Cut Line= 3
      1949715.46     13871840.47       1950370.8     13871822.82
      1950866.79       13871794.
#Sta/Elev= 30
  4484.9 1708.14  4506.8 1704.23  4551.8  1699.9  4581.8 1690.14  4623.8  1680.9
  4632.8 1675.99  4650.8 1670.16  4701.5 1662.34  4716.8 1656.18    4732    1654
    4757 1651.87  4782.9 1645.61  4836.4 1639.71  4905.1    1632  4971.9 1628.23
  4998.9 1618.42  5008.6 1617.65    5009 1617.15  5013.2 1617.65    5035  1625.7
    5068 1629.29  5191.1  1628.6  5224.1 1630.42  5275.2 1630.37  5329.3 1634.79
  5347.3 1634.42  5449.5 1639.97  5512.6 1641.21  5569.3 1645.54  5637.3 1647.81
#Mann= 6 ,-1 , 0
  4484.9    .035       0  4623.8     .07       0    4732    .035       0
  4836.4     .07       0  5008.6     .05       0  5013.2     .07       0
#XS Ineff= 2 , 0
                         5067.65         1629.62
Permanent Ineff=
       F       F
Bank Sta=5008.6,5013.2
XS Rating Curve= 0 ,0
Exp/Cntr=0.3,0.1

Type RM Length L Ch R = 1 ,2773    ,441,441,441
BEGIN DESCRIPTION:
Stream0669 6.0
END DESCRIPTION:
XS GIS Cut Line= 4
      1949635.05     13871988.76        1949925.       13872025.
        1950325.       13872075.      1950524.98     13871925.01
#Sta/Elev= 30
  4310.1 1710.76  4352.9 1708.58  4376.9 1704.85  4416.6 1702.15  4464.6 1696.86
  4484.8 1687.15  4499.9 1683.23    4522 1674.52  4534.8 1670.94  4600.6  1658.5
    4652 1651.96  4685.2 1646.29  4730.6 1639.45  4736.7 1639.86    4782 1634.04
  4815.3 1632.26  4827.4 1629.82  4905.7 1625.68  4956.7 1625.15  4963.4  1620.9
  4975.5 1617.79  4985.3 1612.96  4985.6 1612.46  4989.9 1612.96  5009.6 1616.82
  5029.8 1623.91  5081.5 1623.82  5124.4 1625.96  5185.8 1626.45  5255.4 1630.67
#Mann= 7 ,-1 , 0
  4310.1     .07       0  4352.9    .035       0  4685.2     .07       0
  4985.3     .05       0  4989.9     .07       0  5029.8    .035       0
  5124.4     .07       0
#XS Ineff= 2 , 0
                          5126.5         1626.36
Permanent Ineff=
       F       F
Bank Sta=4985.3,4989.9
XS Rating Curve= 0 ,0
Exp/Cntr=0.3,0.1

Type RM Length L Ch R = 1 ,2332    ,448,448,448
BEGIN DESCRIPTION:
Stream0669 5.0
END DESCRIPTION:
XS GIS Cut Line= 5
      1949634.37     13872029.69        1950025.       13872225.
        1950425.       13872425.      1950544.94     13872465.69
      1951165.79     13872332.86
#Sta/Elev= 30
  4116.4 1708.64  4147.6  1707.8  4268.9 1697.17  4323.9 1677.08  4348.9  1670.3
  4409.8 1662.01    4426 1656.62  4490.3 1650.81  4513.2  1644.3  4554.6 1639.17
  4692.5 1626.18  4807.8 1621.68  4984.4 1619.68  4987.7 1618.97  4992.8 1614.34
  5006.8 1608.58  5007.1 1608.08  5011.5 1608.58  5023.7 1612.21  5034.5 1617.71
  5056.7 1617.29  5072.5 1618.93  5099.4 1625.79  5390.2 1636.75  5439.3 1641.28
  5497.6 1642.78  5543.6 1646.73  5565.1 1646.24  5592.7 1649.72  5761.9 1659.52
#Mann= 6 ,-1 , 0
  4116.4    .035       0  4323.9     .07       0  4554.6    .035       0
  4992.8     .07       0  5006.8     .05       0  5011.5     .07       0
#XS Ineff= 2 , 0
                         5033.56         1617.93
Permanent Ineff=
       F       F
Bank Sta=5006.8,5011.5
XS Rating Curve= 0 ,0
Exp/Cntr=0.3,0.1

Type RM Length L Ch R = 1 ,1884    ,450,450,450
BEGIN DESCRIPTION:
Stream0669 4.0
END DESCRIPTION:
XS GIS Cut Line= 5
      1949626.72     13872500.86        1950175.       13872775.
        1950275.       13872825.      1950388.22      13872847.8
      1951073.65     13872751.95
#Sta/Elev= 30
    4271 1661.95  4290.7 1661.01  4317.5 1656.72  4417.9 1649.72  4448.3 1643.35
  4508.7 1638.01  4587.8 1631.61  4606.1 1628.61  4609.6 1628.49  4766.7 1618.53
  4807.2 1618.53  4847.9 1616.46  4932.1 1615.11  4979.1 1613.11  5007.4 1613.69
  5013.5 1605.76  5020.3 1600.14  5020.6 1599.64    5025 1600.14  5037.1  1605.7
  5053.2 1614.03  5086.9  1620.6  5274.8 1624.13  5371.9 1624.91  5536.8 1630.56
  5562.8 1632.56  5589.3 1632.72  5633.7  1635.7  5736.7 1641.29  5803.4 1644.23
#Mann= 14 ,-1 , 0
    4271     .07       0  4508.7      .1       0  4606.1     .07       0
  4609.6    .035       0  4847.9     .07       0  4932.1     .07       0
  5020.3     .05       0    5025     .07       0  5037.1     .07       0
  5274.8      .1       0  5536.8     .07       0  5589.3    .035       0
  5633.7     .07       0  5736.7    .035       0
Bank Sta=5020.3,5025
XS Rating Curve= 0 ,0
Exp/Cntr=0.3,0.1

Type RM Length L Ch R = 1 ,1434    ,480,480,480
BEGIN DESCRIPTION:
Stream0669 3.0
END DESCRIPTION:
XS GIS Cut Line= 4
      1949621.24     13872839.15      1950144.28     13873238.18
        1950275.       13873275.      1950786.73     13873284.52
#Sta/Elev= 30
  4206.3 1635.12    4289 1631.17  4382.5 1625.44  4458.7 1622.94  4511.9  1619.9
  4556.1 1619.93  4617.7 1616.84    4651 1617.07  4699.7 1614.56  4808.9 1613.45
  4880.8 1609.77  4968.1 1608.14  4971.2 1607.28  4977.5 1602.52  4980.6 1599.17
  4981.3 1596.26  4981.6 1595.76  4986.1 1596.26  4991.6 1597.75    5000 1605.59
  5005.3 1609.56  5038.3 1607.76  5093.8  1609.2  5180.4 1612.66  5268.9 1611.27
  5371.4 1615.63  5389.4 1615.23  5428.1 1617.97  5488.4 1620.57  5511.8 1624.11
#Mann= 11 ,-1 , 0
  4206.3    .035       0    4289      .1       0  4458.7     .07       0
  4617.7    .035       0  4699.7     .07       0  4981.3     .05       0
  4986.1     .07       0    5000      .1       0  5093.8     .07       0
  5268.9      .1       0  5428.1    .035       0
#XS Ineff= 2 , 0
                         5179.37         1612.97
Permanent Ineff=
       F       F
Bank Sta=4981.3,4986.1
XS Rating Curve= 0 ,0
Exp/Cntr=0.3,0.1

Type RM Length L Ch R = 1 ,954     ,475,475,475
BEGIN DESCRIPTION:
Stream0669 2.0
END DESCRIPTION:
XS GIS Cut Line= 3
      1949462.81     13873181.08        1950175.       13873725.
      1950659.85     13873710.38
#Sta/Elev= 30
  4107.9 1649.22  4133.4 1648.16  4162.6 1646.92  4212.1  1639.3    4306  1631.3
  4336.3 1625.56  4351.4 1627.02  4374.5 1625.77  4481.6 1616.79  4494.8 1614.24
  4600.5 1608.85  4650.6 1608.41  4721.9 1605.25  4766.6 1603.25  4943.9 1601.79
  4959.1 1599.87  4973.5 1592.34  4973.9 1591.84  4978.4 1592.34  4982.4 1592.81
  4996.9 1600.57  5004.4  1601.5  5115.4 1602.23  5130.4 1604.03  5172.4 1603.42
  5253.5 1607.03  5310.5 1611.38  5379.5 1612.07  5468.9 1615.65  5489.1 1615.44
#Mann= 7 ,-1 , 0
  4107.9    .035       0  4133.4     .07       0  4374.5    .035       0
  4721.9     .07       0  4973.5     .05       0  4978.4     .07       0
  5468.9    .035       0
Bank Sta=4973.5,4978.4
XS Rating Curve= 0 ,0
Exp/Cntr=0.3,0.1

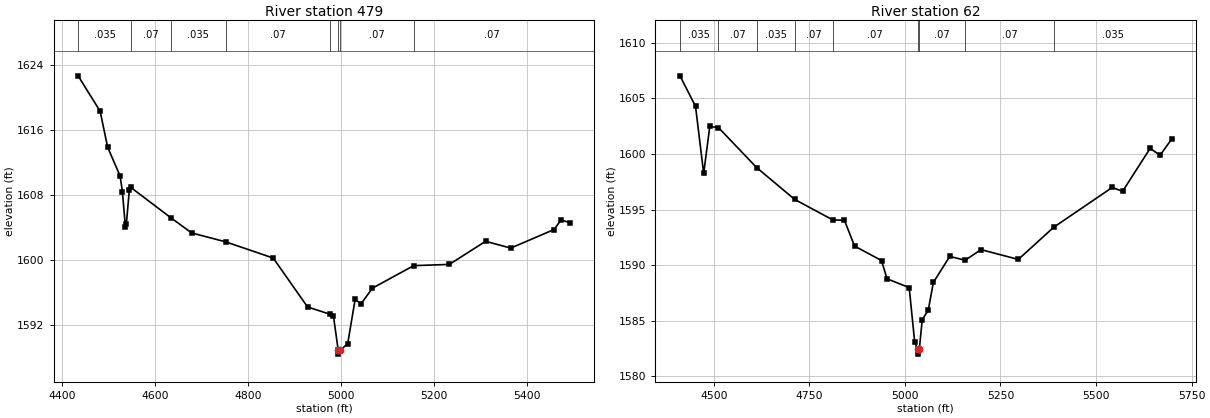
Type RM Length L Ch R = 1 ,479     ,417,417,417
BEGIN DESCRIPTION:
Stream0669 1.0
END DESCRIPTION:
XS GIS Cut Line= 3
      1949424.98     13873574.98      1949840.96     13874039.75
      1950274.99       13874075.
#Sta/Elev= 30
  4433.7 1622.67  4481.1 1618.32  4497.2 1613.91  4524.2 1610.34  4529.1 1608.43
  4535.5 1604.13  4537.7 1604.51    4544 1608.62  4547.4 1608.94  4633.9  1605.2
  4678.4 1603.35  4751.4 1602.26  4854.1 1600.26    4928 1594.25  4975.5 1593.37
  4983.7 1593.18    4994 1588.95  4994.4 1588.45  4998.9 1588.95  5014.5 1589.74
  5030.5 1595.17  5043.2 1594.63  5067.8 1596.56  5156.6 1599.33  5233.4 1599.48
  5311.6 1602.32  5365.8 1601.49  5459.1 1603.77  5474.2 1604.95  5492.9 1604.62
#Mann= 8 ,-1 , 0
  4433.7    .035       0  4547.4     .07       0  4633.9    .035       0
  4751.4     .07       0  4975.5     .07       0    4994     .05       0
  4998.9     .07       0  5156.6     .07       0
Bank Sta=4994,4998.9
XS Rating Curve= 0 ,0
Exp/Cntr=0.3,0.1

Type RM Length L Ch R = 1 ,62      ,0,0,0
BEGIN DESCRIPTION:
Stream0669 0.0
END DESCRIPTION:
XS GIS Cut Line= 5
      1949397.78     13873718.13      1949464.55     13874212.08
      1949559.32     13874331.73      1949957.73     13874457.96
      1950174.43     13874464.21
#Sta/Elev= 30
  4411.7 1607.02  4452.4 1604.28  4473.7 1598.25  4489.7 1602.47  4512.4 1602.37
  4612.1 1598.78  4711.8 1595.91  4811.5 1594.07  4841.8 1594.04  4868.4 1591.72
  4938.8 1590.42  4953.3 1588.78  5011.2 1587.99  5025.7 1583.06    5033 1582.51
  5033.3 1582.01  5037.9 1582.51  5045.4 1585.12    5061 1585.94  5074.4 1588.45
  5117.3 1590.79  5157.6 1590.45  5199.1  1591.4  5296.7 1590.52  5389.2 1593.41
  5542.3 1596.99  5569.3 1596.64  5641.4  1600.5  5667.4 1599.88  5697.5 1601.33
#Mann= 9 ,-1 , 0
  4411.7    .035       0  4512.4     .07       0  4612.1    .035       0
  4711.8     .07       0  4811.5     .07       0    5033     .05       0
  5037.9     .07       0  5157.6     .07       0  5389.2    .035       0
Bank Sta=5033,5037.9
XS Rating Curve= 0 ,0
Exp/Cntr=0.3,0.1

Chan Stop Cuts=-1
Use User Specified Reach Order=0
Composite Channel Slope=5