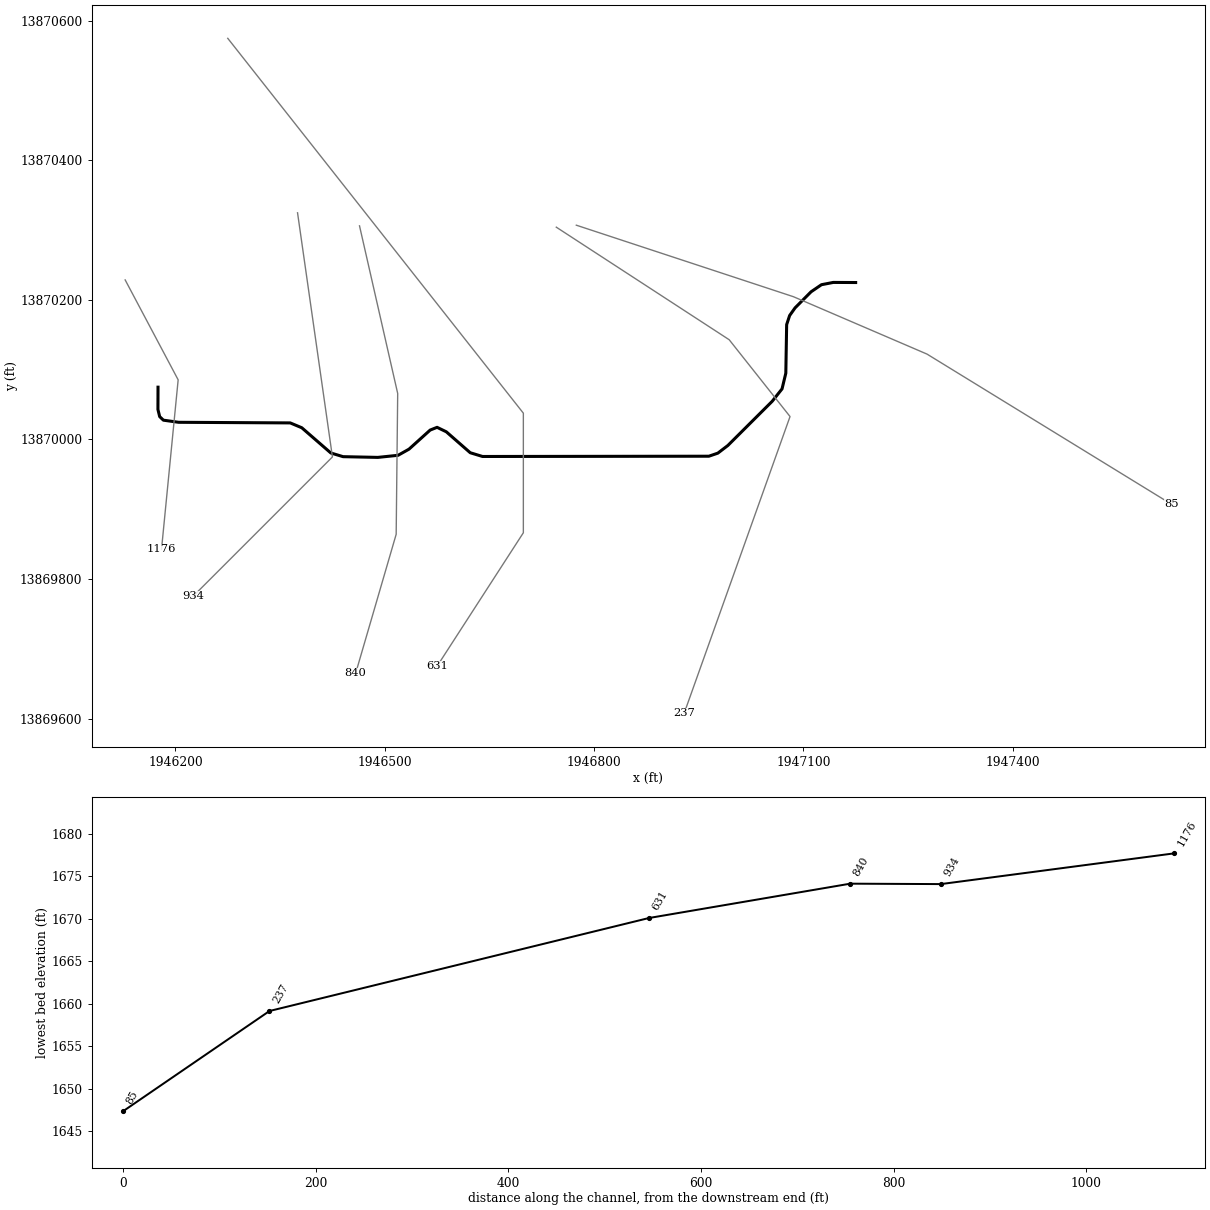
--- Stream0673.prj (project) ---

Proj Title=Stream0673 Base Level Engineering
Current Plan=p01
Default Exp/Contr=0.3,0.1
English Units
Geom File=g01
Flow File=f01
Plan File=p01
BEGIN DESCRIPTION:
Stream0673
END DESCRIPTION:

--- Stream0673.p01 (plan) ---

Plan Title=Multiple Run
Short Identifier=Multiple
Geom File=g01
Flow File=f01
Subcritical Flow
K Sum by GR= 0
Std Step Tol= 0.01
Critical Tol= 0.01
Num of Std Step Trials= 20
Max Error Tol= 0.3
Flow Tol Ratio= 0.001
Split Flow NTrial= 30
Split Flow Tol= 0.02
Split Flow Ratio= 0.02
Log Output Level= 0
Friction Slope Method= 1
Unsteady Friction Slope Method= 2
Unsteady Bridges Friction Slope Method= 1
Parabolic Critical Depth
Global Vel Dist=  1 , 1 , 1
Global Log Level= 0
CheckData=True
Encroach Param= -1, 0, 0, 0
BEGIN DESCRIPTION:
Multiple Run
END DESCRIPTION:

--- Stream0673.f01 (steady flow) ---

Flow Title=Multiple
Number of Profiles=7
Profile Names=10-year,25-year,50-year,1pct_min,100-year,1pct_plu,500-year
River Rch & RM= Stream0673,Reach-1,1176
     533     863    1165     765    1526    3045    2571
Boundary for River Rch & Prof#=Stream0673,Reach-1,1
Up Type=0
Dn Type=3
Dn Slope=0.005
Boundary for River Rch & Prof#=Stream0673,Reach-1,2
Up Type=0
Dn Type=3
Dn Slope=0.005
Boundary for River Rch & Prof#=Stream0673,Reach-1,3
Up Type=0
Dn Type=3
Dn Slope=0.005
Boundary for River Rch & Prof#=Stream0673,Reach-1,4
Up Type=0
Dn Type=3
Dn Slope=0.005
Boundary for River Rch & Prof#=Stream0673,Reach-1,5
Up Type=0
Dn Type=3
Dn Slope=0.005
Boundary for River Rch & Prof#=Stream0673,Reach-1,6
Up Type=0
Dn Type=3
Dn Slope=0.005
Boundary for River Rch & Prof#=Stream0673,Reach-1,7
Up Type=0
Dn Type=3
Dn Slope=0.005

--- Stream0673.g01 (geometry) ---

Geom Title=Existing Conditions

River Reach=Stream0673,Reach-1
Reach XY= 30
      1946175.00     13870075.00      1946174.89     13870043.05
      1946177.37     13870032.82      1946182.70     13870027.70
      1946204.64     13870024.65      1946364.50     13870023.78
      1946381.06     13870016.85      1946422.69     13869980.69
      1946440.28     13869975.39      1946490.09     13869974.35
      1946519.11     13869977.36      1946534.78     13869986.17
      1946565.09     13870013.52      1946575.00     13870017.44
      1946588.21     13870011.05      1946622.55     13869981.02
      1946640.16     13869975.66      1946964.57     13869976.04
      1946977.47     13869980.45      1946991.80     13869991.41
      1947055.39     13870054.80      1947069.48     13870072.56
      1947074.88     13870095.05      1947076.08     13870164.65
      1947080.34     13870177.66      1947088.12     13870188.65
      1947111.13     13870211.77      1947125.99     13870221.88
      1947142.93     13870225.15      1947175.00     13870225.00

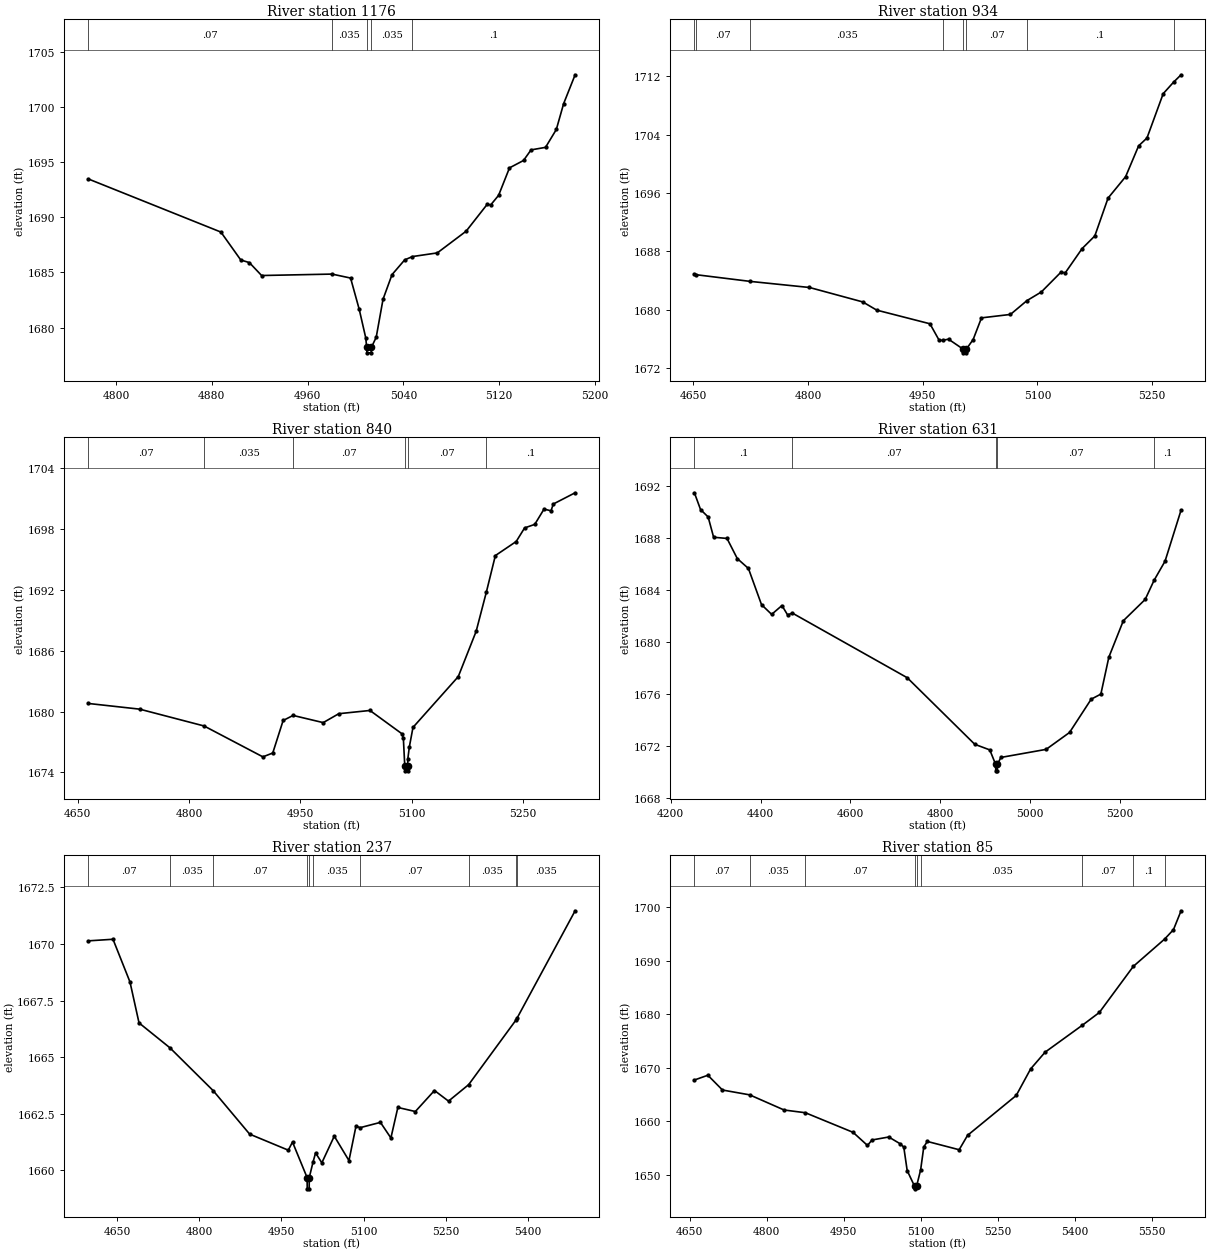
Type RM Length L Ch R = 1,1176,242,242,242
BEGIN DESCRIPTION:
Stream0673 3.0
END DESCRIPTION:
XS GIS Cut Line= 3
      1946127.92     13870228.74      1946203.88     13870085.51
      1946180.00     13869842.41
#Sta/Elev= 30
  4777.0 1693.47  4887.6 1688.66  4904.2 1686.13  4911.4 1685.89  4921.6 1684.72
  4980.4 1684.85  4995.9 1684.49  5003.1 1681.66  5008.6 1679.05  5009.3 1678.21
  5009.6 1677.71  5013.1 1677.71  5013.3 1678.21  5017.3 1679.12  5023.0 1682.57
  5030.5 1684.80  5041.1 1686.14  5047.6 1686.44  5068.3 1686.77  5092.4 1688.74
  5110.1 1691.19  5112.9 1691.12  5119.5 1691.99  5128.6 1694.48  5140.3 1695.15
  5146.6 1696.11  5158.7 1696.34  5167.7 1697.96  5173.8 1700.30  5183.4 1702.92
#Mann=5,-1,0
  4777.0    0.07       0  4980.4   0.035       0  5009.3   0.035       0
  5013.3   0.035       0  5047.6     0.1       0
Bank Sta=5009.3,5013.3
Exp/Cntr=0.3,0.1

Type RM Length L Ch R = 1,934,94,94,94
BEGIN DESCRIPTION:
Stream0673 2.0
END DESCRIPTION:
XS GIS Cut Line= 3
      1946375.00     13870324.97      1946425.00     13869975.00
      1946224.97     13869774.97
#Sta/Elev= 30
  4651.4 1684.83  4653.7 1684.80  4724.7 1683.88  4801.9 1683.05  4871.6 1681.07
  4889.8 1679.95  4959.4 1678.08  4971.6 1675.79  4977.1 1675.84  4983.7 1675.97
  5002.9 1674.60  5003.2 1674.10  5006.7 1674.10  5006.9 1674.60  5015.9 1675.92
  5026.8 1678.89  5064.7 1679.36  5086.2 1681.25  5105.0 1682.43  5130.4 1685.11
  5136.5 1685.08  5158.4 1688.38  5175.0 1690.11  5192.3 1695.29  5215.3 1698.23
  5232.3 1702.45  5243.2 1703.52  5264.4 1709.59  5277.9 1711.16  5287.8 1712.18
#Mann=8,-1,0
  4651.4     0.1       0  4653.7    0.07       0  4724.7   0.035       0
  4977.1    0.07       0  5002.9    0.05       0  5006.9    0.07       0
  5086.2     0.1       0  5277.9    0.07       0
Bank Sta=5002.9,5006.9
Exp/Cntr=0.3,0.1

Type RM Length L Ch R = 1,840,209,209,209
BEGIN DESCRIPTION:
Mapping XS 11775472
END DESCRIPTION:
XS GIS Cut Line= 4
      1946463.82     13870306.24      1946518.55     13870065.98
      1946516.38     13869864.15      1946458.27     13869664.81
#Sta/Elev= 30
  4664.6 1680.80  4733.6 1680.24  4820.4 1678.58  4899.7 1675.53  4913.0 1675.91
  4927.0 1679.12  4940.4 1679.62  4981.0 1678.91  5002.0 1679.79  5044.0 1680.11
  5086.9 1677.82  5089.0 1677.39  5090.9 1674.65  5091.2 1674.15  5094.7 1674.15
  5094.9 1674.65  5095.0 1675.31  5097.1 1676.52  5102.0 1678.44  5163.0 1683.45
  5187.1 1687.92  5201.0 1691.83  5213.0 1695.40  5241.1 1696.79  5252.4 1698.13
  5266.1 1698.48  5278.6 1699.99  5288.0 1699.82  5291.1 1700.49  5320.5 1701.60
#Mann=6,-1,0
  4664.6    0.07       0  4820.4   0.035       0  4940.4    0.07       0
  5090.9    0.05       0  5094.9    0.07       0  5201.0     0.1       0
Bank Sta=5090.9,5094.9
Exp/Cntr=0.3,0.1

Type RM Length L Ch R = 1,631,394,394,394
BEGIN DESCRIPTION:
Stream0673 1.0
END DESCRIPTION:
XS GIS Cut Line= 4
      1946274.99     13870575.02      1946698.67     13870037.76
      1946698.67     13869866.32      1946574.98     13869674.97
#Sta/Elev= 30
  4252.8 1691.49  4266.5 1690.20  4283.4 1689.63  4295.6 1688.07  4325.4 1687.98
  4348.3 1686.43  4373.1 1685.67  4402.2 1682.89  4424.8 1682.14  4447.7 1682.82
  4460.3 1682.10  4470.9 1682.24  4726.6 1677.27  4877.0 1672.15  4910.4 1671.72
  4923.4 1670.61  4923.7 1670.11  4927.2 1670.11  4927.4 1670.61  4935.1 1671.14
  5035.8 1671.76  5088.0 1673.06  5136.2 1675.62  5157.7 1676.01  5175.5 1678.85
  5207.7 1681.65  5256.4 1683.29  5276.2 1684.76  5300.6 1686.23  5336.3 1690.16
#Mann=5,-1,0
  4252.8     0.1       0  4470.9    0.07       0  4923.4    0.05       0
  4927.4    0.07       0  5276.2     0.1       0
Bank Sta=4923.4,4927.4
Exp/Cntr=0.3,0.1

Type RM Length L Ch R = 1,237,152,152,152
BEGIN DESCRIPTION:
Stream0673 0.0
END DESCRIPTION:
XS GIS Cut Line= 4
      1946745.90     13870304.33      1946993.72     13870143.00
      1947080.93     13870032.90      1946929.12     13869607.43
#Sta/Elev= 30
  4597.9 1670.14  4642.7 1670.21  4673.7 1668.32  4690.2 1666.51  4746.5 1665.41
  4825.6 1663.51  4892.0 1661.59  4962.5 1660.88  4970.2 1661.24  4996.8 1659.67
  4997.1 1659.17  5000.6 1659.17  5000.8 1659.67  5007.7 1660.36  5012.3 1660.76
  5023.7 1660.32  5046.4 1661.50  5073.2 1660.42  5085.9 1661.93  5094.2 1661.88
  5130.6 1662.11  5149.7 1661.42  5162.4 1662.77  5194.3 1662.59  5229.2 1663.52
  5254.8 1663.05  5291.6 1663.78  5377.7 1666.63  5380.3 1666.74  5485.8 1671.47
#Mann=10,-1,0
  4597.9    0.07       0  4746.5   0.035       0  4825.6    0.07       0
  4996.8    0.05       0  5000.8    0.07       0  5007.7   0.035       0
  5094.2    0.07       0  5291.6   0.035       0  5377.7    0.07       0
  5380.3   0.035       0
Bank Sta=4996.8,5000.8
Exp/Cntr=0.3,0.1

Type RM Length L Ch R = 1,85,0,0,0
BEGIN DESCRIPTION:
Stream0673 0.1
END DESCRIPTION:
XS GIS Cut Line= 4
      1946774.59     13870307.18      1947085.80     13870204.68
      1947277.32     13870122.39      1947628.13     13869906.94
#Sta/Elev= 30
  4659.0 1667.70  4685.2 1668.59  4713.7 1665.83  4766.6 1664.93  4833.7 1662.10
  4875.1 1661.59  4968.0 1657.93  4996.1 1655.48  5004.8 1656.50  5037.5 1657.06
  5060.3 1655.76  5066.8 1655.15  5073.4 1650.79  5087.7 1647.88  5088.0 1647.38
  5091.7 1647.88  5099.6 1650.93  5105.7 1655.20  5112.6 1656.23  5174.6 1654.68
  5191.0 1657.37  5285.7 1664.81  5313.8 1669.77  5342.0 1672.90  5414.8 1677.95
  5447.6 1680.31  5513.8 1688.92  5574.8 1694.02  5592.0 1695.78  5606.8 1699.30
#Mann=9,-1,0
  4659.0    0.07       0  4766.6   0.035       0  4875.1    0.07       0
  5087.7    0.05       0  5091.7    0.07       0  5099.6   0.035       0
  5414.8    0.07       0  5513.8     0.1       0  5574.8    0.07       0
Bank Sta=5087.7,5091.7
Exp/Cntr=0.3,0.1

Chan Stop Cuts=-1