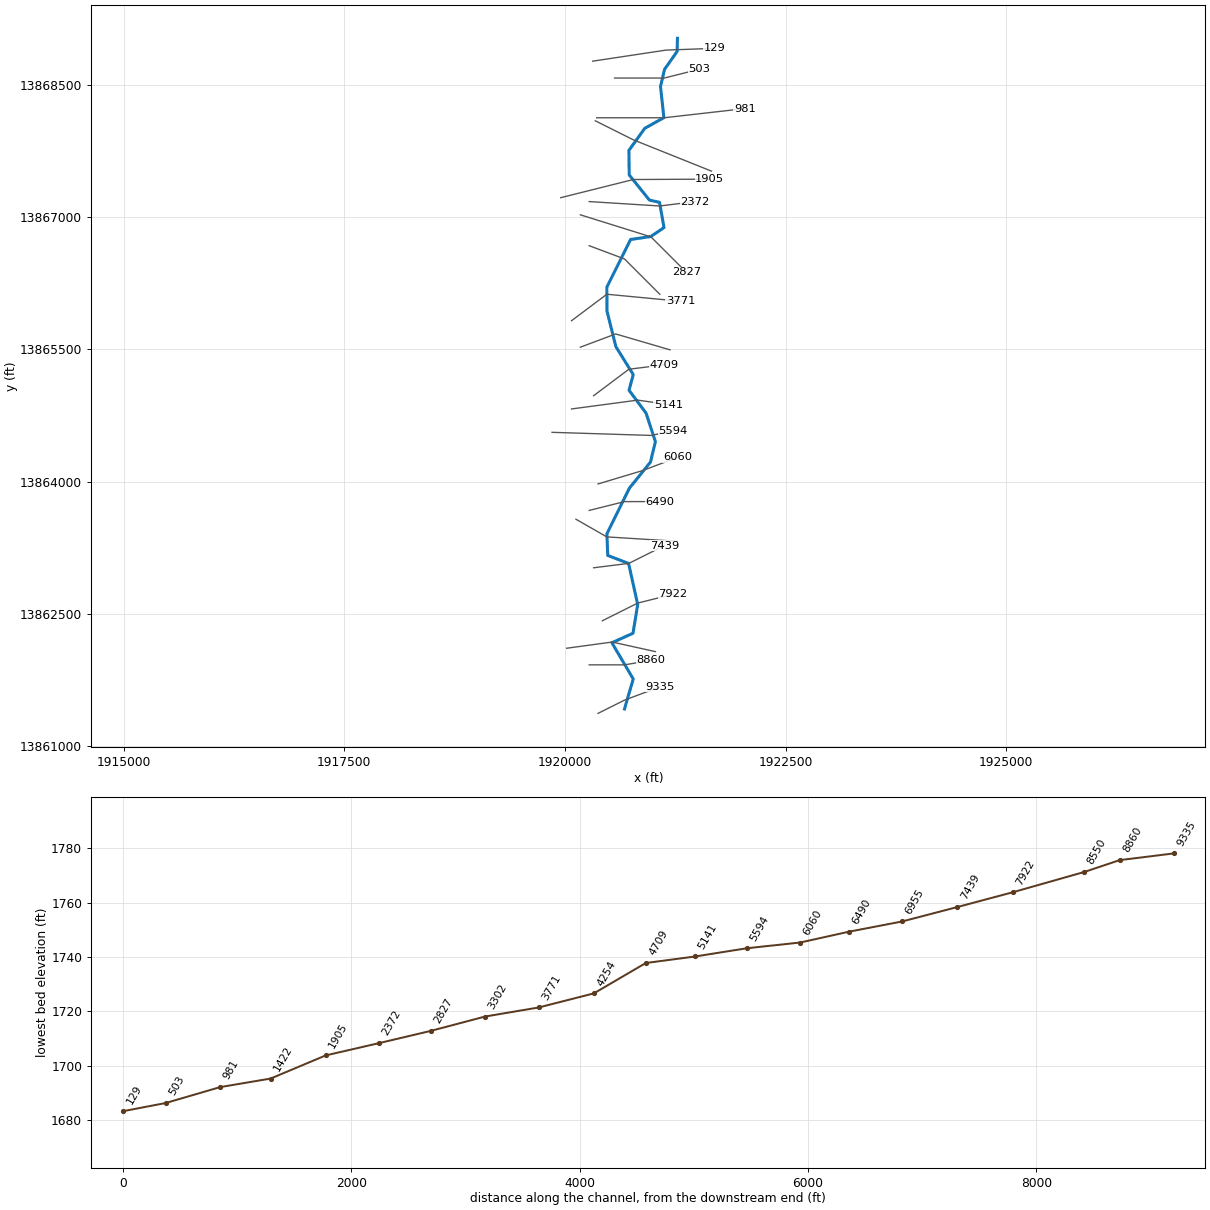
--- Stream0674.prj (project) ---

Proj Title=Stream0674 Base Level Engineering
Current Plan=p01
Default Exp/Contr=0.3,0.1
English Units
Geom File=g01
Flow File=f01
Plan File=p01
BEGIN DESCRIPTION:
Stream0674
END DESCRIPTION:

--- Stream0674.p01 (plan) ---

Plan Title=Multiple Run
Short Identifier=Multiple
Geom File=g01
Flow File=f01
Subcritical Flow
K Sum by GR= 0
Std Step Tol= 0.01
Critical Tol= 0.01
Num of Std Step Trials= 20
Max Error Tol= 0.3
Flow Tol Ratio= 0.001
Split Flow NTrial= 30
Split Flow Tol= 0.02
Split Flow Ratio= 0.02
Log Output Level= 0
Friction Slope Method= 1
Unsteady Friction Slope Method= 2
Unsteady Bridges Friction Slope Method= 1
Parabolic Critical Depth
Global Vel Dist=  1 , 1 , 1
Global Log Level= 0
CheckData=True
Encroach Param= -1, 0, 0, 0
BEGIN DESCRIPTION:
Multiple Run
END DESCRIPTION:

--- Stream0674.f01 (steady flow) ---

Flow Title=Multiple
Number of Profiles=7
Profile Names=10-year,25-year,50-year,1pct_min,100-year,1pct_plu,500-year
River Rch & RM= Stream0674,Reach-1,9335
    2478    4359    6206    4263    8506   16971   15774
River Rch & RM= Stream0674,Reach-1,1422
    2628    4634    6609    4546    9070   18097   16869
Boundary for River Rch & Prof#=Stream0674,Reach-1,1
Up Type=0
Dn Type=3
Dn Slope=0.005
Boundary for River Rch & Prof#=Stream0674,Reach-1,2
Up Type=0
Dn Type=3
Dn Slope=0.005
Boundary for River Rch & Prof#=Stream0674,Reach-1,3
Up Type=0
Dn Type=3
Dn Slope=0.005
Boundary for River Rch & Prof#=Stream0674,Reach-1,4
Up Type=0
Dn Type=3
Dn Slope=0.005
Boundary for River Rch & Prof#=Stream0674,Reach-1,5
Up Type=0
Dn Type=3
Dn Slope=0.005
Boundary for River Rch & Prof#=Stream0674,Reach-1,6
Up Type=0
Dn Type=3
Dn Slope=0.005
Boundary for River Rch & Prof#=Stream0674,Reach-1,7
Up Type=0
Dn Type=3
Dn Slope=0.005

--- Stream0674.g01 (geometry) ---

Geom Title=Existing Conditions

River Reach=Stream0674,Reach-1
Reach XY= 30
      1920675.00     13861425.00      1920774.06     13861764.51
      1920532.18     13862175.33      1920771.85     13862283.31
      1920824.48     13862609.78      1920721.56     13863073.78
      1920485.32     13863164.82      1920475.51     13863409.79
      1920730.52     13863927.43      1920969.52     13864222.56
      1921025.28     13864454.82      1920919.46     13864777.42
      1920726.47     13865037.13      1920774.07     13865214.52
      1920577.27     13865530.94      1920476.22     13865935.50
      1920475.06     13866204.97      1920744.42     13866745.65
      1920973.45     13866778.75      1921123.02     13866880.67
      1921071.63     13867166.85      1920958.24     13867191.45
      1920728.54     13867476.46      1920725.06     13867754.97
      1920904.91     13868005.22      1921121.55     13868126.25
      1921083.08     13868478.30      1921128.76     13868673.44
      1921271.49     13868876.45      1921275.00     13869025.00

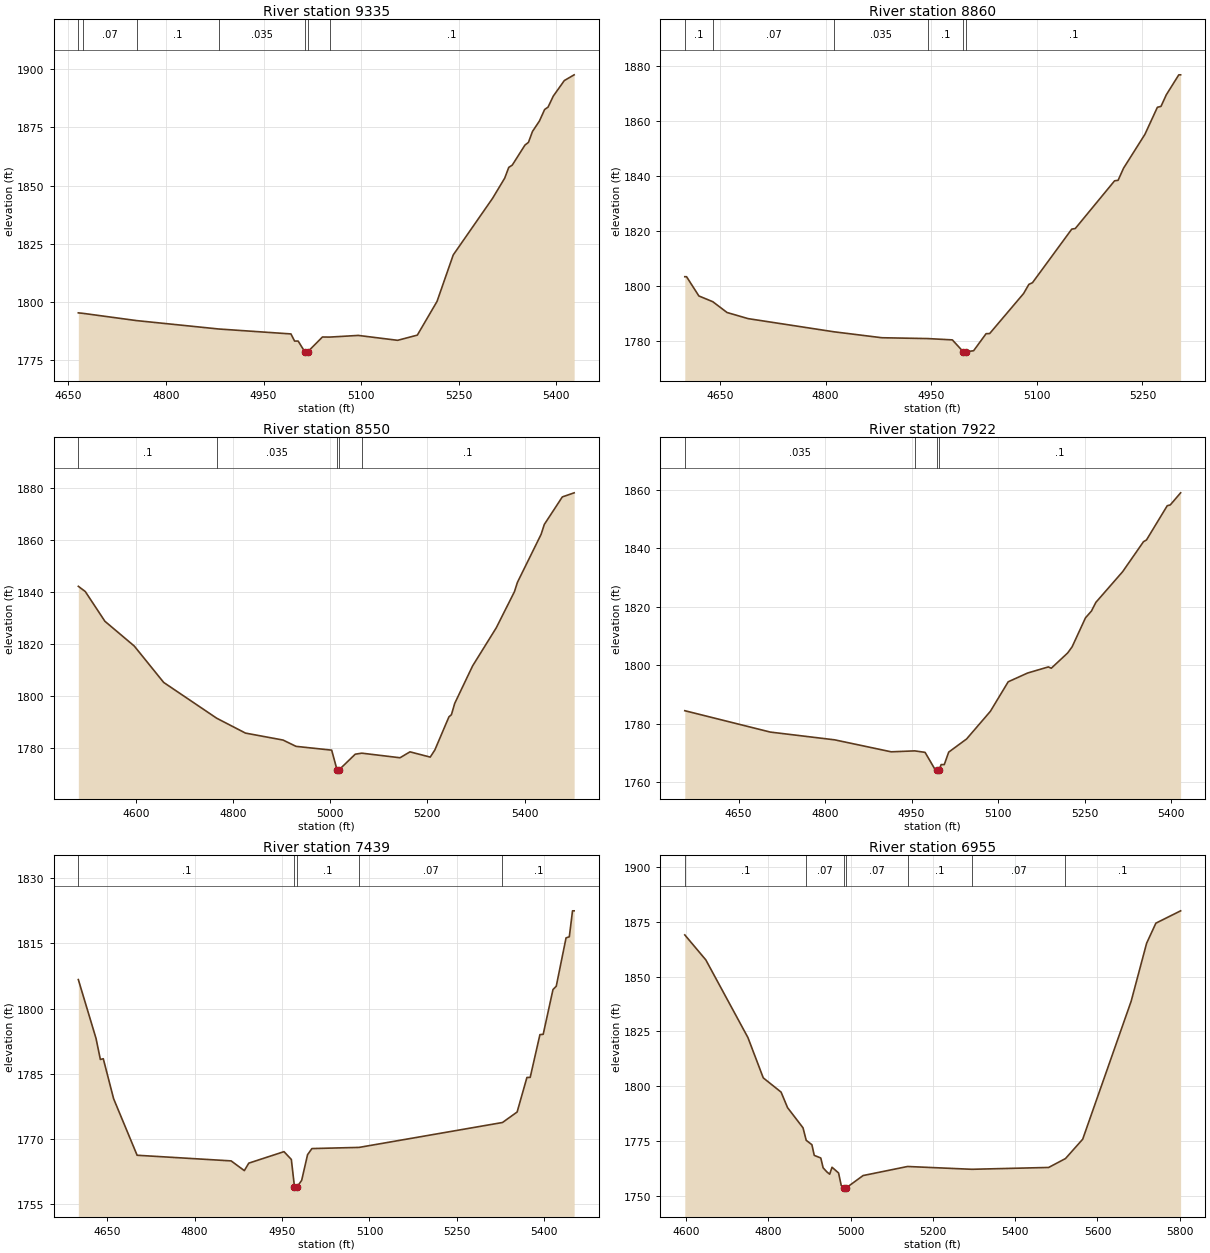
Type RM Length L Ch R = 1,9335,475,475,475
BEGIN DESCRIPTION:
Stream0674 20.0
END DESCRIPTION:
XS GIS Cut Line= 3
      1920375.03     13861375.01      1920675.00     13861525.00
      1921075.02     13861675.01
#Sta/Elev= 30
  4665.2 1795.36  4672.1 1795.17  4754.9 1792.04  4881.0 1788.44  4992.2 1786.32
  4997.8 1783.26  5003.3 1783.26  5013.7 1778.58  5013.9 1778.08  5017.8 1778.58
  5040.6 1785.00  5052.2 1784.97  5095.8 1785.68  5156.3 1783.58  5186.6 1785.81
  5216.9 1800.28  5241.8 1820.22  5302.3 1844.53  5321.0 1853.20  5327.2 1857.81
  5332.6 1858.79  5352.1 1867.38  5357.5 1868.55  5363.7 1873.24  5374.4 1877.73
  5382.4 1882.67  5387.7 1883.71  5395.7 1888.42  5412.7 1895.10  5427.8 1897.55
#Mann=7,-1,0
  4665.2     0.1       0  4672.1    0.07       0  4754.9     0.1       0
  4881.0   0.035       0  5013.7   0.035       0  5017.8   0.035       0
  5052.2     0.1       0
Bank Sta=5013.7,5017.8
Exp/Cntr=0.3,0.1

Type RM Length L Ch R = 1,8860,310,310,310
BEGIN DESCRIPTION:
Stream0674 19.0
END DESCRIPTION:
XS GIS Cut Line= 3
      1920274.98     13861925.00      1920675.00     13861925.00
      1920975.05     13861975.01
#Sta/Elev= 30
  4600.0 1803.38  4602.5 1803.38  4620.0 1796.38  4639.8 1794.29  4660.0 1790.37
  4690.0 1788.14  4812.1 1783.35  4880.0 1781.20  4944.9 1780.90  4980.0 1780.42
  4995.5 1776.11  4995.7 1775.61  4999.6 1776.11  5010.2 1776.48  5027.9 1782.67
  5033.0 1782.73  5081.1 1797.24  5088.7 1800.59  5093.8 1801.20  5149.6 1820.67
  5154.6 1820.89  5210.4 1838.22  5215.4 1838.40  5223.1 1842.79  5253.5 1855.11
  5271.2 1864.94  5276.3 1865.26  5283.9 1869.49  5301.6 1876.73  5304.2 1876.73
#Mann=6,-1,0
  4600.0     0.1       0  4639.8    0.07       0  4812.1   0.035       0
  4944.9     0.1       0  4995.5    0.05       0  4999.6     0.1       0
Bank Sta=4995.5,4999.6
Exp/Cntr=0.3,0.1

Type RM Length L Ch R = 1,8550,628,628,628
BEGIN DESCRIPTION:
Stream0674 18.0
END DESCRIPTION:
XS GIS Cut Line= 3
      1920020.86     13862113.29      1920535.36     13862183.42
      1921025.04     13862074.99
#Sta/Elev= 30
  4481.4 1842.28  4495.7 1840.28  4536.1 1828.85  4596.6 1819.32  4657.1 1805.34
  4766.3 1791.58  4825.5 1785.87  4902.9 1783.19  4929.6 1780.77  5003.0 1779.31
  5014.0 1771.75  5014.3 1771.25  5018.2 1771.75  5051.5 1777.76  5065.1 1778.15
  5143.7 1776.39  5164.2 1778.66  5205.9 1776.64  5215.4 1779.38  5244.4 1792.11
  5249.5 1792.93  5256.3 1797.28  5293.1 1811.68  5341.8 1826.32  5379.2 1840.19
  5385.4 1843.80  5434.2 1862.27  5440.7 1866.04  5477.8 1876.63  5502.2 1878.21
#Mann=5,-1,0
  4481.4     0.1       0  4766.3   0.035       0  5014.0   0.035       0
  5018.2   0.035       0  5065.1     0.1       0
Bank Sta=5014,5018.2
Exp/Cntr=0.3,0.1

Type RM Length L Ch R = 1,7922,483,483,483
BEGIN DESCRIPTION:
Stream0674 17.0
END DESCRIPTION:
XS GIS Cut Line= 3
      1920425.00     13862425.00      1920825.00     13862625.00
      1921224.97     13862724.99
#Sta/Elev= 30
  4556.9 1784.42  4705.0 1777.12  4816.8 1774.46  4914.7 1770.37  4955.5 1770.69
  4973.4 1770.19  4990.1 1764.54  4993.6 1764.27  4993.9 1763.77  4997.9 1764.27
  5001.3 1766.01  5006.7 1766.01  5014.4 1770.27  5045.4 1774.76  5086.6 1784.21
  5117.5 1794.30  5151.0 1797.29  5187.1 1799.39  5192.2 1798.94  5220.6 1804.16
  5228.3 1806.25  5251.5 1816.17  5261.8 1818.48  5269.5 1821.45  5315.9 1831.94
  5352.0 1842.18  5357.2 1842.78  5393.2 1854.48  5398.4 1854.75  5416.4 1858.89
#Mann=4,-1,0
  4556.9   0.035       0  4955.5     0.1       0  4993.6    0.05       0
  4997.9     0.1       0
Bank Sta=4993.6,4997.9
Exp/Cntr=0.3,0.1

Type RM Length L Ch R = 1,7439,484,484,484
BEGIN DESCRIPTION:
Stream0674 16.0
END DESCRIPTION:
XS GIS Cut Line= 3
      1920324.98     13863025.00      1920725.00     13863075.00
      1921124.96     13863274.98
#Sta/Elev= 30
  4600.7 1806.67  4631.0 1793.13  4638.5 1788.25  4643.5 1788.42  4661.2 1779.21
  4701.5 1766.17  4862.7 1764.87  4885.4 1762.63  4893.0 1764.35  4953.4 1767.00
  4966.0 1765.20  4971.4 1758.86  4971.7 1758.36  4975.7 1758.86  4983.7 1760.38
  4993.8 1766.30  5001.3 1767.71  5082.2 1767.98  5328.1 1773.72  5353.2 1776.14
  5370.0 1784.10  5375.6 1784.12  5392.3 1793.98  5397.9 1794.05  5414.7 1804.37
  5420.3 1805.14  5437.1 1816.28  5442.7 1816.54  5448.2 1822.52  5451.0 1822.52
#Mann=5,-1,0
  4600.7     0.1       0  4971.4    0.05       0  4975.7     0.1       0
  5082.2    0.07       0  5328.1     0.1       0
Bank Sta=4971.4,4975.7
Exp/Cntr=0.3,0.1

Type RM Length L Ch R = 1,6955,465,465,465
BEGIN DESCRIPTION:
Stream0674 15.0
END DESCRIPTION:
XS GIS Cut Line= 3
      1920125.04     13863574.98      1920475.00     13863375.00
      1921274.97     13863325.00
#Sta/Elev= 30
  4597.4 1869.05  4648.5 1857.65  4750.7 1822.24  4788.1 1803.80  4831.3 1797.33
  4847.1 1790.22  4884.6 1781.03  4892.4 1775.32  4906.2 1773.32  4911.9 1768.45
  4927.8 1767.26  4933.5 1762.76  4942.9 1760.85  4949.4 1759.86  4955.1 1763.04
  4971.0 1760.42  4977.4 1754.76  4984.6 1753.55  4984.9 1753.05  4989.0 1753.55
  5030.5 1759.24  5138.6 1763.38  5294.7 1762.10  5481.4 1762.94  5522.3 1767.00
  5564.1 1775.83  5681.8 1838.78  5719.4 1865.26  5741.9 1874.41  5802.0 1880.04
#Mann=7,-1,0
  4597.4     0.1       0  4892.4    0.07       0  4984.6    0.05       0
  4989.0    0.07       0  5138.6     0.1       0  5294.7    0.07       0
  5522.3     0.1       0
Bank Sta=4984.6,4989
Exp/Cntr=0.3,0.1

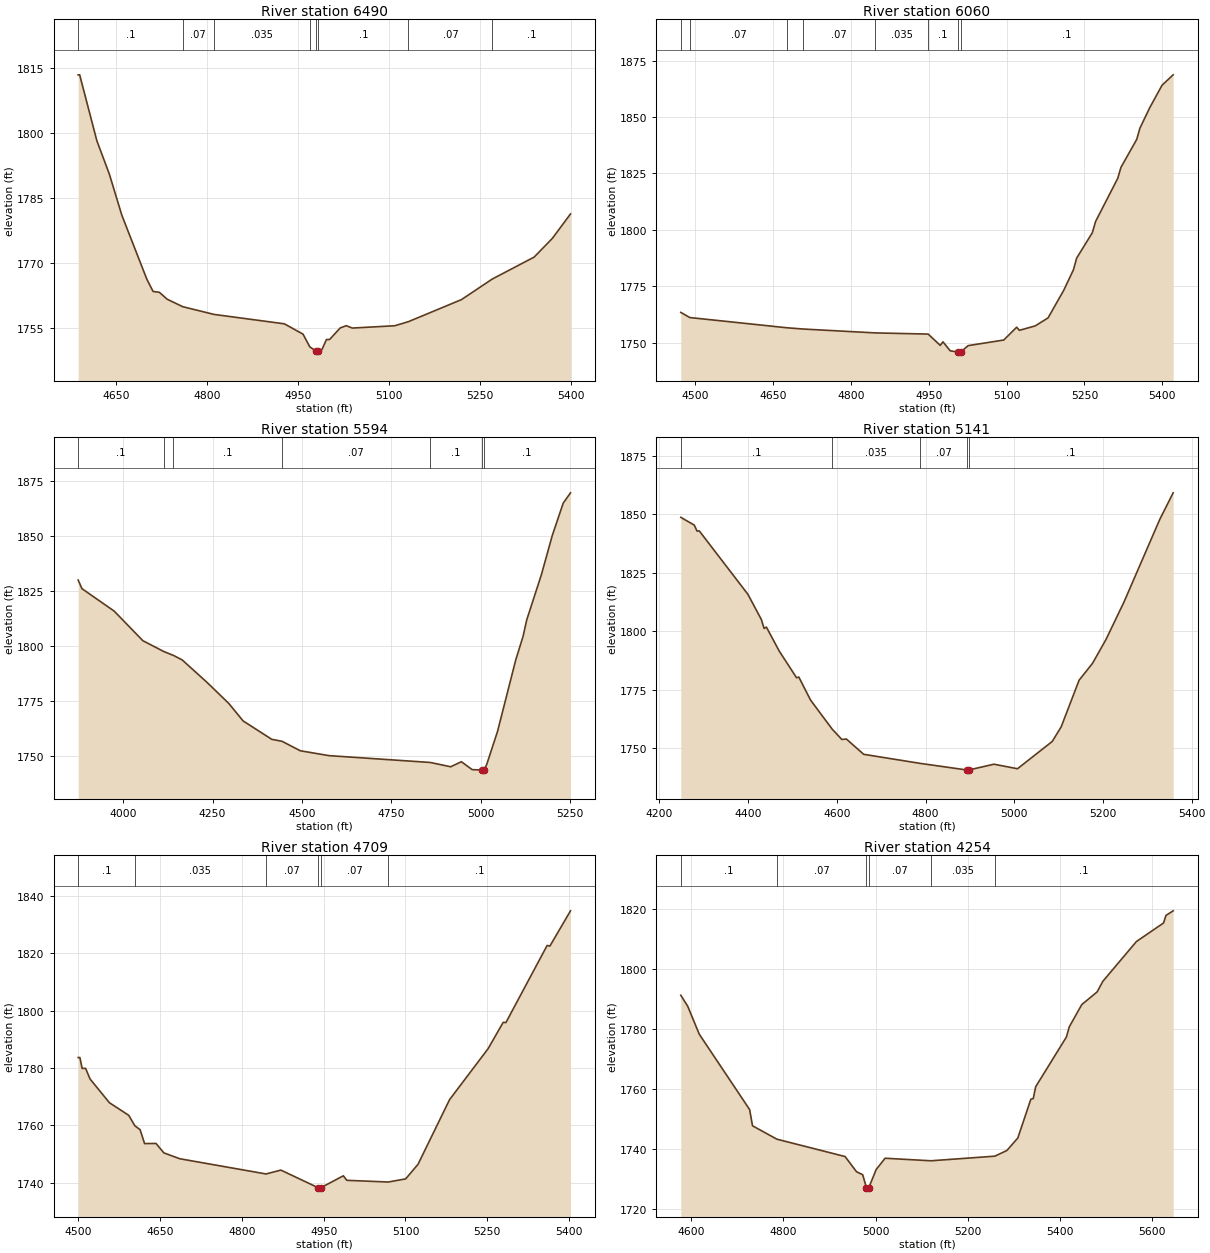
Type RM Length L Ch R = 1,6490,430,430,430
BEGIN DESCRIPTION:
Stream0674 14.0
END DESCRIPTION:
XS GIS Cut Line= 3
      1920275.05     13863675.01      1920675.00     13863775.00
      1921075.04     13863775.00
#Sta/Elev= 30
  4587.7 1813.45  4590.2 1813.45  4618.6 1798.23  4639.2 1790.55  4659.8 1781.07
  4701.0 1766.34  4711.3 1763.51  4721.7 1763.31  4734.5 1761.72  4760.2 1760.00
  4811.6 1758.22  4927.8 1756.05  4958.7 1753.67  4969.8 1750.75  4979.7 1749.79
  4980.0 1749.29  4984.1 1749.79  4989.7 1750.07  4997.4 1752.43  5002.5 1752.43
  5020.0 1755.09  5030.0 1755.62  5040.0 1755.07  5110.0 1755.60  5132.5 1756.54
  5220.0 1761.62  5270.9 1766.37  5340.0 1771.43  5370.0 1775.74  5400.0 1781.38
#Mann=8,-1,0
  4587.7     0.1       0  4760.2    0.07       0  4811.6   0.035       0
  4969.8     0.1       0  4979.7    0.05       0  4984.1     0.1       0
  5132.5    0.07       0  5270.9     0.1       0
Bank Sta=4979.7,4984.1
Exp/Cntr=0.3,0.1

Type RM Length L Ch R = 1,6060,466,466,466
BEGIN DESCRIPTION:
Stream0674 13.0
END DESCRIPTION:
XS GIS Cut Line= 3
      1920375.03     13863975.01      1920875.00     13864125.00
      1921275.02     13864275.01
#Sta/Elev= 30
  4471.8 1763.35  4489.2 1761.07  4677.1 1756.52  4707.7 1755.98  4846.8 1754.26
  4948.7 1753.74  4972.0 1748.72  4977.2 1750.31  4991.2 1746.30  5006.4 1745.79
  5006.8 1745.29  5011.5 1745.79  5025.8 1748.62  5094.4 1751.10  5119.3 1756.78
  5124.6 1755.41  5154.9 1757.35  5179.8 1760.91  5210.1 1773.19  5228.7 1782.23
  5235.0 1787.46  5265.2 1798.72  5271.5 1803.72  5314.2 1822.84  5320.4 1827.73
  5350.7 1840.07  5356.9 1845.06  5375.6 1854.06  5399.6 1864.14  5421.0 1868.74
#Mann=8,-1,0
  4471.8     0.1       0  4489.2    0.07       0  4677.1   0.035       0
  4707.7    0.07       0  4846.8   0.035       0  4948.7     0.1       0
  5006.4    0.05       0  5011.5     0.1       0
Bank Sta=5006.4,5011.5
Exp/Cntr=0.3,0.1

Type RM Length L Ch R = 1,5594,453,453,453
BEGIN DESCRIPTION:
Stream0674 12.0
END DESCRIPTION:
XS GIS Cut Line= 3
      1919854.29     13864560.10      1920975.00     13864525.00
      1921224.99     13864575.00
#Sta/Elev= 30
  3874.4 1829.90  3885.1 1825.99  3975.2 1815.80  4055.2 1802.39  4113.9 1797.46
  4140.7 1795.71  4165.3 1793.65  4235.3 1783.36  4295.3 1773.94  4335.3 1766.00
  4415.4 1757.64  4444.3 1756.72  4495.4 1752.43  4575.5 1750.22  4858.7 1747.12
  4915.6 1745.17  4945.6 1747.46  4975.7 1743.87  5003.3 1743.69  5003.7 1743.19
  5008.4 1743.69  5016.1 1746.08  5046.7 1761.26  5097.6 1793.71  5118.0 1804.36
  5128.2 1811.82  5169.0 1832.23  5199.6 1850.11  5230.2 1864.82  5250.6 1869.49
#Mann=7,-1,0
  3874.4     0.1       0  4113.9    0.07       0  4140.7     0.1       0
  4444.3    0.07       0  4858.7     0.1       0  5003.3    0.05       0
  5008.4     0.1       0
Bank Sta=5003.3,5008.4
Exp/Cntr=0.3,0.1

Type RM Length L Ch R = 1,5141,432,432,432
BEGIN DESCRIPTION:
Stream0674 11.0
END DESCRIPTION:
XS GIS Cut Line= 3
      1920074.99     13864825.00      1920825.00     13864925.00
      1921175.00     13864875.00
#Sta/Elev= 30
  4248.1 1848.64  4278.4 1845.34  4284.7 1842.76  4289.7 1842.86  4399.4 1815.75
  4429.7 1804.97  4436.0 1801.13  4441.1 1801.73  4470.1 1791.46  4509.1 1780.08
  4514.2 1780.38  4540.7 1770.52  4589.6 1758.07  4611.3 1753.68  4621.4 1753.89
  4660.5 1747.35  4787.6 1743.48  4892.5 1740.66  4892.9 1740.16  4897.6 1740.66
  4954.3 1743.12  5007.3 1741.18  5085.6 1752.84  5105.8 1759.09  5146.2 1779.02
  5176.5 1786.25  5206.8 1796.42  5247.2 1812.35  5328.0 1847.71  5358.3 1859.12
#Mann=5,-1,0
  4248.1     0.1       0  4589.6   0.035       0  4787.6    0.07       0
  4892.5    0.05       0  4897.6     0.1       0
Bank Sta=4892.5,4897.6
Exp/Cntr=0.3,0.1

Type RM Length L Ch R = 1,4709,455,455,455
BEGIN DESCRIPTION:
Stream0674 10.0
END DESCRIPTION:
XS GIS Cut Line= 3
      1920324.96     13864974.97      1920725.00     13865275.00
      1921125.04     13865325.00
#Sta/Elev= 30
  4499.6 1783.64  4502.8 1783.64  4506.9 1779.86  4513.2 1779.87  4521.5 1776.15
  4556.9 1767.90  4592.4 1763.49  4603.6 1759.85  4613.2 1758.49  4621.5 1753.64
  4642.4 1753.69  4656.9 1750.39  4686.1 1748.35  4844.2 1743.05  4871.5 1744.39
  4939.8 1738.26  4940.2 1737.76  4944.9 1738.26  4986.1 1742.41  4992.4 1740.83
  5068.5 1740.24  5100.4 1741.33  5123.1 1746.43  5181.0 1768.98  5251.6 1786.73
  5279.3 1795.91  5284.3 1795.84  5359.9 1822.72  5365.0 1822.52  5402.8 1834.80
#Mann=6,-1,0
  4499.6     0.1       0  4603.6   0.035       0  4844.2    0.07       0
  4939.8    0.05       0  4944.9    0.07       0  5068.5     0.1       0
Bank Sta=4939.8,4944.9
Exp/Cntr=0.3,0.1

Type RM Length L Ch R = 1,4254,483,483,483
BEGIN DESCRIPTION:
Stream0674 9.0
END DESCRIPTION:
XS GIS Cut Line= 3
      1920174.99     13865525.00      1920575.00     13865675.00
      1921191.64     13865494.59
#Sta/Elev= 30
  4576.9 1791.29  4592.0 1787.61  4617.0 1778.30  4726.4 1753.15  4732.7 1747.73
  4785.6 1743.26  4933.8 1737.47  4958.7 1732.39  4972.1 1731.39  4980.2 1727.09
  4980.6 1726.59  4985.4 1727.09  5001.4 1733.15  5020.8 1736.90  5120.3 1736.05
  5259.2 1737.59  5285.4 1739.49  5309.1 1743.65  5337.4 1756.60  5342.6 1756.80
  5347.9 1760.76  5414.7 1777.37  5420.9 1780.75  5448.1 1788.19  5481.5 1792.42
  5493.8 1795.94  5566.8 1809.23  5625.7 1815.41  5630.9 1817.92  5646.6 1819.47
#Mann=6,-1,0
  4576.9     0.1       0  4785.6    0.07       0  4980.2    0.05       0
  4985.4    0.07       0  5120.3   0.035       0  5259.2     0.1       0
Bank Sta=4980.2,4985.4
Exp/Cntr=0.3,0.1

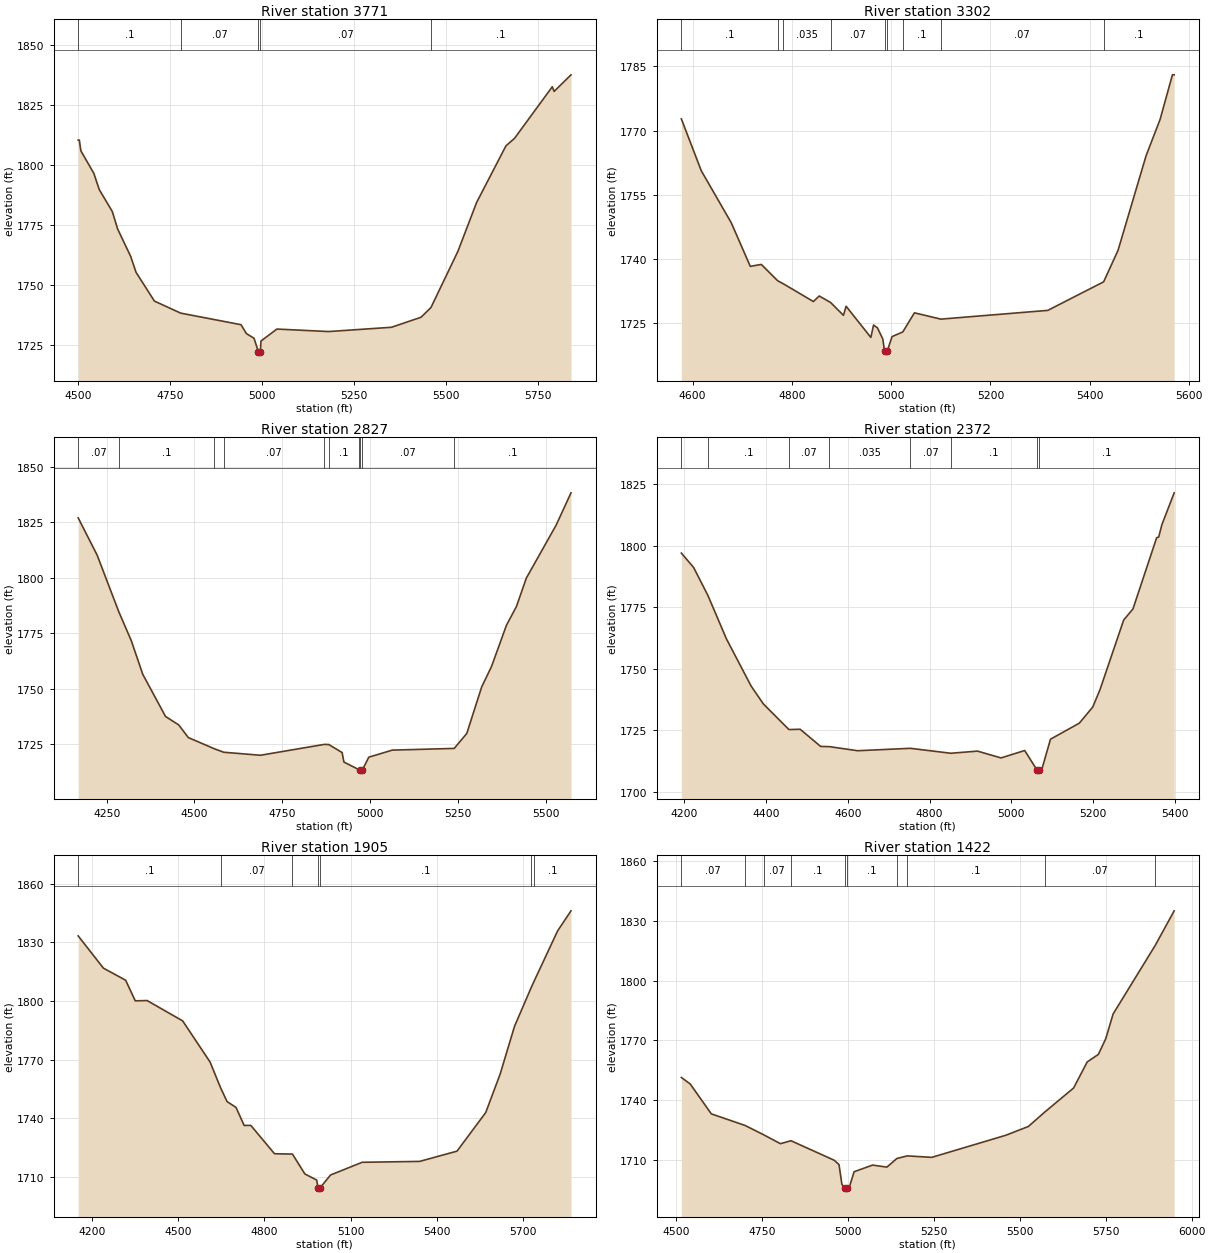
Type RM Length L Ch R = 1,3771,469,469,469
BEGIN DESCRIPTION:
Stream0674 8.0
END DESCRIPTION:
XS GIS Cut Line= 3
      1920074.98     13865824.99      1920475.00     13866125.00
      1921310.98     13866045.20
#Sta/Elev= 30
  4500.1 1810.20  4503.2 1810.20  4507.4 1805.73  4542.8 1796.29  4557.4 1789.56
  4592.8 1780.44  4607.4 1773.13  4642.8 1761.74  4657.4 1755.09  4707.4 1743.09
  4778.8 1738.08  4942.8 1733.26  4957.4 1729.56  4978.2 1727.60  4990.2 1721.91
  4990.6 1721.41  4995.5 1721.91  4997.0 1726.44  5040.3 1731.44  5180.9 1730.40
  5351.7 1732.18  5432.1 1736.35  5459.2 1740.42  5532.5 1763.85  5583.3 1784.20
  5663.1 1807.81  5686.2 1810.89  5789.0 1832.41  5794.0 1830.48  5839.9 1837.39
#Mann=5,-1,0
  4500.1     0.1       0  4778.8    0.07       0  4990.2    0.05       0
  4995.5    0.07       0  5459.2     0.1       0
Bank Sta=4990.2,4995.5
Exp/Cntr=0.3,0.1

Type RM Length L Ch R = 1,3302,475,475,475
BEGIN DESCRIPTION:
Stream0674 7.0
END DESCRIPTION:
XS GIS Cut Line= 3
      1920274.99     13866675.00      1920675.00     13866525.00
      1921075.00     13866125.00
#Sta/Elev= 30
  4577.3 1772.72  4617.4 1760.63  4677.9 1748.48  4716.2 1738.32  4738.4 1738.77
  4771.2 1734.98  4782.7 1734.26  4843.4 1730.11  4855.0 1731.41  4877.8 1729.91
  4903.9 1726.90  4909.3 1729.01  4959.1 1721.74  4964.5 1724.63  4972.5 1723.96
  4983.2 1721.37  4986.6 1718.58  4987.0 1718.08  4992.2 1718.58  5001.8 1721.93
  5023.5 1723.03  5046.9 1727.48  5100.1 1726.01  5315.6 1728.05  5428.1 1734.71
  5457.1 1742.05  5513.6 1764.11  5541.9 1772.61  5566.7 1782.99  5570.2 1782.99
#Mann=9,-1,0
  4577.3     0.1       0  4771.2    0.07       0  4782.7   0.035       0
  4877.8    0.07       0  4986.6    0.05       0  4992.2    0.07       0
  5023.5     0.1       0  5100.1    0.07       0  5428.1     0.1       0
Bank Sta=4986.6,4992.2
Exp/Cntr=0.3,0.1

Type RM Length L Ch R = 1,2827,455,455,455
BEGIN DESCRIPTION:
Stream0674 6.0
END DESCRIPTION:
XS GIS Cut Line= 3
      1920175.00     13867025.00      1920975.00     13866775.00
      1921374.97     13866375.03
#Sta/Elev= 30
  4168.8 1826.94  4222.8 1810.16  4284.0 1784.82  4320.2 1771.55  4352.7 1756.47
  4417.6 1737.45  4455.3 1733.62  4482.6 1727.93  4556.9 1722.87  4583.4 1721.32
  4687.9 1719.96  4869.8 1724.85  4882.7 1724.79  4920.5 1721.20  4925.8 1716.90
  4968.1 1713.50  4972.7 1713.31  4973.1 1712.81  4978.4 1713.31  4996.5 1719.08
  5063.5 1722.28  5239.9 1723.04  5275.7 1729.78  5318.1 1750.72  5346.4 1760.05
  5388.8 1778.57  5417.1 1786.96  5445.4 1799.81  5530.2 1823.64  5572.6 1838.22
#Mann=10,-1,0
  4168.8    0.07       0  4284.0     0.1       0  4556.9   0.035       0
  4583.4    0.07       0  4869.8   0.035       0  4882.7     0.1       0
  4968.1    0.07       0  4972.7    0.05       0  4978.4    0.07       0
  5239.9     0.1       0
Bank Sta=4972.7,4978.4
Exp/Cntr=0.3,0.1

Type RM Length L Ch R = 1,2372,467,467,467
BEGIN DESCRIPTION:
Stream0674 5.0
END DESCRIPTION:
XS GIS Cut Line= 3
      1920275.04     13867175.00      1921075.00     13867125.00
      1921474.97     13867175.00
#Sta/Elev= 30
  4193.3 1796.98  4223.3 1791.15  4258.4 1779.70  4303.5 1762.10  4363.6 1742.97
  4393.7 1735.65  4456.3 1725.20  4483.8 1725.32  4533.9 1718.33  4555.2 1718.25
  4624.1 1716.59  4753.1 1717.57  4852.0 1715.56  4917.2 1716.43  4974.8 1713.66
  5032.6 1716.68  5062.4 1708.79  5062.9 1708.29  5068.3 1708.79  5075.4 1709.59
  5095.6 1721.27  5166.1 1727.81  5198.9 1734.36  5216.5 1741.39  5274.5 1769.76
  5297.2 1774.27  5355.1 1803.25  5360.1 1803.51  5367.7 1808.45  5397.9 1821.50
#Mann=8,-1,0
  4193.3    0.07       0  4258.4     0.1       0  4456.3    0.07       0
  4555.2   0.035       0  4753.1    0.07       0  4852.0     0.1       0
  5062.4    0.05       0  5068.3     0.1       0
Bank Sta=5062.4,5068.3
Exp/Cntr=0.3,0.1

Type RM Length L Ch R = 1,1905,483,483,483
BEGIN DESCRIPTION:
Stream0674 4.0
END DESCRIPTION:
XS GIS Cut Line= 4
      1919952.33     13867219.33      1920375.00     13867325.00
      1920775.00     13867425.00      1921641.60     13867429.25
#Sta/Elev= 30
  4152.3 1833.30  4240.1 1816.80  4317.4 1810.63  4350.9 1800.08  4392.1 1800.23
  4515.8 1789.83  4611.2 1768.78  4647.9 1755.56  4670.4 1748.54  4701.4 1745.58
  4729.7 1736.34  4752.9 1736.37  4835.4 1721.87  4897.8 1721.70  4941.0 1711.53
  4982.2 1708.41  4987.0 1704.27  4987.5 1703.77  4993.0 1704.27  5030.3 1711.00
  5140.3 1717.49  5340.3 1717.95  5470.3 1723.20  5570.3 1742.96  5620.3 1762.58
  5670.3 1787.01  5728.5 1806.88  5739.6 1810.47  5820.3 1835.85  5866.9 1846.12
#Mann=7,-1,0
  4152.3     0.1       0  4647.9    0.07       0  4897.8     0.1       0
  4987.0    0.05       0  4993.0     0.1       0  5728.5    0.07       0
  5739.6     0.1       0
Bank Sta=4987,4993
Exp/Cntr=0.3,0.1

Type RM Length L Ch R = 1,1422,441,441,441
BEGIN DESCRIPTION:
Stream0674 3.0
END DESCRIPTION:
XS GIS Cut Line= 4
      1920344.49     13868090.26      1920675.00     13867925.00
      1920775.00     13867875.00      1921659.96     13867520.38
#Sta/Elev= 30
  4514.4 1751.38  4540.1 1748.14  4601.6 1733.09  4699.9 1727.26  4753.8 1722.59
  4802.9 1718.09  4833.5 1719.58  4959.4 1709.77  4973.4 1707.57  4981.8 1697.70
  4989.8 1695.75  4990.3 1695.25  4996.0 1695.75  5005.1 1697.15  5017.3 1703.99
  5071.1 1707.33  5112.8 1706.32  5141.8 1710.65  5172.2 1711.96  5243.5 1711.22
  5459.0 1722.33  5524.5 1726.73  5573.4 1734.14  5656.3 1746.08  5696.0 1759.20
  5728.3 1762.96  5749.8 1770.81  5771.4 1783.31  5894.5 1817.93  5949.1 1835.15
#Mann=10,-1,0
  4514.4    0.07       0  4699.9   0.035       0  4753.8    0.07       0
  4833.5     0.1       0  4989.8    0.05       0  4996.0     0.1       0
  5141.8    0.07       0  5172.2     0.1       0  5573.4    0.07       0
  5894.5     0.1       0
Bank Sta=4989.8,4996
Exp/Cntr=0.3,0.1

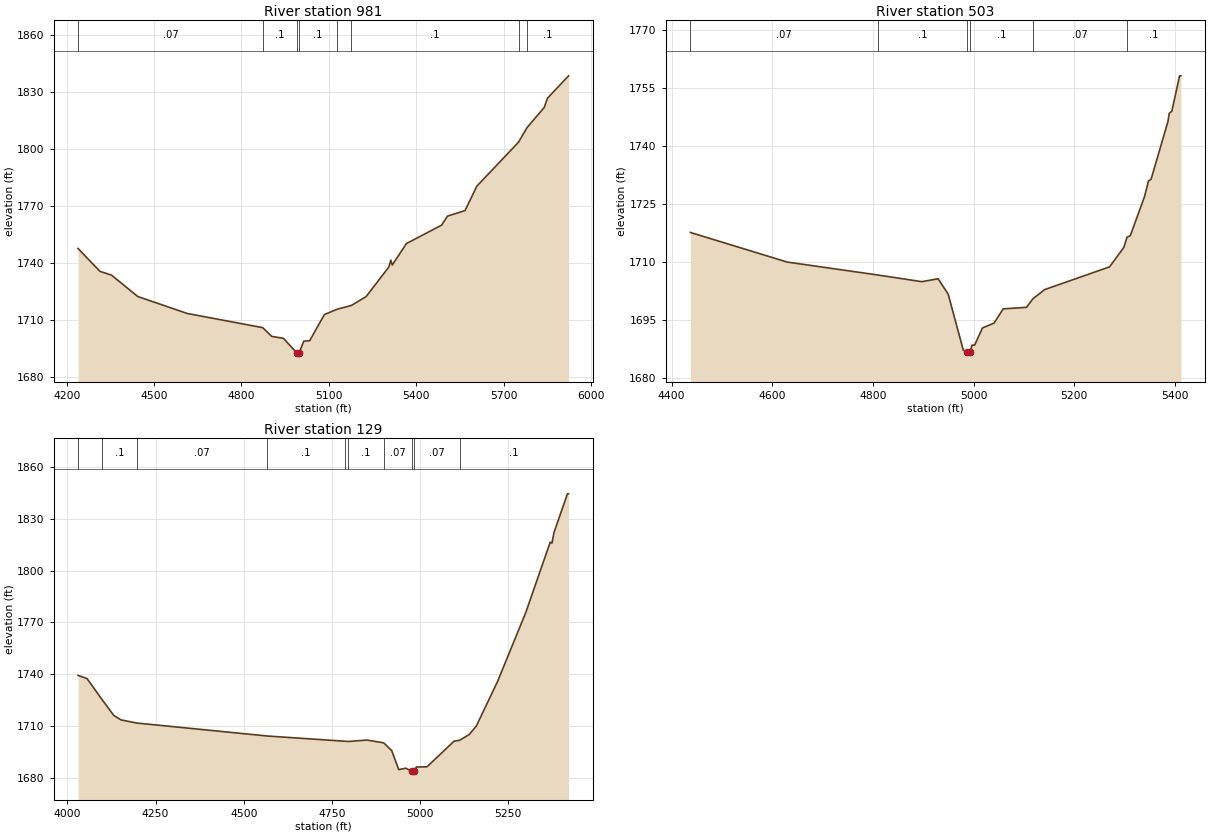
Type RM Length L Ch R = 1,981,478,478,478
BEGIN DESCRIPTION:
Stream0674 2.0
END DESCRIPTION:
XS GIS Cut Line= 4
      1920360.15     13868125.00      1920875.00     13868125.00
      1921125.00     13868125.00      1922037.98     13868228.65
#Sta/Elev= 30
  4239.2 1747.75  4314.1 1735.73  4354.1 1733.71  4444.1 1722.46  4614.1 1713.52
  4872.8 1706.07  4904.1 1701.46  4944.1 1700.45  4990.9 1692.62  4991.4 1692.12
  4997.3 1692.62  5014.1 1698.95  5034.2 1699.18  5084.6 1712.93  5128.2 1715.75
  5176.8 1717.71  5228.1 1722.42  5306.0 1738.00  5312.7 1741.59  5317.7 1739.05
  5366.4 1750.34  5486.9 1760.02  5507.3 1764.78  5567.6 1767.73  5607.9 1780.54
  5751.0 1803.71  5780.3 1811.39  5839.4 1822.03  5850.4 1826.87  5922.9 1838.66
#Mann=8,-1,0
  4239.2    0.07       0  4872.8     0.1       0  4990.9    0.05       0
  4997.3     0.1       0  5128.2    0.07       0  5176.8     0.1       0
  5751.0    0.07       0  5780.3     0.1       0
Bank Sta=4990.9,4997.3
Exp/Cntr=0.3,0.1

Type RM Length L Ch R = 1,503,374,374,374
BEGIN DESCRIPTION:
Stream0674 1.0
END DESCRIPTION:
XS GIS Cut Line= 4
      1920562.81     13868575.00      1921025.00     13868575.00
      1921125.00     13868575.00      1921525.00     13868675.00
#Sta/Elev= 30
  4437.5 1717.65  4629.7 1710.01  4810.0 1706.67  4897.2 1704.95  4929.7 1705.70
  4949.7 1701.73  4979.7 1687.29  4986.5 1686.76  4987.0 1686.26  4992.9 1686.76
  4997.2 1688.59  5002.3 1688.59  5017.7 1693.00  5040.9 1694.28  5059.0 1697.94
  5105.3 1698.33  5118.1 1700.55  5141.4 1702.91  5270.3 1708.77  5298.6 1713.78
  5305.0 1716.42  5311.5 1716.81  5339.8 1726.90  5347.6 1730.95  5352.7 1731.33
  5386.2 1746.22  5388.8 1748.37  5394.0 1748.92  5409.4 1758.05  5412.0 1758.05
#Mann=6,-1,0
  4437.5    0.07       0  4810.0     0.1       0  4986.5    0.05       0
  4992.9     0.1       0  5118.1    0.07       0  5305.0     0.1       0
Bank Sta=4986.5,4992.9
Exp/Cntr=0.3,0.1

Type RM Length L Ch R = 1,129,0,0,0
BEGIN DESCRIPTION:
Stream0674 0.0
END DESCRIPTION:
XS GIS Cut Line= 3
      1920314.68     13868766.27      1921146.22     13868891.70
      1921696.51     13868911.73
#Sta/Elev= 30
  4030.0 1739.24  4055.3 1737.44  4097.8 1725.32  4131.5 1716.04  4151.7 1713.50
  4196.4 1711.67  4566.7 1704.16  4786.7 1701.13  4797.1 1700.98  4849.5 1701.81
  4897.0 1700.21  4919.8 1695.71  4939.8 1684.67  4959.8 1685.52  4976.5 1683.74
  4977.0 1683.24  4983.0 1683.74  4989.8 1686.21  5019.8 1686.31  5097.0 1701.20
  5112.6 1701.66  5139.9 1705.06  5159.9 1709.93  5220.0 1735.68  5300.0 1775.57
  5369.5 1816.40  5374.5 1815.84  5380.1 1821.93  5418.4 1844.41  5421.6 1844.41
#Mann=10,-1,0
  4030.0    0.07       0  4097.8     0.1       0  4196.4    0.07       0
  4566.7     0.1       0  4786.7    0.07       0  4797.1     0.1       0
  4897.0    0.07       0  4976.5    0.05       0  4983.0    0.07       0
  5112.6     0.1       0
Bank Sta=4976.5,4983
Exp/Cntr=0.3,0.1

Chan Stop Cuts=-1