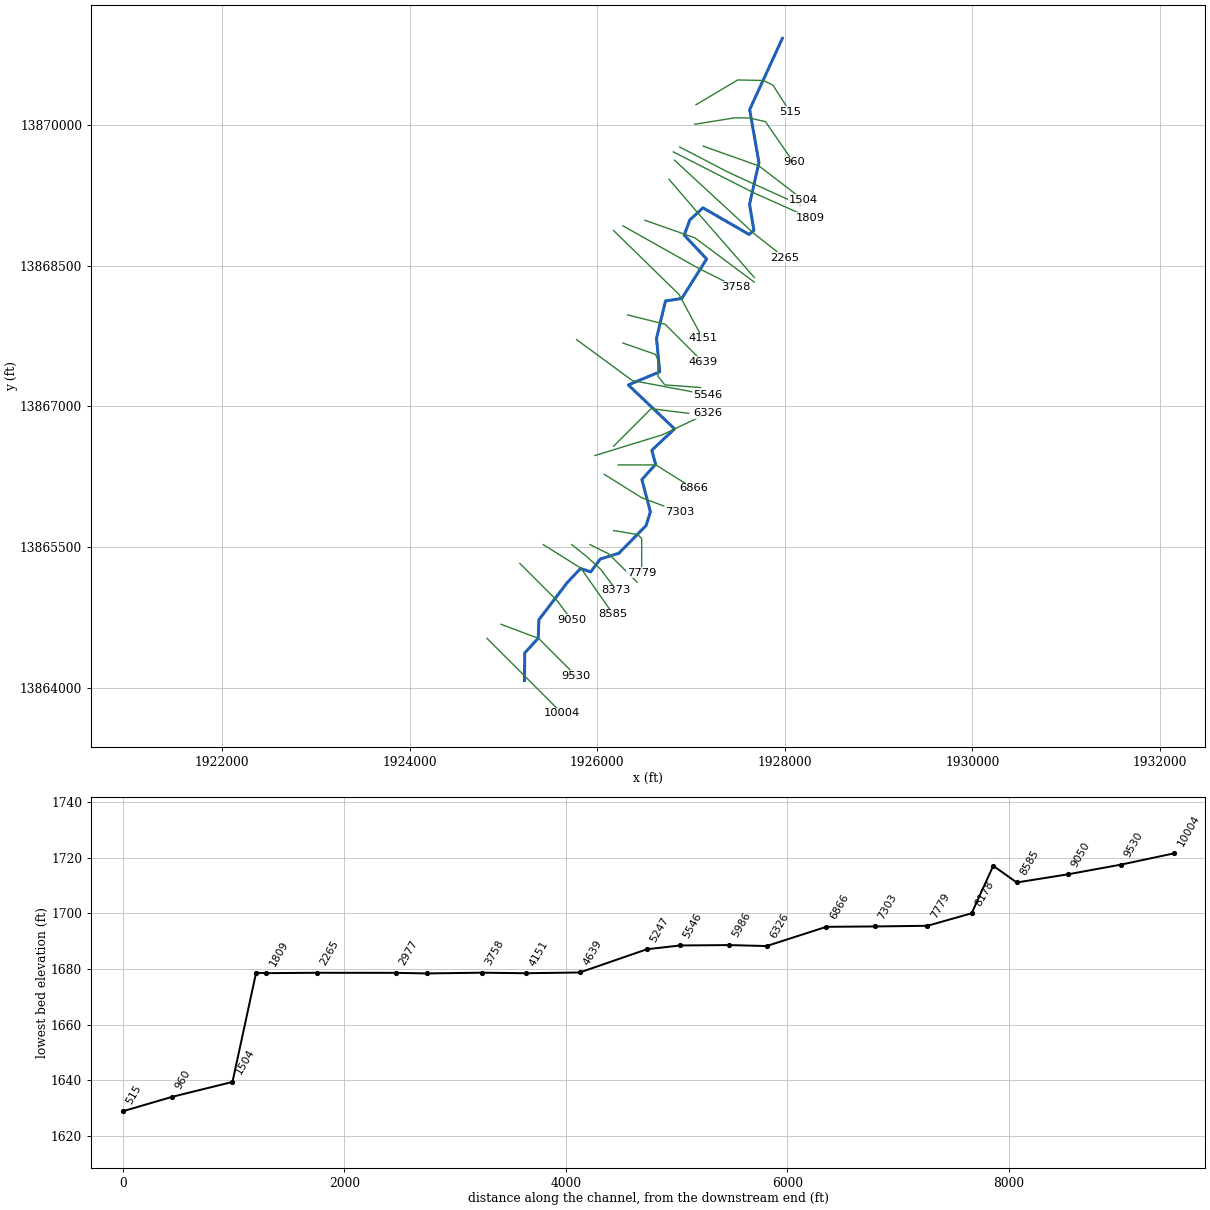
--- Stream0675.prj (project) ---

Proj Title=Stream0675 Base Level Engineering
Current Plan=p01
Default Exp/Contr=0.3,0.1
English Units
Geom File=g01
Flow File=f01
Plan File=p01
Y Axis Title=Elevation
X Axis Title(PF)=Main Channel Distance
X Axis Title(XS)=Station
BEGIN DESCRIPTION:
Stream0675
END DESCRIPTION:
DSS Export Rating Curves= 0
DSS Export Rating Curve Sorted= 0
DSS Export Volume Flow Curves= 0
DXF OffsetX= 0
DXF OffsetY= 0
DXF ScaleX= 1
DXF ScaleY= 10

--- Stream0675.p01 (plan) ---

Plan Title=Multiple Run
Short Identifier=Multiple
Geom File=g01
Flow File=f01
Subcritical Flow
K Sum by GR= 0
Std Step Tol= 0.01
Critical Tol= 0.01
Num of Std Step Trials= 20
Max Error Tol= 0.3
Flow Tol Ratio= 0.001
Split Flow NTrial= 30
Split Flow Tol= 0.02
Split Flow Ratio= 0.02
Log Output Level= 0
Friction Slope Method= 1
Unsteady Friction Slope Method= 2
Unsteady Bridges Friction Slope Method= 1
Parabolic Critical Depth
Global Vel Dist=  1 , 1 , 1
Global Log Level= 0
CheckData=True
Encroach Param= -1, 0, 0, 0
BEGIN DESCRIPTION:
Multiple Run
END DESCRIPTION:

--- Stream0675.f01 (steady flow) ---

Flow Title=Multiple
Number of Profiles=7
Profile Names=10-year,25-year,50-year,1pct_min,100-year,1pct_plu,500-year
River Rch & RM= Stream0675,Reach-1,10004
    2403    4239    6046    4160    8301   16563   15457
River Rch & RM= Stream0675,Reach-1,4151
    2755    4887    6996    4829    9635   19224   18054
Boundary for River Rch & Prof#=Stream0675,Reach-1,1
Up Type=0
Dn Type=3
Dn Slope=0.005
Boundary for River Rch & Prof#=Stream0675,Reach-1,2
Up Type=0
Dn Type=3
Dn Slope=0.005
Boundary for River Rch & Prof#=Stream0675,Reach-1,3
Up Type=0
Dn Type=3
Dn Slope=0.005
Boundary for River Rch & Prof#=Stream0675,Reach-1,4
Up Type=0
Dn Type=3
Dn Slope=0.005
Boundary for River Rch & Prof#=Stream0675,Reach-1,5
Up Type=0
Dn Type=3
Dn Slope=0.005
Boundary for River Rch & Prof#=Stream0675,Reach-1,6
Up Type=0
Dn Type=3
Dn Slope=0.005
Boundary for River Rch & Prof#=Stream0675,Reach-1,7
Up Type=0
Dn Type=3
Dn Slope=0.005

--- Stream0675.g01 (geometry) ---

Geom Title=Existing Conditions
Program Version=4.10

River Reach=Stream0675      ,Reach-1
Reach XY= 30
        1925225.       13864075.      1925227.23      13864369.1
      1925371.52     13864526.26      1925378.54     13864723.54
      1925680.29     13865119.52      1925822.46     13865269.99
      1925931.75     13865234.14      1926033.48     13865371.49
      1926231.17     13865432.86      1926521.18     13865726.58
      1926567.47     13865875.01      1926476.97     13866219.11
      1926623.48     13866381.39      1926582.74     13866531.14
      1926825.16     13866759.76       1926332.5     13867228.17
      1926667.33     13867368.48      1926632.76     13867724.92
      1926728.52     13868123.78      1926902.14     13868150.54
       1927167.4     13868571.67      1926928.12     13868826.63
      1926988.62     13868988.22      1927128.23     13869117.17
      1927618.63     13868834.17      1927671.55     13868876.02
      1927625.05     13869154.96       1927725.2     13869600.08
       1927626.2      13870164.5        1927975.       13870925.

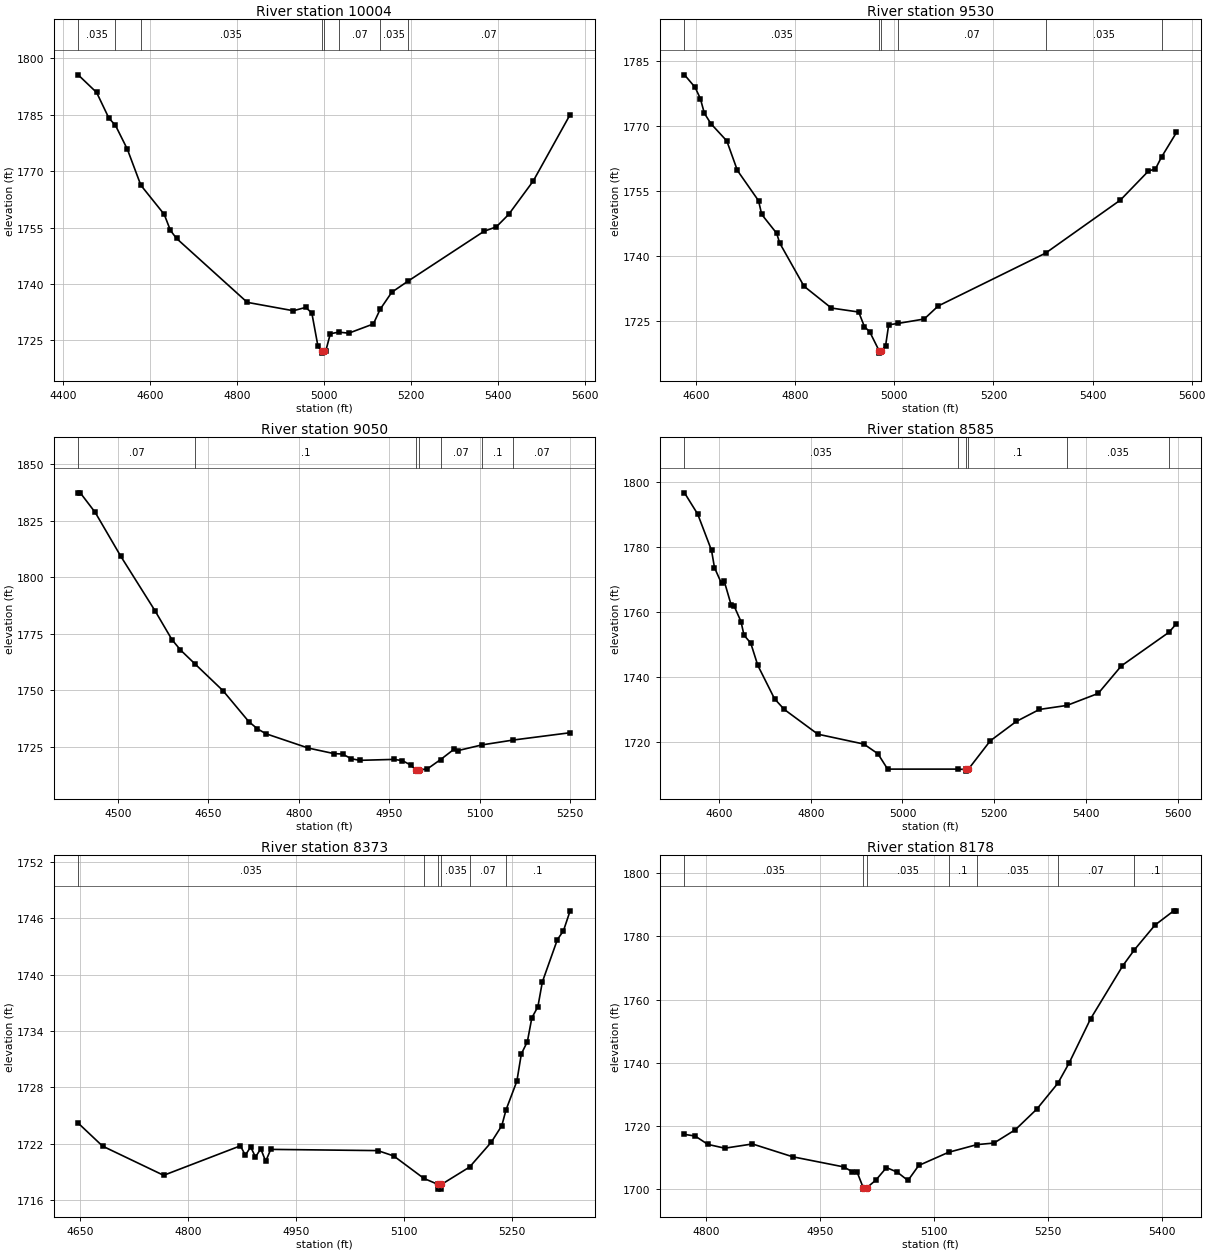
Type RM Length L Ch R = 1 ,10004   ,474,474,474
BEGIN DESCRIPTION:
Stream0675 22.0
END DESCRIPTION:
XS GIS Cut Line= 3
      1924824.98     13864525.02        1925225.       13864125.
        1925625.       13863725.
#Sta/Elev= 30
  4434.3 1795.58  4476.8 1790.89    4505 1784.07  4520.1 1782.16  4547.5 1775.81
  4578.5 1766.25  4632.3  1758.5  4646.5 1754.25  4660.6 1752.11  4823.2 1735.13
  4929.3  1732.9  4957.6 1733.79  4971.7 1732.31  4985.9 1723.41  4994.3 1722.14
  4994.6 1721.64  4998.6 1722.14  5003.6 1722.14  5014.2 1726.78  5033.5 1727.22
  5056.6 1726.94  5113.2 1729.39  5128.9  1733.3  5155.6 1737.82  5192.8 1740.76
  5367.7 1754.01    5396 1755.19  5424.3 1758.48  5480.8 1767.36  5565.7 1785.01
#Mann= 8 ,-1 , 0
  4434.3    .035       0  4520.1     .07       0  4578.5    .035       0
  4994.3    .035       0  4998.6    .035       0  5033.5     .07       0
  5128.9    .035       0  5192.8     .07       0
Bank Sta=4994.3,4998.6
XS Rating Curve= 0 ,0
Exp/Cntr=0.3,0.1

Type RM Length L Ch R = 1 ,9530    ,480,480,480
BEGIN DESCRIPTION:
Stream0675 21.0
END DESCRIPTION:
XS GIS Cut Line= 3
        1924975.       13864675.        1925375.       13864525.
      1925775.01     13864124.99
#Sta/Elev= 30
  4576.5 1781.76  4597.9 1778.88  4608.5 1776.29  4616.6 1772.91  4629.9 1770.49
  4661.9 1766.53  4683.3 1759.72    4726 1752.74  4732.3  1749.6  4762.5 1745.25
  4768.7 1742.99  4817.7 1733.05  4872.9 1728.02  4928.1  1727.1  4939.6 1723.74
  4950.3 1722.55  4969.5 1718.13  4969.8 1717.63  4973.9 1718.13  4982.3 1719.28
  4988.6 1724.15  5007.3 1724.47  5060.3 1725.49  5088.6  1728.5  5305.2 1740.67
  5456.2  1752.9  5512.8 1759.58    5527 1760.09  5539.2  1762.8  5569.4 1768.48
#Mann= 6 ,-1 , 0
  4576.5    .035       0  4969.5    .035       0  4973.9    .035       0
  5007.3     .07       0  5305.2    .035       0  5539.2     .07       0
Bank Sta=4969.5,4973.9
XS Rating Curve= 0 ,0
Exp/Cntr=0.3,0.1

Type RM Length L Ch R = 1 ,9050    ,465,465,465
BEGIN DESCRIPTION:
Stream0675 20.0
END DESCRIPTION:
XS GIS Cut Line= 3
      1925175.02     13865324.98        1925575.       13864925.
      1925725.03     13864724.96
#Sta/Elev= 30
  4434.3 1837.39  4437.8 1837.39  4462.6 1828.71    4505 1809.29  4561.5 1785.27
  4589.8 1772.38    4604 1767.78  4628.1 1761.59  4674.7 1749.69  4717.1  1736.1
  4731.3 1732.92  4745.4 1730.71  4816.1 1724.33  4858.5 1721.89  4872.7  1721.7
  4886.8 1719.65    4901 1718.91  4957.5 1719.32  4971.7 1718.81  4985.8 1716.81
  4994.1 1714.63  4994.4 1714.13  4998.8 1714.63  5013.5 1715.15  5035.3 1719.27
  5057.2 1723.76  5063.5 1723.19  5103.7 1725.74  5155.4 1727.89    5250 1731.14
#Mann= 7 ,-1 , 0
  4434.3     .07       0  4628.1      .1       0  4994.1    .035       0
  4998.8      .1       0  5035.3     .07       0  5103.7      .1       0
  5155.4     .07       0
Bank Sta=4994.1,4998.8
XS Rating Curve= 0 ,0
Exp/Cntr=0.3,0.1

Type RM Length L Ch R = 1 ,8585    ,212,212,212
BEGIN DESCRIPTION:
Stream0675 19.0
END DESCRIPTION:
XS GIS Cut Line= 3
      1925425.01     13865524.99        1925825.       13865275.
      1926170.13     13864783.33
#Sta/Elev= 30
  4524.8 1796.62  4553.7 1790.06  4583.8 1778.92  4590.2 1773.64  4605.6 1768.78
  4611.5 1769.47  4626.8 1762.06  4632.7 1761.95    4648 1757.09  4654.5 1752.92
  4669.2 1750.49  4684.6 1743.64  4721.1 1733.38  4742.4  1730.1  4815.5 1722.51
  4915.7 1719.48  4946.4 1716.51  4967.6 1711.79  5120.7 1711.79  5138.4 1711.67
  5138.7 1711.17  5143.1 1711.67  5191.3 1720.47  5247.9 1726.41  5298.5 1730.11
  5358.3 1731.34  5426.6 1735.03  5477.1 1743.49  5580.9 1753.81  5597.2 1756.46
#Mann= 6 ,-1 , 0
  4524.8    .035       0  5120.7      .1       0  5138.4    .035       0
  5143.1      .1       0  5358.3    .035       0  5580.9     .07       0
Bank Sta=5138.4,5143.1
XS Rating Curve= 0 ,0
Exp/Cntr=0.3,0.1

Type RM Length L Ch R = 1 ,8373    ,195,195,195
BEGIN DESCRIPTION:
Stream0675 D2
END DESCRIPTION:
XS GIS Cut Line= 4
      1925728.53     13865525.21       1925889.1     13865397.18
      1926041.01     13865258.29      1926203.41     13865039.59
#Sta/Elev= 30
    4647  1724.2  4680.9 1721.75  4765.8 1718.64  4872.5 1721.78  4879.3 1720.78
  4886.7 1721.66  4893.4 1720.59  4900.8 1721.46  4907.6 1720.13  4914.6  1721.4
  5063.4 1721.27  5085.5  1720.7  5127.4 1718.31  5147.1 1717.67  5147.5 1717.17
  5151.5 1717.17  5151.8 1717.67  5190.9 1719.52  5221.1 1722.17  5235.7 1723.93
  5241.5  1725.6  5256.6 1728.66  5262.8 1731.56  5271.2 1732.87  5277.4  1735.4
  5285.8 1736.58    5292 1739.22  5312.9 1743.73  5321.3 1744.66  5330.6 1746.79
#Mann= 6 ,-1 , 0
    4647    .035       0  5127.4    .035       0  5147.1    .035       0
  5151.8    .035       0  5190.9     .07       0  5241.5      .1       0
Bank Sta=5147.1,5151.8
XS Rating Curve= 0 ,0
Exp/Cntr=0.3,0.1

Type RM Length L Ch R = 1 ,8178    ,399,399,399
BEGIN DESCRIPTION:
Stream0675 18.0
END DESCRIPTION:
XS GIS Cut Line= 3
      1925924.99       13865525.        1926125.       13865425.
      1926425.02     13865124.98
#Sta/Elev= 30
  4771.8 1717.37  4785.8 1716.86  4802.6 1714.21  4824.9 1713.01  4861.3 1714.35
  4914.4 1710.29  4981.4  1707.1  4992.6  1705.6  4998.9  1705.6  5007.1 1700.57
  5007.4 1700.07  5012.1 1700.57  5023.7 1702.89  5037.8 1706.88    5052 1705.44
  5066.1  1702.8  5080.3 1707.55  5119.5 1711.71  5157.1 1714.15  5179.3 1714.63
  5207.5 1718.85  5235.8 1725.37  5263.5 1733.54  5278.3 1739.93  5306.5 1753.87
    5349 1770.69  5364.3 1775.73  5391.4 1783.54  5416.1 1788.05  5419.7 1788.05
#Mann= 7 ,-1 , 0
  4771.8    .035       0  5007.1    .035       0  5012.1    .035       0
  5119.5      .1       0  5157.1    .035       0  5263.5     .07       0
  5364.3      .1       0
Bank Sta=5007.1,5012.1
XS Rating Curve= 0 ,0
Exp/Cntr=0.3,0.1

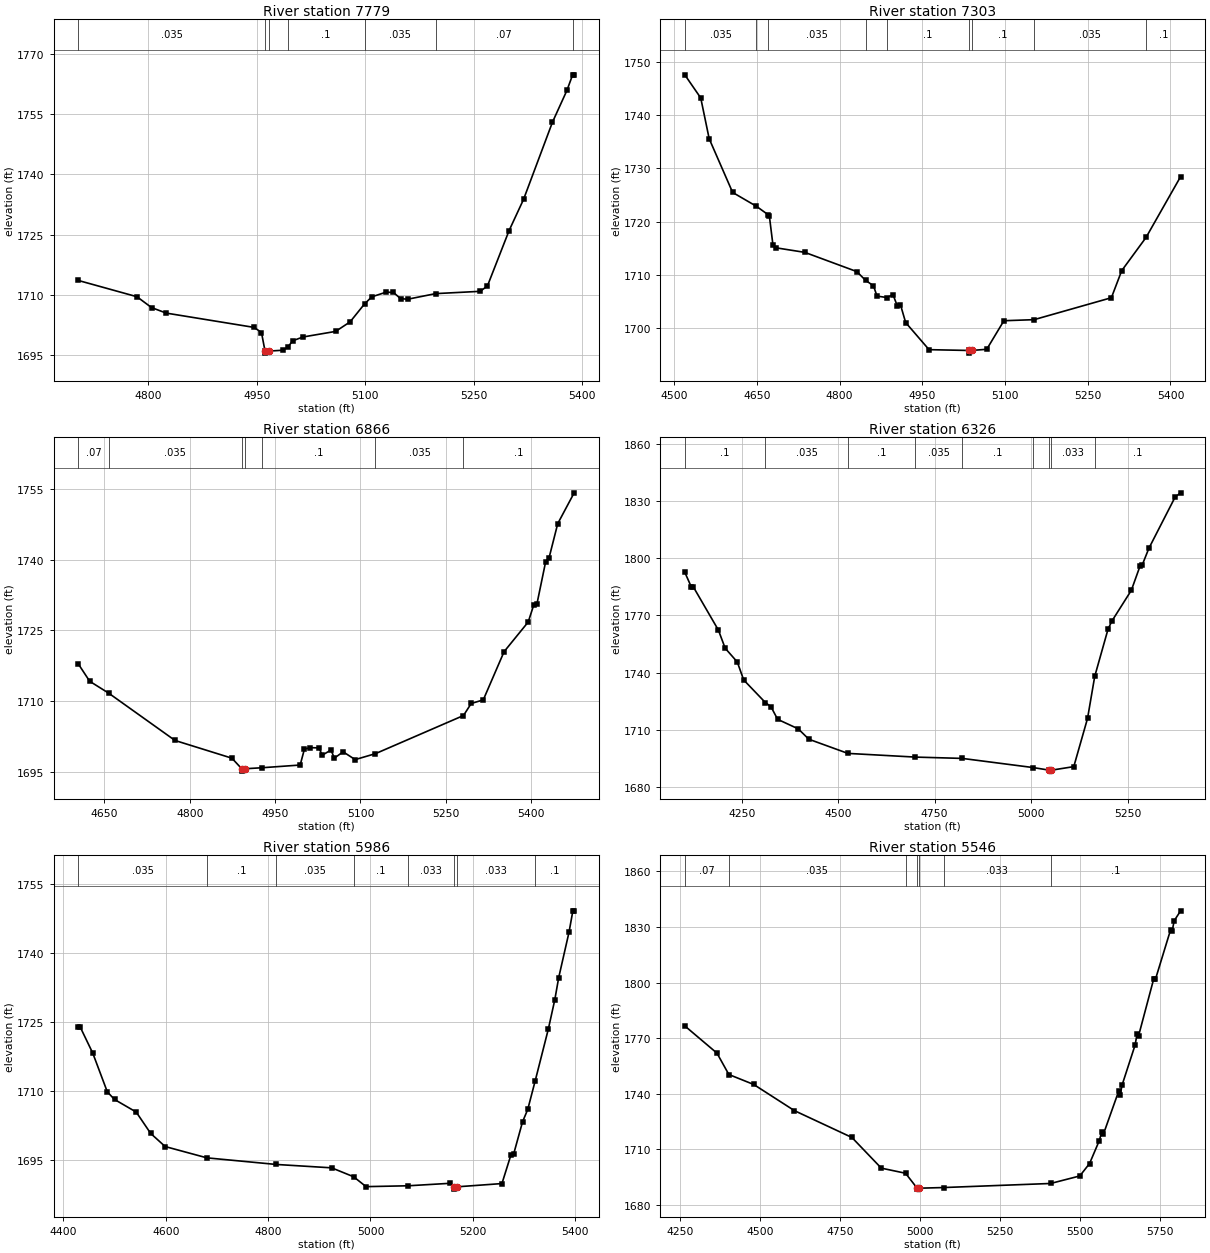
Type RM Length L Ch R = 1 ,7779    ,476,476,476
BEGIN DESCRIPTION:
Stream0675 17.0
END DESCRIPTION:
XS GIS Cut Line= 4
      1926175.04     13865674.99      1926434.96     13865631.67
        1926475.     13865588.85        1926475.     13865224.98
#Sta/Elev= 30
    4703 1713.63  4784.1 1709.59  4804.3 1706.89  4824.6 1705.52  4946.3 1701.96
  4956.4 1700.69  4961.3 1696.07  4961.7 1695.57  4966.6 1696.07  4985.5 1696.29
  4992.6 1697.01  4999.7 1698.65  5013.8 1699.58    5059 1700.97    5079 1703.34
    5099  1707.8    5109 1709.56    5129 1710.73    5139 1710.65    5149 1709.09
    5159 1708.98  5197.4 1710.36    5259 1710.93    5269 1712.26    5299 1726.04
    5319 1733.79    5359 1752.98    5379 1760.87  5386.9 1764.74    5389 1764.74
#Mann= 7 ,-1 , 0
    4703    .035       0  4961.3     .05       0  4966.6    .035       0
  4992.6      .1       0    5099    .035       0  5197.4     .07       0
  5386.9      .1       0
Bank Sta=4961.3,4966.6
XS Rating Curve= 0 ,0
Exp/Cntr=0.3,0.1

Type RM Length L Ch R = 1 ,7303    ,437,437,437
BEGIN DESCRIPTION:
Stream0675 16.0
END DESCRIPTION:
XS GIS Cut Line= 3
      1926074.98     13866275.01        1926475.       13866025.
      1926874.98     13865875.01
#Sta/Elev= 30
  4519.5 1747.56  4548.4 1743.22  4563.7 1735.57  4606.2 1725.49  4649.3 1722.89
  4670.4 1721.32  4672.8 1721.06  4679.3 1715.63  4685.2 1715.09  4737.1 1714.24
  4831.4 1710.63  4847.1    1709  4861.5 1707.97    4868 1706.03  4886.4 1705.76
  4896.9 1706.33  4904.5 1704.25  4910.4 1704.45  4919.9 1701.07  4962.3 1695.98
    5034 1695.83  5034.4 1695.33  5039.3 1695.83  5066.9 1696.05    5098 1701.41
  5152.7 1701.61  5292.9 1705.73  5311.6 1710.81  5355.7 1717.04  5418.4 1728.46
#Mann= 9 ,-1 , 0
  4519.5    .035       0  4649.3     .07       0  4670.4    .035       0
  4847.1     .07       0  4886.4      .1       0    5034     .05       0
  5039.3      .1       0  5152.7    .035       0  5355.7      .1       0
Bank Sta=5034,5039.3
XS Rating Curve= 0 ,0
Exp/Cntr=0.3,0.1

Type RM Length L Ch R = 1 ,6866    ,540,540,540
BEGIN DESCRIPTION:
Stream0675 15.0
END DESCRIPTION:
XS GIS Cut Line= 3
      1926224.99       13866375.        1926625.       13866375.
      1927024.99       13866125.
#Sta/Elev= 30
    4604 1717.89    4624 1714.22  4657.2 1711.72    4774 1701.69    4874 1697.94
  4891.3  1695.7  4891.8  1695.2  4896.7  1695.7  4927.3 1695.92    4994 1696.49
  5001.5 1699.87  5011.7 1700.17    5027 1700.12  5032.9 1698.58  5048.2 1699.67
  5054.1 1697.95  5069.5 1699.29  5090.7 1697.64  5126.4  1698.9  5281.1 1706.97
  5294.7 1709.52  5315.9 1710.28  5352.5 1720.49  5394.9 1726.77  5404.4 1730.28
  5410.3 1730.62  5425.6 1739.54  5431.5 1740.32  5446.8 1747.59  5475.7 1754.12
#Mann= 7 ,-1 , 0
    4604     .07       0  4657.2    .035       0  4891.3     .05       0
  4896.7    .035       0  4927.3      .1       0  5126.4    .035       0
  5281.1      .1       0
Bank Sta=4891.3,4896.7
XS Rating Curve= 0 ,0
Exp/Cntr=0.3,0.1

Type RM Length L Ch R = 1 ,6326    ,340,340,340
BEGIN DESCRIPTION:
Stream0675 14.0
END DESCRIPTION:
XS GIS Cut Line= 3
      1925974.99       13866475.      1926691.77     13866694.86
      1927175.02     13866925.01
#Sta/Elev= 30
  4102.4 1792.69  4118.8 1785.22    4124 1785.19  4189.5 1762.32    4207 1752.82
  4238.4 1745.59    4255 1736.16  4311.1 1724.31  4325.7 1722.08    4343 1715.47
  4396.4 1710.47  4423.9 1705.02  4525.1 1697.58  4699.9 1695.64  4821.5 1694.95
  5005.2 1690.14  5047.2 1688.77  5047.6 1688.27  5052.6 1688.77  5110.5 1690.63
  5146.2    1716  5164.8 1738.04  5199.1 1762.69  5208.8 1766.92  5259.7 1783.24
  5282.4 1796.08    5288 1796.58  5305.1 1805.28  5373.3 1832.25  5387.4 1834.42
#Mann= 9 ,-1 , 0
  4102.4      .1       0  4311.1    .035       0  4525.1      .1       0
  4699.9    .035       0  4821.5      .1       0  5005.2    .033       0
  5047.2     .05       0  5052.6    .033       0  5164.8      .1       0
Bank Sta=5047.2,5052.6
XS Rating Curve= 0 ,0
Exp/Cntr=0.3,0.1

Type RM Length L Ch R = 1 ,5986    ,440,440,440
BEGIN DESCRIPTION:
Stream0675 13.0
END DESCRIPTION:
XS GIS Cut Line= 3
      1926174.99     13866574.99        1926575.       13866975.
      1926974.99       13866925.
#Sta/Elev= 30
  4429.2 1723.91  4432.7 1723.91  4457.5 1718.17  4485.8 1709.78  4499.9 1708.12
  4542.3 1705.38  4570.6 1700.73  4598.9 1697.88  4680.5 1695.42  4815.5 1693.99
  4924.2 1693.25  4967.1 1691.31  4991.4 1689.16  5074.1 1689.35  5156.1 1689.89
  5163.5 1689.12  5163.9 1688.62  5168.9 1689.12  5256.9 1689.83  5274.6 1696.11
  5279.6 1696.18  5297.2 1703.28  5307.3 1705.95    5322 1712.23  5347.6 1723.46
  5360.2 1729.83  5367.8 1734.63  5387.9 1744.47  5395.5 1749.15    5398 1749.15
#Mann= 8 ,-1 , 0
  4429.2    .035       0  4680.5      .1       0  4815.5    .035       0
  4967.1      .1       0  5074.1    .033       0  5163.5     .05       0
  5168.9    .033       0    5322      .1       0
Bank Sta=5163.5,5168.9
XS Rating Curve= 0 ,0
Exp/Cntr=0.3,0.1

Type RM Length L Ch R = 1 ,5546    ,299,299,299
BEGIN DESCRIPTION:
Stream0675 12.0
END DESCRIPTION:
XS GIS Cut Line= 3
      1925780.99     13867711.07        1926375.       13867275.
      1927174.97     13867125.01
#Sta/Elev= 30
  4263.7 1776.57  4364.3 1761.88  4401.5 1750.34  4479.3 1744.96  4606.7 1730.83
  4786.4 1716.36  4878.3 1699.81  4954.1 1697.05  4990.4 1688.98  4990.8 1688.48
  4996.2 1688.98  5073.9 1689.34  5407.8 1691.53  5499.1 1695.59  5529.7  1702.3
  5560.2  1714.7  5567.8 1719.46  5572.9 1718.08  5620.4 1741.18  5625.5 1739.42
  5631.4 1744.65  5672.1 1766.25    5678 1772.06  5683.1 1771.32  5730.6 1802.13
  5735.7 1801.71  5783.2  1828.5  5788.3 1827.92  5794.2 1833.29  5814.5 1838.69
#Mann= 7 ,-1 , 0
  4263.7     .07       0  4401.5    .035       0  4954.1      .1       0
  4990.4     .05       0  4996.2      .1       0  5073.9    .033       0
  5407.8      .1       0
Bank Sta=4990.4,4996.2
XS Rating Curve= 0 ,0
Exp/Cntr=0.3,0.1

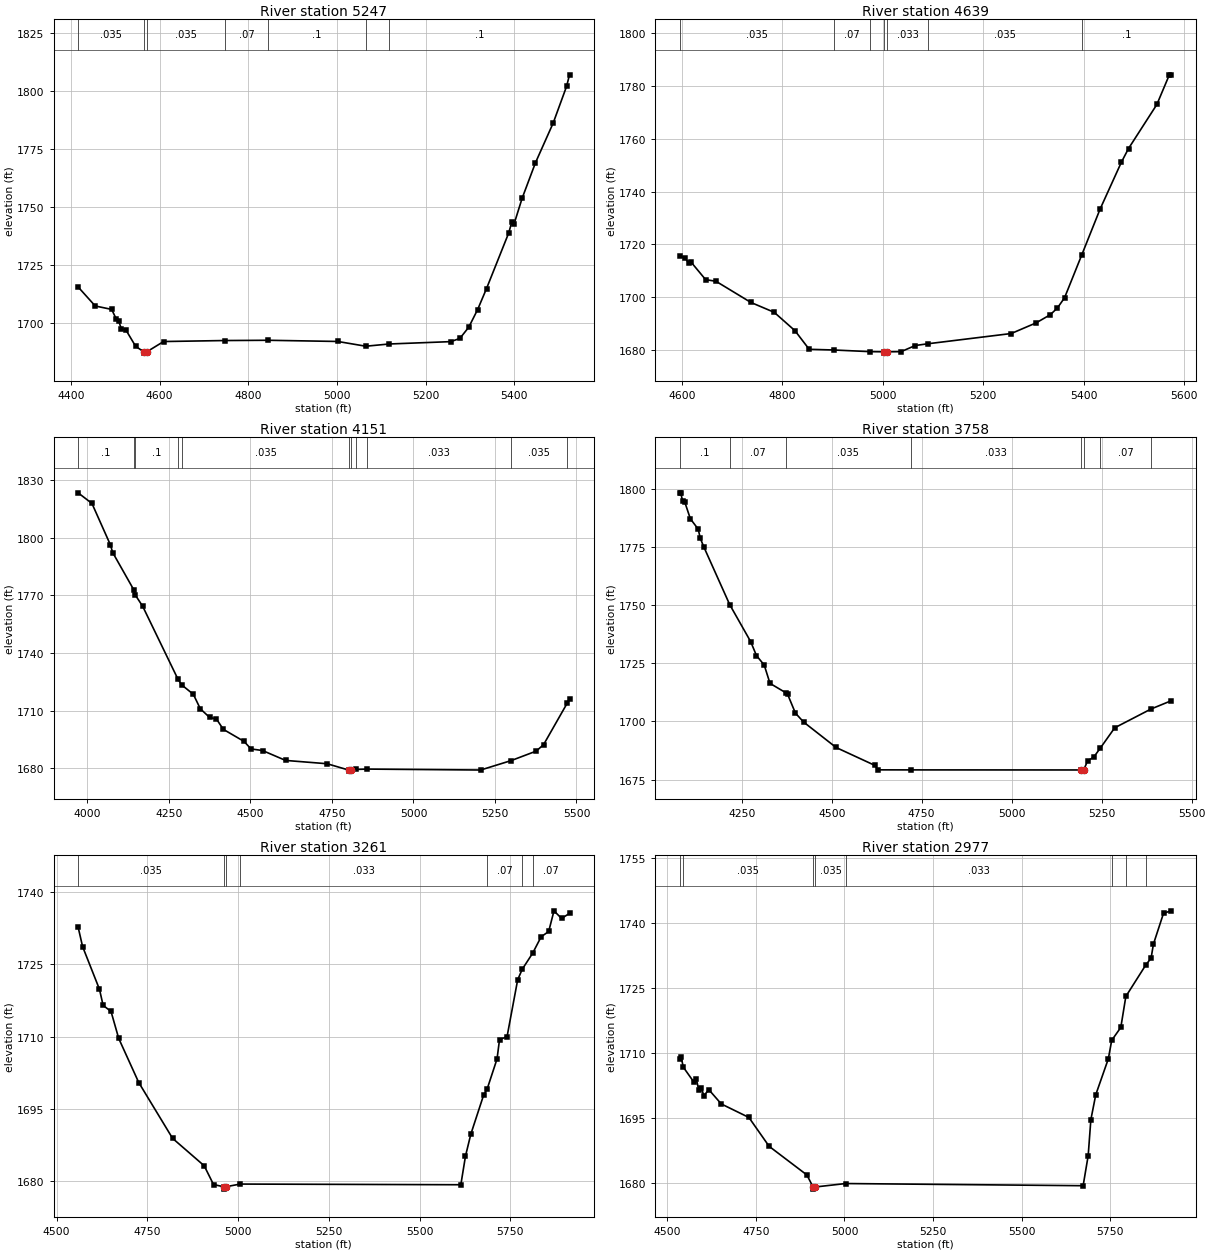
Type RM Length L Ch R = 1 ,5247    ,608,608,608
BEGIN DESCRIPTION:
Stream0675 11.0
END DESCRIPTION:
XS GIS Cut Line= 6
      1926275.02     13867674.99      1926622.66     13867554.08
      1926646.53     13867497.66       1926648.7     13867320.79
      1926721.39      13867228.8      1927101.66     13867200.47
#Sta/Elev= 30
  4416.3 1715.61  4454.9 1707.42    4492 1705.95  4502.7 1701.66  4508.1 1700.79
  4513.7 1697.64  4524.5 1696.97  4546.1 1690.06  4564.9 1687.63  4565.3 1687.13
  4570.7 1687.63  4609.1 1692.12  4747.1 1692.55  4844.9 1692.66    5002 1692.15
  5065.2  1690.1  5117.8 1691.06  5257.2 1692.08  5277.5 1693.47  5297.5 1698.28
  5317.6  1705.9  5337.6 1714.92  5387.8 1738.92  5394.7 1743.63  5399.7 1742.69
  5417.8 1753.71  5447.9 1769.02    5488 1786.17  5518.1 1801.89  5524.8  1806.9
#Mann= 7 ,-1 , 0
  4416.3    .035       0  4564.9     .05       0  4570.7    .035       0
  4747.1     .07       0  4844.9      .1       0  5065.2    .035       0
  5117.8      .1       0
Bank Sta=4564.9,4570.7
XS Rating Curve= 0 ,0
Exp/Cntr=0.3,0.1

Type RM Length L Ch R = 1 ,4639    ,488,488,488
BEGIN DESCRIPTION:
Stream0675 10.0
END DESCRIPTION:
XS GIS Cut Line= 3
      1926324.99       13867975.        1926725.       13867875.
      1927124.99     13867475.01
#Sta/Elev= 30
  4595.8  1715.4  4606.1 1714.96  4613.9 1712.82    4619 1713.11  4647.4  1706.6
    4668 1705.98  4737.5 1697.96  4783.9 1694.22  4825.2 1687.25  4853.5  1680.2
  4903.7 1679.93  4974.6 1679.31  5002.6 1679.25  5003.1 1678.75  5008.5 1679.25
  5036.4 1679.31  5064.7 1681.64  5090.2 1682.31  5255.6 1686.18  5305.1 1690.21
  5333.4 1693.32  5347.5 1695.86  5361.7 1699.72  5395.6  1715.8  5432.4 1733.32
  5474.8  1751.1    5489 1756.29  5545.5 1773.01  5570.3 1784.23  5573.8 1784.23
#Mann= 7 ,-1 , 0
  4595.8    .035       0  4903.7     .07       0  4974.6    .033       0
  5002.6    .033       0  5008.5    .033       0  5090.2    .035       0
  5395.6      .1       0
Bank Sta=5002.6,5008.5
XS Rating Curve= 0 ,0
Exp/Cntr=0.3,0.1

Type RM Length L Ch R = 1 ,4151    ,393,393,393
BEGIN DESCRIPTION:
Stream0675 9.0
END DESCRIPTION:
XS GIS Cut Line= 3
        1926175.       13868875.      1926872.98     13868193.13
      1927124.99     13867725.02
#Sta/Elev= 30
  3971.3 1823.32  4013.7 1817.81  4070.2  1796.3  4077.4 1792.24  4141.6 1772.98
  4147.3 1769.98  4169.2 1764.33  4277.9 1726.22  4289.5  1723.3  4324.8 1718.46
  4346.1 1710.95  4374.4 1706.46  4395.6  1705.6  4416.9 1700.21  4480.4 1693.93
  4501.7 1690.03    4537  1689.2  4607.7 1684.05    4735 1682.33  4802.4 1678.98
  4802.9 1678.48  4809.1 1678.98  4823.4 1679.37  4858.3 1679.54  5206.2 1679.06
  5300.3    1684  5376.5  1688.9  5399.2 1692.27  5472.1 1713.98  5478.7 1716.16
#Mann= 11 ,-1 , 0
  3971.3      .1       0  4141.6     .07       0  4147.3      .1       0
  4277.9     .07       0  4289.5    .035       0  4802.4    .033       0
  4809.1    .035       0  4823.4     .07       0  4858.3    .033       0
  5300.3    .035       0  5472.1     .07       0
Bank Sta=4802.4,4809.1
XS Rating Curve= 0 ,0
Exp/Cntr=0.3,0.1

Type RM Length L Ch R = 1 ,3758    ,497,497,497
BEGIN DESCRIPTION:
Stream0675 8.0
END DESCRIPTION:
XS GIS Cut Line= 3
      1926275.03     13868924.98        1927075.       13868475.
      1927475.04     13868274.98
#Sta/Elev= 30
  4077.8 1798.28  4080.6 1798.28  4085.7 1794.85  4091.5 1794.47  4107.4 1787.12
  4129.1 1782.69  4135.1 1778.68    4145 1774.96  4216.7 1750.23    4275 1734.31
    4291 1728.34  4312.6 1724.25  4328.6 1716.39  4371.9 1712.41  4377.7 1711.63
  4399.3 1703.59    4422 1699.76  4512.2 1688.83  4620.5 1681.09  4628.5 1679.22
    4721  1679.2  5193.5 1679.17    5194 1678.67  5200.2 1679.17  5210.9 1683.11
  5227.6 1684.63  5245.9 1688.49  5286.3  1697.3  5387.1 1705.37  5442.9  1708.9
#Mann= 8 ,-1 , 0
  4077.8      .1       0  4216.7     .07       0  4371.9    .035       0
    4721    .033       0  5193.5    .033       0  5200.2    .033       0
  5245.9     .07       0  5387.1    .035       0
Bank Sta=5193.5,5200.2
XS Rating Curve= 0 ,0
Exp/Cntr=0.3,0.1

Type RM Length L Ch R = 1 ,3261    ,284,284,284
BEGIN DESCRIPTION:
Stream0675 7.0
END DESCRIPTION:
XS GIS Cut Line= 3
      1926509.41     13868984.46      1927043.39     13868796.38
      1927675.04     13868324.97
#Sta/Elev= 30
  4559.1 1732.72  4571.4 1728.68    4618 1719.81    4628 1716.49  4649.8 1715.23
    4671 1709.64  4726.2  1700.5  4819.5 1688.93  4906.6 1683.25  4932.3 1679.36
  4959.9 1678.91  4960.4 1678.41  4966.6 1678.91  5005.9 1679.46  5613.9 1679.32
  5626.7 1685.25  5641.3 1689.77  5676.7  1697.9    5686 1699.06  5713.7  1705.4
  5720.5 1709.38  5741.3 1710.02  5770.5 1721.78    5783 1723.96  5811.9 1727.31
  5835.2  1730.7    5856  1731.8  5870.6 1736.08  5891.5  1734.5  5913.4 1735.55
#Mann= 7 ,-1 , 0
  4559.1    .035       0  4959.9    .035       0  4966.6    .035       0
  5005.9    .033       0    5686     .07       0    5783    .035       0
  5811.9     .07       0
Bank Sta=4959.9,4966.6
XS Rating Curve= 0 ,0
Exp/Cntr=0.3,0.1

Type RM Length L Ch R = 1 ,2977    ,712,712,712
BEGIN DESCRIPTION:
Stream0675 6.0
END DESCRIPTION:
XS GIS Cut Line= 3
       1926765.9     13869421.67      1927065.88      13869071.7
      1927675.02     13868374.98
#Sta/Elev= 30
  4535.2 1708.68  4539.4 1709.01  4545.4 1706.76  4574.6 1703.39  4582.3 1703.93
  4588.8 1701.56  4596.5 1702.04  4603.1 1700.17  4617.4 1701.57  4652.5 1698.28
  4730.4 1695.16  4787.5  1688.5    4894 1681.89  4911.4 1679.12  4911.9 1678.62
  4918.2 1679.12  5003.5 1679.91  5673.4 1679.41  5687.6 1686.33  5695.2 1694.65
    5709  1700.4  5744.5  1708.7    5754 1712.96  5779.7 1715.94  5793.9 1723.09
  5850.4 1730.38  5865.1 1731.93  5871.7 1735.16  5900.2 1742.29  5921.6 1742.85
#Mann= 8 ,-1 , 0
  4535.2     .07       0  4545.4    .035       0  4911.4    .035       0
  4918.2    .035       0  5003.5    .033       0    5754     .07       0
  5793.9    .035       0  5850.4     .07       0
Bank Sta=4911.4,4918.2
XS Rating Curve= 0 ,0
Exp/Cntr=0.3,0.1

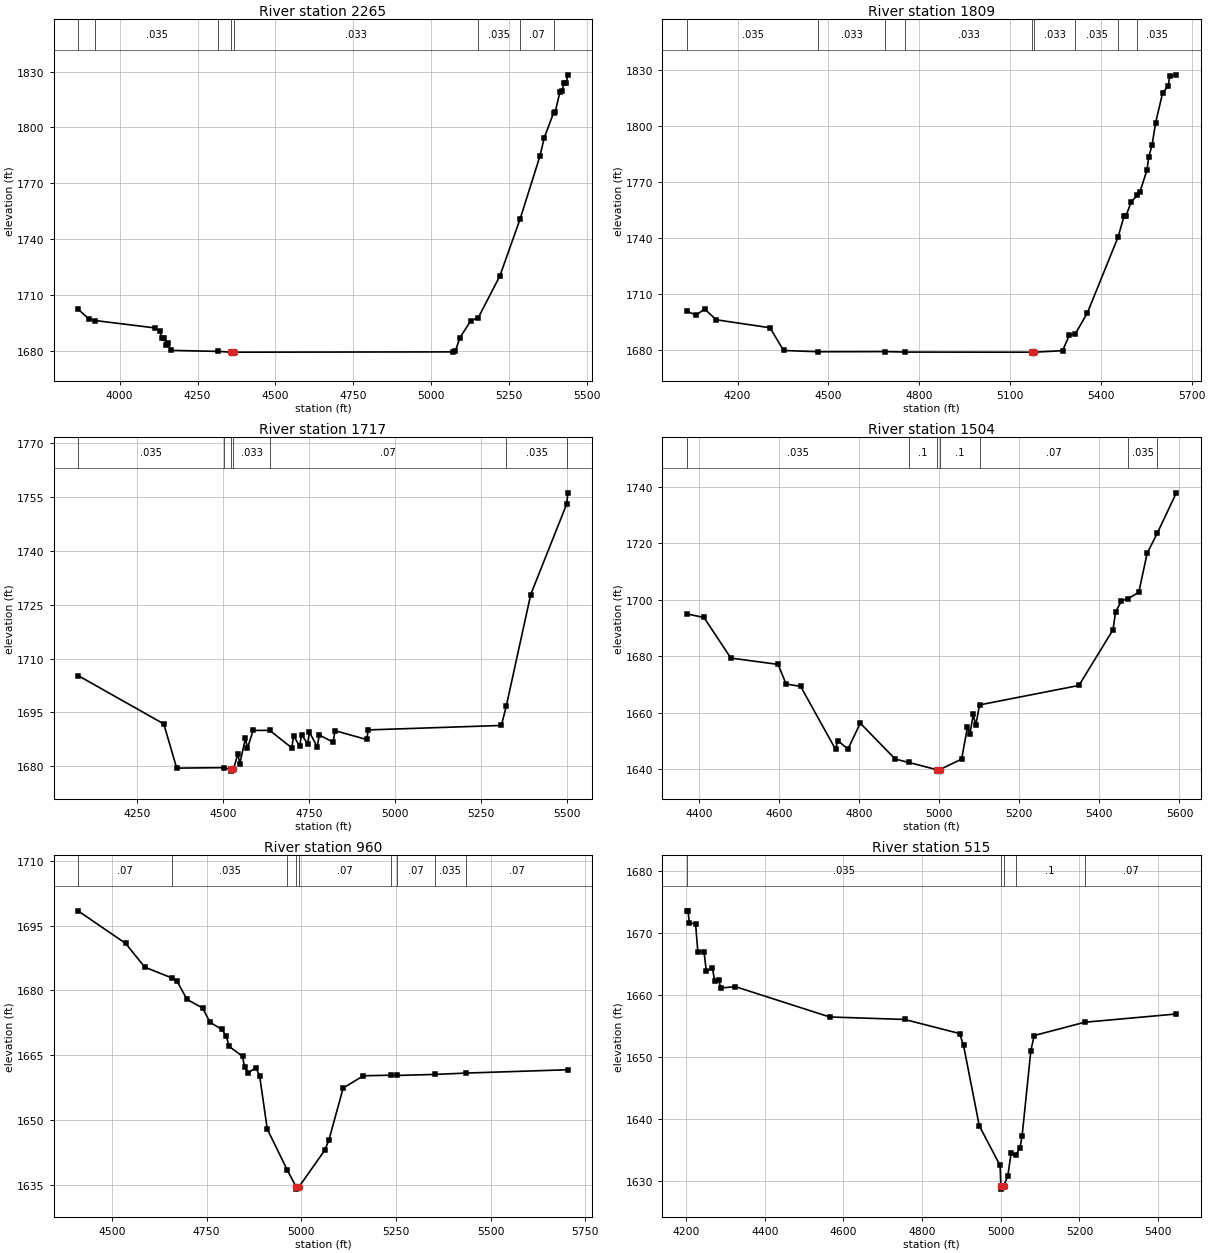
Type RM Length L Ch R = 1 ,2265    ,456,456,456
BEGIN DESCRIPTION:
Stream0675 5.0
END DESCRIPTION:
XS GIS Cut Line= 3
      1926825.02     13869624.98      1927667.23      13868847.1
      1928000.04     13868584.37
#Sta/Elev= 30
  3866.8 1702.32  3902.2 1696.91    3922 1696.16  4114.3 1692.18  4128.5 1690.47
  4135.8 1686.79  4142.6 1687.03    4150 1683.01  4156.8 1683.93  4164.2 1680.13
  4317.1 1679.56  4358.7 1679.14  4359.2 1678.64  4365.5 1679.14  5070.5 1679.31
  5076.8 1679.68  5091.3 1686.82  5126.5 1696.12  5149.9 1697.56  5219.5 1720.09
  5284.4 1750.72  5347.8 1784.42  5362.2  1794.6  5392.3 1808.04  5397.5 1808.56
  5411.9 1818.94  5418.3 1819.72  5426.4 1823.94  5432.7 1823.86  5437.3 1828.32
#Mann= 8 ,-1 , 0
  3866.8     .07       0    3922    .035       0  4317.1    .033       0
  4358.7    .033       0  4365.5    .033       0  5149.9    .035       0
  5284.4     .07       0  5392.3      .1       0
Bank Sta=4358.7,4365.5
XS Rating Curve= 0 ,0
Exp/Cntr=0.3,0.1

Type RM Length L Ch R = 1 ,1809    ,92,92,92
BEGIN DESCRIPTION:
Stream0675 4.0
END DESCRIPTION:
XS GIS Cut Line= 3
      1926811.94     13869713.97      1927675.72     13869274.37
      1928268.13     13869010.31
#Sta/Elev= 30
  4031.6  1701.1  4062.7 1698.83  4091.1 1702.18  4129.5 1696.38  4307.4  1692.1
  4351.9 1679.92  4466.9 1679.25  4687.4 1679.32  4754.2 1679.08  5171.8 1679.01
  5172.3 1678.51  5178.6 1679.01  5273.7 1679.81  5295.6 1688.03  5316.1 1688.93
  5355.6  1700.1  5457.1 1740.79  5477.2 1752.26  5482.7 1751.87  5500.5 1759.66
  5520.2 1763.01  5529.2  1764.9  5552.4 1776.62  5558.4 1783.75  5569.3 1790.05
  5581.1 1802.07  5604.3 1818.05  5622.1 1821.47  5627.6 1826.85  5649.4 1827.67
#Mann= 9 ,-1 , 0
  4031.6    .035       0  4466.9    .033       0  4687.4     .07       0
  4754.2    .033       0  5171.8    .033       0  5178.6    .033       0
  5316.1    .035       0  5457.1     .07       0  5520.2    .035       0
Bank Sta=5171.8,5178.6
XS Rating Curve= 0 ,0
Exp/Cntr=0.3,0.1

Type RM Length L Ch R = 1 ,1717    ,213,213,213
BEGIN DESCRIPTION:
Stream0675 D
END DESCRIPTION:
XS GIS Cut Line= 4
      1926880.58     13869765.99      1927385.79     13869502.97
      1927627.98       13869391.      1928163.08     13869149.42
#Sta/Elev= 30
  4078.3 1705.29  4327.6 1691.79  4365.1 1679.48  4501.5 1679.61  4523.1 1679.14
  4523.6 1678.64  4529.9 1679.14    4543 1683.45  4548.6 1680.69  4565.1 1687.86
  4570.7 1684.97  4587.2 1689.98  4635.4    1690  4699.6 1685.13  4705.1 1688.49
  4722.5 1685.54    4728 1688.84  4745.5 1686.25    4751  1689.5  4773.9 1685.34
  4779.4 1688.73  4819.8 1686.71  4825.3 1689.91    4917 1687.46  4922.5 1690.13
  5308.9 1691.37  5322.9 1696.68  5394.2 1727.87  5499.1 1753.17  5501.8 1756.21
#Mann= 7 ,-1 , 0
  4078.3    .035       0  4501.5    .033       0  4523.1     .05       0
  4529.9    .033       0  4635.4     .07       0  5322.9    .035       0
  5499.1     .07       0
Bank Sta=4523.1,4529.9
XS Rating Curve= 0 ,0
Exp/Cntr=0.3,0.1

Type RM Length L Ch R = 1 ,1504    ,544,544,544
BEGIN DESCRIPTION:
Stream0675 3.0
END DESCRIPTION:
XS GIS Cut Line= 3
      1927130.91      13869775.2      1927725.71     13869563.58
      1928195.56     13869203.96
#Sta/Elev= 30
  4369.1 1695.03  4412.5 1693.75  4479.6 1679.37  4597.5 1677.13  4617.6 1670.18
  4653.9 1669.33  4741.1 1647.03  4746.4 1650.16    4772 1647.11  4802.8 1656.32
    4890 1643.59  4924.2 1642.39    4994 1639.82  4994.5 1639.32  5000.8 1639.82
  5055.9 1643.58  5070.5  1654.9  5076.8 1652.63    5085  1659.4  5091.3  1655.5
  5100.6 1662.78  5348.8 1669.67    5434 1689.39  5440.3 1695.68  5454.9 1699.59
  5471.9 1700.47  5498.4 1702.66  5519.2 1716.49  5544.8 1723.69  5592.1 1737.91
#Mann= 7 ,-1 , 0
  4369.1    .035       0  4924.2      .1       0    4994     .05       0
  5000.8      .1       0  5100.6     .07       0  5471.9    .035       0
  5544.8     .07       0
Bank Sta=4994,5000.8
XS Rating Curve= 0 ,0
Exp/Cntr=0.3,0.1

Type RM Length L Ch R = 1 ,960     ,445,445,445
BEGIN DESCRIPTION:
Stream0675 2.0
END DESCRIPTION:
XS GIS Cut Line= 5
      1927040.97      13870008.8      1927469.73      13870077.3
        1927625.       13870075.      1927794.33     13870036.71
       1928095.2     13869600.74
#Sta/Elev= 30
  4410.6 1698.41  4536.2 1690.87  4586.8 1685.37  4657.5  1682.9  4672.3 1682.08
  4698.2 1677.89  4739.5 1675.92    4759  1672.6  4789.4 1670.99  4801.5 1669.54
  4809.6 1667.01  4844.8 1664.73  4850.1 1662.25  4860.1  1660.9  4880.1 1662.12
  4890.1 1660.13  4910.1 1647.89  4963.4 1638.31  4986.5 1634.47    4987 1633.97
  4993.6 1634.47  5061.6 1642.94  5072.5 1645.23  5110.6 1657.39  5164.1 1660.22
  5236.1 1660.35  5251.9 1660.29  5353.1 1660.53  5433.8 1660.84  5703.4 1661.61
#Mann= 9 ,-1 , 0
  4410.6     .07       0  4657.5    .035       0  4963.4     .07       0
  4986.5     .05       0  4993.6     .07       0  5236.1    .035       0
  5251.9     .07       0  5353.1    .035       0  5433.8     .07       0
Bank Sta=4986.5,4993.6
XS Rating Curve= 0 ,0
Exp/Cntr=0.3,0.1

Type RM Length L Ch R = 1 ,515     ,0,0,0
BEGIN DESCRIPTION:
Stream0675 1.0
END DESCRIPTION:
XS GIS Cut Line= 5
      1927053.64     13870216.42      1927499.61     13870481.24
        1927775.       13870475.        1927875.       13870425.
      1928057.18     13870139.04
#Sta/Elev= 30
  4201.3 1673.58  4204.8 1673.58  4208.5 1671.62  4224.1 1671.49  4229.9 1666.97
  4245.5 1667.01  4251.4  1663.9    4267  1664.3  4272.8 1662.31  4282.6 1662.47
  4288.4 1661.16  4325.4 1661.37    4565 1656.49  4755.4 1656.09  4895.4 1653.82
  4905.4  1651.9  4945.4 1638.96  4998.2 1632.58  5000.3 1629.27  5000.8 1628.77
  5007.4 1629.27  5017.8 1630.88  5026.2 1634.51  5037.9 1634.21  5048.5 1635.36
  5054.1 1637.25  5076.5 1651.07  5084.9  1653.5  5213.3 1655.64  5446.3 1656.97
#Mann= 5 ,-1 , 0
  4201.3    .035       0  5000.3    .035       0  5007.4    .035       0
  5037.9      .1       0  5213.3     .07       0
Bank Sta=5000.3,5007.4
XS Rating Curve= 0 ,0
Exp/Cntr=0.3,0.1

Chan Stop Cuts=-1
Use User Specified Reach Order=0
Composite Channel Slope=5