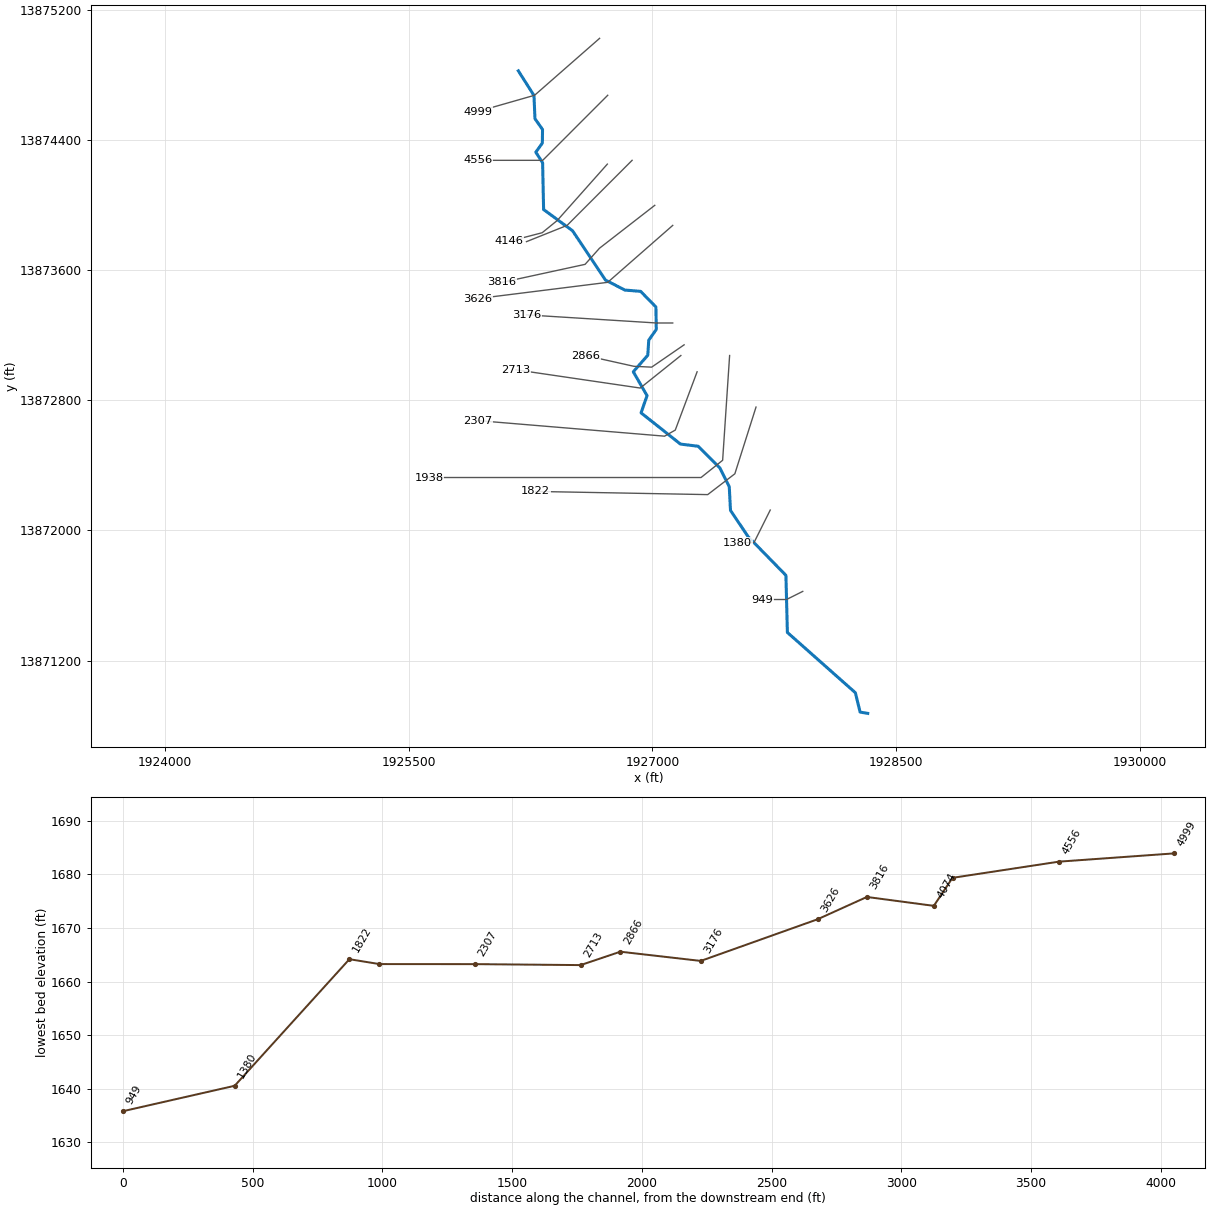
--- Stream0676.prj (project) ---

Proj Title=Stream0676 Base Level Engineering
Current Plan=p01
Default Exp/Contr=0.3,0.1
English Units
Geom File=g01
Flow File=f01
Plan File=p01
BEGIN DESCRIPTION:
Stream0676
END DESCRIPTION:

--- Stream0676.p01 (plan) ---

Plan Title=Multiple Run
Short Identifier=Multiple
Geom File=g01
Flow File=f01
Subcritical Flow
K Sum by GR= 0
Std Step Tol= 0.01
Critical Tol= 0.01
Num of Std Step Trials= 20
Max Error Tol= 0.3
Flow Tol Ratio= 0.001
Split Flow NTrial= 30
Split Flow Tol= 0.02
Split Flow Ratio= 0.02
Log Output Level= 0
Friction Slope Method= 1
Unsteady Friction Slope Method= 2
Unsteady Bridges Friction Slope Method= 1
Parabolic Critical Depth
Global Vel Dist=  1 , 1 , 1
Global Log Level= 0
CheckData=True
Encroach Param= -1, 0, 0, 0
BEGIN DESCRIPTION:
Multiple Run
END DESCRIPTION:

--- Stream0676.f01 (steady flow) ---

Flow Title=Multiple
Number of Profiles=7
Profile Names=10-year,25-year,50-year,1pct_min,100-year,1pct_plu,500-year
River Rch & RM= Stream0676,Reach-1,4999
    1778    3086    4353    2966    5918   11809   10800
Boundary for River Rch & Prof#=Stream0676,Reach-1,1
Up Type=0
Dn Type=3
Dn Slope=0.005
Boundary for River Rch & Prof#=Stream0676,Reach-1,2
Up Type=0
Dn Type=3
Dn Slope=0.005
Boundary for River Rch & Prof#=Stream0676,Reach-1,3
Up Type=0
Dn Type=3
Dn Slope=0.005
Boundary for River Rch & Prof#=Stream0676,Reach-1,4
Up Type=0
Dn Type=3
Dn Slope=0.005
Boundary for River Rch & Prof#=Stream0676,Reach-1,5
Up Type=0
Dn Type=3
Dn Slope=0.005
Boundary for River Rch & Prof#=Stream0676,Reach-1,6
Up Type=0
Dn Type=3
Dn Slope=0.005
Boundary for River Rch & Prof#=Stream0676,Reach-1,7
Up Type=0
Dn Type=3
Dn Slope=0.005

--- Stream0676.g01 (geometry) ---

Geom Title=Existing Conditions

River Reach=Stream0676,Reach-1
Reach XY= 30
      1926175.00     13874825.00      1926271.25     13874673.45
      1926277.27     13874530.94      1926323.89     13874464.45
      1926322.64     13874380.89      1926282.56     13874325.00
      1926324.34     13874259.84      1926330.45     13873972.53
      1926508.50     13873842.05      1926711.43     13873538.47
      1926830.97     13873477.33      1926927.44     13873469.48
      1927021.48     13873373.54      1927023.80     13873235.51
      1926977.36     13873169.02      1926971.36     13873076.50
      1926882.30     13872975.08      1926966.93     13872828.31
      1926930.11     13872722.70      1927172.58     13872530.54
      1927281.17     13872517.14      1927414.24     13872384.68
      1927472.75     13872269.07      1927480.48     13872122.56
      1927588.63     13871961.79      1927821.46     13871723.54
      1927830.46     13871372.55      1928248.82     13871001.86
      1928277.84     13870882.76      1928325.00     13870875.00

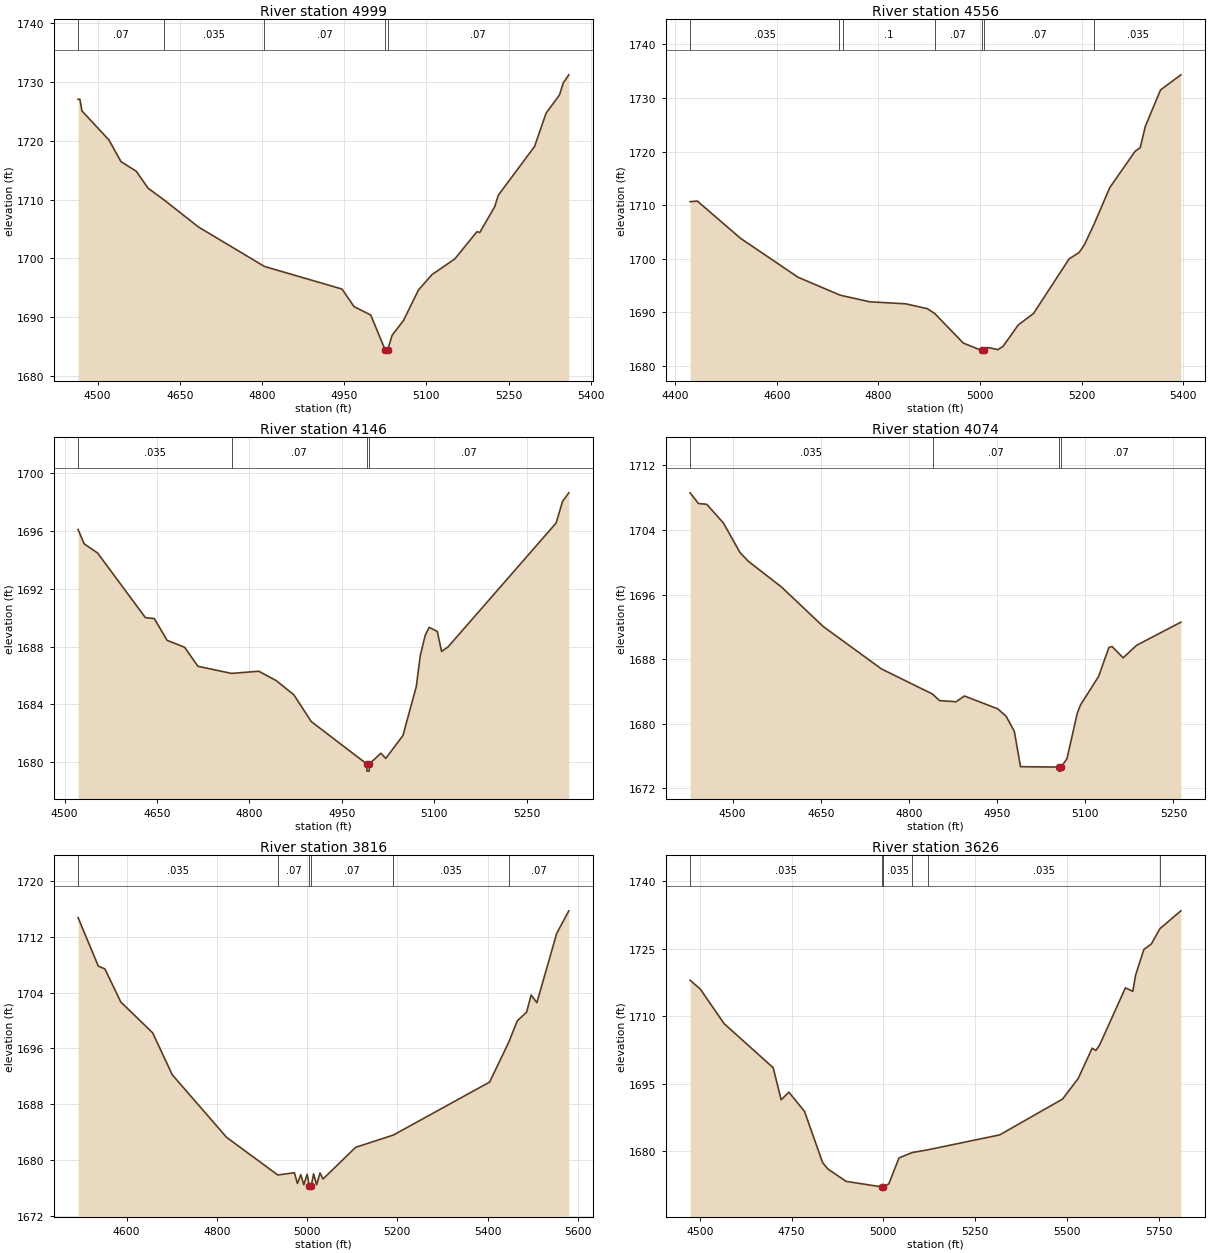
Type RM Length L Ch R = 1,4999,443,443,443
BEGIN DESCRIPTION:
Stream0676 11.0
END DESCRIPTION:
XS GIS Cut Line= 3
      1926674.98     13875024.98      1926275.00     13874675.00
      1925924.99     13874575.00
#Sta/Elev= 30
  4464.4 1727.04  4467.7 1727.04  4471.5 1725.06  4520.8 1720.12  4542.7 1716.45
  4570.7 1714.81  4592.0 1711.95  4620.3 1710.02  4684.1 1705.35  4804.5 1698.65
  4946.1 1694.81  4967.9 1691.84  4998.5 1690.40  5025.0 1684.43  5025.3 1683.93
  5029.2 1684.43  5037.5 1686.97  5058.3 1689.48  5085.6 1694.67  5110.3 1697.27
  5151.9 1699.93  5192.2 1704.55  5197.4 1704.42  5224.7 1708.80  5231.2 1710.74
  5297.5 1719.04  5318.3 1724.66  5343.0 1727.79  5349.5 1729.78  5359.9 1731.19
#Mann=5,-1,0
  4464.4    0.07       0  4620.3   0.035       0  4804.5    0.07       0
  5025.0    0.05       0  5029.2    0.07       0
Bank Sta=5025,5029.2
Exp/Cntr=0.3,0.1

Type RM Length L Ch R = 1,4556,410,410,410
BEGIN DESCRIPTION:
Stream0676 10.0
END DESCRIPTION:
XS GIS Cut Line= 3
      1926725.03     13874675.03      1926325.00     13874275.00
      1925925.03     13874275.00
#Sta/Elev= 30
  4429.5 1710.65  4443.7 1710.77  4528.5 1703.83  4641.7 1696.56  4723.1 1693.27
  4729.4 1693.10  4783.1 1691.97  4853.8 1691.59  4896.2 1690.69  4911.0 1689.77
  4966.9 1684.27  5003.1 1682.89  5003.4 1682.39  5007.1 1682.39  5007.3 1682.89
  5015.2 1683.44  5035.2 1683.04  5045.2 1683.65  5075.2 1687.65  5105.2 1689.78
  5175.2 1699.97  5195.2 1701.20  5205.2 1702.59  5224.4 1706.46  5255.2 1713.27
  5305.2 1720.07  5315.2 1720.74  5325.2 1724.71  5355.2 1731.52  5395.2 1734.33
#Mann=7,-1,0
  4429.5   0.035       0  4723.1    0.07       0  4729.4     0.1       0
  4911.0    0.07       0  5003.1    0.05       0  5007.3    0.07       0
  5224.4   0.035       0
Bank Sta=5003.1,5007.3
Exp/Cntr=0.3,0.1

Type RM Length L Ch R = 1,4146,72,72,72
BEGIN DESCRIPTION:
Stream0676 D2
END DESCRIPTION:
XS GIS Cut Line= 4
      1926722.74     13874251.78      1926413.74     13873904.60
      1926321.73     13873829.94      1926115.09     13873776.11
#Sta/Elev= 30
  4521.9 1696.11  4531.8 1695.12  4553.6 1694.48  4631.3 1690.00  4645.6 1689.94
  4666.5 1688.43  4694.9 1687.95  4716.6 1686.63  4771.1 1686.14  4815.3 1686.29
  4843.7 1685.64  4872.2 1684.66  4900.6 1682.80  4990.6 1679.87  4990.9 1679.37
  4994.6 1679.37  4994.9 1679.87  5013.5 1680.61  5021.5 1680.25  5049.4 1681.84
  5071.0 1685.22  5077.5 1687.36  5085.4 1688.76  5091.9 1689.33  5105.1 1689.05
  5112.1 1687.66  5122.5 1687.97  5298.1 1696.56  5308.5 1698.06  5318.7 1698.65
#Mann=4,-1,0
  4521.9   0.035       0  4771.1    0.07       0  4990.6    0.05       0
  4994.9    0.07       0
Bank Sta=4990.6,4994.9
Exp/Cntr=0.3,0.1

Type RM Length L Ch R = 1,4074,258,258,258
BEGIN DESCRIPTION:
Stream0676 9.0
END DESCRIPTION:
XS GIS Cut Line= 3
      1926875.00     13874275.00      1926475.00     13873875.00
      1926225.03     13873775.01
#Sta/Elev= 30
  4427.8 1708.59  4441.9 1707.27  4456.1 1707.17  4484.4 1704.86  4512.6 1701.20
  4526.8 1700.12  4583.4 1696.92  4654.1 1692.05  4753.1 1686.80  4840.2 1683.68
  4852.1 1682.87  4880.3 1682.73  4894.5 1683.44  4951.1 1681.85  4965.2 1680.95
  4979.3 1679.08  4989.9 1674.69  5054.6 1674.64  5054.9 1674.14  5058.6 1674.14
  5058.9 1674.64  5068.9 1675.67  5086.4 1681.30  5091.8 1682.32  5122.7 1685.86
  5140.2 1689.44  5145.6 1689.57  5164.5 1688.17  5187.3 1689.71  5262.7 1692.58
#Mann=4,-1,0
  4427.8   0.035       0  4840.2    0.07       0  5054.6    0.05       0
  5058.9    0.07       0
Bank Sta=5054.6,5058.9
Exp/Cntr=0.3,0.1

Type RM Length L Ch R = 1,3816,190,190,190
BEGIN DESCRIPTION:
Stream0676 D3
END DESCRIPTION:
XS GIS Cut Line= 4
      1927014.40     13873998.32      1926674.16     13873734.46
      1926585.62     13873635.50      1926073.48     13873524.39
#Sta/Elev= 30
  4492.7 1714.76  4537.6 1707.79  4552.1 1707.40  4587.4 1702.65  4658.0 1698.22
  4701.4 1692.21  4821.8 1683.23  4935.2 1677.83  4972.0 1678.15  4978.7 1676.62
  4986.2 1677.88  4992.9 1676.43  5000.4 1677.94  5004.9 1676.30  5005.2 1675.80
  5009.3 1676.30  5014.6 1677.99  5021.3 1676.42  5028.8 1678.12  5035.5 1677.26
  5107.8 1681.80  5191.4 1683.56  5404.6 1691.16  5446.9 1696.87  5466.0 1699.95
  5486.5 1701.19  5496.7 1703.65  5509.3 1702.55  5553.3 1712.50  5580.1 1715.73
#Mann=6,-1,0
  4492.7   0.035       0  4935.2    0.07       0  5004.9    0.05       0
  5009.3    0.07       0  5191.4   0.035       0  5446.9    0.07       0
Bank Sta=5004.9,5009.3
Exp/Cntr=0.3,0.1

Type RM Length L Ch R = 1,3626,450,450,450
BEGIN DESCRIPTION:
Stream0676 8.0
END DESCRIPTION:
XS GIS Cut Line= 3
      1927124.98     13873874.98      1926725.00     13873525.00
      1925925.01     13873425.00
#Sta/Elev= 30
  4473.3 1717.99  4501.3 1716.00  4565.8 1708.37  4699.6 1698.58  4721.5 1691.45
  4742.4 1693.16  4785.1 1688.88  4834.4 1677.52  4848.7 1676.10  4898.5 1673.35
  4995.5 1672.13  4995.8 1671.63  4999.9 1672.13  5014.9 1672.80  5042.6 1678.55
  5078.6 1679.75  5122.1 1680.37  5317.2 1683.67  5488.5 1691.62  5531.3 1696.22
  5569.1 1702.91  5579.2 1702.40  5589.3 1703.58  5659.8 1716.31  5680.0 1715.52
  5687.6 1719.14  5710.2 1724.84  5730.4 1726.03  5754.0 1729.45  5811.0 1733.40
#Mann=6,-1,0
  4473.3   0.035       0  4995.5   0.035       0  4999.9   0.035       0
  5078.6    0.07       0  5122.1   0.035       0  5754.0    0.07       0
Bank Sta=4995.5,4999.9
Exp/Cntr=0.3,0.1

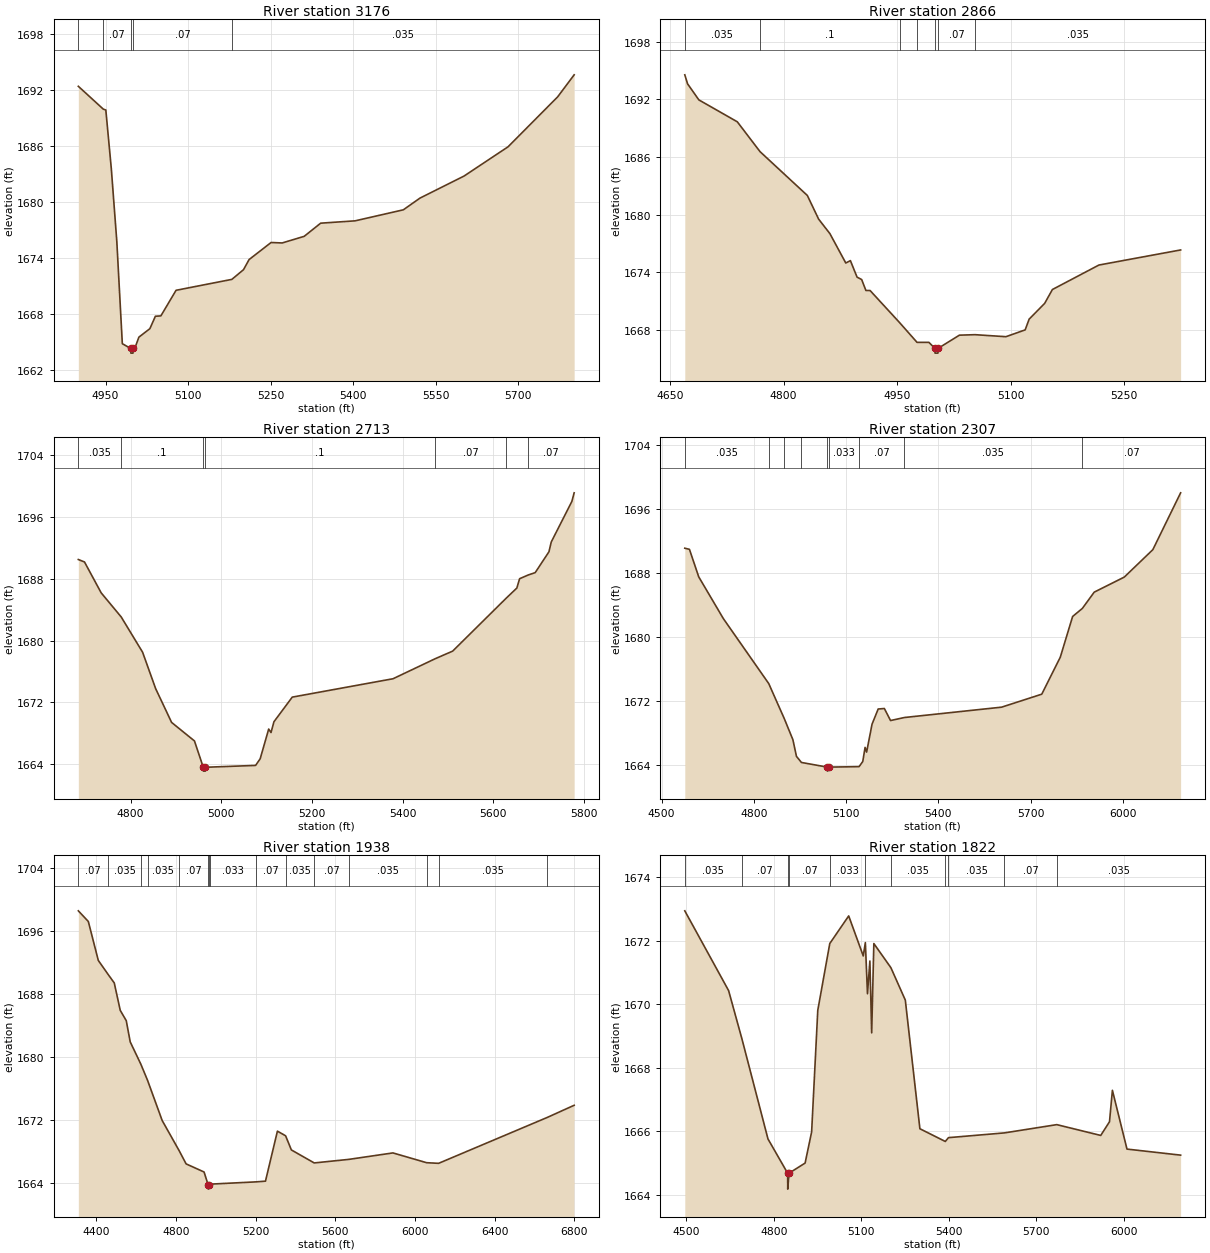
Type RM Length L Ch R = 1,3176,310,310,310
BEGIN DESCRIPTION:
Stream0676 7.0
END DESCRIPTION:
XS GIS Cut Line= 3
      1927125.05     13873275.00      1927025.00     13873275.00
      1926225.01     13873325.00
#Sta/Elev= 30
  4900.4 1692.44  4945.7 1690.00  4950.4 1689.90  4960.4 1683.61  4970.4 1675.80
  4980.4 1664.87  4995.7 1664.36  4996.0 1663.86  4999.8 1663.86  5000.1 1664.36
  5003.0 1664.36  5010.5 1665.57  5030.5 1666.48  5040.5 1667.81  5050.5 1667.85
  5078.1 1670.59  5179.6 1671.76  5200.8 1672.80  5210.9 1673.88  5250.9 1675.71
  5271.0 1675.66  5311.1 1676.37  5341.1 1677.78  5403.7 1678.03  5491.4 1679.21
  5521.5 1680.46  5601.6 1682.82  5681.8 1685.96  5772.0 1691.31  5802.0 1693.67
#Mann=5,-1,0
  4900.4     0.1       0  4945.7    0.07       0  4995.7    0.05       0
  5000.1    0.07       0  5179.6   0.035       0
Bank Sta=4995.7,5000.1
Exp/Cntr=0.3,0.1

Type RM Length L Ch R = 1,2866,153,153,153
BEGIN DESCRIPTION:
Stream0676 D4
END DESCRIPTION:
XS GIS Cut Line= 4
      1927195.03     13873140.73      1926995.34     13873003.55
      1926885.96     13873008.76      1926589.57     13873074.63
#Sta/Elev= 30
  4669.3 1694.55  4673.0 1693.61  4687.9 1691.94  4738.7 1689.66  4768.8 1686.55
  4831.3 1681.99  4846.2 1679.53  4861.1 1678.02  4882.1 1674.96  4888.2 1675.21
  4897.0 1673.49  4903.1 1673.24  4908.7 1672.10  4914.2 1672.10  4953.3 1668.75
  4976.3 1666.70  4992.0 1666.70  4999.8 1666.08  5000.1 1665.58  5003.9 1665.58
  5004.2 1666.08  5032.3 1667.45  5053.0 1667.50  5093.8 1667.29  5119.2 1668.00
  5124.5 1669.12  5145.0 1670.76  5155.2 1672.20  5216.7 1674.75  5324.7 1676.32
#Mann=7,-1,0
  4669.3   0.035       0  4768.8     0.1       0  4953.3   0.035       0
  4976.3    0.07       0  4999.8    0.05       0  5004.2    0.07       0
  5053.0   0.035       0
Bank Sta=4999.8,5004.2
Exp/Cntr=0.3,0.1

Type RM Length L Ch R = 1,2713,406,406,406
BEGIN DESCRIPTION:
Stream0676 6.0
END DESCRIPTION:
XS GIS Cut Line= 3
      1927175.01     13873075.01      1926925.00     13872875.00
      1926159.97     13872987.31
#Sta/Elev= 30
  4684.8 1690.50  4698.4 1690.18  4735.2 1686.18  4779.3 1683.06  4826.5 1678.49
  4855.3 1673.77  4890.5 1669.39  4940.9 1666.99  4960.3 1663.58  4960.7 1663.08
  4964.5 1663.08  4964.8 1663.58  5075.7 1663.82  5085.8 1664.68  5104.6 1668.53
  5109.7 1668.08  5116.2 1669.48  5156.6 1672.67  5378.8 1675.05  5471.6 1677.64
  5510.3 1678.63  5628.7 1685.51  5651.8 1686.80  5657.9 1688.01  5677.1 1688.50
  5692.3 1688.80  5722.6 1691.50  5727.7 1692.77  5773.1 1698.02  5778.2 1699.14
#Mann=7,-1,0
  4684.8   0.035       0  4779.3     0.1       0  4960.3   0.035       0
  4964.8     0.1       0  5471.6    0.07       0  5628.7   0.035       0
  5677.1    0.07       0
Bank Sta=4960.3,4964.8
Exp/Cntr=0.3,0.1

Type RM Length L Ch R = 1,2307,369,369,369
BEGIN DESCRIPTION:
Stream0676 5.0
END DESCRIPTION:
XS GIS Cut Line= 4
      1927275.00     13872974.99      1927140.60     13872616.60
      1927074.76     13872579.19      1925925.03     13872675.00
#Sta/Elev= 30
  4575.6 1691.07  4590.7 1690.93  4621.0 1687.49  4701.1 1682.28  4848.6 1674.18
  4899.2 1669.80  4927.1 1667.18  4938.7 1665.10  4954.9 1664.34  5039.1 1663.76
  5039.4 1663.26  5043.6 1663.76  5142.3 1663.82  5154.3 1664.46  5161.8 1666.22
  5166.8 1665.63  5184.4 1669.11  5204.4 1671.01  5224.5 1671.07  5244.6 1669.57
  5289.8 1669.95  5605.8 1671.24  5736.3 1672.86  5796.5 1677.47  5836.6 1682.55
  5868.3 1683.56  5906.9 1685.59  6004.7 1687.47  6097.5 1690.89  6187.8 1697.98
#Mann=9,-1,0
  4575.6   0.035       0  4848.6    0.07       0  4899.2   0.035       0
  4954.9   0.033       0  5039.1   0.033       0  5043.6   0.033       0
  5142.3    0.07       0  5289.8   0.035       0  5868.3    0.07       0
Bank Sta=5039.1,5043.6
Exp/Cntr=0.3,0.1

Type RM Length L Ch R = 1,1938,116,116,116
BEGIN DESCRIPTION:
Stream0676 4.0
END DESCRIPTION:
XS GIS Cut Line= 4
      1927475.00     13873075.04      1927432.06     13872430.91
      1927299.15     13872325.00      1925624.96     13872325.00
#Sta/Elev= 30
  4310.0 1698.55  4360.2 1697.20  4410.3 1692.26  4460.1 1690.47  4490.4 1689.41
  4520.5 1685.93  4550.6 1684.63  4570.6 1681.93  4623.4 1679.14  4657.8 1677.05
  4731.0 1671.97  4815.7 1668.17  4851.2 1666.47  4941.4 1665.44  4962.3 1663.77
  4962.6 1663.27  4966.8 1663.77  4970.3 1663.90  5202.4 1664.19  5249.7 1664.28
  5309.7 1670.62  5350.8 1670.03  5379.7 1668.24  5494.4 1666.59  5668.0 1667.04
  5889.7 1667.86  6058.8 1666.62  6119.1 1666.54  6665.8 1672.37  6799.7 1673.90
#Mann=15,-1,0
  4310.0    0.07       0  4460.1   0.035       0  4623.4    0.07       0
  4657.8   0.035       0  4815.7    0.07       0  4962.3   0.033       0
  4966.8    0.07       0  4970.3   0.033       0  5202.4    0.07       0
  5350.8   0.035       0  5494.4    0.07       0  5668.0   0.035       0
  6058.8    0.07       0  6119.1   0.035       0  6665.8    0.07       0
Bank Sta=4962.3,4966.8
Exp/Cntr=0.3,0.1

Type RM Length L Ch R = 1,1822,442,442,442
BEGIN DESCRIPTION:
Stream0676 D
END DESCRIPTION:
XS GIS Cut Line= 4
      1927637.49     13872758.13      1927507.27     13872347.95
      1927340.17     13872219.92      1926281.11     13872239.45
#Sta/Elev= 30
  4494.8 1672.94  4645.0 1670.43  4691.0 1668.90  4780.0 1665.76  4847.5 1664.68
  4847.8 1664.18  4852.0 1664.68  4907.3 1665.00  4929.7 1665.98  4950.8 1669.81
  4991.9 1671.91  5056.8 1672.78  5106.7 1671.52  5113.9 1671.94  5121.2 1670.33
  5129.4 1671.36  5135.6 1669.10  5143.0 1671.91  5201.5 1671.15  5250.9 1670.13
  5300.9 1666.08  5388.0 1665.68  5398.8 1665.80  5590.9 1665.95  5770.3 1666.21
  5921.0 1665.87  5951.0 1666.30  5961.0 1667.29  6011.0 1665.44  6194.9 1665.25
#Mann=11,-1,0
  4494.8   0.035       0  4691.0    0.07       0  4847.5   0.033       0
  4852.0    0.07       0  4991.9   0.033       0  5113.9    0.07       0
  5201.5   0.035       0  5388.0    0.07       0  5398.8   0.035       0
  5590.9    0.07       0  5770.3   0.035       0
Bank Sta=4847.5,4852
Exp/Cntr=0.3,0.1

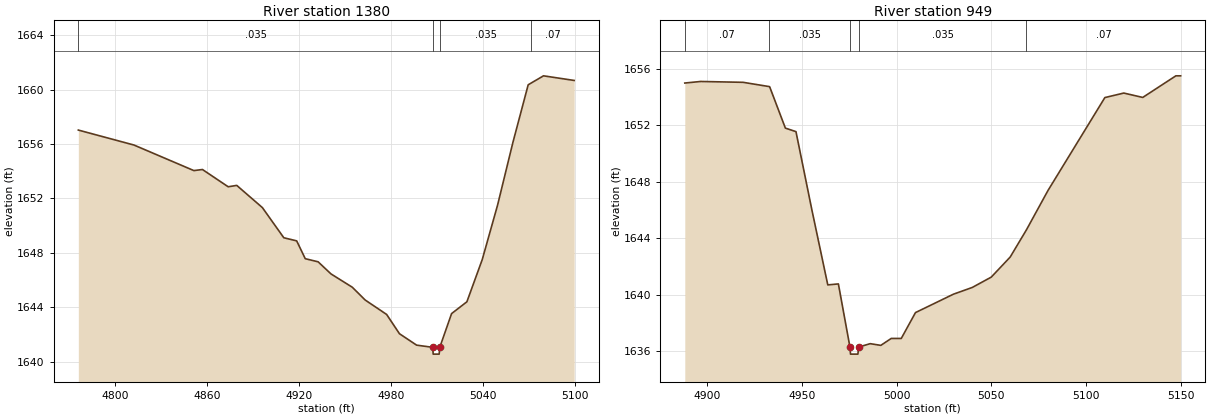
Type RM Length L Ch R = 1,1380,431,431,431
BEGIN DESCRIPTION:
Stream0676 3.0
END DESCRIPTION:
XS GIS Cut Line= 3
      1927724.98     13872124.96      1927625.00     13871925.00
      1927524.96     13871925.00
#Sta/Elev= 30
  4776.1 1657.03  4812.4 1655.93  4851.5 1654.05  4857.1 1654.13  4873.9 1652.86
  4879.5 1652.96  4896.2 1651.33  4910.2 1649.11  4918.6 1648.88  4924.2 1647.57
  4932.6 1647.34  4941.0 1646.45  4954.9 1645.47  4963.3 1644.53  4977.3 1643.47
  4985.7 1642.05  4996.9 1641.21  5007.4 1641.05  5007.7 1640.55  5011.6 1640.55
  5012.0 1641.05  5019.7 1643.53  5029.7 1644.40  5039.7 1647.50  5049.7 1651.50
  5059.7 1656.11  5069.7 1660.36  5071.8 1660.50  5079.7 1661.02  5099.7 1660.68
#Mann=4,-1,0
  4776.1   0.035       0  5007.4   0.035       0  5012.0   0.035       0
  5071.8    0.07       0
Bank Sta=5007.4,5012
Exp/Cntr=0.3,0.1

Type RM Length L Ch R = 1,949,0,0,0
BEGIN DESCRIPTION:
Stream0676 2.0
END DESCRIPTION:
XS GIS Cut Line= 3
      1927925.03     13871625.01      1927825.00     13871575.00
      1927675.04     13871575.00
#Sta/Elev= 30
  4888.2 1654.99  4896.6 1655.10  4919.0 1655.04  4932.7 1654.74  4933.0 1654.73
  4941.3 1651.80  4946.9 1651.55  4955.3 1646.01  4963.7 1640.70  4969.3 1640.77
  4975.4 1636.30  4975.7 1635.80  4979.6 1635.80  4980.0 1636.30  4986.1 1636.54
  4991.7 1636.42  4997.2 1636.91  5002.5 1636.91  5010.0 1638.74  5030.0 1640.04
  5040.0 1640.52  5050.0 1641.25  5060.0 1642.67  5068.6 1644.60  5080.0 1647.39
  5110.0 1653.96  5120.0 1654.28  5130.0 1653.97  5147.5 1655.50  5150.0 1655.50
#Mann=5,-1,0
  4888.2    0.07       0  4932.7   0.035       0  4975.4   0.035       0
  4980.0   0.035       0  5068.6    0.07       0
Bank Sta=4975.4,4980
Exp/Cntr=0.3,0.1

Chan Stop Cuts=-1