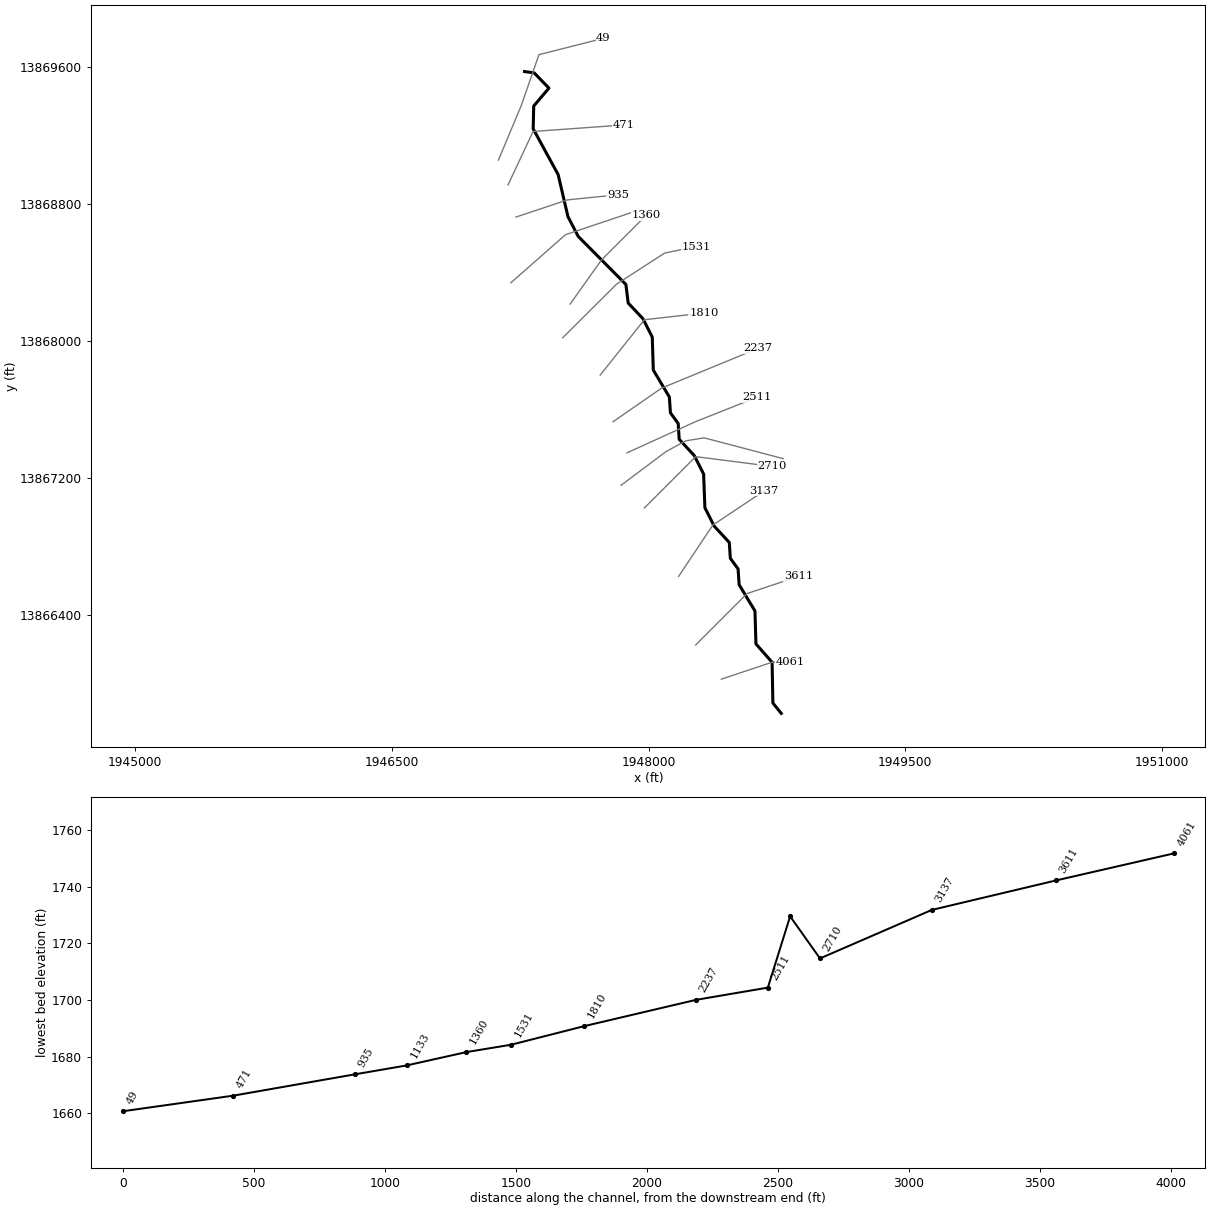
--- Stream0679.prj (project) ---

Proj Title=Stream0679 Base Level Engineering
Current Plan=p01
Default Exp/Contr=0.3,0.1
English Units
Geom File=g01
Flow File=f01
Plan File=p01
Y Axis Title=Elevation
X Axis Title(PF)=Main Channel Distance
X Axis Title(XS)=Station
BEGIN DESCRIPTION:
Stream0679
END DESCRIPTION:
DSS Export Rating Curves= 0
DSS Export Rating Curve Sorted= 0
DSS Export Volume Flow Curves= 0
DXF OffsetX= 0
DXF OffsetY= 0
DXF ScaleX= 1
DXF ScaleY= 10

--- Stream0679.p01 (plan) ---

Plan Title=Multiple Run
Short Identifier=Multiple
Geom File=g01
Flow File=f01
Subcritical Flow
K Sum by GR= 0
Std Step Tol= 0.01
Critical Tol= 0.01
Num of Std Step Trials= 20
Max Error Tol= 0.3
Flow Tol Ratio= 0.001
Split Flow NTrial= 30
Split Flow Tol= 0.02
Split Flow Ratio= 0.02
Log Output Level= 0
Friction Slope Method= 1
Unsteady Friction Slope Method= 2
Unsteady Bridges Friction Slope Method= 1
Parabolic Critical Depth
Global Vel Dist=  1 , 1 , 1
Global Log Level= 0
CheckData=True
Encroach Param= -1, 0, 0, 0
BEGIN DESCRIPTION:
Multiple Run
END DESCRIPTION:

--- Stream0679.f01 (steady flow) ---

Flow Title=Multiple
Number of Profiles=7
Profile Names=10-year,25-year,50-year,1pct_min,100-year,1pct_plu,500-year
River Rch & RM= Stream0679,Reach-1,4061
     625    1028    1401     928    1853    3696    3184
River Rch & RM= Stream0679,Reach-1,3137
    1210    2083    2927    1991    3973    7927    7222
Boundary for River Rch & Prof#=Stream0679,Reach-1,1
Up Type=0
Dn Type=3
Dn Slope=0.005
Boundary for River Rch & Prof#=Stream0679,Reach-1,2
Up Type=0
Dn Type=3
Dn Slope=0.005
Boundary for River Rch & Prof#=Stream0679,Reach-1,3
Up Type=0
Dn Type=3
Dn Slope=0.005
Boundary for River Rch & Prof#=Stream0679,Reach-1,4
Up Type=0
Dn Type=3
Dn Slope=0.005
Boundary for River Rch & Prof#=Stream0679,Reach-1,5
Up Type=0
Dn Type=3
Dn Slope=0.005
Boundary for River Rch & Prof#=Stream0679,Reach-1,6
Up Type=0
Dn Type=3
Dn Slope=0.005
Boundary for River Rch & Prof#=Stream0679,Reach-1,7
Up Type=0
Dn Type=3
Dn Slope=0.005

--- Stream0679.g01 (geometry) ---

Geom Title=Existing Conditions
Program Version=4.10

River Reach=Stream0679      ,Reach-1
Reach XY= 30
        1948775.       13865825.      1948725.96      13865885.4
      1948721.45     13866123.53      1948627.07     13866230.86
      1948621.25     13866423.45      1948528.83     13866576.58
      1948522.65     13866669.03      1948477.36     13866730.98
      1948471.38      13866823.5      1948383.16     13866918.95
      1948328.75     13867026.55      1948321.25     13867223.45
      1948266.84     13867331.05      1948178.62      13867426.5
      1948172.64     13867519.02      1948127.35     13867580.97
      1948121.17     13867673.42      1948027.24     13867830.93
      1948021.25     13868023.45      1947966.84     13868131.05
      1947880.54     13868222.58      1947867.14     13868331.17
      1947588.62     13868611.78      1947528.82     13868726.58
      1947471.17     13868973.42      1947325.49     13869240.22
      1947328.55     13869373.53      1947417.43     13869478.35
      1947331.27     13869567.24        1947275.       13869575.

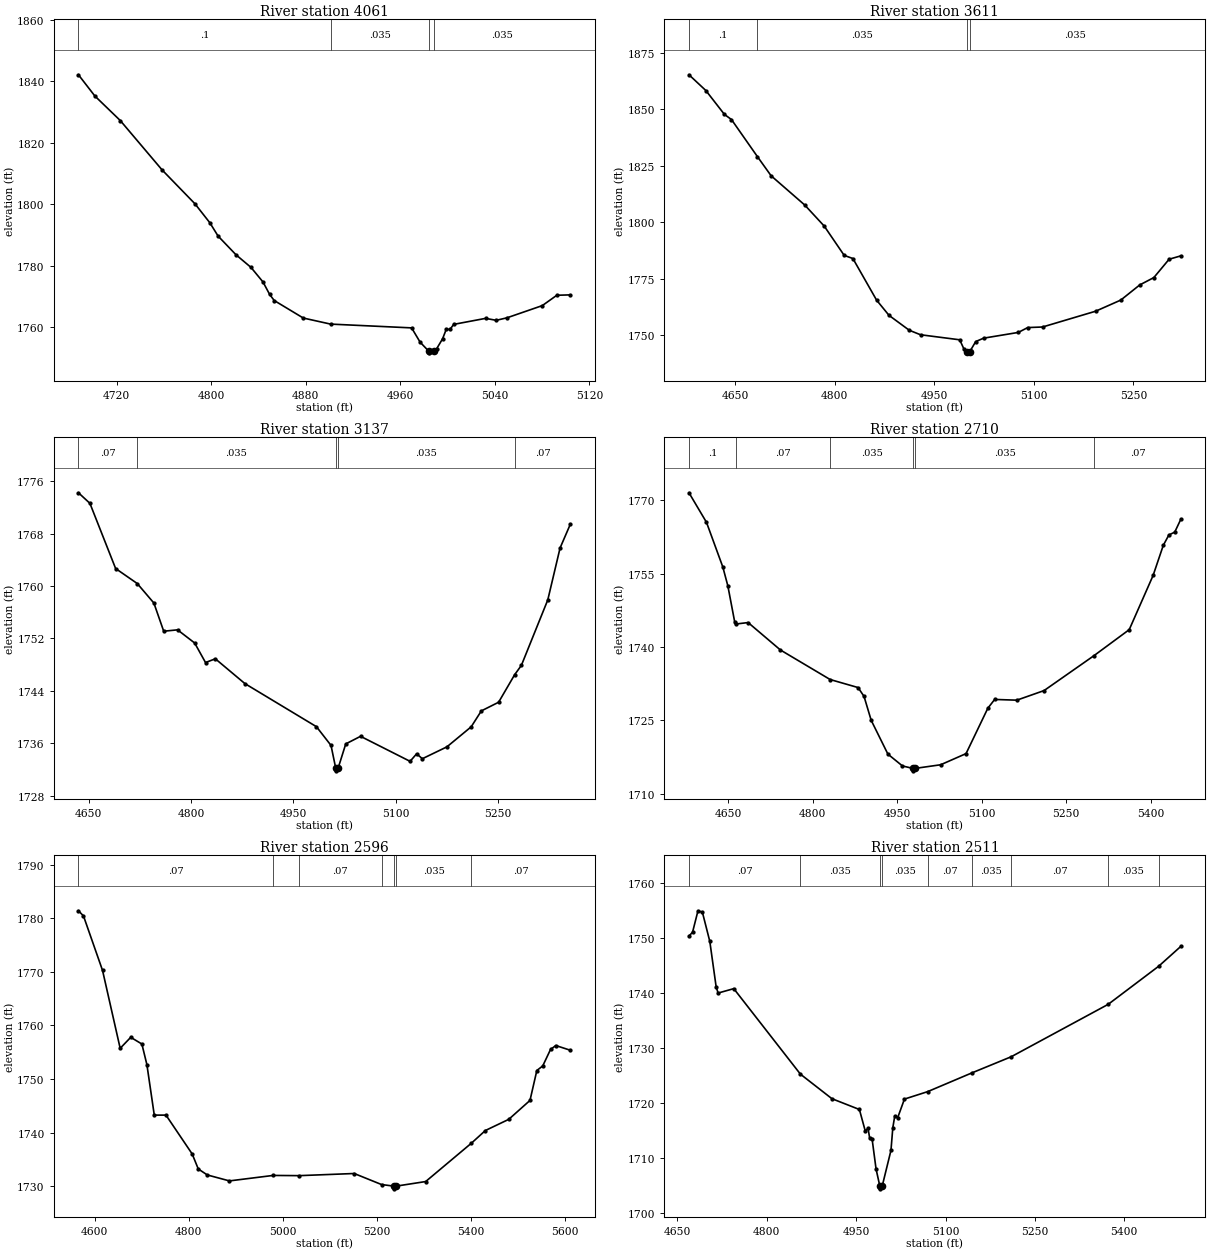
Type RM Length L Ch R = 1 ,4061    ,450,450,450
BEGIN DESCRIPTION:
Stream0679 9.0
END DESCRIPTION:
XS GIS Cut Line= 3
      1948424.96     13866024.99        1948725.       13866125.
      1948825.03       13866125.
#Sta/Elev= 30
  4687.6  1842.1  4701.5  1835.2    4723 1827.23  4758.4 1811.18  4786.2 1800.18
  4798.8 1794.02  4805.8 1789.68    4821 1783.59  4833.6 1779.52  4843.8 1774.77
  4849.4 1770.74  4853.3 1768.74  4877.9 1763.05    4901 1761.08  4969.6 1759.85
  4976.8  1755.2  4984.2 1752.24  4984.4 1751.74  4988.2 1752.24  4990.9 1753.15
  4995.8  1756.3  4998.9 1759.37  5002.1 1759.35  5005.2 1760.99  5032.2 1762.94
  5041.2 1762.31  5050.2 1763.11  5080.2 1767.09  5092.5 1770.45  5103.9 1770.58
#Mann= 4 ,-1 , 0
  4687.6      .1       0    4901    .035       0  4984.2    .035       0
  4988.2    .035       0
Bank Sta=4984.2,4988.2
XS Rating Curve= 0 ,0
Exp/Cntr=0.3,0.1

Type RM Length L Ch R = 1 ,3611    ,474,474,474
BEGIN DESCRIPTION:
Stream0679 8.0
END DESCRIPTION:
XS GIS Cut Line= 3
      1948275.02     13866225.02        1948575.       13866525.
      1948875.03     13866625.01
#Sta/Elev= 30
  4580.8 1865.21  4606.2 1858.25  4634.2 1847.67  4644.8  1845.4  4683.8 1829.02
  4704.5 1820.52  4755.1 1807.59  4784.4 1798.28  4814.5 1785.31  4827.6 1783.92
  4863.3  1765.5    4882 1758.77  4912.4  1752.2  4929.4  1750.2  4988.4 1747.97
  4994.8 1743.87  4999.5  1742.7  4999.8  1742.2  5003.5  1742.7  5012.5 1747.19
  5024.4 1748.69  5076.6 1751.23  5090.8 1753.38  5113.1 1753.63    5193 1760.61
  5230.9 1765.54  5259.4 1772.23  5280.7  1775.5  5303.7 1783.62  5321.3  1785.1
#Mann= 4 ,-1 , 0
  4580.8      .1       0  4683.8    .035       0  4999.5    .035       0
  5003.5    .035       0
Bank Sta=4999.5,5003.5
XS Rating Curve= 0 ,0
Exp/Cntr=0.3,0.1

Type RM Length L Ch R = 1 ,3137    ,427,427,427
BEGIN DESCRIPTION:
Stream0679 7.0
END DESCRIPTION:
XS GIS Cut Line= 3
      1948174.99     13866624.99        1948375.       13866925.
      1948674.98     13867124.99
#Sta/Elev= 30
    4635 1774.24  4651.8 1772.63  4689.5 1762.68  4721.2 1760.39  4745.6 1757.41
    4760 1753.11  4780.3 1753.32  4805.4 1751.31  4821.3 1748.33  4835.7  1748.9
    4879 1745.12  4983.9 1738.54  5005.3 1735.68    5012  1732.3  5012.2  1731.8
    5016  1732.3  5026.9 1735.91  5048.6 1737.07  5121.2 1733.25  5130.8  1734.4
  5139.2 1733.65  5175.2 1735.46  5210.8 1738.52  5225.7 1740.95    5251 1742.27
  5274.5 1746.47  5284.4  1747.9  5323.1 1757.89  5341.1 1765.81  5356.1 1769.43
#Mann= 5 ,-1 , 0
    4635     .07       0  4721.2    .035       0    5012    .035       0
    5016    .035       0  5274.5     .07       0
Bank Sta=5012,5016
XS Rating Curve= 0 ,0
Exp/Cntr=0.3,0.1

Type RM Length L Ch R = 1 ,2710    ,114,114,114
BEGIN DESCRIPTION:
Stream0679 6.0
END DESCRIPTION:
XS GIS Cut Line= 3
      1947974.99     13867024.99        1948275.       13867325.
      1948720.32     13867268.24
#Sta/Elev= 30
  4580.5  1771.5  4611.6 1765.46  4640.6 1756.33  4649.5 1752.49  4661.8 1745.03
  4664.4 1744.69  4685.5 1744.98  4742.8 1739.38  4831.1 1733.34  4880.7  1731.7
  4891.3 1729.89    4904    1725  4933.7 1718.09  4959.5 1715.68    4978 1715.18
  4978.3 1714.68    4982 1715.18  5027.3 1715.92  5072.4  1718.2  5111.1 1727.48
  5123.2 1729.27  5162.5 1729.12  5210.9 1731.08  5299.7 1738.23  5362.1 1743.53
  5404.5 1754.61  5422.6 1760.77  5432.5 1762.88  5442.9 1763.46  5453.7 1766.09
#Mann= 6 ,-1 , 0
  4580.5      .1       0  4664.4     .07       0  4831.1    .035       0
    4978    .035       0    4982    .035       0  5299.7     .07       0
Bank Sta=4978,4982
XS Rating Curve= 0 ,0
Exp/Cntr=0.3,0.1

Type RM Length L Ch R = 1 ,2596    ,85,85,85
BEGIN DESCRIPTION:
Stream0679 6.1
END DESCRIPTION:
XS GIS Cut Line= 5
      1947838.43     13867157.13      1948102.31     13867355.04
       1948216.9     13867417.54      1948324.54      13867434.9
      1948786.21     13867313.41
#Sta/Elev= 30
  4565.3 1781.39    4576 1780.43  4616.6 1770.26  4654.1 1755.74  4676.6 1757.79
  4700.3 1756.54    4711 1752.69  4726.7 1743.28  4751.6 1743.28  4807.4 1736.03
  4820.3 1733.24  4839.5 1732.12  4886.6 1731.01  4979.6 1732.03  5035.2 1731.99
  5152.2 1732.39  5210.4 1730.33  5237.1 1730.03  5237.4 1729.53  5241.1 1730.03
  5304.3 1730.89  5401.7 1738.05  5431.4 1740.41  5481.1 1742.49  5526.3 1746.02
  5540.9  1751.6  5553.5 1752.46    5570 1755.52  5581.2 1756.26  5612.1 1755.38
#Mann= 7 ,-1 , 0
  4565.3     .07       0  4979.6      .1       0  5035.2     .07       0
  5210.4    .035       0  5237.1    .035       0  5241.1    .035       0
  5401.7     .07       0
Bank Sta=5237.1,5241.1
XS Rating Curve= 0 ,0
Exp/Cntr=0.3,0.1

Type RM Length L Ch R = 1 ,2511    ,274,274,274
BEGIN DESCRIPTION:
Mapping XS 6581a22d
END DESCRIPTION:
XS GIS Cut Line= 3
        1947874.     13867347.51      1948274.01     13867529.29
      1948633.05     13867671.88
#Sta/Elev= 30
  4669.3 1750.32  4675.3 1751.01  4684.4 1754.91  4691.8 1754.66  4704.3 1749.33
  4714.9  1741.1  4718.2 1739.96  4744.5 1740.76  4856.4 1725.22  4909.3 1720.76
  4955.4  1718.8  4965.3 1714.87  4969.9 1715.39  4972.6 1713.63  4976.7 1713.46
  4983.4 1707.97  4989.7 1704.88  4989.9 1704.38  4993.7 1704.88  5008.4 1711.37
  5011.5 1715.49  5014.8 1717.64  5019.7 1717.31    5031 1720.69  5069.9 1722.04
  5143.8 1725.43  5210.2 1728.38  5373.1 1737.91  5457.8 1744.83    5495 1748.44
#Mann= 9 ,-1 , 0
  4669.3     .07       0  4856.4    .035       0  4989.7    .035       0
  4993.7    .035       0  5069.9     .07       0  5143.8    .035       0
  5210.2     .07       0  5373.1    .035       0  5457.8     .07       0
Bank Sta=4989.7,4993.7
XS Rating Curve= 0 ,0
Exp/Cntr=0.3,0.1

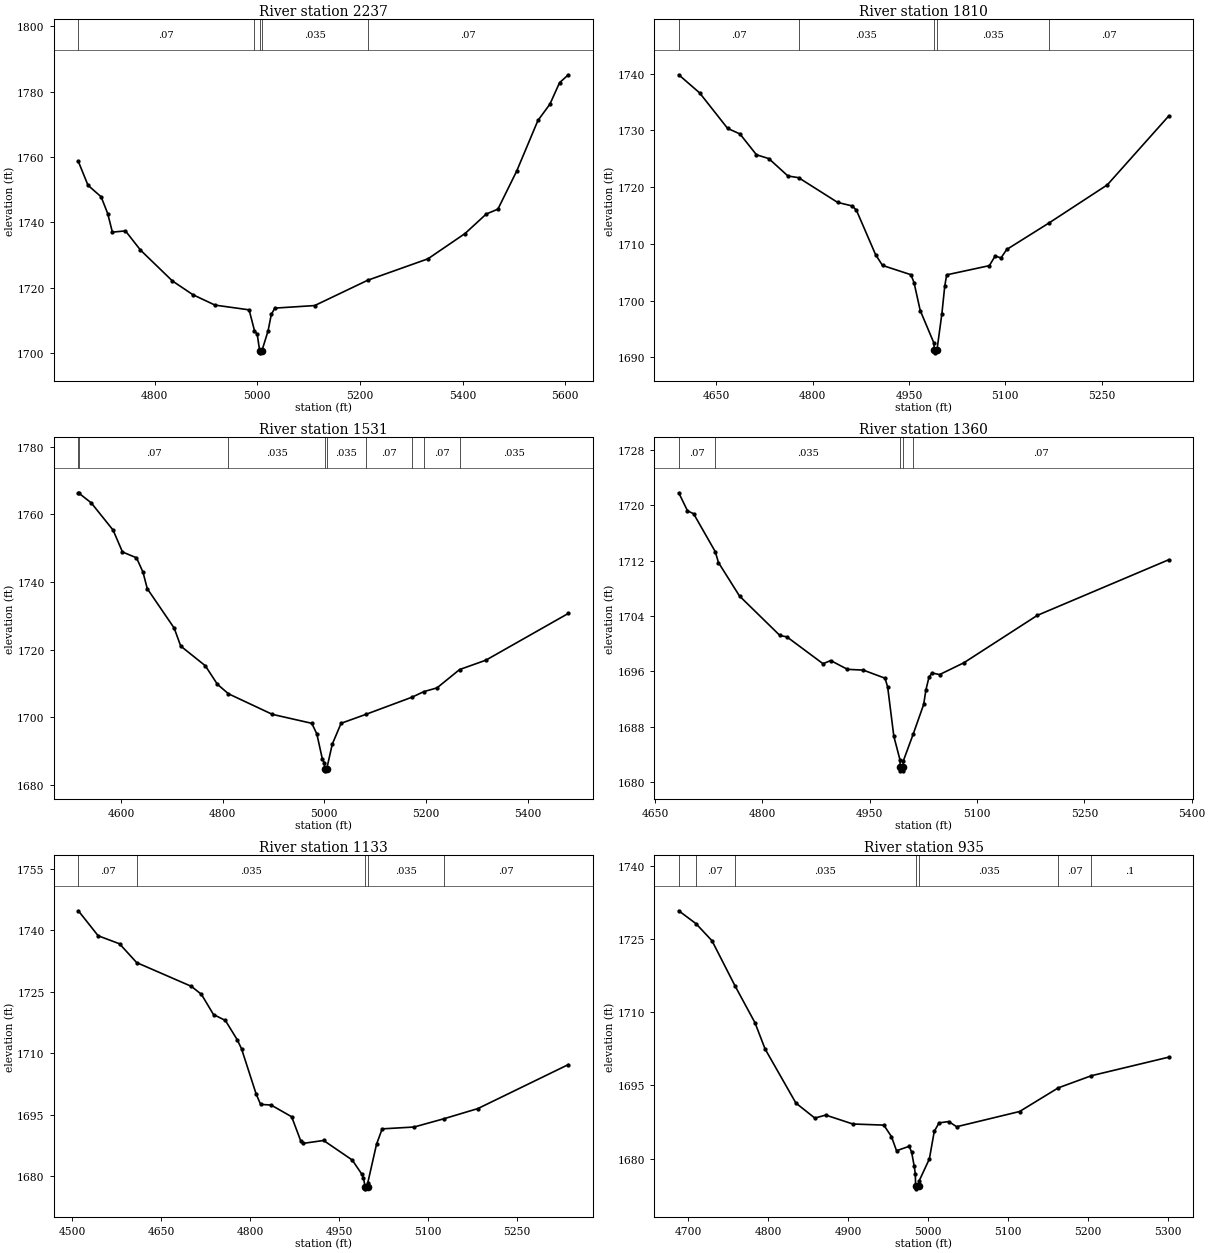
Type RM Length L Ch R = 1 ,2237    ,427,427,427
BEGIN DESCRIPTION:
Stream0679 5.0
END DESCRIPTION:
XS GIS Cut Line= 3
      1947792.04      13867528.9        1948075.       13867725.
      1948639.44     13867957.72
#Sta/Elev= 30
  4651.2  1758.6    4670 1751.32  4695.6 1747.79  4708.4 1742.66  4717.5 1736.99
    4743 1737.37  4772.2 1731.51  4834.3 1722.08  4874.3 1717.86  4917.5 1714.67
  4983.9 1713.22  4994.4 1706.85  4999.7 1705.77  5004.6 1700.57  5004.8 1700.07
  5008.6 1700.57  5020.9 1706.81  5027.2 1711.84  5034.1 1713.75  5111.7 1714.53
  5214.8 1722.26  5332.4 1728.83  5404.7 1736.57    5446 1742.53  5468.7 1744.02
  5505.2 1755.63  5546.7 1771.15    5570 1776.12  5588.8  1782.7    5606 1785.12
#Mann= 5 ,-1 , 0
  4651.2     .07       0  4994.4    .035       0  5004.6    .035       0
  5008.6    .035       0  5214.8     .07       0
Bank Sta=5004.6,5008.6
XS Rating Curve= 0 ,0
Exp/Cntr=0.3,0.1

Type RM Length L Ch R = 1 ,1810    ,279,279,279
BEGIN DESCRIPTION:
Stream0679 4.0
END DESCRIPTION:
XS GIS Cut Line= 3
      1947717.04     13867801.57        1947975.       13868125.
      1948322.09     13868164.21
#Sta/Elev= 30
  4591.4 1739.81  4623.9 1736.62  4667.5 1730.36  4686.7 1729.38  4712.4 1725.71
  4731.7 1725.03  4761.4 1721.97    4778 1721.67  4838.8 1717.31  4861.7 1716.68
  4868.1 1715.92    4898 1708.08  4908.7  1706.2    4953 1704.56  4957.8 1703.16
  4967.4 1698.25  4988.5 1692.58  4989.5 1691.29  4989.7 1690.79  4993.5 1691.29
  5001.1 1697.66  5005.6 1702.54  5008.6 1704.54    5075 1706.16  5084.1 1707.85
  5093.2 1707.53  5102.1 1709.01  5168.3 1713.71  5258.7  1720.4  5354.4 1732.55
#Mann= 5 ,-1 , 0
  4591.4     .07       0    4778    .035       0  4989.5    .035       0
  4993.5    .035       0  5168.3     .07       0
Bank Sta=4989.5,4993.5
XS Rating Curve= 0 ,0
Exp/Cntr=0.3,0.1

Type RM Length L Ch R = 1 ,1531    ,171,171,171
BEGIN DESCRIPTION:
Mapping XS df99cbb4
END DESCRIPTION:
XS GIS Cut Line= 4
      1947498.06     13868019.65       1947812.9     13868333.18
      1948093.73      13868514.4      1948275.51      13868552.1
#Sta/Elev= 30
  4516.2 1766.39  4517.8 1766.21  4541.5 1763.42  4584.6 1755.35    4603  1748.9
  4630.6 1747.18  4643.3 1742.97  4651.8 1738.06  4704.8  1726.4  4717.6  1721.1
  4766.1 1715.27  4789.7 1709.82  4811.5    1707  4897.9 1700.92  4975.5 1698.27
  4985.4 1695.17  4996.3 1687.74  5000.5 1686.54  5000.8 1684.73    5001 1684.23
  5004.8 1684.73  5015.8 1692.09  5033.2 1698.28  5081.3 1700.88  5172.5 1705.98
  5196.1 1707.64  5221.9 1708.74  5266.4 1714.16    5318 1716.92  5480.4 1730.75
#Mann= 9 ,-1 , 0
  4516.2      .1       0  4517.8     .07       0  4811.5    .035       0
  5000.8    .035       0  5004.8    .035       0  5081.3     .07       0
  5172.5    .035       0  5196.1     .07       0  5266.4    .035       0
Bank Sta=5000.8,5004.8
XS Rating Curve= 0 ,0
Exp/Cntr=0.3,0.1

Type RM Length L Ch R = 1 ,1360    ,227,227,227
BEGIN DESCRIPTION:
Stream0679 3.0
END DESCRIPTION:
XS GIS Cut Line= 3
      1947541.66     13868216.77        1947725.       13868475.
       1947985.6     13868734.69
#Sta/Elev= 30
  4683.3 1721.79  4695.5 1719.19  4704.1 1718.76  4734.3 1713.29  4738.8 1711.71
  4768.2 1706.88  4824.6 1701.18  4834.4 1700.98  4884.9  1697.1  4895.6 1697.56
    4919 1696.29  4941.1 1696.18  4971.5 1695.01  4975.2 1693.73  4983.8 1686.62
  4992.5 1683.18  4992.6 1682.13  4992.9 1681.63  4996.4 1681.63  4996.6 1682.13
  4996.8 1682.99  5010.7 1686.89  5025.5 1691.22  5028.6 1693.31  5032.9 1695.15
  5037.1 1695.77  5047.7 1695.53  5081.7 1697.24  5184.2 1704.08  5367.9 1712.12
#Mann= 5 ,-1 , 0
  4683.3     .07       0  4734.3    .035       0  4992.6    .035       0
  4996.6    .035       0  5010.7     .07       0
Bank Sta=4992.6,4996.6
XS Rating Curve= 0 ,0
Exp/Cntr=0.3,0.1

Type RM Length L Ch R = 1 ,1133    ,198,198,198
BEGIN DESCRIPTION:
Mapping XS 11ce5aee
END DESCRIPTION:
XS GIS Cut Line= 3
      1947195.29     13868341.05      1947514.63     13868622.12
      1947895.42     13868749.65
#Sta/Elev= 30
  4510.3 1744.72  4543.7 1738.63  4579.8 1736.67  4608.7 1732.09    4701  1726.3
    4718 1724.35  4738.4 1719.42  4758.4 1717.99  4778.4 1713.29  4785.7 1711.08
  4810.3 1700.08  4817.9 1697.52  4835.6 1697.37  4870.3 1694.51  4885.6 1688.63
  4890.1 1688.03  4924.2 1688.73  4972.5 1683.97  4988.3  1680.6  4991.5 1679.57
  4994.3 1677.44  4994.6 1676.94  4998.3 1677.44  4998.7 1678.36  5013.6 1687.85
  5023.1 1691.56  5076.9 1692.01  5126.9 1694.01  5184.5  1696.5  5337.3 1707.23
#Mann= 5 ,-1 , 0
  4510.3     .07       0  4608.7    .035       0  4994.3    .035       0
  4998.3    .035       0  5126.9     .07       0
Bank Sta=4994.3,4998.3
XS Rating Curve= 0 ,0
Exp/Cntr=0.3,0.1

Type RM Length L Ch R = 1 ,935     ,464,464,464
BEGIN DESCRIPTION:
Stream0679 2.0
END DESCRIPTION:
XS GIS Cut Line= 3
      1947225.02     13868725.01        1947525.       13868825.
      1947820.35     13868855.23
#Sta/Elev= 30
    4688 1730.78  4709.6 1728.14  4729.6 1724.64  4758.2 1715.46  4783.4 1707.83
    4796 1702.47  4834.6 1691.37  4858.3 1688.29  4871.9 1688.91  4905.8 1687.08
  4944.6 1686.85  4954.1 1684.51  4960.5  1681.6  4976.3 1682.51  4979.4 1681.31
  4982.6 1678.44    4984 1676.88  4984.4 1674.29  4984.7 1673.79  4988.4 1674.29
  4988.9 1675.45  5001.6 1679.93  5007.7 1685.56  5013.7 1687.31  5025.8 1687.58
  5035.7 1686.52  5114.5 1689.64  5162.9 1694.49  5204.4 1696.98  5301.1 1700.78
#Mann= 7 ,-1 , 0
    4688      .1       0  4709.6     .07       0  4758.2    .035       0
  4984.4    .035       0  4988.4    .035       0  5162.9     .07       0
  5204.4      .1       0
Bank Sta=4984.4,4988.4
XS Rating Curve= 0 ,0
Exp/Cntr=0.3,0.1

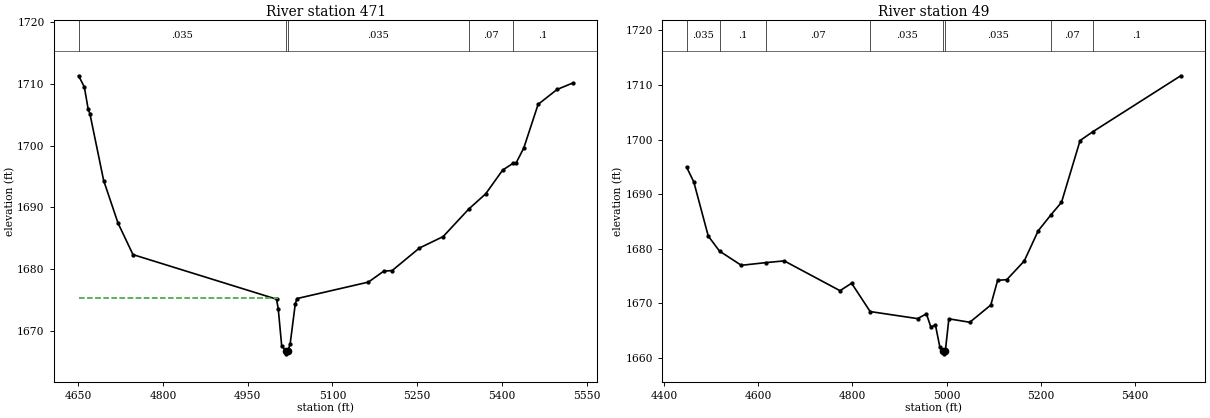
Type RM Length L Ch R = 1 ,471     ,422,422,422
BEGIN DESCRIPTION:
Stream0679 1.0
END DESCRIPTION:
XS GIS Cut Line= 3
       1947178.6      13868912.8        1947325.       13869225.
      1947853.03     13869262.77
#Sta/Elev= 30
  4650.8  1711.3    4661  1709.5  4667.6    1706  4670.9 1705.14  4695.2 1694.34
  4720.6 1687.45  4747.1 1682.34  5001.1 1675.12  5004.1 1673.56  5010.2 1667.58
  5017.2 1666.77  5017.4 1666.27  5021.2 1666.77  5025.2 1667.88  5034.2 1674.33
  5037.2 1675.22  5163.7 1677.89  5190.6 1679.65  5205.7 1679.76  5253.8  1683.4
  5295.9 1685.26  5341.3 1689.73  5371.1 1692.18  5401.2 1696.03  5419.8 1697.14
  5425.2 1697.22  5438.6 1699.62  5463.9 1706.67  5497.4 1709.08    5525 1710.12
#Mann= 5 ,-1 , 0
  4650.8    .035       0  5017.2    .035       0  5021.2    .035       0
  5341.3     .07       0  5419.8      .1       0
#XS Ineff= 2 , 0
         5001.15 1675.36
Permanent Ineff=
       F       F
Bank Sta=5017.2,5021.2
XS Rating Curve= 0 ,0
Exp/Cntr=0.3,0.1

Type RM Length L Ch R = 1 ,49      ,0,0,0
BEGIN DESCRIPTION:
Stream0679 0.0
END DESCRIPTION:
XS GIS Cut Line= 4
      1947122.48     13869057.97      1947255.29     13869374.98
      1947359.18     13869673.68      1947735.81     13869769.12
#Sta/Elev= 30
    4448 1694.93  4463.2 1692.24  4493.9 1682.33  4517.8 1679.57    4564 1676.97
  4617.2 1677.47  4655.1 1677.78  4773.5 1672.32  4798.1 1673.69  4837.5  1668.5
    4938 1667.21  4956.9 1668.08  4966.3 1665.65  4975.9 1666.08  4985.5 1661.95
    4993 1661.26  4993.3 1660.76    4997 1661.26  5004.5 1667.17    5049 1666.54
  5093.5  1669.7    5108 1674.22  5127.4 1674.34  5164.4 1677.75  5194.1 1683.29
  5221.4 1686.24  5243.5  1688.5    5283 1699.82  5309.9 1701.42  5496.5 1711.67
#Mann= 8 ,-1 , 0
    4448    .035       0  4517.8      .1       0  4617.2     .07       0
  4837.5    .035       0    4993    .035       0    4997    .035       0
  5221.4     .07       0  5309.9      .1       0
Bank Sta=4993,4997
XS Rating Curve= 0 ,0
Exp/Cntr=0.3,0.1

Chan Stop Cuts=-1
Use User Specified Reach Order=0
Composite Channel Slope=5