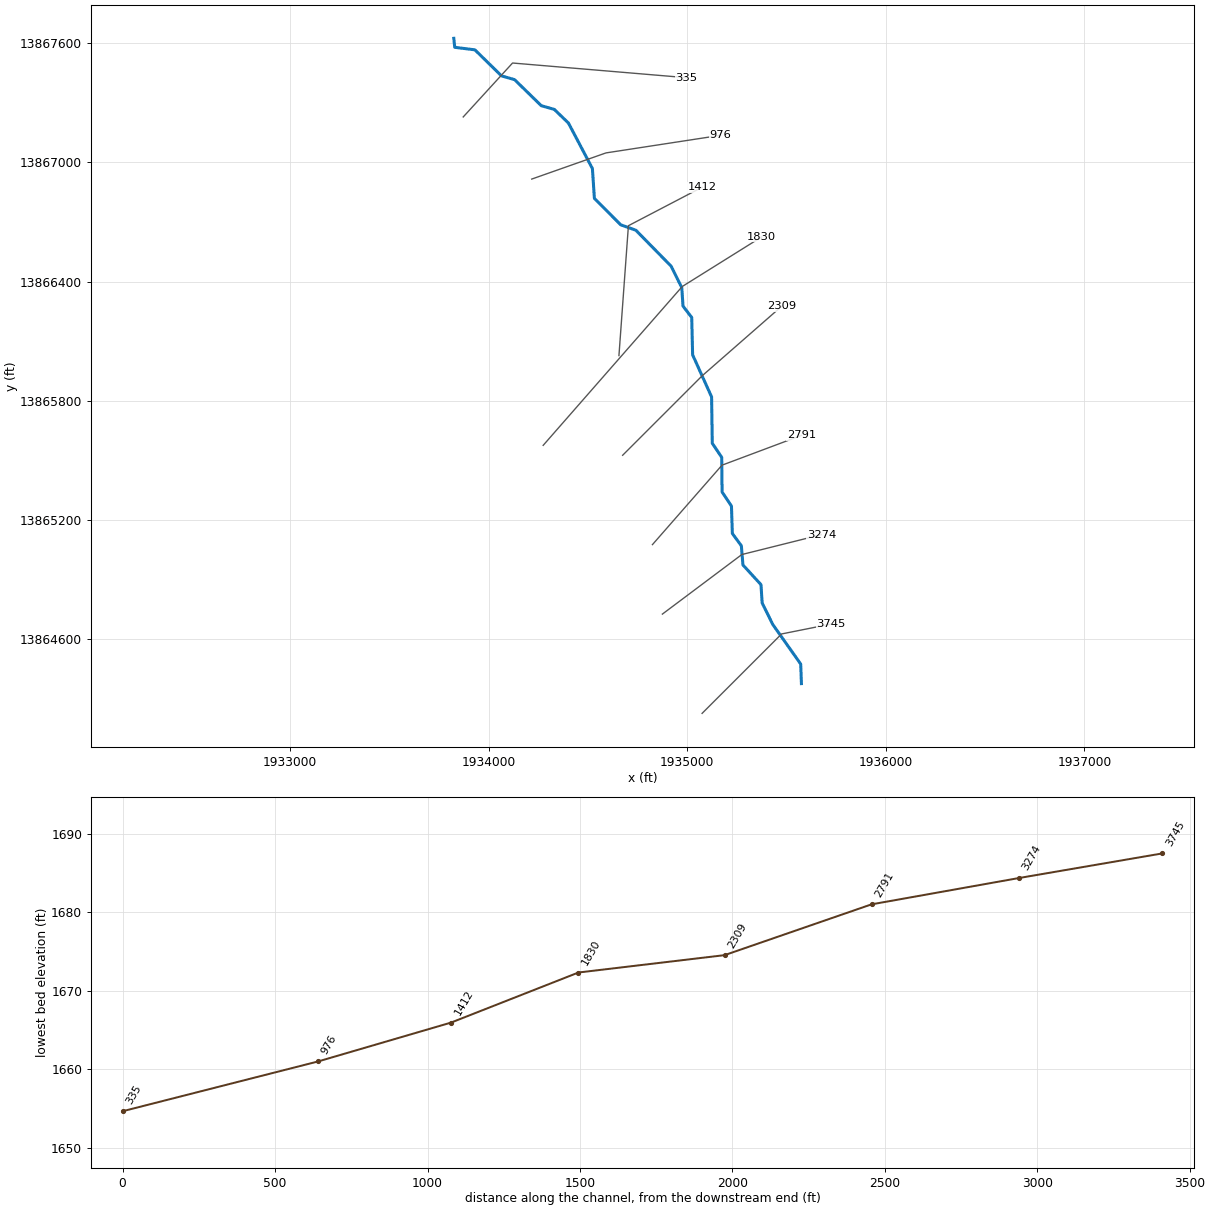
--- Stream0680.prj (project) ---

Proj Title=Stream0680 Base Level Engineering
Current Plan=p01
Default Exp/Contr=0.3,0.1
English Units
Geom File=g01
Flow File=f01
Plan File=p01
BEGIN DESCRIPTION:
Stream0680
END DESCRIPTION:

--- Stream0680.p01 (plan) ---

Plan Title=Multiple Run
Short Identifier=Multiple
Geom File=g01
Flow File=f01
Subcritical Flow
K Sum by GR= 0
Std Step Tol= 0.01
Critical Tol= 0.01
Num of Std Step Trials= 20
Max Error Tol= 0.3
Flow Tol Ratio= 0.001
Split Flow NTrial= 30
Split Flow Tol= 0.02
Split Flow Ratio= 0.02
Log Output Level= 0
Friction Slope Method= 1
Unsteady Friction Slope Method= 2
Unsteady Bridges Friction Slope Method= 1
Parabolic Critical Depth
Global Vel Dist=  1 , 1 , 1
Global Log Level= 0
CheckData=True
Encroach Param= -1, 0, 0, 0
BEGIN DESCRIPTION:
Multiple Run
END DESCRIPTION:

--- Stream0680.f01 (steady flow) ---

Flow Title=Multiple
Number of Profiles=7
Profile Names=10-year,25-year,50-year,1pct_min,100-year,1pct_plu,500-year
River Rch & RM= Stream0680,Reach-1,3745
    2019    3529    5003    3424    6832   13631   12580
Boundary for River Rch & Prof#=Stream0680,Reach-1,1
Up Type=0
Dn Type=3
Dn Slope=0.005
Boundary for River Rch & Prof#=Stream0680,Reach-1,2
Up Type=0
Dn Type=3
Dn Slope=0.005
Boundary for River Rch & Prof#=Stream0680,Reach-1,3
Up Type=0
Dn Type=3
Dn Slope=0.005
Boundary for River Rch & Prof#=Stream0680,Reach-1,4
Up Type=0
Dn Type=3
Dn Slope=0.005
Boundary for River Rch & Prof#=Stream0680,Reach-1,5
Up Type=0
Dn Type=3
Dn Slope=0.005
Boundary for River Rch & Prof#=Stream0680,Reach-1,6
Up Type=0
Dn Type=3
Dn Slope=0.005
Boundary for River Rch & Prof#=Stream0680,Reach-1,7
Up Type=0
Dn Type=3
Dn Slope=0.005

--- Stream0680.g01 (geometry) ---

Geom Title=Existing Conditions

River Reach=Stream0680,Reach-1
Reach XY= 30
      1935575.00     13864375.00      1935571.37     13864473.50
      1935430.84     13864672.71      1935377.33     13864780.97
      1935371.38     13864873.50      1935280.54     13864972.58
      1935272.64     13865069.02      1935227.27     13865130.94
      1935222.73     13865269.06      1935175.52     13865340.22
      1935173.78     13865514.49      1935126.22     13865585.50
      1935122.74     13865819.06      1935027.26     13866030.94
      1935022.74     13866219.06      1934978.86     13866276.60
      1934972.67     13866369.03      1934919.17     13866477.30
      1934741.67     13866658.35      1934665.32     13866685.78
      1934532.82     13866818.81      1934522.75     13866969.07
      1934402.01     13867198.52      1934331.07     13867266.85
      1934265.32     13867285.78      1934131.05     13867416.84
      1934065.32     13867435.78      1933931.15     13867567.16
      1933829.68     13867579.75      1933825.00     13867625.00

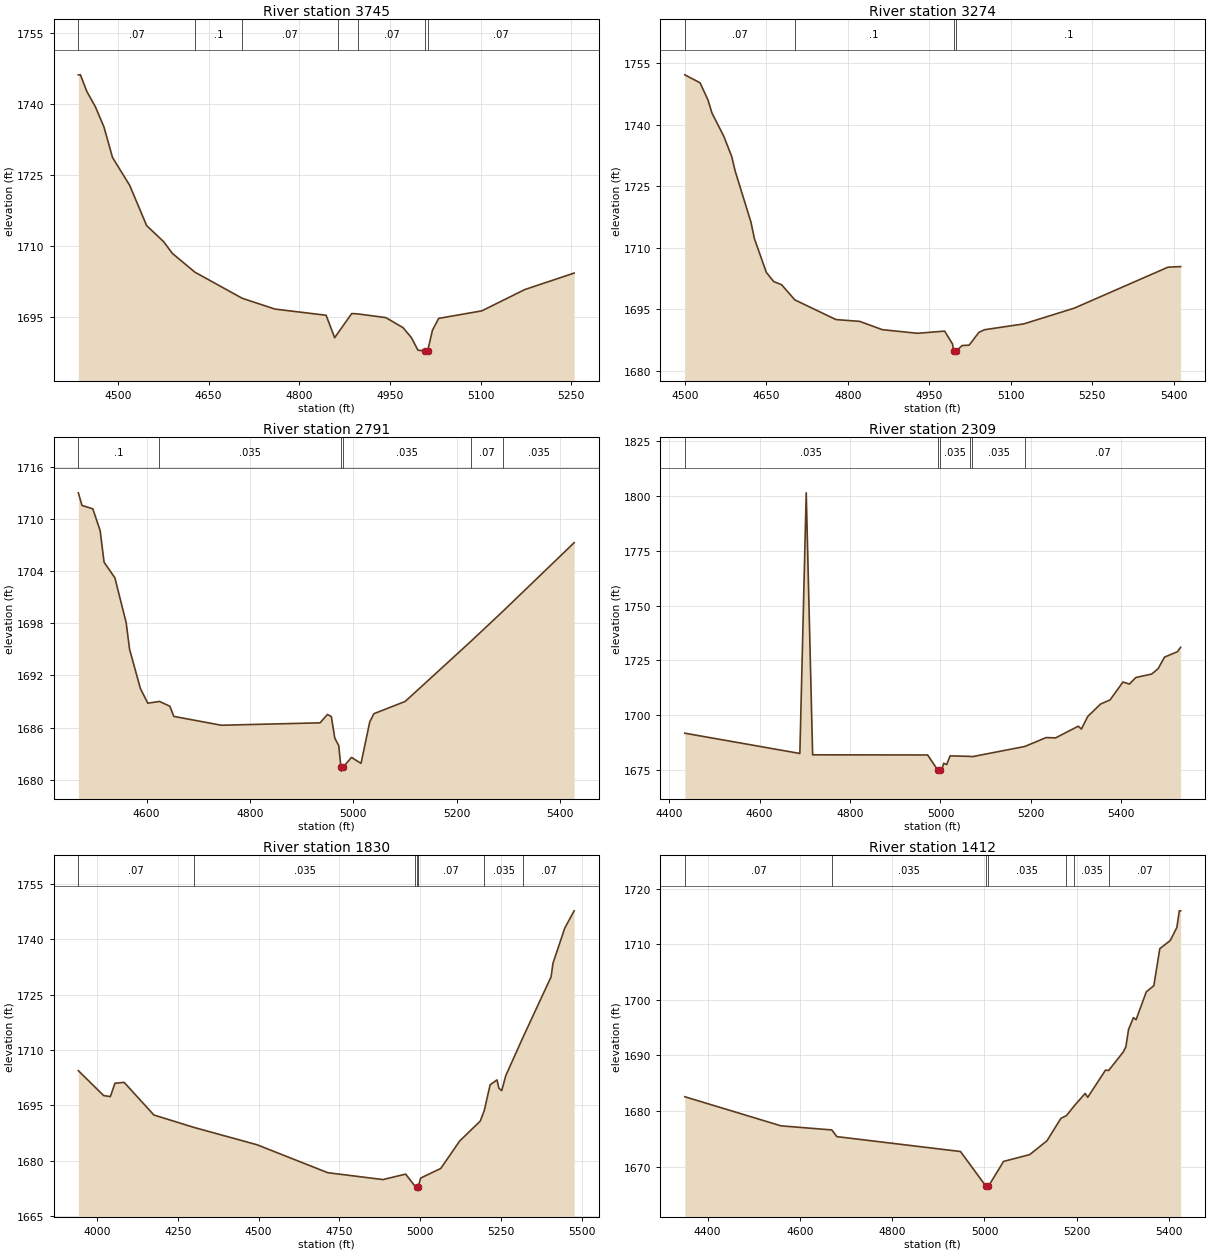
Type RM Length L Ch R = 1,3745,471,471,471
BEGIN DESCRIPTION:
Stream0680 7.0
END DESCRIPTION:
XS GIS Cut Line= 3
      1935075.00     13864225.00      1935475.00     13864625.00
      1935724.97     13864674.99
#Sta/Elev= 30
  4434.3 1746.22  4437.8 1746.22  4448.4 1742.70  4462.6 1739.45  4476.7 1735.22
  4490.9 1728.77  4519.2 1722.92  4547.4 1714.39  4575.7 1710.98  4589.9 1708.53
  4627.2 1704.57  4705.5 1699.06  4759.6 1696.78  4844.4 1695.47  4858.6 1690.72
  4863.3 1691.61  4886.8 1695.84  4897.4 1695.75  4943.4 1694.97  4971.7 1692.86
  4985.8 1690.71  4996.4 1688.08  5007.8 1687.98  5008.2 1687.48  5012.5 1687.98
  5020.4 1692.32  5030.6 1694.81  5102.0 1696.40  5173.3 1700.90  5254.9 1704.38
#Mann=7,-1,0
  4434.3    0.07       0  4627.2     0.1       0  4705.5    0.07       0
  4863.3     0.1       0  4897.4    0.07       0  5007.8    0.05       0
  5012.5    0.07       0
Bank Sta=5007.8,5012.5
Exp/Cntr=0.3,0.1

Type RM Length L Ch R = 1,3274,483,483,483
BEGIN DESCRIPTION:
Stream0680 6.0
END DESCRIPTION:
XS GIS Cut Line= 3
      1934875.03     13864725.02      1935275.00     13865025.00
      1935675.02     13865125.01
#Sta/Elev= 30
  4500.1 1752.10  4528.2 1750.16  4542.8 1745.96  4550.1 1742.78  4571.9 1737.13
  4586.5 1732.18  4592.8 1728.67  4621.9 1716.20  4628.2 1712.22  4650.1 1704.00
  4663.6 1701.77  4678.2 1701.00  4702.5 1697.31  4778.2 1692.51  4821.9 1692.07
  4863.6 1690.05  4928.2 1689.17  4978.2 1689.70  4992.8 1686.54  4994.6 1684.84
  4994.9 1684.34  4999.3 1684.84  5010.4 1686.19  5023.3 1686.28  5041.3 1689.40
  5051.6 1690.04  5123.8 1691.46  5216.5 1695.28  5389.2 1705.27  5412.4 1705.41
#Mann=4,-1,0
  4500.1    0.07       0  4702.5     0.1       0  4994.6    0.05       0
  4999.3     0.1       0
Bank Sta=4994.6,4999.3
Exp/Cntr=0.3,0.1

Type RM Length L Ch R = 1,2791,482,482,482
BEGIN DESCRIPTION:
Stream0680 5.0
END DESCRIPTION:
XS GIS Cut Line= 3
      1934825.02     13865075.03      1935175.00     13865475.00
      1935575.03     13865625.01
#Sta/Elev= 30
  4468.1 1713.02  4475.2 1711.57  4496.1 1711.18  4510.3 1708.67  4517.9 1705.03
  4538.8 1703.24  4560.6 1698.07  4567.2 1695.01  4588.1 1690.50  4602.4 1688.81
  4625.0 1689.01  4645.1 1688.46  4652.7 1687.29  4744.7 1686.27  4935.5 1686.55
  4949.7 1687.51  4957.3 1687.27  4964.0 1684.78  4971.6 1683.93  4975.8 1681.49
  4976.2 1680.99  4980.6 1681.49  4996.3 1682.57  5014.7 1681.88  5031.6 1686.66
  5039.6 1687.60  5100.1 1689.01  5227.9 1695.97  5289.4 1699.41  5426.8 1707.28
#Mann=6,-1,0
  4468.1     0.1       0  4625.0   0.035       0  4975.8   0.035       0
  4980.6   0.035       0  5227.9    0.07       0  5289.4   0.035       0
Bank Sta=4975.8,4980.6
Exp/Cntr=0.3,0.1

Type RM Length L Ch R = 1,2309,479,479,479
BEGIN DESCRIPTION:
Stream0680 4.0
END DESCRIPTION:
XS GIS Cut Line= 3
      1934674.99     13865524.99      1935075.00     13865925.00
      1935474.99     13866275.00
#Sta/Elev= 30
  4434.3 1691.82  4688.9 1682.57  4703.0 1801.42  4717.2 1681.95  4971.7 1681.89
  4994.0 1675.02  4994.4 1674.52  4998.9 1675.02  5003.3 1675.02  5007.1 1678.11
  5013.8 1677.51  5021.4 1681.48  5064.8 1681.25  5070.8 1681.13  5186.7 1685.76
  5234.0 1689.83  5254.8 1689.67  5305.1 1695.02  5311.8 1693.68  5326.0 1699.45
  5354.5 1705.13  5375.4 1706.99  5403.9 1715.16  5418.1 1714.21  5432.3 1717.21
  5467.4 1718.78  5481.7 1721.23  5495.9 1726.50  5524.4 1728.98  5531.5 1730.98
#Mann=6,-1,0
  4434.3   0.035       0  4994.0   0.035       0  4998.9   0.035       0
  5064.8    0.07       0  5070.8   0.035       0  5186.7    0.07       0
Bank Sta=4994,4998.9
Exp/Cntr=0.3,0.1

Type RM Length L Ch R = 1,1830,418,418,418
BEGIN DESCRIPTION:
Stream0680 3.0
END DESCRIPTION:
XS GIS Cut Line= 3
      1934275.03     13865575.03      1934975.00     13866375.00
      1935375.03     13866625.02
#Sta/Elev= 30
  3941.8 1704.42  4020.1 1697.68  4040.9 1697.39  4055.2 1701.01  4083.6 1701.25
  4175.7 1692.40  4300.4 1689.02  4494.6 1684.35  4713.9 1676.76  4884.7 1674.90
  4954.9 1676.38  4985.2 1672.97  4988.6 1672.81  4988.9 1672.31  4993.5 1672.81
  5001.4 1675.31  5063.7 1677.92  5122.1 1685.35  5185.8 1690.75  5198.3 1693.62
  5216.4 1700.59  5237.7 1701.92  5243.6 1699.65  5252.4 1699.01  5264.8 1703.06
  5318.0 1713.44  5405.1 1729.85  5411.0 1733.57  5447.6 1743.11  5476.5 1747.75
#Mann=7,-1,0
  3941.8    0.07       0  4300.4   0.035       0  4985.2    0.07       0
  4988.6    0.05       0  4993.5    0.07       0  5198.3   0.035       0
  5318.0    0.07       0
Bank Sta=4988.6,4993.5
Exp/Cntr=0.3,0.1

Type RM Length L Ch R = 1,1412,436,436,436
BEGIN DESCRIPTION:
Stream0680 2.0
END DESCRIPTION:
XS GIS Cut Line= 3
      1934656.36     13866027.10      1934704.03     13866681.29
      1935074.98     13866874.99
#Sta/Elev= 30
  4350.7 1682.56  4559.2 1677.32  4669.4 1676.58  4680.2 1675.38  4948.1 1672.70
  5003.5 1666.43  5003.8 1665.93  5008.5 1666.43  5041.5 1670.92  5098.0 1672.14
  5135.5 1674.63  5165.7 1678.67  5177.8 1679.17  5195.1 1680.97  5218.2 1683.15
  5223.8 1682.45  5262.3 1687.35  5269.2 1687.29  5300.8 1690.61  5306.5 1691.56
  5312.3 1694.68  5322.9 1696.80  5328.6 1696.42  5350.7 1701.44  5367.1 1702.55
  5380.0 1709.21  5402.6 1710.67  5416.9 1713.02  5422.3 1716.02  5425.1 1716.02
#Mann=7,-1,0
  4350.7    0.07       0  4669.4   0.035       0  5003.5   0.035       0
  5008.5   0.035       0  5177.8    0.07       0  5195.1   0.035       0
  5269.2    0.07       0
Bank Sta=5003.5,5008.5
Exp/Cntr=0.3,0.1

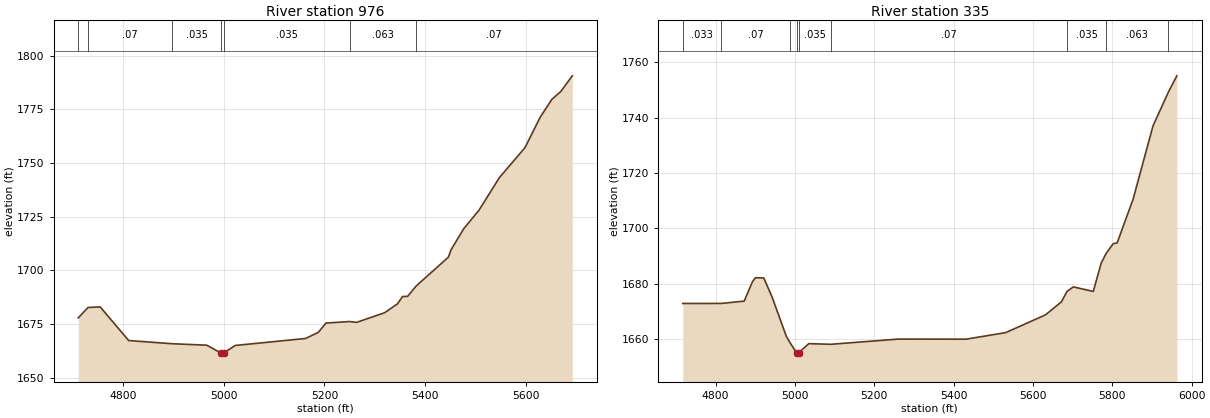
Type RM Length L Ch R = 1,976,641,641,641
BEGIN DESCRIPTION:
Mapping XS a02fdddd
END DESCRIPTION:
XS GIS Cut Line= 3
      1934217.26     13866916.10      1934591.02     13867047.92
      1935167.83     13867136.53
#Sta/Elev= 30
  4711.8 1677.88  4731.3 1682.73  4755.4 1682.96  4811.9 1667.31  4898.4 1665.82
  4966.6 1665.15  4995.0 1661.48  4995.4 1660.98  5000.1 1661.48  5023.2 1665.02
  5162.7 1668.27  5187.9 1671.13  5203.2 1675.46  5249.8 1676.16  5263.9 1675.78
  5319.5 1680.27  5344.9 1684.39  5355.0 1687.81  5365.1 1687.91  5382.0 1692.71
  5446.0 1706.17  5451.1 1709.54  5476.4 1719.43  5506.7 1728.06  5547.2 1743.25
  5597.8 1757.17  5628.1 1771.39  5651.1 1779.67  5668.6 1783.28  5691.7 1790.64
#Mann=7,-1,0
  4711.8   0.033       0  4731.3    0.07       0  4898.4   0.035       0
  4995.0   0.035       0  5000.1   0.035       0  5249.8   0.063       0
  5382.0    0.07       0
Bank Sta=4995,5000.1
Exp/Cntr=0.3,0.1

Type RM Length L Ch R = 1,335,0,0,0
BEGIN DESCRIPTION:
Stream0680 0.0
END DESCRIPTION:
XS GIS Cut Line= 3
      1933872.47     13867229.08      1934120.75     13867500.69
      1934994.86     13867426.93
#Sta/Elev= 30
  4717.5 1672.93  4814.9 1672.94  4872.3 1673.77  4893.3 1680.81  4900.7 1682.23
  4921.7 1682.12  4942.6 1675.26  4978.4 1661.08  4987.3 1658.87  5004.2 1655.14
  5004.6 1654.64  5009.3 1655.14  5035.1 1658.42  5090.8 1658.19  5260.4 1660.07
  5431.0 1660.03  5531.3 1662.40  5631.7 1668.81  5671.8 1673.51  5685.8 1677.26
  5701.9 1678.91  5752.1 1677.27  5772.2 1687.56  5784.9 1691.07  5802.3 1694.49
  5812.3 1694.80  5852.4 1710.53  5902.6 1737.01  5941.4 1749.22  5962.7 1755.09
#Mann=9,-1,0
  4717.5   0.033       0  4814.9    0.07       0  4987.3   0.035       0
  5004.2   0.035       0  5009.3   0.035       0  5090.8    0.07       0
  5685.8   0.035       0  5784.9   0.063       0  5941.4    0.07       0
Bank Sta=5004.2,5009.3
Exp/Cntr=0.3,0.1

Chan Stop Cuts=-1