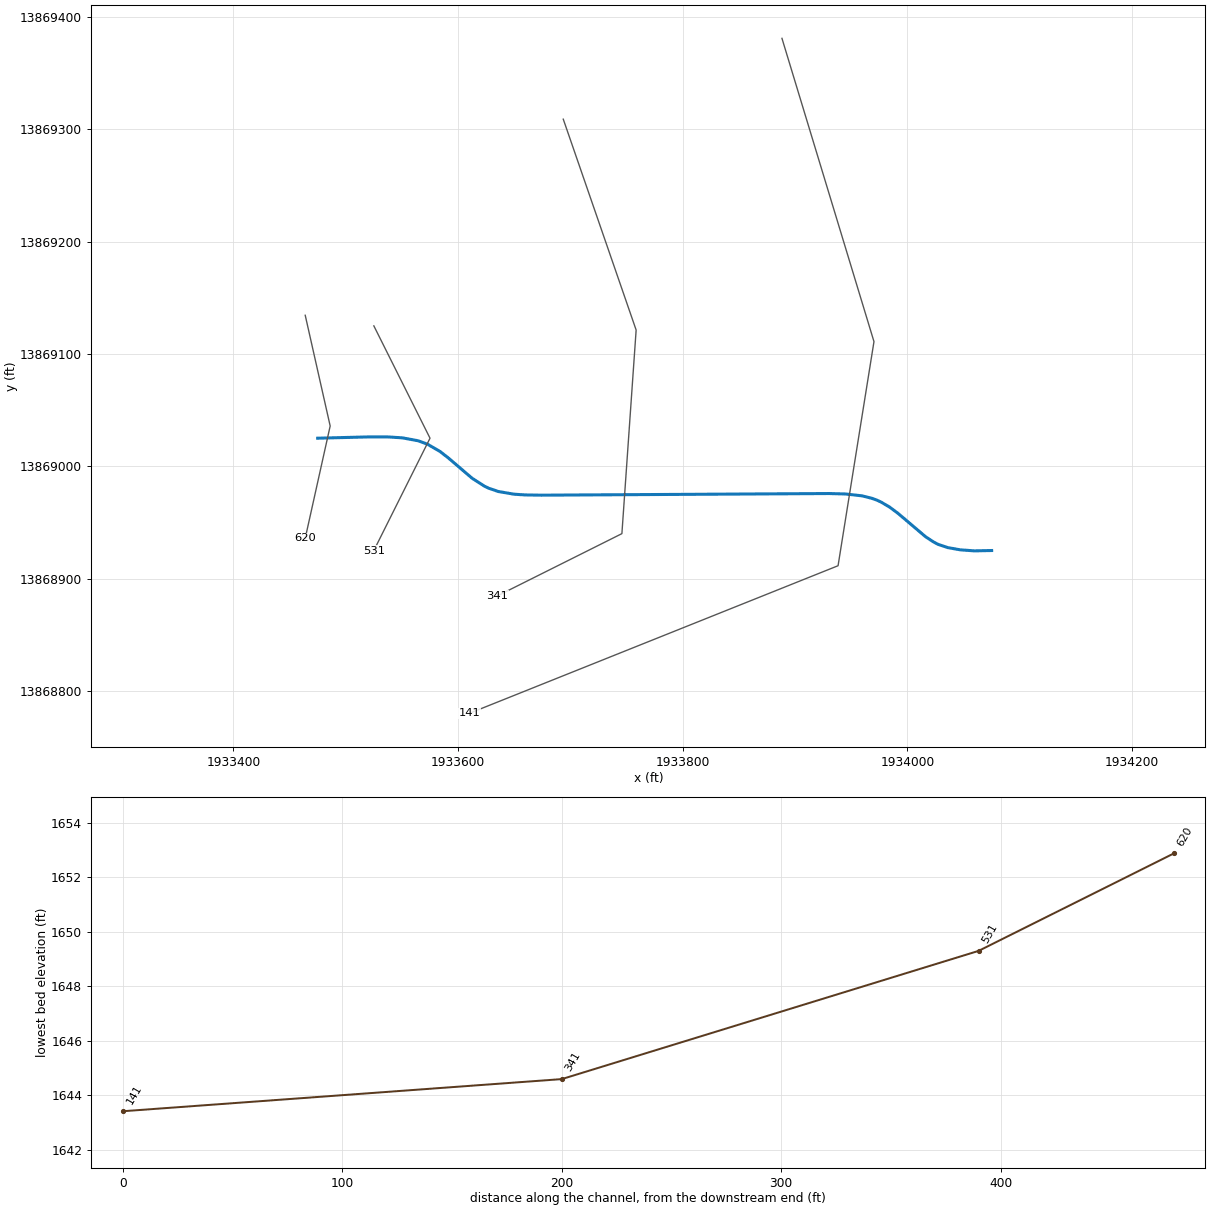
--- Stream0681.prj (project) ---

Proj Title=Stream0681 Base Level Engineering
Current Plan=p01
Default Exp/Contr=0.3,0.1
English Units
Geom File=g01
Flow File=f01
Plan File=p01
BEGIN DESCRIPTION:
Stream0681
END DESCRIPTION:

--- Stream0681.p01 (plan) ---

Plan Title=Multiple Run
Short Identifier=Multiple
Geom File=g01
Flow File=f01
Subcritical Flow
K Sum by GR= 0
Std Step Tol= 0.01
Critical Tol= 0.01
Num of Std Step Trials= 20
Max Error Tol= 0.3
Flow Tol Ratio= 0.001
Split Flow NTrial= 30
Split Flow Tol= 0.02
Split Flow Ratio= 0.02
Log Output Level= 0
Friction Slope Method= 1
Unsteady Friction Slope Method= 2
Unsteady Bridges Friction Slope Method= 1
Parabolic Critical Depth
Global Vel Dist=  1 , 1 , 1
Global Log Level= 0
CheckData=True
Encroach Param= -1, 0, 0, 0
BEGIN DESCRIPTION:
Multiple Run
END DESCRIPTION:

--- Stream0681.f01 (steady flow) ---

Flow Title=Multiple
Number of Profiles=7
Profile Names=10-year,25-year,50-year,1pct_min,100-year,1pct_plu,500-year
River Rch & RM= Stream0681,Reach-1,620
     662    1087    1480     978    1951    3892    3336
Boundary for River Rch & Prof#=Stream0681,Reach-1,1
Up Type=0
Dn Type=3
Dn Slope=0.005
Boundary for River Rch & Prof#=Stream0681,Reach-1,2
Up Type=0
Dn Type=3
Dn Slope=0.005
Boundary for River Rch & Prof#=Stream0681,Reach-1,3
Up Type=0
Dn Type=3
Dn Slope=0.005
Boundary for River Rch & Prof#=Stream0681,Reach-1,4
Up Type=0
Dn Type=3
Dn Slope=0.005
Boundary for River Rch & Prof#=Stream0681,Reach-1,5
Up Type=0
Dn Type=3
Dn Slope=0.005
Boundary for River Rch & Prof#=Stream0681,Reach-1,6
Up Type=0
Dn Type=3
Dn Slope=0.005
Boundary for River Rch & Prof#=Stream0681,Reach-1,7
Up Type=0
Dn Type=3
Dn Slope=0.005

--- Stream0681.g01 (geometry) ---

Geom Title=Existing Conditions

River Reach=Stream0681,Reach-1
Reach XY= 30
      1933475.00     13869025.00      1933520.64     13869026.15
      1933537.19     13869026.14      1933550.32     13869025.33
      1933564.25     13869022.75      1933572.74     13869019.67
      1933583.96     13869013.13      1933591.16     13869007.55
      1933612.37     13868989.42      1933623.47     13868982.27
      1933627.30     13868980.45      1933635.86     13868977.52
      1933649.87     13868975.13      1933659.70     13868974.49
      1933673.93     13868974.27      1933930.33     13868975.73
      1933945.25     13868975.32      1933959.66     13868973.67
      1933968.61     13868971.40      1933972.82     13868969.84
      1933976.68     13868968.07      1933984.17     13868963.66
      1933991.43     13868958.27      1934016.17     13868937.29
      1934023.53     13868932.47      1934027.32     13868930.51
      1934035.78     13868927.62      1934047.39     13868925.56
      1934059.64     13868924.70      1934075.00     13868925.00

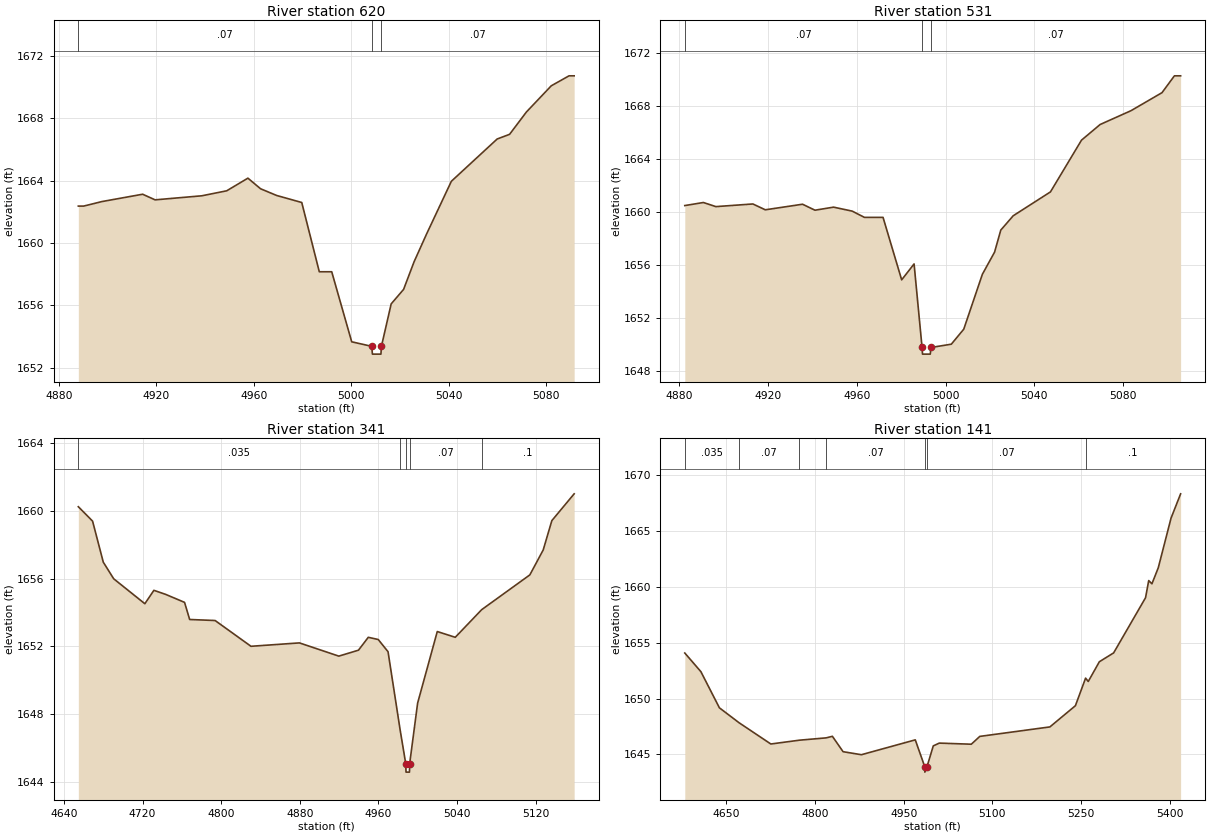
Type RM Length L Ch R = 1,620,89,89,89
BEGIN DESCRIPTION:
Stream0681 2.0
END DESCRIPTION:
XS GIS Cut Line= 3
      1933463.90     13869134.43      1933486.11     13869035.87
      1933463.88     13868935.84
#Sta/Elev= 29
  4888.0 1662.37  4890.2 1662.37  4897.7 1662.66  4914.4 1663.13  4919.5 1662.77
  4938.7 1663.03  4948.9 1663.35  4957.6 1664.16  4962.8 1663.48  4969.4 1663.05
  4979.7 1662.60  4986.9 1658.16  4992.0 1658.16  5000.2 1653.67  5008.4 1653.38
  5008.7 1652.88  5012.2 1652.88  5012.4 1653.38  5016.4 1656.10  5021.5 1657.03
  5025.8 1658.80  5030.9 1660.57  5041.1 1663.96  5059.9 1666.67  5065.0 1666.97
  5071.9 1668.40  5082.1 1670.08  5089.4 1670.72  5091.5 1670.72
#Mann=3,-1,0
  4888.0    0.07       0  5008.4    0.05       0  5012.4    0.07       0
Bank Sta=5008.4,5012.4
Exp/Cntr=0.3,0.1

Type RM Length L Ch R = 1,531,190,190,190
BEGIN DESCRIPTION:
Stream0681 1.0
END DESCRIPTION:
XS GIS Cut Line= 3
      1933525.00     13869124.99      1933575.00     13869025.00
      1933525.00     13868925.00
#Sta/Elev= 30
  4882.4 1660.50  4890.8 1660.73  4896.4 1660.42  4913.1 1660.62  4918.7 1660.18
  4935.5 1660.60  4941.1 1660.15  4949.5 1660.38  4957.9 1660.08  4963.4 1659.61
  4971.8 1659.61  4980.2 1654.90  4985.8 1656.10  4989.4 1649.80  4989.6 1649.30
  4993.1 1649.30  4993.4 1649.80  5002.6 1650.05  5008.2 1651.18  5016.6 1655.32
  5022.1 1656.99  5024.9 1658.65  5030.5 1659.73  5047.3 1661.53  5061.3 1665.43
  5069.7 1666.61  5083.6 1667.65  5097.6 1669.01  5103.2 1670.28  5106.0 1670.28
#Mann=3,-1,0
  4882.4    0.07       0  4989.4    0.05       0  4993.4    0.07       0
Bank Sta=4989.4,4993.4
Exp/Cntr=0.3,0.1

Type RM Length L Ch R = 1,341,200,200,200
BEGIN DESCRIPTION:
Stream0681 0.0
END DESCRIPTION:
XS GIS Cut Line= 4
      1933693.63     13869309.02      1933758.51     13869121.30
      1933745.83     13868940.03      1933634.68     13868884.45
#Sta/Elev= 30
  4654.6 1660.24  4669.1 1659.39  4680.0 1656.97  4690.6 1655.99  4722.3 1654.52
  4731.5 1655.31  4743.5 1655.07  4762.7 1654.60  4767.9 1653.59  4793.8 1653.53
  4830.3 1652.01  4879.6 1652.21  4919.7 1651.43  4939.7 1651.78  4949.7 1652.54
  4959.8 1652.41  4969.8 1651.69  4982.1 1647.08  4987.8 1645.09  4988.1 1644.59
  4991.6 1644.59  4991.8 1645.09  4999.9 1648.66  5019.9 1652.88  5038.2 1652.54
  5065.1 1654.17  5114.1 1656.22  5127.7 1657.69  5136.5 1659.42  5159.2 1661.00
#Mann=5,-1,0
  4654.6   0.035       0  4982.1    0.07       0  4987.8    0.05       0
  4991.8    0.07       0  5065.1     0.1       0
Bank Sta=4987.8,4991.8
Exp/Cntr=0.3,0.1

Type RM Length L Ch R = 1,141,0,0,0
BEGIN DESCRIPTION:
Stream0681 0.1
END DESCRIPTION:
XS GIS Cut Line= 4
      1933888.33     13869380.99      1933970.25     13869110.98
      1933938.28     13868911.46      1933609.95     13868780.01
#Sta/Elev= 30
  4580.2 1654.08  4607.4 1652.41  4638.7 1649.17  4672.0 1647.83  4725.6 1645.93
  4773.8 1646.27  4819.2 1646.48  4829.6 1646.62  4847.7 1645.24  4878.6 1644.97
  4969.7 1646.30  4985.6 1643.91  4985.9 1643.41  4989.6 1643.91  5000.1 1645.76
  5010.2 1646.01  5064.4 1645.91  5078.7 1646.61  5197.2 1647.46  5240.3 1649.36
  5257.5 1651.83  5262.0 1651.53  5280.8 1653.30  5304.9 1654.09  5358.8 1659.03
  5364.2 1660.57  5369.6 1660.28  5380.3 1661.71  5401.9 1666.16  5418.1 1668.34
#Mann=7,-1,0
  4580.2   0.035       0  4672.0    0.07       0  4773.8   0.035       0
  4819.2    0.07       0  4985.6    0.05       0  4989.6    0.07       0
  5257.5     0.1       0
Bank Sta=4985.6,4989.6
Exp/Cntr=0.3,0.1

Chan Stop Cuts=-1