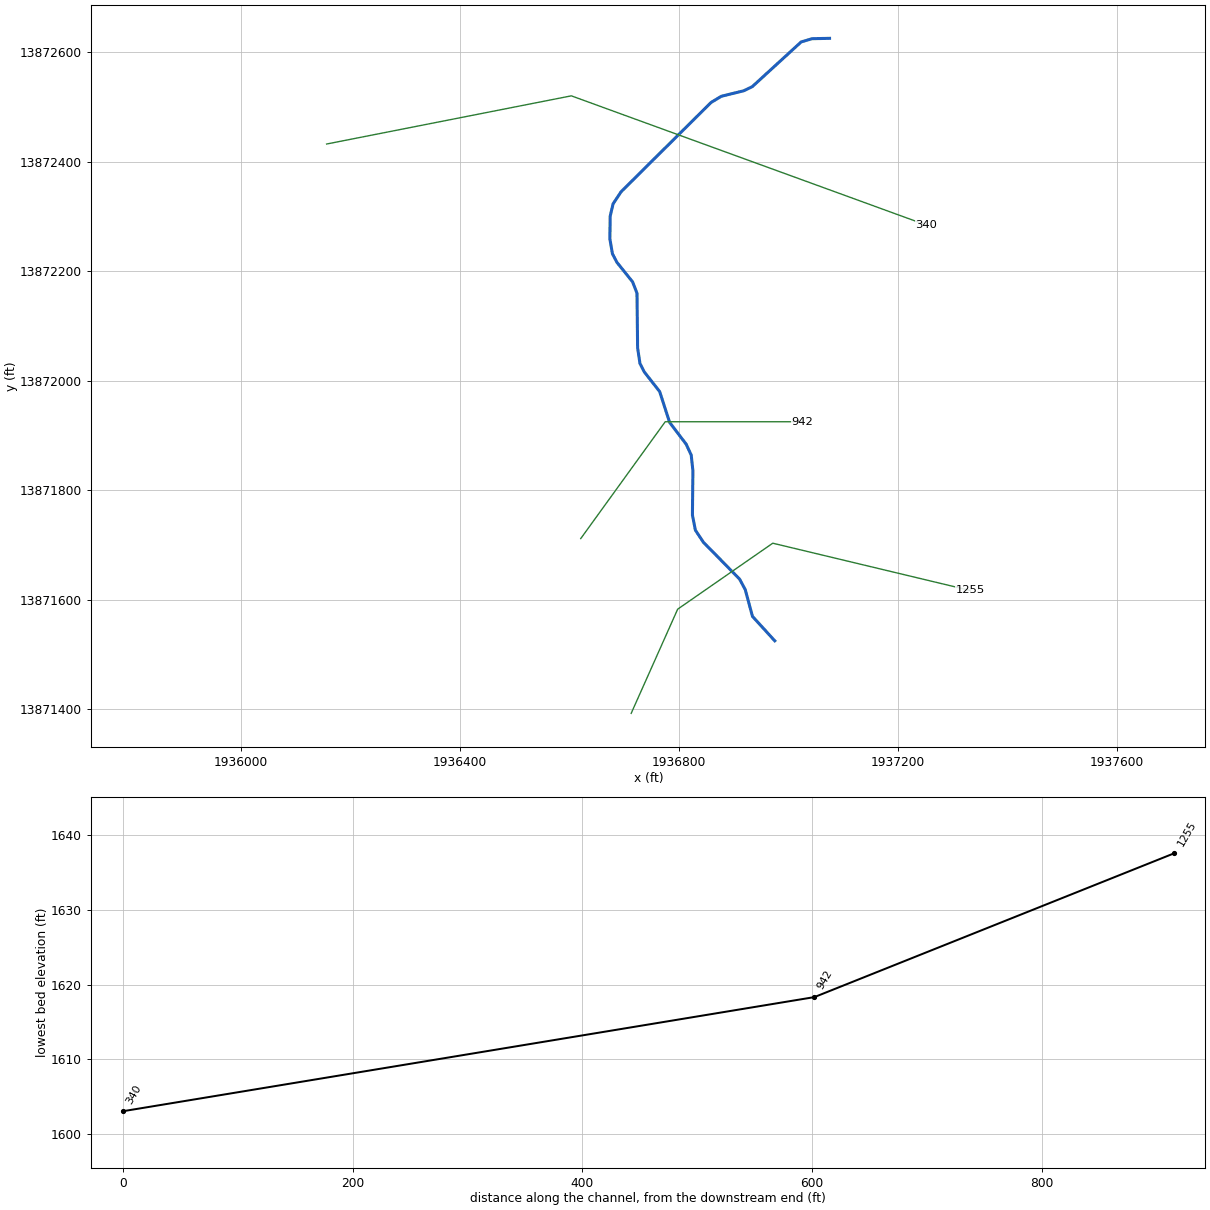
--- Stream0682.prj (project) ---

Proj Title=Stream0682 Base Level Engineering
Current Plan=p01
Default Exp/Contr=0.3,0.1
English Units
Geom File=g01
Flow File=f01
Plan File=p01
BEGIN DESCRIPTION:
Stream0682
END DESCRIPTION:

--- Stream0682.p01 (plan) ---

Plan Title=Multiple Run
Short Identifier=Multiple
Geom File=g01
Flow File=f01
Subcritical Flow
K Sum by GR= 0
Std Step Tol= 0.01
Critical Tol= 0.01
Num of Std Step Trials= 20
Max Error Tol= 0.3
Flow Tol Ratio= 0.001
Split Flow NTrial= 30
Split Flow Tol= 0.02
Split Flow Ratio= 0.02
Log Output Level= 0
Friction Slope Method= 1
Unsteady Friction Slope Method= 2
Unsteady Bridges Friction Slope Method= 1
Parabolic Critical Depth
Global Vel Dist=  1 , 1 , 1
Global Log Level= 0
CheckData=True
Encroach Param= -1, 0, 0, 0
BEGIN DESCRIPTION:
Multiple Run
END DESCRIPTION:

--- Stream0682.f01 (steady flow) ---

Flow Title=Multiple
Number of Profiles=7
Profile Names=10-year,25-year,50-year,1pct_min,100-year,1pct_plu,500-year
River Rch & RM= Stream0682,Reach-1,1255
     545     884    1192     782    1560    3113    2626
Boundary for River Rch & Prof#=Stream0682,Reach-1,1
Up Type=0
Dn Type=3
Dn Slope=0.005
Boundary for River Rch & Prof#=Stream0682,Reach-1,2
Up Type=0
Dn Type=3
Dn Slope=0.005
Boundary for River Rch & Prof#=Stream0682,Reach-1,3
Up Type=0
Dn Type=3
Dn Slope=0.005
Boundary for River Rch & Prof#=Stream0682,Reach-1,4
Up Type=0
Dn Type=3
Dn Slope=0.005
Boundary for River Rch & Prof#=Stream0682,Reach-1,5
Up Type=0
Dn Type=3
Dn Slope=0.005
Boundary for River Rch & Prof#=Stream0682,Reach-1,6
Up Type=0
Dn Type=3
Dn Slope=0.005
Boundary for River Rch & Prof#=Stream0682,Reach-1,7
Up Type=0
Dn Type=3
Dn Slope=0.005

--- Stream0682.g01 (geometry) ---

Geom Title=Existing Conditions

River Reach=Stream0682,Reach-1
Reach XY= 30
      1936975.00     13871525.00      1936934.30     13871569.60
      1936921.08     13871618.51      1936910.73     13871637.74
      1936844.65     13871705.02      1936830.05     13871727.09
      1936824.65     13871754.69      1936825.54     13871835.29
      1936822.46     13871864.13      1936813.25     13871884.00
      1936783.06     13871923.76      1936764.85     13871980.02
      1936736.75     13872016.00      1936728.85     13872031.51
      1936724.59     13872059.74      1936723.44     13872159.58
      1936715.50     13872180.25      1936686.77     13872216.08
      1936678.65     13872231.60      1936673.95     13872258.69
      1936674.47     13872300.08      1936679.81     13872322.87
      1936694.49     13872345.00      1936858.69     13872507.92
      1936877.39     13872519.19      1936918.36     13872529.26
      1936934.03     13872536.84      1937023.11     13872618.38
      1937043.05     13872624.34      1937075.00     13872625.00

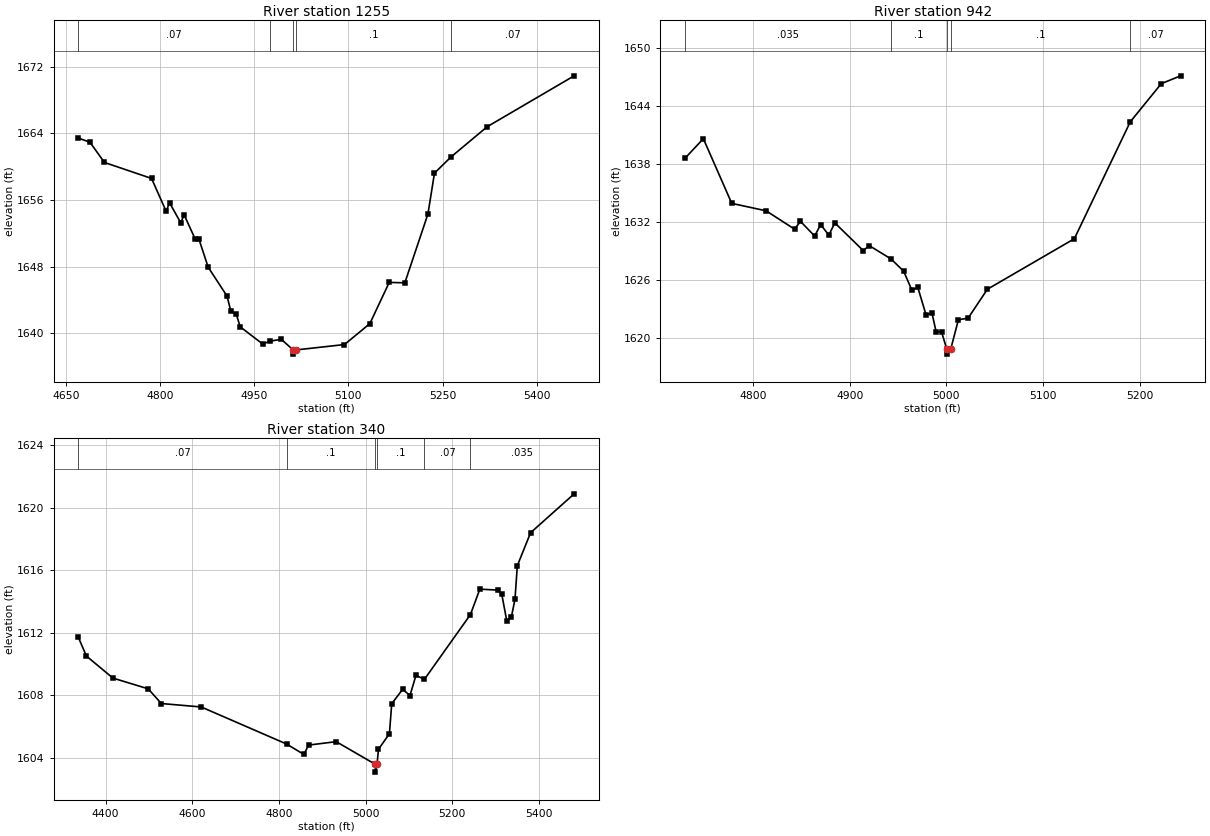
Type RM Length L Ch R = 1,1255,313,313,313
BEGIN DESCRIPTION:
Stream0682 2.0
END DESCRIPTION:
XS GIS Cut Line= 4
      1936712.82     13871392.55      1936797.71     13871582.78
      1936971.35     13871703.25      1937331.62     13871616.98
#Sta/Elev= 30
  4669.6 1663.43  4688.0 1662.95  4711.2 1660.51  4786.3 1658.59  4809.5 1654.65
  4815.0 1655.67  4832.8 1653.26  4838.2 1654.22  4856.0 1651.28  4861.5 1651.37
  4876.4 1647.95  4906.6 1644.46  4912.7 1642.63  4921.4 1642.27  4927.5 1640.78
  4963.3 1638.72  4975.4 1639.06  4993.0 1639.28  5012.0 1638.00  5012.2 1637.50
  5016.0 1638.00  5093.7 1638.65  5134.1 1641.16  5165.0 1646.11  5189.9 1646.06
  5226.7 1654.32  5237.1 1659.23  5263.3 1661.16  5321.1 1664.80  5459.7 1670.91
#Mann=5,-1,0
  4669.6    0.07       0  4975.4     0.1       0  5012.0    0.05       0
  5016.0     0.1       0  5263.3    0.07       0
Bank Sta=5012,5016
Exp/Cntr=0.3,0.1

Type RM Length L Ch R = 1,942,602,602,602
BEGIN DESCRIPTION:
Stream0682 1.0
END DESCRIPTION:
XS GIS Cut Line= 3
      1936620.78     13871711.69      1936775.00     13871925.00
      1937024.98     13871925.00
#Sta/Elev= 30
  4729.3 1638.58  4748.5 1640.63  4777.9 1633.93  4813.5 1633.16  4842.9 1631.26
  4849.0 1632.07  4863.7 1630.55  4869.9 1631.73  4878.4 1630.65  4884.6 1631.91
  4914.0 1629.04  4920.2 1629.56  4942.7 1628.18  4955.8 1626.91  4964.3 1624.95
  4970.5 1625.22  4979.0 1622.38  4985.2 1622.56  4989.4 1620.64  4995.0 1620.64
  5000.5 1618.82  5000.8 1618.32  5004.5 1618.82  5012.5 1621.88  5022.5 1622.04
  5042.5 1625.04  5132.5 1630.27  5190.4 1642.38  5222.5 1646.33  5242.5 1647.14
#Mann=5,-1,0
  4729.3   0.035       0  4942.7     0.1       0  5000.5    0.05       0
  5004.5     0.1       0  5190.4    0.07       0
Bank Sta=5000.5,5004.5
Exp/Cntr=0.3,0.1

Type RM Length L Ch R = 1,340,0,0,0
BEGIN DESCRIPTION:
Stream0682 0.0
END DESCRIPTION:
XS GIS Cut Line= 3
      1936156.77     13872432.03      1936603.59     13872520.01
      1937251.14     13872284.32
#Sta/Elev= 30
  4336.9 1611.72  4355.5 1610.52  4416.6 1609.11  4498.2 1608.42  4528.5 1607.48
  4620.5 1607.26  4817.5 1604.89  4857.6 1604.22  4868.3 1604.82  4932.1 1605.04
  5022.4 1603.59  5022.7 1603.09  5026.4 1603.59  5029.7 1604.55  5055.0 1605.55
  5060.3 1607.47  5085.6 1608.39  5102.4 1607.99  5116.2 1609.28  5135.8 1609.03
  5241.9 1613.17  5263.7 1614.80  5304.6 1614.74  5314.3 1614.47  5325.9 1612.77
  5336.5 1613.02  5344.8 1614.15  5350.2 1616.30  5380.8 1618.41  5481.4 1620.90
#Mann=6,-1,0
  4336.9    0.07       0  4817.5     0.1       0  5022.4    0.05       0
  5026.4     0.1       0  5135.8    0.07       0  5241.9   0.035       0
Bank Sta=5022.4,5026.4
Exp/Cntr=0.3,0.1

Chan Stop Cuts=-1