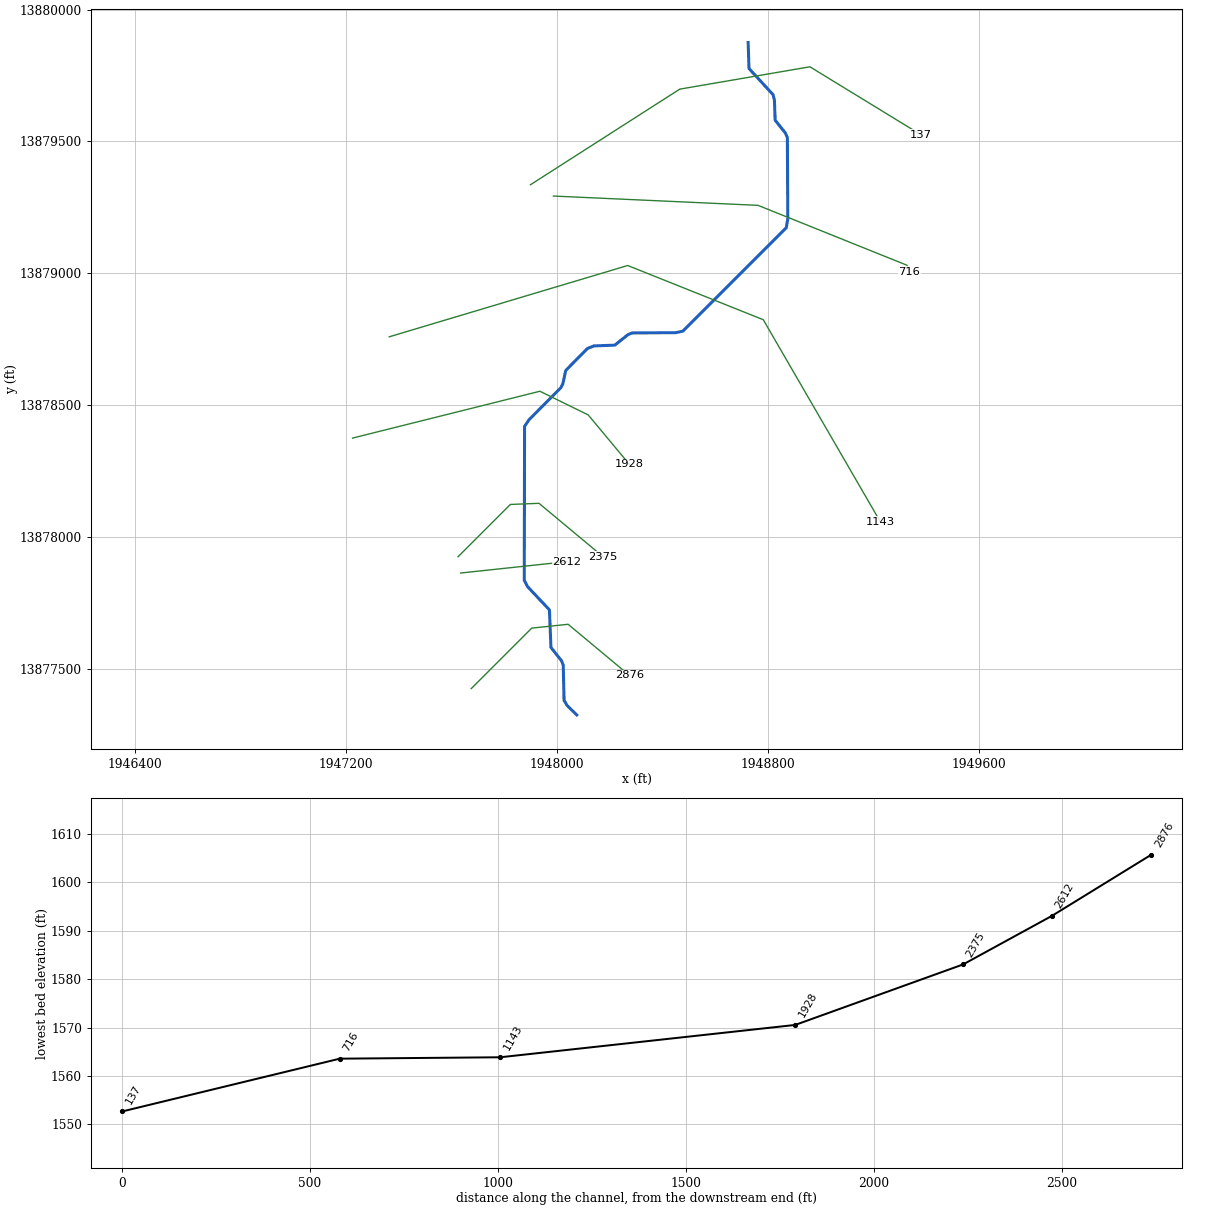
--- Stream0685.prj (project) ---

Proj Title=Stream0685 Base Level Engineering
Current Plan=p01
Default Exp/Contr=0.3,0.1
English Units
Geom File=g01
Flow File=f01
Plan File=p01
Y Axis Title=Elevation
X Axis Title(PF)=Main Channel Distance
X Axis Title(XS)=Station
BEGIN DESCRIPTION:
Stream0685
END DESCRIPTION:
DSS Export Rating Curves= 0
DSS Export Rating Curve Sorted= 0
DSS Export Volume Flow Curves= 0
DXF OffsetX= 0
DXF OffsetY= 0
DXF ScaleX= 1
DXF ScaleY= 10

--- Stream0685.p01 (plan) ---

Plan Title=Multiple Run
Short Identifier=Multiple
Geom File=g01
Flow File=f01
Subcritical Flow
K Sum by GR= 0
Std Step Tol= 0.01
Critical Tol= 0.01
Num of Std Step Trials= 20
Max Error Tol= 0.3
Flow Tol Ratio= 0.001
Split Flow NTrial= 30
Split Flow Tol= 0.02
Split Flow Ratio= 0.02
Log Output Level= 0
Friction Slope Method= 1
Unsteady Friction Slope Method= 2
Unsteady Bridges Friction Slope Method= 1
Parabolic Critical Depth
Global Vel Dist=  1 , 1 , 1
Global Log Level= 0
CheckData=True
Encroach Param= -1, 0, 0, 0
BEGIN DESCRIPTION:
Multiple Run
END DESCRIPTION:

--- Stream0685.f01 (steady flow) ---

Flow Title=Multiple
Program Version=4.10
Number of Profiles= 7
Profile Names=10-year,25-year,50-year,1pct_min,100-year,1pct_plu,500-year
River Rch & RM=Stream0685,Reach-1         ,2876
     384     609     808     522    1042    2079    1702
Boundary for River Rch & Prof#=Stream0685,Reach-1         , 1
Up Type= 0
Dn Type= 3
Dn Slope=0.008
Boundary for River Rch & Prof#=Stream0685,Reach-1         , 2
Up Type= 0
Dn Type= 3
Dn Slope=0.008
Boundary for River Rch & Prof#=Stream0685,Reach-1         , 3
Up Type= 0
Dn Type= 3
Dn Slope=0.008
Boundary for River Rch & Prof#=Stream0685,Reach-1         , 4
Up Type= 0
Dn Type= 3
Dn Slope=0.008
Boundary for River Rch & Prof#=Stream0685,Reach-1         , 5
Up Type= 0
Dn Type= 3
Dn Slope=0.008
Boundary for River Rch & Prof#=Stream0685,Reach-1         , 6
Up Type= 0
Dn Type= 3
Dn Slope=0.008
Boundary for River Rch & Prof#=Stream0685,Reach-1         , 7
Up Type= 0
Dn Type= 3
Dn Slope=0.008
DSS Import GetInterval= 0
DSS Import GetPeak= 0
DSS Import FillOption= 0

--- Stream0685.g01 (geometry) ---

Geom Title=Existing Conditions
Program Version=4.10

River Reach=Stream0685      ,Reach-1
Reach XY= 30
        1948075.       13877325.      1948037.92      13877361.5
      1948027.01     13877380.38      1948023.77     13877514.49
      1948016.86     13877531.05      1947977.27     13877580.94
      1947971.44     13877723.53       1947888.4     13877811.69
      1947876.06     13877835.44      1947877.17     13878419.56
      1947894.61     13878445.16      1948014.22     13878565.32
      1948022.46     13878581.05      1948033.15     13878631.07
      1948115.19     13878714.49      1948140.21     13878724.48
      1948219.43     13878727.47      1948268.94     13878766.86
      1948284.66     13878773.62      1948450.12     13878774.71
      1948477.45     13878780.46      1948869.54     13879172.55
      1948875.46     13879206.63      1948873.78      13879514.5
      1948866.86     13879531.06      1948827.47     13879580.57
      1948824.75     13879656.71      1948819.46     13879677.42
      1948728.39     13879776.41        1948725.       13879875.

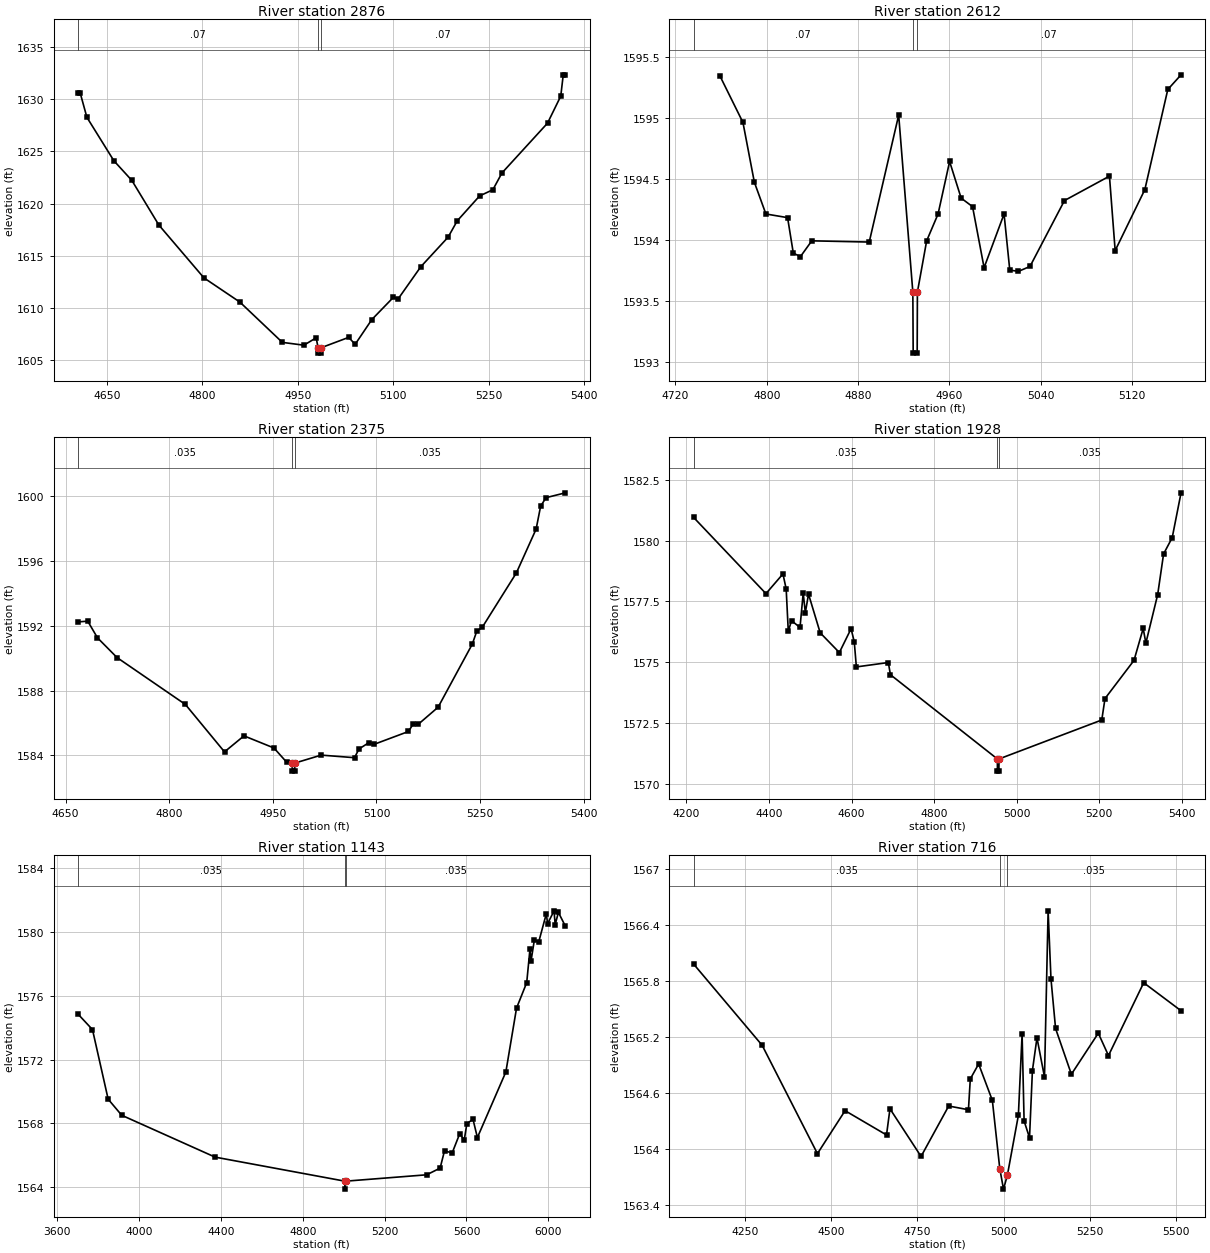
Type RM Length L Ch R = 1 ,2876    ,264,264,264
BEGIN DESCRIPTION:
Stream0685 3.0
END DESCRIPTION:
XS GIS Cut Line= 4
      1947675.03     13877425.03      1947904.34     13877654.34
      1948042.41     13877668.82      1948275.01     13877474.99
#Sta/Elev= 30
  4604.5 1630.61    4608 1630.61  4618.6 1628.26    4661  1624.1  4689.3 1622.21
  4731.7 1617.94  4802.5 1612.88    4859 1610.56  4925.7  1606.7  4959.6 1606.43
  4978.9 1607.14  4981.9 1606.17  4982.2 1605.67  4985.7 1605.67  4985.9 1606.17
    5030 1607.18  5040.1 1606.51  5066.4 1608.89  5100.3 1611.02  5108.1  1610.9
  5143.2 1613.94  5186.2 1616.78  5200.5 1618.34  5235.7 1620.73  5256.5 1621.32
  5270.8 1622.93  5342.4  1627.7  5363.2 1630.29  5367.1 1632.33  5370.4 1632.33
#Mann= 3 ,-1 , 0
  4604.5     .07       0  4981.9     .05       0  4985.9     .07       0
Bank Sta=4981.9,4985.9
XS Rating Curve= 0 ,0
Exp/Cntr=0.3,0.1

Type RM Length L Ch R = 1 ,2612    ,237,237,237
BEGIN DESCRIPTION:
Mapping XS 478833a6
END DESCRIPTION:
XS GIS Cut Line= 2
1947635.0491539213877863.2861108      1948036.56     13877906.22
#Sta/Elev= 30
    4759 1595.34  4779.1 1594.96  4789.1 1594.47  4799.2 1594.21  4818.2 1594.18
  4823.2 1593.89  4829.4 1593.86  4839.4 1593.99  4889.7 1593.98  4915.5 1595.02
  4927.9 1593.57  4928.2 1593.07  4931.7 1593.07  4931.9 1593.57    4940 1593.99
    4950 1594.21  4960.1 1594.64  4970.2 1594.34  4980.2 1594.27  4990.3 1593.77
  5007.8 1594.21  5012.8 1593.75  5020.4 1593.74  5030.5 1593.78  5060.7 1594.32
  5100.1 1594.52  5105.1 1593.91  5131.1 1594.41  5151.2 1595.23  5162.8 1595.35
#Mann= 3 ,-1 , 0
  4735.9     .07       0  4927.9     .05       0  4931.9     .07       0
Bank Sta=4927.9,4931.9
XS Rating Curve= 0 ,0
Exp/Cntr=0.3,0.1

Type RM Length L Ch R = 1 ,2375    ,447,447,447
BEGIN DESCRIPTION:
Stream0685 2.0
END DESCRIPTION:
XS GIS Cut Line= 4
      1947624.98     13877924.98       1947823.3      13878123.3
      1947931.84     13878127.63      1948174.99     13877925.01
#Sta/Elev= 30
  4667.8 1592.24    4682 1592.29  4696.1 1591.26  4724.4 1590.04  4823.4 1587.14
    4880 1584.21  4908.2  1585.2  4951.6 1584.45    4970 1583.57    4978 1583.52
  4978.2 1583.02  4981.7 1583.02    4982 1583.52    5020 1584.01  5068.2 1583.85
  5074.7 1584.39    5089 1584.78  5096.8 1584.68  5146.3 1585.47  5152.8 1585.91
  5160.6 1585.92  5189.2 1586.97  5238.7 1590.87  5245.2 1591.67    5253  1591.9
  5302.5 1595.27  5331.1 1597.98  5337.6 1599.39  5345.4 1599.92  5373.4 1600.22
#Mann= 3 ,-1 , 0
  4667.8    .035       0    4978    .035       0    4982    .035       0
Bank Sta=4978,4982
XS Rating Curve= 0 ,0
Exp/Cntr=0.3,0.1

Type RM Length L Ch R = 1 ,1928    ,785,785,785
BEGIN DESCRIPTION:
Stream0685 1.0
END DESCRIPTION:
XS GIS Cut Line= 4
      1947225.03     13878375.01      1947935.32     13878552.58
      1948118.39     13878462.94      1948274.98     13878275.02
#Sta/Elev= 30
  4217.3 1580.95  4392.5 1577.82  4433.7 1578.63  4441.5 1578.01  4446.6 1576.27
  4454.4 1576.71    4475 1576.43  4482.7 1577.84  4487.9 1577.04  4495.6  1577.8
  4523.9 1576.21  4570.3  1575.4  4598.7 1576.38  4606.4 1575.84  4611.5 1574.81
  4688.9 1574.99    4694 1574.49    4953 1571.03  4953.2 1570.53  4956.7 1570.53
    4957 1571.03  5205.9 1572.63  5213.7 1573.51    5284 1575.08  5306.2 1576.39
  5312.7 1575.79  5341.3 1577.78  5355.6 1579.45  5376.5 1580.12  5397.9 1581.96
#Mann= 3 ,-1 , 0
  4217.3    .035       0    4953    .035       0    4957    .035       0
Bank Sta=4953,4957
XS Rating Curve= 0 ,0
Exp/Cntr=0.3,0.1

Type RM Length L Ch R = 1 ,1143    ,427,427,427
BEGIN DESCRIPTION:
Stream0685 0.0
END DESCRIPTION:
XS GIS Cut Line= 4
      1947363.87       13878759.      1948268.26     13879029.44
       1948782.4     13878823.88      1949225.77     13878058.61
#Sta/Elev= 30
  3701.2 1574.86  3772.4 1573.88    3849 1569.51  3915.2  1568.5  4371.7 1565.87
  5005.8 1564.36  5006.1 1563.86  5009.8 1564.36  5405.6 1564.76  5471.3 1565.18
  5492.8 1566.27  5530.1 1566.13  5567.4 1567.35  5588.9 1566.93  5602.1 1567.97
  5631.9 1568.25  5653.5  1567.1  5792.6 1571.22  5844.8 1575.23  5894.5 1576.83
  5910.3 1578.92    5916 1578.22  5931.8  1579.5  5953.3 1579.39  5990.6 1581.17
  5996.4 1580.52  6027.9 1581.34  6033.7 1580.48  6049.4 1581.24  6083.3 1580.38
#Mann= 3 ,-1 , 0
  3701.2    .035       0  5005.8    .035       0  5009.8    .035       0
Bank Sta=5005.8,5009.8
XS Rating Curve= 0 ,0
Exp/Cntr=0.3,0.1

Type RM Length L Ch R = 1 ,716     ,579,579,579
BEGIN DESCRIPTION:
Mapping XS 19b84b07
END DESCRIPTION:
XS GIS Cut Line= 4
      1947986.56     13879292.89      1948762.52     13879257.62
      1949327.04     13879030.631949336.3818515413879004.9964519
#Sta/Elev= 30
  4101.5 1565.98  4300.1 1565.11  4460.3 1563.95  4540.4 1564.41  4660.5 1564.15
  4670.5 1564.43  4760.6 1563.92  4840.7 1564.46  4897.9 1564.42  4903.3 1564.75
  4927.5 1564.91  4967.2 1564.52  4988.7 1563.79  4999.5 1563.57  5010.8 1563.72
  5042.6 1564.36  5053.4 1565.23  5059.2  1564.3  5074.9 1564.12  5083.3 1564.84
  5096.5 1565.19  5118.3 1564.77  5128.8 1566.55  5137.1 1565.82  5150.4 1565.29
  5196.2  1564.8  5274.2 1565.24  5303.7    1565  5405.8 1565.78    5514 1565.48
#Mann= 3 ,-1 , 0
  4101.5    .035       0  4988.7    .035       0  5010.8    .035       0
#XS Ineff= 2 , 0
                         5139.01         1565.41
Permanent Ineff=
       F       F
#Block Obstruct= 2 , 0
                         5338.19         1563.35
Bank Sta=4988.7,5010.8
XS Rating Curve= 0 ,0
Exp/Cntr=0.3,0.1

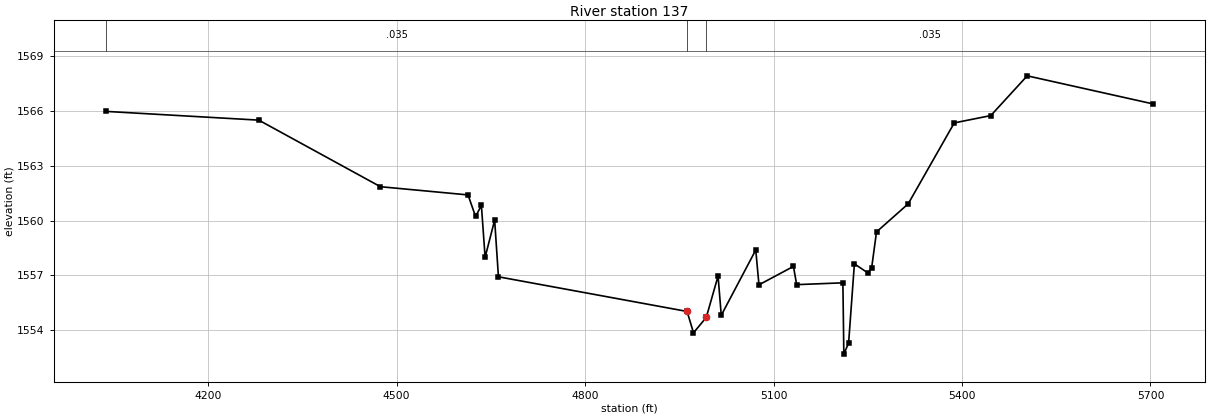
Type RM Length L Ch R = 1 ,137     ,0,0,0
BEGIN DESCRIPTION:
Stream0685 0.1
END DESCRIPTION:
XS GIS Cut Line= 4
      1947899.63     13879335.79      1948465.67     13879698.27
      1948959.35       13879783.      1949380.51     13879525.29
#Sta/Elev= 30
  4037.3 1565.99  4280.7 1565.51  4474.3 1561.86  4613.7 1561.41  4625.7 1560.23
    4635 1560.83  4640.9 1557.99  4656.1 1560.03  4662.1 1556.92  4962.4 1555.02
  4972.6 1553.85  4992.9 1554.69  5011.7 1556.96  5016.8 1554.81  5071.7 1558.39
  5076.8 1556.48  5131.7 1557.49  5136.8 1556.49  5210.4 1556.59  5211.9 1552.68
  5219.5 1553.29  5228.7 1557.63  5250.3 1557.13  5256.2 1557.42  5263.9 1559.38
  5314.3 1560.92  5387.7 1565.36  5445.8 1565.76  5503.8 1567.94  5704.1  1566.4
#Mann= 3 ,-1 , 0
  4037.3    .035       0  4962.4    .035       0  4992.9    .035       0
#XS Ineff= 2 , 0
                         5071.52         1557.92
Permanent Ineff=
       F       F
Bank Sta=4962.4,4992.9
XS Rating Curve= 0 ,0
Exp/Cntr=0.3,0.1

Chan Stop Cuts=-1
Use User Specified Reach Order=0
Composite Channel Slope=5