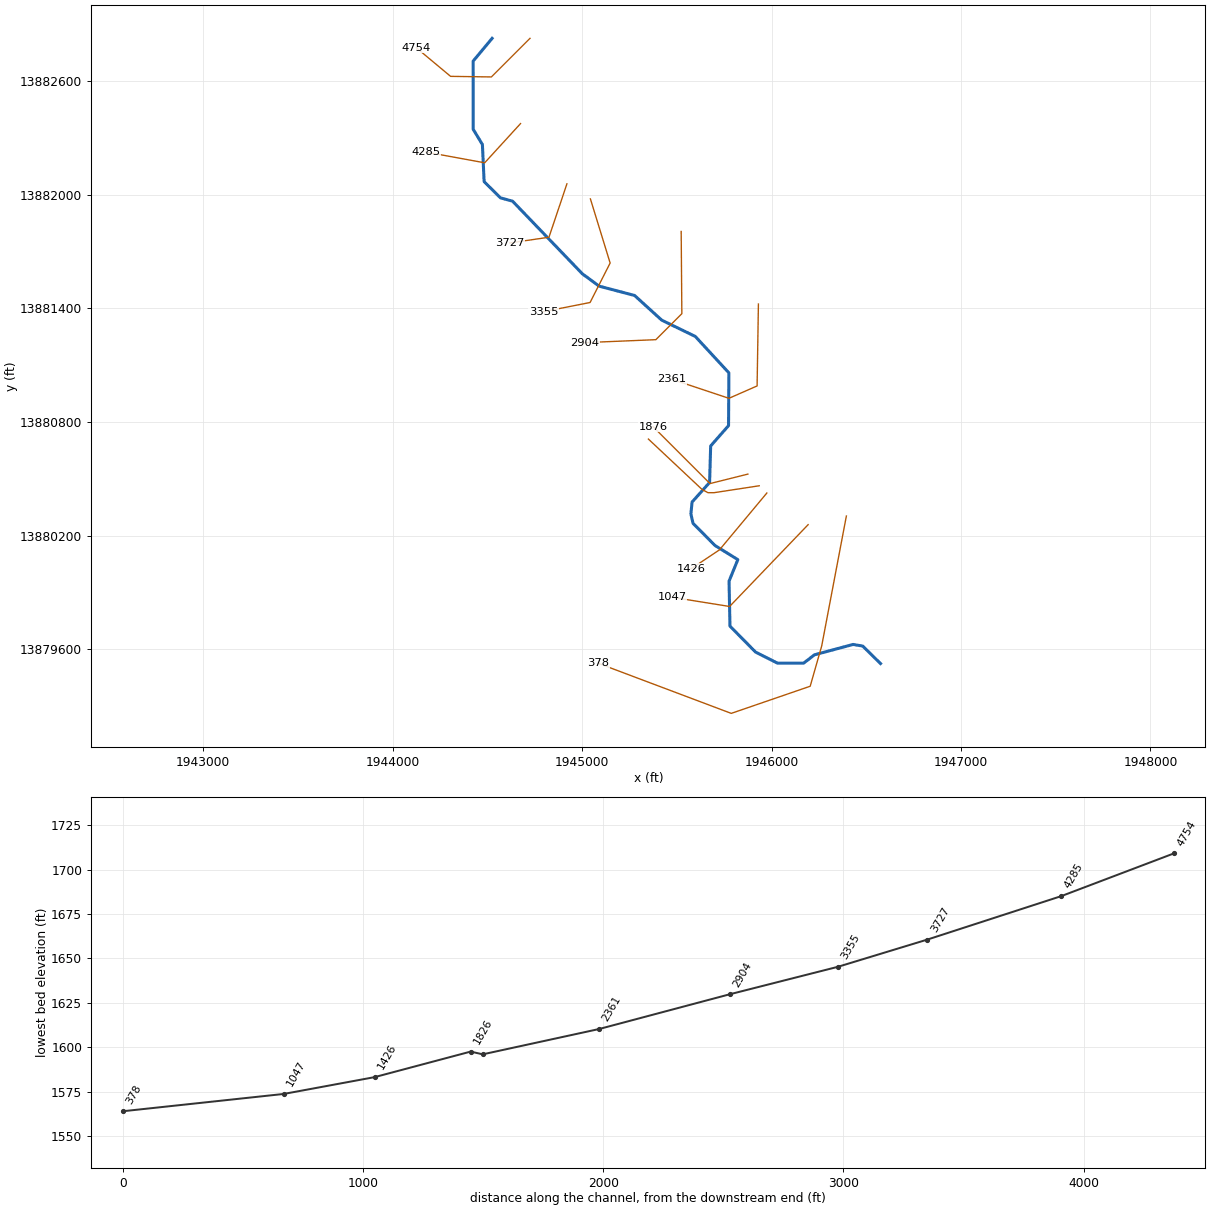
--- Stream0691.prj (project) ---

Proj Title=Stream0691 Base Level Engineering
Current Plan=p01
Default Exp/Contr=0.3,0.1
English Units
Geom File=g01
Flow File=f01
Plan File=p01
BEGIN DESCRIPTION:
Stream0691
END DESCRIPTION:

--- Stream0691.p01 (plan) ---

Plan Title=Multiple Run
Short Identifier=Multiple
Geom File=g01
Flow File=f01
Subcritical Flow
K Sum by GR= 0
Std Step Tol= 0.01
Critical Tol= 0.01
Num of Std Step Trials= 20
Max Error Tol= 0.3
Flow Tol Ratio= 0.001
Split Flow NTrial= 30
Split Flow Tol= 0.02
Split Flow Ratio= 0.02
Log Output Level= 0
Friction Slope Method= 1
Unsteady Friction Slope Method= 2
Unsteady Bridges Friction Slope Method= 1
Parabolic Critical Depth
Global Vel Dist=  1 , 1 , 1
Global Log Level= 0
CheckData=True
Encroach Param= -1, 0, 0, 0
BEGIN DESCRIPTION:
Multiple Run
END DESCRIPTION:

--- Stream0691.f01 (steady flow) ---

Flow Title=Multiple
Number of Profiles=7
Profile Names=10-year,25-year,50-year,1pct_min,100-year,1pct_plu,500-year
River Rch & RM= Stream0691,Reach-1,4754
     481     776    1044     682    1362    2717    2278
Boundary for River Rch & Prof#=Stream0691,Reach-1,1
Up Type=0
Dn Type=3
Dn Slope=0.005
Boundary for River Rch & Prof#=Stream0691,Reach-1,2
Up Type=0
Dn Type=3
Dn Slope=0.005
Boundary for River Rch & Prof#=Stream0691,Reach-1,3
Up Type=0
Dn Type=3
Dn Slope=0.005
Boundary for River Rch & Prof#=Stream0691,Reach-1,4
Up Type=0
Dn Type=3
Dn Slope=0.005
Boundary for River Rch & Prof#=Stream0691,Reach-1,5
Up Type=0
Dn Type=3
Dn Slope=0.005
Boundary for River Rch & Prof#=Stream0691,Reach-1,6
Up Type=0
Dn Type=3
Dn Slope=0.005
Boundary for River Rch & Prof#=Stream0691,Reach-1,7
Up Type=0
Dn Type=3
Dn Slope=0.005

--- Stream0691.g01 (geometry) ---

Geom Title=Existing Conditions

River Reach=Stream0691,Reach-1
Reach XY= 30
      1944525.00     13882825.00      1944424.95     13882705.02
      1944425.07     13882345.03      1944473.78     13882264.49
      1944482.80     13882068.79      1944568.93     13881983.15
      1944633.15     13881965.32      1945001.06     13881582.30
      1945089.60     13881517.19      1945277.10     13881467.71
      1945420.33     13881337.50      1945597.41     13881251.57
      1945774.65     13881059.49      1945772.93     13880780.86
      1945678.55     13880673.53      1945672.93     13880480.86
      1945580.41     13880377.42      1945574.16     13880314.93
      1945585.43     13880265.21      1945701.54     13880148.02
      1945821.96     13880073.58      1945775.54     13879959.79
      1945780.46     13879722.55      1945915.32     13879585.76
      1946030.93     13879527.23      1946169.06     13879527.25
      1946226.60     13879571.14      1946430.04     13879625.85
      1946481.20     13879617.32      1946575.00     13879525.00

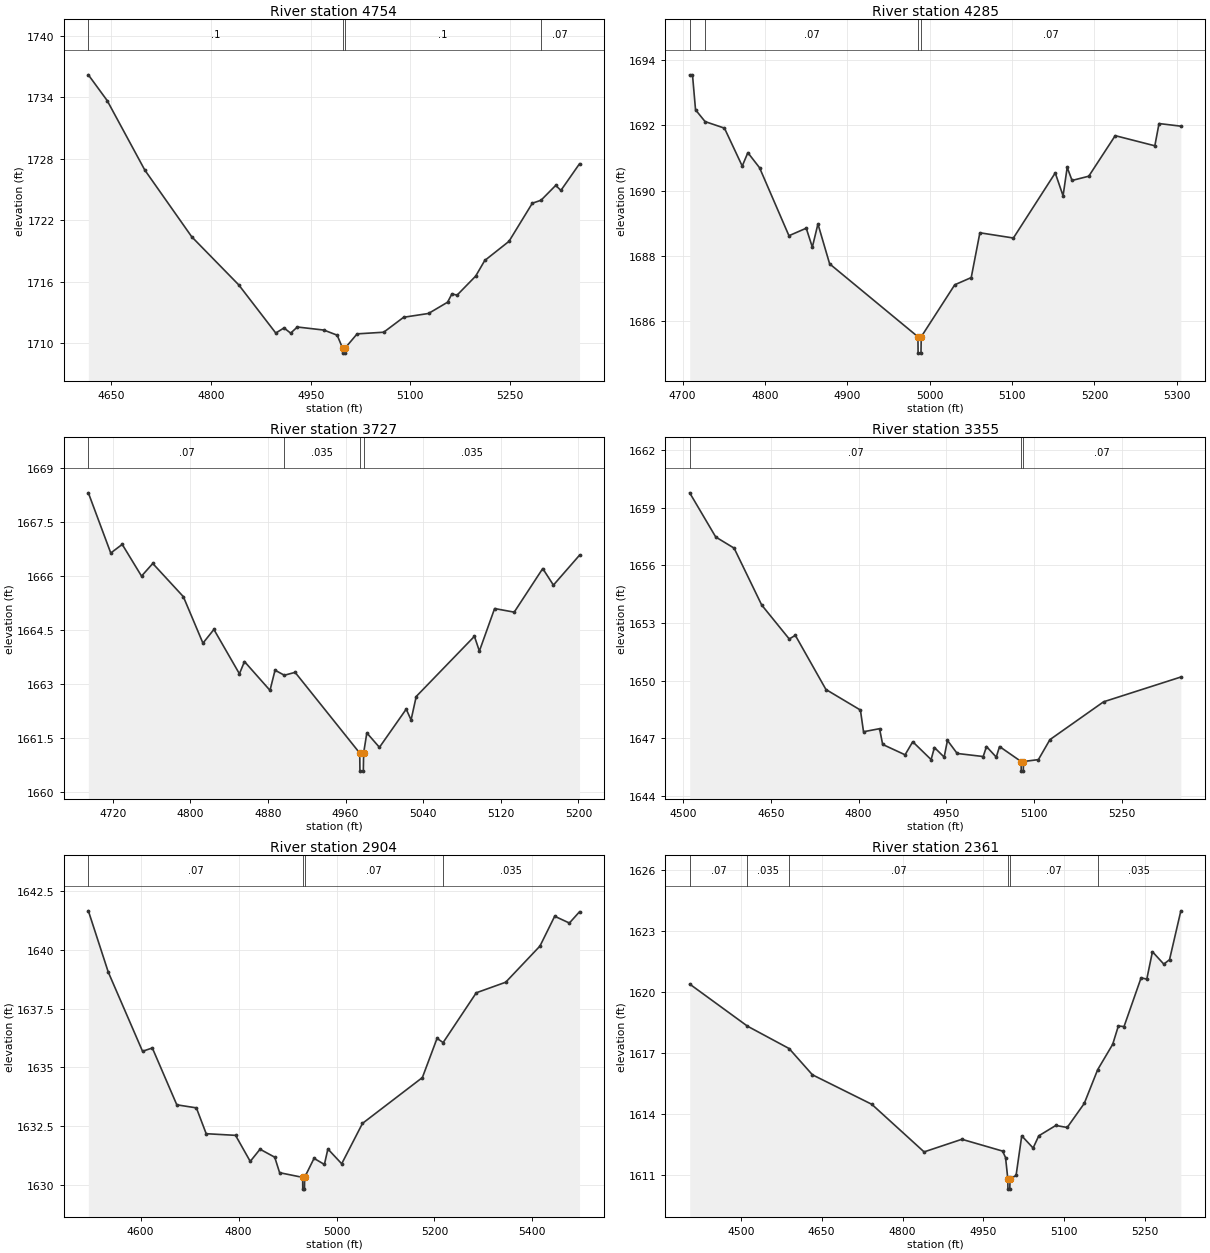
Type RM Length L Ch R = 1,4754,469,469,469
BEGIN DESCRIPTION:
Stream0691 9.0
END DESCRIPTION:
XS GIS Cut Line= 4
      1944725.00     13882825.00      1944521.23     13882621.23
      1944305.83     13882624.31      1944124.99     13882775.01
#Sta/Elev= 30
  4615.5 1736.21  4643.8 1733.70  4700.4 1726.92  4771.1 1720.40  4841.8 1715.71
  4897.5 1711.01  4909.9 1711.51  4919.9 1711.00  4929.9 1711.60  4969.9 1711.30
  4989.9 1710.80  4997.9 1709.55  4998.2 1709.05  5001.7 1709.05  5001.9 1709.55
  5019.9 1710.93  5059.9 1711.09  5089.9 1712.55  5127.3 1712.92  5156.0 1714.02
  5162.5 1714.83  5170.3 1714.71  5198.3 1716.57  5211.9 1718.09  5248.4 1719.96
  5283.5 1723.68  5296.6 1723.97  5318.7 1725.42  5326.5 1724.93  5354.5 1727.53
#Mann=4,-1,0
  4615.5     0.1       0  4997.9    0.05       0  5001.9     0.1       0
  5296.6    0.07       0
Bank Sta=4997.9,5001.9
Exp/Cntr=0.3,0.1

Type RM Length L Ch R = 1,4285,558,558,558
BEGIN DESCRIPTION:
Stream0691 8.0
END DESCRIPTION:
XS GIS Cut Line= 3
      1944674.99     13882374.98      1944485.79     13882168.07
      1944175.03     13882224.99
#Sta/Elev= 30
  4708.6 1693.54  4712.0 1693.54  4715.7 1692.47  4727.3 1692.11  4750.8 1691.91
  4772.4 1690.75  4779.2 1691.16  4793.4 1690.70  4829.1 1688.62  4850.1 1688.85
  4857.5 1688.27  4864.3 1688.98  4878.5 1687.76  4985.7 1685.53  4985.9 1685.03
  4989.4 1685.03  4989.7 1685.53  5030.4 1687.12  5050.4 1687.34  5060.9 1688.71
  5101.6 1688.55  5152.4 1690.54  5161.9 1689.84  5166.9 1690.71  5172.8 1690.31
  5193.1 1690.44  5225.2 1691.68  5273.3 1691.37  5278.4 1692.05  5304.9 1691.97
#Mann=4,-1,0
  4708.6     0.1       0  4727.3    0.07       0  4985.7    0.05       0
  4989.7    0.07       0
Bank Sta=4985.7,4989.7
Exp/Cntr=0.3,0.1

Type RM Length L Ch R = 1,3727,372,372,372
BEGIN DESCRIPTION:
Stream0691 7.0
END DESCRIPTION:
XS GIS Cut Line= 3
      1944919.81     13882056.94      1944825.00     13881775.00
      1944618.40     13881745.17
#Sta/Elev= 30
  4694.9 1668.30  4718.0 1666.63  4729.8 1666.87  4749.7 1665.99  4761.3 1666.34
  4792.8 1665.42  4813.0 1664.13  4824.3 1664.51  4850.6 1663.28  4855.8 1663.62
  4882.1 1662.82  4887.3 1663.38  4896.9 1663.24  4908.0 1663.32  4974.6 1661.08
  4974.8 1660.58  4978.3 1660.58  4978.6 1661.08  4981.9 1661.64  4994.9 1661.24
  5022.5 1662.30  5027.5 1662.00  5032.8 1662.65  5092.8 1664.32  5097.9 1663.91
  5113.6 1665.09  5133.8 1664.99  5163.2 1666.20  5174.2 1665.74  5201.1 1666.57
#Mann=4,-1,0
  4694.9    0.07       0  4896.9   0.035       0  4974.6   0.035       0
  4978.6   0.035       0
Bank Sta=4974.6,4978.6
Exp/Cntr=0.3,0.1

Type RM Length L Ch R = 1,3355,451,451,451
BEGIN DESCRIPTION:
Stream0691 6.0
END DESCRIPTION:
XS GIS Cut Line= 4
      1945043.80     13881977.54      1945147.96     13881639.02
      1945042.06     13881430.69      1944795.48     13881382.07
#Sta/Elev= 30
  4511.3 1659.78  4555.8 1657.48  4587.2 1656.90  4634.3 1653.94  4681.4 1652.17
  4691.8 1652.36  4744.1 1649.54  4803.0 1648.47  4808.3 1647.34  4835.7 1647.50
  4841.0 1646.68  4879.3 1646.14  4892.4 1646.82  4923.8 1645.89  4929.4 1646.52
  4946.1 1646.02  4951.7 1646.89  4968.3 1646.21  5012.8 1646.05  5018.4 1646.57
  5035.1 1646.02  5040.7 1646.57  5077.6 1645.79  5077.8 1645.29  5081.3 1645.29
  5081.6 1645.79  5107.1 1645.89  5126.8 1646.93  5218.5 1648.90  5350.5 1650.19
#Mann=3,-1,0
  4511.3    0.07       0  5077.6    0.05       0  5081.6    0.07       0
Bank Sta=5077.6,5081.6
Exp/Cntr=0.3,0.1

Type RM Length L Ch R = 1,2904,543,543,543
BEGIN DESCRIPTION:
Stream0691 5.0
END DESCRIPTION:
XS GIS Cut Line= 4
      1945522.96     13881805.68      1945526.43     13881371.66
      1945389.28     13881234.51      1945014.30     13881218.89
#Sta/Elev= 30
  4493.1 1641.67  4533.8 1639.06  4603.8 1635.69  4623.8 1635.83  4673.8 1633.41
  4713.8 1633.28  4733.8 1632.18  4793.8 1632.11  4823.8 1631.00  4843.8 1631.52
  4873.8 1631.18  4883.8 1630.52  4930.9 1630.32  4931.1 1629.82  4934.6 1629.82
  4934.9 1630.32  4954.1 1631.13  4975.3 1630.87  4982.4 1631.53  5010.6 1630.90
  5053.1 1632.62  5175.4 1634.57  5205.4 1636.24  5217.8 1636.06  5285.5 1638.18
  5345.6 1638.63  5415.6 1640.17  5445.7 1641.44  5475.7 1641.15  5496.4 1641.63
#Mann=4,-1,0
  4493.1    0.07       0  4930.9    0.05       0  4934.9    0.07       0
  5217.8   0.035       0
Bank Sta=4930.9,4934.9
Exp/Cntr=0.3,0.1

Type RM Length L Ch R = 1,2361,485,485,485
BEGIN DESCRIPTION:
Stream0691 4.0
END DESCRIPTION:
XS GIS Cut Line= 4
      1945930.58     13881422.61      1945923.64     13880990.29
      1945775.00     13880925.00      1945475.04     13881024.99
#Sta/Elev= 30
  4405.3 1620.40  4512.5 1618.33  4589.7 1617.23  4632.9 1615.94  4743.0 1614.49
  4840.0 1612.15  4910.1 1612.77  4985.6 1612.19  4991.1 1611.87  4995.3 1610.82
  4995.5 1610.32  4999.0 1610.32  4999.3 1610.82  5010.6 1610.99  5021.1 1612.94
  5042.2 1612.34  5052.7 1612.94  5084.3 1613.45  5105.4 1613.35  5137.0 1614.53
  5161.9 1616.19  5189.8 1617.44  5200.3 1618.34  5210.8 1618.31  5242.5 1620.71
  5253.0 1620.64  5263.5 1621.99  5284.6 1621.38  5295.2 1621.60  5316.2 1624.00
#Mann=6,-1,0
  4405.3    0.07       0  4512.5   0.035       0  4589.7    0.07       0
  4995.3    0.05       0  4999.3    0.07       0  5161.9   0.035       0
Bank Sta=4995.3,4999.3
Exp/Cntr=0.3,0.1

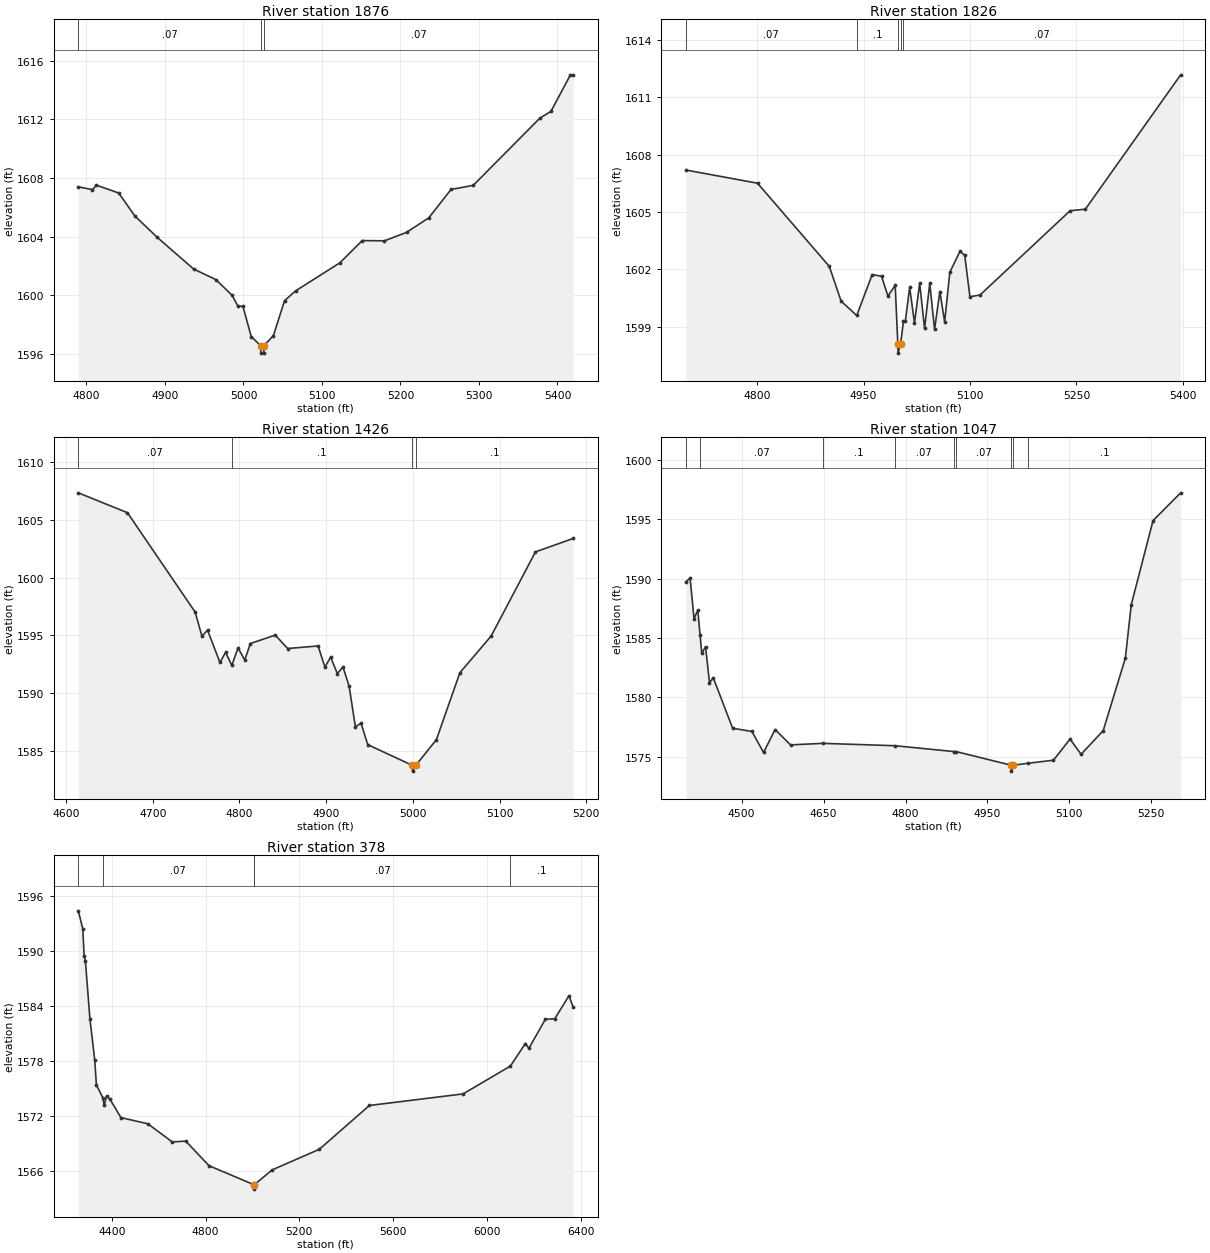
Type RM Length L Ch R = 1,1876,50,50,50
BEGIN DESCRIPTION:
Stream0691 3.0
END DESCRIPTION:
XS GIS Cut Line= 3
      1945874.97     13880524.99      1945675.00     13880475.00
      1945374.99     13880775.01
#Sta/Elev= 30
  4789.6 1607.40  4807.6 1607.21  4812.8 1607.51  4841.1 1606.98  4861.7 1605.41
  4890.1 1603.96  4936.5 1601.80  4964.8 1601.08  4985.4 1600.02  4993.1 1599.26
  4999.3 1599.26  5009.9 1597.20  5022.0 1596.57  5022.3 1596.07  5025.8 1596.07
  5026.0 1596.57  5038.2 1597.27  5052.3 1599.64  5066.4 1600.31  5123.0 1602.23
  5151.3 1603.74  5179.6 1603.72  5207.9 1604.30  5236.1 1605.29  5264.4 1607.22
  5292.7 1607.50  5377.6 1612.08  5391.7 1612.54  5416.5 1615.03  5420.0 1615.03
#Mann=3,-1,0
  4789.6    0.07       0  5022.0    0.05       0  5026.0    0.07       0
Bank Sta=5022,5026
Exp/Cntr=0.3,0.1

Type RM Length L Ch R = 1,1826,400,400,400
BEGIN DESCRIPTION:
Stream0671 D
END DESCRIPTION:
XS GIS Cut Line= 5
      1945934.88     13880463.39      1945697.00     13880426.93
      1945664.02     13880426.93      1945632.77     13880444.29
      1945349.92     13880709.89
#Sta/Elev= 30
  4699.4 1607.20  4800.5 1606.51  4901.6 1602.16  4918.3 1600.34  4940.3 1599.59
  4962.1 1601.73  4975.3 1601.64  4984.2 1600.61  4994.5 1601.16  4998.2 1598.12
  4998.5 1597.62  5002.2 1598.12  5006.2 1599.29  5008.8 1599.29  5014.9 1601.06
  5021.7 1599.19  5029.0 1601.28  5035.9 1598.91  5043.2 1601.28  5050.0 1598.86
  5057.4 1600.84  5064.2 1599.26  5071.5 1601.85  5085.7 1602.94  5092.5 1602.74
  5099.8 1600.57  5114.0 1600.66  5241.0 1605.07  5262.5 1605.15  5396.8 1612.18
#Mann=5,-1,0
  4699.4    0.07       0  4940.3     0.1       0  4998.2    0.05       0
  5002.2     0.1       0  5006.2    0.07       0
Bank Sta=4998.2,5002.2
Exp/Cntr=0.3,0.1

Type RM Length L Ch R = 1,1426,379,379,379
BEGIN DESCRIPTION:
Stream0691 2.0
END DESCRIPTION:
XS GIS Cut Line= 3
      1945975.02     13880425.02      1945725.00     13880125.00
      1945575.02     13880025.01
#Sta/Elev= 30
  4614.1 1607.34  4670.8 1605.62  4748.9 1597.02  4756.7 1594.94  4763.2 1595.46
  4777.5 1592.66  4784.0 1593.54  4791.2 1592.40  4798.3 1593.92  4806.1 1592.88
  4812.6 1594.30  4841.3 1595.03  4855.6 1593.87  4890.7 1594.09  4898.6 1592.25
  4905.1 1593.13  4912.9 1591.70  4919.4 1592.27  4926.5 1590.60  4933.7 1587.10
  4940.2 1587.40  4948.0 1585.55  4999.4 1583.76  4999.6 1583.26  5003.4 1583.76
  5027.2 1585.99  5054.2 1591.77  5090.3 1594.95  5141.4 1602.23  5184.9 1603.39
#Mann=4,-1,0
  4614.1    0.07       0  4791.2     0.1       0  4999.4    0.05       0
  5003.4     0.1       0
Bank Sta=4999.4,5003.4
Exp/Cntr=0.3,0.1

Type RM Length L Ch R = 1,1047,669,669,669
BEGIN DESCRIPTION:
Stream0691 1.0
END DESCRIPTION:
XS GIS Cut Line= 3
      1946193.04     13880258.18      1945778.53     13879826.30
      1945475.03     13879875.00
#Sta/Elev= 30
  4397.7 1589.72  4405.6 1590.05  4412.8 1586.63  4419.7 1587.35  4423.8 1585.28
  4426.9 1583.72  4433.9 1584.27  4441.1 1581.24  4448.0 1581.65  4483.5 1577.40
  4518.8 1577.13  4540.1 1575.36  4561.2 1577.29  4589.5 1576.00  4648.4 1576.13
  4780.5 1575.93  4888.1 1575.44  4892.3 1575.44  4993.3 1574.29  4993.5 1573.79
  4997.3 1574.29  5023.9 1574.45  5070.8 1574.71  5101.2 1576.49  5121.4 1575.21
  5161.9 1577.20  5202.4 1583.30  5213.3 1587.82  5253.1 1594.89  5303.7 1597.23
#Mann=9,-1,0
  4397.7     0.1       0  4423.8    0.07       0  4648.4     0.1       0
  4780.5    0.07       0  4888.1     0.1       0  4892.3    0.07       0
  4993.3    0.05       0  4997.3    0.07       0  5023.9     0.1       0
Bank Sta=4993.3,4997.3
Exp/Cntr=0.3,0.1

Type RM Length L Ch R = 1,378,0,0,0
BEGIN DESCRIPTION:
Stream0691 0.0
END DESCRIPTION:
XS GIS Cut Line= 5
      1946394.85     13880303.77      1946264.64     13879617.97
      1946203.87     13879405.29      1945787.21     13879262.06
      1945084.03     13879526.84
#Sta/Elev= 30
  4257.3 1594.39  4276.4 1592.45  4282.4 1589.44  4287.5 1588.96  4306.9 1582.64
  4327.3 1578.17  4334.6 1575.43  4361.8 1574.04  4368.0 1573.19  4378.2 1574.24
  4392.0 1573.89  4439.2 1571.87  4553.8 1571.20  4658.3 1569.22  4715.7 1569.31
  4815.1 1566.63  5004.9 1564.58  5005.2 1564.08  5008.9 1564.58  5084.9 1566.18
  5285.7 1568.42  5499.1 1573.19  5898.9 1574.45  6100.7 1577.48  6164.4 1579.94
  6179.6 1579.42  6249.9 1582.58  6289.8 1582.63  6350.3 1585.13  6368.5 1583.92
#Mann=5,-1,0
  4257.3     0.1       0  4361.8    0.07       0  5004.9    0.05       0
  5008.9    0.07       0  6100.7     0.1       0
Bank Sta=5004.9,5008.9
Exp/Cntr=0.3,0.1

Chan Stop Cuts=-1