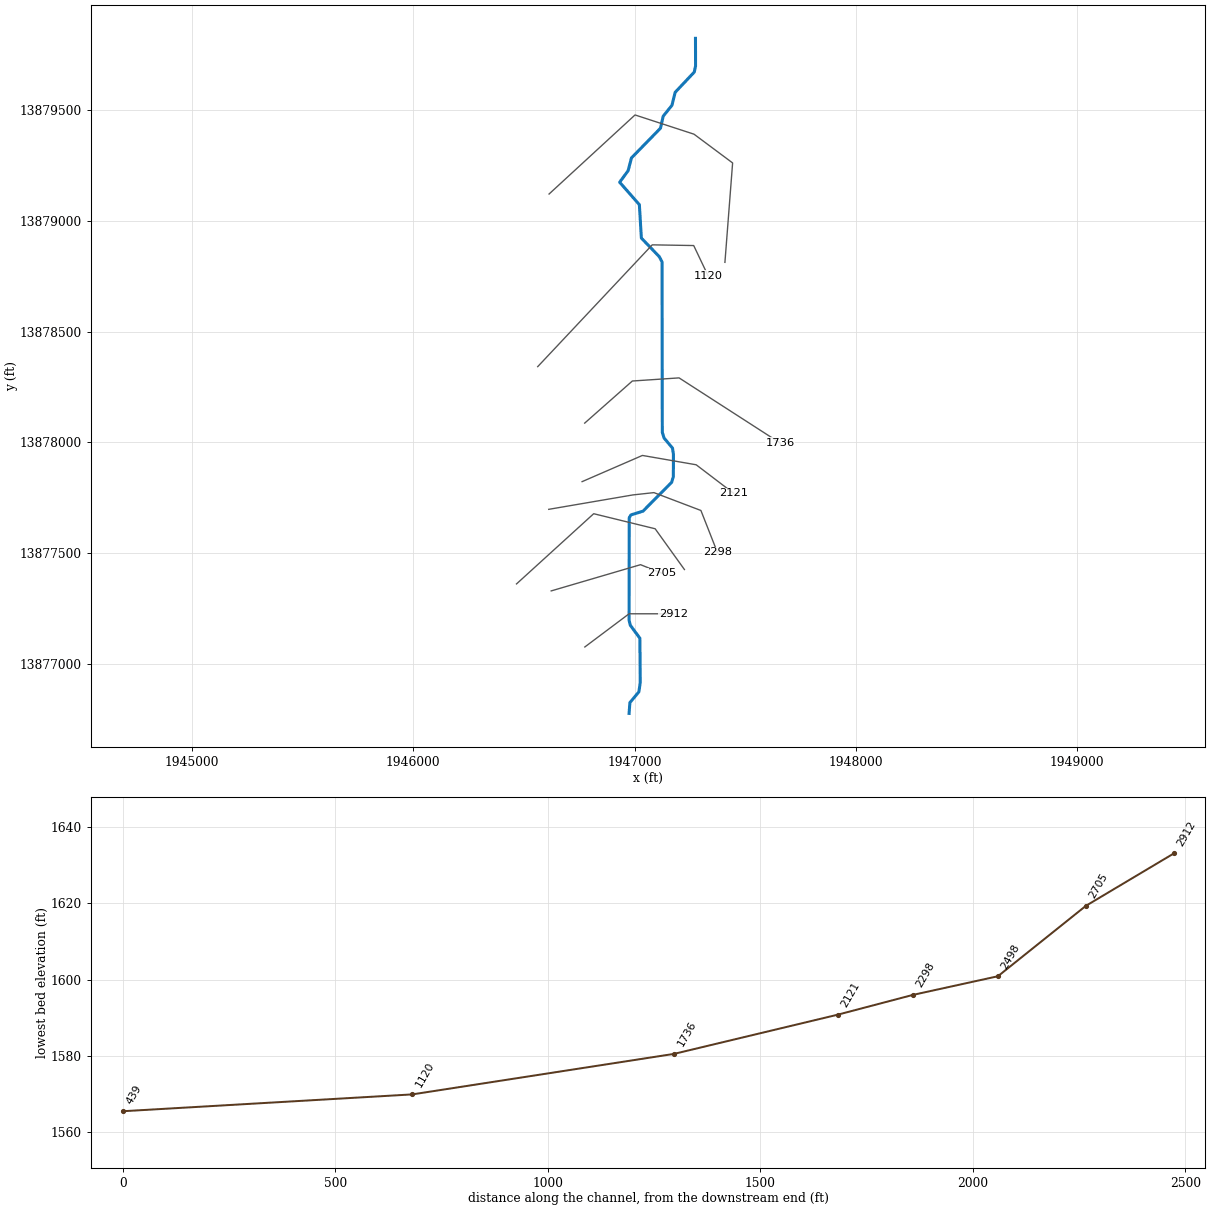
--- Stream0692.prj (project) ---

Proj Title=Stream0692 Base Level Engineering
Current Plan=p01
Default Exp/Contr=0.3,0.1
English Units
Geom File=g01
Flow File=f01
Plan File=p01
BEGIN DESCRIPTION:
Stream0692
END DESCRIPTION:

--- Stream0692.p01 (plan) ---

Plan Title=Multiple Run
Short Identifier=Multiple
Geom File=g01
Flow File=f01
Subcritical Flow
K Sum by GR= 0
Std Step Tol= 0.01
Critical Tol= 0.01
Num of Std Step Trials= 20
Max Error Tol= 0.3
Flow Tol Ratio= 0.001
Split Flow NTrial= 30
Split Flow Tol= 0.02
Split Flow Ratio= 0.02
Log Output Level= 0
Friction Slope Method= 1
Unsteady Friction Slope Method= 2
Unsteady Bridges Friction Slope Method= 1
Parabolic Critical Depth
Global Vel Dist=  1 , 1 , 1
Global Log Level= 0
CheckData=True
Encroach Param= -1, 0, 0, 0
BEGIN DESCRIPTION:
Multiple Run
END DESCRIPTION:

--- Stream0692.f01 (steady flow) ---

Flow Title=Multiple
Number of Profiles=7
Profile Names=10-year,25-year,50-year,1pct_min,100-year,1pct_plu,500-year
River Rch & RM= Stream0692,Reach-1,2912
     280     433     567     362     722    1440    1146
Boundary for River Rch & Prof#=Stream0692,Reach-1,1
Up Type=0
Dn Type=3
Dn Slope=0.005
Boundary for River Rch & Prof#=Stream0692,Reach-1,2
Up Type=0
Dn Type=3
Dn Slope=0.005
Boundary for River Rch & Prof#=Stream0692,Reach-1,3
Up Type=0
Dn Type=3
Dn Slope=0.005
Boundary for River Rch & Prof#=Stream0692,Reach-1,4
Up Type=0
Dn Type=3
Dn Slope=0.005
Boundary for River Rch & Prof#=Stream0692,Reach-1,5
Up Type=0
Dn Type=3
Dn Slope=0.005
Boundary for River Rch & Prof#=Stream0692,Reach-1,6
Up Type=0
Dn Type=3
Dn Slope=0.005
Boundary for River Rch & Prof#=Stream0692,Reach-1,7
Up Type=0
Dn Type=3
Dn Slope=0.005

--- Stream0692.g01 (geometry) ---

Geom Title=Existing Conditions

River Reach=Stream0692,Reach-1
Reach XY= 30
      1946975.00     13876775.00      1946978.65     13876823.49
      1947019.47     13876872.58      1947025.46     13876914.81
      1947023.78     13877114.50      1946980.75     13877172.67
      1946975.07     13877195.03      1946975.66     13877659.17
      1946983.11     13877671.61      1947037.95     13877688.74
      1947167.19     13877818.81      1947175.06     13877844.99
      1947175.39     13877945.13      1947171.23     13877973.43
      1947133.14     13878018.94      1947125.07     13878045.03
      1947123.94     13878814.56      1947111.60     13878838.31
      1947030.48     13878922.56      1947021.43     13879073.53
      1946932.30     13879174.92      1946970.53     13879226.65
      1946985.75     13879284.68      1947116.86     13879418.94
      1947129.19     13879473.26      1947168.90     13879522.81
      1947183.16     13879581.05      1947269.56     13879672.54
      1947275.37     13879699.85      1947275.00     13879825.00

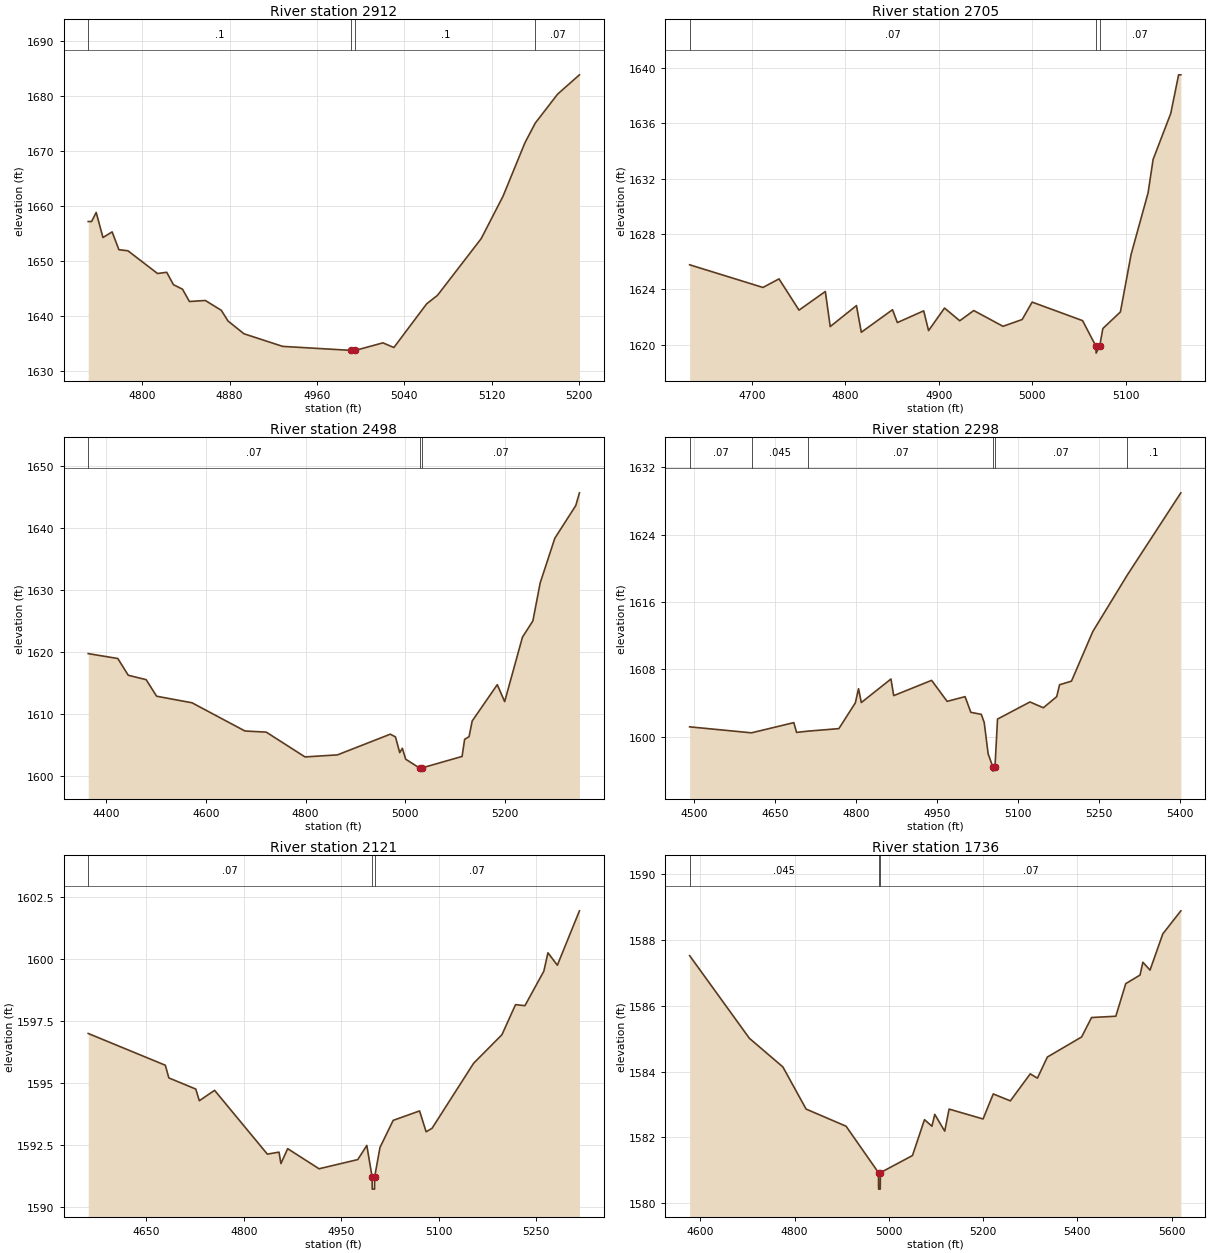
Type RM Length L Ch R = 1,2912,207,207,207
BEGIN DESCRIPTION:
Stream0692 4.0
END DESCRIPTION:
XS GIS Cut Line= 3
      1946775.02     13877075.01      1946975.00     13877225.00
      1947175.02     13877225.00
#Sta/Elev= 30
  4750.5 1657.13  4753.6 1657.13  4757.8 1658.78  4764.0 1654.22  4772.4 1655.24
  4778.6 1652.00  4786.9 1651.80  4814.0 1647.67  4822.4 1647.89  4828.6 1645.63
  4836.9 1644.81  4843.2 1642.57  4857.8 1642.76  4872.4 1640.97  4878.6 1639.02
  4893.2 1636.70  4928.6 1634.41  4991.2 1633.68  4991.4 1633.18  4995.2 1633.68
  5020.5 1635.05  5030.5 1634.20  5060.5 1642.14  5070.5 1643.71  5110.5 1654.02
  5130.5 1661.73  5150.5 1671.43  5160.0 1675.03  5180.5 1680.31  5200.5 1683.82
#Mann=4,-1,0
  4750.5     0.1       0  4991.2    0.05       0  4995.2     0.1       0
  5160.0    0.07       0
Bank Sta=4991.2,4995.2
Exp/Cntr=0.3,0.1

Type RM Length L Ch R = 1,2705,207,207,207
BEGIN DESCRIPTION:
Mapping XS 56c5708d
END DESCRIPTION:
XS GIS Cut Line= 3
      1946623.13     13877328.35      1947026.75     13877446.84
      1947124.47     13877407.74
#Sta/Elev= 30
  4633.3 1625.78  4711.8 1624.14  4729.0 1624.76  4750.4 1622.50  4778.6 1623.85
  4783.8 1621.31  4811.9 1622.83  4817.1 1620.90  4850.5 1622.53  4855.7 1621.60
  4883.9 1622.45  4889.1 1621.02  4906.2 1622.65  4922.5 1621.73  4937.5 1622.47
  4968.8 1621.33  4989.3 1621.82  5000.0 1623.08  5054.0 1621.74  5068.3 1619.89
  5068.5 1619.39  5072.3 1619.89  5075.7 1621.17  5094.5 1622.37  5105.9 1626.52
  5124.1 1630.98  5129.5 1633.40  5148.4 1636.73  5156.8 1639.52  5159.2 1639.52
#Mann=3,-1,0
  4633.3    0.07       0  5068.3    0.05       0  5072.3    0.07       0
Bank Sta=5068.3,5072.3
Exp/Cntr=0.3,0.1

Type RM Length L Ch R = 1,2498,200,200,200
BEGIN DESCRIPTION:
Stream0692 3.0
END DESCRIPTION:
XS GIS Cut Line= 4
      1946466.38     13877359.91      1946815.06     13877677.13
      1947092.77     13877609.12      1947225.01     13877424.98
#Sta/Elev= 30
  4364.6 1619.81  4423.9 1619.02  4444.8 1616.32  4480.6 1615.61  4501.6 1612.94
  4572.5 1611.88  4678.6 1607.33  4721.2 1607.15  4798.9 1603.15  4863.8 1603.48
  4969.8 1606.82  4980.1 1606.37  4988.6 1603.84  4993.8 1604.54  5000.6 1602.78
  5028.3 1601.36  5028.5 1600.86  5032.3 1601.36  5113.5 1603.23  5118.6 1605.99
  5127.5 1606.42  5133.7 1608.94  5184.0 1614.80  5198.8 1612.07  5234.4 1622.46
  5255.3 1625.08  5270.0 1631.23  5299.3 1638.42  5341.2 1643.68  5348.6 1645.74
#Mann=3,-1,0
  4364.6    0.07       0  5028.3    0.05       0  5032.3    0.07       0
Bank Sta=5028.3,5032.3
Exp/Cntr=0.3,0.1

Type RM Length L Ch R = 1,2298,177,177,177
BEGIN DESCRIPTION:
Stream0692 D
END DESCRIPTION:
XS GIS Cut Line= 5
      1946612.05     13877696.93      1946992.24     13877762.03
      1947087.30     13877772.44      1947299.54     13877691.72
      1947373.76     13877502.91
#Sta/Elev= 30
  4491.2 1601.20  4606.0 1600.49  4684.5 1601.70  4689.6 1600.54  4710.9 1600.69
  4768.1 1600.99  4798.6 1604.04  4804.6 1605.72  4809.7 1604.08  4864.7 1606.87
  4869.8 1604.90  4940.1 1606.71  4968.9 1604.22  5002.2 1604.78  5012.9 1602.92
  5032.3 1602.68  5037.7 1601.72  5045.0 1598.00  5053.7 1596.45  5053.9 1595.95
  5057.7 1596.45  5062.4 1602.12  5122.6 1604.15  5147.4 1603.46  5172.2 1604.78
  5177.5 1606.19  5199.6 1606.62  5239.1 1612.49  5303.4 1619.22  5402.5 1628.94
#Mann=6,-1,0
  4491.2    0.07       0  4606.0   0.045       0  4710.9    0.07       0
  5053.7    0.05       0  5057.7    0.07       0  5303.4     0.1       0
Bank Sta=5053.7,5057.7
Exp/Cntr=0.3,0.1

Type RM Length L Ch R = 1,2121,385,385,385
BEGIN DESCRIPTION:
Mapping XS ff998af8
END DESCRIPTION:
XS GIS Cut Line= 4
      1946762.74     13877822.05      1947035.23     13877940.40
      1947278.15     13877898.23      1947447.18     13877769.49
#Sta/Elev= 30
  4560.6 1597.01  4679.3 1595.73  4684.7 1595.22  4726.2 1594.77  4731.6 1594.30
  4755.1 1594.72  4836.3 1592.15  4854.3 1592.23  4857.2 1591.77  4867.6 1592.37
  4915.9 1591.56  4975.5 1591.93  4989.4 1592.50  4997.5 1591.24  4997.8 1590.74
  5001.3 1590.74  5001.5 1591.24  5009.7 1592.42  5030.0 1593.51  5070.6 1593.89
  5080.7 1593.05  5089.8 1593.19  5153.8 1595.81  5197.4 1596.96  5218.3 1598.17
  5232.8 1598.13  5261.9 1599.52  5268.2 1600.26  5282.7 1599.76  5316.7 1601.95
#Mann=3,-1,0
  4560.6    0.07       0  4997.5    0.05       0  5001.5    0.07       0
Bank Sta=4997.5,5001.5
Exp/Cntr=0.3,0.1

Type RM Length L Ch R = 1,1736,616,616,616
BEGIN DESCRIPTION:
Stream0692 2.0
END DESCRIPTION:
XS GIS Cut Line= 4
      1946774.49     13878086.51      1946989.75     13878276.72
      1947200.84     13878290.82      1947657.75     13877996.33
#Sta/Elev= 30
  4577.2 1587.52  4704.0 1585.01  4775.1 1584.14  4824.4 1582.86  4909.2 1582.34
  4978.0 1580.93  4978.2 1580.43  4981.7 1580.43  4982.0 1580.93  5050.1 1581.45
  5075.6 1582.54  5091.4 1582.34  5097.4 1582.70  5118.5 1582.19  5127.8 1582.86
  5199.9 1582.56  5221.5 1583.32  5257.8 1583.11  5300.0 1583.93  5315.2 1583.80
  5336.3 1584.44  5409.0 1585.05  5430.1 1585.64  5481.6 1585.68  5502.7 1586.67
  5533.0 1586.93  5539.0 1587.32  5554.2 1587.08  5581.3 1588.18  5619.6 1588.88
#Mann=3,-1,0
  4577.2   0.045       0  4978.0    0.05       0  4982.0    0.07       0
Bank Sta=4978,4982
Exp/Cntr=0.3,0.1

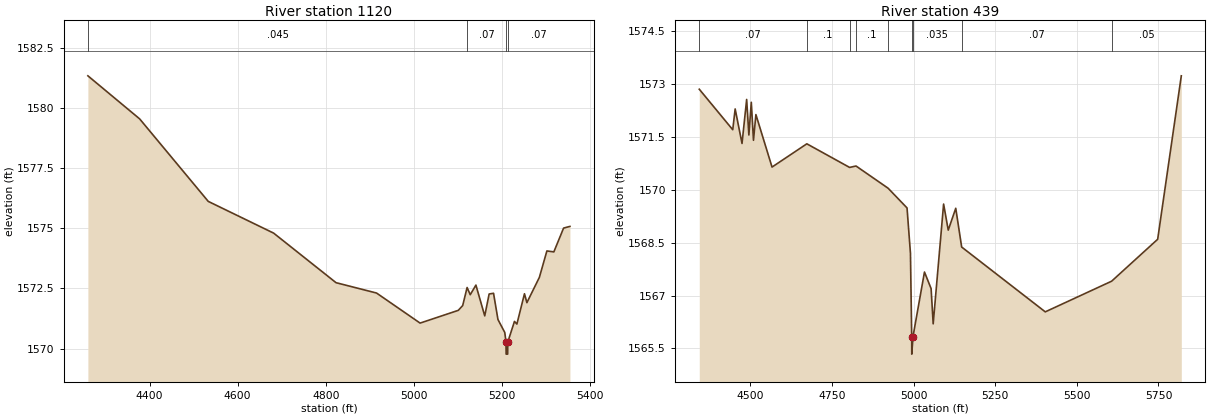
Type RM Length L Ch R = 1,1120,681,681,681
BEGIN DESCRIPTION:
Stream0692 1.0
END DESCRIPTION:
XS GIS Cut Line= 4
      1946562.20     13878341.61      1947079.64     13878891.95
      1947266.98     13878888.76      1947332.09     13878752.04
#Sta/Elev= 30
  4260.0 1581.34  4377.5 1579.55  4533.2 1576.12  4681.7 1574.80  4823.3 1572.74
  4915.2 1572.31  5014.1 1571.06  5100.8 1571.59  5110.8 1571.79  5120.8 1572.54
  5127.9 1572.24  5140.8 1572.64  5160.8 1571.36  5170.8 1572.27  5180.8 1572.30
  5190.8 1571.21  5206.3 1570.67  5209.1 1570.27  5209.4 1569.77  5212.9 1569.77
  5213.1 1570.27  5228.3 1571.13  5233.8 1571.02  5251.0 1572.28  5256.5 1571.91
  5284.8 1572.96  5301.9 1574.06  5317.7 1574.02  5339.8 1575.01  5354.2 1575.08
#Mann=4,-1,0
  4260.0   0.045       0  5120.8    0.07       0  5209.1   0.045       0
  5213.1    0.07       0
Bank Sta=5209.1,5213.1
Exp/Cntr=0.3,0.1

Type RM Length L Ch R = 1,439,0,0,0
BEGIN DESCRIPTION:
Stream0692 0.0
END DESCRIPTION:
XS GIS Cut Line= 5
      1946613.46     13879121.57      1947001.81     13879478.84
      1947268.34     13879391.92      1947442.77     13879262.03
      1947408.04     13878812.78
#Sta/Elev= 30
  4343.8 1572.86  4446.3 1571.71  4453.7 1572.30  4474.7 1571.32  4488.9 1572.57
  4495.7 1571.56  4503.1 1572.49  4509.8 1571.41  4517.2 1572.14  4566.6 1570.65
  4673.2 1571.31  4804.1 1570.64  4823.8 1570.68  4922.0 1570.05  4980.0 1569.49
  4990.5 1568.20  4994.3 1565.84  4994.5 1565.34  4998.3 1565.84  5033.4 1567.67
  5053.7 1567.20  5060.1 1566.20  5092.0 1569.60  5106.2 1568.86  5129.2 1569.48
  5147.3 1568.38  5403.3 1566.54  5606.5 1567.41  5747.5 1568.60  5819.9 1573.24
#Mann=9,-1,0
  4343.8    0.07       0  4673.2     0.1       0  4804.1   0.035       0
  4823.8     0.1       0  4922.0   0.035       0  4994.3   0.035       0
  4998.3   0.035       0  5147.3    0.07       0  5606.5    0.05       0
Bank Sta=4994.3,4998.3
Exp/Cntr=0.3,0.1

Chan Stop Cuts=-1