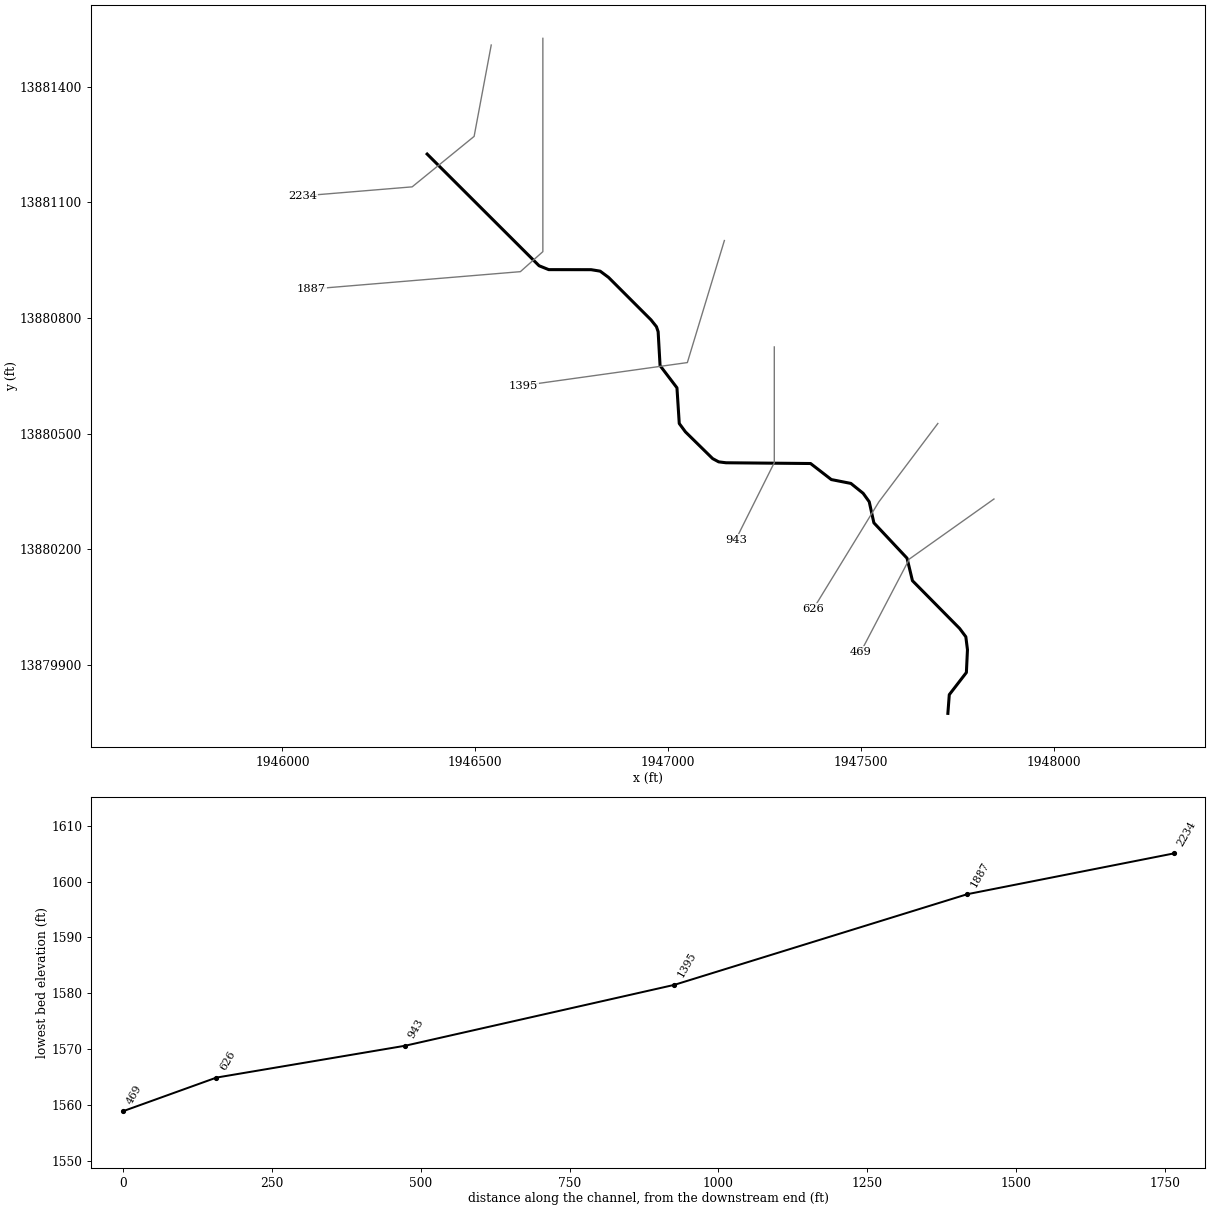
--- Stream0693.prj (project) ---

Proj Title=Stream0693 Base Level Engineering
Current Plan=p01
Default Exp/Contr=0.3,0.1
English Units
Geom File=g01
Flow File=f01
Plan File=p01
BEGIN DESCRIPTION:
Stream0693
END DESCRIPTION:

--- Stream0693.p01 (plan) ---

Plan Title=Multiple Run
Short Identifier=Multiple
Geom File=g01
Flow File=f01
Subcritical Flow
K Sum by GR= 0
Std Step Tol= 0.01
Critical Tol= 0.01
Num of Std Step Trials= 20
Max Error Tol= 0.3
Flow Tol Ratio= 0.001
Split Flow NTrial= 30
Split Flow Tol= 0.02
Split Flow Ratio= 0.02
Log Output Level= 0
Friction Slope Method= 1
Unsteady Friction Slope Method= 2
Unsteady Bridges Friction Slope Method= 1
Parabolic Critical Depth
Global Vel Dist=  1 , 1 , 1
Global Log Level= 0
CheckData=True
Encroach Param= -1, 0, 0, 0
BEGIN DESCRIPTION:
Multiple Run
END DESCRIPTION:

--- Stream0693.f01 (steady flow) ---

Flow Title=Multiple
Number of Profiles=7
Profile Names=10-year,25-year,50-year,1pct_min,100-year,1pct_plu,500-year
River Rch & RM= Stream0693,Reach-1,2234
     603     991    1349     892    1781    3553    3050
Boundary for River Rch & Prof#=Stream0693,Reach-1,1
Up Type=0
Dn Type=3
Dn Slope=0.005
Boundary for River Rch & Prof#=Stream0693,Reach-1,2
Up Type=0
Dn Type=3
Dn Slope=0.005
Boundary for River Rch & Prof#=Stream0693,Reach-1,3
Up Type=0
Dn Type=3
Dn Slope=0.005
Boundary for River Rch & Prof#=Stream0693,Reach-1,4
Up Type=0
Dn Type=3
Dn Slope=0.005
Boundary for River Rch & Prof#=Stream0693,Reach-1,5
Up Type=0
Dn Type=3
Dn Slope=0.005
Boundary for River Rch & Prof#=Stream0693,Reach-1,6
Up Type=0
Dn Type=3
Dn Slope=0.005
Boundary for River Rch & Prof#=Stream0693,Reach-1,7
Up Type=0
Dn Type=3
Dn Slope=0.005

--- Stream0693.g01 (geometry) ---

Geom Title=Existing Conditions

River Reach=Stream0693,Reach-1
Reach XY= 30
      1946375.00     13881225.00      1946665.20     13880935.48
      1946690.16     13880925.40      1946800.11     13880925.27
      1946823.53     13880921.46      1946845.16     13880905.39
      1946955.37     13880795.16      1946969.48     13880777.43
      1946973.84     13880764.52      1946978.86     13880676.60
      1947022.64     13880619.02      1947028.61     13880526.48
      1947044.61     13880504.80      1947115.17     13880435.47
      1947130.84     13880427.05      1947149.87     13880424.70
      1947369.07     13880422.76      1947422.85     13880381.15
      1947473.58     13880371.14      1947505.37     13880345.48
      1947521.11     13880323.57      1947533.18     13880268.98
      1947619.13     13880177.28      1947633.16     13880118.95
      1947755.42     13879995.15      1947771.54     13879973.51
      1947775.78     13879940.09      1947772.98     13879880.92
      1947728.65     13879823.49      1947725.00     13879775.00

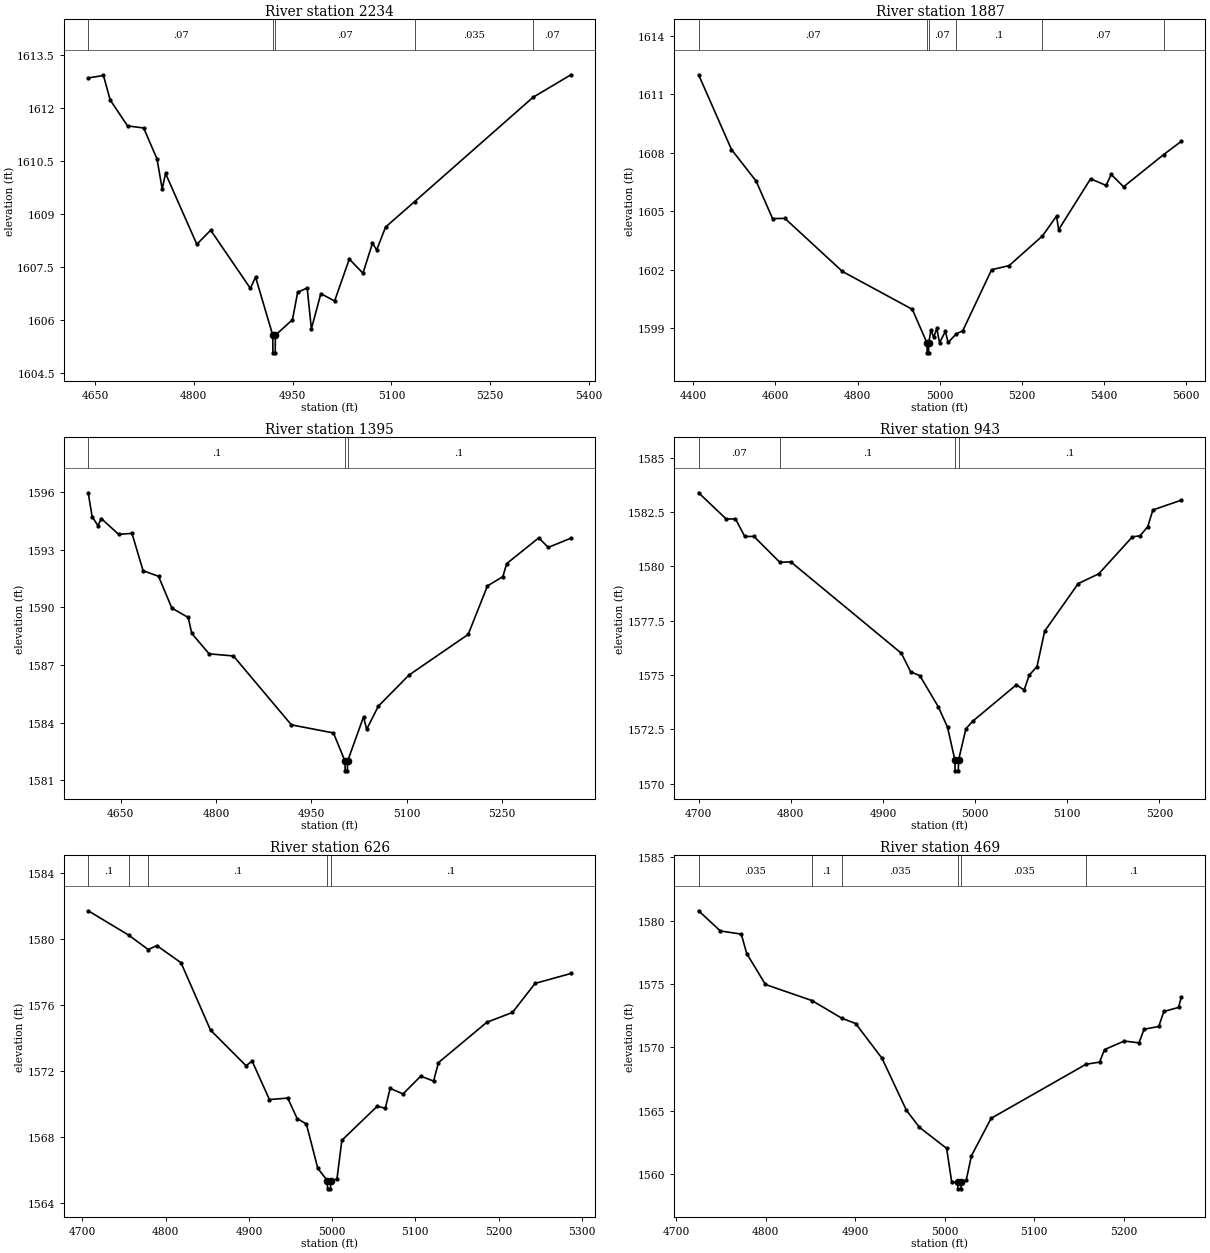
Type RM Length L Ch R = 1,2234,347,347,347
BEGIN DESCRIPTION:
Stream0693 5.0
END DESCRIPTION:
XS GIS Cut Line= 4
      1946541.15     13881507.66      1946496.78     13881270.80
      1946336.18     13881140.00      1946052.86     13881116.53
#Sta/Elev= 30
  4639.9 1612.86  4663.0 1612.93  4673.1 1612.24  4699.5 1611.50  4724.0 1611.44
  4744.3 1610.56  4752.1 1609.71  4757.2 1610.15  4804.7 1608.14  4825.7 1608.54
  4885.9 1606.89  4893.8 1607.21  4919.9 1605.56  4920.1 1605.06  4923.6 1605.06
  4923.9 1605.56  4949.8 1606.00  4957.7 1606.78  4972.1 1606.90  4978.5 1605.74
  4992.9 1606.74  5013.7 1606.53  5036.0 1607.72  5056.8 1607.32  5071.2 1608.17
  5077.6 1607.98  5091.1 1608.63  5135.1 1609.35  5314.8 1612.31  5372.3 1612.95
#Mann=5,-1,0
  4639.9    0.07       0  4919.9    0.05       0  4923.9    0.07       0
  5135.1   0.035       0  5314.8    0.07       0
Bank Sta=4919.9,4923.9
Exp/Cntr=0.3,0.1

Type RM Length L Ch R = 1,1887,492,492,492
BEGIN DESCRIPTION:
Stream0693 4.0
END DESCRIPTION:
XS GIS Cut Line= 4
      1946675.00     13881525.03      1946675.00     13880972.00
      1946616.70     13880920.14      1946075.04     13880875.00
#Sta/Elev= 30
  4413.2 1612.00  4493.2 1608.17  4553.2 1606.55  4593.2 1604.63  4623.2 1604.64
  4763.2 1601.92  4933.2 1599.98  4969.1 1598.25  4969.3 1597.75  4972.8 1597.75
  4973.1 1598.25  4978.6 1598.92  4985.3 1598.55  4992.8 1599.00  4999.5 1598.27
  5013.7 1598.85  5020.4 1598.28  5040.0 1598.72  5056.0 1598.88  5126.2 1602.01
  5168.9 1602.22  5249.9 1603.74  5284.3 1604.76  5289.3 1604.06  5367.1 1606.67
  5404.7 1606.33  5417.3 1606.89  5447.4 1606.26  5544.9 1607.91  5587.8 1608.59
#Mann=6,-1,0
  4413.2    0.07       0  4969.1    0.05       0  4973.1    0.07       0
  5040.0     0.1       0  5249.9    0.07       0  5544.9     0.1       0
Bank Sta=4969.1,4973.1
Exp/Cntr=0.3,0.1

Type RM Length L Ch R = 1,1395,452,452,452
BEGIN DESCRIPTION:
Stream0693 3.0
END DESCRIPTION:
XS GIS Cut Line= 3
      1947145.59     13881000.84      1947049.61     13880684.46
      1946624.97     13880625.00
#Sta/Elev= 30
  4598.9 1595.95  4605.0 1594.71  4614.2 1594.24  4619.4 1594.61  4646.8 1593.79
  4667.7 1593.84  4685.2 1591.90  4709.5 1591.61  4730.4 1589.96  4756.2 1589.47
  4761.8 1588.64  4789.1 1587.58  4827.3 1587.47  4918.5 1583.89  4984.7 1583.47
  5002.9 1582.00  5003.1 1581.50  5006.6 1581.50  5006.9 1582.00  5032.0 1584.30
  5037.0 1583.66  5055.3 1584.86  5103.3 1586.47  5196.7 1588.59  5227.0 1591.11
  5251.2 1591.59  5257.3 1592.27  5307.8 1593.61  5322.6 1593.11  5358.3 1593.59
#Mann=3,-1,0
  4598.9     0.1       0  5002.9    0.05       0  5006.9     0.1       0
Bank Sta=5002.9,5006.9
Exp/Cntr=0.3,0.1

Type RM Length L Ch R = 1,943,317,317,317
BEGIN DESCRIPTION:
Stream0693 2.0
END DESCRIPTION:
XS GIS Cut Line= 3
      1947275.00     13880724.97      1947275.00     13880425.00
      1947174.99     13880224.98
#Sta/Elev= 30
  4700.1 1583.39  4730.1 1582.18  4740.1 1582.19  4750.1 1581.38  4760.1 1581.38
  4788.2 1580.19  4800.1 1580.21  4920.1 1576.00  4930.1 1575.15  4940.1 1574.97
  4960.1 1573.54  4970.1 1572.60  4978.1 1571.09  4978.3 1570.59  4981.8 1570.59
  4982.1 1571.09  4990.1 1572.53  4997.6 1572.88  5044.8 1574.55  5053.2 1574.31
  5058.8 1575.00  5067.2 1575.39  5075.5 1577.02  5111.9 1579.21  5134.2 1579.66
  5170.6 1581.36  5179.0 1581.41  5187.3 1581.83  5192.9 1582.60  5223.7 1583.05
#Mann=4,-1,0
  4700.1    0.07       0  4788.2     0.1       0  4978.1    0.05       0
  4982.1     0.1       0
Bank Sta=4978.1,4982.1
Exp/Cntr=0.3,0.1

Type RM Length L Ch R = 1,626,157,157,157
BEGIN DESCRIPTION:
Stream0693 R
END DESCRIPTION:
XS GIS Cut Line= 3
      1947698.98     13880526.55      1947546.18     13880323.40
      1947376.06     13880045.66
#Sta/Elev= 30
  4707.0 1581.73  4755.4 1580.26  4779.1 1579.38  4789.4 1579.62  4818.5 1578.58
  4853.9 1574.50  4896.6 1572.34  4903.9 1572.62  4924.7 1570.29  4946.7 1570.38
  4958.0 1569.14  4969.1 1568.81  4982.8 1566.12  4994.3 1565.38  4994.5 1564.88
  4998.0 1564.88  4998.3 1565.38  5005.8 1565.47  5011.7 1567.82  5054.3 1569.89
  5063.9 1569.76  5069.7 1570.97  5085.2 1570.63  5106.5 1571.71  5121.9 1571.41
  5127.8 1572.53  5185.8 1574.97  5216.7 1575.57  5243.9 1577.33  5286.9 1577.93
#Mann=5,-1,0
  4707.0     0.1       0  4755.4   0.035       0  4779.1     0.1       0
  4994.3    0.05       0  4998.3     0.1       0
Bank Sta=4994.3,4998.3
Exp/Cntr=0.3,0.1

Type RM Length L Ch R = 1,469,0,0,0
BEGIN DESCRIPTION:
Stream0693 1.0
END DESCRIPTION:
XS GIS Cut Line= 3
      1947844.45     13880330.73      1947625.00     13880175.00
      1947499.65     13879935.17
#Sta/Elev= 30
  4724.9 1580.77  4749.2 1579.18  4772.6 1578.93  4778.7 1577.40  4799.6 1574.96
  4851.7 1573.69  4885.0 1572.30  4900.5 1571.88  4930.0 1569.14  4957.2 1565.05
  4971.8 1563.70  5002.2 1562.04  5007.9 1559.39  5014.6 1559.35  5014.8 1558.85
  5018.3 1558.85  5018.6 1559.35  5024.3 1559.58  5029.9 1561.45  5052.0 1564.41
  5158.1 1568.67  5173.2 1568.84  5178.8 1569.83  5200.9 1570.50  5217.3 1570.36
  5223.0 1571.43  5239.4 1571.65  5245.1 1572.83  5261.5 1573.15  5264.6 1573.94
#Mann=6,-1,0
  4724.9   0.035       0  4851.7     0.1       0  4885.0   0.035       0
  5014.6   0.035       0  5018.6   0.035       0  5158.1     0.1       0
Bank Sta=5014.6,5018.6
Exp/Cntr=0.3,0.1

Chan Stop Cuts=-1