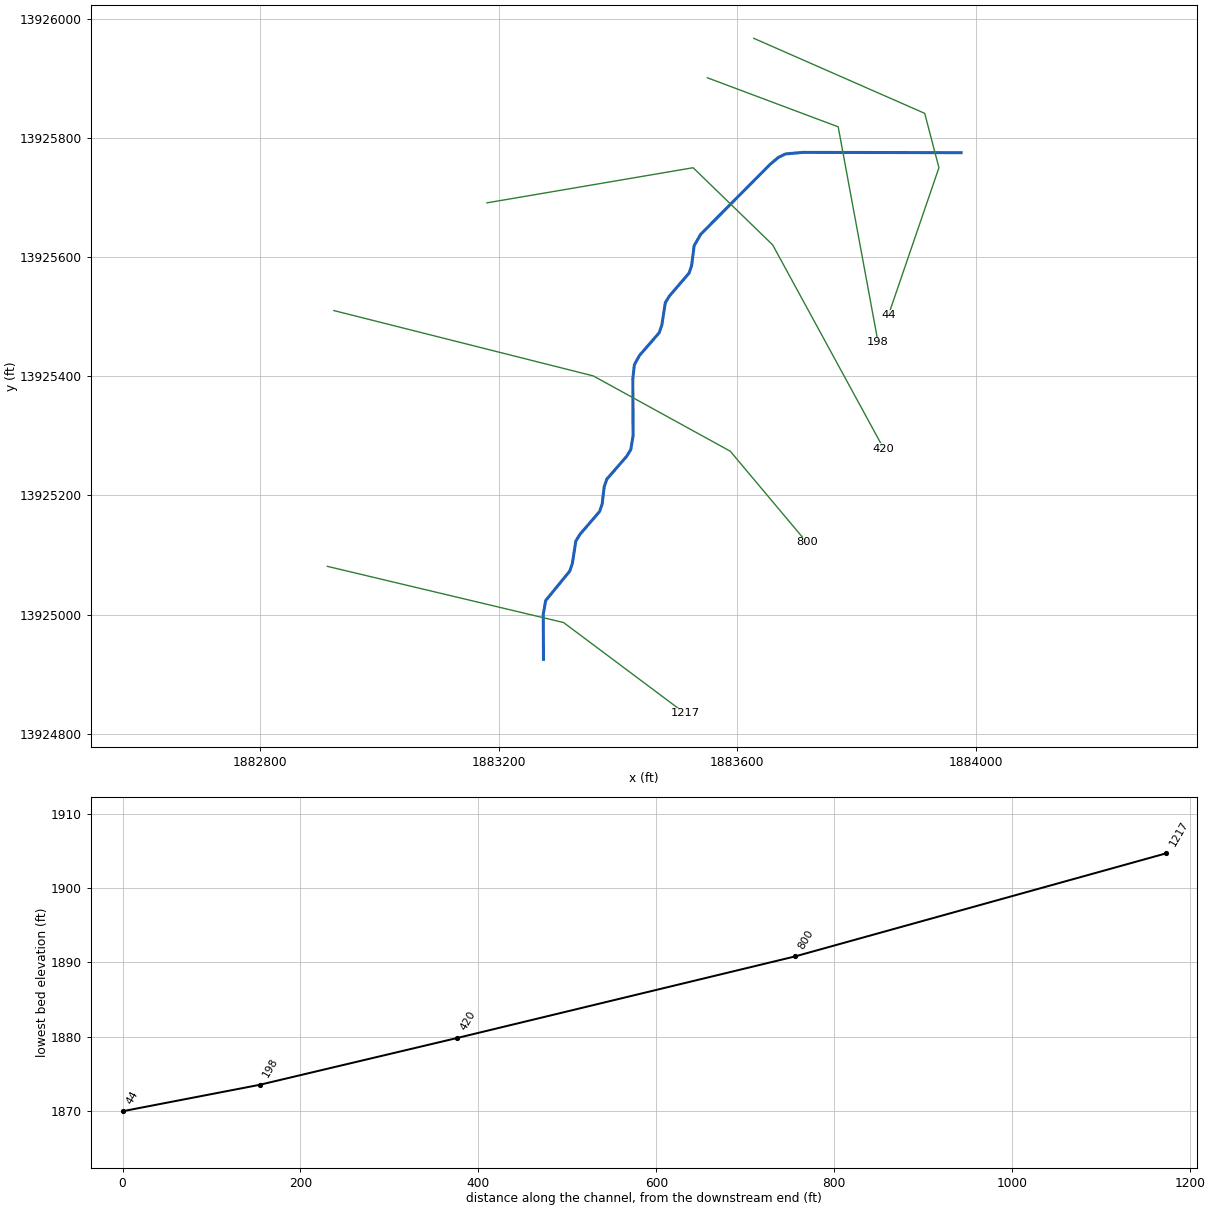
--- Stream1007.prj (project) ---

Proj Title=Stream1007 Base Level Engineering
Current Plan=p01
Default Exp/Contr=0.3,0.1
English Units
Geom File=g01
Flow File=f01
Plan File=p01
BEGIN DESCRIPTION:
Stream1007
END DESCRIPTION:

--- Stream1007.p01 (plan) ---

Plan Title=Multiple Run
Short Identifier=Multiple
Geom File=g01
Flow File=f01
Subcritical Flow
K Sum by GR= 0
Std Step Tol= 0.01
Critical Tol= 0.01
Num of Std Step Trials= 20
Max Error Tol= 0.3
Flow Tol Ratio= 0.001
Split Flow NTrial= 30
Split Flow Tol= 0.02
Split Flow Ratio= 0.02
Log Output Level= 0
Friction Slope Method= 1
Unsteady Friction Slope Method= 2
Unsteady Bridges Friction Slope Method= 1
Parabolic Critical Depth
Global Vel Dist=  1 , 1 , 1
Global Log Level= 0
CheckData=True
Encroach Param= -1, 0, 0, 0
BEGIN DESCRIPTION:
Multiple Run
END DESCRIPTION:

--- Stream1007.f01 (steady flow) ---

Flow Title=Multiple
Number of Profiles=7
Profile Names=10-year,25-year,50-year,1pct_min,100-year,1pct_plu,500-year
River Rch & RM= Stream1007,Reach-1,1217
     344     547     729     473     943    1881    1551
Boundary for River Rch & Prof#=Stream1007,Reach-1,1
Up Type=0
Dn Type=3
Dn Slope=0.005
Boundary for River Rch & Prof#=Stream1007,Reach-1,2
Up Type=0
Dn Type=3
Dn Slope=0.005
Boundary for River Rch & Prof#=Stream1007,Reach-1,3
Up Type=0
Dn Type=3
Dn Slope=0.005
Boundary for River Rch & Prof#=Stream1007,Reach-1,4
Up Type=0
Dn Type=3
Dn Slope=0.005
Boundary for River Rch & Prof#=Stream1007,Reach-1,5
Up Type=0
Dn Type=3
Dn Slope=0.005
Boundary for River Rch & Prof#=Stream1007,Reach-1,6
Up Type=0
Dn Type=3
Dn Slope=0.005
Boundary for River Rch & Prof#=Stream1007,Reach-1,7
Up Type=0
Dn Type=3
Dn Slope=0.005

--- Stream1007.g01 (geometry) ---

Geom Title=Existing Conditions

River Reach=Stream1007,Reach-1
Reach XY= 30
      1883275.00     13924925.00      1883274.52     13925000.20
      1883278.63     13925023.50      1883318.91     13925072.81
      1883323.34     13925085.69      1883329.16     13925123.28
      1883336.08     13925134.55      1883368.92     13925172.80
      1883373.35     13925185.68      1883376.67     13925214.31
      1883381.12     13925227.18      1883414.20     13925265.33
      1883421.24     13925276.56      1883425.19     13925299.92
      1883424.67     13925395.14      1883427.25     13925419.07
      1883435.80     13925434.67      1883468.88     13925472.82
      1883473.33     13925485.69      1883479.16     13925523.28
      1883486.08     13925534.55      1883518.90     13925572.81
      1883523.30     13925585.70      1883527.50     13925618.97
      1883538.62     13925638.22      1883654.83     13925755.40
      1883668.81     13925767.19      1883680.85     13925772.94
      1883709.80     13925775.49      1883975.00     13925775.00

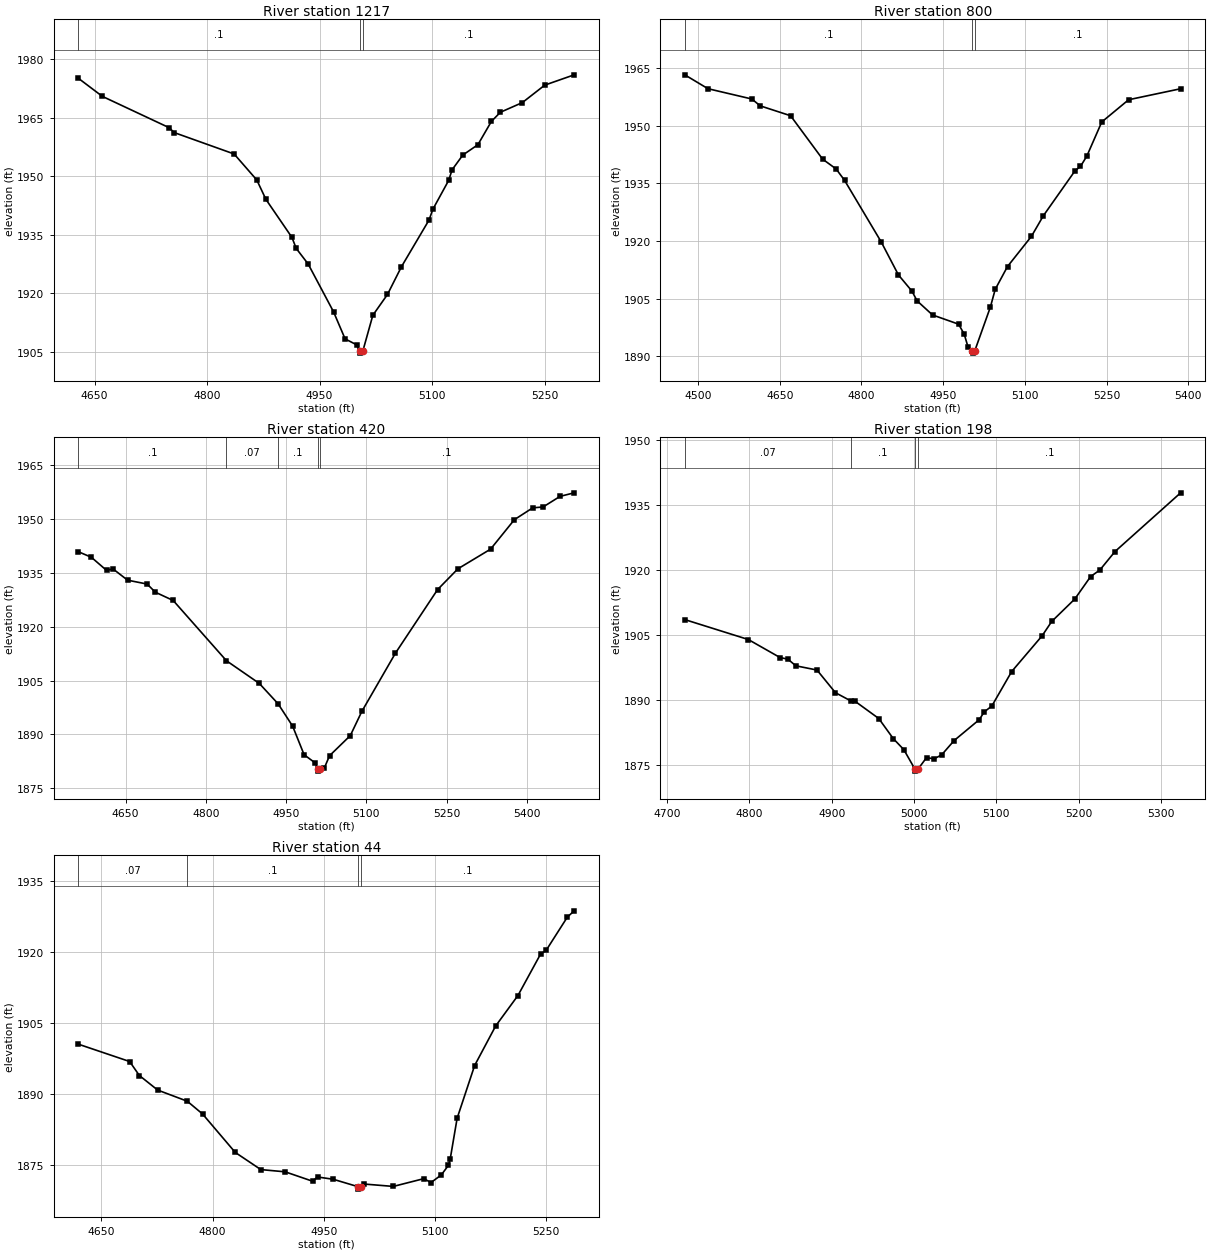
Type RM Length L Ch R = 1,1217,417,417,417
BEGIN DESCRIPTION:
Stream1007 2.0
END DESCRIPTION:
XS GIS Cut Line= 3
      1882912.70     13925080.89      1883308.53     13924986.64
      1883512.20     13924834.19
#Sta/Elev= 30
  4628.2 1975.18  4660.2 1970.54  4749.6 1962.48  4755.8 1961.27  4836.0 1955.76
  4866.2 1949.10  4878.4 1944.12  4913.1 1934.37  4918.8 1931.55  4934.7 1927.56
  4968.6 1915.29  4984.0 1908.35  4999.4 1906.83  5003.6 1905.20  5003.9 1904.70
  5007.6 1905.20  5021.0 1914.41  5040.5 1919.74  5059.2 1926.87  5096.0 1938.85
  5101.0 1941.57  5122.1 1948.98  5126.7 1951.71  5141.0 1955.49  5161.1 1958.14
  5179.1 1964.11  5191.1 1966.46  5220.4 1968.94  5250.3 1973.42  5289.5 1976.06
#Mann=3,-1,0
  4628.2     0.1       0  5003.6    0.05       0  5007.6     0.1       0
Bank Sta=5003.6,5007.6
Exp/Cntr=0.3,0.1

Type RM Length L Ch R = 1,800,380,380,380
BEGIN DESCRIPTION:
Stream1007 1.1
END DESCRIPTION:
XS GIS Cut Line= 4
      1882923.60     13925510.07      1883358.47     13925400.42
      1883587.98     13925274.13      1883716.18     13925121.33
#Sta/Elev= 30
  4475.8 1963.21  4518.3 1959.60  4598.8 1956.92  4614.2 1955.14  4669.9 1952.57
  4728.7 1941.28  4753.5 1938.72  4768.9 1935.78  4836.2 1919.75  4867.9 1911.14
  4892.7 1906.93  4902.0 1904.42  4930.4 1900.74  4978.3 1898.34  4988.6 1895.72
  4995.5 1892.44  5003.7 1891.31  5004.0 1890.81  5007.7 1891.31  5036.6 1902.80
  5045.5 1907.42  5068.0 1913.34  5111.9 1921.19  5133.8 1926.55  5192.2 1938.30
  5201.9 1939.38  5213.6 1942.07  5241.0 1950.95  5290.3 1956.73  5385.7 1959.59
#Mann=3,-1,0
  4475.8     0.1       0  5003.7    0.05       0  5007.7     0.1       0
Bank Sta=5003.7,5007.7
Exp/Cntr=0.3,0.1

Type RM Length L Ch R = 1,420,222,222,222
BEGIN DESCRIPTION:
Stream1007 0.0
END DESCRIPTION:
XS GIS Cut Line= 4
      1883180.19     13925690.83      1883525.77     13925749.77
      1883659.07     13925620.40      1883845.42     13925278.07
#Sta/Elev= 30
  4561.9 1940.80  4586.2 1939.26  4614.8 1935.59  4626.5 1936.04  4653.9 1932.89
  4690.4 1931.81  4705.7 1929.55  4739.1 1927.24  4838.6 1910.49  4899.9 1904.19
  4935.1 1898.51  4962.2 1892.31  4983.6 1884.37  5004.5 1882.06  5009.3 1880.31
  5009.5 1879.81  5013.3 1880.31  5021.3 1880.66  5031.1 1884.09  5069.9 1889.69
  5091.4 1896.40  5154.3 1912.63  5232.9 1930.27  5270.8 1936.04  5331.9 1941.52
  5376.3 1949.70  5410.5 1952.99  5430.0 1953.24  5461.7 1956.19  5488.0 1957.17
#Mann=5,-1,0
  4561.9     0.1       0  4838.6    0.07       0  4935.1     0.1       0
  5009.3    0.05       0  5013.3     0.1       0
Bank Sta=5009.3,5013.3
Exp/Cntr=0.3,0.1

Type RM Length L Ch R = 1,198,154,154,154
BEGIN DESCRIPTION:
Stream1007 0.1
END DESCRIPTION:
XS GIS Cut Line= 3
      1883549.63     13925900.71      1883768.97     13925818.36
      1883835.80     13925456.78
#Sta/Elev= 30
  4721.7 1908.49  4798.8 1903.89  4837.3 1899.73  4846.9 1899.35  4856.5 1897.82
  4882.2 1896.84  4904.6 1891.61  4923.3 1889.71  4928.1 1889.67  4957.2 1885.65
  4974.9 1880.99  4987.6 1878.47  5001.0 1874.00  5001.2 1873.50  5005.0 1874.00
  5015.2 1876.62  5024.3 1876.34  5033.5 1877.24  5048.7 1880.56  5079.2 1885.38
  5085.3 1887.18  5094.5 1888.54  5118.6 1896.50  5155.5 1904.74  5167.2 1908.06
  5195.2 1913.24  5214.4 1918.42  5225.7 1919.95  5244.0 1924.20  5323.7 1937.76
#Mann=4,-1,0
  4721.7    0.07       0  4923.3     0.1       0  5001.0    0.05       0
  5005.0     0.1       0
Bank Sta=5001,5005
Exp/Cntr=0.3,0.1

Type RM Length L Ch R = 1,44,0,0,0
BEGIN DESCRIPTION:
Stream0451 0.2
END DESCRIPTION:
XS GIS Cut Line= 4
      1883627.52     13925966.87      1883913.97     13925841.01
      1883937.84     13925749.86      1883853.19     13925502.44
#Sta/Elev= 30
  4618.9 1900.51  4688.1 1896.85  4701.2 1893.90  4725.9 1890.83  4765.8 1888.48
  4786.4 1885.79  4830.5 1877.68  4865.0 1874.06  4897.8 1873.59  4934.7 1871.61
  4941.5 1872.50  4962.6 1872.02  4996.4 1870.44  4996.6 1869.94  5000.4 1870.44
  5004.5 1871.01  5043.6 1870.51  5084.8 1872.15  5094.4 1871.32  5108.4 1872.94
  5117.9 1874.95  5120.3 1876.24  5129.7 1884.89  5153.3 1896.01  5181.7 1904.36
  5211.7 1910.77  5242.2 1919.51  5249.7 1920.29  5278.3 1927.30  5287.5 1928.63
#Mann=4,-1,0
  4618.9    0.07       0  4765.8     0.1       0  4996.4    0.05       0
  5000.4     0.1       0
Bank Sta=4996.4,5000.4
Exp/Cntr=0.3,0.1

Chan Stop Cuts=-1