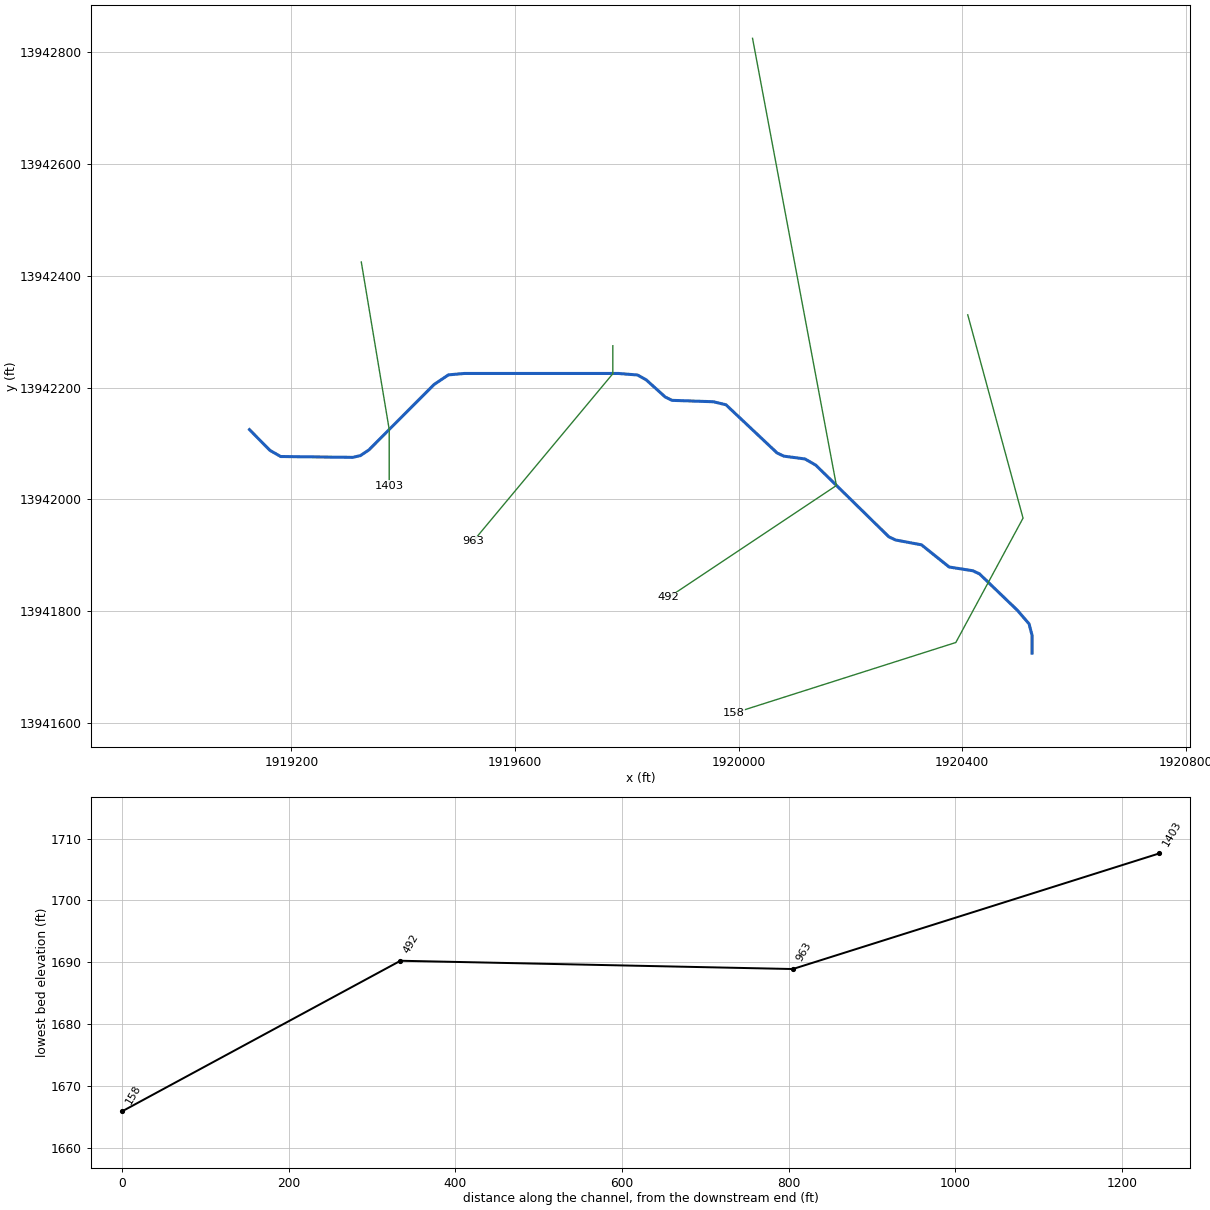
--- Stream1011.prj (project) ---

Proj Title=Stream1011 Base Level Engineering
Current Plan=p01
Default Exp/Contr=0.3,0.1
English Units
Geom File=g01
Flow File=f01
Plan File=p01
Y Axis Title=Elevation
X Axis Title(PF)=Main Channel Distance
X Axis Title(XS)=Station
BEGIN DESCRIPTION:
Stream1011
END DESCRIPTION:
DSS Export Rating Curves= 0
DSS Export Rating Curve Sorted= 0
DSS Export Volume Flow Curves= 0
DXF OffsetX= 0
DXF OffsetY= 0
DXF ScaleX= 1
DXF ScaleY= 10

--- Stream1011.p01 (plan) ---

Plan Title=Multiple Run
Short Identifier=Multiple
Geom File=g01
Flow File=f01
Subcritical Flow
K Sum by GR= 0
Std Step Tol= 0.01
Critical Tol= 0.01
Num of Std Step Trials= 20
Max Error Tol= 0.3
Flow Tol Ratio= 0.001
Split Flow NTrial= 30
Split Flow Tol= 0.02
Split Flow Ratio= 0.02
Log Output Level= 0
Friction Slope Method= 1
Unsteady Friction Slope Method= 2
Unsteady Bridges Friction Slope Method= 1
Parabolic Critical Depth
Global Vel Dist=  1 , 1 , 1
Global Log Level= 0
CheckData=True
Encroach Param= -1, 0, 0, 0
BEGIN DESCRIPTION:
Multiple Run
END DESCRIPTION:

--- Stream1011.f01 (steady flow) ---

Flow Title=Multiple
Number of Profiles=7
Profile Names=10-year,25-year,50-year,1pct_min,100-year,1pct_plu,500-year
River Rch & RM= Stream1011,Reach-1,1403
     601     993    1358     903    1801    3594    3116
Boundary for River Rch & Prof#=Stream1011,Reach-1,1
Up Type=0
Dn Type=3
Dn Slope=0.005
Boundary for River Rch & Prof#=Stream1011,Reach-1,2
Up Type=0
Dn Type=3
Dn Slope=0.005
Boundary for River Rch & Prof#=Stream1011,Reach-1,3
Up Type=0
Dn Type=3
Dn Slope=0.005
Boundary for River Rch & Prof#=Stream1011,Reach-1,4
Up Type=0
Dn Type=3
Dn Slope=0.005
Boundary for River Rch & Prof#=Stream1011,Reach-1,5
Up Type=0
Dn Type=3
Dn Slope=0.005
Boundary for River Rch & Prof#=Stream1011,Reach-1,6
Up Type=0
Dn Type=3
Dn Slope=0.005
Boundary for River Rch & Prof#=Stream1011,Reach-1,7
Up Type=0
Dn Type=3
Dn Slope=0.005

--- Stream1011.g01 (geometry) ---

Geom Title=Existing Conditions
Program Version=4.10

River Reach=Stream1011      ,Reach-1
Reach XY= 30
        1919125.       13942125.       1919161.5     13942087.91
      1919180.79     13942076.88      1919309.84     13942075.36
      1919323.53     13942078.53      1919338.32     13942088.37
      1919454.84     13942205.39      1919480.85     13942222.94
       1919509.8     13942225.49      1919785.19     13942225.45
      1919819.06     13942222.74      1919834.65     13942214.15
      1919868.97     13942183.19      1919880.98     13942177.36
      1919954.95     13942174.87      1919977.42     13942169.46
      1920068.96     13942083.18      1920081.05     13942077.54
      1920118.95     13942072.47      1920138.21     13942061.37
      1920268.94     13941933.14      1920281.04      13941927.5
      1920327.19      13941918.9      1920376.74     13941879.19
      1920418.97     13941872.51      1920431.07     13941866.87
      1920498.68     13941801.87       1920519.7     13941777.54
      1920525.08     13941756.89        1920525.       13941725.

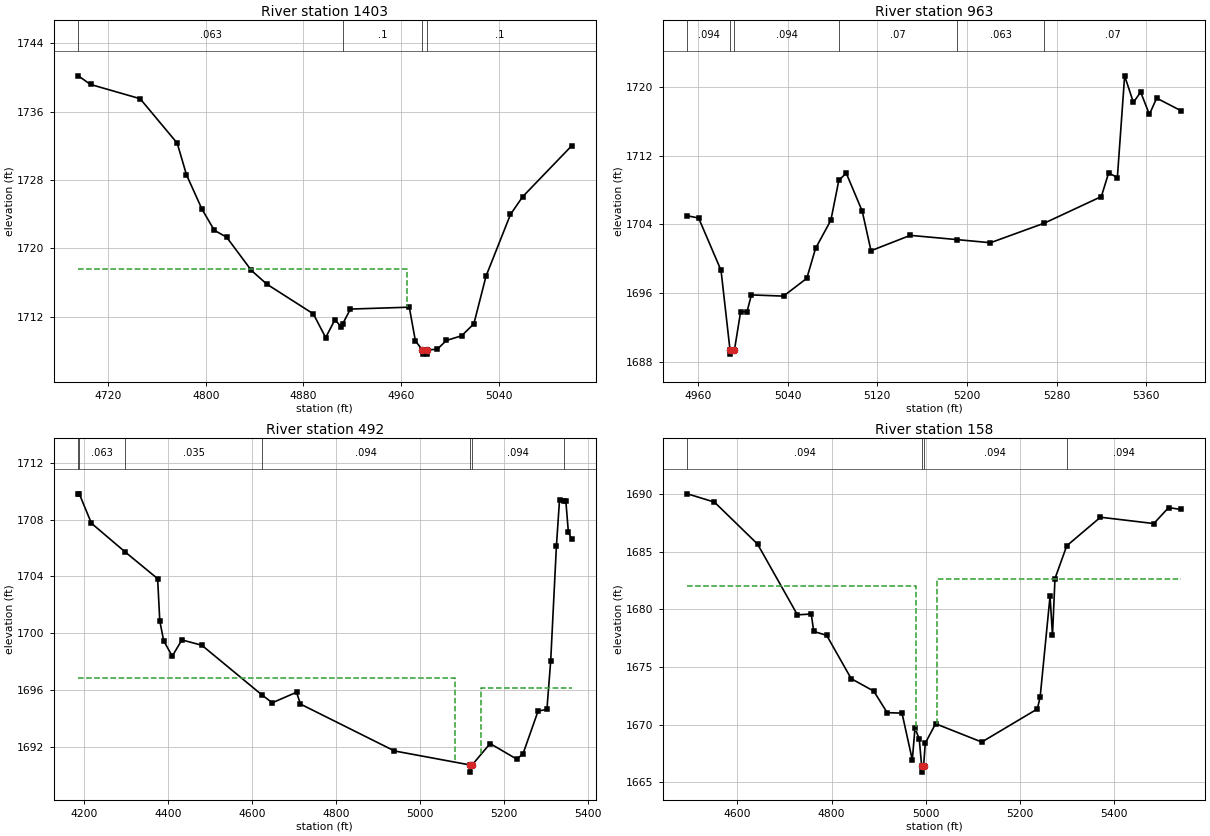
Type RM Length L Ch R = 1 ,1403    ,440,440,440
BEGIN DESCRIPTION:
Stream1011 3.0
END DESCRIPTION:
XS GIS Cut Line= 3
        1919325.     13942424.98        1919375.       13942125.
        1919375.     13942025.01
#Sta/Elev= 30
  4695.5 1740.21  4705.6  1739.2  4746.2 1737.53  4776.6 1732.32  4784.2 1728.61
  4796.9 1724.58    4807 1722.11  4817.1  1721.3  4837.4  1717.4  4850.1 1715.79
  4888.1 1712.32  4898.2 1709.54  4905.8 1711.63  4910.9 1710.81  4912.2 1711.16
  4918.5 1712.88  4966.7  1713.1  4971.7 1709.16  4977.3  1708.1  4977.6  1707.6
  4981.1  1707.6  4981.3  1708.1  4989.5 1708.16  4997.1  1709.2  5009.6 1709.75
  5019.6 1711.15  5029.6 1716.75  5049.6 1723.97  5059.6 1726.05  5099.6 1731.99
#Mann= 4 ,-1 , 0
  4695.5    .063       0  4912.2      .1       0  4977.3     .05       0
  4981.3      .1       0
#XS Ineff= 2 , 0
          4964.5 1717.53
Permanent Ineff=
       F       F
#Block Obstruct= 2 , 0
         4918.59 1712.89
Bank Sta=4977.3,4981.3
XS Rating Curve= 0 ,0
Exp/Cntr=0.3,0.1

Type RM Length L Ch R = 1 ,963     ,471,471,471
BEGIN DESCRIPTION:
Stream1011 2.0
END DESCRIPTION:
XS GIS Cut Line= 3
        1919775.     13942274.99        1919775.       13942225.
        1919525.       13941925.
#Sta/Elev= 30
  4950.4 1705.01  4960.4 1704.75  4980.4 1698.65  4988.4 1689.39  4988.6 1688.89
  4992.4 1689.39  4997.9 1693.83  5003.6 1693.83  5007.5 1695.79  5036.2 1695.65
    5057 1697.73  5064.8 1701.21  5078.5  1704.5  5085.6 1709.15  5092.2 1709.98
  5106.5 1705.54  5114.3 1700.94  5149.4 1702.73  5191.5 1702.23    5221 1701.87
  5269.2 1704.16    5320 1707.25  5326.5 1710.01  5334.3 1709.47  5340.8 1721.32
  5348.6 1718.22  5355.1 1719.42  5362.9 1716.83  5369.4 1718.72  5390.9 1717.27
#Mann= 6 ,-1 , 0
  4950.4    .094       0  4988.4     .05       0  4992.4    .094       0
  5085.6     .07       0  5191.5    .063       0  5269.2     .07       0
#XS Ineff= 2 , 0
                         5090.37         1709.53
Permanent Ineff=
       F       F
Bank Sta=4988.4,4992.4
XS Rating Curve= 0 ,0
Exp/Cntr=0.3,0.1

Type RM Length L Ch R = 1 ,492     ,334,334,334
BEGIN DESCRIPTION:
Stream1011 1.0
END DESCRIPTION:
XS GIS Cut Line= 3
      1920024.99     13942825.03        1920175.       13942025.
      1919875.02     13941825.01
#Sta/Elev= 30
  4186.4 1709.81    4189 1709.81  4217.8 1707.74  4298.6 1705.71  4375.5 1703.84
  4380.6 1700.87  4389.9 1699.47  4410.3 1698.39  4433.2 1699.53  4480.6 1699.16
  4623.9 1695.66  4648.5 1695.11  4706.2 1695.85  4715.5 1695.02  4939.3 1691.72
  5120.1 1690.73  5120.3 1690.23  5124.1 1690.73  5167.1 1692.24  5230.2 1691.15
  5245.2  1691.5  5281.3 1694.53  5302.3 1694.64  5311.3 1698.05  5324.9 1706.12
  5332.4 1709.41  5343.5 1709.29  5347.4 1709.29  5353.4 1707.12  5360.9 1706.64
#Mann= 7 ,-1 , 0
  4186.4    .094       0    4189    .063       0  4298.6    .035       0
  4623.9    .094       0  5120.1     .05       0  5124.1    .094       0
  5343.5     .12       0
#XS Ineff= 2 , 0
         5084.53 1696.84 5145.74         1696.16
Permanent Ineff=
       F       F
Bank Sta=5120.1,5124.1
XS Rating Curve= 0 ,0
Exp/Cntr=0.3,0.1

Type RM Length L Ch R = 1 ,158     ,0,0,0
BEGIN DESCRIPTION:
Stream1011 0.0
END DESCRIPTION:
XS GIS Cut Line= 4
      1920410.03     13942330.34      1920508.93     13941966.67
      1920388.64     13941744.13      1919990.48     13941617.34
#Sta/Elev= 30
  4493.9 1690.03  4551.3 1689.31  4642.8 1685.67  4727.5 1679.53  4756.9  1679.6
  4762.1 1678.09  4789.6 1677.75  4841.7 1673.99  4889.6 1672.91  4918.1 1671.04
  4949.6    1671  4971.5 1666.94  4977.2 1669.72  4986.3 1668.73  4991.4 1666.38
  4991.6 1665.88  4995.4 1666.38    4999 1668.39  5020.9 1670.08    5119 1668.49
    5237 1671.36    5243  1672.4    5264 1681.14  5269.2 1677.74  5274.5 1682.68
  5299.5 1685.52  5371.1    1688  5484.4 1687.45  5515.9 1688.84  5541.6 1688.67
#Mann= 4 ,-1 , 0
  4493.9    .094       0  4991.4     .05       0  4995.4    .094       0
  5299.5    .094       0
#XS Ineff= 2 , 0
         4979.82 1682.05 5022.87         1682.68
Permanent Ineff=
       F       F
Bank Sta=4991.4,4995.4
XS Rating Curve= 0 ,0
Exp/Cntr=0.3,0.1

Chan Stop Cuts=-1
Use User Specified Reach Order=0
Composite Channel Slope=5