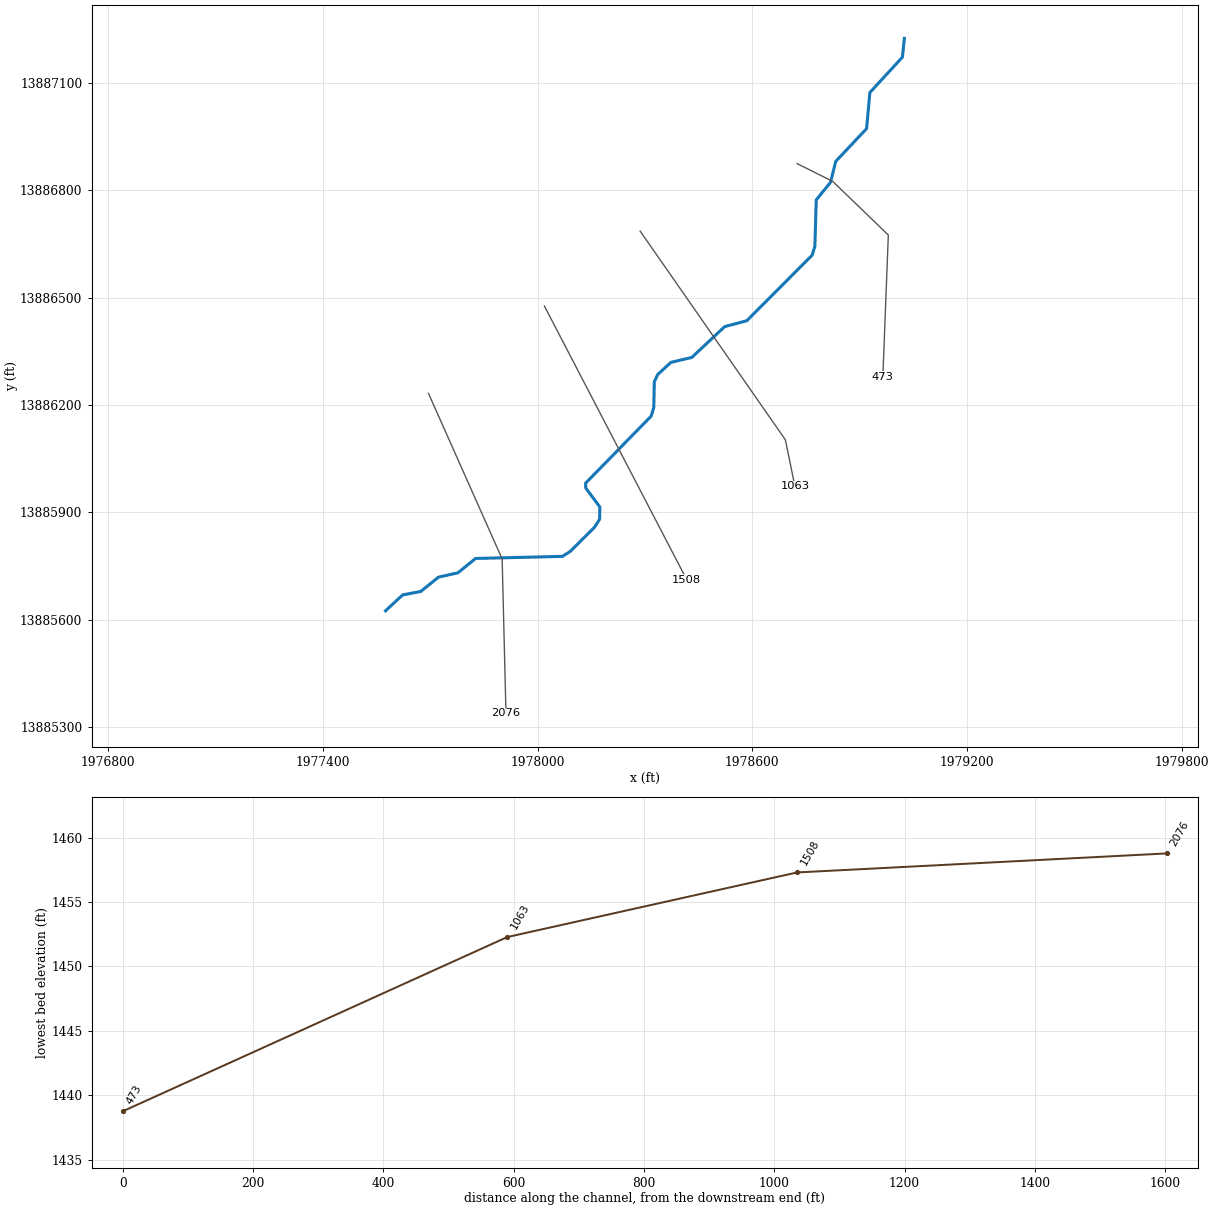
--- Stream1013.prj (project) ---

Proj Title=Stream1013 Base Level Engineering
Current Plan=p01
Default Exp/Contr=0.3,0.1
English Units
Geom File=g01
Flow File=f01
Plan File=p01
BEGIN DESCRIPTION:
Stream1013
END DESCRIPTION:

--- Stream1013.p01 (plan) ---

Plan Title=Multiple Run
Short Identifier=Multiple
Geom File=g01
Flow File=f01
Subcritical Flow
K Sum by GR= 0
Std Step Tol= 0.01
Critical Tol= 0.01
Num of Std Step Trials= 20
Max Error Tol= 0.3
Flow Tol Ratio= 0.001
Split Flow NTrial= 30
Split Flow Tol= 0.02
Split Flow Ratio= 0.02
Log Output Level= 0
Friction Slope Method= 1
Unsteady Friction Slope Method= 2
Unsteady Bridges Friction Slope Method= 1
Parabolic Critical Depth
Global Vel Dist=  1 , 1 , 1
Global Log Level= 0
CheckData=True
Encroach Param= -1, 0, 0, 0
BEGIN DESCRIPTION:
Multiple Run
END DESCRIPTION:

--- Stream1013.f01 (steady flow) ---

Flow Title=Multiple
Number of Profiles=7
Profile Names=10-year,25-year,50-year,1pct_min,100-year,1pct_plu,500-year
River Rch & RM= Stream1013,Reach-1,2076
     468     750    1005     653    1303    2600    2167
Boundary for River Rch & Prof#=Stream1013,Reach-1,1
Up Type=0
Dn Type=3
Dn Slope=0.005
Boundary for River Rch & Prof#=Stream1013,Reach-1,2
Up Type=0
Dn Type=3
Dn Slope=0.005
Boundary for River Rch & Prof#=Stream1013,Reach-1,3
Up Type=0
Dn Type=3
Dn Slope=0.005
Boundary for River Rch & Prof#=Stream1013,Reach-1,4
Up Type=0
Dn Type=3
Dn Slope=0.005
Boundary for River Rch & Prof#=Stream1013,Reach-1,5
Up Type=0
Dn Type=3
Dn Slope=0.005
Boundary for River Rch & Prof#=Stream1013,Reach-1,6
Up Type=0
Dn Type=3
Dn Slope=0.005
Boundary for River Rch & Prof#=Stream1013,Reach-1,7
Up Type=0
Dn Type=3
Dn Slope=0.005

--- Stream1013.g01 (geometry) ---

Geom Title=Existing Conditions

River Reach=Stream1013,Reach-1
Reach XY= 30
      1977575.00     13885625.00      1977622.64     13885669.33
      1977673.33     13885679.04      1977722.80     13885718.93
      1977777.18     13885731.12      1977826.55     13885771.25
      1978069.16     13885777.05      1978091.80     13885791.42
      1978158.79     13885858.29      1978173.23     13885880.63
      1978173.94     13885915.20      1978134.33     13885968.45
      1978134.15     13885981.73      1978317.14     13886168.83
      1978324.74     13886193.29      1978326.10     13886264.67
      1978335.39     13886285.10      1978372.43     13886319.26
      1978431.02     13886333.19      1978522.72     13886419.13
      1978584.68     13886435.78      1978767.18     13886618.81
      1978774.89     13886643.23      1978778.76     13886773.44
      1978818.86     13886822.83      1978833.16     13886881.05
      1978919.46     13886972.58      1978928.61     13887073.50
      1979019.67     13887172.49      1979025.00     13887225.00

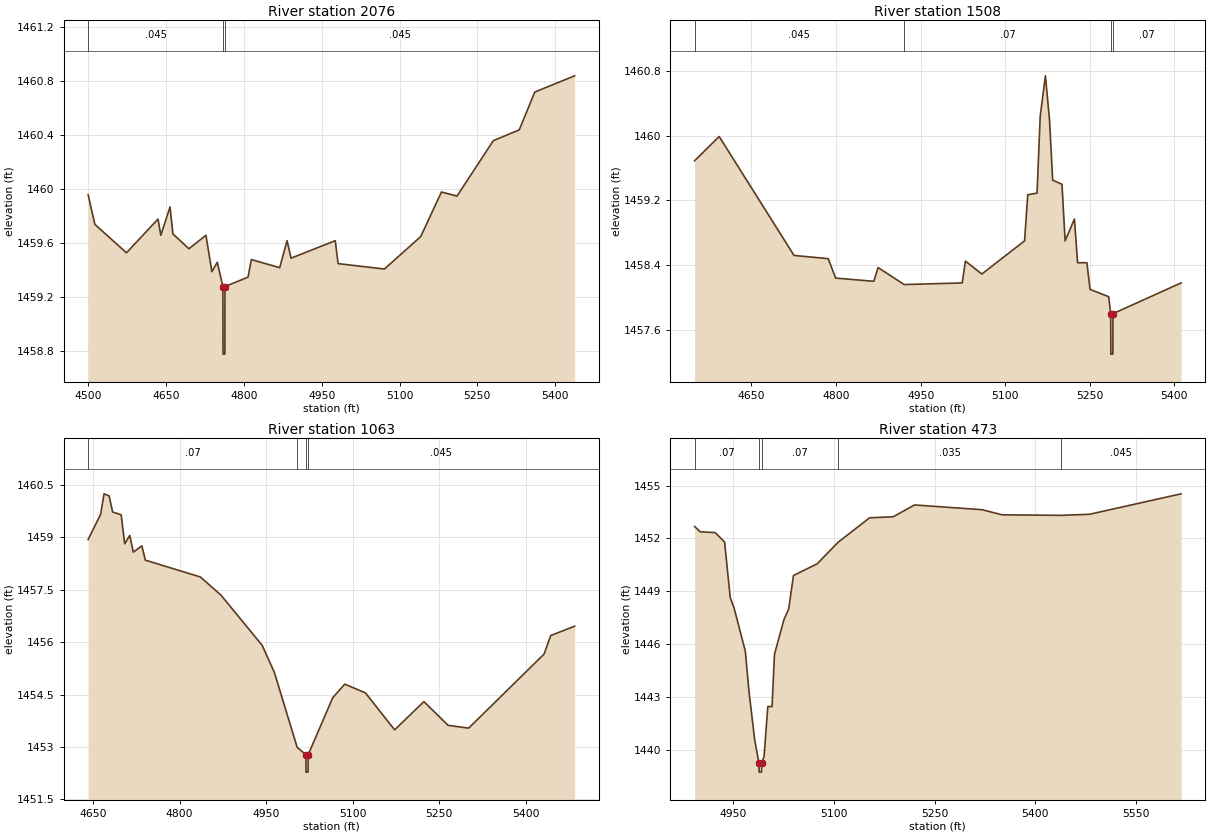
Type RM Length L Ch R = 1,2076,568,568,568
BEGIN DESCRIPTION:
Stream1013 2.0
END DESCRIPTION:
XS GIS Cut Line= 3
      1977694.98     13886232.60      1977900.87     13885769.83
      1977911.55     13885338.27
#Sta/Elev= 30
  4499.4 1459.96  4512.5 1459.74  4573.4 1459.53  4634.2 1459.78  4639.6 1459.66
  4657.4 1459.87  4662.9 1459.67  4693.8 1459.56  4726.6 1459.66  4738.1 1459.39
  4748.5 1459.46  4759.3 1459.28  4759.6 1458.78  4763.1 1458.78  4763.3 1459.28
  4807.8 1459.35  4814.2 1459.48  4868.9 1459.42  4883.0 1459.62  4890.8 1459.49
  4976.0 1459.62  4981.5 1459.45  5070.8 1459.41  5140.8 1459.65  5180.8 1459.98
  5210.8 1459.95  5280.8 1460.36  5330.8 1460.44  5360.8 1460.72  5437.6 1460.84
#Mann=3,-1,0
  4499.4   0.045       0  4759.3   0.045       0  4763.3   0.045       0
Bank Sta=4759.3,4763.3
Exp/Cntr=0.3,0.1

Type RM Length L Ch R = 1,1508,445,445,445
BEGIN DESCRIPTION:
Stream1013 1.2
END DESCRIPTION:
XS GIS Cut Line= 2
      1978018.89     13886476.85      1978416.92     13885711.58
#Sta/Elev= 30
  4549.2 1459.69  4592.8 1459.99  4725.5 1458.52  4786.2 1458.48  4799.3 1458.24
  4866.9 1458.20  4874.6 1458.37  4920.9 1458.16  5023.7 1458.18  5029.4 1458.45
  5058.5 1458.29  5134.3 1458.70  5139.9 1459.27  5156.4 1459.29  5162.0 1460.24
  5171.2 1460.74  5178.5 1460.20  5184.1 1459.45  5200.6 1459.40  5206.2 1458.70
  5222.7 1458.97  5228.3 1458.43  5244.8 1458.43  5250.4 1458.10  5283.4 1458.01
  5287.0 1457.80  5287.3 1457.30  5290.8 1457.30  5291.0 1457.80  5411.8 1458.18
#Mann=4,-1,0
  4549.2   0.045       0  4920.9    0.07       0  5287.0    0.05       0
  5291.0    0.07       0
Bank Sta=5287,5291
Exp/Cntr=0.3,0.1

Type RM Length L Ch R = 1,1063,590,590,590
BEGIN DESCRIPTION:
Stream1013 1.1
END DESCRIPTION:
XS GIS Cut Line= 3
      1978286.62     13886686.16      1978692.45     13886102.97
      1978719.07     13885973.07
#Sta/Elev= 30
  4641.4 1458.94  4663.0 1459.66  4669.0 1460.25  4677.8 1460.19  4683.9 1459.73
  4698.7 1459.65  4704.8 1458.82  4713.6 1459.06  4719.7 1458.58  4734.5 1458.76
  4740.6 1458.35  4835.8 1457.87  4871.6 1457.35  4943.1 1455.91  4964.1 1455.14
  5003.7 1452.99  5018.8 1452.78  5019.0 1452.28  5022.5 1452.28  5022.8 1452.78
  5065.3 1454.41  5086.2 1454.80  5122.0 1454.55  5172.6 1453.49  5223.3 1454.30
  5265.2 1453.62  5300.9 1453.54  5431.5 1455.66  5443.0 1456.19  5484.5 1456.46
#Mann=4,-1,0
  4641.4    0.07       0  5003.7   0.045       0  5018.8    0.05       0
  5022.8   0.045       0
Bank Sta=5018.8,5022.8
Exp/Cntr=0.3,0.1

Type RM Length L Ch R = 1,473,0,0,0
BEGIN DESCRIPTION:
Stream1013 1.0
END DESCRIPTION:
XS GIS Cut Line= 4
      1978725.00     13886875.00      1978825.00     13886825.00
      1978980.21     13886675.29      1978964.94     13886279.03
#Sta/Elev= 30
  4892.8 1452.68  4901.2 1452.38  4923.5 1452.33  4937.5 1451.80  4945.9 1448.63
  4951.5 1448.07  4968.3 1445.61  4973.9 1443.27  4982.2 1440.60  4988.6 1439.25
  4988.9 1438.75  4992.4 1438.75  4992.6 1439.25  4996.2 1439.64  5001.8 1442.47
  5008.1 1442.47  5011.7 1445.43  5025.8 1447.40  5032.8 1447.99  5040.0 1449.90
  5075.2 1450.56  5106.6 1451.79  5153.2 1453.17  5188.4 1453.23  5220.1 1453.90
  5320.6 1453.63  5350.6 1453.34  5438.3 1453.31  5480.5 1453.37  5616.8 1454.53
#Mann=5,-1,0
  4892.8    0.07       0  4988.6    0.05       0  4992.6    0.07       0
  5106.6   0.035       0  5438.3   0.045       0
Bank Sta=4988.6,4992.6
Exp/Cntr=0.3,0.1

Chan Stop Cuts=-1