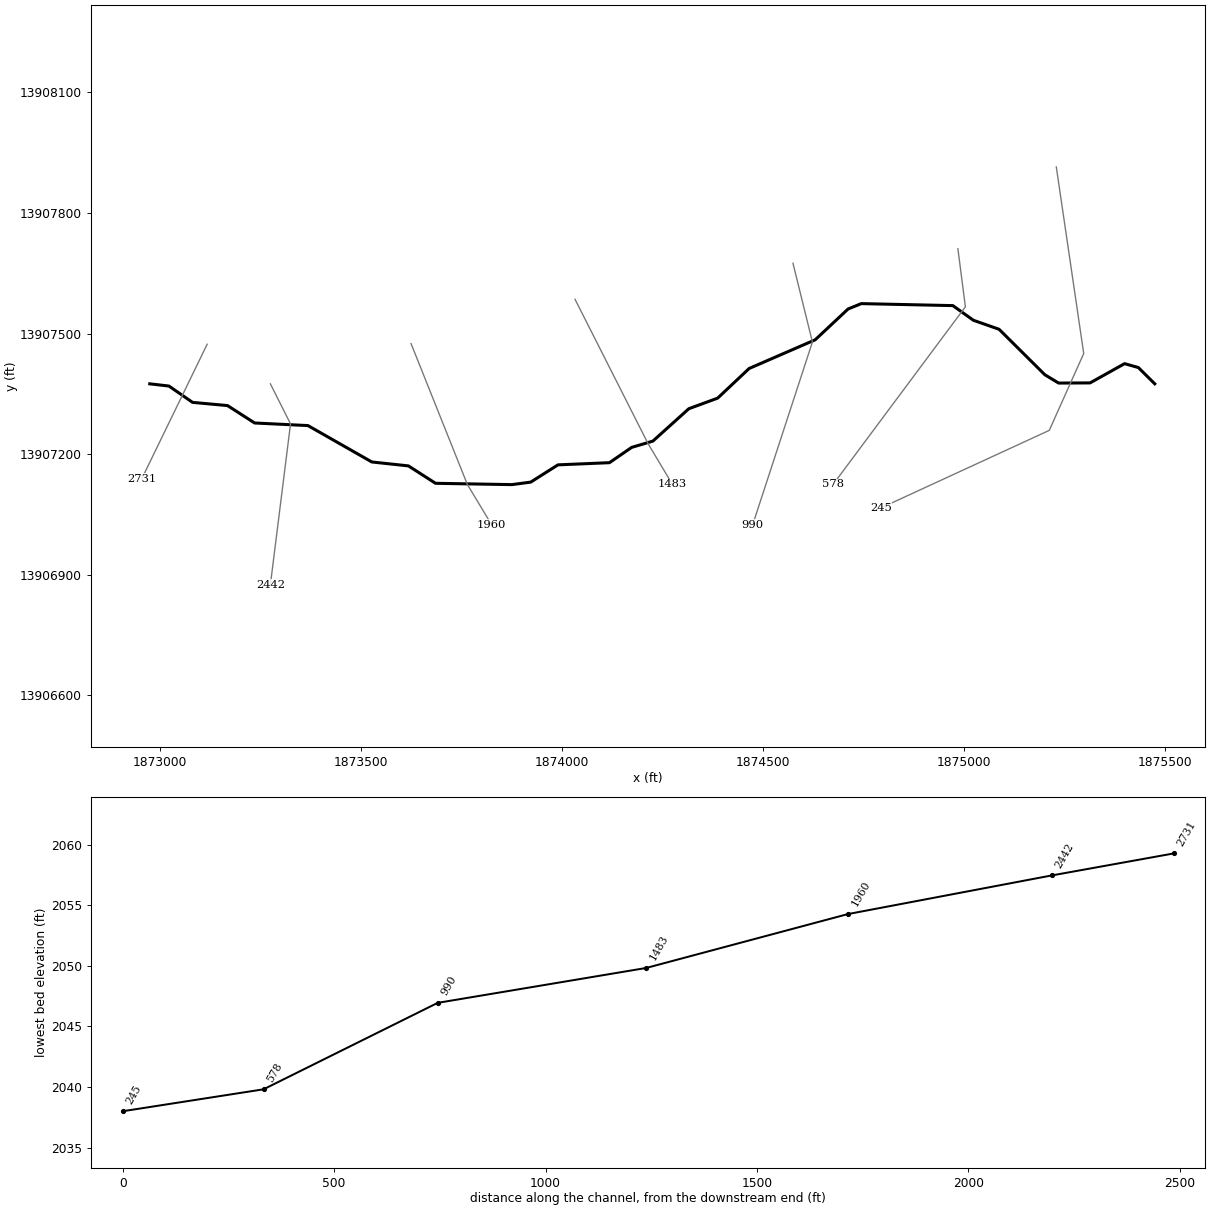
--- Stream1332.prj (project) ---

Proj Title=Stream1332 Base Level Engineering
Current Plan=p01
Default Exp/Contr=0.3,0.1
English Units
Geom File=g01
Flow File=f01
Plan File=p01
Y Axis Title=Elevation
X Axis Title(PF)=Main Channel Distance
X Axis Title(XS)=Station
BEGIN DESCRIPTION:
Stream1332
END DESCRIPTION:
DSS Export Rating Curves= 0
DSS Export Rating Curve Sorted= 0
DSS Export Volume Flow Curves= 0
DXF OffsetX= 0
DXF OffsetY= 0
DXF ScaleX= 1
DXF ScaleY= 10

--- Stream1332.p01 (plan) ---

Plan Title=Multiple Run
Short Identifier=Multiple
Geom File=g01
Flow File=f01
Subcritical Flow
K Sum by GR= 0
Std Step Tol= 0.01
Critical Tol= 0.01
Num of Std Step Trials= 20
Max Error Tol= 0.3
Flow Tol Ratio= 0.001
Split Flow NTrial= 30
Split Flow Tol= 0.02
Split Flow Ratio= 0.02
Log Output Level= 0
Friction Slope Method= 1
Unsteady Friction Slope Method= 2
Unsteady Bridges Friction Slope Method= 1
Parabolic Critical Depth
Global Vel Dist=  1 , 1 , 1
Global Log Level= 0
CheckData=True
Encroach Param= -1, 0, 0, 0
BEGIN DESCRIPTION:
Multiple Run
END DESCRIPTION:

--- Stream1332.f01 (steady flow) ---

Flow Title=Multiple
Number of Profiles=7
Profile Names=10-year,25-year,50-year,1pct_min,100-year,1pct_plu,500-year
River Rch & RM= Stream1332,Reach-1,2731
    1334    2292    3209    2169    4328    8635    7783
Boundary for River Rch & Prof#=Stream1332,Reach-1,1
Up Type=0
Dn Type=3
Dn Slope=0.005
Boundary for River Rch & Prof#=Stream1332,Reach-1,2
Up Type=0
Dn Type=3
Dn Slope=0.005
Boundary for River Rch & Prof#=Stream1332,Reach-1,3
Up Type=0
Dn Type=3
Dn Slope=0.005
Boundary for River Rch & Prof#=Stream1332,Reach-1,4
Up Type=0
Dn Type=3
Dn Slope=0.005
Boundary for River Rch & Prof#=Stream1332,Reach-1,5
Up Type=0
Dn Type=3
Dn Slope=0.005
Boundary for River Rch & Prof#=Stream1332,Reach-1,6
Up Type=0
Dn Type=3
Dn Slope=0.005
Boundary for River Rch & Prof#=Stream1332,Reach-1,7
Up Type=0
Dn Type=3
Dn Slope=0.005

--- Stream1332.g01 (geometry) ---

Geom Title=Existing Conditions
Program Version=4.10

River Reach=Stream1332      ,Reach-1
Reach XY= 30
        1872975.       13907375.      1873022.68      13907369.5
      1873081.47     13907328.85      1873168.41     13907320.89
      1873235.89     13907277.59      1873368.49     13907271.15
      1873527.36     13907180.63      1873618.41     13907170.87
      1873685.88     13907127.56       1873875.8     13907124.27
      1873922.67     13907130.52      1873990.42     13907173.44
      1874118.49     13907178.85      1874173.79     13907216.88
      1874226.51     13907232.51      1874315.99     13907313.13
      1874387.67     13907339.41      1874465.97     13907413.17
       1874630.3     13907484.54      1874712.11     13907561.18
      1874744.96     13907574.54       1874972.7     13907569.56
      1875023.79     13907533.12      1875087.72     13907510.68
      1875201.52     13907397.64      1875235.77      13907376.9
      1875314.05     13907377.29      1875399.94     13907425.21
       1875434.2     13907415.48        1875475.       13907375.

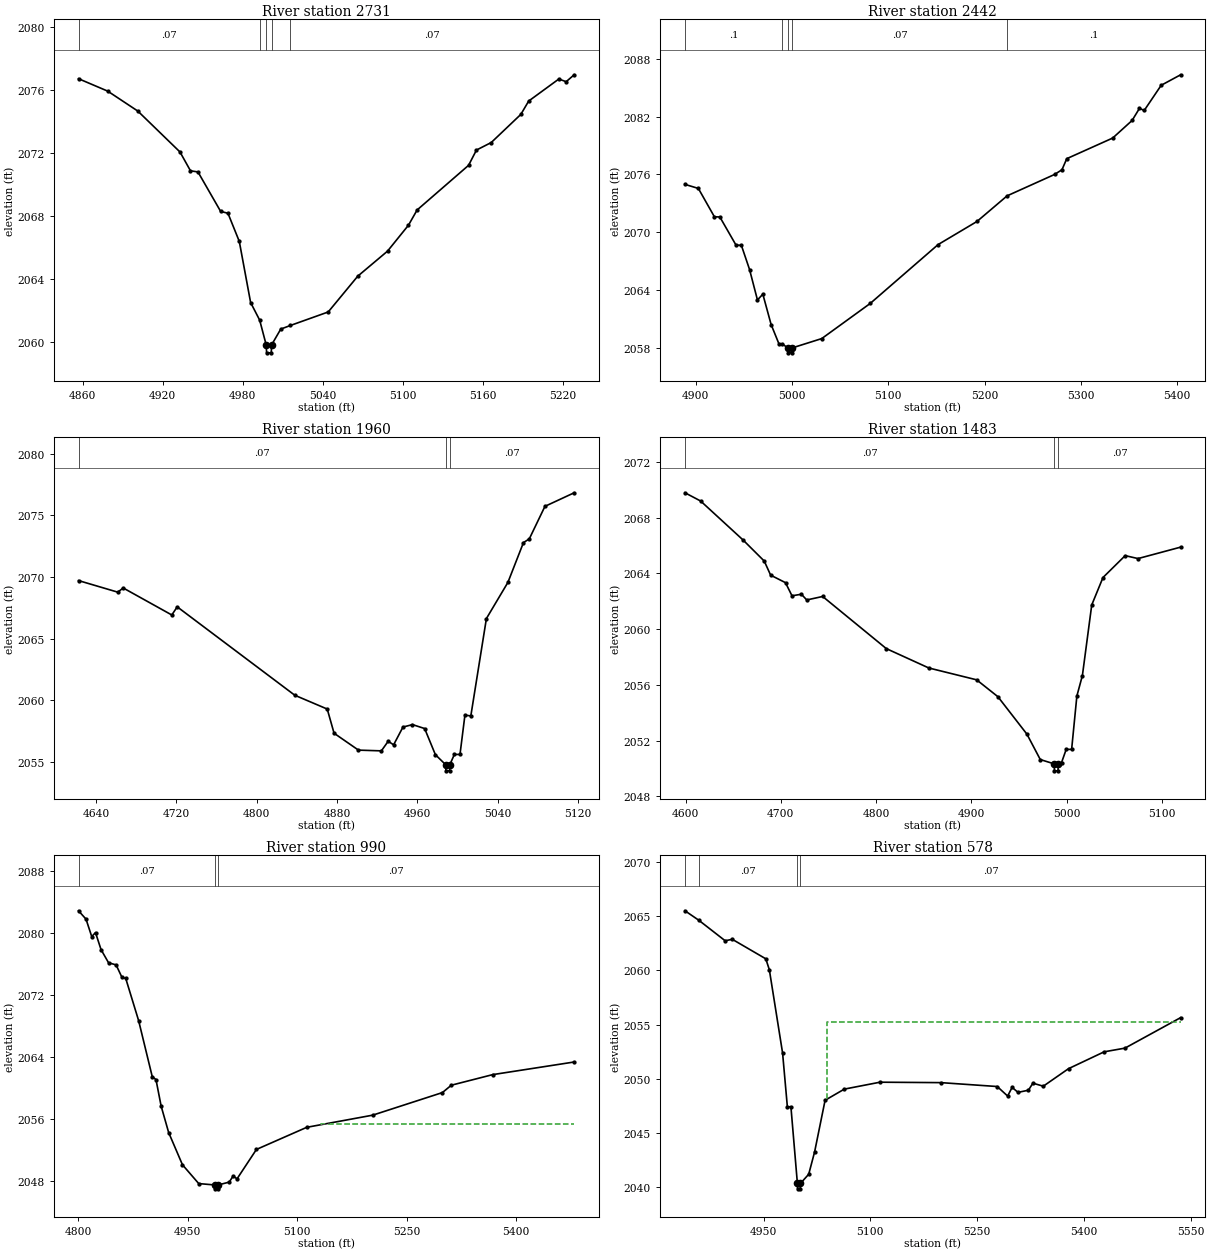
Type RM Length L Ch R = 1 ,2731    ,289,289,289
BEGIN DESCRIPTION:
Stream1232 6.0
END DESCRIPTION:
XS GIS Cut Line= 2
      1873117.77     13907473.44      1872955.22     13907139.05
#Sta/Elev= 30
  4856.8 2076.73  4878.7 2075.94  4901.3 2074.67  4932.9 2072.07  4940.8 2070.87
  4946.4  2070.8  4963.4 2068.29  4968.9 2068.17  4977.4 2066.38  4985.9 2062.49
  4992.7 2061.37  4997.6 2059.79  4997.9 2059.29  5001.4 2059.29  5001.6 2059.79
  5008.5  2060.8  5015.7 2061.03  5044.1 2061.89  5066.3 2064.17  5088.6 2065.76
  5104.3 2067.41  5110.8 2068.38  5149.4 2071.22  5155.3 2072.19  5166.4 2072.67
  5188.6 2074.46  5194.5 2075.31  5217.1 2076.71  5222.6 2076.54  5228.6 2076.98
#Mann= 5 ,-1 , 0
  4856.8     .07       0  4992.7     .07       0  4997.6     .05       0
  5001.6     .07       0  5015.7     .07       0
Bank Sta=4997.6,5001.6
XS Rating Curve= 0 ,0
Exp/Cntr=0.3,0.1

Type RM Length L Ch R = 1 ,2442    ,482,482,482
BEGIN DESCRIPTION:
Stream1232 5.0
END DESCRIPTION:
XS GIS Cut Line= 3
      1873275.02     13907374.97      1873325.14     13907275.34
        1873275.     13906874.99
#Sta/Elev= 30
  4888.7 2074.96  4902.6 2074.54  4919.3 2071.59  4924.9 2071.58  4941.7 2068.66
  4947.3 2068.63  4955.8 2066.12    4964 2062.96  4969.6 2063.56  4978.2 2060.41
  4986.3 2058.41  4989.8  2058.4  4995.6 2057.97  4995.8 2057.47  4999.4 2057.47
  4999.7 2057.97  5030.8 2058.95  5081.2  2062.6  5151.7 2068.71  5192.1 2071.11
  5223.4 2073.77  5272.7 2075.99  5280.4 2076.48  5285.4 2077.63  5333.1 2079.77
  5353.3  2081.6  5360.9 2082.85  5365.9 2082.64  5383.5 2085.25  5403.7 2086.34
#Mann= 5 ,-1 , 0
  4888.7      .1       0  4989.8     .07       0  4995.6     .05       0
  4999.7     .07       0  5223.4      .1       0
Bank Sta=4995.6,4999.7
XS Rating Curve= 0 ,0
Exp/Cntr=0.3,0.1

Type RM Length L Ch R = 1 ,1960    ,477,477,477
BEGIN DESCRIPTION:
Stream1232 4.0
END DESCRIPTION:
XS GIS Cut Line= 3
      1873624.99     13907475.03      1873764.95     13907124.88
      1873824.99     13907025.02
#Sta/Elev= 30
  4622.7 2069.71  4661.8 2068.77  4667.2 2069.11  4715.6 2066.92    4721 2067.58
  4838.1 2060.41  4870.4 2059.29  4877.2 2057.33  4901.5 2055.96  4924.3  2055.9
  4931.1 2056.68  4936.5 2056.39  4945.8 2057.83  4955.3 2058.03  4967.4 2057.71
  4978.1 2055.59  4988.3 2054.78  4988.6 2054.28  4992.2 2054.28  4992.5 2054.78
    4997 2055.61  5002.6 2055.61  5007.5 2058.79  5013.4 2058.74  5028.9 2066.63
  5050.3 2069.56  5065.8 2072.79  5071.6 2073.09  5087.2 2075.73  5116.3 2076.83
#Mann= 3 ,-1 , 0
  4622.7     .07       0  4988.3     .05       0  4992.5     .07       0
Bank Sta=4988.3,4992.5
XS Rating Curve= 0 ,0
Exp/Cntr=0.3,0.1

Type RM Length L Ch R = 1 ,1483    ,493,493,493
BEGIN DESCRIPTION:
Stream1232 3.0
END DESCRIPTION:
XS GIS Cut Line= 3
       1874032.9     13907585.22      1874214.38     13907226.51
      1874274.98     13907125.04
#Sta/Elev= 30
  4599.4 2069.78  4615.8 2069.19  4660.4 2066.39  4682.6 2064.88  4689.3 2063.87
  4704.9 2063.33  4711.7 2062.39  4721.6  2062.5  4727.2 2062.09  4743.9 2062.34
  4810.7  2058.6  4855.3 2057.21  4905.5 2056.36  4927.8 2055.15  4958.3 2052.46
  4972.3 2050.64  4986.9 2050.33  4987.2 2049.83  4990.9 2049.83  4991.2 2050.33
  4994.6 2050.42  4999.5 2051.37  5005.2 2051.37  5010.7  2055.2  5016.5 2056.67
  5026.3 2061.73  5038.1  2063.7  5061.4 2065.27  5074.9 2065.06  5119.6 2065.88
#Mann= 3 ,-1 , 0
  4599.4     .07       0  4986.9     .05       0  4991.2     .07       0
Bank Sta=4986.9,4991.2
XS Rating Curve= 0 ,0
Exp/Cntr=0.3,0.1

Type RM Length L Ch R = 1 ,990     ,412,412,412
BEGIN DESCRIPTION:
Stream1232 2.0
END DESCRIPTION:
XS GIS Cut Line= 3
      1874575.01     13907674.96      1874623.36     13907478.96
      1874474.99     13907024.96
#Sta/Elev= 30
  4800.1 2082.88  4810.4  2081.8  4818.2 2079.55  4823.4 2080.06    4831 2077.86
  4841.3 2076.16  4851.6 2075.89  4859.7 2074.27  4864.8 2074.15  4882.5 2068.69
  4901.2 2061.44  4906.3 2061.07  4913.4 2057.63  4923.7 2054.22  4942.6 2050.06
  4964.9 2047.63  4987.1 2047.45  4987.4 2046.95  4991.1 2046.95  4991.4 2047.45
  5006.7 2047.82  5012.1 2048.61  5017.4 2048.24    5044 2052.04    5113  2054.9
  5203.4 2056.47    5299 2059.39  5311.2 2060.34    5368 2061.71  5479.6 2063.34
#Mann= 3 ,-1 , 0
  4800.1     .07       0  4987.1     .05       0  4991.4     .07       0
#XS Ineff= 2 , 0
                         5131.91         2055.36
Permanent Ineff=
       F       F
Bank Sta=4987.1,4991.4
XS Rating Curve= 0 ,0
Exp/Cntr=0.3,0.1

Type RM Length L Ch R = 1 ,578     ,333,333,333
BEGIN DESCRIPTION:
Stream1232 1.0
END DESCRIPTION:
XS GIS Cut Line= 3
      1874985.27     13907710.96       1875003.9      13907566.6
      1874674.99     13907124.99
#Sta/Elev= 30
  4839.6 2065.52  4858.9 2064.65    4896 2062.75  4906.1 2062.88  4953.1 2061.08
  4958.1 2060.07  4976.7 2052.37  4983.4  2047.4  4988.4  2047.4  4997.5 2040.31
  4997.7 2039.81  5001.5 2039.81  5001.8 2040.31  5013.4 2041.16  5021.7 2043.23
  5036.4    2048  5063.4 2049.03  5113.5 2049.67  5199.1 2049.63  5278.2 2049.27
  5292.8 2048.39  5299.1 2049.19  5307.4 2048.73    5322 2048.93  5328.3 2049.58
  5342.9  2049.3  5378.3 2050.92  5428.4 2052.48  5457.6 2052.82  5535.8 2055.64
#Mann= 4 ,-1 , 0
  4839.6      .1       0  4858.9     .07       0  4997.5     .05       0
  5001.8     .07       0
#XS Ineff= 2 , 0
                         5038.56         2055.21
Permanent Ineff=
       F       F
Bank Sta=4997.5,5001.8
XS Rating Curve= 0 ,0
Exp/Cntr=0.3,0.1

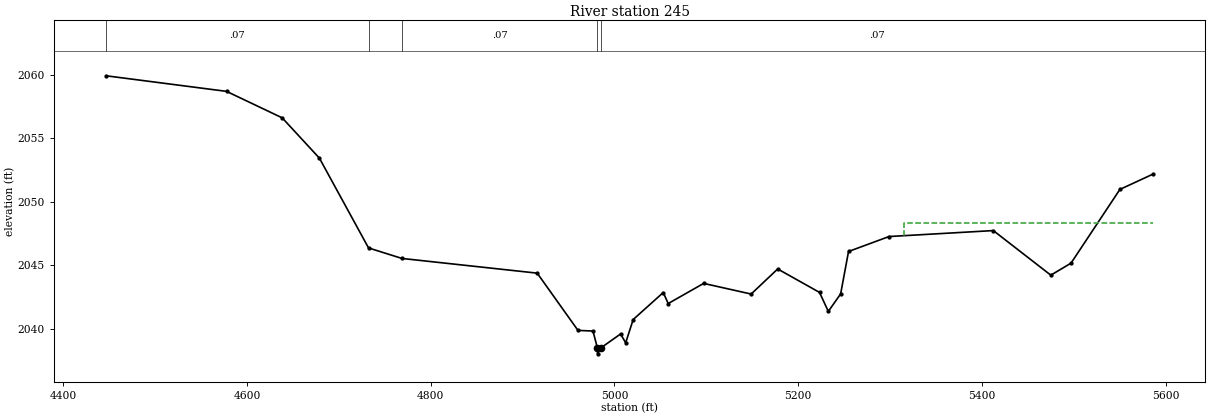
Type RM Length L Ch R = 1 ,245     ,0,0,0
BEGIN DESCRIPTION:
Stream1232 0.0
END DESCRIPTION:
XS GIS Cut Line= 4
      1875230.03     13907914.68      1875298.26     13907450.36
      1875212.54     13907259.21      1874793.92     13907066.37
#Sta/Elev= 30
  4446.6 2059.95  4577.7 2058.72  4638.3 2056.63  4678.8 2053.45  4732.3 2046.36
  4768.7 2045.53  4915.9 2044.37  4960.3 2039.85  4976.6  2039.8  4981.3  2038.5
  4981.6    2038  4985.8  2038.5  5006.7 2039.57  5012.2 2038.87  5020.4 2040.71
  5053.1 2042.84  5058.5 2041.97  5097.1 2043.56  5148.8 2042.72  5177.7  2044.7
  5223.2 2042.85  5232.8 2041.35  5246.2 2042.73  5254.8 2046.08  5298.9 2047.26
  5412.4 2047.73    5475 2044.21    5497 2045.16  5550.2 2050.98  5586.3 2052.19
#Mann= 5 ,-1 , 0
  4446.6     .07       0  4732.3      .1       0  4768.7     .07       0
  4981.3     .05       0  4985.8     .07       0
#XS Ineff= 2 , 0
                          5314.8         2048.32
Permanent Ineff=
       F       F
Bank Sta=4981.3,4985.8
XS Rating Curve= 0 ,0
Exp/Cntr=0.3,0.1

Chan Stop Cuts=-1
Use User Specified Reach Order=0
Composite Channel Slope=5