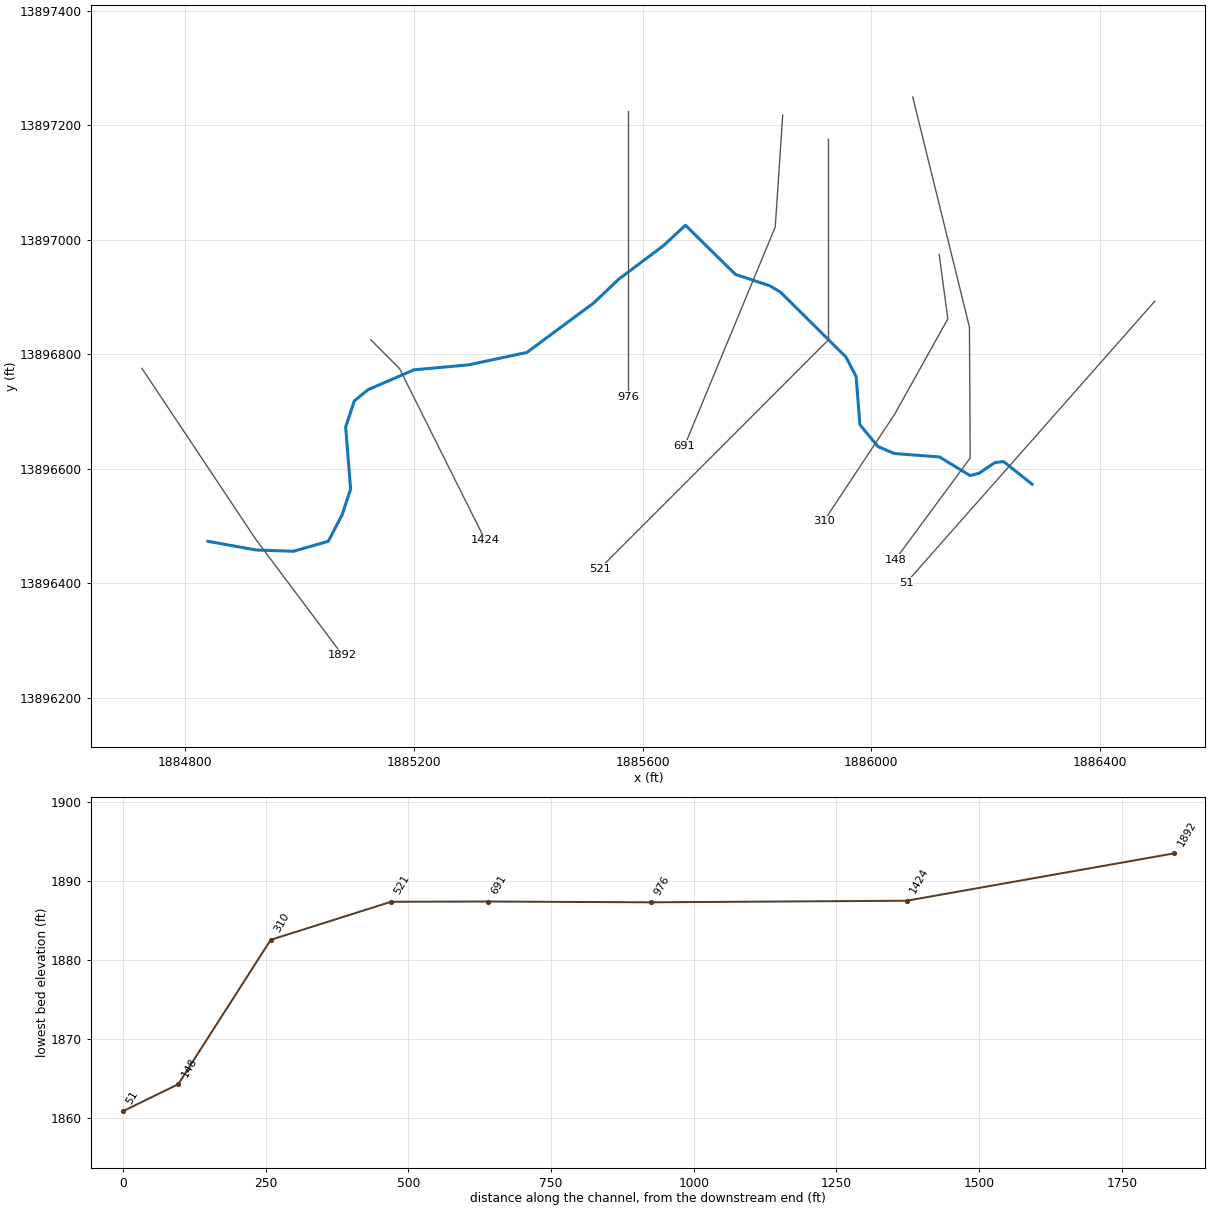
--- Stream9235.prj (project) ---

Proj Title=Stream9235 Base Level Engineering
Current Plan=p01
Default Exp/Contr=0.3,0.1
English Units
Geom File=g01
Flow File=f01
Plan File=p01
BEGIN DESCRIPTION:
Stream9235
END DESCRIPTION:

--- Stream9235.p01 (plan) ---

Plan Title=Multiple Run
Short Identifier=Multiple
Geom File=g01
Flow File=f01
Subcritical Flow
K Sum by GR= 0
Std Step Tol= 0.01
Critical Tol= 0.01
Num of Std Step Trials= 20
Max Error Tol= 0.3
Flow Tol Ratio= 0.001
Split Flow NTrial= 30
Split Flow Tol= 0.02
Split Flow Ratio= 0.02
Log Output Level= 0
Friction Slope Method= 1
Unsteady Friction Slope Method= 2
Unsteady Bridges Friction Slope Method= 1
Parabolic Critical Depth
Global Vel Dist=  1 , 1 , 1
Global Log Level= 0
CheckData=True
Encroach Param= -1, 0, 0, 0
BEGIN DESCRIPTION:
Multiple Run
END DESCRIPTION:

--- Stream9235.f01 (steady flow) ---

Flow Title=Multiple
Number of Profiles=7
Profile Names=10-year,25-year,50-year,1pct_min,100-year,1pct_plu,500-year
River Rch & RM= Stream9235,Reach-1,1892
    1427    2472    3483    2372    4732    9442    8632
River Rch & RM= Stream9235,Reach-1,691
    1454    2523    3558    2426    4840    9657    8845
Boundary for River Rch & Prof#=Stream9235,Reach-1,1
Up Type=0
Dn Type=3
Dn Slope=0.005
Boundary for River Rch & Prof#=Stream9235,Reach-1,2
Up Type=0
Dn Type=3
Dn Slope=0.005
Boundary for River Rch & Prof#=Stream9235,Reach-1,3
Up Type=0
Dn Type=3
Dn Slope=0.005
Boundary for River Rch & Prof#=Stream9235,Reach-1,4
Up Type=0
Dn Type=3
Dn Slope=0.005
Boundary for River Rch & Prof#=Stream9235,Reach-1,5
Up Type=0
Dn Type=3
Dn Slope=0.005
Boundary for River Rch & Prof#=Stream9235,Reach-1,6
Up Type=0
Dn Type=3
Dn Slope=0.005
Boundary for River Rch & Prof#=Stream9235,Reach-1,7
Up Type=0
Dn Type=3
Dn Slope=0.005

--- Stream9235.g01 (geometry) ---

Geom Title=Existing Conditions

River Reach=Stream9235,Reach-1
Reach XY= 30
      1884840.19     13896472.99      1884924.83     13896457.80
      1884989.93     13896455.63      1885050.69     13896472.99
      1885074.57     13896518.57      1885089.76     13896564.14
      1885081.08     13896672.65      1885096.27     13896718.22
      1885120.14     13896737.75      1885200.43     13896772.47
      1885295.92     13896781.15      1885397.92     13896802.85
      1885515.10     13896889.66      1885558.51     13896930.89
      1885636.63     13896989.49      1885675.00     13897025.00
      1885762.24     13896939.23      1885822.63     13896919.22
      1885841.32     13896907.93      1885955.39     13896795.00
      1885973.25     13896760.90      1885979.94     13896676.60
      1886011.33     13896638.52      1886040.03     13896626.32
      1886118.91     13896620.30      1886172.29     13896587.89
      1886187.68     13896591.56      1886215.92     13896610.58
      1886231.06     13896612.22      1886280.84     13896572.71

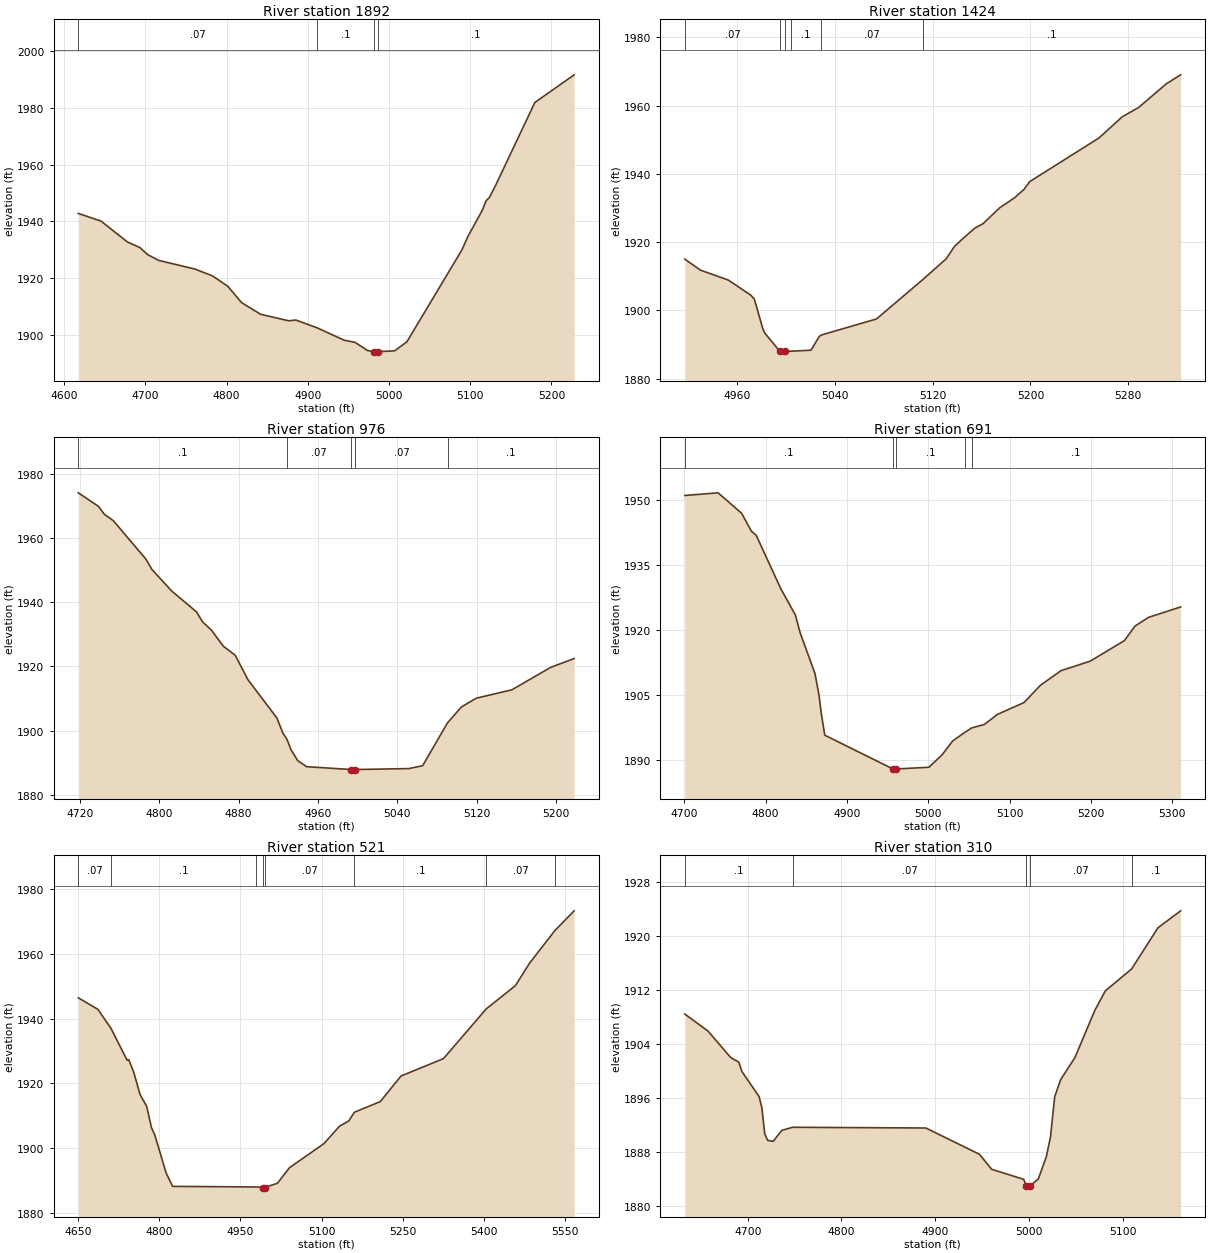
Type RM Length L Ch R = 1,1892,468,468,468
BEGIN DESCRIPTION:
Stream9235 3.0
END DESCRIPTION:
XS GIS Cut Line= 3
      1884725.01     13896774.99      1884925.00     13896475.00
      1885074.97     13896275.03
#Sta/Elev= 30
  4617.4 1942.79  4645.3 1940.09  4677.8 1932.73  4693.3 1930.73  4703.0 1928.21
  4716.4 1926.22  4760.7 1923.19  4782.4 1920.79  4801.4 1917.10  4818.4 1911.33
  4841.9 1907.21  4876.5 1904.91  4885.2 1905.19  4910.7 1902.52  4944.6 1898.09
  4958.3 1897.28  4973.4 1894.43  4981.8 1894.01  4982.0 1893.51  4985.8 1894.01
  5007.0 1894.33  5022.0 1897.53  5089.8 1929.98  5097.0 1934.62  5114.8 1943.89
  5119.5 1947.28  5123.3 1948.30  5130.8 1952.45  5179.5 1981.92  5227.9 1991.68
#Mann=4,-1,0
  4617.4    0.07       0  4910.7     0.1       0  4981.8    0.05       0
  4985.8     0.1       0
Bank Sta=4981.8,4985.8
Exp/Cntr=0.3,0.1

Type RM Length L Ch R = 1,1424,448,448,448
BEGIN DESCRIPTION:
Stream9235 2.0
END DESCRIPTION:
XS GIS Cut Line= 3
      1885125.03     13896824.97      1885175.00     13896775.00
      1885325.01     13896474.98
#Sta/Elev= 30
  4916.9 1915.05  4929.8 1911.81  4952.6 1908.91  4970.7 1904.55  4973.8 1903.41
  4980.7 1894.79  4982.3 1893.44  4994.8 1888.01  4995.0 1887.51  4998.8 1888.01
  5003.7 1888.07  5020.3 1888.37  5027.0 1892.38  5028.8 1892.83  5073.9 1897.52
  5111.9 1909.08  5131.0 1915.14  5137.7 1918.75  5143.6 1920.74  5154.4 1924.11
  5161.2 1925.44  5174.6 1930.03  5187.0 1933.04  5194.7 1935.48  5199.5 1937.79
  5256.1 1950.54  5275.2 1956.76  5288.6 1959.48  5311.3 1966.42  5323.0 1969.05
#Mann=6,-1,0
  4916.9    0.07       0  4994.8    0.05       0  4998.8    0.07       0
  5003.7     0.1       0  5028.8    0.07       0  5111.9     0.1       0
Bank Sta=4994.8,4998.8
Exp/Cntr=0.3,0.1

Type RM Length L Ch R = 1,976,285,285,285
BEGIN DESCRIPTION:
Stream9235 1.0
END DESCRIPTION:
XS GIS Cut Line= 3
      1885575.00     13897224.96      1885575.00     13896975.00
      1885575.00     13896724.96
#Sta/Elev= 30
  4718.3 1974.24  4738.5 1970.05  4744.5 1967.56  4753.5 1965.57  4786.5 1953.51
  4792.5 1950.31  4812.6 1943.53  4837.5 1937.05  4843.5 1933.96  4852.5 1931.36
  4864.5 1926.34  4876.5 1923.52  4889.4 1915.85  4918.5 1903.93  4924.5 1899.25
  4928.8 1897.20  4932.6 1894.11  4939.5 1890.61  4948.5 1888.70  4993.6 1887.81
  4993.9 1887.31  4997.6 1887.81  5051.4 1888.10  5065.5 1889.00  5090.6 1902.39
  5104.5 1907.33  5119.5 1910.09  5155.5 1912.71  5194.5 1919.70  5218.3 1922.48
#Mann=5,-1,0
  4718.3     0.1       0  4928.8    0.07       0  4993.6    0.05       0
  4997.6    0.07       0  5090.6     0.1       0
Bank Sta=4993.6,4997.6
Exp/Cntr=0.3,0.1

Type RM Length L Ch R = 1,691,170,170,170
BEGIN DESCRIPTION:
Stream9235 6.0
END DESCRIPTION:
XS GIS Cut Line= 3
      1885844.97     13897217.36      1885831.94     13897022.04
      1885673.51     13896640.05
#Sta/Elev= 30
  4700.8 1951.15  4741.7 1951.76  4770.6 1947.04  4782.6 1942.91  4788.6 1941.92
  4818.7 1929.62  4836.7 1923.50  4842.7 1919.32  4860.8 1909.96  4865.7 1905.02
  4868.5 1900.81  4872.8 1895.72  4956.6 1887.91  4956.8 1887.41  4960.6 1887.91
  5000.8 1888.31  5017.0 1891.18  5030.0 1894.39  5044.8 1896.36  5053.5 1897.41
  5069.0 1898.21  5084.9 1900.52  5117.7 1903.27  5137.7 1907.24  5163.0 1910.63
  5198.9 1912.83  5241.1 1917.60  5254.1 1920.95  5270.4 1922.95  5310.1 1925.37
#Mann=5,-1,0
  4700.8     0.1       0  4956.6    0.05       0  4960.6     0.1       0
  5044.8    0.07       0  5053.5     0.1       0
Bank Sta=4956.6,4960.6
Exp/Cntr=0.3,0.1

Type RM Length L Ch R = 1,521,211,211,211
BEGIN DESCRIPTION:
Stream9235 5.0
END DESCRIPTION:
XS GIS Cut Line= 3
      1885925.00     13897174.95      1885925.00     13896825.00
      1885525.03     13896425.03
#Sta/Elev= 30
  4650.8 1946.45  4686.9 1942.90  4711.1 1937.01  4740.9 1927.18  4743.9 1927.34
  4752.9 1923.58  4764.9 1916.57  4777.0 1912.95  4785.9 1906.34  4791.9 1904.17
  4812.9 1892.38  4824.9 1888.23  4979.8 1888.05  4990.9 1887.88  4991.2 1887.38
  4994.9 1887.88  5018.6 1889.21  5040.7 1894.00  5104.4 1901.44  5133.1 1906.82
  5150.1 1908.43  5160.5 1911.11  5208.5 1914.42  5246.7 1922.31  5325.0 1927.67
  5404.2 1943.06  5457.7 1950.17  5484.3 1957.20  5530.5 1967.16  5566.4 1973.31
#Mann=8,-1,0
  4650.8    0.07       0  4711.1     0.1       0  4979.8    0.07       0
  4990.9    0.05       0  4994.9    0.07       0  5160.5     0.1       0
  5404.2    0.07       0  5530.5     0.1       0
Bank Sta=4990.9,4994.9
Exp/Cntr=0.3,0.1

Type RM Length L Ch R = 1,310,162,162,162
BEGIN DESCRIPTION:
Stream9235 0.0
END DESCRIPTION:
XS GIS Cut Line= 4
      1886118.40     13896974.31      1886133.59     13896861.45
      1886040.28     13896694.35      1885916.56     13896507.69
#Sta/Elev= 30
  4632.8 1908.42  4657.6 1905.90  4681.8 1901.99  4690.4 1901.32  4693.9 1899.90
  4712.1 1896.23  4715.1 1894.56  4718.1 1890.73  4721.2 1889.75  4727.2 1889.62
  4736.3 1891.23  4747.9 1891.69  4890.1 1891.58  4947.3 1887.70  4960.3 1885.48
  4994.5 1884.00  4997.2 1883.05  4997.5 1882.55  5001.2 1883.05  5010.1 1884.03
  5018.7 1887.37  5023.1 1890.24  5027.6 1896.20  5033.9 1898.71  5049.2 1901.99
  5070.5 1908.98  5081.6 1911.84  5109.7 1915.08  5137.8 1921.16  5162.0 1923.67
#Mann=5,-1,0
  4632.8     0.1       0  4747.9    0.07       0  4997.2    0.05       0
  5001.2    0.07       0  5109.7     0.1       0
Bank Sta=4997.2,5001.2
Exp/Cntr=0.3,0.1

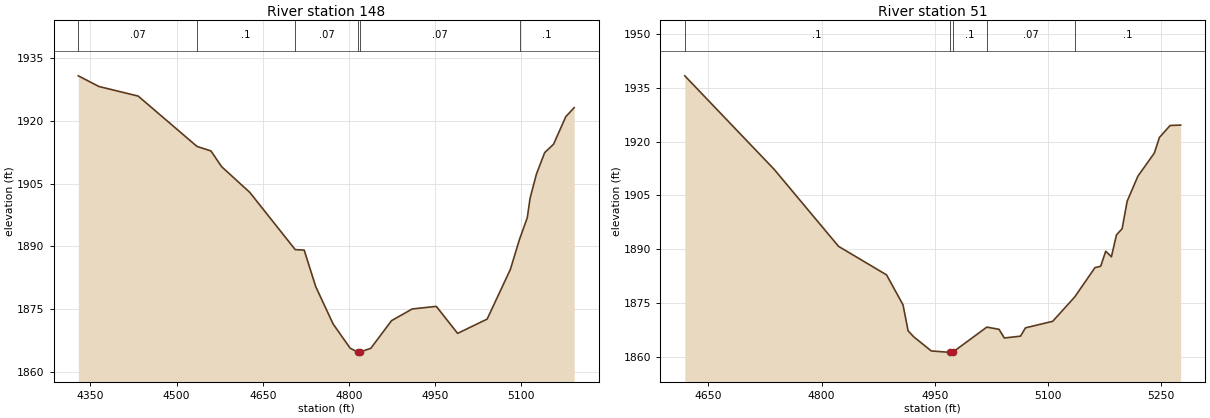
Type RM Length L Ch R = 1,148,97,97,97
BEGIN DESCRIPTION:
Mapping XS 038d2b8e
END DESCRIPTION:
XS GIS Cut Line= 4
      1886072.24     13897248.88      1886171.35     13896847.12
      1886172.66     13896618.39      1886041.65     13896440.82
#Sta/Elev= 30
  4329.0 1930.74  4364.9 1928.19  4433.2 1925.90  4535.6 1913.87  4559.9 1912.79
  4578.4 1909.04  4627.5 1902.89  4706.6 1889.21  4722.2 1889.10  4742.3 1880.37
  4772.6 1871.44  4802.2 1865.66  4815.2 1864.74  4815.4 1864.24  4819.2 1864.74
  4838.2 1865.63  4874.2 1872.23  4910.2 1875.03  4952.2 1875.65  4989.3 1869.20
  5040.7 1872.61  5081.1 1884.47  5097.1 1891.68  5110.6 1896.83  5115.4 1901.45
  5126.4 1907.21  5140.9 1912.40  5156.3 1914.39  5177.6 1920.97  5192.2 1923.13
#Mann=6,-1,0
  4329.0    0.07       0  4535.6     0.1       0  4706.6    0.07       0
  4815.2    0.05       0  4819.2    0.07       0  5097.1     0.1       0
Bank Sta=4815.2,4819.2
Exp/Cntr=0.3,0.1

Type RM Length L Ch R = 1,51,0,0,0
BEGIN DESCRIPTION:
Stream9235 T
END DESCRIPTION:
XS GIS Cut Line= 3
      1886495.27     13896892.26      1886279.15     13896647.49
      1886060.38     13896400.07
#Sta/Elev= 30
  4618.7 1938.28  4737.1 1912.25  4822.4 1890.81  4886.0 1882.87  4907.8 1874.52
  4914.5 1867.31  4921.9 1865.65  4945.2 1861.71  4969.4 1861.32  4969.6 1860.82
  4973.4 1861.32  5018.8 1868.34  5034.9 1867.73  5042.0 1865.31  5063.4 1865.82
  5070.0 1868.14  5106.0 1869.95  5135.3 1876.75  5162.1 1884.91  5169.6 1885.27
  5176.3 1889.47  5183.8 1887.91  5190.5 1894.01  5198.0 1895.72  5204.7 1903.39
  5218.9 1910.35  5240.7 1916.79  5247.4 1921.12  5261.6 1924.46  5275.5 1924.57
#Mann=5,-1,0
  4618.7     0.1       0  4969.4    0.05       0  4973.4     0.1       0
  5018.8    0.07       0  5135.3     0.1       0
Bank Sta=4969.4,4973.4
Exp/Cntr=0.3,0.1

Chan Stop Cuts=-1