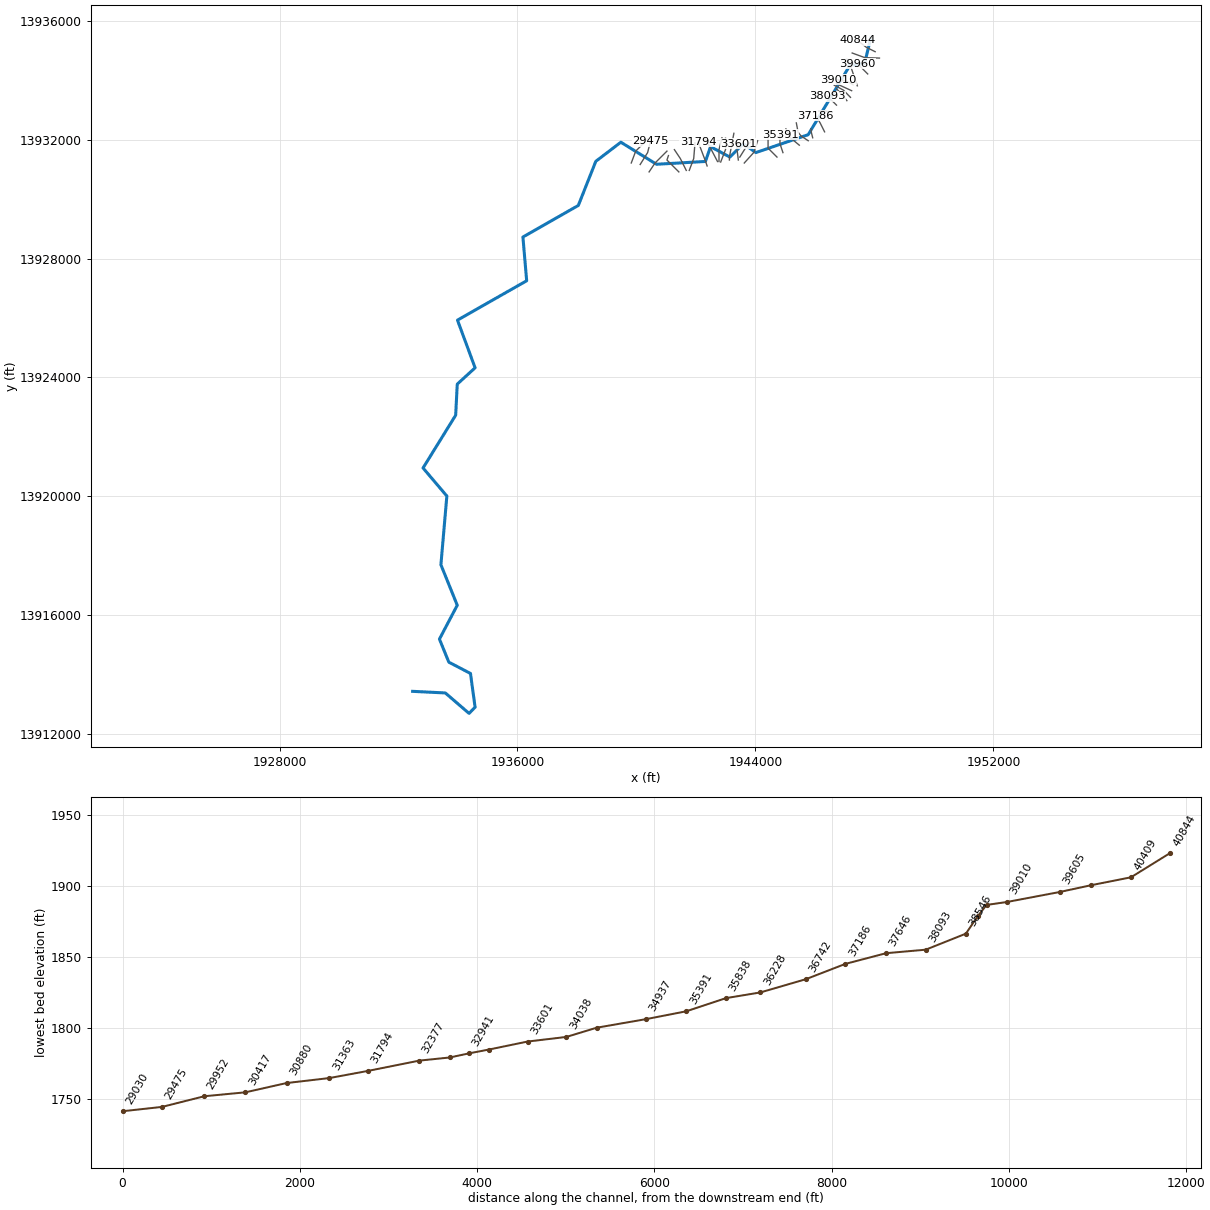
--- Third Creek.prj (project) ---

Proj Title=Third Creek Base Level Engineering
Current Plan=p01
Default Exp/Contr=0.3,0.1
English Units
Geom File=g01
Flow File=f01
Plan File=p01
Y Axis Title=Elevation
X Axis Title(PF)=Main Channel Distance
X Axis Title(XS)=Station
BEGIN DESCRIPTION:
Third Creek
END DESCRIPTION:
DSS Export Rating Curves= 0
DSS Export Rating Curve Sorted= 0
DSS Export Volume Flow Curves= 0
DXF OffsetX= 0
DXF OffsetY= 0
DXF ScaleX= 1
DXF ScaleY= 10

--- Third Creek.p01 (plan) ---

Plan Title=Multiple Run
Short Identifier=Multiple
Geom File=g01
Flow File=f01
Subcritical Flow
K Sum by GR= 0
Std Step Tol= 0.01
Critical Tol= 0.01
Num of Std Step Trials= 20
Max Error Tol= 0.3
Flow Tol Ratio= 0.001
Split Flow NTrial= 30
Split Flow Tol= 0.02
Split Flow Ratio= 0.02
Log Output Level= 0
Friction Slope Method= 1
Unsteady Friction Slope Method= 2
Unsteady Bridges Friction Slope Method= 1
Parabolic Critical Depth
Global Vel Dist=  1 , 1 , 1
Global Log Level= 0
CheckData=True
Encroach Param= -1, 0, 0, 0
BEGIN DESCRIPTION:
Multiple Run
END DESCRIPTION:

--- Third Creek.f01 (steady flow) ---

Flow Title=Multiple
Number of Profiles=7
Profile Names=10-year,25-year,50-year,1pct_min,100-year,1pct_plu,500-year
River Rch & RM= Third Creek,Reach-1,40844
    1537    2661    3748    2552    5091   10158    9270
River Rch & RM= Third Creek,Reach-1,34379
    2368    4182    5968    4107    8194   16350   15264
River Rch & RM= Third Creek,Reach-1,28109
    4457    8067   11697    8159   16279   32480   31166
River Rch & RM= Third Creek,Reach-1,18710
    5002    9117   13280    9299   18555   37021   35822
River Rch & RM= Third Creek,Reach-1,13862
    5041    9170   13340    9327   18610   37132   35821
River Rch & RM= Third Creek,Reach-1,7410
    5263    9592   13971    9778   19511   38929   37635
River Rch & RM= Third Creek,Reach-1,6959
    7578   13977   20525   14469   28870   57603   56487
Boundary for River Rch & Prof#=Third Creek,Reach-1,1
Up Type=0
Dn Type=3
Dn Slope=0.005
Boundary for River Rch & Prof#=Third Creek,Reach-1,2
Up Type=0
Dn Type=3
Dn Slope=0.005
Boundary for River Rch & Prof#=Third Creek,Reach-1,3
Up Type=0
Dn Type=3
Dn Slope=0.005
Boundary for River Rch & Prof#=Third Creek,Reach-1,4
Up Type=0
Dn Type=3
Dn Slope=0.005
Boundary for River Rch & Prof#=Third Creek,Reach-1,5
Up Type=0
Dn Type=3
Dn Slope=0.005
Boundary for River Rch & Prof#=Third Creek,Reach-1,6
Up Type=0
Dn Type=3
Dn Slope=0.005
Boundary for River Rch & Prof#=Third Creek,Reach-1,7
Up Type=0
Dn Type=3
Dn Slope=0.005

--- Third Creek.g01 (geometry) ---

Geom Title=Existing Conditions
Program Version=4.10

River Reach=Third Creek     ,Reach-1
Reach XY= 30
        1947875.       13935425.      1947667.31     13934568.43
      1947180.18     13934520.44       1945773.5     13932178.46
      1944014.66     13931575.89        1943591.     13931874.23
       1943140.4     13931425.07      1942490.16     13931774.64
      1942319.15     13931277.04      1940674.89     13931182.31
        1939475.       13931925.      1938633.09     13931281.31
      1938045.21     13929794.59      1936182.67     13928731.52
      1936308.58      13927258.2      1933982.36     13925931.32
        1934575.       13924325.        1933975.       13923775.
      1933921.25     13922726.55       1932824.5     13920949.96
      1933625.09      13920004.9      1933425.52     13917690.22
        1933975.       13916325.      1933376.22      13915185.5
      1933691.63     13914408.29      1934419.61     13914027.44
      1934574.64     13912890.16      1934371.78     13912682.87
      1933573.41     13913371.18        1932475.       13913425.

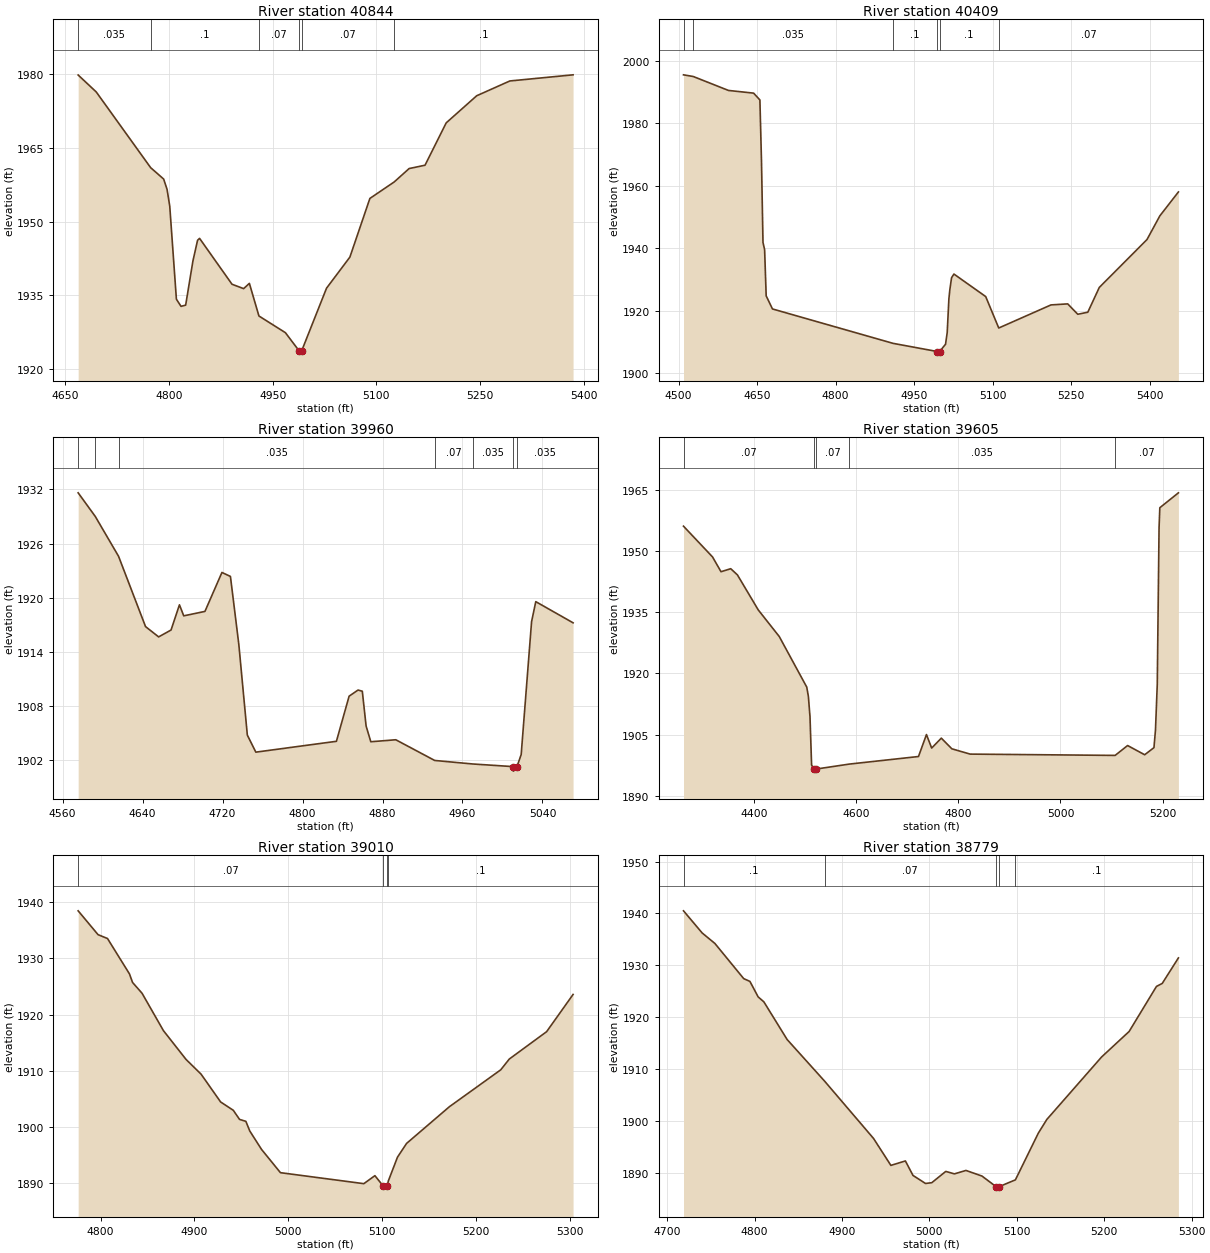
Type RM Length L Ch R = 1 ,40844   ,435,435,435
BEGIN DESCRIPTION:
Third Creek 75.0
END DESCRIPTION:
XS GIS Cut Line= 3
      1948025.03     13934974.98        1947725.       13935125.
      1947427.46     13935361.29
#Sta/Elev= 30
  4668.9 1979.84    4695  1976.4  4773.7 1960.98  4792.5 1958.66  4797.4 1956.57
  4801.3 1953.15  4810.9 1934.21  4817.6 1932.75  4824.3    1933  4834.8 1941.99
  4841.5  1946.2  4844.4 1946.59  4891.3 1937.25  4908.1 1936.36  4916.4 1937.43
  4930.2 1930.79  4968.5 1927.39  4988.1 1923.73  4988.4 1923.23  4992.1 1923.73
  5027.9 1936.44  5061.7 1942.78  5090.6 1954.72  5125.7 1958.07  5147.3  1960.8
  5170.3 1961.48  5200.9  1970.1    5245 1975.62  5292.9 1978.63  5384.3 1979.88
#Mann= 6 ,-1 , 0
  4668.9    .035       0  4773.7      .1       0  4930.2     .07       0
  4988.1     .05       0  4992.1     .07       0  5125.7      .1       0
Bank Sta=4988.1,4992.1
XS Rating Curve= 0 ,0
Exp/Cntr=0.3,0.1

Type RM Length L Ch R = 1 ,40409   ,449,449,449
BEGIN DESCRIPTION:
Third Creek 74.0
END DESCRIPTION:
XS GIS Cut Line= 3
      1948169.91     13934760.16        1947675.       13934775.
      1947252.72      13934930.4
#Sta/Elev= 30
  4509.4 1995.46  4528.1 1994.92  4595.3 1990.46  4643.3  1989.6  4655.3 1987.42
  4658.3 1968.06  4661.2 1941.82  4664.3 1939.52  4667.3 1924.71  4679.3 1920.53
  4909.5 1909.52  4994.4 1906.89  4994.6 1906.39  4998.4 1906.89  5009.8 1909.23
    5013 1913.01  5016.2 1923.76    5018 1926.66  5021.3 1930.51  5025.8  1931.7
  5086.5 1924.49  5111.4 1914.43  5211.2 1921.82  5243.1 1922.15  5262.3 1918.83
  5281.5 1919.48  5303.4 1927.41  5394.5 1942.74    5419 1950.31  5454.5 1957.97
#Mann= 6 ,-1 , 0
  4509.4      .1       0  4528.1    .035       0  4909.5      .1       0
  4994.4     .05       0  4998.4      .1       0  5111.4     .07       0
Bank Sta=4994.4,4998.4
XS Rating Curve= 0 ,0
Exp/Cntr=0.3,0.1

Type RM Length L Ch R = 1 ,39960   ,355,355,355
BEGIN DESCRIPTION:
Third Creek 73.0
END DESCRIPTION:
XS GIS Cut Line= 3
      1947775.01     13934224.99        1947475.       13934525.
      1947424.99     13934575.01
#Sta/Elev= 30
  4575.6 1931.61  4592.7    1929    4616 1924.59    4643 1916.81  4656.1 1915.67
  4668.5 1916.43  4676.9 1919.22  4681.2    1918  4702.4 1918.49  4719.4  1922.8
  4727.9 1922.36  4736.3 1914.83  4744.8 1904.81  4753.3 1902.92  4833.9 1904.12
  4846.6 1909.11  4855.5 1909.79  4859.8 1909.66  4863.6 1905.81  4868.3 1904.07
  4893.3 1904.29  4932.2    1902  4970.3 1901.61  5010.5 1901.32  5010.8 1900.82
  5014.5 1901.32  5018.7 1902.65  5029.1 1917.36  5033.3 1919.57  5070.6 1917.23
#Mann= 7 ,-1 , 0
  4575.6      .1       0  4592.7     .07       0    4616    .035       0
  4932.2     .07       0  4970.3    .035       0  5010.5    .035       0
  5014.5    .035       0
Bank Sta=5010.5,5014.5
XS Rating Curve= 0 ,0
Exp/Cntr=0.3,0.1

Type RM Length L Ch R = 1 ,39605   ,595,595,595
BEGIN DESCRIPTION:
Third Creek 72.0
END DESCRIPTION:
XS GIS Cut Line= 3
      1947424.99     13933825.02      1947174.69      13934562.5
      1947075.02     13934724.96
#Sta/Elev= 30
  4261.6 1956.04  4318.5  1948.5  4335.1 1944.88  4354.1 1945.62  4367.2 1944.11
    4408 1935.53  4449.2    1929    4503 1916.62  4506.2 1914.35  4509.4 1909.32
  4512.5 1897.53  4516.9 1896.53  4517.1 1896.03  4520.9 1896.53  4586.7 1897.76
  4721.9 1899.61  4737.5 1904.99  4747.7 1901.68  4766.6 1904.11  4787.2  1901.5
    4823  1900.2    5107 1899.88  5131.5  1902.3  5164.9 1900.04  5183.1 1901.78
  5186.1 1906.14  5189.6 1917.33  5193.1 1955.66  5194.6 1960.56    5231 1964.21
#Mann= 5 ,-1 , 0
  4261.6     .07       0  4516.9    .035       0  4520.9     .07       0
  4586.7    .035       0    5107     .07       0
Bank Sta=4516.9,4520.9
XS Rating Curve= 0 ,0
Exp/Cntr=0.3,0.1

Type RM Length L Ch R = 1 ,39010   ,231,231,231
BEGIN DESCRIPTION:
Third Creek 71.0
END DESCRIPTION:
XS GIS Cut Line= 3
      1947274.97     13933875.02        1947075.       13933975.
      1946775.01       13934025.
#Sta/Elev= 30
  4776.1 1938.41  4797.3 1934.18  4807.4 1933.49  4830.8 1927.21  4834.1 1925.69
  4844.2 1923.78    4867 1917.14  4891.1 1912.03  4907.2  1909.4    4928 1904.47
  4941.5 1902.99  4948.2 1901.37  4954.9 1901.03  4959.1 1899.31  4971.6 1896.05
  4991.8 1891.91  5080.7 1889.96  5092.5 1891.38  5101.6 1889.49  5101.8 1888.99
  5105.3 1888.99  5105.6 1889.49  5106.8 1890.43  5116.6 1894.67  5126.3 1897.11
  5171.9 1903.62  5226.7 1910.18  5235.8 1912.09  5275.6 1916.95  5303.8 1923.56
#Mann= 4 ,-1 , 0
  4776.1     .07       0  5101.6     .05       0  5105.6     .07       0
  5106.8      .1       0
Bank Sta=5101.6,5105.6
XS Rating Curve= 0 ,0
Exp/Cntr=0.3,0.1

Type RM Length L Ch R = 1 ,38779   ,100,100,100
BEGIN DESCRIPTION:
Mapping XS 97f035da
END DESCRIPTION:
XS GIS Cut Line= 2
      1947234.55     13933661.08      1946720.15     13933897.89
#Sta/Elev= 30
  4718.6  1940.5    4740 1936.23  4754.5 1934.22  4787.5 1927.44  4794.6 1926.91
    4804 1923.93  4810.6 1922.96  4837.2 1915.71  4880.1 1907.69  4936.1 1896.65
  4955.9 1891.47  4972.5 1892.33  4981.2 1889.54  4995.5 1887.99  5002.7 1888.14
  5018.7 1890.31  5028.6 1889.84  5041.8  1890.5  5060.1 1889.42  5076.1  1887.4
  5076.4  1886.9  5080.1  1887.4  5098.4 1888.69  5124.6 1897.68  5134.3 1900.31
    5197 1912.35  5228.5 1917.26  5259.8 1925.94  5266.4 1926.52  5284.9 1931.43
#Mann= 5 ,-1 , 0
  4718.6      .1       0  4880.1     .07       0  5076.1     .05       0
  5080.1     .07       0  5098.4      .1       0
Bank Sta=5076.1,5080.1
XS Rating Curve= 0 ,0
Exp/Cntr=0.3,0.1

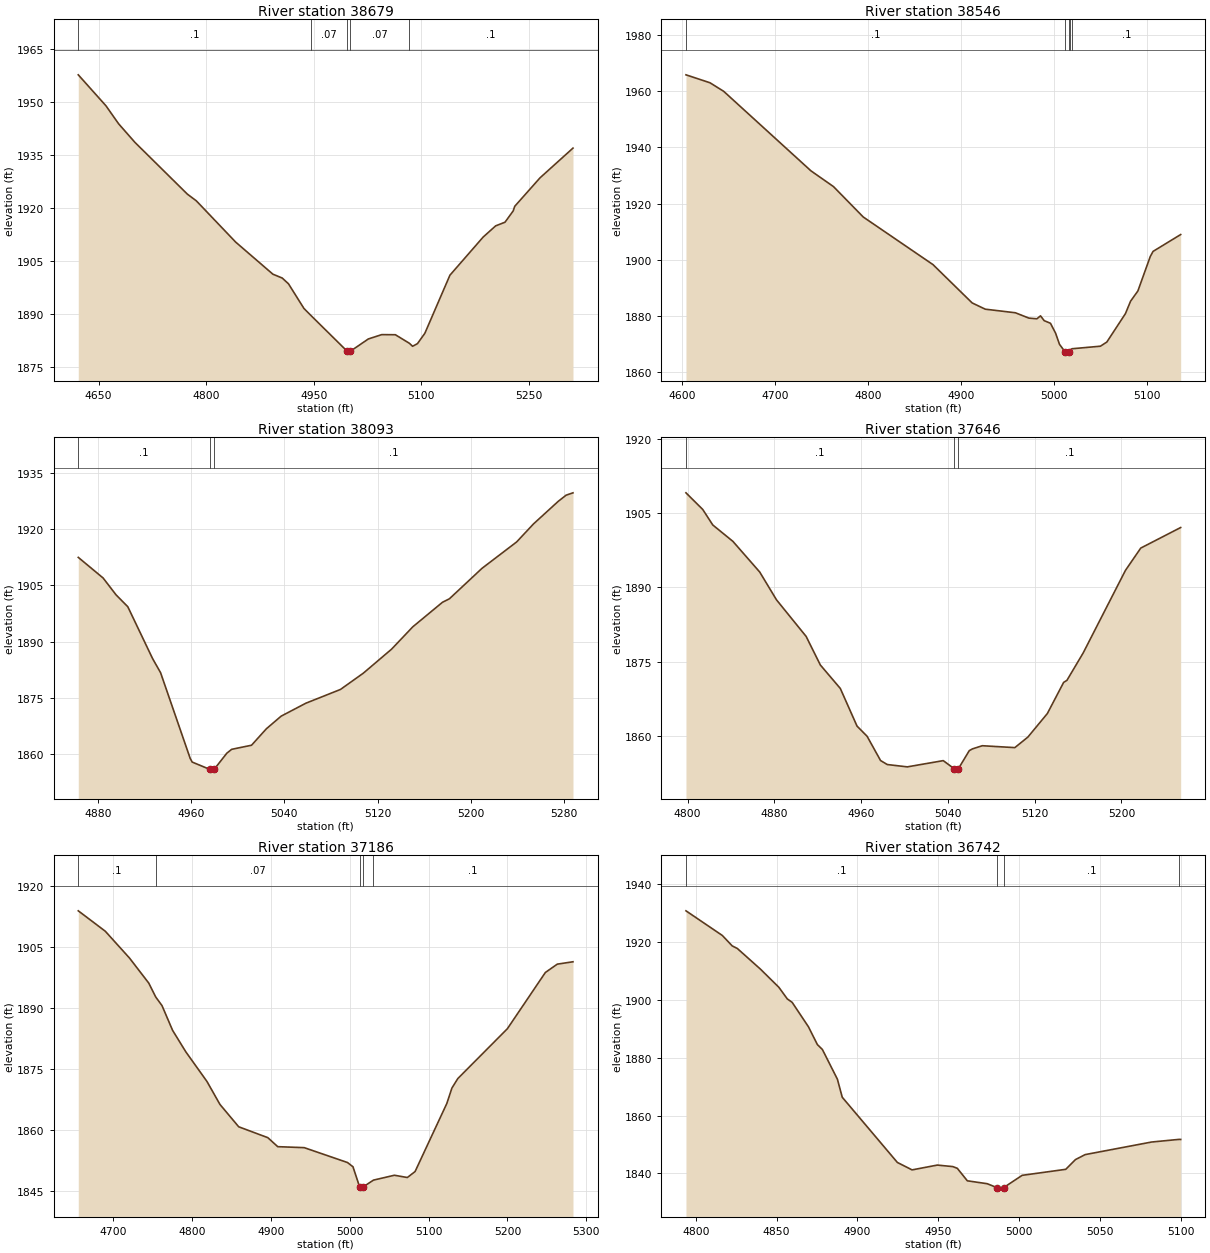
Type RM Length L Ch R = 1 ,38679   ,133,133,133
BEGIN DESCRIPTION:
Third Creek 70.1
END DESCRIPTION:
XS GIS Cut Line= 4
      1947195.21     13933436.42      1946962.59     13933677.72
      1946835.85     13933747.17      1946650.05     13933844.41
#Sta/Elev= 30
  4621.8 1957.74  4660.5 1948.94    4678 1943.87  4700.8  1938.6  4773.8 1923.95
  4786.3 1922.05  4841.2 1910.35    4893 1901.27    4906 1900.18  4914.7 1898.56
  4936.3 1891.56  4945.5 1889.68  4996.7 1879.41    4997 1878.91  5000.7 1879.41
    5026 1882.92  5044.7 1884.15  5063.7 1884.12  5083.2  1881.7  5087.7 1880.85
  5094.5  1881.6  5104.8 1884.54  5139.7 1900.98    5186 1911.78  5203.4 1914.95
  5216.5    1916  5227.9  1919.2    5230 1920.49  5265.3 1928.57  5311.2 1936.98
#Mann= 5 ,-1 , 0
  4621.8      .1       0  4945.5     .07       0  4996.7     .05       0
  5000.7     .07       0  5083.2      .1       0
Bank Sta=4996.7,5000.7
XS Rating Curve= 0 ,0
Exp/Cntr=0.3,0.1

Type RM Length L Ch R = 1 ,38546   ,453,453,453
BEGIN DESCRIPTION:
Third Creek 70.0
END DESCRIPTION:
XS GIS Cut Line= 3
      1947074.97     13933325.03        1946825.       13933625.
      1946724.99     13933725.01
#Sta/Elev= 30
  4604.5  1965.9  4630.3 1963.07  4645.1 1960.01  4738.9 1931.66  4763.1 1926.05
  4795.1 1915.21  4870.1 1898.23  4912.2 1884.57  4926.3 1882.34  4958.7 1881.06
  4973.2 1879.16  4981.8 1878.91  4985.7 1879.97  4989.6 1878.26  4996.4 1877.31
  5001.9 1873.79  5006.1 1869.81    5012 1867.17  5012.2 1866.67    5016 1867.17
  5017.3 1867.79  5019.6 1868.23  5050.1 1869.14    5057 1870.62    5077 1880.75
  5082.5 1885.17  5090.4 1888.84  5103.7 1901.12  5106.7 1902.94  5136.4 1908.95
#Mann= 5 ,-1 , 0
  4604.5      .1       0    5012     .05       0    5016      .1       0
  5017.3     .07       0  5019.6      .1       0
Bank Sta=5012,5016
XS Rating Curve= 0 ,0
Exp/Cntr=0.3,0.1

Type RM Length L Ch R = 1 ,38093   ,447,447,447
BEGIN DESCRIPTION:
Third Creek 69.0
END DESCRIPTION:
XS GIS Cut Line= 3
      1946725.02     13933174.98        1946625.       13933275.
      1946424.99     13933475.01
#Sta/Elev= 30
  4863.2 1912.48  4884.5 1906.97  4895.6 1902.47  4905.7 1899.28  4926.9 1885.46
  4933.8 1881.66  4959.2 1858.75  4960.9 1857.78  4975.8 1855.86  4976.1 1855.36
  4979.6 1855.36  4979.8 1855.86  4990.6 1860.15  4994.8 1861.19  5011.8 1862.28
  5024.5 1866.67  5037.2 1870.05  5058.4 1873.51  5088.1 1877.19  5107.7 1881.54
  5131.9 1887.95  5150.1 1893.92  5175.6 1900.49  5181.5 1901.41  5209.5 1909.56
  5239.2 1916.61  5253.6 1921.41  5274.8 1927.44  5281.6  1929.1  5287.5 1929.73
#Mann= 3 ,-1 , 0
  4863.2      .1       0  4975.8     .05       0  4979.8      .1       0
Bank Sta=4975.8,4979.8
XS Rating Curve= 0 ,0
Exp/Cntr=0.3,0.1

Type RM Length L Ch R = 1 ,37646   ,460,460,460
BEGIN DESCRIPTION:
Third Creek 68.0
END DESCRIPTION:
XS GIS Cut Line= 3
      1946574.97     13932925.01        1946375.       13932975.
      1946125.02       13932975.
#Sta/Elev= 30
  4798.5 1909.11    4814 1905.74  4823.2 1902.62  4841.8  1899.3  4866.5 1893.11
    4882 1887.48  4909.3  1880.1  4922.4 1874.33  4940.8 1869.59  4956.2 1861.99
  4965.5 1859.93  4977.9 1855.03  4984.1 1854.22  5002.6 1853.75  5035.7 1855.01
  5045.7 1853.39  5045.9 1852.89  5049.7 1853.39  5059.7 1857.03  5062.7 1857.39
  5071.7 1858.02  5101.7 1857.64  5113.7 1859.76  5131.7 1864.53  5146.7 1870.82
  5149.7 1871.22  5164.7 1876.76  5203.7 1893.45  5217.8 1897.95  5254.6  1902.1
#Mann= 3 ,-1 , 0
  4798.5      .1       0  5045.7     .05       0  5049.7      .1       0
Bank Sta=5045.7,5049.7
XS Rating Curve= 0 ,0
Exp/Cntr=0.3,0.1

Type RM Length L Ch R = 1 ,37186   ,444,444,444
BEGIN DESCRIPTION:
Third Creek 67.0
END DESCRIPTION:
XS GIS Cut Line= 3
      1946324.99     13932275.01        1946175.       13932575.
      1946025.02     13932824.96
#Sta/Elev= 30
  4656.1 1913.92  4690.3  1908.9    4721 1902.29  4745.4 1896.12  4754.3 1892.67
  4762.2 1890.57  4775.6 1884.48  4792.3  1879.2  4819.2 1871.87  4835.6 1866.23
  4859.4 1860.71  4896.3 1858.03  4908.9 1855.81  4942.4 1855.57  4997.2 1851.91
  5004.2 1850.86  5012.7 1845.85  5012.9 1845.35  5016.7 1845.85  5030.2 1847.57
  5056.7 1848.77  5073.1 1848.21  5082.9 1849.68  5123.1 1866.44  5129.6 1870.26
  5137.1  1872.6  5199.9 1884.88    5248 1898.73  5263.1 1900.78    5283 1901.37
#Mann= 5 ,-1 , 0
  4656.1      .1       0  4754.3     .07       0  5012.7     .05       0
  5016.7     .07       0  5030.2      .1       0
Bank Sta=5012.7,5016.7
XS Rating Curve= 0 ,0
Exp/Cntr=0.3,0.1

Type RM Length L Ch R = 1 ,36742   ,514,514,514
BEGIN DESCRIPTION:
Third Creek 66.0
END DESCRIPTION:
XS GIS Cut Line= 3
        1945925.     13932075.01        1945875.       13932275.
        1945875.     13932374.96
#Sta/Elev= 30
  4793.9 1930.68  4816.4 1922.17  4822.5 1918.58  4825.7 1917.67    4840 1910.54
  4851.4 1904.27  4856.6 1900.27  4859.6 1899.09  4869.7 1890.63  4875.2 1884.51
  4878.3 1882.82  4887.6 1872.55  4890.6 1866.32  4924.7 1843.81  4933.8 1841.24
  4949.4  1842.9    4959 1842.38  4961.8 1841.78    4968 1837.47  4980.3 1836.47
  4986.4  1835.1  4986.7  1834.6  4990.4  1835.1  5001.9 1839.36  5028.9 1841.44
  5034.9  1844.8  5040.9 1846.52    5082 1850.86  5099.1 1851.78    5100 1851.75
#Mann= 4 ,-1 , 0
  4793.9      .1       0  4986.4     .05       0  4990.4      .1       0
  5099.1    .035       0
Bank Sta=4986.4,4990.4
XS Rating Curve= 0 ,0
Exp/Cntr=0.3,0.1

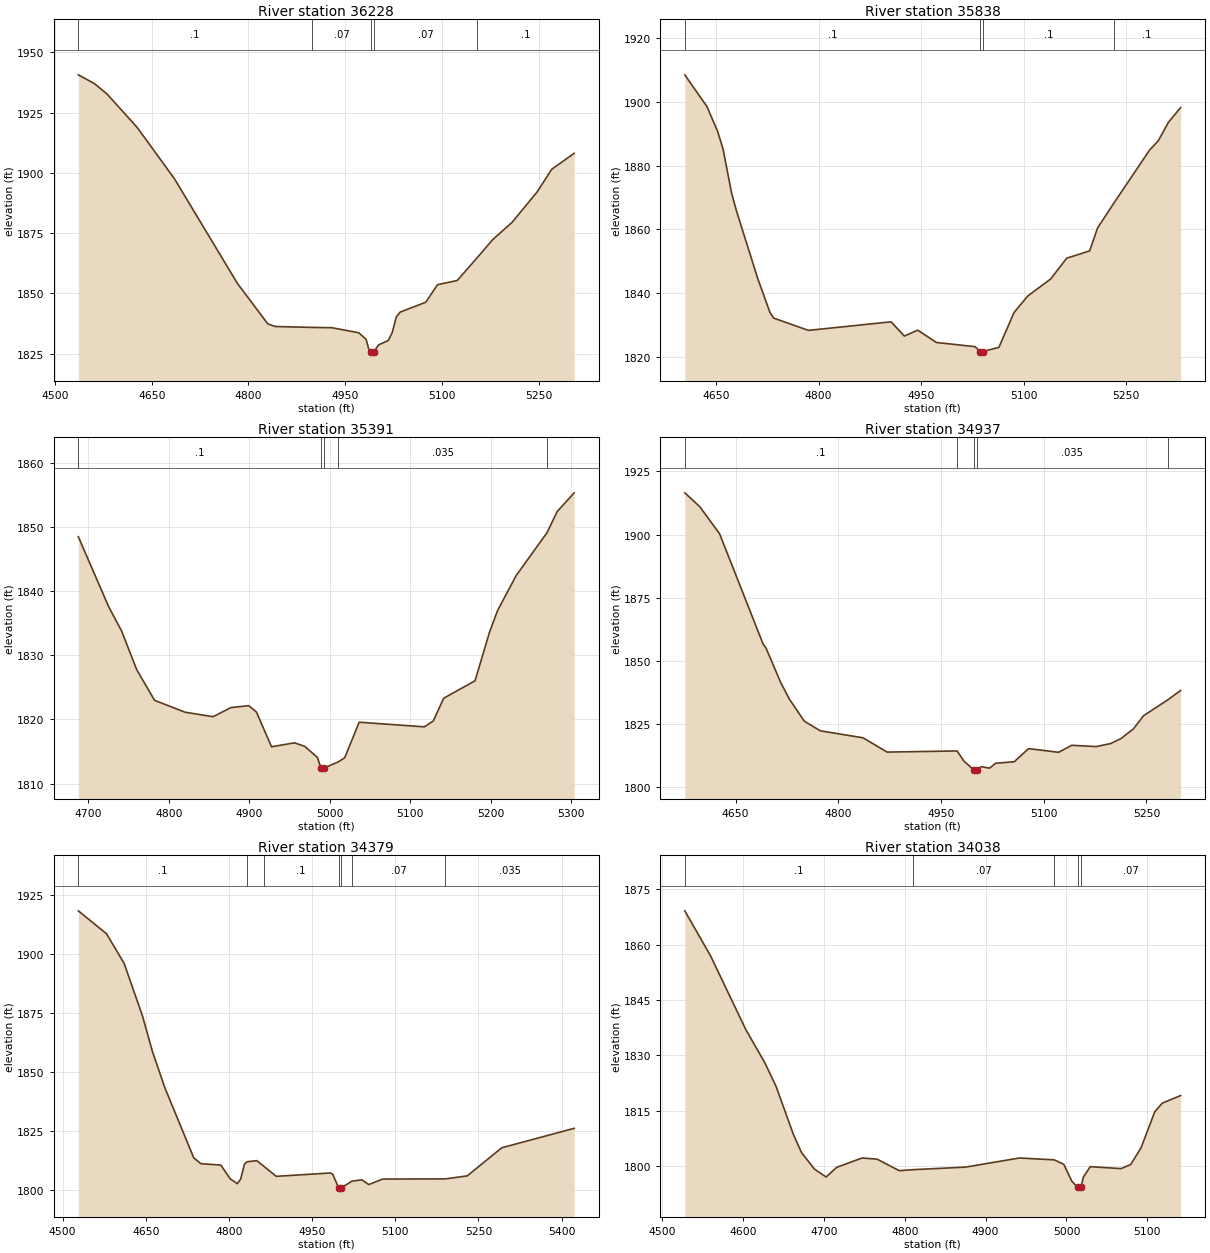
Type RM Length L Ch R = 1 ,36228   ,390,390,390
BEGIN DESCRIPTION:
Third Creek 65.0
END DESCRIPTION:
XS GIS Cut Line= 4
      1945775.01     13931974.99      1945532.23     13932137.48
      1945434.53     13932261.85      1945374.99     13932575.04
#Sta/Elev= 30
  4536.2 1940.64  4561.2    1937  4580.8 1932.67  4627.7 1918.76  4685.2 1897.58
  4782.9 1854.18  4830.1 1837.37  4841.6 1836.28  4898.9  1835.9  4929.3 1835.78
  4971.2 1833.69  4982.7 1830.93  4986.5 1827.09  4990.6 1825.74  4990.9 1825.24
  4994.6 1825.74  5001.8 1828.64  5017.1  1830.5  5023.2 1833.87  5029.3 1840.19
  5035.4 1842.25  5075.1 1846.33  5093.4 1853.62  5123.9 1855.36  5154.3 1864.63
  5178.9 1872.28  5209.1  1879.5  5247.9 1892.09  5270.5 1901.48  5305.3 1908.09
#Mann= 5 ,-1 , 0
  4536.2      .1       0  4898.9     .07       0  4990.6     .05       0
  4994.6     .07       0  5154.3      .1       0
Bank Sta=4990.6,4994.6
XS Rating Curve= 0 ,0
Exp/Cntr=0.3,0.1

Type RM Length L Ch R = 1 ,35838   ,447,447,447
BEGIN DESCRIPTION:
Third Creek 64.0
END DESCRIPTION:
XS GIS Cut Line= 3
      1945474.96     13931825.03        1945175.       13932075.
      1945024.99     13932375.02
#Sta/Elev= 30
    4604 1908.43  4636.5 1898.46  4652.2 1890.62    4660 1885.17  4672.5 1871.38
  4679.5 1865.88  4710.7 1844.65  4728.7 1833.95  4734.2 1832.17  4784.9 1828.33
    4906 1831.01  4925.5 1826.55  4945.1  1828.4  4972.4 1824.53    5029 1823.23
  5036.4  1821.7  5036.6  1821.2  5040.4  1821.7  5063.9 1823.02    5086 1833.92
  5106.1 1839.11  5139.7 1844.45  5163.1 1850.95  5196.7 1853.26  5208.3 1860.42
  5231.8 1868.09  5284.3  1884.8  5297.3 1887.81  5312.1 1893.55  5329.9 1898.18
#Mann= 4 ,-1 , 0
    4604      .1       0  5036.4     .05       0  5040.4      .1       0
  5231.8      .1       0
Bank Sta=5036.4,5040.4
XS Rating Curve= 0 ,0
Exp/Cntr=0.3,0.1

Type RM Length L Ch R = 1 ,35391   ,454,454,454
BEGIN DESCRIPTION:
Third Creek 63.0
END DESCRIPTION:
XS GIS Cut Line= 3
      1944925.01     13931574.96        1944825.       13931875.
        1944825.     13932175.03
#Sta/Elev= 30
  4687.6  1848.5  4725.5 1837.54  4741.3 1833.83  4760.2 1827.76  4782.4 1822.98
  4820.3 1821.13  4855.1 1820.43  4877.2 1821.85  4899.4 1822.15  4908.9 1821.17
  4927.8 1815.74  4956.3 1816.35    4969 1815.81  4984.8 1814.07  4989.1 1812.44
  4989.3 1811.94  4993.1 1812.44  5010.6 1813.37  5018.7 1814.03  5036.7 1819.57
  5117.7 1818.85  5128.8 1819.77  5141.7 1823.31  5180.7 1826.03  5198.7 1833.61
  5208.7 1836.98  5231.7 1842.42  5270.1 1849.12  5282.7 1852.41  5303.9 1855.35
#Mann= 5 ,-1 , 0
  4687.6      .1       0  4989.1     .05       0  4993.1      .1       0
  5010.6    .035       0  5270.1      .1       0
Bank Sta=4989.1,4993.1
XS Rating Curve= 0 ,0
Exp/Cntr=0.3,0.1

Type RM Length L Ch R = 1 ,34937   ,558,558,558
BEGIN DESCRIPTION:
Third Creek 62.0
END DESCRIPTION:
XS GIS Cut Line= 3
      1944725.03     13931424.97        1944425.       13931725.
        1944425.     13932024.99
#Sta/Elev= 30
  4575.7 1916.49  4597.6 1911.02  4626.5 1900.32  4690.1 1856.66  4694.4 1855.08
  4715.6 1841.58  4728.3 1834.97  4750.3 1826.17  4773.7 1822.35    4836  1819.6
  4871.3 1813.94  4973.5 1814.39  4983.7  1810.3    4998 1806.91  4998.3 1806.41
    5002 1806.91  5008.9 1808.17  5020.9 1807.59  5029.9 1809.54  5056.9 1810.12
  5077.9 1815.31  5121.8 1813.86  5140.9 1816.63  5176.9 1816.12  5197.9 1817.33
  5212.9  1819.3  5230.9 1823.08  5245.9 1828.34  5281.4 1834.63    5300 1838.32
#Mann= 5 ,-1 , 0
  4575.7      .1       0  4973.5    .035       0    4998    .035       0
    5002    .035       0  5281.4      .1       0
Bank Sta=4998,5002
XS Rating Curve= 0 ,0
Exp/Cntr=0.3,0.1

Type RM Length L Ch R = 1 ,34379   ,341,341,341
BEGIN DESCRIPTION:
Third Creek 61.0
END DESCRIPTION:
XS GIS Cut Line= 3
      1943624.98     13931224.98      1943946.68     13931581.83
      1944074.99     13931974.98
#Sta/Elev= 30
  4528.5 1918.31  4579.5 1908.55  4611.2 1895.97  4644.1 1873.84  4662.2 1858.62
  4684.5 1843.33  4736.6 1813.63  4749.5 1811.14  4785.5 1810.54  4802.4 1804.69
  4815.2 1802.68  4821.2 1804.61  4827.9 1810.84  4832.4 1811.93  4850.1 1812.43
  4862.5 1810.14  4885.3 1805.77  4983.4 1807.21  4987.5 1806.52  4997.9 1800.85
  4998.2 1800.35    5002 1800.85  5021.8 1803.71  5039.5 1804.31  5052.1 1802.29
  5077.4 1804.62  5190.2 1804.69  5229.7 1805.96    5292 1817.88  5422.5 1826.12
#Mann= 7 ,-1 , 0
  4528.5      .1       0  4832.4     .07       0  4862.5      .1       0
  4997.9     .05       0    5002      .1       0  5021.8     .07       0
  5190.2    .035       0
Bank Sta=4997.9,5002
XS Rating Curve= 0 ,0
Exp/Cntr=0.3,0.1

Type RM Length L Ch R = 1 ,34038   ,437,437,437
BEGIN DESCRIPTION:
Third Creek 60.0
END DESCRIPTION:
XS GIS Cut Line= 3
      1943474.98     13931424.97        1943725.       13931825.
      1943825.03     13931925.03
#Sta/Elev= 30
    4528 1869.11  4559.7 1857.01  4603.4 1837.03  4626.9 1828.06  4641.1 1821.52
  4662.3 1808.65  4672.3 1803.77  4688.3 1799.29  4702.8 1797.14  4715.9 1799.76
  4747.2 1802.28  4765.9 1801.96  4793.2 1798.85  4810.2 1799.12  4875.1 1799.81
  4941.8 1802.28    4985 1801.77  4996.7 1800.58  5006.6 1796.02  5013.8 1794.36
  5014.1 1793.86  5017.9 1794.36  5020.9  1797.1  5029.4 1799.93  5067.6 1799.41
  5079.5 1800.52  5092.3 1805.05  5109.2 1814.77  5118.5 1817.11  5141.2 1819.17
#Mann= 5 ,-1 , 0
    4528      .1       0  4810.2     .07       0    4985     .07       0
  5013.8     .05       0  5017.9     .07       0
Bank Sta=5013.8,5017.9
XS Rating Curve= 0 ,0
Exp/Cntr=0.3,0.1

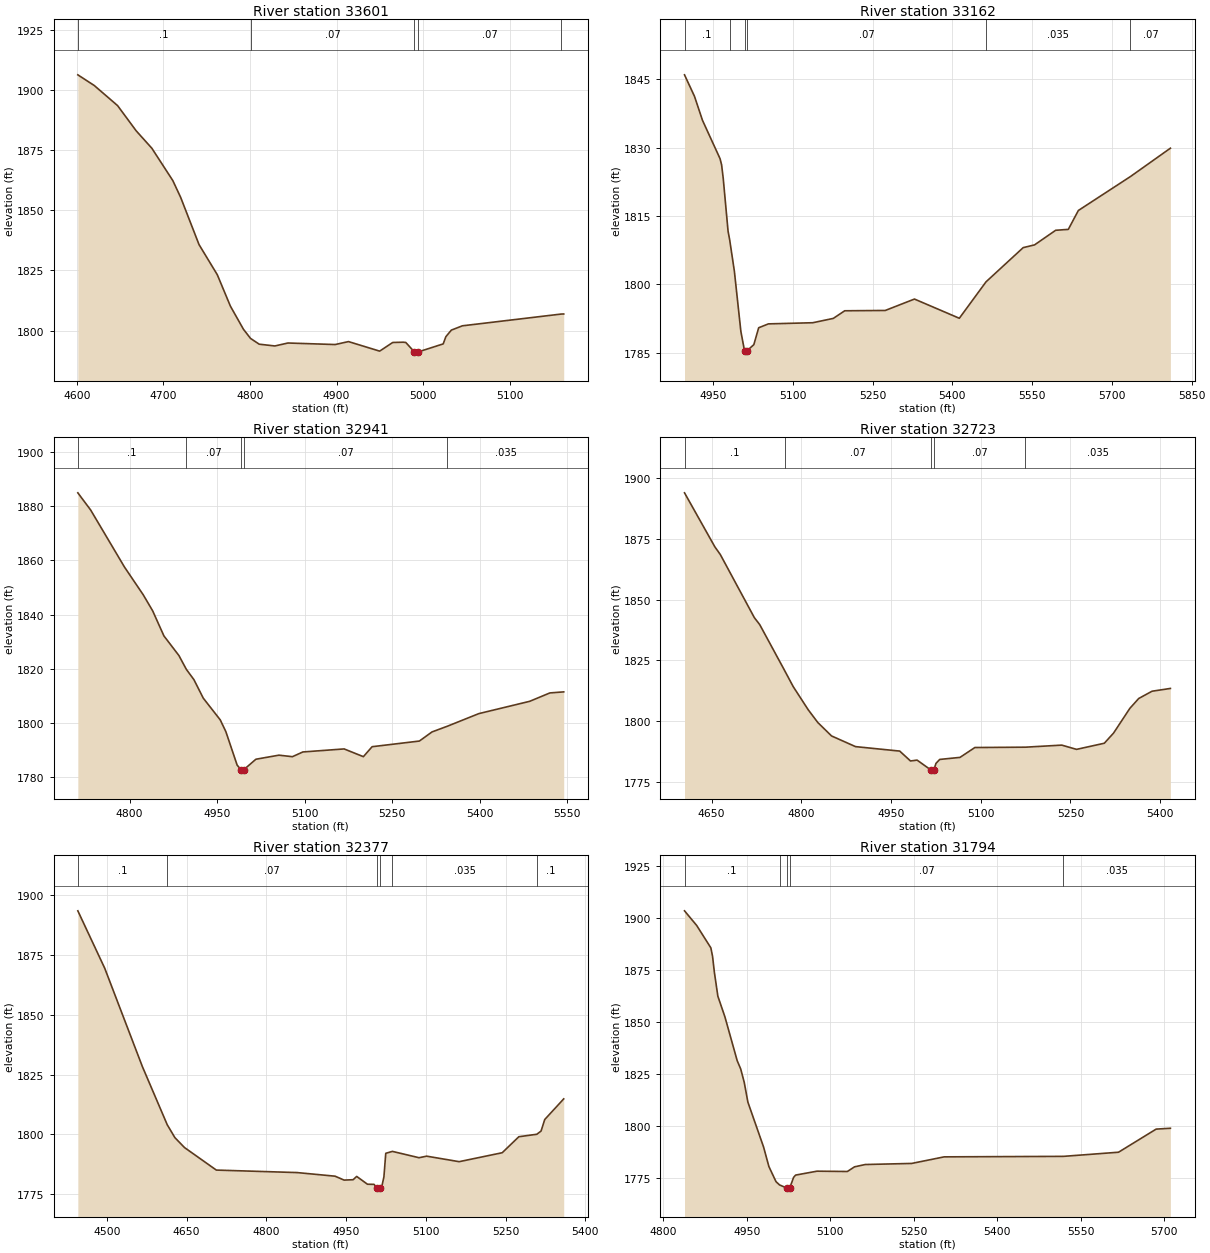
Type RM Length L Ch R = 1 ,33601   ,439,439,439
BEGIN DESCRIPTION:
Third Creek 59.0
END DESCRIPTION:
XS GIS Cut Line= 3
        1943425.       13931325.        1943375.       13931725.
      1943424.99     13931874.97
#Sta/Elev= 30
  4601.2  1906.4  4620.2 1901.95  4647.1  1893.6  4668.6  1883.1  4686.7 1875.85
  4710.9 1862.41    4720 1855.39  4741.2 1835.76  4762.3 1823.23  4777.4 1810.18
  4792.5 1800.54  4800.7 1796.73  4810.7 1794.34  4828.8  1793.6  4843.9 1794.83
  4898.4 1794.19  4913.8 1795.42  4949.8 1791.45  4964.9 1795.05    4977 1795.16
    4980 1795.06  4989.9 1791.12  4990.2 1790.62  4994.3 1791.12  5023.2 1794.46
  5026.3 1797.47  5032.6 1800.19  5045.3 1801.98  5159.6 1806.88  5162.4  1806.9
#Mann= 5 ,-1 , 0
  4601.2      .1       0  4800.7     .07       0  4989.9     .05       0
  4994.3     .07       0  5159.6    .035       0
Bank Sta=4989.9,4994.3
XS Rating Curve= 0 ,0
Exp/Cntr=0.3,0.1

Type RM Length L Ch R = 1 ,33162   ,221,221,221
BEGIN DESCRIPTION:
Third Creek 58.0
END DESCRIPTION:
XS GIS Cut Line= 3
        1943125.     13931325.02        1943125.       13931425.
        1943275.     13932224.98
#Sta/Elev= 30
  4896.1 1845.94  4914.9 1841.22  4929.9 1835.97  4962.9 1827.58  4965.9  1826.2
  4968.9 1823.27    4978  1811.7  4981.1 1809.74  4989.9 1802.89  5002.1 1789.71
    5009 1785.45  5009.3 1784.95  5013.5 1785.45  5026.5 1786.81  5035.6 1790.51
  5053.9 1791.36  5137.3 1791.61    5176 1792.56  5197.4 1794.23  5273.7  1794.3
  5328.6  1796.8    5413 1792.59  5463.2 1800.57  5533.1 1808.07  5554.5 1808.67
  5594.2 1811.87    5618 1812.07  5636.9 1816.21  5734.9 1823.65    5810 1829.86
#Mann= 6 ,-1 , 0
  4896.1      .1       0  4981.1     .07       0    5009     .05       0
  5013.5     .07       0  5463.2    .035       0  5734.9     .07       0
Bank Sta=5009,5013.5
XS Rating Curve= 0 ,0
Exp/Cntr=0.3,0.1

Type RM Length L Ch R = 1 ,32941   ,218,218,218
BEGIN DESCRIPTION:
Mapping XS 715e7036
END DESCRIPTION:
XS GIS Cut Line= 3
       1942831.6     13931257.38      1942996.01     13931681.27
      1942994.18     13932059.21
#Sta/Elev= 30
  4711.4 1884.85  4733.4 1878.51  4791.3 1857.52  4823.5 1847.27  4839.6 1841.38
  4858.9 1832.14  4884.6  1824.9  4897.4 1819.79  4910.3 1816.02  4926.4 1809.18
  4955.4 1801.21  4965.1 1796.83  4984.4 1784.53  4991.1 1782.81  4991.4 1782.31
  4995.6 1782.81  5016.5 1786.69    5056 1788.19  5079.1 1787.63    5097 1789.37
  5167.7 1790.49  5200.7 1787.64  5215.7 1791.31  5296.7 1793.39  5318.3 1796.75
  5344.7 1798.86  5398.7 1803.51  5485.7 1808.03  5520.3 1811.12    5544 1811.51
#Mann= 5 ,-1 , 0
  4711.4      .1       0  4897.4     .07       0  4991.1     .05       0
  4995.6     .07       0  5344.7    .035       0
Bank Sta=4991.1,4995.6
XS Rating Curve= 0 ,0
Exp/Cntr=0.3,0.1

Type RM Length L Ch R = 1 ,32723   ,346,346,346
BEGIN DESCRIPTION:
Third Creek 57.0
END DESCRIPTION:
XS GIS Cut Line= 3
        1942775.     13931275.04        1942775.       13931675.
      1942875.01     13932075.03
#Sta/Elev= 30
  4604.8 1893.99  4655.6 1871.72  4664.6  1868.6  4721.6 1842.58  4730.6  1839.7
    4772 1820.89  4786.6 1814.16  4811.6 1804.66  4827.7 1799.39  4850.6 1793.88
  4890.7 1789.48  4964.6 1787.64  4982.6 1783.57  4993.6 1783.93  5016.6 1779.89
    5017 1779.39  5021.6 1779.89  5025.2 1782.57  5031.4  1784.2  5065.4 1785.05
  5090.2 1789.11  5174.7 1789.25  5235.5  1790.1  5260.2 1788.35  5306.6 1790.87
  5322.1 1795.06  5349.3 1805.23  5364.2 1809.31  5386.4 1812.29  5417.1 1813.44
#Mann= 5 ,-1 , 0
  4604.8      .1       0    4772     .07       0  5016.6     .05       0
  5021.6     .07       0  5174.7    .035       0
Bank Sta=5016.6,5021.6
XS Rating Curve= 0 ,0
Exp/Cntr=0.3,0.1

Type RM Length L Ch R = 1 ,32377   ,583,583,583
BEGIN DESCRIPTION:
Third Creek 56.0
END DESCRIPTION:
XS GIS Cut Line= 3
      1942724.98     13931275.03      1942464.99     13931772.33
      1942286.64     13932076.66
#Sta/Elev= 30
  4445.3 1893.32  4495.9 1869.35  4566.7 1828.31  4613.5 1804.02  4627.9 1798.64
  4645.9 1794.52  4705.8 1785.11  4857.6 1784.07  4929.2 1782.56  4946.1 1780.93
  4963.1 1781.09  4969.8 1782.46  4990.1  1779.2  5002.4 1779.15  5008.1 1777.66
  5008.5 1777.16  5013.1 1777.66  5017.5 1778.68    5021 1782.28  5024.5 1792.11
    5037 1792.91  5087.1 1790.27  5101.4 1790.92  5162.5 1788.62  5243.5 1792.35
  5274.8 1799.03  5308.6 1800.06  5316.6  1801.4  5323.5 1806.21  5359.2 1814.83
#Mann= 6 ,-1 , 0
  4445.3      .1       0  4613.5     .07       0  5008.1     .05       0
  5013.1     .07       0    5037    .035       0  5308.6      .1       0
Bank Sta=5008.1,5013.1
XS Rating Curve= 0 ,0
Exp/Cntr=0.3,0.1

Type RM Length L Ch R = 1 ,31794   ,431,431,431
BEGIN DESCRIPTION:
Third Creek 55.0
END DESCRIPTION:
XS GIS Cut Line= 3
      1942374.99     13931125.03        1942325.       13931275.
      1942072.31     13931943.77
#Sta/Elev= 30
  4838.1 1903.54  4860.1 1896.46  4885.4 1885.77  4888.5 1881.68  4891.7 1874.14
    4898 1862.55  4910.7  1852.6  4932.8 1831.52  4939.1 1827.55  4945.4 1821.16
    4952 1811.61  4980.2 1790.05  4989.7 1780.71  5002.5 1773.44  5008.8 1771.88
  5022.1 1770.35  5022.4 1769.85  5027.1 1770.35  5034.1  1775.5  5037.7 1776.59
  5076.2 1778.47  5130.7 1778.32  5143.5 1780.55  5162.8 1781.67  5246.2 1782.19
  5304.7 1785.35    5519 1785.59  5617.9 1787.58  5685.5 1798.68  5711.1 1799.09
#Mann= 5 ,-1 , 0
  4838.1      .1       0  5008.8     .07       0  5022.1     .05       0
  5027.1     .07       0    5519    .035       0
Bank Sta=5022.1,5027.1
XS Rating Curve= 0 ,0
Exp/Cntr=0.3,0.1

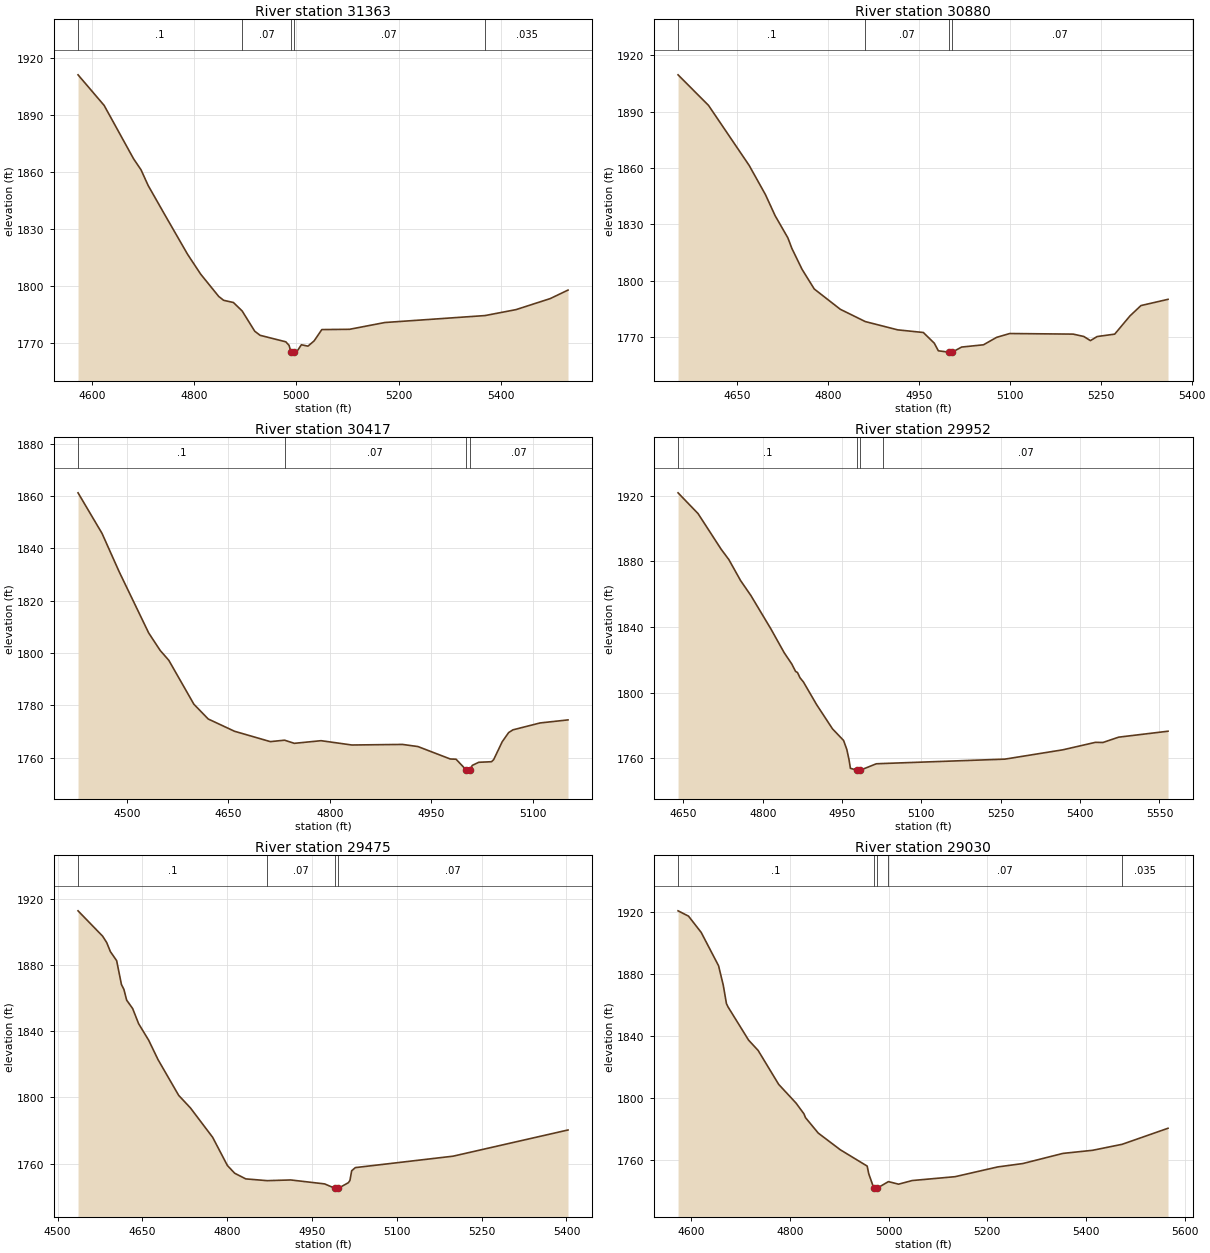
Type RM Length L Ch R = 1 ,31363   ,483,483,483
BEGIN DESCRIPTION:
Third Creek 54.0
END DESCRIPTION:
XS GIS Cut Line= 3
      1941775.01     13930975.03        1941925.       13931375.
      1941968.44     13931905.16
#Sta/Elev= 30
  4572.5 1911.27  4623.6 1895.18  4681.3 1867.06  4695.8 1861.31  4709.8 1853.03
  4742.1 1837.78    4787 1816.83  4812.6 1806.41  4847.9 1794.69  4857.5 1792.66
  4876.7 1791.49  4893.8 1787.04  4918.4  1776.4  4928.9 1774.24  4979.2 1770.82
  4985.6 1768.94  4989.3 1765.37  4989.6 1764.87  4994.3 1765.37  5001.4 1765.92
  5009.7 1769.27  5022.6 1768.54  5034.7 1771.33  5049.7 1777.26  5103.9  1777.4
  5173.1 1780.97  5369.2 1784.63  5429.8 1787.75  5496.8 1793.56  5531.6 1798.03
#Mann= 5 ,-1 , 0
  4572.5      .1       0  4893.8     .07       0  4989.3     .05       0
  4994.3     .07       0  5369.2    .035       0
Bank Sta=4989.3,4994.3
XS Rating Curve= 0 ,0
Exp/Cntr=0.3,0.1

Type RM Length L Ch R = 1 ,30880   ,463,463,463
BEGIN DESCRIPTION:
Third Creek 53.0
END DESCRIPTION:
XS GIS Cut Line= 3
      1941675.01     13930974.99        1941475.       13931375.
      1941274.99     13931675.02
#Sta/Elev= 30
  4553.2 1909.63  4603.4 1893.36  4670.5 1861.34  4697.3  1845.8  4713.4 1834.49
  4734.2 1822.82  4740.9 1817.12  4757.7 1805.98  4777.8 1795.52  4820.7 1784.72
  4861.9 1778.17  4915.3 1773.76  4957.6 1772.35  4975.7 1766.64  4982.4 1762.59
  5000.1 1761.86  5000.5 1761.36  5005.2 1761.86  5020.7 1764.59  5056.8  1765.8
  5078.4 1769.76    5100  1771.8  5204.6 1771.49  5222.2 1770.23  5233.1 1768.02
  5244.2  1770.2  5273.1 1771.48  5298.3 1781.19  5316.4  1786.7    5361 1790.02
#Mann= 4 ,-1 , 0
  4553.2      .1       0  4861.9     .07       0  5000.1     .05       0
  5005.2     .07       0
Bank Sta=5000.1,5005.2
XS Rating Curve= 0 ,0
Exp/Cntr=0.3,0.1

Type RM Length L Ch R = 1 ,30417   ,465,465,465
BEGIN DESCRIPTION:
Third Creek 52.0
END DESCRIPTION:
XS GIS Cut Line= 3
      1941424.97     13930925.03        1941025.       13931325.
      1941075.02     13931475.05
#Sta/Elev= 30
    4428 1861.26  4463.4 1845.77  4488.8 1831.06  4532.4 1807.66  4549.4 1800.97
  4562.1 1797.21  4599.1 1780.43  4620.3 1774.77  4659.1 1770.08  4712.1 1766.11
    4733 1766.66  4747.6 1765.46    4787 1766.47  4832.5 1764.82  4907.3 1765.04
  4930.1 1764.23  4977.9 1759.47  4986.4 1759.39  5001.3 1755.33  5001.7 1754.83
  5006.8 1755.33  5010.4 1757.02  5019.9 1758.21  5038.8 1758.43    5042 1759.23
  5054.6 1766.06  5064.1 1769.57  5070.4 1770.61  5110.5 1773.25  5151.8 1774.42
#Mann= 4 ,-1 , 0
    4428      .1       0    4733     .07       0  5001.3     .05       0
  5006.8     .07       0
Bank Sta=5001.3,5006.8
XS Rating Curve= 0 ,0
Exp/Cntr=0.3,0.1

Type RM Length L Ch R = 1 ,29952   ,477,477,477
BEGIN DESCRIPTION:
Third Creek 51.0
END DESCRIPTION:
XS GIS Cut Line= 3
      1940424.99     13930924.99        1940625.       13931225.
      1941024.96     13931624.96
#Sta/Elev= 30
    4640 1921.81  4677.8 1909.15  4721.6 1887.34    4736 1881.11  4758.2  1868.3
  4777.6 1859.21  4815.3 1838.92  4840.6 1824.31    4855 1817.39  4862.2 1812.86
  4865.8 1812.19  4870.6 1808.98  4877.1 1806.39  4901.9 1792.63    4932 1777.82
  4952.9 1770.76    4959 1765.29  4963.2 1759.03  4965.8 1753.79  4978.3 1752.55
  4978.8 1752.05    4984 1752.55  5014.7 1756.52    5028  1756.7  5257.8 1759.36
  5367.4 1765.05    5429 1769.61  5443.2 1769.52  5472.9 1772.77  5566.2 1776.39
#Mann= 4 ,-1 , 0
    4640      .1       0  4978.3     .05       0    4984      .1       0
    5028     .07       0
Bank Sta=4978.3,4984
XS Rating Curve= 0 ,0
Exp/Cntr=0.3,0.1

Type RM Length L Ch R = 1 ,29475   ,445,445,445
BEGIN DESCRIPTION:
Third Creek 50.0
END DESCRIPTION:
XS GIS Cut Line= 3
      1940124.98     13931174.97        1940375.       13931575.
       1940471.7     13931957.84
#Sta/Elev= 30
  4536.1 1912.86  4579.6 1897.53  4586.8 1893.67  4593.3  1888.2  4604.4 1882.71
  4612.9 1868.26  4617.3 1865.27  4622.1 1858.84  4632.7 1853.75  4643.3 1844.57
    4661 1834.62  4677.6 1822.87  4714.1 1801.26  4734.9 1793.65  4774.2 1775.88
  4800.2 1758.86  4813.2 1754.14  4832.8 1750.73  4870.7 1749.66  4912.2 1750.09
  4972.2  1747.7  4990.6 1745.04  4991.1 1744.54  4996.5 1745.04  5014.3 1748.44
    5017 1749.78  5020.1 1755.65  5026.6 1757.56  5199.5 1764.47  5402.7 1780.31
#Mann= 4 ,-1 , 0
  4536.1      .1       0  4870.7     .07       0  4990.6     .05       0
  4996.5     .07       0
Bank Sta=4990.6,4996.5
XS Rating Curve= 0 ,0
Exp/Cntr=0.3,0.1

Type RM Length L Ch R = 1 ,29030   ,470,470,470
BEGIN DESCRIPTION:
Third Creek 49.0
END DESCRIPTION:
XS GIS Cut Line= 3
        1939825.     13931224.99        1939975.       13931625.
        1940375.       13932025.
#Sta/Elev= 30
  4573.3 1920.65  4594.5 1917.24  4620.2 1906.75  4655.4  1885.3    4665 1872.69
  4671.4  1860.9  4674.6 1858.78  4716.3 1837.39  4735.5 1830.81  4777.2 1808.94
  4812.4 1796.88  4828.4 1789.99  4831.6  1787.5  4857.3  1777.6  4902.1 1766.83
  4956.6 1756.31  4959.8 1751.32  4970.2 1741.99  4970.7 1741.49  4976.1 1741.99
  4999.6 1746.32  5020.2 1744.68  5047.8 1747.02  5134.7  1749.5  5221.1 1755.78
    5272 1757.96  5353.2 1764.49  5413.3 1766.48  5473.3 1770.35  5566.2 1780.67
#Mann= 5 ,-1 , 0
  4573.3      .1       0  4970.2     .05       0  4976.1      .1       0
  4999.6     .07       0  5473.3    .035       0
Bank Sta=4970.2,4976.1
XS Rating Curve= 0 ,0
Exp/Cntr=0.3,0.1