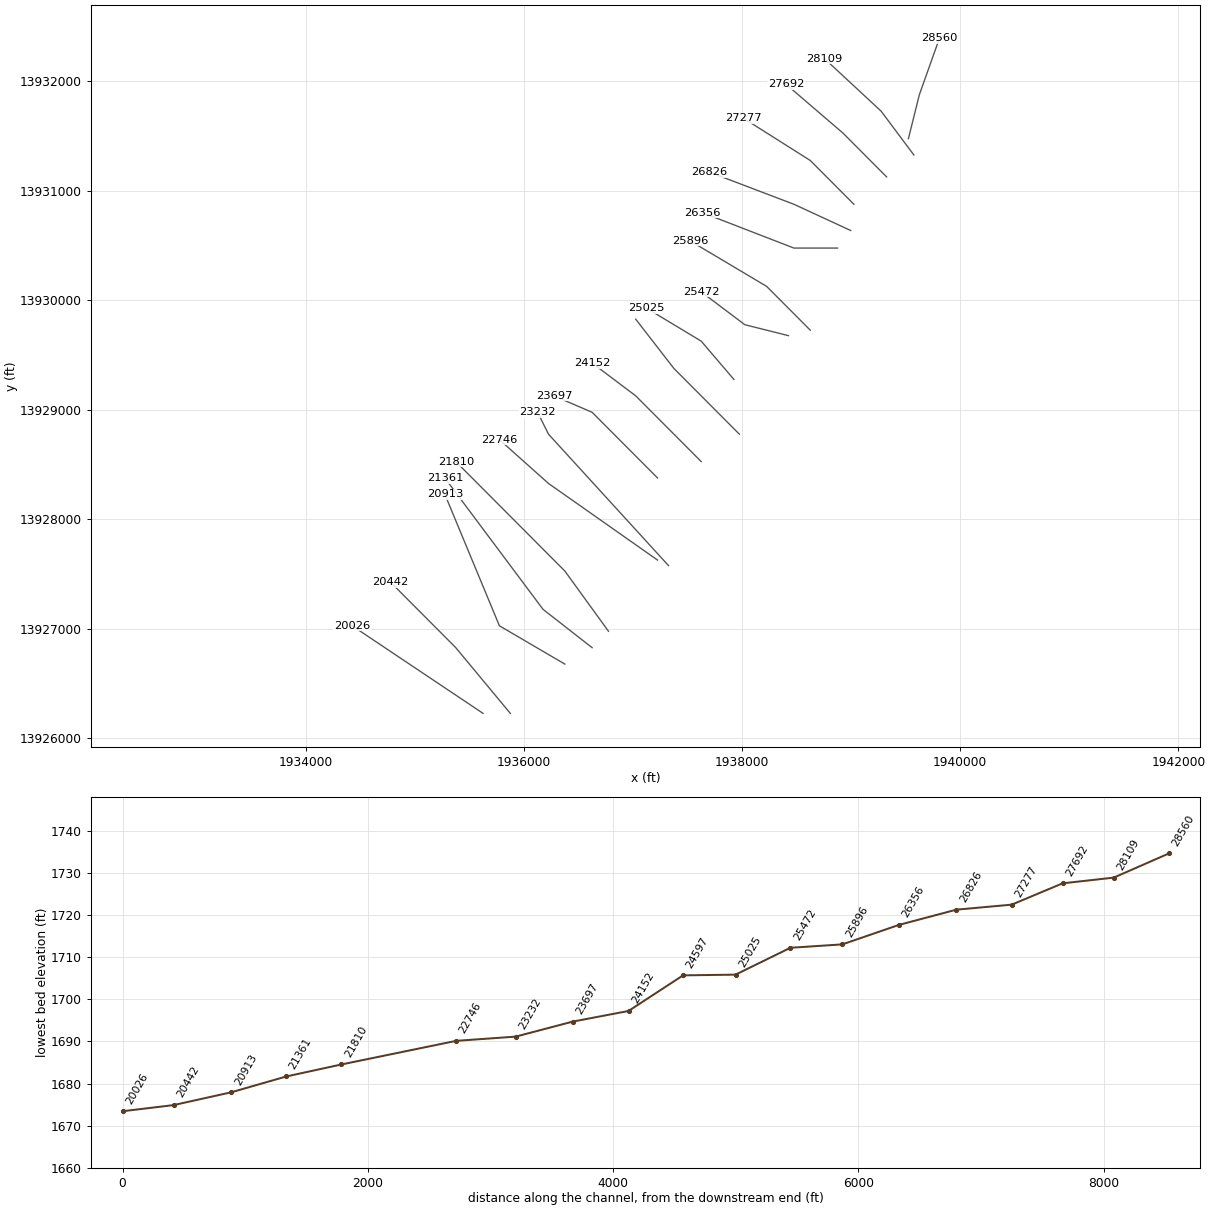
HEC-RAS study Third Creek.prj: Third Creek Base Level Engineering

--- Third Creek.g01 (geometry) --- (continued)

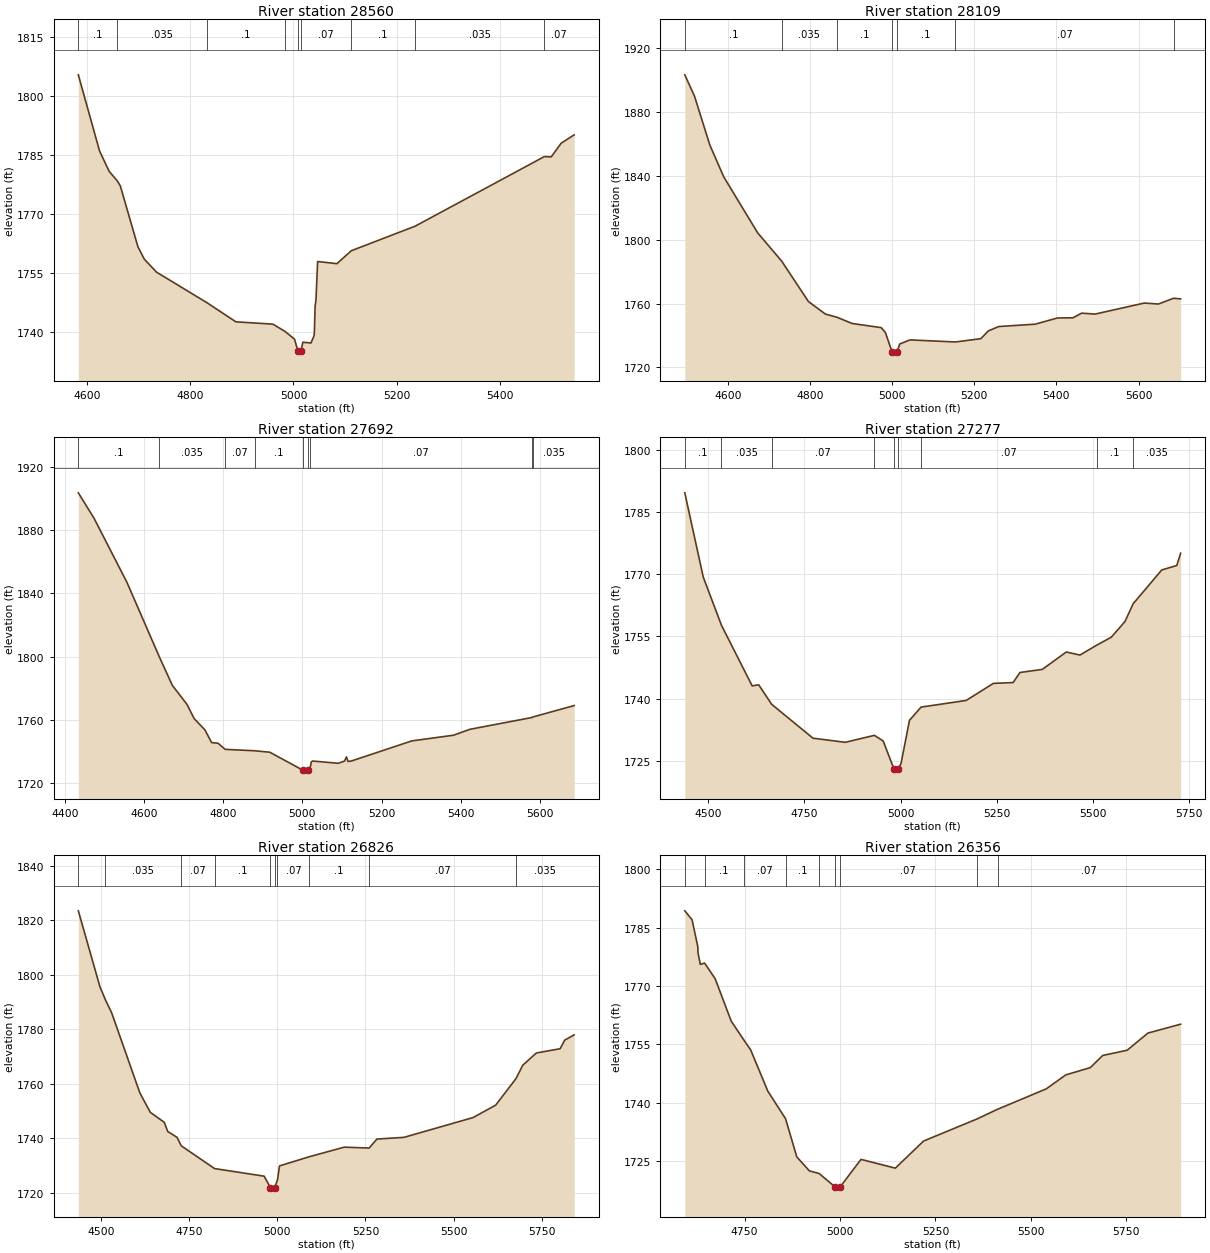
Type RM Length L Ch R = 1 ,28560   ,451,451,451
BEGIN DESCRIPTION:
Third Creek 48.0
END DESCRIPTION:
XS GIS Cut Line= 3
      1939524.99     13931474.97        1939625.       13931875.
      1939809.08     13932390.58
#Sta/Elev= 30
  4583.5 1805.33  4624.6 1786.01  4643.2 1780.85  4659.1 1778.39  4664.8 1777.16
  4698.8 1761.75  4711.2 1758.57  4735.1 1755.26  4832.5 1747.53  4888.5 1742.68
  4960.2 1742.09  4983.9 1740.22  5002.1 1738.26  5008.6 1735.24  5009.1 1734.74
  5014.6 1735.24    5018  1737.5  5033.9 1737.32  5039.5 1739.05  5040.3 1739.66
  5041.9 1746.66  5043.5 1748.21  5046.7 1757.98  5084.1 1757.43  5111.8  1760.7
  5235.5 1766.94  5485.6 1784.59    5499 1784.52  5518.1 1787.98  5543.3  1790.1
#Mann= 9 ,-1 , 0
  4583.5      .1       0  4659.1    .035       0  4832.5      .1       0
  4983.9     .07       0  5008.6     .05       0  5014.6     .07       0
  5111.8      .1       0  5235.5    .035       0  5485.6     .07       0
Bank Sta=5008.6,5014.6
XS Rating Curve= 0 ,0
Exp/Cntr=0.3,0.1

Type RM Length L Ch R = 1 ,28109   ,417,417,417
BEGIN DESCRIPTION:
Third Creek 47.0
END DESCRIPTION:
XS GIS Cut Line= 3
      1939575.02     13931324.98        1939275.       13931725.
      1938755.74     13932205.21
#Sta/Elev= 30
  4495.1 1903.37  4518.7 1890.04  4556.2 1859.28    4590  1839.4  4672.5 1804.36
  4731.3 1786.53  4796.2  1761.3  4837.5 1753.45  4865.6 1751.48  4902.2 1747.58
  4973.5 1744.94  4983.5 1741.91  5000.2 1729.48  5000.7 1728.98  5011.9 1729.48
  5018.3 1734.68  5043.2 1737.27  5154.1 1735.97  5215.9 1738.04  5234.2  1742.9
  5259.4 1745.64  5348.4 1747.13  5402.4    1751  5440.2 1751.12  5461.4 1754.03
  5494.2 1753.45  5613.9 1760.35  5648.5 1759.75  5685.1 1763.36  5702.4 1762.97
#Mann= 7 ,-1 , 0
  4495.1      .1       0  4731.3    .035       0  4865.6      .1       0
  5000.2     .05       0  5011.9      .1       0  5154.1     .07       0
  5685.1      .1       0
Bank Sta=5000.2,5011.9
XS Rating Curve= 0 ,0
Exp/Cntr=0.3,0.1

Type RM Length L Ch R = 1 ,27692   ,415,415,415
BEGIN DESCRIPTION:
Third Creek 46.0
END DESCRIPTION:
XS GIS Cut Line= 3
        1939325.       13931125.        1938925.       13931525.
       1938403.2     13931971.11
#Sta/Elev= 30
  4434.3 1903.48    4474  1887.4  4557.2 1846.83  4638.9 1799.83  4671.7 1781.82
  4708.6 1769.84  4726.9 1760.79    4754 1753.69  4770.9 1745.64  4787.1 1745.25
  4805.1 1741.38  4879.3 1740.49  4917.8 1739.57  5002.1 1728.12  5002.6 1727.62
  5013.8 1728.12  5020.4 1730.44  5022.6 1733.42    5026    1734  5090.6 1732.58
  5106.6 1733.99  5111.4 1736.63  5115.4 1733.75  5123.3 1733.96  5276.5 1746.72
  5381.8 1750.31  5423.3 1754.05    5580  1761.5  5582.9 1761.88  5686.5 1769.05
#Mann= 9 ,-1 , 0
  4434.3      .1       0  4638.9    .035       0  4805.1     .07       0
  4879.3      .1       0  5002.1     .05       0  5013.8      .1       0
  5020.4     .07       0    5580      .1       0  5582.9    .035       0
Bank Sta=5002.1,5013.8
XS Rating Curve= 0 ,0
Exp/Cntr=0.3,0.1

Type RM Length L Ch R = 1 ,27277   ,451,451,451
BEGIN DESCRIPTION:
Third Creek 45.0
END DESCRIPTION:
XS GIS Cut Line= 3
        1939025.       13930875.        1938625.       13931275.
       1938012.8      13931660.6
#Sta/Elev= 30
    4439 1789.57  4486.9 1769.31  4534.3 1757.68  4614.2 1743.08  4631.1 1743.34
  4664.9 1738.64  4772.3 1730.48  4856.3 1729.49    4932 1731.17  4954.8 1729.81
  4982.9 1723.05  4983.4 1722.55  4994.6 1723.05  5001.4 1724.45  5023.2 1734.79
  5053.3 1737.97  5170.6 1739.57  5241.3 1743.68  5292.7 1743.88  5310.4  1746.3
  5368.5 1747.05    5431 1751.24  5466.4  1750.5  5509.8 1752.87    5548 1754.81
  5583.4 1758.56  5604.8 1762.86  5679.2    1771  5718.2 1772.07  5728.2 1775.02
#Mann= 9 ,-1 , 0
    4439      .1       0  4534.3    .035       0  4664.9     .07       0
    4932      .1       0  4982.9     .05       0  4994.6      .1       0
  5053.3     .07       0  5509.8      .1       0  5604.8    .035       0
Bank Sta=4982.9,4994.6
XS Rating Curve= 0 ,0
Exp/Cntr=0.3,0.1

Type RM Length L Ch R = 1 ,26826   ,470,470,470
BEGIN DESCRIPTION:
Third Creek 44.0
END DESCRIPTION:
XS GIS Cut Line= 3
      1938995.69     13930635.49        1938475.       13930875.
      1937696.16     13931170.09
#Sta/Elev= 30
    4436 1823.46  4497.3  1795.6    4513 1790.76  4530.5 1786.05  4610.3 1756.72
  4640.1 1749.53  4679.7 1745.87  4689.6  1742.5    4716 1740.35  4727.9 1737.25
  4822.4  1728.9    4963 1726.11  4980.9 1721.86  4981.4 1721.36  4992.7 1721.86
  5000.7 1724.75  5006.6 1729.89  5090.9 1733.24    5190 1736.76  5260.8 1736.43
  5282.6 1739.72  5359.6 1740.36  5555.3 1747.61  5619.4 1752.16  5677.1 1761.91
  5696.4 1766.84  5734.9 1771.31  5802.3 1772.87  5815.1 1776.01    5842 1777.96
#Mann= 10 ,-1 , 0
    4436      .1       0    4513    .035       0  4727.9     .07       0
  4822.4      .1       0  4980.9     .05       0  4992.7      .1       0
  5000.7     .07       0  5090.9      .1       0  5260.8     .07       0
  5677.1    .035       0
Bank Sta=4980.9,4992.7
XS Rating Curve= 0 ,0
Exp/Cntr=0.3,0.1

Type RM Length L Ch R = 1 ,26356   ,460,460,460
BEGIN DESCRIPTION:
Third Creek 43.0
END DESCRIPTION:
XS GIS Cut Line= 3
      1938875.02       13930475.        1938475.       13930475.
      1937635.58     13930798.72
#Sta/Elev= 30
  4593.1 1789.32  4612.2 1787.03  4627.2  1780.1  4627.8 1778.46  4633.8 1775.53
  4644.9 1775.89  4672.8 1771.84  4714.8 1760.94    4748 1756.07  4765.8 1753.54
  4810.8 1742.92  4857.2 1735.84  4886.7 1726.01  4919.7 1722.41  4945.1 1721.75
  4987.9 1718.22  4988.4 1717.72  4999.8 1718.22    5055 1725.37    5145 1723.12
    5219 1730.09  5358.1 1735.73  5413.1 1738.27  5540.5 1743.51  5591.9 1747.11
  5656.2 1748.99  5688.4  1752.1  5752.7 1753.46  5807.1 1757.87  5892.8 1760.15
#Mann= 9 ,-1 , 0
  4593.1    .035       0  4644.9      .1       0    4748     .07       0
  4857.2      .1       0  4945.1     .07       0  4987.9     .05       0
  4999.8     .07       0  5358.1    .035       0  5413.1     .07       0
Bank Sta=4987.9,4999.8
XS Rating Curve= 0 ,0
Exp/Cntr=0.3,0.1

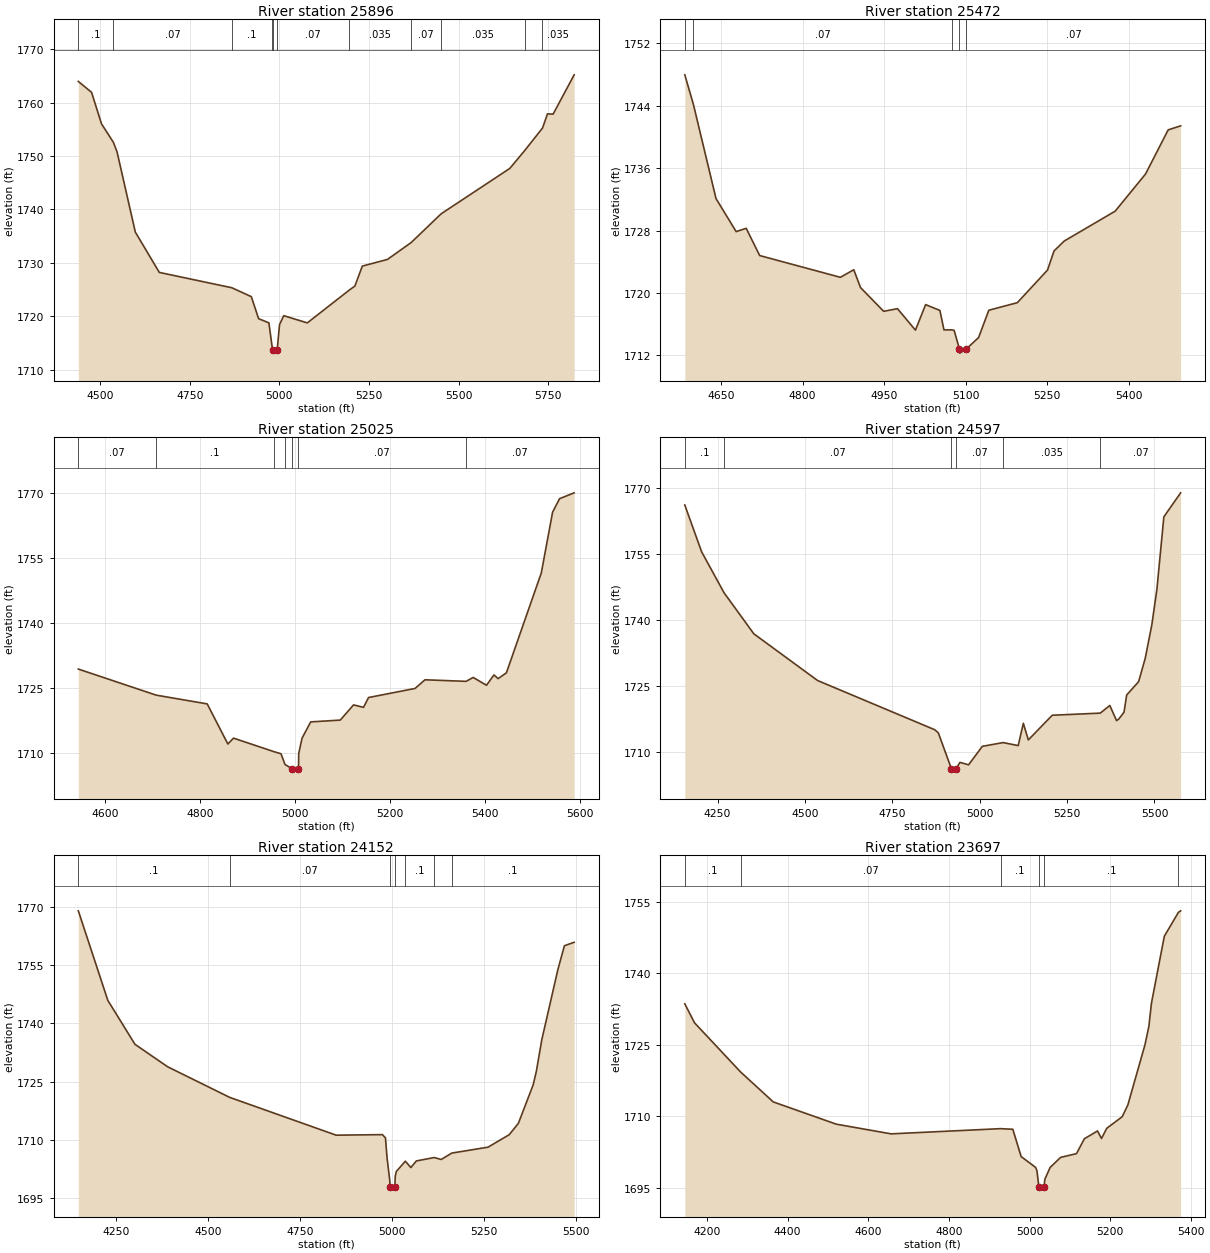
Type RM Length L Ch R = 1 ,25896   ,424,424,424
BEGIN DESCRIPTION:
Third Creek 42.0
END DESCRIPTION:
XS GIS Cut Line= 3
      1938624.98     13929725.02        1938225.       13930125.
      1937522.35     13930541.57
#Sta/Elev= 30
  4439.4 1763.97  4476.3 1761.92    4504 1756.03  4537.2 1752.56  4547.4 1750.77
  4598.3 1735.76  4665.2 1728.21  4867.4 1725.34  4921.8 1723.67    4942 1719.55
  4970.7 1718.77    4979 1714.66  4981.7  1713.6  4982.2  1713.1  4993.7  1713.6
  5000.4 1718.44  5012.2 1720.11  5077.9 1718.76  5195.4 1724.93  5210.5 1725.65
  5231.2 1729.39  5301.3 1730.64  5367.4  1733.8  5451.2 1739.19  5642.5 1747.68
  5684.8 1751.09  5733.6 1755.23  5747.6 1757.89  5763.2 1757.84  5821.9  1765.2
#Mann= 11 ,-1 , 0
  4439.4      .1       0  4537.2     .07       0  4867.4      .1       0
    4979     .07       0  4981.7     .05       0  4993.7     .07       0
  5195.4    .035       0  5367.4     .07       0  5451.2    .035       0
  5684.8     .07       0  5733.6    .035       0
Bank Sta=4981.7,4993.7
XS Rating Curve= 0 ,0
Exp/Cntr=0.3,0.1

Type RM Length L Ch R = 1 ,25472   ,447,447,447
BEGIN DESCRIPTION:
Third Creek 41.0
END DESCRIPTION:
XS GIS Cut Line= 3
      1938424.96     13929675.01        1938025.       13929775.
      1937624.97     13930075.02
#Sta/Elev= 30
  4583.1 1747.97  4598.8 1744.22  4640.5 1732.11  4677.6 1727.87  4696.1 1728.29
  4720.9  1724.8  4869.3 1722.01    4894 1722.98  4906.4  1720.7    4949 1717.65
  4974.4 1717.99  5007.5 1715.24  5026.2 1718.51  5052.5 1717.76    5060 1715.27
  5074.3 1715.27  5078.7 1715.21  5088.5 1712.79    5089 1712.29  5100.6 1712.79
  5123.7 1714.29  5142.5 1717.79    5195 1718.76  5250.5 1722.94  5262.5 1725.39
  5281.2 1726.66    5375 1730.49  5430.9 1735.26  5472.5 1740.91  5495.4 1741.43
#Mann= 5 ,-1 , 0
  4583.1      .1       0  4598.8     .07       0  5074.3     .07       0
  5088.5     .05       0  5100.6     .07       0
Bank Sta=5088.5,5100.6
XS Rating Curve= 0 ,0
Exp/Cntr=0.3,0.1

Type RM Length L Ch R = 1 ,25025   ,428,428,428
BEGIN DESCRIPTION:
Third Creek 40.0
END DESCRIPTION:
XS GIS Cut Line= 3
        1937925.       13929275.        1937625.       13929625.
      1937124.97     13929925.02
#Sta/Elev= 30
  4543.3 1729.43  4707.3 1723.42  4814.7  1721.4  4858.2 1712.15  4870.1 1713.51
  4955.4 1710.38  4970.1 1709.91  4978.5 1707.44    4994  1706.4  4994.5  1705.9
  5006.9  1706.4  5007.4 1709.96  5014.4 1713.49  5032.6 1717.25  5094.9 1717.67
  5122.9 1721.17  5143.9 1720.61  5154.4 1722.87  5252.3 1724.96  5273.3 1726.96
  5359.8  1726.6  5374.8  1727.5  5402.8  1725.7  5418.5 1728.08  5427.3 1727.23
  5444.7 1728.56  5518.2 1751.59    5542 1765.61  5556.7 1768.72  5587.4 1770.07
#Mann= 7 ,-1 , 0
  4543.3     .07       0  4707.3      .1       0  4955.4     .07       0
  4978.5     .07       0    4994     .05       0  5006.9     .07       0
  5359.8     .07       0
Bank Sta=4994,5006.9
XS Rating Curve= 0 ,0
Exp/Cntr=0.3,0.1

Type RM Length L Ch R = 1 ,24597   ,445,445,445
BEGIN DESCRIPTION:
Third Creek 39.0
END DESCRIPTION:
XS GIS Cut Line= 3
      1937974.99     13928775.01        1937375.       13929375.
        1937025.       13929825.
#Sta/Elev= 30
  4156.3 1766.16  4204.5 1755.52  4268.7 1746.22  4353.8 1736.91  4536.3  1726.3
  4871.4 1715.13  4881.6 1714.43  4919.3 1706.23  4919.8 1705.73  4932.3 1706.23
  4943.6 1707.72  4968.2 1707.16  5007.6 1711.36  5067.1 1712.21  5110.2 1711.53
  5124.9 1716.59  5139.2 1712.82  5207.6 1718.42    5345  1718.9  5372.4 1720.64
  5391.6 1717.19  5398.5  1717.6  5412.9  1719.1  5420.5 1723.01  5454.7 1726.04
  5473.7 1731.36  5492.7 1739.04  5507.1 1747.07  5526.9 1763.46  5574.9 1768.92
#Mann= 6 ,-1 , 0
  4156.3      .1       0  4268.7     .07       0  4919.3     .05       0
  4932.3     .07       0  5067.1    .035       0    5345     .07       0
Bank Sta=4919.3,4932.3
XS Rating Curve= 0 ,0
Exp/Cntr=0.3,0.1

Type RM Length L Ch R = 1 ,24152   ,455,455,455
BEGIN DESCRIPTION:
Third Creek 38.0
END DESCRIPTION:
XS GIS Cut Line= 3
      1937624.98     13928525.02        1937025.       13929125.
        1936625.       13929425.
#Sta/Elev= 30
  4146.5 1769.07  4226.7 1745.97  4300.5 1734.63  4389.6 1728.82  4558.2 1720.93
  4847.8 1711.18  4973.4 1711.32  4981.8  1710.5  4986.1 1705.39  4993.7 1699.37
    4994 1697.76  4994.5 1697.26  5007.1 1697.76  5008.5 1700.62  5011.3 1701.81
  5035.9 1704.47  5050.9 1702.83  5065.9 1704.54  5114.5 1705.41  5133.4 1704.91
  5162.2 1706.56  5260.9 1708.09  5318.5 1711.31  5343.4 1714.25  5383.5 1724.16
  5392.1 1727.62  5407.1 1735.85  5450.6 1753.86  5468.5 1760.06    5495 1760.95
#Mann= 7 ,-1 , 0
  4146.5      .1       0  4558.2     .07       0    4994     .05       0
  5007.1     .07       0  5035.9      .1       0  5114.5     .07       0
  5162.2      .1       0
Bank Sta=4994,5007.1
XS Rating Curve= 0 ,0
Exp/Cntr=0.3,0.1

Type RM Length L Ch R = 1 ,23697   ,465,465,465
BEGIN DESCRIPTION:
Third Creek 37.0
END DESCRIPTION:
XS GIS Cut Line= 3
      1937224.97     13928375.03        1936625.       13928975.
      1936274.98     13929125.01
#Sta/Elev= 30
    4145 1733.59  4169.1 1729.61  4283.2 1719.31  4364.3 1713.02  4520.7 1708.35
  4656.5 1706.32  4927.8 1707.41  4958.3 1707.28  4978.9 1701.56  5014.9 1699.28
  5018.2 1698.56  5022.7 1695.23  5023.2 1694.73  5035.8 1695.23  5037.5 1696.75
  5050.8 1699.28  5076.9 1701.39  5116.1 1702.17  5135.7 1705.29  5168.3 1706.93
  5178.1 1705.35  5191.2 1707.49  5229.4 1709.91  5243.4 1712.36  5285.8 1724.97
  5295.5 1728.82  5302.1 1733.78  5333.9 1747.76  5368.8 1752.77  5374.3 1753.09
#Mann= 6 ,-1 , 0
    4145      .1       0  4283.2     .07       0  4927.8      .1       0
  5022.7     .05       0  5035.8      .1       0  5368.8    .035       0
Bank Sta=5022.7,5035.8
XS Rating Curve= 0 ,0
Exp/Cntr=0.3,0.1

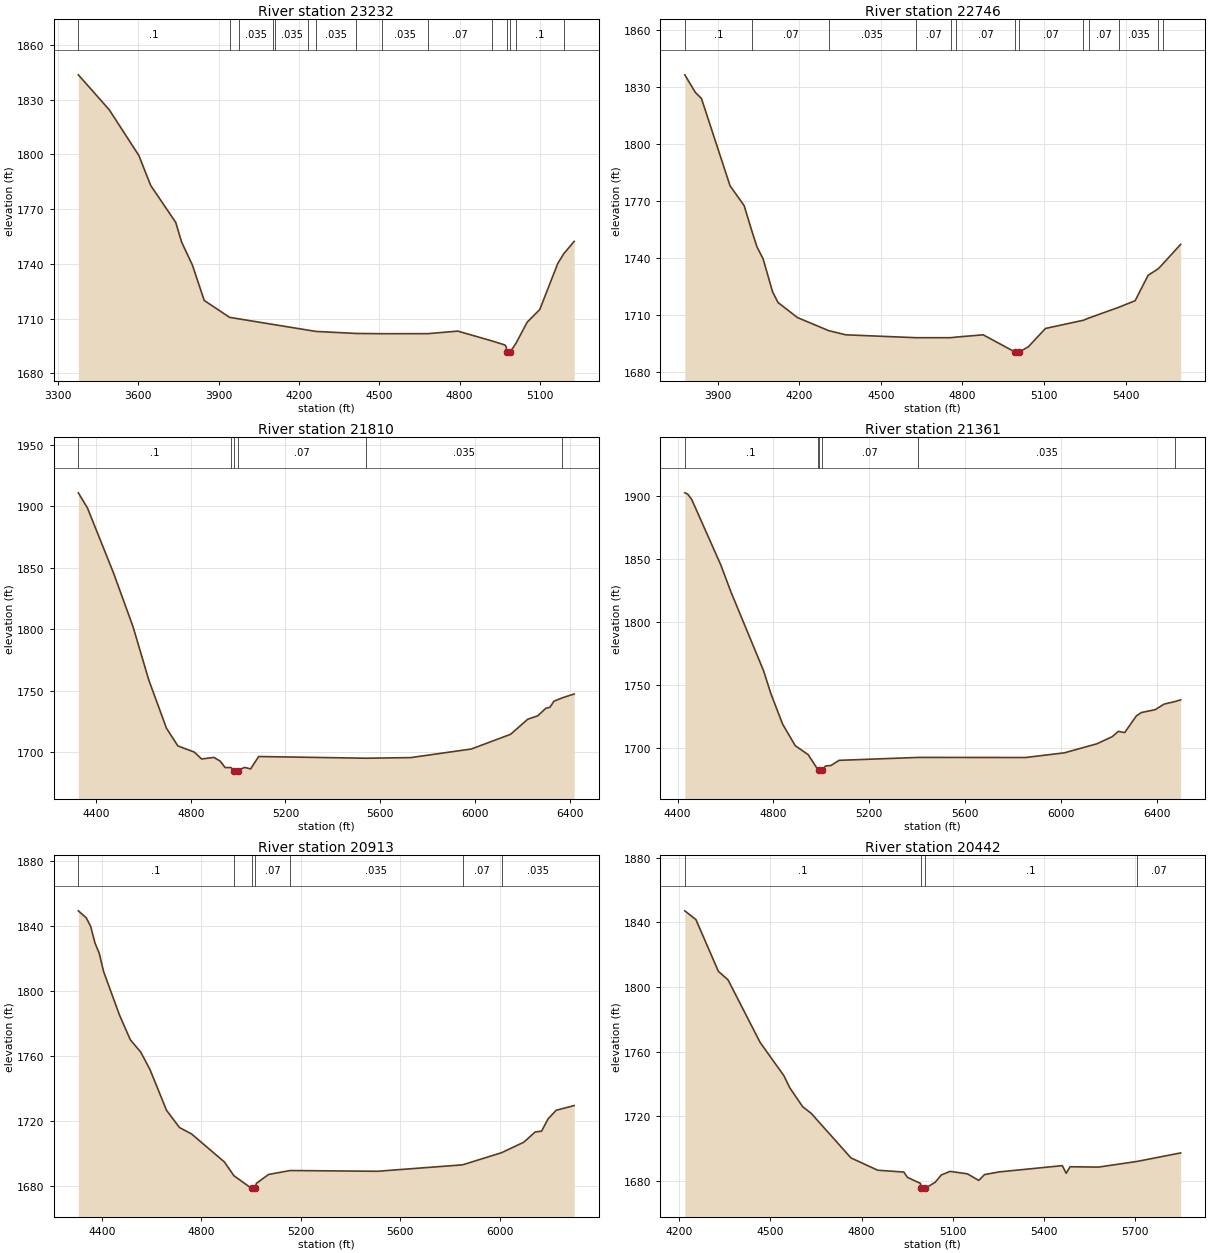
Type RM Length L Ch R = 1 ,23232   ,486,486,486
BEGIN DESCRIPTION:
Third Creek 36.0
END DESCRIPTION:
XS GIS Cut Line= 3
      1937325.01     13927574.99        1936225.       13928775.
        1936125.       13928975.
#Sta/Elev= 30
  3376.2 1843.63  3491.7 1824.49  3602.2 1799.45  3646.6 1782.97  3739.8 1762.83
    3762 1751.97    3802 1739.45  3846.4 1720.01  3941.1 1710.75  3974.7 1709.95
  4104.4 1706.85  4111.7 1706.68  4234.1 1703.75  4262.9 1703.06    4414 1701.94
  4511.3  1701.8  4681.3 1701.82    4793 1703.22  4921.1 1697.84    4969 1695.64
  4974.1 1694.55  4975.5 1691.66    4976 1691.16  4988.6 1691.66  5010.7 1696.63
  5052.3 1708.13  5099.2 1715.03  5166.3 1740.21  5188.4 1745.54  5227.7 1752.36
#Mann= 15 ,-1 , 0
  3376.2      .1       0  3941.1     .07       0  3974.7    .035       0
  4104.4     .07       0  4111.7    .035       0  4234.1     .07       0
  4262.9    .035       0    4414     .07       0  4511.3    .035       0
  4681.3     .07       0  4921.1     .07       0  4975.5     .05       0
  4988.6     .07       0  5010.7      .1       0  5188.4    .035       0
Bank Sta=4975.5,4988.6
XS Rating Curve= 0 ,0
Exp/Cntr=0.3,0.1

Type RM Length L Ch R = 1 ,22746   ,936,936,936
BEGIN DESCRIPTION:
Third Creek 35.0
END DESCRIPTION:
XS GIS Cut Line= 3
      1937225.04     13927624.97        1936225.       13928325.
      1935774.99     13928725.01
#Sta/Elev= 30
  3779.3 1836.49    3818 1827.27  3840.6 1824.02  3945.8 1778.11  3997.4 1767.73
  4026.9 1753.88  4045.1 1745.86  4067.1 1739.76  4102.1 1722.37    4122 1716.77
  4193.5 1708.85    4308 1701.99    4371 1699.78  4629.7 1698.26    4757 1698.26
  4776.2 1698.58  4876.3 1699.78  4994.3 1690.65  4994.8 1690.15  5007.5 1690.65
  5042.3 1693.49  5105.3 1703.12  5244.6 1707.43  5264.8 1708.61  5376.8 1714.37
  5434.8  1717.7  5482.6 1731.08  5519.8 1734.49  5536.3    1737  5602.1 1747.35
#Mann= 13 ,-1 , 0
  3779.3      .1       0  4026.9     .07       0    4308    .035       0
  4629.7     .07       0    4757    .035       0  4776.2     .07       0
  4994.3     .05       0  5007.5     .07       0  5244.6    .035       0
  5264.8     .07       0  5376.8    .035       0  5519.8      .1       0
  5536.3    .035       0
Bank Sta=4994.3,5007.5
XS Rating Curve= 0 ,0
Exp/Cntr=0.3,0.1

Type RM Length L Ch R = 1 ,21810   ,449,449,449
BEGIN DESCRIPTION:
Third Creek 34.0
END DESCRIPTION:
XS GIS Cut Line= 3
      1936774.99     13926975.01        1936375.       13927525.
      1935374.98     13928525.02
#Sta/Elev= 30
  4325.2 1911.02  4363.8 1898.69  4474.9 1845.25  4556.5 1801.93  4623.3 1758.41
  4697.5 1719.45  4745.7 1705.05  4814.7 1700.05  4845.9 1694.42  4897.8 1695.69
  4923.8 1692.78  4945.2 1687.43  4969.6 1687.44  4984.5 1685.03    4985 1684.53
  4997.8 1685.03  5027.5 1687.56  5052.9 1686.34  5086.9 1696.42  5539.2 1695.04
  5729.2 1695.53  5985.5 1702.55  6150.9 1714.49  6223.5 1726.77  6266.3  1729.6
  6299.4 1735.62  6317.2 1736.52  6334.2 1741.46    6370 1744.22  6419.5 1747.32
#Mann= 6 ,-1 , 0
  4325.2      .1       0  4969.6     .07       0  4984.5     .05       0
  4997.8     .07       0  5539.2    .035       0    6370     .07       0
Bank Sta=4984.5,4997.8
XS Rating Curve= 0 ,0
Exp/Cntr=0.3,0.1

Type RM Length L Ch R = 1 ,21361   ,448,448,448
BEGIN DESCRIPTION:
Third Creek 33.0
END DESCRIPTION:
XS GIS Cut Line= 3
        1936625.       13926825.        1936175.       13927175.
      1935274.99     13928375.01
#Sta/Elev= 30
    4430 1902.67  4441.6 1901.78  4458.8 1897.45  4580.4 1845.37  4622.4 1824.12
    4759 1761.34  4789.4 1743.23  4838.2  1719.1  4891.1 1701.88  4945.2 1694.76
  4984.8 1683.12  4989.7 1682.18  4990.2 1681.68  5003.1 1682.18  5017.7 1685.77
  5040.2 1686.13    5074 1690.24  5403.9 1692.56    5854 1692.51  6015.2 1696.23
  6150.2 1703.37    6214 1708.98  6240.2 1713.26  6266.5 1712.28  6315.2 1725.51
  6335.7 1728.17    6394 1730.49  6431.5 1734.94  6478.7 1737.03  6500.1  1738.3
#Mann= 6 ,-1 , 0
    4430      .1       0  4984.8     .07       0  4989.7     .05       0
  5003.1     .07       0  5403.9    .035       0  6478.7     .07       0
Bank Sta=4989.7,5003.1
XS Rating Curve= 0 ,0
Exp/Cntr=0.3,0.1

Type RM Length L Ch R = 1 ,20913   ,471,471,471
BEGIN DESCRIPTION:
Third Creek 32.0
END DESCRIPTION:
XS GIS Cut Line= 3
      1936374.98     13926675.01        1935775.       13927025.
        1935275.       13928225.
#Sta/Elev= 30
  4305.4 1849.56  4337.4 1845.22    4355 1839.98  4372.2 1829.81  4389.5 1823.41
  4406.9  1812.2    4471 1785.28  4514.6 1770.03  4556.3 1762.46  4593.3  1751.8
  4660.4 1726.47  4712.4 1715.91  4760.8 1711.96  4893.1 1694.66  4931.3 1686.18
  5002.1 1678.42  5002.6 1677.92  5015.5 1678.42  5021.8  1681.5  5070.5 1686.96
  5157.4 1689.39  5508.8 1688.93  5851.1  1692.9  6008.6 1700.42  6097.5 1706.87
    6143 1713.16    6169 1713.68    6195 1721.22  6227.5 1726.56    6300 1729.45
#Mann= 7 ,-1 , 0
  4305.4      .1       0  4931.3     .07       0  5002.1     .05       0
  5015.5     .07       0  5157.4    .035       0  5851.1     .07       0
  6008.6    .035       0
Bank Sta=5002.1,5015.5
XS Rating Curve= 0 ,0
Exp/Cntr=0.3,0.1

Type RM Length L Ch R = 1 ,20442   ,416,416,416
BEGIN DESCRIPTION:
Third Creek 31.0
END DESCRIPTION:
XS GIS Cut Line= 3
        1935875.       13926225.        1935375.       13926825.
      1934774.97     13927425.03
#Sta/Elev= 30
  4219.2 1847.13  4255.8 1841.69  4329.6 1809.67  4361.2 1804.43  4466.7 1765.71
  4544.8 1745.11  4564.3 1737.57  4606.7 1725.87  4634.6  1721.8  4765.4 1694.18
  4853.3 1686.57  4939.2 1685.44  4950.9 1682.15  4993.8 1678.41  4996.2 1675.37
  4996.7 1674.87  5009.6 1675.37  5042.2 1679.12  5062.3 1683.64  5090.9 1685.86
  5148.3 1684.32  5185.3 1680.25  5204.4 1683.87  5252.1 1685.52    5460 1689.41
  5472.7 1684.67  5485.4 1688.72  5578.8 1688.51  5705.2    1692  5848.8 1697.28
#Mann= 4 ,-1 , 0
  4219.2      .1       0  4996.2     .05       0  5009.6      .1       0
  5705.2     .07       0
#Block Obstruct= 2 , 0
                         5458.74         1689.94
Bank Sta=4996.2,5009.6
XS Rating Curve= 0 ,0
Exp/Cntr=0.3,0.1

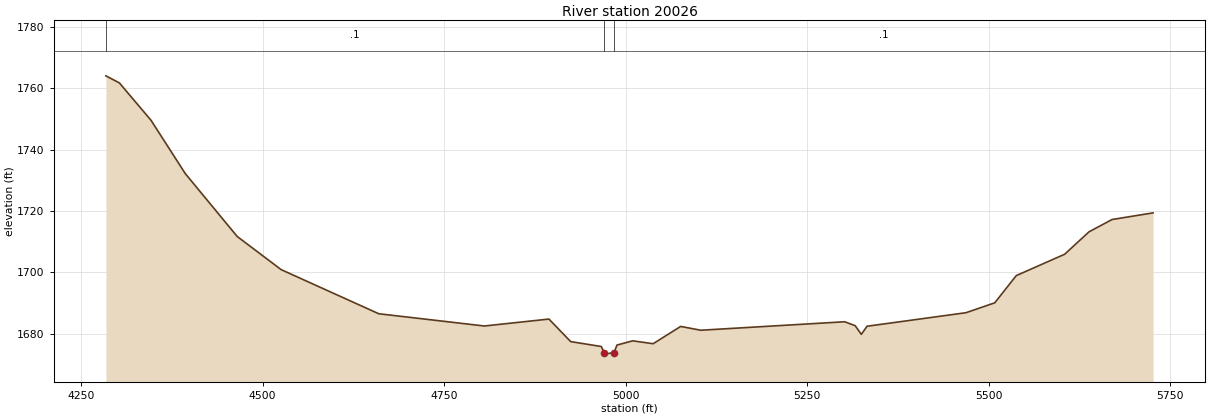
Type RM Length L Ch R = 1 ,20026   ,446,446,446
BEGIN DESCRIPTION:
Third Creek 30.0
END DESCRIPTION:
XS GIS Cut Line= 3
      1935624.98     13926225.01        1935025.       13926625.
        1934425.       13927025.
#Sta/Elev= 30
  4284.2 1764.04  4302.8 1761.73  4346.3 1749.58  4393.6 1732.18    4465 1711.73
  4525.6 1700.92    4660 1686.56  4805.4 1682.57  4894.4 1684.83  4924.3 1677.49
  4966.5 1675.89  4970.5 1673.91    4971 1673.41    4984 1673.91  4988.1 1676.36
  5009.7 1677.74  5037.9  1676.8  5075.8 1682.43  5103.5 1681.19  5301.8 1683.95
  5316.2 1682.66  5324.6 1679.85  5332.5 1682.49  5468.8  1686.9  5508.4 1690.12
    5538 1698.98  5604.6 1705.93  5638.2 1713.24    5670 1717.25  5726.4 1719.41
#Mann= 3 ,-1 , 0
  4284.2      .1       0  4970.5     .05       0    4984      .1       0
#Block Obstruct= 2 , 0
                         5272.53         1683.47
Bank Sta=4970.5,4984
XS Rating Curve= 0 ,0
Exp/Cntr=0.3,0.1