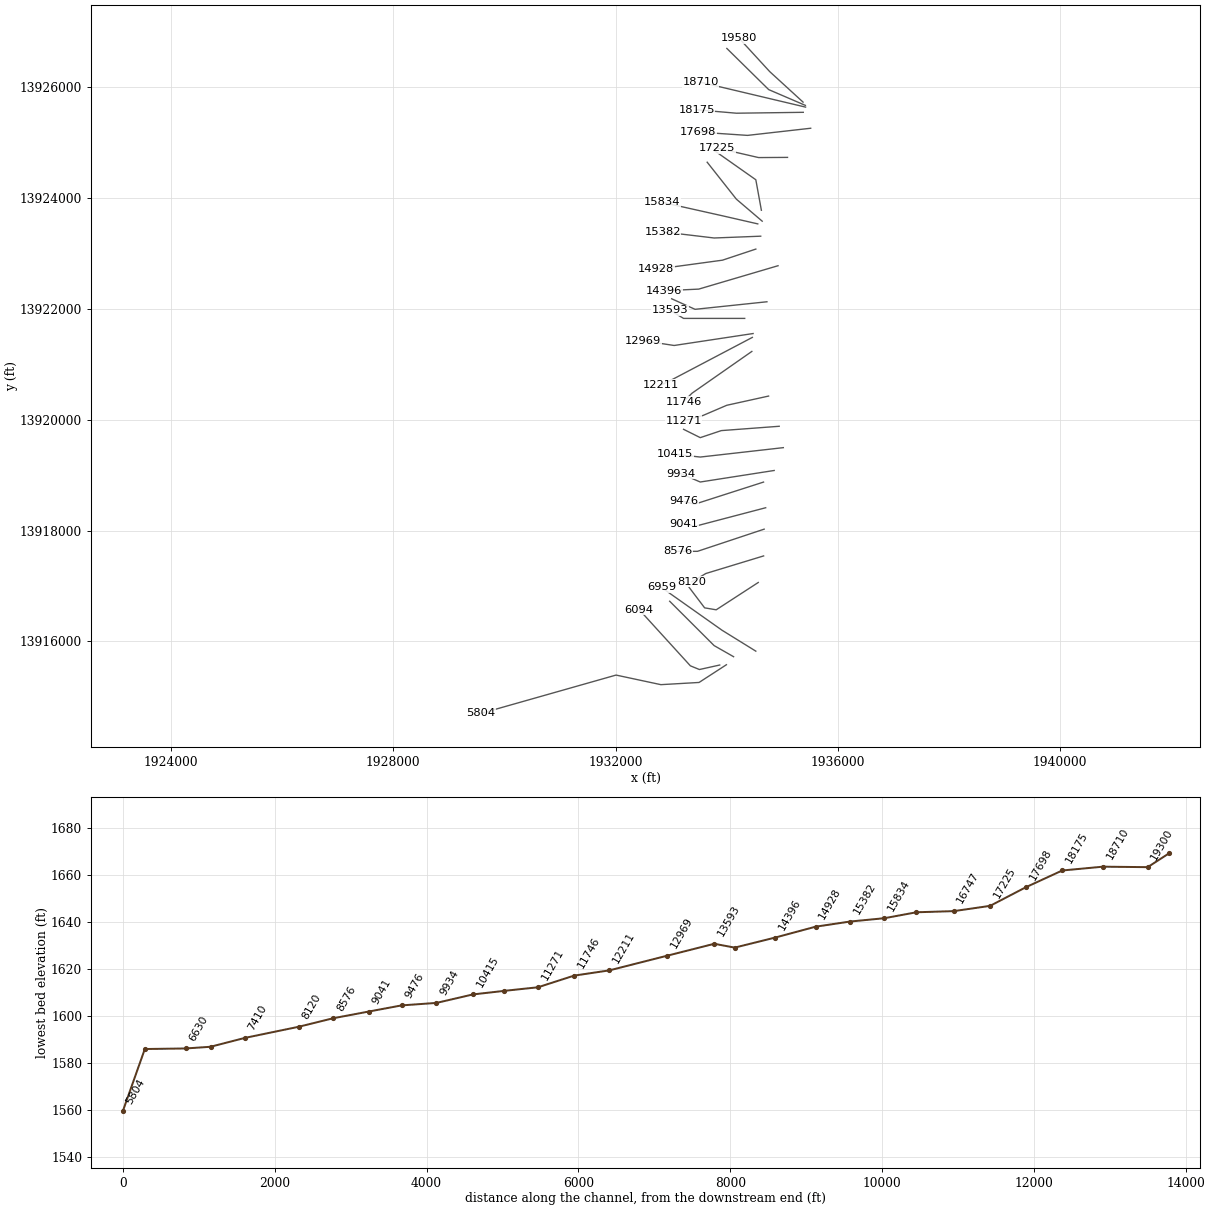
HEC-RAS study Third Creek.prj: Third Creek Base Level Engineering

--- Third Creek.g01 (geometry) --- (continued)

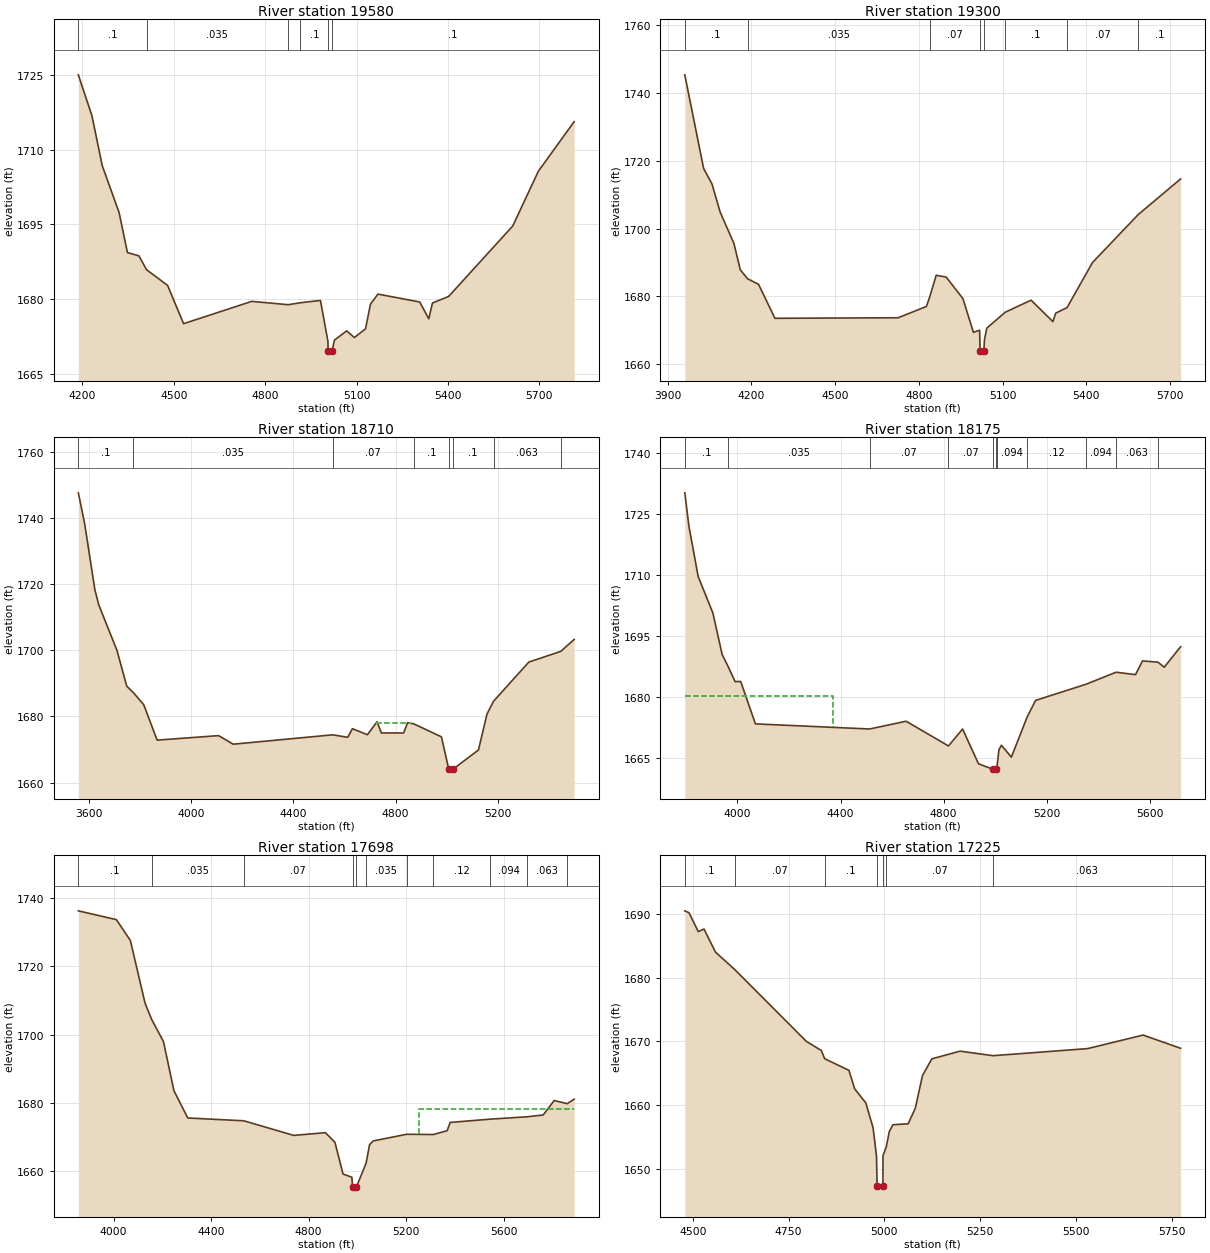
Type RM Length L Ch R = 1 ,19580   ,280,280,280
BEGIN DESCRIPTION:
Third Creek 29.0
END DESCRIPTION:
XS GIS Cut Line= 3
      1935375.01     13925724.99        1934775.       13926275.
        1934225.       13926875.
#Sta/Elev= 30
  4186.5 1725.01  4231.1 1716.83  4264.9  1706.8  4320.4 1697.36  4347.7 1689.34
  4385.5 1688.67  4410.6 1685.89  4479.7 1682.74    4532 1675.06  4755.9 1679.54
  4875.3 1678.87  4915.7 1679.26  4981.4 1679.73    5006 1671.52  5006.6 1669.65
  5007.1 1669.15  5020.1 1669.65  5027.2 1671.76  5067.6 1673.61  5092.8 1672.28
  5129.5 1674.03  5145.7 1678.99  5170.2    1681  5307.5 1679.41    5337 1676.04
  5349.2 1679.21  5402.1 1680.52  5612.7 1694.66    5697 1705.67  5814.4 1715.61
#Mann= 6 ,-1 , 0
  4186.5      .1       0  4410.6    .035       0  4875.3     .07       0
  4915.7      .1       0  5006.6     .05       0  5020.1      .1       0
#Block Obstruct= 2 , 0
                         5184.81         1680.82
Bank Sta=5006.6,5020.1
XS Rating Curve= 0 ,0
Exp/Cntr=0.3,0.1

Type RM Length L Ch R = 1 ,19300   ,590,590,590
BEGIN DESCRIPTION:
Third Creek 28.2
END DESCRIPTION:
XS GIS Cut Line= 3
      1935416.83     13925666.01      1934756.48     13925950.54
      1934003.85     13926692.63
#Sta/Elev= 30
  3961.4 1745.29  4028.8 1717.72  4058.9 1713.13    4088 1704.86  4137.3 1695.63
  4160.2 1687.85  4186.1 1685.21  4225.5 1683.58  4284.3 1673.56  4725.6 1673.72
  4826.8 1677.05  4839.1 1679.97    4862 1686.25  4897.7  1685.7  4957.6 1679.37
  4995.3 1669.41  5017.4 1670.07  5019.1  1663.8  5019.6  1663.3  5032.7  1663.8
  5034.5 1667.05    5043 1670.66  5109.9 1675.38  5201.7  1678.9  5279.9 1672.59
  5290.2 1675.09  5330.6 1676.72    5422 1690.02  5585.3  1704.1  5737.4 1714.63
#Mann= 8 ,-1 , 0
  3961.4      .1       0  4186.1    .035       0  4839.1     .07       0
  5019.1     .05       0  5032.7     .07       0  5109.9      .1       0
  5330.6     .07       0  5585.3      .1       0
#Block Obstruct= 2 , 0
                          5200.8         1678.56
Bank Sta=5019.1,5032.7
XS Rating Curve= 0 ,0
Exp/Cntr=0.3,0.1

Type RM Length L Ch R = 1 ,18710   ,535,535,535
BEGIN DESCRIPTION:
Third Creek 28.1
END DESCRIPTION:
XS GIS Cut Line= 2
      1935420.48     13925634.81      1933531.73     13926083.46
#Sta/Elev= 30
  3558.2 1747.53    3583 1738.23  3623.1 1718.21  3638.6 1713.62  3709.5 1699.94
  3747.9 1689.14  3773.7  1687.2  3814.3 1683.55  3866.7 1672.86  4107.2 1674.22
  4164.7 1671.63  4554.5 1674.46  4612.9 1673.71  4631.4 1676.31    4690 1674.49
  4727.7 1678.39  4744.6 1675.04  4831.9 1675.02  4847.3  1678.1  4871.3 1677.78
  4979.9 1673.85  5008.7    1664  5009.2  1663.5  5023.7    1664  5124.8 1669.88
  5158.2 1680.72  5183.7 1684.59  5322.1 1696.43  5447.5 1699.67  5499.5 1703.27
#Mann= 8 ,-1 , 0
  3558.2      .1       0  3773.7    .035       0  4554.5     .07       0
  4871.3      .1       0  5008.7     .05       0  5023.7      .1       0
  5183.7    .063       0  5447.5    .035       0
#XS Ineff= 1 ,-1
 4722.78 4860.64 1678.16
Permanent Ineff=
       F
Bank Sta=5008.7,5023.7
XS Rating Curve= 0 ,0
Exp/Cntr=0.3,0.1

Type RM Length L Ch R = 1 ,18175   ,477,477,477
BEGIN DESCRIPTION:
Third Creek 28.0
END DESCRIPTION:
XS GIS Cut Line= 3
      1935379.25     13925540.99        1934175.       13925525.
      1933457.95     13925587.13
#Sta/Elev= 30
  3795.7 1730.32  3811.7  1722.1  3847.7 1709.72  3904.7 1700.76  3940.7 1690.56
  3963.3 1687.68    3991 1683.89  4012.7 1683.92  4069.7  1673.5  4512.7 1672.24
  4654.7 1674.15  4818.9 1668.07  4873.7 1672.24  4935.5 1663.68  4990.2 1662.38
  4990.7 1661.88  5005.2 1662.38    5008 1663.44  5014.8 1667.15  5024.4 1668.25
    5063 1665.32  5124.2 1675.18  5156.9 1679.27  5352.1 1683.23  5469.3  1686.2
  5544.7 1685.61  5571.9 1688.98  5631.8 1688.68  5656.2 1687.42  5719.8 1692.49
#Mann= 11 ,-1 , 0
  3795.7      .1       0  3963.3    .035       0  4512.7     .07       0
  4818.9     .07       0  4990.2     .05       0  5005.2     .07       0
    5008    .094       0  5124.2     .12       0  5352.1    .094       0
  5469.3    .063       0  5631.8    .035       0
#XS Ineff= 2 , 0
         4371.63 1680.44
Permanent Ineff=
       F       F
Bank Sta=4990.2,5005.2
XS Rating Curve= 0 ,0
Exp/Cntr=0.3,0.1

Type RM Length L Ch R = 1 ,17698   ,473,473,473
BEGIN DESCRIPTION:
Third Creek 27.0
END DESCRIPTION:
XS GIS Cut Line= 3
      1935512.41     13925253.81        1934375.       13925125.
      1933487.61     13925185.02
#Sta/Elev= 30
    3855 1736.27  4011.1 1733.69  4068.5 1727.59  4128.9 1709.19    4156 1704.45
  4204.3 1697.98  4247.2 1683.61    4304 1675.62  4533.6  1674.8  4738.7 1670.52
  4868.6 1671.32  4907.8 1668.48    4941  1659.2  4977.2 1658.28    4980 1655.29
  4980.5 1654.79  4995.1 1655.29  5035.5 1662.37  5049.8 1667.81  5064.5  1668.9
  5202.4 1670.85  5311.7 1670.78  5368.2  1671.9  5380.3 1674.31  5545.1 1675.28
  5696.4 1675.97  5762.1  1676.5  5807.2 1680.73  5860.5 1679.81  5889.1 1681.12
#Mann= 11 ,-1 , 0
    3855      .1       0    4156    .035       0  4533.6     .07       0
    4980     .05       0  4995.1     .07       0  5035.5    .035       0
  5202.4    .094       0  5311.7     .12       0  5545.1    .094       0
  5696.4    .063       0  5860.5    .035       0
#XS Ineff= 2 , 0
                         5250.75         1678.12
Permanent Ineff=
       F       F
Bank Sta=4980,4995.1
XS Rating Curve= 0 ,0
Exp/Cntr=0.3,0.1

Type RM Length L Ch R = 1 ,17225   ,478,478,478
BEGIN DESCRIPTION:
Third Creek 26.0
END DESCRIPTION:
XS GIS Cut Line= 3
      1935095.38     13924728.23        1934575.       13924725.
      1933821.89     13924898.82
#Sta/Elev= 30
  4479.3 1690.46  4490.4 1690.16  4514.4  1687.2  4529.4 1687.61  4559.4 1683.98
  4609.5 1681.26  4796.5 1669.99  4835.3 1668.57  4844.1 1667.28  4907.4 1665.45
  4922.4 1662.56  4951.6 1660.33  4970.4 1656.45  4979.4    1652  4980.8 1647.33
  4981.3 1646.83    4996 1647.33  4996.3 1652.07  5004.8 1653.44  5012.7 1655.84
    5022 1656.92    5062 1657.08  5080.5  1659.5  5099.2 1664.62  5123.6 1667.25
  5197.5 1668.46    5283 1667.75    5530 1668.86  5674.7 1670.98  5772.6 1668.91
#Mann= 7 ,-1 , 0
  4479.3      .1       0  4609.5     .07       0  4844.1      .1       0
  4980.8     .05       0    4996      .1       0  5004.8     .07       0
    5283    .063       0
Bank Sta=4980.8,4996
XS Rating Curve= 0 ,0
Exp/Cntr=0.3,0.1

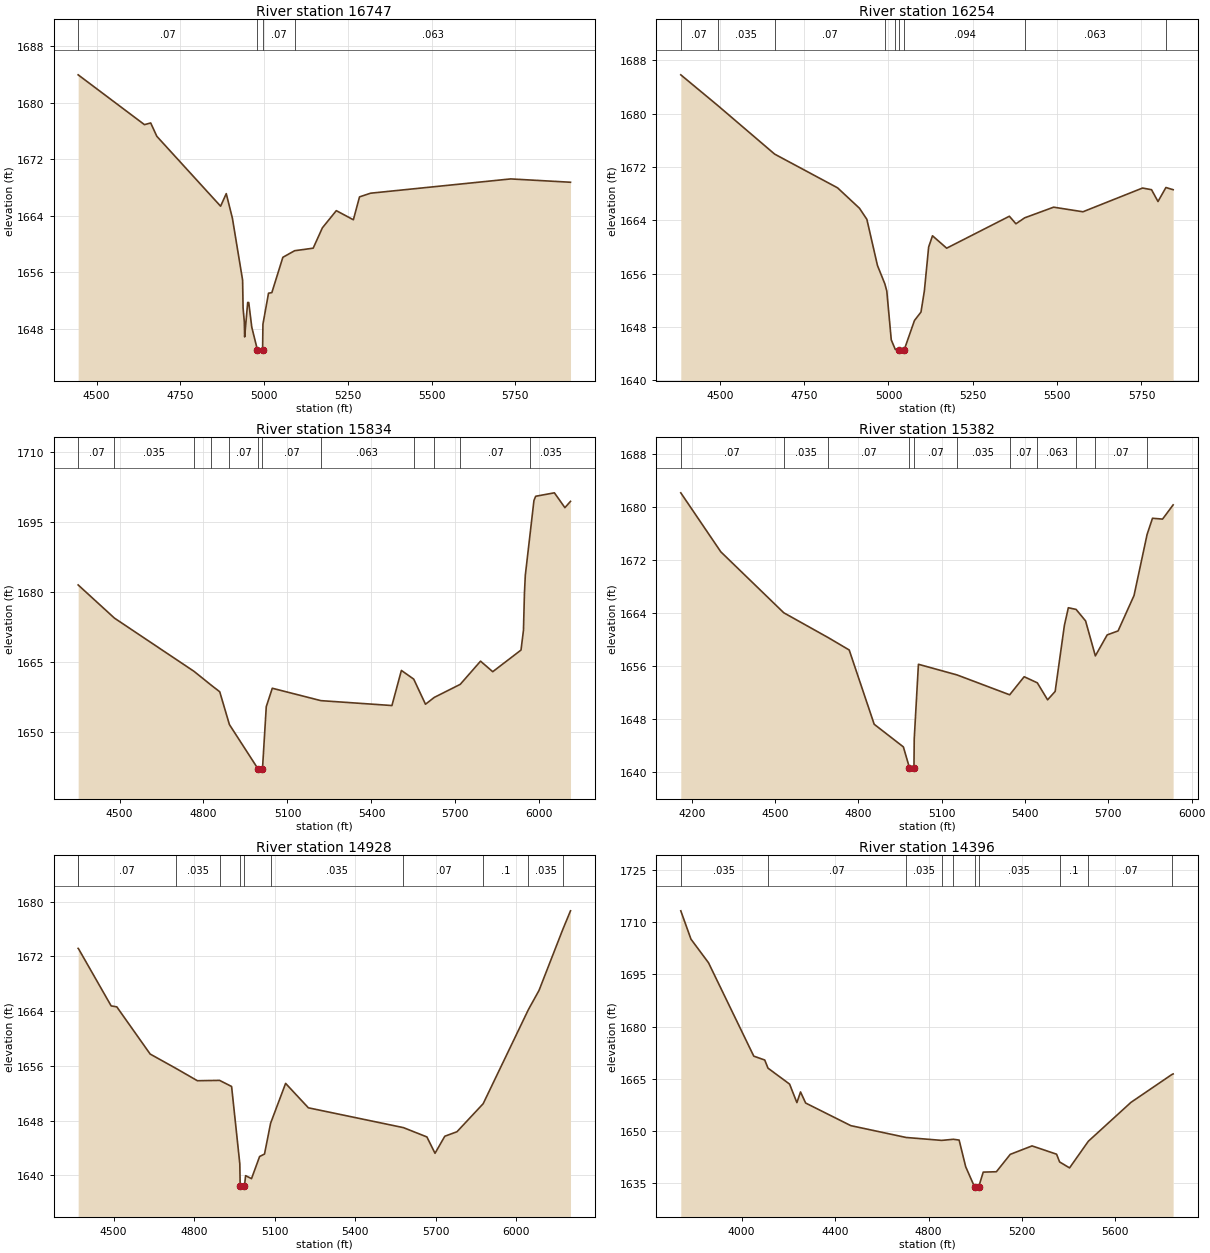
Type RM Length L Ch R = 1 ,16747   ,493,493,493
BEGIN DESCRIPTION:
Third Creek 25.0
END DESCRIPTION:
XS GIS Cut Line= 3
        1934625.     13923775.02        1934525.       13924325.
      1933780.53     13924850.07
#Sta/Elev= 30
  4444.7 1683.97  4642.7 1676.92  4661.3 1677.16  4679.6 1675.27    4870 1665.38
  4886.9 1667.16  4905.2 1663.69  4935.7 1654.92  4937.1 1651.01  4940.8 1649.01
  4941.8 1646.88  4950.9 1651.76    4954 1651.75  4963.1 1648.26  4979.7 1645.09
  4980.2 1644.59  4995.4 1645.09  4996.4 1648.69  5013.1 1653.07    5023 1653.15
  5055.9 1658.15    5091 1659.08  5146.4 1659.44  5173.9 1662.32  5215.5 1664.75
  5266.4 1663.46  5284.8  1666.7  5317.8 1667.22  5736.1 1669.24  5914.7 1668.77
#Mann= 4 ,-1 , 0
  4444.7     .07       0  4979.7     .05       0  4995.4     .07       0
    5091    .063       0
Bank Sta=4979.7,4995.4
XS Rating Curve= 0 ,0
Exp/Cntr=0.3,0.1

Type RM Length L Ch R = 1 ,16254   ,420,420,420
BEGIN DESCRIPTION:
Third Creek 24.0
END DESCRIPTION:
XS GIS Cut Line= 3
      1934639.74     13923578.15        1934175.       13923975.
      1933649.77     13924641.36
#Sta/Elev= 30
  4384.3 1685.84  4493.2 1681.27  4662.5 1673.95  4849.1 1668.89    4914 1665.83
  4935.9 1664.17  4967.4 1657.24  4989.3 1654.48    4995 1653.42  5008.3 1646.08
  5020.2 1644.66    5031  1644.6  5031.5  1644.1  5046.7  1644.6    5077 1648.99
  5096.4 1650.26  5106.4 1653.43  5119.1 1660.01  5130.5  1661.7  5172.5 1659.84
  5358.4 1664.63  5377.8  1663.5  5403.7 1664.39  5489.6 1665.99  5576.5  1665.3
  5753.2 1668.86  5779.9 1668.61    5799 1666.84  5822.5 1668.94  5843.9 1668.61
#Mann= 9 ,-1 , 0
  4384.3     .07       0  4493.2    .035       0  4662.5     .07       0
  4989.3    .063       0  5020.2    .094       0    5031     .05       0
  5046.7    .094       0  5403.7    .063       0  5822.5    .094       0
Bank Sta=5031,5046.7
XS Rating Curve= 0 ,0
Exp/Cntr=0.3,0.1

Type RM Length L Ch R = 1 ,15834   ,452,452,452
BEGIN DESCRIPTION:
Third Creek 23.0
END DESCRIPTION:
XS GIS Cut Line= 3
      1934560.27     13923529.18        1933925.       13923675.
      1932844.83     13923917.28
#Sta/Elev= 30
  4352.3 1681.52    4482  1674.4  4766.1 1662.99    4827 1660.05  4858.1  1658.6
  4892.6 1651.57  4994.7 1642.08  4995.2 1641.58  5010.8 1642.08  5024.3 1655.41
  5045.8 1659.36  5219.5  1656.7  5473.2 1655.65    5507 1663.18    5551 1661.32
  5593.1 1655.93  5624.3 1657.39  5717.3  1660.2  5789.8 1665.17  5833.3 1662.91
  5934.3 1667.55  5943.1 1671.81  5946.6 1679.78  5949.7  1683.6  5967.9 1693.06
  5980.5 1699.62  5986.6 1700.54  6053.6 1701.28  6091.1  1698.1  6111.1 1699.45
#Mann= 12 ,-1 , 0
  4352.3     .07       0    4482    .035       0  4766.1     .07       0
    4827    .035       0  4892.6     .07       0  4994.7     .05       0
  5010.8     .07       0  5219.5    .063       0    5551    .035       0
  5624.3      .1       0  5717.3     .07       0  5967.9    .035       0
#Block Obstruct= 2 , 0
                         5523.48         1662.91
Bank Sta=4994.7,5010.8
XS Rating Curve= 0 ,0
Exp/Cntr=0.3,0.1

Type RM Length L Ch R = 1 ,15382   ,454,454,454
BEGIN DESCRIPTION:
Third Creek 22.0
END DESCRIPTION:
XS GIS Cut Line= 3
      1934613.32      13923307.5        1933775.       13923275.
      1932847.42     13923385.64
#Sta/Elev= 30
  4160.2  1682.2  4304.3 1673.29  4531.1 1664.08  4691.9 1660.31  4766.7 1658.46
  4856.7 1647.24  4961.8 1643.82  4983.8 1640.66  4984.3 1640.16  4999.9 1640.66
  5000.9 1645.02    5016  1656.3  5155.2 1654.69  5344.6 1651.69  5396.8 1654.42
  5444.2  1653.5  5481.2 1650.93  5508.4  1652.2  5541.7 1662.18  5555.9 1664.84
  5583.8 1664.59    5618 1662.85  5653.2 1657.57  5695.8 1660.74    5735 1661.34
  5792.4 1666.68  5839.6 1675.93  5858.9 1678.36  5895.2 1678.23  5933.3 1680.38
#Mann= 11 ,-1 , 0
  4160.2     .07       0  4531.1    .035       0  4691.9     .07       0
  4983.8     .05       0  4999.9     .07       0  5155.2    .035       0
  5344.6     .07       0  5444.2    .063       0  5583.8    .035       0
  5653.2     .07       0  5839.6      .1       0
#Block Obstruct= 2 , 0
                         5034.96         1656.37
Bank Sta=4983.8,4999.9
XS Rating Curve= 0 ,0
Exp/Cntr=0.3,0.1

Type RM Length L Ch R = 1 ,14928   ,532,532,532
BEGIN DESCRIPTION:
Third Creek 21.0
END DESCRIPTION:
XS GIS Cut Line= 3
      1934525.05     13923075.02        1933925.       13922875.
      1932732.85     13922712.34
#Sta/Elev= 30
  4367.6 1673.17  4368.6 1673.14  4490.7 1664.76  4511.7 1664.62  4636.1 1657.72
  4732.4 1655.62  4812.2 1653.82  4894.8 1653.87  4939.7 1652.98  4970.3 1641.69
  4971.7 1638.47  4972.2 1637.97  4987.8 1638.47  4991.9 1639.94  5013.9  1639.5
  5044.2 1642.74  5062.4  1643.1  5085.1  1647.6  5141.1 1653.43  5225.9 1649.86
  5580.5 1646.96  5667.9  1645.6  5698.2 1643.21  5734.5  1645.7    5780 1646.36
  5877.7 1650.46  6046.6 1664.24  6085.9 1667.02  6174.8 1675.96  6203.3 1678.66
#Mann= 11 ,-1 , 0
  4367.6    .035       0  4368.6     .07       0  4732.4    .035       0
  4894.8     .07       0  4971.7     .05       0  4987.8     .07       0
  5085.1    .035       0  5580.5     .07       0  5877.7      .1       0
  6046.6    .035       0  6174.8    .094       0
#Block Obstruct= 2 , 0
                         5141.36         1653.45
Bank Sta=4971.7,4987.8
XS Rating Curve= 0 ,0
Exp/Cntr=0.3,0.1

Type RM Length L Ch R = 1 ,14396   ,534,534,534
BEGIN DESCRIPTION:
Third Creek 20.0
END DESCRIPTION:
XS GIS Cut Line= 3
        1934925.       13922775.      1933497.54     13922353.24
      1932878.68     13922324.22
#Sta/Elev= 30
  3739.3 1713.19  3782.8 1705.07  3857.9  1698.3  4051.8  1671.5  4098.7 1670.39
  4112.6 1668.06  4205.1 1663.48  4236.4 1658.17    4252 1661.23  4273.9 1658.05
  4467.4 1651.56    4704 1648.17  4856.4 1647.33  4906.6 1647.65    4931 1647.42
  4959.2 1639.75    4998 1633.85  4998.5 1633.35  5014.1 1633.85  5034.2 1638.23
  5090.5 1638.34    5150 1643.33  5243.2 1645.75  5348.3 1643.37  5361.2 1641.15
  5403.8 1639.44  5484.2 1647.08  5666.6 1658.23  5841.8 1666.23  5847.3 1666.39
#Mann= 10 ,-1 , 0
  3739.3    .035       0  4112.6     .07       0    4704    .035       0
  4856.4     .07       0  4906.6    .035       0    4998    .035       0
  5014.1    .035       0  5361.2      .1       0  5484.2     .07       0
  5841.8      .1       0
#Block Obstruct= 2 , 0
                         5253.25         1645.35
Bank Sta=4998,5014.1
XS Rating Curve= 0 ,0
Exp/Cntr=0.3,0.1

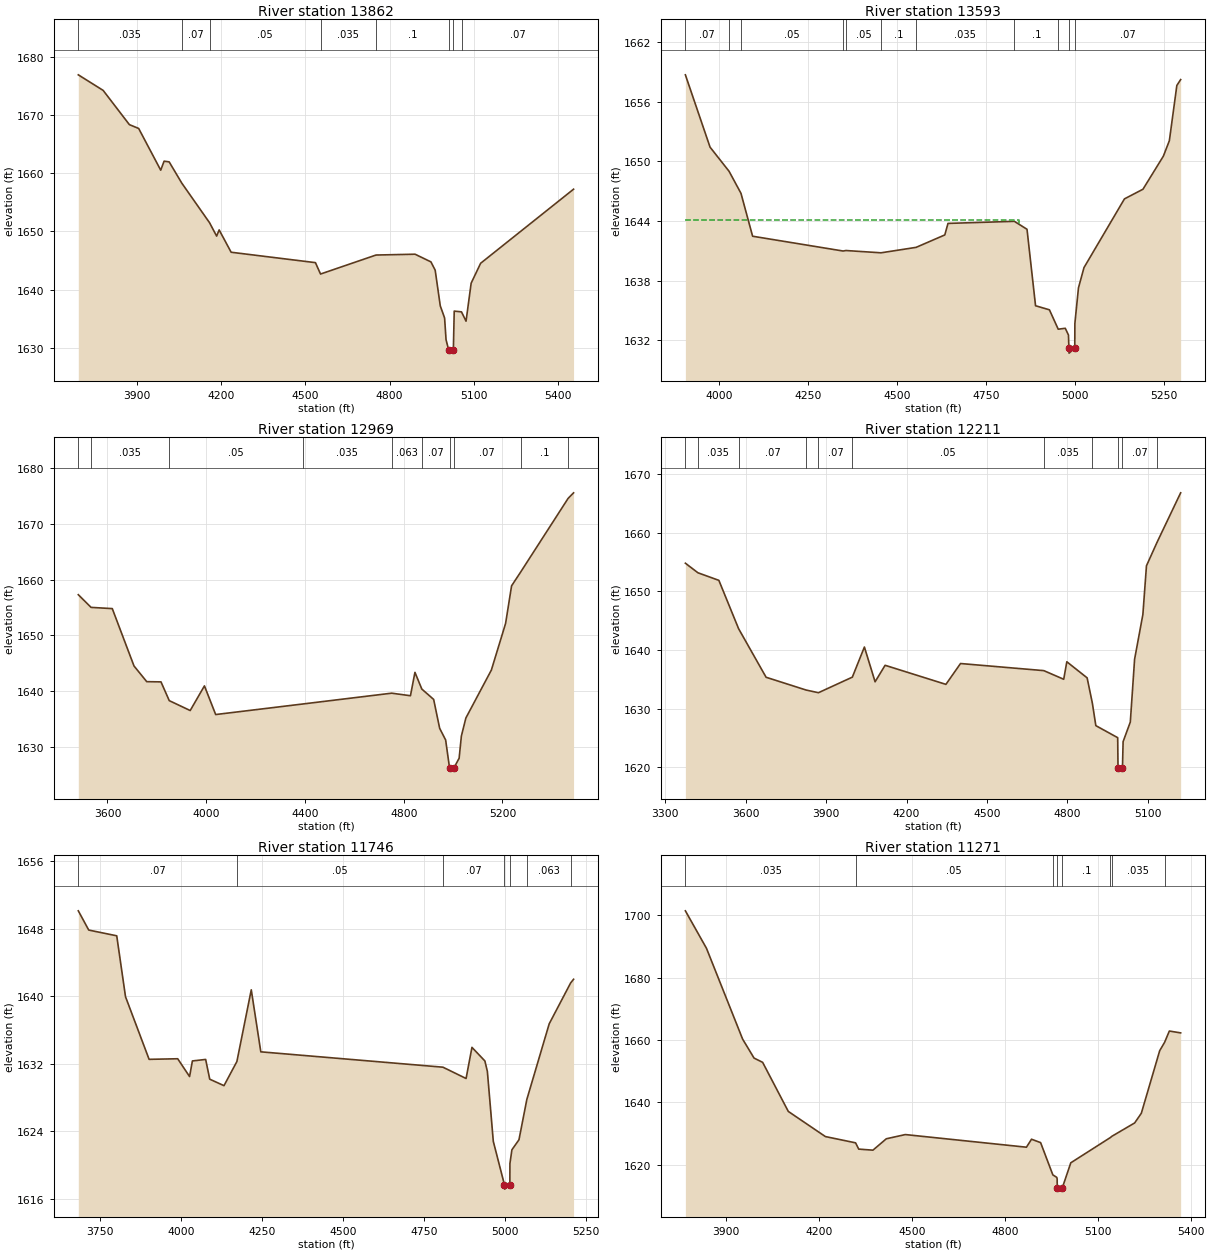
Type RM Length L Ch R = 1 ,13862   ,269,269,269
BEGIN DESCRIPTION:
Third Creek 19.0
END DESCRIPTION:
XS GIS Cut Line= 3
      1934725.01       13922125.      1933431.69      13921988.8
      1933009.41     13922179.22
#Sta/Elev= 30
  3691.7 1676.95  3780.2 1674.27  3873.6 1668.38  3906.7 1667.72  3985.2 1660.54
  3997.2 1662.09  4015.3 1661.97  4060.3 1658.31  4159.1  1651.5  4184.3  1649.2
  4193.3 1650.26    4236 1646.42  4536.2 1644.63  4554.3 1642.67  4751.9 1645.94
    4891 1646.08  4947.5 1644.76  4962.6 1643.33  4980.7  1637.2  4996.1 1635.11
  5001.3 1631.37  5010.8 1629.56  5011.3 1629.06  5027.3 1629.56  5030.4 1636.29
  5056.3 1636.16  5072.5 1634.56  5090.7  1641.1  5124.4 1644.52  5455.4 1657.27
#Mann= 8 ,-1 , 0
  3691.7    .035       0  4060.3     .07       0  4159.1     .05       0
  4554.3    .035       0  4751.9      .1       0  5010.8     .05       0
  5027.3      .1       0  5056.3     .07       0
#XS Ineff= 2 , 0
         4880.62 1645.99
Permanent Ineff=
       F       F
Bank Sta=5010.8,5027.3
XS Rating Curve= 0 ,0
Exp/Cntr=0.3,0.1

Type RM Length L Ch R = 1 ,13593   ,624,624,624
BEGIN DESCRIPTION:
Third Creek 18.0
END DESCRIPTION:
XS GIS Cut Line= 3
      1934325.03       13921825.        1933225.       13921825.
      1932974.98     13921975.01
#Sta/Elev= 30
  3904.5 1658.71  3973.8 1651.43  4027.4 1648.99  4060.7 1646.78  4093.4 1642.46
  4347.6 1640.97  4355.7 1641.02  4454.3 1640.79  4552.9 1641.34  4633.4 1642.59
  4642.4 1643.75  4828.8 1643.96  4864.4 1643.16  4888.4 1635.46  4927.4 1635.05
  4952.1  1633.1  4971.9 1633.19  4980.9 1632.51  4982.1 1631.19  4982.6 1630.69
  4998.6 1631.19  4998.9 1633.69    5009 1637.26  5024.5  1639.3  5138.2 1646.22
  5190.2 1647.19  5247.5 1650.52  5264.4 1652.08  5285.4 1657.64  5296.1 1658.23
#Mann= 11 ,-1 , 0
  3904.5     .07       0  4027.4    .035       0  4060.7     .05       0
  4347.6      .1       0  4355.7     .05       0  4454.3      .1       0
  4552.9    .035       0  4828.8      .1       0  4952.1     .07       0
  4982.1     .05       0  4998.6     .07       0
#XS Ineff= 2 , 0
         4840.56 1644.07
Permanent Ineff=
       F       F
Bank Sta=4982.1,4998.6
XS Rating Curve= 0 ,0
Exp/Cntr=0.3,0.1

Type RM Length L Ch R = 1 ,12969   ,758,758,758
BEGIN DESCRIPTION:
Third Creek 17.1
END DESCRIPTION:
XS GIS Cut Line= 3
      1934476.23     13921552.16      1933055.15     13921336.77
      1932492.95     13921422.46
#Sta/Elev= 30
    3482  1657.3  3533.7 1655.02  3619.6  1654.8  3707.6 1644.49  3759.2 1641.67
  3816.9 1641.63  3850.4 1638.26  3935.2 1636.48  3992.9 1640.91  4038.4 1635.76
  4391.8 1637.66  4751.2  1639.6  4827.3 1639.14  4845.5 1643.34  4873.4 1640.34
  4921.3 1638.48  4945.6 1633.29  4969.9 1631.18  4985.9 1626.09  4986.4 1625.59
  5002.5 1626.09  5024.5 1627.91  5033.6  1631.9  5051.8 1635.14    5155 1643.75
  5212.7 1652.14  5236.9 1658.89  5273.8 1661.38  5465.9 1674.61    5488 1675.61
#Mann= 10 ,-1 , 0
    3482     .07       0  3533.7    .035       0  3850.4     .05       0
  4391.8    .035       0  4751.2    .063       0  4873.4     .07       0
  4985.9     .05       0  5002.5     .07       0  5273.8      .1       0
  5465.9    .035       0
#Block Obstruct= 2 , 0
         4835.66 1639.76
Bank Sta=4985.9,5002.5
XS Rating Curve= 0 ,0
Exp/Cntr=0.3,0.1

Type RM Length L Ch R = 1 ,12211   ,465,465,465
BEGIN DESCRIPTION:
Third Creek 17.0
END DESCRIPTION:
XS GIS Cut Line= 3
      1934462.68     13921482.72        1933025.       13920725.
      1932825.04     13920625.02
#Sta/Elev= 30
  3374.6  1654.8  3421.4 1653.17  3499.6 1651.88  3573.3 1643.64  3675.9 1635.37
  3825.5 1633.19  3871.3 1632.74  3997.8 1635.39  4042.8 1640.52  4082.8  1634.6
  4120.1 1637.41  4347.1 1634.16  4401.6 1637.71  4712.5  1636.5  4786.8 1635.03
  4798.4 1638.01  4874.2 1635.27  4893.8 1630.94  4906.7 1627.13  4988.3 1625.08
  4989.5 1619.88    4990 1619.38  5006.1 1619.88  5008.5  1624.4  5035.4 1627.74
  5051.4 1638.44  5082.3 1646.06  5095.7 1654.36  5135.2 1658.36  5223.3 1666.79
#Mann= 11 ,-1 , 0
  3374.6     .07       0  3421.4    .035       0  3573.3     .07       0
  3825.5    .035       0  3871.3     .07       0  3997.8     .05       0
  4712.5    .035       0  4893.8     .07       0  4989.5     .05       0
  5006.1     .07       0  5135.2    .035       0
#Block Obstruct= 2 , 0
         4043.96 1639.94
Bank Sta=4989.5,5006.1
XS Rating Curve= 0 ,0
Exp/Cntr=0.3,0.1

Type RM Length L Ch R = 1 ,11746   ,475,475,475
BEGIN DESCRIPTION:
Third Creek 16.0
END DESCRIPTION:
XS GIS Cut Line= 3
       1934453.5     13921229.52        1933375.       13920475.
      1933224.98     13920324.98
#Sta/Elev= 30
  3683.8 1650.12    3716 1647.84  3802.4 1647.16  3829.5 1639.94  3902.3 1632.52
  3990.6 1632.59  4027.2 1630.48  4035.9 1632.33  4076.8 1632.51  4089.4 1630.17
  4133.4  1629.4  4173.2 1632.26  4217.6 1640.76    4247 1633.41  4809.1 1631.59
  4880.5 1630.25  4898.6 1633.94  4938.5 1632.33  4946.2 1631.09  4964.5  1622.8
    4999 1617.64  4999.5 1617.14  5015.6 1617.64  5015.8 1620.17  5021.9  1621.8
  5043.7 1622.99    5068 1627.77    5137 1636.73  5203.1 1641.57  5212.2 1642.01
#Mann= 7 ,-1 , 0
  3683.8     .07       0  4173.2     .05       0  4809.1     .07       0
    4999     .05       0  5015.6     .07       0    5068    .063       0
  5203.1    .035       0
#XS Ineff= 2 , 0
          4900.1 1633.12
Permanent Ineff=
       F       F
#Block Obstruct= 2 , 0
          4204.2 1636.32
Bank Sta=4999,5015.6
XS Rating Curve= 0 ,0
Exp/Cntr=0.3,0.1

Type RM Length L Ch R = 1 ,11271   ,447,447,447
BEGIN DESCRIPTION:
Third Creek 15.0
END DESCRIPTION:
XS GIS Cut Line= 4
      1934754.73     13920424.67      1934002.22     13920258.52
        1933575.       13920075.      1933225.01       13919975.
#Sta/Elev= 30
  3768.5 1701.41  3836.7 1689.38  3953.4 1660.28  3990.3  1654.2    4018 1652.84
  4100.9  1637.1  4220.7 1629.04  4318.2 1627.03  4328.3 1625.02  4374.3 1624.68
  4417.4 1628.33  4478.8 1629.68  4870.1 1625.63  4886.4 1628.19  4915.8  1627.1
  4955.3 1616.76    4968 1615.96  4969.3 1615.39  4969.5 1612.69    4970 1612.19
  4986.2 1612.69  5013.3 1620.63  5140.6 1628.69    5147 1629.19  5219.5  1633.4
  5241.1 1636.51  5300.4 1656.57  5316.2 1659.24  5331.6 1662.87  5368.1 1662.28
#Mann= 8 ,-1 , 0
  3768.5    .035       0  4318.2     .05       0  4955.3      .1       0
  4969.5     .05       0  4986.2      .1       0  5140.6      .1       0
    5147    .035       0  5316.2    .063       0
#Block Obstruct= 2 , 0
         4482.92 1629.94
Bank Sta=4969.5,4986.2
XS Rating Curve= 0 ,0
Exp/Cntr=0.3,0.1

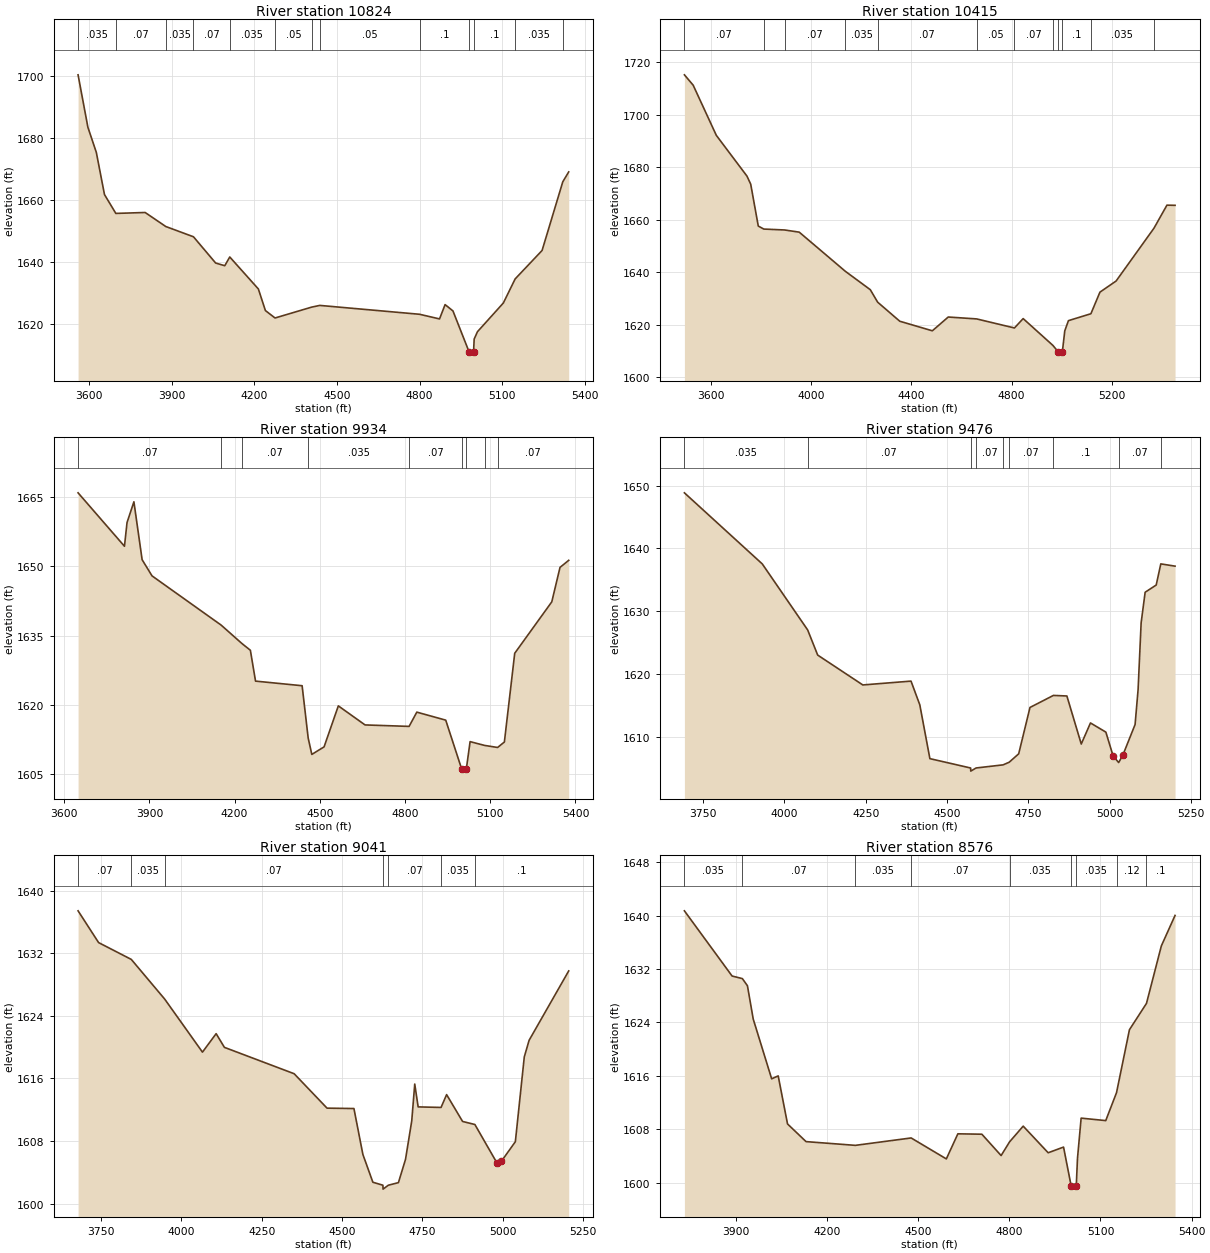
Type RM Length L Ch R = 1 ,10824   ,409,409,409
BEGIN DESCRIPTION:
Third Creek 14.0
END DESCRIPTION:
XS GIS Cut Line= 4
      1934945.72     13919879.97      1933904.02     13919801.91
        1933525.       13919675.      1933225.03     13919824.98
#Sta/Elev= 30
  3561.1 1700.47  3596.8 1683.53  3627.3 1675.44  3656.9 1661.83  3698.1 1655.74
  3804.4 1656.04  3879.3 1651.51  3979.7  1648.2  4060.1 1639.73  4093.2 1638.86
  4111.3 1641.68  4215.1 1631.35  4240.6 1624.39  4275.6 1621.99  4408.1 1625.49
  4437.8 1626.05  4799.7 1623.19  4872.2 1621.69  4892.4 1626.31  4920.9 1624.27
    4979 1611.15  4979.5 1610.65  4995.7 1611.15  4997.8 1615.17  5009.7 1617.55
  5103.7 1626.83  5146.5  1634.6  5244.2 1643.78  5319.3 1665.95  5340.8 1669.14
#Mann= 13 ,-1 , 0
  3561.1    .035       0  3698.1     .07       0  3879.3    .035       0
  3979.7     .07       0  4111.3    .035       0  4275.6     .05       0
  4408.1     .07       0  4437.8     .05       0  4799.7      .1       0
    4979     .05       0  4995.7      .1       0  5146.5    .035       0
  5319.3    .063       0
#Block Obstruct= 2 , 0
         4479.02 1627.07
Bank Sta=4979,4995.7
XS Rating Curve= 0 ,0
Exp/Cntr=0.3,0.1

Type RM Length L Ch R = 1 ,10415   ,481,481,481
BEGIN DESCRIPTION:
Third Creek 13.0
END DESCRIPTION:
XS GIS Cut Line= 3
      1935019.92     13919494.57        1933525.       13919325.
      1933074.98       13919375.
#Sta/Elev= 30
  3494.7  1715.2  3529.7 1711.25    3622 1692.14    3744 1676.64  3759.2 1673.55
  3789.4 1657.57  3811.4 1656.42  3894.8 1656.07  3952.8 1655.24  4136.9 1640.31
  4236.2 1633.32  4265.7 1628.55  4353.9 1621.29  4483.8 1617.65  4547.2  1622.9
  4660.4 1622.18  4811.3 1618.73  4846.1  1622.3  4964.9 1612.07  4985.7 1609.64
  4986.2 1609.14  5002.4 1609.64  5012.1 1617.62  5026.7 1621.52  5116.3 1624.15
  5152.4 1632.38  5216.9 1636.63  5367.9 1656.75  5419.6 1665.53    5452 1665.47
#Mann= 12 ,-1 , 0
  3494.7     .07       0  3811.4    .035       0  3894.8     .07       0
  4136.9    .035       0  4265.7     .07       0  4660.4     .05       0
  4811.3     .07       0  4964.9      .1       0  4985.7     .05       0
  5002.4      .1       0  5116.3    .035       0  5367.9      .1       0
#Block Obstruct= 2 , 0
         4593.98 1623.09
Bank Sta=4985.7,5002.4
XS Rating Curve= 0 ,0
Exp/Cntr=0.3,0.1

Type RM Length L Ch R = 1 ,9934    ,458,458,458
BEGIN DESCRIPTION:
Third Creek 12.0
END DESCRIPTION:
XS GIS Cut Line= 3
      1934855.46     13919082.85        1933525.       13918875.
      1933174.99     13919025.01
#Sta/Elev= 30
  3648.9 1666.01  3812.2  1654.4  3821.3 1659.56  3845.5 1664.06  3874.4 1651.48
  3909.3 1647.96  4152.7 1637.26  4225.8 1633.26  4255.5  1631.8  4273.7 1625.09
  4437.7 1624.09    4459 1612.74  4471.8 1609.16    4515  1610.8  4565.2 1619.71
  4659.3 1615.57  4814.3 1615.25  4841.5 1618.35  4943.3 1616.61  4999.2 1606.03
  4999.7 1605.53  5015.9 1606.03  5029.1 1611.94  5079.8 1611.12    5126 1610.67
  5149.8 1611.86  5186.2 1631.14  5316.7 1642.32  5345.7 1649.81  5376.3 1651.34
#Mann= 9 ,-1 , 0
  3648.9     .07       0  4152.7    .035       0  4225.8     .07       0
    4459    .035       0  4814.3     .07       0  4999.2     .05       0
  5015.9     .07       0  5079.8      .1       0    5126     .07       0
#Block Obstruct= 2 , 0
         4842.56 1618.44
Bank Sta=4999.2,5015.9
XS Rating Curve= 0 ,0
Exp/Cntr=0.3,0.1

Type RM Length L Ch R = 1 ,9476    ,435,435,435
BEGIN DESCRIPTION:
Third Creek 11.0
END DESCRIPTION:
XS GIS Cut Line= 3
      1934664.04     13918873.86        1933425.       13918475.
      1933225.01       13918525.
#Sta/Elev= 30
  3692.7 1648.85  3932.1 1637.51  4071.5 1626.99  4102.3 1622.98    4241 1618.22
  4389.1 1618.83  4416.1 1615.05  4447.1 1606.47  4572.2 1604.98  4572.7 1604.48
    4589 1604.98  4672.2 1605.48  4690.8  1605.9    4720 1607.24  4754.7 1614.63
  4826.7 1616.55  4868.1 1616.46  4912.3  1608.8  4940.6 1612.16  4987.9  1610.7
  5010.4 1606.86  5027.3 1605.85  5040.6 1607.09  5077.7 1611.91  5086.9 1617.46
  5096.3 1628.13  5108.6    1633  5142.6 1634.15  5156.7 1637.52  5200.5 1637.16
#Mann= 9 ,-1 , 0
  3692.7    .035       0  4071.5     .07       0  4572.2     .05       0
    4589     .07       0  4672.2    .035       0  4690.8     .07       0
  4826.7      .1       0  5027.3     .07       0  5156.7      .1       0
#Block Obstruct= 2 , 0
          4797.6 1616.57
Bank Sta=5010.4,5040.6
XS Rating Curve= 0 ,0
Exp/Cntr=0.3,0.1

Type RM Length L Ch R = 1 ,9041    ,465,465,465
BEGIN DESCRIPTION:
Third Creek 10.0
END DESCRIPTION:
XS GIS Cut Line= 3
      1934702.63     13918411.09        1933425.       13918075.
      1933224.95     13918125.01
#Sta/Elev= 30
  3678.5 1637.42  3742.4 1633.36  3844.2 1631.21  3948.1 1626.14  4065.7 1619.36
  4108.3 1621.72    4134 1619.97  4351.1  1616.6  4453.5  1612.2  4537.2 1612.15
  4565.1 1606.28  4596.2 1602.73  4627.4 1602.35  4627.9 1601.85  4644.3 1602.35
  4675.7 1602.68  4697.8 1605.66  4717.2 1610.58  4726.5 1615.28  4737.1 1612.36
  4808.4 1612.29  4825.7 1613.93  4875.4  1610.5  4913.7 1610.11  4982.5 1605.19
  4996.4 1605.42  5039.7 1607.91  5067.5 1618.75  5082.5 1620.87  5205.8 1629.74
#Mann= 7 ,-1 , 0
  3678.5     .07       0  3844.2    .035       0  3948.1     .07       0
  4627.4     .05       0  4644.3     .07       0  4808.4    .035       0
  4913.7      .1       0
#Block Obstruct= 2 , 0
         4828.17 1612.46
Bank Sta=4982.5,4996.4
XS Rating Curve= 0 ,0
Exp/Cntr=0.3,0.1

Type RM Length L Ch R = 1 ,8576    ,456,456,456
BEGIN DESCRIPTION:
Third Creek 9.0
END DESCRIPTION:
XS GIS Cut Line= 3
      1934675.01       13918025.        1933475.       13917625.
      1933125.02       13917625.
#Sta/Elev= 30
  3730.5 1640.73  3887.4 1630.96  3921.3 1630.57    3938  1629.5    3957 1624.51
  4017.7 1615.55  4039.2 1615.99  4069.9 1608.79  4130.9 1606.14  4293.3 1605.58
  4476.8 1606.69  4592.6 1603.55  4630.6 1607.31  4709.6 1607.25  4772.9 1604.05
  4800.8 1606.11  4845.6 1608.46  4927.8 1604.47  4978.4 1605.32  5003.4 1599.52
  5003.9 1599.02  5020.3 1599.52  5024.3 1603.64  5036.3 1609.66  5117.3 1609.29
  5152.8 1613.48  5195.3 1622.91  5251.4 1626.86  5300.3 1635.47  5345.4 1640.04
#Mann= 9 ,-1 , 0
  3730.5    .035       0  3921.3     .07       0  4293.3    .035       0
  4476.8     .07       0  4800.8    .035       0  5003.4    .035       0
  5020.3    .035       0  5152.8     .12       0  5251.4      .1       0
#Block Obstruct= 2 , 0
         4837.16 1608.08
Bank Sta=5003.4,5020.3
XS Rating Curve= 0 ,0
Exp/Cntr=0.3,0.1

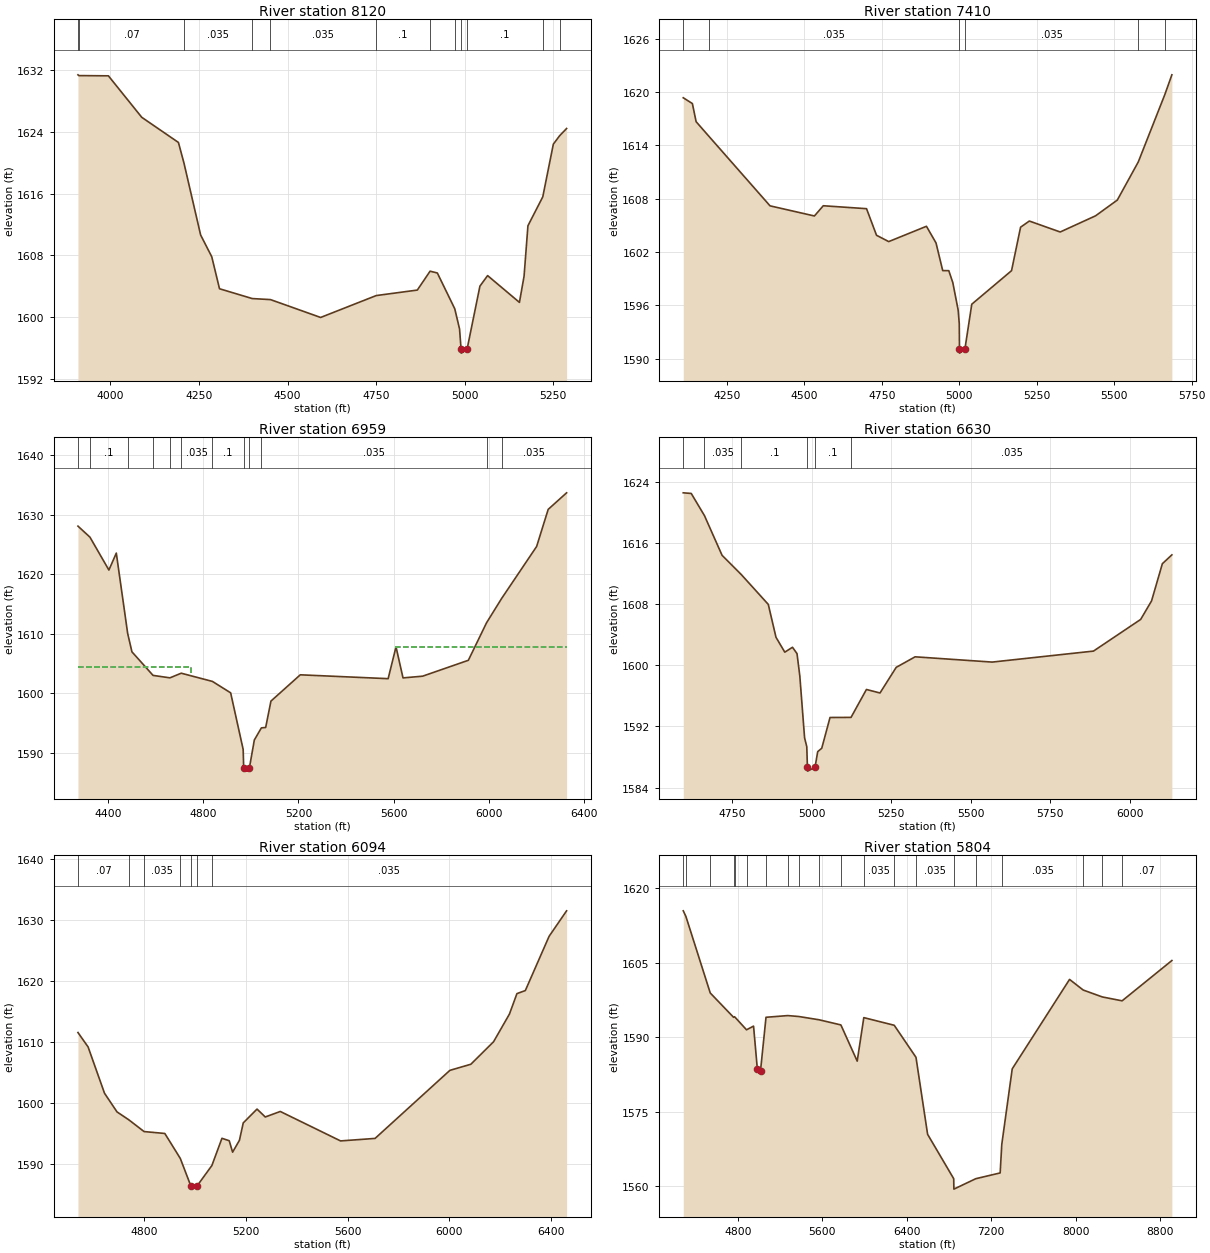
Type RM Length L Ch R = 1 ,8120    ,710,710,710
BEGIN DESCRIPTION:
Third Creek 8.0
END DESCRIPTION:
XS GIS Cut Line= 3
      1934665.29     13917542.27        1933625.       13917225.
      1933375.03     13917075.02
#Sta/Elev= 30
  3908.4 1631.35  3910.5 1631.25  3994.3 1631.22  4088.4 1625.86  4191.9 1622.61
  4207.6 1619.94  4254.6 1610.65    4286 1607.84  4307.9  1603.7  4400.5 1602.43
  4451.7  1602.3  4593.3 1599.99  4750.3 1602.82  4866.2 1603.53  4902.2 1605.97
  4922.7 1605.74  4971.9 1601.11  4985.4  1598.5  4989.7 1595.88  4990.2 1595.38
  5006.6 1595.88  5042.9 1604.04  5064.6  1605.4  5154.4 1601.94  5167.5 1605.33
  5178.4 1611.84  5220.3 1615.58  5250.1 1622.39  5267.9 1623.48  5287.5 1624.41
#Mann= 12 ,-1 , 0
  3908.4    .035       0  3910.5     .07       0  4207.6    .035       0
  4400.5     .07       0  4451.7    .035       0  4750.3      .1       0
  4902.2    .035       0  4971.9      .1       0  4989.7     .05       0
  5006.6      .1       0  5220.3     .07       0  5267.9    .094       0
#Block Obstruct= 2 , 0
          4901.3 1605.62
Bank Sta=4989.7,5006.6
XS Rating Curve= 0 ,0
Exp/Cntr=0.3,0.1

Type RM Length L Ch R = 1 ,7410    ,451,451,451
BEGIN DESCRIPTION:
Third Creek 7.0
END DESCRIPTION:
XS GIS Cut Line= 4
      1934568.81     13917063.27      1933811.76     13916570.63
      1933603.53     13916606.03      1933325.02     13916974.97
#Sta/Elev= 30
  4109.5 1619.34  4138.9 1618.69    4151 1616.65  4191.2 1615.05  4389.5 1607.19
  4532.7 1606.05  4561.3  1607.2  4700.9 1606.87  4733.1 1603.88  4772.5 1603.17
  4894.2 1604.89  4925.1 1603.02  4946.7 1599.91  4966.3  1599.9  4979.3 1598.56
  4996.6 1595.46  5000.1 1593.94  5000.8 1591.13  5001.3 1590.63  5018.5 1591.13
  5040.5 1596.13  5168.8  1599.9    5198 1604.79  5226.3 1605.48  5325.8 1604.25
  5440.1 1606.07  5510.1 1607.84  5577.7 1612.12  5663.1 1619.67  5686.2 1621.92
#Mann= 6 ,-1 , 0
  4109.5     .07       0  4191.2    .035       0  5000.8    .035       0
  5018.5    .035       0  5577.7    .094       0  5663.1     .12       0
#XS Ineff= 2 , 0
         4588.01 1606.91 5229.97         1605.23
Permanent Ineff=
       F       F
Bank Sta=5000.8,5018.5
XS Rating Curve= 0 ,0
Exp/Cntr=0.3,0.1

Type RM Length L Ch R = 1 ,6959    ,329,329,329
BEGIN DESCRIPTION:
Third Creek 6.0
END DESCRIPTION:
XS GIS Cut Line= 3
      1934525.03     13915824.98      1933917.59     13916201.84
      1932825.02     13916974.98
#Sta/Elev= 30
  4273.5 1628.05  4323.8  1626.2  4403.5 1620.67  4434.6 1623.52  4482.4    1610
  4500.3 1606.92  4589.1 1602.96  4659.9 1602.55  4707.4 1603.33  4838.5 1601.95
  4915.1 1600.03  4967.7 1590.51  4969.9 1587.37  4970.4 1586.87  4993.7 1587.37
  5014.6  1592.1  5044.2 1594.14  5062.3 1594.21  5084.4 1598.64  5207.7 1603.06
  5576.9 1602.41    5610 1607.76  5639.4 1602.54  5721.8 1602.83    5914  1605.5
  5990.5 1611.81  6054.1 1615.91  6200.9 1624.63  6249.5 1630.87  6326.8 1633.65
#Mann= 12 ,-1 , 0
  4273.5     .07       0  4323.8      .1       0  4482.4     .07       0
  4589.1      .1       0  4659.9     .07       0  4707.4    .035       0
  4838.5      .1       0  4969.9     .05       0  4993.7      .1       0
  5044.2    .035       0  5990.5    .094       0  6054.1    .035       0
#XS Ineff= 2 , 0
         4749.25 1604.31 5610.89         1607.78
Permanent Ineff=
       F       F
Bank Sta=4969.9,4993.7
XS Rating Curve= 0 ,0
Exp/Cntr=0.3,0.1

Type RM Length L Ch R = 1 ,6630    ,536,536,536
BEGIN DESCRIPTION:
Third Creek 5.0
END DESCRIPTION:
XS GIS Cut Line= 3
      1934124.96     13915725.02        1933775.       13915925.
      1932975.03     13916724.97
#Sta/Elev= 30
  4597.2 1622.62  4622.2 1622.54  4663.8 1619.63  4719.1 1614.43  4779.4 1611.91
  4864.2    1608  4888.4 1603.69    4916 1601.74  4940.2 1602.38  4954.4 1601.55
  4963.2 1598.63  4978.2 1590.51  4985.1 1589.35  4987.1 1586.65  4987.6 1586.15
  5010.9 1586.65  5019.4  1588.7  5032.1 1589.15  5058.1 1593.18    5124 1593.19
  5172.4 1596.85    5215 1596.39  5265.9 1599.75  5325.3 1601.13  5567.2 1600.44
  5885.4 1601.88  6033.6 1606.03  6067.8 1608.46  6101.7 1613.33  6131.6 1614.49
#Mann= 6 ,-1 , 0
  4597.2     .07       0  4663.8    .035       0  4779.4      .1       0
  4987.1     .05       0  5010.9      .1       0    5124    .035       0
#XS Ineff= 2 , 0
                         5320.68         1600.89
Permanent Ineff=
       F       F
Bank Sta=4987.1,5010.9
XS Rating Curve= 0 ,0
Exp/Cntr=0.3,0.1

Type RM Length L Ch R = 1 ,6094    ,290,290,290
BEGIN DESCRIPTION:
Third Creek 4.0
END DESCRIPTION:
XS GIS Cut Line= 4
      1933875.02       13915575.      1933510.01     13915493.89
      1933347.36      13915560.4      1932425.01     13916574.98
#Sta/Elev= 30
  4540.1 1611.54  4579.9 1609.18  4644.5  1601.6  4693.6 1598.55  4739.8 1597.26
    4800 1595.33  4881.5 1595.02  4942.3 1590.94    4984 1586.41  4984.5 1585.91
  5007.9 1586.41  5066.6 1589.78  5106.1 1594.23  5134.7 1593.83    5148 1591.96
  5174.8  1593.9  5189.8 1596.75    5244 1599.01  5276.4 1597.72  5335.4 1598.62
  5572.4  1593.8    5708 1594.21  6002.2 1605.35  6084.6 1606.35  6173.8 1610.03
  6236.2 1614.56  6265.7 1617.91  6298.7 1618.41  6392.3  1627.3  6460.9 1631.46
#Mann= 7 ,-1 , 0
  4540.1     .07       0  4739.8      .1       0    4800    .035       0
  4942.3     .07       0    4984     .05       0  5007.9     .07       0
  5066.6    .035       0
#Block Obstruct= 2 , 0
                         5247.25         1598.44
Bank Sta=4984,5007.9
XS Rating Curve= 0 ,0
Exp/Cntr=0.3,0.1

Type RM Length L Ch R = 1 ,5804    ,270,270,270
BEGIN DESCRIPTION:
Mapping XS 48dc8fd4
END DESCRIPTION:
XS GIS Cut Line= 5
      1933995.85     13915580.33       1933503.3     13915260.67
       1932816.9     13915220.91      1932009.83     13915393.83
      1929580.21     13914703.17
#Sta/Elev= 30
  4284.1 1615.44  4309.3  1614.3  4539.6 1598.91  4760.2 1594.02  4769.9 1594.13
    4883  1591.5  4949.6 1592.24  4985.6 1583.57  5015.7  1583.3  5067.5 1594.02
    5273 1594.36  5375.8 1594.18  5568.9 1593.52  5776.4 1592.48  5930.9  1585.2
  5993.4 1593.95  6281.5 1592.41  6487.5 1585.96  6597.4 1570.47  6844.6 1561.54
  6846.2 1559.44  7053.8 1561.54  7284.4  1562.7  7299.5 1568.41  7398.5 1583.64
  7941.3 1601.64  8070.6  1599.5  8251.6 1598.11    8439 1597.33  8910.1 1605.44
#Mann= 20 ,-1 , 0
  4284.1    .035       0  4309.3     .07       0  4539.6    .035       0
  4760.2     .07       0  4769.9    .035       0    4883     .07       0
  5067.5    .035       0    5273    .094       0  5375.8     .12       0
  5568.9    .094       0  5776.4    .063       0  5993.4    .035       0
  6281.5    .063       0  6487.5    .035       0  6844.6     .05       0
  7053.8    .035       0  7299.5    .035       0  8070.6    .094       0
  8251.6    .035       0    8439     .07       0
#Block Obstruct= 2 , 0
                         5083.92         1594.71
Bank Sta=4985.6,5015.7
XS Rating Curve= 0 ,0
Exp/Cntr=0.3,0.1