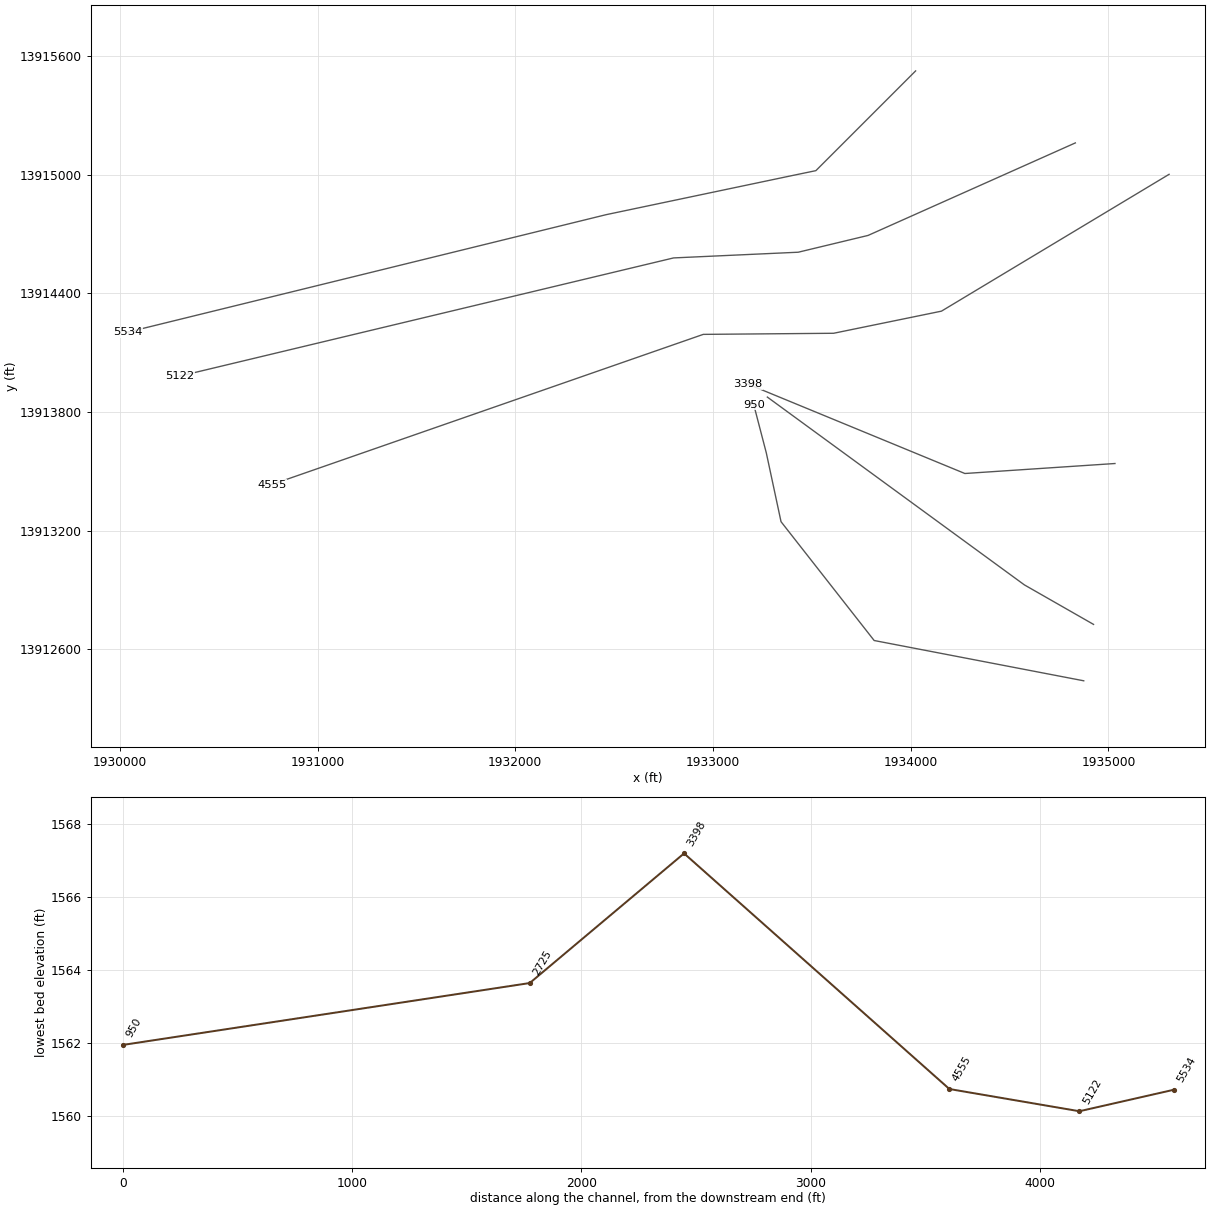
HEC-RAS study Third Creek.prj: Third Creek Base Level Engineering

--- Third Creek.g01 (geometry) --- (continued)

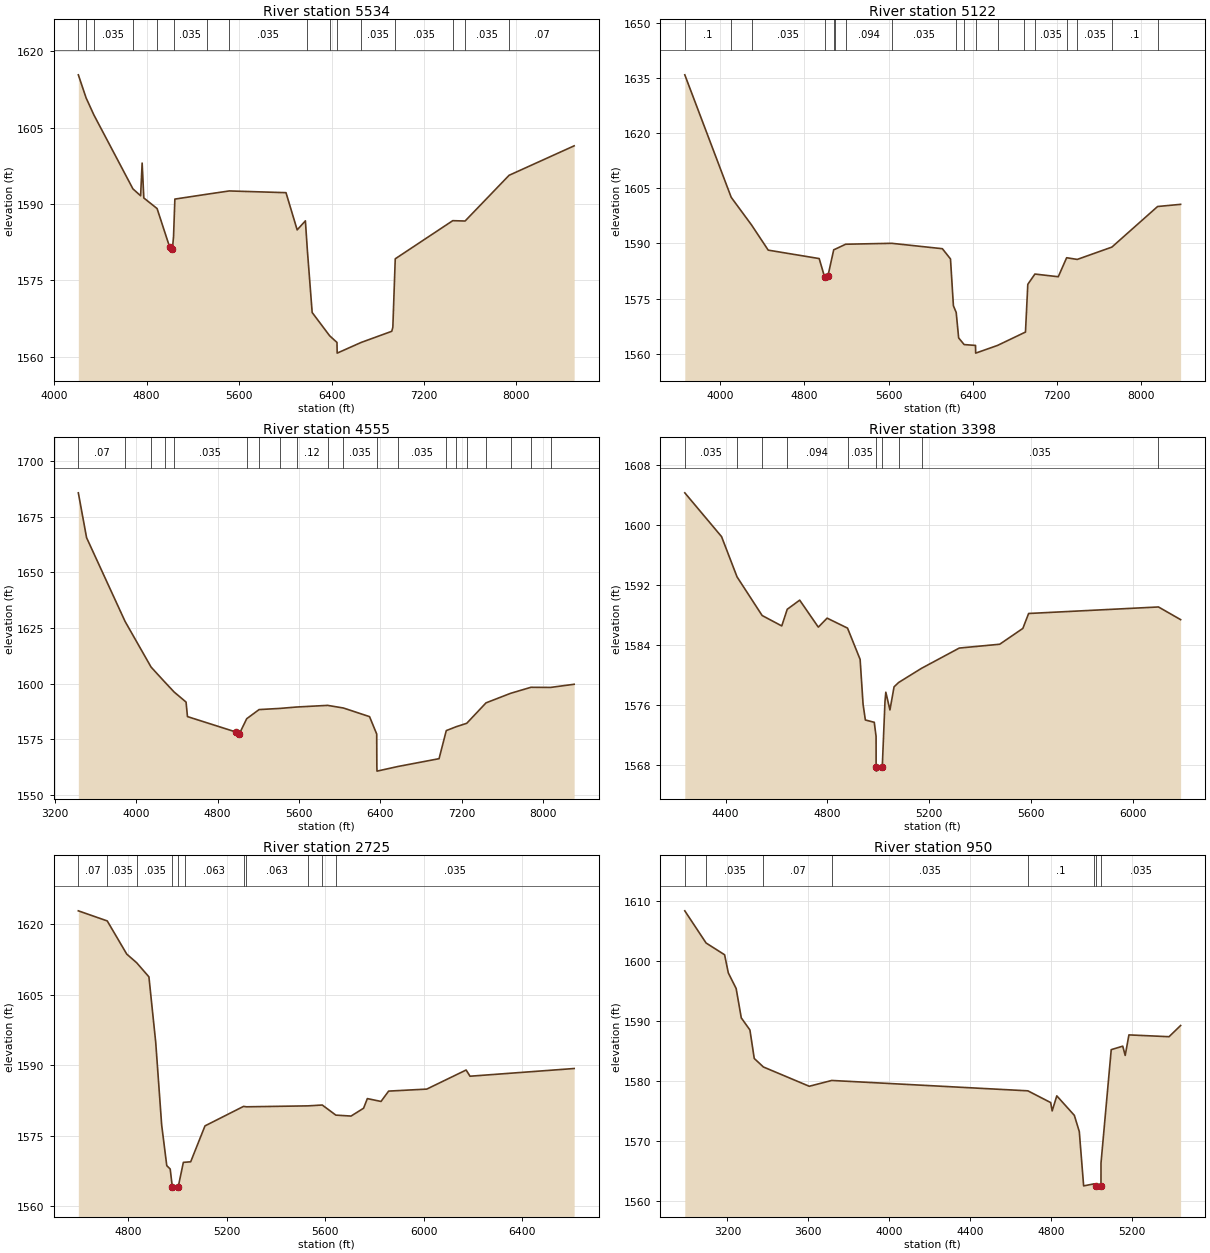
Type RM Length L Ch R = 1 ,5534    ,412,412,412
BEGIN DESCRIPTION:
Third Creek 3.0
END DESCRIPTION:
XS GIS Cut Line= 5
      1934024.98     13915524.98      1933520.44     13915020.44
      1933398.26     13914995.11      1932460.06     13914797.86
      1930038.53     13914203.17
#Sta/Elev= 30
  4209.2 1615.38  4276.3 1610.86  4343.4 1607.52  4681.6 1592.98  4748.2 1591.62
  4761.4 1598.05  4775.8 1591.19  4890.7 1589.11  5000.7 1581.46  5023.1 1581.11
  5033.1  1583.6  5044.6 1590.97    5321 1591.92  5515.2 1592.57  6006.2 1592.23
  6102.9 1584.92    6174  1586.7  6191.1 1580.92  6232.7 1568.69  6383.8 1564.12
  6447.4 1562.81    6449 1560.71  6656.6 1562.81  6921.6    1565  6930.8 1565.81
  6951.6 1579.24  7449.2 1586.73  7555.9 1586.66  7936.4 1595.64  8499.7 1601.43
#Mann= 16 ,-1 , 0
  4209.2    .035       0  4276.3     .07       0  4343.4    .035       0
  4681.6    .063       0  4890.7     .07       0  5033.1    .035       0
    5321    .094       0  5515.2    .035       0  6191.1     .07       0
  6383.8    .035       0  6447.4     .05       0  6656.6    .035       0
  6951.6    .035       0  7449.2     .07       0  7555.9    .035       0
  7936.4     .07       0
#Block Obstruct= 2 , 0
                         5993.01         1592.22
Bank Sta=5000.7,5023.1
XS Rating Curve= 0 ,0
Exp/Cntr=0.3,0.1

Type RM Length L Ch R = 1 ,5122    ,567,567,567
BEGIN DESCRIPTION:
Third Creek 2.2
END DESCRIPTION:
XS GIS Cut Line= 5
      1934832.92     13915160.79      1933784.49     13914692.76
       1933431.2     13914607.81      1932800.78     13914578.97
      1930302.44     13913980.95
#Sta/Elev= 30
  3663.5 1635.97  4104.6 1602.58  4298.7 1595.01  4456.2 1588.19  4940.6 1585.89
  4991.6  1580.9  5023.1 1581.09  5078.7  1588.3  5092.2 1588.45  5192.4  1589.8
    5630 1590.05  6111.1 1588.58  6188.2 1585.79    6216 1573.02  6242.4 1571.21
  6265.8 1564.27    6318 1562.45    6426 1562.22  6427.6 1560.12  6635.3 1562.22
  6889.7 1565.71  6900.8 1565.86  6922.9 1578.87  6990.3 1581.67  7212.4 1580.94
    7292 1586.12  7392.6 1585.66  7721.9 1589.02  8156.2 1600.08    8375 1600.67
#Mann= 18 ,-1 , 0
  3663.5      .1       0  4104.6     .07       0  4298.7    .035       0
  4991.6     .07       0  5078.7    .035       0  5092.2     .07       0
  5192.4    .094       0    5630    .035       0  6242.4     .07       0
    6318    .035       0    6426     .05       0  6635.3    .035       0
  6889.7     .07       0  6990.3    .035       0    7292     .07       0
  7392.6    .035       0  7721.9      .1       0  8156.2     .07       0
#Block Obstruct= 2 , 0
                          5403.6         1590.18
Bank Sta=4991.6,5023.1
XS Rating Curve= 0 ,0
Exp/Cntr=0.3,0.1

Type RM Length L Ch R = 1 ,4555    ,1157,1157,1157
BEGIN DESCRIPTION:
Third Creek 2.1
END DESCRIPTION:
XS GIS Cut Line= 5
      1935307.05     13915001.86      1934155.66     13914309.65
      1933610.05     13914197.77      1932950.91     13914192.19
      1930767.73     13913432.34
#Sta/Elev= 30
  3431.6 1685.72  3512.7 1665.57  3890.4 1628.01  4146.4 1607.46  4278.6 1600.86
  4372.1 1596.29    4490 1591.74  4503.8 1585.22  4981.8 1578.27  5014.5 1577.58
  5085.8 1584.27  5207.3 1588.37  5416.6 1588.91    5575 1589.52  5880.8 1590.26
  6035.9 1589.08  6292.7  1585.2    6363 1577.39  6364.4 1562.83    6366 1560.73
  6573.7 1562.83  6975.6 1566.32  7046.4 1578.93  7144.2 1580.68  7247.5 1582.21
  7436.9 1591.39  7678.2 1595.67  7878.1 1598.38  8070.8 1598.32  8302.8 1599.74
#Mann= 20 ,-1 , 0
  3431.6     .07       0  3890.4      .1       0  4146.4    .035       0
  4278.6      .1       0  4372.1    .035       0  5085.8    .063       0
  5207.3    .035       0  5416.6    .094       0    5575     .12       0
  5880.8    .094       0  6035.9    .035       0  6364.4    .035       0
  6573.7    .035       0  7046.4    .035       0  7144.2     .07       0
  7247.5    .063       0  7436.9    .035       0  7678.2     .07       0
  7878.1     .07       0  8070.8     .07       0
#Block Obstruct= 2 , 0
                         5823.18          1589.9
Bank Sta=4981.8,5014.5
XS Rating Curve= 0 ,0
Exp/Cntr=0.3,0.1

Type RM Length L Ch R = 1 ,3398    ,673,673,673
BEGIN DESCRIPTION:
Third Creek 2.0
END DESCRIPTION:
XS GIS Cut Line= 3
      1935033.31      13913538.9      1934274.09      13913488.4
      1933175.79     13913941.02
#Sta/Elev= 30
  4239.7 1604.31  4384.2 1598.47  4445.1  1593.1  4543.7 1587.95  4620.8 1586.56
  4642.3 1588.78  4691.3    1590  4764.5  1586.4  4799.1  1587.6  4879.3 1586.27
  4928.8  1582.1  4940.4 1576.11  4949.4 1574.02  4984.4 1573.71  4991.5 1571.83
  4991.7  1567.7  4992.2  1567.2  5015.8  1567.7  5026.5 1576.47  5029.8 1577.72
    5046 1575.36  5062.2 1578.44  5080.2 1579.02  5170.2 1580.91  5318.5 1583.61
  5477.5 1584.12  5568.4 1586.23  5591.1 1588.22  6101.4 1589.09  6188.5  1587.4
#Mann= 10 ,-1 , 0
  4239.7    .035       0  4445.1     .07       0  4543.7    .035       0
  4642.3    .094       0  4879.3    .035       0  4991.7    .035       0
  5015.8    .035       0  5080.2    .063       0  5170.2    .035       0
  6101.4    .094       0
Bank Sta=4991.7,5015.8
XS Rating Curve= 0 ,0
Exp/Cntr=0.3,0.1

Type RM Length L Ch R = 1 ,2725    ,1775,1775,1775
BEGIN DESCRIPTION:
Third Creek 1.0
END DESCRIPTION:
XS GIS Cut Line= 3
      1934924.96     13912725.02        1934575.       13912925.
      1933274.99     13913875.01
#Sta/Elev= 30
  4597.5 1622.87  4714.9 1620.72  4794.2 1613.65    4834 1611.84  4884.1 1608.82
  4911.7  1594.9  4935.9 1577.28  4956.6 1568.64  4970.5 1567.92  4979.1 1564.14
  4979.6 1563.64  5003.2 1564.14  5023.9 1569.33  5030.1 1569.36  5053.7 1569.46
  5111.8  1577.1  5268.4 1581.25  5280.1 1581.16  5530.1 1581.36  5587.9 1581.54
  5643.1 1579.39  5704.9 1579.19  5755.7 1580.86    5771 1582.91  5826.5  1582.3
  5857.4  1584.5  6012.3 1584.93  6172.1 1588.99  6187.9 1587.67  6610.7 1589.31
#Mann= 11 ,-1 , 0
  4597.5     .07       0  4714.9    .035       0    4834    .035       0
  4979.1     .05       0  5003.2    .035       0  5030.1    .063       0
  5268.4      .1       0  5280.1    .063       0  5530.1      .1       0
  5587.9    .063       0  5643.1    .035       0
Bank Sta=4979.1,5003.2
XS Rating Curve= 0 ,0
Exp/Cntr=0.3,0.1

Type RM Length L Ch R = 1 ,950     ,0,0,0
BEGIN DESCRIPTION:
Third Creek 0.0
END DESCRIPTION:
XS GIS Cut Line= 5
      1934875.38     13912439.74      1933815.27     13912643.53
      1933344.21      13913244.6       1933269.7     13913592.74
       1933206.1     13913836.88
#Sta/Elev= 30
  2989.3 1608.37  3094.6    1603  3186.1 1601.04  3204.4 1598.02  3243.2 1595.41
  3268.6 1590.51  3311.3 1588.49  3332.7 1583.74  3377.9 1582.32  3604.6  1579.1
  3715.9 1580.07  4685.5 1578.34  4798.3 1576.38  4805.7 1574.99  4828.6  1577.5
  4915.3 1574.25  4939.8 1571.54  4961.3 1562.48  5014.4 1562.83  5022.8 1562.44
  5023.3 1561.94    5047 1562.44  5047.2  1566.3  5047.3 1566.35  5097.7 1585.21
  5154.6 1585.79  5166.8 1584.25  5185.2 1587.67  5383.6 1587.37  5440.8 1589.24
#Mann= 8 ,-1 , 0
  2989.3     .07       0  3094.6    .035       0  3377.9     .07       0
  3715.9    .035       0  4685.5      .1       0  5014.4    .035       0
  5022.8     .05       0    5047    .035       0
Bank Sta=5022.8,5047
XS Rating Curve= 0 ,0
Exp/Cntr=0.3,0.1

Chan Stop Cuts=-1
Use User Specified Reach Order=0
Composite Channel Slope=5