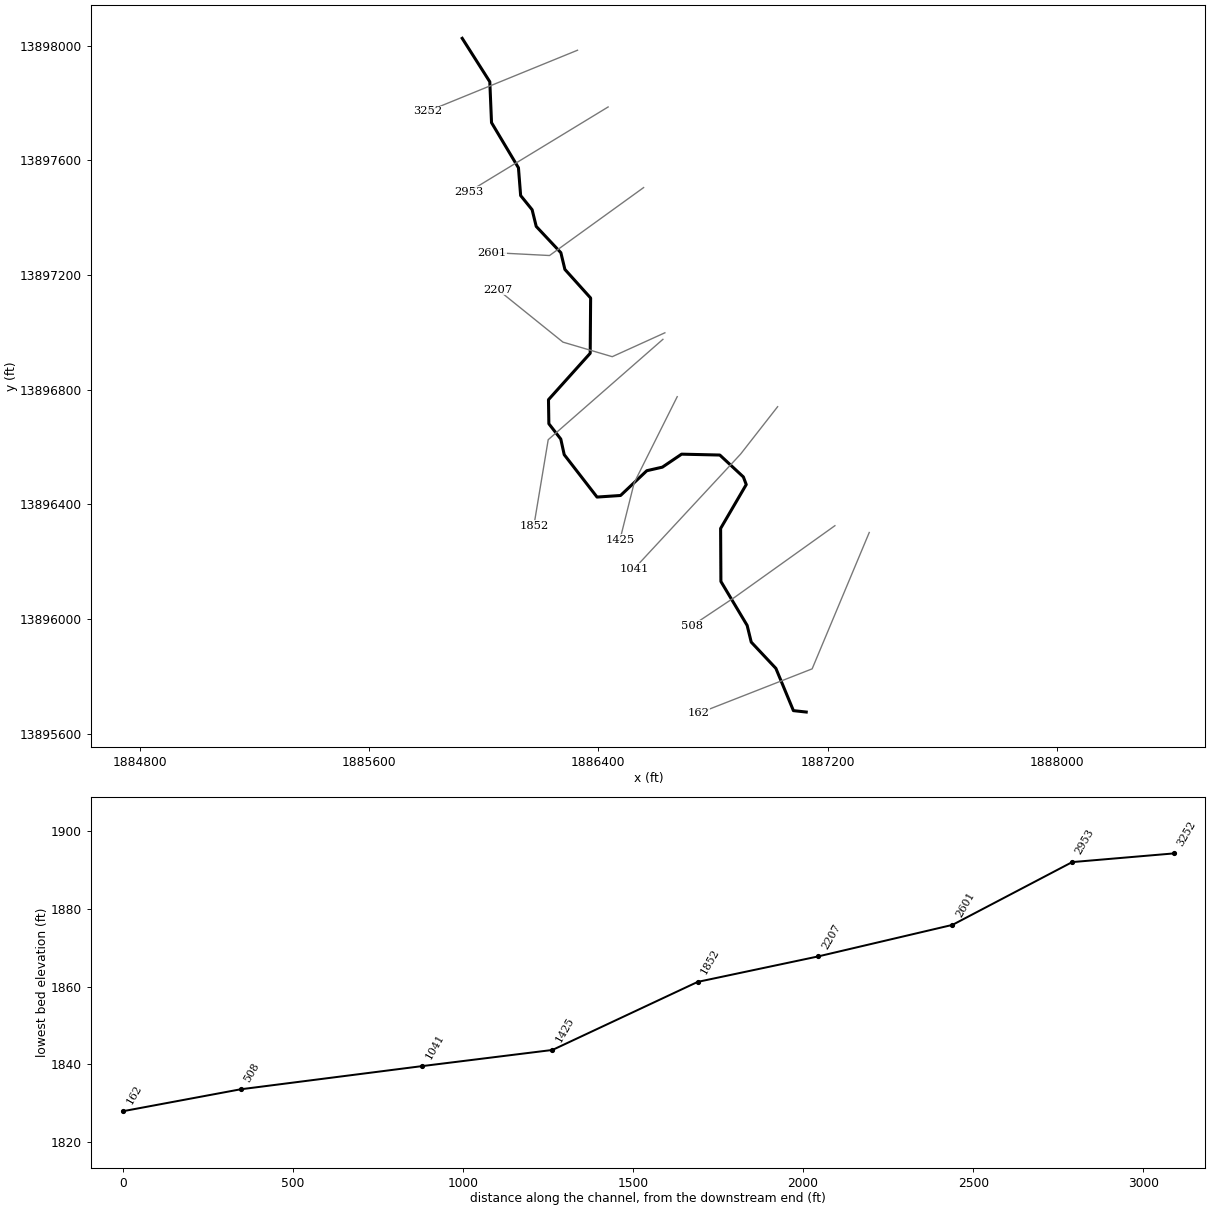
--- Tomas Creek.prj (project) ---

Proj Title=Tomas Creek Base Level Engineering
Current Plan=p01
Default Exp/Contr=0.3,0.1
English Units
Geom File=g01
Flow File=f01
Plan File=p01
Y Axis Title=Elevation
X Axis Title(PF)=Main Channel Distance
X Axis Title(XS)=Station
BEGIN DESCRIPTION:
Tomas Creek
END DESCRIPTION:
DSS Export Rating Curves= 0
DSS Export Rating Curve Sorted= 0
DSS Export Volume Flow Curves= 0
DXF OffsetX= 0
DXF OffsetY= 0
DXF ScaleX= 1
DXF ScaleY= 10

--- Tomas Creek.p01 (plan) ---

Plan Title=Multiple Run
Short Identifier=Multiple
Geom File=g01
Flow File=f01
Subcritical Flow
K Sum by GR= 0
Std Step Tol= 0.01
Critical Tol= 0.01
Num of Std Step Trials= 20
Max Error Tol= 0.3
Flow Tol Ratio= 0.001
Split Flow NTrial= 30
Split Flow Tol= 0.02
Split Flow Ratio= 0.02
Log Output Level= 0
Friction Slope Method= 1
Unsteady Friction Slope Method= 2
Unsteady Bridges Friction Slope Method= 1
Parabolic Critical Depth
Global Vel Dist=  1 , 1 , 1
Global Log Level= 0
CheckData=True
Encroach Param= -1, 0, 0, 0
BEGIN DESCRIPTION:
Multiple Run
END DESCRIPTION:

--- Tomas Creek.f01 (steady flow) ---

Flow Title=Multiple
Program Version=4.10
Number of Profiles= 7
Profile Names=10-year,25-year,50-year,1pct_min,100-year,1pct_plu,500-year
River Rch & RM=Tomas Creek,Reach-1         ,3252
     831    1401    1941    1304    2601    5190    4606
River Rch & RM=Tomas Creek,Reach-1         ,1425
    2016    3550    5058    3479    6942   13852   12921
Boundary for River Rch & Prof#=Tomas Creek,Reach-1         , 1
Up Type= 0
Dn Type= 3
Dn Slope=0.008
Boundary for River Rch & Prof#=Tomas Creek,Reach-1         , 2
Up Type= 0
Dn Type= 3
Dn Slope=0.008
Boundary for River Rch & Prof#=Tomas Creek,Reach-1         , 3
Up Type= 0
Dn Type= 3
Dn Slope=0.008
Boundary for River Rch & Prof#=Tomas Creek,Reach-1         , 4
Up Type= 0
Dn Type= 3
Dn Slope=0.008
Boundary for River Rch & Prof#=Tomas Creek,Reach-1         , 5
Up Type= 0
Dn Type= 3
Dn Slope=0.008
Boundary for River Rch & Prof#=Tomas Creek,Reach-1         , 6
Up Type= 0
Dn Type= 3
Dn Slope=0.008
Boundary for River Rch & Prof#=Tomas Creek,Reach-1         , 7
Up Type= 0
Dn Type= 3
Dn Slope=0.008
DSS Import GetInterval= 0
DSS Import GetPeak= 0
DSS Import FillOption= 0

--- Tomas Creek.g01 (geometry) ---

Geom Title=Existing Conditions
Program Version=4.10

River Reach=Tomas Creek     ,Reach-1
Reach XY= 30
        1885925.       13898025.      1886021.25     13897873.45
      1886027.25     13897730.93      1886121.17     13897573.42
      1886128.83     13897476.58      1886168.86     13897427.17
      1886183.16     13897368.95      1886269.13     13897277.28
      1886283.18     13897218.96      1886372.94     13897119.14
      1886371.46     13896926.46      1886225.93     13896764.52
      1886227.26     13896680.56      1886268.85     13896627.17
      1886280.84     13896572.71      1886395.26     13896424.87
      1886477.36     13896430.39      1886568.95     13896516.84
      1886623.25     13896529.22      1886690.22     13896574.51
      1886823.56     13896571.47      1886905.74     13896495.08
      1886915.76     13896468.46      1886826.36     13896315.35
      1886827.35     13896130.52       1886918.9     13895977.19
      1886933.16     13895918.95      1887019.16     13895827.29
      1887080.28      13895679.9        1887125.       13895675.

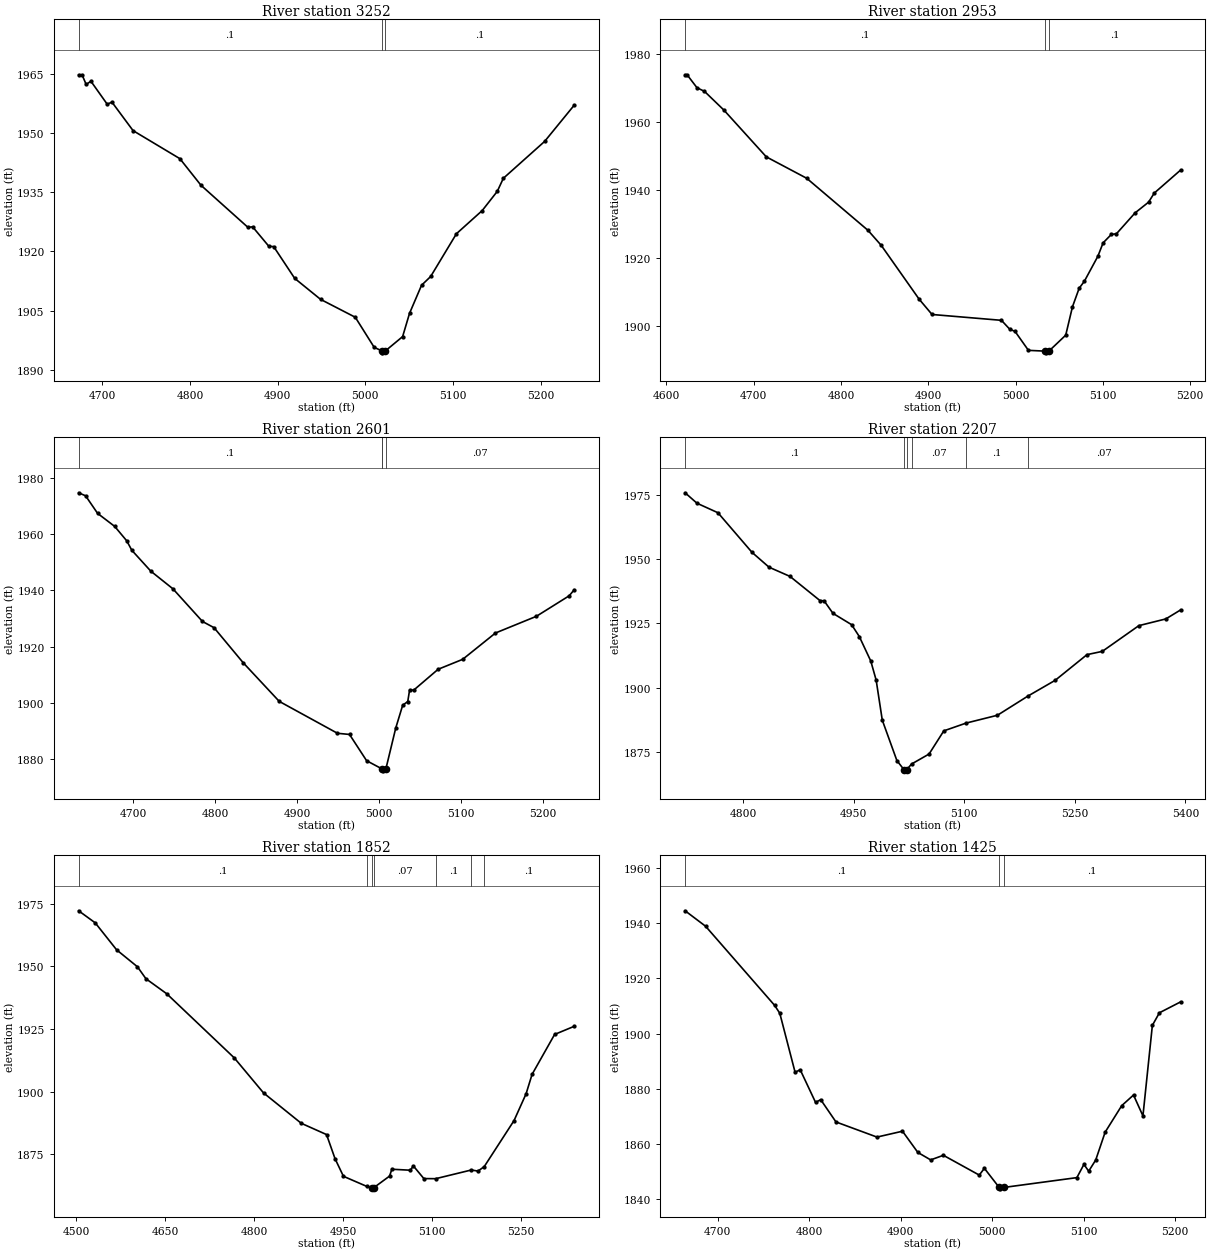
Type RM Length L Ch R = 1 ,3252    ,299,299,299
BEGIN DESCRIPTION:
Tomas Creek 8.0
END DESCRIPTION:
XS GIS Cut Line= 2
      1886327.22     13897983.55       1885803.8     13897770.02
#Sta/Elev= 30
    4673 1964.73  4676.9 1964.73  4681.6 1962.28    4687  1963.1  4705.6 1957.28
    4711 1957.81  4735.1 1950.59  4788.5 1943.49  4812.6 1936.75  4866.1 1926.11
  4871.5 1926.23  4890.1 1921.28  4895.5 1921.23  4919.5 1913.18    4949 1907.87
  4988.6 1903.34  5010.2 1895.71    5019 1894.83  5019.3 1894.33    5023 1894.83
  5042.6 1898.44  5050.5 1904.34  5064.2 1911.44  5074.6 1913.66    5104 1924.49
  5133.4 1930.35  5150.6 1935.22  5157.5 1938.52  5204.6 1947.86  5238.3 1957.02
#Mann= 3 ,-1 , 0
    4673      .1       0    5019     .05       0    5023      .1       0
Bank Sta=5019,5023
XS Rating Curve= 0 ,0
Exp/Cntr=0.3,0.1

Type RM Length L Ch R = 1 ,2953    ,352,352,352
BEGIN DESCRIPTION:
Tomas Creek 7.0
END DESCRIPTION:
XS GIS Cut Line= 2
      1886433.96     13897785.61      1885949.18     13897490.59
#Sta/Elev= 30
  4621.5 1973.94  4623.8 1973.94  4635.1 1970.13  4643.7 1969.06    4666 1963.53
  4714.5 1949.78  4760.8 1943.47    4831 1928.14  4846.2  1923.7  4889.5 1907.89
  4904.3 1903.38  4983.8 1901.66  4993.4 1899.01  4999.3 1898.42  5014.7 1892.82
  5034.1 1892.59  5034.3 1892.09  5038.1 1892.59  5057.4 1897.29  5065.1 1905.63
  5072.8 1911.11  5078.7 1913.14  5094.2 1920.51  5100.2 1924.46  5109.6 1926.94
  5115.5 1927.14  5136.8 1933.28  5152.3 1936.45  5158.8 1939.12    5189  1945.9
#Mann= 3 ,-1 , 0
  4621.5      .1       0  5034.1     .05       0  5038.1      .1       0
Bank Sta=5034.1,5038.1
XS Rating Curve= 0 ,0
Exp/Cntr=0.3,0.1

Type RM Length L Ch R = 1 ,2601    ,394,394,394
BEGIN DESCRIPTION:
Tomas Creek 6.0
END DESCRIPTION:
XS GIS Cut Line= 3
      1886557.71     13897504.39      1886229.57     13897267.41
       1886028.9     13897277.76
#Sta/Elev= 30
    4633  1974.7  4641.5 1973.63  4656.2 1967.38  4677.1 1962.75  4691.8 1957.63
    4698 1954.28  4721.2 1946.86  4748.3 1940.57  4784.4 1928.97  4798.5 1926.77
  4834.1 1914.33  4878.2 1900.59  4949.4 1889.25  4964.1 1888.84    4985 1879.51
  5003.6 1876.63  5004.4 1876.41  5004.6 1875.91  5008.4 1876.41  5020.6 1891.11
  5029.1 1899.23  5035.3 1900.53  5037.5 1904.59  5042.6 1904.59  5072.4 1911.99
  5102.4 1915.52  5142.5 1924.88  5192.5 1930.81  5232.6  1938.1  5238.7 1940.22
#Mann= 4 ,-1 , 0
    4633      .1       0  5003.6     .07       0  5004.4     .05       0
  5008.4     .07       0
Bank Sta=5004.4,5008.4
XS Rating Curve= 0 ,0
Exp/Cntr=0.3,0.1

Type RM Length L Ch R = 1 ,2207    ,355,355,355
BEGIN DESCRIPTION:
Tomas Creek 5.0
END DESCRIPTION:
XS GIS Cut Line= 4
       1886631.9     13896997.87      1886448.32     13896914.54
      1886276.45     13896965.32      1886049.32     13897148.32
#Sta/Elev= 30
    4721 1975.68  4737.1 1971.63  4765.6 1967.93  4811.8 1952.57  4834.9 1946.81
  4863.4 1943.23  4904.1 1933.84  4909.6 1933.77  4921.7  1928.9    4947  1924.5
  4957.4 1919.91    4973  1910.4  4980.3 1902.98  4988.6 1887.47  5008.4  1871.8
  5017.9  1868.3  5018.2  1867.8  5021.9  1868.3  5028.3 1870.44  5052.1 1874.32
  5072.1 1883.31  5102.5 1886.34  5144.9 1889.37  5186.2  1896.8  5223.3 1902.93
  5266.4 1912.88  5287.2 1914.15  5336.8 1924.13  5373.4 1926.74  5393.5 1930.24
#Mann= 6 ,-1 , 0
    4721      .1       0  5017.9     .05       0  5021.9      .1       0
  5028.3     .07       0  5102.5      .1       0  5186.2     .07       0
Bank Sta=5017.9,5021.9
XS Rating Curve= 0 ,0
Exp/Cntr=0.3,0.1

Type RM Length L Ch R = 1 ,1852    ,427,427,427
BEGIN DESCRIPTION:
Tomas Creek 4.0
END DESCRIPTION:
XS GIS Cut Line= 3
      1886625.03     13896975.03        1886225.       13896625.
        1886175.     13896324.99
#Sta/Elev= 30
  4503.7 1972.16  4531.7 1967.34  4567.8 1956.57  4602.9 1949.81  4617.2 1945.05
  4652.3 1939.05  4766.2 1913.46  4815.5  1899.5  4879.1 1887.38  4921.8 1882.87
  4936.1 1873.25  4950.3 1866.22  4989.8 1862.18  4997.7 1861.72  4997.9 1861.22
  5001.7 1861.72  5028.1 1866.31  5031.9 1869.04  5063.1 1868.65  5068.2 1870.36
  5085.9 1865.31  5105.8 1865.27    5166 1868.74  5177.2  1868.3  5187.7 1870.08
    5238 1888.46  5258.3 1899.14  5268.4 1906.89  5306.4 1922.82  5339.4 1926.06
#Mann= 7 ,-1 , 0
  4503.7      .1       0  4989.8     .07       0  4997.7     .05       0
  5001.7     .07       0  5105.8      .1       0    5166     .07       0
  5187.7      .1       0
#Block Obstruct= 2 , 0
                         5060.69         1868.82
Bank Sta=4997.7,5001.7
XS Rating Curve= 0 ,0
Exp/Cntr=0.3,0.1

Type RM Length L Ch R = 1 ,1425    ,384,384,384
BEGIN DESCRIPTION:
Tomas Creek 3.0
END DESCRIPTION:
XS GIS Cut Line= 3
      1886675.02     13896775.03        1886525.       13896475.
        1886475.       13896275.
#Sta/Elev= 30
  4664.5 1944.57  4686.9 1938.96  4762.4 1910.23    4768 1907.38  4784.7 1885.99
  4790.3 1886.89  4807.1 1875.04  4812.7 1876.05  4829.4 1867.95  4874.2 1862.46
  4902.1 1864.59  4918.9 1856.88  4932.9 1854.18  4946.8 1855.85    4986 1848.67
  4991.6 1851.12  5007.8 1844.18  5008.2 1843.68  5012.7 1844.18  5092.7 1847.75
  5100.4 1852.55  5105.6 1850.08  5113.3 1854.15  5123.6 1864.25  5141.7 1873.86
  5154.6 1877.72  5164.9 1870.15  5175.2 1902.99  5182.9 1907.56  5206.1 1911.52
#Mann= 3 ,-1 , 0
  4664.5      .1       0  5007.8     .05       0  5012.7      .1       0
Bank Sta=5007.8,5012.7
XS Rating Curve= 0 ,0
Exp/Cntr=0.3,0.1

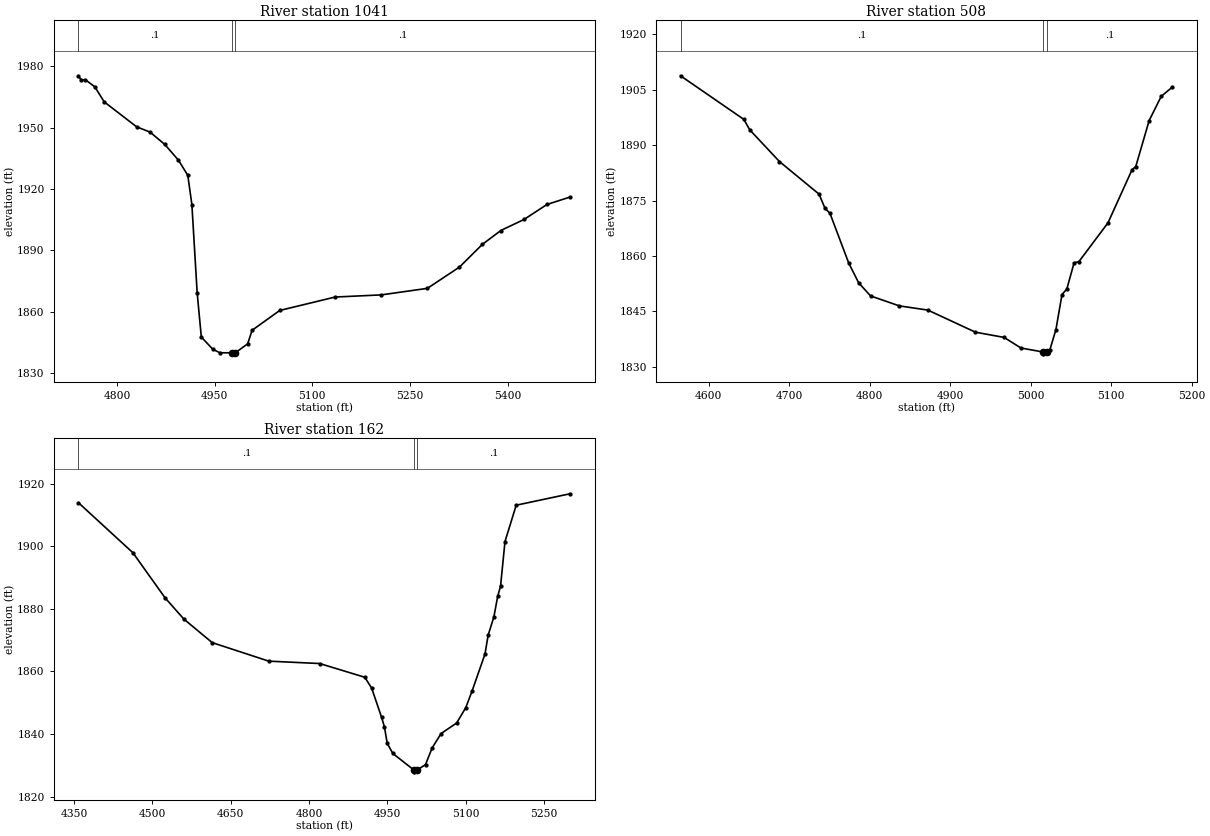
Type RM Length L Ch R = 1 ,1041    ,533,533,533
BEGIN DESCRIPTION:
Tomas Creek 2.0
END DESCRIPTION:
XS GIS Cut Line= 3
      1887025.22     13896740.06      1886896.02     13896574.71
      1886525.01     13896175.01
#Sta/Elev= 30
  4740.7 1975.36    4745 1973.21  4751.3 1973.41  4765.8 1970.01  4780.3 1962.61
    4830 1950.45  4850.8 1947.82  4873.4 1941.81  4894.2 1934.18  4908.7 1926.74
    4915 1912.47  4923.1 1869.37  4929.5 1847.71  4947.3 1841.69  4958.2 1840.03
  4976.7 1840.01  4977.1 1839.51  4981.6 1840.01  5000.7 1844.39  5007.5 1851.02
    5050 1860.71  5135.1 1867.26  5205.9 1868.31  5276.8  1871.5  5326.1  1881.9
  5361.3 1892.99  5389.6 1899.76  5425.3 1905.16  5460.5 1912.48  5495.9 1916.11
#Mann= 3 ,-1 , 0
  4740.7      .1       0  4976.7     .05       0  4981.6      .1       0
Bank Sta=4976.7,4981.6
XS Rating Curve= 0 ,0
Exp/Cntr=0.3,0.1

Type RM Length L Ch R = 1 ,508     ,346,346,346
BEGIN DESCRIPTION:
Tomas Creek 1.0
END DESCRIPTION:
XS GIS Cut Line= 3
        1887225.       13896325.        1886875.       13896075.
        1886725.       13895975.
#Sta/Elev= 30
  4565.2 1908.77  4643.9 1896.96  4651.2 1894.13  4688.1 1885.56  4737.2 1876.75
  4744.6 1872.94  4750.8 1871.54  4774.1 1858.08  4786.4 1852.76  4801.2 1849.21
  4836.8 1846.52  4872.4 1845.37  4931.4  1839.4  4967.1 1837.98  4987.9 1835.12
  5015.4 1834.04  5015.8 1833.54  5020.3 1834.04  5023.9 1834.65  5031.4 1840.12
  5038.9 1849.59  5044.9 1851.07  5053.9 1858.15  5059.9 1858.48    5096 1868.98
    5126  1883.4  5130.5  1884.2  5147.1 1896.64  5162.1  1903.2  5175.6 1905.65
#Mann= 3 ,-1 , 0
  4565.2      .1       0  5015.4     .05       0  5020.3      .1       0
Bank Sta=5015.4,5020.3
XS Rating Curve= 0 ,0
Exp/Cntr=0.3,0.1

Type RM Length L Ch R = 1 ,162     ,0,0,0
BEGIN DESCRIPTION:
Tomas Creek 0.0
END DESCRIPTION:
XS GIS Cut Line= 3
       1887344.8     13896301.27      1887145.63     13895825.63
      1886749.11     13895670.34
#Sta/Elev= 30
  4358.2 1913.87  4462.6 1897.87  4524.1 1883.49  4560.1 1876.69  4614.4 1869.17
  4722.8 1863.25  4820.3 1862.49  4906.7  1858.1  4919.8 1854.64  4938.9 1845.29
  4944.2 1842.31  4949.7 1836.97  4960.4 1833.75  5001.4 1828.39  5001.8 1827.89
  5006.4 1828.39    5023 1830.21  5035.6 1835.51  5052.8 1840.12  5082.6 1843.49
  5100.1  1848.4  5112.4 1853.82  5136.9 1865.53    5143 1871.61  5153.8  1877.3
  5161.3    1884  5166.7 1887.19  5175.2 1901.47  5196.7 1913.07  5299.7 1916.72
#Mann= 3 ,-1 , 0
  4358.2      .1       0  5001.4     .05       0  5006.4      .1       0
Bank Sta=5001.4,5006.4
XS Rating Curve= 0 ,0
Exp/Cntr=0.3,0.1

Chan Stop Cuts=-1
Use User Specified Reach Order=0
Composite Channel Slope=5