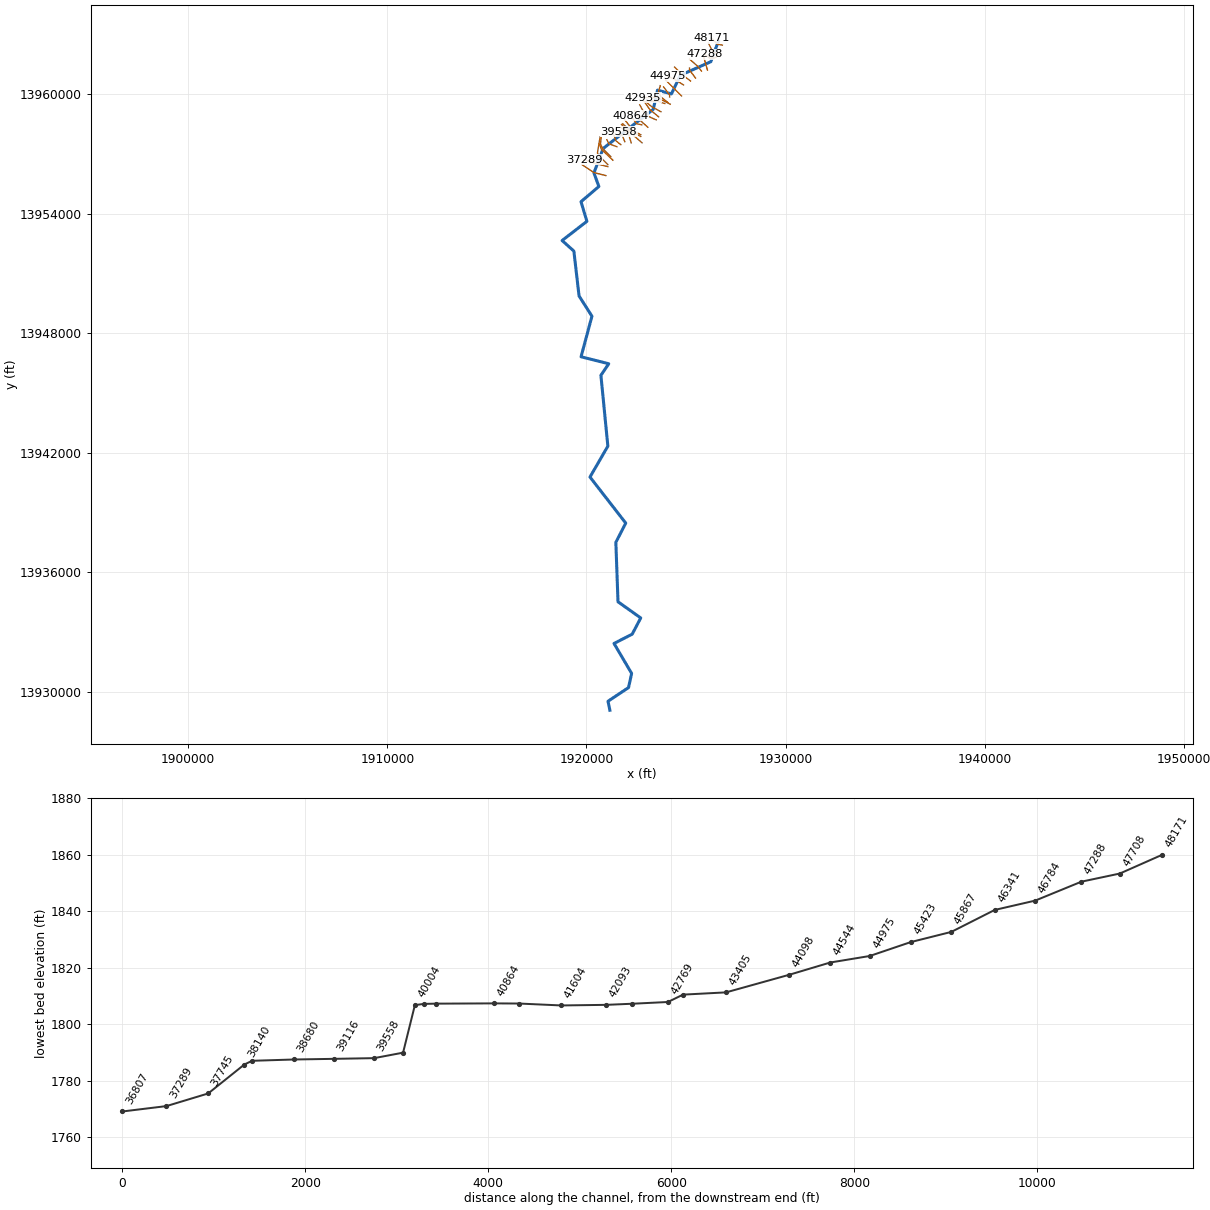
--- Town Creek.prj (project) ---

Proj Title=Town Creek Base Level Engineering
Current Plan=p01
Default Exp/Contr=0.3,0.1
English Units
Geom File=g01
Flow File=f01
Plan File=p01
Y Axis Title=Elevation
X Axis Title(PF)=Main Channel Distance
X Axis Title(XS)=Station
BEGIN DESCRIPTION:
Town Creek
END DESCRIPTION:
DSS Export Rating Curves= 0
DSS Export Rating Curve Sorted= 0
DSS Export Volume Flow Curves= 0
DXF OffsetX= 0
DXF OffsetY= 0
DXF ScaleX= 1
DXF ScaleY= 10

--- Town Creek.p01 (plan) ---

Plan Title=Multiple Run
Short Identifier=Multiple
Geom File=g01
Flow File=f01
Subcritical Flow
K Sum by GR= 0
Std Step Tol= 0.01
Critical Tol= 0.01
Num of Std Step Trials= 20
Max Error Tol= 0.3
Flow Tol Ratio= 0.001
Split Flow NTrial= 30
Split Flow Tol= 0.02
Split Flow Ratio= 0.02
Log Output Level= 0
Friction Slope Method= 1
Unsteady Friction Slope Method= 2
Unsteady Bridges Friction Slope Method= 1
Parabolic Critical Depth
Global Vel Dist=  1 , 1 , 1
Global Log Level= 0
CheckData=True
Encroach Param= -1, 0, 0, 0
BEGIN DESCRIPTION:
Multiple Run
END DESCRIPTION:

--- Town Creek.f01 (steady flow) ---

Flow Title=Multiple
Number of Profiles=7
Profile Names=10-year,25-year,50-year,1pct_min,100-year,1pct_plu,500-year
River Rch & RM= Town Creek,Reach-1,48171
    2328    4154    5966    4133    8247   16454   15579
River Rch & RM= Town Creek,Reach-1,44098
    2484    4439    6381    4422    8823   17605   16684
River Rch & RM= Town Creek,Reach-1,42376
    3738    6813    9926    6963   13892   27718   26921
River Rch & RM= Town Creek,Reach-1,41140
    3825    6974   10162    7128   14222   28376   27558
River Rch & RM= Town Creek,Reach-1,40239
    3956    7212   10508    7368   14700   29331   28467
River Rch & RM= Town Creek,Reach-1,37289
    5434    9993   14648   10324   20599   41101   40292
River Rch & RM= Town Creek,Reach-1,35077
    5624   10341   15154   10675   21300   42499   41622
River Rch & RM= Town Creek,Reach-1,31470
    6554   12114   17816   12590   25120   50121   49393
River Rch & RM= Town Creek,Reach-1,30565
    6641   12271   18042   12745   25429   50737   49962
River Rch & RM= Town Creek,Reach-1,27828
    7030   13011   19152   13542   27019   53910   53187
River Rch & RM= Town Creek,Reach-1,26723
    7061   13053   19198   13561   27058   53988   53162
River Rch & RM= Town Creek,Reach-1,23947
    7173   13248   19472   13744   27423   54716   53794
River Rch & RM= Town Creek,Reach-1,19826
    7201   13295   19537   13787   27508   54886   53934
River Rch & RM= Town Creek,Reach-1,19210
    9791   18266   27032   19197   38303   76426   76050
River Rch & RM= Town Creek,Reach-1,16699
    9826   18321   27105   19242   38392   76602   76167
River Rch & RM= Town Creek,Reach-1,15579
    9840   18329   27098   19222   38352   76523   75970
River Rch & RM= Town Creek,Reach-1,12493
   10616   19793   29279   20777   41456   82715   82172
River Rch & RM= Town Creek,Reach-1,8943
   10559   19643   29013   20554   41011   81828   81020
River Rch & RM= Town Creek,Reach-1,2263
   10749   19996   29534   20921   41743   83287   82448
Boundary for River Rch & Prof#=Town Creek,Reach-1,1
Up Type=0
Dn Type=3
Dn Slope=0.005
Boundary for River Rch & Prof#=Town Creek,Reach-1,2
Up Type=0
Dn Type=3
Dn Slope=0.005
Boundary for River Rch & Prof#=Town Creek,Reach-1,3
Up Type=0
Dn Type=3
Dn Slope=0.005
Boundary for River Rch & Prof#=Town Creek,Reach-1,4
Up Type=0
Dn Type=3
Dn Slope=0.005
Boundary for River Rch & Prof#=Town Creek,Reach-1,5
Up Type=0
Dn Type=3
Dn Slope=0.005
Boundary for River Rch & Prof#=Town Creek,Reach-1,6
Up Type=0
Dn Type=3
Dn Slope=0.005
Boundary for River Rch & Prof#=Town Creek,Reach-1,7
Up Type=0
Dn Type=3
Dn Slope=0.005

--- Town Creek.g01 (geometry) ---

Geom Title=Existing Conditions
Program Version=4.10

River Reach=Town Creek      ,Reach-1
Reach XY= 30
        1926625.       13962675.      1926245.25      13961644.6
      1924715.21     13960964.48       1924266.9     13960028.35
      1923564.89      13960214.7      1923355.24     13959253.97
      1920835.76     13957284.68      1920375.07     13956059.61
      1920621.53      13955376.5       1919726.2      13954614.5
      1920021.39      13953626.5      1918776.22      13952664.5
      1919366.79     13952131.67      1919627.06     13949880.85
       1920273.8     13948864.49      1919728.72     13946826.54
      1921117.69      13946475.1      1920724.57     13945895.18
       1921073.8      13942335.5       1920176.2      13940785.5
      1921971.37      13938473.5       1921474.9      13937504.9
      1921583.03     13934521.65      1922724.49     13933709.79
      1922295.47     13932894.63      1921382.79     13932428.42
      1922267.47     13930925.01      1922111.38     13930211.78
      1921080.82     13929527.31        1921175.       13929075.

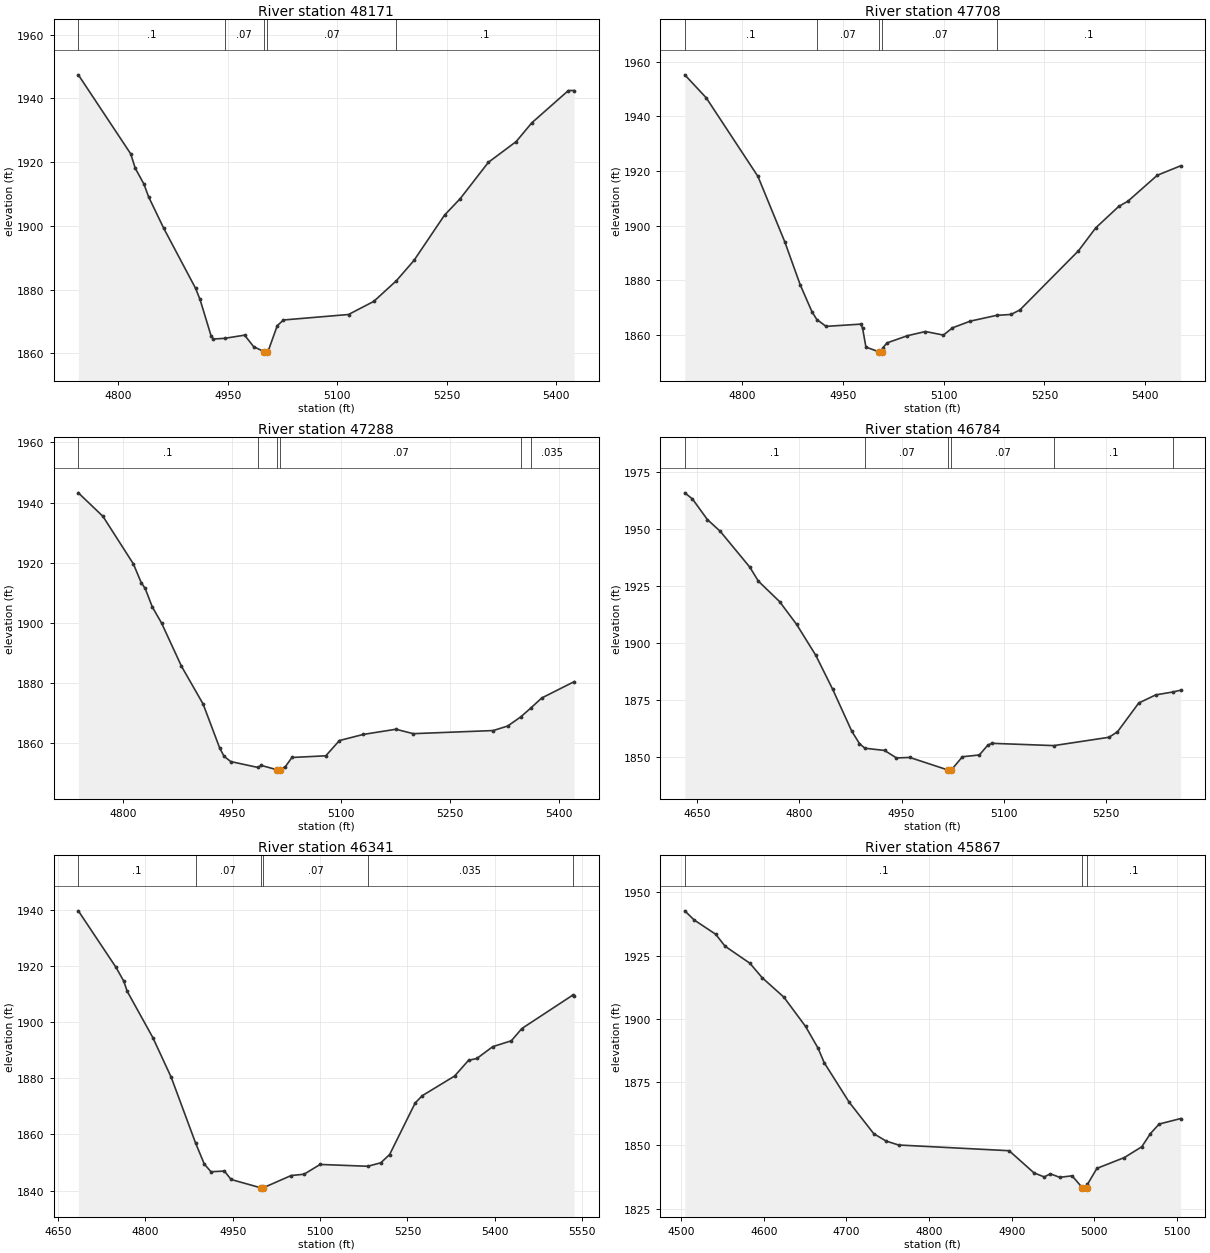
Type RM Length L Ch R = 1 ,48171   ,463,463,463
BEGIN DESCRIPTION:
Town Creek 90.0
END DESCRIPTION:
XS GIS Cut Line= 3
      1926824.96     13962475.01        1926575.       13962525.
      1926274.98     13962825.02
#Sta/Elev= 30
  4745.1 1947.37  4816.9 1922.56    4823 1918.09    4835 1913.06  4841.4 1909.07
  4861.8 1899.35  4905.6 1880.42  4911.8 1876.89    4927 1865.42  4930.1 1864.47
  4945.4 1864.68  4972.9 1865.68  4985.2 1862.08  4999.1 1860.54  4999.4 1860.04
  5003.5 1860.54  5005.5 1860.91  5017.6 1868.66  5026.1 1870.44  5115.2 1872.16
  5149.8 1876.27  5180.7 1882.74  5204.9 1889.13  5246.7 1903.34  5268.3 1908.54
  5306.8 1919.92  5344.9 1926.43  5366.2 1932.29  5416.4 1942.44  5424.3 1942.45
#Mann= 5 ,-1 , 0
  4745.1      .1       0  4945.4     .07       0  4999.1     .05       0
  5003.5     .07       0  5180.7      .1       0
Bank Sta=4999.1,5003.5
XS Rating Curve= 0 ,0
Exp/Cntr=0.3,0.1

Type RM Length L Ch R = 1 ,47708   ,420,420,420
BEGIN DESCRIPTION:
Town Creek 89.0
END DESCRIPTION:
XS GIS Cut Line= 3
      1926575.02     13962024.99        1926325.       13962175.
      1926124.99     13962575.02
#Sta/Elev= 30
  4714.1 1955.22  4746.1 1946.79  4823.1 1918.04  4863.1 1894.11  4886.1 1878.38
  4903.6 1868.54  4910.8  1865.7  4924.6 1863.19  4976.3 1864.01    4979 1862.52
    4984 1855.61  5003.2  1853.9  5003.5  1853.4  5007.8  1853.9  5008.9 1855.28
  5015.6 1857.16  5045.8 1859.77  5072.7 1861.31  5099.5    1860  5112.9 1862.65
  5139.7 1865.12  5178.9 1867.23  5200.1 1867.54  5213.5 1869.22  5300.7 1890.85
  5326.5 1899.26  5360.7 1907.07  5374.5 1909.01  5418.1 1918.47  5452.9 1921.93
#Mann= 5 ,-1 , 0
  4714.1      .1       0  4910.8     .07       0  5003.2     .05       0
  5007.8     .07       0  5178.9      .1       0
Bank Sta=5003.2,5007.8
XS Rating Curve= 0 ,0
Exp/Cntr=0.3,0.1

Type RM Length L Ch R = 1 ,47288   ,504,504,504
BEGIN DESCRIPTION:
Town Creek 88.0
END DESCRIPTION:
XS GIS Cut Line= 4
      1926525.03     13961875.01      1926393.34     13961822.34
      1926202.39     13961806.12      1925923.91     13962017.18
#Sta/Elev= 30
  4738.1 1943.23    4772 1935.39    4814 1919.52  4824.7 1913.31  4830.2 1911.36
  4839.9 1905.26  4852.8 1899.82  4880.1 1885.49    4910 1872.85  4932.9 1858.15
  4938.9 1855.44    4948 1853.71  4985.4 1851.75  4990.1 1852.42  5011.1 1851.02
  5011.4 1850.52  5015.7 1851.02  5023.3 1852.03  5032.3 1855.07  5078.9 1855.62
  5097.7 1860.71  5130.8 1862.76  5175.5 1864.47  5199.4    1863  5309.6 1864.04
  5329.5 1865.55  5347.5  1868.6  5361.1  1871.5  5376.3 1874.88    5421 1880.32
#Mann= 6 ,-1 , 0
  4738.1      .1       0  4985.4     .07       0  5011.1     .05       0
  5015.7     .07       0  5347.5      .1       0  5361.1    .035       0
Bank Sta=5011.1,5015.7
XS Rating Curve= 0 ,0
Exp/Cntr=0.3,0.1

Type RM Length L Ch R = 1 ,46784   ,443,443,443
BEGIN DESCRIPTION:
Town Creek 87.0
END DESCRIPTION:
XS GIS Cut Line= 3
      1926074.99     13961225.04        1925975.       13961575.
      1925874.99     13961925.03
#Sta/Elev= 30
  4631.8 1965.84  4643.1 1963.13  4664.9 1954.14  4683.7 1949.01  4727.3 1933.24
  4739.8 1927.13    4771 1918.15    4796 1908.14  4824.1 1894.62    4849 1879.67
    4877 1861.31  4888.2 1855.93  4896.2 1853.87  4925.1  1852.9  4942.6 1849.61
  4962.1 1849.83  5018.2 1844.33  5018.5 1843.83  5023.1 1844.33  5039.4 1850.13
  5064.3 1850.92  5076.8 1855.26    5083 1856.02  5173.7 1855.02  5254.6 1858.67
  5267.1 1861.08  5298.3 1873.69  5323.3 1877.26  5348.4 1878.53  5359.8  1879.3
#Mann= 6 ,-1 , 0
  4631.8      .1       0  4896.2     .07       0  5018.2     .05       0
  5023.1     .07       0  5173.7      .1       0  5348.4    .035       0
Bank Sta=5018.2,5023.1
XS Rating Curve= 0 ,0
Exp/Cntr=0.3,0.1

Type RM Length L Ch R = 1 ,46341   ,474,474,474
BEGIN DESCRIPTION:
Town Creek 86.0
END DESCRIPTION:
XS GIS Cut Line= 3
      1925774.97     13961175.03        1925575.       13961425.
      1925175.02     13961774.99
#Sta/Elev= 30
  4684.7 1939.63  4749.4  1919.5  4762.7  1914.6  4768.6 1910.99  4812.6 1894.51
  4844.3 1880.31    4886 1856.98    4901 1849.47  4912.5 1846.71  4935.5 1846.96
  4947.1 1843.95  4997.6 1841.02    4998 1840.52  5002.5 1841.02  5050.2 1845.36
  5072.4 1845.83    5100 1849.31  5181.8 1848.66  5204.2  1849.9  5219.4 1852.85
  5263.2 1871.19  5275.2 1873.77    5331  1880.8  5354.9  1886.4  5369.1 1887.04
  5396.5 1891.26  5428.4 1893.35  5446.5 1897.72    5534 1909.63  5536.3 1909.41
#Mann= 6 ,-1 , 0
  4684.7      .1       0    4886     .07       0  4997.6     .05       0
  5002.5     .07       0  5181.8    .035       0    5534      .1       0
Bank Sta=4997.6,5002.5
XS Rating Curve= 0 ,0
Exp/Cntr=0.3,0.1

Type RM Length L Ch R = 1 ,45867   ,444,444,444
BEGIN DESCRIPTION:
Town Creek 85.0
END DESCRIPTION:
XS GIS Cut Line= 3
      1925475.03     13960824.97        1925175.       13961225.
        1925175.     13961324.96
#Sta/Elev= 30
  4504.5 1942.74  4515.7 1939.16  4541.9 1933.48  4553.2 1928.76  4583.2 1922.04
  4598.2 1916.29  4624.4 1908.62  4650.7 1897.03  4665.7 1888.49  4673.2 1882.73
  4703.2 1867.21  4733.2 1854.65  4748.2 1851.74  4763.2 1850.19    4897 1847.93
    4927 1839.19  4939.4 1837.57  4946.9  1838.8  4958.2 1837.41  4973.2 1838.01
  4985.7 1833.25  4986.1 1832.75  4990.7 1833.25  4991.8 1834.66  5003.2 1840.95
  5036.5 1845.24  5057.5  1849.5    5068 1854.72  5078.5 1858.47  5104.5 1860.64
#Mann= 3 ,-1 , 0
  4504.5      .1       0  4985.7     .05       0  4990.7      .1       0
Bank Sta=4985.7,4990.7
XS Rating Curve= 0 ,0
Exp/Cntr=0.3,0.1

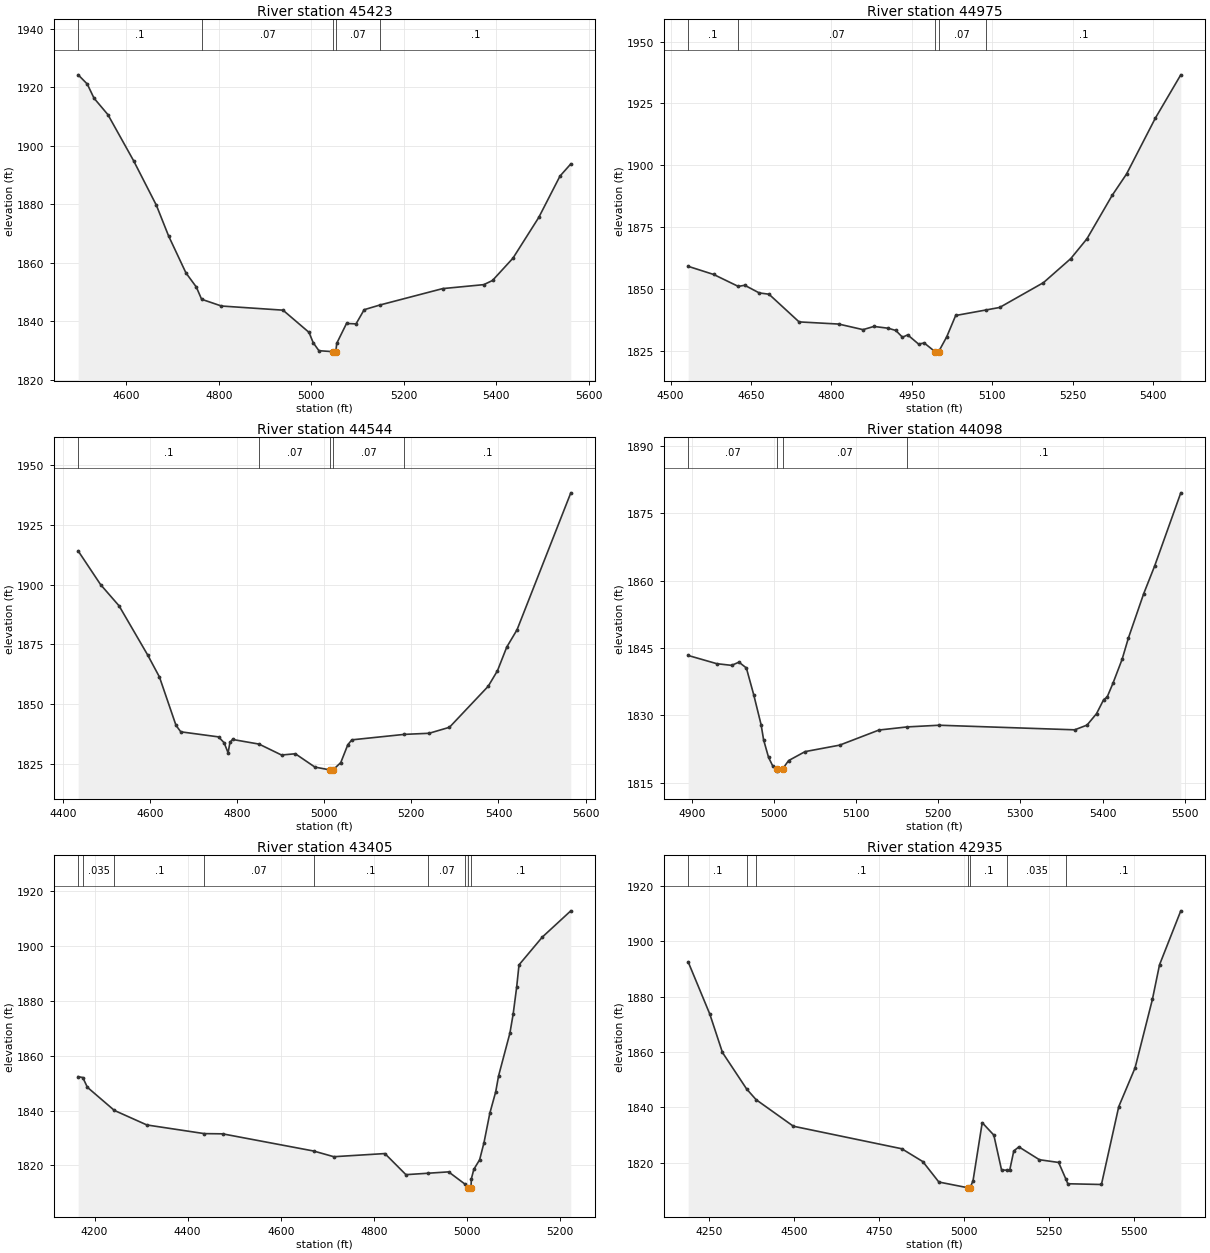
Type RM Length L Ch R = 1 ,45423   ,448,448,448
BEGIN DESCRIPTION:
Town Creek 84.0
END DESCRIPTION:
XS GIS Cut Line= 3
      1925225.02     13960674.99        1924825.       13960975.
      1924425.01     13961374.99
#Sta/Elev= 30
  4495.6  1924.3  4515.2 1921.16  4529.9 1916.31  4559.9 1910.69  4615.5 1894.93
  4664.9 1879.66  4691.2 1869.21  4728.7 1856.58  4751.2 1851.74  4762.6 1847.56
  4805.5 1845.25  4938.7 1843.83  4994.9 1836.25    5004 1832.72  5016.4 1829.97
    5047 1829.64  5047.5 1829.14    5053 1829.64  5054.9 1832.48  5076.1 1839.28
  5096.7 1839.15  5114.3 1843.99    5148 1845.58    5284  1851.2  5373.1 1852.56
  5391.9 1853.98  5436.1  1861.6  5491.9 1875.52  5537.9 1889.68  5561.3 1893.84
#Mann= 5 ,-1 , 0
  4495.6      .1       0  4762.6     .07       0    5047     .05       0
    5053     .07       0    5148      .1       0
Bank Sta=5047,5053
XS Rating Curve= 0 ,0
Exp/Cntr=0.3,0.1

Type RM Length L Ch R = 1 ,44975   ,431,431,431
BEGIN DESCRIPTION:
Town Creek 83.0
END DESCRIPTION:
XS GIS Cut Line= 3
      1924874.99     13960475.01        1924475.       13960725.
        1924075.       13960925.
#Sta/Elev= 30
  4532.7 1859.26  4580.4 1855.96  4626.2 1851.15  4638.2 1851.61  4665.3 1848.52
  4683.5    1848  4739.6 1836.83  4813.6 1835.95  4858.9  1833.7  4879.1 1834.99
  4905.9 1834.27    4920 1833.37  4932.5 1830.63  4942.2 1831.59  4962.5 1827.88
  4973.1 1828.31  4993.7 1824.72  4994.2 1824.22  4999.7 1824.72    5015 1830.79
  5031.7 1839.41  5088.1 1841.63  5113.7 1842.65  5195.5 1852.68  5246.4 1862.37
  5276.6 1870.38  5323.5 1887.86  5350.4 1896.51    5404 1919.01  5451.6 1936.55
#Mann= 5 ,-1 , 0
  4532.7      .1       0  4626.2     .07       0  4993.7     .05       0
  4999.7     .07       0  5088.1      .1       0
Bank Sta=4993.7,4999.7
XS Rating Curve= 0 ,0
Exp/Cntr=0.3,0.1

Type RM Length L Ch R = 1 ,44544   ,446,446,446
BEGIN DESCRIPTION:
Town Creek 82.0
END DESCRIPTION:
XS GIS Cut Line= 3
      1924775.01     13959924.99        1924375.       13960325.
      1923974.99     13960725.01
#Sta/Elev= 30
  4434.8 1914.13  4486.4    1900  4528.8 1891.12  4594.2 1870.62  4621.4 1861.37
  4659.5 1841.07  4670.5 1838.38  4757.1 1836.26  4769.9 1833.83  4779.1 1829.59
  4783.4 1833.93  4789.3 1835.18  4850.2 1833.24  4901.8 1828.67  4933.6 1829.19
  4978.5 1823.61  5013.5 1822.42    5014 1821.92    5020 1822.42  5037.9  1825.5
  5054.1 1832.99  5063.4 1835.02  5183.9 1837.31  5240.8 1837.77  5287.5 1840.28
  5376.5 1857.46  5397.8 1863.98    5419 1873.83  5442.7 1881.11  5566.2 1938.46
#Mann= 5 ,-1 , 0
  4434.8      .1       0  4850.2     .07       0  5013.5     .05       0
    5020     .07       0  5183.9      .1       0
Bank Sta=5013.5,5020
XS Rating Curve= 0 ,0
Exp/Cntr=0.3,0.1

Type RM Length L Ch R = 1 ,44098   ,693,693,693
BEGIN DESCRIPTION:
Town Creek 81.0
END DESCRIPTION:
XS GIS Cut Line= 3
        1924175.       13959875.        1924175.       13959975.
        1923875.       13960375.
#Sta/Elev= 30
  4895.3 1843.33  4930.2  1841.5  4948.2 1841.13  4957.2 1841.84  4966.2 1840.55
  4975.2 1834.57  4984.2 1827.89  4987.2 1824.56  4993.2 1820.68  4998.4 1818.72
  5003.6  1818.1  5004.1  1817.6  5010.3  1818.1  5017.7 1819.95  5037.7 1821.94
  5079.8 1823.38  5127.7 1826.74  5162.3 1827.44  5201.1 1827.81  5366.1 1826.79
  5381.1 1827.84  5392.7 1830.39  5401.4 1833.51  5405.6 1834.07  5412.7 1837.15
  5423.9 1842.51  5431.4 1847.16  5450.2 1857.11  5463.4  1863.2  5495.3 1879.51
#Mann= 4 ,-1 , 0
  4895.3     .07       0  5003.6     .05       0  5010.3     .07       0
  5162.3      .1       0
Bank Sta=5003.6,5010.3
XS Rating Curve= 0 ,0
Exp/Cntr=0.3,0.1

Type RM Length L Ch R = 1 ,43405   ,470,470,470
BEGIN DESCRIPTION:
Town Creek 80.0
END DESCRIPTION:
XS GIS Cut Line= 4
      1924095.37     13959591.63       1923729.8      13959880.3
      1923620.06     13960157.22      1923705.38     13960439.42
#Sta/Elev= 30
  4164.7  1852.4  4174.6 1852.08  4184.5 1848.52  4242.4 1840.08  4312.3 1834.77
  4435.7 1831.61    4475 1831.53  4670.6 1825.26    4714 1823.18  4823.7 1824.33
  4868.9 1816.63  4917.1 1817.16  4960.6 1817.65    4995 1813.28    5002 1811.85
  5002.5 1811.35  5008.7 1811.85  5009.5 1815.09  5014.8 1818.57  5027.3 1822.07
  5036.7 1828.35  5049.2 1839.06  5061.8 1846.84    5068 1852.69  5092.4 1868.33
  5099.4 1875.31  5106.9  1885.1  5111.9  1893.2  5162.1 1903.36  5223.2 1912.92
#Mann= 9 ,-1 , 0
  4164.7      .1       0  4174.6    .035       0  4242.4      .1       0
  4435.7     .07       0  4670.6      .1       0  4917.1     .07       0
    4995      .1       0    5002     .05       0  5008.7      .1       0
Bank Sta=5002,5008.7
XS Rating Curve= 0 ,0
Exp/Cntr=0.3,0.1

Type RM Length L Ch R = 1 ,42935   ,166,166,166
BEGIN DESCRIPTION:
Town Creek 79.0
END DESCRIPTION:
XS GIS Cut Line= 3
      1924204.17     13959509.78      1923534.84     13959853.34
      1922836.94     13959845.58
#Sta/Elev= 30
  4187.8 1892.54  4251.5 1873.71  4288.8 1859.84  4359.9 1846.69  4387.9 1842.81
  4497.6 1833.24  4816.8 1825.11  4878.7 1820.48  4925.9 1813.11  5011.1 1811.05
  5011.6 1810.55  5017.8 1811.05  5026.5 1813.58  5053.5 1834.53  5087.7 1830.04
  5110.5 1817.44  5127.3 1817.39  5134.5 1817.42  5146.5 1824.33  5161.5 1825.79
  5221.8 1821.16  5278.5 1820.17  5300.2 1814.07  5305.5 1812.49  5404.5 1812.22
  5455.5 1840.31  5503.5 1854.29  5554.5 1878.97  5575.5 1891.47  5638.1 1910.94
#Mann= 7 ,-1 , 0
  4187.8      .1       0  4359.9    .035       0  4387.9      .1       0
  5011.1     .05       0  5017.8      .1       0  5127.3    .035       0
  5300.2      .1       0
Bank Sta=5011.1,5017.8
XS Rating Curve= 0 ,0
Exp/Cntr=0.3,0.1

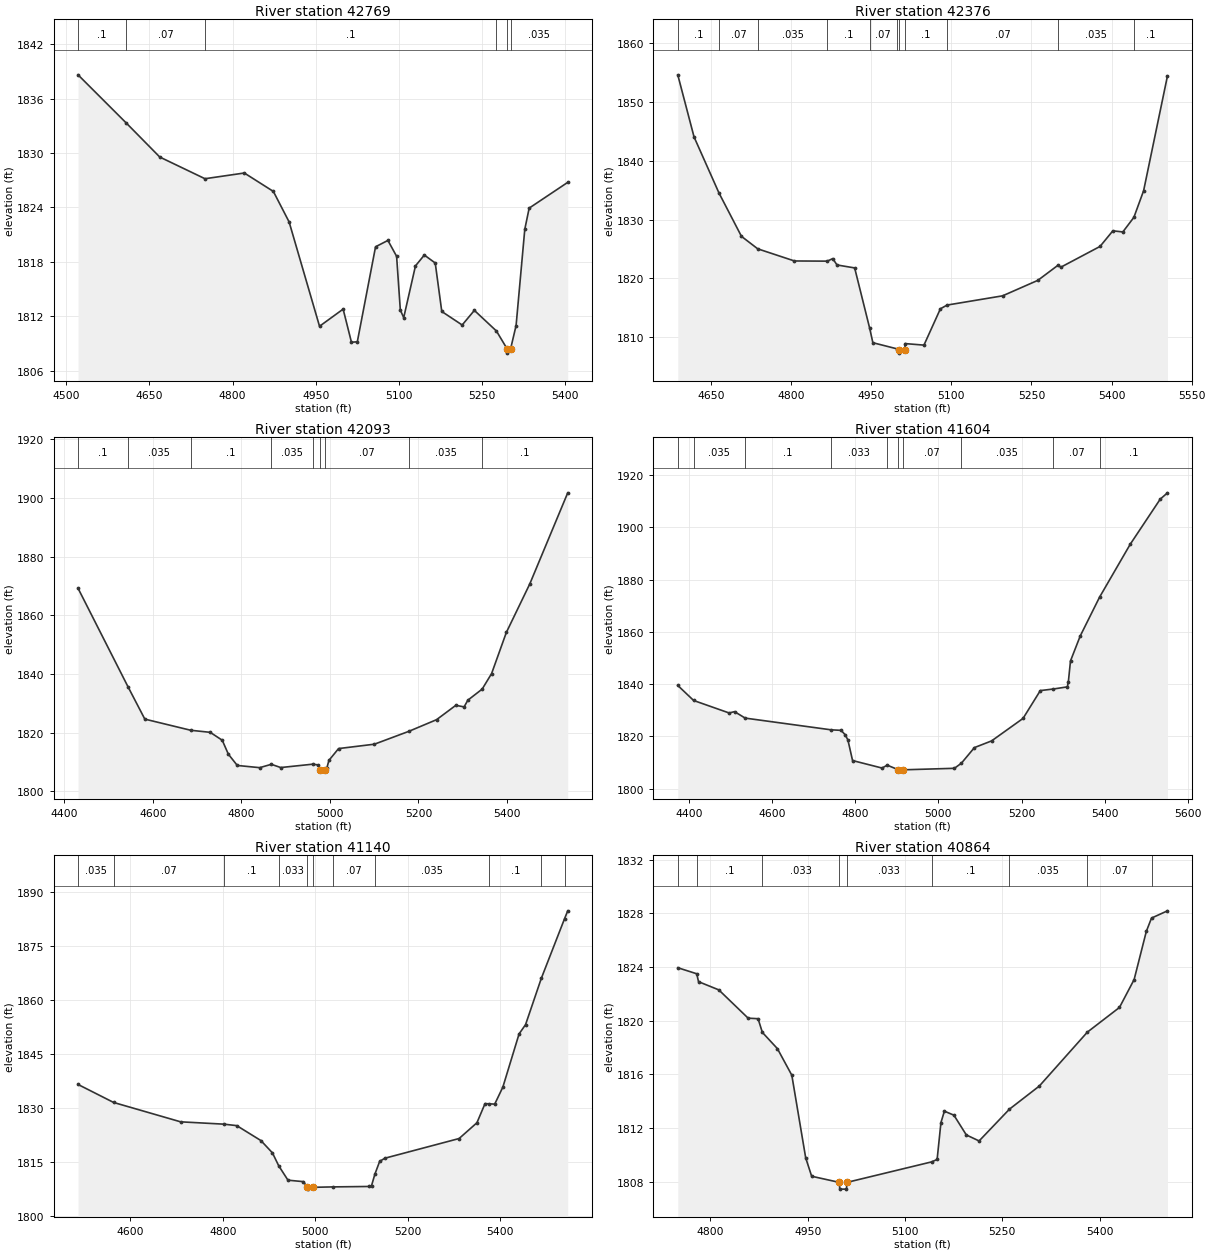
Type RM Length L Ch R = 1 ,42769   ,393,393,393
BEGIN DESCRIPTION:
Town Creek 78.0
END DESCRIPTION:
XS GIS Cut Line= 3
      1923930.85     13959543.15      1923483.63     13959688.35
      1923075.02       13959625.
#Sta/Elev= 30
  4521.1 1838.61  4607.5 1833.34  4668.6 1829.55  4750.2 1827.16  4821.2 1827.79
  4873.6 1825.76    4902  1822.4  4956.9  1810.9  4999.5 1812.79  5014.5 1809.14
  5025.1 1809.19    5058 1819.66  5080.3 1820.36    5096 1818.61  5102.7 1812.69
  5108.8 1811.85    5130 1817.55    5146 1818.75  5165.7 1817.87  5177.5 1812.53
  5214.3 1811.04  5236.3 1812.65  5276.1 1810.38  5295.1 1808.44  5295.6 1807.94
  5301.8 1808.44  5311.6 1810.98  5327.3 1821.59  5335.2 1823.92  5404.8 1826.76
#Mann= 6 ,-1 , 0
  4521.1      .1       0  4607.5     .07       0  4750.2      .1       0
  5276.1    .035       0  5295.1     .05       0  5301.8    .035       0
Bank Sta=5295.1,5301.8
XS Rating Curve= 0 ,0
Exp/Cntr=0.3,0.1

Type RM Length L Ch R = 1 ,42376   ,283,283,283
BEGIN DESCRIPTION:
Mapping XS 91e08b51
END DESCRIPTION:
XS GIS Cut Line= 3
      1923742.28     13959127.95      1923285.86     13959377.15
      1922978.97     13959629.28
#Sta/Elev= 30
  4587.5 1854.58    4618 1844.03  4664.7 1834.51  4706.8 1827.15  4737.3 1825.03
    4806 1822.97  4867.5 1822.94  4877.7 1823.37  4885.8 1822.29  4918.8 1821.79
  4946.9 1811.56  4952.9 1809.09    4998 1808.05  5002.1 1807.82  5002.6 1807.32
  5013.1 1807.82  5013.2 1808.94  5048.6 1808.68  5079.4 1814.85  5091.9 1815.48
  5195.9 1817.05  5261.9 1819.68  5300.2 1822.28  5304.7  1821.9  5378.4 1825.44
  5402.4 1828.09  5421.1  1827.9  5441.8 1830.38    5460  1834.9  5504.7 1854.41
#Mann= 11 ,-1 , 0
  4587.5      .1       0  4664.7     .07       0  4737.3    .035       0
  4867.5      .1       0  4946.9     .07       0    4998      .1       0
  5002.1     .05       0  5013.1      .1       0  5091.9     .07       0
  5300.2    .035       0  5441.8      .1       0
Bank Sta=5002.1,5013.1
XS Rating Curve= 0 ,0
Exp/Cntr=0.3,0.1

Type RM Length L Ch R = 1 ,42093   ,489,489,489
BEGIN DESCRIPTION:
Town Creek 77.0
END DESCRIPTION:
XS GIS Cut Line= 3
      1923625.04     13958874.97      1923186.72     13959236.04
      1922874.98     13959675.03
#Sta/Elev= 30
    4431  1869.2  4543.7 1835.71  4581.9 1824.64  4685.7 1820.84  4729.6 1820.14
  4756.8 1817.45  4770.6  1812.7  4790.8 1808.86  4841.4 1808.11  4867.7 1809.25
    4889 1808.15  4960.9 1809.29  4974.1 1809.04  4977.5 1807.43    4978 1806.93
  4988.5 1807.43  4993.2 1808.05  4997.8 1810.59  5019.6 1814.61  5100.5  1816.1
  5178.5 1820.49    5241 1824.45  5284.5 1829.34  5303.2  1828.8  5311.6 1831.08
    5344 1834.86  5365.3 1840.15  5398.6 1854.15  5451.5 1870.65  5537.3 1901.69
#Mann= 9 ,-1 , 0
    4431      .1       0  4543.7    .035       0  4685.7      .1       0
  4867.7    .035       0  4960.9     .07       0  4977.5     .05       0
  4988.5     .07       0  5178.5    .035       0    5344      .1       0
Bank Sta=4977.5,4988.5
XS Rating Curve= 0 ,0
Exp/Cntr=0.3,0.1

Type RM Length L Ch R = 1 ,41604   ,464,464,464
BEGIN DESCRIPTION:
Town Creek 76.0
END DESCRIPTION:
XS GIS Cut Line= 3
      1923501.35      13958721.7      1922962.63     13958961.83
        1922675.       13959475.
#Sta/Elev= 30
    4373 1839.51  4411.1 1833.76  4496.5 1828.98  4509.6 1829.48  4535.2 1827.01
  4742.1 1822.52  4765.8 1822.33  4775.7 1820.66  4782.3 1818.65  4793.5 1810.77
  4864.4  1807.9  4876.9    1809    4904 1807.22  4904.5 1806.72    4915 1807.22
  5038.6  1807.8  5055.3 1809.75  5086.7 1815.73    5128 1818.29  5203.6 1826.89
  5245.2 1837.54  5276.8 1838.15  5310.3 1838.97  5312.7 1841.01  5317.8  1848.9
  5341.2 1858.44  5387.6 1873.26  5461.6 1893.57  5533.6 1910.79  5551.1 1913.22
#Mann= 10 ,-1 , 0
    4373      .1       0  4411.1    .035       0  4535.2      .1       0
  4742.1    .033       0  4876.9     .07       0    4904     .05       0
    4915     .07       0  5055.3    .035       0  5276.8     .07       0
  5387.6      .1       0
Bank Sta=4904,4915
XS Rating Curve= 0 ,0
Exp/Cntr=0.3,0.1

Type RM Length L Ch R = 1 ,41140   ,276,276,276
BEGIN DESCRIPTION:
Town Creek 75.0
END DESCRIPTION:
XS GIS Cut Line= 3
      1923078.32     13958355.47       1922738.7     13958657.27
        1922425.       13959175.
#Sta/Elev= 30
  4486.7 1836.53  4563.7 1831.52  4708.7 1826.13  4802.5 1825.48  4830.2 1825.07
  4882.4 1820.92  4907.4 1817.49    4921 1813.89    4941 1809.89  4974.5 1809.48
  4982.9  1807.9  4983.4  1807.4  4994.3  1807.9  5038.3 1808.02    5117 1808.14
  5121.9 1808.39  5129.1 1811.57  5139.4 1815.12  5150.6    1816  5311.3 1821.48
  5349.9 1825.87  5367.4 1831.19  5376.5 1831.14  5388.4 1831.06    5406 1835.79
  5441.1  1850.6  5455.1 1853.17  5489.3 1866.09  5539.6 1882.69  5546.4 1884.85
#Mann= 11 ,-1 , 0
  4486.7    .035       0  4563.7     .07       0  4802.5      .1       0
    4921    .033       0  4982.9    .033       0  4994.3    .033       0
  5038.3     .07       0  5129.1    .035       0  5376.5      .1       0
  5489.3     .07       0  5539.6      .1       0
Bank Sta=4982.9,4994.3
XS Rating Curve= 0 ,0
Exp/Cntr=0.3,0.1

Type RM Length L Ch R = 1 ,40864   ,625,625,625
BEGIN DESCRIPTION:
Town Creek 74.0
END DESCRIPTION:
XS GIS Cut Line= 3
      1922774.95     13958475.01        1922525.       13958525.
        1922225.       13958925.
#Sta/Elev= 30
  4749.8 1823.95    4779  1823.5  4781.8 1822.91    4813  1822.3  4858.3 1820.19
  4873.6 1820.15  4880.2 1819.13  4903.4 1817.92  4925.6 1815.94    4947 1809.78
  4956.2 1808.41    4999 1807.95  4999.5 1807.45  5009.9 1807.45  5010.4 1807.95
  5141.1 1809.48  5149.6 1809.66  5155.5 1812.41  5160.8 1813.26  5175.5 1812.96
  5194.6 1811.49  5214.3 1811.04  5261.1 1813.41  5307.1 1815.13  5381.2 1819.15
  5430.7 1820.99  5453.3 1823.07  5472.1 1826.66  5480.1 1827.65  5504.7 1828.19
#Mann= 9 ,-1 , 0
  4749.8     .07       0    4779      .1       0  4880.2    .033       0
    4999    .033       0  5010.4    .033       0  5141.1      .1       0
  5261.1    .035       0  5381.2     .07       0  5480.1    .035       0
Bank Sta=4999,5010.4
XS Rating Curve= 0 ,0
Exp/Cntr=0.3,0.1

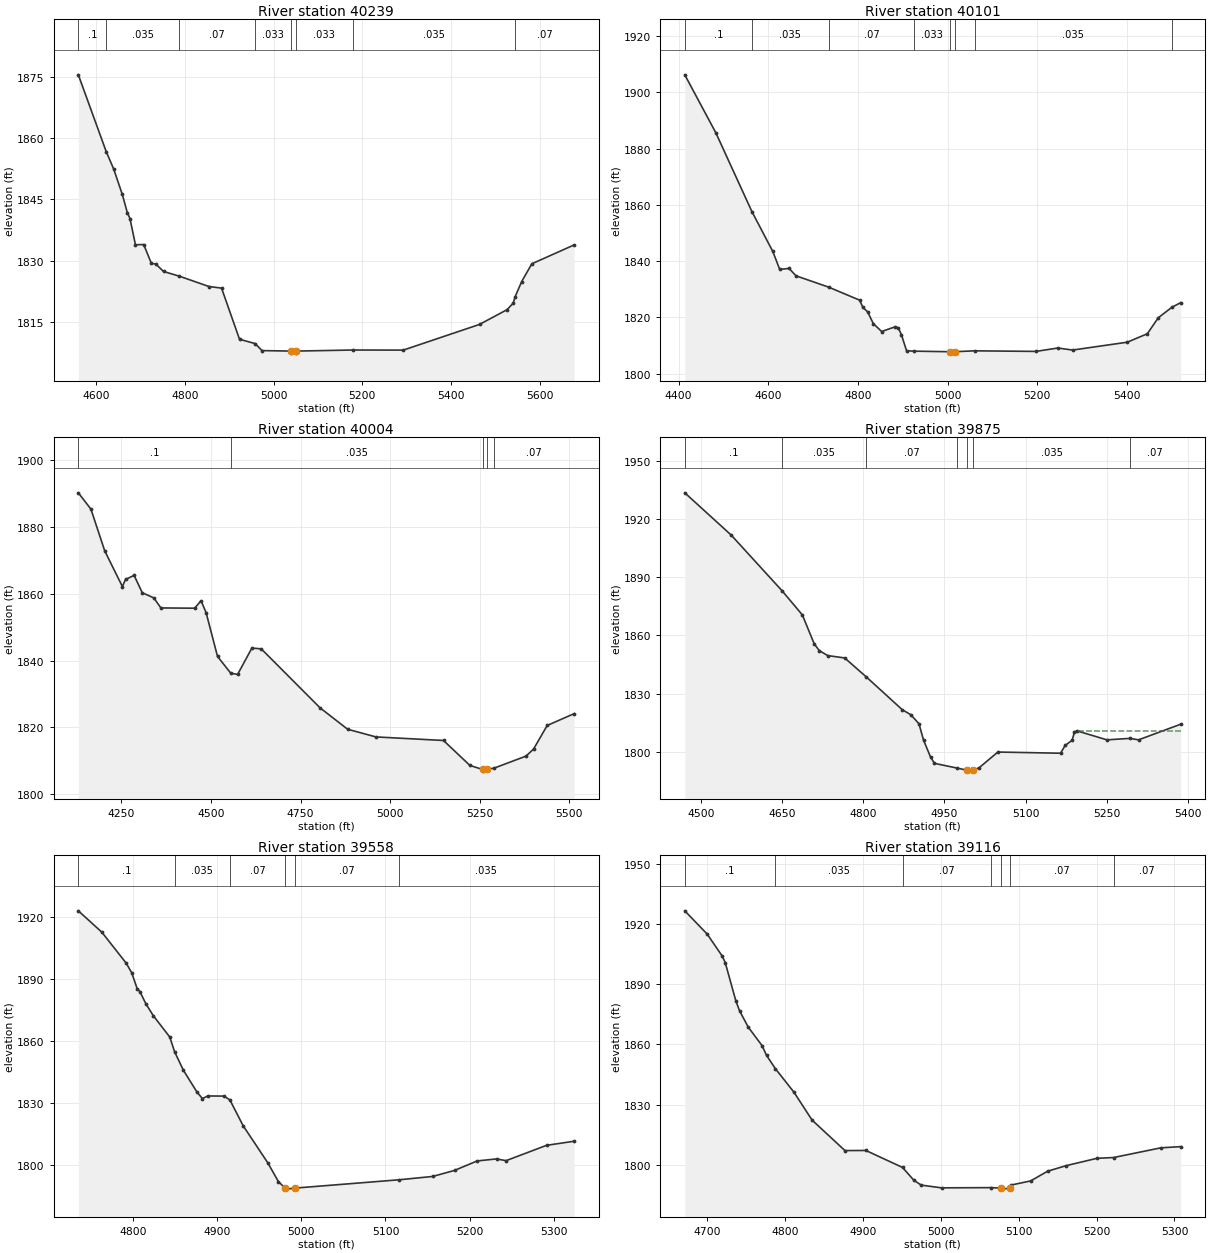
Type RM Length L Ch R = 1 ,40239   ,138,138,138
BEGIN DESCRIPTION:
Town Creek 73.0
END DESCRIPTION:
XS GIS Cut Line= 3
      1922725.01     13957974.99       1922346.5     13958187.15
      1921925.03     13958724.96
#Sta/Elev= 30
  4560.2  1875.5  4623.1 1856.68  4639.8 1852.45  4659.3 1846.21  4670.5 1841.78
  4676.5 1840.32  4688.9 1833.89  4707.5 1833.95  4724.7 1829.36    4735 1829.15
  4752.2 1827.35  4788.1 1826.19  4854.5 1823.67  4882.9 1823.28  4923.4 1810.75
  4958.3 1809.71  4974.1 1807.98  5038.8 1807.86  5039.3 1807.36    5050 1807.36
  5050.5 1807.86  5178.6 1808.12  5292.4  1808.1  5464.2 1814.39    5526 1817.99
  5540.1 1819.59  5544.4 1821.16  5559.2 1824.89    5582 1829.23  5677.4 1833.86
#Mann= 8 ,-1 , 0
  4560.2      .1       0  4623.1    .035       0  4788.1     .07       0
  4958.3    .033       0  5038.8    .033       0  5050.5    .033       0
  5178.6    .035       0  5544.4     .07       0
Bank Sta=5038.8,5050.5
XS Rating Curve= 0 ,0
Exp/Cntr=0.3,0.1

Type RM Length L Ch R = 1 ,40101   ,97,97,97
BEGIN DESCRIPTION:
Town Creek 72.0
END DESCRIPTION:
XS GIS Cut Line= 3
      1922721.96     13957890.27      1922196.85     13958182.49
        1921825.       13958525.
#Sta/Elev= 30
  4413.7 1906.25  4482.9 1885.65  4563.5  1857.6  4610.1 1843.42  4625.5 1837.06
  4646.5 1837.39  4661.8 1834.77  4734.4 1830.76  4803.7 1826.12  4811.3  1823.5
  4821.6 1821.99  4834.5 1817.74    4853 1814.96  4883.6 1816.66  4890.1 1816.25
  4897.1 1813.84  4908.6  1808.1  4926.3 1807.97  5004.6 1807.77  5005.1 1807.27
  5016.3 1807.77  5060.3 1808.09  5197.2 1807.88  5246.2 1809.09  5279.1 1808.36
  5401.2 1811.16    5446 1814.17  5470.2 1819.83  5500.8 1823.59  5520.2 1825.21
#Mann= 8 ,-1 , 0
  4413.7      .1       0  4563.5    .035       0  4734.4     .07       0
  4926.3    .033       0  5004.6    .033       0  5016.3    .033       0
  5060.3    .035       0  5500.8     .07       0
Bank Sta=5004.6,5016.3
XS Rating Curve= 0 ,0
Exp/Cntr=0.3,0.1

Type RM Length L Ch R = 1 ,40004   ,129,129,129
BEGIN DESCRIPTION:
Town Creek 72.1
END DESCRIPTION:
XS GIS Cut Line= 5
      1922791.01     13957569.54      1922328.78     13957973.18
      1922148.66     13958114.24       1922072.7     13958179.34
       1921760.2     13958489.68
#Sta/Elev= 30
  4130.3 1890.29  4165.4 1885.41  4203.8 1872.92  4253.1 1862.19    4262 1864.33
  4285.9 1865.53  4308.7 1860.32  4340.7 1858.79  4360.6 1855.77  4454.7 1855.69
  4472.5 1857.94  4486.6 1854.38  4518.5 1841.23  4555.5 1836.19  4574.6 1835.84
  4614.3 1843.73  4640.5  1843.5  4804.5 1825.81  4881.4 1819.39  4960.2 1817.09
  5148.8 1816.02  5222.4 1808.54  5257.9 1807.33  5258.4 1806.83  5269.6 1807.33
  5290.2 1807.74  5378.8 1811.33    5400 1813.45    5438 1820.52  5513.2 1824.07
#Mann= 5 ,-1 , 0
  4130.3      .1       0  4555.5    .035       0  5257.9    .035       0
  5269.6    .035       0  5290.2     .07       0
Bank Sta=5257.9,5269.6
XS Rating Curve= 0 ,0
Exp/Cntr=0.3,0.1

Type RM Length L Ch R = 1 ,39875   ,317,317,317
BEGIN DESCRIPTION:
Town Creek 71.1
END DESCRIPTION:
XS GIS Cut Line= 3
      1922244.95     13957568.84      1922125.04     13957974.05
      1921773.07     13958319.14
#Sta/Elev= 30
  4470.6 1933.62  4556.2 1911.84  4650.3 1883.04  4687.6 1870.65  4709.5 1855.74
  4718.9  1852.2  4734.5 1849.63  4765.8 1848.42  4805.7 1838.63  4872.2 1821.69
  4887.8 1819.14    4903 1814.46  4911.5 1805.92  4924.4 1797.27  4931.6 1794.02
  4973.9 1791.55  4991.5 1790.51    4992 1790.01  5003.2 1790.51  5014.3 1791.82
  5048.7 1799.86  5164.4 1799.25  5172.9 1803.27  5185.8 1805.97  5190.1 1810.23
  5194.4 1810.81  5250.1 1806.15  5292.4 1806.91  5308.4 1806.15  5386.1 1814.21
#Mann= 7 ,-1 , 0
  4470.6      .1       0  4650.3    .035       0  4805.7     .07       0
  4973.9    .035       0  4991.5    .035       0  5003.2    .035       0
  5292.4     .07       0
#XS Ineff= 2 , 0
                          5196.2         1810.66
Permanent Ineff=
       F       F
Bank Sta=4991.5,5003.2
XS Rating Curve= 0 ,0
Exp/Cntr=0.3,0.1

Type RM Length L Ch R = 1 ,39558   ,442,442,442
BEGIN DESCRIPTION:
Town Creek 71.0
END DESCRIPTION:
XS GIS Cut Line= 3
      1921925.01     13957624.98        1921825.       13957875.
      1921625.02     13958124.97
#Sta/Elev= 30
  4734.9 1922.96  4762.8 1912.63  4791.9 1897.55  4798.4 1892.88  4804.8  1885.3
  4808.1 1883.81  4815.2 1877.89  4824.2 1872.04  4843.6 1861.79  4849.3 1854.69
  4859.8 1845.68  4875.9 1835.13  4882.4 1831.94  4888.8 1833.23  4908.2 1833.16
  4915.1 1831.28  4930.8  1818.8  4959.9 1800.96  4972.8 1791.69  4980.7 1788.57
  4981.2 1788.07  4992.4 1788.57  5115.7 1792.58    5156 1794.21  5182.1 1797.14
    5209 1801.73    5232 1802.71  5243.4 1801.87  5291.5  1809.3  5324.3 1811.29
#Mann= 6 ,-1 , 0
  4734.9      .1       0  4849.3    .035       0  4915.1     .07       0
  4980.7     .05       0  4992.4     .07       0  5115.7    .035       0
Bank Sta=4980.7,4992.4
XS Rating Curve= 0 ,0
Exp/Cntr=0.3,0.1

Type RM Length L Ch R = 1 ,39116   ,436,436,436
BEGIN DESCRIPTION:
Town Creek 70.0
END DESCRIPTION:
XS GIS Cut Line= 3
      1921725.03     13957474.98        1921475.       13957675.
      1921375.04     13957974.88
#Sta/Elev= 30
  4671.6 1926.65  4700.4 1915.01  4719.6  1904.1  4723.5 1900.82  4737.1 1881.75
  4741.9 1876.77    4753 1868.64  4770.7 1859.44  4776.5 1854.55  4787.8 1847.93
  4811.8 1836.12  4834.9 1822.28  4877.1 1807.05    4904  1807.1    4951 1798.64
  4965.5 1792.27    4975 1789.82  5001.2 1788.46    5065 1788.57  5077.5 1788.32
    5078 1787.82  5089.4 1788.32  5089.7  1789.8  5115.4 1791.91  5137.2 1796.75
  5160.5 1799.48  5200.4 1803.18    5222 1803.59  5282.6 1808.43  5307.9 1809.01
#Mann= 7 ,-1 , 0
  4671.6      .1       0  4787.8    .035       0    4951     .07       0
    5065     .07       0  5077.5     .05       0  5089.4     .07       0
    5222     .07       0
Bank Sta=5077.5,5089.4
XS Rating Curve= 0 ,0
Exp/Cntr=0.3,0.1

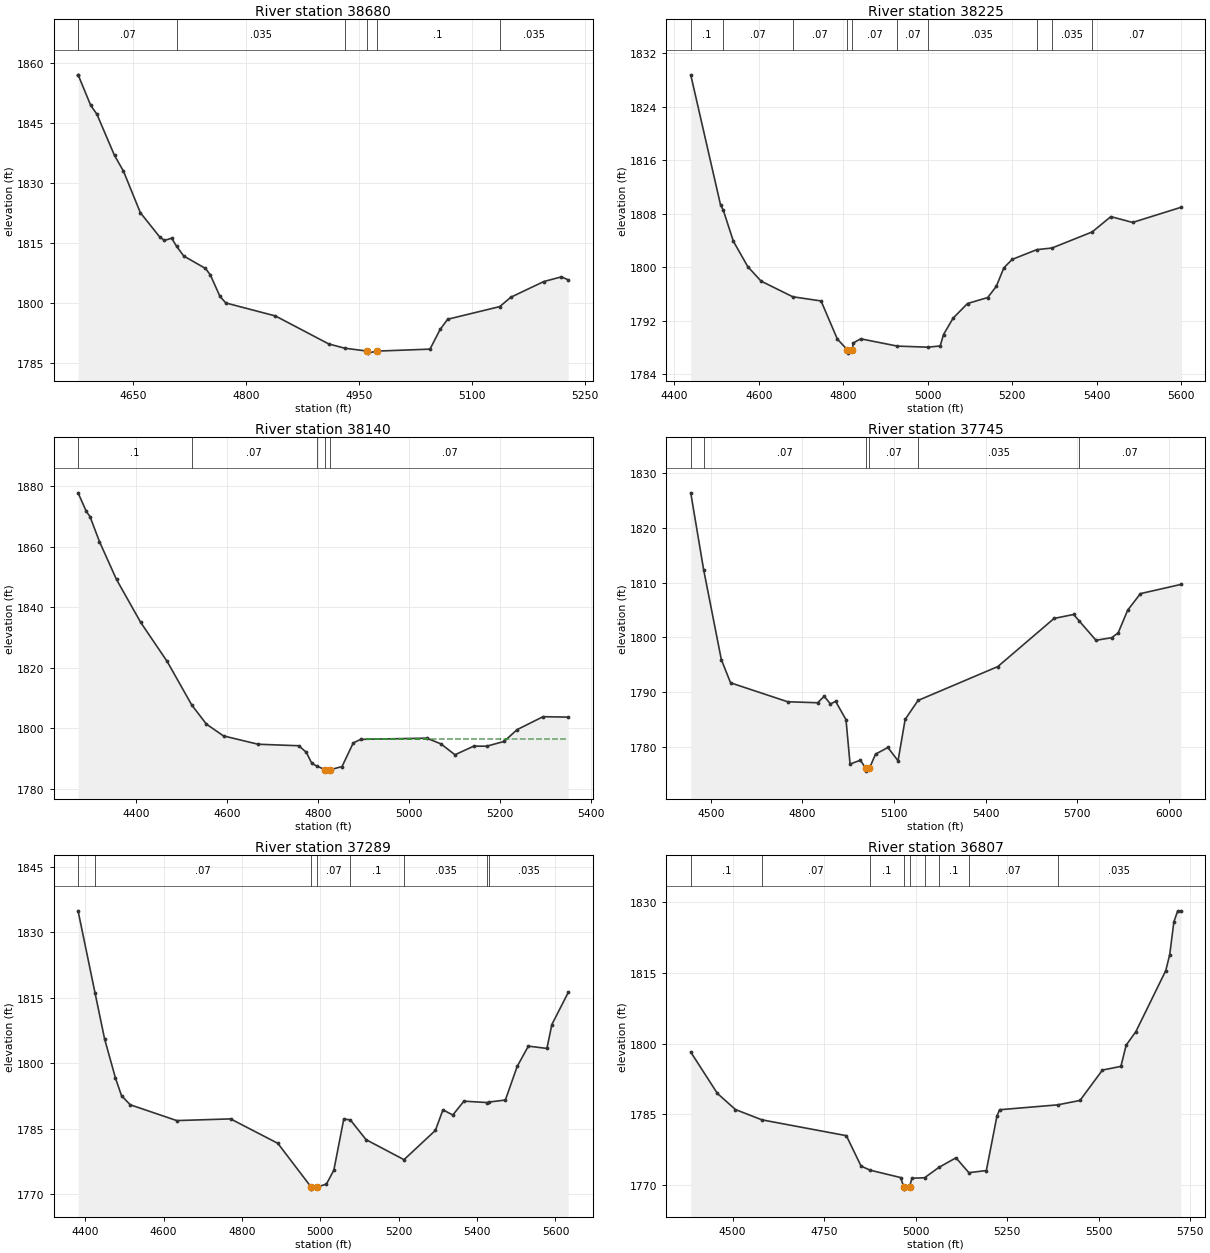
Type RM Length L Ch R = 1 ,38680   ,455,455,455
BEGIN DESCRIPTION:
Town Creek 69.0
END DESCRIPTION:
XS GIS Cut Line= 3
      1921524.97     13957375.01        1921125.       13957525.
      1921024.99     13957725.02
#Sta/Elev= 30
    4577 1857.15  4577.4 1857.01  4593.8 1849.52    4602 1847.32  4625.4    1837
  4637.3 1833.08  4659.7  1822.7  4685.3 1816.66  4691.7 1815.76  4701.3 1816.32
  4707.9 1814.26  4717.4 1811.86  4746.2 1808.75  4752.6 1807.16  4765.4 1801.77
  4773.2 1800.13  4839.1 1796.88  4909.9 1789.88  4931.2 1788.82  4961.3 1788.09
  4961.8 1787.59  4973.3 1788.09  5044.3 1788.59  5057.7 1793.51  5067.8 1796.06
  5136.9 1799.22  5151.6 1801.56  5195.2 1805.47  5218.7 1806.65  5227.8 1805.91
#Mann= 7 ,-1 , 0
    4577      .1       0  4577.4     .07       0  4707.9    .035       0
  4931.2      .1       0  4961.3     .05       0  4973.3      .1       0
  5136.9    .035       0
Bank Sta=4961.3,4973.3
XS Rating Curve= 0 ,0
Exp/Cntr=0.3,0.1

Type RM Length L Ch R = 1 ,38225   ,85,85,85
BEGIN DESCRIPTION:
Town Creek 68.0
END DESCRIPTION:
XS GIS Cut Line= 4
      1921224.99     13956875.01        1920825.       13957275.
       1920702.5     13957502.81      1920739.88      13957836.8
#Sta/Elev= 30
  4439.1 1828.74  4509.7 1809.28  4516.3 1808.47  4540.1 1803.85  4574.1 1800.07
  4605.5  1797.9  4680.5 1795.56  4747.6 1794.93  4786.2 1789.23  4809.9 1787.63
  4810.4 1787.13  4821.9 1787.63  4823.6 1788.64  4841.4 1789.27  4928.3 1788.18
  5000.4 1788.02  5029.6  1788.2  5037.5 1789.91  5060.3 1792.37  5094.4 1794.55
  5142.1 1795.44  5162.5 1797.11  5180.3 1799.88    5200 1801.14  5258.2  1802.6
  5294.4 1802.85  5389.5 1805.25  5433.6 1807.54  5485.3 1806.67  5599.5 1808.93
#Mann= 10 ,-1 , 0
  4439.1      .1       0  4516.3     .07       0  4680.5     .07       0
  4809.9     .05       0  4821.9     .07       0  4928.3     .07       0
  5000.4    .035       0  5258.2     .07       0  5294.4    .035       0
  5389.5     .07       0
Bank Sta=4809.9,4821.9
XS Rating Curve= 0 ,0
Exp/Cntr=0.3,0.1

Type RM Length L Ch R = 1 ,38140   ,395,395,395
BEGIN DESCRIPTION:
Town Creek 68.1
END DESCRIPTION:
XS GIS Cut Line= 4
      1921325.69     13956698.79      1920879.69     13957119.83
      1920746.23     13957241.36      1920656.15     13957508.33
#Sta/Elev= 30
  4273.5 1877.79  4291.6 1871.67  4299.8 1869.92  4320.5 1861.66  4357.9 1849.15
  4410.9 1834.98    4469 1822.07    4523 1807.67  4555.2 1801.34  4592.7 1797.45
  4668.4  1794.7  4757.8  1794.2  4774.3 1792.05  4786.4  1788.4  4797.2  1787.5
  4815.4 1786.31  4815.9 1785.81  4827.4 1786.31  4852.7 1787.31  4877.4 1795.14
  4893.8 1796.31  5038.5 1796.71  5069.5 1794.84  5100.6 1791.22  5141.8 1794.07
  5170.3 1794.05  5208.3 1795.62  5236.8 1799.51  5293.8  1803.8  5349.1 1803.66
#Mann= 5 ,-1 , 0
  4273.5      .1       0    4523     .07       0  4797.2     .07       0
  4815.4     .05       0  4827.4     .07       0
#XS Ineff= 2 , 0
                          4904.9         1796.57
Permanent Ineff=
       F       F
Bank Sta=4815.4,4827.4
XS Rating Curve= 0 ,0
Exp/Cntr=0.3,0.1

Type RM Length L Ch R = 1 ,37745   ,456,456,456
BEGIN DESCRIPTION:
Town Creek 67.0
END DESCRIPTION:
XS GIS Cut Line= 4
      1921075.01     13956474.99        1920675.       13956875.
      1920548.65      13957051.2      1920683.41     13957862.57
#Sta/Elev= 30
  4434.3  1826.4  4476.5 1812.38  4534.5 1795.94  4564.7  1791.7  4751.7 1788.24
    4850 1788.06  4871.2 1789.24  4891.8 1787.84  4908.7 1788.31  4942.7 1784.97
    4956 1776.86    4990 1777.57  5007.4 1776.07  5007.9 1775.57  5019.4 1776.07
  5039.3 1778.67  5079.9 1779.89  5113.1 1777.46  5136.4 1785.02  5178.6 1788.48
  5439.9 1794.67    5624 1803.46  5687.9 1804.18  5705.4 1803.06  5761.2 1799.47
  5812.8 1799.94  5833.9 1800.82    5865 1804.97  5906.8 1807.99  6039.3 1809.67
#Mann= 6 ,-1 , 0
  4434.3      .1       0  4476.5     .07       0  5007.4     .05       0
  5019.4     .07       0  5178.6    .035       0  5705.4     .07       0
Bank Sta=5007.4,5019.4
XS Rating Curve= 0 ,0
Exp/Cntr=0.3,0.1

Type RM Length L Ch R = 1 ,37289   ,482,482,482
BEGIN DESCRIPTION:
Town Creek 66.0
END DESCRIPTION:
XS GIS Cut Line= 3
      1921075.04     13956374.99        1920475.       13956525.
      1919874.97     13956725.01
#Sta/Elev= 30
  4381.5 1834.97  4424.8 1816.15  4449.2 1805.59    4477 1796.59  4492.4 1792.55
  4514.7 1790.46  4633.4 1786.83  4770.8 1787.22  4891.4 1781.61  4976.2  1771.6
  4976.7  1771.1  4992.1  1771.6  5015.4 1772.26  5034.4 1775.47  5059.7  1787.2
  5076.5 1786.98  5116.6 1782.45  5213.4 1777.86  5293.6 1784.59  5312.7  1789.3
  5337.9 1788.11  5366.4 1791.29  5425.9 1790.97    5431 1791.09  5472.1 1791.55
  5502.2 1799.25  5530.7 1803.92  5578.1 1803.39  5590.8 1808.88  5632.5 1816.24
#Mann= 8 ,-1 , 0
  4381.5      .1       0  4424.8     .07       0  4976.2     .05       0
  4992.1     .07       0  5076.5      .1       0  5213.4    .035       0
  5425.9     .07       0    5431    .035       0
Bank Sta=4976.2,4992.1
XS Rating Curve= 0 ,0
Exp/Cntr=0.3,0.1

Type RM Length L Ch R = 1 ,36807   ,515,515,515
BEGIN DESCRIPTION:
Town Creek 65.0
END DESCRIPTION:
XS GIS Cut Line= 3
      1920974.99       13955925.        1920375.       13956075.
      1919774.97     13956475.02
#Sta/Elev= 30
  4385.4 1798.22  4458.2 1789.46  4507.6 1786.04    4580 1783.86  4810.7 1780.51
  4850.9 1774.07  4875.8  1773.2  4959.1 1771.64  4967.4 1769.69  4967.9 1769.19
  4983.3 1769.69    4990  1771.5  5024.5  1771.6  5063.9 1773.81  5110.3 1775.82
  5145.6 1772.67  5193.3 1773.13  5222.1  1784.6  5229.3    1786  5387.8 1787.03
  5449.2 1787.97  5510.5  1794.4    5561 1795.18  5575.4 1799.68    5602 1802.55
  5683.6 1815.46  5694.4 1818.83  5705.8 1825.79  5716.1 1828.07    5725 1828.12
#Mann= 9 ,-1 , 0
  4385.4      .1       0    4580     .07       0  4875.8      .1       0
  4967.4     .05       0  4983.3      .1       0  5024.5     .07       0
  5063.9      .1       0  5145.6     .07       0  5387.8    .035       0
Bank Sta=4967.4,4983.3
XS Rating Curve= 0 ,0
Exp/Cntr=0.3,0.1