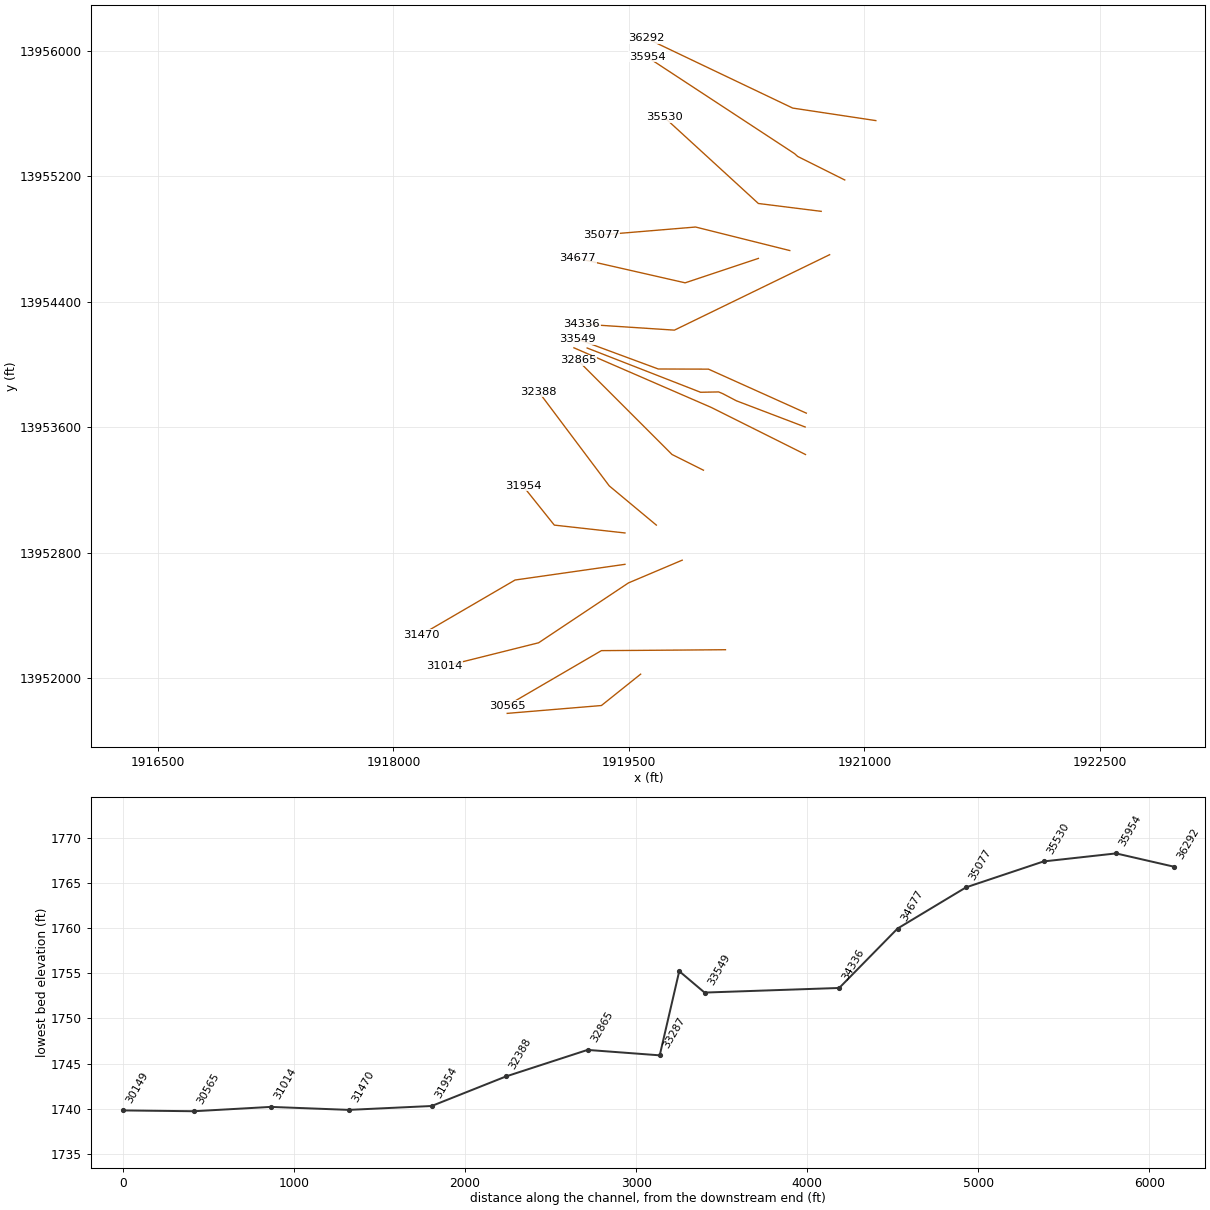
HEC-RAS study Town Creek.prj: Town Creek Base Level Engineering

--- Town Creek.g01 (geometry) --- (continued)

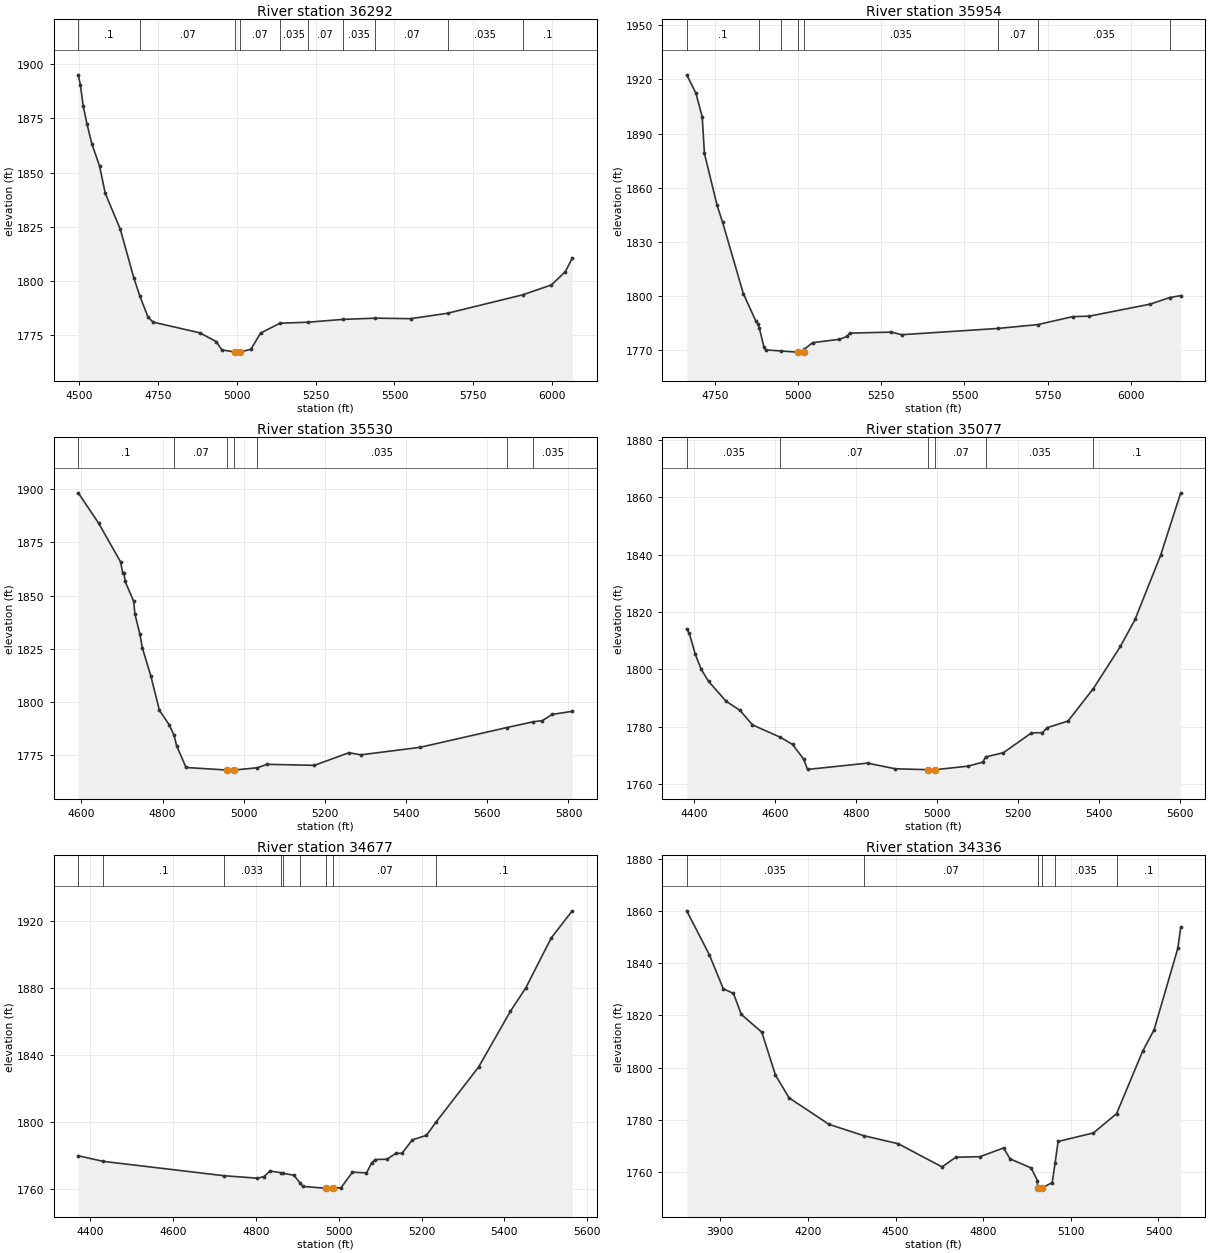
Type RM Length L Ch R = 1 ,36292   ,338,338,338
BEGIN DESCRIPTION:
Mapping XS 7d0163ca
END DESCRIPTION:
XS GIS Cut Line= 3
      1921073.12     13955553.35      1920543.79     13955633.13
      1919611.91     13956077.69
#Sta/Elev= 30
  4496.3 1895.03  4503.1 1890.39  4512.2 1880.59  4524.3 1872.25  4539.5 1863.21
  4563.8  1853.1    4582 1840.46  4629.9 1823.84    4673 1801.35    4692 1793.04
  4717.9 1783.39  4733.7  1781.1  4882.3 1776.16  4933.9 1772.16  4952.1 1768.31
  4993.4 1767.31  4993.9 1766.81  5009.4 1767.31  5044.2 1768.59  5075.1 1776.08
  5136.5 1780.58  5224.9 1781.06  5335.5 1782.34    5439 1782.92  5551.5 1782.69
  5668.3 1785.18  5907.1 1793.68  5998.2 1798.24  6042.1 1804.34  6064.1 1810.56
#Mann= 10 ,-1 , 0
  4496.3      .1       0    4692     .07       0  4993.4     .05       0
  5009.4     .07       0  5136.5    .035       0  5224.9     .07       0
  5335.5    .035       0    5439     .07       0  5668.3    .035       0
  5907.1      .1       0
Bank Sta=4993.4,5009.4
XS Rating Curve= 0 ,0
Exp/Cntr=0.3,0.1

Type RM Length L Ch R = 1 ,35954   ,424,424,424
BEGIN DESCRIPTION:
Town Creek 64.0
END DESCRIPTION:
XS GIS Cut Line= 4
      1920874.99     13955175.01        1920575.       13955325.
      1920555.99     13955342.43       1919615.7     13955959.55
#Sta/Elev= 30
  4664.6 1922.59  4692.1 1912.52  4711.2 1899.33  4717.9 1879.02  4755.8 1850.32
  4772.6 1840.78  4834.8 1801.34  4872.2 1786.17  4879.9 1784.38    4883 1782.21
  4896.7 1771.79  4901.9 1770.08    4949 1769.45  5000.6 1768.78  5001.1 1768.28
  5016.6 1768.78  5017.5  1770.3  5043.2 1774.09  5123.3 1775.92  5147.3 1777.54
  5154.5 1779.36  5280.1 1779.94  5310.9 1778.49  5600.3 1781.96  5720.7  1784.1
  5825.5 1788.52  5875.7 1788.79  6058.7 1795.44  6117.5  1799.1  6150.5 1800.17
#Mann= 8 ,-1 , 0
  4664.6      .1       0    4883     .07       0    4949    .035       0
  5000.6    .035       0  5016.6    .035       0  5600.3     .07       0
  5720.7    .035       0  6117.5      .1       0
Bank Sta=5000.6,5016.6
XS Rating Curve= 0 ,0
Exp/Cntr=0.3,0.1

Type RM Length L Ch R = 1 ,35530   ,453,453,453
BEGIN DESCRIPTION:
Town Creek 63.0
END DESCRIPTION:
XS GIS Cut Line= 3
      1920724.98       13954975.        1920325.       13955025.
      1919725.03     13955574.98
#Sta/Elev= 30
  4592.3 1898.37  4642.7 1884.04  4696.6 1865.85  4701.7 1860.85  4704.9 1860.77
  4707.8 1856.65  4728.8 1847.37  4731.9  1841.4    4744 1831.92  4750.1 1825.51
  4771.3 1812.06  4792.4 1795.96  4816.6 1789.14  4828.1 1784.34  4834.7 1779.36
  4857.8 1769.11  4959.8 1767.89  4960.3 1767.39  4975.8 1767.89  5033.9 1768.99
  5057.3 1770.59  5173.9 1770.12  5259.4 1776.06  5288.2 1775.05  5434.4  1778.6
  5648.7 1787.92  5713.4 1790.63  5735.5 1791.15  5759.9 1794.09  5809.3 1795.54
#Mann= 7 ,-1 , 0
  4592.3      .1       0  4828.1     .07       0  4959.8     .05       0
  4975.8     .07       0  5033.9    .035       0  5648.7    .063       0
  5713.4    .035       0
Bank Sta=4959.8,4975.8
XS Rating Curve= 0 ,0
Exp/Cntr=0.3,0.1

Type RM Length L Ch R = 1 ,35077   ,400,400,400
BEGIN DESCRIPTION:
Town Creek 62.0
END DESCRIPTION:
XS GIS Cut Line= 3
      1920525.01       13954725.        1919925.       13954875.
      1919324.95       13954825.
#Sta/Elev= 30
  4381.5  1814.1    4388 1812.51  4402.5 1805.37  4417.2 1800.07  4435.7 1795.79
    4479 1788.87    4513 1785.73  4543.9 1780.66  4612.5 1776.35  4642.9 1773.84
  4670.7 1768.67    4680 1765.11  4828.4 1767.31  4896.5 1765.34  4978.8 1765.02
  4979.3 1764.52    4995 1765.02  5076.8 1766.26    5113 1767.66  5120.1 1769.48
  5164.1 1770.95  5233.4 1777.86  5260.5 1777.94  5272.5 1779.69  5323.7 1781.99
  5386.3 1793.33  5453.1 1808.02  5489.3 1817.41  5552.5 1839.82  5602.1 1861.56
#Mann= 6 ,-1 , 0
  4381.5    .035       0  4612.5     .07       0  4978.8     .05       0
    4995     .07       0  5120.1    .035       0  5386.3      .1       0
Bank Sta=4978.8,4995
XS Rating Curve= 0 ,0
Exp/Cntr=0.3,0.1

Type RM Length L Ch R = 1 ,34677   ,341,341,341
BEGIN DESCRIPTION:
Town Creek 61.0
END DESCRIPTION:
XS GIS Cut Line= 3
      1920324.99       13954675.      1919858.43     13954519.31
      1919174.99       13954675.
#Sta/Elev= 30
  4371.1 1779.85  4431.2 1776.52  4722.2 1767.97  4803.9 1766.47  4819.8 1767.45
  4834.1 1770.77  4860.5 1769.76  4865.7 1769.35  4891.7 1768.27  4906.5 1763.74
  4913.2 1761.59  4969.7 1760.46  4970.2 1759.96  4985.9 1760.46  5005.5 1760.77
  5033.2 1770.09  5067.1 1769.62  5079.4 1775.52  5088.6  1777.6  5116.3 1777.78
  5137.8  1781.2  5153.1  1781.4  5177.8 1789.34  5211.7 1791.99  5235.4 1800.02
  5337.8 1832.73  5414.8 1866.04  5451.7 1879.88  5513.2 1909.66  5563.9 1925.82
#Mann= 9 ,-1 , 0
  4371.1    .035       0  4431.2      .1       0  4722.2    .033       0
  4860.5     .07       0  4865.7    .033       0  4906.5     .07       0
  4969.7     .05       0  4985.9     .07       0  5235.4      .1       0
Bank Sta=4969.7,4985.9
XS Rating Curve= 0 ,0
Exp/Cntr=0.3,0.1

Type RM Length L Ch R = 1 ,34336   ,787,787,787
BEGIN DESCRIPTION:
Mapping XS 1ece7bd8
END DESCRIPTION:
XS GIS Cut Line= 3
      1920778.69      13954698.6      1919790.02     13954217.74
      1919199.39     13954256.46
#Sta/Elev= 30
  3784.9 1860.06  3862.1 1843.29  3910.1 1830.19    3945 1828.39  3971.8 1820.36
  4042.1 1813.52  4088.8 1797.09  4135.5 1788.35  4272.3  1778.2  4391.9 1773.84
  4509.1 1770.78  4659.2 1761.89  4705.9 1765.59  4789.4 1765.83  4869.7 1769.17
  4891.9 1764.99  4964.1 1761.49  4985.7 1756.67    4986 1753.88  4986.5 1753.38
  5002.3 1753.88  5036.2 1755.91  5046.3 1763.52  5056.4 1771.65  5177.5 1774.93
  5256.6 1782.31  5345.8 1806.24    5385 1814.45  5466.2 1845.65  5476.2 1853.67
#Mann= 6 ,-1 , 0
  3784.9    .035       0  4391.9     .07       0    4986     .05       0
  5002.3     .07       0  5046.3    .035       0  5256.6      .1       0
Bank Sta=4986,5002.3
XS Rating Curve= 0 ,0
Exp/Cntr=0.3,0.1

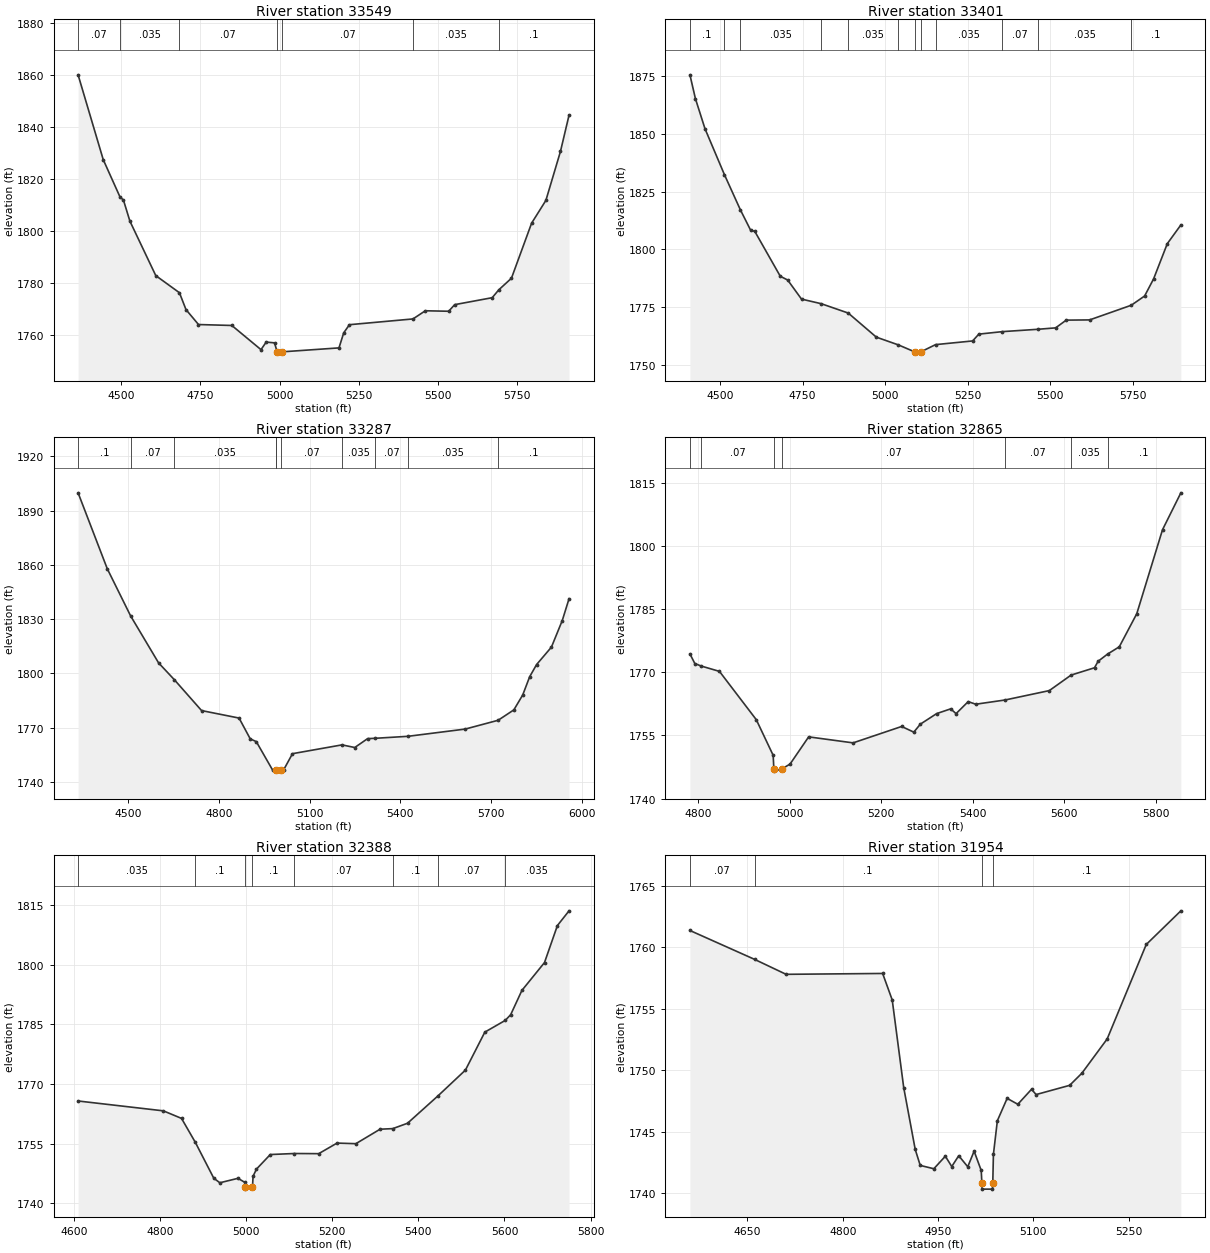
Type RM Length L Ch R = 1 ,33549   ,148,148,148
BEGIN DESCRIPTION:
Mapping XS 6671d8f9
END DESCRIPTION:
XS GIS Cut Line= 4
      1920630.17     13953688.64      1920007.12     13953969.11
      1919687.19     13953970.14      1919173.81     13954160.11
#Sta/Elev= 30
  4363.5 1860.15  4442.9 1827.46  4495.4  1813.2  4506.9 1811.81  4527.2 1803.73
  4608.9 1782.75  4683.6 1776.15  4704.3 1769.65  4743.8 1763.89  4849.1 1763.53
  4941.2 1754.21  4957.6 1757.13  4983.9 1756.83  4992.2 1753.37  4992.7 1752.87
  5008.5 1753.37  5187.5 1754.89  5202.5  1760.7  5220.5 1763.83  5421.2 1766.05
  5460.3  1769.2  5533.9 1769.01    5553 1771.56  5671.4 1774.24  5692.3 1777.28
  5732.2 1781.74  5795.9 1802.97    5841 1811.75    5887 1830.61  5914.1  1844.6
#Mann= 7 ,-1 , 0
  4363.5     .07       0  4495.4    .035       0  4683.6     .07       0
  4992.2     .05       0  5008.5     .07       0  5421.2    .035       0
  5692.3      .1       0
Bank Sta=4992.2,5008.5
XS Rating Curve= 0 ,0
Exp/Cntr=0.3,0.1

Type RM Length L Ch R = 1 ,33401   ,114,114,114
BEGIN DESCRIPTION:
Town Creek 60.1
END DESCRIPTION:
XS GIS Cut Line= 6
      1920623.02     13953600.37      1920184.68     13953767.45
      1920097.88     13953813.03      1920071.84     13953823.88
      1919956.82     13953821.71      1919234.13     13954103.84
#Sta/Elev= 30
  4408.9 1875.36  4425.6 1865.06  4454.5  1852.1  4513.3  1832.3  4561.5 1817.14
  4592.4 1808.37  4605.4 1807.76  4682.4 1788.43  4704.9 1786.78  4746.7 1778.56
  4806.5 1776.57  4888.1 1772.54  4973.2 1762.14  5040.3 1758.77  5090.1 1755.74
  5090.6 1755.24  5107.2 1755.74  5152.5 1758.91  5264.7  1760.5  5283.5 1763.44
    5355 1764.52  5462.2 1765.53  5515.9 1766.14  5548.1 1769.48  5618.9 1769.58
    5745 1775.91  5785.4  1779.9  5812.6  1787.3    5854 1802.48  5895.1 1810.57
#Mann= 12 ,-1 , 0
  4408.9      .1       0  4513.3     .07       0  4561.5    .035       0
  4806.5     .07       0  4888.1    .035       0  5040.3     .07       0
  5090.1     .05       0  5107.2     .07       0  5152.5    .035       0
    5355     .07       0  5462.2    .035       0    5745      .1       0
Bank Sta=5090.1,5107.2
XS Rating Curve= 0 ,0
Exp/Cntr=0.3,0.1

Type RM Length L Ch R = 1 ,33287   ,422,422,422
BEGIN DESCRIPTION:
Town Creek 60.0
END DESCRIPTION:
XS GIS Cut Line= 3
      1920624.99     13953425.01        1920025.       13953725.
       1919149.9     13954105.11
#Sta/Elev= 30
  4333.4 1899.84  4429.9 1857.88  4507.3 1831.75  4599.8 1805.79  4652.3 1796.42
  4742.1 1779.41  4866.2 1775.27  4903.1 1763.78  4923.3 1762.22  4976.9 1746.59
  4988.4 1746.42  4989.3 1746.42  4989.8 1745.92  5006.4 1746.42  5013.6 1746.59
    5043 1755.57  5206.9 1760.44  5249.1 1758.98  5291.6 1763.89  5315.9 1764.07
  5424.9 1765.17  5614.7 1769.18  5723.5 1774.04  5775.7  1779.8  5805.1 1788.07
    5828 1798.13  5850.9 1804.86    5900  1814.5  5935.9 1829.22  5958.3 1841.26
#Mann= 10 ,-1 , 0
  4333.4      .1       0  4507.3     .07       0  4652.3    .035       0
  4988.4     .07       0  4989.3     .05       0  5006.4     .07       0
  5206.9    .035       0  5315.9     .07       0  5424.9    .035       0
  5723.5      .1       0
Bank Sta=4989.3,5006.4
XS Rating Curve= 0 ,0
Exp/Cntr=0.3,0.1

Type RM Length L Ch R = 1 ,32865   ,477,477,477
BEGIN DESCRIPTION:
Town Creek 59.0
END DESCRIPTION:
XS GIS Cut Line= 3
      1919975.01       13953325.        1919775.       13953425.
      1919175.03     13954024.97
#Sta/Elev= 30
  4782.5  1774.4  4793.2 1772.11  4807.4  1771.5    4847 1770.24  4927.4 1758.76
  4964.3 1750.28  4965.8 1747.02  4966.3 1746.52  4982.9 1747.02  5001.2  1748.2
  5041.8 1754.67  5138.8 1753.24  5244.9 1757.14  5271.4 1755.79  5285.7 1757.69
  5321.3  1760.2    5352 1761.33  5363.7 1760.19  5390.2 1763.05  5406.6 1762.43
  5470.9 1763.44  5567.3 1765.67  5614.9 1769.36    5666  1771.1  5673.9 1772.64
  5694.6 1774.36  5720.1 1776.08  5758.3 1783.95  5814.5 1803.92  5854.6  1812.7
#Mann= 7 ,-1 , 0
  4782.5    .094       0  4807.4     .07       0  4965.8     .05       0
  4982.9     .07       0  5470.9     .07       0  5614.9    .035       0
  5694.6      .1       0
Bank Sta=4965.8,4982.9
XS Rating Curve= 0 ,0
Exp/Cntr=0.3,0.1

Type RM Length L Ch R = 1 ,32388   ,434,434,434
BEGIN DESCRIPTION:
Town Creek 58.0
END DESCRIPTION:
XS GIS Cut Line= 3
      1919674.97     13952975.02        1919375.       13953225.
      1918924.98     13953825.02
#Sta/Elev= 30
  4609.5 1765.75  4807.6 1763.27  4849.8 1761.37  4881.9 1755.34  4924.7 1746.33
  4938.8 1745.18    4981  1746.3  4996.8 1745.28  4997.4 1744.08  4997.9 1743.58
  5014.6 1744.08    5016 1746.82  5023.9 1748.62    5056 1752.28  5111.8 1752.54
  5168.5  1752.5    5211 1755.16  5254.8 1755.01    5311 1758.65  5340.6  1758.8
  5374.8 1760.15  5445.1 1766.99  5509.3 1773.52  5554.4 1783.07  5601.8 1786.02
  5614.4 1787.45  5640.5 1793.56    5693 1800.57    5723 1809.88    5750 1813.58
#Mann= 8 ,-1 , 0
  4609.5    .035       0  4881.9      .1       0  4997.4     .05       0
  5014.6      .1       0  5111.8     .07       0  5340.6      .1       0
  5445.1     .07       0  5601.8    .035       0
Bank Sta=4997.4,5014.6
XS Rating Curve= 0 ,0
Exp/Cntr=0.3,0.1

Type RM Length L Ch R = 1 ,31954   ,484,484,484
BEGIN DESCRIPTION:
Town Creek 57.0
END DESCRIPTION:
XS GIS Cut Line= 3
      1919474.99       13952925.        1919025.       13952975.
      1918825.01     13953224.99
#Sta/Elev= 30
  4559.4 1761.37  4661.1 1759.02  4710.8  1757.8  4862.8 1757.87  4877.9 1755.71
    4896 1748.57  4914.1 1743.54    4922 1742.24  4943.4 1741.97  4961.5 1742.99
  4971.6 1742.15  4982.6 1743.03  4996.8 1742.13  5006.8  1743.4    5018 1741.83
    5019 1740.81  5019.5 1740.31  5035.7 1740.31  5036.2 1740.81  5037.2 1743.14
  5043.4 1745.88  5058.8  1747.7  5075.6 1747.22  5097.2 1748.44  5104.4 1748.01
  5157.2 1748.76  5176.5 1749.75  5216.3 1752.54  5277.8 1760.23  5332.3 1762.97
#Mann= 4 ,-1 , 0
  4559.4     .07       0  4661.1      .1       0    5019     .05       0
  5036.2      .1       0
Bank Sta=5019,5036.2
XS Rating Curve= 0 ,0
Exp/Cntr=0.3,0.1

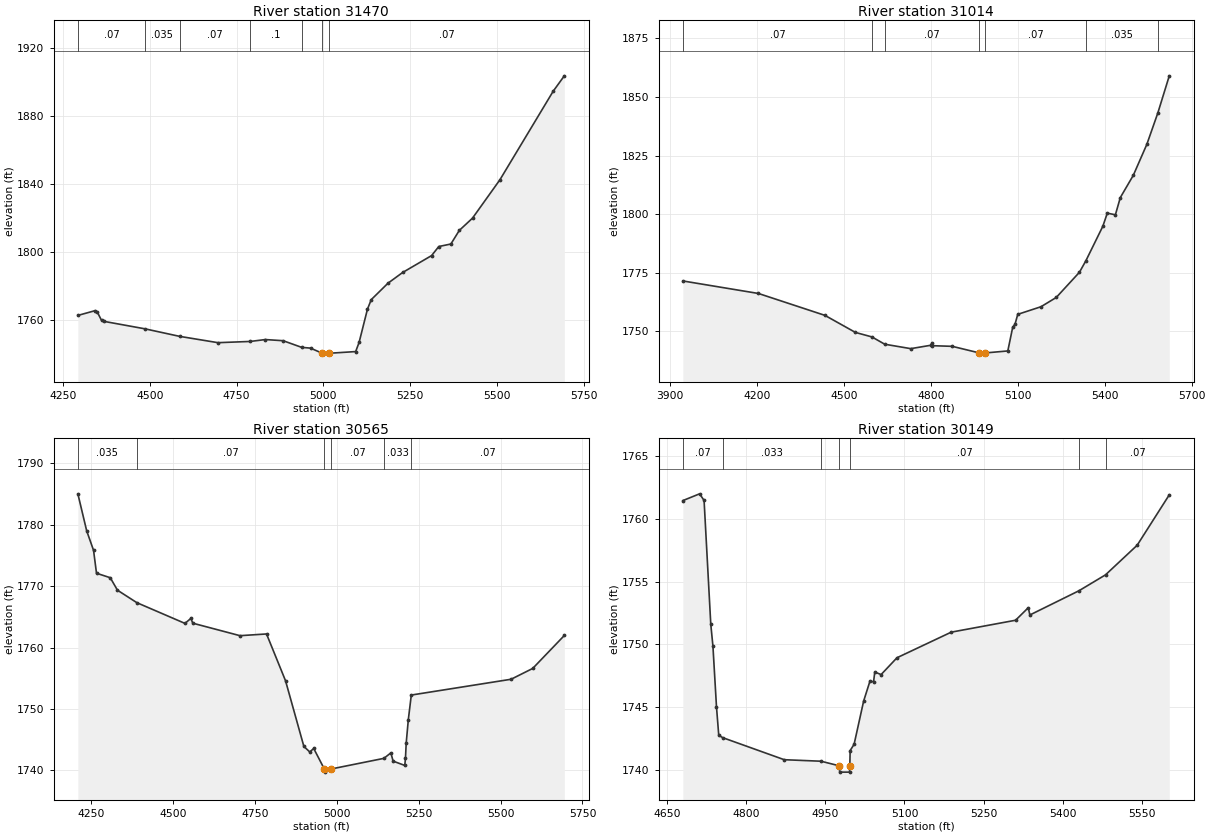
Type RM Length L Ch R = 1 ,31470   ,456,456,456
BEGIN DESCRIPTION:
Town Creek 56.0
END DESCRIPTION:
XS GIS Cut Line= 3
      1919475.03       13952725.        1918775.       13952625.
      1918174.96     13952274.98
#Sta/Elev= 30
  4292.4 1762.62  4342.5 1765.45  4348.6 1764.48  4360.7 1759.69  4366.5 1759.17
  4486.4 1754.72  4585.6 1750.32  4696.1 1746.61  4789.2 1747.33  4832.5 1748.44
    4884 1747.76  4937.4 1743.85  4962.8 1743.41  4996.9 1740.38  4997.4 1739.88
  5016.4 1740.38  5092.9 1741.38  5102.8 1746.75  5126.9  1766.3  5137.9 1771.91
  5186.1 1781.56  5228.3 1787.85  5311.7 1797.78  5332.5 1803.11  5367.3 1804.58
  5391.6 1812.58  5429.6 1819.78  5508.6 1842.32  5662.1 1894.35  5694.2  1903.4
#Mann= 7 ,-1 , 0
  4292.4     .07       0  4486.4    .035       0  4585.6     .07       0
  4789.2      .1       0  4937.4     .07       0  4996.9     .05       0
  5016.4     .07       0
Bank Sta=4996.9,5016.4
XS Rating Curve= 0 ,0
Exp/Cntr=0.3,0.1

Type RM Length L Ch R = 1 ,31014   ,449,449,449
BEGIN DESCRIPTION:
Town Creek 55.0
END DESCRIPTION:
XS GIS Cut Line= 4
      1919839.66      13952751.5      1919497.25      13952606.5
        1918925.       13952225.      1918324.97     13952074.99
#Sta/Elev= 30
  3944.7 1771.46  4205.6 1766.11  4434.9 1756.76  4539.9 1749.49  4597.1 1747.55
  4641.2 1744.44    4731 1742.55  4799.5 1743.98  4804.7    1745  4805.6 1743.81
  4874.1 1743.54    4968 1740.71  4968.5 1740.21  4987.5 1740.71  5065.8 1741.57
  5082.8 1751.77  5090.5 1752.92  5100.1  1757.2  5180.2 1760.45  5232.8  1764.4
  5312.9 1775.17  5335.2 1780.11  5393.6 1794.82    5409 1800.41  5436.9 1799.71
  5453.9 1807.07  5498.7 1816.57  5545.4  1829.8  5583.4 1843.23  5622.8 1859.05
#Mann= 7 ,-1 , 0
  3944.7     .07       0  4597.1    .035       0  4641.2     .07       0
    4968     .05       0  4987.5     .07       0  5335.2    .035       0
  5583.4     .07       0
Bank Sta=4968,4987.5
XS Rating Curve= 0 ,0
Exp/Cntr=0.3,0.1

Type RM Length L Ch R = 1 ,30565   ,416,416,416
BEGIN DESCRIPTION:
Town Creek 54.0
END DESCRIPTION:
XS GIS Cut Line= 4
      1920115.28     13952180.76      1919555.38     13952176.42
        1919325.       13952175.      1918725.02     13951825.01
#Sta/Elev= 30
  4209.7 1785.01  4236.6 1778.99  4257.6 1775.81  4266.6 1772.09  4308.6 1771.36
  4330.6 1769.33  4389.8  1767.3  4536.6 1763.93  4554.6 1764.74  4560.6 1763.96
  4704.6 1761.93  4785.6 1762.21  4843.7 1754.58  4899.6 1743.91  4917.6 1743.01
  4929.6 1743.58  4962.1 1740.23  4962.6 1739.73  4981.8 1740.23  5143.8 1741.97
  5165.1 1742.86    5172 1741.52  5207.5 1740.82  5209.7 1741.95  5211.9 1744.43
  5218.4 1748.26  5227.5 1752.27  5532.1 1754.84  5598.1  1756.6  5694.6 1761.96
#Mann= 6 ,-1 , 0
  4209.7    .035       0  4389.8     .07       0  4962.1     .05       0
  4981.8     .07       0  5143.8    .033       0  5227.5     .07       0
Bank Sta=4962.1,4981.8
XS Rating Curve= 0 ,0
Exp/Cntr=0.3,0.1

Type RM Length L Ch R = 1 ,30149   ,466,466,466
BEGIN DESCRIPTION:
Town Creek 53.0
END DESCRIPTION:
XS GIS Cut Line= 3
      1919574.97     13952024.98        1919325.       13951825.
        1918725.       13951775.
#Sta/Elev= 30
  4679.8 1761.47  4711.6 1762.01  4720.1 1761.48  4732.8 1751.61  4736.9 1749.85
  4743.6 1745.04  4747.9 1742.76  4755.3 1742.57  4872.1 1740.81  4941.7 1740.69
  4976.7 1740.32  4977.2 1739.82  4995.9 1739.82  4996.4 1740.32    4997 1741.54
  5004.5 1742.04  5022.6 1745.49  5034.6 1747.08  5041.4 1747.02  5043.7  1747.8
  5055.7  1747.6  5085.8 1748.94  5188.6 1750.98  5310.6 1751.93  5334.7 1752.93
  5337.7 1752.35  5430.7 1754.28  5481.1 1755.55  5541.1 1757.91    5602 1761.93
#Mann= 7 ,-1 , 0
  4679.8     .07       0  4755.3    .033       0  4941.7     .07       0
  4976.7     .05       0  4996.4     .07       0  5430.7    .035       0
  5481.1     .07       0
Bank Sta=4976.7,4996.4
XS Rating Curve= 0 ,0
Exp/Cntr=0.3,0.1