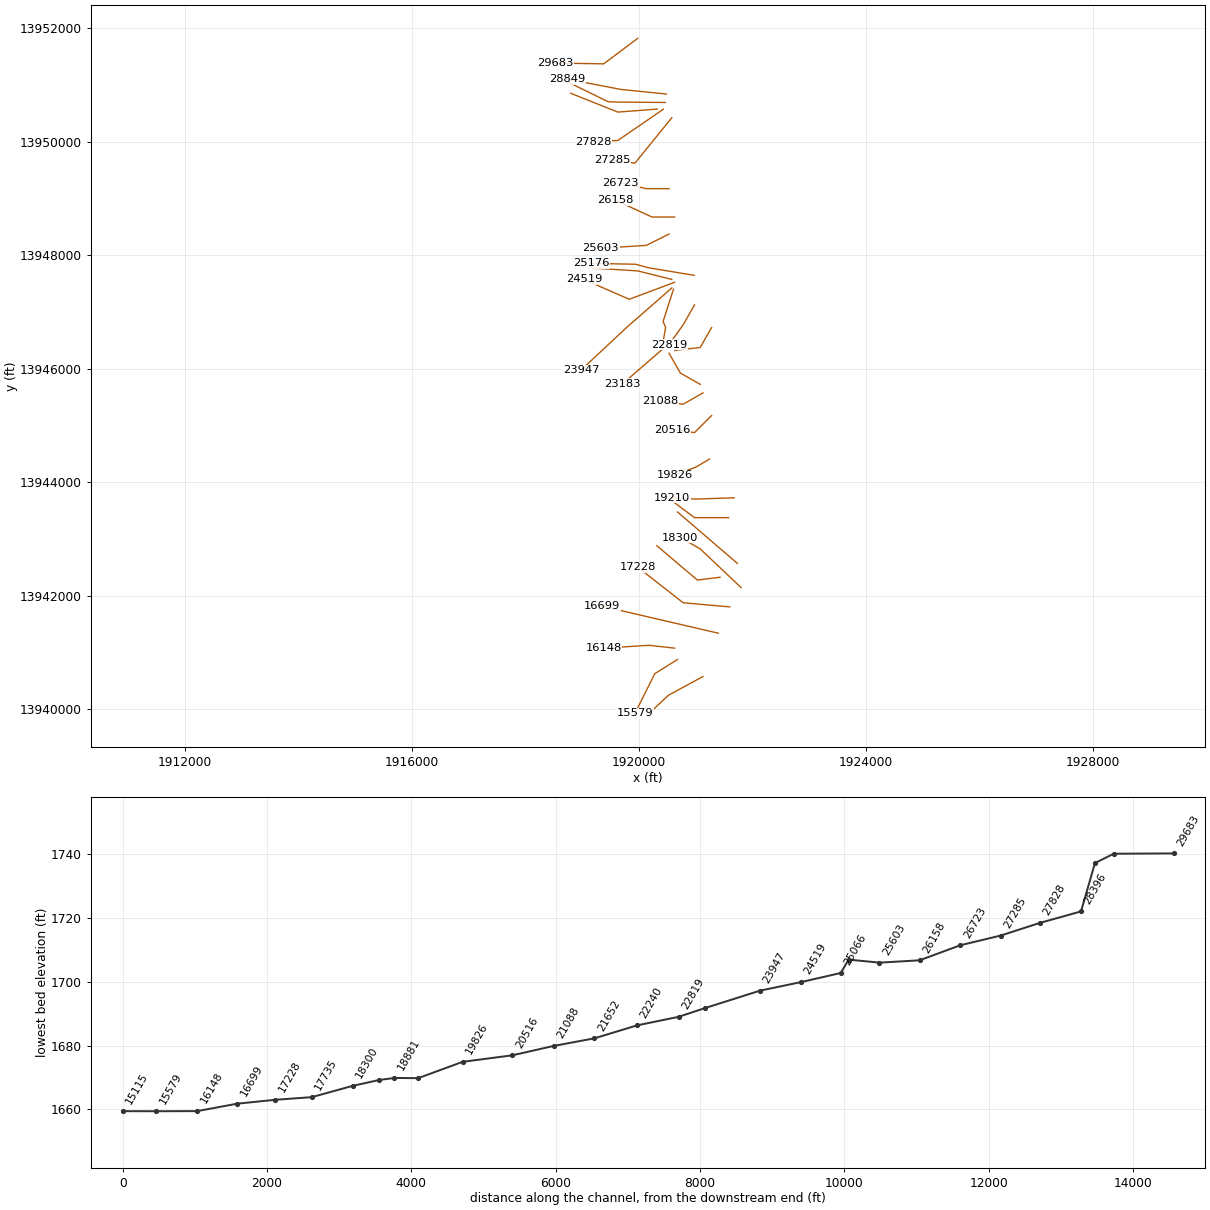
HEC-RAS study Town Creek.prj: Town Creek Base Level Engineering

--- Town Creek.g01 (geometry) --- (continued)

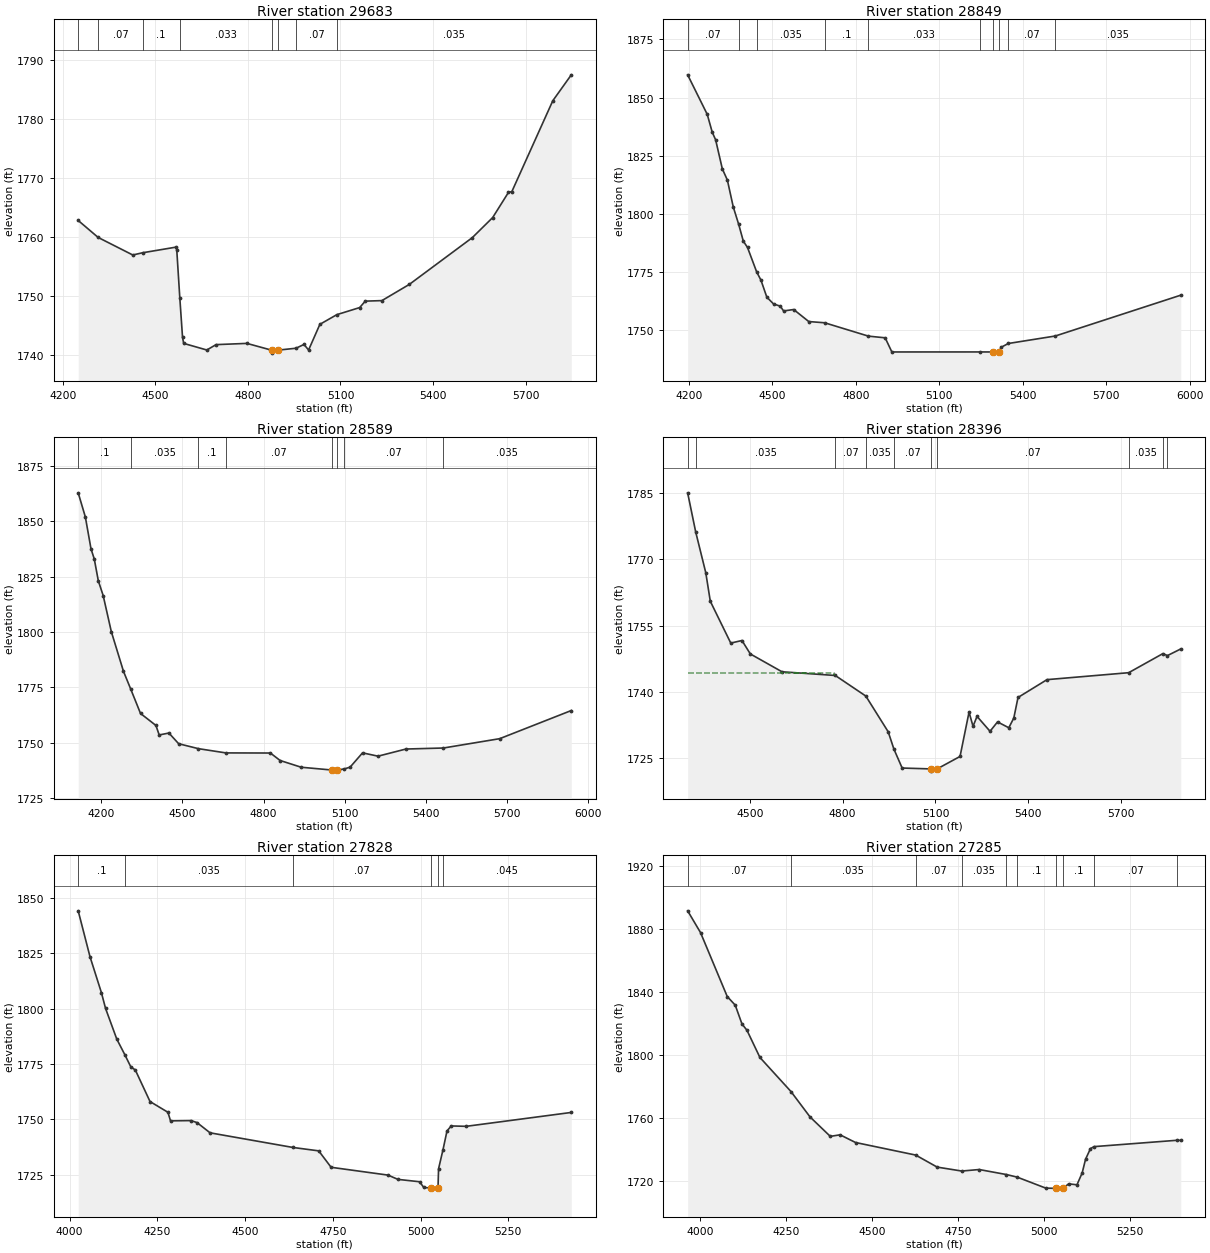
Type RM Length L Ch R = 1 ,29683   ,834,834,834
BEGIN DESCRIPTION:
Town Creek 52.0
END DESCRIPTION:
XS GIS Cut Line= 3
      1919975.04     13951825.03        1919375.       13951375.
      1918526.37     13951389.43
#Sta/Elev= 30
  4249.6  1762.8  4314.4 1759.92  4426.6 1756.95  4458.6 1757.33  4565.4 1758.27
  4569.1 1757.88    4579 1749.73  4587.9 1742.99  4591.6 1741.97  4666.6 1740.85
  4696.6 1741.76  4796.6 1741.97  4876.7 1740.82  4877.2 1740.32  4896.5 1740.82
  4955.8 1741.15  4981.6 1741.79  4996.6 1740.85  5033.2  1745.2  5088.2 1746.84
  5162.3 1748.04  5180.3 1749.13  5234.3 1749.22  5323.3 1751.97  5527.4 1759.89
  5593.4 1763.29  5644.4 1767.54  5655.7  1767.7  5788.4 1783.09  5848.4 1787.48
#Mann= 8 ,-1 , 0
  4249.6    .035       0  4314.4     .07       0  4458.6      .1       0
    4579    .033       0  4876.7     .05       0  4896.5    .033       0
  4955.8     .07       0  5088.2    .035       0
Bank Sta=4876.7,4896.5
XS Rating Curve= 0 ,0
Exp/Cntr=0.3,0.1

Type RM Length L Ch R = 1 ,28849   ,260,260,260
BEGIN DESCRIPTION:
Town Creek 51.0
END DESCRIPTION:
XS GIS Cut Line= 3
      1920479.42       13950843.        1919675.       13950925.
      1918728.85     13951106.05
#Sta/Elev= 30
  4195.6  1859.8    4266 1842.81  4283.9 1835.16  4296.1 1831.89  4320.2  1819.4
  4338.3 1814.59  4359.5 1803.04  4378.9 1795.59  4395.6 1788.35  4410.7 1785.62
  4443.5 1775.15    4459 1771.58  4480.1 1764.27  4504.2 1761.36  4528.3  1760.4
  4540.4 1758.34  4576.6 1758.96  4630.8 1753.79  4687.9 1753.26  4845.2 1747.52
  4905.3  1746.8  4929.4 1740.72  5246.8 1740.73  5293.8 1740.72  5294.3 1740.22
  5313.6 1740.72  5322.4 1742.75  5347.8 1744.36  5516.8 1747.58  5967.5 1765.12
#Mann= 10 ,-1 , 0
  4195.6     .07       0  4378.9      .1       0  4443.5    .035       0
  4687.9      .1       0  4845.2    .033       0  5246.8     .07       0
  5293.8     .05       0  5313.6     .07       0  5347.8     .07       0
  5516.8    .035       0
Bank Sta=5293.8,5313.6
XS Rating Curve= 0 ,0
Exp/Cntr=0.3,0.1

Type RM Length L Ch R = 1 ,28589   ,193,193,193
BEGIN DESCRIPTION:
Town Creek 51.1
END DESCRIPTION:
XS GIS Cut Line= 4
      1920459.83      13950694.1       1919613.5     13950701.91
      1919454.65     13950707.12      1918720.27      13951066.5
#Sta/Elev= 30
  4114.8 1862.73  4141.2 1851.87  4162.2 1837.45  4174.2 1832.93  4189.2 1823.06
  4207.2 1816.39  4237.2 1800.17  4282.2 1782.27    4309 1774.26  4345.2 1763.28
  4402.2 1757.86  4414.2 1753.59  4450.2 1754.45  4486.2 1749.63  4559.5  1747.4
  4660.9 1745.49  4825.3 1745.44  4861.3 1742.07  4939.3 1739.03  5052.4 1737.78
  5052.9 1737.28  5072.2 1737.78  5098.7 1738.27  5120.1 1739.09    5166 1745.52
  5223.2 1744.02  5326.3 1747.24  5464.9  1747.7    5673 1751.91  5937.7  1764.6
#Mann= 8 ,-1 , 0
  4114.8      .1       0    4309    .035       0  4559.5      .1       0
  4660.9     .07       0  5052.4     .05       0  5072.2     .07       0
  5098.7     .07       0  5464.9    .035       0
Bank Sta=5052.4,5072.2
XS Rating Curve= 0 ,0
Exp/Cntr=0.3,0.1

Type RM Length L Ch R = 1 ,28396   ,568,568,568
BEGIN DESCRIPTION:
Town Creek 50.0
END DESCRIPTION:
XS GIS Cut Line= 3
      1920320.36     13950577.79        1919625.       13950525.
      1918793.03     13950856.39
#Sta/Elev= 30
  4299.5 1785.06  4325.6 1776.18  4358.1 1766.98  4372.7 1760.53  4438.8 1751.08
    4475 1751.66    4502 1748.62  4604.3 1744.59  4776.4 1743.75    4875  1739.1
  4947.3 1731.02  4965.8  1727.1  4992.4 1722.82  5085.5 1722.62    5086 1722.12
  5105.3 1722.62  5179.4 1725.44  5208.5 1735.46  5221.4 1732.25  5234.3  1734.5
  5276.3 1731.13  5300.5 1733.25  5336.9 1731.93  5353.1 1734.13  5366.7 1738.78
  5460.3 1742.81  5724.1 1744.38  5834.7  1748.7  5849.4 1748.25  5892.4 1749.75
#Mann= 10 ,-1 , 0
  4299.5      .1       0  4325.6    .035       0  4776.4     .07       0
    4875    .035       0  4965.8     .07       0  5085.5     .05       0
  5105.3     .07       0  5724.1    .035       0  5834.7     .07       0
  5849.4    .035       0
#XS Ineff= 2 , 0
         4773.63 1744.31
Permanent Ineff=
       F       F
Bank Sta=5085.5,5105.3
XS Rating Curve= 0 ,0
Exp/Cntr=0.3,0.1

Type RM Length L Ch R = 1 ,27828   ,543,543,543
BEGIN DESCRIPTION:
Town Creek 49.0
END DESCRIPTION:
XS GIS Cut Line= 3
        1920425.       13950575.        1919625.       13950025.
      1919191.71     13950004.36
#Sta/Elev= 30
  4024.7  1844.2  4058.2 1823.55  4090.9 1807.21  4102.6 1800.14  4134.6 1786.28
  4157.4 1779.27  4174.7  1773.7  4187.4 1772.34  4229.3 1758.08  4280.3 1753.23
  4287.7 1749.36  4346.2 1749.48  4363.2 1748.57  4400.4 1743.95  4636.6 1737.34
  4709.8 1735.81  4745.1 1728.39  4906.9 1724.87  4935.6 1722.93  4997.1 1721.86
  5009.1 1719.27  5028.8 1719.03  5029.3 1718.53  5049.6 1719.03  5051.2 1727.73
  5063.9 1736.37  5075.2  1744.8  5087.2 1747.06    5130 1746.89  5429.3 1753.16
#Mann= 6 ,-1 , 0
  4024.7      .1       0  4157.4    .035       0  4636.6     .07       0
  5028.8     .05       0  5049.6     .07       0  5063.9    .045       0
Bank Sta=5028.8,5049.6
XS Rating Curve= 0 ,0
Exp/Cntr=0.3,0.1

Type RM Length L Ch R = 1 ,27285   ,562,562,562
BEGIN DESCRIPTION:
Town Creek 48.0
END DESCRIPTION:
XS GIS Cut Line= 3
      1920574.98     13950424.97        1919925.       13949625.
      1919524.95     13949675.01
#Sta/Elev= 30
  3964.6 1891.35  4002.1  1877.5  4079.7 1836.91    4103 1831.43  4122.5 1819.52
  4137.1 1815.46  4174.8 1798.19    4265 1776.57  4320.5 1760.42  4379.4 1748.07
  4407.9 1749.06  4452.8 1744.18  4627.6  1736.2  4690.2 1728.55  4761.6 1726.05
  4812.3 1727.01  4891.7 1723.82  4922.5 1722.21    5006  1715.2  5034.9 1715.06
  5035.4 1714.56  5055.8 1715.06  5072.5 1717.91  5096.7 1717.32  5111.8 1724.84
  5121.7 1733.58    5136 1740.32  5146.5 1741.56  5386.9 1745.58  5398.5 1745.54
#Mann= 10 ,-1 , 0
  3964.6     .07       0    4265    .035       0  4627.6     .07       0
  4761.6    .035       0  4891.7     .07       0  4922.5      .1       0
  5034.9     .05       0  5055.8      .1       0  5146.5     .07       0
  5386.9    .045       0
Bank Sta=5034.9,5055.8
XS Rating Curve= 0 ,0
Exp/Cntr=0.3,0.1

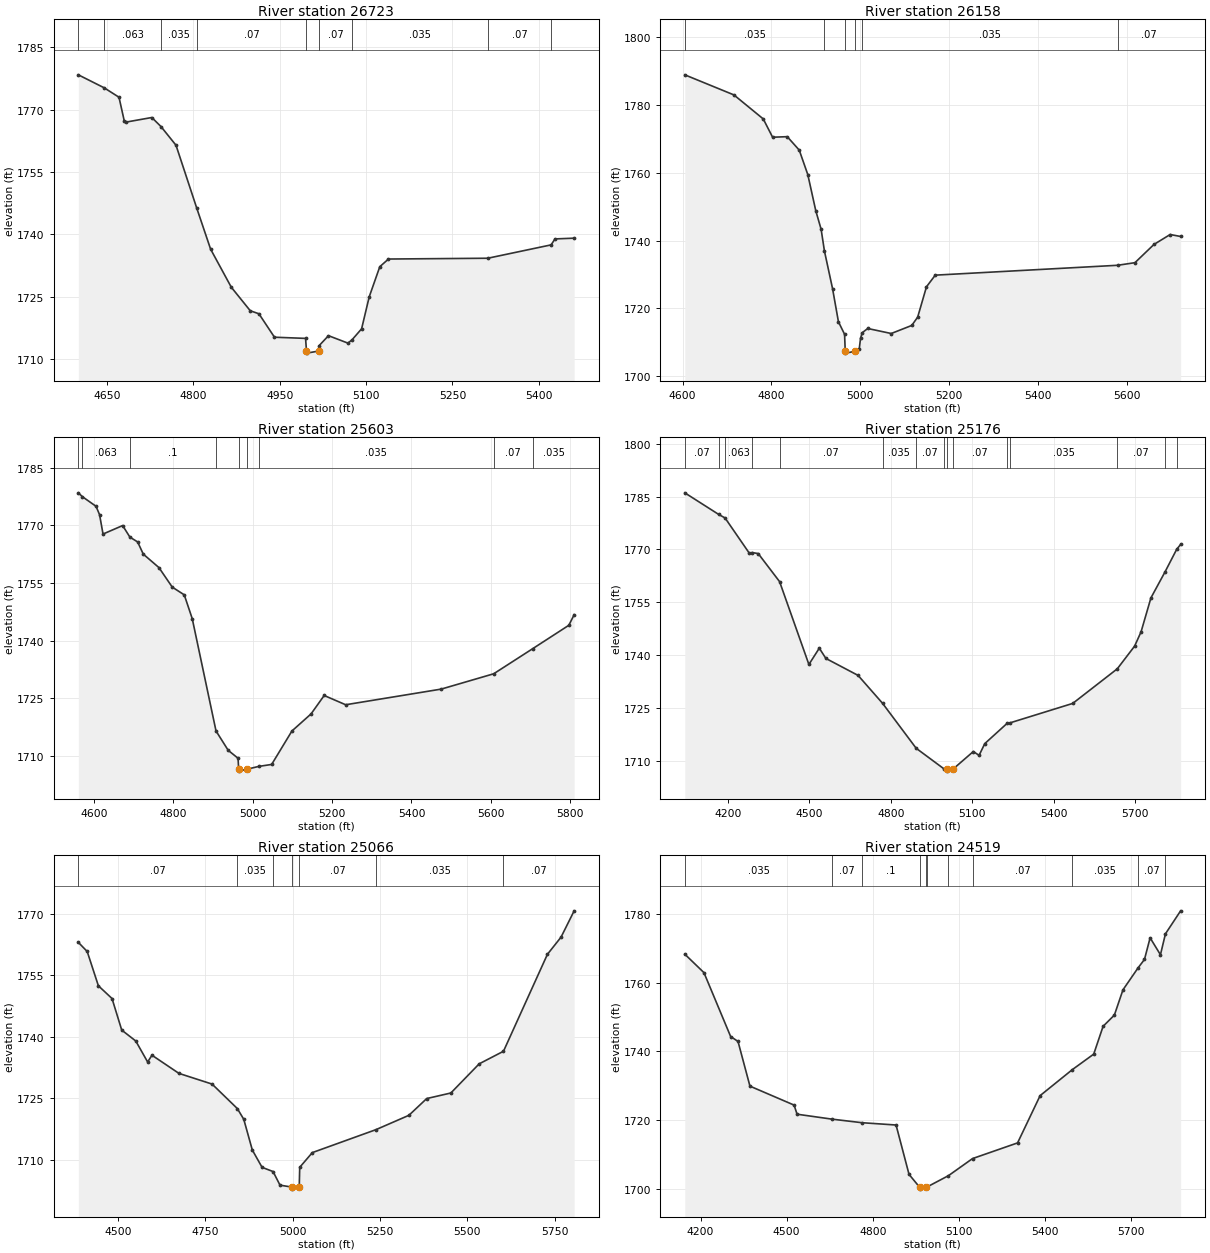
Type RM Length L Ch R = 1 ,26723   ,565,565,565
BEGIN DESCRIPTION:
Town Creek 47.0
END DESCRIPTION:
XS GIS Cut Line= 3
      1920524.99       13949175.        1920125.       13949175.
      1919674.97     13949275.01
#Sta/Elev= 30
  4600.3 1778.34  4645.2 1775.22  4670.9 1772.96    4680 1767.31  4682.9 1766.98
  4727.9 1768.09  4743.8 1765.92  4769.9 1761.43  4805.7 1746.42    4830 1736.47
  4865.9 1727.33  4898.9 1721.67  4913.9 1720.95  4940.9 1715.32  4994.9 1715.04
  4996.5    1712    4997  1711.5  5017.6    1712  5018.3 1713.28  5034.7 1715.69
  5068.5  1713.9  5075.8 1714.73  5092.2 1717.34  5105.4 1725.01  5123.8 1732.26
  5138.9  1734.1  5311.3 1734.29  5421.3  1737.5    5428 1738.93  5461.3 1739.11
#Mann= 9 ,-1 , 0
  4600.3    .035       0  4645.2    .063       0  4743.8    .035       0
  4805.7     .07       0  4996.5     .05       0  5017.6     .07       0
  5075.8    .035       0  5311.3     .07       0  5421.3    .035       0
Bank Sta=4996.5,5017.6
XS Rating Curve= 0 ,0
Exp/Cntr=0.3,0.1

Type RM Length L Ch R = 1 ,26158   ,555,555,555
BEGIN DESCRIPTION:
Town Creek 46.0
END DESCRIPTION:
XS GIS Cut Line= 3
      1920625.05       13948675.        1920225.       13948675.
      1919575.03     13948974.98
#Sta/Elev= 30
    4605  1788.9  4715.6 1782.97  4781.6 1775.88  4802.6 1770.49  4835.6 1770.65
  4862.6 1766.68  4881.8 1759.47  4899.8 1748.79  4911.8 1743.33  4919.3 1736.89
  4937.6 1725.77  4950.8 1716.02  4964.6 1712.34  4966.1 1707.28  4966.6 1706.78
  4987.2 1707.28  4997.6 1708.04  5000.6 1711.19  5004.5 1712.82  5016.7 1714.05
  5069.6 1712.57  5115.8 1714.95  5129.1  1717.4  5148.9 1726.35  5168.7 1729.79
  5579.1  1732.7  5618.1 1733.47  5660.9 1738.85  5697.4 1741.78  5720.9  1741.2
#Mann= 6 ,-1 , 0
    4605    .035       0  4919.3     .07       0  4966.1     .05       0
  4987.2     .07       0  5004.5    .035       0  5579.1     .07       0
Bank Sta=4966.1,4987.2
XS Rating Curve= 0 ,0
Exp/Cntr=0.3,0.1

Type RM Length L Ch R = 1 ,25603   ,427,427,427
BEGIN DESCRIPTION:
Town Creek 45.0
END DESCRIPTION:
XS GIS Cut Line= 3
      1920525.02     13948375.01        1920125.       13948175.
      1919324.99       13948125.
#Sta/Elev= 30
  4560.9  1778.5  4571.2 1777.49  4605.5 1774.99  4614.4  1772.8  4623.1 1767.77
  4672.5 1769.98  4690.7 1766.98  4710.3 1765.71  4724.5 1762.54  4763.9 1759.04
  4797.5 1753.95  4827.7 1751.94  4847.8 1745.74  4907.7  1716.5  4938.4 1711.46
  4963.2  1709.4  4964.7 1706.55  4965.2 1706.05  4985.8 1706.55  5015.4 1707.28
  5047.8 1707.79  5098.9  1716.5    5147 1720.94  5180.1 1725.74  5234.2 1723.33
  5474.7  1727.4    5607 1731.39  5705.6 1737.95  5796.3 1744.02  5809.7 1746.78
#Mann= 9 ,-1 , 0
  4560.9    .035       0  4571.2    .063       0  4690.7      .1       0
  4907.7     .07       0  4964.7     .05       0  4985.8     .07       0
  5015.4    .035       0    5607     .07       0  5705.6    .035       0
Bank Sta=4964.7,4985.8
XS Rating Curve= 0 ,0
Exp/Cntr=0.3,0.1

Type RM Length L Ch R = 1 ,25176   ,110,110,110
BEGIN DESCRIPTION:
Town Creek 44.1
END DESCRIPTION:
XS GIS Cut Line= 5
       1920970.3     13947647.22      1920165.59     13947780.04
      1920032.77      13947816.5      1919936.42     13947842.54
      1919163.02     13947858.16
#Sta/Elev= 30
  4041.2 1786.08  4165.7 1779.96  4189.5 1778.94  4278.3 1768.99    4290  1769.1
  4311.7 1768.82  4390.4 1760.85  4498.4 1737.31  4536.7 1741.94    4561 1739.02
  4679.6  1734.2  4769.7 1726.28  4893.7 1713.49  4996.8  1707.6    5007  1707.5
  5007.5    1707  5028.3  1707.5  5104.2 1712.57  5125.4 1711.48  5146.4 1714.82
  5228.3 1720.55  5239.5 1720.72  5470.4 1726.24  5634.5 1736.07  5698.4 1742.52
  5722.1 1746.57  5758.5 1756.23  5810.9 1763.68  5853.4 1770.03  5867.9 1771.42
#Mann= 15 ,-1 , 0
  4041.2     .07       0  4165.7    .035       0  4189.5    .063       0
    4290    .035       0  4390.4     .07       0  4769.7    .035       0
  4893.7     .07       0  4996.8     .07       0    5007     .05       0
  5028.3     .07       0  5228.3     .07       0  5239.5    .035       0
  5634.5     .07       0  5810.9    .035       0  5853.4     .07       0
Bank Sta=5007,5028.3
XS Rating Curve= 0 ,0
Exp/Cntr=0.3,0.1

Type RM Length L Ch R = 1 ,25066   ,547,547,547
BEGIN DESCRIPTION:
Town Creek 44.0
END DESCRIPTION:
XS GIS Cut Line= 3
      1920575.03     13947574.99        1919975.       13947725.
      1919174.95       13947775.
#Sta/Elev= 30
  4386.1 1762.99  4411.5 1760.76  4443.5  1752.4  4482.6 1749.29  4510.4 1741.59
  4550.6 1738.93  4584.6 1733.81    4597 1735.46  4674.3 1731.03  4769.2 1728.42
  4841.4 1722.46  4859.9 1719.84  4884.4 1712.34  4912.4 1708.11  4943.8 1707.09
  4963.7 1703.77  4997.5  1703.3    4998  1702.8  5018.8  1703.3  5020.2 1708.12
  5056.3 1711.71  5238.3  1717.3  5332.8  1720.8  5383.9 1724.89  5453.1 1726.25
  5534.2 1733.36  5603.8 1736.43  5729.6 1760.07  5768.7 1764.27  5806.2 1770.68
#Mann= 7 ,-1 , 0
  4386.1     .07       0  4841.4    .035       0  4943.8     .07       0
  4997.5     .05       0  5018.8     .07       0  5238.3    .035       0
  5603.8     .07       0
Bank Sta=4997.5,5018.8
XS Rating Curve= 0 ,0
Exp/Cntr=0.3,0.1

Type RM Length L Ch R = 1 ,24519   ,572,572,572
BEGIN DESCRIPTION:
Town Creek 43.0
END DESCRIPTION:
XS GIS Cut Line= 3
      1920624.96     13947524.99        1919825.       13947225.
      1919024.98     13947575.01
#Sta/Elev= 30
  4145.2 1768.27    4212 1762.89  4304.9 1744.33  4330.6  1742.9  4372.2  1729.9
    4526 1724.39  4536.4 1721.74  4658.6  1720.3  4762.7 1719.27  4881.3  1718.6
  4926.5 1704.25  4963.9 1700.46  4964.4 1699.96  4985.2 1700.46  4988.4 1700.55
    5064 1703.88  5147.7 1708.84  5304.7  1713.4  5383.3 1727.15  5495.6 1734.71
    5570 1739.21  5602.7  1747.3    5642 1750.56  5671.9  1757.9  5724.4 1764.27
  5746.8 1766.73  5766.5 1773.02  5802.5  1768.1  5819.9 1774.18  5872.8 1780.87
#Mann= 11 ,-1 , 0
  4145.2    .035       0  4658.6     .07       0  4762.7      .1       0
  4963.9     .05       0  4985.2      .1       0  4988.4     .07       0
    5064      .1       0  5147.7     .07       0  5495.6    .035       0
  5724.4     .07       0  5819.9    .035       0
Bank Sta=4963.9,4985.2
XS Rating Curve= 0 ,0
Exp/Cntr=0.3,0.1

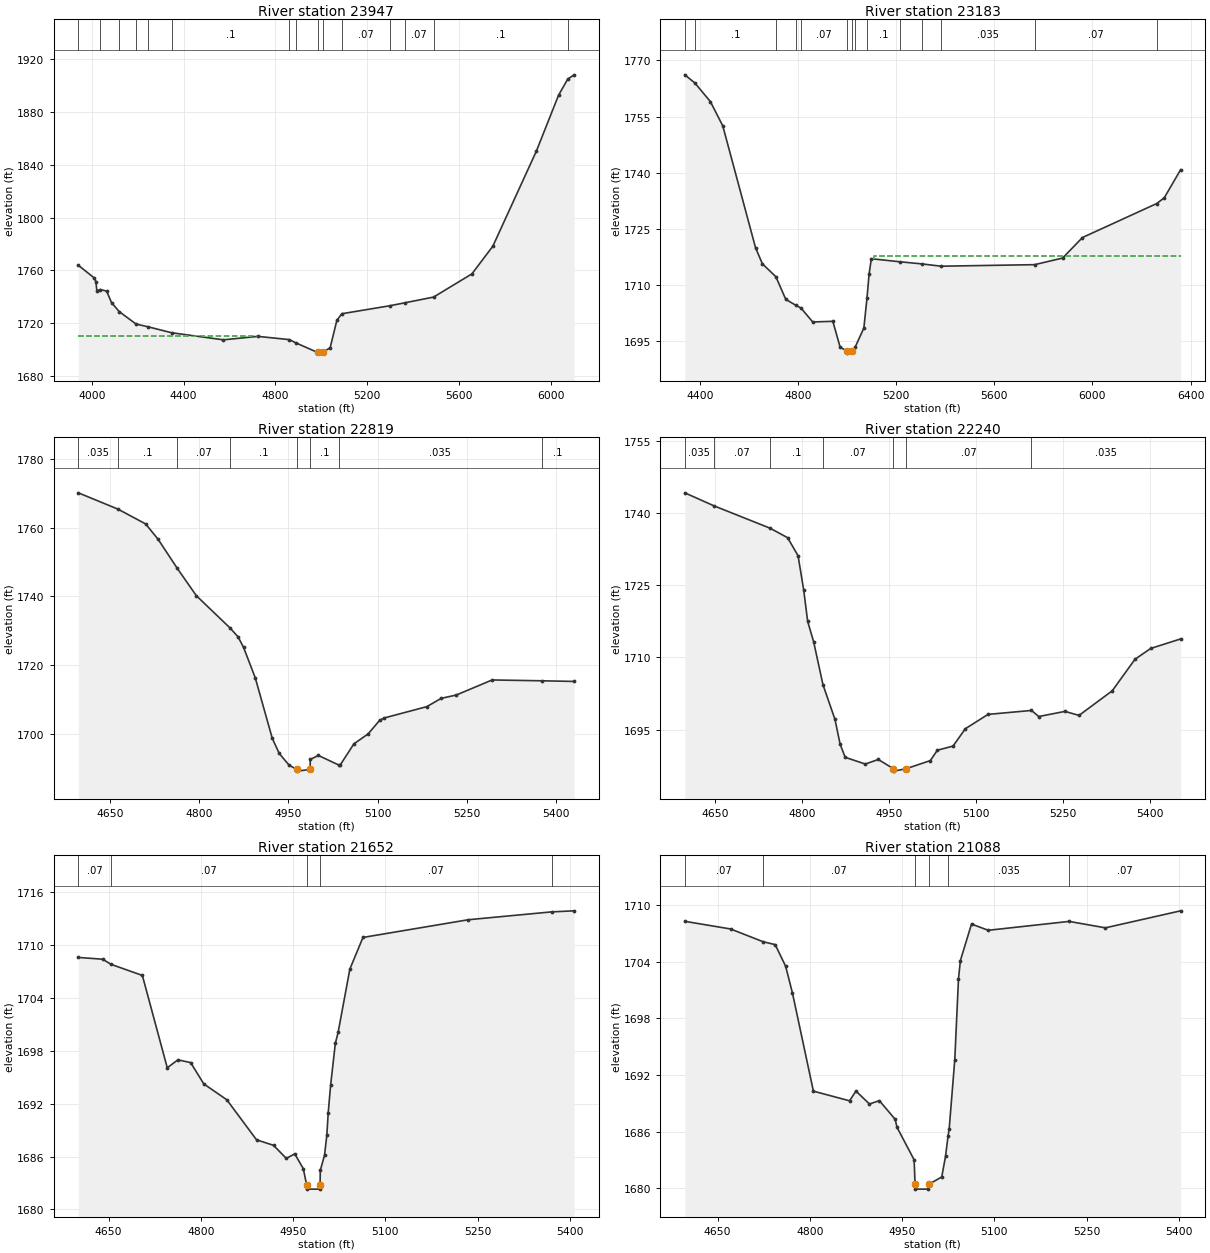
Type RM Length L Ch R = 1 ,23947   ,764,764,764
BEGIN DESCRIPTION:
Town Creek 42.0
END DESCRIPTION:
XS GIS Cut Line= 3
        1920575.       13947425.        1919775.       13946725.
        1918975.       13945975.
#Sta/Elev= 30
  3941.6 1763.86  4011.6 1754.16    4018 1751.45  4022.2 1744.72  4038.1 1745.47
  4064.7 1744.27  4086.1  1735.6  4119.4  1728.8    4193  1719.3  4246.8 1717.16
    4348  1712.7  4573.6 1707.34  4723.7 1709.96  4860.7  1707.5  4890.4 1704.94
  4983.9 1697.76  4984.4 1697.26  5005.7 1697.76  5038.4 1701.38  5067.7 1722.14
  5089.4 1727.13  5299.7 1733.22  5364.3 1735.44  5488.7 1739.73    5656 1757.36
    5747 1778.32  5936.1  1850.2  6033.4 1892.84  6073.2    1905  6101.2 1908.25
#Mann= 15 ,-1 , 0
  3941.6    .035       0  4038.1      .1       0  4119.4     .07       0
    4193      .1       0  4246.8     .07       0    4348      .1       0
  4860.7     .07       0  4890.4      .1       0  4983.9     .05       0
  5005.7      .1       0  5089.4     .07       0  5299.7    .035       0
  5364.3     .07       0  5488.7      .1       0  6073.2     .07       0
#XS Ineff= 2 , 0
            4723  1710.3
Permanent Ineff=
       F       F
Bank Sta=4983.9,5005.7
XS Rating Curve= 0 ,0
Exp/Cntr=0.3,0.1

Type RM Length L Ch R = 1 ,23183   ,364,364,364
BEGIN DESCRIPTION:
Town Creek 41.0
END DESCRIPTION:
XS GIS Cut Line= 5
      1920605.03     13947403.43      1920421.02     13946832.29
      1920466.16     13946729.86      1920394.98     13946330.55
      1919710.97     13945738.56
#Sta/Elev= 30
  4337.4 1766.15  4378.5 1763.97  4441.7    1759  4492.3 1752.51  4625.9 1719.95
  4653.8 1715.65  4708.9  1712.2  4749.2 1706.15  4790.1 1704.57  4811.2 1703.83
  4859.1 1700.11  4941.2 1700.28  4970.7 1693.42  4999.1 1692.28  4999.6 1691.78
    5021 1692.28  5032.1 1693.37  5067.7 1698.49  5080.6 1706.58    5089  1712.9
  5098.2 1717.01  5216.1 1716.18  5303.7 1715.63  5382.5 1715.01    5764 1715.42
  5878.4 1717.19  5959.2 1722.67  6262.3 1731.76  6292.9 1733.29  6359.6  1740.8
#Mann= 14 ,-1 , 0
  4337.4    .035       0  4378.5      .1       0  4708.9     .07       0
  4790.1      .1       0  4811.2     .07       0  4999.1     .05       0
    5021     .07       0  5032.1    .035       0  5080.6      .1       0
  5216.1    .035       0  5303.7      .1       0  5382.5    .035       0
    5764     .07       0  6262.3      .1       0
#XS Ineff= 2 , 0
                         5108.89         1717.62
Permanent Ineff=
       F       F
Bank Sta=4999.1,5021
XS Rating Curve= 0 ,0
Exp/Cntr=0.3,0.1

Type RM Length L Ch R = 1 ,22819   ,579,579,579
BEGIN DESCRIPTION:
Town Creek 40.0
END DESCRIPTION:
XS GIS Cut Line= 3
      1920974.98     13947124.96        1920775.       13946775.
      1920524.99     13946424.99
#Sta/Elev= 30
  4597.2 1770.13  4663.9 1765.37  4710.2 1761.08  4730.9 1756.68  4763.6 1748.09
  4795.6 1740.14  4852.1 1730.77  4865.7 1728.15  4874.8 1725.12  4894.5 1716.25
  4923.1 1698.61  4934.8  1694.2  4951.7 1690.72  4964.9 1689.55  4965.4 1689.05
  4986.8 1689.55  4986.9 1692.44  5000.5 1693.62  5034.8 1690.84  5037.3 1690.85
  5060.3    1697    5084 1699.87  5103.7 1703.87  5111.1 1704.53  5182.9 1707.84
  5206.9 1710.25  5232.3 1711.22  5292.6 1715.61  5375.7 1715.37  5430.4 1715.18
#Mann= 8 ,-1 , 0
  4597.2    .035       0  4663.9      .1       0  4763.6     .07       0
  4852.1      .1       0  4964.9     .05       0  4986.8      .1       0
  5034.8    .035       0  5375.7      .1       0
Bank Sta=4964.9,4986.8
XS Rating Curve= 0 ,0
Exp/Cntr=0.3,0.1

Type RM Length L Ch R = 1 ,22240   ,588,588,588
BEGIN DESCRIPTION:
Town Creek 39.0
END DESCRIPTION:
XS GIS Cut Line= 3
      1921274.98     13946724.97        1921075.       13946375.
      1920625.05     13946325.01
#Sta/Elev= 30
  4597.1 1744.18  4647.4 1741.48  4744.5 1736.82  4774.6 1734.85  4792.6 1731.11
  4802.3    1724  4809.2 1717.45  4819.5 1713.22  4835.6  1704.3  4856.3  1697.1
  4865.1 1691.99  4873.9 1689.22  4908.7 1687.82  4931.1 1688.77  4957.2 1686.85
  4957.7 1686.35  4979.1 1686.85  5020.9 1688.54    5033 1690.69  5060.1 1691.56
  5081.3 1695.16  5120.5 1698.14  5195.5 1698.96    5208  1697.7  5253.3 1698.76
  5277.5 1697.93  5334.8 1703.03  5374.1 1709.59  5401.2 1711.84  5452.9 1713.82
#Mann= 7 ,-1 , 0
  4597.1    .035       0  4647.4     .07       0  4744.5      .1       0
  4835.6     .07       0  4957.2     .05       0  4979.1     .07       0
  5195.5    .035       0
Bank Sta=4957.2,4979.1
XS Rating Curve= 0 ,0
Exp/Cntr=0.3,0.1

Type RM Length L Ch R = 1 ,21652   ,564,564,564
BEGIN DESCRIPTION:
Town Creek 38.0
END DESCRIPTION:
XS GIS Cut Line= 3
      1921074.98     13945725.01        1920725.       13945925.
        1920525.       13946275.
#Sta/Elev= 30
  4600.8 1708.59  4640.4 1708.39  4653.9 1707.81  4704.9 1706.55  4745.4 1696.07
  4762.7 1696.97  4783.4 1696.66  4804.8 1694.24  4842.2 1692.44  4890.5  1687.9
  4918.2 1687.27  4938.9 1685.79  4952.7  1686.3  4966.6 1684.62    4972  1682.8
  4972.5  1682.3  4993.4  1682.3  4993.9  1682.8  4994.2 1684.42  5001.1 1686.14
  5004.9 1688.45  5007.1 1690.98  5011.1 1694.15  5018.7 1698.85  5023.2 1700.08
  5042.3 1707.27  5063.6 1710.86  5234.9 1712.87  5370.2 1713.76    5407 1713.88
#Mann= 5 ,-1 , 0
  4600.8     .07       0  4653.9     .07       0    4972     .05       0
  4993.9     .07       0  5370.2      .1       0
Bank Sta=4972,4993.9
XS Rating Curve= 0 ,0
Exp/Cntr=0.3,0.1

Type RM Length L Ch R = 1 ,21088   ,572,572,572
BEGIN DESCRIPTION:
Town Creek 37.0
END DESCRIPTION:
XS GIS Cut Line= 3
        1921125.       13945575.        1920775.       13945375.
      1920375.03       13945425.
#Sta/Elev= 30
  4596.8 1708.27  4671.2 1707.46  4724.1 1706.11  4743.8  1705.8  4760.8 1703.51
  4771.8 1700.69  4805.9 1690.29  4864.7 1689.27  4875.1  1690.3  4897.1 1688.93
  4913.1 1689.29  4938.9 1687.31  4941.8 1686.47  4969.7 1683.02  4971.2 1680.42
  4971.7 1679.92  4992.7 1679.92  4993.2 1680.42  5014.6 1681.21  5020.7 1683.38
  5024.8  1685.5  5026.7 1686.31  5035.8 1693.64  5041.8 1702.16  5044.9 1704.12
    5063 1707.98  5090.2 1707.32  5221.6 1708.26  5280.7 1707.58    5403 1709.38
#Mann= 6 ,-1 , 0
  4596.8     .07       0  4724.1     .07       0  4971.2     .05       0
  4993.2     .07       0  5024.8    .035       0  5221.6     .07       0
Bank Sta=4971.2,4993.2
XS Rating Curve= 0 ,0
Exp/Cntr=0.3,0.1

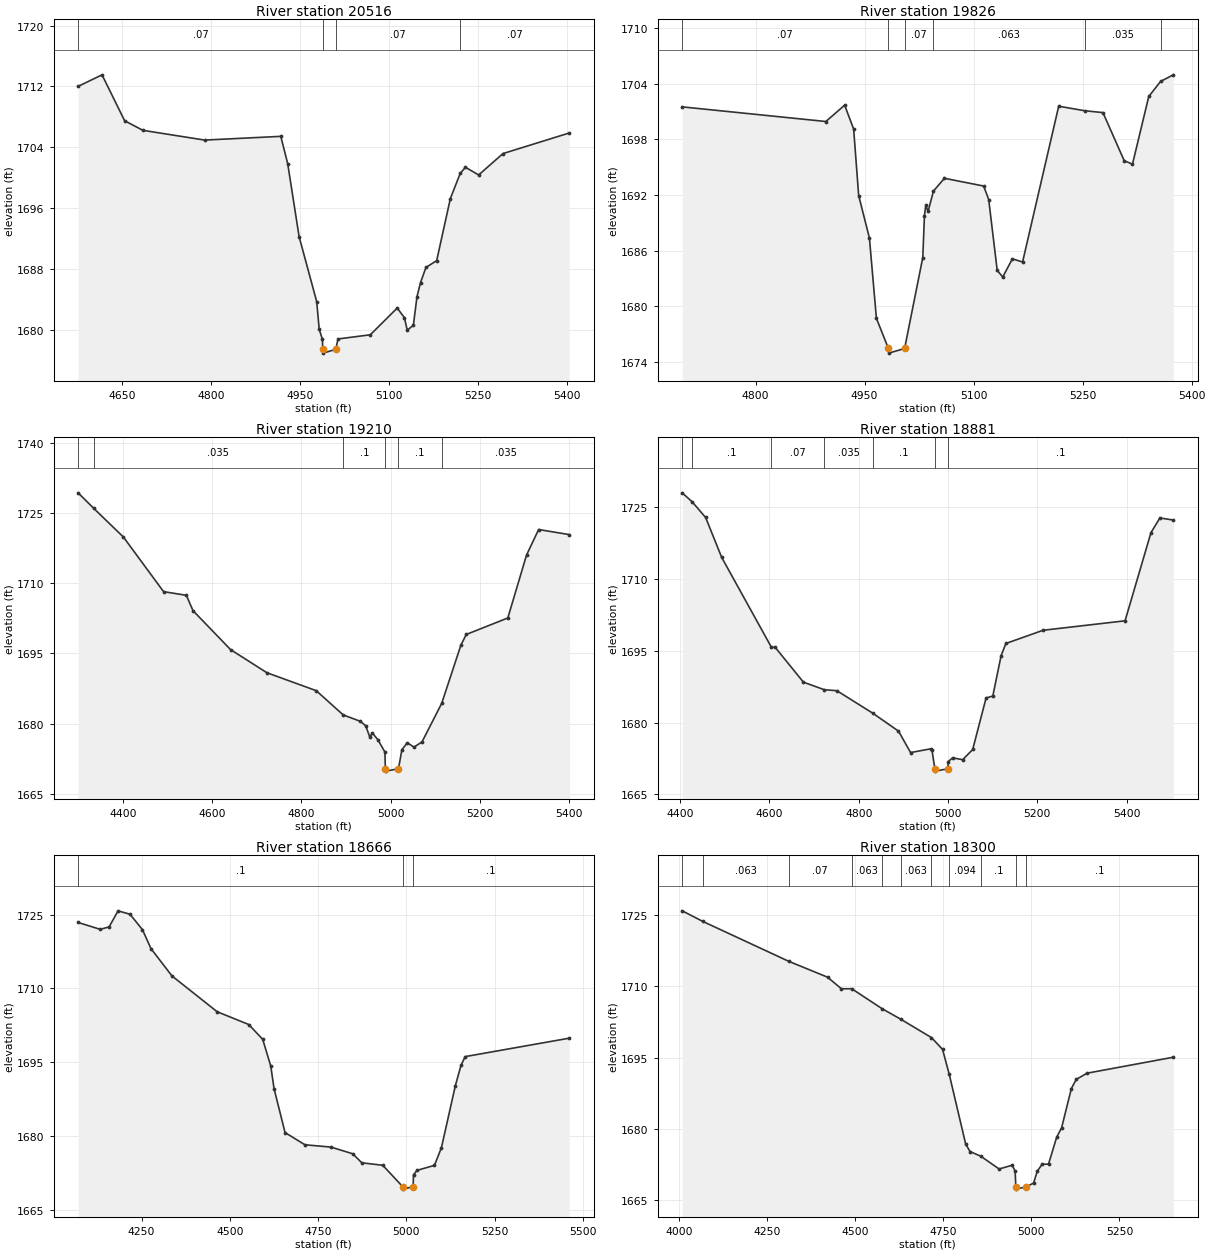
Type RM Length L Ch R = 1 ,20516   ,690,690,690
BEGIN DESCRIPTION:
Town Creek 36.0
END DESCRIPTION:
XS GIS Cut Line= 3
      1921274.98     13945174.98        1920975.       13944875.
      1920574.95     13944925.01
#Sta/Elev= 30
  4575.7 1712.01    4616 1713.53  4654.1  1707.5  4684.9 1706.24  4788.9 1704.96
  4917.2 1705.45  4928.9 1701.83    4948 1692.29  4977.7 1683.73  4981.9  1680.1
  4987.3  1678.8  4987.8 1677.48  4988.3 1676.98  5009.9 1677.48  5013.5 1678.84
    5068 1679.39  5113.3  1682.9  5125.4 1681.64  5130.2    1680  5140.5 1680.63
  5146.6 1684.38  5152.6 1686.25  5161.7 1688.23  5179.8 1689.13  5202.8 1697.27
  5219.4 1700.58  5228.2 1701.39  5250.5 1700.38  5291.5 1703.19  5403.1 1705.89
#Mann= 4 ,-1 , 0
  4575.7     .07       0  4987.8     .05       0  5009.9     .07       0
  5219.4     .07       0
Bank Sta=4987.8,5009.9
XS Rating Curve= 0 ,0
Exp/Cntr=0.3,0.1

Type RM Length L Ch R = 1 ,19826   ,616,616,616
BEGIN DESCRIPTION:
Town Creek 35.0
END DESCRIPTION:
XS GIS Cut Line= 3
      1921236.73     13944406.39       1921000.7     13944267.37
        1920625.       13944125.
#Sta/Elev= 30
  4699.1 1701.52  4896.7 1699.94  4922.6  1701.7    4935 1699.12  4941.9 1691.95
  4956.7 1687.35  4966.3 1678.69  4982.8 1675.43  4983.3 1674.93  5005.1 1675.43
  5030.1 1685.25  5032.4 1689.78  5034.2 1690.88  5037.4 1690.23  5044.8 1692.43
  5059.9 1693.81  5113.9 1692.97  5120.8 1691.51  5132.5 1683.86  5140.1 1683.15
  5153.4 1685.11  5167.4 1684.77  5217.1 1701.59  5253.1  1701.1    5278  1700.9
  5307.2 1695.71  5318.6 1695.33    5341 1702.64  5357.3 1704.27  5374.8 1704.98
#Mann= 6 ,-1 , 0
  4699.1     .07       0  4982.8     .05       0  5005.1     .07       0
  5044.8    .063       0  5253.1    .035       0  5357.3     .07       0
#XS Ineff= 2 , 0
                         5060.34         1693.75
Permanent Ineff=
       F       F
Bank Sta=4982.8,5005.1
XS Rating Curve= 0 ,0
Exp/Cntr=0.3,0.1

Type RM Length L Ch R = 1 ,19210   ,329,329,329
BEGIN DESCRIPTION:
Town Creek 34.0
END DESCRIPTION:
XS GIS Cut Line= 3
      1921675.02       13943725.      1920985.26     13943702.88
      1920574.97       13943725.
#Sta/Elev= 30
  4299.6  1729.4  4334.3 1726.11  4401.2 1719.93  4491.2 1708.24  4542.2 1707.46
  4557.2 1704.17  4641.3 1695.84  4722.8 1690.88  4833.4 1687.04  4893.9 1681.85
  4932.4 1680.47  4944.4 1679.51  4953.4 1677.14  4959.4 1677.97  4971.5 1676.55
  4987.4  1673.9  4988.4 1670.31  4988.9 1669.81  5017.8 1670.31  5025.5  1674.4
  5037.5 1675.88  5052.6 1674.95  5070.6 1676.07  5114.8 1684.34  5157.7 1696.77
  5169.7 1699.07  5262.9  1702.6  5304.9 1716.08    5332 1721.54  5400.6 1720.46
#Mann= 6 ,-1 , 0
  4299.6     .07       0  4334.3    .035       0  4893.9      .1       0
  4988.4     .05       0  5017.8      .1       0  5114.8    .035       0
Bank Sta=4988.4,5017.8
XS Rating Curve= 0 ,0
Exp/Cntr=0.3,0.1

Type RM Length L Ch R = 1 ,18881   ,215,215,215
BEGIN DESCRIPTION:
Town Creek 33.0
END DESCRIPTION:
XS GIS Cut Line= 3
      1921574.97       13943375.        1920975.       13943375.
      1920575.06     13943674.96
#Sta/Elev= 30
  4404.6 1728.02  4426.7 1726.16  4457.1 1722.87  4493.1 1714.52  4604.2 1695.79
  4613.1 1695.71  4676.1 1688.46  4722.5 1686.89  4751.1 1686.67  4831.8 1681.95
    4889 1678.23  4916.1 1673.75  4961.1 1674.53  4964.1 1674.21  4970.4 1670.37
  4970.9 1669.87  4999.8 1670.37  5000.1 1671.84  5010.2 1672.65  5032.7 1672.26
  5055.2 1674.39  5085.2 1685.17  5100.2 1685.55  5118.9 1694.03  5129.5 1696.54
  5212.7  1699.3  5396.4 1701.28  5454.5 1719.72  5474.5 1722.77  5504.5 1722.33
#Mann= 7 ,-1 , 0
  4404.6     .07       0  4426.7      .1       0  4604.2     .07       0
  4722.5    .035       0  4831.8      .1       0  4970.4     .05       0
  4999.8      .1       0
Bank Sta=4970.4,4999.8
XS Rating Curve= 0 ,0
Exp/Cntr=0.3,0.1

Type RM Length L Ch R = 1 ,18666   ,366,366,366
BEGIN DESCRIPTION:
Town Creek 32.1
END DESCRIPTION:
XS GIS Cut Line= 2
      1921730.16     13942569.15      1920674.92     13943476.05
#Sta/Elev= 30
  4070.2 1723.39  4132.8 1721.99  4158.1 1722.49  4183.5 1725.75  4217.4 1725.05
  4252.5 1721.92  4276.7 1718.07  4336.1 1712.53  4464.2 1705.25  4553.6 1702.66
  4593.2 1699.65  4616.1  1694.2  4625.3 1689.65  4656.5 1680.71  4712.8 1678.23
  4786.4 1677.76  4848.4  1676.4  4873.9 1674.57  4933.4 1674.06  4989.8 1669.72
  4990.3 1669.22  5019.3 1669.72  5020.4 1672.13  5030.4 1673.03  5079.8 1674.05
  5099.5 1677.64  5139.1 1690.26  5154.9 1694.34  5166.8 1696.14  5461.6 1699.88
#Mann= 3 ,-1 , 0
  4070.2      .1       0  4989.8     .05       0  5019.3      .1       0
Bank Sta=4989.8,5019.3
XS Rating Curve= 0 ,0
Exp/Cntr=0.3,0.1

Type RM Length L Ch R = 1 ,18300   ,565,565,565
BEGIN DESCRIPTION:
Town Creek 32.0
END DESCRIPTION:
XS GIS Cut Line= 3
      1921794.66     13942142.92        1921075.       13942825.
      1920725.04     13943024.98
#Sta/Elev= 30
  4008.5 1725.82  4067.2 1723.59    4311 1715.22  4421.4 1711.88  4460.7 1709.45
    4490 1709.46  4576.3 1705.26  4628.4 1703.09  4716.4  1699.2  4747.8 1696.72
  4766.7 1691.52  4813.3 1676.89  4825.7 1675.28  4856.4 1674.29  4908.4 1671.61
  4945.6  1672.4  4953.9 1671.17  4955.9 1667.88  4956.4 1667.38    4986 1667.88
  5006.4 1668.66  5016.7 1671.14  5030.5 1672.59  5048.7 1672.64    5072 1678.31
  5085.8 1680.24  5113.5 1688.48  5127.3 1690.42  5158.4 1691.73  5403.1 1695.08
#Mann= 11 ,-1 , 0
  4008.5     .07       0  4067.2    .063       0    4311     .07       0
    4490    .063       0  4576.3     .07       0  4628.4    .063       0
  4716.4    .035       0  4766.7    .094       0  4856.4      .1       0
  4955.9     .05       0    4986      .1       0
Bank Sta=4955.9,4986
XS Rating Curve= 0 ,0
Exp/Cntr=0.3,0.1

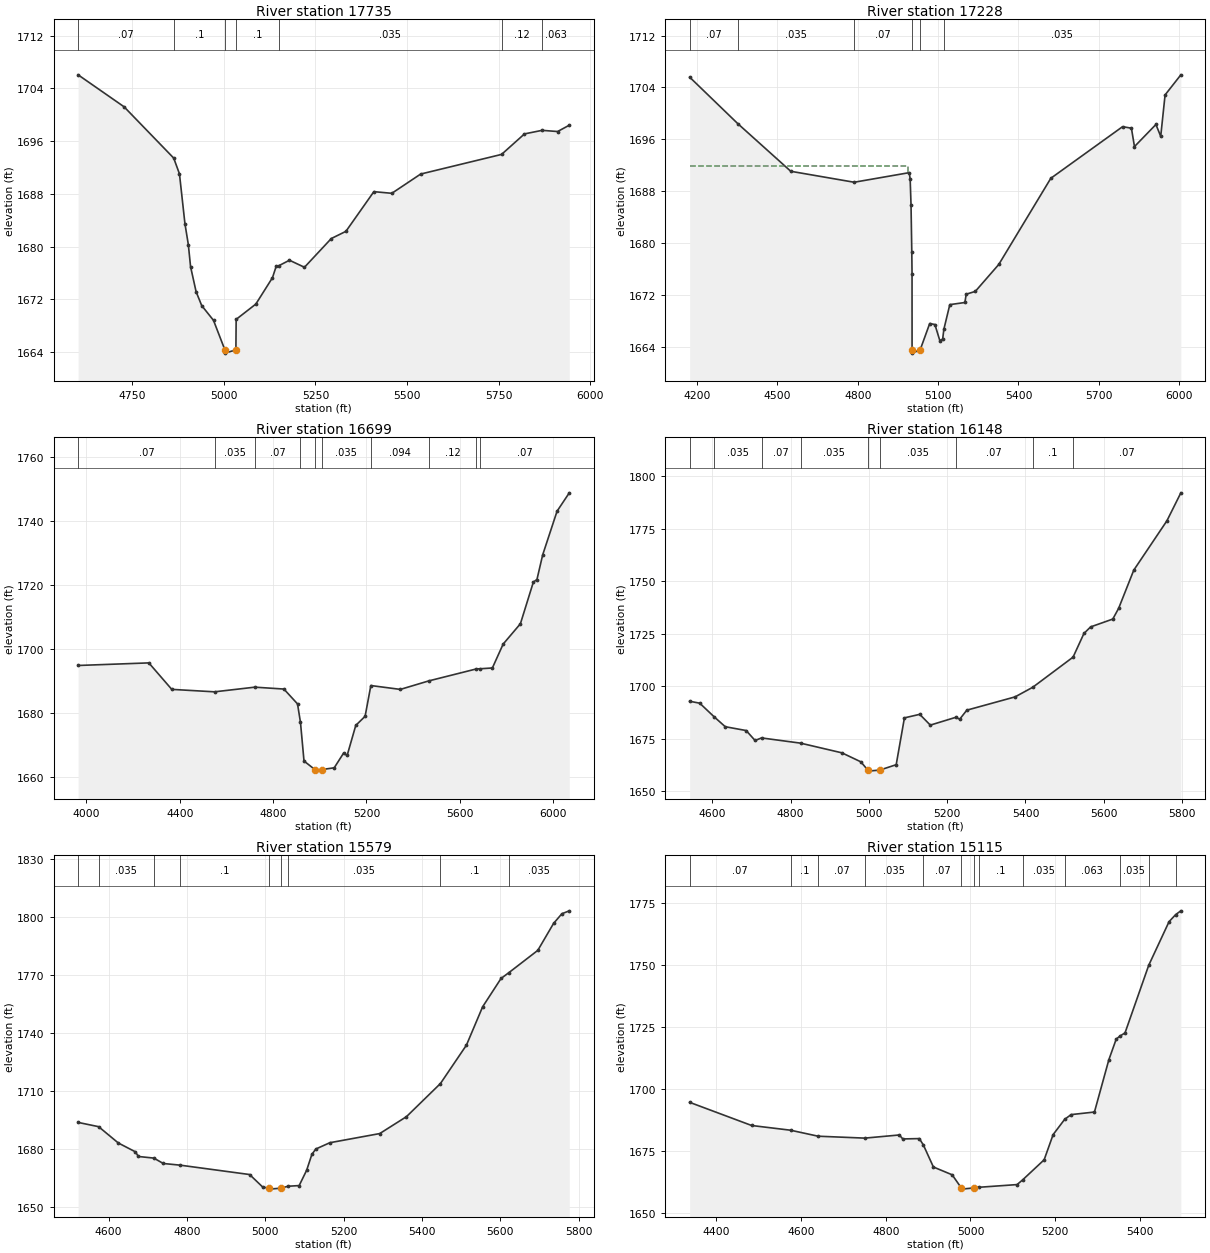
Type RM Length L Ch R = 1 ,17735   ,507,507,507
BEGIN DESCRIPTION:
Town Creek 31.0
END DESCRIPTION:
XS GIS Cut Line= 3
      1921425.01       13942325.        1921025.       13942275.
       1920310.2     13942881.26
#Sta/Elev= 30
  4602.3 1706.06  4727.8 1701.21  4863.2 1693.43  4878.9 1691.04  4893.9 1683.46
  4903.1 1680.32  4909.2 1676.96  4924.3 1673.17  4939.6 1671.06  4971.8 1668.82
  5002.8 1664.35  5003.3 1663.85  5032.9 1664.35  5033.6 1668.97  5087.3 1671.29
  5132.7 1675.29    5143 1677.04  5150.5 1677.12  5179.1 1677.94    5220 1676.87
  5293.2 1681.23  5333.1 1682.32  5409.4 1688.34  5458.4 1688.09  5537.1 1691.01
  5757.9 1693.99  5820.4  1697.1  5868.5 1697.64  5910.8 1697.46  5942.7 1698.42
#Mann= 7 ,-1 , 0
  4602.3     .07       0  4863.2      .1       0  5002.8     .05       0
  5032.9      .1       0  5150.5    .035       0  5757.9     .12       0
  5868.5    .063       0
Bank Sta=5002.8,5032.9
XS Rating Curve= 0 ,0
Exp/Cntr=0.3,0.1

Type RM Length L Ch R = 1 ,17228   ,529,529,529
BEGIN DESCRIPTION:
Town Creek 30.0
END DESCRIPTION:
XS GIS Cut Line= 3
      1921595.19     13941802.07        1920775.       13941875.
      1919979.17     13942498.15
#Sta/Elev= 30
  4172.2 1705.59  4351.9 1698.42  4549.8 1691.07  4786.5 1689.38  4992.1 1690.86
  4995.6 1689.86  4998.8 1685.91  5001.7 1678.55  5002.6  1675.3  5002.7 1663.52
  5003.2 1663.02  5032.9 1663.52  5068.6 1667.59    5088 1667.43  5106.4 1664.95
    5117 1665.19  5121.4 1666.69  5143.6  1670.5    5200 1670.83  5204.8 1672.11
  5238.8 1672.54  5326.5  1676.7  5520.8 1689.99  5788.7 1697.95  5821.8 1697.72
  5833.2 1694.88  5913.3 1698.29  5931.2 1696.46  5947.5 1702.85  6006.4 1705.95
#Mann= 6 ,-1 , 0
  4172.2     .07       0  4351.9    .035       0  4786.5     .07       0
  5002.7     .05       0  5032.9     .07       0  5121.4    .035       0
#XS Ineff= 2 , 0
         4986.51 1691.84
Permanent Ineff=
       F       F
Bank Sta=5002.7,5032.9
XS Rating Curve= 0 ,0
Exp/Cntr=0.3,0.1

Type RM Length L Ch R = 1 ,16699   ,551,551,551
BEGIN DESCRIPTION:
Town Creek 29.0
END DESCRIPTION:
XS GIS Cut Line= 3
      1921394.46     13941338.47        1920375.       13941575.
      1919344.49     13941815.29
#Sta/Elev= 30
  3964.7 1694.87  4267.8 1695.68    4366 1687.39  4549.3 1686.62  4721.8 1688.08
  4846.5 1687.49  4904.9 1682.84  4917.6 1677.02  4932.7 1664.95  4979.1 1662.29
  4979.6 1661.79  5009.5 1662.29  5062.1 1662.83  5102.1 1667.41  5117.5  1666.7
  5154.5 1676.11  5194.5 1678.96  5219.1 1688.59  5345.5 1687.38  5467.2 1690.04
  5671.2 1693.79  5685.4 1693.83  5739.8 1694.09    5786 1701.57  5859.9 1707.93
  5915.4 1720.98  5930.8 1721.79  5955.4 1729.51    6017 1743.18  6069.4 1748.93
#Mann= 10 ,-1 , 0
  3964.7     .07       0  4549.3    .035       0  4721.8     .07       0
  4917.6    .035       0  4979.1    .035       0  5009.5    .035       0
  5219.1    .094       0  5467.2     .12       0  5671.2      .1       0
  5685.4     .07       0
Bank Sta=4979.1,5009.5
XS Rating Curve= 0 ,0
Exp/Cntr=0.3,0.1

Type RM Length L Ch R = 1 ,16148   ,569,569,569
BEGIN DESCRIPTION:
Town Creek 28.0
END DESCRIPTION:
XS GIS Cut Line= 3
      1920624.97       13941075.        1920175.       13941125.
        1919375.       13941075.
#Sta/Elev= 30
  4542.5 1692.74  4568.2 1691.83  4604.6 1685.41  4633.4 1680.62  4686.8  1678.8
  4709.5 1674.07    4726 1675.28  4825.6  1672.8  4931.3 1668.18  4979.6  1663.9
  4997.5 1659.97    4998 1659.47    5028 1659.97  5069.9 1662.53  5090.9 1684.83
    5130 1686.52    5157 1681.38  5221.6 1685.07  5232.2 1684.23  5250.2  1688.5
  5373.5 1694.83  5418.7 1699.42  5521.6 1713.77  5549.3 1725.03  5566.3 1728.15
    5623 1731.89    5638 1737.03  5676.6  1755.2  5761.2 1778.69  5796.8 1792.01
#Mann= 9 ,-1 , 0
  4542.5     .07       0  4604.6    .035       0    4726     .07       0
  4825.6    .035       0  4997.5    .035       0    5028    .035       0
  5221.6     .07       0  5418.7      .1       0  5521.6     .07       0
Bank Sta=4997.5,5028
XS Rating Curve= 0 ,0
Exp/Cntr=0.3,0.1

Type RM Length L Ch R = 1 ,15579   ,464,464,464
BEGIN DESCRIPTION:
Town Creek 27.0
END DESCRIPTION:
XS GIS Cut Line= 3
      1920675.02     13940875.01        1920275.       13940625.
      1919925.02     13939925.04
#Sta/Elev= 30
  4521.9 1693.86  4574.3 1691.66  4624.6 1683.24  4668.2 1678.68  4675.8 1676.28
  4715.2 1675.45  4739.5 1672.66  4782.5  1671.8  4959.9 1666.96  4993.6 1660.44
  5009.6 1659.93  5010.1 1659.43  5040.3 1659.93  5057.9 1660.92  5086.4 1661.26
  5105.5 1669.16  5118.9 1677.38  5128.9 1680.13  5164.7 1683.38  5292.1  1688.1
  5360.4 1696.83  5447.1 1713.91  5513.5 1733.73  5554.9 1753.53  5601.9 1768.15
  5621.8 1771.14  5695.8 1782.66    5736 1796.55  5757.2 1801.55  5776.2 1803.06
#Mann= 9 ,-1 , 0
  4521.9     .07       0  4574.3    .035       0  4715.2     .07       0
  4782.5      .1       0  5009.6     .05       0  5040.3      .1       0
  5057.9    .035       0  5447.1      .1       0  5621.8    .035       0
Bank Sta=5009.6,5040.3
XS Rating Curve= 0 ,0
Exp/Cntr=0.3,0.1

Type RM Length L Ch R = 1 ,15115   ,624,624,624
BEGIN DESCRIPTION:
Town Creek 26.0
END DESCRIPTION:
XS GIS Cut Line= 3
      1921125.01     13940575.01      1920517.57     13940245.64
      1920175.01     13939925.01
#Sta/Elev= 30
  4336.8 1694.45  4483.2 1685.11    4575 1683.21  4640.3 1680.79  4750.5 1680.02
    4832 1681.29  4840.2 1679.69  4879.3 1679.83  4889.1 1677.16  4912.5 1668.37
  4956.8 1665.23  4978.4 1659.95  4978.9 1659.45  5009.1 1659.95  5020.2  1660.2
  5110.1 1661.28  5123.1 1663.15  5174.1 1671.28  5195.3 1681.44  5222.5 1687.58
  5237.7  1689.5  5292.9 1690.54  5326.9 1711.61  5344.3 1719.95  5353.6 1721.23
  5365.1 1722.45  5421.1 1749.72  5469.1  1767.3  5484.7 1770.15    5497 1771.68
#Mann= 13 ,-1 , 0
  4336.8     .07       0    4575      .1       0  4640.3     .07       0
  4750.5    .035       0  4889.1     .07       0  4978.4     .05       0
  5009.1     .07       0  5020.2      .1       0  5123.1    .035       0
  5222.5    .063       0  5353.6    .035       0  5421.1      .1       0
  5484.7    .035       0
Bank Sta=4978.4,5009.1
XS Rating Curve= 0 ,0
Exp/Cntr=0.3,0.1