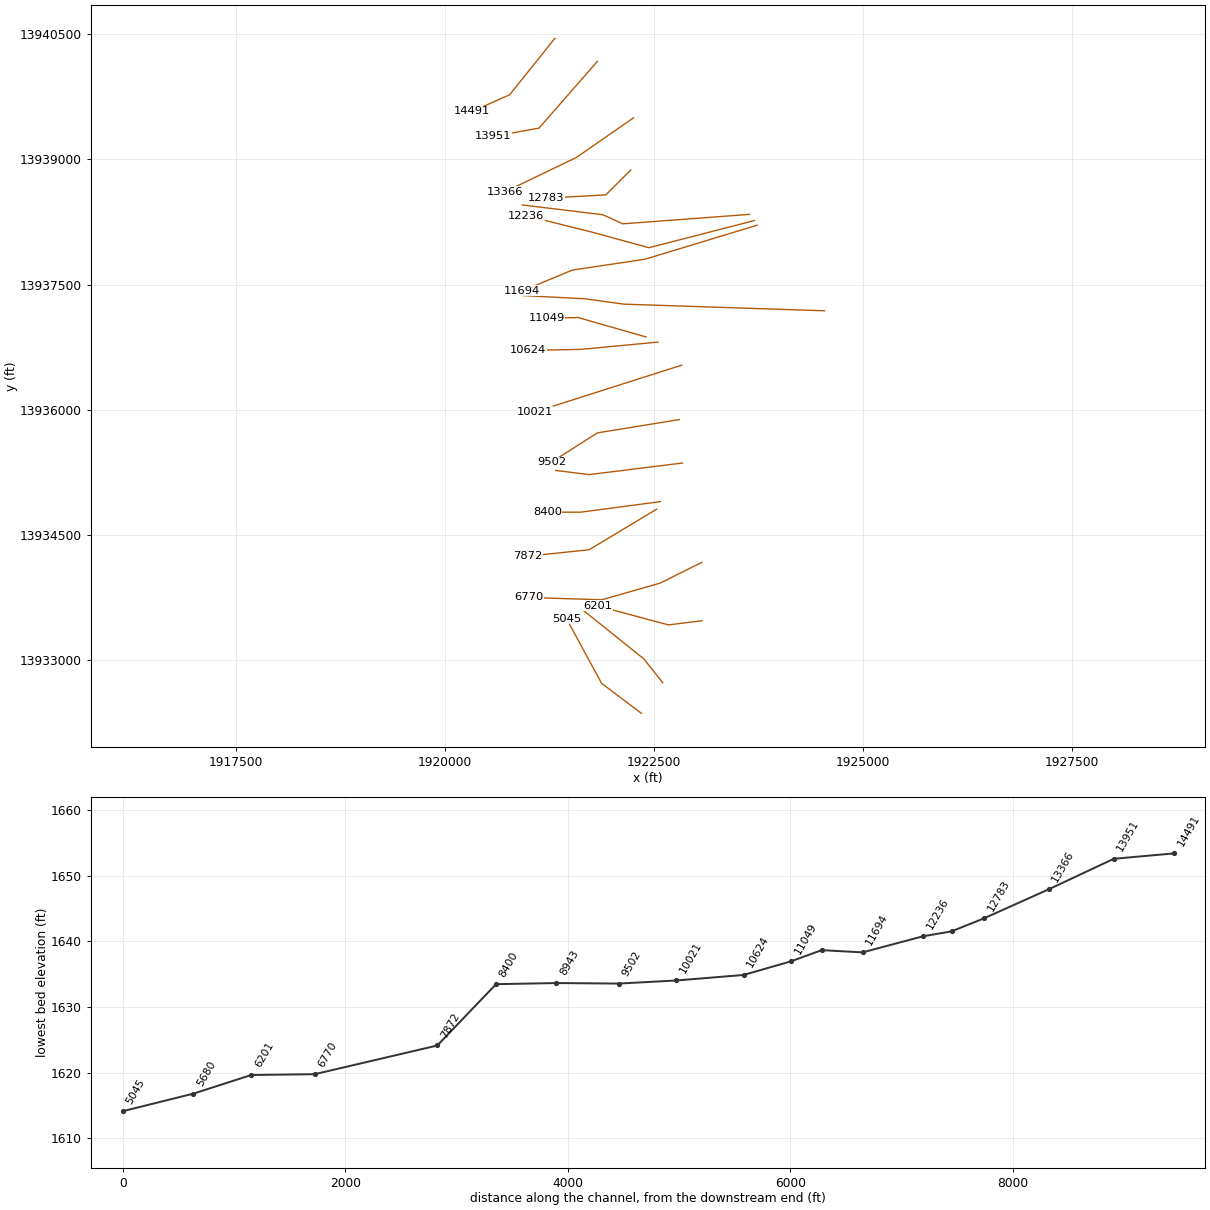
HEC-RAS study Town Creek.prj: Town Creek Base Level Engineering

--- Town Creek.g01 (geometry) --- (continued)

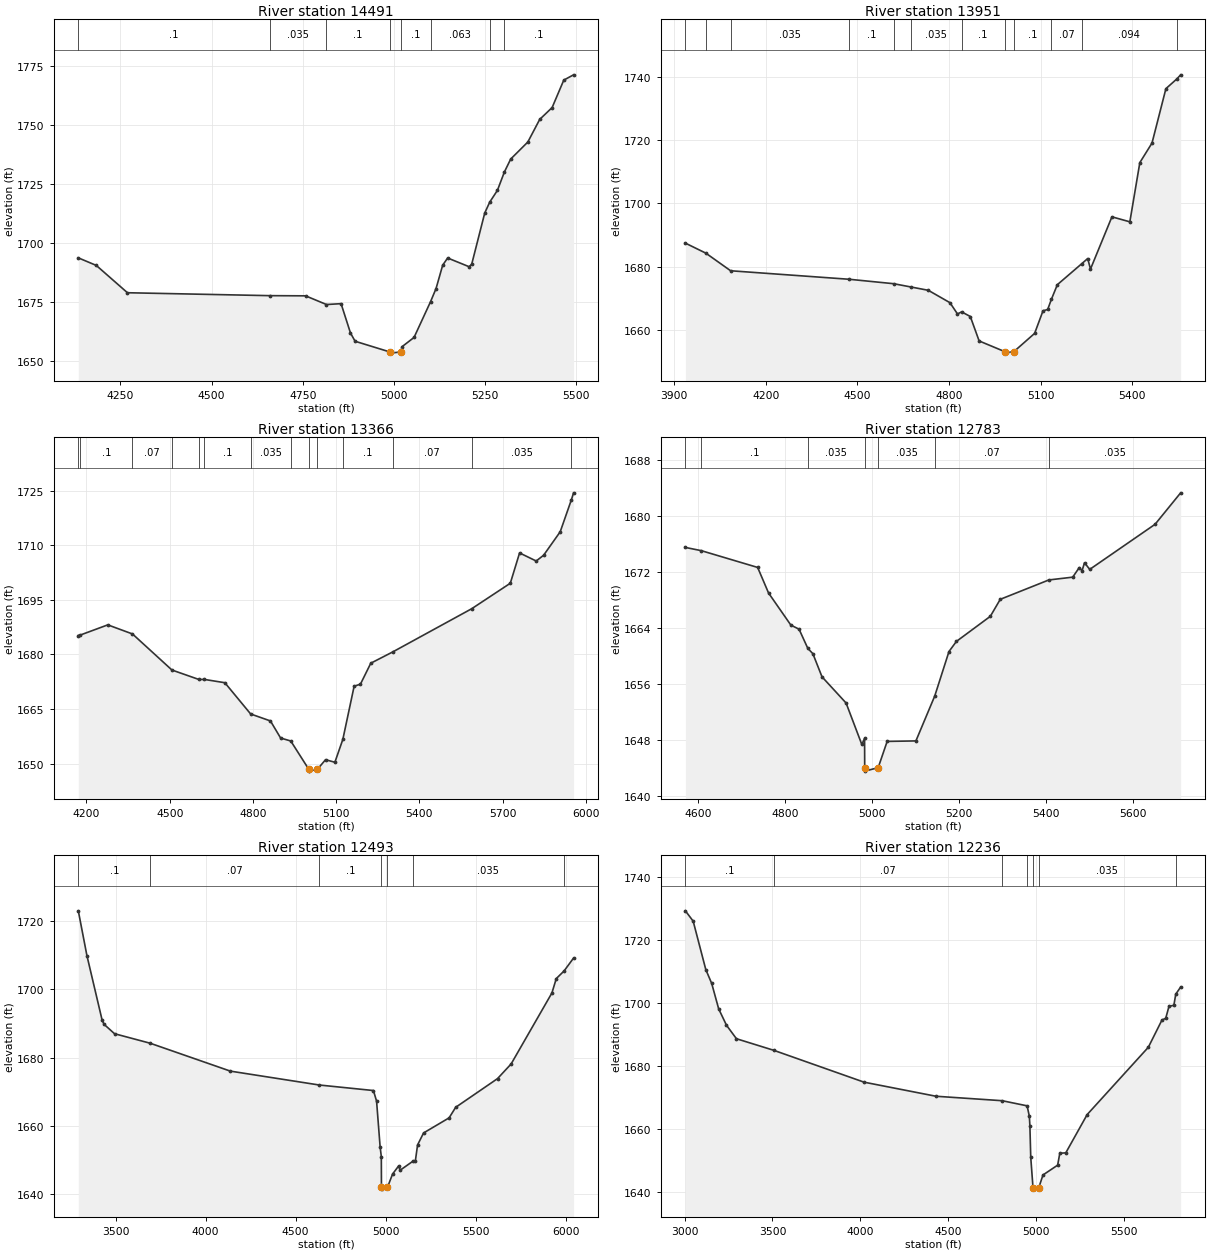
Type RM Length L Ch R = 1 ,14491   ,540,540,540
BEGIN DESCRIPTION:
Town Creek 25.0
END DESCRIPTION:
XS GIS Cut Line= 3
      1921315.58     13940450.25        1920775.       13939775.
      1920325.02     13939575.01
#Sta/Elev= 30
  4134.8 1693.69  4184.1 1690.49  4269.5 1678.94  4658.9 1677.71  4757.7 1677.63
    4815 1673.96    4855 1674.32  4880.7 1661.95  4893.4 1658.43  4988.6 1653.91
  4989.1 1653.41  5019.4 1653.91  5022.1 1656.13    5055 1660.04  5100.2 1675.15
  5115.3 1680.71  5133.5 1690.59  5147.1 1693.63    5206 1689.94  5213.1 1691.04
  5248.7 1712.62  5262.4 1717.24  5283.5 1722.23  5302.7 1730.02  5319.9 1735.46
  5366.9 1742.67  5399.4 1752.22  5433.5 1757.24  5465.4 1768.84  5492.2 1771.07
#Mann= 8 ,-1 , 0
  4134.8      .1       0  4658.9    .035       0    4815      .1       0
  4988.6     .05       0  5019.4      .1       0  5100.2    .063       0
  5262.4    .094       0  5302.7      .1       0
Bank Sta=4988.6,5019.4
XS Rating Curve= 0 ,0
Exp/Cntr=0.3,0.1

Type RM Length L Ch R = 1 ,13951   ,585,585,585
BEGIN DESCRIPTION:
Town Creek 24.0
END DESCRIPTION:
XS GIS Cut Line= 3
      1921824.98     13940174.98        1921125.       13939375.
        1920575.       13939275.
#Sta/Elev= 30
    3937 1687.43  4004.1 1684.25  4085.1 1678.68  4473.9 1675.98  4619.2 1674.58
  4676.2 1673.53  4732.5 1672.49  4803.4 1668.57  4828.1    1665  4841.8 1665.66
  4870.1 1664.19    4899 1656.45  4982.3 1653.09  4982.8 1652.59  5013.1 1653.09
  5080.8 1658.85  5108.2 1665.99  5123.5 1666.41  5135.9 1669.69  5155.2 1674.27
  5235.5 1680.95  5254.6 1682.55  5263.7 1679.21  5333.9 1695.76  5392.6 1694.18
  5425.3 1712.93  5465.2 1719.13  5510.7 1736.36  5546.5 1739.44    5559 1740.74
#Mann= 12 ,-1 , 0
    3937    .063       0  4004.1      .1       0  4085.1    .035       0
  4473.9      .1       0  4619.2    .063       0  4676.2    .035       0
  4841.8      .1       0  4982.3     .05       0  5013.1      .1       0
  5135.9     .07       0  5235.5    .094       0  5546.5      .1       0
Bank Sta=4982.3,5013.1
XS Rating Curve= 0 ,0
Exp/Cntr=0.3,0.1

Type RM Length L Ch R = 1 ,13366   ,583,583,583
BEGIN DESCRIPTION:
Town Creek 23.0
END DESCRIPTION:
XS GIS Cut Line= 3
      1922256.62     13939497.76        1921575.       13939025.
      1920714.24     13938609.32
#Sta/Elev= 30
  4170.5 1685.21  4177.9 1685.35  4276.8 1688.14  4365.8 1685.64    4508 1675.73
  4605.3 1673.13  4625.2 1673.14  4698.8 1672.24  4791.8 1663.65  4863.2 1661.73
  4899.8 1657.04  4936.5 1656.22  5001.4 1648.44  5001.9 1647.94  5032.4 1648.44
  5061.8 1651.08  5095.5 1650.38  5124.2 1656.68  5164.9 1671.28  5187.6 1671.84
  5224.9  1677.6  5303.5 1680.68  5588.6 1692.57  5727.9 1699.58  5761.3 1707.91
  5821.2 1705.69  5847.9 1707.27  5907.8 1713.73  5948.4 1722.59  5955.9 1724.43
#Mann= 14 ,-1 , 0
  4170.5     .07       0  4177.9      .1       0  4365.8     .07       0
    4508      .1       0  4605.3     .07       0  4625.2      .1       0
  4791.8    .035       0  4936.5     .07       0  5001.4     .05       0
  5032.4     .07       0  5124.2      .1       0  5303.5     .07       0
  5588.6    .035       0  5948.4      .1       0
Bank Sta=5001.4,5032.4
XS Rating Curve= 0 ,0
Exp/Cntr=0.3,0.1

Type RM Length L Ch R = 1 ,12783   ,290,290,290
BEGIN DESCRIPTION:
Town Creek 22.0
END DESCRIPTION:
XS GIS Cut Line= 3
      1922224.97     13938874.97        1921925.       13938575.
      1921211.79     13938535.99
#Sta/Elev= 30
  4570.9  1675.5  4607.4 1675.04    4737 1672.64  4762.1 1668.98  4813.4 1664.39
  4832.2 1663.81  4852.2 1661.08    4864  1660.3  4884.9    1657  4940.3 1653.25
  4976.4 1647.33  4982.8 1648.18  4983.1 1644.01  4983.6 1643.51  5014.1 1644.01
  5034.7 1647.76  5100.8 1647.83  5144.1 1654.25  5176.8 1660.61  5193.9 1662.06
  5271.9 1665.65  5294.7 1668.08  5406.4 1670.85  5461.3 1671.25  5476.3 1672.62
  5482.7 1672.16  5488.4 1673.31  5500.4 1672.36  5650.6 1678.81  5709.4 1683.31
#Mann= 7 ,-1 , 0
  4570.9     .07       0  4607.4      .1       0  4852.2    .035       0
  4983.1    .035       0  5014.1    .035       0  5144.1     .07       0
  5406.4    .035       0
Bank Sta=4983.1,5014.1
XS Rating Curve= 0 ,0
Exp/Cntr=0.3,0.1

Type RM Length L Ch R = 1 ,12493   ,257,257,257
BEGIN DESCRIPTION:
Town Creek 21.1
END DESCRIPTION:
XS GIS Cut Line= 4
      1923643.17     13938341.65      1922128.45     13938228.81
      1921889.73     13938337.32      1920926.17     13938454.51
#Sta/Elev= 30
  3292.7 1722.98  3340.6 1709.87  3424.7 1691.07  3435.8 1689.77  3493.9 1687.02
  3692.3 1684.23  4137.7 1676.07  4631.2 1672.01  4932.5 1670.39    4950 1667.29
  4969.7  1653.9  4976.3 1651.07  4977.1 1642.04  4977.7 1641.54  5010.3 1642.04
  5038.9 1645.95  5071.9 1648.28  5081.1 1647.08  5150.6 1649.66  5165.7 1649.88
  5177.8 1654.47  5211.1 1657.98  5353.1  1662.4  5389.4 1665.48  5622.1 1673.88
  5697.6 1678.17  5924.3 1698.95  5948.4 1703.15  5991.9 1705.39  6044.5 1709.16
#Mann= 7 ,-1 , 0
  3292.7      .1       0  3692.3     .07       0  4631.2      .1       0
  4977.1     .05       0  5010.3      .1       0  5150.6    .035       0
  5991.9    .094       0
Bank Sta=4977.1,5010.3
XS Rating Curve= 0 ,0
Exp/Cntr=0.3,0.1

Type RM Length L Ch R = 1 ,12236   ,542,542,542
BEGIN DESCRIPTION:
Town Creek 21.0
END DESCRIPTION:
XS GIS Cut Line= 4
      1923704.46     13938267.96      1922441.48     13937942.55
        1921775.       13938125.      1920975.05     13938324.99
#Sta/Elev= 30
  3004.5  1729.3  3048.8 1726.01  3120.7 1710.61  3154.2 1706.22  3194.1  1698.1
  3238.5 1692.91  3295.2 1688.62  3508.2 1684.93  4021.6 1674.81  4431.1 1670.33
  4808.2 1668.91  4950.1 1667.28  4962.9 1663.93  4965.9 1660.93  4970.8 1650.89
  4983.6 1641.29  4984.2 1640.79  5016.8 1641.29  5040.4 1645.29  5123.9 1648.41
  5136.3  1652.2  5170.3 1652.33    5292  1664.5  5640.3 1685.91  5717.7 1694.55
  5739.3 1695.12  5757.9 1698.93  5785.7 1699.27  5796.5  1702.8  5824.3 1705.07
#Mann= 7 ,-1 , 0
  3004.5      .1       0  3508.2     .07       0  4808.2      .1       0
  4950.1    .035       0  4983.6    .035       0  5016.8    .035       0
  5796.5    .094       0
Bank Sta=4983.6,5016.8
XS Rating Curve= 0 ,0
Exp/Cntr=0.3,0.1

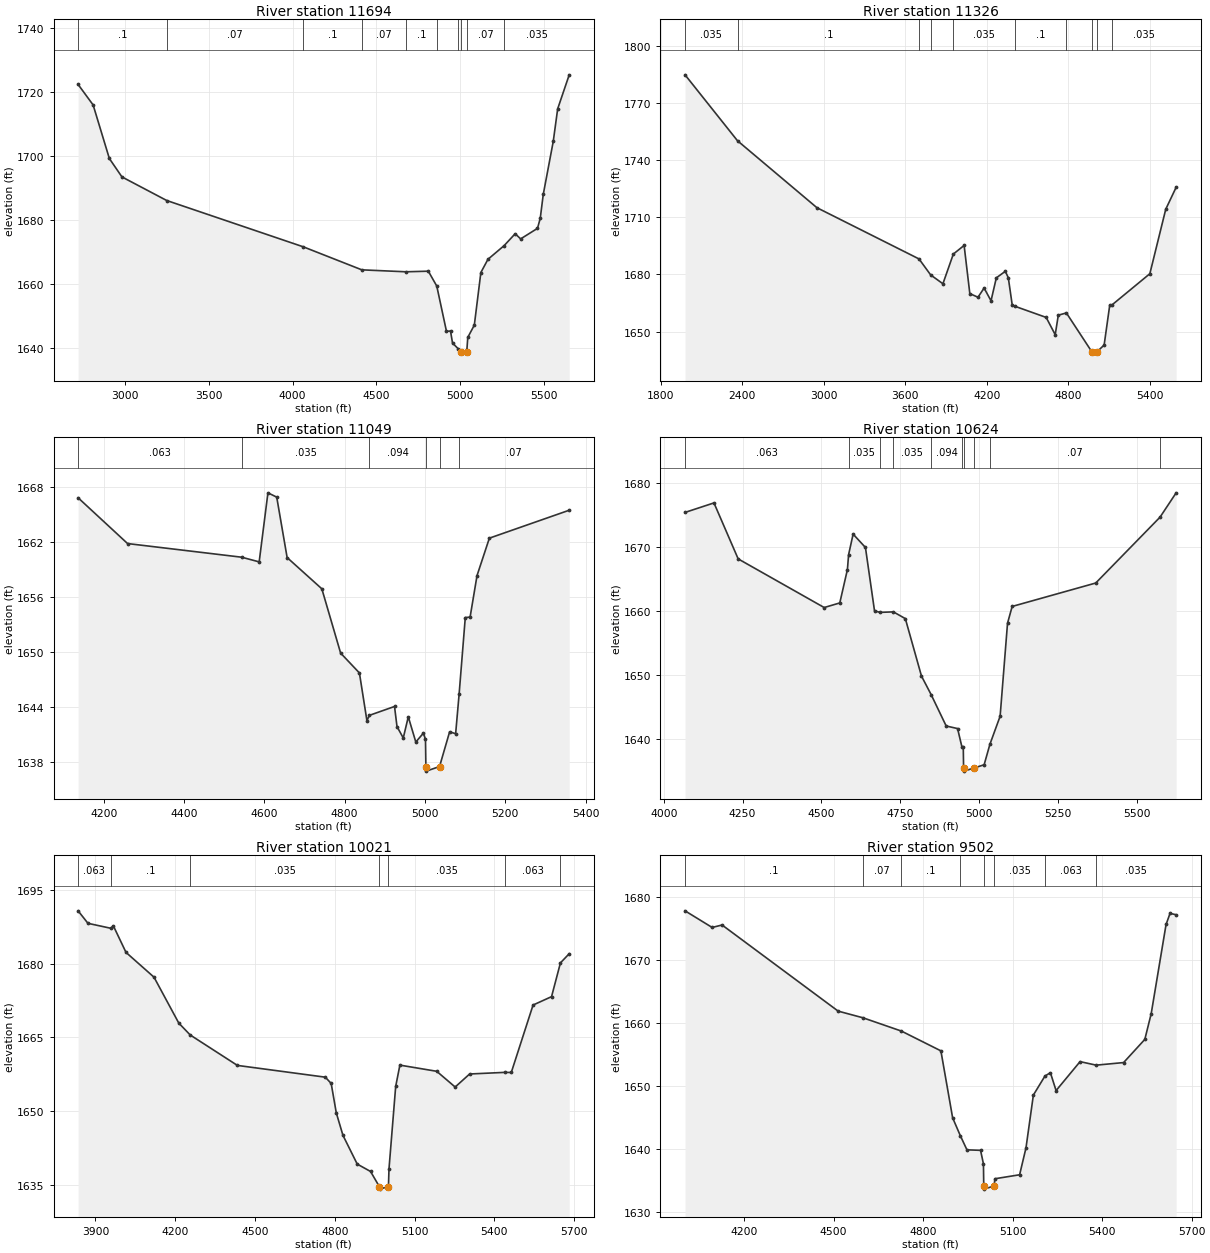
Type RM Length L Ch R = 1 ,11694   ,368,368,368
BEGIN DESCRIPTION:
Town Creek 20.0
END DESCRIPTION:
XS GIS Cut Line= 4
      1923734.87     13938211.54      1922393.58     13937804.41
        1921525.       13937675.      1920924.99     13937424.99
#Sta/Elev= 30
  2720.1 1722.48  2809.8 1716.05  2906.5 1699.29  2981.7 1693.52    3249 1686.13
    4064 1671.62  4412.8 1664.42  4676.4 1663.81  4809.5    1664  4859.9 1659.34
  4917.7 1645.18  4941.8 1645.26    4954 1641.48  4987.1 1639.75  5005.5 1638.84
  5006.1 1638.34  5038.8 1638.84  5044.9 1643.27  5083.9 1647.11  5122.9 1663.58
  5165.2 1667.72  5261.6    1672  5327.7 1675.73  5360.2 1674.11  5460.7 1677.41
  5477.2 1680.56  5495.1 1688.02  5554.8 1704.64  5581.2 1714.85    5650 1725.49
#Mann= 10 ,-1 , 0
  2720.1      .1       0    3249     .07       0    4064      .1       0
  4412.8     .07       0  4676.4      .1       0  4859.9    .094       0
  4987.1     .07       0  5005.5     .05       0  5038.8     .07       0
  5261.6    .035       0
Bank Sta=5005.5,5038.8
XS Rating Curve= 0 ,0
Exp/Cntr=0.3,0.1

Type RM Length L Ch R = 1 ,11326   ,277,277,277
BEGIN DESCRIPTION:
Town Creek 19.1
END DESCRIPTION:
XS GIS Cut Line= 4
       1924542.1     13937187.23      1922142.13     13937266.54
      1921668.52      13937331.4      1920933.11     13937369.41
#Sta/Elev= 30
  1978.2 1784.86  2364.5 1750.23  2949.3 1715.06  3700.8 1688.16  3786.7 1679.75
  3876.8 1675.12  3953.5 1690.72  4032.9 1695.25  4074.9 1669.95    4135 1668.03
    4180 1672.86    4231 1666.17    4270 1678.22  4336.1 1681.65  4358.2 1678.29
  4387.2 1663.88  4409.2 1663.23    4637 1657.44  4703.6 1648.36  4726.3 1658.62
  4785.8 1659.79    4975 1639.18  4975.6 1638.68  5008.3 1639.18  5063.8 1642.94
  5105.1 1663.96  5118.8 1663.84  5400.2 1680.38  5517.4 1714.27  5593.9  1725.8
#Mann= 10 ,-1 , 0
  1978.2    .035       0  2364.5      .1       0  3700.8    .035       0
  3786.7    .063       0  3953.5    .035       0  4409.2      .1       0
  4785.8    .094       0    4975     .05       0  5008.3    .094       0
  5118.8    .035       0
Bank Sta=4975,5008.3
XS Rating Curve= 0 ,0
Exp/Cntr=0.3,0.1

Type RM Length L Ch R = 1 ,11049   ,425,425,425
BEGIN DESCRIPTION:
Town Creek 19.0
END DESCRIPTION:
XS GIS Cut Line= 3
      1922405.96     13936873.78      1921595.02     13937105.97
      1921215.73      13937097.6
#Sta/Elev= 30
  4136.2 1666.82  4259.4 1661.82  4543.4 1660.33  4587.1 1659.82  4608.9 1667.36
  4630.8 1666.89  4656.7 1660.29  4743.1 1656.88  4789.9 1649.86  4836.7 1647.69
  4855.4 1642.48  4861.5 1643.06  4924.1 1644.03  4930.3 1641.83  4945.9 1640.59
  4958.4  1642.9  4977.1 1640.15  4995.9 1641.11  5001.2 1640.45  5002.2 1637.47
  5002.9 1636.97  5036.2 1637.47  5061.3 1641.26  5076.3 1641.06    5085  1645.4
  5100.3 1653.74  5112.3 1653.79  5129.6 1658.33  5160.3 1662.41  5359.1 1665.46
#Mann= 6 ,-1 , 0
  4136.2    .063       0  4543.4    .035       0  4861.5    .094       0
  5002.2     .05       0  5036.2    .094       0    5085     .07       0
Bank Sta=5002.2,5036.2
XS Rating Curve= 0 ,0
Exp/Cntr=0.3,0.1

Type RM Length L Ch R = 1 ,10624   ,603,603,603
BEGIN DESCRIPTION:
Town Creek 18.0
END DESCRIPTION:
XS GIS Cut Line= 3
      1922548.41     13936812.06        1921625.       13936725.
      1920994.42     13936712.88
#Sta/Elev= 30
  4067.3 1675.43  4159.1 1676.92  4235.9 1668.15  4508.8 1660.53  4558.3 1661.25
  4582.5 1666.48  4586.3 1668.82  4600.6 1672.03  4639.7 1669.94  4668.5 1660.01
    4686 1659.77  4728.4 1659.85  4766.3 1658.79  4817.5 1649.79    4848  1646.9
  4895.9 1641.97    4932 1641.57    4946 1638.65  4950.1 1638.65  4951.1  1635.4
  4951.8  1634.9  4985.2  1635.4  5016.3  1635.9  5034.7 1639.12    5067  1643.5
  5090.5 1658.07  5105.2  1660.7  5370.4 1664.37  5574.4 1674.69  5625.5  1678.5
#Mann= 10 ,-1 , 0
  4067.3    .063       0  4586.3    .035       0    4686     .07       0
  4728.4    .035       0    4848    .094       0    4946    .035       0
  4951.1    .035       0  4985.2    .035       0  5034.7     .07       0
  5574.4      .1       0
Bank Sta=4951.1,4985.2
XS Rating Curve= 0 ,0
Exp/Cntr=0.3,0.1

Type RM Length L Ch R = 1 ,10021   ,519,519,519
BEGIN DESCRIPTION:
Town Creek 17.0
END DESCRIPTION:
XS GIS Cut Line= 3
      1922834.12     13936536.01      1921720.93     13936181.09
      1921075.01       13935975.
#Sta/Elev= 30
  3835.1 1690.84  3872.2 1688.29  3957.3 1687.29    3968 1687.74  4015.2 1682.36
  4120.5  1677.3  4213.6 1667.94  4256.6 1665.51    4434  1659.3  4764.6  1656.9
  4786.6 1655.62  4805.8 1649.62  4830.8 1645.04  4884.5 1639.17  4934.7 1637.66
  4967.8 1634.56  4968.5 1634.06  5001.9 1634.56  5003.9 1638.16  5029.1 1655.01
  5044.9 1659.36  5183.4  1658.1  5252.7 1654.89  5307.1 1657.55  5438.8 1657.88
  5463.7 1657.86  5545.6 1671.62  5615.1 1673.33  5648.5 1680.22  5681.5 1682.09
#Mann= 7 ,-1 , 0
  3835.1    .063       0  3957.3      .1       0  4256.6    .035       0
  4967.8    .035       0  5001.9    .035       0  5438.8    .063       0
  5648.5    .035       0
Bank Sta=4967.8,5001.9
XS Rating Curve= 0 ,0
Exp/Cntr=0.3,0.1

Type RM Length L Ch R = 1 ,9502    ,559,559,559
BEGIN DESCRIPTION:
Town Creek 16.0
END DESCRIPTION:
XS GIS Cut Line= 3
      1922806.15     13935883.93        1921825.       13935725.
      1921274.97     13935374.98
#Sta/Elev= 30
  4002.2 1677.79    4093 1675.15  4126.4 1675.54  4515.4 1661.86  4598.7  1660.8
  4727.4 1658.69  4859.7 1655.55    4899 1644.92  4924.7 1642.09    4947 1639.83
  4992.6 1639.75  5002.3  1637.6  5003.3 1634.09  5003.9 1633.59  5037.6 1634.09
  5040.9 1635.24  5123.5 1635.87  5144.9 1640.15  5169.6 1648.53  5208.4 1651.55
  5226.7 1652.08  5245.7 1649.24  5326.1 1653.84    5380 1653.28    5472 1653.69
  5543.1 1657.37  5564.5 1661.46  5614.3 1675.62  5627.6 1677.38  5648.1 1677.17
#Mann= 8 ,-1 , 0
  4002.2      .1       0  4598.7     .07       0  4727.4      .1       0
  4924.7    .035       0  5003.3    .035       0  5037.6    .035       0
  5208.4    .063       0    5380    .035       0
Bank Sta=5003.3,5037.6
XS Rating Curve= 0 ,0
Exp/Cntr=0.3,0.1

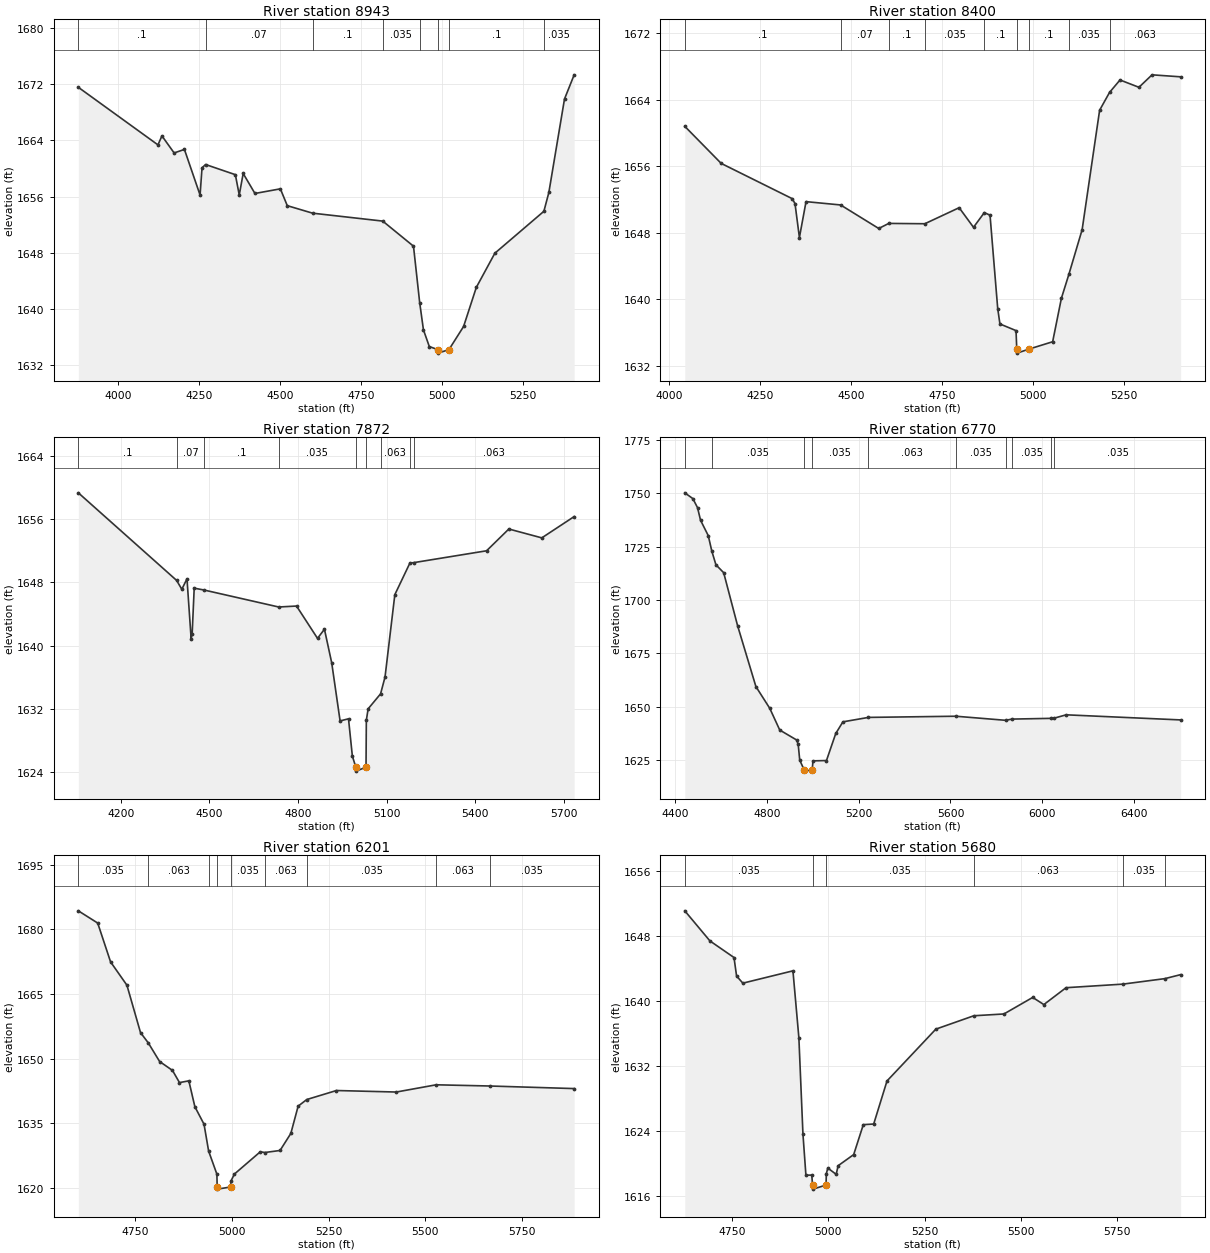
Type RM Length L Ch R = 1 ,8943    ,543,543,543
BEGIN DESCRIPTION:
Town Creek 15.0
END DESCRIPTION:
XS GIS Cut Line= 3
      1922843.37     13935363.93        1921725.       13935225.
      1921324.97       13935275.
#Sta/Elev= 30
  3877.3 1671.58    4123 1663.37  4135.3 1664.65  4172.9 1662.22  4204.7 1662.72
    4253 1656.21    4259  1660.1    4270 1660.57  4361.9 1659.12  4373.9 1656.22
    4386 1659.29  4422.3 1656.44  4500.8  1657.1  4522.1  1654.7  4600.2 1653.63
  4816.7  1652.5  4911.6 1648.92  4930.7 1640.87  4942.3 1636.99  4960.4 1634.61
  4986.6 1634.17  4987.3 1633.67    5021 1634.17  5066.2 1637.47  5105.5 1643.05
  5162.7 1647.92    5314  1653.9  5329.3 1656.58  5377.6 1669.91  5407.4 1673.36
#Mann= 8 ,-1 , 0
  3877.3      .1       0    4270     .07       0  4600.2      .1       0
  4816.7    .035       0  4930.7      .1       0  4986.6     .05       0
    5021      .1       0    5314    .035       0
Bank Sta=4986.6,5021
XS Rating Curve= 0 ,0
Exp/Cntr=0.3,0.1

Type RM Length L Ch R = 1 ,8400    ,528,528,528
BEGIN DESCRIPTION:
Town Creek 14.0
END DESCRIPTION:
XS GIS Cut Line= 3
       1922578.6      13934901.4        1921625.       13934775.
      1921225.04       13934775.
#Sta/Elev= 30
    4043 1660.79    4143 1656.33    4338 1652.09  4345.7  1651.5  4357.8 1647.41
    4376 1651.73    4471 1651.33  4575.7  1648.5  4603.3 1649.11  4702.3 1649.07
  4796.6    1651    4836 1648.64  4865.7 1650.41  4881.4  1650.1  4902.5 1638.86
  4908.6 1637.01  4952.8 1636.21  4954.8    1634  4955.5  1633.5  4989.4    1634
  5053.4 1634.87  5077.4  1640.1  5098.1    1643  5134.4 1648.36  5182.4 1662.73
  5209.6 1664.87  5238.4 1666.37  5290.4 1665.49  5326.4 1666.99  5404.9 1666.75
#Mann= 9 ,-1 , 0
    4043      .1       0    4471     .07       0  4603.3      .1       0
  4702.3    .035       0  4865.7      .1       0  4954.8     .05       0
  4989.4      .1       0  5098.1    .035       0  5209.6    .063       0
Bank Sta=4954.8,4989.4
XS Rating Curve= 0 ,0
Exp/Cntr=0.3,0.1

Type RM Length L Ch R = 1 ,7872    ,1102,1102,1102
BEGIN DESCRIPTION:
Town Creek 13.0
END DESCRIPTION:
XS GIS Cut Line= 3
      1922533.97     13934811.02        1921725.       13934325.
      1920993.52     13934248.61
#Sta/Elev= 30
  4056.3 1659.31  4389.1 1648.25  4406.8 1647.13  4424.3 1648.45  4438.3 1640.91
  4441.8 1641.49  4448.7 1647.27  4482.6 1647.03  4734.8 1644.89  4795.3 1645.01
  4866.3 1640.93  4889.8 1642.08  4914.4 1637.84  4942.8  1630.5  4971.3 1630.77
  4984.3 1626.07    4996 1624.66  4996.7 1624.16  5030.6 1624.66  5031.7 1630.59
  5037.8 1632.03  5079.9 1633.92    5095 1636.05  5128.2 1646.45  5179.2 1650.44
  5191.7 1650.49  5438.9 1651.99  5514.3 1654.74  5625.9 1653.62  5735.5 1656.31
#Mann= 9 ,-1 , 0
  4056.3      .1       0  4389.1     .07       0  4482.6      .1       0
  4734.8    .035       0    4996    .035       0  5030.6    .035       0
  5079.9    .063       0  5179.2    .094       0  5191.7    .063       0
Bank Sta=4996,5030.6
XS Rating Curve= 0 ,0
Exp/Cntr=0.3,0.1

Type RM Length L Ch R = 1 ,6770    ,569,569,569
BEGIN DESCRIPTION:
Town Creek 12.0
END DESCRIPTION:
XS GIS Cut Line= 4
        1923075.       13934175.        1922575.       13933925.
      1921876.93     13933725.83      1920999.41     13933753.46
#Sta/Elev= 30
    4441 1750.17  4476.2 1747.46  4496.5 1743.22  4509.7 1737.33  4543.3 1730.12
  4559.1 1722.77  4576.8 1716.46  4610.6 1712.75  4671.4 1687.88  4751.2  1659.4
  4811.8 1649.18  4855.2 1639.04    4929 1634.37  4935.7 1632.27  4942.4 1624.92
  4962.1 1620.29  4962.8 1619.79  4996.9 1620.29    5000  1624.6    5059 1624.75
  5099.5 1637.42  5130.7 1642.88  5242.2 1644.96  5623.4 1645.51  5840.5  1643.6
  5868.7 1644.17  6037.9 1644.51  6052.7 1644.62  6104.8 1646.17  6603.9 1643.78
#Mann= 10 ,-1 , 0
    4441      .1       0  4559.1    .035       0  4962.1    .035       0
  4996.9    .035       0  5242.2    .063       0  5623.4    .035       0
  5840.5    .063       0  5868.7    .035       0  6037.9    .063       0
  6052.7    .035       0
Bank Sta=4962.1,4996.9
XS Rating Curve= 0 ,0
Exp/Cntr=0.3,0.1

Type RM Length L Ch R = 1 ,6201    ,521,521,521
BEGIN DESCRIPTION:
Town Creek 11.0
END DESCRIPTION:
XS GIS Cut Line= 3
      1923075.01       13933475.        1922675.       13933425.
      1921825.31     13933652.74
#Sta/Elev= 30
  4602.3 1684.33  4652.4 1681.49  4685.7 1672.47    4728 1667.05  4763.2 1656.03
  4783.2 1653.66  4812.6 1649.32  4845.9 1647.25    4864 1644.42  4888.2 1644.83
  4903.8 1638.82  4927.5 1634.75  4939.4 1628.51  4960.8 1623.14  4961.5 1620.17
  4962.2 1619.67  4996.4 1620.17    4997 1621.52  5006.1 1623.17    5073 1628.34
    5085 1628.18  5124.2 1628.65  5152.1 1632.61    5171 1638.95  5193.4 1640.49
  5270.1 1642.58    5425 1642.23  5528.1 1643.91  5666.9 1643.63  5885.1 1643.03
#Mann= 9 ,-1 , 0
  4602.3    .035       0  4783.2    .063       0  4939.4    .035       0
  4961.5    .035       0  4996.4    .035       0    5085    .063       0
  5193.4    .035       0  5528.1    .063       0  5666.9    .035       0
Bank Sta=4961.5,4996.4
XS Rating Curve= 0 ,0
Exp/Cntr=0.3,0.1

Type RM Length L Ch R = 1 ,5680    ,635,635,635
BEGIN DESCRIPTION:
Town Creek 10.0
END DESCRIPTION:
XS GIS Cut Line= 3
      1922606.95     13932732.76      1922380.16     13933017.72
      1921659.08     13933596.45
#Sta/Elev= 30
  4626.7 1651.15    4692 1647.44  4754.6 1645.39  4761.3 1643.11  4777.6 1642.23
  4907.8 1643.75  4923.2 1635.51  4933.8 1623.63  4941.5 1618.55  4956.8 1618.56
  4958.7 1617.33  4959.5 1616.83  4993.8 1617.33  4994.6 1618.73  4998.4 1619.43
  5020.2 1618.65  5025.3 1619.72  5065.7 1621.09  5090.7 1624.78  5117.7 1624.86
  5152.3 1630.17  5279.2 1636.56    5378 1638.21  5456.2 1638.43    5531 1640.47
    5560 1639.59  5617.7 1641.67  5765.2 1642.11  5874.7 1642.79  5915.5 1643.28
#Mann= 6 ,-1 , 0
  4626.7    .035       0  4958.7    .035       0  4993.8    .035       0
    5378    .063       0  5765.2    .035       0  5874.7    .063       0
Bank Sta=4958.7,4993.8
XS Rating Curve= 0 ,0
Exp/Cntr=0.3,0.1

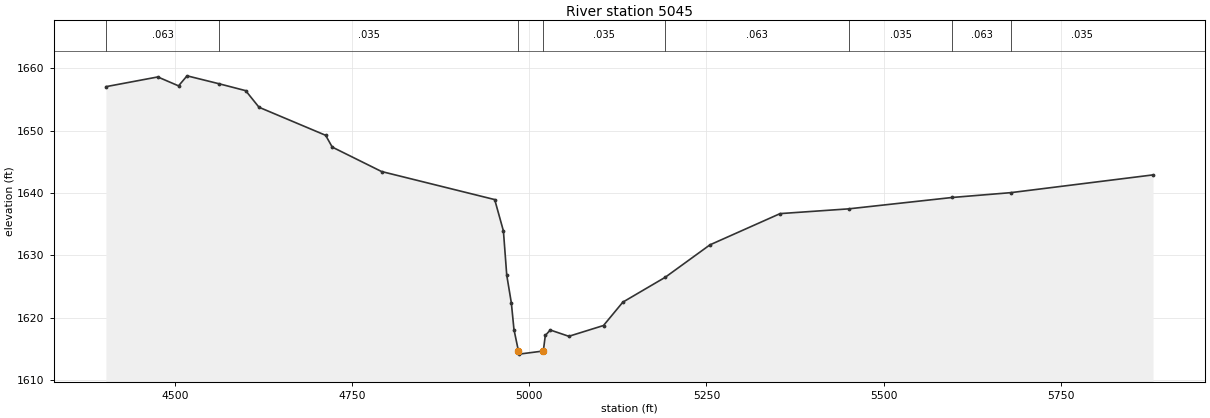
Type RM Length L Ch R = 1 ,5045    ,546,546,546
BEGIN DESCRIPTION:
Town Creek 9.0
END DESCRIPTION:
XS GIS Cut Line= 3
      1922351.73     13932365.31        1921875.       13932725.
      1921454.94     13933498.39
#Sta/Elev= 30
  4402.8 1657.05    4476 1658.61  4505.3 1657.18  4517.3 1658.79  4562.7 1657.51
    4600 1656.41  4618.8 1653.75  4712.8 1649.25  4722.1 1647.36  4791.7 1643.44
  4951.3 1638.94  4963.6 1633.91  4968.3 1626.82  4974.8 1622.36  4978.5 1618.09
  4984.8 1614.65  4985.6 1614.15  5019.9 1614.65  5022.7 1617.14  5029.7 1618.02
  5055.9 1617.01  5104.8 1618.74  5132.1 1622.49  5191.8 1626.47    5255 1631.68
    5354 1636.69  5450.5 1637.45    5597 1639.28  5679.3 1640.05  5880.1  1642.9
#Mann= 8 ,-1 , 0
  4402.8    .063       0  4562.7    .035       0  4984.8    .035       0
  5019.9    .035       0  5191.8    .063       0  5450.5    .035       0
    5597    .063       0  5679.3    .035       0
Bank Sta=4984.8,5019.9
XS Rating Curve= 0 ,0
Exp/Cntr=0.3,0.1