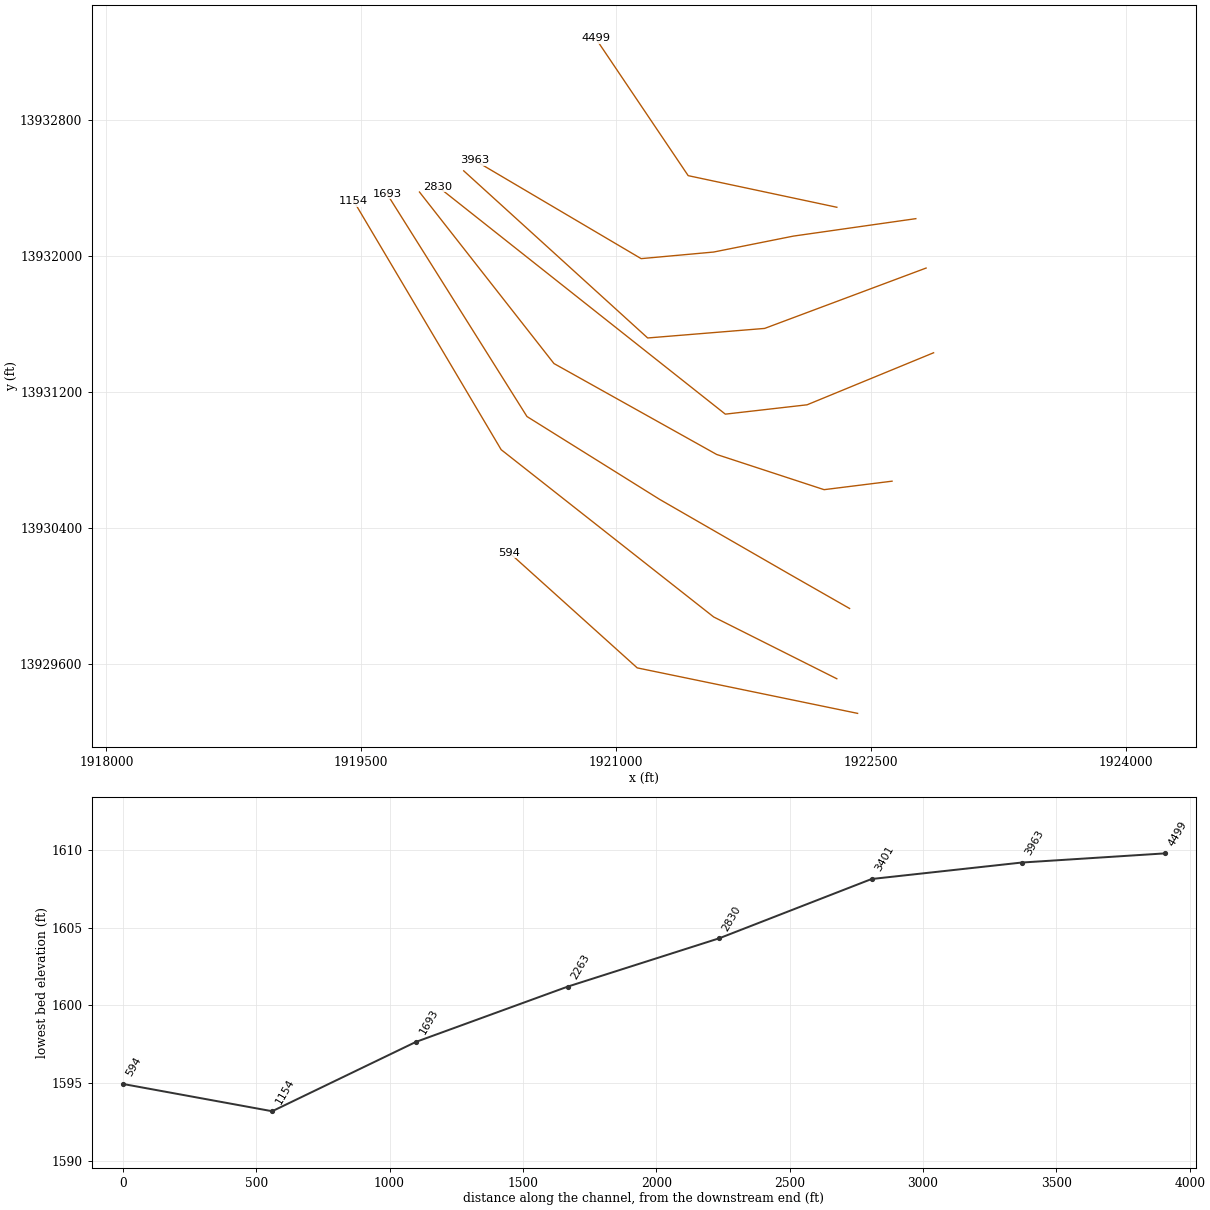
HEC-RAS study Town Creek.prj: Town Creek Base Level Engineering

--- Town Creek.g01 (geometry) --- (continued)

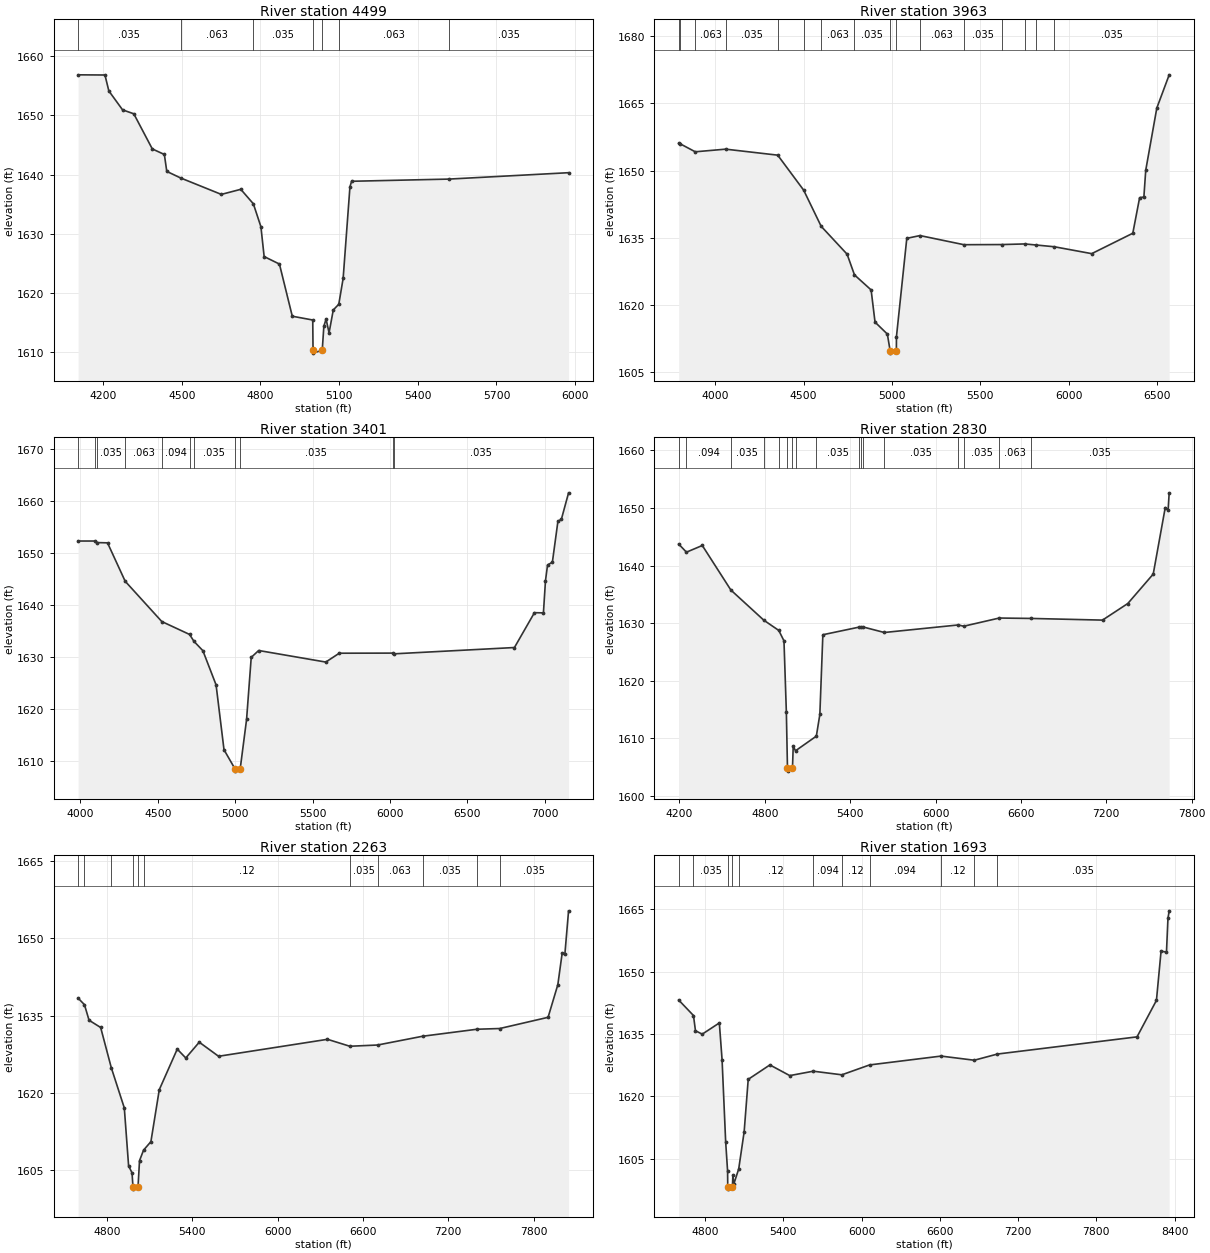
Type RM Length L Ch R = 1 ,4499    ,536,536,536
BEGIN DESCRIPTION:
Town Creek 8.0
END DESCRIPTION:
XS GIS Cut Line= 3
      1922300.14     13932288.74        1921425.       13932475.
      1920880.34       13933284.
#Sta/Elev= 30
  4104.9 1656.86  4207.4 1656.83  4222.2 1654.14  4274.5 1650.94  4317.4 1650.27
  4387.9 1644.33  4433.9 1643.39  4443.1 1640.53  4495.9 1639.42  4651.1 1636.64
  4725.3  1637.5  4773.2 1635.05    4802 1631.17  4814.3 1626.13  4872.6 1624.86
  4921.6 1616.04  4999.6  1615.4  5000.7  1610.3  5001.4  1609.8  5035.8  1610.3
    5042 1614.36  5050.4 1615.55  5061.8 1613.24  5077.9  1617.1  5098.9 1618.07
  5115.5 1622.44  5141.4 1637.91  5147.7 1638.86  5518.8 1639.23  5974.9 1640.31
#Mann= 7 ,-1 , 0
  4104.9    .035       0  4495.9    .063       0  4773.2    .035       0
  5000.7    .035       0  5035.8    .035       0  5098.9    .063       0
  5518.8    .035       0
Bank Sta=5000.7,5035.8
XS Rating Curve= 0 ,0
Exp/Cntr=0.3,0.1

Type RM Length L Ch R = 1 ,3963    ,562,562,562
BEGIN DESCRIPTION:
Town Creek 7.0
END DESCRIPTION:
XS GIS Cut Line= 5
      1922765.12     13932221.66      1922044.08     13932118.82
        1921575.       13932025.      1921148.07     13931986.07
      1920166.02     13932565.98
#Sta/Elev= 30
  3793.3  1656.1  3803.5 1655.95  3887.1  1654.2  4059.1 1654.79  4353.7 1653.45
  4500.6 1645.63  4599.7 1637.55  4746.4 1631.32  4788.2 1626.69  4882.4 1623.33
  4904.5 1616.14  4974.2 1613.47  4990.2 1609.71  4990.9 1609.21  5025.3 1609.71
  5025.8 1612.91  5084.3 1634.86  5158.9 1635.48  5407.5 1633.44  5621.6 1633.47
    5752 1633.61  5813.9 1633.38  5919.2 1632.98  6130.8 1631.44  6363.3    1636
  6401.9 1643.94    6426  1644.1  6436.5 1650.07  6499.2 1663.98  6569.2  1671.4
#Mann= 16 ,-1 , 0
  3793.3    .063       0  3803.5    .035       0  3887.1    .063       0
  4059.1    .035       0  4353.7    .063       0  4500.6    .035       0
  4599.7    .063       0  4788.2    .035       0  4990.2    .035       0
  5025.3    .035       0  5158.9    .063       0  5407.5    .035       0
  5621.6    .063       0    5752    .035       0  5813.9    .063       0
  5919.2    .035       0
Bank Sta=4990.2,5025.3
XS Rating Curve= 0 ,0
Exp/Cntr=0.3,0.1

Type RM Length L Ch R = 1 ,3401    ,571,571,571
BEGIN DESCRIPTION:
Town Creek 6.0
END DESCRIPTION:
XS GIS Cut Line= 4
      1922825.54     13931930.67        1921875.       13931575.
       1921186.5     13931518.67       1920103.6     13932503.42
#Sta/Elev= 30
  3985.1 1652.31  4092.2 1652.31  4109.9 1652.01  4175.4 1651.96  4289.5 1644.59
    4526 1636.86  4705.6 1634.38  4734.1 1633.05  4791.5 1631.27  4876.9  1624.7
  4928.1 1612.25  4997.8 1608.65  4998.6 1608.15    5033 1608.65  5073.9 1618.06
    5104 1629.98  5152.2  1631.3  5585.7 1629.08  5672.9 1630.78  6017.1  1630.8
  6025.9 1630.66  6804.7 1631.87    6934 1638.56    6992 1638.52  7005.3  1644.7
  7018.7 1647.71  7049.9 1648.25  7085.6 1656.08  7107.9 1656.47  7154.5 1661.56
#Mann= 11 ,-1 , 0
  3985.1    .094       0  4092.2    .063       0  4109.9    .035       0
  4289.5    .063       0    4526    .094       0  4705.6    .063       0
  4734.1    .035       0  4997.8    .035       0    5033    .035       0
  6017.1    .063       0  6025.9    .035       0
Bank Sta=4997.8,5033
XS Rating Curve= 0 ,0
Exp/Cntr=0.3,0.1

Type RM Length L Ch R = 1 ,2830    ,567,567,567
BEGIN DESCRIPTION:
Town Creek 5.0
END DESCRIPTION:
XS GIS Cut Line= 4
       1922869.6     13931431.52        1922125.       13931125.
      1921643.58     13931069.94      1919952.55     13932409.68
#Sta/Elev= 30
  4194.8 1643.74  4249.3 1642.33  4360.8 1643.49  4561.6 1635.76  4792.9 1630.53
  4898.2 1628.75  4934.8 1626.94  4951.5 1614.62  4959.4 1604.83  4960.1 1604.33
  4994.6 1604.83  4999.7 1608.64  5015.9 1607.86  5162.3  1610.4  5186.9 1614.16
  5208.1    1628  5460.2 1629.31  5477.9 1629.34  5487.7 1629.37  5639.9 1628.39
  6159.6  1629.7  6198.2 1629.48  6448.1  1630.9  6671.5 1630.83  7173.4 1630.54
  7351.2 1633.42  7529.9 1638.53  7614.3 1650.07  7634.6 1649.68    7642 1652.63
#Mann= 17 ,-1 , 0
  4194.8    .063       0  4249.3    .094       0  4561.6    .035       0
  4792.9    .063       0  4898.2    .035       0  4959.4    .035       0
  4994.6    .035       0  5015.9     .07       0  5162.3    .035       0
  5460.2    .063       0  5477.9     .12       0  5487.7    .063       0
  5639.9    .035       0  6159.6    .063       0  6198.2    .035       0
  6448.1    .063       0  6671.5    .035       0
Bank Sta=4959.4,4994.6
XS Rating Curve= 0 ,0
Exp/Cntr=0.3,0.1

Type RM Length L Ch R = 1 ,2263    ,570,570,570
BEGIN DESCRIPTION:
Town Creek 4.0
END DESCRIPTION:
XS GIS Cut Line= 5
        1922625.       13930675.        1922225.       13930625.
      1921592.88     13930832.25      1920634.81     13931368.04
      1919843.13     13932378.48
#Sta/Elev= 30
  4596.9 1638.39  4641.8 1637.11  4674.2 1634.08  4755.8 1632.67  4830.5 1624.85
  4922.1 1617.02  4952.3 1605.76  4976.5 1604.38  4982.8 1601.72  4983.6 1601.22
  5018.7 1601.72  5029.2 1606.77  5057.6 1608.81  5109.2 1610.46  5168.1 1620.57
  5294.4 1628.46  5354.4 1626.74  5449.2 1629.81    5585 1627.07  6351.1 1630.37
  6508.1 1629.02  6703.6 1629.26  7020.6 1630.97  7402.2 1632.33  7562.7 1632.47
  7902.5 1634.65  7971.1    1641  8001.6 1647.14  8020.7 1646.97  8046.6 1655.37
#Mann= 11 ,-1 , 0
  4596.9     .12       0  4641.8    .035       0  4830.5      .1       0
  4982.8     .05       0  5018.7      .1       0  5057.6     .12       0
  6508.1    .035       0  6703.6    .063       0  7020.6    .035       0
  7402.2    .063       0  7562.7    .035       0
Bank Sta=4982.8,5018.7
XS Rating Curve= 0 ,0
Exp/Cntr=0.3,0.1

Type RM Length L Ch R = 1 ,1693    ,539,539,539
BEGIN DESCRIPTION:
Town Creek 3.0
END DESCRIPTION:
XS GIS Cut Line= 5
      1922375.02     13929924.99        1922025.       13930125.
       1921257.2     13930567.58      1920475.95     13931055.86
      1919651.29     13932368.81
#Sta/Elev= 30
  4597.1 1643.19  4710.5 1639.46  4725.8  1635.8  4777.6 1634.97  4908.9 1637.67
  4929.8 1628.83  4957.3 1609.09  4972.2 1601.98  4973.3 1598.15  4974.1 1597.65
  5009.2 1598.15  5012.6 1600.96  5020.4 1598.93  5057.6 1602.54  5099.2 1611.47
  5130.3 1624.09  5296.5 1627.56  5448.9 1624.99    5629 1626.05  5848.2 1625.18
    6061 1627.56  6608.9 1629.69  6863.6 1628.69  7041.1 1630.18  8111.7 1634.32
  8260.5  1643.1  8295.9 1654.94  8337.5 1654.75  8348.8 1662.85  8358.2 1664.67
#Mann= 11 ,-1 , 0
  4597.1    .094       0  4710.5    .035       0  4973.3    .035       0
  5009.2    .035       0  5057.6     .12       0    5629    .094       0
  5848.2     .12       0    6061    .094       0  6608.9     .12       0
  6863.6    .094       0  7041.1    .035       0
Bank Sta=4973.3,5009.2
XS Rating Curve= 0 ,0
Exp/Cntr=0.3,0.1

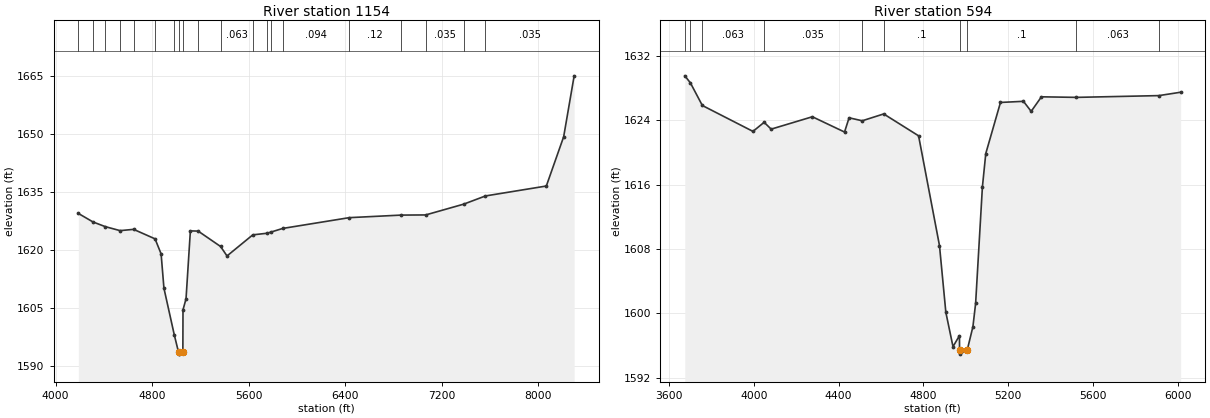
Type RM Length L Ch R = 1 ,1154    ,560,560,560
BEGIN DESCRIPTION:
Town Creek 2.0
END DESCRIPTION:
XS GIS Cut Line= 4
      1922299.87     13929511.01        1921575.       13929875.
      1920324.04     13930860.55      1919455.99      13932325.4
#Sta/Elev= 30
  4189.1 1629.48  4310.6 1627.28  4412.3 1626.07  4534.9 1625.04    4647 1625.37
  4824.5 1622.92  4874.6 1619.05  4898.1 1610.18  4983.3 1598.22  5018.8 1593.68
  5019.6 1593.18  5054.8 1593.68  5055.9  1604.6  5081.1 1607.46    5117 1624.98
  5181.6 1624.92  5367.1 1620.95  5420.5 1618.51  5633.8 1623.95  5753.3 1624.37
  5786.6 1624.69  5882.1 1625.61  6433.1 1628.39  6863.4 1629.05  7065.7 1629.09
  7381.3 1631.88    7561 1633.99    8065 1636.55  8208.6 1649.26  8295.5 1664.98
#Mann= 20 ,-1 , 0
  4189.1    .094       0  4310.6    .063       0  4412.3     .12       0
  4534.9    .063       0    4647    .035       0  4824.5      .1       0
  4983.3    .035       0  5018.8    .035       0  5054.8    .035       0
  5181.6    .094       0  5367.1    .063       0  5633.8    .094       0
  5753.3    .035       0  5786.6    .063       0  5882.1    .094       0
  6433.1     .12       0  6863.4    .094       0  7065.7    .035       0
  7381.3    .063       0    7561    .035       0
Bank Sta=5018.8,5054.8
XS Rating Curve= 0 ,0
Exp/Cntr=0.3,0.1

Type RM Length L Ch R = 1 ,594     ,0,0,0
BEGIN DESCRIPTION:
Town Creek 1.0
END DESCRIPTION:
XS GIS Cut Line= 3
      1922422.25       13929307.        1921125.       13929575.
       1920371.6     13930254.05
#Sta/Elev= 30
  3674.9 1629.55  3701.2 1628.68  3757.7 1625.86  3996.5 1622.64  4049.1 1623.77
  4082.3 1622.92  4276.6 1624.46  4428.4 1622.56  4449.9 1624.33  4511.9 1623.96
  4613.2 1624.81  4777.7 1622.09  4876.3 1608.44  4906.3 1600.14    4940 1595.87
  4970.6 1597.24  4970.9 1595.44  4971.8 1594.94  5007.1 1595.44    5034 1598.35
  5046.8 1601.26  5078.8 1615.74  5094.7 1619.89    5164 1626.24  5272.4 1626.38
  5308.8 1625.13  5357.2 1626.94  5522.1 1626.87  5911.3 1627.09  6013.8 1627.51
#Mann= 10 ,-1 , 0
  3674.9    .063       0  3701.2    .094       0  3757.7    .063       0
  4049.1    .035       0  4511.9    .063       0  4613.2      .1       0
  4970.9    .035       0  5007.1      .1       0  5522.1    .063       0
  5911.3    .035       0
Bank Sta=4970.9,5007.1
XS Rating Curve= 0 ,0
Exp/Cntr=0.3,0.1

Chan Stop Cuts=-1
Use User Specified Reach Order=0
Composite Channel Slope=5