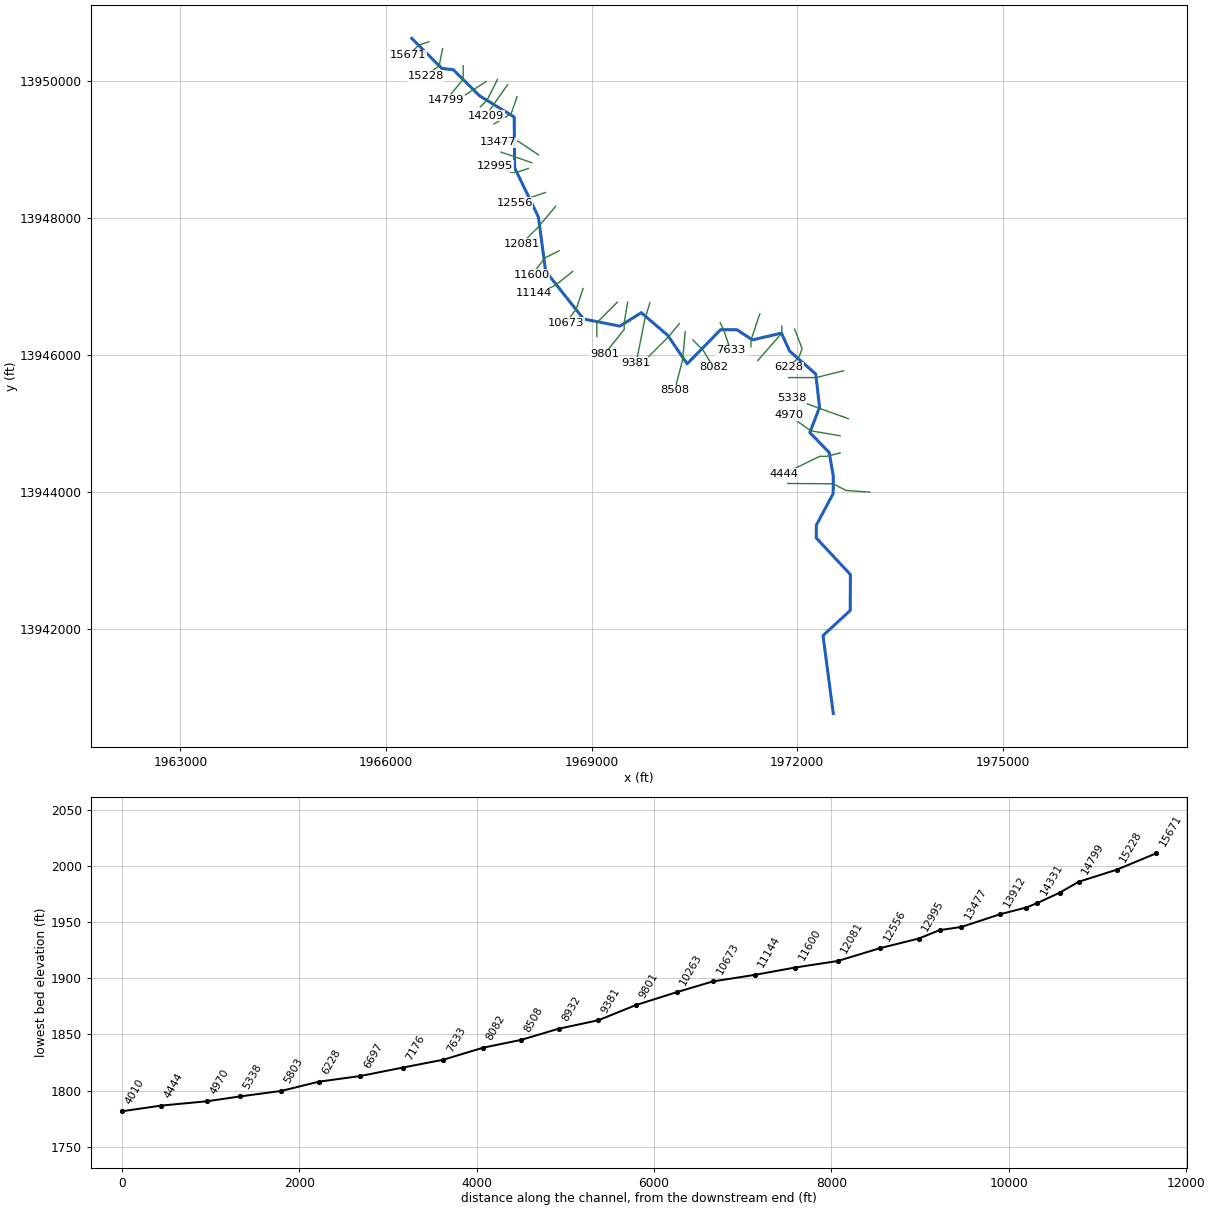
--- Turkey Bottom Creek.prj (project) ---

Proj Title=Turkey Bottom Creek Base Level Engineering
Current Plan=p01
Default Exp/Contr=0.3,0.1
English Units
Geom File=g01
Flow File=f01
Plan File=p01
Y Axis Title=Elevation
X Axis Title(PF)=Main Channel Distance
X Axis Title(XS)=Station
BEGIN DESCRIPTION:
Turkey Bottom Creek
END DESCRIPTION:
DSS Export Rating Curves= 0
DSS Export Rating Curve Sorted= 0
DSS Export Volume Flow Curves= 0
DXF OffsetX= 0
DXF OffsetY= 0
DXF ScaleX= 1
DXF ScaleY= 10

--- Turkey Bottom Creek.p01 (plan) ---

Plan Title=Multiple Run
Short Identifier=Multiple
Geom File=g01
Flow File=f01
Subcritical Flow
K Sum by GR= 0
Std Step Tol= 0.01
Critical Tol= 0.01
Num of Std Step Trials= 20
Max Error Tol= 0.3
Flow Tol Ratio= 0.001
Split Flow NTrial= 30
Split Flow Tol= 0.02
Split Flow Ratio= 0.02
Log Output Level= 0
Friction Slope Method= 1
Unsteady Friction Slope Method= 2
Unsteady Bridges Friction Slope Method= 1
Parabolic Critical Depth
Global Vel Dist=  1 , 1 , 1
Global Log Level= 0
CheckData=True
Encroach Param= -1, 0, 0, 0
BEGIN DESCRIPTION:
Multiple Run
END DESCRIPTION:

--- Turkey Bottom Creek.f01 (steady flow) ---

Flow Title=Multiple
Number of Profiles=7
Profile Names=10-year,25-year,50-year,1pct_min,100-year,1pct_plu,500-year
River Rch & RM= Turkey Bottom Cr,Reach-1,15671
     229     350     453     286     571    1140     889
River Rch & RM= Turkey Bottom Cr,Reach-1,15228
     703    1167    1600    1063    2121    4232    3673
River Rch & RM= Turkey Bottom Cr,Reach-1,12556
     769    1302    1810    1221    2437    4863    4384
River Rch & RM= Turkey Bottom Cr,Reach-1,7176
    1041    1787    2507    1705    3403    6790    6222
River Rch & RM= Turkey Bottom Cr,Reach-1,5803
    1423    2480    3512    2409    4807    9591    8942
River Rch & RM= Turkey Bottom Cr,Reach-1,1264
    1537    2689    3816    2623    5233   10441    9770
Boundary for River Rch & Prof#=Turkey Bottom Cr,Reach-1,1
Up Type=0
Dn Type=3
Dn Slope=0.005
Boundary for River Rch & Prof#=Turkey Bottom Cr,Reach-1,2
Up Type=0
Dn Type=3
Dn Slope=0.005
Boundary for River Rch & Prof#=Turkey Bottom Cr,Reach-1,3
Up Type=0
Dn Type=3
Dn Slope=0.005
Boundary for River Rch & Prof#=Turkey Bottom Cr,Reach-1,4
Up Type=0
Dn Type=3
Dn Slope=0.005
Boundary for River Rch & Prof#=Turkey Bottom Cr,Reach-1,5
Up Type=0
Dn Type=3
Dn Slope=0.005
Boundary for River Rch & Prof#=Turkey Bottom Cr,Reach-1,6
Up Type=0
Dn Type=3
Dn Slope=0.005
Boundary for River Rch & Prof#=Turkey Bottom Cr,Reach-1,7
Up Type=0
Dn Type=3
Dn Slope=0.005

--- Turkey Bottom Creek.g01 (geometry) ---

Geom Title=Existing Conditions
Program Version=4.10

River Reach=Turkey Bottom Cr,Reach-1
Reach XY= 30
        1966375.       13950625.       1966815.2     13950185.48
      1966981.19     13950167.18      1967365.32     13949785.76
      1967869.69     13949477.52       1967876.2     13948735.51
      1968222.82     13948019.55      1968328.55     13947226.47
      1968880.62     13946530.62      1969410.96      13946425.1
      1969723.72     13946621.63       1970108.7     13946292.13
      1970393.28     13945874.92      1970880.44     13946372.83
      1971119.56     13946372.83      1971344.99     13946224.98
      1971769.31     13946323.12      1971888.47     13946061.43
      1972269.53     13945727.45      1972324.48     13945240.22
      1972183.04     13944871.68      1972465.88     13944581.76
      1972525.46     13944235.19      1972522.76     13943980.93
      1972278.55     13943523.53      1972276.05     13943335.43
      1972775.32     13942800.11      1972771.96     13942276.42
      1972375.37     13941909.83        1972525.       13940775.

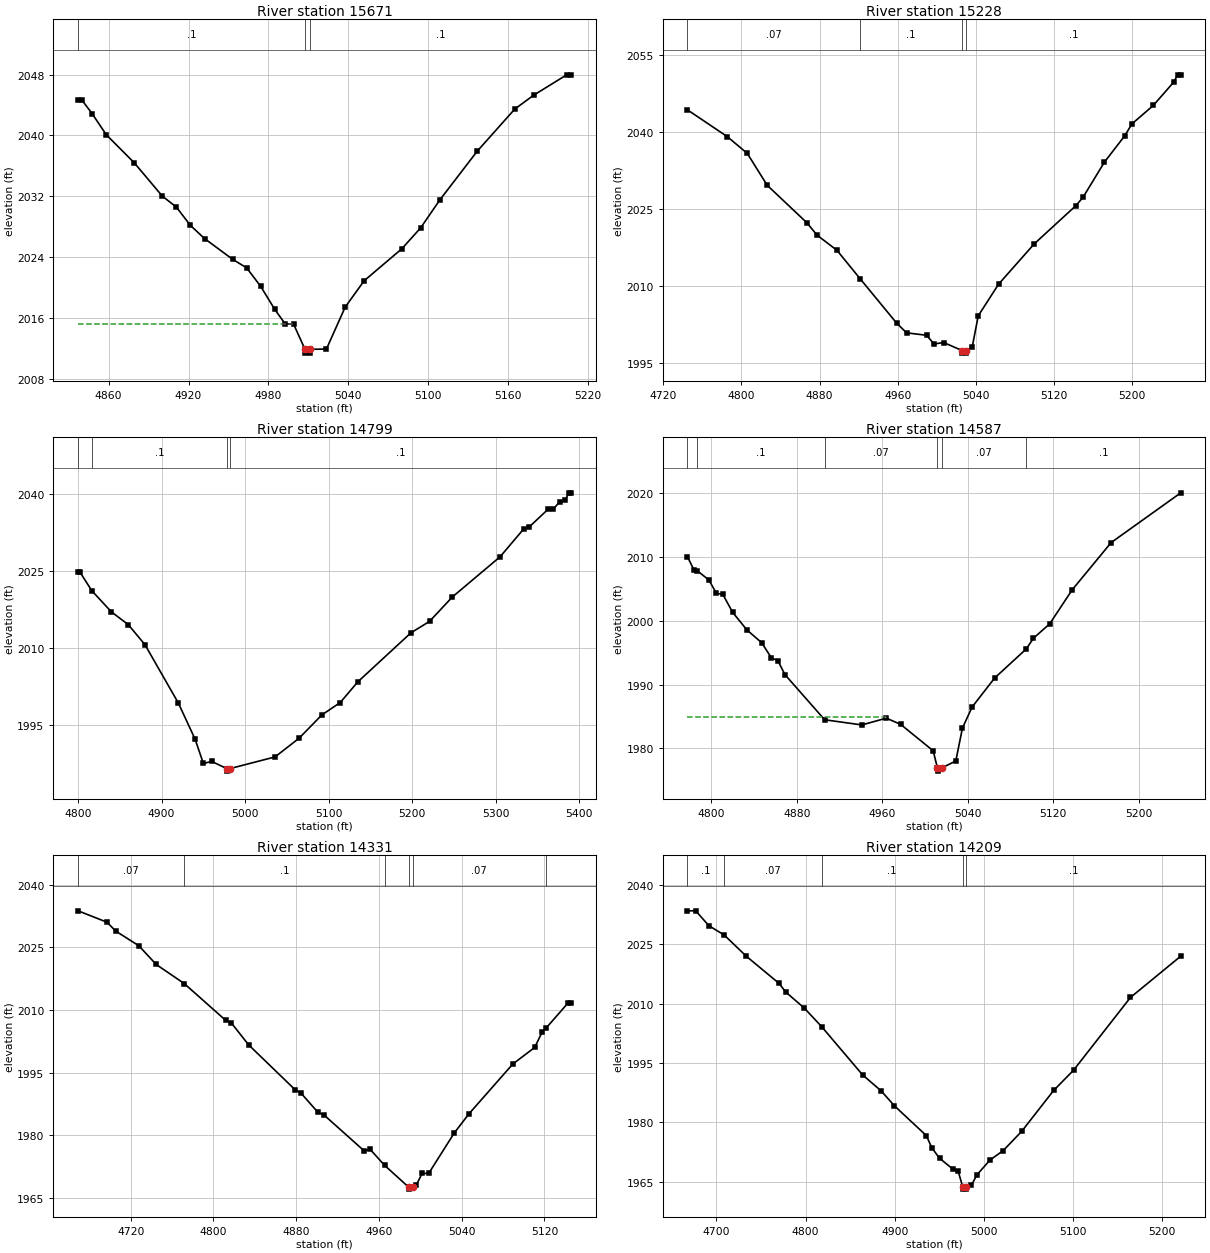
Type RM Length L Ch R = 1 ,15671   ,443,443,443
BEGIN DESCRIPTION:
Turkey Bottom Creek 79.0
END DESCRIPTION:
XS GIS Cut Line= 3
        1966625.       13950575.        1966475.       13950525.
      1966325.03     13950375.03
#Sta/Elev= 30
  4837.1  2044.7  4839.7  2044.7  4847.6 2042.87  4858.2  2040.1  4879.3 2036.39
  4900.3 2032.02  4910.9 2030.57  4921.4 2028.17    4932 2026.44  4953.1 2023.71
  4963.6 2022.59  4974.1 2020.17  4984.7 2017.13  4992.6 2015.21  4998.8 2015.21
  5007.4 2011.88  5007.6 2011.38  5011.1 2011.38  5011.4 2011.88  5023.5 2011.92
  5037.6 2017.44  5051.8 2020.89  5080.1  2025.1  5094.2 2027.84  5108.4 2031.47
  5136.6 2037.91  5164.9 2043.47  5179.1 2045.29  5203.8 2047.96  5207.3 2047.96
#Mann= 3 ,-1 , 0
  4837.1      .1       0  5007.4     .05       0  5011.4      .1       0
#XS Ineff= 2 , 0
          4998.7 2015.27
Permanent Ineff=
       F       F
Bank Sta=5007.4,5011.4
XS Rating Curve= 0 ,0
Exp/Cntr=0.3,0.1

Type RM Length L Ch R = 1 ,15228   ,429,429,429
BEGIN DESCRIPTION:
Turkey Bottom Creek 78.0
END DESCRIPTION:
XS GIS Cut Line= 3
        1966825.     13950474.98        1966775.       13950225.
      1966575.03     13950075.02
#Sta/Elev= 30
  4744.8 2044.23  4785.6 2039.01    4806 2035.75  4826.4 2029.54  4867.2  2022.2
  4877.4 2019.83  4897.8 2016.87  4921.6 2011.31  4958.9 2002.68  4969.1 2000.79
  4989.5 2000.32  4997.2 1998.62    5007 1998.91  5025.9 1997.34  5026.1 1996.84
  5029.6 1996.84  5029.9 1997.34  5036.2 1997.99  5042.4 2004.11  5063.3 2010.29
  5099.7 2018.12  5142.4 2025.58  5149.7 2027.21  5171.6 2034.06  5192.4 2039.19
  5199.7  2041.5  5221.6 2045.09  5242.4 2049.62  5246.6 2051.06  5249.7 2051.06
#Mann= 4 ,-1 , 0
  4744.8     .07       0  4921.6      .1       0  5025.9     .05       0
  5029.9      .1       0
Bank Sta=5025.9,5029.9
XS Rating Curve= 0 ,0
Exp/Cntr=0.3,0.1

Type RM Length L Ch R = 1 ,14799   ,212,212,212
BEGIN DESCRIPTION:
Turkey Bottom Creek 77.0
END DESCRIPTION:
XS GIS Cut Line= 3
        1967125.     13950225.03        1967125.       13950025.
      1966875.03     13949725.04
#Sta/Elev= 30
    4800  2024.7  4802.5  2024.7  4816.4 2021.15    4840 2017.02    4860 2014.57
    4880 2010.68    4920 1999.34    4940 1992.33    4950 1987.59    4960 1987.98
    4978  1986.6  4978.3  1986.1    4982  1986.6  5035.8 1988.86  5064.5 1992.48
  5091.8 1997.01  5113.9 1999.43  5134.8 2003.43  5198.5 2012.97  5220.7 2015.18
    5248 2019.92  5305.3 2027.75  5333.9 2033.23  5340.4 2033.58  5362.6 2036.96
  5369.1 2037.04  5376.9 2038.47  5383.4 2038.77  5387.3 2040.16  5390.5 2040.16
#Mann= 4 ,-1 , 0
    4800     .07       0  4816.4      .1       0    4978     .05       0
    4982      .1       0
Bank Sta=4978,4982
XS Rating Curve= 0 ,0
Exp/Cntr=0.3,0.1

Type RM Length L Ch R = 1 ,14587   ,256,256,256
BEGIN DESCRIPTION:
Mapping XS 64be9c21
END DESCRIPTION:
XS GIS Cut Line= 2
      1967461.81     13949995.23      1967072.86     13949746.29
#Sta/Elev= 30
  4777.7 2010.02  4783.6    2008  4786.6 2007.86  4797.7 2006.39  4804.8 2004.28
  4810.7 2004.15    4820 2001.31  4833.3 1998.56  4847.1 1996.56  4856.3 1994.17
  4862.3 1993.75  4868.9 1991.56  4906.1 1984.48  4940.9 1983.67  4963.9 1984.73
  4977.3 1983.75  5007.7 1979.62  5011.7 1976.93  5011.9 1976.43  5015.7 1976.93
  5028.9 1978.02  5035.1 1983.17  5044.1 1986.46  5065.2 1991.01    5095  1995.6
  5101.6 1997.26  5116.8 1999.51  5137.9 2004.85  5174.3 2012.24  5239.5 2020.04
#Mann= 6 ,-1 , 0
  4777.7     .07       0  4786.6      .1       0  4906.1     .07       0
  5011.7     .05       0  5015.7     .07       0    5095      .1       0
#XS Ineff= 2 , 0
         4963.74 1984.85
Permanent Ineff=
       F       F
Bank Sta=5011.7,5015.7
XS Rating Curve= 0 ,0
Exp/Cntr=0.3,0.1

Type RM Length L Ch R = 1 ,14331   ,122,122,122
BEGIN DESCRIPTION:
Turkey Bottom Creek 76.0
END DESCRIPTION:
XS GIS Cut Line= 3
      1967625.01     13950025.02        1967475.       13949725.
      1967374.97     13949624.97
#Sta/Elev= 30
  4669.1  2033.7  4697.1 2030.97  4705.5 2028.85  4727.8 2025.35  4744.6 2020.87
  4771.8 2016.28  4811.7 2007.51  4817.3 2006.86    4834 2001.62  4878.8 1990.91
  4884.3 1990.16  4901.1 1985.45  4906.7 1984.87  4945.8 1976.23  4951.4 1976.62
  4965.6 1972.75  4988.6 1967.59  4988.8 1967.09  4992.6 1967.59  4996.2 1968.09
  5001.7 1970.86  5008.1 1970.86  5032.8 1980.53    5047 1985.11  5089.4 1997.03
  5110.6 2001.01  5117.7 2004.66  5121.4 2005.58  5142.4 2011.53    5146 2011.53
#Mann= 6 ,-1 , 0
  4669.1     .07       0  4771.8      .1       0  4965.6     .07       0
  4988.6     .05       0  4992.6     .07       0  5121.4      .1       0
Bank Sta=4988.6,4992.6
XS Rating Curve= 0 ,0
Exp/Cntr=0.3,0.1

Type RM Length L Ch R = 1 ,14209   ,297,297,297
BEGIN DESCRIPTION:
Mapping XS 2fa5a7d3
END DESCRIPTION:
XS GIS Cut Line= 2
      1967774.19     13949949.06      1967455.57     13949496.71
#Sta/Elev= 30
  4667.6 2033.43  4676.8 2033.43  4691.6 2029.67  4708.8 2027.32  4733.7 2021.94
  4770.4 2015.09  4777.8 2012.92  4798.7 2008.86  4818.1 2004.18    4864 1992.01
  4884.9 1987.95  4899.7  1984.2  4935.5 1976.67  4941.7 1973.59  4950.3 1970.96
  4965.1 1968.25  4971.2 1967.72  4976.4 1963.66  4976.6 1963.16  4980.1 1963.16
  4980.4 1963.66    4986 1964.08  4992.1 1966.72  5006.9  1970.5  5021.7 1972.88
  5042.6 1977.78  5078.3 1988.07  5100.7  1993.2  5164.5 2011.56  5220.9 2021.98
#Mann= 5 ,-1 , 0
  4667.6      .1       0  4708.8     .07       0  4818.1      .1       0
  4976.4     .05       0  4980.4      .1       0
Bank Sta=4976.4,4980.4
XS Rating Curve= 0 ,0
Exp/Cntr=0.3,0.1

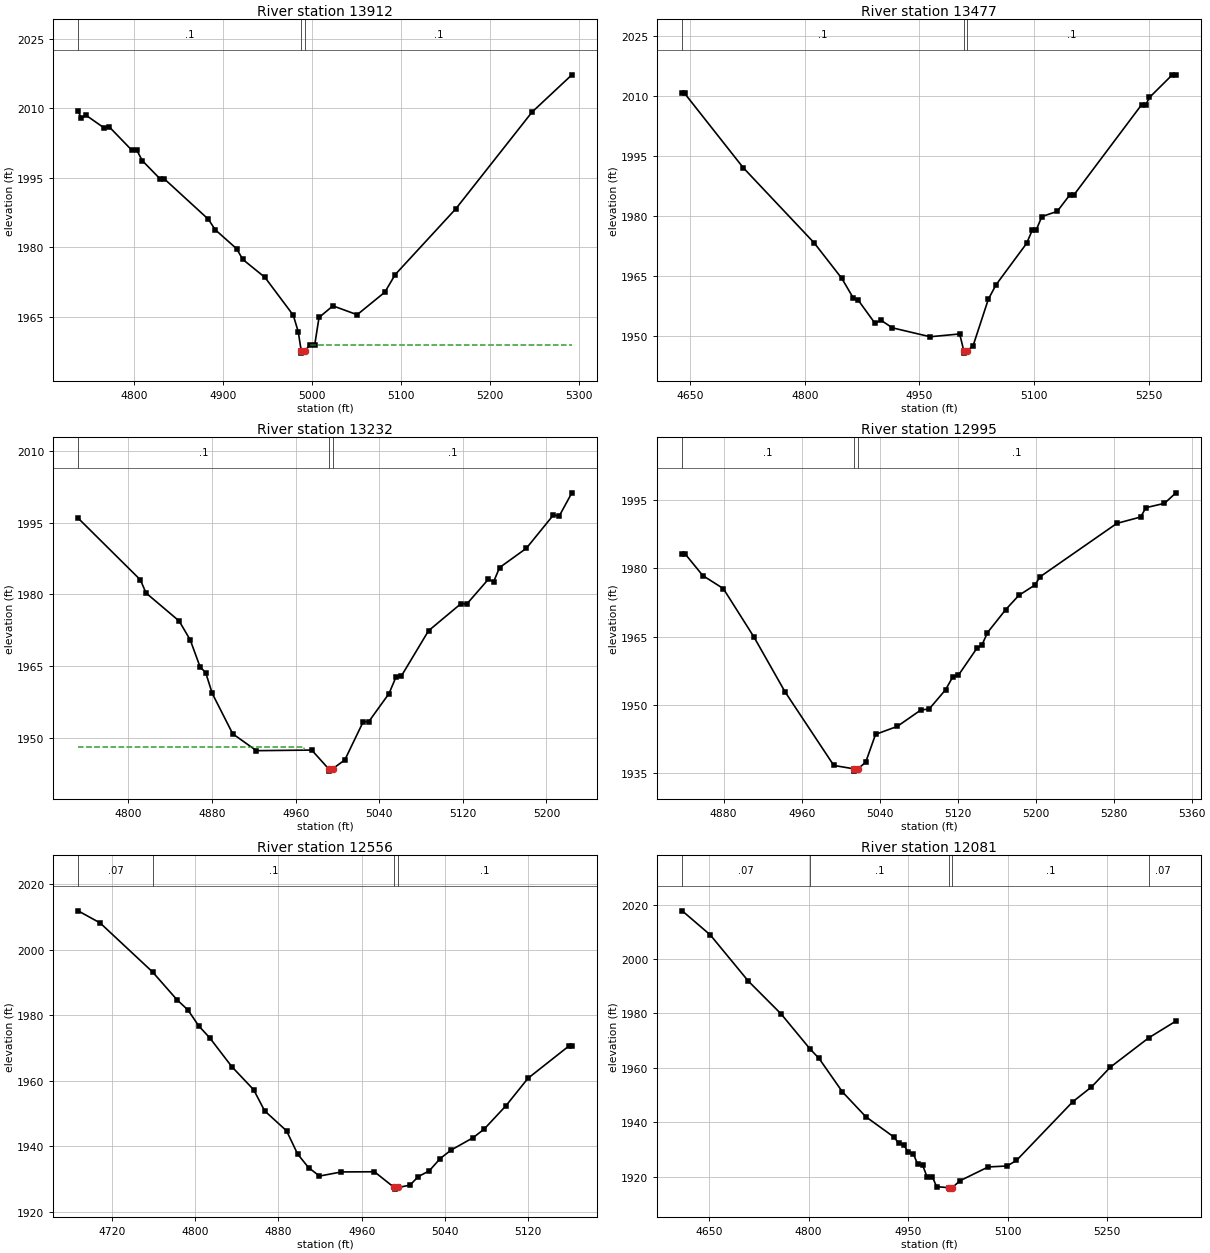
Type RM Length L Ch R = 1 ,13912   ,435,435,435
BEGIN DESCRIPTION:
Turkey Bottom Creek 75.0
END DESCRIPTION:
XS GIS Cut Line= 3
      1967911.31     13949773.04        1967825.       13949525.
      1967574.98     13949374.99
#Sta/Elev= 30
  4737.6 2009.42  4741.2 2007.81  4746.5 2008.47    4767 2005.72  4772.3 2006.02
  4798.1 2000.89  4803.4 2000.97  4809.6 1998.69  4829.2 1994.82  4834.5 1994.72
  4883.8 1986.03  4891.4 1983.79  4915.5 1979.67  4922.5 1977.35  4947.3 1973.49
  4979.1 1965.32  4984.7 1961.75    4988 1957.64  4988.2 1957.14    4992 1957.64
  4997.6 1958.82  5003.1 1958.82    5008 1964.83  5023.6 1967.34  5050.8 1965.43
  5081.9  1970.3  5093.5 1974.09  5161.6  1988.3  5247.1 2009.16  5291.8  2017.2
#Mann= 3 ,-1 , 0
  4737.6      .1       0    4988     .05       0    4992      .1       0
#XS Ineff= 2 , 0
                         4998.02         1958.98
Permanent Ineff=
       F       F
Bank Sta=4988,4992
XS Rating Curve= 0 ,0
Exp/Cntr=0.3,0.1

Type RM Length L Ch R = 1 ,13477   ,245,245,245
BEGIN DESCRIPTION:
Turkey Bottom Creek 74.0
END DESCRIPTION:
XS GIS Cut Line= 4
      1968225.04     13948924.97        1967925.       13949125.
        1967825.       13949125.      1967640.49     13949105.91
#Sta/Elev= 30
  4639.5 2010.74  4642.6 2010.74  4719.2 1992.19  4812.3 1973.35  4848.4  1964.5
  4863.4  1959.6  4869.4 1959.18  4891.9 1953.26  4899.4 1954.08  4914.5 1952.16
    4964 1949.93  5002.6 1950.63  5008.1 1946.34  5008.4 1945.84  5012.1 1946.34
  5020.1 1947.65  5040.1 1959.29  5050.1 1962.89  5090.1 1973.23  5097.6 1976.55
  5102.6 1976.55  5110.2 1979.95  5130.3 1981.25    5147 1985.44    5152 1985.33
  5240.8 2007.92  5245.9  2007.8  5250.9 2009.69  5280.8 2015.35  5285.6 2015.35
#Mann= 3 ,-1 , 0
  4639.5      .1       0  5008.1     .05       0  5012.1      .1       0
Bank Sta=5008.1,5012.1
XS Rating Curve= 0 ,0
Exp/Cntr=0.3,0.1

Type RM Length L Ch R = 1 ,13232   ,237,237,237
BEGIN DESCRIPTION:
Mapping XS 68893f5d
END DESCRIPTION:
XS GIS Cut Line= 2
      1968126.42     13948810.62      1967679.55     13948964.42
#Sta/Elev= 30
  4751.8 1995.96  4811.4 1983.04  4816.8 1980.29  4848.5 1974.42  4859.1 1970.47
  4868.6 1964.78  4873.9 1963.62  4880.2 1959.25  4899.8  1950.8  4922.5 1947.27
  4975.4  1947.4  4991.5 1943.49  4991.7 1942.99  4995.5 1943.49  5007.1 1945.34
  5024.7 1953.34    5030 1953.35  5049.4 1959.24  5055.9 1962.61  5061.2  1962.9
  5087.2 1972.38  5118.4 1978.08  5123.7 1977.94  5144.3 1983.12  5149.6 1982.69
  5155.2 1985.61  5180.8 1989.64  5206.8 1996.64  5212.1 1996.32  5224.4 2001.26
#Mann= 3 ,-1 , 0
  4751.8      .1       0  4991.5     .05       0  4995.5      .1       0
#XS Ineff= 2 , 0
         4967.67 1947.99
Permanent Ineff=
       F       F
Bank Sta=4991.5,4995.5
XS Rating Curve= 0 ,0
Exp/Cntr=0.3,0.1

Type RM Length L Ch R = 1 ,12995   ,439,439,439
BEGIN DESCRIPTION:
Turkey Bottom Creek 73.0
END DESCRIPTION:
XS GIS Cut Line= 4
      1968075.02     13948725.01        1967925.       13948675.
      1967837.37     13948667.63      1967595.03     13948762.71
#Sta/Elev= 30
  4837.5 1983.27  4840.2 1983.27  4858.6 1978.44  4879.7 1975.57  4911.3 1964.87
  4942.9 1952.93    4993 1936.74  5013.7 1935.99    5014 1935.49  5017.7 1935.99
  5025.7 1937.44  5035.8 1943.56  5058.1 1945.31  5082.3 1948.92  5090.8 1949.13
  5107.6 1953.35  5115.2 1956.26  5120.6 1956.49  5139.6 1962.42    5145 1963.22
  5150.6 1965.91  5169.4 1970.98  5182.8 1974.09  5199.2 1976.35  5204.6 1978.17
  5283.3 1989.89  5307.7 1991.29  5313.1 1993.34  5332.1 1994.29  5343.9  1996.6
#Mann= 3 ,-1 , 0
  4837.5      .1       0  5013.7     .05       0  5017.7      .1       0
Bank Sta=5013.7,5017.7
XS Rating Curve= 0 ,0
Exp/Cntr=0.3,0.1

Type RM Length L Ch R = 1 ,12556   ,475,475,475
BEGIN DESCRIPTION:
Turkey Bottom Creek 72.0
END DESCRIPTION:
XS GIS Cut Line= 3
      1968325.04     13948375.01        1968025.       13948275.
      1967874.99       13948225.
#Sta/Elev= 30
  4687.6 2011.84  4708.7 2008.15  4759.1 1993.19  4782.5 1984.72  4793.1 1981.58
  4803.6 1976.67  4814.1 1973.05  4835.2 1964.29  4856.3  1957.2  4866.8 1950.78
  4887.9 1944.66  4898.5 1937.59    4909 1933.44  4919.5 1930.86  4940.6 1932.12
  4972.3 1932.17  4991.3 1927.37  4991.6 1926.87  4995.3 1927.37  5006.5 1928.11
  5014.4 1930.69    5025 1932.46  5035.5 1936.21    5046  1938.8  5067.1 1942.57
  5077.7 1945.19  5098.7 1952.34  5119.8  1960.7  5159.4 1970.63    5162 1970.63
#Mann= 4 ,-1 , 0
  4687.6     .07       0  4759.1      .1       0  4991.3     .05       0
  4995.3      .1       0
Bank Sta=4991.3,4995.3
XS Rating Curve= 0 ,0
Exp/Cntr=0.3,0.1

Type RM Length L Ch R = 1 ,12081   ,481,481,481
BEGIN DESCRIPTION:
Turkey Bottom Creek 71.0
END DESCRIPTION:
XS GIS Cut Line= 3
      1968475.01     13948175.01        1968225.       13947875.
      1967974.98     13947624.98
#Sta/Elev= 30
  4609.5 2017.72  4651.8 2008.88  4709.1 1991.92  4758.6 1979.82  4801.8 1967.07
  4815.8 1963.47    4851 1951.18  4886.1 1942.09  4929.1  1934.5  4935.6 1932.29
  4943.4 1931.78  4949.9 1929.06  4957.7 1928.54  4964.2 1924.71    4972 1924.17
  4978.5 1919.98  4986.4 1920.03  4992.9 1916.38  5012.2 1915.96  5012.4 1915.46
  5016.2 1915.96  5028.3 1918.56  5070.7 1923.61    5099 1923.96  5113.2 1925.98
    5198 1947.55  5226.3 1952.99  5254.6 1960.24  5312.5 1971.04  5353.6 1977.21
#Mann= 5 ,-1 , 0
  4609.5     .07       0  4801.8      .1       0  5012.2     .05       0
  5016.2      .1       0  5312.5     .07       0
Bank Sta=5012.2,5016.2
XS Rating Curve= 0 ,0
Exp/Cntr=0.3,0.1

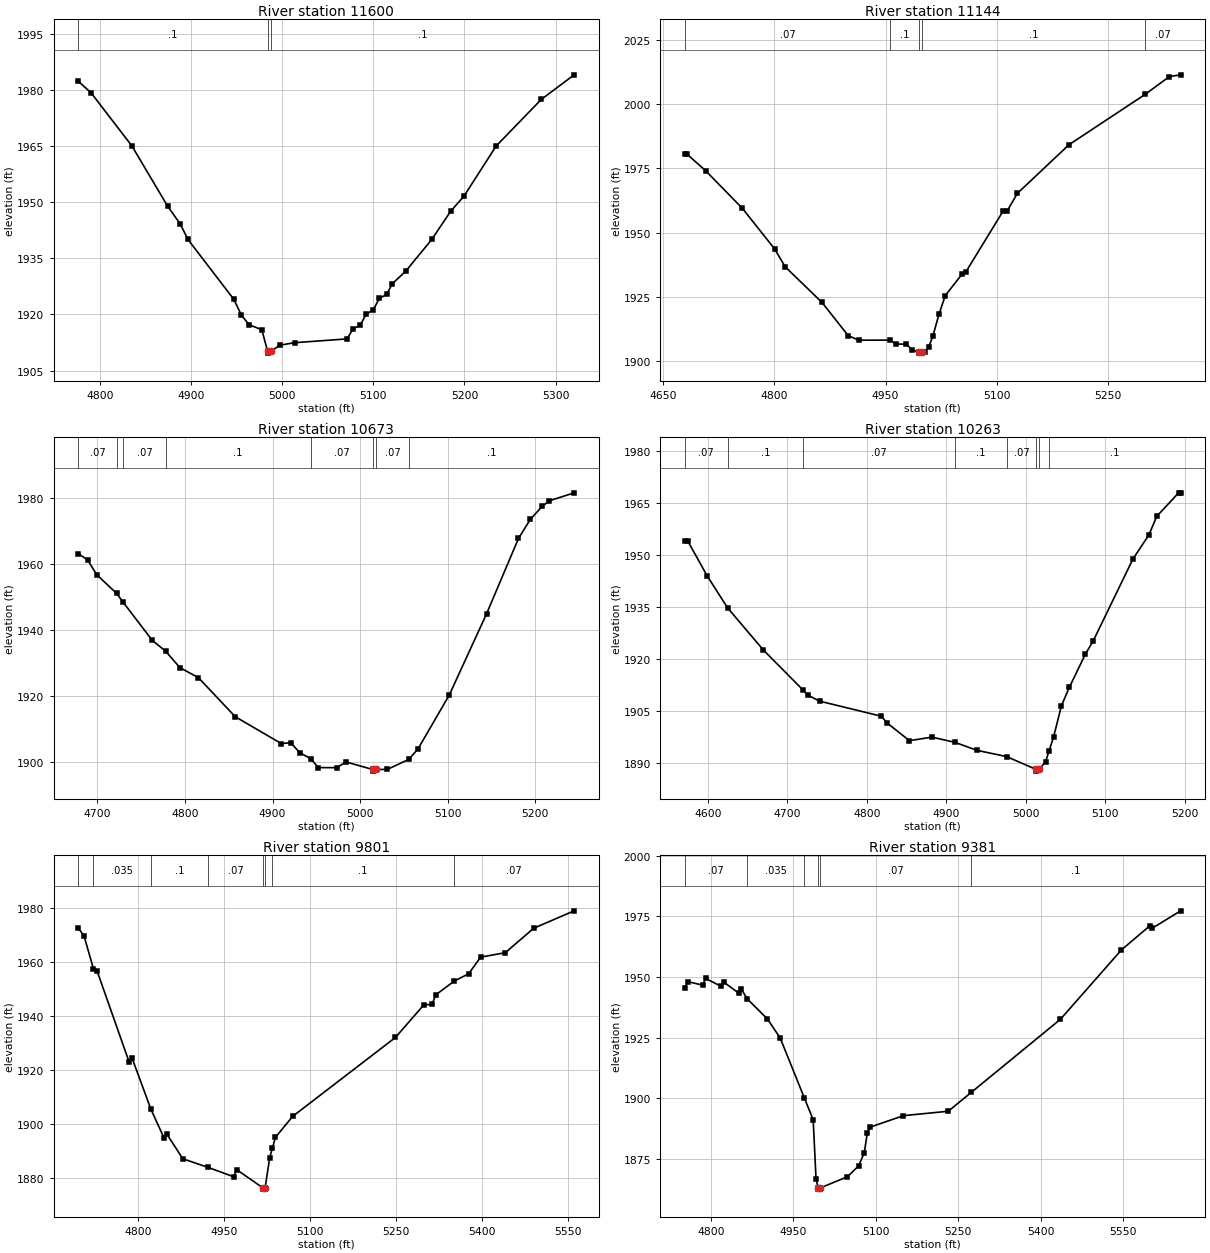
Type RM Length L Ch R = 1 ,11600   ,456,456,456
BEGIN DESCRIPTION:
Turkey Bottom Creek 70.0
END DESCRIPTION:
XS GIS Cut Line= 3
      1968524.99     13947524.99        1968325.       13947425.
      1968124.97     13947174.96
#Sta/Elev= 30
  4776.5 1982.39  4790.5  1979.3  4835.2 1965.11  4874.3 1949.03  4888.3 1944.21
  4896.7 1940.07    4947 1924.06  4955.4  1919.8  4963.8 1917.25  4977.7 1915.93
  4984.1 1910.16  4984.4 1909.66  4988.1 1910.16  4997.3 1911.78  5013.7 1912.45
  5071.3 1913.47  5077.7 1916.14  5085.7 1917.11  5092.1 1920.07  5100.1 1921.27
  5106.5 1924.28  5114.6 1925.36    5121 1928.28  5135.4 1931.53  5164.2  1940.1
    5185 1947.66  5199.4 1951.63  5234.6 1965.03  5284.2 1977.53  5320.3 1984.12
#Mann= 3 ,-1 , 0
  4776.5      .1       0  4984.1     .05       0  4988.1      .1       0
Bank Sta=4984.1,4988.1
XS Rating Curve= 0 ,0
Exp/Cntr=0.3,0.1

Type RM Length L Ch R = 1 ,11144   ,471,471,471
BEGIN DESCRIPTION:
Turkey Bottom Creek 69.0
END DESCRIPTION:
XS GIS Cut Line= 4
      1968725.01     13947225.01        1968475.       13947025.
        1968375.       13946975.      1968150.42     13946902.69
#Sta/Elev= 30
  4679.6 1980.45  4682.8 1980.45  4707.6 1974.08  4757.2 1959.41  4800.5 1943.66
  4814.9 1936.64  4864.5 1922.79  4899.7 1909.88  4914.1 1908.11  4956.3 1908.14
  4963.7 1906.64  4978.2 1906.55  4986.2 1904.25  4994.6 1903.58  4994.8 1903.08
  4998.6 1903.58  5002.6 1903.58  5008.2 1905.47  5013.7 1909.65  5022.1 1918.32
  5030.5  1925.5  5052.9 1933.75  5058.5 1934.82  5108.8 1958.57  5114.2 1958.57
  5127.6 1965.25    5197 1984.15  5299.8 2003.79  5332.2 2010.67  5347.5 2011.38
#Mann= 5 ,-1 , 0
  4679.6     .07       0  4956.3      .1       0  4994.6     .05       0
  4998.6      .1       0  5299.8     .07       0
Bank Sta=4994.6,4998.6
XS Rating Curve= 0 ,0
Exp/Cntr=0.3,0.1

Type RM Length L Ch R = 1 ,10673   ,410,410,410
BEGIN DESCRIPTION:
Turkey Bottom Creek 68.0
END DESCRIPTION:
XS GIS Cut Line= 3
      1968875.01     13946975.03        1968775.       13946675.
      1968624.98     13946474.97
#Sta/Elev= 30
  4678.2 1963.27  4688.8 1961.31  4699.3 1956.81  4721.9  1951.2  4729.6 1948.43
  4762.6 1936.94  4777.8 1933.68  4794.2 1928.67  4815.3 1925.63  4857.4 1913.78
  4910.1 1905.62  4920.7  1905.9  4931.2 1902.85  4943.7 1901.03  4952.3 1898.34
  4973.4 1898.32  4983.9 1900.07  5014.3 1897.77  5014.6 1897.27  5018.3 1897.77
  5030.9 1897.78  5055.7 1900.83  5066.3 1904.08  5101.8 1920.32  5144.5 1945.02
  5180.9 1967.85  5194.5 1973.66    5208 1977.57  5216.3 1979.29  5244.5 1981.69
#Mann= 8 ,-1 , 0
  4678.2     .07       0  4721.9      .1       0  4729.6     .07       0
  4777.8      .1       0  4943.7     .07       0  5014.3     .05       0
  5018.3     .07       0  5055.7      .1       0
Bank Sta=5014.3,5018.3
XS Rating Curve= 0 ,0
Exp/Cntr=0.3,0.1

Type RM Length L Ch R = 1 ,10263   ,462,462,462
BEGIN DESCRIPTION:
Turkey Bottom Creek 67.0
END DESCRIPTION:
XS GIS Cut Line= 3
      1969374.99     13946774.99        1969075.       13946475.
        1969075.     13946275.05
#Sta/Elev= 30
  4570.9 1954.08  4574.4 1954.08  4599.2 1943.89  4624.7 1934.74  4669.9 1922.54
  4720.1 1910.95  4726.4 1909.47  4740.6 1907.82  4818.4 1903.47  4825.4 1901.56
  4853.7 1896.42    4882 1897.44    4911 1895.94  4938.6 1893.64  4976.1 1891.83
  5013.1 1888.14  5013.4 1887.64  5017.1 1888.14  5025.1 1890.36  5029.5 1893.48
  5035.1 1897.45  5045.1 1906.55  5055.1 1911.85  5075.1 1921.33  5085.1 1925.21
  5135.1 1948.82  5155.1 1955.73  5165.1 1961.13  5192.6 1967.89  5195.1 1967.89
#Mann= 8 ,-1 , 0
  4570.9     .07       0  4624.7      .1       0  4720.1     .07       0
    4911      .1       0  4976.1     .07       0  5013.1     .05       0
  5017.1     .07       0  5029.5      .1       0
Bank Sta=5013.1,5017.1
XS Rating Curve= 0 ,0
Exp/Cntr=0.3,0.1

Type RM Length L Ch R = 1 ,9801    ,420,420,420
BEGIN DESCRIPTION:
Turkey Bottom Creek 66.0
END DESCRIPTION:
XS GIS Cut Line= 4
      1969524.99     13946774.96        1969475.       13946475.
        1969475.       13946375.      1969184.61     13946016.32
#Sta/Elev= 30
  4695.5 1972.63  4705.6 1969.58  4721.8 1957.64  4728.4 1956.63  4784.2 1923.08
  4789.2  1924.6  4822.1 1905.67    4845 1895.05  4850.1 1896.38  4877.9  1887.3
  4922.3 1884.08  4966.7 1880.64  4971.7  1883.3  5017.6 1876.57  5017.9 1876.07
  5021.6 1876.57  5029.6  1887.7  5034.2 1891.16  5039.6 1895.22  5069.6 1902.96
  5249.1 1932.15  5298.6  1944.2    5313 1944.37  5319.5  1947.9  5351.5 1952.97
    5377 1955.72  5397.8 1961.85  5440.9  1963.5  5490.5 1972.54  5561.1 1978.98
#Mann= 8 ,-1 , 0
  4695.5     .07       0  4721.8    .035       0  4822.1      .1       0
  4922.3     .07       0  5017.6     .05       0  5021.6     .07       0
  5034.2      .1       0  5351.5     .07       0
#XS Ineff= 2 , 0
         4971.58 1883.15
Permanent Ineff=
       F       F
Bank Sta=5017.6,5021.6
XS Rating Curve= 0 ,0
Exp/Cntr=0.3,0.1

Type RM Length L Ch R = 1 ,9381    ,449,449,449
BEGIN DESCRIPTION:
Turkey Bottom Creek 65.0
END DESCRIPTION:
XS GIS Cut Line= 3
      1969850.37     13946768.62        1969775.       13946525.
      1969649.96     13945890.41
#Sta/Elev= 30
  4752.7 1945.41  4757.8 1948.12  4785.2 1946.66  4790.5 1949.42  4817.8 1946.29
  4823.1 1947.99  4850.5 1943.42  4855.7 1944.93  4866.4 1940.97    4903 1932.72
  4926.2  1924.9  4970.4 1900.05  4986.2 1891.23  4991.4 1866.88  4995.2 1863.16
  4995.5 1862.66  4999.2 1863.16  5048.5 1867.77  5068.9 1872.25  5079.1 1877.64
  5084.7 1885.81  5089.8 1888.19  5150.4 1892.92  5231.9 1894.73  5274.1 1902.57
  5435.8 1932.58  5546.8 1961.15  5598.2 1971.04  5603.3 1970.15  5654.5 1977.26
#Mann= 6 ,-1 , 0
  4752.7     .07       0  4866.4    .035       0  4970.4     .07       0
  4995.2     .05       0  4999.2     .07       0  5274.1      .1       0
Bank Sta=4995.2,4999.2
XS Rating Curve= 0 ,0
Exp/Cntr=0.3,0.1

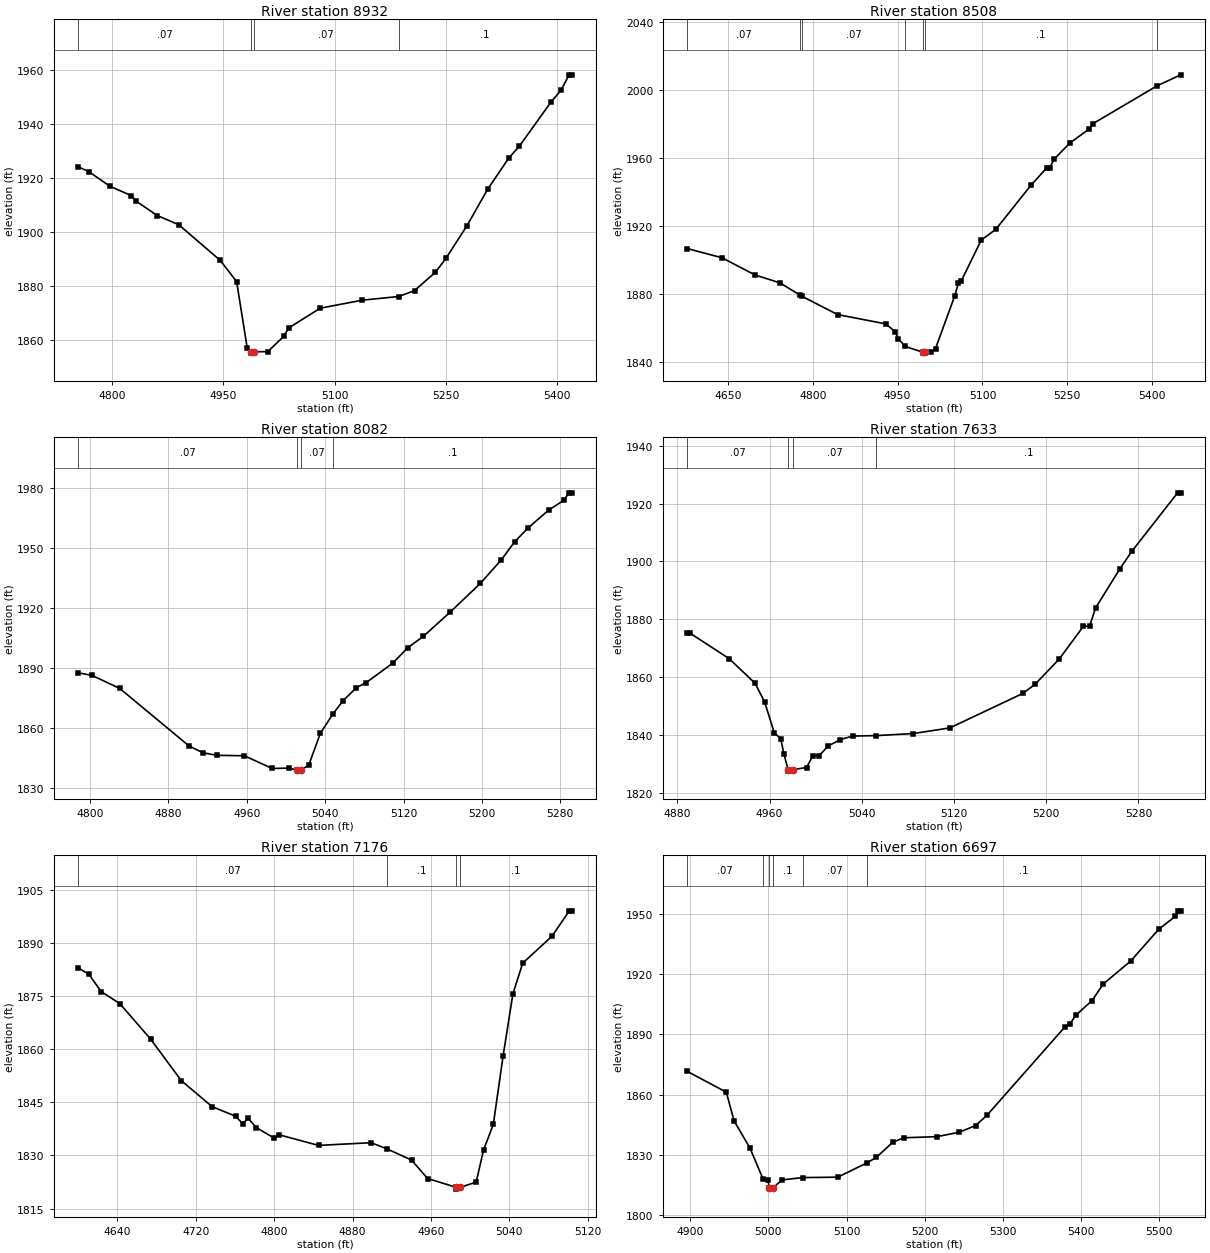
Type RM Length L Ch R = 1 ,8932    ,424,424,424
BEGIN DESCRIPTION:
Turkey Bottom Creek 64.0
END DESCRIPTION:
XS GIS Cut Line= 3
      1970278.37     13946461.95        1970125.       13946275.
      1969824.98     13945974.98
#Sta/Elev= 30
    4754 1924.05  4768.3 1922.24    4797 1916.79  4825.7 1913.38  4832.2 1911.29
  4860.9 1905.97  4889.6 1902.61  4945.6 1889.42  4967.8 1881.57  4982.2 1856.79
  4986.6 1855.57  4986.9 1855.07  4990.6 1855.57  5009.9 1855.62  5031.2 1861.23
  5038.2 1864.41  5080.7  1871.7  5137.2 1874.66  5186.3 1876.02  5207.9  1878.2
  5236.2 1885.04  5250.4 1890.17  5278.6 1902.18  5306.9 1915.84  5335.2  1927.3
  5349.4 1931.63  5391.8 1947.89  5405.9 1952.45  5416.5 1958.07  5420.1 1958.07
#Mann= 4 ,-1 , 0
    4754     .07       0  4986.6     .05       0  4990.6     .07       0
  5186.3      .1       0
Bank Sta=4986.6,4990.6
XS Rating Curve= 0 ,0
Exp/Cntr=0.3,0.1

Type RM Length L Ch R = 1 ,8508    ,426,426,426
BEGIN DESCRIPTION:
Turkey Bottom Creek 63.0
END DESCRIPTION:
XS GIS Cut Line= 3
      1970365.64     13946344.45        1970325.       13945925.
      1970210.57     13945488.57
#Sta/Elev= 30
    4578  1906.7  4639.6 1901.25    4698 1891.11  4741.7 1886.52  4778.2 1879.14
  4780.5 1878.65  4843.8 1867.83  4929.1 1862.33  4945.9 1857.66  4950.9 1853.68
  4963.4 1849.07  4994.9 1845.62  4995.2 1845.12  4998.9 1845.62  5009.8 1845.71
    5017 1847.82  5051.1  1878.9  5057.4 1886.23  5062.6  1887.6  5097.8 1911.67
  5123.5 1917.96  5185.5 1943.85  5213.8 1954.24    5219 1954.24  5226.9 1959.39
  5254.2  1968.7  5288.9 1977.16  5294.6 1980.08  5408.7  2002.5  5450.6 2008.98
#Mann= 7 ,-1 , 0
    4578     .07       0  4778.2      .1       0  4780.5     .07       0
  4963.4      .1       0  4994.9     .05       0  4998.9      .1       0
  5408.7     .07       0
Bank Sta=4994.9,4998.9
XS Rating Curve= 0 ,0
Exp/Cntr=0.3,0.1

Type RM Length L Ch R = 1 ,8082    ,449,449,449
BEGIN DESCRIPTION:
Turkey Bottom Creek 62.0
END DESCRIPTION:
XS GIS Cut Line= 3
      1970475.01     13946224.99        1970625.       13946075.
      1970775.02     13945824.97
#Sta/Elev= 30
  4787.9 1887.41    4802  1886.1  4830.3 1879.58    4901 1850.81  4915.2 1847.43
  4929.3 1846.13  4957.6  1845.9  4985.9 1839.54  5002.9 1839.74  5011.6 1838.72
  5011.9 1838.22  5015.6 1838.72  5023.3 1841.36    5035 1857.08  5047.8 1866.79
  5058.3 1873.49  5071.9 1880.01  5081.6 1882.43  5108.9 1892.22  5124.4 1900.04
    5140 1905.58  5167.2 1917.62  5198.3 1932.12  5219.6 1943.86  5233.3 1952.92
  5246.9 1959.82  5268.2 1968.86  5283.8  1973.8  5288.6 1977.46  5291.6 1977.46
#Mann= 4 ,-1 , 0
  4787.9     .07       0  5011.6     .05       0  5015.6     .07       0
  5047.8      .1       0
Bank Sta=5011.6,5015.6
XS Rating Curve= 0 ,0
Exp/Cntr=0.3,0.1

Type RM Length L Ch R = 1 ,7633    ,457,457,457
BEGIN DESCRIPTION:
Turkey Bottom Creek 61.0
END DESCRIPTION:
XS GIS Cut Line= 3
      1970874.98     13946475.04        1970925.       13946375.
      1971025.01     13946074.98
#Sta/Elev= 30
  4888.6 1875.08  4891.4 1875.08    4925 1866.35  4947.3 1857.91  4955.7 1851.47
  4964.1 1840.73  4969.7  1838.7  4972.5 1833.34  4976.1 1827.98  4976.3 1827.48
  4980.1 1827.98  4992.1 1828.73  4997.7 1832.88  5003.1 1832.88    5011 1836.21
  5021.5  1838.4  5032.1  1839.6  5052.7 1839.76  5084.8 1840.48  5116.4 1842.42
  5179.6 1854.32  5190.2 1857.45  5211.3 1866.24  5232.3 1877.56  5237.6 1877.56
  5242.9 1883.94    5264 1897.48  5274.5 1903.59    5314 1923.69  5316.7 1923.69
#Mann= 4 ,-1 , 0
  4888.6     .07       0  4976.1     .05       0  4980.1     .07       0
  5052.7      .1       0
Bank Sta=4976.1,4980.1
XS Rating Curve= 0 ,0
Exp/Cntr=0.3,0.1

Type RM Length L Ch R = 1 ,7176    ,479,479,479
BEGIN DESCRIPTION:
Turkey Bottom Creek 60.0
END DESCRIPTION:
XS GIS Cut Line= 3
      1971454.59      13946607.2        1971325.       13946225.
        1971325.     13946124.98
#Sta/Elev= 30
    4600 1883.02    4611 1881.12  4623.4 1876.31  4642.4  1872.9  4673.8  1862.9
  4705.2 1851.14  4736.6 1843.81  4760.7 1841.07    4768 1838.94  4773.3 1840.54
  4781.8 1837.88  4799.4 1835.01  4804.7 1835.87  4845.2 1832.85  4898.9 1833.61
  4915.4 1831.83  4940.2  1828.7  4956.5  1823.5  4985.8    1821    4986  1820.5
    4990    1821  5006.1  1822.5  5013.6 1831.52  5023.6  1838.8  5033.6 1858.15
  5043.6 1875.69  5053.6 1884.33  5083.6 1891.97  5101.1  1899.1  5103.6  1899.1
#Mann= 4 ,-1 , 0
    4600     .07       0  4915.4      .1       0  4985.8     .05       0
    4990      .1       0
Bank Sta=4985.8,4990
XS Rating Curve= 0 ,0
Exp/Cntr=0.3,0.1

Type RM Length L Ch R = 1 ,6697    ,469,469,469
BEGIN DESCRIPTION:
Turkey Bottom Creek 59.0
END DESCRIPTION:
XS GIS Cut Line= 3
        1971775.     13946425.02        1971775.       13946325.
      1971425.02     13945925.02
#Sta/Elev= 30
  4896.1 1871.58  4946.1  1861.2  4956.1 1846.86  4976.1 1833.59  4992.9 1818.22
  4999.4 1817.62  5001.1 1813.45  5001.4 1812.95  5005.4 1813.45  5017.5 1817.56
  5044.2  1818.7  5088.7  1818.9  5126.1 1826.03    5138 1828.71  5158.9 1836.22
  5173.1 1838.51  5215.8 1839.07  5244.3 1841.28  5265.2 1844.62  5279.4  1849.6
  5379.1 1893.56  5385.7 1895.11  5393.3 1899.49  5414.2 1906.84  5428.4 1915.05
  5463.6  1926.5  5499.6 1942.36  5520.5 1948.68  5524.3 1951.48  5527.6 1951.48
#Mann= 6 ,-1 , 0
  4896.1     .07       0  4992.9      .1       0  5001.1     .05       0
  5005.4      .1       0  5044.2     .07       0  5126.1      .1       0
Bank Sta=5001.1,5005.4
XS Rating Curve= 0 ,0
Exp/Cntr=0.3,0.1

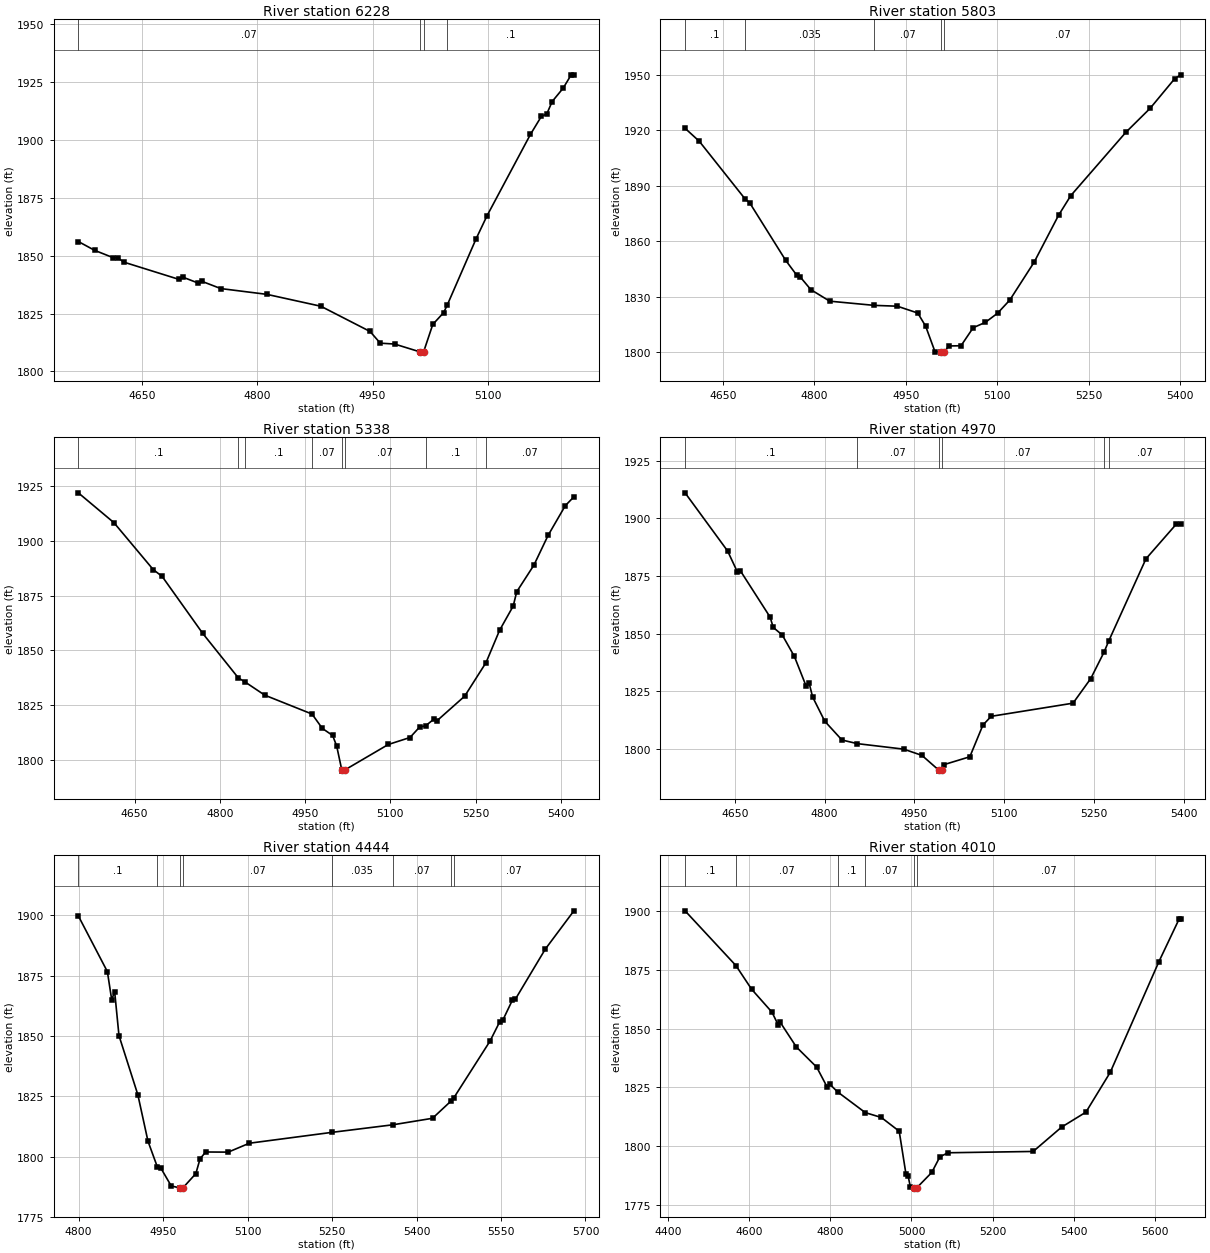
Type RM Length L Ch R = 1 ,6228    ,425,425,425
BEGIN DESCRIPTION:
Turkey Bottom Creek 58.0
END DESCRIPTION:
XS GIS Cut Line= 4
      1971962.71     13946380.22      1972070.68     13946097.24
        1972025.       13945975.      1971875.01     13945825.01
#Sta/Elev= 30
  4566.7  1856.1  4587.8 1852.31  4612.5 1849.06  4617.8 1849.17  4625.8 1847.21
  4697.4 1839.79  4702.7 1840.73  4722.1 1838.24  4727.4 1838.94  4752.2 1835.78
  4812.3 1833.28  4882.6 1828.15  4946.7 1817.25    4960  1812.2  4978.7 1811.82
  5012.1  1808.4  5012.4  1807.9  5016.4  1808.4  5028.4  1820.3  5042.5 1825.37
  5047.2 1828.63  5084.9 1857.34  5099.1 1867.25  5155.6 1902.35  5169.8 1910.12
  5176.9  1911.2  5183.9 1916.55  5198.1 1922.27  5208.7 1928.08  5212.2 1928.08
#Mann= 4 ,-1 , 0
  4566.7     .07       0  5012.1     .05       0  5016.4     .07       0
  5047.2      .1       0
Bank Sta=5012.1,5016.4
XS Rating Curve= 0 ,0
Exp/Cntr=0.3,0.1

Type RM Length L Ch R = 1 ,5803    ,465,465,465
BEGIN DESCRIPTION:
Turkey Bottom Creek 57.0
END DESCRIPTION:
XS GIS Cut Line= 3
      1972675.04     13945775.01        1972275.       13945675.
      1971875.05       13945675.
#Sta/Elev= 30
  4588.1 1921.03  4611.3 1914.07  4686.7 1882.79  4693.8 1880.91  4753.1  1849.7
  4771.1 1841.74  4776.3 1840.99  4794.3 1833.91  4825.2 1827.69  4898.3 1825.42
    4936 1824.98  4969.5 1821.29  4982.4 1814.21  4997.9 1800.28  5007.9 1800.14
  5008.3 1799.64  5012.9 1800.14  5020.4  1803.5  5040.4 1803.63  5060.4 1813.37
  5080.4 1816.26  5100.4 1821.21  5120.4  1828.3  5160.4 1848.82  5200.4 1874.13
  5220.4 1884.71  5310.4 1918.79  5350.4 1931.82  5390.4 1947.71  5400.4  1949.9
#Mann= 5 ,-1 , 0
  4588.1      .1       0  4686.7    .035       0  4898.3     .07       0
  5007.9     .05       0  5012.9     .07       0
Bank Sta=5007.9,5012.9
XS Rating Curve= 0 ,0
Exp/Cntr=0.3,0.1

Type RM Length L Ch R = 1 ,5338    ,368,368,368
BEGIN DESCRIPTION:
Turkey Bottom Creek 56.0
END DESCRIPTION:
XS GIS Cut Line= 3
      1972743.98     13945075.65        1972325.       13945225.
        1971925.       13945375.
#Sta/Elev= 30
  4551.1    1922  4613.7 1908.37  4682.9  1886.9  4698.6 1883.77  4770.1 1857.69
  4832.8 1837.33  4844.1 1835.58  4879.1 1829.49  4962.3 1820.85  4980.5 1814.27
  4998.6 1811.05  5005.7 1806.23  5014.7 1795.25  5015.1 1794.75  5019.8 1795.25
  5096.5 1806.93  5134.7 1810.12  5151.6  1814.9    5162 1815.45  5176.6 1818.48
  5181.9 1817.71  5230.9 1829.02  5268.5 1844.38  5292.3 1859.12  5316.3 1870.22
  5322.5 1876.77  5352.8 1888.97  5377.7 1902.54    5408 1916.14  5423.1 1920.16
#Mann= 8 ,-1 , 0
  4551.1      .1       0  4832.8     .07       0  4844.1      .1       0
  4962.3     .07       0  5014.7     .05       0  5019.8     .07       0
    5162      .1       0  5268.5     .07       0
Bank Sta=5014.7,5019.8
XS Rating Curve= 0 ,0
Exp/Cntr=0.3,0.1

Type RM Length L Ch R = 1 ,4970    ,526,526,526
BEGIN DESCRIPTION:
Turkey Bottom Creek 55.0
END DESCRIPTION:
XS GIS Cut Line= 3
      1972625.03     13944824.99      1972196.02     13944898.78
      1971875.02     13945124.98
#Sta/Elev= 30
  4566.9 1911.12    4638  1885.9  4654.3 1876.84  4659.4 1877.29    4709 1857.24
  4714.2 1852.78  4729.3 1849.49  4749.6 1840.17  4769.1 1827.37  4774.2 1828.61
    4780 1822.64  4800.3 1812.11    4829 1803.97  4854.6 1802.39  4932.2    1800
  4962.7 1797.29  4990.5 1790.97  4990.9 1790.47  4995.7 1790.97  5000.2 1793.34
  5042.7  1796.7  5064.6 1810.46  5078.4 1814.23  5215.1 1819.93  5244.7 1830.58
  5266.9 1842.04  5275.1 1847.09    5337 1882.53  5387.5 1897.51  5394.9 1897.59
#Mann= 6 ,-1 , 0
  4566.9      .1       0  4854.6     .07       0  4990.5     .05       0
  4995.7     .07       0  5266.9      .1       0  5275.1     .07       0
Bank Sta=4990.5,4995.7
XS Rating Curve= 0 ,0
Exp/Cntr=0.3,0.1

Type RM Length L Ch R = 1 ,4444    ,434,434,434
BEGIN DESCRIPTION:
Turkey Bottom Creek 54.0
END DESCRIPTION:
XS GIS Cut Line= 4
      1972625.03     13944575.01        1972425.       13944525.
        1972325.       13944525.      1971809.38     13944272.97
#Sta/Elev= 30
  4799.4 1899.75    4851 1876.65  4858.7 1864.98  4863.9 1868.41  4871.6 1850.15
  4905.1 1825.64  4923.1 1806.39  4939.8 1795.69  4946.3  1795.1  4964.4 1787.85
  4979.7 1787.03  4980.1 1786.53    4985 1787.03  5008.1 1792.95  5015.6  1799.1
  5025.6 1801.92  5065.6 1801.86  5103.1 1805.55  5249.7 1810.05  5357.8 1813.18
  5428.4 1815.88  5461.8 1823.14  5465.9 1824.23  5530.5 1847.85  5547.4 1855.69
    5553 1856.41    5570 1864.71  5575.5  1865.2  5628.7 1885.97  5679.5 1901.84
#Mann= 8 ,-1 , 0
  4799.4      .1       0  4939.8     .07       0  4979.7     .05       0
    4985     .07       0  5249.7    .035       0  5357.8     .07       0
  5461.8    .035       0  5465.9     .07       0
Bank Sta=4979.7,4985
XS Rating Curve= 0 ,0
Exp/Cntr=0.3,0.1

Type RM Length L Ch R = 1 ,4010    ,447,447,447
BEGIN DESCRIPTION:
Turkey Bottom Creek 53.0
END DESCRIPTION:
XS GIS Cut Line= 4
      1973058.61     13944002.94      1972708.23     13944028.97
        1972525.       13944125.      1971861.54     13944129.91
#Sta/Elev= 30
  4441.8 1900.19  4567.1 1876.87  4605.9 1866.76    4656    1857  4671.5 1851.54
  4676.6 1852.62  4716.2 1842.15  4766.3 1833.56  4792.3    1825  4798.9 1826.23
  4817.8 1823.01  4886.1 1814.17  4925.6 1812.11  4969.7 1806.25  4986.2 1788.16
  4991.8 1787.03  4997.2 1782.57  5007.3 1782.06  5007.7 1781.56  5012.7 1782.06
    5050 1788.68    5070 1795.33    5090 1797.06    5300 1797.62    5370 1807.99
    5430 1814.37    5490 1831.36    5610 1878.55  5659.3 1896.53  5663.5 1896.53
#Mann= 6 ,-1 , 0
  4441.8      .1       0  4567.1     .07       0  4817.8      .1       0
  4886.1     .07       0  5007.3     .05       0  5012.7     .07       0
Bank Sta=5007.3,5012.7
XS Rating Curve= 0 ,0
Exp/Cntr=0.3,0.1