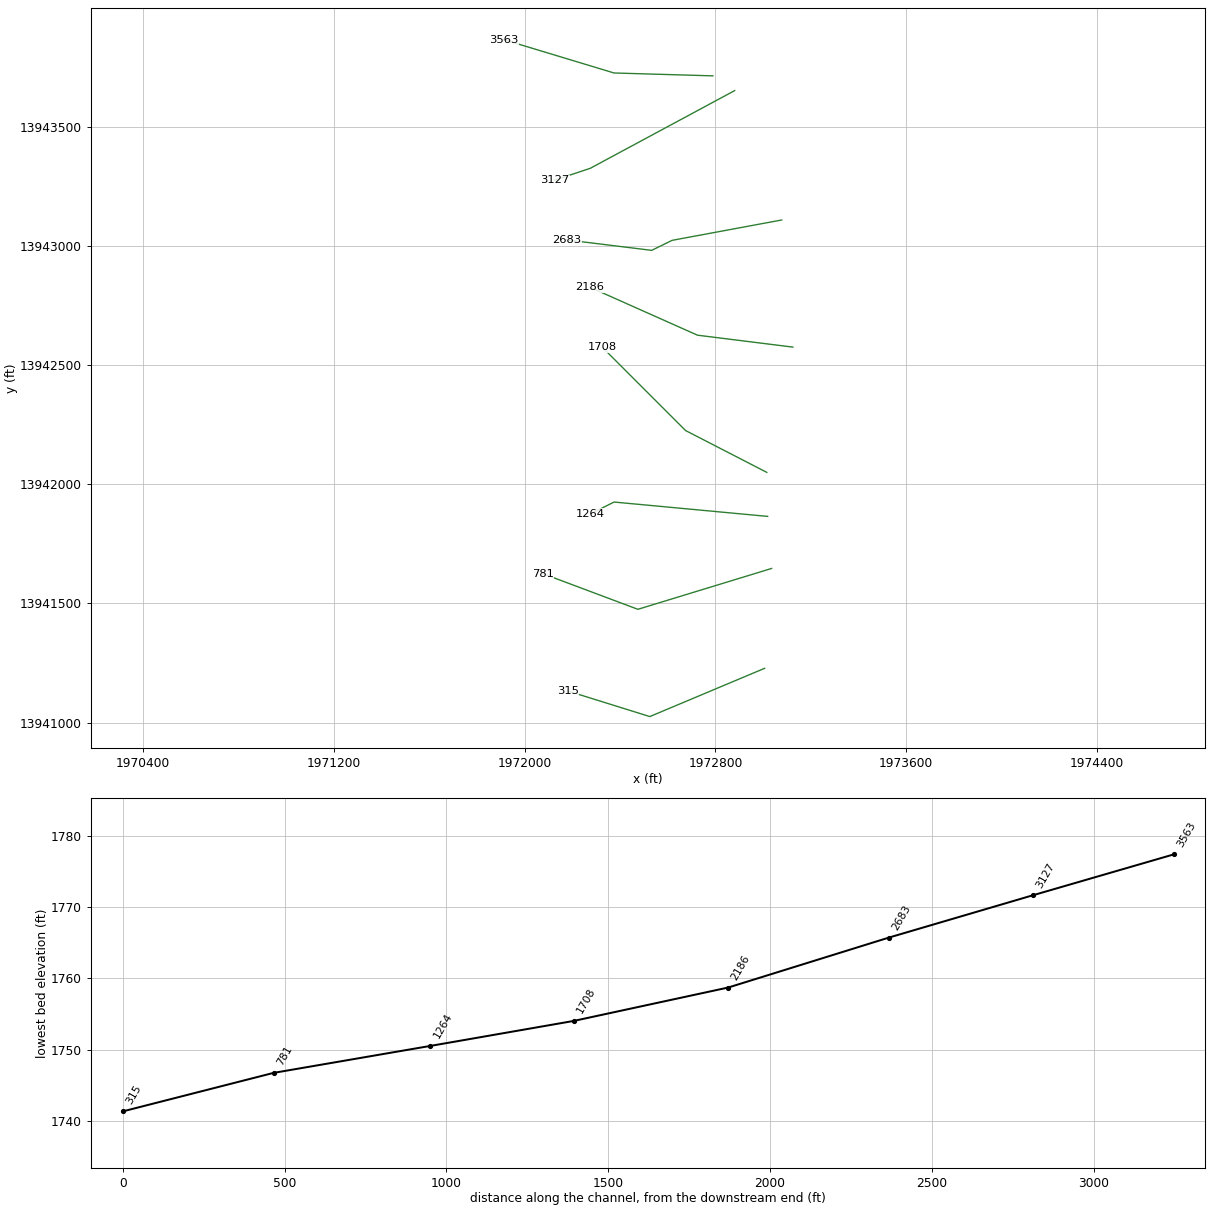
HEC-RAS study Turkey Bottom Creek.prj: Turkey Bottom Creek Base Level Engineering

--- Turkey Bottom Creek.g01 (geometry) --- (continued)

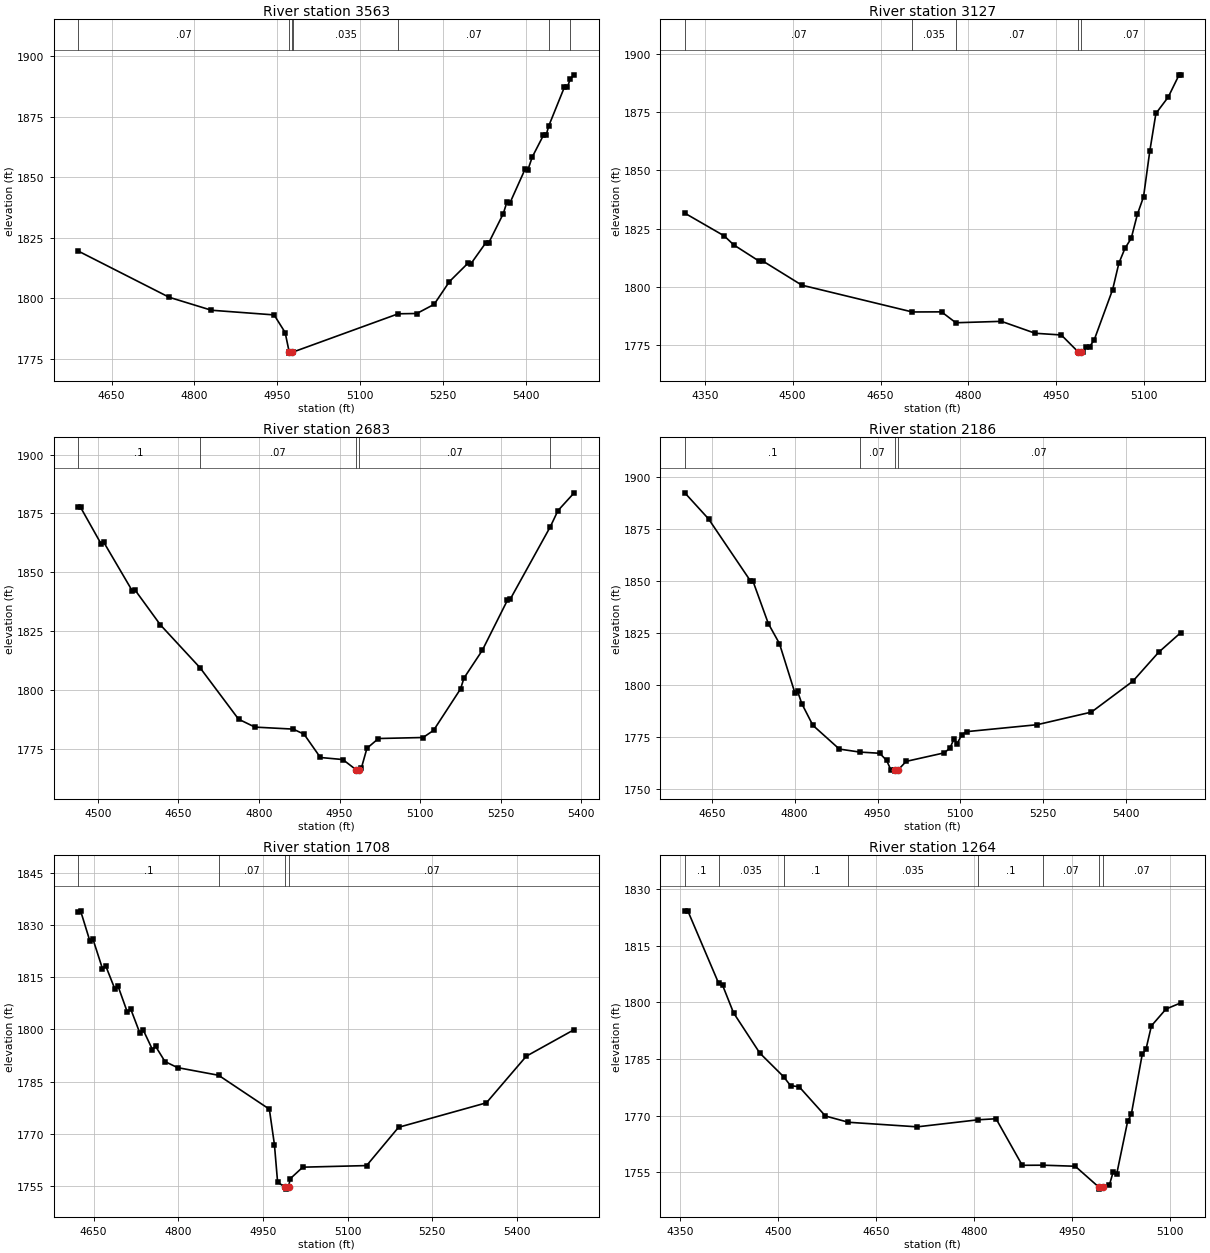
Type RM Length L Ch R = 1 ,3563    ,436,436,436
BEGIN DESCRIPTION:
Turkey Bottom Creek 52.0
END DESCRIPTION:
XS GIS Cut Line= 3
      1972789.48     13943712.95        1972375.       13943725.
      1971912.22     13943864.85
#Sta/Elev= 30
  4589.9 1819.54  4754.4 1800.47    4831 1795.11  4944.5 1793.18  4964.5 1785.91
  4971.8 1777.89  4972.2 1777.39  4977.3 1777.89  4979.6 1777.91  5169.3 1793.64
    5203 1793.76  5234.4 1797.55  5262.2 1806.98  5295.1 1814.42  5300.3 1814.09
  5328.1 1823.02  5333.3 1822.97  5359.7 1835.05  5366.2  1839.8  5371.5 1839.35
  5399.2 1853.45  5404.4 1853.25    5412 1858.36  5432.2 1867.35  5437.4 1867.56
    5442 1871.27  5470.3 1887.25  5475.6 1887.31  5481.3 1890.78    5488 1892.37
#Mann= 7 ,-1 , 0
  4589.9     .07       0  4971.8    .035       0  4977.3     .07       0
  4979.6    .035       0  5169.3     .07       0    5442    .035       0
  5481.3     .07       0
Bank Sta=4971.8,4977.3
XS Rating Curve= 0 ,0
Exp/Cntr=0.3,0.1

Type RM Length L Ch R = 1 ,3127    ,444,444,444
BEGIN DESCRIPTION:
Turkey Bottom Creek 51.0
END DESCRIPTION:
XS GIS Cut Line= 3
      1972880.84     13943650.99        1972275.       13943325.
      1972124.99       13943275.
#Sta/Elev= 30
  4315.9 1831.68  4383.1 1821.94  4399.4 1818.08  4443.2 1811.02  4448.9 1811.17
  4515.6  1800.8  4704.2  1789.3    4754 1789.35  4778.4 1784.68  4856.2 1785.28
  4913.8 1780.17  4958.4 1779.43  4987.3 1772.15  4987.8 1771.65  4992.8 1772.15
  4995.8 1772.18    5001  1774.4  5006.5  1774.4  5014.4 1777.23    5046 1798.92
  5056.6  1810.2  5067.1 1816.64  5077.7 1820.88  5088.2 1831.18  5098.7 1838.67
  5109.3 1858.15  5119.8 1874.43  5140.9 1881.49  5159.4 1891.01    5162 1891.01
#Mann= 5 ,-1 , 0
  4315.9     .07       0  4704.2    .035       0  4778.4     .07       0
  4987.3     .05       0  4992.8     .07       0
Bank Sta=4987.3,4992.8
XS Rating Curve= 0 ,0
Exp/Cntr=0.3,0.1

Type RM Length L Ch R = 1 ,2683    ,497,497,497
BEGIN DESCRIPTION:
Turkey Bottom Creek 50.0
END DESCRIPTION:
XS GIS Cut Line= 4
      1973078.46      13943108.3      1972618.48     13943022.89
      1972532.85     13942980.86      1972174.99       13943025.
#Sta/Elev= 30
  4463.4 1877.56  4467.7 1877.56  4505.7 1862.16  4510.8 1862.79  4563.6 1842.31
  4568.7 1842.65  4616.4 1827.73  4690.2 1809.57  4761.9 1787.77  4792.4  1784.4
  4863.6 1783.55  4883.9 1781.41  4914.4 1771.51  4956.2 1770.64  4981.4 1766.23
  4981.9 1765.73    4987 1766.23  4990.8 1767.06  5001.1 1775.41  5022.6 1779.56
  5105.7 1779.99  5125.2    1783  5175.6 1800.62  5181.8 1805.16  5215.9  1816.9
  5262.9 1838.22    5268  1838.6  5342.8 1869.39    5357 1876.21  5387.2 1883.76
#Mann= 5 ,-1 , 0
  4463.4      .1       0  4690.2     .07       0  4981.4     .05       0
    4987     .07       0  5342.8    .035       0
Bank Sta=4981.4,4987
XS Rating Curve= 0 ,0
Exp/Cntr=0.3,0.1

Type RM Length L Ch R = 1 ,2186    ,478,478,478
BEGIN DESCRIPTION:
Turkey Bottom Creek 49.0
END DESCRIPTION:
XS GIS Cut Line= 3
      1973125.02       13942575.        1972725.       13942625.
      1972273.52     13942826.16
#Sta/Elev= 30
  4601.2 1892.22  4644.1 1879.74  4719.6 1850.13  4724.7 1849.77  4752.4 1829.48
  4772.5 1819.91  4800.3 1796.39  4805.3 1797.06  4812.9 1791.12    4833  1780.7
  4880.9  1769.3  4917.9 1767.86  4953.9 1767.29  4966.5 1763.86  4974.1 1759.34
  4981.3 1759.22  4981.8 1758.72    4987 1759.22  5001.8 1763.39  5070.6 1767.47
    5081 1769.73  5088.4 1774.11  5093.9 1771.83  5102.9 1776.28  5111.6 1777.67
  5238.7 1780.98  5337.1 1787.03  5412.3 1801.89  5458.8 1815.73  5498.6 1825.09
#Mann= 4 ,-1 , 0
  4601.2      .1       0  4917.9     .07       0  4981.3     .05       0
    4987     .07       0
Bank Sta=4981.3,4987
XS Rating Curve= 0 ,0
Exp/Cntr=0.3,0.1

Type RM Length L Ch R = 1 ,1708    ,444,444,444
BEGIN DESCRIPTION:
Turkey Bottom Creek 48.0
END DESCRIPTION:
XS GIS Cut Line= 3
      1973015.87      13942049.4        1972675.       13942225.
      1972325.01     13942574.99
#Sta/Elev= 30
  4622.9 1833.82  4626.9 1834.16  4643.4 1825.45    4649 1825.91  4665.6 1817.54
  4671.2  1818.4  4687.7 1811.62  4693.4  1812.4  4709.9  1804.9  4715.5 1805.98
  4732.1 1798.87  4737.7  1799.9  4754.2 1794.21  4759.9 1795.12  4776.4 1790.76
  4798.6 1789.02  4871.4 1786.81  4961.3 1777.05  4970.3 1766.85  4975.9 1756.06
  4989.6 1754.53    4990 1754.03  4995.3 1754.53  4998.1    1757  5020.5 1760.35
  5133.6 1760.81  5190.2 1771.83  5345.8 1778.88  5416.5  1792.3  5501.3 1799.95
#Mann= 4 ,-1 , 0
  4622.9      .1       0  4871.4     .07       0  4989.6     .05       0
  4995.3     .07       0
Bank Sta=4989.6,4995.3
XS Rating Curve= 0 ,0
Exp/Cntr=0.3,0.1

Type RM Length L Ch R = 1 ,1264    ,483,483,483
BEGIN DESCRIPTION:
Turkey Bottom Creek 47.0
END DESCRIPTION:
XS GIS Cut Line= 3
      1973019.28     13941864.76        1972375.       13941925.
        1972275.       13941875.
#Sta/Elev= 30
    4357 1824.24  4361.6 1824.24  4408.9    1805  4414.9  1804.5  4431.6 1797.22
  4471.8 1786.56  4508.2 1780.31  4518.8 1777.93    4532 1777.64  4572.2 1769.89
  4607.5 1768.23  4712.8 1767.02  4806.1 1768.89  4833.4 1769.16  4873.5 1756.83
  4905.4 1756.86  4954.6 1756.58  4990.9 1751.02  4991.4 1750.52  4997.1 1751.02
  5006.9 1751.63  5012.5 1754.97  5018.1 1754.56  5034.8 1768.48  5040.4 1770.33
  5057.2 1786.29  5062.8 1787.52  5071.2 1793.78  5093.5 1798.22  5115.9 1799.84
#Mann= 8 ,-1 , 0
    4357      .1       0  4408.9    .035       0  4508.2      .1       0
  4607.5    .035       0  4806.1      .1       0  4905.4     .07       0
  4990.9     .05       0  4997.1     .07       0
Bank Sta=4990.9,4997.1
XS Rating Curve= 0 ,0
Exp/Cntr=0.3,0.1

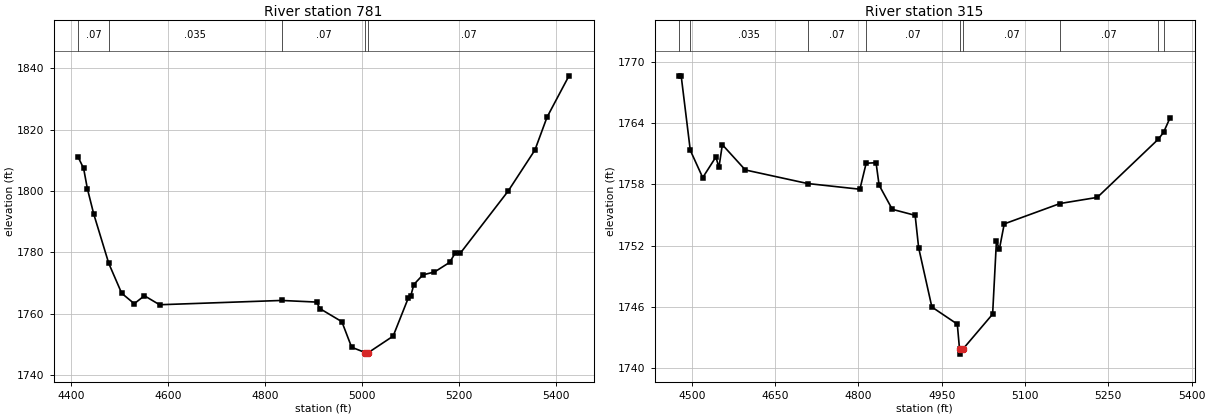
Type RM Length L Ch R = 1 ,781     ,466,466,466
BEGIN DESCRIPTION:
Turkey Bottom Creek 46.0
END DESCRIPTION:
XS GIS Cut Line= 3
      1973035.92     13941646.34        1972475.       13941475.
      1972075.01       13941625.
#Sta/Elev= 30
  4413.9 1811.09  4425.3  1807.4  4433.1 1800.73  4446.2 1792.49  4477.3 1776.35
  4503.9 1766.63  4529.9 1763.21  4550.8 1765.81  4582.2 1762.87    4834 1764.27
  4906.3 1763.74  4913.2 1761.61  4958.6 1757.34  4978.8 1748.99  5007.1 1747.25
  5007.6 1746.75  5013.3 1747.25  5064.5 1752.63  5095.6    1765    5101 1765.77
  5107.2 1769.47  5125.9 1772.62  5149.9 1773.56  5181.1 1776.69  5192.6 1779.71
  5203.3 1779.71  5302.1 1799.99  5357.3 1813.37  5382.2 1824.06  5427.6 1837.59
#Mann= 5 ,-1 , 0
  4413.9     .07       0  4477.3    .035       0    4834     .07       0
  5007.1     .05       0  5013.3     .07       0
Bank Sta=5007.1,5013.3
XS Rating Curve= 0 ,0
Exp/Cntr=0.3,0.1

Type RM Length L Ch R = 1 ,315     ,0,0,0
BEGIN DESCRIPTION:
Turkey Bottom Creek 45.0
END DESCRIPTION:
XS GIS Cut Line= 3
      1973006.77     13941227.48        1972525.       13941025.
      1972180.06     13941132.52
#Sta/Elev= 30
  4477.1 1768.64  4480.8 1768.64  4497.2 1761.34  4519.6 1758.66  4543.3 1760.68
  4548.8 1759.66  4554.9 1761.89  4596.3 1759.41  4708.3 1758.08  4802.6 1757.52
  4813.9 1760.07  4831.7 1760.12  4837.2 1757.92  4860.9 1755.55  4902.1 1754.96
  4908.4 1751.78  4932.2 1745.97    4978 1744.29    4982 1741.85  4982.5 1741.35
  4988.2 1741.85  5041.6 1745.27  5048.5 1752.47  5053.7 1751.62  5062.5 1754.12
  5163.1 1756.12  5230.1 1756.72    5340 1762.43  5349.3 1763.09    5361 1764.51
#Mann= 9 ,-1 , 0
  4477.1      .1       0  4497.2    .035       0  4708.3     .07       0
  4813.9     .07       0    4982     .05       0  4988.2     .07       0
  5163.1     .07       0    5340      .1       0  5349.3     .07       0
Bank Sta=4982,4988.2
XS Rating Curve= 0 ,0
Exp/Cntr=0.3,0.1

Chan Stop Cuts=-1
Use User Specified Reach Order=0
Composite Channel Slope=5