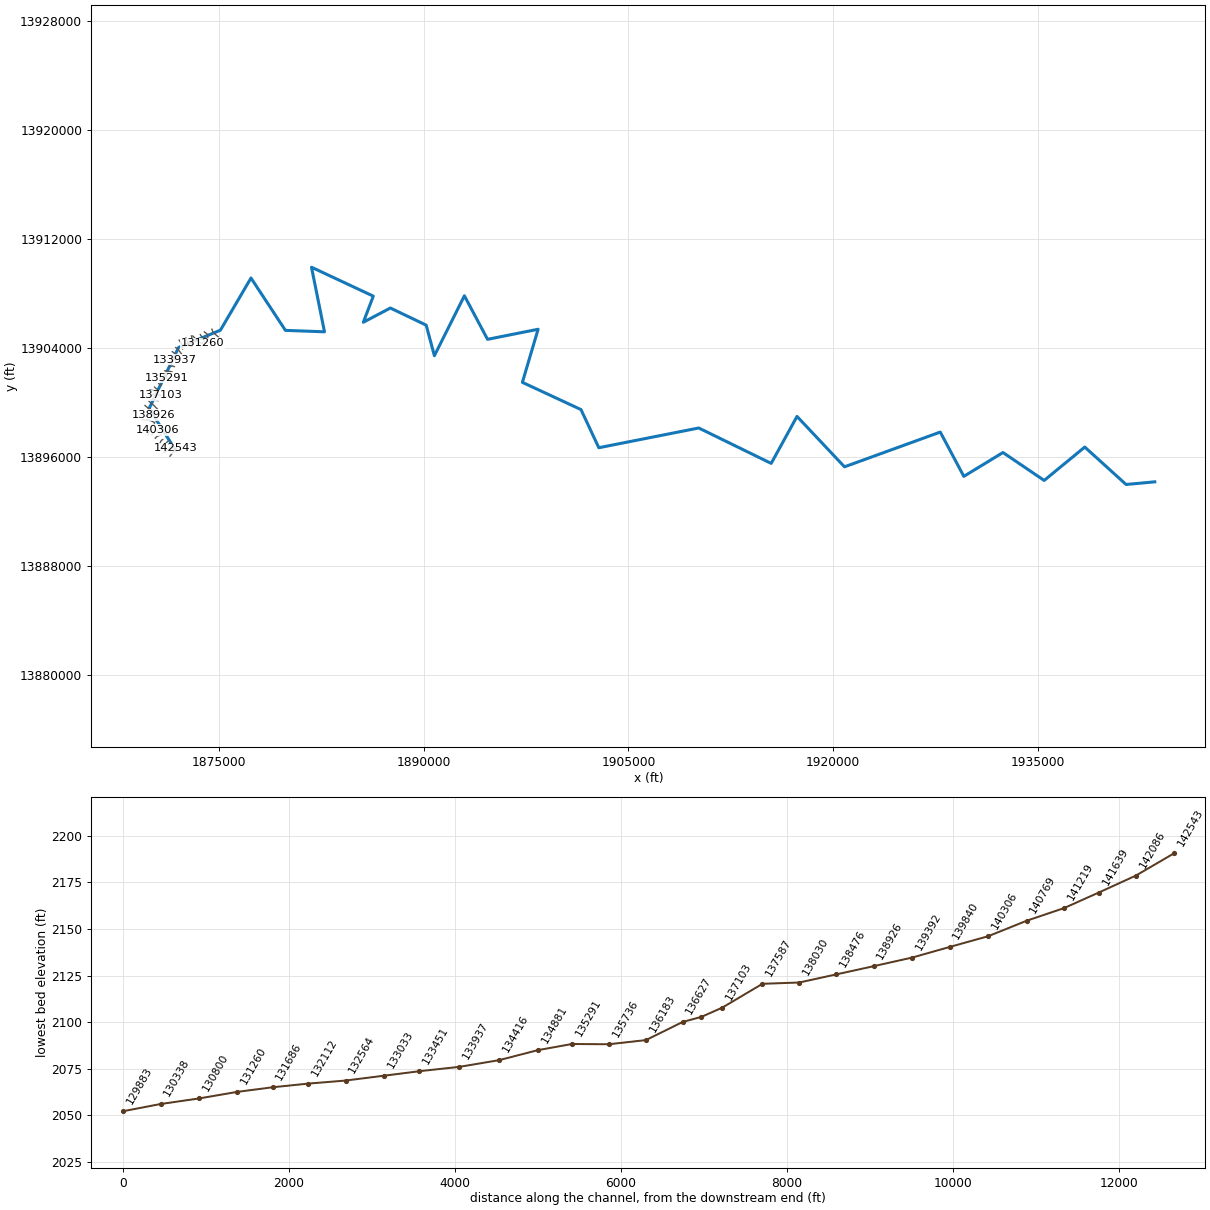
--- Turtle Creek.prj (project) ---

Proj Title=Turtle Creek Base Level Engineering
Current Plan=p01
Default Exp/Contr=0.3,0.1
English Units
Geom File=g01
Flow File=f01
Plan File=p01
Y Axis Title=Elevation
X Axis Title(PF)=Main Channel Distance
X Axis Title(XS)=Station
BEGIN DESCRIPTION:
Turtle Creek
END DESCRIPTION:
DSS Export Rating Curves= 0
DSS Export Rating Curve Sorted= 0
DSS Export Volume Flow Curves= 0
DXF OffsetX= 0
DXF OffsetY= 0
DXF ScaleX= 1
DXF ScaleY= 10

--- Turtle Creek.p01 (plan) ---

Plan Title=Multiple Run
Short Identifier=Multiple
Geom File=g01
Flow File=f01
Subcritical Flow
K Sum by GR= 0
Std Step Tol= 0.01
Critical Tol= 0.01
Num of Std Step Trials= 20
Max Error Tol= 0.3
Flow Tol Ratio= 0.001
Split Flow NTrial= 30
Split Flow Tol= 0.02
Split Flow Ratio= 0.02
Log Output Level= 0
Friction Slope Method= 1
Unsteady Friction Slope Method= 2
Unsteady Bridges Friction Slope Method= 1
Parabolic Critical Depth
Global Vel Dist=  1 , 1 , 1
Global Log Level= 0
CheckData=True
Encroach Param= -1, 0, 0, 0
BEGIN DESCRIPTION:
Multiple Run
END DESCRIPTION:

--- Turtle Creek.f01 (steady flow) ---

Flow Title=Multiple
Number of Profiles=7
Profile Names=10-year,25-year,50-year,1pct_min,100-year,1pct_plu,500-year
River Rch & RM= Turtle Creek,Reach-1,142543
     184     274     350     217     434     866     654
River Rch & RM= Turtle Creek,Reach-1,141219
    1260    2153    3003    2024    4039    8058    7217
River Rch & RM= Turtle Creek,Reach-1,136627
    1788    3107    4383    2983    5951   11875   10847
River Rch & RM= Turtle Creek,Reach-1,133033
    2288    4033    5743    3939    7860   15683   14570
River Rch & RM= Turtle Creek,Reach-1,129883
    2415    4242    6026    4124    8228   16417   15171
River Rch & RM= Turtle Creek,Reach-1,126904
    3408    6097    8766    6063   12098   24138   22803
River Rch & RM= Turtle Creek,Reach-1,122609
    3704    6609    9488    6549   13067   26072   24522
River Rch & RM= Turtle Creek,Reach-1,118044
    4389    7878   11355    7865   15693   31312   29656
River Rch & RM= Turtle Creek,Reach-1,108368
    4719    8485   12244    8489   16937   33794   32065
River Rch & RM= Turtle Creek,Reach-1,102777
    5104    9203   13304    9238   18433   36778   35009
River Rch & RM= Turtle Creek,Reach-1,99519
    5482    9908   14346    9975   19903   39712   37901
River Rch & RM= Turtle Creek,Reach-1,95097
    5704   10321   14954   10405   20760   41422   39582
River Rch & RM= Turtle Creek,Reach-1,91668
    5946   10760   15593   10849   21646   43190   41267
River Rch & RM= Turtle Creek,Reach-1,82360
    5970   10796   15636   10872   21693   43283   41305
River Rch & RM= Turtle Creek,Reach-1,77405
    7012   12745   18524   12920   25780   51437   49390
River Rch & RM= Turtle Creek,Reach-1,69230
    9740   17900   26216   18413   36738   73303   71354
River Rch & RM= Turtle Creek,Reach-1,66350
    9780   17966   26306   18471   36854   73533   71533
River Rch & RM= Turtle Creek,Reach-1,64121
   10377   19035   27851   19540   38988   77791   75524
River Rch & RM= Turtle Creek,Reach-1,60888
   12018   22134   32478   22845   45581   90947   88736
River Rch & RM= Turtle Creek,Reach-1,57586
   12035   22158   32503   22855   45603   90989   88723
River Rch & RM= Turtle Creek,Reach-1,55776
   12730   23464   34448   24240   48366   96502   94226
River Rch & RM= Turtle Creek,Reach-1,52391
   12939   23859   35037   24661   49205   98177   95907
River Rch & RM= Turtle Creek,Reach-1,52157
   13012   23988   35221   24786   49454   98673   96352
River Rch & RM= Turtle Creek,Reach-1,50511
   13149   24240   35593   25047   49976   99715   97368
River Rch & RM= Turtle Creek,Reach-1,47862
   13135   24202   35523   24988   49857   99477   97055
River Rch & RM= Turtle Creek,Reach-1,45736
   13291   24471   35900   25239   50358  100477   97917
River Rch & RM= Turtle Creek,Reach-1,38613
   15016   27717   40736   28684   57232  114192  111619
River Rch & RM= Turtle Creek,Reach-1,32643
   16588   30698   45197   31878   63606  126910  124448
River Rch & RM= Turtle Creek,Reach-1,31983
   16752   31002   45647   32196   64239  128174  125688
River Rch & RM= Turtle Creek,Reach-1,30029
   16720   30925   45517   32092   64032  127761  125184
River Rch & RM= Turtle Creek,Reach-1,28129
   16737   30947   45538   32098   64043  127783  125138
River Rch & RM= Turtle Creek,Reach-1,24410
   17007   31433   46241   32584   65013  129718  126951
River Rch & RM= Turtle Creek,Reach-1,19822
   17725   32790   48270   34034   67906  135490  132753
River Rch & RM= Turtle Creek,Reach-1,16356
   17709   32754   48210   33986   67812  135302  132529
River Rch & RM= Turtle Creek,Reach-1,15337
   17846   32996   48555   34220   68279  136234  133367
River Rch & RM= Turtle Creek,Reach-1,12751
   17879   33053   48636   34275   68388  136451  133559
River Rch & RM= Turtle Creek,Reach-1,10605
   17852   32974   48488   34148   68134  135946  132884
River Rch & RM= Turtle Creek,Reach-1,2205
   18596   34373   50572   35632   71094  141852  138777
Boundary for River Rch & Prof#=Turtle Creek,Reach-1,1
Up Type=0
Dn Type=3
Dn Slope=0.005
Boundary for River Rch & Prof#=Turtle Creek,Reach-1,2
Up Type=0
Dn Type=3
Dn Slope=0.005
Boundary for River Rch & Prof#=Turtle Creek,Reach-1,3
Up Type=0
Dn Type=3
Dn Slope=0.005
Boundary for River Rch & Prof#=Turtle Creek,Reach-1,4
Up Type=0
Dn Type=3
Dn Slope=0.005
Boundary for River Rch & Prof#=Turtle Creek,Reach-1,5
Up Type=0
Dn Type=3
Dn Slope=0.005
Boundary for River Rch & Prof#=Turtle Creek,Reach-1,6
Up Type=0
Dn Type=3
Dn Slope=0.005
Boundary for River Rch & Prof#=Turtle Creek,Reach-1,7
Up Type=0
Dn Type=3
Dn Slope=0.005

--- Turtle Creek.g01 (geometry) ---

Geom Title=Existing Conditions
Program Version=4.10

River Reach=Turtle Creek    ,Reach-1
Reach XY= 30
        1871825.       13896475.       1869874.5     13899550.04
      1872035.77      13904034.7      1875098.97      13905297.8
      1877340.27     13909124.62      1879865.32     13905285.76
       1882727.3     13905180.09        1881775.     13909917.93
      1886305.23     13907795.09      1885572.58     13905880.54
      1887556.57     13906925.18      1890181.17     13905667.14
      1890780.93     13903427.24      1892981.11      13907823.2
      1894676.56     13904628.76      1898381.45     13905367.26
      1897230.13     13901472.72        1901525.       13899475.
      1902830.93     13896677.24       1910154.9      13898125.1
       1915464.5     13895526.22      1917354.97     13898974.93
       1920835.7      13895275.8       1927854.8     13897825.22
      1929580.68     13894576.97      1932450.08      13896325.2
      1935469.06     13894277.26      1938445.08     13896725.52
      1941472.55     13893980.46        1943575.       13894175.

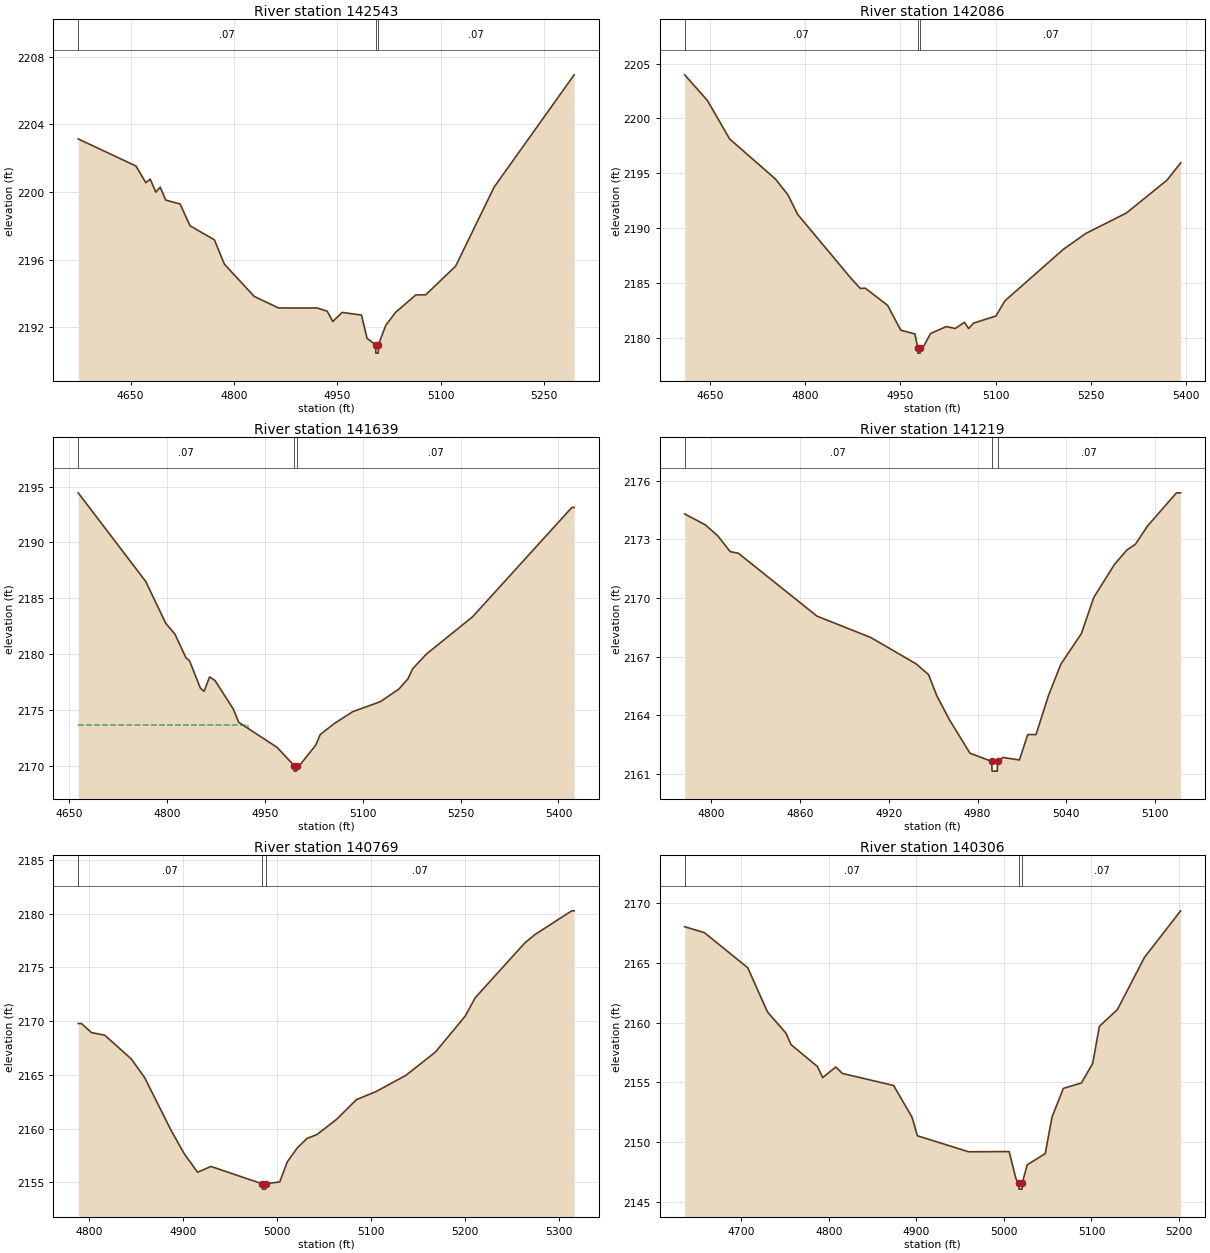
Type RM Length L Ch R = 1 ,142543  ,457,457,457
BEGIN DESCRIPTION:
Turtle Creek 256.0
END DESCRIPTION:
XS GIS Cut Line= 2
      1871399.38     13896052.88      1871842.08     13896620.58
#Sta/Elev= 30
  4574.1 2203.14  4657.8 2201.54  4672.3 2200.55  4678.6 2200.76  4686.8 2199.99
  4693.1 2200.29  4701.2 2199.52    4722 2199.29  4736.5    2198  4771.8 2197.17
  4786.3 2195.73  4829.7 2193.82    4865 2193.14  4921.1 2193.14  4935.5 2192.95
  4943.7 2192.34  4957.2 2192.88  4985.3 2192.72  4993.4 2191.34  5005.9 2190.97
  5006.1 2190.47  5009.6 2190.47  5009.9 2190.97  5020.6 2192.12    5035 2192.89
    5064 2193.91  5078.5 2193.92  5121.9 2195.61    5178  2200.3    5294 2206.93
#Mann= 3 ,-1 , 0
  4574.1     .07       0  5005.9     .05       0  5009.9     .07       0
Bank Sta=5005.9,5009.9
XS Rating Curve= 0 ,0
Exp/Cntr=0.3,0.1

Type RM Length L Ch R = 1 ,142086  ,447,447,447
BEGIN DESCRIPTION:
Turtle Creek 255.0
END DESCRIPTION:
XS GIS Cut Line= 3
      1870974.97     13896324.98        1871275.       13896575.
      1871575.03     13896825.03
#Sta/Elev= 30
  4610.1 2203.98  4645.9 2201.64  4681.1 2198.12  4752.7  2194.5  4772.8 2193.03
  4787.8 2191.27  4872.4  2185.4  4886.7  2184.5  4894.6 2184.52  4929.7 2182.96
  4950.5 2180.69  4972.7 2180.35  4977.2  2179.1  4977.4  2178.6  4980.9  2178.6
  4981.2  2179.1    4987 2179.28  4997.4 2180.39  5022.1 2181.02  5036.4 2180.85
  5050.8 2181.41  5057.3 2180.84  5065.1 2181.34  5100.2 2181.98  5114.5 2183.37
    5207 2188.09  5242.1 2189.52  5305.9 2191.38  5369.7 2194.37  5391.2 2195.95
#Mann= 3 ,-1 , 0
  4610.1     .07       0  4977.2     .05       0  4981.2     .07       0
Bank Sta=4977.2,4981.2
XS Rating Curve= 0 ,0
Exp/Cntr=0.3,0.1

Type RM Length L Ch R = 1 ,141639  ,420,420,420
BEGIN DESCRIPTION:
Turtle Creek 254.0
END DESCRIPTION:
XS GIS Cut Line= 3
      1870825.01     13896575.03        1870975.       13896875.
      1871274.97     13897174.97
#Sta/Elev= 30
  4664.4 2194.44  4767.8  2186.5  4798.5 2182.75  4812.5 2181.79  4829.3 2179.68
  4834.9 2179.39  4851.6 2176.94  4857.2 2176.66  4865.6 2177.95    4874 2177.62
  4901.9 2175.08  4910.3 2173.88    4969 2171.64    4995 2170.01  4995.2 2169.51
  4998.7 2169.51    4999 2170.01  5003.3 2170.01  5028.1 2171.83  5035.1 2172.79
  5056.3 2173.76  5084.6 2174.83  5127.1 2175.73  5155.3 2176.85  5169.5 2177.78
  5176.6 2178.68  5197.8    2180  5268.5 2183.34  5420.5 2193.13    5424 2193.13
#Mann= 3 ,-1 , 0
  4664.4     .07       0    4995     .05       0    4999     .07       0
#XS Ineff= 2 , 0
         4924.16 2173.67
Permanent Ineff=
       F       F
Bank Sta=4995,4999
XS Rating Curve= 0 ,0
Exp/Cntr=0.3,0.1

Type RM Length L Ch R = 1 ,141219  ,450,450,450
BEGIN DESCRIPTION:
Turtle Creek 253.0
END DESCRIPTION:
XS GIS Cut Line= 3
        1870675.     13897024.99        1870775.       13897225.
      1870874.98     13897274.99
#Sta/Elev= 30
  4781.9  2174.3  4795.9 2173.74  4804.3 2173.18  4812.7 2172.37  4818.2 2172.29
  4871.4 2169.07  4907.7 2167.98  4938.4 2166.63  4946.8 2166.08  4952.4    2165
  4960.8 2163.79  4974.8 2162.06  4989.5 2161.64  4989.8 2161.14  4993.3 2161.14
  4993.5 2161.64  4997.1 2161.84  5008.3 2161.71  5013.9 2163.01  5019.5 2163.01
  5027.9    2165  5036.3 2166.61  5050.2 2168.18  5058.6 2170.03  5072.6 2171.72
    5081 2172.46  5086.6 2172.74    5095 2173.69  5114.5 2175.38  5117.3 2175.38
#Mann= 3 ,-1 , 0
  4781.9     .07       0  4989.5     .05       0  4993.5     .07       0
Bank Sta=4989.5,4993.5
XS Rating Curve= 0 ,0
Exp/Cntr=0.3,0.1

Type RM Length L Ch R = 1 ,140769  ,463,463,463
BEGIN DESCRIPTION:
Turtle Creek 252.0
END DESCRIPTION:
XS GIS Cut Line= 3
      1870325.03     13897375.03        1870475.       13897525.
      1870774.98     13897624.99
#Sta/Elev= 30
    4788 2169.78  4791.5 2169.78  4802.1 2168.94  4816.2  2168.7  4844.5 2166.49
  4858.7 2164.76    4887 2159.83  4901.1 2157.64  4915.2 2155.94  4929.4 2156.48
  4983.9 2154.87  4984.2 2154.37  4987.7 2154.37  4987.9 2154.87  5002.7 2155.04
  5010.6 2156.89  5021.2 2158.19  5031.7 2159.09  5042.3 2159.45  5063.3 2160.87
  5084.4  2162.7  5105.5 2163.46  5137.1 2164.96  5168.7 2167.14  5200.4 2170.49
  5210.9 2172.18  5263.6 2177.27  5274.2 2178.04  5313.7 2180.27  5316.3 2180.27
#Mann= 3 ,-1 , 0
    4788     .07       0  4983.9     .05       0  4987.9     .07       0
Bank Sta=4983.9,4987.9
XS Rating Curve= 0 ,0
Exp/Cntr=0.3,0.1

Type RM Length L Ch R = 1 ,140306  ,466,466,466
BEGIN DESCRIPTION:
Turtle Creek 251.0
END DESCRIPTION:
XS GIS Cut Line= 3
      1870075.03     13897625.04        1870275.       13897925.
      1870475.03     13897975.01
#Sta/Elev= 30
  4635.2 2168.01  4657.7 2167.52  4707.3 2164.58  4729.8 2160.89  4750.8 2159.13
  4756.8 2158.15  4786.9 2156.33  4792.9  2155.4  4807.9 2156.29  4815.4 2155.75
    4874 2154.74  4895.1 2152.07  4901.1 2150.54  4959.7  2149.2    5006 2149.22
  5013.7 2146.96  5016.9 2146.58  5017.2 2146.08  5020.7 2146.08  5020.9 2146.58
  5026.6 2148.11  5047.2 2149.05    5055 2152.11  5067.9  2154.5  5088.5 2154.95
  5101.4 2156.58  5109.1 2159.69  5129.7 2161.09  5160.6 2165.45  5201.9 2169.34
#Mann= 3 ,-1 , 0
  4635.2     .07       0  5016.9     .05       0  5020.9     .07       0
Bank Sta=5016.9,5020.9
XS Rating Curve= 0 ,0
Exp/Cntr=0.3,0.1

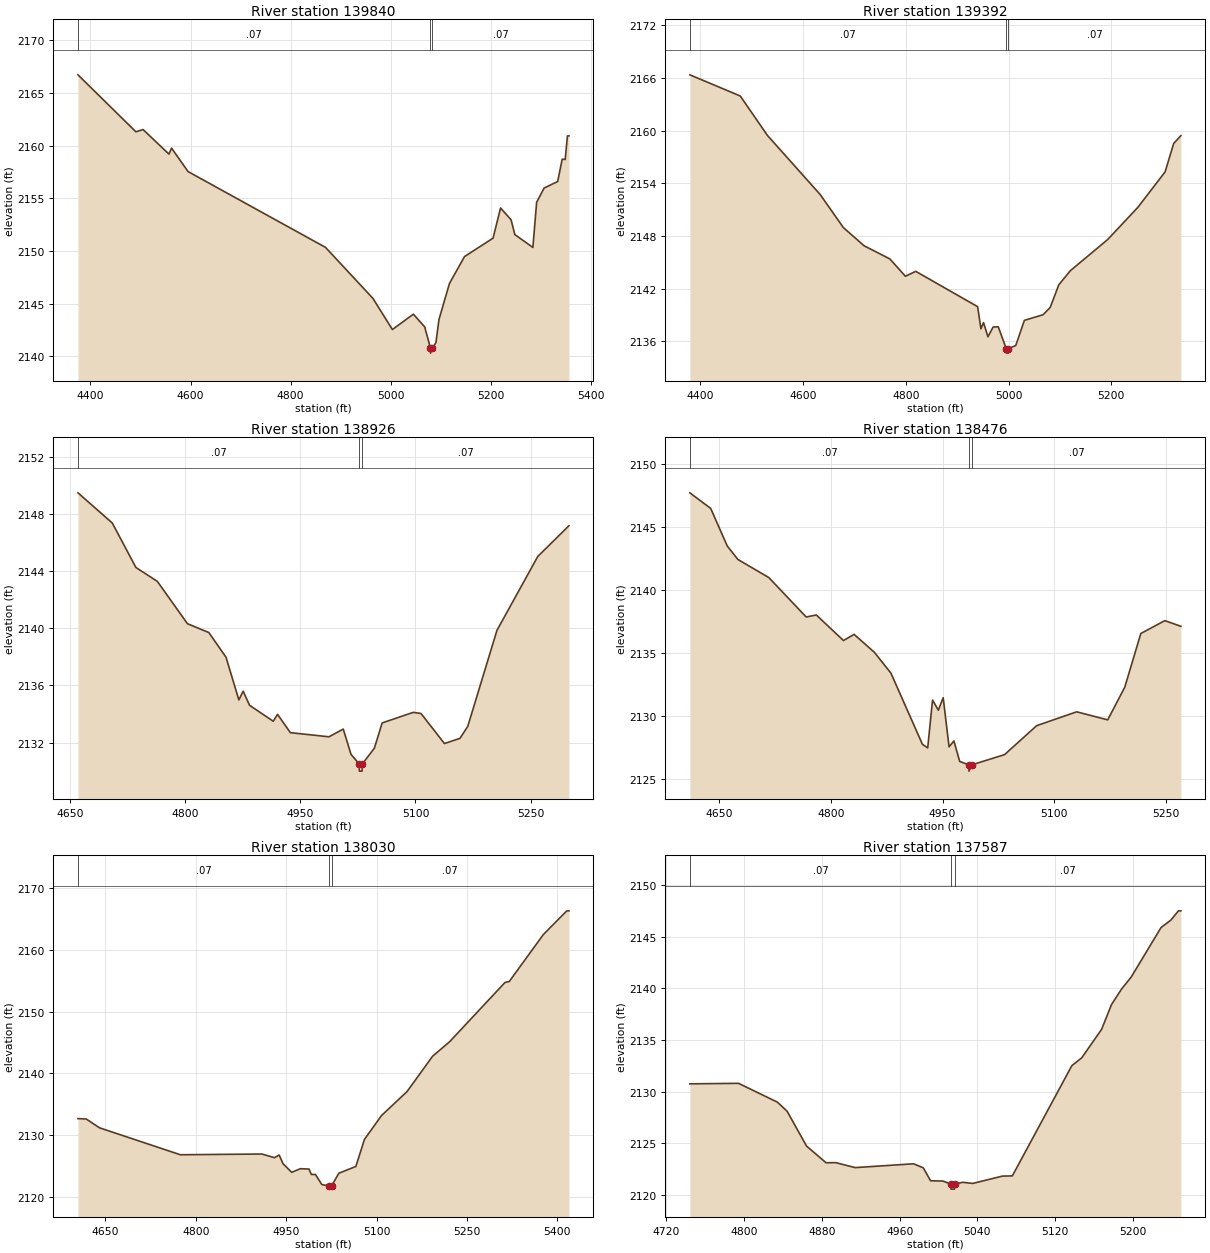
Type RM Length L Ch R = 1 ,139840  ,448,448,448
BEGIN DESCRIPTION:
Turtle Creek 250.0
END DESCRIPTION:
XS GIS Cut Line= 3
      1869796.35      13897630.2        1869975.       13898225.
        1870275.       13898425.
#Sta/Elev= 30
    4375 2166.73  4490.8 2161.32  4505.3 2161.53  4556.9  2159.2  4562.1 2159.77
  4595.2 2157.54    4870 2150.34  4964.7  2145.5  5003.6 2142.54  5045.6    2144
  5068.2 2142.79  5079.7  2140.8  5079.9  2140.3  5083.7  2140.8  5090.7 2141.29
  5096.7 2143.48  5117.7 2146.91  5147.8 2149.47  5204.9 2151.22  5219.9 2154.08
  5240.9 2152.97  5248.4 2151.56  5284.5 2150.34    5292 2154.62    5307 2155.98
  5334.1  2156.6  5343.1 2158.72  5349.1 2158.69  5353.6 2160.93  5356.6 2160.93
#Mann= 3 ,-1 , 0
    4375     .07       0  5079.7     .05       0  5083.7     .07       0
Bank Sta=5079.7,5083.7
XS Rating Curve= 0 ,0
Exp/Cntr=0.3,0.1

Type RM Length L Ch R = 1 ,139392  ,466,466,466
BEGIN DESCRIPTION:
Turtle Creek 249.0
END DESCRIPTION:
XS GIS Cut Line= 3
      1869357.33     13898734.16        1869975.       13898675.
        1870275.       13898525.
#Sta/Elev= 30
  4379.4 2166.34  4477.5 2163.93  4530.3 2159.45    4633 2152.72  4678.4 2148.94
  4718.6 2146.88  4768.8 2145.38    4799 2143.41  4819.1 2143.97  4939.6 2139.95
    4946 2137.43  4951.1 2138.14  4959.7 2136.52  4969.8 2137.63  4979.8 2137.66
  4995.4 2135.16  4995.6 2134.66  4999.1 2134.66  4999.4 2135.16  5013.9 2135.53
  5030.6 2138.39    5067 2139.03  5080.9 2139.86  5097.7 2142.44  5120.1 2144.04
  5192.8 2147.59  5251.5 2151.25  5304.6 2155.29  5321.3 2158.52  5335.3 2159.42
#Mann= 3 ,-1 , 0
  4379.4     .07       0  4995.4     .05       0  4999.4     .07       0
Bank Sta=4995.4,4999.4
XS Rating Curve= 0 ,0
Exp/Cntr=0.3,0.1

Type RM Length L Ch R = 1 ,138926  ,450,450,450
BEGIN DESCRIPTION:
Turtle Creek 248.0
END DESCRIPTION:
XS GIS Cut Line= 3
      1869624.99     13898974.99        1869925.       13899125.
      1870225.04     13899074.99
#Sta/Elev= 30
  4660.3 2149.47    4705 2147.36  4735.8 2144.25  4763.7 2143.28  4802.9 2140.32
  4830.8  2139.7  4853.2 2137.97  4869.9 2134.99  4875.5  2135.6  4883.9 2134.61
  4914.7  2133.5  4920.3 2133.98    4937  2132.7  4987.3 2132.41  5005.9 2132.95
    5016 2131.18  5026.7 2130.51  5026.9 2130.01  5030.4 2130.01  5030.7 2130.51
  5046.4 2131.61  5056.6 2133.38  5097.1 2134.12  5107.2 2134.04  5137.7 2131.94
  5157.9  2132.3  5168.1 2133.14  5206.1 2139.85  5259.3 2145.02  5299.9 2147.17
#Mann= 3 ,-1 , 0
  4660.3     .07       0  5026.7     .05       0  5030.7     .07       0
Bank Sta=5026.7,5030.7
XS Rating Curve= 0 ,0
Exp/Cntr=0.3,0.1

Type RM Length L Ch R = 1 ,138476  ,446,446,446
BEGIN DESCRIPTION:
Turtle Creek 247.0
END DESCRIPTION:
XS GIS Cut Line= 3
      1869574.96     13899775.03        1869875.       13899525.
      1870124.98     13899425.01
#Sta/Elev= 30
  4610.5 2147.72  4638.5 2146.48  4660.7  2143.5    4675 2142.43  4716.6 2140.99
  4766.8 2137.86  4780.4 2138.02  4816.9 2135.99  4831.2 2136.48  4858.5 2135.05
  4880.7  2133.4    4923 2127.75  4930.1 2127.47  4936.6 2131.26  4944.4 2130.46
  4950.9 2131.45  4958.8 2127.55  4965.3 2128.02  4973.1 2126.39  4985.4 2126.12
  4985.6 2125.62  4989.4 2126.12  5033.4 2126.93  5076.5 2129.23  5130.3 2130.33
    5172 2129.69  5194.9 2132.28  5216.5 2136.55  5248.8 2137.57  5270.3 2137.12
#Mann= 3 ,-1 , 0
  4610.5     .07       0  4985.4     .05       0  4989.4     .07       0
Bank Sta=4985.4,4989.4
XS Rating Curve= 0 ,0
Exp/Cntr=0.3,0.1

Type RM Length L Ch R = 1 ,138030  ,443,443,443
BEGIN DESCRIPTION:
Turtle Creek 246.0
END DESCRIPTION:
XS GIS Cut Line= 3
      1869874.99     13900075.01        1870175.       13899825.
      1870475.01     13899524.99
#Sta/Elev= 30
  4604.4 2132.68  4618.1 2132.62  4640.2 2131.19  4774.3 2126.83  4909.7 2126.95
  4930.5 2126.36  4938.3 2126.79  4944.8 2125.37  4959.1 2123.99  4973.4 2124.57
  4987.8 2124.52  4991.7 2123.64  4998.5 2123.64  5009.1 2122.01  5021.2 2121.77
  5021.5 2121.27    5025 2121.27  5025.2 2121.77  5037.3 2123.84  5065.6 2124.94
  5079.8 2129.31  5108.1 2133.17  5150.5 2137.05  5192.9 2142.77  5221.2 2145.12
  5313.1 2154.71  5320.2 2154.87  5376.8 2162.47  5415.7  2166.3  5419.2  2166.3
#Mann= 3 ,-1 , 0
  4604.4     .07       0  5021.2     .05       0  5025.2     .07       0
Bank Sta=5021.2,5025.2
XS Rating Curve= 0 ,0
Exp/Cntr=0.3,0.1

Type RM Length L Ch R = 1 ,137587  ,484,484,484
BEGIN DESCRIPTION:
Turtle Creek 245.0
END DESCRIPTION:
XS GIS Cut Line= 3
      1870025.01       13900175.        1870275.       13900175.
      1870524.96     13900125.01
#Sta/Elev= 30
  4744.3 2130.76  4794.3 2130.81  4834.3 2128.99  4844.3 2128.11  4864.3 2124.74
  4884.3 2123.13  4894.3 2123.14  4914.3 2122.66  4974.3 2123.03  4984.3 2122.64
  4991.8 2121.39  5004.5 2121.36  5012.7 2121.08  5012.9 2120.58  5016.4 2120.58
  5016.7 2121.08  5024.9 2121.24  5035.1 2121.13  5065.7 2121.84  5075.9 2121.86
  5137.1 2132.52  5147.3 2133.28  5167.7 2136.03  5177.9 2138.43  5188.1 2139.91
  5198.3 2141.11  5228.8 2145.87    5239  2146.6  5246.7 2147.49  5249.2 2147.49
#Mann= 3 ,-1 , 0
  4744.3     .07       0  5012.7     .05       0  5016.7     .07       0
Bank Sta=5012.7,5016.7
XS Rating Curve= 0 ,0
Exp/Cntr=0.3,0.1

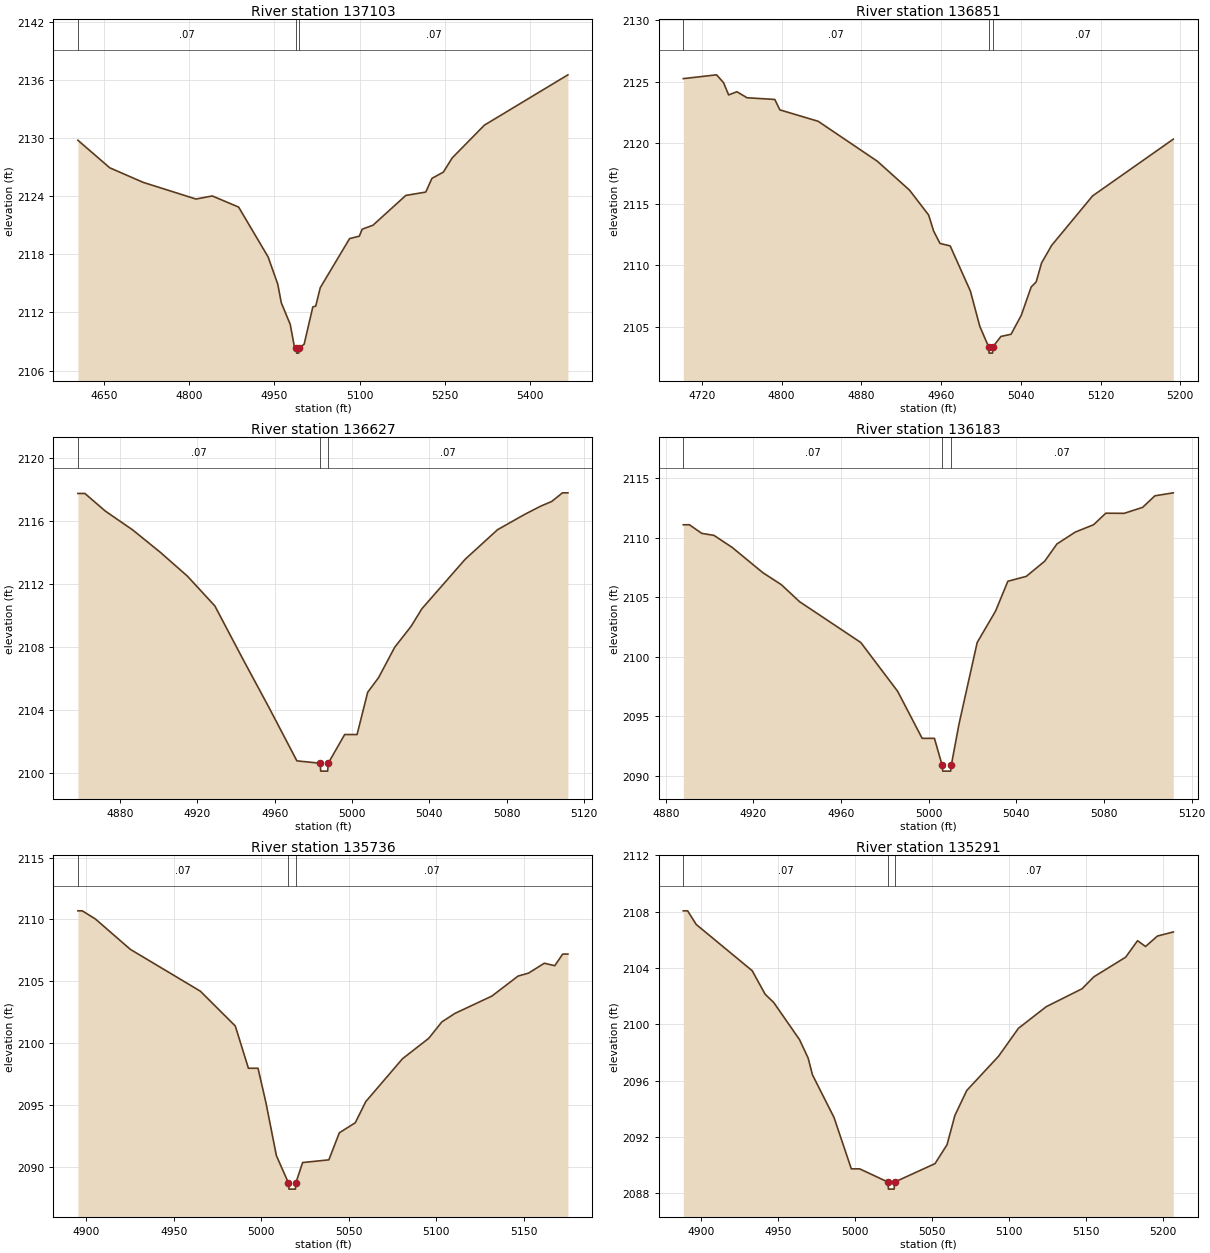
Type RM Length L Ch R = 1 ,137103  ,252,252,252
BEGIN DESCRIPTION:
Turtle Creek 244.0
END DESCRIPTION:
XS GIS Cut Line= 3
      1869913.75     13900463.77        1870275.       13900625.
      1870727.46     13900509.76
#Sta/Elev= 30
  4604.3 2129.76  4660.4 2126.92  4719.2 2125.42  4812.1  2123.7  4840.8 2124.02
  4887.2 2122.87  4939.1 2117.73  4956.1 2114.92  4962.3    2113    4978 2110.78
  4985.6 2108.39    4989 2108.31  4989.3 2107.81  4992.8 2107.81    4993 2108.31
  5002.5 2108.73  5017.8 2112.57  5022.9 2112.66  5030.9 2114.56  5082.5 2119.62
  5099.6 2119.87  5104.7 2120.59  5123.7    2121  5181.4 2124.07  5216.6 2124.42
  5227.4 2125.83  5247.6 2126.48  5263.1 2127.94  5319.8 2131.32  5466.8 2136.51
#Mann= 3 ,-1 , 0
  4604.3     .07       0    4989     .05       0    4993     .07       0
Bank Sta=4989,4993
XS Rating Curve= 0 ,0
Exp/Cntr=0.3,0.1

Type RM Length L Ch R = 1 ,136851  ,224,224,224
BEGIN DESCRIPTION:
Mapping XS 9357b8bf
END DESCRIPTION:
XS GIS Cut Line= 2
      1869932.25     13900918.13      1870414.76     13900823.48
#Sta/Elev= 30
  4701.3 2125.24  4734.7 2125.55  4741.7 2124.91  4746.8 2123.91  4755.1 2124.17
  4765.2 2123.68  4793.1 2123.54  4798.2 2122.69  4836.6 2121.76    4896  2118.5
  4928.3 2116.14  4947.5 2114.11  4952.5  2112.8  4958.9 2111.79  4969.1 2111.59
  4989.4  2107.9  4998.9 2105.01  5007.8 2103.34  5008.1 2102.84  5011.6 2102.84
  5011.9 2103.34    5020  2104.2  5030.2 2104.38  5040.4 2105.92  5050.4 2108.24
  5055.4 2108.65  5060.8  2110.2    5071 2111.64    5112 2115.67    5193  2120.3
#Mann= 3 ,-1 , 0
  4701.3     .07       0  5007.8     .05       0  5011.9     .07       0
Bank Sta=5007.8,5011.9
XS Rating Curve= 0 ,0
Exp/Cntr=0.3,0.1

Type RM Length L Ch R = 1 ,136627  ,444,444,444
BEGIN DESCRIPTION:
Turtle Creek 243.0
END DESCRIPTION:
XS GIS Cut Line= 3
      1870274.97     13901125.03        1870375.       13901025.
      1870475.03     13900974.98
#Sta/Elev= 29
  4858.3 2117.75  4861.9 2117.75  4872.5 2116.63  4886.6 2115.44  4900.8 2114.03
  4914.9 2112.51  4929.1 2110.62  4943.2 2107.34  4957.3 2104.13  4971.5  2100.8
  4983.6 2100.65  4983.8 2100.15  4987.4 2100.15  4987.7 2100.65  4996.2 2102.47
  4999.8 2102.47  5002.6 2102.47  5008.1 2105.15  5013.7 2106.07  5022.1 2108.01
  5030.5 2109.32  5036.1 2110.44  5058.5 2113.58  5075.2 2115.45  5089.2 2116.42
  5097.6 2116.95  5103.2 2117.24  5108.8 2117.79  5111.6 2117.79
#Mann= 3 ,-1 , 0
  4858.3     .07       0  4983.6     .05       0  4987.7     .07       0
Bank Sta=4983.6,4987.7
XS Rating Curve= 0 ,0
Exp/Cntr=0.3,0.1

Type RM Length L Ch R = 1 ,136183  ,447,447,447
BEGIN DESCRIPTION:
Turtle Creek 242.0
END DESCRIPTION:
XS GIS Cut Line= 3
      1870575.02     13901374.99        1870675.       13901325.
      1870775.02     13901274.99
#Sta/Elev= 30
    4888 2111.07  4890.8 2111.07  4896.4 2110.35    4902 2110.18  4910.3 2109.17
  4924.3 2107.05  4932.7 2106.05  4941.1 2104.61    4969 2101.19  4985.8  2097.1
    4997 2093.15  5002.6 2093.15  5006.1  2090.9  5006.4  2090.4    5010  2090.4
  5010.3  2090.9  5013.8 2094.34  5022.1 2101.19  5030.5 2103.83  5036.1 2106.33
  5044.5 2106.74  5052.9 2108.01  5058.5 2109.46  5066.9 2110.46  5075.2 2111.07
  5080.8 2112.04  5089.2 2112.03  5097.6 2112.53  5103.2  2113.5  5111.6 2113.75
#Mann= 3 ,-1 , 0
    4888     .07       0  5006.1     .05       0  5010.3     .07       0
Bank Sta=5006.1,5010.3
XS Rating Curve= 0 ,0
Exp/Cntr=0.3,0.1

Type RM Length L Ch R = 1 ,135736  ,445,445,445
BEGIN DESCRIPTION:
Turtle Creek 241.0
END DESCRIPTION:
XS GIS Cut Line= 3
      1870725.03       13901725.        1870825.       13901725.
      1870924.98     13901575.04
#Sta/Elev= 30
  4895.1 2110.69  4897.6 2110.69  4905.1 2110.03  4925.1 2107.57  4965.1 2104.19
  4985.1 2101.37  4992.6 2097.95  4998.1 2097.95  5002.6 2095.18  5008.6 2090.88
  5015.5 2088.67  5015.8 2088.17  5019.5 2088.17  5019.7 2088.67  5023.6 2090.32
  5038.6 2090.54  5044.6 2092.73  5053.7 2093.54  5059.7 2095.25  5080.7 2098.72
  5095.7 2100.37  5103.2  2101.7  5110.7 2102.39  5131.8 2103.79  5146.8 2105.41
  5152.8 2105.65  5161.8 2106.45  5167.8 2106.25  5172.3 2107.19  5175.3 2107.19
#Mann= 3 ,-1 , 0
  4895.1     .07       0  5015.5     .05       0  5019.7     .07       0
Bank Sta=5015.5,5019.7
XS Rating Curve= 0 ,0
Exp/Cntr=0.3,0.1

Type RM Length L Ch R = 1 ,135291  ,410,410,410
BEGIN DESCRIPTION:
Turtle Creek 240.0
END DESCRIPTION:
XS GIS Cut Line= 3
      1871025.02     13902074.99        1871125.       13902025.
      1871174.99     13901825.04
#Sta/Elev= 30
  4888.7 2108.06  4891.5 2108.06  4897.1 2107.09  4933.4 2103.81  4941.8 2102.14
  4947.4 2101.55  4964.1 2098.92  4969.7 2097.61  4972.5 2096.42  4986.5 2093.39
  4997.7 2089.75  5003.1 2089.75  5021.5 2088.81  5021.8 2088.31  5025.5 2088.31
  5025.8 2088.81    5052 2090.12  5059.8 2091.46  5064.9 2093.54  5072.6 2095.31
  5093.3 2097.75  5106.1 2099.72  5124.2 2101.26  5147.4 2102.53  5155.1 2103.38
  5175.7 2104.77  5183.4 2105.94  5188.6 2105.53  5196.3 2106.27  5206.6 2106.56
#Mann= 3 ,-1 , 0
  4888.7     .07       0  5021.5     .05       0  5025.8     .07       0
Bank Sta=5021.5,5025.8
XS Rating Curve= 0 ,0
Exp/Cntr=0.3,0.1

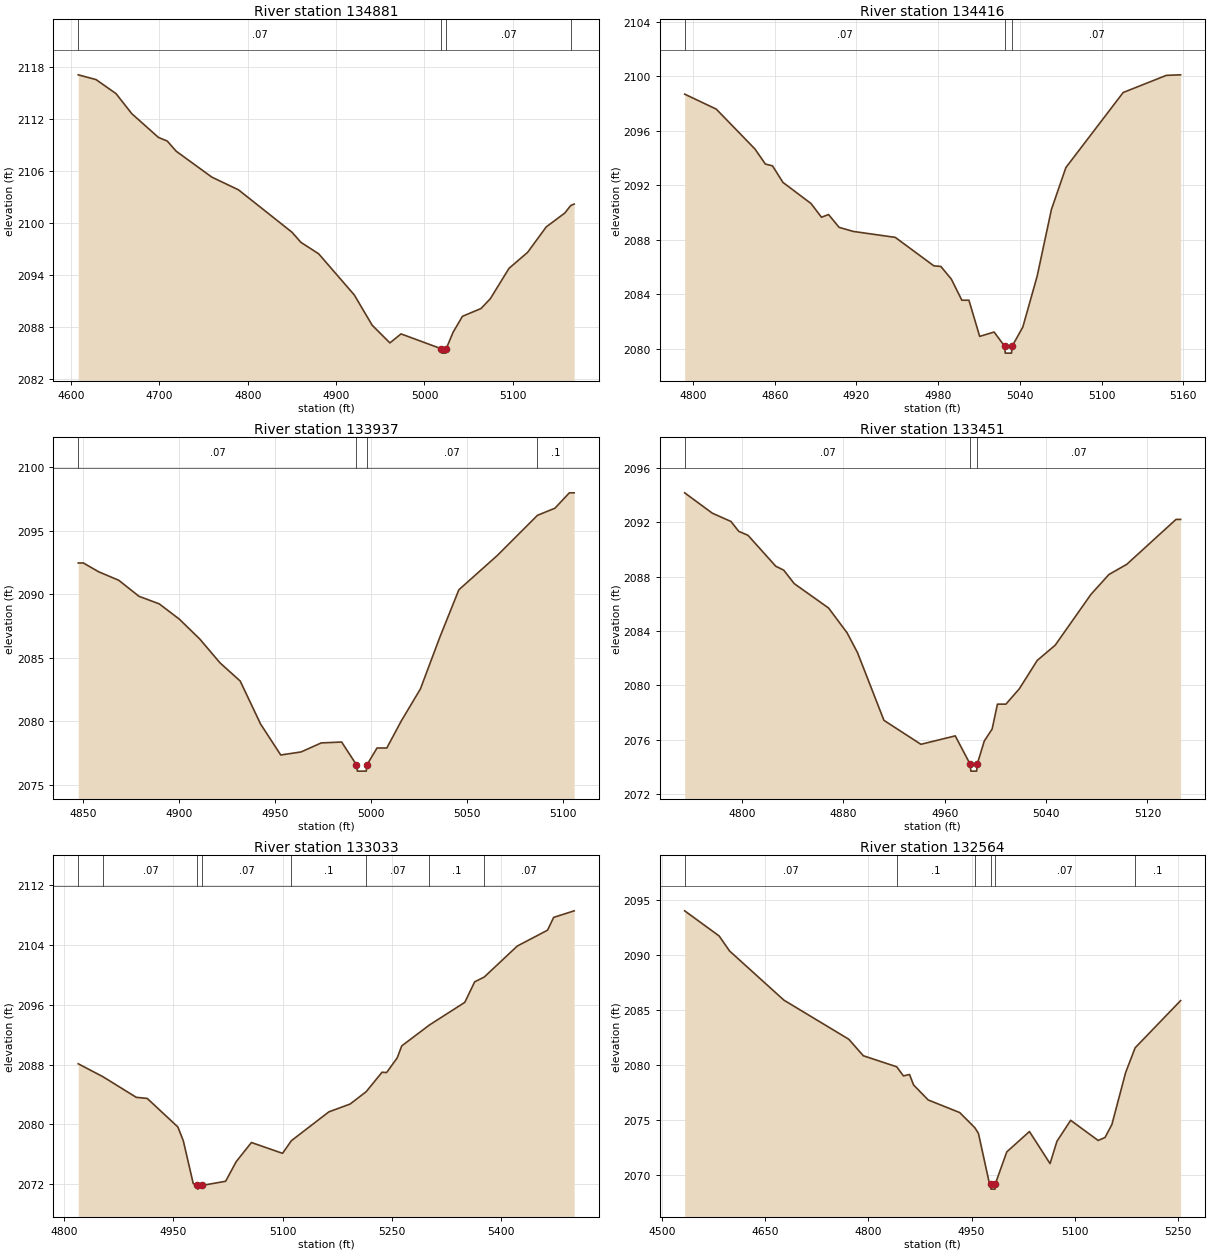
Type RM Length L Ch R = 1 ,134881  ,465,465,465
BEGIN DESCRIPTION:
Turtle Creek 239.0
END DESCRIPTION:
XS GIS Cut Line= 3
      1871024.98       13902325.        1871425.       13902275.
      1871574.96     13902225.01
#Sta/Elev= 30
  4608.2 2117.14  4628.4 2116.59  4651.1 2114.96  4668.7 2112.67  4698.9 2109.92
    4709 2109.49  4719.1 2108.32  4759.4 2105.33  4789.6 2103.86  4850.1 2098.97
  4860.2  2097.8  4880.3 2096.48  4920.6 2091.73  4940.8 2088.24  4960.9 2086.19
  4973.5 2087.23  5019.2 2085.51  5019.6 2085.01  5024.1 2085.01  5024.6 2085.51
  5032.4 2087.42    5043 2089.26    5064 2090.16  5074.6  2091.3  5095.7  2094.8
  5116.7 2096.64  5137.8 2099.58  5158.9 2101.19  5165.5 2102.05  5169.4 2102.22
#Mann= 4 ,-1 , 0
  4608.2     .07       0  5019.2     .05       0  5024.6     .07       0
  5165.5      .1       0
Bank Sta=5019.2,5024.6
XS Rating Curve= 0 ,0
Exp/Cntr=0.3,0.1

Type RM Length L Ch R = 1 ,134416  ,479,479,479
BEGIN DESCRIPTION:
Turtle Creek 238.0
END DESCRIPTION:
XS GIS Cut Line= 3
      1871374.96     13902624.99        1871575.       13902675.
      1871724.99       13902625.
#Sta/Elev= 30
  4793.8  2098.7    4817  2097.6  4845.4 2094.67  4853.1 2093.56  4858.3 2093.43
    4866 2092.21  4886.6 2090.66  4894.3 2089.65  4899.5 2089.85  4907.2 2088.91
  4917.5 2088.61  4948.5 2088.17  4976.8 2086.08    4982 2086.03  4989.7  2085.1
  4997.4 2083.55  5002.6 2083.55  5010.5 2080.89  5021.1 2081.21  5028.9 2080.16
  5029.3 2079.66  5033.9 2079.66  5034.3 2080.16  5042.2 2081.58  5052.7 2085.31
  5063.2 2090.22  5073.8  2093.3  5115.9 2098.82  5147.6 2100.08  5158.1 2100.12
#Mann= 3 ,-1 , 0
  4793.8     .07       0  5028.9     .05       0  5034.3     .07       0
Bank Sta=5028.9,5034.3
XS Rating Curve= 0 ,0
Exp/Cntr=0.3,0.1

Type RM Length L Ch R = 1 ,133937  ,486,486,486
BEGIN DESCRIPTION:
Turtle Creek 237.0
END DESCRIPTION:
XS GIS Cut Line= 3
      1871524.98     13903074.99        1871675.       13903125.
      1871774.97       13903125.
#Sta/Elev= 30
  4847.6 2092.45  4850.3 2092.45  4858.2 2091.76  4868.7 2091.09  4879.2 2089.83
  4889.8 2089.23  4900.3 2088.02  4910.9 2086.46  4921.4 2084.59  4931.9 2083.16
  4942.5 2079.78    4953 2077.34  4963.6 2077.58  4974.1 2078.29  4984.7 2078.36
  4992.4 2076.57  4992.9 2076.07  4997.5 2076.07  4997.9 2076.57  5003.1 2077.89
  5008.2 2077.89  5015.7 2080.01  5025.7 2082.54  5035.7 2086.57  5045.7 2090.34
  5065.7 2093.04  5086.6  2096.2  5095.7 2096.76  5103.2 2097.97  5105.7 2097.97
#Mann= 4 ,-1 , 0
  4847.6     .07       0  4992.4     .05       0  4997.9     .07       0
  5086.6      .1       0
Bank Sta=4992.4,4997.9
XS Rating Curve= 0 ,0
Exp/Cntr=0.3,0.1

Type RM Length L Ch R = 1 ,133451  ,418,418,418
BEGIN DESCRIPTION:
Turtle Creek 236.0
END DESCRIPTION:
XS GIS Cut Line= 3
      1871574.98     13903725.02        1871775.       13903575.
      1871875.03     13903474.97
#Sta/Elev= 30
  4754.7 2094.15  4776.6 2092.65  4791.2 2092.05  4797.4 2091.32  4804.7 2091.03
  4826.6 2088.76  4832.9 2088.47  4841.2 2087.48  4868.3 2085.69  4882.9 2083.87
  4891.2  2082.4    4912 2077.44  4941.2 2075.68  4968.3  2076.3  4980.1 2074.21
  4980.6 2073.71  4985.2 2073.71  4985.6 2074.21  4991.2 2075.92  4997.4  2076.8
  5001.6 2078.63  5008.3 2078.63  5018.9 2079.76    5033 2081.84  5047.2 2082.96
  5075.4 2086.69  5089.6 2088.15  5103.7  2088.9  5142.6  2092.2  5146.2  2092.2
#Mann= 3 ,-1 , 0
  4754.7     .07       0  4980.1     .05       0  4985.6     .07       0
Bank Sta=4980.1,4985.6
XS Rating Curve= 0 ,0
Exp/Cntr=0.3,0.1

Type RM Length L Ch R = 1 ,133033  ,469,469,469
BEGIN DESCRIPTION:
Turtle Creek 235.0
END DESCRIPTION:
XS GIS Cut Line= 3
      1871824.99     13904025.01        1871975.       13903925.
        1872275.     13903524.99
#Sta/Elev= 30
  4819.7 2088.12  4854.1 2086.36  4899.3 2083.63  4914.4 2083.48  4956.4 2079.66
  4963.9  2077.8  4977.5 2072.08  4983.3 2071.84  4983.8 2071.34  4989.6 2071.84
  5021.9 2072.39  5036.5 2075.03  5057.3 2077.58    5100 2076.13  5112.1 2077.82
  5163.5 2081.68  5192.7 2082.73  5214.7 2084.38  5236.5 2086.99  5242.7 2086.94
  5257.3 2088.91  5263.5 2090.51  5301.5 2093.31    5350 2096.34  5363.5 2099.08
  5376.7 2099.73  5421.9 2103.87  5463.5    2106  5471.9 2107.71    5500 2108.59
#Mann= 8 ,-1 , 0
  4819.7      .1       0  4854.1     .07       0  4983.3     .05       0
  4989.6     .07       0  5112.1      .1       0  5214.7     .07       0
  5301.5      .1       0  5376.7     .07       0
Bank Sta=4983.3,4989.6
XS Rating Curve= 0 ,0
Exp/Cntr=0.3,0.1

Type RM Length L Ch R = 1 ,132564  ,452,452,452
BEGIN DESCRIPTION:
Turtle Creek 234.0
END DESCRIPTION:
XS GIS Cut Line= 3
      1872075.01     13904574.98        1872325.       13904175.
        1872325.     13903924.98
#Sta/Elev= 30
  4532.6 2093.98  4582.7  2091.7    4598 2090.33    4677 2085.87  4771.4 2082.32
  4792.6 2080.82  4841.1 2079.82    4851 2078.99  4859.8 2079.12  4865.7 2078.17
  4886.9 2076.81  4932.9 2075.66  4954.8 2074.29  4960.1 2073.77  4975.4 2069.41
  4977.8 2069.21  4978.3 2068.71  4984.3 2068.71  4984.8 2069.21  5001.3 2072.09
  5034.3 2073.94  5064.3 2071.03  5074.3 2073.05  5094.3 2074.96  5134.3 2073.13
  5144.3  2073.4  5154.3 2074.58  5174.3  2079.3  5188.1 2081.54  5254.3 2085.83
#Mann= 6 ,-1 , 0
  4532.6     .07       0  4841.1      .1       0  4954.8     .07       0
  4977.8     .05       0  4984.8     .07       0  5188.1      .1       0
Bank Sta=4977.8,4984.8
XS Rating Curve= 0 ,0
Exp/Cntr=0.3,0.1

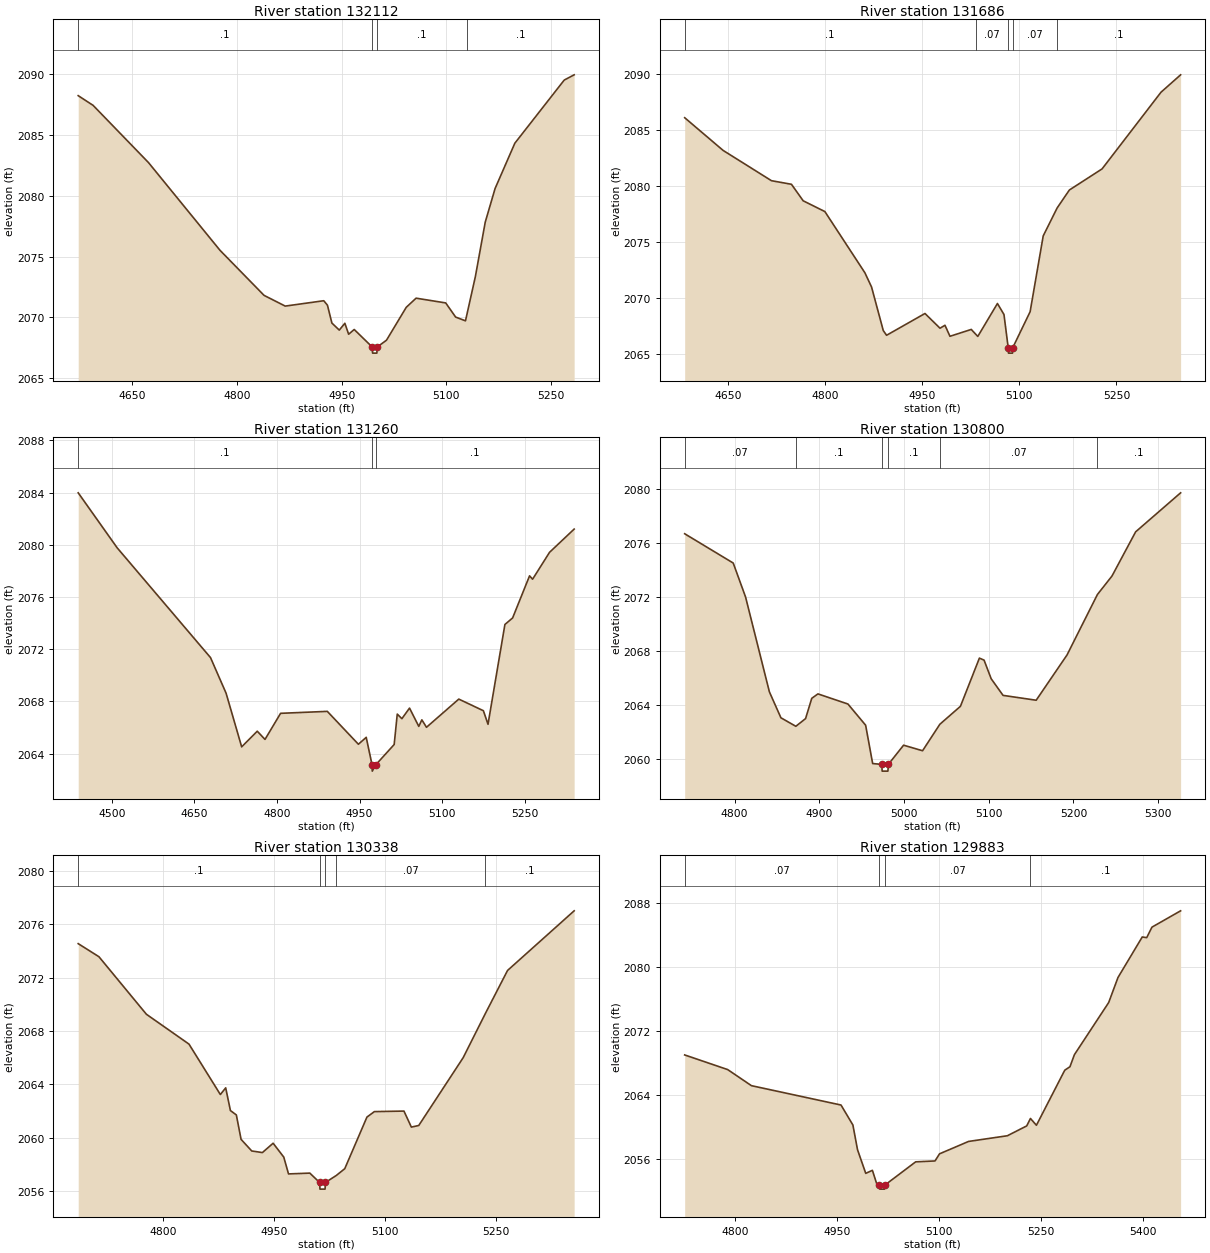
Type RM Length L Ch R = 1 ,132112  ,426,426,426
BEGIN DESCRIPTION:
Turtle Creek 233.0
END DESCRIPTION:
XS GIS Cut Line= 3
      1872574.99     13904725.03        1872725.       13904325.
      1872925.02     13904124.98
#Sta/Elev= 30
  4572.8  2088.2  4594.2  2087.4  4673.4 2082.71  4775.8 2075.51  4838.9 2071.81
  4869.2 2070.93  4924.4 2071.37  4929.7    2071    4936 2069.54  4946.6 2068.96
  4954.6 2069.52    4960 2068.62    4968 2069.01  4993.8 2067.57  4994.3 2067.07
  5000.4 2067.07  5000.9 2067.57  5014.2 2068.13  5042.5 2070.83  5056.6 2071.58
    5099 2071.19  5113.2 2070.03  5127.3 2069.72  5129.3 2070.23  5141.5 2073.36
  5155.6 2077.82  5169.7 2080.58    5198  2084.3  5268.7 2089.48  5282.9 2089.91
#Mann= 4 ,-1 , 0
  4572.8      .1       0  4993.8     .05       0  5000.9      .1       0
  5129.3      .1       0
Bank Sta=4993.8,5000.9
XS Rating Curve= 0 ,0
Exp/Cntr=0.3,0.1

Type RM Length L Ch R = 1 ,131686  ,426,426,426
BEGIN DESCRIPTION:
Turtle Creek 232.0
END DESCRIPTION:
XS GIS Cut Line= 3
        1872975.       13904875.        1873075.       13904475.
        1873025.     13904124.97
#Sta/Elev= 30
  4583.3 2086.09  4642.6 2083.18  4717.3 2080.48  4748.2 2080.16  4766.3 2078.69
  4799.8 2077.73  4861.6 2072.28  4871.9 2071.01    4890 2067.13  4895.1 2066.71
  4954.4 2068.65  4977.6 2067.34  4985.3  2067.6    4993 2066.62  5025.9 2067.23
  5032.5 2066.82    5036 2066.61  5066.3 2069.54  5076.4 2068.56  5082.9 2065.62
  5083.4 2065.12  5089.6 2065.12  5090.1 2065.62  5116.8 2068.81    5137 2075.56
  5158.5 2078.05  5177.4 2079.65  5227.9 2081.53  5318.9 2088.36  5349.2 2089.91
#Mann= 5 ,-1 , 0
  4583.3      .1       0  5032.5     .07       0  5082.9     .05       0
  5090.1     .07       0  5158.5      .1       0
Bank Sta=5082.9,5090.1
XS Rating Curve= 0 ,0
Exp/Cntr=0.3,0.1

Type RM Length L Ch R = 1 ,131260  ,460,460,460
BEGIN DESCRIPTION:
Turtle Creek 231.0
END DESCRIPTION:
XS GIS Cut Line= 3
      1873074.99     13904875.01        1873475.       13904475.
      1873774.99     13904325.01
#Sta/Elev= 30
  4438.8 2083.98  4509.5 2079.77  4679.2 2071.35  4707.5 2068.62  4735.8 2064.51
  4764.1 2065.71  4778.2 2065.08  4806.5 2067.08  4891.4 2067.23  4947.9 2064.71
  4962.1 2065.24  4972.6 2063.15  4973.1 2062.65  4979.8 2063.15  5012.9 2064.69
  5018.5 2067.02  5026.9 2066.67  5040.8 2067.48  5057.6 2066.08  5063.2 2066.58
  5071.6 2066.01  5130.3 2068.17    5175 2067.28  5183.4 2066.24  5214.1 2073.89
  5228.1 2074.39  5258.9 2077.62  5264.4 2077.36  5295.2 2079.42  5339.9  2081.2
#Mann= 3 ,-1 , 0
  4438.8      .1       0  4972.6     .05       0  4979.8      .1       0
Bank Sta=4972.6,4979.8
XS Rating Curve= 0 ,0
Exp/Cntr=0.3,0.1

Type RM Length L Ch R = 1 ,130800  ,462,462,462
BEGIN DESCRIPTION:
Turtle Creek 230.0
END DESCRIPTION:
XS GIS Cut Line= 3
      1873624.98     13904975.02        1873775.       13904775.
      1873924.98     13904475.03
#Sta/Elev= 30
  4741.1  2076.7  4798.4 2074.53    4813 2072.01  4841.1 2064.99  4854.7 2063.07
  4872.3 2062.44  4883.8 2063.01  4891.1 2064.51  4898.4 2064.84  4933.8 2064.09
  4954.7 2062.52    4963 2059.68  4973.7 2059.62  4974.2 2059.12    4981 2059.12
  4981.5 2059.62  4999.5 2061.04  5021.9 2060.63  5042.3 2062.59  5066.6 2063.92
    5089 2067.49  5094.5 2067.34  5102.9 2065.96  5116.9 2064.73    5156 2064.37
  5192.4 2067.72  5228.3  2072.2  5245.5 2073.57  5273.4 2076.84  5326.5 2079.73
#Mann= 6 ,-1 , 0
  4741.1     .07       0  4872.3      .1       0  4973.7     .05       0
  4981.5      .1       0  5042.3     .07       0  5228.3      .1       0
Bank Sta=4973.7,4981.5
XS Rating Curve= 0 ,0
Exp/Cntr=0.3,0.1

Type RM Length L Ch R = 1 ,130338  ,455,455,455
BEGIN DESCRIPTION:
Turtle Creek 229.0
END DESCRIPTION:
XS GIS Cut Line= 3
      1873924.98     13905175.01        1874175.       13904975.
        1874175.     13904624.98
#Sta/Elev= 30
  4685.2 2074.55  4713.2 2073.57  4777.3 2069.26  4834.9 2067.02  4877.3 2063.24
  4884.5 2063.74  4890.9 2062.04  4898.9 2061.71  4905.3 2059.88  4919.7 2059.01
  4934.1 2058.89  4948.6 2059.59    4963 2058.55  4969.4 2057.29  4998.2 2057.35
  5011.4 2056.65  5011.9 2056.15  5018.8 2056.15  5019.3 2056.65  5033.9 2057.17
  5045.4 2057.68  5075.4 2061.55  5085.4 2061.96  5125.4    2062  5135.4  2060.8
  5145.4 2060.92  5205.4    2066  5235.3  2069.3  5265.4 2072.54  5355.4 2077.01
#Mann= 5 ,-1 , 0
  4685.2      .1       0  5011.4     .05       0  5019.3      .1       0
  5033.9     .07       0  5235.3      .1       0
Bank Sta=5011.4,5019.3
XS Rating Curve= 0 ,0
Exp/Cntr=0.3,0.1

Type RM Length L Ch R = 1 ,129883  ,424,424,424
BEGIN DESCRIPTION:
Turtle Creek 228.0
END DESCRIPTION:
XS GIS Cut Line= 3
        1874475.     13905375.01        1874575.       13905125.
      1874924.97     13904825.03
#Sta/Elev= 30
  4725.9 2069.04  4789.2 2067.21  4824.2  2065.2  4956.1 2062.78  4973.6 2060.28
  4980.4 2057.19  4992.5 2054.24  5002.3 2054.62  5008.9 2052.87  5012.5 2052.77
    5013 2052.27  5020.1 2052.27  5020.6 2052.77    5066 2055.68  5094.5 2055.79
  5101.1 2056.68  5143.9 2058.23    5201 2058.94  5229.5 2060.17    5235  2061.1
  5243.8 2060.25  5285.5 2067.13  5293.2 2067.57  5299.7 2069.07  5350.2 2075.59
  5363.9 2078.72  5399.6 2083.78  5406.2  2083.7  5413.9 2085.01  5456.1 2087.05
#Mann= 4 ,-1 , 0
  4725.9     .07       0  5012.5     .05       0  5020.6     .07       0
    5235      .1       0
Bank Sta=5012.5,5020.6
XS Rating Curve= 0 ,0
Exp/Cntr=0.3,0.1