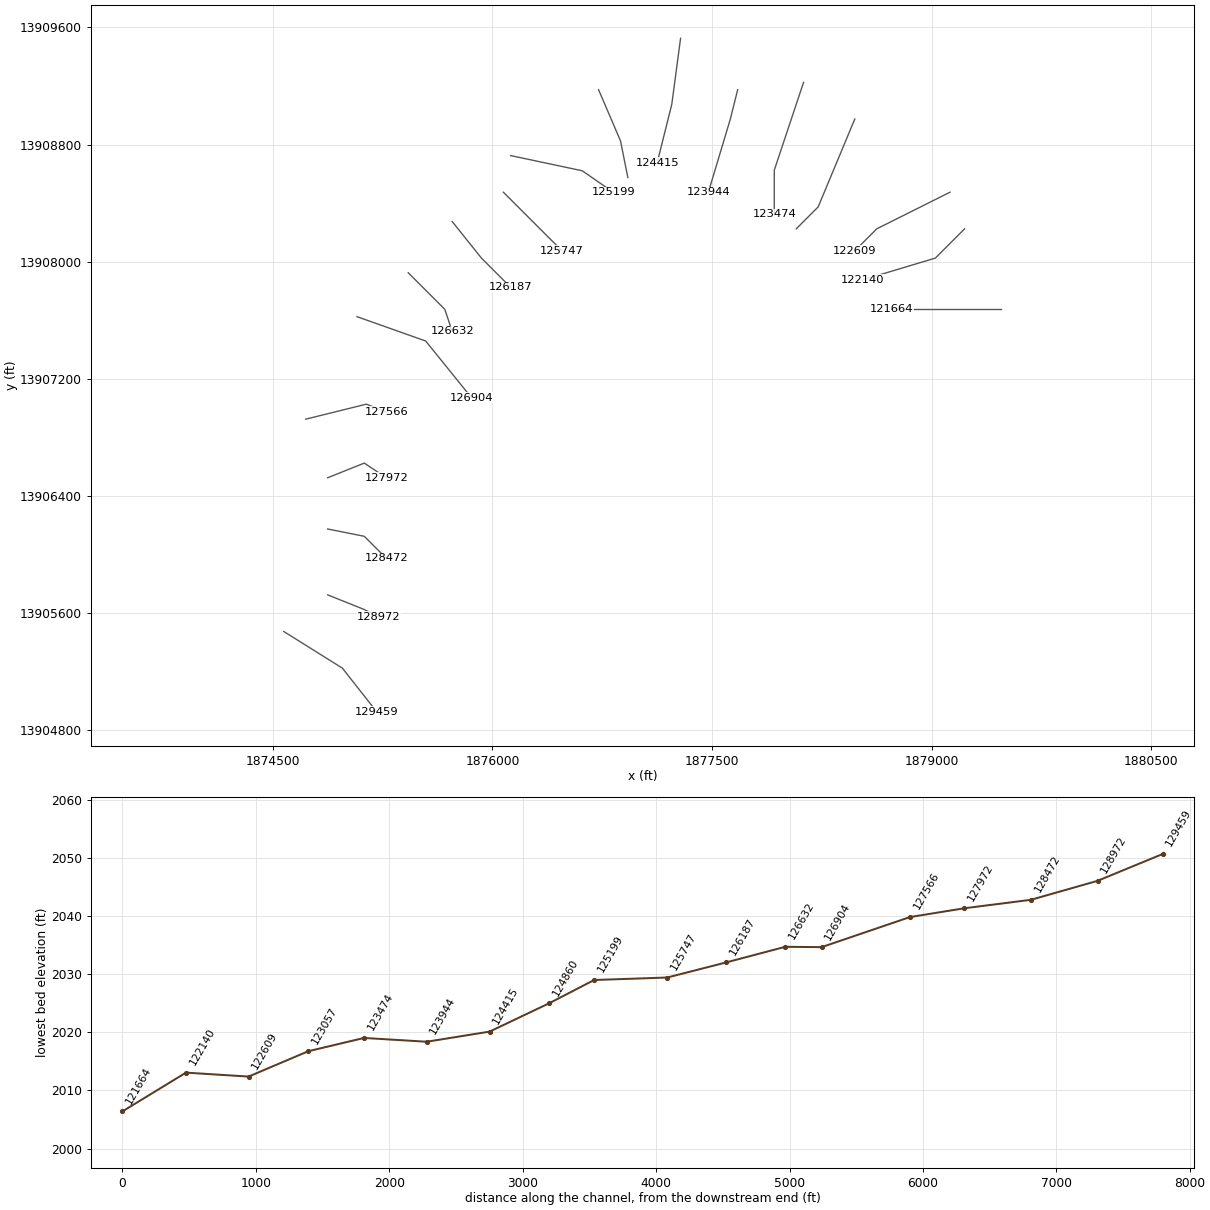
HEC-RAS study Turtle Creek.prj: Turtle Creek Base Level Engineering

--- Turtle Creek.g01 (geometry) --- (continued)

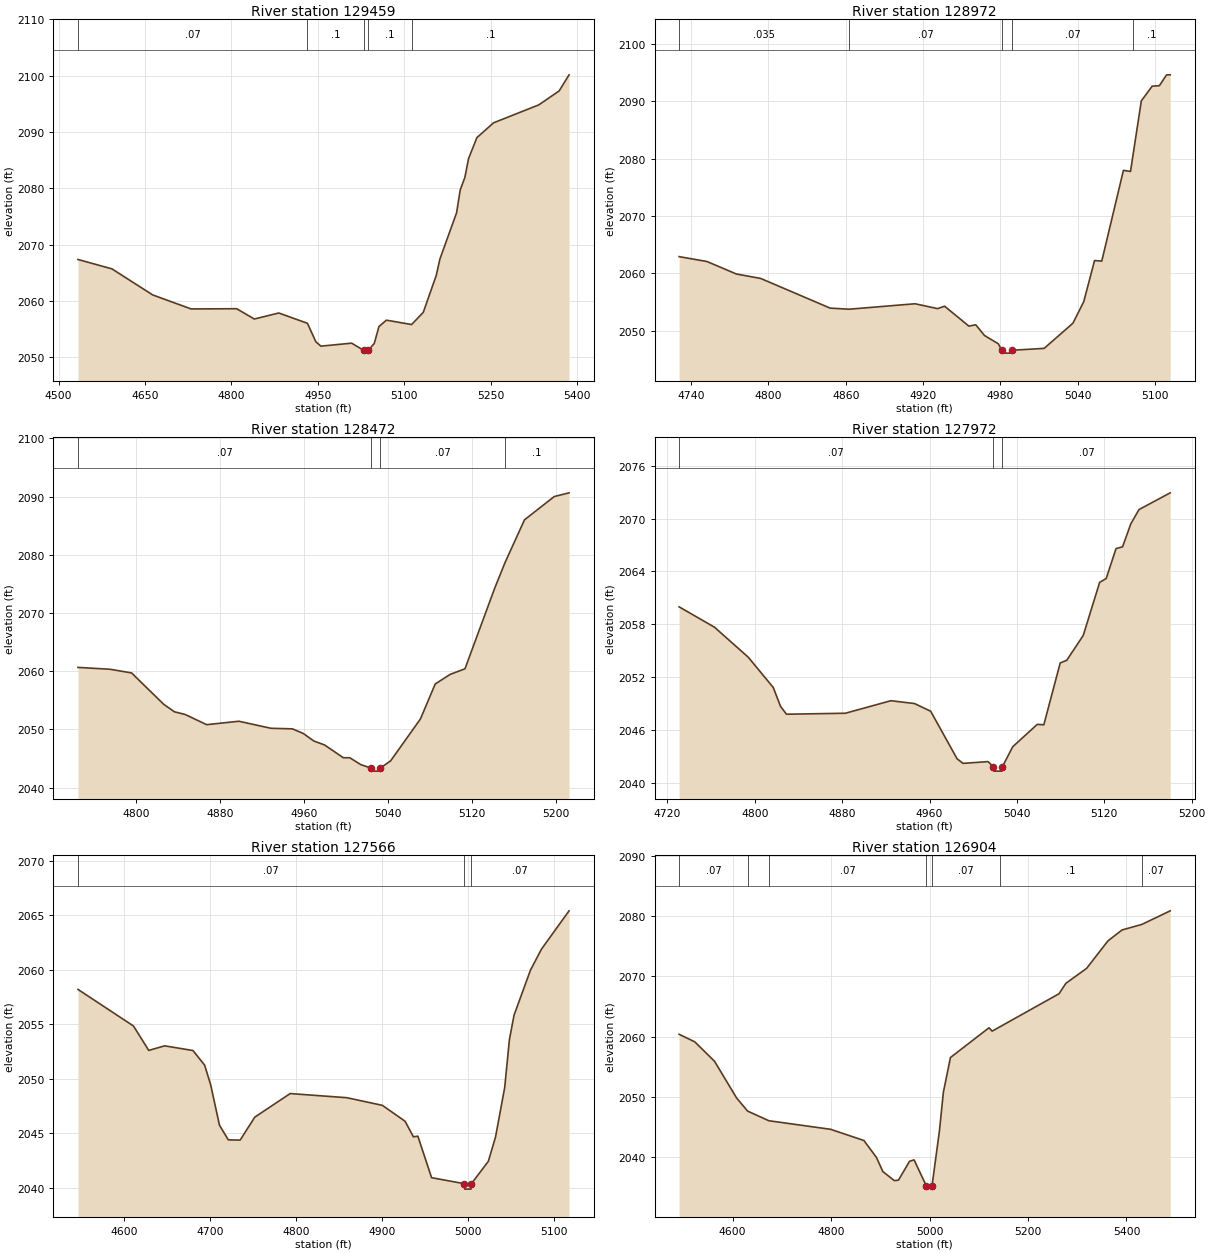
Type RM Length L Ch R = 1 ,129459  ,487,487,487
BEGIN DESCRIPTION:
Turtle Creek 227.0
END DESCRIPTION:
XS GIS Cut Line= 3
      1874574.98     13905475.01        1874975.       13905225.
      1875210.19     13904925.93
#Sta/Elev= 30
  4533.6 2067.35  4592.6 2065.68  4663.3 2061.05    4730 2058.56    4809  2058.6
  4839.6 2056.77  4882.1 2057.84  4931.8 2056.01  4946.4 2052.73  4955.2 2051.95
  5008.5 2052.48  5029.3 2051.21  5029.8 2050.71  5037.4 2051.21  5047.8 2052.44
  5055.9 2055.44  5068.9 2056.57  5112.5 2055.79  5132.8 2057.95  5155.3 2064.51
  5161.7 2067.44  5190.6 2075.64  5196.9 2079.69    5205 2081.94  5211.4 2085.28
  5225.8 2088.99  5254.7 2091.63  5333.3 2094.82  5368.6  2097.3  5385.8 2100.16
#Mann= 5 ,-1 , 0
  4533.6     .07       0  4931.8      .1       0  5029.3     .05       0
  5037.4      .1       0  5112.5      .1       0
Bank Sta=5029.3,5037.4
XS Rating Curve= 0 ,0
Exp/Cntr=0.3,0.1

Type RM Length L Ch R = 1 ,128972  ,500,500,500
BEGIN DESCRIPTION:
Turtle Creek 226.0
END DESCRIPTION:
XS GIS Cut Line= 3
      1874874.97     13905725.01        1875125.       13905625.
      1875225.01       13905575.
#Sta/Elev= 30
  4730.7 2062.91  4752.3 2062.06  4775.2 2059.88    4794 2059.11  4847.9 2053.94
  4862.7 2053.75  4913.8  2054.7  4931.3 2053.85  4936.7 2054.28  4955.6  2050.8
  4960.9 2051.04  4967.7 2049.17  4978.4 2047.73  4981.1  2046.6  4981.6  2046.1
  4988.8  2046.1  4989.3  2046.6    5014 2046.93  5036.3 2051.31  5044.7 2055.06
  5053.1 2062.23  5058.7 2062.13  5075.5 2077.94    5081 2077.75  5083.1 2080.83
  5089.4 2090.05  5097.8  2092.6  5103.4 2092.69    5109 2094.58  5111.8 2094.58
#Mann= 5 ,-1 , 0
  4730.7    .035       0  4862.7     .07       0  4981.1     .05       0
  4989.3     .07       0  5083.1      .1       0
Bank Sta=4981.1,4989.3
XS Rating Curve= 0 ,0
Exp/Cntr=0.3,0.1

Type RM Length L Ch R = 1 ,128472  ,500,500,500
BEGIN DESCRIPTION:
Turtle Creek 225.0
END DESCRIPTION:
XS GIS Cut Line= 3
      1874874.96     13906175.01        1875125.       13906125.
      1875274.98     13905975.02
#Sta/Elev= 30
    4745 2060.65  4775.6 2060.33    4796  2059.7  4826.6  2054.3  4836.8 2053.02
    4847 2052.56  4867.4 2050.81    4898  2051.4  4928.6 2050.19    4949 2050.09
  4959.2 2049.31  4969.4    2048  4979.6 2047.32  4997.4 2045.13  5003.5 2045.13
  5014.1 2043.94  5024.1 2043.33  5024.6 2042.83  5031.9 2042.83  5032.4 2043.33
  5042.4  2044.6  5070.7 2051.78  5084.8  2057.8    5099 2059.45  5113.1 2060.41
  5141.4 2074.27  5151.3  2078.7  5169.7    2086    5198    2090  5212.1 2090.64
#Mann= 4 ,-1 , 0
    4745     .07       0  5024.1     .05       0  5032.4     .07       0
  5151.3      .1       0
Bank Sta=5024.1,5032.4
XS Rating Curve= 0 ,0
Exp/Cntr=0.3,0.1

Type RM Length L Ch R = 1 ,127972  ,406,406,406
BEGIN DESCRIPTION:
Turtle Creek 224.0
END DESCRIPTION:
XS GIS Cut Line= 3
      1874874.96     13906524.98        1875125.       13906625.
      1875275.02     13906524.99
#Sta/Elev= 30
  4730.7 2059.99  4763.1 2057.68    4794 2054.28  4816.9 2050.85  4823.6  2048.7
    4829 2047.82  4882.9 2047.93  4924.6 2049.35  4946.2 2049.03    4961 2048.16
  4985.2 2042.77  4990.6 2042.25  5013.5 2042.45  5018.4 2041.87  5018.9 2041.37
  5026.2 2041.37  5026.7 2041.87  5036.1 2044.13  5058.6 2046.67  5064.6 2046.62
  5079.6 2053.63  5085.6 2053.93  5100.7 2056.75  5115.7 2062.76  5121.7  2063.2
  5130.7 2066.59  5136.7 2066.79  5144.2 2069.38  5151.7 2071.01  5180.3 2072.91
#Mann= 3 ,-1 , 0
  4730.7     .07       0  5018.4     .05       0  5026.7     .07       0
Bank Sta=5018.4,5026.7
XS Rating Curve= 0 ,0
Exp/Cntr=0.3,0.1

Type RM Length L Ch R = 1 ,127566  ,662,662,662
BEGIN DESCRIPTION:
Turtle Creek 223.0
END DESCRIPTION:
XS GIS Cut Line= 3
      1874724.96     13906924.99      1875139.14     13907027.48
      1875274.98     13906975.01
#Sta/Elev= 30
  4545.8 2058.19  4610.5 2054.83  4628.3 2052.59  4646.8 2053.01  4679.8 2052.58
  4693.4 2051.24  4700.4 2049.45  4710.7 2045.73    4721 2044.38  4734.8 2044.36
  4751.9 2046.47  4793.1 2048.63  4859.1 2048.25  4900.5 2047.55    4927 2046.09
  4936.7 2044.66  4941.9 2044.72  4957.9 2040.91    4996 2040.36  4996.5 2039.86
  5003.8 2039.86  5004.3 2040.36    5024 2042.41  5032.4 2044.64  5043.1 2049.19
  5048.6 2053.59    5054 2055.83  5073.2 2059.97    5086 2061.89  5118.1  2065.4
#Mann= 3 ,-1 , 0
  4545.8     .07       0    4996     .05       0  5004.3     .07       0
Bank Sta=4996,5004.3
XS Rating Curve= 0 ,0
Exp/Cntr=0.3,0.1

Type RM Length L Ch R = 1 ,126904  ,272,272,272
BEGIN DESCRIPTION:
Turtle Creek 222.0
END DESCRIPTION:
XS GIS Cut Line= 3
        1875075.       13907625.      1875544.41     13907458.64
      1875858.46     13907070.11
#Sta/Elev= 30
  4491.3 2060.38  4523.1 2059.13  4563.2 2055.91    4608 2049.82  4630.3 2047.64
  4673.6 2046.03    4799 2044.61  4866.7 2042.75  4892.3 2039.93  4905.1  2037.6
  4928.5 2036.09  4936.9 2036.17  4959.4  2039.3  4968.7 2039.53  4993.7 2035.18
  4994.2 2034.68    5005 2035.18  5020.1 2044.33  5028.1 2050.74  5042.5 2056.52
  5120.8 2061.46  5127.2  2060.9  5142.7 2061.61  5263.1 2067.11  5276.9 2068.83
  5319.1 2071.32  5362.3 2075.87    5391 2077.69  5431.5 2078.62  5488.9 2080.87
#Mann= 7 ,-1 , 0
  4491.3     .07       0  4630.3      .1       0  4673.6     .07       0
  4993.7     .05       0    5005     .07       0  5142.7      .1       0
  5431.5     .07       0
Bank Sta=4993.7,5005
XS Rating Curve= 0 ,0
Exp/Cntr=0.3,0.1

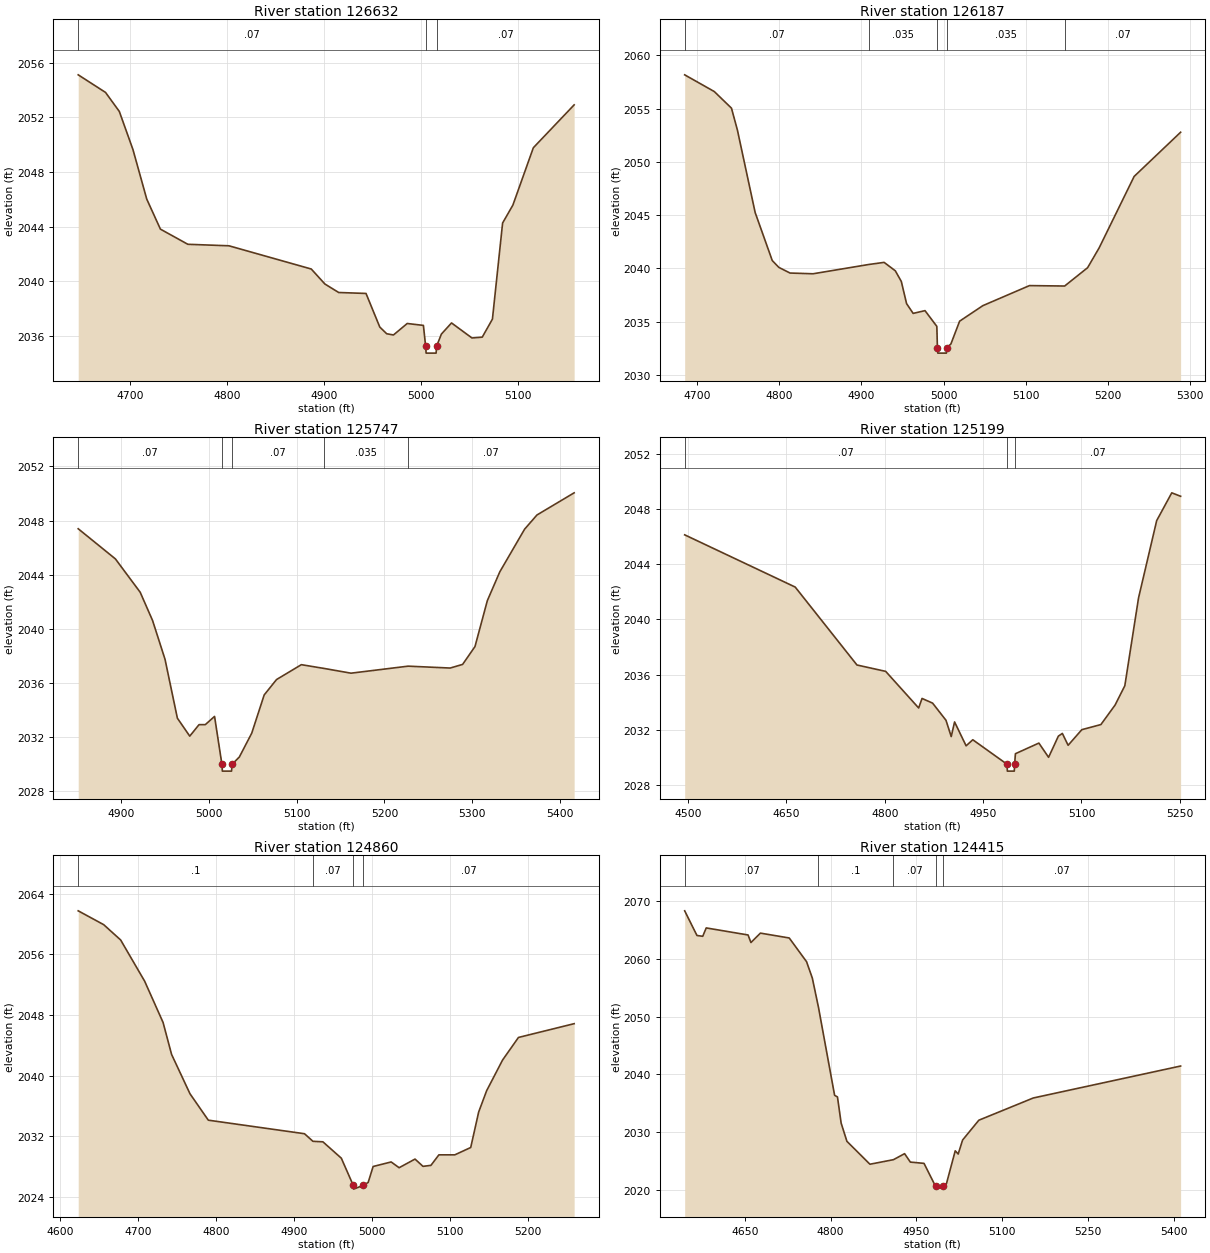
Type RM Length L Ch R = 1 ,126632  ,445,445,445
BEGIN DESCRIPTION:
Turtle Creek 221.0
END DESCRIPTION:
XS GIS Cut Line= 3
      1875425.03     13907924.97        1875675.       13907675.
      1875724.99     13907525.02
#Sta/Elev= 30
  4646.5 2055.12  4674.7 2053.83  4688.9 2052.44    4703 2049.64  4717.2 2046.02
  4731.3 2043.82  4759.6 2042.71    4802  2042.6  4886.9  2040.9    4901  2039.8
  4915.2 2039.18  4943.4 2039.11  4957.6 2036.65  4964.7 2036.16  4971.7 2036.07
  4985.9 2036.91  5002.6 2036.77  5004.9 2035.24  5005.4 2034.74  5015.7 2034.74
  5016.2 2035.24  5021.1 2036.13  5031.6 2036.95  5052.7 2035.85  5063.3 2035.91
  5073.8 2037.23  5084.3 2044.27  5094.9 2045.58    5116 2049.78  5158.1 2052.92
#Mann= 3 ,-1 , 0
  4646.5     .07       0  5004.9     .05       0  5016.2     .07       0
Bank Sta=5004.9,5016.2
XS Rating Curve= 0 ,0
Exp/Cntr=0.3,0.1

Type RM Length L Ch R = 1 ,126187  ,440,440,440
BEGIN DESCRIPTION:
Turtle Creek 220.0
END DESCRIPTION:
XS GIS Cut Line= 3
      1875724.98     13908275.02        1875925.       13908025.
      1876124.98     13907825.02
#Sta/Elev= 30
  4685.2 2058.17  4721.2  2056.6  4742.1 2055.04  4749.3 2052.99  4770.9 2045.24
  4791.7 2040.73  4799.7 2040.09  4813.3 2039.56  4841.3 2039.49  4908.8 2040.36
  4927.7 2040.56  4941.3 2039.77  4948.6 2038.77    4955 2036.69    4963 2035.77
  4977.4 2036.03  4991.8 2034.55  4992.5 2032.54    4993 2032.04  5003.4 2032.04
  5003.9 2032.54  5008.9  2032.9  5019.5 2035.04  5047.8  2036.5  5104.4 2038.38
  5147.2 2038.34  5175.1 2040.06  5189.2 2041.93  5231.7 2048.63  5288.2 2052.78
#Mann= 5 ,-1 , 0
  4685.2     .07       0  4908.8    .035       0  4992.5    .035       0
  5003.9    .035       0  5147.2     .07       0
Bank Sta=4992.5,5003.9
XS Rating Curve= 0 ,0
Exp/Cntr=0.3,0.1

Type RM Length L Ch R = 1 ,125747  ,548,548,548
BEGIN DESCRIPTION:
Turtle Creek 219.0
END DESCRIPTION:
XS GIS Cut Line= 3
      1876075.03     13908474.97        1876175.       13908375.
      1876474.97     13908075.03
#Sta/Elev= 30
  4850.7 2047.39  4893.1 2045.16  4921.4 2042.69  4935.5  2040.6  4949.7 2037.73
  4963.8 2033.37  4977.9 2032.04  4988.5 2032.89  4995.6 2032.89  5006.2  2033.5
  5014.6 2029.95  5015.1 2029.45  5025.6 2029.45  5026.1 2029.95  5034.5  2030.5
  5048.6 2032.26  5062.8 2035.09  5076.9 2036.23  5105.2 2037.33  5131.2 2037.05
  5161.8  2036.7    5227 2037.22  5274.9 2037.08  5289.1 2037.35  5303.2 2038.67
  5317.3 2042.07  5331.5  2044.2  5359.8 2047.36  5373.9 2048.41  5416.3 2050.05
#Mann= 5 ,-1 , 0
  4850.7     .07       0  5014.6     .05       0  5026.1     .07       0
  5131.2    .035       0    5227     .07       0
Bank Sta=5014.6,5026.1
XS Rating Curve= 0 ,0
Exp/Cntr=0.3,0.1

Type RM Length L Ch R = 1 ,125199  ,339,339,339
BEGIN DESCRIPTION:
Turtle Creek 218.0
END DESCRIPTION:
XS GIS Cut Line= 3
      1876125.05     13908724.99       1876613.5     13908621.34
      1876824.98     13908475.01
#Sta/Elev= 30
  4494.7 2046.12  4663.3 2042.34  4757.5  2036.7  4801.3 2036.24  4851.6 2033.59
  4856.8 2034.28  4872.9 2033.94  4893.3  2032.7  4901.3 2031.52  4906.4 2032.58
    4924 2030.85  4934.2 2031.29  4986.4 2029.52  4986.9 2029.02  4997.5 2029.02
    4998 2029.52  4999.2 2030.28    5035 2031.05  5049.8 2030.02  5064.7 2031.55
  5070.8 2031.75  5079.6 2030.89  5100.5 2032.02  5129.6 2032.39  5151.2  2033.8
  5166.1  2035.2    5187 2041.55  5214.7 2047.15  5237.7 2049.16  5251.2 2048.91
#Mann= 3 ,-1 , 0
  4494.7     .07       0  4986.4     .05       0    4998     .07       0
Bank Sta=4986.4,4998
XS Rating Curve= 0 ,0
Exp/Cntr=0.3,0.1

Type RM Length L Ch R = 1 ,124860  ,445,445,445
BEGIN DESCRIPTION:
Turtle Creek 217.0
END DESCRIPTION:
XS GIS Cut Line= 3
      1876724.99     13909175.02        1876875.       13908825.
      1876925.01     13908574.96
#Sta/Elev= 30
  4623.5 2061.76  4656.2 2059.93  4677.9 2057.91  4708.7 2052.46  4732.3 2047.01
  4743.2 2042.79  4766.8 2037.59  4790.3  2034.1  4913.6 2032.31  4924.4 2031.31
  4937.2 2031.24  4960.8 2029.08  4976.1 2025.49  4976.6 2024.99  4988.9 2025.49
  4995.2 2025.87  5001.6 2027.98  5024.7 2028.58  5034.9 2027.82  5055.3 2028.96
  5065.5    2028  5075.7 2028.13  5085.9 2029.52  5106.3 2029.52  5126.7 2030.49
  5136.9 2035.18  5147.1 2037.99  5167.5 2042.04  5187.9 2045.03  5259.3 2046.85
#Mann= 4 ,-1 , 0
  4623.5      .1       0  4924.4     .07       0  4976.1     .05       0
  4988.9     .07       0
Bank Sta=4976.1,4988.9
XS Rating Curve= 0 ,0
Exp/Cntr=0.3,0.1

Type RM Length L Ch R = 1 ,124415  ,471,471,471
BEGIN DESCRIPTION:
Turtle Creek 216.0
END DESCRIPTION:
XS GIS Cut Line= 3
      1877285.12      13909526.3        1877225.       13909075.
        1877125.       13908675.
#Sta/Elev= 30
  4544.7 2068.31  4566.2 2064.04  4576.3  2063.9  4582.4 2065.35  4655.6 2064.13
  4660.6 2062.82  4677.2 2064.45  4727.6 2063.61  4757.9 2059.51    4768 2056.67
  4778.8 2051.59    4807 2036.37    4812 2036.09  4818.4 2031.57  4828.5 2028.41
  4868.8 2024.44    4910 2025.23  4929.4 2026.27  4939.5 2024.81  4963.4 2024.59
  4983.5 2020.63    4984 2020.13  4996.3 2020.63  5002.6 2021.06    5018 2026.76
  5023.2 2026.21  5030.9 2028.63  5059.3 2032.06  5154.6 2035.91  5412.3 2041.44
#Mann= 5 ,-1 , 0
  4544.7     .07       0  4778.8      .1       0    4910     .07       0
  4983.5     .05       0  4996.3     .07       0
Bank Sta=4983.5,4996.3
XS Rating Curve= 0 ,0
Exp/Cntr=0.3,0.1

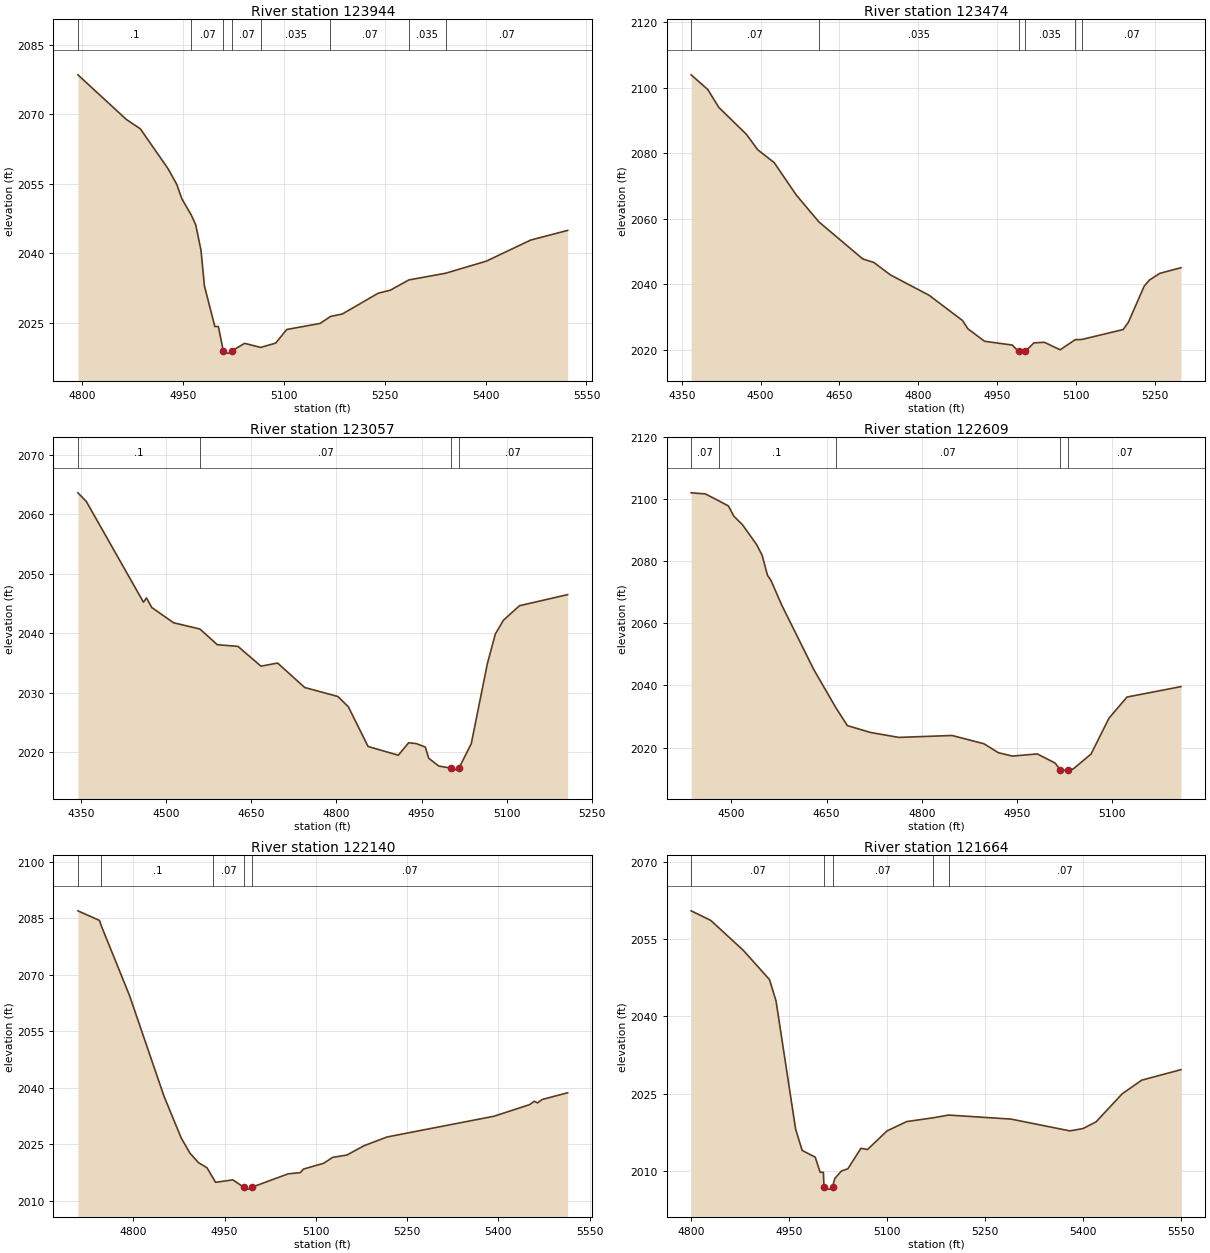
Type RM Length L Ch R = 1 ,123944  ,470,470,470
BEGIN DESCRIPTION:
Turtle Creek 215.0
END DESCRIPTION:
XS GIS Cut Line= 3
        1877675.     13909174.99        1877625.       13908975.
      1877474.99     13908474.96
#Sta/Elev= 30
  4793.9 2078.46    4866 2068.82  4886.7 2066.81  4927.9 2058.21  4940.8 2054.84
  4948.5 2051.69  4962.6 2048.16  4969.1 2046.08  4976.9 2040.61    4982 2032.92
  4997.5 2024.14  5002.7 2024.14  5010.1 2018.89  5010.6 2018.39  5022.5 2018.39
    5023 2018.89  5041.8  2020.5  5065.7 2019.62  5087.9 2020.55  5104.4 2023.49
    5154  2024.8  5169.4  2026.3  5187.1 2026.84  5240.2 2031.31  5258.4 2031.98
    5286 2034.19  5340.5 2035.63  5401.1 2038.24  5467.2  2042.8  5522.1 2044.88
#Mann= 8 ,-1 , 0
  4793.9      .1       0  4962.6     .07       0  5010.1     .05       0
    5023     .07       0  5065.7    .035       0  5169.4     .07       0
    5286    .035       0  5340.5     .07       0
Bank Sta=5010.1,5023
XS Rating Curve= 0 ,0
Exp/Cntr=0.3,0.1

Type RM Length L Ch R = 1 ,123474  ,417,417,417
BEGIN DESCRIPTION:
Turtle Creek 214.0
END DESCRIPTION:
XS GIS Cut Line= 3
        1878125.     13909225.01        1877925.       13908625.
        1877925.     13908324.96
#Sta/Elev= 30
  4367.8  2103.9  4399.4 2099.43  4420.5 2093.96  4473.2 2085.73  4494.3  2081.1
  4525.9 2077.13  4568.1 2067.22    4611 2059.06  4694.6 2047.76  4715.7 2046.68
  4747.3 2042.88  4821.1 2036.66  4884.3    2029  4894.9 2026.43  4926.5 2022.66
  4979.2  2021.5  4991.1 2019.54  4991.6 2019.04  5004.1 2019.54  5020.3 2022.16
  5040.3 2022.35  5070.3 2020.06  5099.2 2023.15  5111.5  2023.2  5190.3 2026.23
  5200.3 2028.47  5230.3 2039.44  5240.3 2041.32  5260.3 2043.38  5300.3 2045.08
#Mann= 6 ,-1 , 0
  4367.8     .07       0    4611    .035       0  4991.1     .05       0
  5004.1    .035       0  5099.2    .035       0  5111.5     .07       0
Bank Sta=4991.1,5004.1
XS Rating Curve= 0 ,0
Exp/Cntr=0.3,0.1

Type RM Length L Ch R = 1 ,123057  ,448,448,448
BEGIN DESCRIPTION:
Turtle Creek 213.0
END DESCRIPTION:
XS GIS Cut Line= 3
      1878474.99     13908974.99        1878225.       13908375.
      1878075.01     13908225.01
#Sta/Elev= 30
    4345 2063.65  4359.6 2062.23  4460.4 2045.22  4465.8 2045.94    4475 2044.33
  4513.4 2041.76  4559.8  2040.7  4590.4 2038.06  4626.7 2037.78  4667.3 2034.44
  4696.5 2034.97  4744.2 2030.85  4802.7 2029.33  4821.1 2027.59  4855.8 2020.91
  4908.9 2019.44  4927.3 2021.55  4940.8 2021.39  4956.5 2020.82  4962.5 2018.93
  4980.4 2017.61  5002.6 2017.26  5003.1 2016.76  5015.7 2017.26  5037.4 2021.38
  5065.7 2034.85  5079.8 2039.87    5094 2042.18  5122.3 2044.63  5207.1  2046.5
#Mann= 4 ,-1 , 0
    4345      .1       0  4559.8     .07       0  5002.6     .05       0
  5015.7     .07       0
Bank Sta=5002.6,5015.7
XS Rating Curve= 0 ,0
Exp/Cntr=0.3,0.1

Type RM Length L Ch R = 1 ,122609  ,469,469,469
BEGIN DESCRIPTION:
Turtle Creek 212.0
END DESCRIPTION:
XS GIS Cut Line= 3
      1879125.01       13908475.        1878625.       13908225.
      1878474.97     13908074.97
#Sta/Elev= 30
  4436.7  2102.1  4459.1 2101.75  4479.9 2099.56  4495.4 2097.86  4503.8 2094.62
  4517.8 2091.73  4540.1 2085.32  4548.5 2081.95  4556.9 2075.52  4562.5 2073.82
  4579.3 2065.92  4629.6  2045.2  4664.5 2032.86  4682.7 2027.06    4719 2024.86
  4763.7 2023.26  4847.6 2023.88  4897.9  2021.2  4920.3 2018.34  4942.6 2017.24
  4981.7 2017.94  5009.9 2014.98  5017.5 2012.89    5018 2012.39  5030.6 2012.89
  5038.2 2013.08  5066.4  2017.9  5094.7 2029.48    5123 2036.27  5207.9 2039.63
#Mann= 5 ,-1 , 0
  4436.7     .07       0  4479.9      .1       0  4664.5     .07       0
  5017.5     .05       0  5030.6     .07       0
Bank Sta=5017.5,5030.6
XS Rating Curve= 0 ,0
Exp/Cntr=0.3,0.1

Type RM Length L Ch R = 1 ,122140  ,476,476,476
BEGIN DESCRIPTION:
Turtle Creek 211.0
END DESCRIPTION:
XS GIS Cut Line= 3
      1879225.01     13908225.01        1879025.       13908025.
      1878524.97     13907874.99
#Sta/Elev= 30
    4709 2087.01  4744.4 2084.46  4747.6 2082.97  4793.9 2064.48  4850.4  2037.8
  4878.7 2026.69  4892.9 2022.68    4907 2020.12  4921.1 2018.75  4931.3 2015.97
  4935.3 2014.88  4963.6 2015.53  4981.7 2013.57  4982.2 2013.07  4994.4 2013.07
  4994.9 2013.57  5054.5 2017.13  5074.5 2017.45  5079.7  2018.4  5112.8 2019.93
  5127.6  2021.5  5151.1 2022.13  5178.9 2024.58  5217.2 2026.93  5392.9 2032.44
  5451.2 2035.51  5459.1 2036.41  5464.3 2035.99  5472.1 2036.89  5513.9 2038.67
#Mann= 5 ,-1 , 0
    4709     .07       0  4747.6      .1       0  4931.3     .07       0
  4981.7     .05       0  4994.9     .07       0
Bank Sta=4981.7,4994.9
XS Rating Curve= 0 ,0
Exp/Cntr=0.3,0.1

Type RM Length L Ch R = 1 ,121664  ,473,473,473
BEGIN DESCRIPTION:
Turtle Creek 210.0
END DESCRIPTION:
XS GIS Cut Line= 3
      1879475.01       13907675.        1879275.       13907675.
      1878725.01       13907675.
#Sta/Elev= 30
  4800.5 2060.54  4830.5 2058.68  4880.5 2052.84  4920.5 2047.16  4930.5    2043
  4960.5 2018.05  4970.5 2013.93  4990.5 2012.62    4998 2009.68    5003 2009.68
  5003.9  2006.9  5004.4  2006.4  5016.6  2006.4  5017.1  2006.9  5020.5 2008.47
  5030.5 2009.92  5040.5 2010.36  5060.5 2014.34  5070.5  2014.1  5100.5 2017.73
  5130.5 2019.54  5171.3 2020.28  5194.9 2020.81  5290.5 2020.02  5380.5 2017.73
  5400.5 2018.18  5420.5 2019.48  5460.5 2024.94  5490.5  2027.6  5550.5 2029.64
#Mann= 5 ,-1 , 0
  4800.5     .07       0  5003.9     .05       0  5017.1     .07       0
  5171.3    .035       0  5194.9     .07       0
Bank Sta=5003.9,5017.1
XS Rating Curve= 0 ,0
Exp/Cntr=0.3,0.1