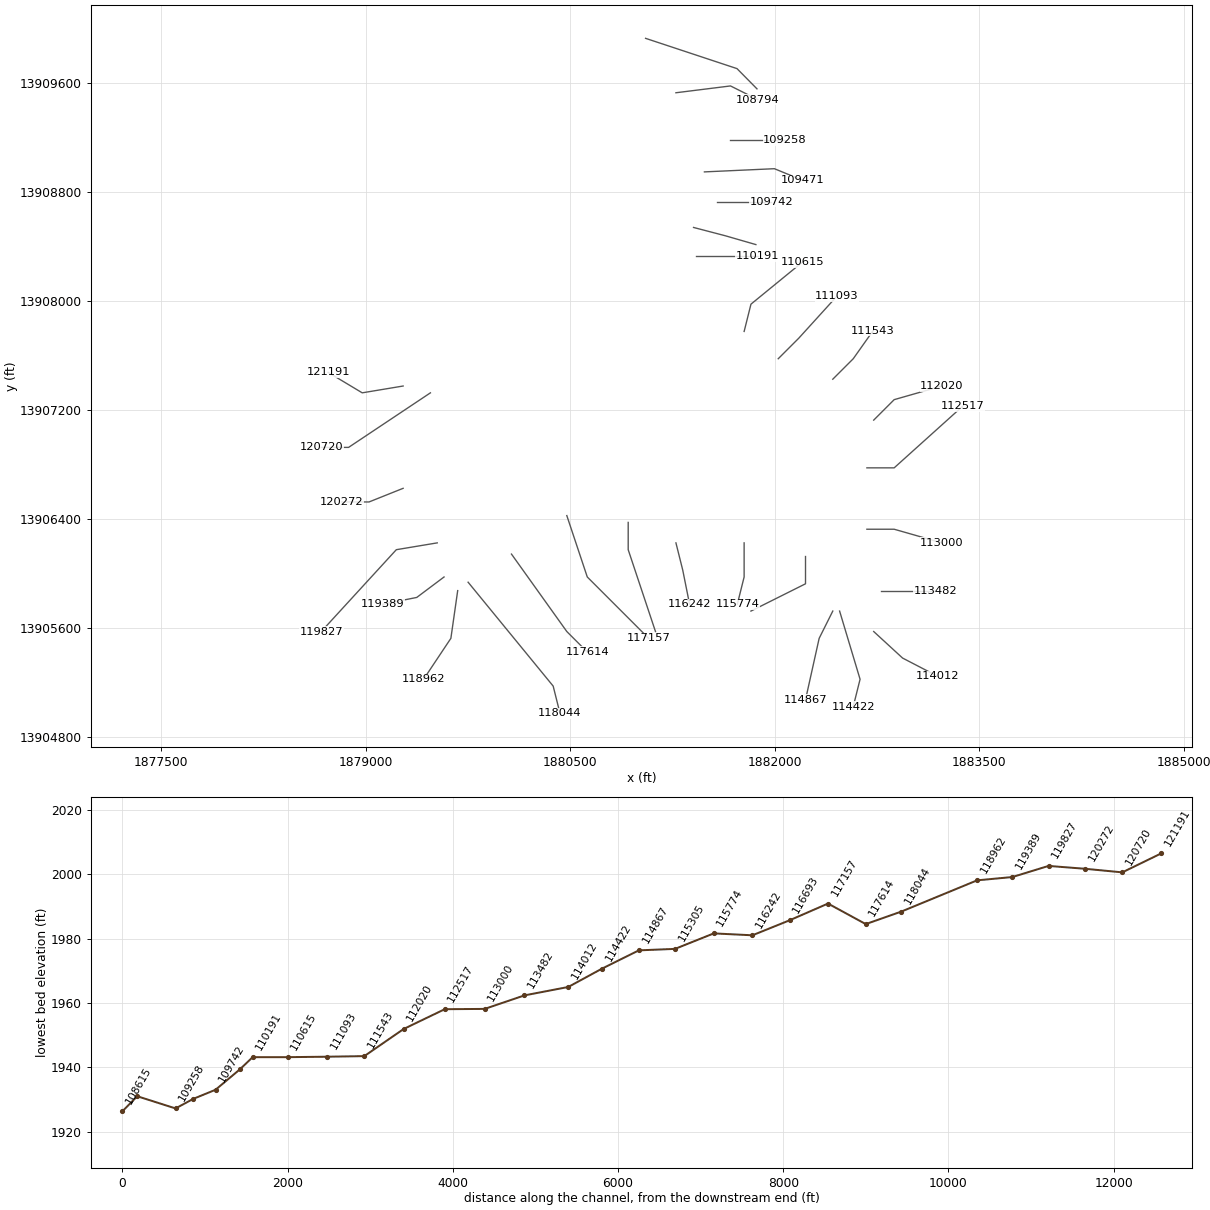
HEC-RAS study Turtle Creek.prj: Turtle Creek Base Level Engineering

--- Turtle Creek.g01 (geometry) --- (continued)

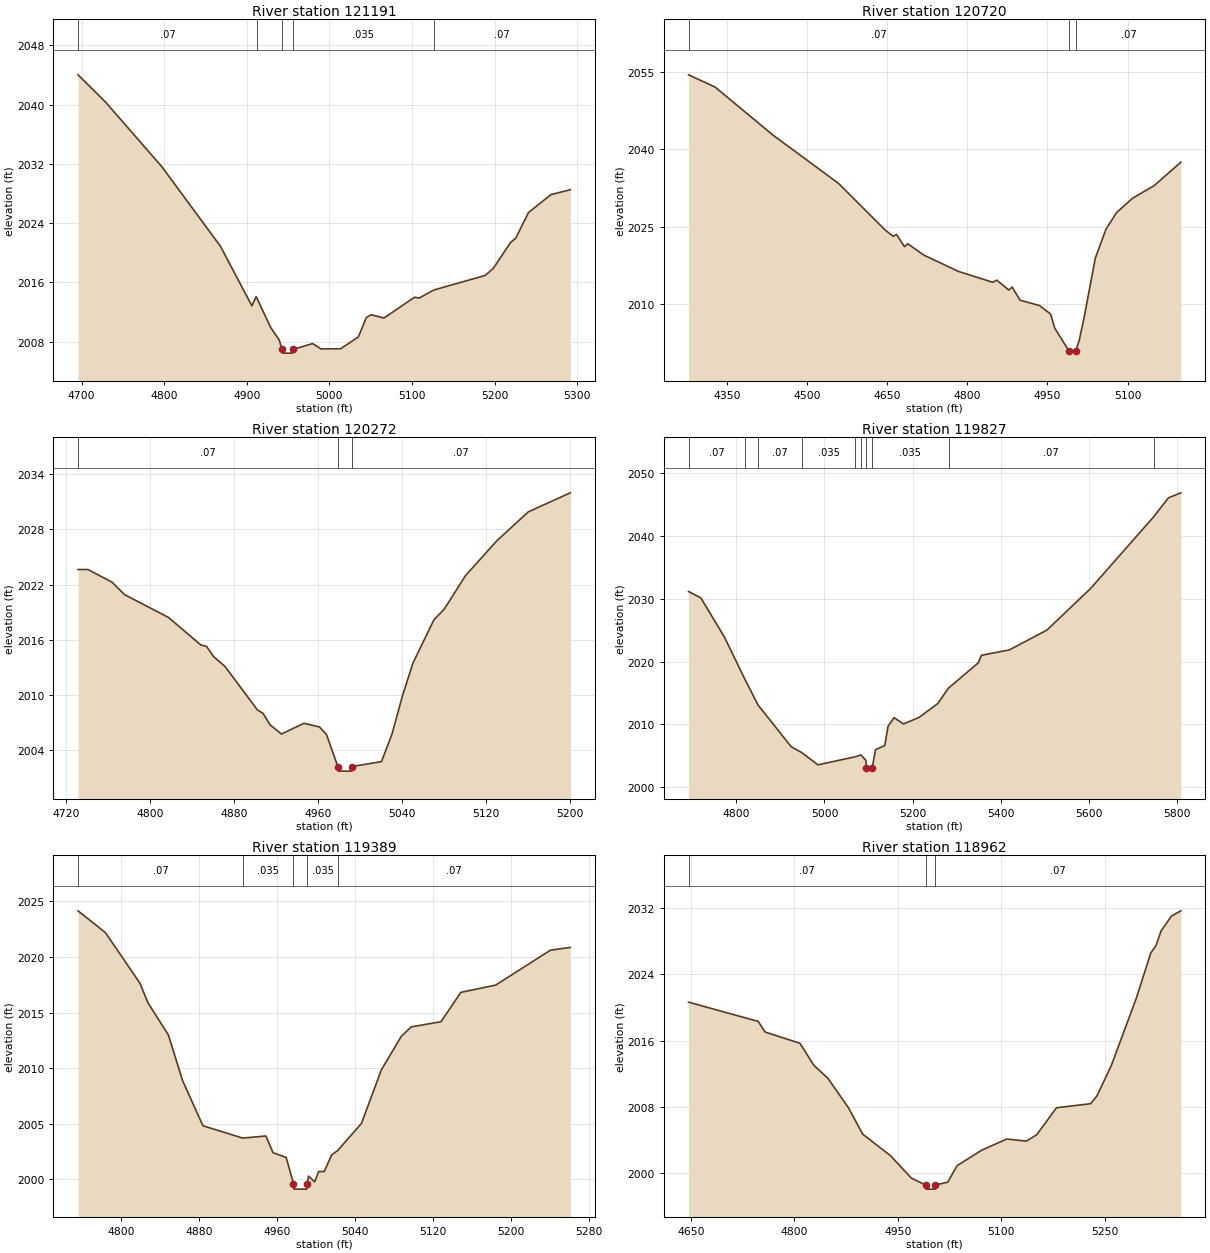
Type RM Length L Ch R = 1 ,121191  ,471,471,471
BEGIN DESCRIPTION:
Turtle Creek 209.0
END DESCRIPTION:
XS GIS Cut Line= 3
      1879275.04     13907375.01        1878975.       13907325.
      1878725.02     13907474.99
#Sta/Elev= 30
  4695.8 2044.01  4728.8 2040.37  4797.2 2031.62  4868.2 2020.87  4906.2 2012.84
  4911.3 2014.08  4912.7 2013.79    4929  2009.9  4939.2 2008.25  4942.7 2006.96
  4943.2 2006.46  4955.4 2006.46  4955.9 2006.96  4979.7 2007.75  4989.8 2007.03
  5013.6 2007.05    5035 2008.64  5044.7 2011.26  5050.5 2011.64  5066.1  2011.2
    5103    2014  5108.8  2013.9  5126.4 2014.98  5188.5 2016.94  5198.2 2017.88
  5219.6 2021.44  5225.4 2021.94    5241 2025.44  5268.2 2027.85  5291.5 2028.51
#Mann= 5 ,-1 , 0
  4695.8     .07       0  4912.7    .035       0  4942.7    .035       0
  4955.9    .035       0  5126.4     .07       0
Bank Sta=4942.7,4955.9
XS Rating Curve= 0 ,0
Exp/Cntr=0.3,0.1

Type RM Length L Ch R = 1 ,120720  ,448,448,448
BEGIN DESCRIPTION:
Turtle Creek 208.0
END DESCRIPTION:
XS GIS Cut Line= 3
      1879474.98     13907324.99        1878875.       13906925.
      1878674.98       13906925.
#Sta/Elev= 30
  4278.6 2054.45  4328.2 2052.09  4436.3 2042.81  4559.5 2033.41  4646.6 2024.39
  4661.7 2023.18  4667.7 2023.55  4682.7 2021.18  4688.7 2021.75  4718.8 2019.55
  4783.4  2016.4    4848 2014.28  4855.5  2014.7    4878 2012.78    4884 2013.37
    4899 2010.81  4935.1 2009.79  4956.1 2008.14  4963.6 2005.45    4990 2001.07
  4990.5 2000.57  5003.4 2001.07  5009.7 2003.06  5019.7 2007.95  5039.7 2018.95
  5059.7 2024.57  5079.7 2027.81  5109.7 2030.57  5149.7 2032.99  5199.7 2037.53
#Mann= 3 ,-1 , 0
  4278.6     .07       0    4990     .05       0  5003.4     .07       0
Bank Sta=4990,5003.4
XS Rating Curve= 0 ,0
Exp/Cntr=0.3,0.1

Type RM Length L Ch R = 1 ,120272  ,445,445,445
BEGIN DESCRIPTION:
Turtle Creek 207.0
END DESCRIPTION:
XS GIS Cut Line= 3
        1879275.       13906625.        1879025.       13906525.
      1878824.96       13906525.
#Sta/Elev= 30
  4731.1 2023.64  4740.5 2023.64  4763.4 2022.27  4775.5  2020.9  4817.3 2018.42
  4848.2 2015.42  4853.6 2015.27  4860.3 2014.16  4871.1  2013.1  4902.1 2008.35
  4907.5 2007.97  4914.2 2006.72    4925 2005.72  4946.5 2006.89  4961.3 2006.49
    4968 2005.66  4978.8 2002.18  4979.3 2001.68  4991.7 2001.68  4992.2 2002.18
  5020.4 2002.72  5030.4 2005.71  5040.4 2009.87  5050.4 2013.45  5070.4 2018.16
  5080.4 2019.35  5100.4 2022.96  5130.4 2026.77  5160.4 2029.92  5200.4 2031.99
#Mann= 3 ,-1 , 0
  4731.1     .07       0  4978.8     .05       0  4992.2     .07       0
Bank Sta=4978.8,4992.2
XS Rating Curve= 0 ,0
Exp/Cntr=0.3,0.1

Type RM Length L Ch R = 1 ,119827  ,438,438,438
BEGIN DESCRIPTION:
Turtle Creek 206.0
END DESCRIPTION:
XS GIS Cut Line= 3
      1879525.01       13906225.        1879225.       13906175.
      1878674.99     13905574.99
#Sta/Elev= 30
  4691.3 2031.15  4719.2 2030.14  4772.4 2023.96  4819.7 2017.12  4849.4 2013.07
  4924.5 2006.45  4948.8  2005.5  4985.3 2003.57  5070.2 2004.86  5082.8 2005.14
  5094.4 2004.28  5095.1 2003.07  5095.6 2002.57  5108.5 2003.07    5116    2006
    5137 2006.63  5144.4 2009.69  5158.2 2011.08  5179.5 2010.07  5214.7 2011.11
  5257.2 2013.31    5282  2015.8  5349.1 2019.77  5356.5    2021    5420 2021.86
  5505.1    2025  5604.4 2031.62    5748 2043.05  5781.3 2046.05  5809.4 2046.85
#Mann= 10 ,-1 , 0
  4691.3     .07       0  4819.7    .035       0  4849.4     .07       0
  4948.8    .035       0  5070.2     .07       0  5082.8    .035       0
  5095.1    .035       0  5108.5    .035       0    5282     .07       0
    5748      .1       0
Bank Sta=5095.1,5108.5
XS Rating Curve= 0 ,0
Exp/Cntr=0.3,0.1

Type RM Length L Ch R = 1 ,119389  ,427,427,427
BEGIN DESCRIPTION:
Turtle Creek 205.0
END DESCRIPTION:
XS GIS Cut Line= 3
      1879574.96     13905974.97        1879375.       13905825.
        1879125.       13905775.
#Sta/Elev= 30
  4755.6 2024.15  4783.7 2022.19  4819.1 2017.64  4827.4 2015.87  4848.3 2012.98
  4862.8 2008.89  4883.7 2004.82  4924.5 2003.71  4948.3  2003.9  4955.6  2002.4
  4969.1 2001.97  4976.6 1999.62  4977.1 1999.12  4990.2 1999.12  4990.7 1999.62
    4992 2000.29  4998.3 1999.77  5002.4  2000.7  5008.1  2000.7  5015.8  2002.2
  5021.9 2002.59  5046.3 2005.03  5066.7 2009.84  5087.1 2012.85  5097.3 2013.71
  5127.9 2014.18  5148.3 2016.82    5184 2017.47  5240.1 2020.61  5260.5 2020.86
#Mann= 5 ,-1 , 0
  4755.6     .07       0  4924.5    .035       0  4976.6    .035       0
  4990.7    .035       0  5021.9     .07       0
Bank Sta=4976.6,4990.7
XS Rating Curve= 0 ,0
Exp/Cntr=0.3,0.1

Type RM Length L Ch R = 1 ,118962  ,918,918,918
BEGIN DESCRIPTION:
Turtle Creek 204.0
END DESCRIPTION:
XS GIS Cut Line= 3
      1879674.99     13905874.95        1879625.       13905525.
      1879424.98     13905224.97
#Sta/Elev= 30
  4646.3 2020.63  4747.3 2018.31  4757.4 2017.03  4807.9 2015.67  4828.1 2013.01
  4848.3 2011.47  4878.6 2007.86  4898.8 2004.73  4939.2 2002.13  4969.5 1999.42
  4990.2 1998.59  4990.7 1998.09  5003.9 1998.09  5004.4 1998.59  5022.3 1998.93
  5035.9 2000.92  5071.9  2002.8    5108 2004.13  5136.5 2003.88  5151.5 2004.66
  5180.1  2007.9  5229.7 2008.39  5238.7 2009.32  5259.7 2013.01  5295.8 2021.09
  5316.8 2026.54  5324.3 2027.44  5331.8 2029.22  5346.8 2031.01  5360.4 2031.64
#Mann= 3 ,-1 , 0
  4646.3     .07       0  4990.2     .05       0  5004.4     .07       0
Bank Sta=4990.2,5004.4
XS Rating Curve= 0 ,0
Exp/Cntr=0.3,0.1

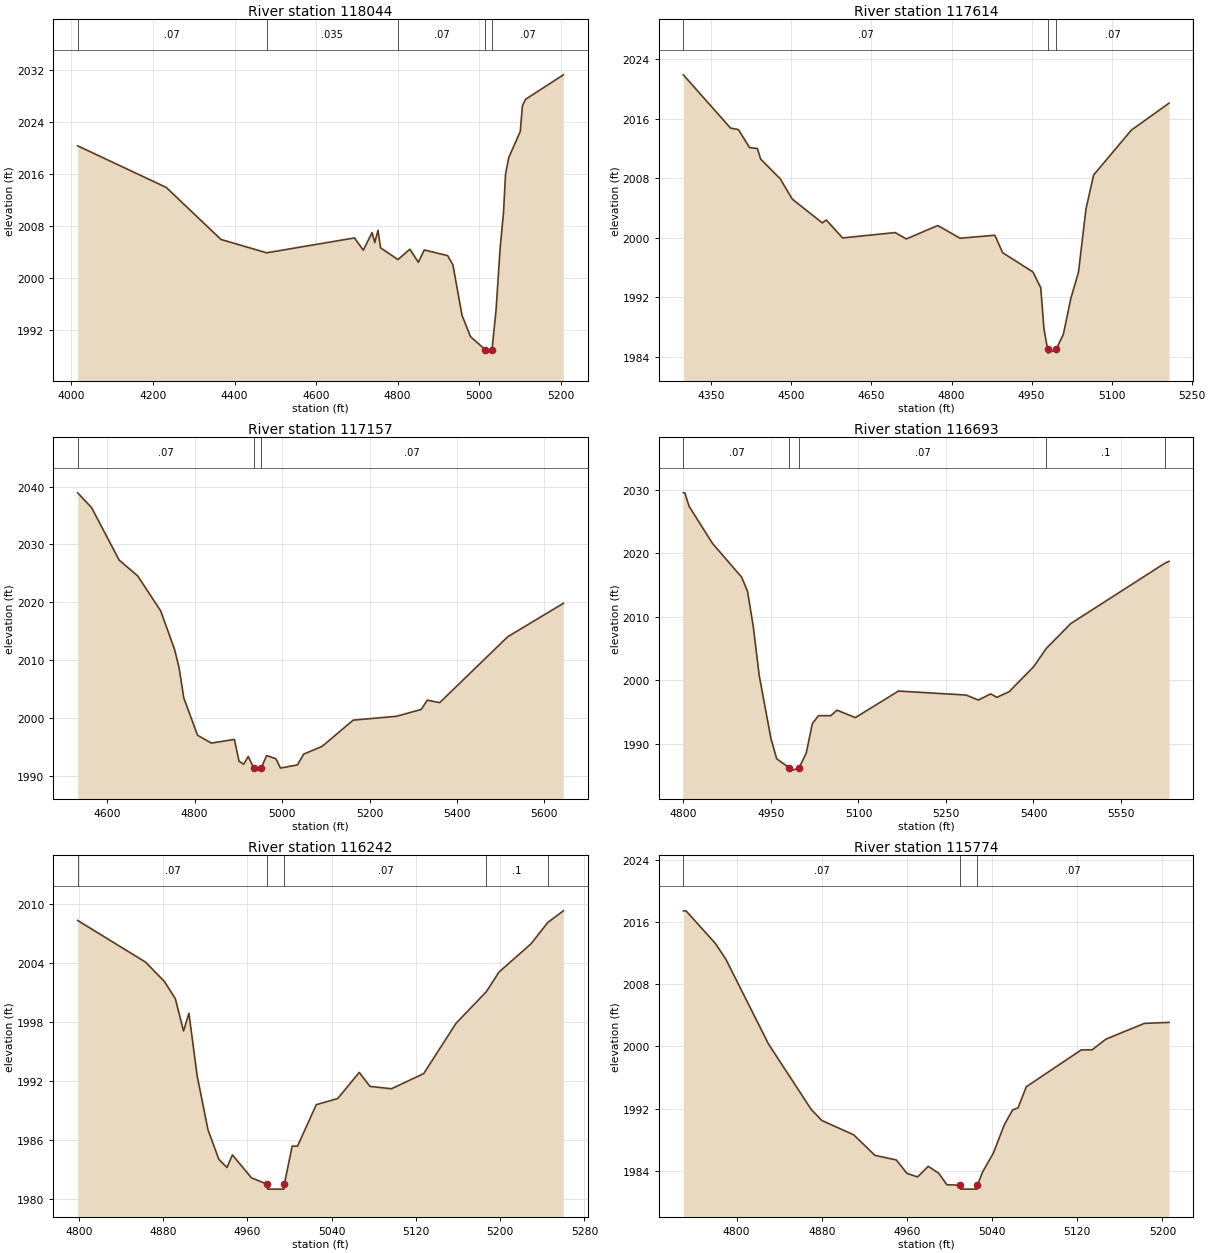
Type RM Length L Ch R = 1 ,118044  ,430,430,430
BEGIN DESCRIPTION:
Turtle Creek 203.0
END DESCRIPTION:
XS GIS Cut Line= 3
      1879751.33     13905936.63        1880375.       13905175.
      1880425.01     13904974.96
#Sta/Elev= 30
  4015.6 2020.28  4232.7 2013.88  4366.9 2005.87  4478.8 2003.82  4694.2 2006.11
  4715.7 2004.22  4737.3 2006.94  4743.8 2005.39  4751.7 2007.29  4758.1 2004.58
  4800.7 2002.78  4829.9 2004.37  4850.7 2002.36  4865.1 2004.26  4922.5 2003.38
  4935.4 2001.97  4957.7  1994.2  4978.5 1990.92  5015.2 1988.88  5015.7 1988.38
  5031.2 1988.88  5041.2 1995.05  5051.5 2004.83  5059.3 2009.89  5064.4 2015.93
  5072.2 2018.46  5100.5 2022.49  5105.7 2026.43  5113.4 2027.44  5206.2 2031.21
#Mann= 5 ,-1 , 0
  4015.6     .07       0  4478.8    .035       0  4800.7     .07       0
  5015.2     .05       0  5031.2     .07       0
Bank Sta=5015.2,5031.2
XS Rating Curve= 0 ,0
Exp/Cntr=0.3,0.1

Type RM Length L Ch R = 1 ,117614  ,457,457,457
BEGIN DESCRIPTION:
Turtle Creek 202.0
END DESCRIPTION:
XS GIS Cut Line= 3
      1880069.31     13906142.82        1880475.       13905575.
        1880625.       13905425.
#Sta/Elev= 30
  4297.5 2021.92  4385.9 2014.76  4400.6 2014.56  4421.5 2012.14  4436.2 2012.01
  4442.4 2010.59  4479.2 2007.92  4501.4 2005.22  4557.9 2002.01  4565.2  2002.4
  4595.9 1999.99  4694.3 2000.71  4715.2 1999.85  4774.1 2001.66  4815.9 1999.95
  4881.1 2000.35  4895.8    1998  4952.4 1995.42  4967.1  1993.3  4973.2 1987.75
    4980    1985  4980.5  1984.5    4996    1985  5009.5 1987.03  5023.6 1991.89
  5037.8 1995.37  5051.9  2003.9  5066.1 2008.44  5136.8 2014.48  5207.5 2018.11
#Mann= 3 ,-1 , 0
  4297.5     .07       0    4980     .05       0    4996     .07       0
Bank Sta=4980,4996
XS Rating Curve= 0 ,0
Exp/Cntr=0.3,0.1

Type RM Length L Ch R = 1 ,117157  ,464,464,464
BEGIN DESCRIPTION:
Turtle Creek 201.0
END DESCRIPTION:
XS GIS Cut Line= 3
      1880474.98     13906425.05        1880625.       13905975.
      1881075.01     13905524.99
#Sta/Elev= 30
  4532.6 2038.91  4564.3 2036.36  4627.5 2027.29  4669.7 2024.58  4722.4 2018.54
    4754 2011.91  4764.5 2008.73  4775.1 2003.55  4806.7 1997.07  4838.3 1995.72
    4891 1996.35  4901.6 1992.58  4912.1 1992.07  4922.7  1993.4  4935.6 1991.38
  4936.1 1990.88  4951.8 1991.38  4964.8 1993.57  4985.9 1993.02  4996.4 1991.41
  5035.3 1991.96  5049.4 1993.81  5091.8 1995.16  5162.6 1999.68  5261.5 2000.34
  5318.1 2001.52  5332.3 2003.13  5360.5  2002.7  5516.1 2014.07  5643.4 2019.84
#Mann= 3 ,-1 , 0
  4532.6     .07       0  4935.6     .05       0  4951.8     .07       0
Bank Sta=4935.6,4951.8
XS Rating Curve= 0 ,0
Exp/Cntr=0.3,0.1

Type RM Length L Ch R = 1 ,116693  ,451,451,451
BEGIN DESCRIPTION:
Turtle Creek 200.0
END DESCRIPTION:
XS GIS Cut Line= 3
        1880925.     13906375.02        1880925.       13906175.
      1881125.01     13905574.98
#Sta/Elev= 30
  4799.9 2029.51  4802.4 2029.51  4809.9 2027.36  4849.9 2021.54  4899.9 2016.22
  4909.9 2014.01  4919.9 2008.36  4929.9 2000.77  4949.9 1990.87  4959.9 1987.63
  4981.8 1986.19  4982.3 1985.69  4998.1 1986.19  5010.5 1988.52    5021 1993.16
  5031.5 1994.42  5052.6 1994.42  5063.2 1995.29  5094.8 1994.12  5168.6  1998.3
  5284.5 1997.67  5305.6 1996.89  5326.7 1997.85  5337.2 1997.31  5358.3 1998.19
  5400.5 2002.15    5422 2005.01  5463.7 2008.91  5624.9 2018.41  5632.4 2018.72
#Mann= 5 ,-1 , 0
  4799.9     .07       0  4981.8     .05       0  4998.1     .07       0
    5422      .1       0  5624.9     .07       0
Bank Sta=4981.8,4998.1
XS Rating Curve= 0 ,0
Exp/Cntr=0.3,0.1

Type RM Length L Ch R = 1 ,116242  ,468,468,468
BEGIN DESCRIPTION:
Turtle Creek 199.0
END DESCRIPTION:
XS GIS Cut Line= 3
      1881275.01     13906224.98        1881325.       13906025.
        1881375.     13905774.98
#Sta/Elev= 30
  4798.9 2008.32  4863.3 2004.09  4881.3 2002.11  4891.6 2000.37  4899.4 1997.09
  4904.5  1998.9  4912.3 1992.54  4922.6 1987.05  4932.9 1984.05  4940.6 1983.22
  4945.8  1984.5  4963.8 1982.17  4978.8 1981.52  4979.3 1981.02  4994.6 1981.02
  4995.1 1981.52  5002.5 1985.39  5007.6 1985.39  5025.4  1989.6  5045.8 1990.23
  5066.2 1992.88  5076.4 1991.46  5096.8 1991.22  5127.4 1992.76    5158 1997.86
  5186.9 2001.09  5198.8 2003.07  5229.4 2005.96  5245.2 2008.12    5260  2009.3
#Mann= 5 ,-1 , 0
  4798.9     .07       0  4978.8     .05       0  4995.1     .07       0
  5186.9      .1       0  5245.2     .07       0
Bank Sta=4978.8,4995.1
XS Rating Curve= 0 ,0
Exp/Cntr=0.3,0.1

Type RM Length L Ch R = 1 ,115774  ,469,469,469
BEGIN DESCRIPTION:
Turtle Creek 198.0
END DESCRIPTION:
XS GIS Cut Line= 3
        1881775.       13906225.        1881775.       13905975.
      1881724.99     13905774.95
#Sta/Elev= 30
    4750 2017.48  4752.5 2017.48    4780 2013.29    4790 2011.22    4830 2000.31
    4870  1991.9    4880 1990.46    4910 1988.61    4930 1985.96    4950 1985.37
    4960 1983.64    4970 1983.18    4980 1984.55    4990 1983.64  4997.5 1982.18
  5009.9 1982.11  5010.4 1981.61  5025.7 1981.61  5026.2 1982.11  5030.9 1983.77
  5041.2 1986.26  5051.5 1989.91  5059.3 1991.82  5064.4 1992.09  5072.1  1994.8
  5123.7 1999.55    5134 1999.57  5146.9 2000.94    5183 2002.97  5206.2  2003.1
#Mann= 3 ,-1 , 0
    4750     .07       0  5009.9     .05       0  5026.2     .07       0
Bank Sta=5009.9,5026.2
XS Rating Curve= 0 ,0
Exp/Cntr=0.3,0.1

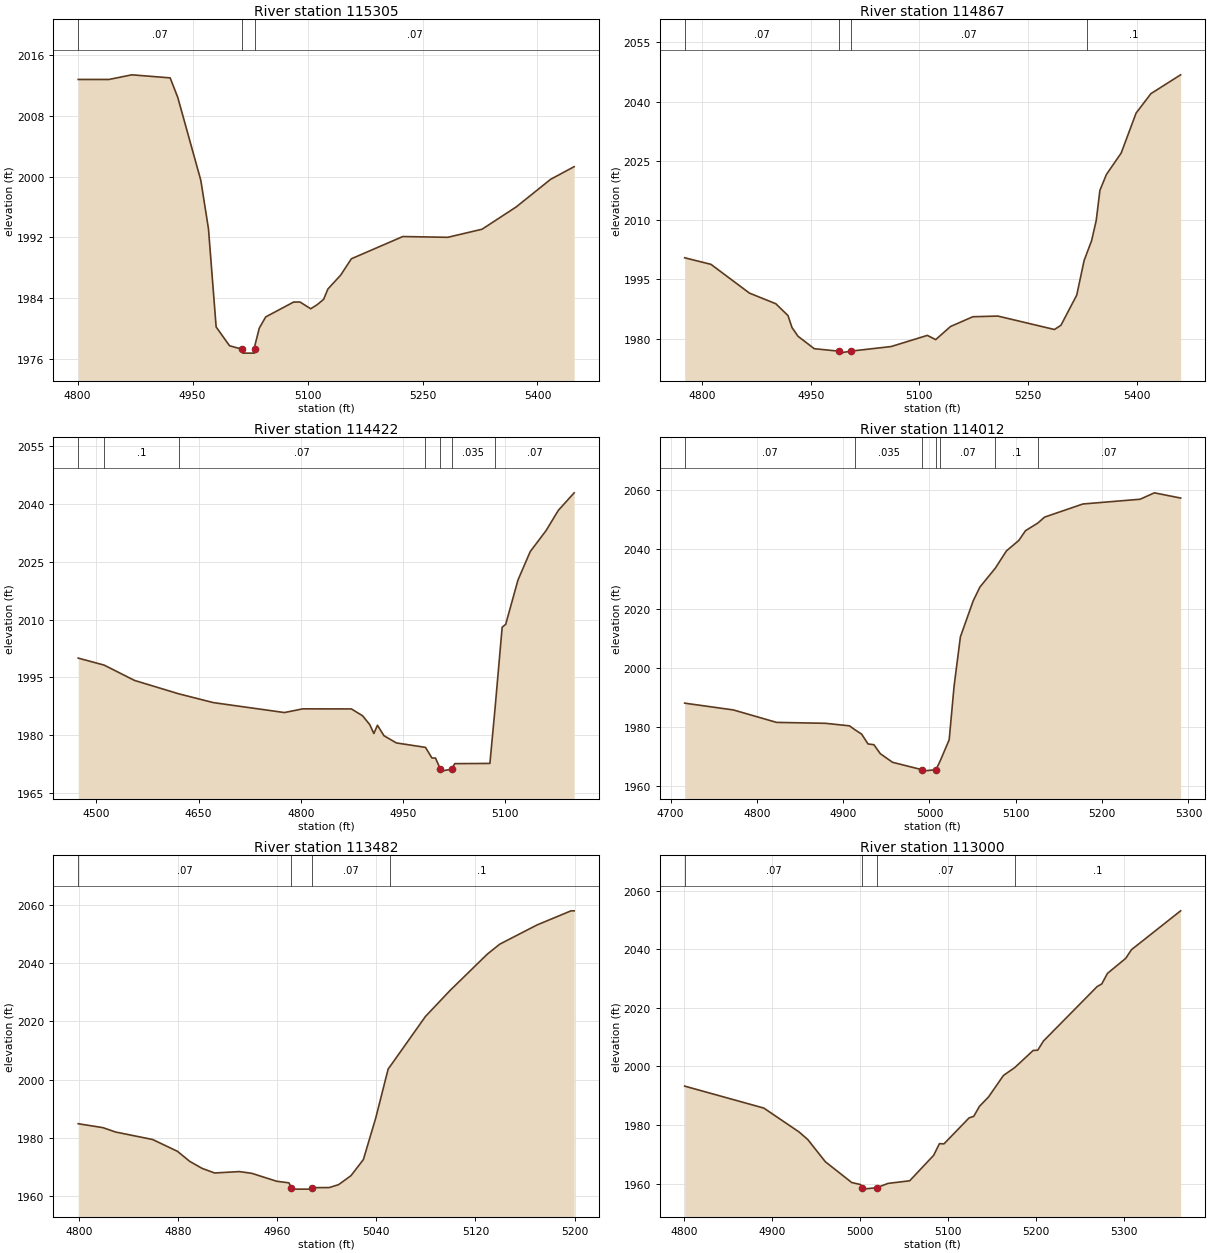
Type RM Length L Ch R = 1 ,115305  ,438,438,438
BEGIN DESCRIPTION:
Turtle Creek 197.0
END DESCRIPTION:
XS GIS Cut Line= 3
        1882225.       13906125.        1882225.       13905925.
      1881825.01       13905725.
#Sta/Elev= 30
  4800.7 2012.76  4840.7 2012.76  4870.7 2013.37  4920.7 2012.97  4930.7 2010.38
  4960.7 1999.51  4970.7 1993.13  4980.7 1980.24  4998.2 1977.77  5014.9  1977.3
  5015.4  1976.8  5030.7  1976.8  5031.2  1977.3  5031.4 1977.86    5037 1980.09
  5045.4 1981.56  5081.8 1983.51  5090.1 1983.52  5104.1 1982.63  5112.5 1983.16
  5120.9 1983.86  5126.5 1985.22  5143.2 1987.05  5157.2  1989.2  5224.3 1992.12
    5283 1992.02  5327.7 1993.08  5372.4 1996.02  5417.2 1999.64  5447.9  2001.3
#Mann= 3 ,-1 , 0
  4800.7     .07       0  5014.9     .05       0  5031.2     .07       0
Bank Sta=5014.9,5031.2
XS Rating Curve= 0 ,0
Exp/Cntr=0.3,0.1

Type RM Length L Ch R = 1 ,114867  ,445,445,445
BEGIN DESCRIPTION:
Turtle Creek 196.0
END DESCRIPTION:
XS GIS Cut Line= 3
        1882425.       13905725.        1882325.       13905525.
        1882225.     13905074.99
#Sta/Elev= 30
  4776.1 2000.47  4812.4 1998.81  4865.5 1991.53  4901.9 1988.84  4918.7 1985.85
  4924.2 1982.83  4932.6  1980.6    4955 1977.46  4988.7 1976.84  4989.2 1976.34
  5005.2 1976.84  5061.2 1978.01  5111.1 1980.83  5122.6 1979.76  5143.1 1983.08
  5173.9 1985.55  5208.4 1985.72  5286.5 1982.32  5295.5 1983.39  5317.3 1991.02
  5327.5 1999.78    5332 2001.97  5337.8 2004.79  5344.2 2009.89  5349.3 2017.54
  5358.2 2021.53  5378.7 2026.99  5399.2 2037.08  5419.7 2042.01  5460.7 2046.77
#Mann= 4 ,-1 , 0
  4776.1     .07       0  4988.7     .05       0  5005.2     .07       0
    5332      .1       0
Bank Sta=4988.7,5005.2
XS Rating Curve= 0 ,0
Exp/Cntr=0.3,0.1

Type RM Length L Ch R = 1 ,114422  ,410,410,410
BEGIN DESCRIPTION:
Turtle Creek 195.0
END DESCRIPTION:
XS GIS Cut Line= 3
        1882475.       13905725.        1882625.       13905225.
      1882574.99     13905024.97
#Sta/Elev= 30
  4473.3 1999.99  4511.3 1998.18    4556  1994.2  4620.9 1990.73  4671.7 1988.45
  4776.1 1985.87    4803 1986.83  4874.4 1986.81  4890.9 1985.03  4901.4 1982.74
  4907.4 1980.43  4912.7 1982.58  4922.2 1979.87  4940.5 1977.99  4983.2 1976.84
  4992.7 1974.08  4997.9 1974.08  5005.1 1971.18  5005.6 1970.68  5021.6 1971.18
  5026.2 1972.62  5077.8 1972.68  5085.3 1986.84  5095.8 2008.01    5101 2008.75
    5119 2020.23    5137 2027.61  5160.2 2033.04  5178.3 2038.31  5201.5 2042.85
#Mann= 7 ,-1 , 0
  4473.3     .07       0  4511.3      .1       0  4620.9     .07       0
  4983.2    .035       0  5005.1    .035       0  5021.6    .035       0
  5085.3     .07       0
Bank Sta=5005.1,5021.6
XS Rating Curve= 0 ,0
Exp/Cntr=0.3,0.1

Type RM Length L Ch R = 1 ,114012  ,530,530,530
BEGIN DESCRIPTION:
Turtle Creek 194.0
END DESCRIPTION:
XS GIS Cut Line= 3
      1882724.97     13905575.03      1882936.46     13905380.62
       1883191.4      13905248.3
#Sta/Elev= 30
  4716.4 1987.97  4772.9 1985.67  4822.8 1981.46  4879.4 1981.15  4907.3 1980.29
    4914 1978.89  4921.4 1977.49  4928.8 1974.16  4935.6 1973.91    4943 1970.87
  4957.2 1967.95    4991 1965.46  4991.5 1964.96  5007.5 1965.46  5012.3 1968.36
  5022.8 1975.57  5028.5 1993.77  5035.8 2010.42  5050.6 2022.59  5058.4 2027.27
  5076.3 2033.69  5089.2 2039.54  5103.4 2043.03  5111.3 2046.38  5125.3  2048.9
  5133.4 2050.96  5177.7 2055.39    5244    2057  5260.5 2059.17  5290.9  2057.4
#Mann= 7 ,-1 , 0
  4716.4     .07       0    4914    .035       0    4991    .035       0
  5007.5    .035       0  5012.3     .07       0  5076.3      .1       0
  5125.3     .07       0
Bank Sta=4991,5007.5
XS Rating Curve= 0 ,0
Exp/Cntr=0.3,0.1

Type RM Length L Ch R = 1 ,113482  ,482,482,482
BEGIN DESCRIPTION:
Turtle Creek 193.0
END DESCRIPTION:
XS GIS Cut Line= 3
      1882774.99       13905875.        1882975.       13905875.
      1883174.99       13905875.
#Sta/Elev= 30
  4799.6 1984.84  4819.6 1983.48  4829.6    1982  4859.6 1979.41  4879.6 1975.36
  4889.6 1971.88  4899.6 1969.47  4909.6  1967.9  4929.6 1968.38  4939.6 1967.78
  4959.6 1965.07  4969.6  1964.5  4971.4 1962.85  4971.9 1962.35  4987.4 1962.35
  4987.9 1962.85  5002.1 1962.89  5009.6 1963.89  5019.6 1966.98  5029.6 1972.52
  5039.6 1986.85  5049.6 2003.67  5051.3 2004.64  5079.6 2021.68  5099.6 2030.69
  5129.6 2043.16  5139.6 2046.57  5169.6 2053.16  5197.1 2058.03  5199.6 2058.03
#Mann= 4 ,-1 , 0
  4799.6     .07       0  4971.4     .05       0  4987.9     .07       0
  5051.3      .1       0
Bank Sta=4971.4,4987.9
XS Rating Curve= 0 ,0
Exp/Cntr=0.3,0.1

Type RM Length L Ch R = 1 ,113000  ,483,483,483
BEGIN DESCRIPTION:
Turtle Creek 192.0
END DESCRIPTION:
XS GIS Cut Line= 3
      1882674.99       13906325.        1882875.       13906325.
      1883224.99       13906225.
#Sta/Elev= 30
  4800.4  1993.3  4890.4 1985.81  4930.4 1977.68  4940.4 1975.07  4960.4 1967.49
  4990.4  1960.4  5000.4 1959.72  5002.5 1958.65    5003 1958.15  5019.1 1958.65
  5031.6  1960.1  5056.3    1961  5083.6 1969.71  5090.1 1973.66  5095.3  1973.6
  5123.9 1982.48  5129.1 1982.98  5135.6 1986.39    5146 1989.62  5162.9 1996.94
  5175.9 1999.66  5196.7 2005.47  5201.9 2005.56  5208.4 2008.69  5269.5 2027.28
  5274.7 2028.17  5281.2 2031.77    5302 2036.91  5308.5 2039.86  5364.4 2053.12
#Mann= 4 ,-1 , 0
  4800.4     .07       0  5002.5     .05       0  5019.1     .07       0
  5175.9      .1       0
Bank Sta=5002.5,5019.1
XS Rating Curve= 0 ,0
Exp/Cntr=0.3,0.1

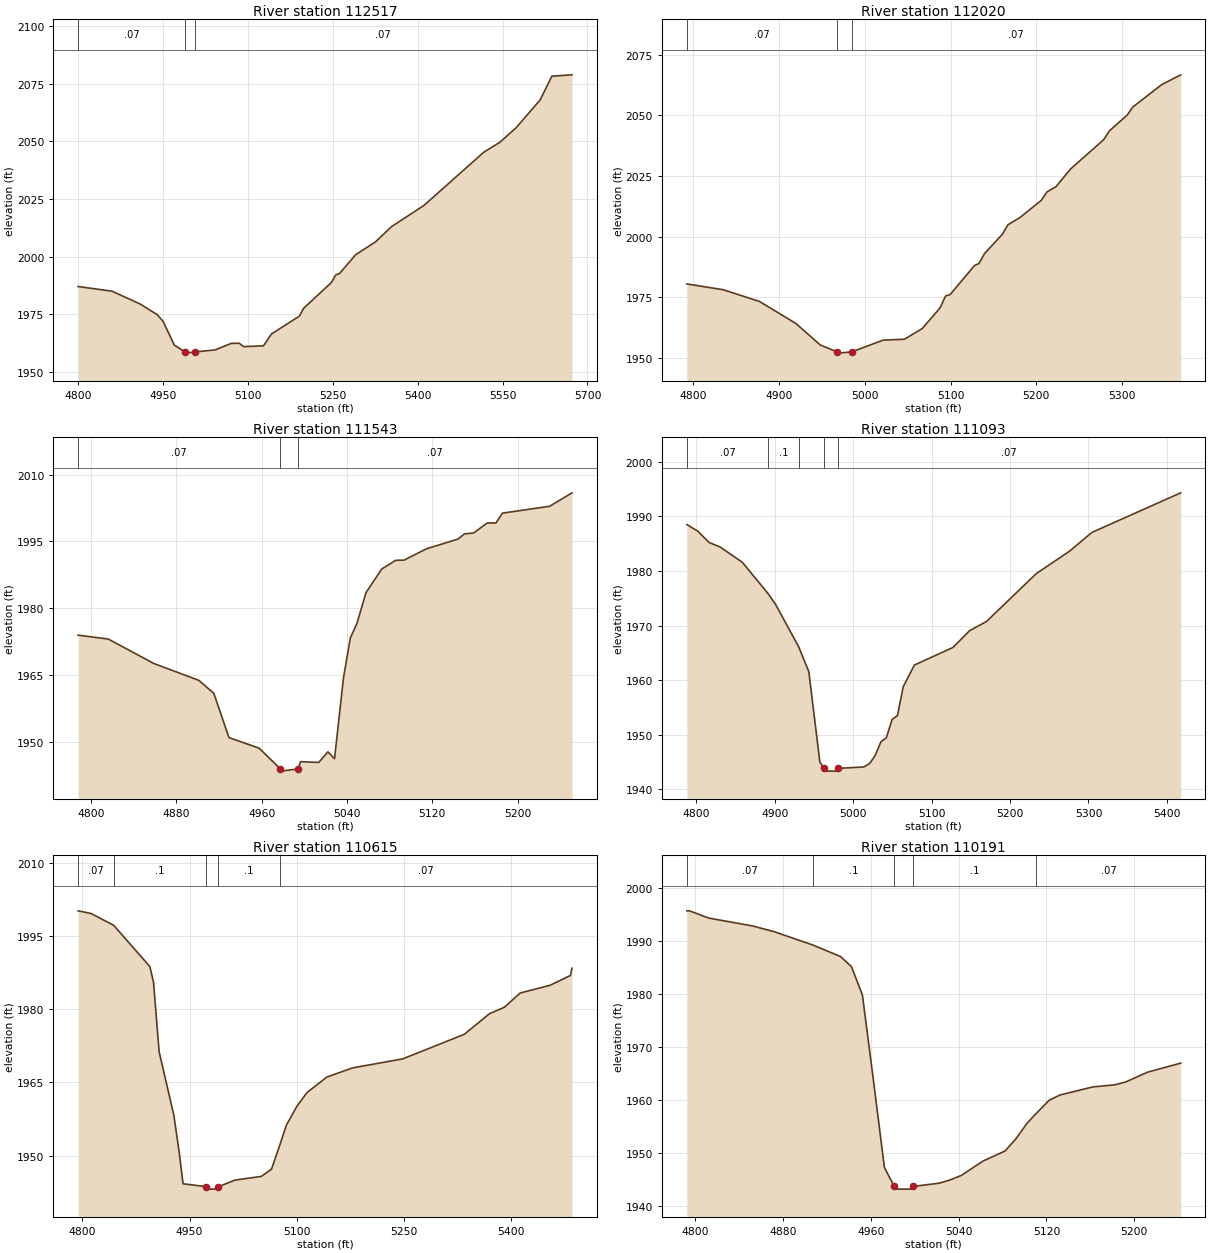
Type RM Length L Ch R = 1 ,112517  ,497,497,497
BEGIN DESCRIPTION:
Turtle Creek 191.0
END DESCRIPTION:
XS GIS Cut Line= 3
      1882674.98       13906775.        1882875.       13906775.
        1883375.       13907225.
#Sta/Elev= 30
    4800    1987    4860 1984.95    4910 1979.35    4940 1974.73    4950 1971.92
    4970 1961.55  4989.2 1958.56  4989.7 1958.06  5005.8 1958.56  5042.2 1959.46
  5070.6  1962.3  5084.8 1962.34  5092.3  1960.9  5127.5 1961.22  5141.7 1966.39
    5191 1974.13  5198.5 1977.53  5247.8  1988.8  5255.3 1992.04    5262 1992.64
  5290.4  2000.8  5325.5 2006.38  5353.9 2013.01  5410.7 2022.12  5516.9 2045.33
  5545.3 2049.65  5573.7 2055.87  5616.3 2067.97  5637.2 2078.33  5672.7 2078.92
#Mann= 3 ,-1 , 0
    4800     .07       0  4989.2     .05       0  5005.8     .07       0
Bank Sta=4989.2,5005.8
XS Rating Curve= 0 ,0
Exp/Cntr=0.3,0.1

Type RM Length L Ch R = 1 ,112020  ,477,477,477
BEGIN DESCRIPTION:
Turtle Creek 190.0
END DESCRIPTION:
XS GIS Cut Line= 3
        1882725.       13907125.        1882875.       13907275.
      1883224.96     13907374.99
#Sta/Elev= 30
  4792.4 1980.48  4834.8 1978.09  4877.3 1973.22  4919.7 1964.14    4948 1955.29
  4967.9 1952.42  4968.4 1951.92  4984.6 1952.42  5021.4 1957.29  5046.1 1957.65
  5066.9 1962.03  5087.7 1970.56  5094.2 1975.51  5099.4 1976.05    5128 1988.07
  5133.2 1988.94  5139.7 1993.03  5160.5    2001    5167 2004.91  5181.3 2007.95
    5206 2015.02  5212.5 2018.46  5222.9  2020.6  5239.8 2027.84  5278.8 2040.07
  5285.3 2043.63  5306.1 2050.19  5312.6 2053.49  5346.4 2062.76  5368.5 2066.78
#Mann= 3 ,-1 , 0
  4792.4     .07       0  4967.9     .05       0  4984.6     .07       0
Bank Sta=4967.9,4984.6
XS Rating Curve= 0 ,0
Exp/Cntr=0.3,0.1

Type RM Length L Ch R = 1 ,111543  ,450,450,450
BEGIN DESCRIPTION:
Turtle Creek 189.0
END DESCRIPTION:
XS GIS Cut Line= 3
      1882424.97     13907424.97        1882575.       13907575.
      1882720.02     13907779.89
#Sta/Elev= 30
  4787.8 1973.98  4816.1 1973.11  4858.6 1967.65    4901 1963.85  4915.1 1960.92
  4929.3    1951  4957.6 1948.63  4977.5 1943.98    4978 1943.48  4994.2 1943.98
  4996.4  1945.6  5013.5 1945.43  5022.1 1947.81  5028.3 1946.27  5036.7 1964.44
  5043.1 1973.34  5049.2 1976.54  5057.8 1983.52  5072.6 1988.83  5085.7 1990.77
  5093.5 1990.82  5114.4 1993.34    5144 1995.53  5150.1  1996.7  5158.8 1996.91
  5171.5 1999.15  5179.7 1999.15  5185.8 2001.35  5230.1  2002.9    5251 2005.91
#Mann= 3 ,-1 , 0
  4787.8     .07       0  4977.5     .05       0  4994.2     .07       0
Bank Sta=4977.5,4994.2
XS Rating Curve= 0 ,0
Exp/Cntr=0.3,0.1

Type RM Length L Ch R = 1 ,111093  ,478,478,478
BEGIN DESCRIPTION:
Turtle Creek 188.0
END DESCRIPTION:
XS GIS Cut Line= 3
        1882025.       13907575.        1882175.       13907725.
      1882455.88     13908034.26
#Sta/Elev= 30
  4787.8 1988.52  4801.9 1987.29  4816.1 1985.23  4830.2  1984.4  4858.5 1981.61
  4891.2 1975.89  4900.9  1973.9  4930.4 1966.11  4943.4 1961.53  4957.5 1944.93
  4963.2  1943.8  4963.7  1943.3  4979.5  1943.3    4980  1943.8  5013.8 1944.07
  5021.2 1944.74    5028 1946.17  5035.4  1948.7  5042.2  1949.4  5049.6 1952.78
  5056.4 1953.48  5063.8 1958.77    5078 1962.75  5127.3 1965.98  5148.5 1969.06
  5169.9 1970.73  5233.4 1979.51    5276 1983.64  5304.4 1987.07  5417.7 1994.33
#Mann= 5 ,-1 , 0
  4787.8     .07       0  4891.2      .1       0  4930.4     .07       0
  4963.2     .05       0    4980     .07       0
Bank Sta=4963.2,4980
XS Rating Curve= 0 ,0
Exp/Cntr=0.3,0.1

Type RM Length L Ch R = 1 ,110615  ,424,424,424
BEGIN DESCRIPTION:
Turtle Creek 187.0
END DESCRIPTION:
XS GIS Cut Line= 3
      1881775.01     13907775.03        1881825.       13907975.
      1882200.78     13908282.06
#Sta/Elev= 30
  4793.9 2000.14  4811.9  1999.6  4843.7 1997.18  4894.4 1988.72  4899.5 1985.48
  4907.3 1971.29  4927.9 1958.32  4935.6 1950.51  4940.8 1944.26  4973.6 1943.66
  4974.1 1943.16  4989.9 1943.16  4990.4 1943.66  5013.7 1945.02  5050.3 1945.76
  5064.6 1947.24  5076.3 1952.21  5085.5 1956.26  5099.8 1960.03  5114.2 1962.92
  5142.1 1966.11  5178.1 1967.98  5248.4 1969.83  5334.6 1974.86  5369.7 1979.07
  5390.6 1980.39  5412.8 1983.32  5454.5 1984.89  5483.2 1986.91  5485.3 1988.38
#Mann= 5 ,-1 , 0
  4793.9     .07       0  4843.7      .1       0  4973.6     .05       0
  4990.4      .1       0  5076.3     .07       0
Bank Sta=4973.6,4990.4
XS Rating Curve= 0 ,0
Exp/Cntr=0.3,0.1

Type RM Length L Ch R = 1 ,110191  ,155,155,155
BEGIN DESCRIPTION:
Turtle Creek 186.0
END DESCRIPTION:
XS GIS Cut Line= 3
      1881424.96       13908325.        1881625.       13908325.
      1881874.96       13908325.
#Sta/Elev= 30
  4792.4 1995.61  4794.9 1995.61  4812.4 1994.24  4852.4 1992.76  4872.4 1991.65
  4907.5 1989.14  4932.4    1987  4942.4 1985.08  4952.4 1979.72  4962.4 1963.68
  4972.4 1947.24  4981.4 1943.65  4981.9 1943.15  4997.9 1943.15  4998.4 1943.65
  5022.4 1944.27  5032.4 1944.89  5042.4 1945.72  5062.4 1948.46  5082.4 1950.34
  5092.4 1952.68  5102.4 1955.58  5110.9 1957.45  5122.4 1959.88  5132.4  1960.9
  5162.4 1962.42  5182.4 1962.81  5192.4 1963.36  5212.4 1965.21  5242.4  1966.9
#Mann= 5 ,-1 , 0
  4792.4     .07       0  4907.5      .1       0  4981.4     .05       0
  4998.4      .1       0  5110.9     .07       0
Bank Sta=4981.4,4998.4
XS Rating Curve= 0 ,0
Exp/Cntr=0.3,0.1

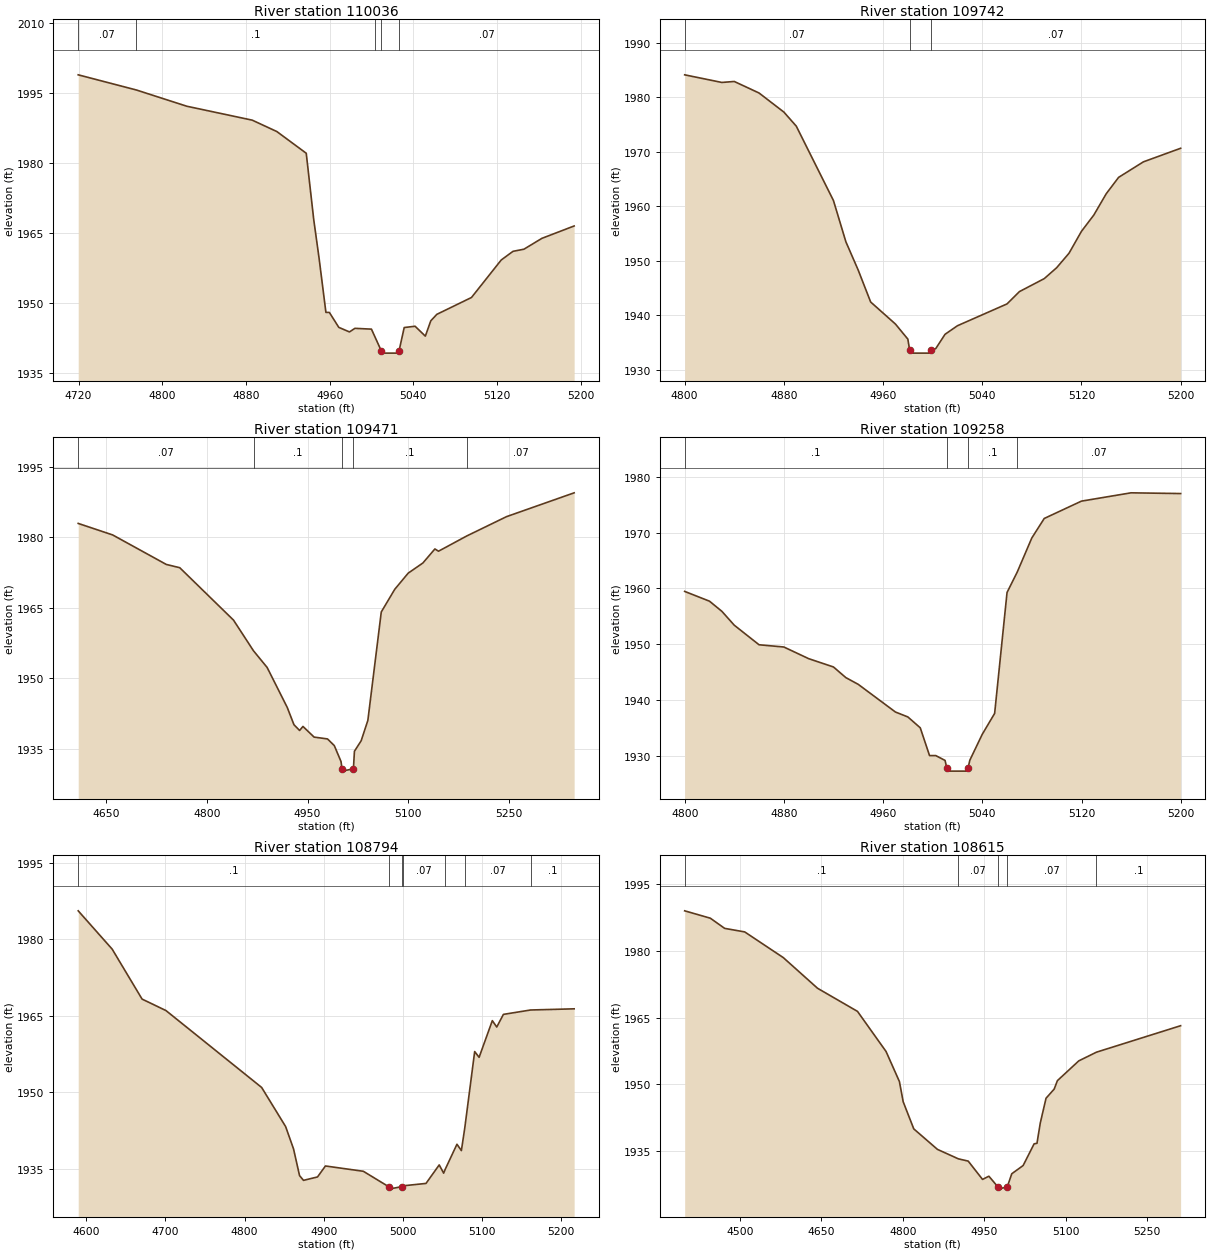
Type RM Length L Ch R = 1 ,110036  ,294,294,294
BEGIN DESCRIPTION:
Turtle Creek 188.1
END DESCRIPTION:
XS GIS Cut Line= 3
      1881404.15     13908537.47      1881636.36     13908476.71
      1881861.07     13908411.89
#Sta/Elev= 30
  4719.7 1998.98  4775.3 1995.73  4823.5 1992.25    4886 1989.27  4909.5 1986.83
  4937.6 1982.18  4944.8 1967.89  4949.9 1959.64  4956.4 1948.08  4959.7 1948.08
  4968.7 1944.88  4978.9  1943.9  4984.1 1944.67  4999.9  1944.5  5003.6 1942.67
  5009.3 1939.86  5009.8 1939.36  5025.8 1939.36  5026.3 1939.86  5031.2 1944.84
  5041.6 1945.12  5051.4    1943  5056.6 1946.28  5062.4 1947.67  5095.5 1951.28
  5123.9 1959.31  5135.2 1961.17  5145.6 1961.62  5162.8 1963.95  5193.6  1966.6
#Mann= 5 ,-1 , 0
  4719.7     .07       0  4775.3      .1       0  5003.6     .07       0
  5009.3     .05       0  5026.3     .07       0
Bank Sta=5009.3,5026.3
XS Rating Curve= 0 ,0
Exp/Cntr=0.3,0.1

Type RM Length L Ch R = 1 ,109742  ,271,271,271
BEGIN DESCRIPTION:
Turtle Creek 185.0
END DESCRIPTION:
XS GIS Cut Line= 3
      1881574.98       13908725.        1881775.       13908725.
      1881974.98       13908725.
#Sta/Elev= 30
    4800 1984.14    4830 1982.74    4840 1982.92    4860  1980.8    4880  1977.3
    4890 1974.72    4920 1961.05    4930 1953.49    4940 1948.26    4950 1942.42
    4970 1938.37    4980  1935.6  4981.5 1933.53    4982 1933.03    4998 1933.03
  4998.5 1933.53  5002.5 1933.86    5010 1936.49    5020 1938.06    5060 1942.07
    5070 1944.33    5090 1946.71    5100 1948.71    5110 1951.38    5120 1955.39
    5130 1958.39    5140  1962.3    5150 1965.31    5170 1968.16    5200 1970.65
#Mann= 3 ,-1 , 0
    4800     .07       0  4981.5     .05       0  4998.5     .07       0
Bank Sta=4981.5,4998.5
XS Rating Curve= 0 ,0
Exp/Cntr=0.3,0.1

Type RM Length L Ch R = 1 ,109471  ,213,213,213
BEGIN DESCRIPTION:
Mapping XS c075967f
END DESCRIPTION:
XS GIS Cut Line= 3
      1881483.84     13908944.82      1881996.94     13908968.21
       1882205.4     13908882.58
#Sta/Elev= 30
  4608.3 1982.89  4659.5 1980.45  4739.6 1974.16  4759.6 1973.47  4839.7 1962.32
  4869.5 1955.79  4889.8 1952.25  4919.8 1943.74  4929.8 1940.06  4938.2 1938.84
  4943.2  1939.7  4959.8 1937.43  4979.8 1937.04  4989.9 1935.62  4999.9 1932.24
  5001.4 1930.69  5001.9 1930.19  5018.4 1930.69  5019.9 1934.42  5029.9 1936.64
  5039.9 1940.98  5059.9 1964.05    5080 1968.88    5100 1972.31  5121.9 1974.47
  5139.8 1977.46  5145.2 1976.98  5187.4 1980.23  5246.5 1984.33  5347.3  1989.4
#Mann= 5 ,-1 , 0
  4608.3     .07       0  4869.5      .1       0  5001.4     .05       0
  5018.4      .1       0  5187.4     .07       0
Bank Sta=5001.4,5018.4
XS Rating Curve= 0 ,0
Exp/Cntr=0.3,0.1

Type RM Length L Ch R = 1 ,109258  ,464,464,464
BEGIN DESCRIPTION:
Turtle Creek 184.0
END DESCRIPTION:
XS GIS Cut Line= 3
      1881674.98       13909175.        1881875.       13909175.
      1882074.98       13909175.
#Sta/Elev= 30
  4799.9 1959.46  4819.9 1957.71  4829.9 1955.89  4839.9  1953.4  4859.9 1949.89
  4879.9 1949.49  4899.9  1947.4  4919.9 1945.91  4929.9    1944  4939.9 1942.79
  4969.9 1937.83  4979.9 1936.95  4989.9    1935  4997.4 1930.02  5002.4 1930.02
  5009.9 1929.15  5011.4 1927.73  5011.9 1927.23  5027.9 1927.23  5028.4 1927.73
  5029.9 1929.19  5039.9 1933.83  5049.9 1937.58  5059.9 1959.26  5068.2 1962.97
  5079.9 1969.05  5089.9 1972.54  5119.9 1975.65  5159.9 1977.14  5199.9 1977.01
#Mann= 4 ,-1 , 0
  4799.9      .1       0  5011.4     .05       0  5028.4      .1       0
  5068.2     .07       0
Bank Sta=5011.4,5028.4
XS Rating Curve= 0 ,0
Exp/Cntr=0.3,0.1

Type RM Length L Ch R = 1 ,108794  ,179,179,179
BEGIN DESCRIPTION:
Turtle Creek 183.0
END DESCRIPTION:
XS GIS Cut Line= 3
      1881274.97       13909525.        1881675.       13909575.
      1881874.96     13909475.02
#Sta/Elev= 30
  4589.7  1985.6  4632.6 1978.09  4670.4 1968.29  4700.6 1966.04  4821.5 1950.96
  4851.8 1943.29  4861.8 1938.91  4869.4 1933.67  4874.4 1932.74  4892.1 1933.41
  4902.1 1935.56    4950 1934.52  4981.8 1931.52  4982.3 1931.02  4998.9 1931.52
  5000.3 1931.67  5029.2 1932.14  5045.9 1935.77  5051.5 1934.15  5053.4 1934.88
  5068.3 1939.82  5073.9 1938.58  5078.2 1943.03  5090.7    1958  5096.3 1956.87
    5113 1964.06  5118.6 1962.81    5127 1965.29  5161.3 1966.15  5216.4 1966.38
#Mann= 7 ,-1 , 0
  4589.7      .1       0  4981.8     .05       0  4998.9      .1       0
  5000.3     .07       0  5053.4      .1       0  5078.2     .07       0
  5161.3      .1       0
Bank Sta=4981.8,4998.9
XS Rating Curve= 0 ,0
Exp/Cntr=0.3,0.1

Type RM Length L Ch R = 1 ,108615  ,247,247,247
BEGIN DESCRIPTION:
Mapping XS 9d1d9de4
END DESCRIPTION:
XS GIS Cut Line= 3
      1881052.43     13909923.98      1881722.78     13909701.96
      1881869.17     13909553.58
#Sta/Elev= 30
  4397.7 1989.05    4445 1987.39  4471.4  1985.1  4508.4  1984.3  4579.5 1978.52
  4642.7 1971.61  4716.4  1966.4  4769.1 1957.36  4793.7  1950.6  4800.7 1946.03
  4820.2 1939.93  4863.9 1935.31  4902.3 1933.19  4920.6 1932.67    4947 1928.55
  4958.7 1929.27  4975.4 1926.86  4975.9 1926.36  4992.6 1926.86  5000.9 1929.82
  5021.9 1931.68  5042.1 1936.56  5047.4 1936.68  5053.5 1941.25  5064.1 1946.83
  5079.1 1948.89  5085.1  1950.8  5124.5 1955.25  5157.1 1957.21  5312.3 1963.17
#Mann= 5 ,-1 , 0
  4397.7      .1       0  4902.3     .07       0  4975.4     .05       0
  4992.6     .07       0  5157.1      .1       0
Bank Sta=4975.4,4992.6
XS Rating Curve= 0 ,0
Exp/Cntr=0.3,0.1