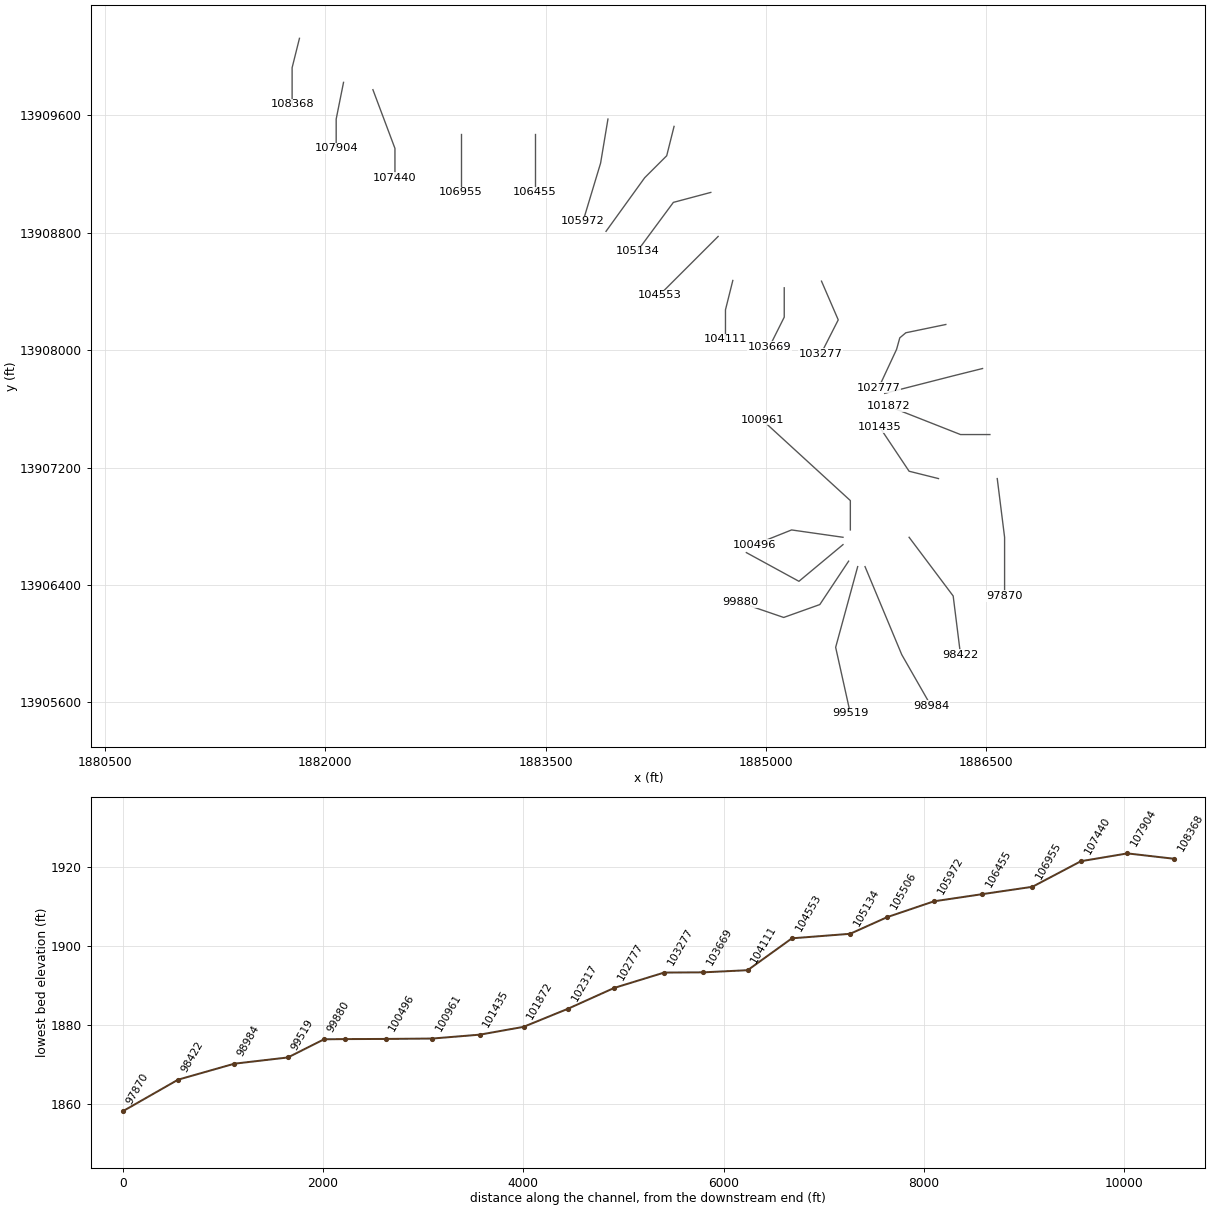
HEC-RAS study Turtle Creek.prj: Turtle Creek Base Level Engineering

--- Turtle Creek.g01 (geometry) --- (continued)

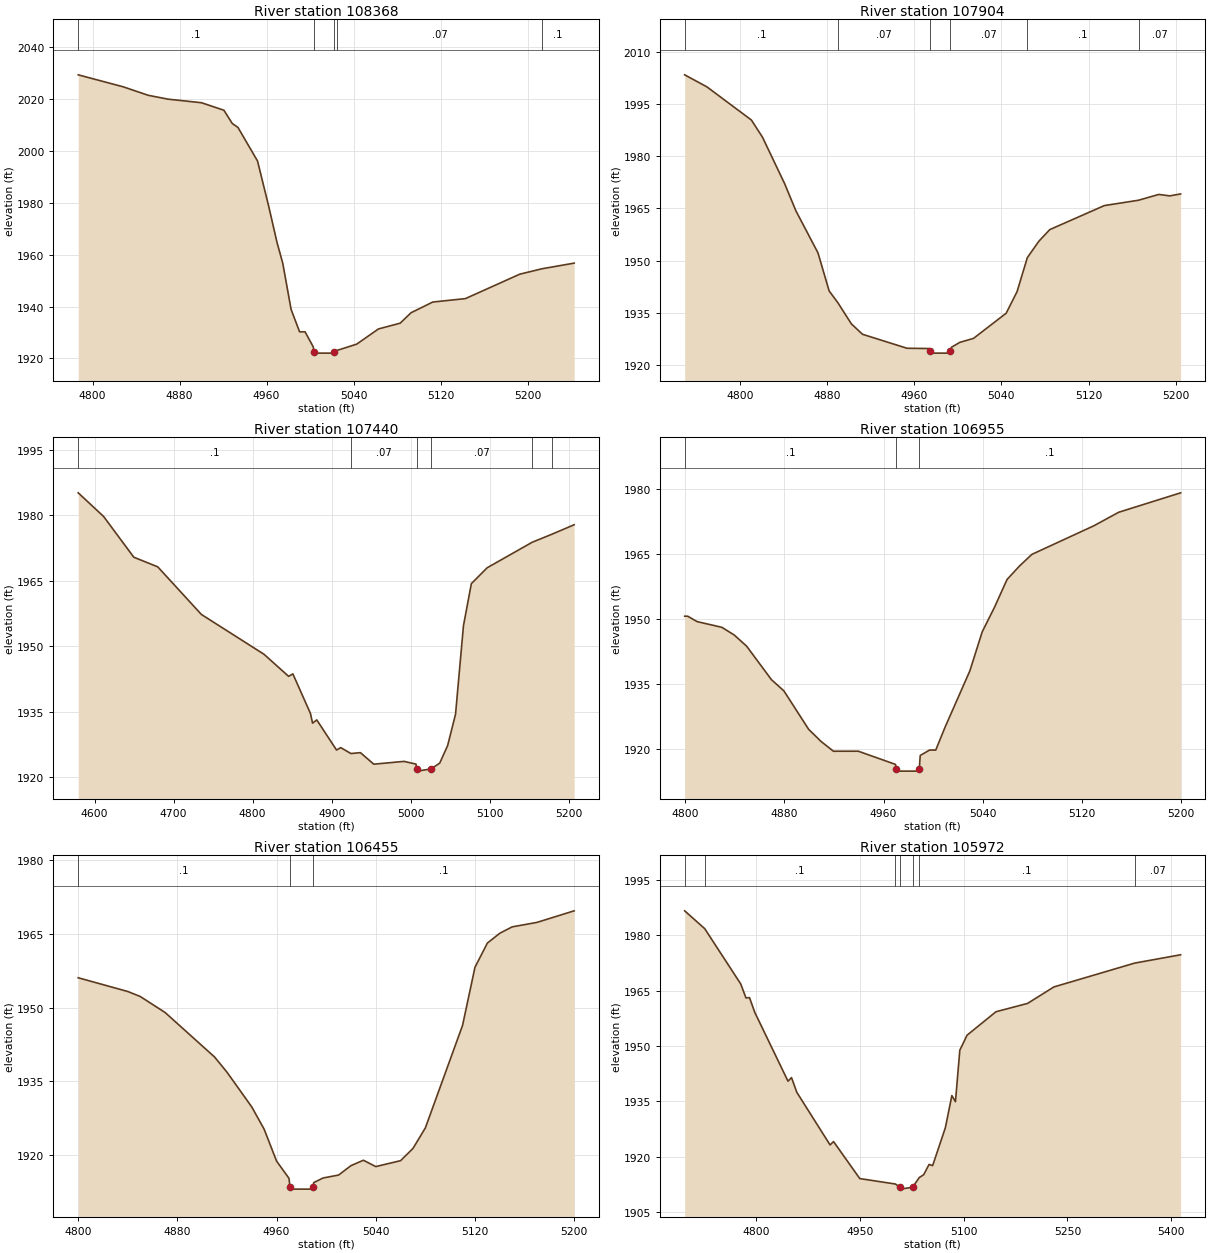
Type RM Length L Ch R = 1 ,108368  ,464,464,464
BEGIN DESCRIPTION:
Turtle Creek 182.0
END DESCRIPTION:
XS GIS Cut Line= 3
      1881824.99     13910124.97        1881775.       13909925.
        1881775.     13909675.03
#Sta/Elev= 30
  4786.8 2029.37    4828 2024.77  4851.2 2021.48  4869.2    2020  4900.2 2018.61
  4920.8 2015.72  4928.5  2010.6  4933.7  2009.1  4951.7 1996.16    4962 1978.68
  4969.7 1964.64  4974.9 1956.77  4982.6  1938.9  4990.4 1930.29  4995.4 1930.29
  5002.9 1924.54  5003.8 1922.57  5004.3 1922.07  5021.5 1922.07    5022 1922.57
  5025.2 1923.16  5042.9 1925.53  5062.9 1931.39  5082.9 1933.62  5092.9 1937.64
  5112.9 1941.77  5142.9 1943.09  5192.9 1952.51  5213.3 1954.59  5242.9 1956.77
#Mann= 5 ,-1 , 0
  4786.8      .1       0  5003.8     .05       0    5022      .1       0
  5025.2     .07       0  5213.3      .1       0
Bank Sta=5003.8,5022
XS Rating Curve= 0 ,0
Exp/Cntr=0.3,0.1

Type RM Length L Ch R = 1 ,107904  ,464,464,464
BEGIN DESCRIPTION:
Turtle Creek 181.0
END DESCRIPTION:
XS GIS Cut Line= 3
      1882124.99     13909824.97        1882075.       13909575.
        1882075.     13909375.02
#Sta/Elev= 30
  4749.5  2003.4  4769.9 1999.94  4810.7 1990.41  4820.9 1985.46  4841.3 1972.05
  4851.5 1964.33  4871.8 1952.22    4882  1941.3    4890 1937.92  4902.4 1931.83
  4912.6 1928.84  4953.4 1924.82  4973.8 1924.74  4974.9 1923.92  4975.4 1923.42
  4992.6 1923.42  4993.1 1923.92  4994.2 1925.11  5001.9 1926.52  5014.4 1927.65
  5044.4 1934.89  5054.4 1941.11  5063.8 1950.86  5074.4 1955.59  5084.4 1958.92
  5134.4 1965.82  5165.8 1967.36  5184.4 1969.03  5194.4 1968.61  5204.4 1969.17
#Mann= 6 ,-1 , 0
  4749.5      .1       0    4890     .07       0  4974.9     .05       0
  4993.1     .07       0  5063.8      .1       0  5165.8     .07       0
Bank Sta=4974.9,4993.1
XS Rating Curve= 0 ,0
Exp/Cntr=0.3,0.1

Type RM Length L Ch R = 1 ,107440  ,485,485,485
BEGIN DESCRIPTION:
Turtle Creek 180.0
END DESCRIPTION:
XS GIS Cut Line= 3
      1882324.99     13909775.02        1882475.       13909375.
        1882475.     13909175.03
#Sta/Elev= 30
  4579.4 1985.17  4611.5 1979.76  4649.7 1970.43    4680 1968.22  4735.2 1957.32
  4814.4  1948.2  4845.5 1943.15  4850.9 1943.71  4873.1 1934.66  4875.8 1932.43
  4881.1 1933.18  4906.1 1926.28  4911.4 1926.83  4924.3 1925.48  4936.3 1925.68
  4953.2 1923.04  4991.5 1923.68  5006.6 1923.06  5007.5 1921.95    5008 1921.45
  5025.7 1921.95  5036.6 1923.29  5046.6  1927.3  5056.6 1934.49  5066.6 1954.73
  5076.6 1964.38  5096.6 1968.01  5153.5 1973.85  5178.2 1975.67  5206.6 1977.86
#Mann= 6 ,-1 , 0
  4579.4      .1       0  4924.3     .07       0  5007.5     .05       0
  5025.7     .07       0  5153.5      .1       0  5178.2     .07       0
Bank Sta=5007.5,5025.7
XS Rating Curve= 0 ,0
Exp/Cntr=0.3,0.1

Type RM Length L Ch R = 1 ,106955  ,500,500,500
BEGIN DESCRIPTION:
Turtle Creek 179.0
END DESCRIPTION:
XS GIS Cut Line= 3
        1882925.     13909475.02        1882925.       13909275.
        1882925.     13909075.02
#Sta/Elev= 30
  4799.6 1950.73  4802.1 1950.73  4809.6 1949.49  4829.6 1948.17  4839.6 1946.39
  4849.6 1943.81  4869.6 1936.08  4879.6 1933.51  4899.6 1924.63  4909.6 1921.83
  4919.6 1919.57  4939.6 1919.58  4969.6 1916.54  4970.4 1915.48  4970.9 1914.98
  4988.3 1914.98  4988.8 1915.48  4989.6  1918.6  4997.1 1919.84  5002.1 1919.84
  5009.6 1925.11  5029.6 1938.11  5039.6 1947.15  5049.6 1952.87  5059.6 1959.21
  5069.6  1962.3  5079.6    1965  5129.6  1971.6  5149.6 1974.72  5199.6 1979.21
#Mann= 3 ,-1 , 0
  4799.6      .1       0  4970.4     .05       0  4988.8      .1       0
Bank Sta=4970.4,4988.8
XS Rating Curve= 0 ,0
Exp/Cntr=0.3,0.1

Type RM Length L Ch R = 1 ,106455  ,483,483,483
BEGIN DESCRIPTION:
Turtle Creek 178.0
END DESCRIPTION:
XS GIS Cut Line= 3
        1883425.     13909475.02        1883425.       13909275.
        1883425.     13909075.02
#Sta/Elev= 30
    4800 1956.06    4840 1953.27    4850 1952.26    4870 1949.02    4910 1939.96
    4920 1936.88    4940 1929.81    4950 1925.28    4960 1918.81    4970 1915.32
  4970.8 1913.62  4971.3 1913.12  4988.7 1913.12  4989.2 1913.62    4990 1914.45
  4997.5 1915.38    5010 1915.98    5020 1917.89    5030 1918.99    5040  1917.7
    5060  1918.9    5070 1921.39    5080 1925.56    5110 1946.39    5120 1958.19
    5130  1963.1    5140  1965.1    5150  1966.4    5170 1967.31    5200 1969.66
#Mann= 3 ,-1 , 0
    4800      .1       0  4970.8     .05       0  4989.2      .1       0
Bank Sta=4970.8,4989.2
XS Rating Curve= 0 ,0
Exp/Cntr=0.3,0.1

Type RM Length L Ch R = 1 ,105972  ,466,466,466
BEGIN DESCRIPTION:
Turtle Creek 177.0
END DESCRIPTION:
XS GIS Cut Line= 3
        1883925.       13909575.        1883875.       13909275.
      1883755.69     13908879.12
#Sta/Elev= 30
  4696.2 1986.54  4725.2 1981.72  4777.3 1966.78  4784.9    1963    4790 1963.08
  4797.6 1959.11  4845.7 1940.49  4850.8 1941.46  4858.4  1937.5  4906.6 1923.25
  4911.6 1924.17  4949.6 1914.16  5001.2 1912.69  5007.6 1911.81  5008.1 1911.31
    5026 1911.81  5035.7 1914.45  5042.1 1915.22  5049.8 1917.98    5055 1917.67
  5073.4 1927.91  5082.8 1936.59    5088 1934.95  5094.3 1948.85  5104.8 1952.92
  5146.6 1959.26  5192.2  1961.5  5230.5 1965.97  5347.3 1972.41  5413.8 1974.66
#Mann= 7 ,-1 , 0
  4696.2     .07       0  4725.2      .1       0  5001.2     .07       0
  5007.6     .05       0    5026     .07       0  5035.7      .1       0
  5347.3     .07       0
Bank Sta=5007.6,5026
XS Rating Curve= 0 ,0
Exp/Cntr=0.3,0.1

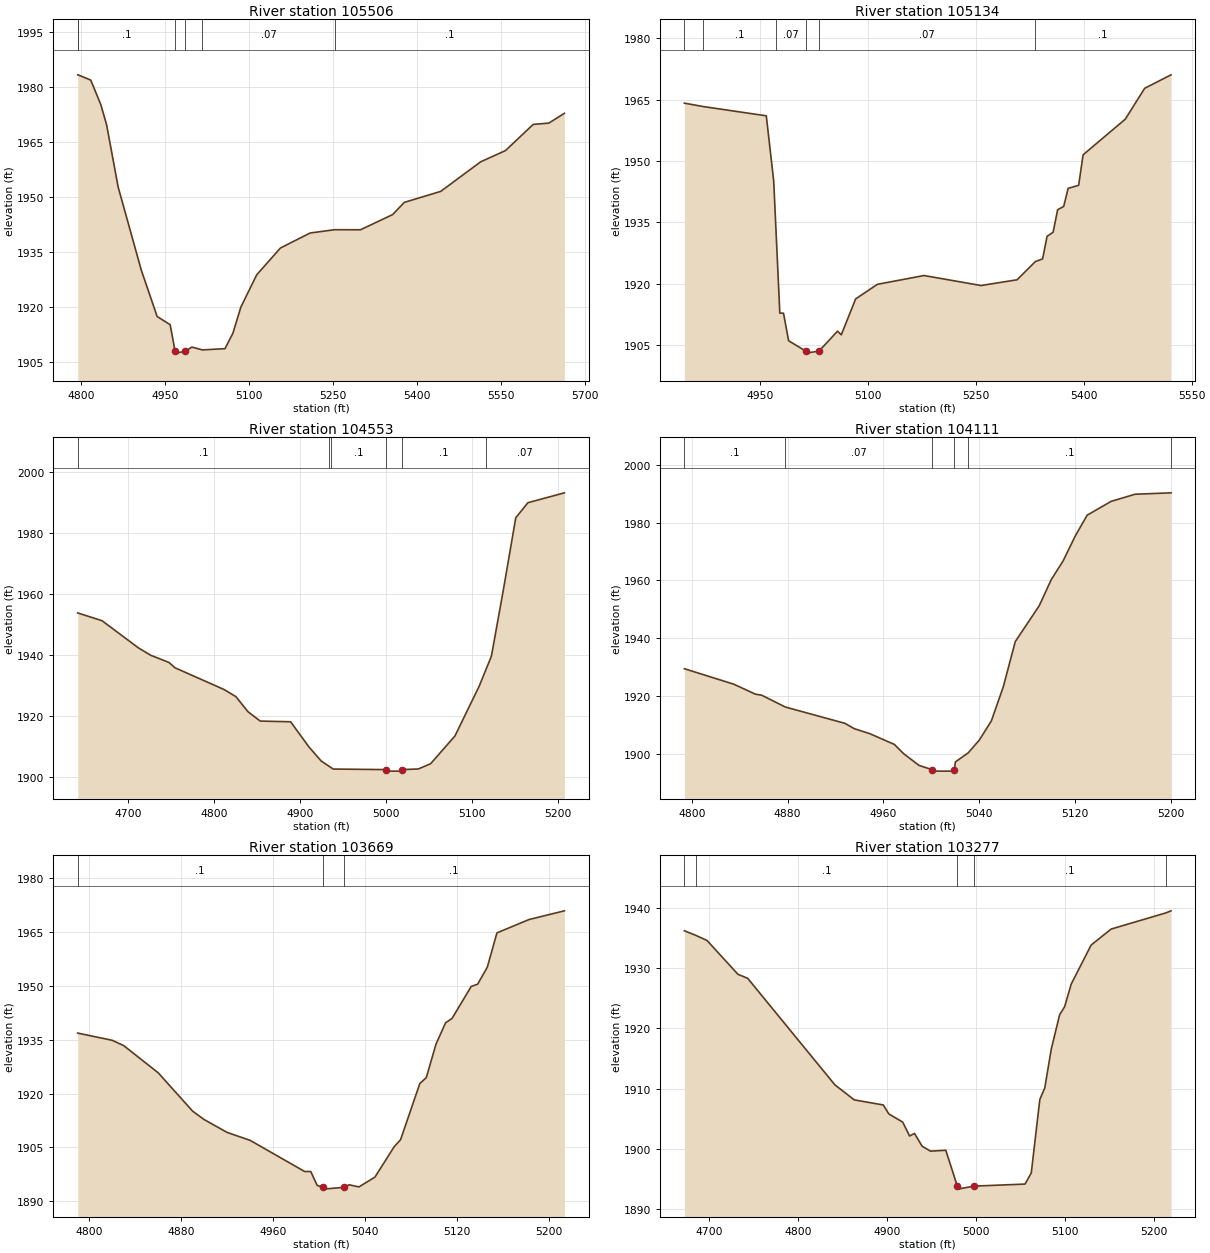
Type RM Length L Ch R = 1 ,105506  ,372,372,372
BEGIN DESCRIPTION:
Turtle Creek 176.0
END DESCRIPTION:
XS GIS Cut Line= 4
      1884374.99     13909524.97        1884325.       13909325.
        1884175.       13909175.      1883911.91     13908809.86
#Sta/Elev= 30
  4794.3 1983.36  4794.8 1983.36  4817.5 1981.92  4835.5 1975.21  4845.8  1969.7
  4866.4  1952.7  4907.7 1929.99    4936 1917.32  4959.2 1915.09    4968 1907.82
  4968.5 1907.32  4986.4 1907.82  4997.8 1908.98  5016.7  1908.2    5057 1908.54
  5071.1 1912.74  5085.3 1919.88  5113.6 1928.71    5156 1936.05    5209 1940.14
  5252.5 1941.04  5298.8 1941.02  5356.1 1945.17    5377 1948.51    5442 1951.52
  5513.2 1959.59  5557.4 1962.65    5607 1969.82  5634.7 1970.16  5662.6 1972.84
#Mann= 6 ,-1 , 0
  4794.3     .07       0  4794.8      .1       0    4968     .05       0
  4986.4      .1       0  5016.7     .07       0  5252.5      .1       0
Bank Sta=4968,4986.4
XS Rating Curve= 0 ,0
Exp/Cntr=0.3,0.1

Type RM Length L Ch R = 1 ,105134  ,581,581,581
BEGIN DESCRIPTION:
Turtle Creek 175.0
END DESCRIPTION:
XS GIS Cut Line= 3
      1884625.04     13909075.01       1884370.3     13909007.11
      1884125.01     13908675.01
#Sta/Elev= 30
  4844.8 1964.13  4871.1  1963.3  4958.7 1961.04    4969  1945.1  4972.2 1932.96
  4977.5 1912.85  4982.6 1912.85  4989.7 1906.12  5013.5 1903.59    5014 1903.09
    5032 1903.59  5057.7 1908.45  5062.9 1907.55  5082.9 1916.33  5113.1 1919.89
  5177.9 1922.04  5257.2  1919.6  5307.3    1921  5332.8 1925.46  5342.8 1926.09
    5349 1931.62  5357.4 1932.61  5363.7 1938.11  5372.1 1938.91  5378.3 1943.33
  5392.9 1944.07  5399.1 1951.52  5457.7 1960.22  5484.7 1967.76  5521.3 1971.05
#Mann= 6 ,-1 , 0
  4844.8     .07       0  4871.1      .1       0  4972.2     .07       0
  5013.5     .05       0    5032     .07       0  5332.8      .1       0
Bank Sta=5013.5,5032
XS Rating Curve= 0 ,0
Exp/Cntr=0.3,0.1

Type RM Length L Ch R = 1 ,104553  ,442,442,442
BEGIN DESCRIPTION:
Turtle Creek 174.0
END DESCRIPTION:
XS GIS Cut Line= 3
      1884674.97     13908774.97        1884425.       13908525.
      1884275.03     13908375.03
#Sta/Elev= 30
  4641.5 1953.75  4669.7 1951.21  4712.2 1942.28  4726.3 1939.89  4747.5 1937.54
  4754.6 1935.78  4811.2 1928.72  4825.3 1926.35  4839.4 1921.39  4853.6 1918.34
  4888.9 1918.11  4910.2 1909.88  4924.3  1905.3  4933.7 1903.52  4935.7 1903.14
  4938.4 1902.63  4999.9 1902.45  5000.4 1901.95  5017.9 1901.95  5018.4 1902.45
  5037.4 1902.66  5051.6 1904.37  5079.9 1913.46  5108.1 1929.78  5116.1 1935.32
  5122.3 1939.62  5136.4 1961.67  5150.6 1984.93  5164.7 1989.84  5207.1 1993.08
#Mann= 6 ,-1 , 0
  4641.5      .1       0  4933.7     .07       0  4935.7      .1       0
  4999.9     .05       0  5018.4      .1       0  5116.1     .07       0
Bank Sta=4999.9,5018.4
XS Rating Curve= 0 ,0
Exp/Cntr=0.3,0.1

Type RM Length L Ch R = 1 ,104111  ,442,442,442
BEGIN DESCRIPTION:
Turtle Creek 173.0
END DESCRIPTION:
XS GIS Cut Line= 3
      1884775.01     13908475.04        1884725.       13908275.
        1884725.       13908075.
#Sta/Elev= 30
  4793.8  1929.4  4835.1 1924.02  4853.1 1920.57  4858.3 1920.22  4878.1 1916.11
  4927.8 1910.46  4935.6 1908.61  4948.5 1906.89  4969.1 1903.15  4976.8 1899.94
  4989.7 1895.87  5000.7 1894.39  5001.2 1893.89  5018.7 1893.89  5019.2 1894.39
    5020 1897.07  5030.7 1900.22    5040 1904.67    5050 1911.26    5060 1923.11
    5070  1938.8    5090 1951.22    5100 1960.25    5110 1966.82    5120 1975.36
    5130 1982.61    5150 1987.41    5170 1989.88  5199.9 1990.37    5200 1990.37
#Mann= 6 ,-1 , 0
  4793.8      .1       0  4878.1     .07       0  5000.7     .05       0
  5019.2     .07       0  5030.7      .1       0  5199.9     .07       0
Bank Sta=5000.7,5019.2
XS Rating Curve= 0 ,0
Exp/Cntr=0.3,0.1

Type RM Length L Ch R = 1 ,103669  ,392,392,392
BEGIN DESCRIPTION:
Turtle Creek 172.0
END DESCRIPTION:
XS GIS Cut Line= 3
        1885125.     13908424.98        1885125.       13908225.
      1885024.99     13908024.99
#Sta/Elev= 30
  4790.2 1936.87  4820.2 1934.86  4830.2 1933.38  4860.2 1925.81  4890.2  1915.1
  4900.2 1912.76  4920.2 1909.17  4940.2 1906.96  4987.7 1898.27    4993 1898.27
  4998.6 1894.41  5003.3 1893.85  5003.8 1893.35  5021.8 1893.85  5026.5 1894.56
  5034.9 1893.96  5048.9  1896.7  5065.6 1905.16  5071.2 1907.14    5088 1922.82
  5093.6 1924.44    5102 1933.75  5110.4 1939.75    5116 1940.95  5132.7 1949.88
  5138.3 1950.51  5146.7 1955.25  5155.1 1964.82    5183 1968.54  5213.8 1970.97
#Mann= 3 ,-1 , 0
  4790.2      .1       0  5003.3     .05       0  5021.8      .1       0
Bank Sta=5003.3,5021.8
XS Rating Curve= 0 ,0
Exp/Cntr=0.3,0.1

Type RM Length L Ch R = 1 ,103277  ,500,500,500
BEGIN DESCRIPTION:
Turtle Creek 171.0
END DESCRIPTION:
XS GIS Cut Line= 3
      1885378.61     13908470.33      1885492.62     13908206.52
      1885374.99     13907974.97
#Sta/Elev= 30
  4672.3 1936.25    4685 1935.49  4697.7 1934.64  4732.6    1929  4743.5 1928.34
  4841.5 1910.63  4863.3 1908.13    4896 1907.28  4902.1  1905.8  4917.8 1904.43
  4925.5 1902.12    4931 1902.55  4939.6 1900.43    4949  1899.6  4966.2 1899.75
  4979.2 1893.79  4979.7 1893.29  4997.7 1893.79  5055.3 1894.13  5062.3 1895.98
  5071.9 1908.18  5077.5 1910.13  5084.8 1916.58  5094.2 1922.29  5099.8 1923.62
  5107.2 1927.38  5129.6 1933.87  5152.1 1936.53  5213.3  1939.2  5219.4 1939.56
#Mann= 5 ,-1 , 0
  4672.3     .07       0    4685      .1       0  4979.2     .05       0
  4997.7      .1       0  5213.3     .07       0
Bank Sta=4979.2,4997.7
XS Rating Curve= 0 ,0
Exp/Cntr=0.3,0.1

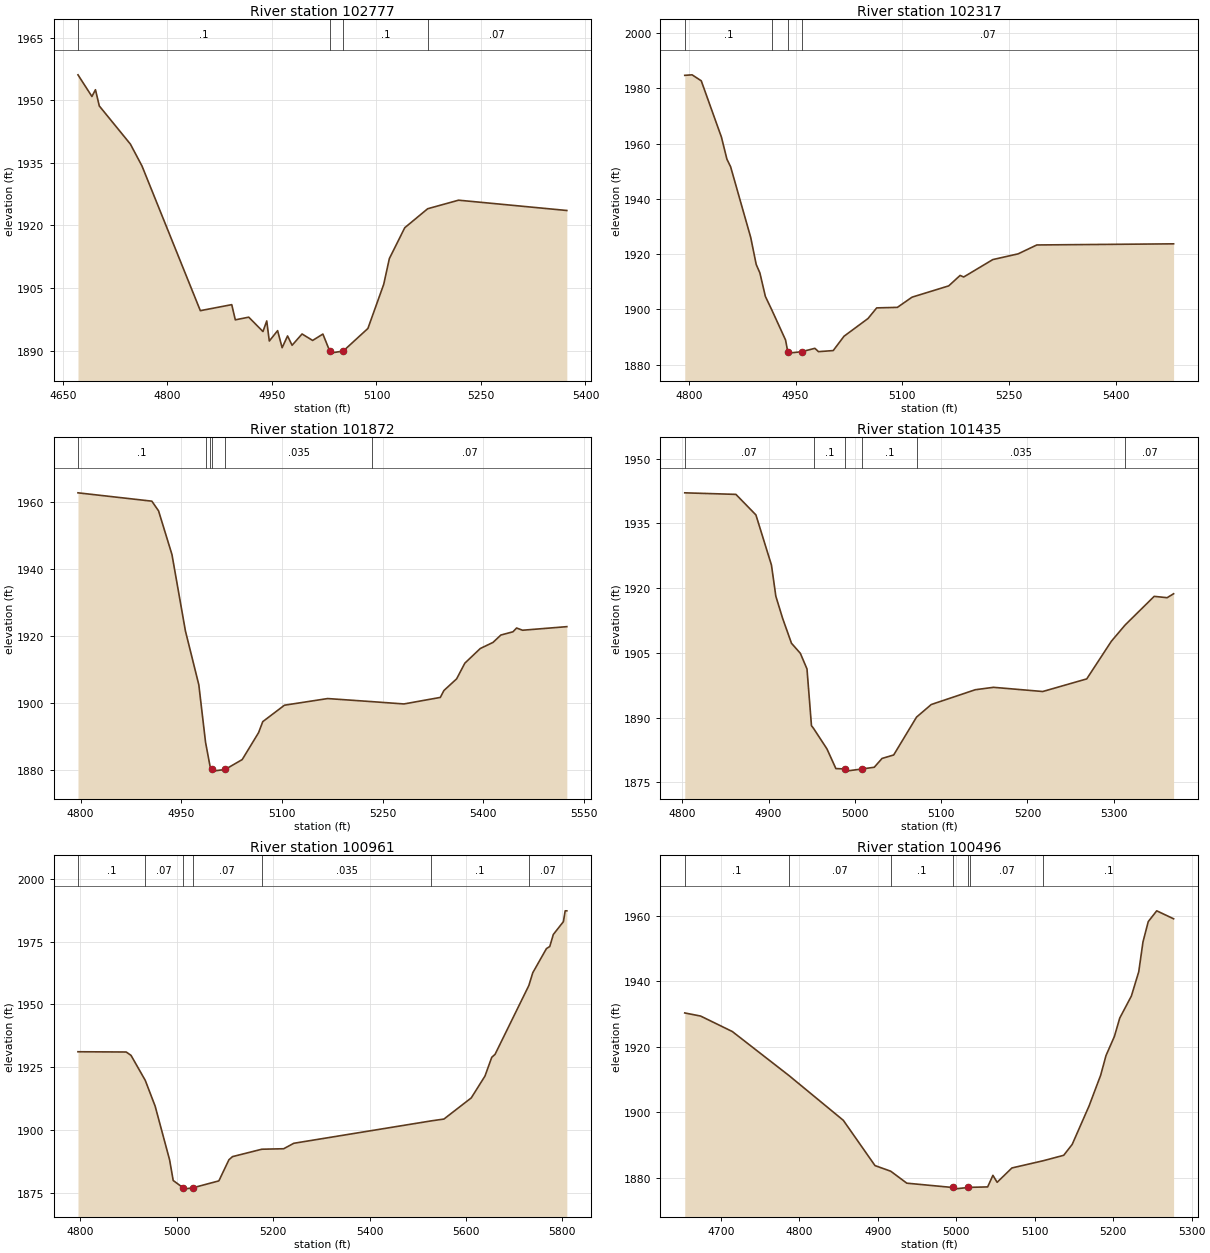
Type RM Length L Ch R = 1 ,102777  ,460,460,460
BEGIN DESCRIPTION:
Turtle Creek 170.0
END DESCRIPTION:
XS GIS Cut Line= 5
      1886224.96     13908174.99      1885952.77     13908118.63
      1885911.54     13908083.91      1885889.84     13908005.79
      1885768.01     13907744.11
#Sta/Elev= 30
  4671.6 1956.11  4691.6 1950.92  4696.7 1952.54  4702.2 1948.65  4746.8 1939.51
  4763.5 1934.25  4847.2 1899.58  4892.3 1901.02  4897.4 1897.38  4916.7 1898.02
  4937.1 1894.57  4942.5 1897.12  4946.2  1892.3  4958.1 1894.79  4964.6  1890.7
  4972.4 1893.52  4978.9 1891.28  4993.2 1893.99  5008.4 1892.44  5023.1 1893.97
  5032.9  1889.9  5033.4  1889.4  5052.3  1889.9  5087.7 1895.31  5110.4 1905.89
  5118.5 1912.07  5140.6 1919.46  5173.5 1924.01  5217.8 1926.06  5373.2 1923.59
#Mann= 4 ,-1 , 0
  4671.6      .1       0  5032.9     .05       0  5052.3      .1       0
  5173.5     .07       0
Bank Sta=5032.9,5052.3
XS Rating Curve= 0 ,0
Exp/Cntr=0.3,0.1

Type RM Length L Ch R = 1 ,102317  ,445,445,445
BEGIN DESCRIPTION:
Turtle Creek 169.0
END DESCRIPTION:
XS GIS Cut Line= 3
      1886475.03     13907875.01        1886275.       13907825.
      1885808.61     13907705.65
#Sta/Elev= 30
  4794.1 1984.72  4804.4 1984.91  4817.3 1982.75  4845.7 1962.35  4853.4 1954.38
  4858.6 1951.63  4886.9 1926.01  4894.6 1916.26  4899.8 1913.17  4907.5 1904.69
    4917 1899.54  4935.9  1888.9    4939 1884.65  4939.5 1884.15  4958.5 1884.65
  4977.1 1885.89  4982.2 1884.69  5002.9 1885.07  5018.1 1890.26  5051.9 1896.69
  5064.1 1900.53  5093.2 1900.72  5113.8 1904.41  5165.4  1908.5  5181.4 1912.28
  5186.5 1911.72  5227.4 1918.02    5263 1920.09  5289.3 1923.31  5481.7 1923.72
#Mann= 4 ,-1 , 0
  4794.1      .1       0    4917     .07       0    4939     .05       0
  4958.5     .07       0
Bank Sta=4939,4958.5
XS Rating Curve= 0 ,0
Exp/Cntr=0.3,0.1

Type RM Length L Ch R = 1 ,101872  ,437,437,437
BEGIN DESCRIPTION:
Turtle Creek 168.0
END DESCRIPTION:
XS GIS Cut Line= 3
      1886524.97       13907425.        1886325.       13907425.
      1885833.68     13907618.73
#Sta/Elev= 30
  4796.2  1962.7  4906.2 1960.21  4916.2 1957.32  4936.2 1944.25  4956.2 1921.46
  4976.2 1905.34  4986.2 1888.18  4987.6 1886.68  4992.9 1881.02  4995.9 1880.06
  4996.4 1879.56  5015.4 1880.06  5040.8 1883.01  5065.2 1891.06  5071.4 1894.34
  5103.7 1899.25  5168.1 1901.24  5233.9 1900.32  5281.7 1899.63  5335.9 1901.58
  5341.2 1903.63  5360.2 1907.14  5372.4 1911.81  5395.4 1916.19  5414.4 1918.02
  5426.1 1920.22  5444.1 1921.19  5449.5 1922.31  5458.4 1921.65  5524.3 1922.72
#Mann= 6 ,-1 , 0
  4796.2      .1       0  4987.6     .07       0  4992.9    .035       0
  4995.9    .035       0  5015.4    .035       0  5233.9     .07       0
Bank Sta=4995.9,5015.4
XS Rating Curve= 0 ,0
Exp/Cntr=0.3,0.1

Type RM Length L Ch R = 1 ,101435  ,474,474,474
BEGIN DESCRIPTION:
Turtle Creek 167.0
END DESCRIPTION:
XS GIS Cut Line= 3
      1886174.99       13907125.        1885975.       13907175.
        1885775.       13907475.
#Sta/Elev= 30
  4802.8 1942.08  4862.1 1941.72  4885.3 1936.96  4903.3 1925.35  4908.4 1918.12
  4916.2 1913.03  4926.5 1907.23  4936.8 1904.89  4944.5 1901.27  4949.7 1888.12
  4952.1  1887.5  4967.7 1882.72    4978 1878.18  4988.9 1878.09  4989.4 1877.59
  5008.4 1878.09  5022.5 1878.49  5031.5 1880.53    5045 1881.33  5071.5 1890.11
  5088.6 1893.03  5139.6 1896.45  5160.7 1897.01  5217.8 1896.04  5268.8 1898.96
  5297.4  1907.7  5313.3 1911.45    5347 1918.09    5362 1917.78  5369.5 1918.69
#Mann= 6 ,-1 , 0
  4802.8     .07       0  4952.1      .1       0  4988.9     .05       0
  5008.4      .1       0  5071.5    .035       0  5313.3     .07       0
Bank Sta=4988.9,5008.4
XS Rating Curve= 0 ,0
Exp/Cntr=0.3,0.1

Type RM Length L Ch R = 1 ,100961  ,465,465,465
BEGIN DESCRIPTION:
Turtle Creek 166.0
END DESCRIPTION:
XS GIS Cut Line= 3
        1885575.     13906775.01        1885575.       13906975.
      1884975.02     13907524.98
#Sta/Elev= 30
  4795.3 1931.21  4895.3 1931.11  4905.3 1929.78  4934.9 1919.82  4955.3 1909.62
  4985.3 1888.27  4992.8 1880.04  5013.6 1877.11  5014.1 1876.61  5033.1 1877.11
  5087.5 1879.89  5108.4 1888.29  5115.8 1889.53  5176.6 1892.47  5221.9 1892.66
  5242.9 1894.83  5528.1 1903.74  5554.3 1904.46    5611 1912.87  5639.4 1921.53
  5653.5    1929  5660.3 1930.17  5730.4 1957.52  5738.6 1962.62    5767 1972.23
  5773.8 1973.03  5781.2 1977.82  5802.1 1982.92  5805.8 1987.22  5809.2 1987.22
#Mann= 7 ,-1 , 0
  4795.3      .1       0  4934.9     .07       0  5013.6     .05       0
  5033.1     .07       0  5176.6    .035       0  5528.1      .1       0
  5730.4     .07       0
Bank Sta=5013.6,5033.1
XS Rating Curve= 0 ,0
Exp/Cntr=0.3,0.1

Type RM Length L Ch R = 1 ,100496  ,409,409,409
BEGIN DESCRIPTION:
Turtle Creek 165.0
END DESCRIPTION:
XS GIS Cut Line= 3
      1885525.01       13906725.        1885175.       13906775.
      1884925.02     13906675.01
#Sta/Elev= 30
  4654.2 1930.37  4674.4 1929.42  4714.8 1924.69  4787.1 1911.21  4856.2 1897.55
  4896.6  1883.7  4916.6 1881.99  4937.1 1878.33  4995.5 1877.01    4996 1876.51
    5015 1877.01    5017 1877.05  5040.1 1877.19  5046.8 1880.73  5052.2  1878.6
    5071 1882.98  5111.1  1885.2    5137 1886.85  5147.8 1890.18  5169.3 1901.93
  5184.1 1911.35  5190.9 1917.36  5201.6  1923.2  5208.4 1928.81  5223.2 1935.54
  5232.6 1942.97    5238  1952.1  5244.7 1958.29  5255.5 1961.59    5277 1959.16
#Mann= 7 ,-1 , 0
  4654.2      .1       0  4787.1     .07       0  4916.6      .1       0
  4995.5     .05       0    5015      .1       0    5017     .07       0
  5111.1      .1       0
Bank Sta=4995.5,5015
XS Rating Curve= 0 ,0
Exp/Cntr=0.3,0.1

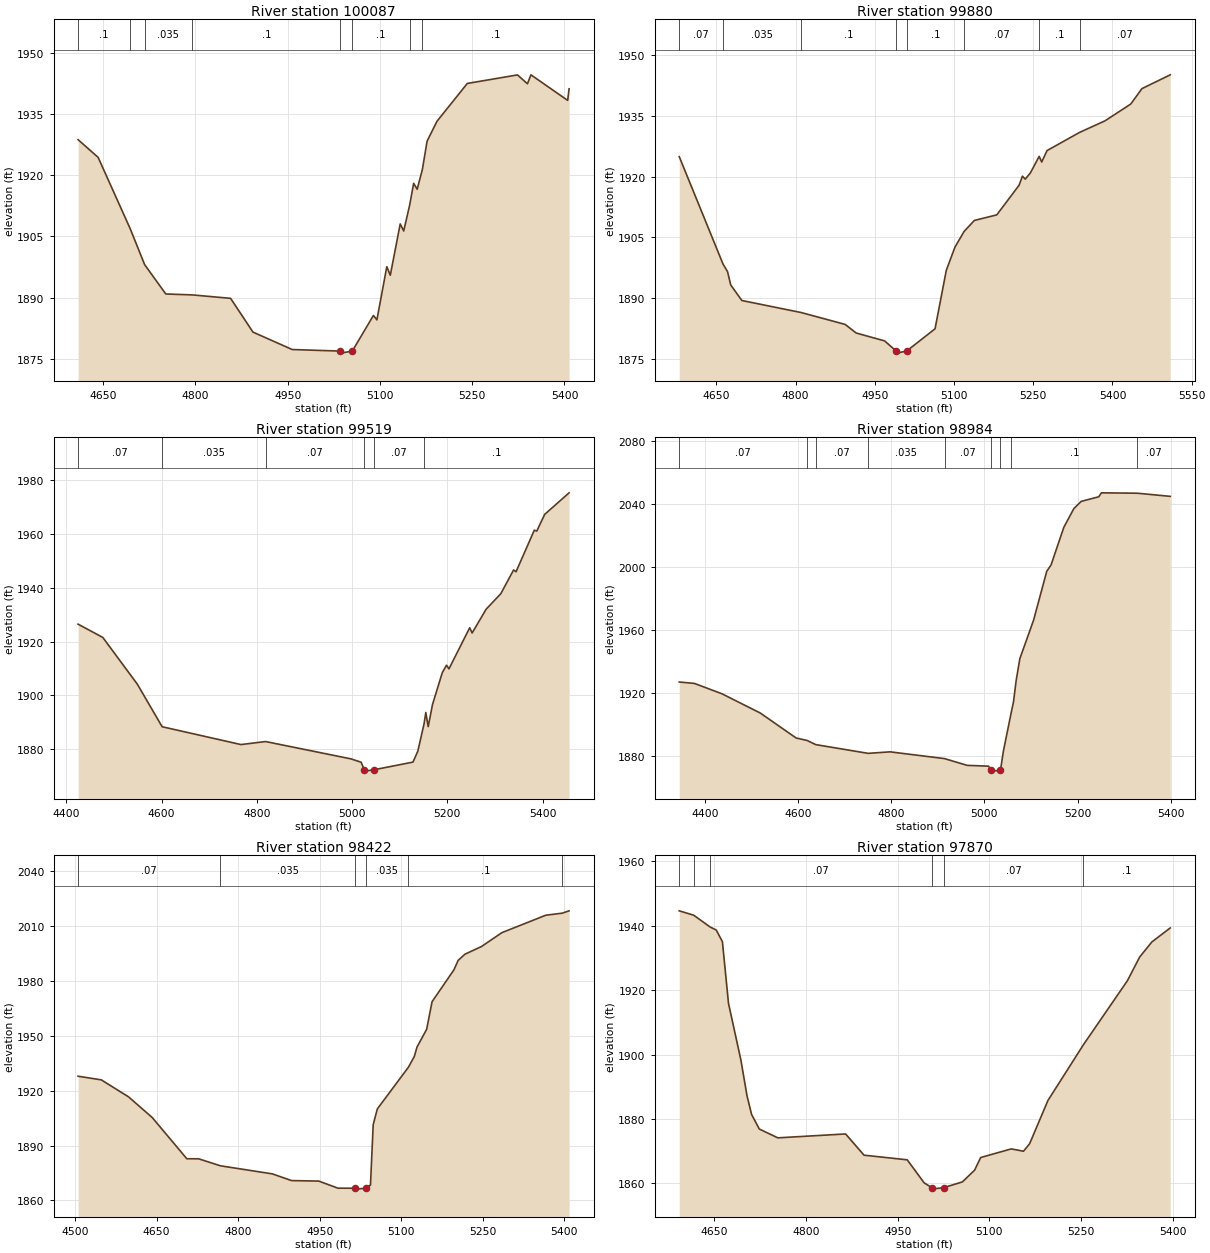
Type RM Length L Ch R = 1 ,100087  ,207,207,207
BEGIN DESCRIPTION:
Turtle Creek 164.0
END DESCRIPTION:
XS GIS Cut Line= 3
      1885525.02     13906675.02        1885225.       13906425.
       1884867.1     13906620.59
#Sta/Elev= 30
  4609.1 1928.68  4641.7 1924.35    4694 1906.85  4717.3 1898.12  4751.7 1890.94
  4794.7 1890.71  4857.1 1889.87  4893.5 1881.61  4957.3 1877.35  5035.5 1876.97
    5036 1876.47    5055 1876.97  5089.3 1885.68    5095 1884.61  5111.1 1897.61
  5116.8 1895.53  5132.9 1908.07  5138.6 1906.35  5148.2 1912.63  5154.8    1918
  5160.5 1916.55    5169 1921.43  5176.6 1928.31  5192.7 1933.18    5242 1942.43
  5323.6 1944.52  5339.8 1942.35  5345.5 1944.54  5405.2 1938.29  5407.5 1941.12
#Mann= 8 ,-1 , 0
  4609.1      .1       0    4694     .07       0  4717.3    .035       0
  4794.7      .1       0  5035.5     .05       0    5055      .1       0
  5148.2     .07       0    5169      .1       0
Bank Sta=5035.5,5055
XS Rating Curve= 0 ,0
Exp/Cntr=0.3,0.1

Type RM Length L Ch R = 1 ,99880   ,361,361,361
BEGIN DESCRIPTION:
Mapping XS 5887ca52
END DESCRIPTION:
XS GIS Cut Line= 4
      1885563.27     13906562.24      1885367.12     13906266.54
      1885121.36     13906178.62      1884824.32     13906280.57
#Sta/Elev= 30
  4579.5 1924.96  4662.4 1898.43    4671 1896.55    4677 1893.27  4698.1 1889.42
  4810.6 1886.44  4893.6 1883.52  4914.6 1881.39  4968.5 1879.44  4990.5 1876.92
    4991 1876.42  5010.1 1876.92    5064 1882.43  5085.3 1896.87  5101.7  1902.6
  5119.1 1906.49  5138.4 1909.19  5180.9 1910.57  5223.2  1917.9  5229.5 1920.13
  5234.8  1919.4  5244.4  1920.9  5261.2 1925.02    5266 1923.62  5276.1 1926.45
  5337.6 1930.93  5385.8 1933.79  5434.7 1937.95  5455.8 1941.75  5509.4 1945.16
#Mann= 8 ,-1 , 0
  4579.5     .07       0  4662.4    .035       0  4810.6      .1       0
  4990.5     .05       0  5010.1      .1       0  5119.1     .07       0
  5261.2      .1       0  5337.6     .07       0
Bank Sta=4990.5,5010.1
XS Rating Curve= 0 ,0
Exp/Cntr=0.3,0.1

Type RM Length L Ch R = 1 ,99519   ,535,535,535
BEGIN DESCRIPTION:
Turtle Creek 163.0
END DESCRIPTION:
XS GIS Cut Line= 3
      1885625.01     13906525.03        1885475.       13905975.
        1885575.       13905525.
#Sta/Elev= 30
  4424.6 1926.49  4476.5 1921.55    4549 1904.18  4601.1 1888.34  4766.7 1881.71
  4818.4 1882.83  4997.3  1876.4    5019 1875.15  5025.5 1872.33    5026 1871.83
  5045.9 1872.33  5127.9 1875.19  5138.1 1879.27  5151.3 1889.54  5154.8 1893.65
  5159.9 1888.39  5168.9 1896.61  5189.4 1908.43  5198.3 1911.23  5203.4 1909.86
    5247 1925.15  5252.1  1923.2  5281.5 1932.04  5312.3 1937.81  5339.2 1946.65
  5344.3 1945.96  5382.7 1961.44  5387.8 1961.09  5404.5 1967.32  5455.7 1975.33
#Mann= 6 ,-1 , 0
  4424.6     .07       0  4601.1    .035       0  4818.4     .07       0
  5025.5     .05       0  5045.9     .07       0  5151.3      .1       0
Bank Sta=5025.5,5045.9
XS Rating Curve= 0 ,0
Exp/Cntr=0.3,0.1

Type RM Length L Ch R = 1 ,98984   ,562,562,562
BEGIN DESCRIPTION:
Turtle Creek 162.0
END DESCRIPTION:
XS GIS Cut Line= 3
      1885675.01     13906524.97        1885925.       13905925.
      1886125.01     13905574.98
#Sta/Elev= 30
  4345.4 1926.86  4377.9 1925.97  4436.9  1919.4  4519.2 1907.16  4596.2 1891.29
  4619.7 1889.73  4638.2 1887.09  4750.6 1881.54  4797.7  1882.5  4914.4  1878.2
  4962.9 1873.92    5009 1873.39    5014 1870.75  5014.5 1870.25  5034.4 1870.75
  5040.7 1883.01  5057.7 1907.78  5062.3 1914.15  5068.1 1927.92    5076 1941.73
  5105.5 1966.21  5133.6 1997.14  5142.9 2001.23  5170.3 2025.13  5191.9 2037.07
  5207.7 2041.61  5245.2 2044.52  5250.9 2047.03  5328.1 2046.78  5398.5 2044.79
#Mann= 9 ,-1 , 0
  4345.4     .07       0  4619.7    .035       0  4638.2     .07       0
  4750.6    .035       0  4914.4     .07       0    5014     .05       0
  5034.4     .07       0  5057.7      .1       0  5328.1     .07       0
Bank Sta=5014,5034.4
XS Rating Curve= 0 ,0
Exp/Cntr=0.3,0.1

Type RM Length L Ch R = 1 ,98422   ,552,552,552
BEGIN DESCRIPTION:
Turtle Creek 161.0
END DESCRIPTION:
XS GIS Cut Line= 3
      1885975.02     13906724.98        1886275.       13906325.
        1886325.     13905924.99
#Sta/Elev= 30
  4505.5 1927.96  4548.2 1925.97  4598.2  1916.7  4641.9 1905.36  4705.5 1882.83
  4727.3 1882.79  4767.3 1878.97  4862.8 1874.55  4898.2 1870.88  4948.2 1870.61
  4983.6 1866.72  5015.4 1866.71  5015.9 1866.21  5035.8 1866.71  5043.3 1868.46
  5048.3 1901.45  5055.9 1910.07  5113.1 1932.89  5123.9 1938.75  5128.9 1943.92
  5146.6  1953.6  5156.6 1968.72    5197 1986.24  5204.5 1991.29  5217.1  1994.7
  5247.3 1998.87  5285.1 2006.49  5365.8 2016.02  5396.1 2017.14  5408.6 2018.42
#Mann= 6 ,-1 , 0
  4505.5     .07       0  4767.3    .035       0  5015.4    .035       0
  5035.8    .035       0  5113.1      .1       0  5396.1     .07       0
Bank Sta=5015.4,5035.8
XS Rating Curve= 0 ,0
Exp/Cntr=0.3,0.1

Type RM Length L Ch R = 1 ,97870   ,343,343,343
BEGIN DESCRIPTION:
Turtle Creek 160.0
END DESCRIPTION:
XS GIS Cut Line= 3
        1886575.     13907125.01        1886625.       13906725.
        1886625.     13906325.02
#Sta/Elev= 30
  4592.7 1944.63  4616.4 1943.27  4643.4 1939.59  4653.2 1938.68  4663.3 1935.06
  4673.3 1915.89  4693.5 1898.37  4703.6 1887.17  4711.1  1881.4  4723.7 1876.88
    4754 1874.15  4864.8 1875.36    4895 1868.77  4965.6 1867.33  4993.3 1860.18
  5005.6 1858.73  5006.1 1858.23  5026.1 1858.73  5055.8 1860.47  5075.8 1864.11
  5085.8 1868.05  5135.8 1870.72  5155.8    1870  5165.8 1872.32  5195.8 1885.76
  5253.5 1902.97  5325.8 1922.95  5345.8 1930.28  5365.8 1934.97  5395.8 1939.32
#Mann= 6 ,-1 , 0
  4592.7     .07       0  4616.4      .1       0  4643.4     .07       0
  5005.6     .05       0  5026.1     .07       0  5253.5      .1       0
Bank Sta=5005.6,5026.1
XS Rating Curve= 0 ,0
Exp/Cntr=0.3,0.1