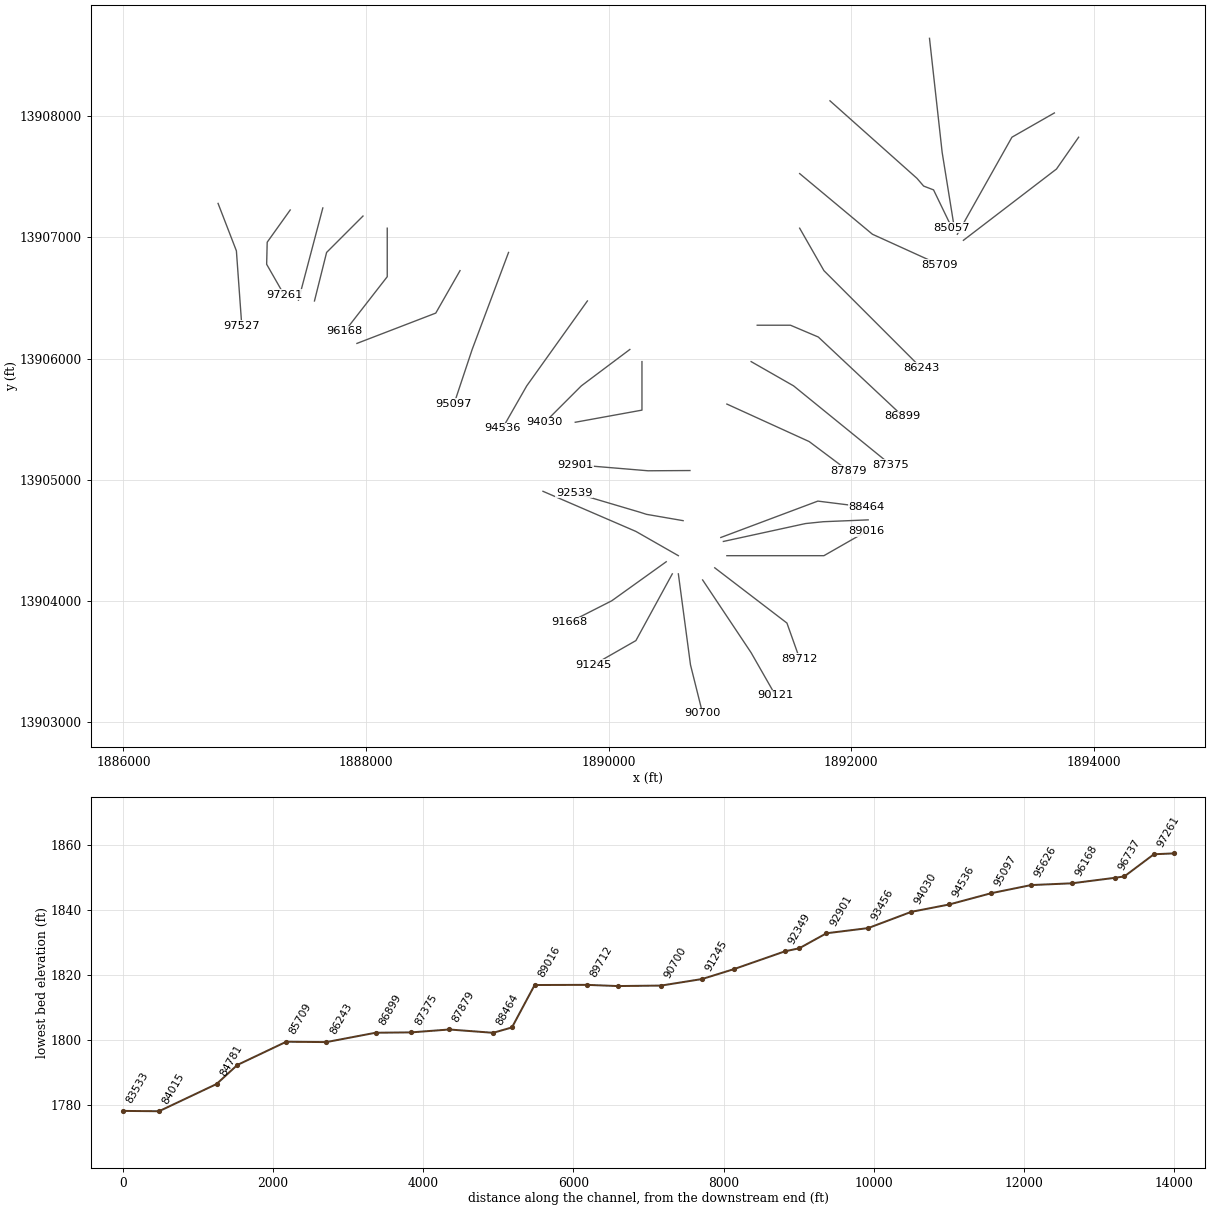
HEC-RAS study Turtle Creek.prj: Turtle Creek Base Level Engineering

--- Turtle Creek.g01 (geometry) --- (continued)

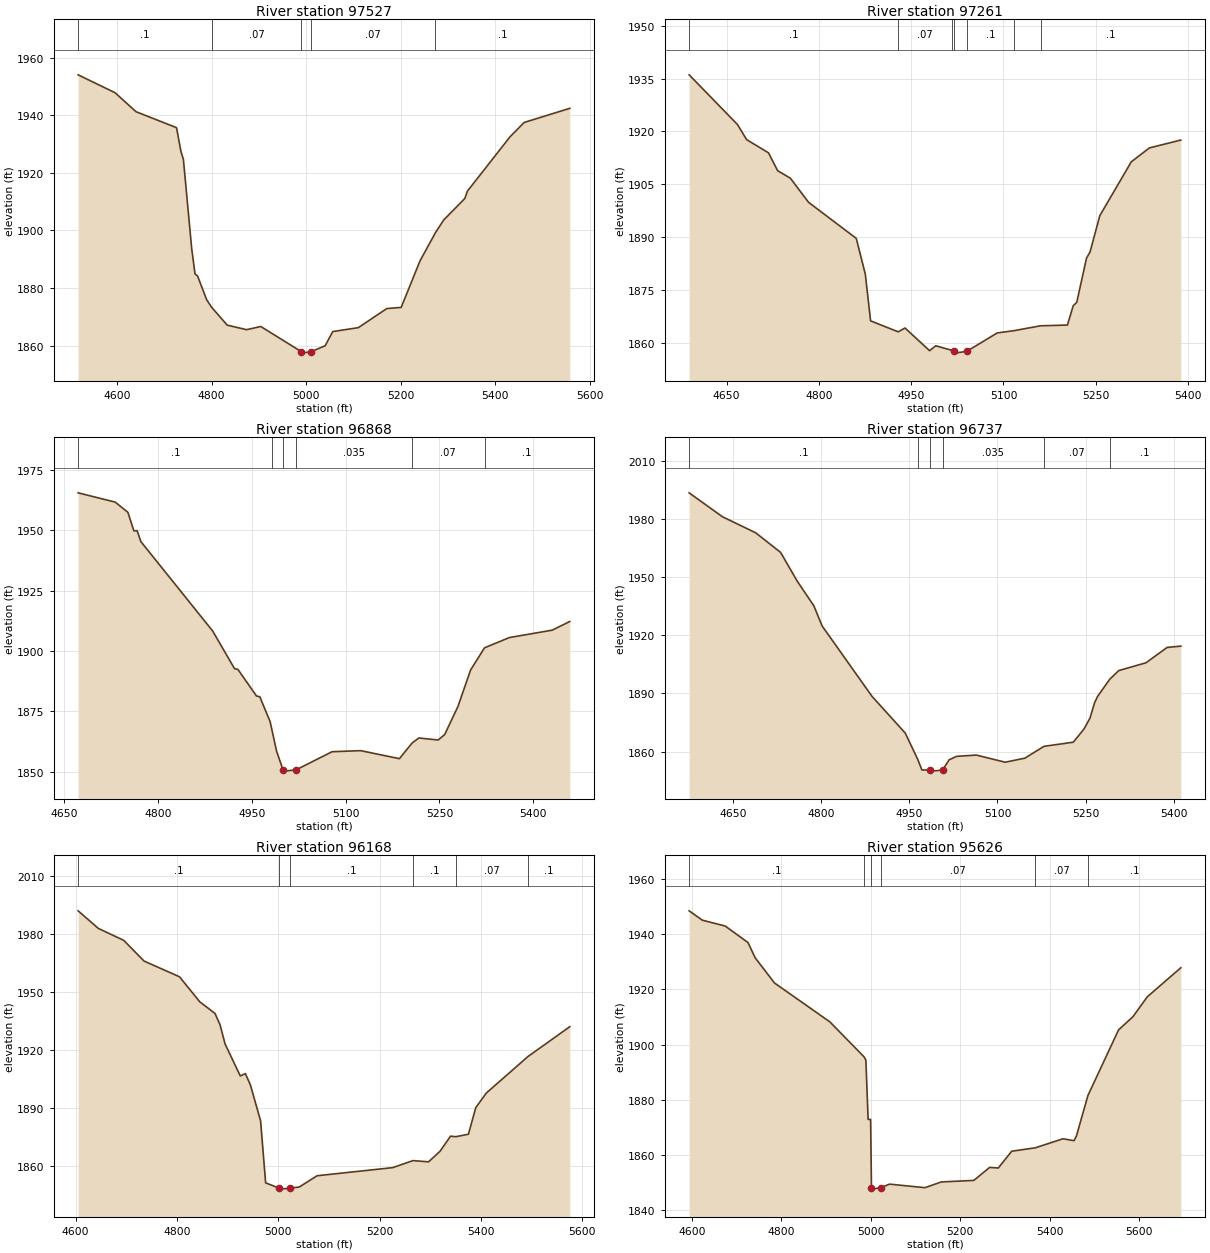
Type RM Length L Ch R = 1 ,97527   ,266,266,266
BEGIN DESCRIPTION:
Mapping XS a9e2248b
END DESCRIPTION:
XS GIS Cut Line= 3
      1886780.29      13907279.2      1886931.35     13906888.14
      1886975.98     13906268.86
#Sta/Elev= 30
  4517.7 1954.02    4596 1947.79  4640.1 1941.22  4725.9 1935.67  4735.1 1927.49
  4740.4 1924.66    4758  1893.6    4765 1884.88  4770.4 1884.17  4789.6 1875.95
    4800 1873.33  4833.1 1867.11  4874.1 1865.53  4904.1 1866.64    4990 1857.89
  4990.5 1857.39  5010.5 1857.89  5040.3 1859.95  5056.3 1864.87  5110.5 1866.24
  5170.7 1872.87  5201.1 1873.27  5240.8 1889.37  5273.4 1899.17    5291 1903.61
  5335.8  1911.1  5341.1 1913.61  5431.3 1932.49  5461.4 1937.49  5557.8 1942.39
#Mann= 5 ,-1 , 0
  4517.7      .1       0    4800     .07       0    4990     .05       0
  5010.5     .07       0  5273.4      .1       0
Bank Sta=4990,5010.5
XS Rating Curve= 0 ,0
Exp/Cntr=0.3,0.1

Type RM Length L Ch R = 1 ,97261   ,393,393,393
BEGIN DESCRIPTION:
Turtle Creek 159.0
END DESCRIPTION:
XS GIS Cut Line= 4
      1887374.99     13907224.98      1887185.32     13906959.44
      1887180.75     13906777.43      1887324.99     13906525.02
#Sta/Elev= 30
  4589.2 1936.05  4667.8 1921.95  4682.6 1917.68  4718.2 1913.92    4733 1908.87
  4753.8 1906.72  4783.3 1899.89  4860.8 1889.67  4875.5 1879.54  4884.1 1866.28
    4929 1863.17    4940 1864.26    4980 1857.82    4990 1859.22  5016.8 1857.89
  5019.6 1857.63  5020.1 1857.13  5040.3 1857.63    5090 1862.86  5117.6 1863.51
  5160.3 1864.88    5204 1865.09  5213.4 1870.55  5219.2 1871.55    5235 1884.06
  5240.8 1885.83  5256.6  1896.1  5307.7 1911.36  5337.2 1915.33  5388.3 1917.55
#Mann= 7 ,-1 , 0
  4589.2      .1       0    4929     .07       0  5016.8      .1       0
  5019.6     .05       0  5040.3      .1       0  5117.6     .07       0
  5160.3      .1       0
Bank Sta=5019.6,5040.3
XS Rating Curve= 0 ,0
Exp/Cntr=0.3,0.1

Type RM Length L Ch R = 1 ,96868   ,131,131,131
BEGIN DESCRIPTION:
Mapping XS ef71124f
END DESCRIPTION:
XS GIS Cut Line= 2
       1887643.9     13907241.96      1887443.12     13906481.52
#Sta/Elev= 30
    4672 1965.42  4731.3 1961.58  4751.6 1957.37  4761.2 1949.69  4766.4 1949.77
  4772.3 1945.28  4887.2 1908.28  4922.3 1892.66  4927.5 1892.42  4957.4 1881.38
  4962.6 1881.09  4979.1 1870.83  4982.9 1866.34  4989.5 1858.55  4999.8 1850.82
  5000.3 1850.32  5020.5 1850.82  5078.2 1858.35  5123.9 1858.79    5186 1855.47
  5206.1 1861.91    5217 1864.02    5248  1863.2  5258.4 1865.47  5279.5 1877.01
  5299.8 1892.15  5322.1 1901.32  5361.8 1905.56  5430.3 1908.62  5458.5 1912.21
#Mann= 6 ,-1 , 0
    4672      .1       0  4982.9    .035       0  4999.8    .035       0
  5020.5    .035       0  5206.1     .07       0  5322.1      .1       0
Bank Sta=4999.8,5020.5
XS Rating Curve= 0 ,0
Exp/Cntr=0.3,0.1

Type RM Length L Ch R = 1 ,96737   ,569,569,569
BEGIN DESCRIPTION:
Turtle Creek 158.0
END DESCRIPTION:
XS GIS Cut Line= 3
      1887975.01     13907175.01        1887675.       13906875.
        1887575.     13906474.99
#Sta/Elev= 30
  4575.4 1993.73    4632 1981.37  4688.6 1973.07    4731 1962.94  4759.3 1948.08
  4787.5 1935.37  4801.7 1924.89  4886.5 1888.55  4943.1 1869.54  4964.3 1855.99
  4971.4 1850.49  4985.7 1850.37  4986.2 1849.87  5006.5 1850.37  5017.7 1855.73
  5030.6 1857.51  5064.1 1858.17  5113.1 1854.48  5146.6 1856.57  5179.2 1862.69
    5229 1864.82  5247.1 1871.58  5257.4 1877.24  5265.1 1885.12  5270.3 1888.47
  5290.9 1897.31  5306.3 1901.83  5352.7 1905.88  5388.8 1913.82    5412 1914.49
#Mann= 6 ,-1 , 0
  4575.4      .1       0  4964.3    .035       0  4985.7    .035       0
  5006.5    .035       0  5179.2     .07       0  5290.9      .1       0
Bank Sta=4985.7,5006.5
XS Rating Curve= 0 ,0
Exp/Cntr=0.3,0.1

Type RM Length L Ch R = 1 ,96168   ,542,542,542
BEGIN DESCRIPTION:
Turtle Creek 157.0
END DESCRIPTION:
XS GIS Cut Line= 3
        1888175.     13907074.97        1888175.       13906675.
      1887824.98     13906224.97
#Sta/Elev= 30
  4605.1 1992.14  4645.1 1983.03  4695.1 1976.88  4735.1 1966.17  4805.1 1958.03
  4845.1 1945.08  4875.1 1939.09  4885.1 1933.21  4895.1 1923.25  4925.1 1906.72
  4935.1 1907.95  4945.1 1902.04  4965.1 1883.52  4975.1 1851.43  5001.9 1848.69
  5002.4 1848.19  5022.7 1848.69  5041.3 1849.26  5076.6 1855.11  5225.9 1859.31
  5265.7 1862.94  5296.5 1862.31  5319.1 1867.76  5339.9 1875.59  5350.6 1875.32
  5375.2 1876.59  5389.7 1890.37  5410.5 1897.89  5492.6 1916.77  5575.2 1932.21
#Mann= 6 ,-1 , 0
  4605.1      .1       0  5001.9     .05       0  5022.7      .1       0
  5265.7      .1       0  5350.6     .07       0  5492.6      .1       0
Bank Sta=5001.9,5022.7
XS Rating Curve= 0 ,0
Exp/Cntr=0.3,0.1

Type RM Length L Ch R = 1 ,95626   ,529,529,529
BEGIN DESCRIPTION:
Turtle Creek 156.0
END DESCRIPTION:
XS GIS Cut Line= 3
        1888775.     13906725.01        1888575.       13906375.
      1887925.04     13906125.01
#Sta/Elev= 30
  4593.5 1948.51    4623 1945.12  4674.1    1943  4725.2    1937  4741.1  1931.5
  4784.3 1922.37  4908.1 1908.28  4984.5 1895.62  4988.7 1894.38  4993.7 1872.92
  4999.3 1872.92  5001.2 1848.15  5001.7 1847.65    5022 1848.15  5041.6 1849.46
  5120.9 1848.18  5157.3 1850.25  5230.2 1850.82  5265.5 1855.53  5284.8  1855.3
  5314.8 1861.39  5367.2 1862.61  5429.5  1865.9  5454.1 1865.21  5459.5 1866.88
  5485.2 1881.56  5553.8 1905.37  5585.9 1910.14    5618 1917.35    5693 1927.88
#Mann= 6 ,-1 , 0
  4593.5      .1       0  4984.5     .07       0  5001.2     .05       0
    5022     .07       0  5367.2     .07       0  5485.2      .1       0
Bank Sta=5001.2,5022
XS Rating Curve= 0 ,0
Exp/Cntr=0.3,0.1

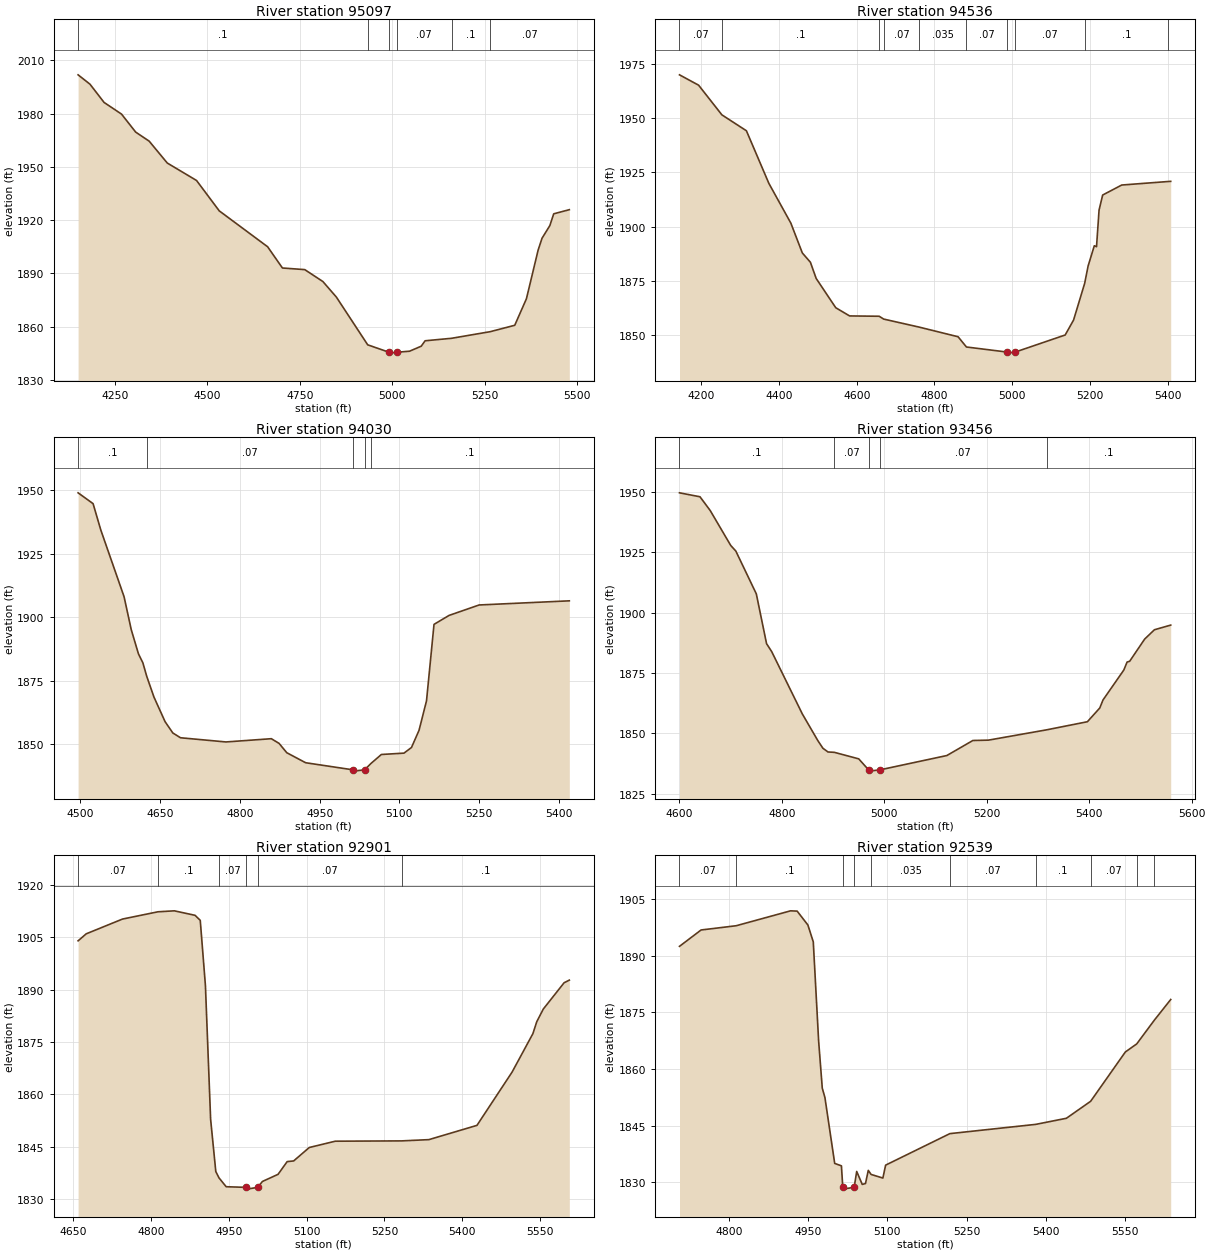
Type RM Length L Ch R = 1 ,95097   ,561,561,561
BEGIN DESCRIPTION:
Turtle Creek 155.0
END DESCRIPTION:
XS GIS Cut Line= 3
      1889175.01     13906875.01        1888875.       13906075.
      1888724.99     13905624.96
#Sta/Elev= 30
  4150.1 2001.84  4182.2 1996.58  4220.4 1986.29  4267.6 1979.73  4305.9 1969.59
  4342.4 1964.49  4391.3 1952.19  4470.5 1942.36  4531.9 1925.26  4662.8 1905.04
  4702.8 1893.09  4763.3 1892.17  4812.3 1885.46  4848.8  1876.7  4933.5 1849.84
  4991.1 1845.66  4991.6 1845.16  5012.5 1845.66  5046.7 1846.24  5078.3 1849.06
  5088.8 1852.11  5160.4 1853.51  5265.2 1857.25  5331.3 1860.84  5362.9 1875.78
  5394.5 1903.14  5405.1 1909.85  5426.2 1916.95  5436.7 1923.59  5478.9 1925.92
#Mann= 6 ,-1 , 0
  4150.1      .1       0  4933.5     .07       0  4991.1     .05       0
  5012.5     .07       0  5160.4      .1       0  5265.2     .07       0
Bank Sta=4991.1,5012.5
XS Rating Curve= 0 ,0
Exp/Cntr=0.3,0.1

Type RM Length L Ch R = 1 ,94536   ,506,506,506
BEGIN DESCRIPTION:
Turtle Creek 154.0
END DESCRIPTION:
XS GIS Cut Line= 3
      1889825.01     13906475.02        1889325.       13905775.
      1889124.98     13905424.97
#Sta/Elev= 30
  4144.2 1969.99  4193.4 1965.21  4253.2 1951.54  4316.3  1944.2    4374 1919.97
  4430.6 1901.62  4460.1 1887.87  4480.9 1883.58  4495.7 1876.12  4546.1 1862.61
  4581.7 1858.83  4657.8 1858.68  4669.3 1857.38  4760.3 1853.69  4860.7 1849.23
  4882.2 1844.51  4986.4 1842.18  4986.9 1841.68  5007.8 1842.18  5136.2 1850.04
  5157.8 1856.95  5186.3 1873.86  5195.2 1881.89  5211.1 1891.18  5216.8 1890.75
  5223.3 1907.62  5232.6 1914.57  5281.6 1919.18  5400.9  1920.8  5407.6 1920.88
#Mann= 10 ,-1 , 0
  4144.2     .07       0  4253.2      .1       0  4657.8    .035       0
  4669.3     .07       0  4760.3    .035       0  4882.2     .07       0
  4986.4     .05       0  5007.8     .07       0  5186.3      .1       0
  5400.9     .07       0
Bank Sta=4986.4,5007.8
XS Rating Curve= 0 ,0
Exp/Cntr=0.3,0.1

Type RM Length L Ch R = 1 ,94030   ,574,574,574
BEGIN DESCRIPTION:
Turtle Creek 153.0
END DESCRIPTION:
XS GIS Cut Line= 3
      1890175.02     13906075.02        1889775.       13905775.
        1889475.       13905475.
#Sta/Elev= 30
  4495.5 1948.92  4523.7 1944.66  4538.2  1934.3    4582 1908.04  4595.5 1895.08
  4609.1 1885.54  4617.4 1882.02  4624.6 1876.75  4638.2 1868.57  4659.1  1858.9
  4673.7 1854.43  4688.2 1852.54  4773.7 1850.89  4859.1 1852.17  4873.7 1850.32
  4888.2 1846.65  4923.7 1842.71  5013.1 1839.91  5013.6 1839.41  5034.5 1839.91
  5046.8 1842.47  5066.2 1845.96  5108.7 1846.49  5122.8 1848.71    5137 1855.45
  5151.1 1867.08  5165.2 1897.16  5193.5 1900.68  5250.1 1904.79  5419.8 1906.42
#Mann= 5 ,-1 , 0
  4495.5      .1       0  4624.6     .07       0  5013.1     .05       0
  5034.5     .07       0  5046.8      .1       0
Bank Sta=5013.1,5034.5
XS Rating Curve= 0 ,0
Exp/Cntr=0.3,0.1

Type RM Length L Ch R = 1 ,93456   ,555,555,555
BEGIN DESCRIPTION:
Turtle Creek 152.0
END DESCRIPTION:
XS GIS Cut Line= 3
        1890275.     13905975.03        1890275.       13905575.
      1889724.95     13905474.99
#Sta/Elev= 30
    4600 1949.53    4640  1947.9    4660  1942.2    4700 1927.77    4710 1925.44
    4750 1907.73    4770 1887.13    4780 1883.86    4840    1858    4870 1847.08
    4880 1843.87    4890 1842.33  4902.4 1842.18    4950 1839.48  4969.3 1834.91
  4969.8 1834.41  4990.8 1834.91    5122 1840.86  5172.8 1847.08  5203.3 1847.23
    5317  1851.5  5396.4 1854.84  5420.6 1860.53  5426.9 1863.84  5467.6 1876.25
  5473.9 1879.52    5479 1879.86  5508.2 1889.02  5527.3 1892.89  5559.1 1894.82
#Mann= 5 ,-1 , 0
    4600      .1       0  4902.4     .07       0  4969.3     .05       0
  4990.8     .07       0    5317      .1       0
Bank Sta=4969.3,4990.8
XS Rating Curve= 0 ,0
Exp/Cntr=0.3,0.1

Type RM Length L Ch R = 1 ,92901   ,362,362,362
BEGIN DESCRIPTION:
Turtle Creek 151.0
END DESCRIPTION:
XS GIS Cut Line= 3
      1890670.68     13905076.95        1890325.       13905075.
      1889724.96       13905125.
#Sta/Elev= 30
  4658.9 1904.01  4674.6 1906.02  4744.6 1910.25  4812.9 1912.33  4844.6 1912.61
  4884.6 1911.32  4894.6 1909.88  4904.6 1891.13  4914.6 1852.85  4924.6 1837.85
  4930.8 1836.04  4944.6 1833.51  4983.8 1833.32  4984.3 1832.82  5005.3 1833.32
  5014.6 1835.02  5044.7 1837.06  5062.3 1840.71  5074.8  1840.9  5104.9 1844.75
  5155.1 1846.56  5283.2 1846.65  5335.7 1847.01  5428.5  1851.1  5496.3 1866.38
  5536.4 1877.39  5543.9 1880.82  5556.5 1884.45  5596.6 1891.98  5606.7 1892.74
#Mann= 6 ,-1 , 0
  4658.9     .07       0  4812.9      .1       0  4930.8     .07       0
  4983.8     .05       0  5005.3     .07       0  5283.2      .1       0
Bank Sta=4983.8,5005.3
XS Rating Curve= 0 ,0
Exp/Cntr=0.3,0.1

Type RM Length L Ch R = 1 ,92539   ,190,190,190
BEGIN DESCRIPTION:
Turtle Creek 150.1
END DESCRIPTION:
XS GIS Cut Line= 4
      1890614.27     13904663.76      1890312.58     13904715.85
      1890258.32     13904733.22      1889715.81      13904893.8
#Sta/Elev= 30
  4706.9 1892.46  4747.7 1896.79    4814 1897.91    4917 1901.86  4929.4 1901.78
  4949.7 1898.11  4959.9 1893.64    4970 1867.43  4976.9 1854.92  4981.9 1852.45
  5000.4 1835.01  5013.1 1834.36  5015.7  1828.7  5016.2  1828.2  5037.2  1828.7
    5042 1832.88  5052.5 1829.45  5058.6 1829.67  5063.9 1833.16  5069.2 1832.09
  5091.5 1831.13  5096.7 1834.55  5218.2 1842.89  5380.6 1845.34  5438.5 1846.95
  5484.4 1851.45    5550  1864.5  5571.5 1866.63  5604.9 1872.93  5635.8 1878.39
#Mann= 10 ,-1 , 0
  4706.9     .07       0    4814      .1       0  5015.7     .05       0
  5037.2      .1       0  5069.2    .035       0  5218.2     .07       0
  5380.6      .1       0  5484.4     .07       0  5571.5      .1       0
  5604.9     .07       0
Bank Sta=5015.7,5037.2
XS Rating Curve= 0 ,0
Exp/Cntr=0.3,0.1

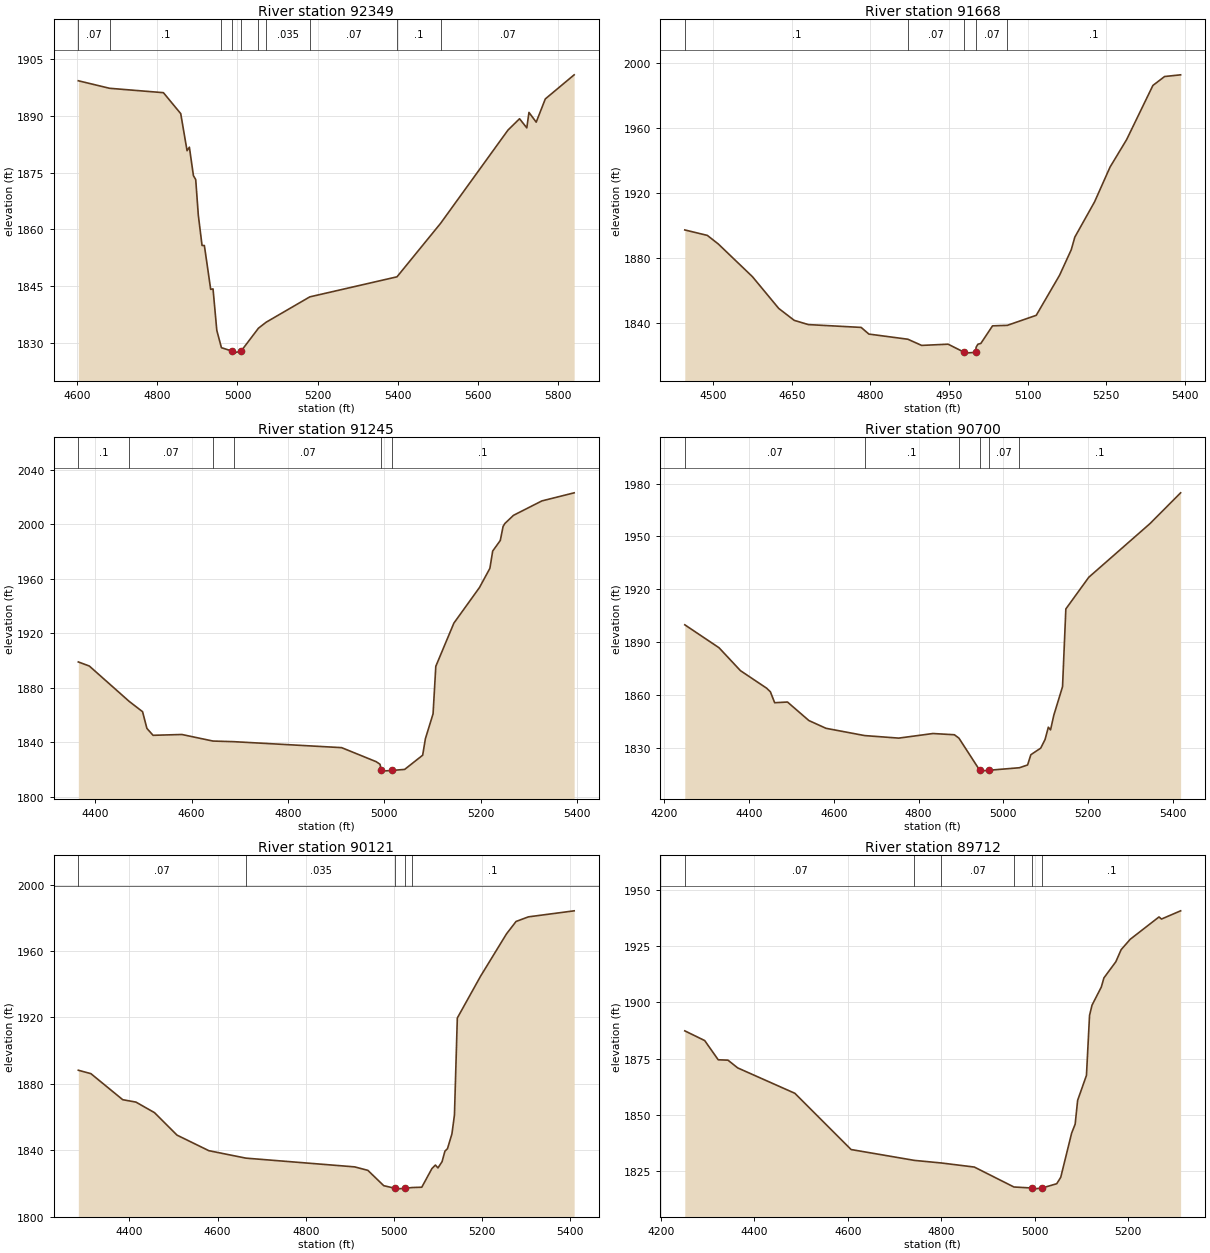
Type RM Length L Ch R = 1 ,92349   ,681,681,681
BEGIN DESCRIPTION:
Turtle Creek 150.0
END DESCRIPTION:
XS GIS Cut Line= 3
      1890575.03     13904374.98        1890225.       13904575.
      1889458.88     13904905.72
#Sta/Elev= 30
  4602.8 1899.27  4680.8 1897.28  4815.2 1896.12  4858.4 1890.58  4874.2 1880.78
    4880 1881.71  4890.1 1874.18  4895.8 1873.15  4902.3 1863.72  4911.6 1855.74
  4917.4 1855.72  4933.2 1844.13    4939 1844.25  4948.4  1833.3    4960 1828.71
  4987.3 1827.77  4987.8 1827.27  5008.8 1827.77  5052.4 1833.86  5071.6 1835.44
  5180.5 1842.14  5398.2 1847.44  5507.1 1861.59  5675.2 1886.23  5704.1 1889.23
  5722.2 1886.82  5727.6  1890.9  5745.7 1888.33  5768.4 1894.47  5840.4 1900.84
#Mann= 10 ,-1 , 0
  4602.8     .07       0  4680.8      .1       0    4960    .035       0
  4987.3    .035       0  5008.8    .035       0  5052.4     .07       0
  5071.6    .035       0  5180.5     .07       0  5398.2      .1       0
  5507.1     .07       0
Bank Sta=4987.3,5008.8
XS Rating Curve= 0 ,0
Exp/Cntr=0.3,0.1

Type RM Length L Ch R = 1 ,91668   ,423,423,423
BEGIN DESCRIPTION:
Turtle Creek 149.0
END DESCRIPTION:
XS GIS Cut Line= 3
        1890475.       13904325.      1890025.83     13904003.12
      1889674.96     13903824.98
#Sta/Elev= 30
  4445.9 1897.38  4488.9 1894.03  4509.8 1888.77  4574.9 1868.72  4625.2 1849.19
  4654.7 1841.89  4681.7 1839.29  4782.4 1837.56  4797.2 1833.47  4871.5 1830.31
  4897.9 1826.51  4948.3 1827.27  4979.2 1822.28  4979.7 1821.78  5000.9 1822.28
  5001.8 1825.43  5005.2 1827.24  5010.8 1827.74  5033.1 1838.52  5061.3 1838.83
  5116.5 1844.98    5161 1869.57  5183.3 1885.23  5190.1 1892.96  5227.8 1914.62
  5257.4    1936    5289 1952.83  5339.1 1986.05  5361.4 1991.53    5392 1992.57
#Mann= 5 ,-1 , 0
  4445.9      .1       0  4871.5     .07       0  4979.2     .05       0
  5000.9     .07       0  5061.3      .1       0
Bank Sta=4979.2,5000.9
XS Rating Curve= 0 ,0
Exp/Cntr=0.3,0.1

Type RM Length L Ch R = 1 ,91245   ,545,545,545
BEGIN DESCRIPTION:
Turtle Creek 148.0
END DESCRIPTION:
XS GIS Cut Line= 3
      1890525.02     13904225.04        1890225.       13903675.
      1889874.96     13903474.98
#Sta/Elev= 30
  4364.8 1898.85  4387.6 1895.86  4470.3 1869.95  4498.2 1862.34  4507.2  1850.1
    4520 1845.02  4579.8 1845.62  4644.3 1840.81  4688.3 1840.34  4911.6 1835.97
  4983.3 1825.68  4991.3 1823.78  4994.2 1819.24  4994.7 1818.74  5015.9 1819.24
  5042.5    1820  5079.9 1830.42  5085.6 1842.57  5101.5 1860.81  5107.2 1895.67
  5144.7 1927.32  5197.9 1953.47  5219.5 1967.55  5225.3 1980.22  5241.1 1987.98
  5246.9 1998.24  5250.5 2000.39  5268.5 2006.43  5327.5 2017.01  5394.5 2022.94
#Mann= 6 ,-1 , 0
  4364.8      .1       0  4470.3     .07       0  4644.3      .1       0
  4688.3     .07       0  4994.2     .05       0  5015.9      .1       0
Bank Sta=4994.2,5015.9
XS Rating Curve= 0 ,0
Exp/Cntr=0.3,0.1

Type RM Length L Ch R = 1 ,90700   ,579,579,579
BEGIN DESCRIPTION:
Turtle Creek 147.0
END DESCRIPTION:
XS GIS Cut Line= 3
        1890575.     13904225.01        1890675.       13903475.
      1890775.01     13903074.96
#Sta/Elev= 30
  4248.8  1899.8  4329.5 1886.78    4380 1873.77  4441.7 1863.82  4450.6 1861.77
  4460.7 1855.57  4490.9 1855.96  4541.4 1845.44  4581.7 1841.04  4672.9 1836.91
  4753.2 1835.47  4833.9 1838.08  4884.4 1837.38  4895.1 1835.47  4944.1 1817.23
  4944.6 1816.73  4965.9 1817.23  5037.7 1818.65    5057 1820.23  5064.7 1826.05
  5087.9 1829.78  5098.2 1834.68  5105.9 1841.67  5111.1 1840.14  5118.8 1848.45
  5139.4 1864.68  5147.2 1908.81  5201.3  1926.8  5345.6 1957.26  5417.8 1974.73
#Mann= 6 ,-1 , 0
  4248.8     .07       0  4672.9      .1       0  4895.1     .07       0
  4944.1     .05       0  4965.9     .07       0  5037.7      .1       0
Bank Sta=4944.1,4965.9
XS Rating Curve= 0 ,0
Exp/Cntr=0.3,0.1

Type RM Length L Ch R = 1 ,90121   ,409,409,409
BEGIN DESCRIPTION:
Turtle Creek 146.0
END DESCRIPTION:
XS GIS Cut Line= 3
      1890775.01     13904174.98        1891175.       13903575.
        1891375.       13903225.
#Sta/Elev= 30
  4284.4 1888.16  4312.9 1886.11    4385 1870.44  4415.1 1868.97  4457.1 1862.63
  4508.2 1849.09  4580.3 1839.73  4664.3 1835.24  4910.8 1829.98  4940.9 1827.88
  4976.9 1818.65  5002.5 1817.08    5003 1816.58  5024.3 1817.08  5041.5 1817.54
  5063.1 1817.73  5086.1 1828.96    5094 1831.08  5099.8 1829.34  5109.1 1833.11
  5115.6 1839.44  5121.4 1840.95  5131.5 1849.88  5137.2 1861.24  5143.7 1919.62
  5196.2 1944.69  5255.3 1970.32  5276.9 1977.75  5304.9 1980.52  5408.6 1984.15
#Mann= 5 ,-1 , 0
  4284.4     .07       0  4664.3    .035       0  5002.5    .035       0
  5024.3    .035       0  5041.5      .1       0
Bank Sta=5002.5,5024.3
XS Rating Curve= 0 ,0
Exp/Cntr=0.3,0.1

Type RM Length L Ch R = 1 ,89712   ,696,696,696
BEGIN DESCRIPTION:
Turtle Creek 145.0
END DESCRIPTION:
XS GIS Cut Line= 3
      1890875.01     13904274.99      1891470.12     13903819.62
      1891575.01     13903524.98
#Sta/Elev= 30
  4250.8 1887.36  4293.4 1883.05  4322.4 1874.49  4343.3 1874.32  4364.1 1870.88
  4486.6 1859.58  4607.1 1834.56  4742.8 1829.73  4800.4 1828.58    4871 1826.77
  4955.8  1817.9  4994.3 1817.45  4994.8 1816.95  5016.1 1817.45  5047.5 1819.35
  5056.1 1822.21  5079.4 1841.83    5087 1845.87  5092.3 1856.46  5111.2 1867.56
  5117.8 1894.24  5123.1 1898.79    5143 1906.85  5148.6 1910.91  5174.1  1918.1
  5185.5 1923.49    5205 1928.11  5266.6 1938.04  5271.9  1937.1  5312.9 1940.76
#Mann= 6 ,-1 , 0
  4250.8     .07       0  4742.8    .035       0  4800.4     .07       0
  4955.8      .1       0  4994.3     .05       0  5016.1      .1       0
Bank Sta=4994.3,5016.1
XS Rating Curve= 0 ,0
Exp/Cntr=0.3,0.1

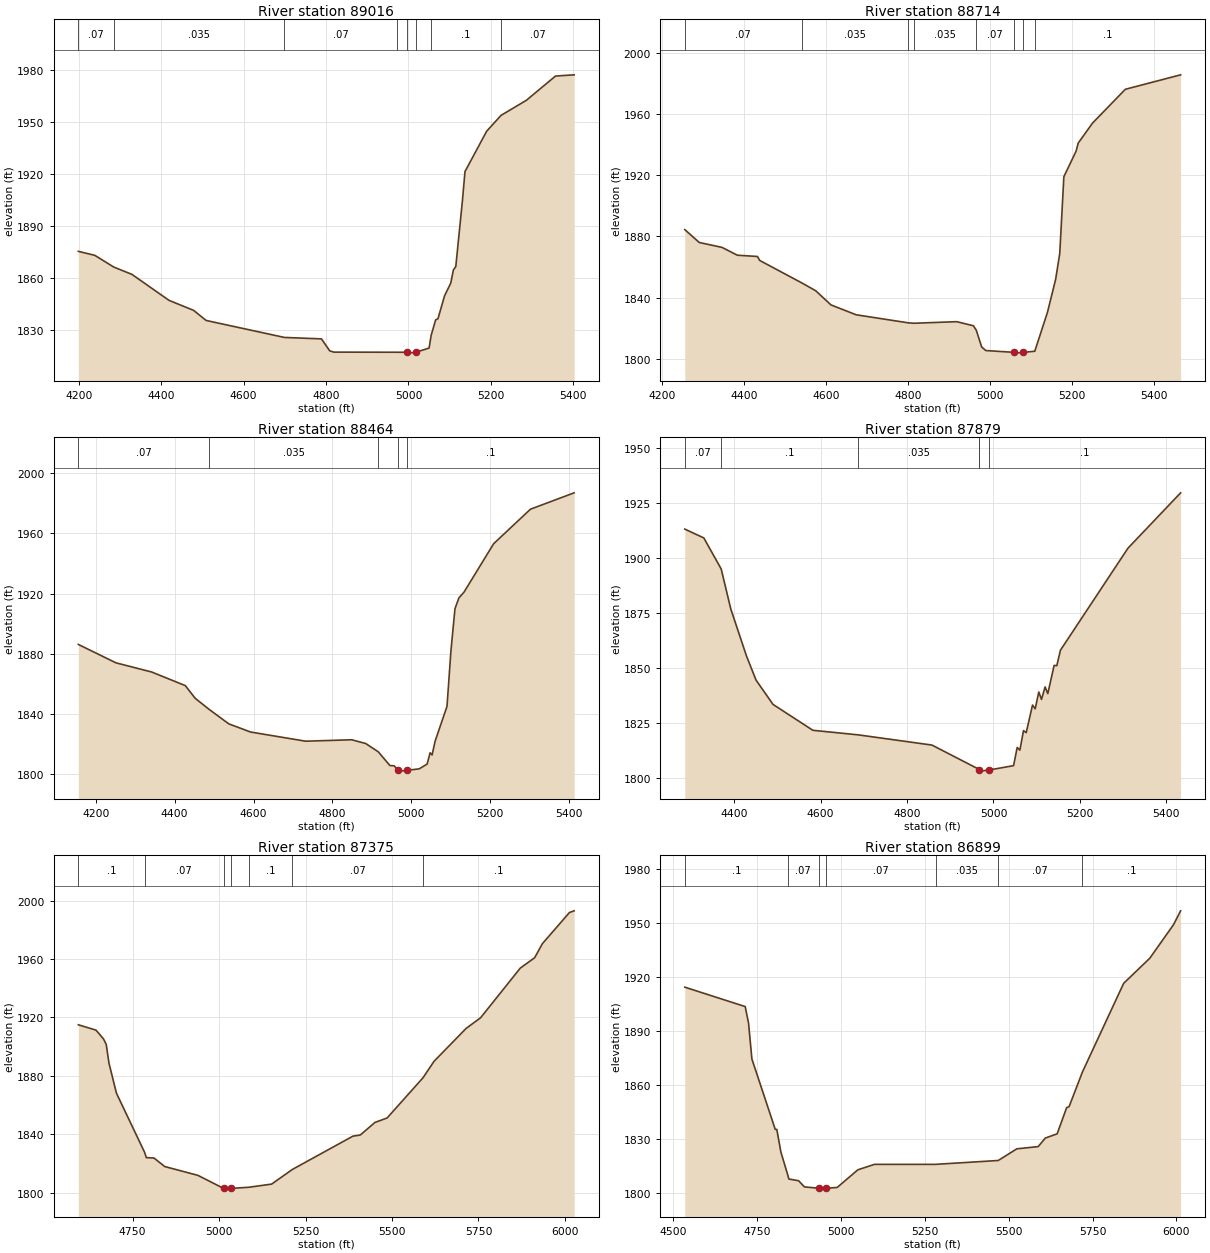
Type RM Length L Ch R = 1 ,89016   ,302,302,302
BEGIN DESCRIPTION:
Turtle Creek 144.0
END DESCRIPTION:
XS GIS Cut Line= 3
      1890974.99       13904375.        1891775.       13904375.
      1892124.98     13904574.99
#Sta/Elev= 30
    4199 1875.49    4239 1873.19  4284.9 1866.45    4329 1862.24    4419 1847.29
    4479 1841.48    4509 1835.71  4699.1 1825.93    4789  1825.1    4809 1818.22
    4819 1817.48  4973.1 1817.41    4996  1817.4  4996.5  1816.9  5017.9  1817.4
  5050.1 1819.82  5055.1 1827.12    5066 1836.02  5071.7 1836.73  5087.6 1849.86
  5102.7 1857.22  5109.1 1864.77  5114.9 1866.76  5130.7 1903.93  5137.2 1921.41
  5189.8 1944.63  5224.7 1953.75  5286.2 1962.44  5356.8 1976.38  5402.1 1977.09
#Mann= 8 ,-1 , 0
    4199     .07       0  4284.9    .035       0  4699.1     .07       0
  4973.1    .033       0    4996    .033       0  5017.9    .033       0
  5055.1      .1       0  5224.7     .07       0
Bank Sta=4996,5017.9
XS Rating Curve= 0 ,0
Exp/Cntr=0.3,0.1

Type RM Length L Ch R = 1 ,88714   ,250,250,250
BEGIN DESCRIPTION:
Turtle Creek 143.1
END DESCRIPTION:
XS GIS Cut Line= 4
      1890946.24     13904492.33      1891623.34      13904639.9
      1891770.91     13904655.09      1892139.85     13904670.28
#Sta/Elev= 30
  4255.5 1884.46  4290.8 1876.05  4346.3 1872.86  4383.8 1867.74  4432.9 1866.92
  4438.5 1864.32    4541  1849.7    4575 1844.59  4612.5  1835.3  4673.9 1828.87
  4801.1 1823.62  4814.9 1823.35  4919.5 1824.37  4960.2  1821.7  4967.2  1818.8
  4980.3 1807.91  4990.4 1805.53  5059.9 1804.35  5060.4 1803.85  5081.8 1804.35
    5110 1805.08    5141 1830.49    5161 1852.09    5171  1868.9    5181 1918.96
    5211 1935.73  5216.1 1940.94  5251.1 1953.98  5331.1 1976.02  5466.1 1985.46
#Mann= 8 ,-1 , 0
  4255.5     .07       0    4541    .035       0  4801.1     .07       0
  4814.9    .035       0  4967.2     .07       0  5059.9     .05       0
  5081.8     .07       0    5110      .1       0
Bank Sta=5059.9,5081.8
XS Rating Curve= 0 ,0
Exp/Cntr=0.3,0.1

Type RM Length L Ch R = 1 ,88464   ,585,585,585
BEGIN DESCRIPTION:
Turtle Creek 143.0
END DESCRIPTION:
XS GIS Cut Line= 3
      1890925.01     13904525.01        1891725.       13904825.
        1892125.       13904775.
#Sta/Elev= 30
  4155.7 1886.23  4250.9 1874.04  4341.7 1867.94  4427.1  1858.9  4452.1  1850.5
  4487.2  1843.2  4537.5 1833.52  4592.7 1828.13  4732.4 1822.05    4849    1823
  4884.6 1820.51  4916.3 1815.04    4946 1805.89  4956.7 1805.74    4967  1802.7
  4967.5  1802.2    4989  1802.7  5020.2 1803.71  5040.3 1806.88  5047.9 1814.35
  5052.9 1812.92  5060.5 1822.01  5090.7 1845.15  5100.8 1882.34  5110.9 1909.89
  5120.9 1917.08  5133.5 1920.76  5209.1 1953.04  5302.3  1975.9  5413.2 1986.77
#Mann= 5 ,-1 , 0
  4155.7     .07       0  4487.2    .035       0  4916.3     .07       0
    4967     .05       0    4989      .1       0
Bank Sta=4967,4989
XS Rating Curve= 0 ,0
Exp/Cntr=0.3,0.1

Type RM Length L Ch R = 1 ,87879   ,504,504,504
BEGIN DESCRIPTION:
Turtle Creek 142.0
END DESCRIPTION:
XS GIS Cut Line= 3
      1890974.99     13905625.01      1891653.36     13905315.92
      1891974.97     13905075.02
#Sta/Elev= 30
  4285.7 1913.27  4329.7 1909.25  4369.9 1895.15  4392.2 1876.91  4428.6 1855.48
  4450.6  1844.6  4489.9 1833.55  4582.1 1821.78  4687.5  1819.7  4857.6 1815.07
  4965.7 1804.13  4967.3 1803.72  4967.8 1803.22  4989.3 1803.72  5046.5 1805.71
  5054.8 1813.97  5061.1 1812.78  5069.4 1821.64  5075.7 1820.72  5090.3 1833.26
  5096.5 1831.55  5104.8 1839.21  5111.1 1835.82  5119.4 1841.51  5125.7 1838.48
  5140.3 1851.29  5146.5 1851.16  5154.9 1858.19  5311.1 1904.57    5433 1929.76
#Mann= 6 ,-1 , 0
  4285.7     .07       0  4369.9      .1       0  4687.5    .035       0
  4965.7      .1       0  4967.3     .05       0  4989.3      .1       0
Bank Sta=4967.3,4989.3
XS Rating Curve= 0 ,0
Exp/Cntr=0.3,0.1

Type RM Length L Ch R = 1 ,87375   ,476,476,476
BEGIN DESCRIPTION:
Turtle Creek 141.0
END DESCRIPTION:
XS GIS Cut Line= 3
      1891174.97     13905975.02        1891525.       13905775.
      1892324.98     13905125.01
#Sta/Elev= 30
  4592.9 1914.91    4644 1911.24  4665.6 1905.26  4673.6 1901.46  4681.5 1888.64
  4703.1 1868.06  4784.7 1827.47  4789.5 1823.92  4811.8 1823.63  4842.7 1817.81
  4938.5 1811.78    5013 1802.83  5013.5 1802.33    5035 1802.83  5085.6  1803.6
  5151.9 1805.77    5212 1815.82  5386.8 1838.59  5408.4 1839.41  5450.7 1848.01
  5485.9 1851.07  5589.9 1878.67  5621.7 1889.93  5714.4 1912.42  5756.2 1919.71
    5871 1953.73  5912.6 1960.86  5934.9 1970.46  6013.2 1991.81  6026.8 1992.97
#Mann= 7 ,-1 , 0
  4592.9      .1       0  4784.7     .07       0    5013     .05       0
    5035     .07       0  5085.6      .1       0    5212     .07       0
  5589.9      .1       0
Bank Sta=5013,5035
XS Rating Curve= 0 ,0
Exp/Cntr=0.3,0.1

Type RM Length L Ch R = 1 ,86899   ,656,656,656
BEGIN DESCRIPTION:
Turtle Creek 140.0
END DESCRIPTION:
XS GIS Cut Line= 4
      1891225.04       13906275.      1891499.28       13906275.
      1891728.71     13906177.77      1892424.97     13905525.03
#Sta/Elev= 30
  4534.5 1914.23  4714.5 1903.46  4724.5 1894.31  4734.5 1874.39  4804.1 1835.35
  4808.7 1835.35    4821 1822.71  4841.6 1809.95  4844.6 1807.83  4873.7 1806.88
    4891 1803.45  4933.7 1802.72  4934.2 1802.22  4955.8 1802.72  4988.7 1803.15
  5050.3 1812.93  5099.7 1815.95  5281.8 1815.96  5468.7  1818.1  5524.1 1824.57
  5587.6  1825.8  5609.1 1830.54  5644.3 1832.88  5672.6  1847.4  5679.9 1847.97
  5719.5 1867.12  5842.6 1916.38  5920.3 1930.24  5991.1 1948.87  6012.3 1956.56
#Mann= 7 ,-1 , 0
  4534.5      .1       0  4841.6     .07       0  4933.7     .05       0
  4955.8     .07       0  5281.8    .035       0  5468.7     .07       0
  5719.5      .1       0
Bank Sta=4933.7,4955.8
XS Rating Curve= 0 ,0
Exp/Cntr=0.3,0.1

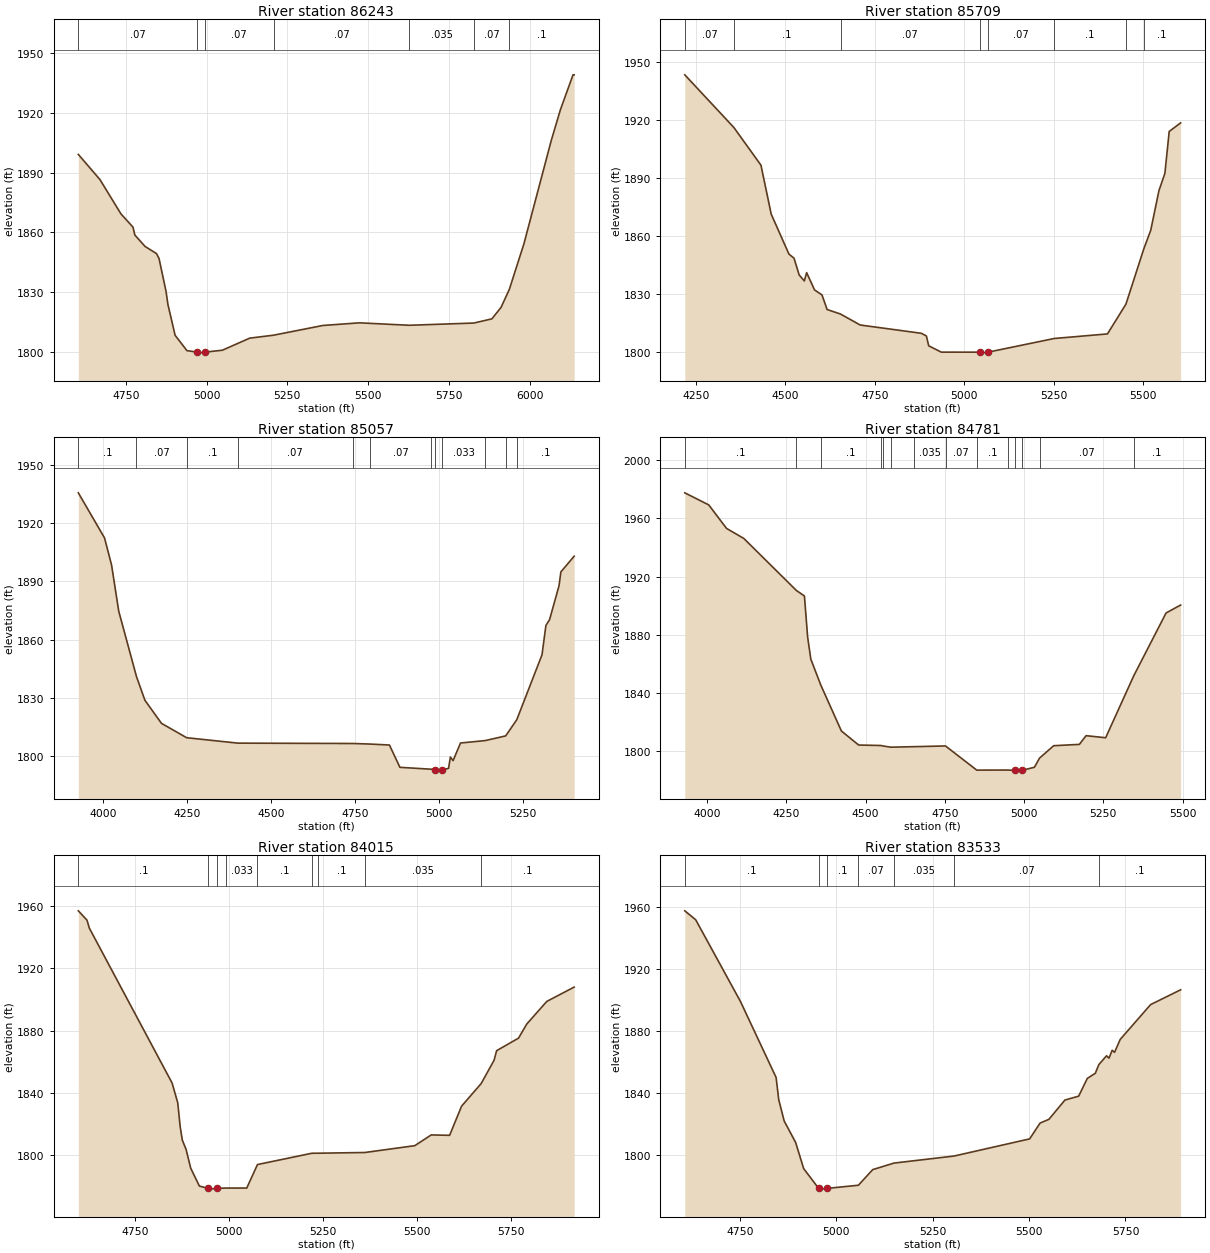
Type RM Length L Ch R = 1 ,86243   ,534,534,534
BEGIN DESCRIPTION:
Turtle Creek 139.0
END DESCRIPTION:
XS GIS Cut Line= 3
      1891574.99     13907075.02        1891775.       13906725.
        1892575.       13905925.
#Sta/Elev= 30
  4603.2 1899.23  4670.2 1886.57    4735 1869.36  4772.4 1862.67  4778.1 1858.71
  4809.8 1852.96  4845.1 1849.38    4853 1846.89  4874.6 1830.43  4880.4 1823.89
  4902.7 1808.31  4939.4 1800.58    4972 1799.84  4972.5 1799.34  4994.6 1799.84
  5048.8 1800.79  5133.6 1806.87  5207.6 1808.36  5359.9 1813.24    5473 1814.57
  5627.2 1813.34  5827.1 1814.46  5883.1 1816.57  5911.4 1822.32    5937 1831.34
  5982.1 1854.22    6067 1906.33  6095.3 1921.78  6134.2 1939.24  6137.7 1939.24
#Mann= 7 ,-1 , 0
  4603.2     .07       0    4972     .05       0  4994.6     .07       0
  5207.6     .07       0  5627.2    .035       0  5827.1     .07       0
    5937      .1       0
Bank Sta=4972,4994.6
XS Rating Curve= 0 ,0
Exp/Cntr=0.3,0.1

Type RM Length L Ch R = 1 ,85709   ,652,652,652
BEGIN DESCRIPTION:
Turtle Creek 138.0
END DESCRIPTION:
XS GIS Cut Line= 3
      1891575.02     13907524.98        1892175.       13907025.
      1892725.04     13906774.98
#Sta/Elev= 30
  4219.5 1943.33  4356.8 1916.06  4432.3 1896.62  4460.9 1871.32  4510.4 1850.67
  4524.7 1848.52    4539 1839.88  4553.4 1836.78  4559.9 1841.07    4582 1832.13
  4602.8 1829.54  4617.1    1822  4654.5 1819.66  4709.6 1813.99  4880.1 1809.71
  4894.4 1808.34  4900.9 1803.24  4936.1 1799.96  5044.1 1799.95  5044.6 1799.45
  5066.7 1799.95  5251.7 1807.02  5400.3 1809.38  5451.9 1824.77  5501.9 1853.38
  5521.2 1862.97  5544.2  1883.5  5560.7 1892.36  5572.8 1914.06  5604.7 1918.49
#Mann= 8 ,-1 , 0
  4219.5     .07       0  4356.8      .1       0  4654.5     .07       0
  5044.1     .05       0  5066.7     .07       0  5251.7      .1       0
  5451.9     .07       0  5501.9      .1       0
Bank Sta=5044.1,5066.7
XS Rating Curve= 0 ,0
Exp/Cntr=0.3,0.1

Type RM Length L Ch R = 1 ,85057   ,276,276,276
BEGIN DESCRIPTION:
Turtle Creek 137.0
END DESCRIPTION:
XS GIS Cut Line= 5
      1891824.98     13908125.02      1892541.74     13907486.25
       1892597.3     13907422.02       1892678.9     13907390.77
      1892829.51     13907079.15
#Sta/Elev= 30
  3925.2 1935.48  4003.4 1912.25  4024.3 1898.35  4045.8 1874.51  4098.6 1840.96
  4123.8 1828.73  4173.1 1816.88  4248.2 1809.48  4401.4 1806.69    4743 1806.51
  4794.9 1806.22  4852.9 1805.72  4884.1 1794.25  4978.3 1793.26  4987.9 1792.79
  4988.4 1792.29  5010.5 1792.79  5029.2 1793.76  5034.6 1799.54  5042.7  1797.7
  5064.8 1806.75  5138.6 1808.01  5199.5 1810.41  5232.6 1818.73  5307.8 1852.13
  5319.5 1867.25  5330.4 1870.24  5358.6  1887.7  5364.1  1894.8  5403.7 1902.86
#Mann= 12 ,-1 , 0
  3925.2      .1       0  4098.6     .07       0  4248.2      .1       0
  4401.4     .07       0    4743    .035       0  4794.9     .07       0
  4978.3    .033       0  4987.9    .033       0  5010.5    .033       0
  5138.6      .1       0  5199.5     .07       0  5232.6      .1       0
Bank Sta=4987.9,5010.5
XS Rating Curve= 0 ,0
Exp/Cntr=0.3,0.1

Type RM Length L Ch R = 1 ,84781   ,766,766,766
BEGIN DESCRIPTION:
Mapping XS e0c6ea53
END DESCRIPTION:
XS GIS Cut Line= 3
       1892645.4     13908640.14      1892749.79     13907700.04
      1892848.14     13907089.69
#Sta/Elev= 30
  3929.8 1977.59  4005.4 1969.29  4061.4 1953.17  4116.1 1946.23  4281.7 1910.55
  4307.2 1906.74  4317.3 1878.55  4327.4 1863.34  4358.8 1845.58  4423.8    1814
  4478.3 1804.36  4548.6 1804.04  4554.9 1803.71    4580 1802.88  4653.5 1803.24
  4752.2 1803.73  4850.8 1787.13  4949.8 1787.18  4970.7 1786.94  4971.2 1786.44
  4993.4 1786.94  5032.7  1789.1  5048.9 1795.39  5093.5  1803.9  5174.5 1804.81
  5195.6 1810.79  5257.4 1809.37  5346.3 1852.04    5448 1895.07  5493.9 1900.52
#Mann= 14 ,-1 , 0
  3929.8      .1       0  4281.7     .07       0  4358.8      .1       0
  4548.6     .07       0  4554.9    .035       0    4580     .07       0
  4653.5    .035       0  4752.2     .07       0  4850.8      .1       0
  4949.8    .033       0  4970.7    .033       0  4993.4    .033       0
  5048.9     .07       0  5346.3      .1       0
Bank Sta=4970.7,4993.4
XS Rating Curve= 0 ,0
Exp/Cntr=0.3,0.1

Type RM Length L Ch R = 1 ,84015   ,482,482,482
BEGIN DESCRIPTION:
Turtle Creek 136.0
END DESCRIPTION:
XS GIS Cut Line= 3
      1893674.98     13908024.99        1893325.       13907825.
      1892874.98     13907024.97
#Sta/Elev= 30
  4597.9 1957.08  4620.9  1951.1  4627.4 1945.88  4847.7 1846.33  4862.8 1833.57
  4869.3 1818.15    4875 1809.55  4885.1 1803.53  4897.3 1791.57  4920.4 1780.03
  4944.2 1778.57  4944.7 1778.07    4967 1778.57  4992.6 1778.77  5046.6 1778.75
  5075.2 1793.88  5219.9 1801.14  5236.8 1801.17  5361.2 1801.63  5494.3 1806.02
    5538 1812.93  5587.1 1812.68    5619 1831.45  5671.1 1845.96  5705.6 1860.99
  5712.3 1867.11  5770.7  1875.2  5792.7 1884.28  5845.9 1898.79  5918.9 1908.03
#Mann= 9 ,-1 , 0
  4597.9      .1       0  4944.2    .033       0    4967      .1       0
  4992.6    .033       0  5075.2      .1       0  5219.9     .07       0
  5236.8      .1       0  5361.2    .035       0  5671.1      .1       0
Bank Sta=4944.2,4967
XS Rating Curve= 0 ,0
Exp/Cntr=0.3,0.1

Type RM Length L Ch R = 1 ,83533   ,577,577,577
BEGIN DESCRIPTION:
Turtle Creek 135.0
END DESCRIPTION:
XS GIS Cut Line= 3
      1893874.98     13907824.97      1893692.34     13907562.68
      1892925.03     13906975.02
#Sta/Elev= 30
    4607 1957.43  4635.3 1951.67  4751.4 1899.04  4843.9 1850.06  4850.7 1835.75
  4864.8 1822.07  4894.5 1808.24  4915.4 1791.35  4954.2 1778.67  4954.7 1778.17
    4977 1778.67  5057.3 1780.67  5094.4 1790.73  5149.5 1794.94  5305.4 1799.48
  5501.5 1810.53  5528.6 1820.73  5551.4 1823.11    5593 1835.55  5628.6 1838.05
  5651.1 1849.49  5671.9 1852.83  5680.9 1858.36    5701 1864.07  5707.3 1862.53
  5715.5  1867.6  5721.8 1866.29  5736.3 1874.58  5815.2 1897.02  5893.1 1906.56
#Mann= 7 ,-1 , 0
    4607      .1       0  4954.2     .05       0    4977      .1       0
  5057.3     .07       0  5149.5    .035       0  5305.4     .07       0
  5680.9      .1       0
Bank Sta=4954.2,4977
XS Rating Curve= 0 ,0
Exp/Cntr=0.3,0.1