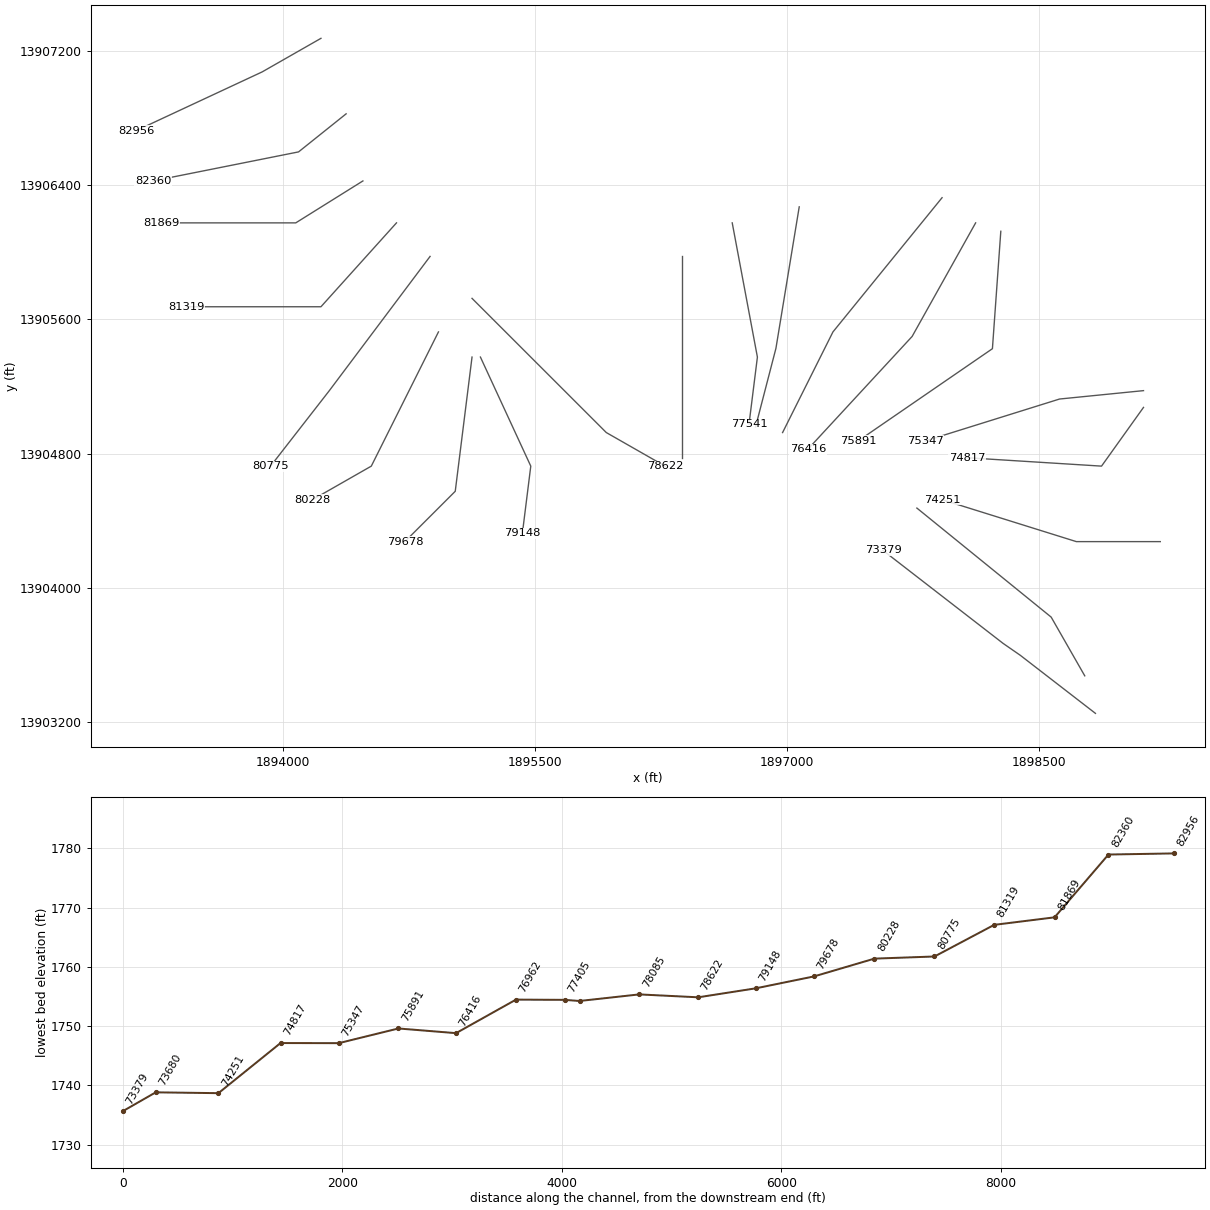
HEC-RAS study Turtle Creek.prj: Turtle Creek Base Level Engineering

--- Turtle Creek.g01 (geometry) --- (continued)

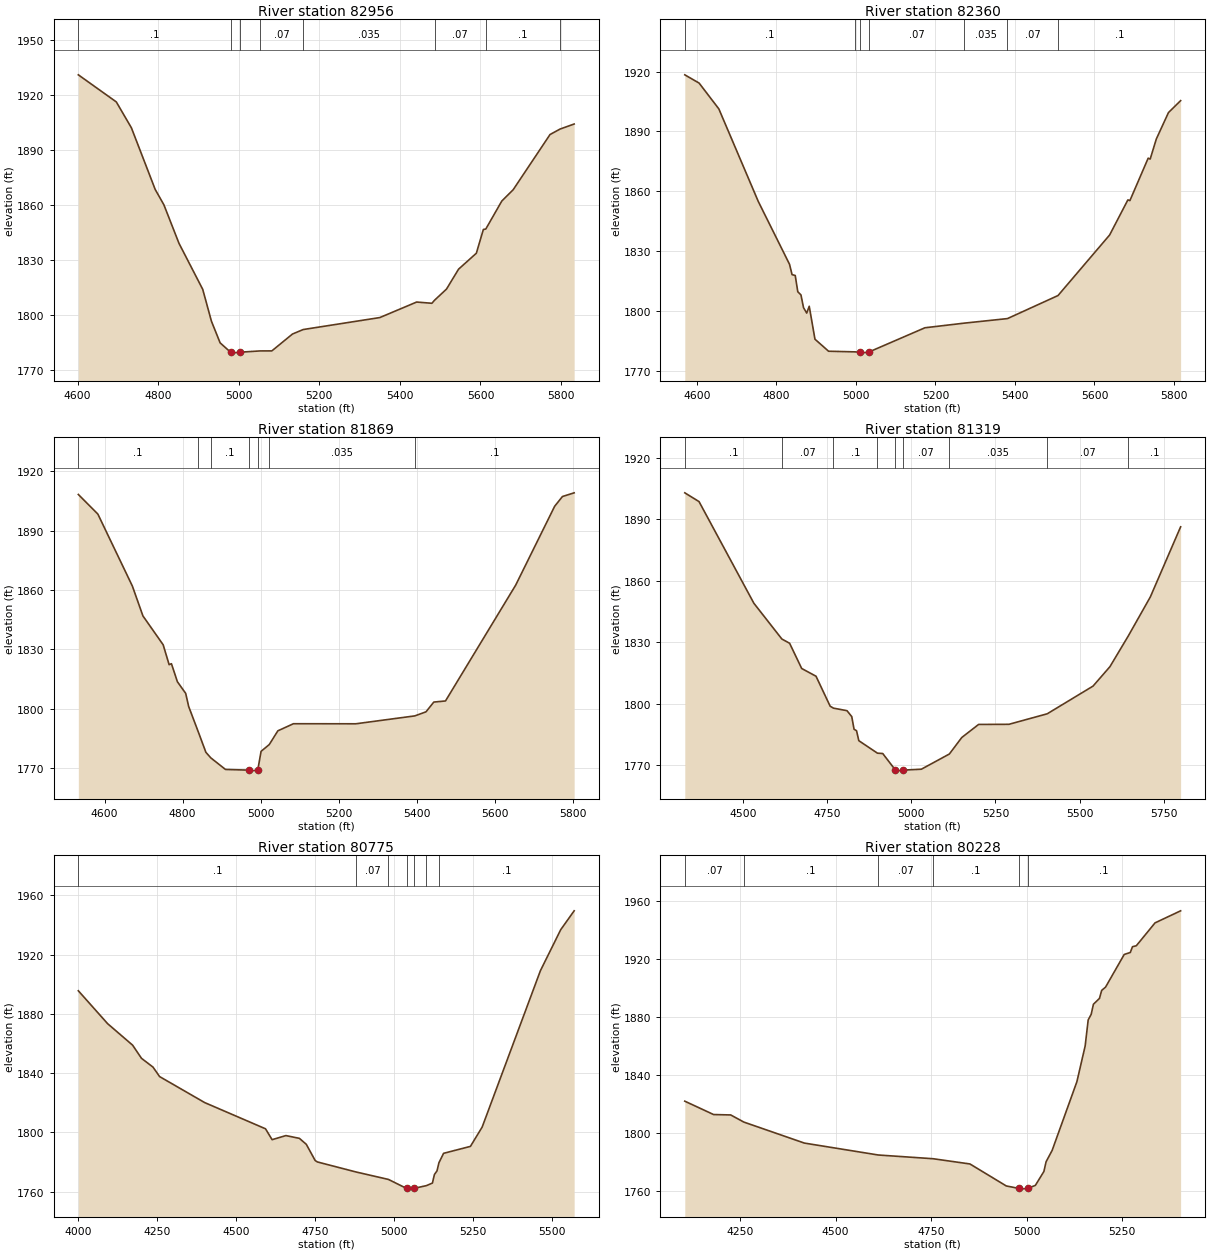
Type RM Length L Ch R = 1 ,82956   ,596,596,596
BEGIN DESCRIPTION:
Turtle Creek 134.0
END DESCRIPTION:
XS GIS Cut Line= 3
      1894225.03     13907275.01        1893875.       13907075.
      1893124.99       13906725.
#Sta/Elev= 30
  4601.7 1931.13    4696 1916.33  4733.5 1902.17  4792.5 1868.55  4814.1 1860.15
  4851.5 1839.15  4910.5 1813.99  4932.1 1796.59  4953.7 1784.76  4979.7 1779.66
  4980.2 1779.16  5002.6 1779.66  5052.7 1780.36  5082.1 1780.38  5133.3 1789.59
  5159.9 1792.04  5350.1 1798.58  5441.5 1807.05  5479.4 1806.38    5486 1808.05
  5515.6 1814.13  5545.6 1825.01  5589.7 1833.71  5607.1 1846.67  5613.2 1846.94
  5652.8 1862.18  5681.1 1868.38  5772.6 1898.52  5797.5 1901.52  5832.5 1904.27
#Mann= 8 ,-1 , 0
  4601.7      .1       0  4979.7     .05       0  5002.6      .1       0
  5052.7     .07       0  5159.9    .035       0    5486     .07       0
  5613.2      .1       0  5797.5     .07       0
Bank Sta=4979.7,5002.6
XS Rating Curve= 0 ,0
Exp/Cntr=0.3,0.1

Type RM Length L Ch R = 1 ,82360   ,491,491,491
BEGIN DESCRIPTION:
Turtle Creek 133.0
END DESCRIPTION:
XS GIS Cut Line= 3
      1894374.97     13906824.98      1894091.59     13906598.08
      1893225.03     13906425.01
#Sta/Elev= 30
  4569.9 1918.37  4605.9 1914.23  4655.5 1901.31  4754.7 1854.93  4833.2 1823.49
  4839.6 1818.29  4847.6 1817.86    4854 1809.72    4862 1808.12  4868.4 1801.77
  4876.4 1799.02  4882.8 1802.43  4897.2 1785.94  4931.4 1779.92  4997.8  1779.6
  5009.2 1779.47  5009.7 1778.97  5032.1 1779.47  5173.7 1791.67  5272.1 1793.98
  5381.2 1796.27  5508.3 1807.81  5638.1 1838.15    5684 1855.72  5689.1 1855.38
    5735 1876.61  5740.1 1876.18  5755.4 1886.18    5786 1899.45  5816.6 1905.44
#Mann= 7 ,-1 , 0
  4569.9      .1       0  4997.8     .07       0  5009.2     .05       0
  5032.1     .07       0  5272.1    .035       0  5381.2     .07       0
  5508.3      .1       0
Bank Sta=5009.2,5032.1
XS Rating Curve= 0 ,0
Exp/Cntr=0.3,0.1

Type RM Length L Ch R = 1 ,81869   ,550,550,550
BEGIN DESCRIPTION:
Turtle Creek 132.0
END DESCRIPTION:
XS GIS Cut Line= 3
        1894475.       13906425.        1894075.       13906175.
        1893275.       13906175.
#Sta/Elev= 30
  4532.5 1908.34  4582.6 1898.42  4671.1    1862  4698.2 1846.89  4750.1 1832.29
  4765.4 1822.23  4771.3 1822.72  4786.6 1813.59  4807.9 1807.69  4815.5 1801.07
  4839.8 1788.43  4859.7 1777.88  4872.3 1775.08  4909.9 1769.22  4969.8 1768.87
  4970.3 1768.37  4992.7 1768.87  5001.2 1778.38  5022.2 1781.81  5044.2 1788.75
  5084.2 1792.35  5244.2 1792.32  5395.4 1796.31  5424.2 1798.37  5444.2 1803.31
  5474.2 1803.87  5654.2 1862.46  5754.2 1902.37  5774.2  1907.3  5804.2 1909.17
#Mann= 7 ,-1 , 0
  4532.5      .1       0  4839.8     .07       0  4872.3      .1       0
  4969.8     .05       0  4992.7      .1       0  5022.2    .035       0
  5395.4      .1       0
Bank Sta=4969.8,4992.7
XS Rating Curve= 0 ,0
Exp/Cntr=0.3,0.1

Type RM Length L Ch R = 1 ,81319   ,544,544,544
BEGIN DESCRIPTION:
Turtle Creek 131.0
END DESCRIPTION:
XS GIS Cut Line= 3
      1894675.02     13906175.02        1894225.       13905675.
      1893425.01       13905675.
#Sta/Elev= 30
  4327.4 1902.88  4369.7  1898.6  4532.6    1849  4615.8 1831.54  4638.7 1829.49
  4674.6 1817.17  4717.2  1813.4  4759.1 1798.79  4768.9 1797.83  4809.1 1796.59
  4823.3 1793.71  4830.1 1787.55  4837.5  1786.8  4844.3 1781.95  4899.6 1775.86
  4915.3 1775.69  4953.1  1767.6  4953.6  1767.1  4976.1  1767.6  5030.1 1768.04
  5113.2 1775.45  5150.1 1783.51  5200.1 1789.88  5290.1 1789.94  5403.9 1795.07
  5540.1  1808.6  5590.1 1818.05  5644.9 1833.11  5710.1 1852.07  5800.1 1886.29
#Mann= 9 ,-1 , 0
  4327.4      .1       0  4615.8     .07       0  4768.9      .1       0
  4899.6     .07       0  4953.1     .05       0  4976.1     .07       0
  5113.2    .035       0  5403.9     .07       0  5644.9      .1       0
Bank Sta=4953.1,4976.1
XS Rating Curve= 0 ,0
Exp/Cntr=0.3,0.1

Type RM Length L Ch R = 1 ,80775   ,547,547,547
BEGIN DESCRIPTION:
Turtle Creek 130.0
END DESCRIPTION:
XS GIS Cut Line= 3
      1894875.02     13905975.02        1894275.       13905175.
      1893925.01     13904725.01
#Sta/Elev= 30
  4000.1 1895.65  4092.8 1873.46    4172 1858.94  4200.1 1850.06  4236.6 1844.12
  4257.4 1837.74  4400.1 1820.19  4592.8 1802.49  4613.7 1795.14  4657.4  1797.9
  4700.1 1796.04    4722 1792.01  4750.1 1781.06  4757.4 1780.09    4880 1773.31
  4982.1 1768.31  5039.3 1762.26  5039.8 1761.76  5062.4 1762.26  5102.4 1764.12
  5121.4 1765.86  5127.7 1771.61  5135.9 1774.08  5141.9  1779.5  5156.7 1785.93
  5241.7 1790.61  5278.8  1803.6  5463.4 1909.23  5527.7 1936.91  5570.2 1949.62
#Mann= 7 ,-1 , 0
  4000.1      .1       0    4880     .07       0  4982.1      .1       0
  5039.3     .05       0  5062.4      .1       0  5102.4     .07       0
  5141.9      .1       0
Bank Sta=5039.3,5062.4
XS Rating Curve= 0 ,0
Exp/Cntr=0.3,0.1

Type RM Length L Ch R = 1 ,80228   ,550,550,550
BEGIN DESCRIPTION:
Turtle Creek 129.0
END DESCRIPTION:
XS GIS Cut Line= 3
      1894924.98     13905524.96        1894525.       13904725.
        1894175.       13904525.
#Sta/Elev= 30
  4105.4 1821.97  4180.8 1812.76  4225.5 1812.49  4259.9 1807.58  4418.4 1793.11
  4611.8  1784.9  4755.1 1782.34  4851.6 1778.73  4946.7 1763.58  4979.8  1761.9
  4980.3  1761.4  5002.9  1761.9  5022.8 1763.99  5045.1 1773.56  5050.9 1780.29
  5066.7 1788.08  5131.5 1835.42  5153.1 1860.01    5161 1877.92  5168.9 1881.82
  5174.7 1888.73  5190.5 1892.75  5196.3 1898.25  5206.4 1900.51  5255.3 1923.02
  5271.2 1924.39  5276.9 1928.34    5287 1929.03    5336 1944.78  5402.9 1953.07
#Mann= 6 ,-1 , 0
  4105.4     .07       0  4259.9      .1       0  4611.8     .07       0
  4755.1      .1       0  4979.8     .05       0  5002.9      .1       0
Bank Sta=4979.8,5002.9
XS Rating Curve= 0 ,0
Exp/Cntr=0.3,0.1

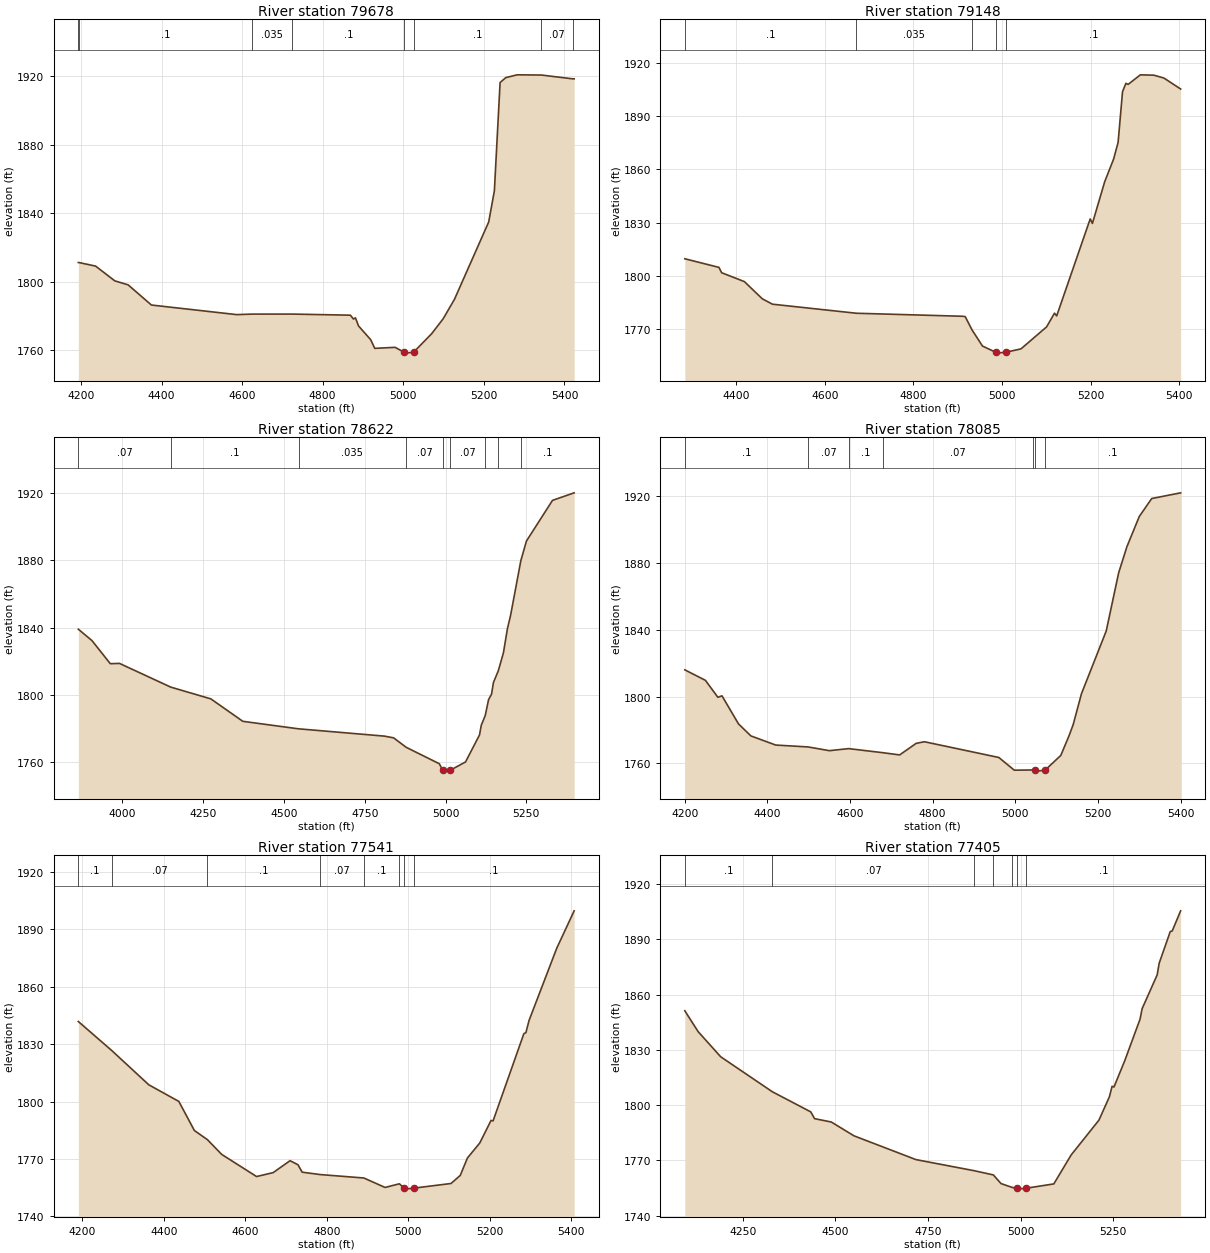
Type RM Length L Ch R = 1 ,79678   ,530,530,530
BEGIN DESCRIPTION:
Turtle Creek 128.0
END DESCRIPTION:
XS GIS Cut Line= 3
        1895125.     13905375.03        1895025.       13904575.
      1894725.02     13904275.02
#Sta/Elev= 30
  4193.6 1811.22  4195.1 1811.22  4236.5 1809.14  4284.3 1800.51  4317.1 1798.22
    4375 1786.44  4586.7 1780.85  4625.5 1781.15    4725 1781.16  4868.8 1780.52
  4876.4 1778.28  4881.4 1778.96    4889 1774.24  4919.2 1766.22  4929.3 1761.17
  4979.7 1761.78  5002.4  1758.9  5002.9  1758.4  5025.6  1758.9  5070.6 1769.77
  5098.9 1778.39  5127.1 1789.79    5212 1834.86  5226.1 1852.98  5240.3 1916.17
  5254.4 1919.03  5282.7 1920.66  5342.8 1920.53  5420.8 1918.32  5424.1 1918.32
#Mann= 8 ,-1 , 0
  4193.6     .07       0  4195.1      .1       0  4625.5    .035       0
    4725      .1       0  5002.4     .05       0  5025.6      .1       0
  5342.8     .07       0  5420.8      .1       0
Bank Sta=5002.4,5025.6
XS Rating Curve= 0 ,0
Exp/Cntr=0.3,0.1

Type RM Length L Ch R = 1 ,79148   ,526,526,526
BEGIN DESCRIPTION:
Turtle Creek 127.0
END DESCRIPTION:
XS GIS Cut Line= 3
      1895174.98     13905375.04        1895475.       13904725.
      1895424.99     13904324.95
#Sta/Elev= 30
  4283.9  1809.6    4361 1804.73    4367 1801.73  4418.4 1796.71  4458.8 1787.02
  4481.7 1783.98  4671.4 1778.87  4911.3 1777.17  4916.8 1776.97  4932.4 1769.41
  4955.8 1760.38  4985.5 1756.89    4986 1756.39  5008.7 1756.89  5042.7 1758.79
  5100.6 1771.21  5118.3 1778.92  5123.3 1777.39  5198.9 1832.04  5203.9 1829.53
  5231.6 1853.01  5251.8 1865.84  5261.9 1875.23  5271.9 1903.82  5279.5  1908.5
  5284.5 1907.91  5312.2  1913.3  5342.5  1913.1  5365.2  1911.5    5403 1905.31
#Mann= 5 ,-1 , 0
  4283.9      .1       0  4671.4    .035       0  4932.4      .1       0
  4985.5     .05       0  5008.7      .1       0
Bank Sta=4985.5,5008.7
XS Rating Curve= 0 ,0
Exp/Cntr=0.3,0.1

Type RM Length L Ch R = 1 ,78622   ,537,537,537
BEGIN DESCRIPTION:
Turtle Creek 126.0
END DESCRIPTION:
XS GIS Cut Line= 3
      1895125.02     13905724.98        1895925.       13904925.
      1896275.04     13904724.98
#Sta/Elev= 30
  3863.4 1839.02  3905.8 1832.23  3962.4 1818.56  3990.7 1818.74  4149.4 1804.68
  4273.5 1797.71  4372.5  1784.4  4544.9 1779.95  4810.9 1775.62  4839.2 1774.59
    4878    1769  4980.6 1759.25  4991.1 1755.37  4991.6 1754.87  5014.3 1755.37
  5061.7 1760.31  5104.9 1776.29  5110.6 1782.16  5122.7  1787.8    5133 1797.23
  5142.3 1800.55  5148.1 1807.42  5163.2 1814.38    5179 1824.98  5191.3 1839.23
  5201.3 1847.34  5232.9 1879.66  5250.3 1891.31  5330.9  1915.4  5397.9 1919.87
#Mann= 9 ,-1 , 0
  3863.4     .07       0  4149.4      .1       0  4544.9    .035       0
    4878     .07       0  4991.1     .05       0  5014.3     .07       0
  5122.7    .033       0  5163.2     .07       0  5232.9      .1       0
Bank Sta=4991.1,5014.3
XS Rating Curve= 0 ,0
Exp/Cntr=0.3,0.1

Type RM Length L Ch R = 1 ,78085   ,544,544,544
BEGIN DESCRIPTION:
Turtle Creek 125.0
END DESCRIPTION:
XS GIS Cut Line= 3
        1896375.     13905974.99        1896375.       13905175.
        1896375.     13904774.99
#Sta/Elev= 30
  4200.2 1816.07  4250.2 1809.75  4280.2 1799.63  4290.2 1800.48  4330.2 1783.66
  4360.2 1776.46  4420.2 1770.99  4498.5 1769.85  4550.2 1767.62  4596.8 1768.85
  4680.5 1766.37  4720.2 1765.07  4760.2 1772.01  4780.2 1772.97  4960.2 1763.54
  4997.7 1755.92    5042 1756.05  5048.6 1755.86  5049.1 1755.36  5071.8 1755.86
  5110.2 1764.77  5130.2 1776.59  5140.2 1783.26  5160.2 1801.74  5220.2 1839.37
  5250.2 1874.16  5270.2 1889.85  5300.2 1907.98  5330.2 1918.71  5400.2 1922.14
#Mann= 7 ,-1 , 0
  4200.2      .1       0  4498.5     .07       0  4596.8      .1       0
  4680.5     .07       0    5042      .1       0  5048.6     .05       0
  5071.8      .1       0
Bank Sta=5048.6,5071.8
XS Rating Curve= 0 ,0
Exp/Cntr=0.3,0.1

Type RM Length L Ch R = 1 ,77541   ,136,136,136
BEGIN DESCRIPTION:
Turtle Creek 124.0
END DESCRIPTION:
XS GIS Cut Line= 3
      1896675.01     13906174.97        1896825.       13905375.
        1896775.     13904975.02
#Sta/Elev= 30
  4190.4 1841.79  4272.1  1826.7  4363.3 1808.75  4437.1 1800.05  4475.2 1784.88
  4507.4 1780.06  4542.2  1772.4  4627.9 1760.82  4668.6 1762.87  4710.1 1769.11
  4729.6 1766.97  4739.8  1763.1  4784.1 1761.85  4891.2 1760.07  4943.3 1755.12
  4978.4 1757.04  4990.2 1754.75  4990.7 1754.25  5013.4 1754.75  5105.1 1757.19
  5127.8 1761.39  5145.4  1770.5  5175.6  1778.3  5203.3  1790.1  5208.4 1789.89
    5284 1835.45    5289 1835.98  5296.6 1842.28  5364.6 1880.03  5407.4  1899.6
#Mann= 8 ,-1 , 0
  4190.4      .1       0  4272.1     .07       0  4507.4      .1       0
  4784.1     .07       0  4891.2      .1       0  4978.4     .07       0
  4990.2     .05       0  5013.4      .1       0
Bank Sta=4990.2,5013.4
XS Rating Curve= 0 ,0
Exp/Cntr=0.3,0.1

Type RM Length L Ch R = 1 ,77405   ,443,443,443
BEGIN DESCRIPTION:
Mapping XS c488dab6
END DESCRIPTION:
XS GIS Cut Line= 3
      1897074.17     13906270.52      1896935.27     13905426.74
      1896814.02     13904959.04
#Sta/Elev= 30
  4093.6 1851.27  4129.6 1839.93  4190.4  1826.3  4329.9 1807.29  4433.6 1796.37
  4443.8  1792.7    4489 1790.87  4550.2 1783.38  4717.4 1770.47    4875 1764.43
  4926.5 1762.15  4947.1 1757.46  4977.1 1755.37  4989.1 1754.94  4989.6 1754.44
  5015.2 1754.94  5089.6 1757.27  5136.5 1773.01  5211.4 1791.87  5239.8 1804.63
  5246.8 1810.23    5252 1809.87  5281.1 1824.14  5322.4 1846.71    5328 1852.39
  5368.6 1870.73  5374.1 1877.12    5404 1894.28  5409.2 1894.56  5431.9  1905.5
#Mann= 7 ,-1 , 0
  4093.6      .1       0  4329.9     .07       0    4875      .1       0
  4926.5     .07       0  4977.1      .1       0  4989.1     .05       0
  5015.2      .1       0
Bank Sta=4989.1,5015.2
XS Rating Curve= 0 ,0
Exp/Cntr=0.3,0.1

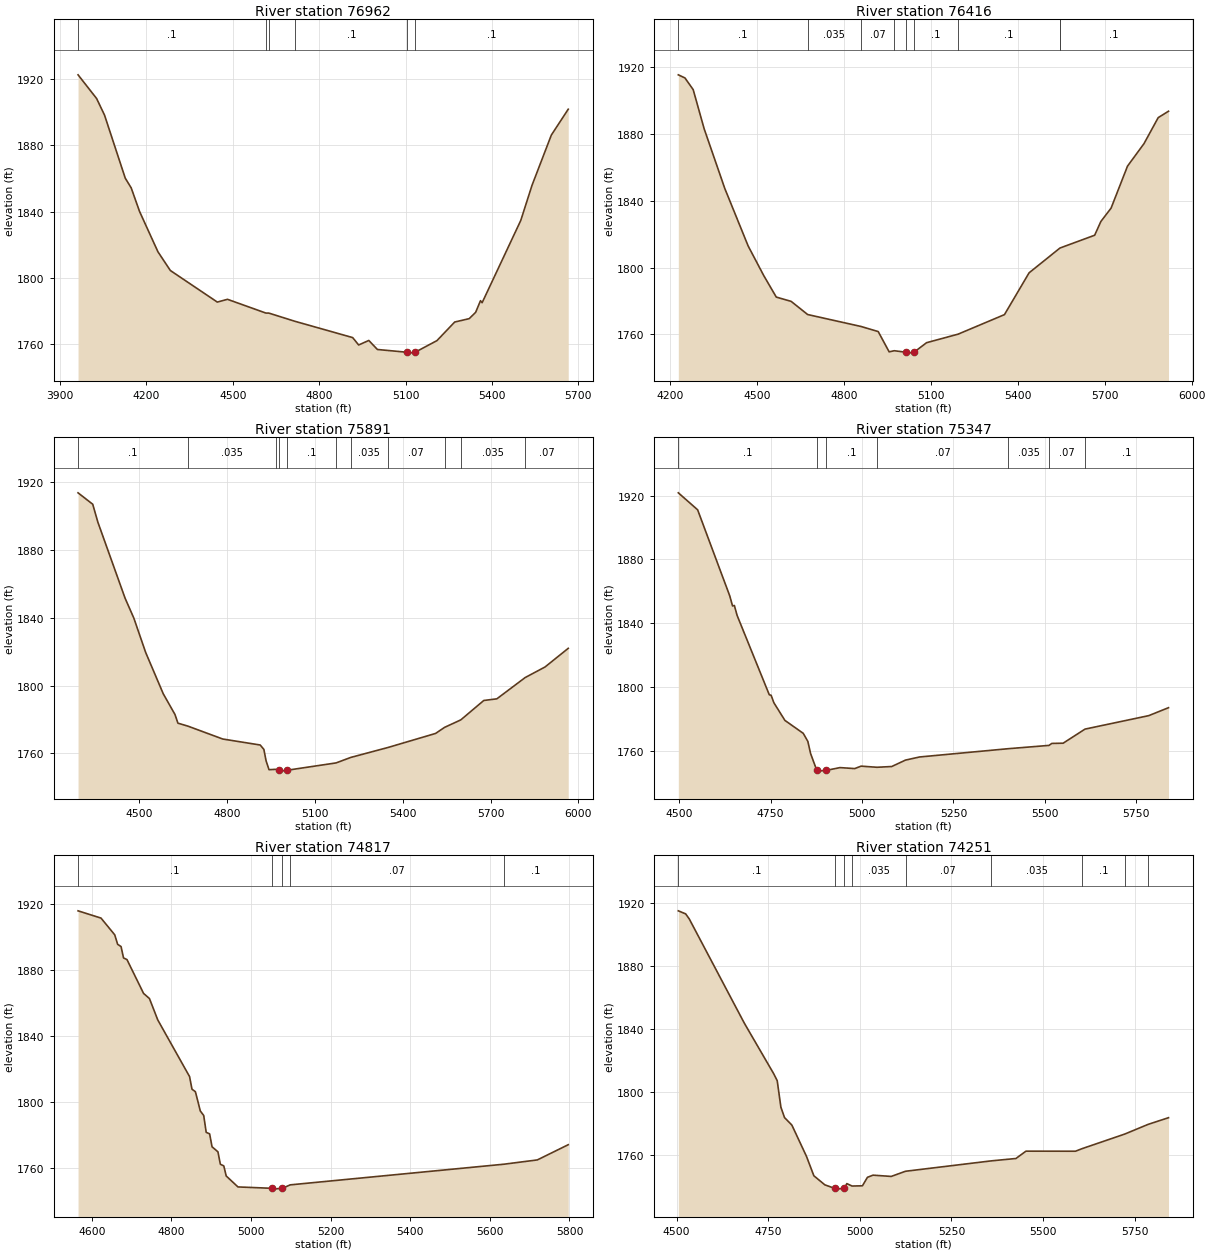
Type RM Length L Ch R = 1 ,76962   ,546,546,546
BEGIN DESCRIPTION:
Turtle Creek 123.0
END DESCRIPTION:
XS GIS Cut Line= 3
      1897925.03     13906325.04        1897275.       13905525.
      1896975.02     13904925.04
#Sta/Elev= 30
  3963.2 1922.65  4027.7 1908.32  4055.2 1898.27    4127 1860.24  4147.8 1854.29
  4176.6 1840.12  4240.5 1815.73  4283.6 1804.41  4446.7 1785.32  4481.9    1787
  4615.3 1778.68  4625.1 1778.69  4716.4  1773.7  4916.5 1763.87  4937.3 1759.41
  4972.5 1762.14  5002.4 1756.68  5106.8 1754.98  5107.3 1754.48  5132.9 1754.98
  5209.2 1762.06  5270.7 1773.28    5321 1775.31  5343.4 1779.14  5360.2 1786.16
  5365.8 1784.91  5499.9 1834.61  5539.1 1855.91  5606.1 1886.24  5664.8 1901.87
#Mann= 6 ,-1 , 0
  3963.2      .1       0  4615.3     .07       0  4625.1    .063       0
  4716.4      .1       0  5106.8     .05       0  5132.9      .1       0
Bank Sta=5106.8,5132.9
XS Rating Curve= 0 ,0
Exp/Cntr=0.3,0.1

Type RM Length L Ch R = 1 ,76416   ,525,525,525
BEGIN DESCRIPTION:
Turtle Creek 122.0
END DESCRIPTION:
XS GIS Cut Line= 3
      1898125.01     13906175.02      1897746.69       13905498.
      1897124.97     13904824.97
#Sta/Elev= 30
  4228.3 1915.22  4251.2 1913.35  4279.6 1906.38  4317.4    1883  4388.7 1847.27
  4469.3  1812.9    4523 1795.23  4566.4 1782.33  4617.8 1779.76  4674.6  1771.9
    4859 1764.75  4918.2 1761.71  4955.9  1749.6  4973.7 1750.25  5015.3 1749.32
  5015.8 1748.82  5041.5 1749.32  5085.1 1755.06  5194.1 1760.17  5353.9 1771.84
  5438.9 1796.83  5544.9 1811.58  5545.2 1811.64  5665.2 1819.31  5686.7 1827.54
  5721.9 1835.52  5778.6 1860.63  5835.3 1874.03  5884.6 1889.64  5920.1 1893.45
#Mann= 9 ,-1 , 0
  4228.3      .1       0  4674.6    .035       0    4859     .07       0
  4973.7      .1       0  5015.3     .05       0  5041.5      .1       0
  5194.1      .1       0  5544.9     .07       0  5545.2      .1       0
Bank Sta=5015.3,5041.5
XS Rating Curve= 0 ,0
Exp/Cntr=0.3,0.1

Type RM Length L Ch R = 1 ,75891   ,544,544,544
BEGIN DESCRIPTION:
Turtle Creek 121.0
END DESCRIPTION:
XS GIS Cut Line= 3
        1898275.     13906124.97        1898225.       13905425.
      1897424.99     13904874.99
#Sta/Elev= 30
  4292.6 1913.51  4342.7 1906.78  4360.2 1896.24    4453  1851.5  4483.1 1839.67
  4523.2 1819.56  4583.3 1795.18  4623.4 1782.94  4633.4 1777.85    4667 1776.14
  4786.3 1768.52  4914.2 1764.99  4926.7 1762.38  4934.2 1755.67  4944.2 1750.45
  4966.9 1750.67  4978.8 1750.11  4979.3 1749.61    5005 1750.11  5173.2 1754.45
  5223.2 1757.68  5350.1 1763.53  5512.6 1771.81  5543.3 1775.39  5598.6 1779.79
    5677 1791.21  5721.6 1792.19  5818.3 1804.72    5886 1810.94  5965.2 1821.93
#Mann= 11 ,-1 , 0
  4292.6      .1       0    4667    .035       0  4966.9      .1       0
  4978.8     .05       0    5005      .1       0  5173.2     .07       0
  5223.2    .035       0  5350.1     .07       0  5543.3      .1       0
  5598.6    .035       0  5818.3     .07       0
Bank Sta=4978.8,5005
XS Rating Curve= 0 ,0
Exp/Cntr=0.3,0.1

Type RM Length L Ch R = 1 ,75347   ,530,530,530
BEGIN DESCRIPTION:
Turtle Creek 120.0
END DESCRIPTION:
XS GIS Cut Line= 3
      1899125.02       13905175.        1898625.       13905125.
      1897824.96     13904874.99
#Sta/Elev= 30
  4497.5 1921.81  4550.3 1911.16  4638.2 1857.11  4645.8 1850.82  4650.8 1851.09
  4658.3 1844.86  4746.3 1795.06  4751.3 1794.77  4758.8 1790.07    4789 1778.98
  4839.2 1770.85  4851.8 1765.76  4859.3 1758.16  4876.2 1747.63  4876.7 1747.13
  4902.7 1747.63  4939.7 1749.34  4979.9 1748.73  4997.5 1750.26  5040.8 1749.55
  5081.2 1750.02  5118.9 1754.06  5157.2 1756.01  5399.4  1761.2  5511.3 1763.28
  5519.1 1764.52    5550 1764.66  5609.8  1773.5  5784.2 1781.96  5838.2 1786.94
#Mann= 7 ,-1 , 0
  4497.5      .1       0  4876.2     .05       0  4902.7      .1       0
  5040.8     .07       0  5399.4    .035       0  5511.3     .07       0
  5609.8      .1       0
Bank Sta=4876.2,4902.7
XS Rating Curve= 0 ,0
Exp/Cntr=0.3,0.1

Type RM Length L Ch R = 1 ,74817   ,566,566,566
BEGIN DESCRIPTION:
Turtle Creek 119.0
END DESCRIPTION:
XS GIS Cut Line= 3
      1899124.99     13905074.99        1898875.       13904725.
      1898074.96       13904775.
#Sta/Elev= 30
  4565.2 1915.73  4622.9 1911.33  4657.4 1901.19  4664.7 1895.44  4673.3 1894.07
  4679.5 1887.18  4688.1 1886.21  4729.9 1865.68  4744.6  1862.6  4765.5 1849.65
  4845.4 1815.33  4851.5 1807.68  4860.1 1806.15  4872.4 1794.51    4881 1791.73
  4887.2 1781.53  4895.8 1780.65  4901.9  1772.8  4916.7 1769.75  4922.8  1762.2
  4931.4 1761.23  4937.5 1755.12    4967 1748.48  5052.1 1747.65  5052.6 1747.15
  5078.7 1747.65  5098.2 1749.73  5635.5 1762.25  5719.2 1764.84  5796.9 1774.05
#Mann= 5 ,-1 , 0
  4565.2      .1       0  5052.1     .05       0  5078.7      .1       0
  5098.2     .07       0  5635.5      .1       0
Bank Sta=5052.1,5078.7
XS Rating Curve= 0 ,0
Exp/Cntr=0.3,0.1

Type RM Length L Ch R = 1 ,74251   ,571,571,571
BEGIN DESCRIPTION:
Turtle Creek 118.0
END DESCRIPTION:
XS GIS Cut Line= 3
      1899225.03       13904275.        1898725.       13904275.
      1897924.98     13904525.01
#Sta/Elev= 30
  4504.5  1914.9  4524.5 1912.98  4534.5 1909.71  4684.5 1843.85  4764.5 1811.92
  4774.5 1807.34  4784.5 1790.58  4794.5 1783.98  4814.5 1779.24  4854.5 1759.37
  4874.5 1747.16  4904.5  1741.4  4931.2 1739.19  4931.7 1738.69  4957.8 1739.19
  4964.5 1742.19  4978.7 1740.65  5007.1 1740.79  5020.8 1746.17    5036 1747.53
  5085.7 1746.73  5124.7    1750    5358 1756.56  5426.2 1758.09  5453.5 1762.73
  5588.6 1762.69    5607 1764.33  5723.3 1773.56  5787.2  1779.7  5842.7 1783.92
#Mann= 9 ,-1 , 0
  4504.5      .1       0  4931.2    .035       0  4957.8      .1       0
  4978.7    .035       0  5124.7     .07       0    5358    .035       0
    5607      .1       0  5723.3     .07       0  5787.2      .1       0
Bank Sta=4931.2,4957.8
XS Rating Curve= 0 ,0
Exp/Cntr=0.3,0.1

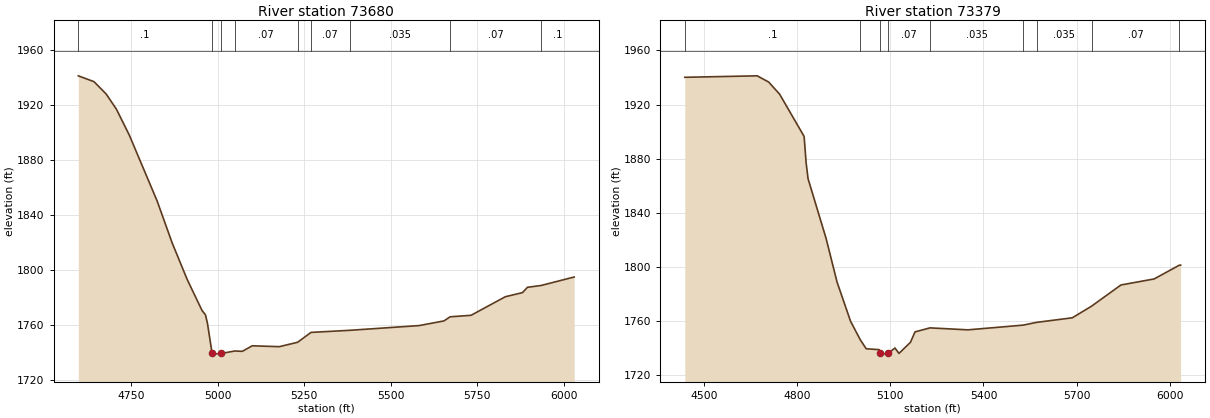
Type RM Length L Ch R = 1 ,73680   ,301,301,301
BEGIN DESCRIPTION:
Turtle Creek 117.0
END DESCRIPTION:
XS GIS Cut Line= 3
      1898774.99     13903475.02        1898575.       13903825.
      1897774.97     13904475.02
#Sta/Elev= 30
  4596.9 1941.15  4642.2 1936.91  4677.5  1927.9    4707 1916.93  4744.4 1898.01
  4825.1 1849.98  4868.3 1819.64  4911.4 1793.28  4954.6 1770.58  4964.7 1767.33
  4970.5 1760.96  4983.8 1739.33  4984.3 1738.83  5010.5 1739.33  5049.6 1741.11
  5071.1 1740.86  5099.8 1744.89  5178.1 1744.25    5231 1747.44  5269.9 1754.63
  5381.1 1756.13  5582.5 1759.58  5654.4 1762.98    5672 1765.95  5732.7 1767.06
  5831.8 1780.56  5881.3 1783.54  5895.7  1787.4  5935.4 1788.74  6030.8 1794.89
#Mann= 9 ,-1 , 0
  4596.9      .1       0  4983.8     .05       0  5010.5      .1       0
  5049.6     .07       0    5231    .035       0  5269.9     .07       0
  5381.1    .035       0    5672     .07       0  5935.4      .1       0
Bank Sta=4983.8,5010.5
XS Rating Curve= 0 ,0
Exp/Cntr=0.3,0.1

Type RM Length L Ch R = 1 ,73379   ,259,259,259
BEGIN DESCRIPTION:
Turtle Creek 116.1
END DESCRIPTION:
XS GIS Cut Line= 4
      1898838.76     13903251.18      1898390.83     13903597.55
      1898289.27     13903667.86      1897573.12     13904222.55
#Sta/Elev= 30
  4438.8 1940.19  4671.6 1941.28  4708.7  1936.7    4744  1927.7  4822.8  1896.5
  4829.2  1877.1  4835.5 1865.24  4893.5 1821.14  4928.8 1788.88  4972.2 1759.95
  5003.7 1746.18  5022.6 1739.61  5064.4 1738.95    5066 1736.14  5066.5 1735.64
  5092.7 1736.14  5115.1 1740.16  5128.1 1736.17  5165.1 1744.41  5179.6 1752.07
  5227.9 1755.04  5349.8 1753.58  5527.5 1757.06  5571.6 1759.13  5685.7 1762.48
  5747.6 1771.04  5842.3 1786.73  5949.2 1791.19  6029.9 1801.32  6034.4  1801.4
#Mann= 9 ,-1 , 0
  4438.8      .1       0  5003.7     .07       0    5066     .05       0
  5092.7     .07       0  5227.9    .035       0  5527.5      .1       0
  5571.6    .035       0  5747.6     .07       0  6029.9      .1       0
Bank Sta=5066,5092.7
XS Rating Curve= 0 ,0
Exp/Cntr=0.3,0.1