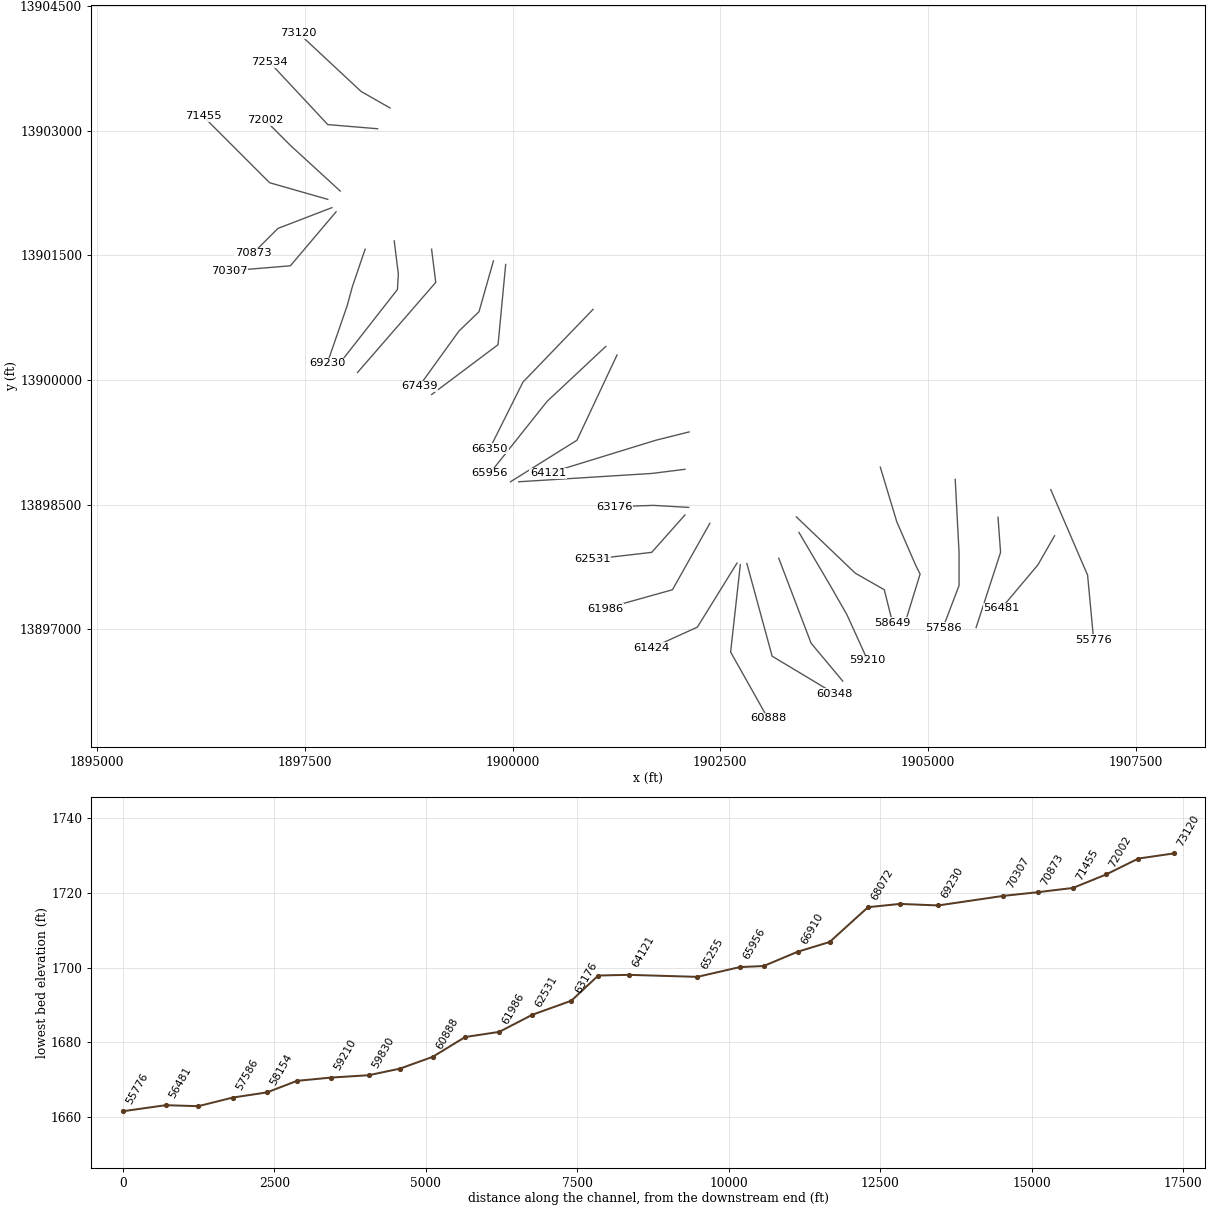
HEC-RAS study Turtle Creek.prj: Turtle Creek Base Level Engineering

--- Turtle Creek.g01 (geometry) --- (continued)

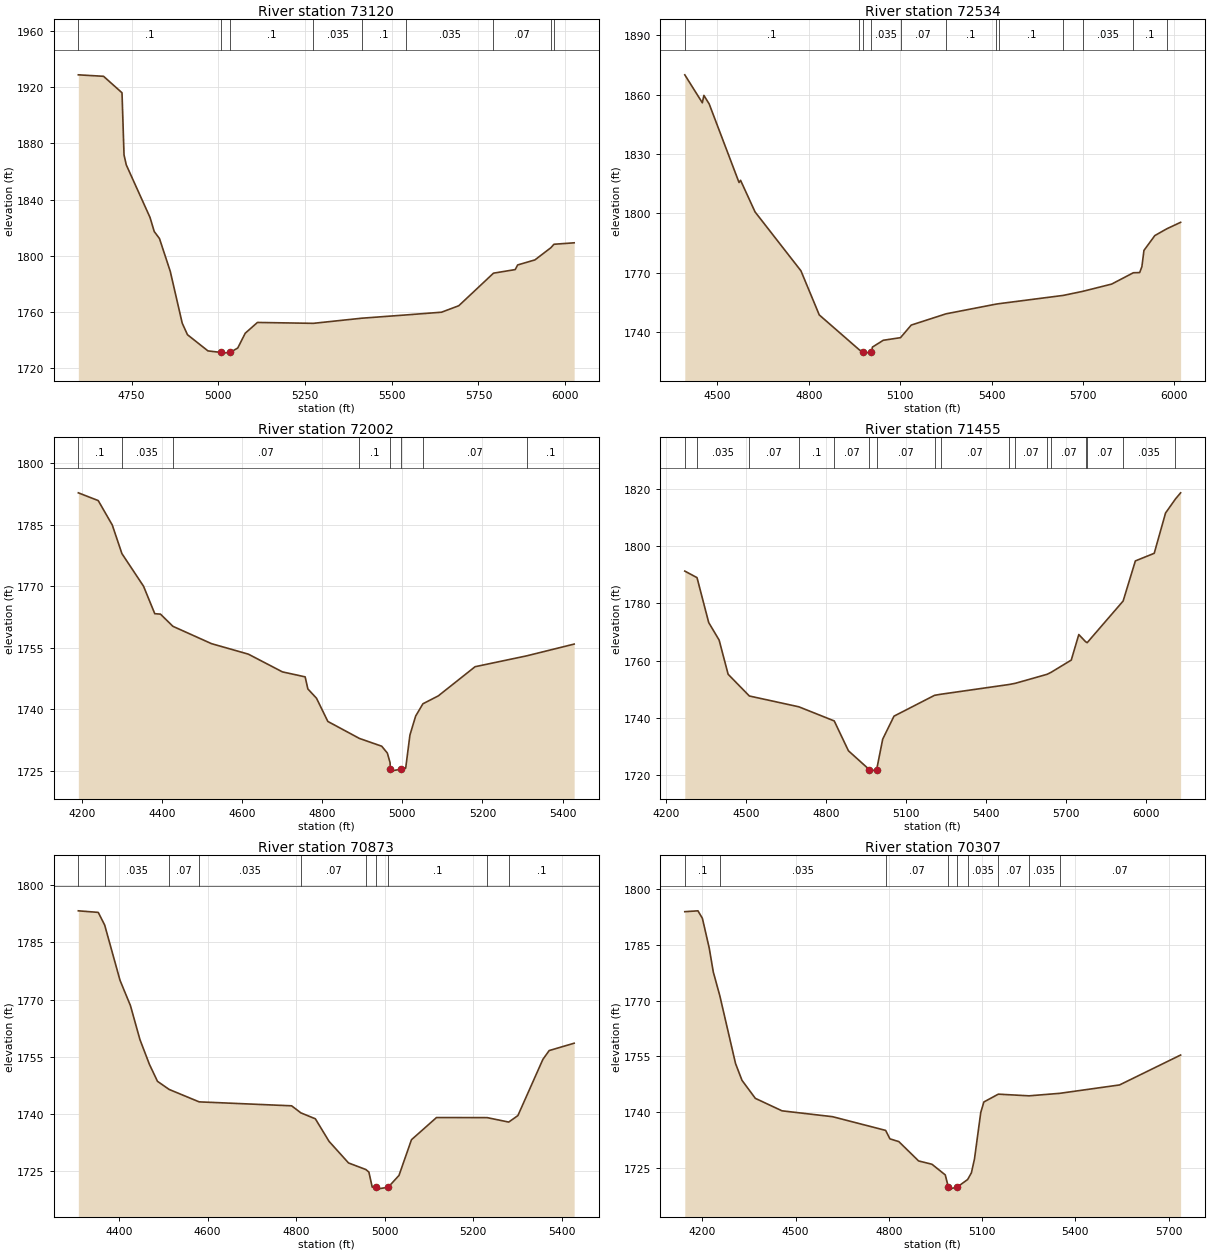
Type RM Length L Ch R = 1 ,73120   ,586,586,586
BEGIN DESCRIPTION:
Turtle Creek 116.0
END DESCRIPTION:
XS GIS Cut Line= 3
      1898524.96     13903275.02        1898175.       13903475.
      1897424.99     13904175.01
#Sta/Elev= 30
  4596.7 1928.77  4669.4 1927.72  4722.6 1915.99  4728.4 1871.74  4734.9 1864.64
  4803.3 1827.24  4815.5  1817.2  4830.6 1812.19  4861.6 1788.89  4896.1 1751.99
  4911.2 1743.75  4970.3 1732.22  5007.7 1731.13  5008.2 1730.63  5034.4 1731.13
  5056.2 1734.29  5077.7 1744.79  5112.9 1752.47  5274.1 1751.84  5413.4 1755.49
  5541.6 1757.83  5643.4 1759.76  5693.2 1764.37  5793.2 1787.56  5855.9 1790.11
  5862.8  1793.4  5912.6    1797  5958.5 1805.66  5967.5 1808.13  6025.7 1809.17
#Mann= 9 ,-1 , 0
  4596.7      .1       0  5007.7     .05       0  5034.4      .1       0
  5274.1    .035       0  5413.4      .1       0  5541.6    .035       0
  5793.2     .07       0  5958.5      .1       0  5967.5    .035       0
Bank Sta=5007.7,5034.4
XS Rating Curve= 0 ,0
Exp/Cntr=0.3,0.1

Type RM Length L Ch R = 1 ,72534   ,532,532,532
BEGIN DESCRIPTION:
Turtle Creek 115.0
END DESCRIPTION:
XS GIS Cut Line= 3
      1898374.95       13903025.        1897775.       13903075.
      1897075.03     13903824.97
#Sta/Elev= 30
    4393 1870.01  4450.6 1855.86  4455.7  1859.6  4473.2 1855.24  4571.1 1815.54
  4576.1 1816.66  4623.7 1800.67  4774.3 1770.89  4834.5 1748.57  4966.2 1730.89
  4979.1 1729.75  4979.6 1729.25  5005.9 1729.75    5009  1732.3  5044.6 1735.75
  5101.2 1737.07  5136.5 1743.44  5250.8 1749.13  5414.7 1754.03  5425.7 1754.28
  5635.8 1758.45  5699.6  1760.5  5794.5 1764.17  5865.7  1769.9  5886.4 1769.99
  5893.7 1772.95  5900.5  1781.2  5936.2 1788.71  5975.3 1792.12  6020.9 1795.41
#Mann= 12 ,-1 , 0
    4393      .1       0  4966.2    .035       0  4979.1    .035       0
  5005.9    .035       0  5101.2     .07       0  5250.8      .1       0
  5414.7     .07       0  5425.7      .1       0  5635.8     .07       0
  5699.6    .035       0  5865.7      .1       0  5975.3     .07       0
Bank Sta=4979.1,5005.9
XS Rating Curve= 0 ,0
Exp/Cntr=0.3,0.1

Type RM Length L Ch R = 1 ,72002   ,547,547,547
BEGIN DESCRIPTION:
Turtle Creek 114.0
END DESCRIPTION:
XS GIS Cut Line= 3
      1897925.03     13902274.97        1897325.       13902825.
      1897025.03     13903124.97
#Sta/Elev= 30
  4190.9 1792.76  4240.6 1790.87  4275.7 1784.92  4299.7 1777.96  4353.7 1770.02
  4381.8 1763.32    4396 1763.22  4427.1 1760.25  4523.6 1756.02  4615.5 1753.47
  4700.6 1749.15  4757.3 1747.94  4764.1    1745  4785.7 1742.73    4814 1737.08
  4892.9 1732.94  4948.5 1731.05  4962.6 1729.38  4969.4 1727.04  4970.1 1725.48
  4970.6 1724.98  4997.1 1725.48  5008.4 1725.71    5019 1733.77  5033.2 1738.37
  5051.4 1741.38  5089.7  1743.3  5181.7 1750.41  5310.7 1753.06  5429.1 1755.92
#Mann= 8 ,-1 , 0
  4190.9      .1       0  4299.7    .035       0  4427.1     .07       0
  4892.9      .1       0  4970.1     .05       0  4997.1      .1       0
  5051.4     .07       0  5310.7      .1       0
Bank Sta=4970.1,4997.1
XS Rating Curve= 0 ,0
Exp/Cntr=0.3,0.1

Type RM Length L Ch R = 1 ,71455   ,582,582,582
BEGIN DESCRIPTION:
Turtle Creek 113.0
END DESCRIPTION:
XS GIS Cut Line= 3
      1897774.96     13902175.01        1897075.       13902375.
      1896275.03     13903174.97
#Sta/Elev= 30
  4270.9 1791.26  4316.7 1788.98  4360.6 1773.28  4399.6 1767.17  4433.4 1755.21
    4513 1747.62  4698.4 1743.85  4831.3 1738.91  4884.5 1728.48  4963.2 1721.87
  4963.7 1721.37  4990.3 1721.87    5013 1732.54  5055.4 1740.58  5207.5 1747.86
  5232.3 1748.25  5485.7 1751.62  5510.2 1752.05  5629.7 1755.21    5645 1755.92
  5720.1 1760.17  5748.4 1769.09  5773.7 1766.61  5779.8 1766.25  5914.6  1780.8
  5960.5 1794.82  6031.2 1797.48  6073.7 1811.56  6110.8 1816.46  6130.2 1818.61
#Mann= 17 ,-1 , 0
  4270.9      .1       0  4316.7    .035       0    4513     .07       0
  4698.4      .1       0  4831.3     .07       0  4963.2     .05       0
  4990.3     .07       0  5207.5    .035       0  5232.3     .07       0
  5485.7    .035       0  5510.2     .07       0  5629.7    .035       0
    5645     .07       0  5773.7    .035       0  5779.8     .07       0
  5914.6    .035       0  6110.8     .07       0
Bank Sta=4963.2,4990.3
XS Rating Curve= 0 ,0
Exp/Cntr=0.3,0.1

Type RM Length L Ch R = 1 ,70873   ,566,566,566
BEGIN DESCRIPTION:
Turtle Creek 112.0
END DESCRIPTION:
XS GIS Cut Line= 3
      1897824.96     13902074.98        1897175.       13901825.
      1896875.03     13901525.03
#Sta/Elev= 30
  4307.9 1793.31  4352.9  1792.9  4367.4 1789.59  4402.1 1775.07  4425.7 1768.41
  4447.1 1759.51  4468.6 1752.98  4486.8 1748.53  4513.2  1746.4  4580.9 1743.14
    4790  1742.1  4810.8 1740.25  4843.6 1738.69  4874.6 1732.76  4918.6 1727.09
  4957.7 1725.37  4964.6 1724.69  4972.1 1720.75    4981 1720.72  4981.5 1720.22
  5008.2 1720.72  5032.6 1723.82  5060.8 1733.19  5117.4 1739.02  5231.8    1739
  5280.6 1737.83  5301.3 1739.53  5357.8 1754.29    5372 1756.61  5428.5 1758.54
#Mann= 10 ,-1 , 0
  4307.9      .1       0  4367.4    .035       0  4513.2     .07       0
  4580.9    .035       0  4810.8     .07       0  4957.7      .1       0
    4981     .05       0  5008.2      .1       0  5231.8    .035       0
  5280.6      .1       0
Bank Sta=4981,5008.2
XS Rating Curve= 0 ,0
Exp/Cntr=0.3,0.1

Type RM Length L Ch R = 1 ,70307   ,1077,1077,1077
BEGIN DESCRIPTION:
Turtle Creek 111.0
END DESCRIPTION:
XS GIS Cut Line= 3
      1897875.03     13902025.04        1897325.       13901375.
      1896584.24     13901313.83
#Sta/Elev= 30
  4143.9 1793.97  4186.2  1794.2  4200.5 1792.18  4222.5 1784.17  4235.6 1777.71
  4256.6 1771.31  4307.1 1753.07  4327.9 1748.54  4370.8 1743.69  4456.6 1740.33
  4619.1 1738.75  4789.9 1735.06  4803.7 1732.78  4832.3 1732.04    4896 1726.83
  4938.9 1725.94  4981.7 1723.07  4991.8 1719.74  4992.3 1719.24  5019.1 1719.74
  5053.7 1721.83  5065.7 1723.62  5075.7 1727.38  5095.8 1739.86  5105.8 1742.71
  5152.3 1744.82    5251 1744.37  5349.6 1745.04  5542.2  1747.3  5738.7 1755.36
#Mann= 9 ,-1 , 0
  4143.9      .1       0  4256.6    .035       0  4789.9     .07       0
  4991.8     .05       0  5019.1     .07       0  5053.7    .035       0
  5152.3     .07       0    5251    .035       0  5349.6     .07       0
Bank Sta=4991.8,5019.1
XS Rating Curve= 0 ,0
Exp/Cntr=0.3,0.1

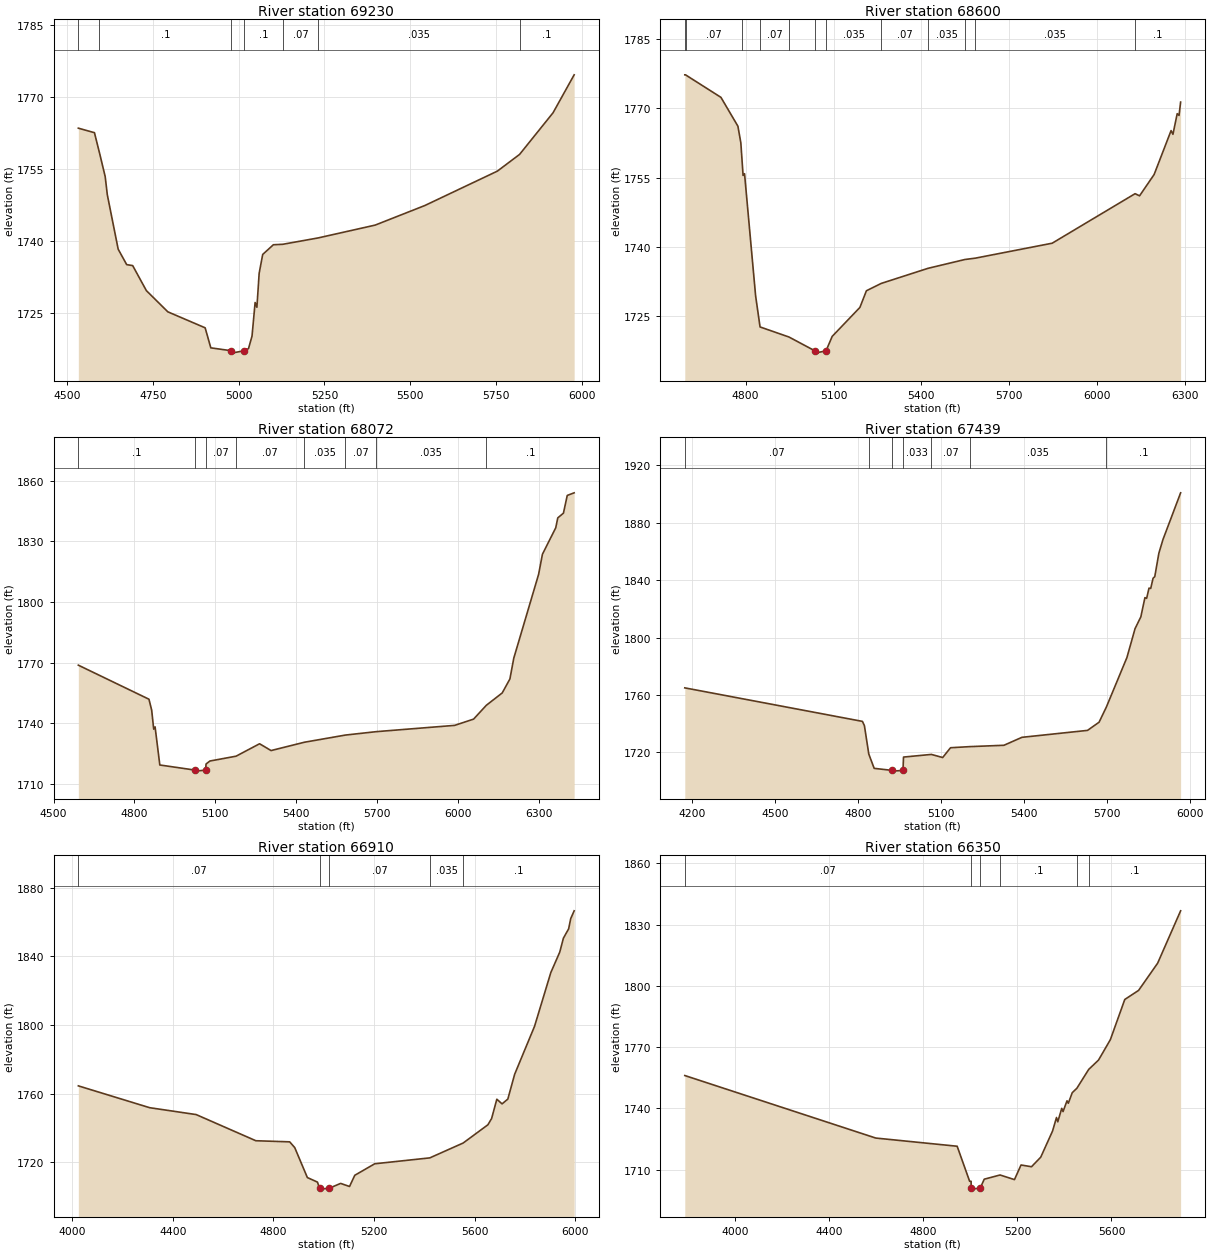
Type RM Length L Ch R = 1 ,69230   ,630,630,630
BEGIN DESCRIPTION:
Turtle Creek 110.0
END DESCRIPTION:
XS GIS Cut Line= 4
        1898225.     13901574.99      1898071.85     13901126.18
        1898008.     13900891.81      1897769.36     13900203.33
#Sta/Elev= 30
  4532.5 1763.52  4579.5 1762.58  4594.1 1758.41  4610.8 1753.45    4617 1749.66
  4648.7 1738.32  4673.5  1735.1    4691  1734.9  4730.9 1729.69  4793.5 1725.27
  4902.3 1721.94  4918.8 1717.77  4978.3 1717.17  4979.3 1716.67  5016.5 1717.17
  5028.7 1717.61    5039 1720.22    5048 1727.21  5053.2 1726.22  5059.8  1733.3
  5070.1 1737.22  5101.2 1739.24  5128.9 1739.34  5231.7 1740.66    5398 1743.33
  5542.6  1747.4  5754.3 1754.57  5819.1 1758.05  5916.8 1766.73  5978.3 1774.63
#Mann= 7 ,-1 , 0
  4532.5    .035       0  4594.1      .1       0  4978.3     .05       0
  5016.5      .1       0  5128.9     .07       0  5231.7    .035       0
  5819.1      .1       0
Bank Sta=4978.3,5016.5
XS Rating Curve= 0 ,0
Exp/Cntr=0.3,0.1

Type RM Length L Ch R = 1 ,68600   ,528,528,528
BEGIN DESCRIPTION:
Turtle Creek 109.0
END DESCRIPTION:
XS GIS Cut Line= 4
      1898575.01     13901674.96        1898625.       13901275.
      1898613.83     13901089.87      1897933.49     13900219.82
#Sta/Elev= 30
  4592.2 1777.24  4594.6 1777.24  4715.6 1772.37  4773.6 1766.13  4783.6 1762.52
  4788.2 1758.27  4791.2 1755.49  4796.2 1755.86    4834 1729.47  4849.2 1722.74
    4948 1720.56  5036.3 1717.58  5037.3 1717.08  5074.5 1717.58  5095.5  1720.7
  5190.1 1726.96  5212.3 1730.56    5263 1732.15  5422.6 1735.41  5548.7 1737.32
  5584.4 1737.61  5846.6 1740.84  6129.8 1751.55    6145 1751.08  6194.8  1755.7
  6252.6 1765.18    6259 1764.38  6273.5 1768.84  6279.8 1768.47  6285.2 1771.35
#Mann= 12 ,-1 , 0
  4592.2      .1       0  4594.6     .07       0  4788.2      .1       0
  4849.2     .07       0    4948    .035       0  5036.3    .035       0
  5074.5    .035       0    5263     .07       0  5422.6    .035       0
  5548.7     .07       0  5584.4    .035       0  6129.8      .1       0
Bank Sta=5036.3,5074.5
XS Rating Curve= 0 ,0
Exp/Cntr=0.3,0.1

Type RM Length L Ch R = 1 ,68072   ,633,633,633
BEGIN DESCRIPTION:
Turtle Creek 108.0
END DESCRIPTION:
XS GIS Cut Line= 3
        1899025.     13901574.99        1899075.       13901175.
      1898133.35     13900090.58
#Sta/Elev= 30
  4591.9 1768.71  4853.9 1751.83    4864 1746.41  4871.5 1737.01  4876.6 1738.13
  4894.2 1719.24  5025.7  1716.7  5026.7  1716.2    5064  1716.7  5065.7 1719.72
    5080 1721.21    5177  1723.6  5264.2 1729.76  5306.9 1726.39  5430.3 1730.51
  5582.7 1734.07  5696.5 1735.75  5987.8 1738.87  6058.1 1741.97  6105.6 1748.85
  6164.4 1754.95  6192.9 1761.89  6207.2 1772.16  6299.3  1813.7  6313.5 1823.67
  6362.9 1836.79  6370.5  1841.7  6391.4 1844.03  6405.6 1852.82  6431.2 1854.11
#Mann= 8 ,-1 , 0
  4591.9      .1       0  5025.7     .05       0    5064     .07       0
    5177     .07       0  5430.3    .035       0  5582.7     .07       0
  5696.5    .035       0  6105.6      .1       0
Bank Sta=5025.7,5064
XS Rating Curve= 0 ,0
Exp/Cntr=0.3,0.1

Type RM Length L Ch R = 1 ,67439   ,529,529,529
BEGIN DESCRIPTION:
Turtle Creek 107.0
END DESCRIPTION:
XS GIS Cut Line= 4
      1899769.41     13901433.73      1899595.62     13900821.87
       1899354.3     13900589.23      1898874.98     13899924.97
#Sta/Elev= 30
  4174.6 1764.93  4815.9 1741.56  4823.1 1738.65    4839 1718.78  4858.4  1708.8
  4924.1 1707.37  4925.1 1706.87  4962.5 1707.37  4964.4 1716.67  5064.9 1718.52
  5105.8 1716.35  5134.1 1723.18  5204.5 1723.96    5327 1724.89    5392 1730.44
  5628.8 1735.28  5670.5 1740.97  5696.8 1751.52  5771.1 1786.08  5800.5 1806.25
  5821.4 1814.48  5836.1 1827.85  5842.3 1827.34  5850.8 1834.45    5857 1834.26
  5865.6  1841.4  5871.7 1842.52  5886.4  1858.8  5901.1 1868.27    5965 1900.93
#Mann= 7 ,-1 , 0
  4174.6     .07       0    4839    .033       0  4924.1    .033       0
  4962.5    .033       0  5064.9     .07       0  5204.5    .035       0
  5696.8      .1       0
Bank Sta=4924.1,4962.5
XS Rating Curve= 0 ,0
Exp/Cntr=0.3,0.1

Type RM Length L Ch R = 1 ,66910   ,560,560,560
BEGIN DESCRIPTION:
Turtle Creek 106.0
END DESCRIPTION:
XS GIS Cut Line= 3
      1899916.98     13901391.11        1899825.       13900425.
      1899024.99     13899824.99
#Sta/Elev= 30
    4025 1764.48  4308.5 1751.74  4493.2 1747.73  4730.5 1732.47  4864.9 1731.82
    4885 1728.48  4935.2    1711  4975.4 1708.33  4983.6 1704.74  4984.6 1704.24
    5022 1704.74  5067.4 1707.58  5102.8 1705.78  5123.6  1712.3  5202.8 1719.02
  5421.9 1722.47  5554.3 1731.13  5652.8 1741.78  5667.4 1745.41  5688.2 1756.68
    5709 1753.97  5731.9 1756.76    5759 1771.22  5838.2 1799.27  5902.8 1830.58
  5938.2 1842.47  5952.8 1850.63  5973.6 1856.08  5981.9 1862.06  5995.5 1866.58
#Mann= 5 ,-1 , 0
    4025     .07       0  4983.6     .05       0    5022     .07       0
  5421.9    .035       0  5554.3      .1       0
Bank Sta=4983.6,5022
XS Rating Curve= 0 ,0
Exp/Cntr=0.3,0.1

Type RM Length L Ch R = 1 ,66350   ,394,394,394
BEGIN DESCRIPTION:
Turtle Creek 105.0
END DESCRIPTION:
XS GIS Cut Line= 3
      1900968.62     13900850.21        1900125.       13899975.
      1899725.01     13899175.02
#Sta/Elev= 30
  3784.4 1756.05    4597 1725.43  4943.5 1721.42  4996.5 1704.27  5002.8 1704.27
  5003.1 1700.92  5004.1 1700.42  5041.7 1700.92  5058.7 1705.29  5126.1 1707.34
  5187.3 1705.08  5215.2 1712.23  5259.9 1711.39  5299.1 1716.06  5349.4 1728.86
  5366.2 1735.49  5371.7 1733.38  5388.5 1739.97  5394.1  1738.4  5410.9 1743.67
  5416.5 1742.48  5433.2 1747.64    5453 1749.83  5503.1 1759.02    5545 1763.61
  5595.4 1773.61  5656.8  1793.3  5715.5 1797.73  5796.6 1811.06  5894.4  1836.7
#Mann= 6 ,-1 , 0
  3784.4     .07       0  5003.1     .05       0  5041.7     .07       0
  5126.1      .1       0    5453     .07       0  5503.1      .1       0
Bank Sta=5003.1,5041.7
XS Rating Curve= 0 ,0
Exp/Cntr=0.3,0.1

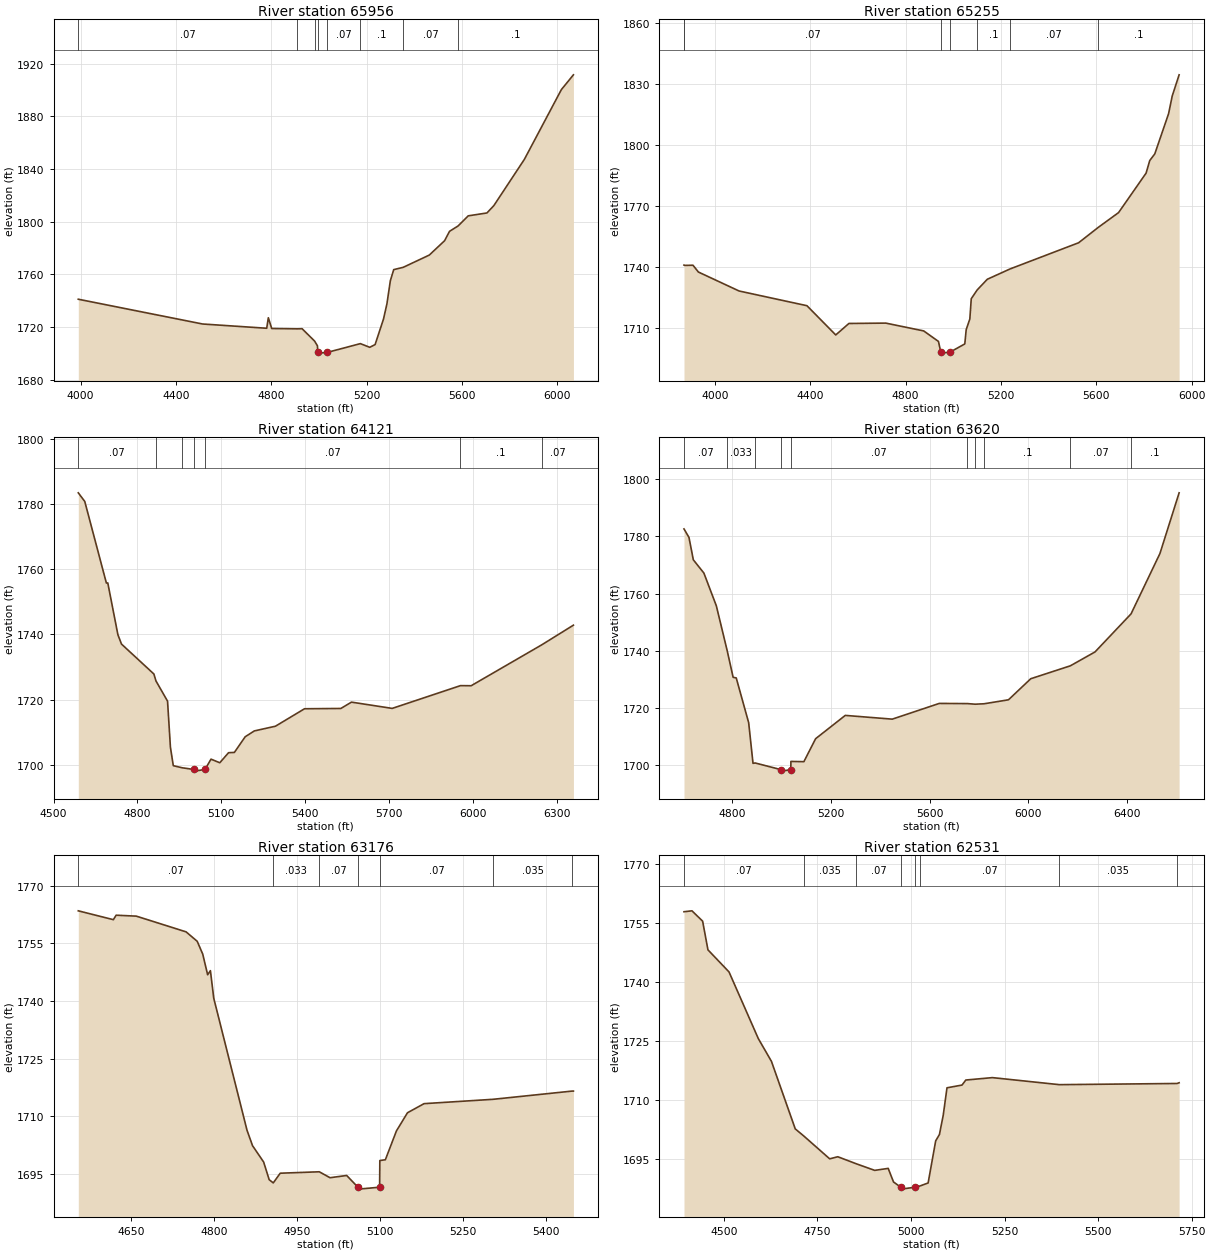
Type RM Length L Ch R = 1 ,65956   ,701,701,701
BEGIN DESCRIPTION:
Turtle Creek 104.0
END DESCRIPTION:
XS GIS Cut Line= 3
      1901122.53     13900404.52      1900414.96     13899742.16
      1899724.98     13898874.97
#Sta/Elev= 30
  3990.7 1741.09  4512.1 1722.27  4781.2 1719.03  4788.1 1727.02  4802.2 1718.84
  4909.4 1718.58  4929.7 1718.69  4982.3 1709.26  4994.1 1705.68  4995.6 1700.63
  4996.6 1700.13  5034.3 1700.63  5174.2 1707.35  5213.5 1704.55    5236 1706.62
  5271.2 1726.01  5285.6 1737.58    5300 1755.18  5314.1 1763.59  5353.9 1765.33
  5463.4 1774.66  5527.5 1785.55  5548.3  1792.7  5584.2 1796.79  5626.8 1804.47
  5705.3 1806.66  5734.1 1812.21  5862.3 1847.39  6017.6 1900.42  6068.1 1911.64
#Mann= 8 ,-1 , 0
  3990.7     .07       0  4909.4      .1       0  4982.3     .07       0
  4995.6     .05       0  5034.3     .07       0  5174.2      .1       0
  5353.9     .07       0  5584.2      .1       0
Bank Sta=4995.6,5034.3
XS Rating Curve= 0 ,0
Exp/Cntr=0.3,0.1

Type RM Length L Ch R = 1 ,65255   ,1134,1134,1134
BEGIN DESCRIPTION:
Turtle Creek 103.0
END DESCRIPTION:
XS GIS Cut Line= 3
       1901257.4     13900301.17        1900775.       13899275.
        1899975.       13898775.
#Sta/Elev= 30
  3870.2 1740.86    3872  1740.7  3907.9 1740.79  3930.7 1737.43  4101.3  1728.1
    4386 1720.86  4506.9 1706.46  4562.1 1712.11  4716.8 1712.29  4875.9 1708.44
  4937.8 1703.27  4947.7 1698.01  4948.7 1697.51  4986.5 1698.01  5048.3 1702.04
  5054.2 1709.08  5069.5 1714.33  5075.4  1724.3  5100.2 1728.61  5142.7 1733.87
  5238.5 1738.97  5525.9 1751.85  5608.7 1759.46  5693.4 1766.69  5808.9 1786.13
  5824.3 1792.32  5845.5 1795.62  5903.3  1815.4  5918.6 1824.12  5947.5 1834.53
#Mann= 7 ,-1 , 0
  3870.2    .035       0    3872     .07       0  4947.7     .05       0
  4986.5     .07       0  5100.2      .1       0  5238.5     .07       0
  5608.7      .1       0
Bank Sta=4947.7,4986.5
XS Rating Curve= 0 ,0
Exp/Cntr=0.3,0.1

Type RM Length L Ch R = 1 ,64121   ,501,501,501
BEGIN DESCRIPTION:
Turtle Creek 102.0
END DESCRIPTION:
XS GIS Cut Line= 3
      1902124.99       13899375.        1901725.       13899275.
      1900425.04     13898875.01
#Sta/Elev= 30
  4588.1 1783.41  4611.3 1780.76  4688.6 1755.75  4693.7 1755.76  4729.8 1739.92
  4742.7 1737.02  4858.7 1727.84  4866.1 1725.72  4907.6 1719.51  4917.9 1705.36
  4928.2 1699.72  4959.9 1699.08  5002.4 1698.55  5003.4 1698.05  5041.5 1698.55
  5063.2 1701.72  5094.6 1700.62    5126  1703.7  5146.9 1703.79  5185.5 1708.59
  5218.2 1710.38    5294 1711.83    5398 1717.18  5528.1 1717.27    5566 1719.21
  5711.9 1717.29    5956 1724.27  5994.4 1724.24    6247 1736.78  6360.5 1742.82
#Mann= 7 ,-1 , 0
  4588.1     .07       0  4866.1      .1       0  4959.9     .07       0
  5002.4     .05       0  5041.5     .07       0    5956      .1       0
    6247     .07       0
Bank Sta=5002.4,5041.5
XS Rating Curve= 0 ,0
Exp/Cntr=0.3,0.1

Type RM Length L Ch R = 1 ,63620   ,444,444,444
BEGIN DESCRIPTION:
Turtle Creek 101.0
END DESCRIPTION:
XS GIS Cut Line= 3
      1902075.03       13898925.        1901675.       13898875.
      1900074.97       13898775.
#Sta/Elev= 30
  4604.9 1782.62  4625.1 1779.65  4642.7 1771.82  4685.6 1767.16  4735.9 1755.73
    4780    1740    4804  1730.7  4816.6 1730.48    4867 1714.82  4884.6 1700.59
  4893.5 1700.72  4998.5 1698.37  4999.5 1697.87  5037.7 1698.37  5038.1 1701.26
  5090.7 1701.18  5138.3 1709.22  5258.5 1717.37  5448.9 1716.06  5639.3 1721.56
  5753.1  1721.5  5784.6 1721.29  5821.2 1721.44  5919.8 1722.83    6010  1730.2
  6170.5 1734.72  6270.5 1739.58  6416.4 1752.89  6533.5 1774.02  6611.2 1795.25
#Mann= 10 ,-1 , 0
  4604.9     .07       0    4780    .033       0  4893.5     .07       0
  4998.5     .05       0  5037.7     .07       0  5753.1      .1       0
  5784.6     .07       0  5821.2      .1       0  6170.5     .07       0
  6416.4      .1       0
Bank Sta=4998.5,5037.7
XS Rating Curve= 0 ,0
Exp/Cntr=0.3,0.1

Type RM Length L Ch R = 1 ,63176   ,645,645,645
BEGIN DESCRIPTION:
Turtle Creek 100.0
END DESCRIPTION:
XS GIS Cut Line= 3
       1902119.7     13898466.07      1901697.84     13898490.81
      1901224.99       13898475.
#Sta/Elev= 30
  4554.5 1763.49  4617.9 1761.19    4623 1762.35  4659.4 1762.11  4749.5 1758.02
  4769.6 1755.57  4779.6 1752.24  4788.5 1746.86  4793.5 1747.93  4799.6 1740.73
  4859.7 1706.44  4869.7 1702.41  4889.8 1698.16  4899.8 1693.57  4907.2 1692.73
  4919.8 1695.25  4990.4 1695.62  5009.9 1694.08    5040 1694.66  5060.4 1691.61
  5061.4 1691.11  5099.6 1691.61    5100 1698.54    5110 1698.75    5130 1706.24
    5150 1710.97    5180 1713.34  5304.9 1714.47  5447.3  1716.6  5450.2 1716.61
#Mann= 7 ,-1 , 0
  4554.5     .07       0  4907.2    .033       0  4990.4     .07       0
  5060.4     .05       0  5099.6     .07       0  5304.9    .035       0
  5447.3     .07       0
Bank Sta=5060.4,5099.6
XS Rating Curve= 0 ,0
Exp/Cntr=0.3,0.1

Type RM Length L Ch R = 1 ,62531   ,545,545,545
BEGIN DESCRIPTION:
Turtle Creek 99.0
END DESCRIPTION:
XS GIS Cut Line= 3
      1902075.02     13898375.02        1901675.       13897925.
      1900958.77     13897842.22
#Sta/Elev= 30
  4393.5 1757.91  4414.8 1758.14  4443.3 1755.51  4457.5 1748.22  4513.9 1742.58
  4592.1 1725.63  4627.2 1719.84  4690.8 1702.66  4714.2  1700.8  4782.8 1695.04
  4804.5 1695.57  4854.4 1693.76  4903.2  1692.1  4939.2 1692.61  4953.4 1689.15
  4972.7 1687.83  4973.7 1687.33  5011.9 1687.83  5024.1 1688.13  5045.9  1688.9
  5066.1 1699.62  5076.1 1701.23  5086.2 1706.11  5096.3 1713.11  5136.5 1713.81
  5146.6 1715.09  5217.7  1715.7  5396.5 1713.91  5711.2 1714.21  5716.6 1714.39
#Mann= 8 ,-1 , 0
  4393.5     .07       0  4714.2    .035       0  4854.4     .07       0
  4972.7    .035       0  5011.9     .07       0  5024.1     .07       0
  5396.5    .035       0  5711.2     .07       0
Bank Sta=4972.7,5011.9
XS Rating Curve= 0 ,0
Exp/Cntr=0.3,0.1

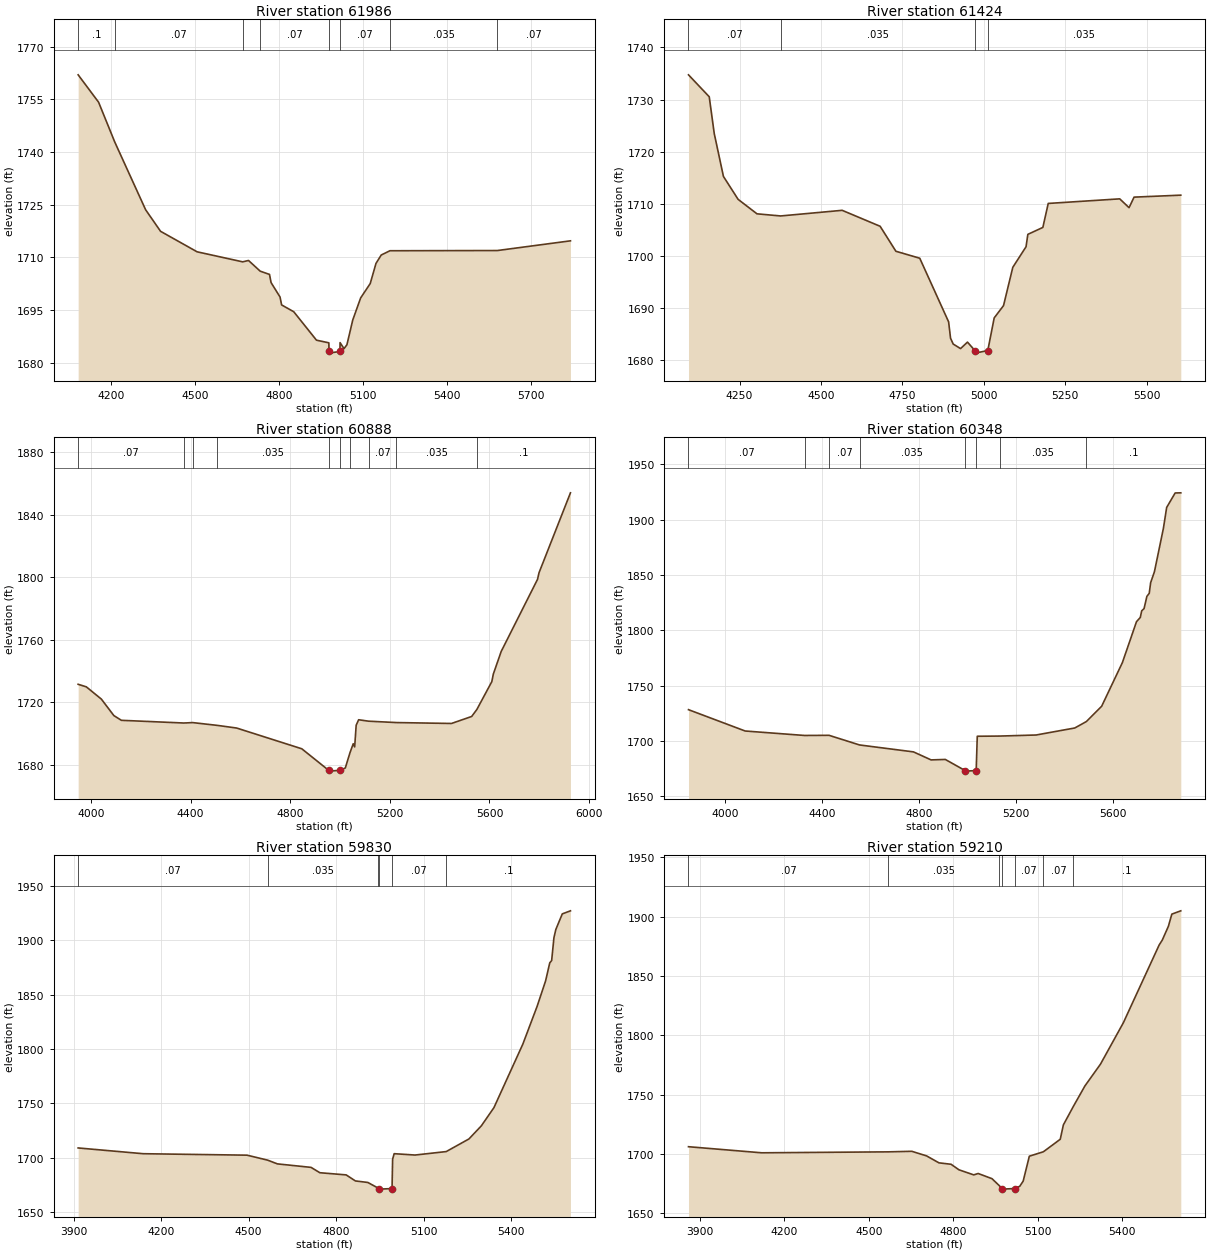
Type RM Length L Ch R = 1 ,61986   ,562,562,562
BEGIN DESCRIPTION:
Turtle Creek 98.0
END DESCRIPTION:
XS GIS Cut Line= 3
      1902374.99     13898274.99        1901925.       13897475.
      1901116.54     13897249.07
#Sta/Elev= 30
  4082.1 1761.96  4155.1 1754.16  4212.5 1742.88    4323 1723.55  4376.3 1717.42
  4506.6 1711.59  4669.5 1708.73  4690.2 1709.12  4731.9 1706.08  4765.1 1705.15
  4770.8 1702.82  4802.7 1698.72  4808.4 1696.47  4851.8 1694.52  4932.7 1686.44
    4977 1685.68  4977.5 1683.25  4978.5 1682.75  5016.7 1683.25    5017 1685.74
  5031.1 1684.02  5041.5 1685.14  5062.3 1692.18  5090.5 1698.46  5124.6 1702.54
  5145.3  1708.3    5164 1710.68    5195 1711.89  5578.6 1711.95  5839.4 1714.71
#Mann= 8 ,-1 , 0
  4082.1      .1       0  4212.5     .07       0  4669.5    .035       0
  4731.9     .07       0  4977.5     .05       0  5016.7     .07       0
    5195    .035       0  5578.6     .07       0
Bank Sta=4977.5,5016.7
XS Rating Curve= 0 ,0
Exp/Cntr=0.3,0.1

Type RM Length L Ch R = 1 ,61424   ,536,536,536
BEGIN DESCRIPTION:
Turtle Creek 97.0
END DESCRIPTION:
XS GIS Cut Line= 3
      1902702.19     13897796.27        1902225.       13897025.
      1901674.39     13896774.66
#Sta/Elev= 30
    4093 1734.75  4156.7 1730.54  4172.1 1723.48  4200.3 1715.26  4245.3 1710.87
  4303.3 1708.09    4376 1707.68  4564.9 1708.76  4681.5  1705.7  4729.9 1700.91
  4803.2 1699.57  4891.8 1687.37  4897.7 1684.23  4905.9 1683.11  4928.5 1682.24
  4949.7 1683.48  4972.5 1681.87  4973.5 1681.37  5012.1 1681.87  5031.8 1688.13
  5060.4 1690.48  5088.9 1697.83  5129.6 1701.78  5135.1 1704.15  5181.2 1705.48
  5197.7 1710.08  5417.3 1710.96  5445.9 1709.27  5461.3 1711.29  5604.8 1711.67
#Mann= 4 ,-1 , 0
    4093     .07       0    4376    .035       0  4972.5    .035       0
  5012.1    .035       0
Bank Sta=4972.5,5012.1
XS Rating Curve= 0 ,0
Exp/Cntr=0.3,0.1

Type RM Length L Ch R = 1 ,60888   ,540,540,540
BEGIN DESCRIPTION:
Turtle Creek 96.0
END DESCRIPTION:
XS GIS Cut Line= 4
      1902741.95     13897777.59        1902675.       13897175.
        1902625.       13896725.      1903074.98     13895925.04
#Sta/Elev= 30
  3948.4 1731.59  3981.2 1729.97  4041.6 1722.12  4091.9 1711.57    4122 1708.56
  4372.9 1706.83  4408.3  1707.1  4507.7 1705.31  4584.9 1703.62  4846.5 1690.35
  4954.5 1676.56  4955.5 1676.06  5000.1 1676.56  5021.2 1678.08  5039.8 1687.77
    5053 1693.57  5058.8 1691.55  5064.8 1705.42  5074.7 1708.92  5114.8    1708
  5225.7 1707.12  5447.6 1706.54  5528.6 1711.01  5549.4 1715.48  5609.5 1733.29
  5615.6 1738.14  5647.1 1752.59  5793.1 1798.74  5799.1 1802.95  5925.3 1854.06
#Mann= 10 ,-1 , 0
  3948.4     .07       0  4372.9    .035       0  4408.3     .07       0
  4507.7    .035       0  4954.5     .05       0  5000.1    .035       0
  5039.8      .1       0  5114.8     .07       0  5225.7    .035       0
  5549.4      .1       0
Bank Sta=4954.5,5000.1
XS Rating Curve= 0 ,0
Exp/Cntr=0.3,0.1

Type RM Length L Ch R = 1 ,60348   ,518,518,518
BEGIN DESCRIPTION:
Turtle Creek 95.0
END DESCRIPTION:
XS GIS Cut Line= 4
      1902820.77     13897790.52        1902975.       13897225.
        1903125.       13896675.      1903874.99       13896225.
#Sta/Elev= 30
  3847.9 1728.42  4081.7 1709.14  4326.7 1705.11  4427.8 1705.24  4553.6 1696.53
  4776.1 1690.27  4848.7 1683.03  4907.4 1683.44  4989.1 1673.39  4990.1 1672.89
  5034.7 1673.39  5039.2  1704.4  5132.5 1704.57  5282.1 1705.53  5441.5 1711.87
  5489.2 1717.67  5552.3  1731.5  5637.8 1770.93  5696.1 1807.93  5711.7 1811.73
  5717.5 1817.72  5727.2  1819.7  5738.9 1830.78  5748.6 1833.54  5754.4 1843.17
    5770 1853.04  5806.9 1892.09  5820.5 1911.12  5855.5 1924.21  5878.8 1924.34
#Mann= 8 ,-1 , 0
  3847.9     .07       0  4326.7    .035       0  4427.8     .07       0
  4553.6    .035       0  4989.1     .05       0  5034.7    .035       0
  5132.5    .035       0  5489.2      .1       0
Bank Sta=4989.1,5034.7
XS Rating Curve= 0 ,0
Exp/Cntr=0.3,0.1

Type RM Length L Ch R = 1 ,59830   ,620,620,620
BEGIN DESCRIPTION:
Turtle Creek 94.0
END DESCRIPTION:
XS GIS Cut Line= 4
      1903204.81     13897853.64        1903425.       13897275.
      1903593.48     13896832.25      1903975.03     13896374.96
#Sta/Elev= 30
  3915.3 1708.96  4138.5 1703.67  4494.6 1702.33  4565.6 1697.72  4598.6 1694.32
  4714.1 1691.11  4744.2  1686.2  4834.5  1684.2  4866.1 1678.65  4908.8 1677.25
  4944.9 1671.96  4946.2 1671.62  4947.2 1671.12  4991.8 1671.62  4993.8 1698.68
  4999.1 1703.69  5070.7 1702.45  5177.7 1705.64  5255.5 1717.23  5298.4  1729.4
  5341.4 1746.09  5440.3 1804.35  5489.8 1839.45  5518.4 1862.52  5532.7 1879.08
  5539.2 1881.19    5547 1902.19  5553.5 1909.76  5575.7 1924.11  5603.7 1926.92
#Mann= 6 ,-1 , 0
  3915.3     .07       0  4565.6    .035       0  4944.9     .07       0
  4946.2     .05       0  4991.8     .07       0  5177.7      .1       0
Bank Sta=4946.2,4991.8
XS Rating Curve= 0 ,0
Exp/Cntr=0.3,0.1

Type RM Length L Ch R = 1 ,59210   ,561,561,561
BEGIN DESCRIPTION:
Turtle Creek 93.0
END DESCRIPTION:
XS GIS Cut Line= 4
      1903447.97     13898164.54        1903825.       13897525.
        1904025.       13897175.      1904275.01     13896624.97
#Sta/Elev= 30
  3859.1 1706.21  4119.4 1701.08  4569.4 1701.88  4652.6 1702.35  4705.2 1698.49
  4749.1 1692.63  4792.3 1691.42  4820.3 1686.78  4872.9 1682.48  4888.7 1683.65
  4937.7  1679.3  4962.8 1673.63  4973.8 1670.99  4974.8 1670.49  5019.5 1670.99
  5036.5  1672.9  5048.6 1677.24  5070.5 1698.22  5120.5 1701.96  5180.4 1712.49
  5191.4 1724.57  5227.1 1740.23  5268.2 1757.45  5323.2 1775.68  5404.5 1810.54
  5531.9  1876.1  5542.9  1880.2  5564.8 1891.89  5576.9 1902.09  5608.8 1904.87
#Mann= 7 ,-1 , 0
  3859.1     .07       0  4569.4    .035       0  4962.8     .07       0
  4973.8     .05       0  5019.5     .07       0  5120.5     .07       0
  5227.1      .1       0
Bank Sta=4973.8,5019.5
XS Rating Curve= 0 ,0
Exp/Cntr=0.3,0.1

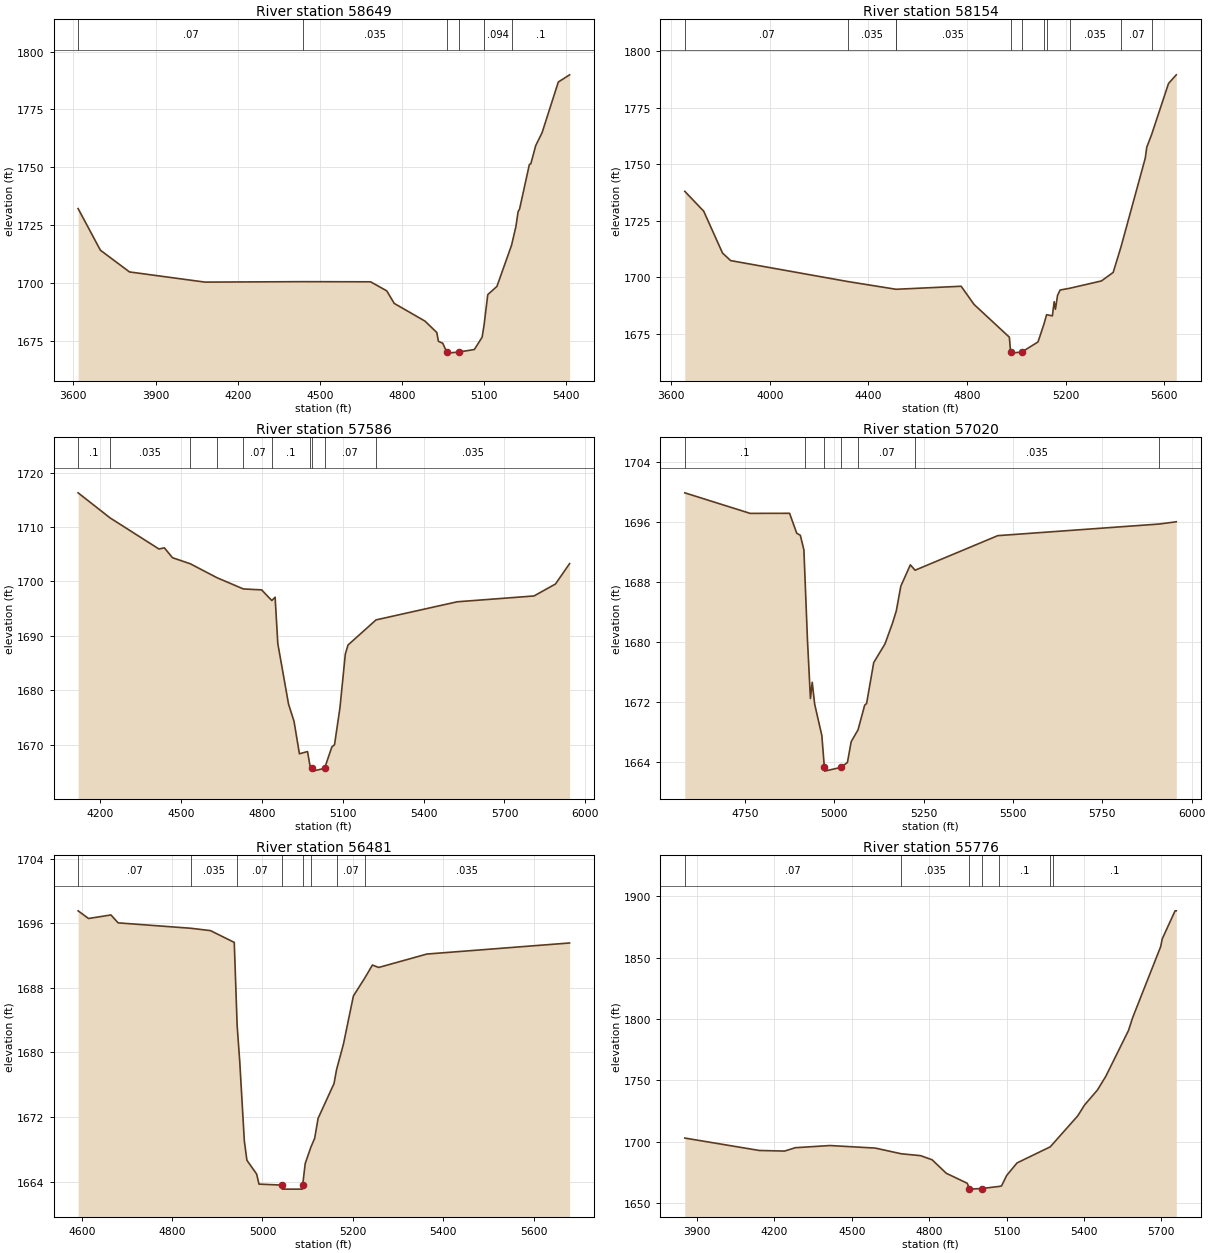
Type RM Length L Ch R = 1 ,58649   ,495,495,495
BEGIN DESCRIPTION:
Turtle Creek 92.0
END DESCRIPTION:
XS GIS Cut Line= 4
      1903416.74     13898352.02        1904125.       13897675.
        1904475.       13897475.        1904575.     13897075.02
#Sta/Elev= 30
  3617.2 1732.12  3698.6 1714.12  3804.9 1704.72  4080.7 1700.32  4438.3 1700.51
  4685.5 1700.45  4744.6 1696.54  4771.9 1691.11  4884.2 1683.46  4927.4 1678.52
  4933.2 1674.72    4949 1673.89  4963.6 1670.11  4964.6 1669.61  5009.3 1670.11
  5064.5 1671.18  5092.9 1676.49  5099.9 1681.71  5113.5 1694.91    5147 1698.47
  5200.5 1716.31  5216.6 1724.53  5224.3 1730.82  5229.5 1731.82  5265.5  1751.2
  5270.7 1751.45  5288.7 1759.37  5311.9 1764.94  5371.2 1786.85  5412.4 1789.96
#Mann= 6 ,-1 , 0
  3617.2     .07       0  4438.3    .035       0  4963.6    .035       0
  5009.3    .035       0  5099.9    .094       0  5200.5      .1       0
Bank Sta=4963.6,5009.3
XS Rating Curve= 0 ,0
Exp/Cntr=0.3,0.1

Type RM Length L Ch R = 1 ,58154   ,568,568,568
BEGIN DESCRIPTION:
Turtle Creek 91.0
END DESCRIPTION:
XS GIS Cut Line= 5
      1904427.14     13898950.97      1904625.05     13898294.76
      1904855.01     13897764.99       1904906.2     13897663.88
        1904725.     13897074.99
#Sta/Elev= 30
  3655.6 1738.11  3732.3 1729.33  3808.7 1710.78  3841.6 1707.46  4316.7 1698.19
  4511.5 1694.78  4512.1 1694.77  4775.9 1696.11  4828.2 1688.07  4971.4 1673.57
  4976.4 1667.02  4977.4 1666.52  5022.1 1667.02  5087.6 1671.48  5112.2 1679.56
  5122.2 1683.52  5145.8 1683.01    5153 1689.28  5158.2 1685.91  5166.7 1692.06
  5177.2 1694.45  5216.1 1695.22  5344.6 1698.46  5392.3 1702.24    5424 1713.56
  5522.4 1752.82  5528.3  1757.6  5548.1 1763.24  5616.6 1785.83    5648 1789.66
#Mann= 11 ,-1 , 0
  3655.6     .07       0  4316.7    .035       0  4511.5     .07       0
  4512.1    .035       0  4976.4    .035       0  5022.1    .035       0
  5112.2    .035       0  5122.2    .094       0  5216.1    .035       0
    5424     .07       0  5548.1      .1       0
Bank Sta=4976.4,5022.1
XS Rating Curve= 0 ,0
Exp/Cntr=0.3,0.1

Type RM Length L Ch R = 1 ,57586   ,566,566,566
BEGIN DESCRIPTION:
Turtle Creek 90.0
END DESCRIPTION:
XS GIS Cut Line= 4
        1905329.     13898804.41        1905375.       13897925.
        1905375.       13897525.      1905182.21       13897019.
#Sta/Elev= 30
  4119.4 1716.28  4237.4 1711.69  4419.2 1705.95  4439.2 1706.17  4469.3 1704.35
  4535.3 1703.24  4633.7 1700.69    4732 1698.61  4799.7 1698.44  4837.5 1696.48
  4849.8 1697.09  4859.8 1688.55  4899.6 1677.43  4919.9 1674.27  4939.9 1668.31
    4970 1668.72  4980.3 1665.77  4987.1 1665.62  4988.1 1665.12    5033 1665.62
    5060 1669.55    5070 1669.98    5090 1676.71    5110 1686.63    5120  1688.3
  5223.8 1692.92  5524.7 1696.25  5809.6 1697.32  5889.2 1699.52  5941.5 1703.27
#Mann= 10 ,-1 , 0
  4119.4      .1       0  4237.4    .035       0  4535.3     .07       0
  4633.7    .035       0    4732     .07       0  4837.5      .1       0
  4980.3     .07       0  4987.1     .05       0    5033     .07       0
  5223.8    .035       0
Bank Sta=4987.1,5033
XS Rating Curve= 0 ,0
Exp/Cntr=0.3,0.1

Type RM Length L Ch R = 1 ,57020   ,539,539,539
BEGIN DESCRIPTION:
Turtle Creek 89.0
END DESCRIPTION:
XS GIS Cut Line= 3
      1905844.17     13898347.45        1905875.       13897925.
      1905580.57     13897019.97
#Sta/Elev= 30
  4581.7 1699.93  4764.6 1697.19  4874.9  1697.2    4895 1694.54    4905 1694.27
    4915 1692.32    4918 1688.72  4925.1 1680.21  4933.3 1672.51  4938.3 1674.67
  4945.1 1671.76  4965.2 1667.57  4972.3 1663.32  4973.3 1662.82  5018.3 1663.32
  5036.8 1663.97  5047.3 1666.74  5066.6 1668.34  5085.1 1671.62  5090.4 1671.83
  5110.4  1677.3    5142 1679.79    5163 1682.56  5173.5 1684.17  5186.2 1687.48
  5212.9 1690.33  5226.1 1689.61  5457.5 1694.22  5909.6 1695.77    5957 1696.07
#Mann= 7 ,-1 , 0
  4581.7      .1       0    4918     .07       0  4972.3     .05       0
  5018.3     .07       0  5066.6     .07       0  5226.1    .035       0
  5909.6     .07       0
Bank Sta=4972.3,5018.3
XS Rating Curve= 0 ,0
Exp/Cntr=0.3,0.1

Type RM Length L Ch R = 1 ,56481   ,705,705,705
BEGIN DESCRIPTION:
Turtle Creek 88.0
END DESCRIPTION:
XS GIS Cut Line= 3
      1906525.02     13898125.03        1906325.       13897775.
      1905884.29     13897251.05
#Sta/Elev= 30
    4592 1697.53  4615.1 1696.58  4664.7 1697.02  4680.6 1696.04  4841.7 1695.37
    4885 1695.08  4937.6 1693.62    4944 1683.34  4949.8 1678.83  4959.9 1669.06
  4965.6 1666.65  4987.2 1664.94  4992.3  1663.7    5043 1663.58    5044 1663.08
    5088 1663.08    5089 1663.58  5094.6 1666.24  5107.2 1668.28  5115.5 1669.36
  5123.2 1671.85  5158.4 1676.15    5164 1677.87  5179.2 1681.02  5201.3 1686.99
  5226.8 1689.24  5243.4 1690.82  5257.3 1690.52  5363.9 1692.18  5679.8 1693.55
#Mann= 8 ,-1 , 0
    4592     .07       0  4841.7    .035       0    4944     .07       0
    5043     .05       0    5089     .07       0  5107.2    .035       0
    5164     .07       0  5226.8    .035       0
Bank Sta=5043,5089
XS Rating Curve= 0 ,0
Exp/Cntr=0.3,0.1

Type RM Length L Ch R = 1 ,55776   ,390,390,390
BEGIN DESCRIPTION:
Turtle Creek 87.0
END DESCRIPTION:
XS GIS Cut Line= 3
      1906479.22     13898680.16      1906922.54     13897650.59
      1906995.74     13896870.78
#Sta/Elev= 30
  3853.3 1703.05    4142 1692.94    4240 1692.45  4281.6 1695.19  4415.6 1696.96
  4591.2 1694.89  4691.8 1690.26  4766.8 1688.72  4811.6 1685.36  4866.4 1674.38
  4947.8 1666.23  4955.6 1661.96  4956.6 1661.46  5004.2 1661.96  5071.1 1663.67
  5080.3 1664.01  5100.4 1672.59  5140.6  1682.8  5269.3 1695.91  5281.5  1698.8
  5375.9 1721.16  5401.7 1729.83  5451.9 1742.14  5484.6 1753.37  5572.5 1790.69
  5588.3    1801    5697 1858.88    5703 1865.19  5752.9 1888.09  5757.5 1888.09
#Mann= 7 ,-1 , 0
  3853.3     .07       0  4691.8    .035       0  4955.6    .035       0
  5004.2    .035       0  5071.1      .1       0  5269.3     .07       0
  5281.5      .1       0
Bank Sta=4955.6,5004.2
XS Rating Curve= 0 ,0
Exp/Cntr=0.3,0.1