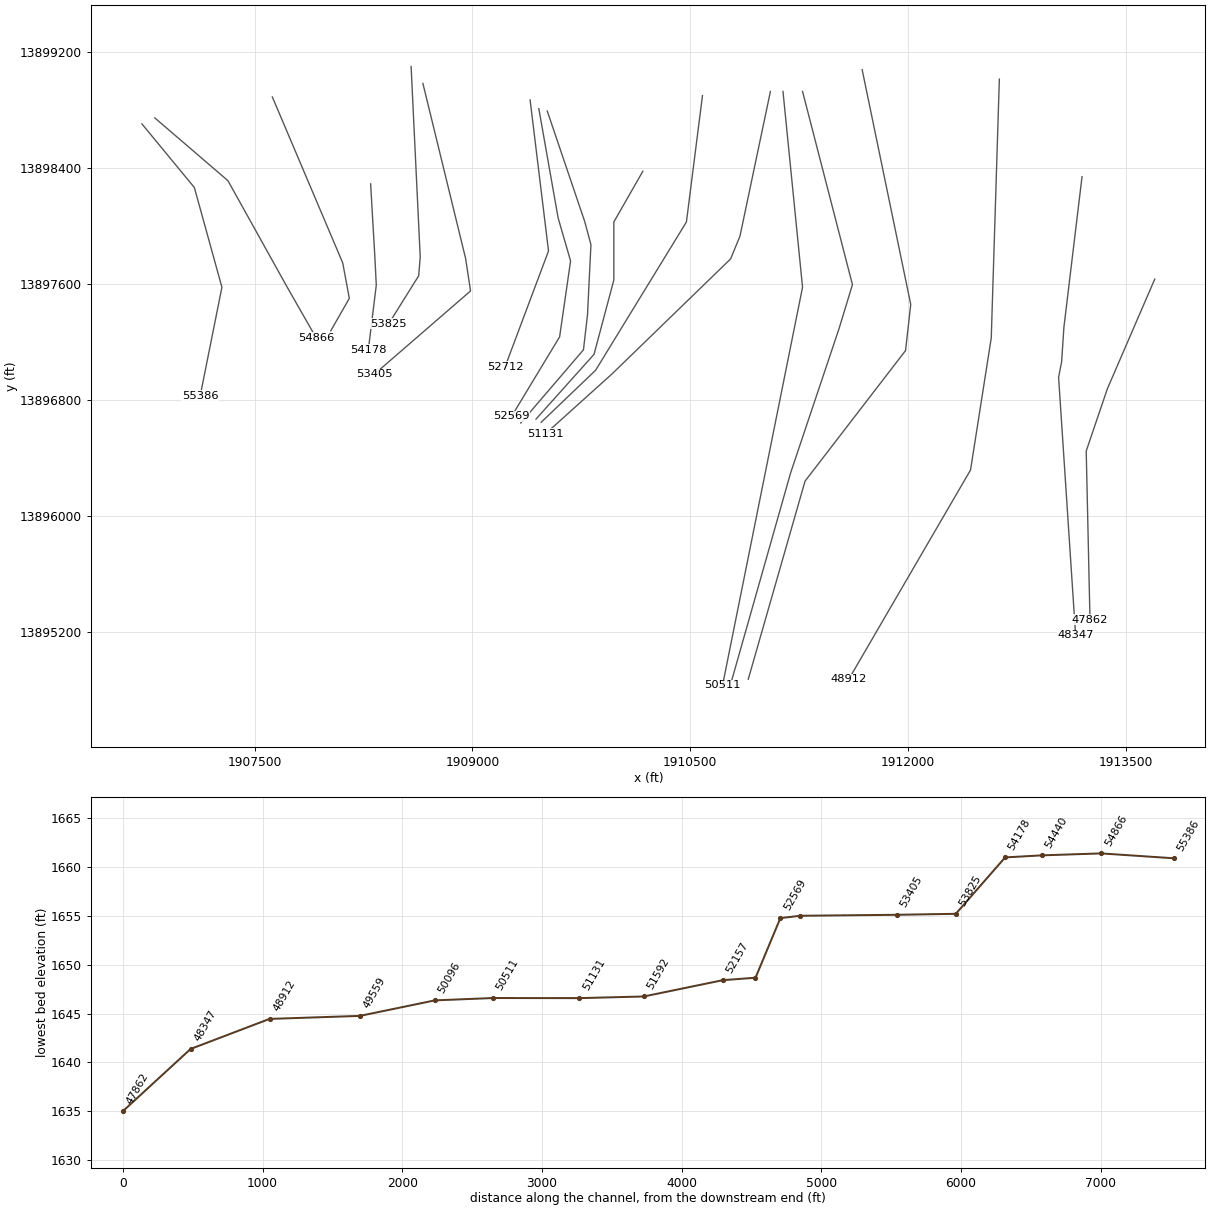
HEC-RAS study Turtle Creek.prj: Turtle Creek Base Level Engineering

--- Turtle Creek.g01 (geometry) --- (continued)

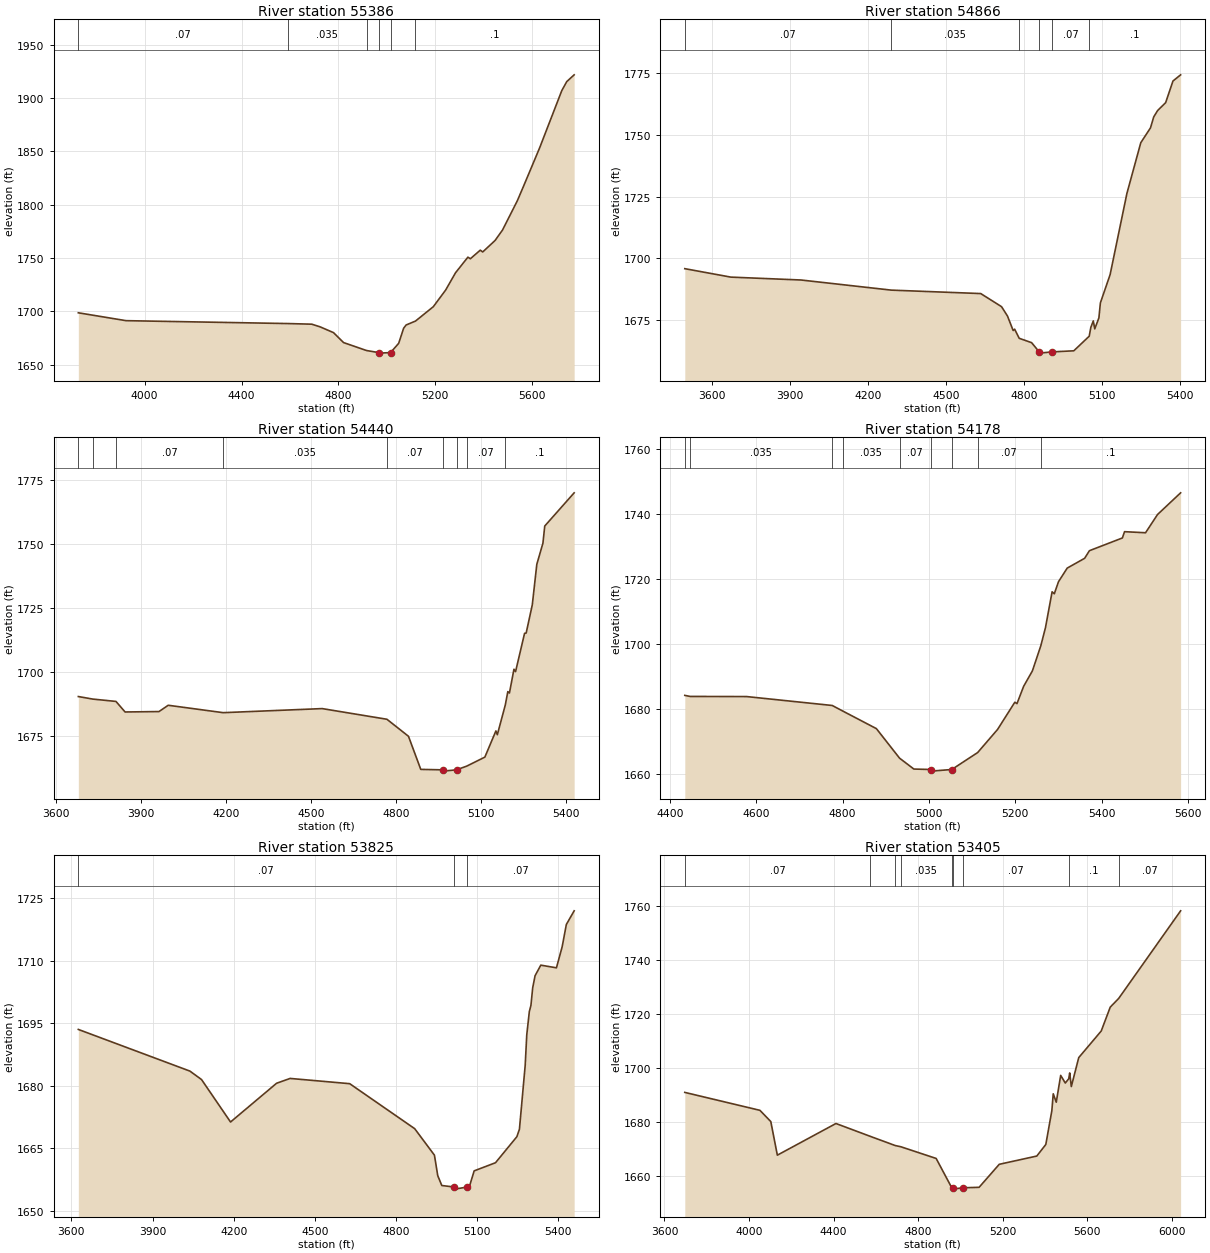
Type RM Length L Ch R = 1 ,55386   ,520,520,520
BEGIN DESCRIPTION:
Turtle Creek 86.0
END DESCRIPTION:
XS GIS Cut Line= 4
      1906723.98     13898701.04      1907085.12     13898262.55
        1907275.       13897575.        1907125.       13896825.
#Sta/Elev= 30
  3726.6 1698.69  3923.5 1691.32  4591.6 1688.61  4690.1 1688.02  4724.4 1685.53
  4779.7 1680.11  4821.2 1670.79  4915.9 1663.35  4966.5 1661.41  4967.5 1660.91
  5015.1 1661.41  5048.7 1670.12  5069.1 1684.22  5079.3 1687.28    5118 1690.94
  5191.5 1704.39  5242.5    1720  5283.3  1736.2  5334.3  1750.8  5344.5 1749.32
  5385.3 1757.35  5395.5  1755.7  5446.5 1766.46  5477.1  1776.2  5538.2  1803.6
  5568.8  1819.9    5630 1853.02  5721.8 1906.85  5742.2 1915.25  5772.8 1921.62
#Mann= 6 ,-1 , 0
  3726.6     .07       0  4591.6    .035       0  4915.9     .07       0
  4966.5     .05       0  5015.1     .07       0    5118      .1       0
Bank Sta=4966.5,5015.1
XS Rating Curve= 0 ,0
Exp/Cntr=0.3,0.1

Type RM Length L Ch R = 1 ,54866   ,426,426,426
BEGIN DESCRIPTION:
Turtle Creek 85.0
END DESCRIPTION:
XS GIS Cut Line= 4
      1906812.54     13898742.68      1907316.46     13898309.66
        1907725.       13897575.      1907924.98     13897225.03
#Sta/Elev= 30
  3494.8  1695.7  3671.9 1692.27  3941.8  1691.1  4289.3 1686.99  4633.7 1685.59
  4713.8 1680.27  4736.7 1676.45  4758.5 1670.59  4764.2 1671.13  4781.7 1667.43
  4829.4 1665.66  4858.8 1661.91  4859.8 1661.41  4907.5 1661.91  4991.8 1662.35
  5051.2 1668.29  5057.4 1671.89  5066.8 1674.49  5072.5 1671.26  5088.4 1675.72
  5094.1  1681.8  5131.6  1693.3  5196.3  1726.3  5249.6 1746.84    5287 1752.88
  5299.3 1757.29  5314.4  1759.9  5345.3 1763.11  5373.4 1771.88  5402.9  1774.4
#Mann= 6 ,-1 , 0
  3494.8     .07       0  4289.3    .035       0  4781.7     .07       0
  4858.8     .05       0  4907.5     .07       0  5051.2      .1       0
Bank Sta=4858.8,4907.5
XS Rating Curve= 0 ,0
Exp/Cntr=0.3,0.1

Type RM Length L Ch R = 1 ,54440   ,262,262,262
BEGIN DESCRIPTION:
Turtle Creek 84.0
END DESCRIPTION:
XS GIS Cut Line= 4
      1907622.34     13898886.84      1908107.32     13897742.68
      1908152.77     13897498.59        1908025.     13897275.01
#Sta/Elev= 30
  3680.1 1690.35  3730.9 1689.36  3812.8 1688.44    3845 1684.32  3964.5 1684.48
  3997.1 1686.94  4190.8 1684.05    4540 1685.64  4768.4 1681.47  4844.3 1674.83
  4887.7 1661.89    4965 1661.71    4966 1661.21  5013.7 1661.71  5050.3 1663.19
  5113.7 1666.68  5152.6 1676.91  5157.7 1675.43  5185.8 1687.06  5194.7 1692.27
  5200.4 1691.73  5216.3 1701.02    5222 1700.09  5253.7 1715.03  5259.4 1715.17
    5281 1726.19  5296.9 1742.01  5318.5 1750.28  5324.9 1756.97  5428.6 1769.94
#Mann= 9 ,-1 , 0
  3680.1     .07       0  3730.9    .035       0  3812.8     .07       0
  4190.8    .035       0  4768.4     .07       0    4965    .033       0
  5013.7     .07       0  5050.3     .07       0  5185.8      .1       0
Bank Sta=4965,5013.7
XS Rating Curve= 0 ,0
Exp/Cntr=0.3,0.1

Type RM Length L Ch R = 1 ,54178   ,353,353,353
BEGIN DESCRIPTION:
Turtle Creek 83.1
END DESCRIPTION:
XS GIS Cut Line= 4
       1908299.4     13898287.71      1908328.04      13897795.5
      1908338.46     13897589.77      1908283.77     13897144.45
#Sta/Elev= 30
  4434.9  1684.3  4447.1 1683.97  4577.9 1683.93  4776.1 1681.19  4801.4 1679.42
  4878.4 1674.07    4932 1664.99  4965.1 1661.64  5004.2  1661.5  5005.2    1661
  5052.9  1661.5  5112.8 1666.71  5158.9 1673.82  5198.8 1682.19  5203.8 1681.76
  5219.3  1687.1  5239.5 1691.83  5258.9 1699.52  5269.7 1705.08  5285.1 1716.15
  5290.2 1715.54  5299.9 1719.25  5320.1 1723.44  5360.4 1726.45  5371.5 1728.79
  5447.8 1732.71  5452.8 1734.64  5501.4 1734.31  5529.1 1739.91  5582.6 1746.59
#Mann= 9 ,-1 , 0
  4434.9     .07       0  4447.1    .035       0  4776.1     .07       0
  4801.4    .035       0    4932     .07       0  5004.2     .05       0
  5052.9     .07       0  5112.8     .07       0  5258.9      .1       0
Bank Sta=5004.2,5052.9
XS Rating Curve= 0 ,0
Exp/Cntr=0.3,0.1

Type RM Length L Ch R = 1 ,53825   ,420,420,420
BEGIN DESCRIPTION:
Turtle Creek 83.0
END DESCRIPTION:
XS GIS Cut Line= 4
      1908578.32     13899097.07      1908641.16     13897784.21
      1908630.61     13897653.97      1908424.98     13897324.97
#Sta/Elev= 30
  3625.7 1693.55  4038.2 1683.55  4081.2 1681.52  4188.4 1671.33  4358.6 1680.63
  4408.7 1681.79  4628.9 1680.53  4869.2 1669.73  4942.2 1663.37  4954.4 1658.46
  4969.4 1656.09  5015.2 1655.72  5016.2 1655.22  5063.9 1655.72  5073.6 1656.31
    5089  1659.6    5168 1661.56    5247 1667.81  5256.4  1669.6  5277.7 1684.93
  5283.5 1692.24    5293 1697.84  5298.9 1699.32  5305.4 1703.53  5314.2 1706.44
  5335.4 1708.98  5393.2 1708.34  5414.4  1713.4  5429.8 1718.74  5458.7 1722.02
#Mann= 3 ,-1 , 0
  3625.7     .07       0  5015.2     .05       0  5063.9     .07       0
Bank Sta=5015.2,5063.9
XS Rating Curve= 0 ,0
Exp/Cntr=0.3,0.1

Type RM Length L Ch R = 1 ,53405   ,693,693,693
BEGIN DESCRIPTION:
Turtle Creek 82.0
END DESCRIPTION:
XS GIS Cut Line= 4
      1908659.52     13898980.41      1908953.92     13897772.98
      1908987.73     13897549.37      1908324.96     13896974.97
#Sta/Elev= 30
  3696.1 1690.94  4051.6  1684.3  4103.1 1680.13    4134  1667.7  4411.3 1679.42
  4574.2 1674.65  4691.4 1671.27  4719.1 1670.79  4885.4 1666.48  4958.6 1655.72
  4963.1 1655.62  4964.1 1655.12  5011.8 1655.62  5088.6 1655.79  5183.9 1664.31
  5361.6 1667.37  5404.3 1671.66  5432.8 1684.17  5439.4 1690.42  5453.7 1687.31
  5474.6 1697.24  5496.4 1694.41  5512.7 1695.98  5517.3 1698.15  5524.9  1693.1
  5560.1 1703.83  5666.4 1713.67  5709.2 1722.52  5749.1 1725.74  6042.1 1758.18
#Mann= 9 ,-1 , 0
  3696.1     .07       0  4574.2    .035       0  4691.4     .07       0
  4719.1    .035       0  4958.6     .07       0  4963.1     .05       0
  5011.8     .07       0  5512.7      .1       0  5749.1     .07       0
Bank Sta=4963.1,5011.8
XS Rating Curve= 0 ,0
Exp/Cntr=0.3,0.1

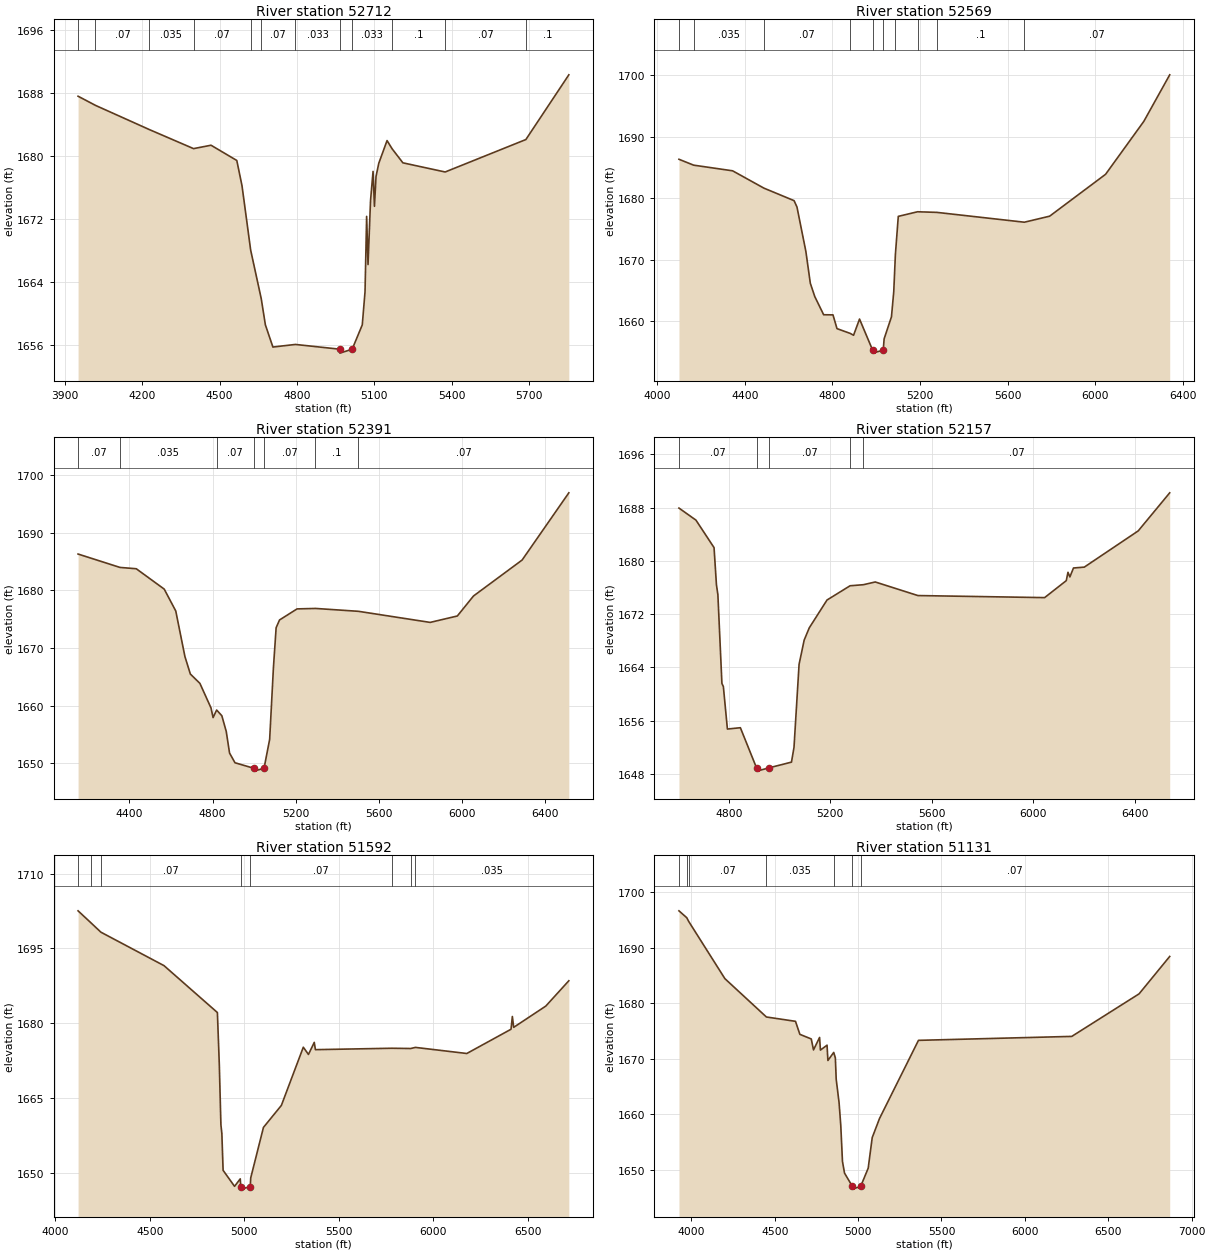
Type RM Length L Ch R = 1 ,52712   ,143,143,143
BEGIN DESCRIPTION:
Turtle Creek 81.0
END DESCRIPTION:
XS GIS Cut Line= 3
      1909398.14       13898866.        1909525.       13897825.
        1909225.       13897025.
#Sta/Elev= 30
  3951.3 1687.57  4018.8 1686.41  4227.3 1683.35  4399.1 1680.93  4466.9 1681.36
  4566.8 1679.43    4587 1676.23  4620.6 1668.07  4661.5 1661.94  4677.6 1658.61
  4706.8 1655.79    4794 1656.12  4965.6 1655.52  4966.6 1655.02  5014.3 1655.52
  5053.4  1658.6  5064.1 1662.81  5070.3 1672.34  5075.7 1666.24  5085.4 1674.33
  5095.2 1678.04  5100.6 1673.62  5106.8 1677.42  5117.5 1679.08  5149.5 1681.95
  5169.1 1680.91  5210.9 1679.13  5374.8 1677.97  5687.8 1682.08  5854.4 1690.28
#Mann= 12 ,-1 , 0
  3951.3    .035       0  4018.8     .07       0  4227.3    .035       0
  4399.1     .07       0  4620.6    .035       0  4661.5     .07       0
    4794    .033       0  4965.6    .033       0  5014.3    .033       0
  5169.1      .1       0  5374.8     .07       0  5687.8      .1       0
Bank Sta=4965.6,5014.3
XS Rating Curve= 0 ,0
Exp/Cntr=0.3,0.1

Type RM Length L Ch R = 1 ,52569   ,178,178,178
BEGIN DESCRIPTION:
Turtle Creek 80.2
END DESCRIPTION:
XS GIS Cut Line= 5
      1909458.25     13898805.91      1909591.06     13898053.31
        1909677.     13897756.44      1909601.48       13897233.
      1909270.89      13896685.4
#Sta/Elev= 30
  4099.1 1686.35  4166.1 1685.39  4344.1 1684.47  4487.1 1681.65    4625 1679.61
  4638.2 1678.57  4678.8 1671.35  4699.1 1666.17  4719.4    1664  4760.1 1661.03
  4802.7 1661.01    4821 1658.77  4881.5 1657.99  4896.7 1657.69    4924 1660.33
  4983.6 1655.28  4984.6 1654.78  5032.3 1655.28  5036.3  1657.1  5069.8 1660.69
  5080.3 1664.79  5087.8 1670.86    5101 1677.05    5189  1677.8  5277.2  1677.7
  5676.9  1676.1  5792.4 1677.08  6047.9  1683.9  6222.6 1692.52  6340.9  1700.1
#Mann= 10 ,-1 , 0
  4099.1     .07       0  4166.1    .035       0  4487.1     .07       0
  4881.5    .035       0  4983.6    .033       0  5032.3    .035       0
  5087.8      .1       0    5189     .07       0  5277.2      .1       0
  5676.9     .07       0
Bank Sta=4983.6,5032.3
XS Rating Curve= 0 ,0
Exp/Cntr=0.3,0.1

Type RM Length L Ch R = 1 ,52391   ,234,234,234
BEGIN DESCRIPTION:
Turtle Creek 80.1
END DESCRIPTION:
XS GIS Cut Line= 6
      1909516.17     13898790.06      1909774.79     13898026.79
      1909817.18     13897868.37      1909793.56     13897384.54
      1909765.67     13897143.72      1909333.99     13896639.22
#Sta/Elev= 30
    4153  1686.3  4354.5 1683.98  4432.9 1683.75  4567.4 1680.22  4622.9 1676.43
    4667 1668.53  4693.1  1665.5  4739.1 1663.88  4792.6 1659.61  4802.4 1657.95
  4819.6 1659.26  4844.6 1658.27  4865.8 1655.54  4881.6 1651.81  4907.8 1650.12
  4998.1 1649.17  4999.1 1648.67  5047.6 1649.17  5074.6 1654.18  5092.6 1666.54
  5105.7 1673.52    5122 1674.87  5206.4 1676.79  5294.9 1676.87  5501.9 1676.37
  5846.6 1674.45  5977.3 1675.56  6055.2 1679.03    6289 1685.26  6513.7 1696.91
#Mann= 7 ,-1 , 0
    4153     .07       0  4354.5    .035       0  4819.6     .07       0
  4998.1     .05       0  5047.6     .07       0  5294.9      .1       0
  5501.9     .07       0
Bank Sta=4998.1,5047.6
XS Rating Curve= 0 ,0
Exp/Cntr=0.3,0.1

Type RM Length L Ch R = 1 ,52157   ,565,565,565
BEGIN DESCRIPTION:
Turtle Creek 80.0
END DESCRIPTION:
XS GIS Cut Line= 5
        1910175.     13898374.99        1909975.       13898025.
        1909975.       13897625.      1909838.59     13897112.47
      1909438.75     13896665.89
#Sta/Elev= 30
  4603.7 1687.93  4670.6 1686.12  4741.9 1681.99  4751.3 1676.42    4757 1674.93
  4772.9 1661.59  4778.6 1661.12  4794.5 1654.74  4845.6 1654.94  4909.1 1648.92
  4910.1 1648.42  4959.1 1648.92  5046.8 1649.77  5056.8 1651.99  5076.8 1664.46
  5096.8 1668.09  5116.8 1669.93  5186.8 1674.12  5277.7 1676.26  5330.2 1676.42
  5376.8 1676.83  5544.7 1674.79  6043.9 1674.48  6129.2 1677.03  6135.9 1678.28
  6143.4 1677.59  6157.6 1678.93  6200.2 1679.06  6412.5  1684.5  6536.6 1690.22
#Mann= 5 ,-1 , 0
  4603.7     .07       0  4909.1     .05       0  4959.1     .07       0
  5277.7      .1       0  5330.2     .07       0
Bank Sta=4909.1,4959.1
XS Rating Curve= 0 ,0
Exp/Cntr=0.3,0.1

Type RM Length L Ch R = 1 ,51592   ,461,461,461
BEGIN DESCRIPTION:
Turtle Creek 79.0
END DESCRIPTION:
XS GIS Cut Line= 4
       1910585.6     13898896.11        1910475.       13898025.
      1909849.44     13897002.72      1909473.97     13896643.68
#Sta/Elev= 30
    4121 1702.54  4189.5 1700.12  4241.7 1698.26  4575.7 1691.55    4858 1682.15
  4868.1 1671.75  4876.6 1659.65  4881.6 1657.91  4888.2 1650.52  4948.7 1647.31
  4978.9 1648.81  4981.8 1647.25  4982.8 1646.75  5031.8 1647.25  5034.3    1649
  5101.6 1659.12  5196.4 1663.53  5312.5  1675.2  5339.7 1673.75  5370.5 1676.17
  5376.4 1674.71  5779.9 1674.99  5880.8 1674.94  5905.8 1675.16  6177.4 1673.94
  6411.3  1678.8  6418.4 1681.36  6425.3 1679.18  6595.1 1683.44  6717.1 1688.52
#Mann= 8 ,-1 , 0
    4121     .07       0  4189.5    .035       0  4241.7     .07       0
  4981.8     .05       0  5031.8     .07       0  5779.9    .035       0
  5880.8     .07       0  5905.8    .035       0
Bank Sta=4981.8,5031.8
XS Rating Curve= 0 ,0
Exp/Cntr=0.3,0.1

Type RM Length L Ch R = 1 ,51131   ,620,620,620
BEGIN DESCRIPTION:
Turtle Creek 78.0
END DESCRIPTION:
XS GIS Cut Line= 5
      1911053.58     13898924.46      1910844.11     13897927.97
      1910779.48     13897770.41      1909962.26     13896977.27
      1909505.24     13896565.58
#Sta/Elev= 30
  3925.9  1696.6  3972.7 1695.36  3984.2  1694.7  4201.3 1684.41  4450.1 1677.52
  4624.6 1676.74  4650.9  1674.4  4719.2 1673.57  4732.6  1671.6    4769 1673.84
  4774.1 1671.57  4813.8 1672.45  4818.9  1669.7  4853.8 1671.15  4863.6 1670.17
  4868.7 1666.32  4885.9 1662.13  4896.1 1658.04  4906.3 1651.56  4918.6 1649.46
  4965.6 1647.08  4966.6 1646.58  5015.6 1647.08  5060.6 1650.35  5084.6 1655.84
  5128.5 1659.28  5361.9 1673.32  6281.2 1674.03  6684.8 1681.68  6868.4  1688.4
#Mann= 7 ,-1 , 0
  3925.9     .07       0  3972.7    .035       0  3984.2     .07       0
  4450.1    .035       0  4853.8     .07       0  4965.6     .05       0
  5015.6     .07       0
Bank Sta=4965.6,5015.6
XS Rating Curve= 0 ,0
Exp/Cntr=0.3,0.1

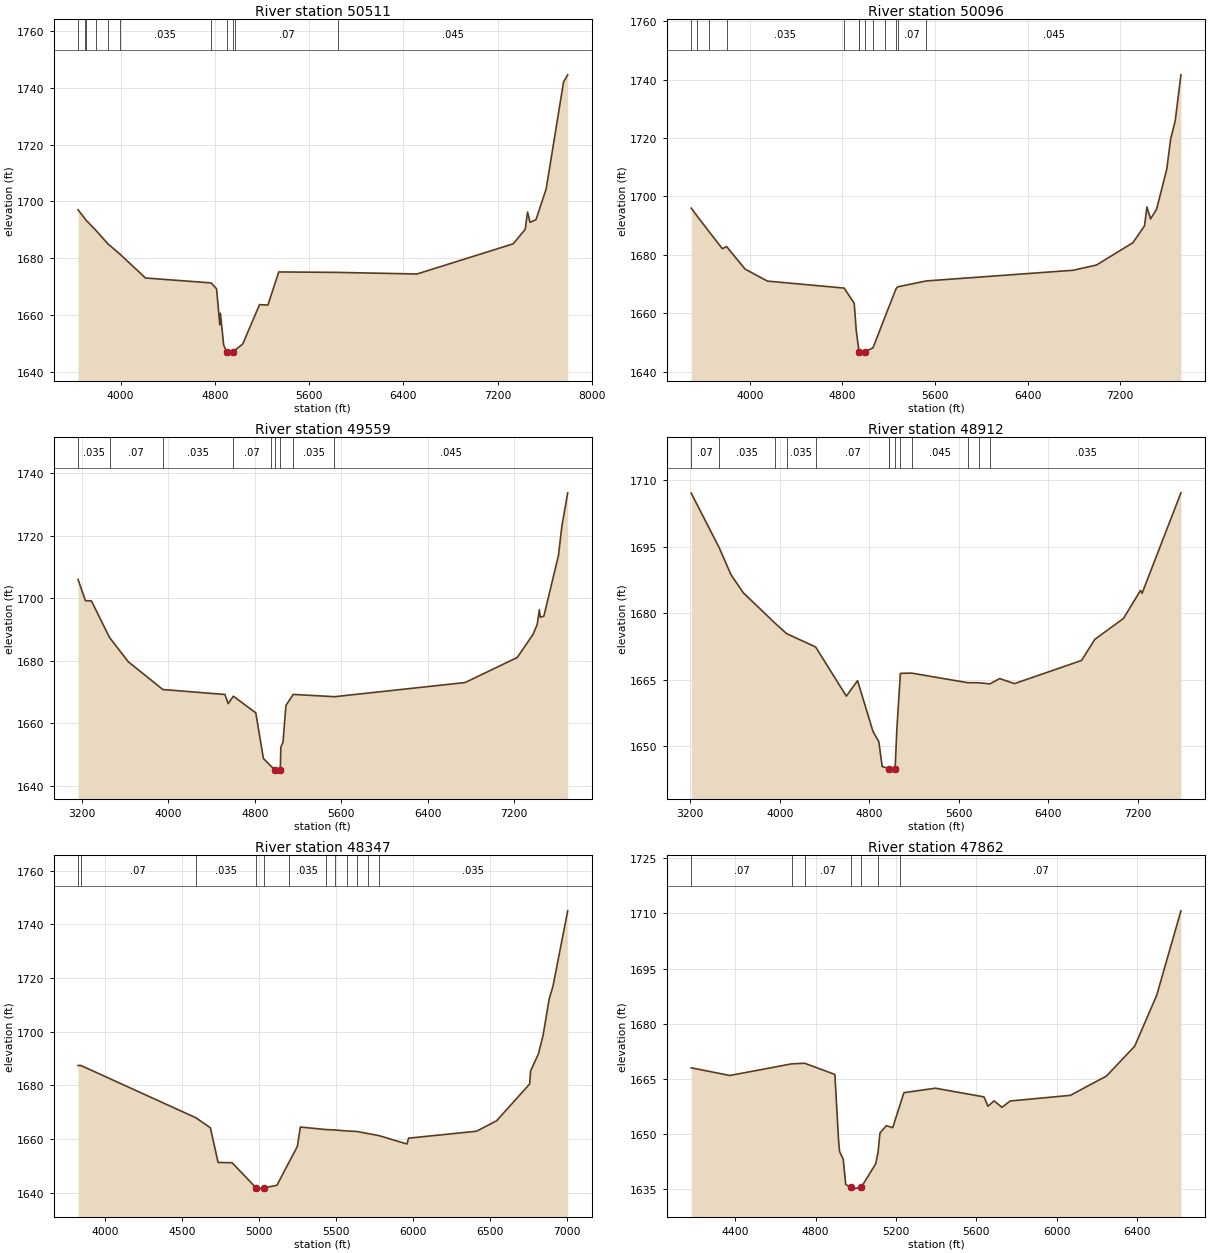
Type RM Length L Ch R = 1 ,50511   ,415,415,415
BEGIN DESCRIPTION:
Turtle Creek 77.0
END DESCRIPTION:
XS GIS Cut Line= 3
      1911140.26     13898924.91        1911275.       13897575.
        1910724.      13894831.2
#Sta/Elev= 30
    3639 1697.05  3695.3 1694.06  3705.1 1693.45  3793.9 1689.67  3892.4 1685.05
    3991 1681.57  4211.7 1673.03  4768.3  1671.3  4814.7  1669.2  4842.2 1656.52
  4847.3 1660.62    4875 1649.41    4900 1647.09    4901 1646.59  4950.6 1647.09
  4972.8 1647.69  5036.4  1649.8  5179.2 1663.65  5250.6 1663.52  5342.4 1675.16
    5845    1675  6515.4 1674.44  7331.3 1685.05  7433.3 1690.12  7453.7 1696.23
  7474.1 1692.63  7525.1 1693.56  7611.6 1704.38  7759.2 1742.07  7794.2 1744.53
#Mann= 11 ,-1 , 0
    3639     .07       0  3695.3    .035       0  3705.1     .07       0
  3793.9    .035       0  3892.4     .07       0    3991    .035       0
  4768.3     .07       0    4900     .05       0  4950.6     .07       0
  4972.8     .07       0    5845    .045       0
Bank Sta=4900,4950.6
XS Rating Curve= 0 ,0
Exp/Cntr=0.3,0.1

Type RM Length L Ch R = 1 ,50096   ,537,537,537
BEGIN DESCRIPTION:
Turtle Creek 76.0
END DESCRIPTION:
XS GIS Cut Line= 5
        1911275.     13898925.01      1911618.73     13897593.05
      1911526.58     13897290.19      1911192.75     13896294.76
       1910786.5     13894862.44
#Sta/Elev= 30
  3494.7    1696  3547.9 1693.15  3648.7 1687.95  3763.2 1682.11  3800.1 1682.82
  3959.8 1675.12  4152.8 1671.01  4816.1 1668.62  4902.6 1663.43  4920.5 1654.04
  4941.3 1647.71  4948.2 1646.85  4949.2 1646.35  4998.8 1646.85  5065.1 1648.17
    5169 1658.78  5263.4 1668.33  5277.6 1669.04  5524.4 1671.06  6794.6 1674.72
  6995.3  1676.5    7311 1684.16  7411.1 1689.95  7431.9 1696.39  7463.1  1692.3
  7515.1  1695.6  7603.1  1709.3    7637 1719.69  7676.1 1725.85  7725.6 1741.63
#Mann= 13 ,-1 , 0
  3494.7     .07       0  3547.9    .035       0  3648.7     .07       0
  3800.1    .035       0  4816.1     .07       0  4941.3    .033       0
  4948.2    .033       0  4998.8    .033       0  5065.1     .07       0
    5169    .045       0  5263.4      .1       0  5277.6     .07       0
  5524.4    .045       0
Bank Sta=4948.2,4998.8
XS Rating Curve= 0 ,0
Exp/Cntr=0.3,0.1

Type RM Length L Ch R = 1 ,49559   ,647,647,647
BEGIN DESCRIPTION:
Turtle Creek 75.0
END DESCRIPTION:
XS GIS Cut Line= 5
      1911685.65     13899074.92       1912020.3     13897456.84
      1911984.67     13897138.64      1911292.22     13896238.33
      1910901.08     13894872.86
#Sta/Elev= 30
  3164.9 1706.01  3233.5 1699.19  3288.8 1699.13  3456.2 1687.45  3630.1 1679.68
  3949.6 1670.82  4523.8 1669.24  4553.6 1666.32  4601.3 1668.69  4808.9 1663.38
  4879.4 1648.81  4951.7 1646.28  4984.9 1645.26  4985.9 1644.76  5035.6 1645.26
  5040.4 1652.39  5060.6 1654.05  5087.6 1665.74    5155 1669.26  5536.7 1668.53
  6744.8 1673.05    7227 1681.05  7372.4  1688.4  7411.4 1691.57  7431.3 1696.31
  7439.9 1693.93  7472.9 1694.24  7608.2 1713.65  7639.4 1722.94  7693.6 1733.64
#Mann= 9 ,-1 , 0
  3164.9    .035       0  3456.2     .07       0  3949.6    .035       0
  4601.3     .07       0  4951.7    .033       0  4984.9    .033       0
  5035.6    .033       0    5155    .035       0  5536.7    .045       0
Bank Sta=4984.9,5035.6
XS Rating Curve= 0 ,0
Exp/Cntr=0.3,0.1

Type RM Length L Ch R = 1 ,48912   ,565,565,565
BEGIN DESCRIPTION:
Turtle Creek 74.0
END DESCRIPTION:
XS GIS Cut Line= 4
      1912630.86     13899010.23        1912575.       13897225.
      1912432.37     13896315.28      1911593.79     13894872.87
#Sta/Elev= 30
    3209 1707.02    3458 1694.79  3564.4 1688.65  3674.5 1684.59  3957.2 1677.77
  4061.2  1675.4  4320.2  1672.4  4594.9 1661.34    4695 1664.82  4832.6  1653.4
    4885 1651.07  4915.1 1645.48  4977.1 1645.02  4979.9 1644.95  4980.9 1644.45
  5030.6 1644.95  5045.7 1653.62  5077.7 1666.46  5177.8 1666.52  5678.1 1664.36
  5778.2 1664.34  5878.3  1664.1  5964.4 1665.28  6097.6 1664.15  6696.8 1669.37
  6814.4  1674.1  7070.9 1678.82  7223.4 1685.14  7237.3 1684.48  7584.4  1707.1
#Mann= 13 ,-1 , 0
    3209     .07       0    3458    .035       0  3957.2     .07       0
  4061.2    .035       0  4320.2     .07       0  4977.1    .033       0
  4979.9    .033       0  5030.6    .033       0  5077.7    .035       0
  5177.8    .045       0  5678.1    .035       0  5778.2    .045       0
  5878.3    .035       0
Bank Sta=4979.9,5030.6
XS Rating Curve= 0 ,0
Exp/Cntr=0.3,0.1

Type RM Length L Ch R = 1 ,48347   ,485,485,485
BEGIN DESCRIPTION:
Turtle Creek 73.1
END DESCRIPTION:
XS GIS Cut Line= 5
      1913200.44     13898337.18      1913075.44      13897298.1
      1913059.81     13897061.12      1913038.98     13896954.35
       1913156.3     13895174.96
#Sta/Elev= 30
  3826.2 1687.43  3843.4 1687.49  4590.5 1667.97  4684.5 1664.24  4734.9  1651.3
  4825.5 1651.22  4980.8 1641.87  4981.8 1641.37  5031.5 1641.87  5116.5  1642.8
  5193.1 1651.24  5248.5 1657.23  5268.5 1664.51  5434.9 1663.56  5491.7 1663.42
  5571.7 1663.04  5633.5 1662.87  5708.4 1662.06  5775.2 1661.36    5960 1658.19
    5970 1660.36    6411 1662.95  6541.3 1666.85  6755.7 1680.56  6761.7 1685.47
  6811.8 1691.69  6841.9 1698.47    6882 1712.18  6906.8 1716.99  7002.3 1745.09
#Mann= 12 ,-1 , 0
  3826.2    .035       0  3843.4     .07       0  4590.5    .035       0
  4980.8     .05       0  5031.5    .035       0  5193.1    .035       0
  5434.9     .07       0  5491.7    .035       0  5571.7     .07       0
  5633.5    .035       0  5708.4    .045       0  5775.2    .035       0
Bank Sta=4980.8,5031.5
XS Rating Curve= 0 ,0
Exp/Cntr=0.3,0.1

Type RM Length L Ch R = 1 ,47862   ,446,446,446
BEGIN DESCRIPTION:
Turtle Creek 73.0
END DESCRIPTION:
XS GIS Cut Line= 5
      1913701.55     13897631.38       1913598.7     13897393.15
        1913375.       13896875.      1913229.21      13896445.8
      1913255.25     13895284.34
#Sta/Elev= 30
  4180.3 1667.99  4372.4  1665.9  4680.2 1669.06    4745 1669.23  4895.7 1666.19
  4913.7 1648.51  4919.2 1645.19  4937.2 1643.14  4949.7 1636.26  4975.9 1635.49
  4976.9 1634.99  5026.9 1635.49  5099.2 1641.91  5110.4 1644.92  5120.3 1650.25
    5152 1652.25  5183.7 1651.71  5220.9 1658.04  5239.6 1661.23  5396.5 1662.44
  5638.3 1660.08  5658.3 1657.53  5688.3    1659  5728.3 1657.24  5768.3 1658.96
  6068.4  1660.5  6248.4 1665.75  6389.1 1673.88  6498.5 1687.71  6619.2 1710.69
#Mann= 7 ,-1 , 0
  4180.3     .07       0  4680.2    .035       0    4745     .07       0
  4975.9     .05       0  5026.9     .07       0  5110.4    .035       0
  5220.9     .07       0
Bank Sta=4975.9,5026.9
XS Rating Curve= 0 ,0
Exp/Cntr=0.3,0.1