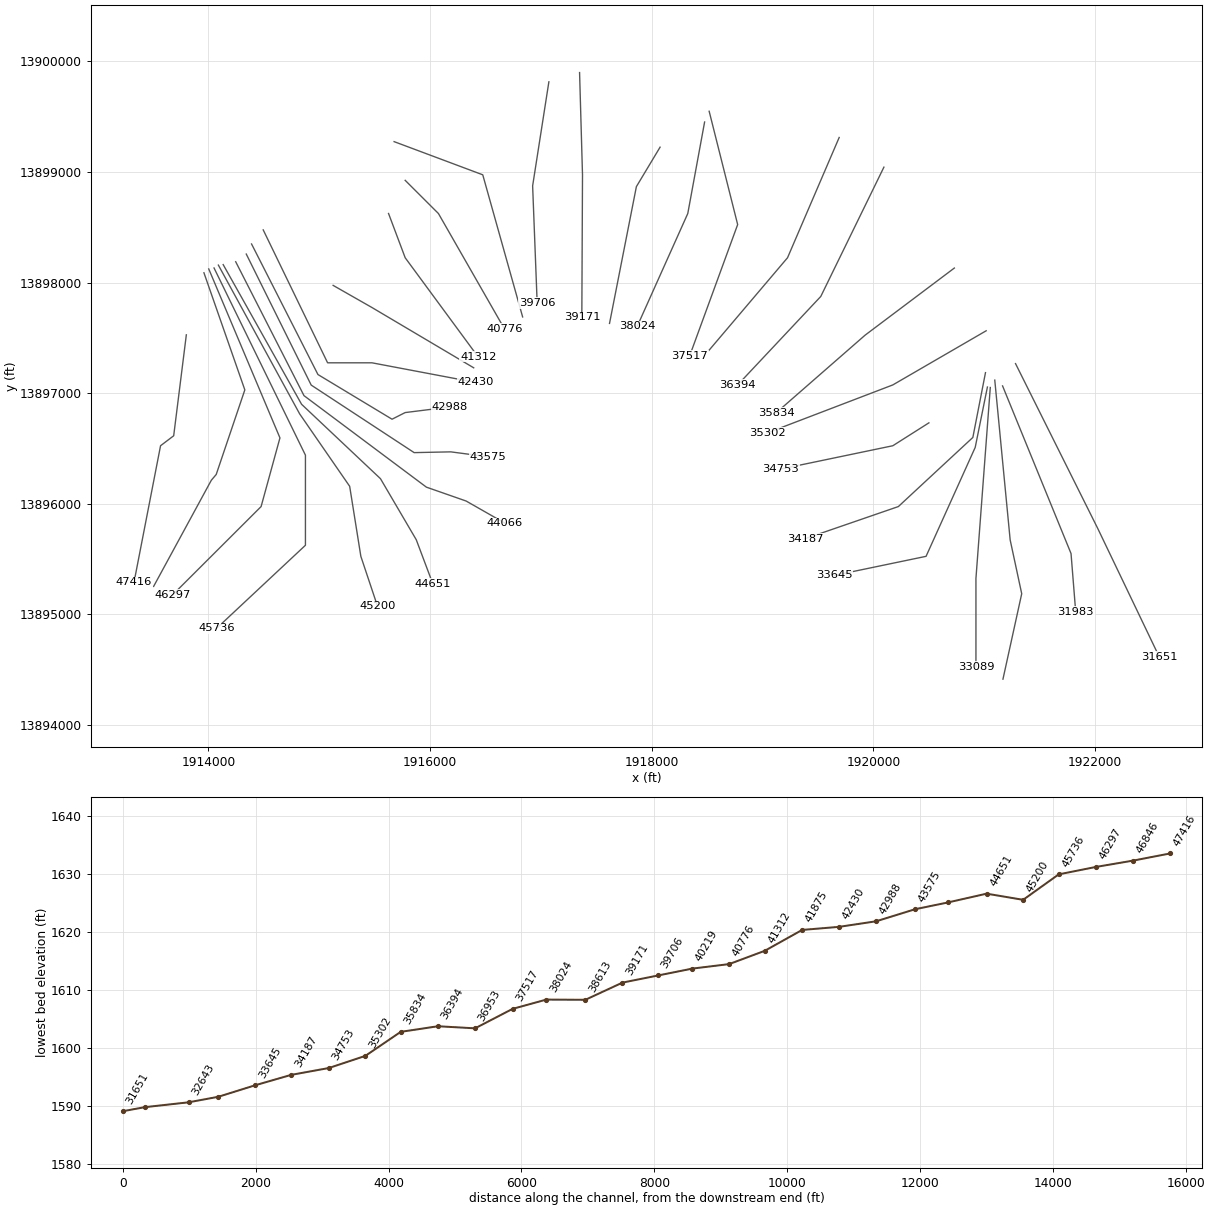
HEC-RAS study Turtle Creek.prj: Turtle Creek Base Level Engineering

--- Turtle Creek.g01 (geometry) --- (continued)

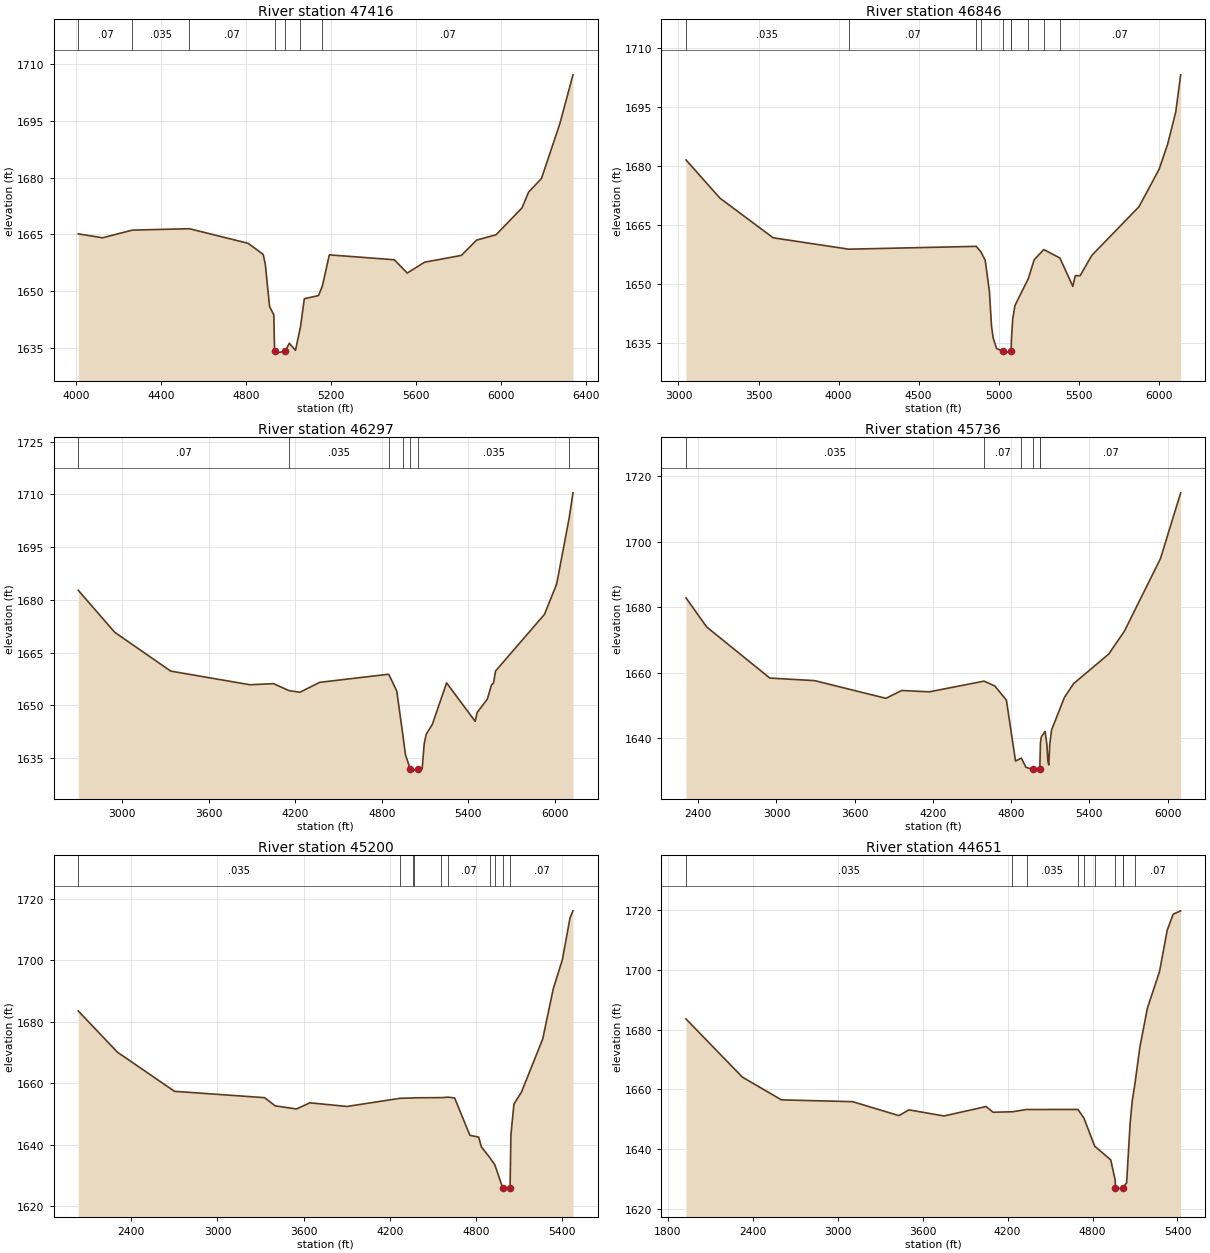
Type RM Length L Ch R = 1 ,47416   ,570,570,570
BEGIN DESCRIPTION:
Turtle Creek 72.0
END DESCRIPTION:
XS GIS Cut Line= 5
      1913800.37     13897527.98        1913725.       13896925.
      1913686.27     13896615.14      1913567.73       13896525.
      1913328.21     13895289.77
#Sta/Elev= 30
  4009.8 1665.16  4123.7 1664.12  4264.8 1666.15  4532.5 1666.52  4808.9 1662.65
  4879.5 1659.73  4889.6 1657.13  4909.7 1645.93  4929.7 1643.72  4933.2 1634.09
  4934.2 1633.59  4984.2 1634.09  5002.4 1636.21  5031.5 1634.33  5054.9 1640.51
  5073.1 1647.99  5139.8 1648.82  5157.9 1651.32  5190.7  1659.6  5496.3  1658.3
  5557.4 1654.79  5638.9 1657.65  5812.1 1659.46  5883.4  1663.5    5975 1664.92
  6097.3 1672.04  6127.8 1676.18    6189 1679.85  6275.3 1694.37  6336.9 1707.25
#Mann= 7 ,-1 , 0
  4009.8     .07       0  4264.8    .035       0  4532.5     .07       0
  4933.2     .05       0  4984.2     .07       0  5054.9    .035       0
  5157.9     .07       0
Bank Sta=4933.2,4984.2
XS Rating Curve= 0 ,0
Exp/Cntr=0.3,0.1

Type RM Length L Ch R = 1 ,46846   ,549,549,549
BEGIN DESCRIPTION:
Turtle Creek 71.0
END DESCRIPTION:
XS GIS Cut Line= 5
      1913959.24     13898089.04      1914328.17       13897030.
      1914069.98     13896265.18      1914025.69     13896212.67
      1913505.25     13895253.09
#Sta/Elev= 30
    3047 1681.48  3259.9 1671.73  3591.2 1661.67  4063.6 1658.77  4859.3 1659.49
  4888.3 1658.13  4915.5 1655.95  4941.6 1648.09  4954.8 1639.24  4965.3 1636.18
  4986.8 1633.49  5026.4 1632.83  5027.4 1632.33  5077.4 1632.83    5079 1635.62
  5087.2 1641.01  5101.3 1644.47  5184.1 1651.23  5221.1 1656.06  5281.1 1658.67
  5381.9 1656.53  5462.6 1649.31  5477.8 1652.04  5508.1 1652.02  5581.4 1657.21
  5876.1 1669.59  6001.6 1679.13  6054.2 1685.42  6105.2 1693.67    6136 1703.12
#Mann= 10 ,-1 , 0
    3047    .035       0  4063.6     .07       0  4859.3    .035       0
  4888.3     .07       0  5026.4     .05       0  5077.4     .07       0
    5079    .035       0  5184.1     .07       0  5281.1    .035       0
  5381.9     .07       0
Bank Sta=5026.4,5077.4
XS Rating Curve= 0 ,0
Exp/Cntr=0.3,0.1

Type RM Length L Ch R = 1 ,46297   ,561,561,561
BEGIN DESCRIPTION:
Turtle Creek 70.0
END DESCRIPTION:
XS GIS Cut Line= 4
      1914002.64     13898123.78      1914645.01     13896595.97
        1914475.       13895975.      1913674.97     13895174.97
#Sta/Elev= 30
  2694.3 1682.72  2946.7  1670.8  3335.5 1659.73  3886.3 1655.84    4049 1656.16
  4154.9  1654.2  4231.7  1653.7  4369.4 1656.53  4848.2 1658.84  4904.1 1654.06
  4946.6 1641.53  4964.4 1635.96  4998.3 1631.76  4999.3 1631.26  5049.3 1631.76
  5080.3 1631.91  5094.5 1639.03  5108.6 1641.76    5151 1644.57    5250 1656.38
    5448 1645.45  5462.2 1647.96  5532.9 1651.78  5561.2  1655.8  5575.3  1656.3
  5589.5 1659.75  5928.9 1675.87  6013.7 1684.51  6100.8  1703.4  6126.9 1710.47
#Mann= 7 ,-1 , 0
  2694.3     .07       0  4154.9    .035       0  4848.2     .07       0
  4946.6    .035       0  4998.3    .035       0  5049.3    .035       0
  6100.8      .1       0
Bank Sta=4998.3,5049.3
XS Rating Curve= 0 ,0
Exp/Cntr=0.3,0.1

Type RM Length L Ch R = 1 ,45736   ,536,536,536
BEGIN DESCRIPTION:
Turtle Creek 69.0
END DESCRIPTION:
XS GIS Cut Line= 5
      1914050.39     13898132.44      1914875.06     13896439.72
        1914875.     13895958.27        1914875.       13895625.
      1914075.01     13894875.01
#Sta/Elev= 30
  2305.7 1682.84  2464.4 1673.96  2948.8 1658.37  3292.9 1657.58    3839 1652.19
  3960.3 1654.58  4171.6 1654.17  4591.7 1657.43  4674.2 1655.96  4763.3 1651.64
  4833.3 1633.06  4877.6 1633.96  4913.3 1631.15  4967.5 1630.48  4968.5 1629.98
  5019.2 1630.48  5024.4 1638.63  5031.4 1640.44  5059.8  1642.1  5073.9 1638.13
  5081.2  1633.1  5088.1 1631.89  5095.4 1637.99  5109.6 1642.54  5208.7 1652.51
  5279.1 1656.68  5548.2  1665.7  5668.4 1672.68  5944.3 1694.76  6099.9 1714.87
#Mann= 6 ,-1 , 0
  2305.7    .035       0  4591.7     .07       0  4877.6    .035       0
  4967.5    .035       0  5019.2    .035       0  5024.4     .07       0
Bank Sta=4967.5,5019.2
XS Rating Curve= 0 ,0
Exp/Cntr=0.3,0.1

Type RM Length L Ch R = 1 ,45200   ,549,549,549
BEGIN DESCRIPTION:
Turtle Creek 68.0
END DESCRIPTION:
XS GIS Cut Line= 5
      1914089.46     13898158.46      1914822.96     13896812.99
      1915274.15     13896158.27        1915375.       13895525.
      1915524.99     13895075.04
#Sta/Elev= 30
  2031.1 1683.48  2303.3  1670.1    2701 1657.37  3327.6 1655.31  3401.8 1652.65
  3549.8 1651.63  3643.2 1653.64  3901.1 1652.45  4270.2  1655.1  4360.6 1655.21
  4369.3 1655.27    4558 1655.32  4604.5 1655.48  4650.4 1655.21  4756.9 1643.06
  4817.6  1642.5  4836.9 1639.28  4894.3  1635.9  4930.6 1633.45  4984.5 1626.09
  4985.5 1625.59  5036.3 1626.09  5042.1 1643.18  5063.1 1653.19  5115.9 1657.15
  5263.4 1674.36  5337.2 1690.73  5400.5 1700.17  5453.2 1713.67  5474.2 1716.02
#Mann= 10 ,-1 , 0
  2031.1    .035       0  4270.2     .07       0  4360.6    .035       0
  4369.3     .07       0    4558    .035       0  4604.5     .07       0
  4894.3    .035       0  4930.6     .07       0  4984.5     .05       0
  5036.3     .07       0
Bank Sta=4984.5,5036.3
XS Rating Curve= 0 ,0
Exp/Cntr=0.3,0.1

Type RM Length L Ch R = 1 ,44651   ,585,585,585
BEGIN DESCRIPTION:
Turtle Creek 67.0
END DESCRIPTION:
XS GIS Cut Line= 5
      1914132.84     13898162.85      1914840.32     13896899.79
      1915552.13     13896227.05        1915875.       13895675.
      1916025.02     13895274.96
#Sta/Elev= 30
  1928.8 1683.61    2327 1664.14  2603.3 1656.52  3105.5 1655.92  3432.8 1651.25
  3503.6 1653.17  3751.1 1651.13  4048.1 1654.29  4097.8 1652.38  4234.6 1652.54
  4334.8  1653.3    4697 1653.31  4739.7 1650.38  4815.5 1641.03  4928.9 1636.43
  4960.3  1629.6  4961.7 1627.15  4962.7 1626.65  5013.6 1627.15  5014.9 1627.18
  5040.8 1628.73  5065.8 1648.71  5080.9 1656.27  5099.3 1661.82  5134.3 1674.09
  5187.7 1687.22  5273.1 1699.41  5327.4 1713.26  5369.3 1718.64  5422.7 1719.78
#Mann= 10 ,-1 , 0
  1928.8    .035       0  4234.6     .07       0  4334.8    .035       0
    4697     .07       0  4739.7      .1       0  4815.5     .07       0
  4961.7     .05       0  5013.6     .07       0  5014.9    .035       0
  5099.3     .07       0
Bank Sta=4961.7,5013.6
XS Rating Curve= 0 ,0
Exp/Cntr=0.3,0.1

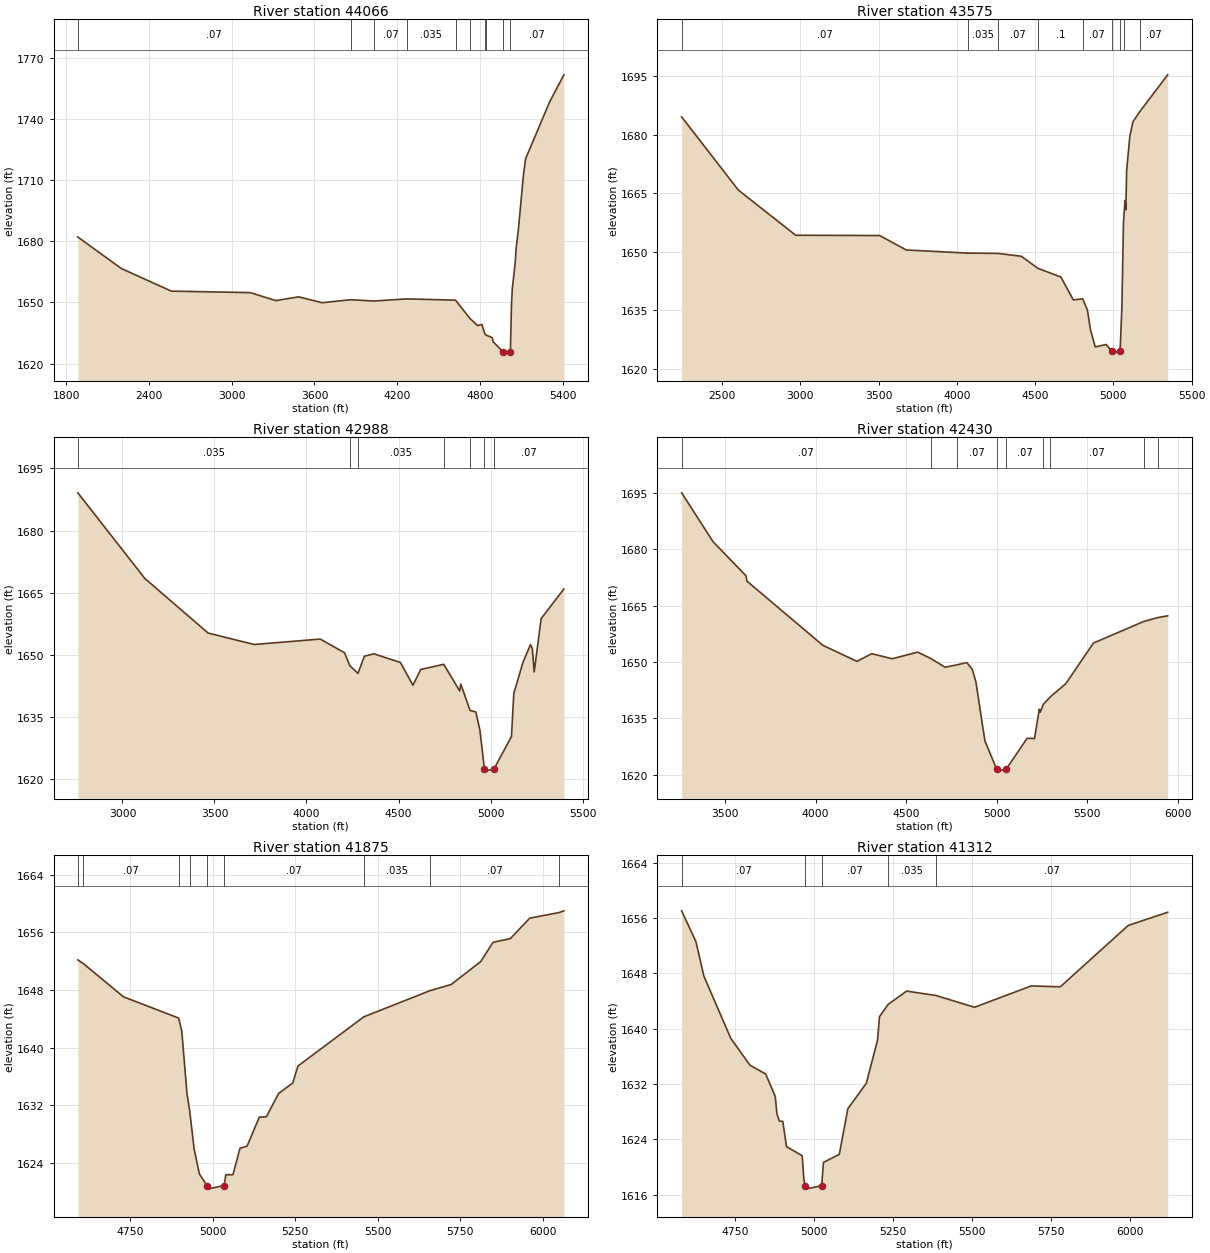
Type RM Length L Ch R = 1 ,44066   ,491,491,491
BEGIN DESCRIPTION:
Turtle Creek 66.0
END DESCRIPTION:
XS GIS Cut Line= 5
       1914245.7     13898188.87      1914862.02     13896977.92
      1915966.33     13896150.57        1916325.       13896025.
      1916675.04     13895824.98
#Sta/Elev= 30
  1885.2 1682.16  2200.7 1666.68  2562.8 1655.59    3135 1654.84  3320.2 1650.93
  3484.8 1652.77  3655.6 1649.89  3861.5 1651.35    4030 1650.72  4269.2 1651.77
    4622 1651.15  4727.6 1642.07  4781.7 1638.67  4813.1 1639.18  4833.2 1634.76
  4843.5 1633.93  4887.3 1632.79  4895.3 1630.66  4967.7 1625.63  4968.7 1625.13
  5019.6 1625.63  5026.9 1648.15  5033.4 1656.87  5054.2 1669.46  5061.4 1676.76
  5076.5 1685.23    5114 1712.58  5129.8 1720.59  5303.3 1748.44    5407 1761.83
#Mann= 10 ,-1 , 0
  1885.2     .07       0  3861.5    .035       0    4030     .07       0
  4269.2    .035       0    4622     .07       0  4727.6      .1       0
  4833.2    .035       0  4843.5     .07       0  4967.7     .05       0
  5019.6     .07       0
Bank Sta=4967.7,5019.6
XS Rating Curve= 0 ,0
Exp/Cntr=0.3,0.1

Type RM Length L Ch R = 1 ,43575   ,587,587,587
BEGIN DESCRIPTION:
Turtle Creek 65.0
END DESCRIPTION:
XS GIS Cut Line= 5
      1914341.21     13898258.27      1914927.13      13897073.4
      1915856.01     13896462.73      1916186.51     13896469.67
      1916525.04     13896424.99
#Sta/Elev= 30
  2241.3 1684.53  2603.5 1665.77  2970.1 1654.19  3506.5 1654.12  3676.4 1650.42
  4067.7 1649.61  4263.9 1649.53  4411.5  1648.8    4518  1645.7  4664.5 1643.48
  4743.8 1637.62  4803.8 1637.88  4833.8 1635.03  4853.8 1629.88  4883.8 1625.56
  4953.8 1626.19  4987.9 1624.47  4988.9 1623.97  5039.8 1624.47  5044.2 1625.85
  5054.2 1635.65  5064.3 1657.51  5069.7 1660.53  5074.3  1663.1  5079.4 1660.74
  5084.5 1670.75  5104.7 1679.47  5124.9 1683.27  5169.6 1685.94  5346.8 1695.32
#Mann= 9 ,-1 , 0
  2241.3     .07       0  4067.7    .035       0  4263.9     .07       0
    4518      .1       0  4803.8     .07       0  4987.9     .05       0
  5039.8     .07       0  5069.7      .1       0  5169.6     .07       0
Bank Sta=4987.9,5039.8
XS Rating Curve= 0 ,0
Exp/Cntr=0.3,0.1

Type RM Length L Ch R = 1 ,42988   ,558,558,558
BEGIN DESCRIPTION:
Turtle Creek 64.0
END DESCRIPTION:
XS GIS Cut Line= 5
      1914388.92     13898349.47      1914987.89     13897168.89
      1915656.41      13896764.9        1915775.       13896825.
        1916175.       13896875.
#Sta/Elev= 30
  2757.6 1689.12  3121.4 1668.44  3465.3 1655.25  3715.9 1652.48  4074.6 1653.79
  4206.6 1650.49  4235.8 1647.34  4279.7  1645.5  4314.4 1649.65  4366.8 1650.22
  4510.4 1648.14  4578.3 1642.64    4621 1646.45  4745.9  1647.7  4832.5 1641.27
  4838.4 1642.94    4889 1636.54  4920.3 1636.18  4942.6 1631.74  4966.7 1622.39
  4967.7 1621.89  5018.6 1622.39  5113.9 1630.25  5126.5 1640.63  5176.9 1648.24
  5217.2 1652.46  5227.3 1651.48  5237.4 1645.86  5275.1 1658.73  5398.6 1665.89
#Mann= 7 ,-1 , 0
  2757.6    .035       0  4235.8     .07       0  4279.7    .035       0
  4745.9      .1       0    4889     .07       0  4966.7     .05       0
  5018.6     .07       0
Bank Sta=4966.7,5018.6
XS Rating Curve= 0 ,0
Exp/Cntr=0.3,0.1

Type RM Length L Ch R = 1 ,42430   ,555,555,555
BEGIN DESCRIPTION:
Turtle Creek 63.0
END DESCRIPTION:
XS GIS Cut Line= 4
      1914494.06     13898476.88        1915075.       13897275.
        1915475.       13897275.      1916407.76     13897098.09
#Sta/Elev= 30
  3260.2 1695.04  3434.6 1681.96  3615.3 1672.97  3620.9 1671.52  4039.8 1654.44
  4228.6 1650.15  4309.9 1652.21  4422.9 1650.85    4564 1652.62  4635.8 1650.93
  4715.1  1648.6    4782 1649.24  4835.1 1649.85  4865.1 1648.03  4885.1 1644.74
  4935.1 1628.96  5000.3 1621.43  5001.3 1620.93  5052.3 1621.43  5168.1 1629.68
  5208.9  1629.6  5235.5 1637.42  5240.5  1636.6  5257.8 1638.73    5296 1640.69
  5381.9 1644.23  5534.6 1655.04  5811.5 1660.77  5893.1 1661.85  5944.5 1662.29
#Mann= 9 ,-1 , 0
  3260.2     .07       0  4635.8    .035       0    4782     .07       0
  5000.3     .05       0  5052.3     .07       0  5257.8    .035       0
    5296     .07       0  5811.5    .035       0  5893.1    .045       0
Bank Sta=5000.3,5052.3
XS Rating Curve= 0 ,0
Exp/Cntr=0.3,0.1

Type RM Length L Ch R = 1 ,41875   ,563,563,563
BEGIN DESCRIPTION:
Turtle Creek 62.0
END DESCRIPTION:
XS GIS Cut Line= 3
      1915124.98     13897975.01        1915475.       13897775.
      1916393.29     13897229.76
#Sta/Elev= 30
  4592.3 1652.17  4609.4 1651.64  4730.5 1647.05  4897.3 1644.11  4906.9 1642.31
  4922.7 1633.61  4930.7  1631.3  4944.3 1625.97  4960.2 1622.51    4983  1620.9
    4984  1620.4  5035.1  1620.9  5040.3  1622.4  5061.7 1622.39  5083.1 1626.07
  5104.5 1626.35  5141.6 1630.38    5163 1630.43    5200 1633.66  5242.9 1635.11
  5258.5 1637.46  5457.9 1644.28    5659 1647.92  5722.3 1648.76  5811.8 1651.94
  5848.9  1654.6  5901.5 1655.12  5959.9 1657.95  6048.8 1658.73  6063.4 1658.97
#Mann= 9 ,-1 , 0
  4592.3    .035       0  4609.4     .07       0  4897.3      .1       0
  4930.7     .07       0    4983     .05       0  5035.1     .07       0
  5457.9    .035       0    5659     .07       0  6048.8    .045       0
Bank Sta=4983,5035.1
XS Rating Curve= 0 ,0
Exp/Cntr=0.3,0.1

Type RM Length L Ch R = 1 ,41312   ,536,536,536
BEGIN DESCRIPTION:
Turtle Creek 61.0
END DESCRIPTION:
XS GIS Cut Line= 3
        1915625.     13898624.99        1915775.       13898225.
      1916433.31     13897328.55
#Sta/Elev= 30
  4580.1 1657.05  4625.5 1652.57  4650.4 1647.62  4735.8  1638.6  4796.4 1634.73
  4846.2 1633.45  4876.5 1630.21  4881.8 1627.72  4889.8 1626.63  4900.5  1626.6
  4912.1 1622.95  4961.9 1621.63  4967.2 1618.22  4971.5  1617.3  4972.5  1616.8
  5023.6  1617.3  5029.3 1620.67  5079.4 1621.82  5106.5 1628.43  5165.1 1632.12
  5200.6 1638.38  5206.8 1641.74  5233.9 1643.51  5292.6 1645.44  5385.5 1644.81
  5507.7  1643.1  5687.5 1646.19  5779.4 1646.06  5994.6 1654.94  6119.5 1656.84
#Mann= 5 ,-1 , 0
  4580.1     .07       0  4971.5     .05       0  5023.6     .07       0
  5233.9    .035       0  5385.5     .07       0
Bank Sta=4971.5,5023.6
XS Rating Curve= 0 ,0
Exp/Cntr=0.3,0.1

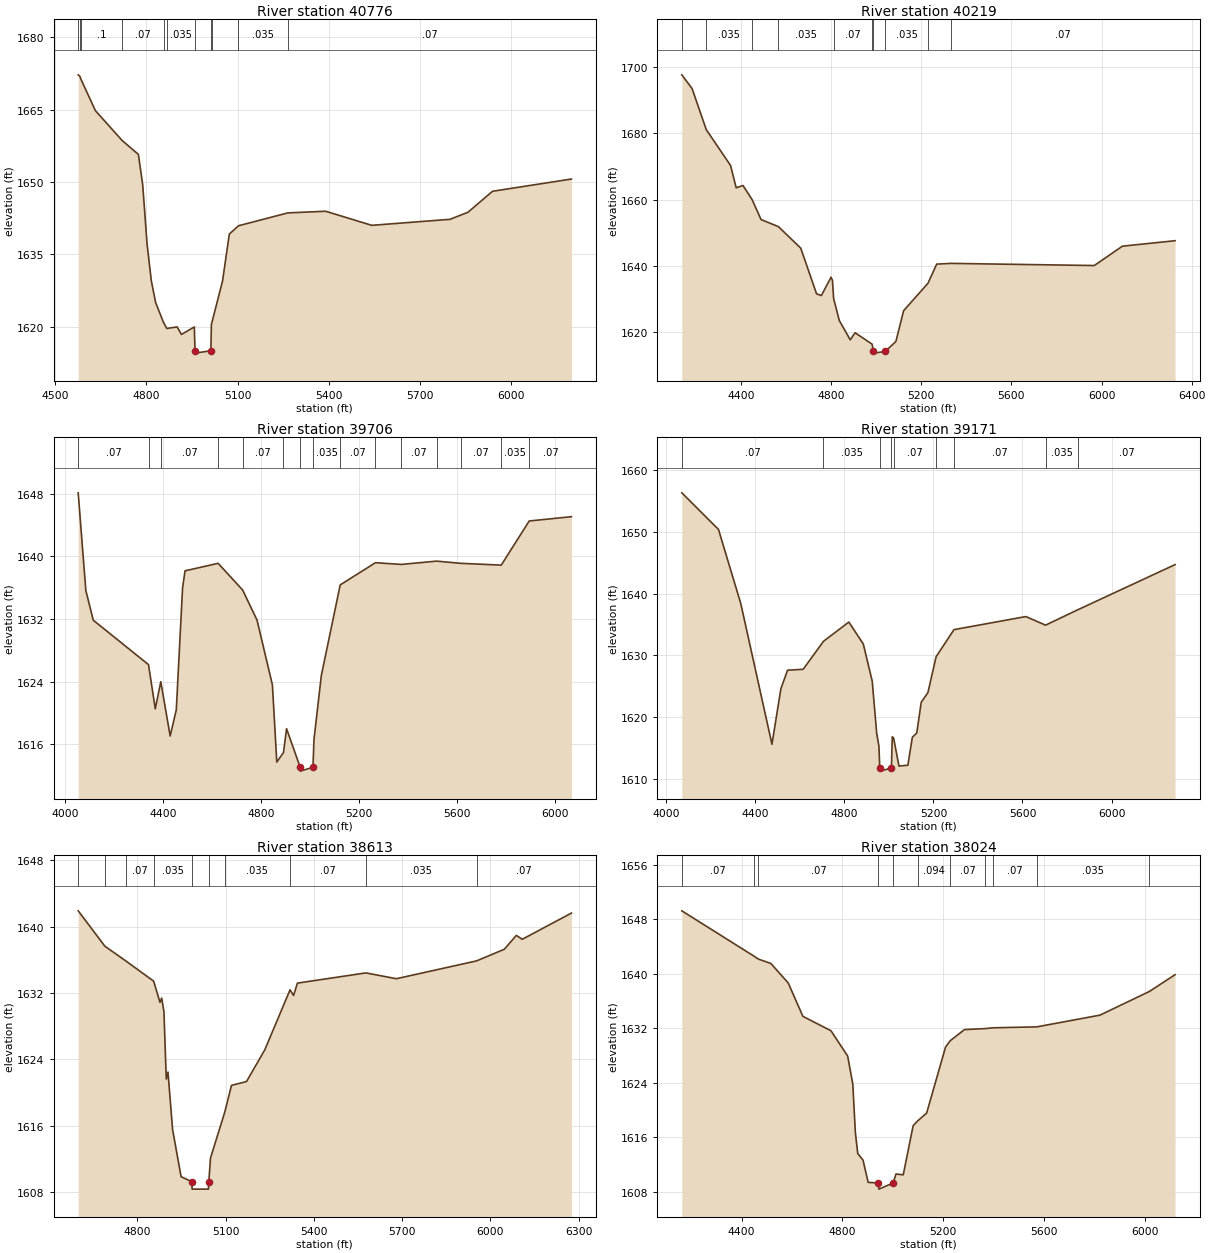
Type RM Length L Ch R = 1 ,40776   ,557,557,557
BEGIN DESCRIPTION:
Turtle Creek 60.0
END DESCRIPTION:
XS GIS Cut Line= 3
      1915774.97     13898925.03        1916075.       13898625.
      1916668.91     13897584.82
#Sta/Elev= 30
  4575.7 1672.22  4581.3 1671.89  4585.3 1671.22  4632.3 1664.79  4720.1 1658.61
  4773.7 1655.71  4787.9 1649.37    4802 1637.26  4816.2 1629.48  4830.3 1625.01
  4856.4 1620.85  4867.1 1619.62    4901 1619.95  4915.2 1618.38  4957.6 1619.94
  4959.8 1615.01  4960.8 1614.51    5012 1615.01  5013.7 1620.45  5016.3 1621.08
  5050.4 1629.47  5072.7 1639.21  5102.8 1640.92  5265.3 1643.59  5389.5 1643.93
  5541.2 1641.01  5798.5 1642.26  5857.5 1643.72  5938.2 1648.07  6197.8 1650.61
#Mann= 11 ,-1 , 0
  4575.7    .035       0  4581.3     .07       0  4585.3      .1       0
  4720.1     .07       0  4856.4      .1       0  4867.1    .035       0
  4959.8    .035       0    5012    .035       0  5016.3     .07       0
  5102.8    .035       0  5265.3     .07       0
Bank Sta=4959.8,5012
XS Rating Curve= 0 ,0
Exp/Cntr=0.3,0.1

Type RM Length L Ch R = 1 ,40219   ,513,513,513
BEGIN DESCRIPTION:
Turtle Creek 59.0
END DESCRIPTION:
XS GIS Cut Line= 3
      1915674.99       13899275.        1916475.       13898975.
      1916834.79     13897689.82
#Sta/Elev= 30
  4137.4 1697.55  4182.8 1693.43    4246 1681.03  4353.7 1670.25  4378.6 1663.54
  4408.9 1664.21    4449 1660.01    4489 1653.97  4566.4 1651.81  4665.2 1645.35
  4735.5 1631.57  4756.8 1631.08  4799.6  1636.6  4805.8 1635.66  4811.1 1630.21
  4836.1 1623.57    4885 1617.73  4906.4 1619.86  4981.8 1616.44    4988 1614.23
    4989 1613.73  5040.2 1614.23  5087.5 1617.26  5121.6 1626.49    5230 1634.79
  5268.5 1640.54  5331.3 1640.76    5968 1640.11  6092.6 1645.94  6326.4 1647.59
#Mann= 10 ,-1 , 0
  4137.4     .07       0    4246    .035       0    4449     .07       0
  4566.4    .035       0  4811.1     .07       0  4981.8    .035       0
    4988    .035       0  5040.2    .035       0    5230    .035       0
  5331.3     .07       0
Bank Sta=4988,5040.2
XS Rating Curve= 0 ,0
Exp/Cntr=0.3,0.1

Type RM Length L Ch R = 1 ,39706   ,535,535,535
BEGIN DESCRIPTION:
Turtle Creek 58.0
END DESCRIPTION:
XS GIS Cut Line= 3
      1917071.59     13899815.78        1916925.       13898875.
      1916965.99     13897815.13
#Sta/Elev= 30
  4053.1 1648.12  4084.3 1635.63  4114.6 1631.84    4340 1626.16  4367.6 1620.51
  4390.1 1623.98  4428.4 1617.04  4453.4 1620.39    4479 1635.97  4489.1 1638.15
  4624.1 1639.11  4724.1  1635.7  4782.8 1631.86  4845.6 1623.57  4863.5 1613.71
  4890.8 1614.93  4903.4 1617.97  4958.9 1613.05  4959.9 1612.55  5011.1 1613.05
  5015.2 1616.57  5045.3 1624.78  5122.3 1636.35  5266.1 1639.19  5371.3 1638.97
  5515.6 1639.39  5613.9 1639.11  5779.4 1638.88  5893.6 1644.52  6065.9 1645.07
#Mann= 15 ,-1 , 0
  4053.1     .07       0    4340      .1       0  4390.1     .07       0
  4624.1    .035       0  4724.1     .07       0  4890.8    .035       0
  4958.9    .035       0  5011.1    .035       0  5122.3     .07       0
  5266.1    .035       0  5371.3     .07       0  5515.6    .035       0
  5613.9     .07       0  5779.4    .035       0  5893.6     .07       0
Bank Sta=4958.9,5011.1
XS Rating Curve= 0 ,0
Exp/Cntr=0.3,0.1

Type RM Length L Ch R = 1 ,39171   ,558,558,558
BEGIN DESCRIPTION:
Turtle Creek 57.0
END DESCRIPTION:
XS GIS Cut Line= 3
      1917348.58     13899899.56        1917375.       13898975.
      1917368.85     13897685.36
#Sta/Elev= 30
  4070.5 1656.26  4235.1 1650.35  4335.2 1638.38  4475.2 1615.66  4515.2 1624.62
  4545.3 1627.62  4615.3 1627.76  4706.5 1632.28  4820.4 1635.39  4885.4 1631.84
  4925.4 1625.85  4945.4 1617.43  4955.4 1615.37  4959.3 1611.82  4960.3 1611.32
  5011.5 1611.82  5015.4 1616.87  5021.6 1616.64  5045.4 1612.14  5085.4 1612.27
  5105.4 1616.77  5125.4 1617.48  5145.4 1622.44  5175.4    1624  5212.3  1629.8
  5292.4 1634.17  5615.4 1636.28  5703.5 1634.89  5847.6 1637.36  6285.1 1644.67
#Mann= 9 ,-1 , 0
  4070.5     .07       0  4706.5    .035       0  4959.3    .035       0
  5011.5    .035       0  5021.6     .07       0  5212.3    .035       0
  5292.4     .07       0  5703.5    .035       0  5847.6     .07       0
Bank Sta=4959.3,5011.5
XS Rating Curve= 0 ,0
Exp/Cntr=0.3,0.1

Type RM Length L Ch R = 1 ,38613   ,589,589,589
BEGIN DESCRIPTION:
Turtle Creek 56.0
END DESCRIPTION:
XS GIS Cut Line= 3
      1918074.98     13899224.96      1917861.16       13898868.
      1917618.78     13897631.12
#Sta/Elev= 30
    4599 1641.89  4689.6 1637.63  4759.8 1635.88  4855.4 1633.42    4877 1630.86
  4882.8 1631.38  4890.4 1629.74  4898.4 1621.62  4904.2 1622.46  4919.8 1615.54
  4948.7 1609.86  4984.9 1609.26  4986.3 1608.36  5041.6 1608.36    5043 1609.26
  5048.7  1612.1  5097.4 1617.67  5120.1 1620.86    5171 1621.32  5233.2 1625.14
    5319 1632.37  5331.1 1631.69  5344.2 1633.18  5576.9 1634.41  5680.5 1633.71
  5953.3 1635.86  6047.4 1637.26  6088.1 1638.93  6108.3 1638.46  6275.5 1641.62
#Mann= 10 ,-1 , 0
    4599     .07       0  4689.6    .035       0  4759.8     .07       0
  4855.4    .035       0  4984.9     .05       0    5043    .035       0
  5097.4    .035       0    5319     .07       0  5576.9    .035       0
  5953.3     .07       0
Bank Sta=4984.9,5043
XS Rating Curve= 0 ,0
Exp/Cntr=0.3,0.1

Type RM Length L Ch R = 1 ,38024   ,507,507,507
BEGIN DESCRIPTION:
Turtle Creek 55.0
END DESCRIPTION:
XS GIS Cut Line= 3
       1918476.7     13899452.28        1918325.       13898625.
      1917869.27     13897606.16
#Sta/Elev= 30
  4162.9 1649.24    4450 1642.57  4466.9 1642.15    4516 1641.52  4585.1 1638.65
  4643.3 1633.75  4754.7 1631.64    4821 1627.92  4841.3 1623.82  4851.5 1616.72
    4861 1613.62    4882 1612.64  4902.3 1609.38  4943.3 1609.29  4944.7 1608.39
  5001.4 1609.29  5012.8 1610.61  5041.5 1610.49  5080.7 1617.69  5098.3 1618.39
  5134.3 1619.55  5209.4 1629.24  5227.3 1630.15  5284.5 1631.81  5364.9 1631.95
  5398.2 1632.07    5572 1632.21  5822.3 1633.93  6018.5 1637.41  6120.1 1639.87
#Mann= 11 ,-1 , 0
  4162.9     .07       0    4450    .035       0  4466.9     .07       0
  4943.3     .05       0  5001.4     .07       0  5098.3    .094       0
  5227.3     .07       0  5364.9    .035       0  5398.2     .07       0
    5572    .035       0  6018.5     .07       0
Bank Sta=4943.3,5001.4
XS Rating Curve= 0 ,0
Exp/Cntr=0.3,0.1

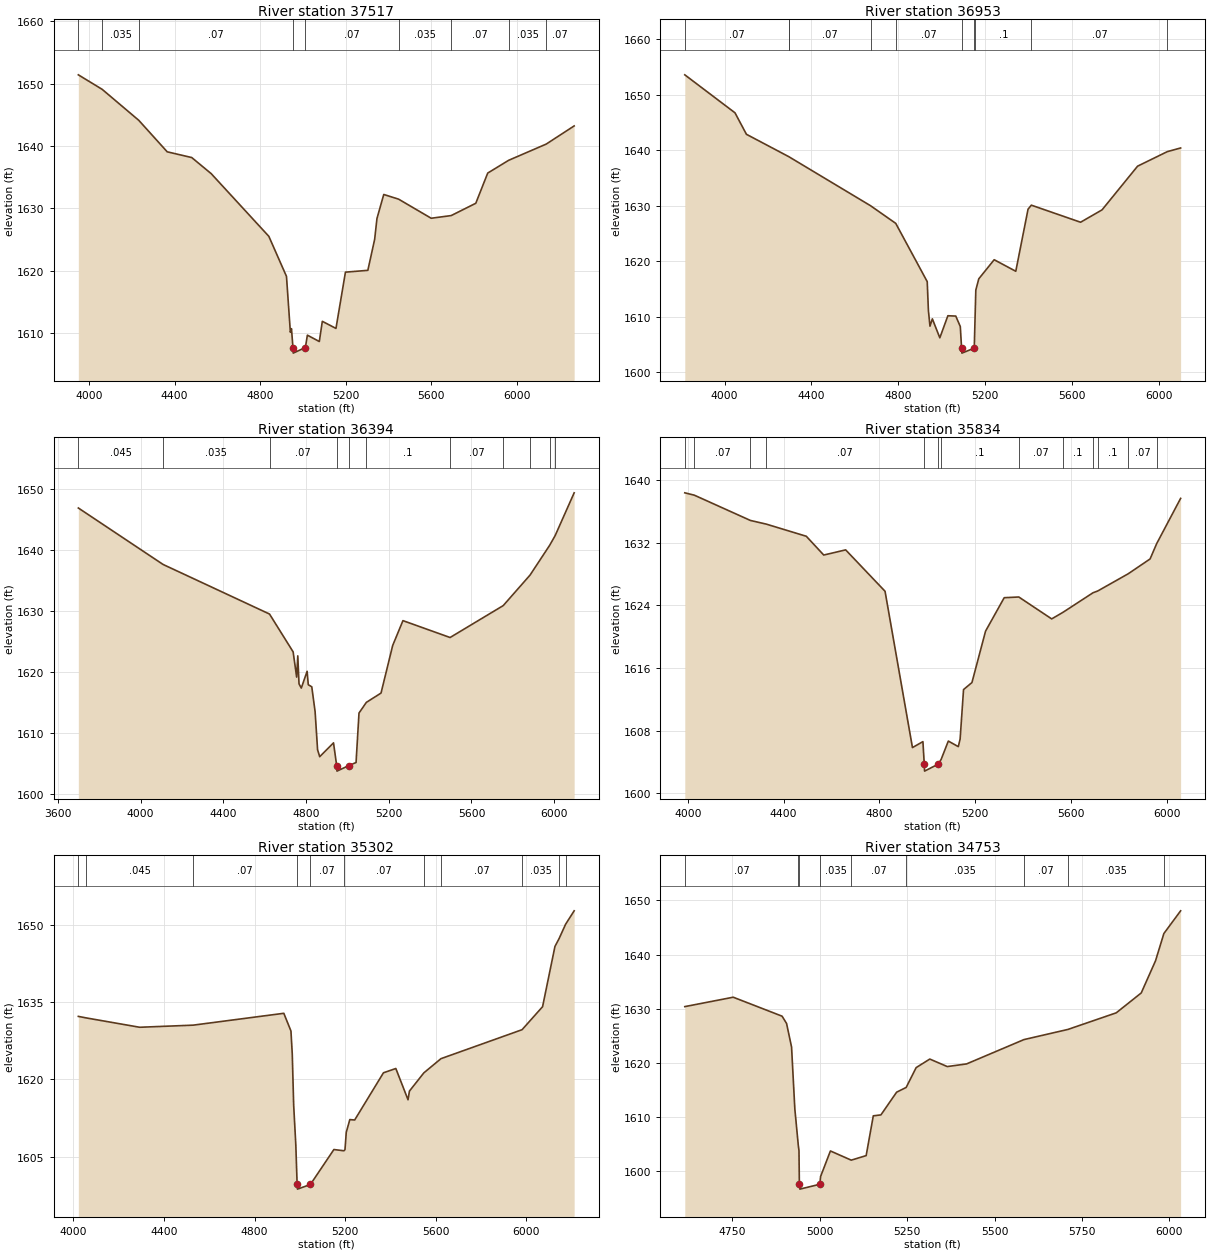
Type RM Length L Ch R = 1 ,37517   ,564,564,564
BEGIN DESCRIPTION:
Turtle Creek 54.0
END DESCRIPTION:
XS GIS Cut Line= 3
      1918517.84     13899549.52        1918775.       13898525.
       1918342.1     13897338.19
#Sta/Elev= 30
  3949.9  1651.4  4061.6 1649.07  4232.6 1644.11  4365.7 1639.06  4480.4 1638.14
  4571.5 1635.56  4841.2 1625.51  4923.7 1619.09  4941.9 1610.13    4947 1610.71
    4954 1607.69  4955.3 1606.79  5012.1 1607.69  5021.5 1609.67  5077.3 1608.65
  5091.4 1611.89  5155.2 1610.75  5199.5 1619.77  5304.3 1620.06  5336.2 1625.03
    5347 1628.37  5378.8 1632.22  5448.2 1631.47  5600.7 1628.41  5694.4 1628.84
  5809.3 1630.81  5865.1 1635.65  5963.2  1637.7  6138.9  1640.3  6269.5 1643.21
#Mann= 9 ,-1 , 0
  3949.9     .07       0  4061.6    .035       0  4232.6     .07       0
    4954     .05       0  5012.1     .07       0  5448.2    .035       0
  5694.4     .07       0  5963.2    .035       0  6138.9     .07       0
Bank Sta=4954,5012.1
XS Rating Curve= 0 ,0
Exp/Cntr=0.3,0.1

Type RM Length L Ch R = 1 ,36953   ,559,559,559
BEGIN DESCRIPTION:
Turtle Creek 53.0
END DESCRIPTION:
XS GIS Cut Line= 3
      1919690.99     13899312.56        1919225.       13898225.
      1918514.58     13897385.82
#Sta/Elev= 30
  3817.2 1653.62  4048.3 1646.77  4100.9  1642.9  4294.7 1638.89  4294.8 1638.89
  4672.3 1630.02  4788.3 1626.84  4933.3 1616.33  4938.7 1611.15    4946  1608.3
  4956.9 1609.62  4991.3  1606.2  5028.4 1610.18  5064.7 1610.12  5085.5 1608.24
  5091.5 1604.34  5092.9 1603.44  5149.8 1604.34    5155 1611.89    5157  1614.8
  5170.7 1616.84  5241.5 1620.28    5341  1618.2  5397.5 1629.39  5412.6 1630.12
  5639.3 1627.04  5738.1 1629.27  5901.8 1637.15  6038.6 1639.77  6099.9 1640.43
#Mann= 10 ,-1 , 0
  3817.2     .07       0  4294.7    .035       0  4294.8     .07       0
  4672.3      .1       0  4788.3     .07       0  5091.5     .05       0
  5149.8     .07       0    5155      .1       0  5412.6     .07       0
  6038.6    .035       0
Bank Sta=5091.5,5149.8
XS Rating Curve= 0 ,0
Exp/Cntr=0.3,0.1

Type RM Length L Ch R = 1 ,36394   ,560,560,560
BEGIN DESCRIPTION:
Turtle Creek 52.0
END DESCRIPTION:
XS GIS Cut Line= 3
      1920094.55     13899044.12        1919525.       13897875.
      1918774.97     13897074.97
#Sta/Elev= 30
  3699.3 1646.85  4109.1 1637.61  4623.6  1629.5  4737.8 1623.31  4754.8 1619.18
  4760.3 1622.66  4766.2 1618.08  4777.3 1617.39  4805.4 1620.14    4811 1617.93
  4827.9  1617.6    4844 1613.53    4856 1607.29  4866.3 1606.16    4933 1608.43
  4948.3  1604.7  4949.7  1603.8  5006.8  1604.7    5042 1605.21  5056.2  1613.3
  5091.8 1615.05  5162.7 1616.57  5219.1 1624.36  5268.7 1628.42  5496.5 1625.66
  5753.5 1630.88  5883.1 1635.87  5978.1 1640.75  6004.5 1642.33  6096.4 1649.33
#Mann= 11 ,-1 , 0
  3699.3    .045       0  4109.1    .035       0  4623.6     .07       0
  4948.3     .05       0  5006.8     .07       0  5091.8      .1       0
  5496.5     .07       0  5753.5      .1       0  5883.1    .035       0
  5978.1     .07       0  6004.5    .035       0
Bank Sta=4948.3,5006.8
XS Rating Curve= 0 ,0
Exp/Cntr=0.3,0.1

Type RM Length L Ch R = 1 ,35834   ,532,532,532
BEGIN DESCRIPTION:
Turtle Creek 51.0
END DESCRIPTION:
XS GIS Cut Line= 3
      1920730.15     13898131.85        1919925.       13897525.
      1919125.03     13896825.03
#Sta/Elev= 30
  3987.3 1638.39  4027.1 1638.09  4261.4 1634.86  4327.9 1634.39  4494.8 1632.84
  4567.7 1630.44  4659.3  1631.1  4823.8 1625.81  4938.3 1605.84    4982  1606.6
  4987.6 1603.73    4989 1602.83  5046.2 1603.73  5058.3 1604.34  5088.1 1606.67
  5129.8 1605.96  5137.4 1606.92  5151.7 1613.25  5186.8 1614.15  5243.7 1620.72
  5321.6 1624.99  5382.5 1625.08  5519.9 1622.28    5567 1623.12  5692.5 1625.62
  5712.4 1625.85  5839.8 1628.05  5930.9 1629.94  5958.5  1631.9  6058.5 1637.68
#Mann= 13 ,-1 , 0
  3987.3    .045       0  4027.1     .07       0  4261.4    .035       0
  4327.9     .07       0  4987.6     .05       0  5046.2     .07       0
  5058.3      .1       0  5382.5     .07       0    5567      .1       0
  5692.5    .035       0  5712.4      .1       0  5839.8     .07       0
  5958.5    .035       0
Bank Sta=4987.6,5046.2
XS Rating Curve= 0 ,0
Exp/Cntr=0.3,0.1

Type RM Length L Ch R = 1 ,35302   ,549,549,549
BEGIN DESCRIPTION:
Turtle Creek 50.0
END DESCRIPTION:
XS GIS Cut Line= 3
      1921017.19     13897564.54        1920175.       13897075.
      1919039.92     13896640.03
#Sta/Elev= 30
  4021.8  1632.2  4057.2  1631.9  4292.8 1630.09  4528.9  1630.5  4929.3  1632.8
  4960.8 1629.36  4966.6 1624.89  4972.8 1615.01  4982.3 1607.23  4988.1 1599.59
  4989.5 1598.69  5046.7 1599.59  5150.4 1606.37  5194.8 1606.13  5199.4 1606.35
  5205.1 1609.72  5220.8 1612.18  5242.2  1612.1  5369.3 1621.26    5424 1622.09
  5477.8 1616.03  5484.1 1617.71  5547.8 1621.25  5623.3    1624  5981.5 1629.62
    6072 1634.08  6126.7 1645.77  6144.7 1647.27  6173.9 1650.09  6211.5 1652.68
#Mann= 11 ,-1 , 0
  4021.8    .035       0  4057.2    .045       0  4528.9     .07       0
  4988.1    .035       0  5046.7     .07       0  5194.8     .07       0
  5547.8    .035       0  5623.3     .07       0  5981.5    .035       0
  6144.7      .1       0  6173.9     .07       0
Bank Sta=4988.1,5046.7
XS Rating Curve= 0 ,0
Exp/Cntr=0.3,0.1

Type RM Length L Ch R = 1 ,34753   ,566,566,566
BEGIN DESCRIPTION:
Turtle Creek 49.0
END DESCRIPTION:
XS GIS Cut Line= 3
      1920500.55     13896732.01        1920175.       13896525.
      1919164.77     13896314.11
#Sta/Elev= 30
  4614.2 1630.36  4752.7  1632.1  4892.4 1628.59  4905.2 1627.25  4919.5 1622.88
  4928.9  1611.4  4938.8 1604.67  4940.7 1603.74  4941.8  1597.5  4943.2  1596.6
  5000.5  1597.5  5002.5 1598.93  5030.6 1603.66  5090.1 1601.96  5132.8  1602.8
  5153.2 1610.16    5175 1610.33  5219.9 1614.53  5247.2 1615.41  5275.8 1619.08
  5314.8 1620.66  5364.8 1619.27  5419.9 1619.76    5584 1624.26  5709.7 1626.14
  5847.9 1629.21  5919.4 1632.89  5960.3 1638.85  5984.1 1643.88    6032 1648.08
#Mann= 9 ,-1 , 0
  4614.2     .07       0  4938.8    .035       0  4941.8    .035       0
  5000.5    .035       0  5090.1     .07       0  5247.2    .035       0
    5584     .07       0  5709.7    .035       0  5984.1     .07       0
Bank Sta=4941.8,5000.5
XS Rating Curve= 0 ,0
Exp/Cntr=0.3,0.1

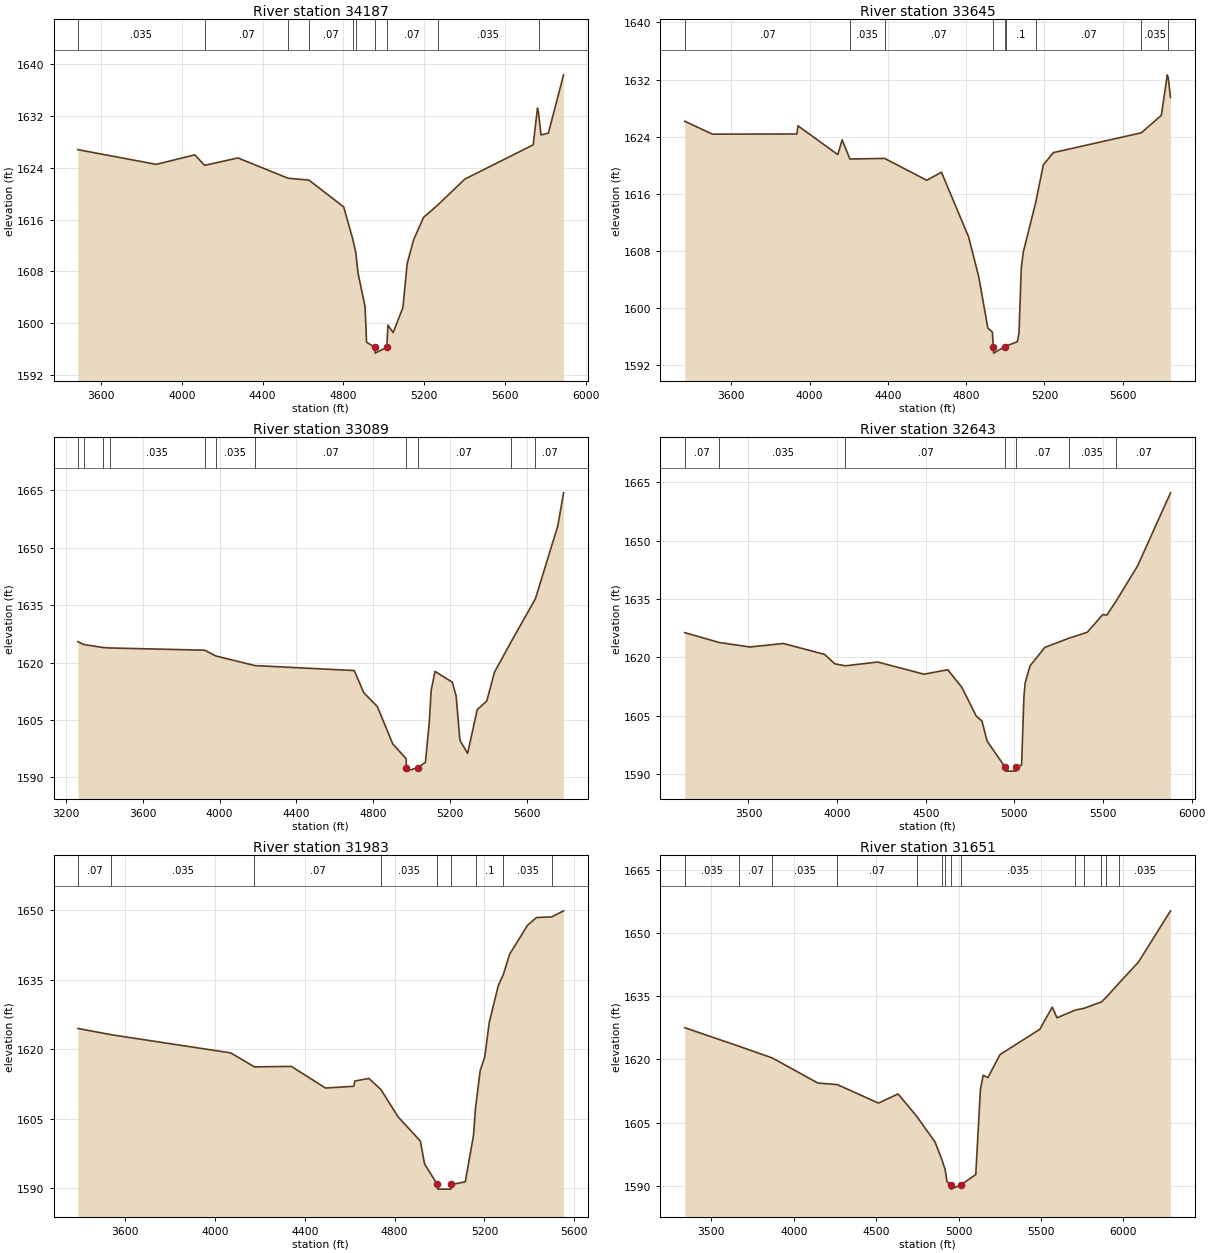
Type RM Length L Ch R = 1 ,34187   ,542,542,542
BEGIN DESCRIPTION:
Turtle Creek 48.0
END DESCRIPTION:
XS GIS Cut Line= 4
      1921011.14     13897186.14      1920897.13     13896600.02
        1920225.       13895975.      1919382.86      13895684.1
#Sta/Elev= 30
  3484.6 1626.78  3872.9 1624.51    4064 1625.98  4112.6 1624.36  4277.6  1625.5
  4526.3 1622.37  4629.3 1622.09  4801.4 1617.95  4846.7 1612.96  4861.6 1610.89
  4872.3 1607.79  4907.4 1602.55  4914.8  1597.1  4956.2 1596.32  4957.7 1595.42
    5015 1596.32  5020.7 1599.73  5046.3 1598.58  5094.8 1602.44  5115.9 1609.21
  5147.7 1612.89  5196.9 1616.33  5266.5 1618.22  5401.6 1622.24  5740.1 1627.52
  5761.3 1633.17  5766.5  1632.5  5778.9 1629.05  5815.3 1629.32  5890.5 1638.31
#Mann= 10 ,-1 , 0
  3484.6    .035       0  4112.6     .07       0  4526.3    .035       0
  4629.3     .07       0  4846.7    .035       0  4861.6     .07       0
  4956.2     .05       0    5015     .07       0  5266.5    .035       0
  5766.5     .07       0
Bank Sta=4956.2,5015
XS Rating Curve= 0 ,0
Exp/Cntr=0.3,0.1

Type RM Length L Ch R = 1 ,33645   ,556,556,556
BEGIN DESCRIPTION:
Turtle Creek 47.0
END DESCRIPTION:
XS GIS Cut Line= 4
      1921028.51     13897055.97      1920918.38     13896509.97
        1920475.       13895525.      1919649.03     13895352.75
#Sta/Elev= 30
  3362.8 1626.15  3504.3 1624.34  3935.5 1624.36    3941 1625.51  4144.6 1621.47
  4166.5 1623.54  4206.2 1620.85  4383.4 1620.94  4598.8 1617.87  4673.8    1619
  4812.6 1609.92  4864.4 1604.33  4910.7 1597.14  4933.9 1596.58  4938.6 1594.53
    4940 1593.63  4997.4 1594.53  5004.7 1594.63  5061.3 1595.23  5069.9 1596.43
  5081.7 1605.66  5091.9 1607.82  5155.8 1614.83    5194 1620.03  5245.1 1621.75
  5694.6 1624.53  5796.7 1626.97  5827.4 1632.66  5832.1 1632.25  5843.7 1629.49
#Mann= 9 ,-1 , 0
  3362.8     .07       0  4206.2    .035       0  4383.4     .07       0
  4938.6     .05       0  4997.4     .07       0  5004.7      .1       0
  5155.8     .07       0  5694.6    .035       0  5832.1     .07       0
Bank Sta=4938.6,4997.4
XS Rating Curve= 0 ,0
Exp/Cntr=0.3,0.1

Type RM Length L Ch R = 1 ,33089   ,446,446,446
BEGIN DESCRIPTION:
Turtle Creek 46.0
END DESCRIPTION:
XS GIS Cut Line= 3
      1921054.42     13897051.56        1920925.       13895325.
        1920925.     13894525.01
#Sta/Elev= 30
    3261 1625.44  3292.4 1624.69  3391.3 1623.92  3426.8  1623.8  3922.1 1623.21
  3979.9 1621.71  4184.4 1619.19  4701.6  1617.9  4751.7 1612.08  4821.9 1608.51
  4902.2 1598.75  4972.3 1594.88    4973 1592.54  4974.4 1591.64  5031.8 1592.54
  5072.4 1593.94  5092.4 1604.26  5102.4 1612.73  5122.4 1617.68  5212.4 1614.86
  5232.4 1611.29  5252.4 1599.67  5292.4 1596.27  5342.4  1607.7  5392.4 1609.97
  5432.4 1617.48  5517.3 1625.24  5645.6 1636.62  5762.4 1655.68  5792.4  1664.3
#Mann= 11 ,-1 , 0
    3261    .045       0  3292.4    .035       0  3391.3     .07       0
  3426.8    .035       0  3922.1     .07       0  3979.9    .035       0
  4184.4     .07       0    4973     .05       0  5031.8     .07       0
  5517.3    .035       0  5645.6     .07       0
Bank Sta=4973,5031.8
XS Rating Curve= 0 ,0
Exp/Cntr=0.3,0.1

Type RM Length L Ch R = 1 ,32643   ,660,660,660
BEGIN DESCRIPTION:
Mapping XS c354ebef
END DESCRIPTION:
XS GIS Cut Line= 4
      1921094.95     13897118.33      1921233.85     13895672.99
      1921338.01     13895186.87      1921168.75     13894414.35
#Sta/Elev= 30
  3140.7 1626.32  3336.1 1623.77  3508.9 1622.63  3696.6 1623.53    3929 1620.73
  3987.9 1618.28  4047.3 1617.79    4229 1618.76  4490.2 1615.63  4624.3 1616.78
  4703.1 1612.29    4785 1604.84  4816.9 1603.61  4846.3 1598.41  4948.3 1591.69
  4949.8 1590.69  5008.7 1590.69  5010.2 1591.69  5040.6 1592.25  5053.8  1609.9
  5061.1 1613.42  5088.3 1617.77  5171.3 1622.51  5306.5 1624.87  5410.9 1626.41
  5498.6 1630.97  5521.7 1630.84  5573.9 1634.44  5695.8 1643.56  5880.7 1662.29
#Mann= 7 ,-1 , 0
  3140.7     .07       0  3336.1    .035       0  4047.3     .07       0
  4948.3     .05       0  5010.2     .07       0  5306.5    .035       0
  5573.9     .07       0
Bank Sta=4948.3,5010.2
XS Rating Curve= 0 ,0
Exp/Cntr=0.3,0.1

Type RM Length L Ch R = 1 ,31983   ,332,332,332
BEGIN DESCRIPTION:
Turtle Creek 45.0
END DESCRIPTION:
XS GIS Cut Line= 3
       1921165.3       13897066.      1921783.01     13895550.25
        1921825.     13895025.01
#Sta/Elev= 30
  3388.9 1624.53  3538.7 1623.17  4070.3 1619.25  4175.4 1616.24  4340.2 1616.34
  4492.3 1611.67  4617.9 1612.05  4623.3 1613.19  4685.8 1613.74  4739.4 1611.32
  4815.4 1605.45  4914.8 1600.23  4933.5 1595.27  4990.6 1590.85  4992.1 1589.85
  5051.2 1589.85  5052.7 1590.85  5114.8 1591.43  5151.3 1601.39  5160.7  1607.5
  5181.4 1615.47  5201.5 1618.37  5221.6 1625.85  5261.7 1633.76  5284.2 1636.15
  5311.8  1640.5  5392.1 1646.81  5432.2 1648.47  5500.2 1648.62  5552.6 1649.92
#Mann= 9 ,-1 , 0
  3388.9     .07       0  3538.7    .035       0  4175.4     .07       0
  4739.4    .035       0  4990.6    .035       0  5052.7    .035       0
  5160.7      .1       0  5284.2    .035       0  5500.2     .07       0
Bank Sta=4990.6,5052.7
XS Rating Curve= 0 ,0
Exp/Cntr=0.3,0.1

Type RM Length L Ch R = 1 ,31651   ,722,722,722
BEGIN DESCRIPTION:
Turtle Creek 44.0
END DESCRIPTION:
XS GIS Cut Line= 3
      1921282.23     13897267.63        1922025.       13895775.
      1922577.68     13894618.95
#Sta/Elev= 30
  3338.3 1627.55  3664.7 1623.18  3869.5 1620.36  4146.2 1614.39  4264.3 1614.02
  4514.1 1609.62  4633.3 1611.79  4745.4 1606.53  4857.2 1600.37  4900.3 1596.05
  4919.3 1593.71    4930 1590.97  4952.1 1590.15  4953.6 1589.15  5014.2 1590.15
  5104.8 1592.63    5133 1612.84  5149.6 1616.24  5178.4 1615.69  5251.9 1621.16
  5493.2 1627.17  5569.4 1632.46  5597.6 1629.91  5709.4 1631.76  5760.2 1632.15
  5867.6 1633.69  5895.7 1634.76  5975.1  1638.2  6091.8 1643.14  6286.9 1655.36
#Mann= 14 ,-1 , 0
  3338.3    .035       0  3664.7     .07       0  3869.5    .035       0
  4264.3     .07       0  4745.4    .035       0  4900.3     .07       0
  4919.3    .035       0  4952.1    .035       0  5014.2    .035       0
  5709.4    .035       0  5760.2     .07       0  5867.6    .035       0
  5895.7     .07       0  5975.1    .035       0
Bank Sta=4952.1,5014.2
XS Rating Curve= 0 ,0
Exp/Cntr=0.3,0.1