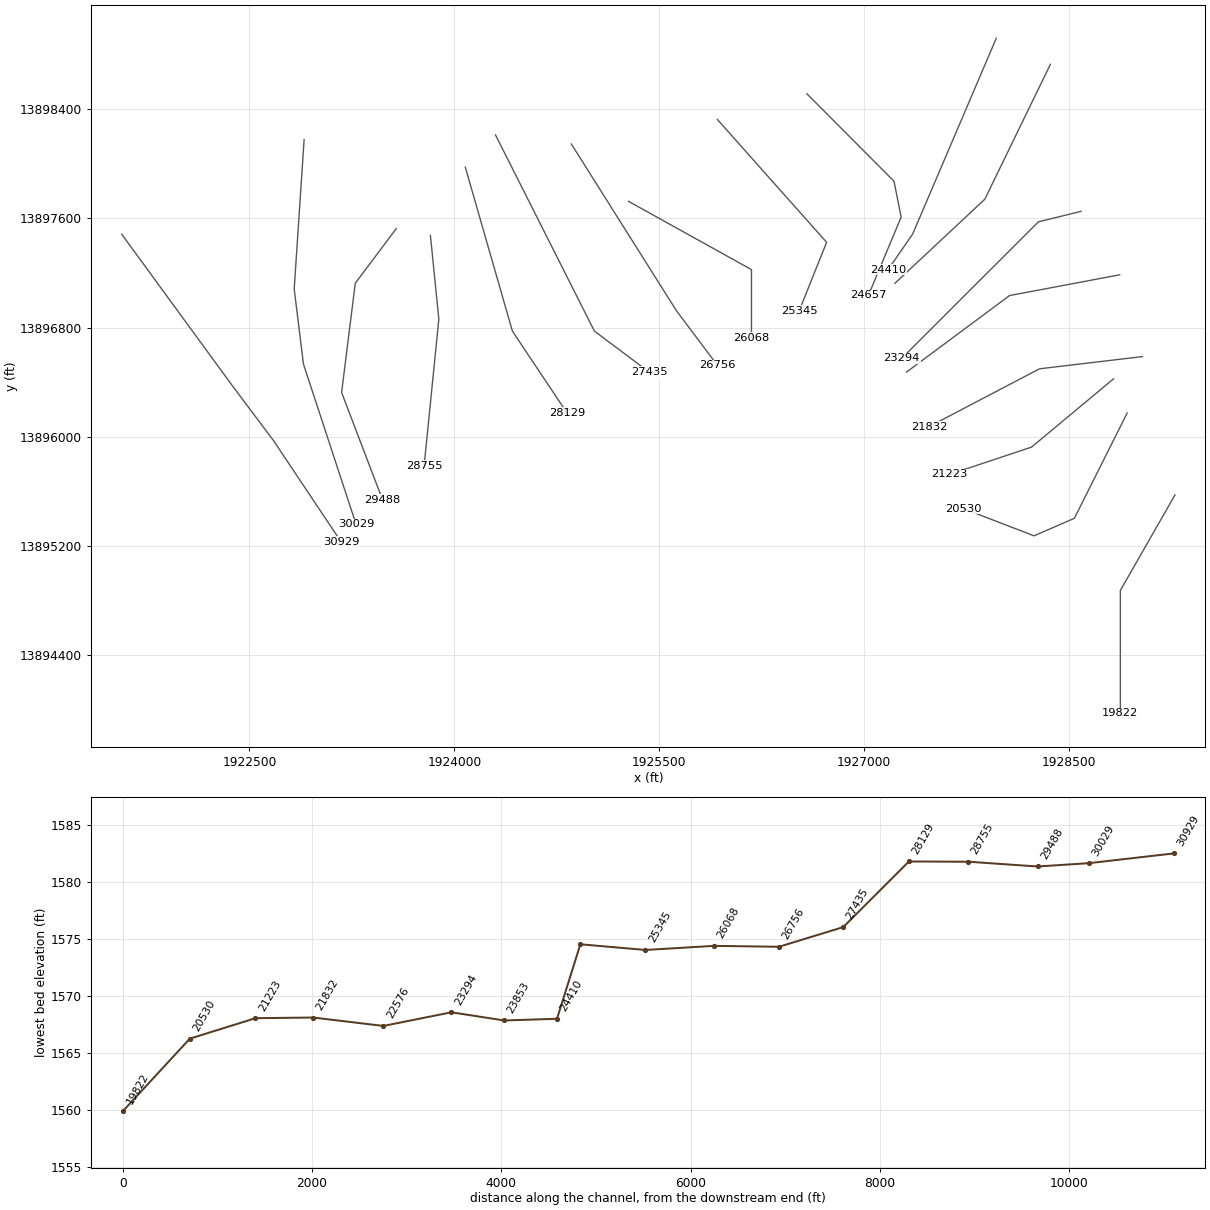
HEC-RAS study Turtle Creek.prj: Turtle Creek Base Level Engineering

--- Turtle Creek.g01 (geometry) --- (continued)

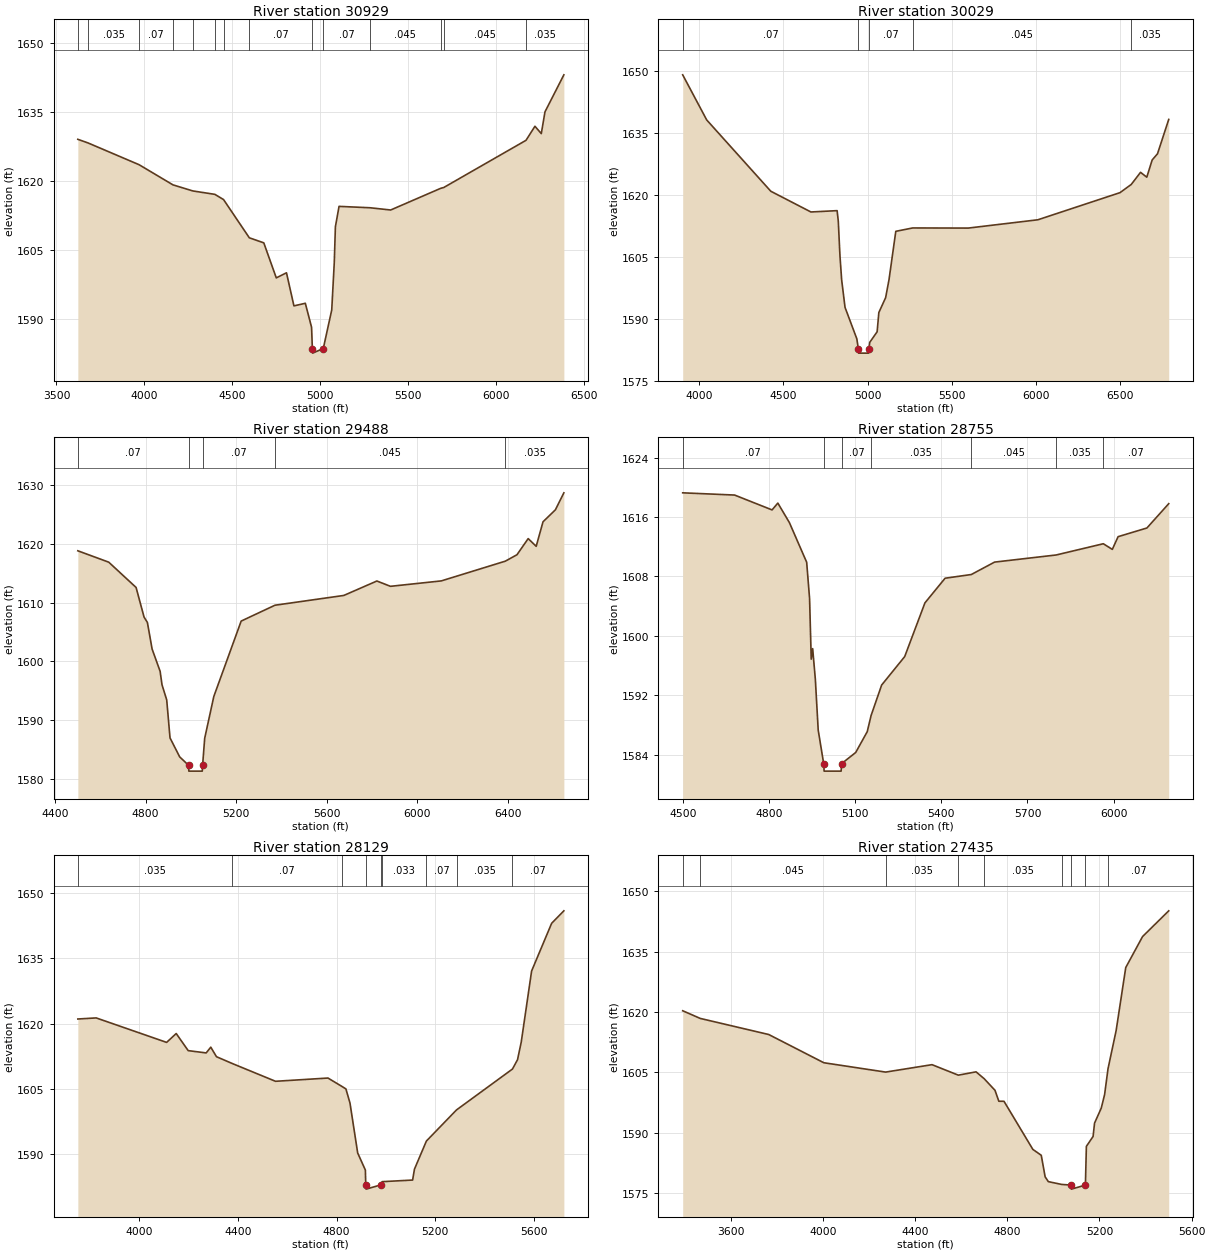
Type RM Length L Ch R = 1 ,30929   ,900,900,900
BEGIN DESCRIPTION:
Turtle Creek 43.0
END DESCRIPTION:
XS GIS Cut Line= 4
      1921565.46     13897484.07        1922375.       13896375.
        1922675.       13895975.      1923170.79     13895232.27
#Sta/Elev= 30
  3621.7 1629.09  3679.1 1628.31  3970.3 1623.56  4163.2 1619.17  4276.2 1617.85
  4401.3 1617.11    4451 1615.97  4597.6 1607.65    4680 1606.55  4751.1 1598.92
  4809.1 1600.03  4851.5 1592.83  4916.4 1593.39  4951.9 1588.17  4956.4 1583.54
  4957.9 1582.54  5018.6 1583.54  5066.7 1591.94  5081.2 1602.32  5087.5 1610.05
  5108.3 1614.49  5284.3 1614.19  5402.1  1613.7  5686.8 1618.42  5704.3  1618.6
  6172.3 1628.87  6223.2 1631.93  6259.3 1630.33  6280.3 1635.07  6387.8 1643.13
#Mann= 14 ,-1 , 0
  3621.7     .07       0  3679.1    .035       0  3970.3     .07       0
  4163.2      .1       0  4276.2     .07       0  4401.3      .1       0
    4451    .035       0  4597.6     .07       0  4956.4     .05       0
  5018.6     .07       0  5284.3    .045       0  5686.8    .035       0
  5704.3    .045       0  6172.3    .035       0
Bank Sta=4956.4,5018.6
XS Rating Curve= 0 ,0
Exp/Cntr=0.3,0.1

Type RM Length L Ch R = 1 ,30029   ,541,541,541
BEGIN DESCRIPTION:
Turtle Creek 42.0
END DESCRIPTION:
XS GIS Cut Line= 4
      1922900.54     13898177.17      1922828.03     13897083.08
      1922895.74     13896532.95      1923281.31     13895358.29
#Sta/Elev= 30
  3901.7 1649.07  4044.2 1638.15    4425 1620.88  4663.3 1615.86    4819 1616.18
  4825.9 1613.64  4835.9 1605.21  4845.9 1599.43    4866 1592.76  4936.1 1585.14
  4945.1 1582.68  4946.6 1581.68  5005.9 1581.68  5007.4 1582.68  5012.8 1584.29
  5056.7 1586.85  5066.8 1591.51  5107.1  1595.1  5127.2 1599.46  5167.5 1611.17
  5267.8 1611.99  5597.9 1611.96  6011.6 1613.97  6499.4 1620.54  6566.3 1622.53
  6621.4 1625.46  6658.5 1624.28  6690.3 1628.44  6722.2 1629.96  6788.8 1638.27
#Mann= 5 ,-1 , 0
  3901.7     .07       0  4945.1     .05       0  5007.4     .07       0
  5267.8    .045       0  6566.3    .035       0
Bank Sta=4945.1,5007.4
XS Rating Curve= 0 ,0
Exp/Cntr=0.3,0.1

Type RM Length L Ch R = 1 ,29488   ,733,733,733
BEGIN DESCRIPTION:
Turtle Creek 41.0
END DESCRIPTION:
XS GIS Cut Line= 4
      1923575.02     13897525.03        1923275.       13897125.
        1923175.       13896325.      1923474.76     13895538.87
#Sta/Elev= 30
  4500.3 1618.79  4636.8 1616.86  4757.6 1612.57    4793 1607.53  4807.6 1606.63
  4828.5 1602.11  4863.9 1598.33  4872.2 1596.05    4893 1593.48  4907.6 1587.03
  4950.3 1583.81  4989.3 1582.39  4990.8 1581.39  5050.1 1581.39  5051.6 1582.39
  5060.8 1586.96  5101.1 1594.06    5222 1606.86  5371.3 1609.55  5675.5 1611.21
  5821.6 1613.66  5881.8 1612.76  6106.4 1613.68  6389.2 1617.03  6440.7 1618.12
  6490.2 1620.86  6525.6 1619.55  6555.7 1623.71  6610.5 1625.75  6647.9 1628.63
#Mann= 5 ,-1 , 0
  4500.3     .07       0  4989.3     .05       0  5051.6     .07       0
  5371.3    .045       0  6389.2    .035       0
Bank Sta=4989.3,5051.6
XS Rating Curve= 0 ,0
Exp/Cntr=0.3,0.1

Type RM Length L Ch R = 1 ,28755   ,626,626,626
BEGIN DESCRIPTION:
Turtle Creek 40.0
END DESCRIPTION:
XS GIS Cut Line= 3
        1923825.     13897474.95      1923886.69     13896862.88
      1923779.15     13895789.43
#Sta/Elev= 30
  4498.3 1619.25  4679.2 1618.95  4809.8 1616.95  4829.9 1617.87  4870.1 1615.25
  4930.4 1609.91  4940.5 1605.04  4946.3 1596.87  4951.3 1598.29  4960.6 1594.18
  4970.6 1587.33  4989.7 1582.81  4991.2 1581.81  5050.5 1581.81    5052 1582.81
  5101.3 1584.32  5141.5 1587.12  5154.9 1589.29  5191.7 1593.39  5272.1 1597.22
  5342.5 1604.44  5412.8 1607.76  5504.2 1608.26  5585.3 1609.93  5800.2 1610.89
  5964.3  1612.4  5995.7 1611.64  6015.8 1613.35  6116.3 1614.52  6192.3 1617.79
#Mann= 7 ,-1 , 0
  4498.3     .07       0  4989.7     .05       0    5052     .07       0
  5154.9    .035       0  5504.2    .045       0  5800.2    .035       0
  5964.3     .07       0
Bank Sta=4989.7,5052
XS Rating Curve= 0 ,0
Exp/Cntr=0.3,0.1

Type RM Length L Ch R = 1 ,28129   ,694,694,694
BEGIN DESCRIPTION:
Turtle Creek 39.0
END DESCRIPTION:
XS GIS Cut Line= 3
      1924080.47     13897974.85        1924425.       13896775.
      1924824.98     13896175.04
#Sta/Elev= 30
  3751.8 1621.05  3826.1  1621.3  4111.5 1615.66  4150.4  1617.7    4199 1613.76
  4271.8 1613.23  4290.5 1614.56  4313.5 1612.36  4378.3 1610.77  4552.8 1606.69
  4765.3 1607.44  4820.9 1605.54    4838 1604.93  4854.5 1601.69  4885.7 1590.17
  4916.9 1586.22  4918.4 1582.83  4919.9 1581.83  4980.8 1582.83  4984.7 1583.55
  5108.3 1583.92  5115.8 1586.44  5164.2 1592.92  5286.2 1600.09    5513 1609.52
  5533.5 1611.68  5548.5 1615.74  5590.5 1632.12  5671.7 1643.12  5721.2 1645.99
#Mann= 9 ,-1 , 0
  3751.8    .035       0  4378.3     .07       0  4820.9      .1       0
  4918.4    .033       0  4980.8      .1       0  4984.7    .033       0
  5164.2     .07       0  5286.2    .035       0    5513     .07       0
Bank Sta=4918.4,4980.8
XS Rating Curve= 0 ,0
Exp/Cntr=0.3,0.1

Type RM Length L Ch R = 1 ,27435   ,679,679,679
BEGIN DESCRIPTION:
Turtle Creek 38.0
END DESCRIPTION:
XS GIS Cut Line= 3
      1924301.22     13898211.75        1925025.       13896775.
      1925425.03     13896474.98
#Sta/Elev= 30
  3391.7  1620.3  3467.9  1618.4    3765 1614.41  4003.9 1607.41  4272.1 1605.09
  4473.4 1606.93  4587.5 1604.33  4664.5 1605.15  4699.4 1603.47  4746.7 1600.57
  4763.4 1597.86  4785.7 1597.85  4910.9 1585.92  4947.5 1584.45  4964.2 1579.12
  4978.1 1577.92  5035.6 1577.23  5076.6 1577.06  5078.1 1576.06    5139 1577.06
  5143.2 1586.67  5172.3 1589.13  5178.6 1592.43  5207.8 1596.16  5222.3 1599.52
  5237.1 1605.92  5272.3 1615.38    5314 1631.02  5386.9  1638.7  5500.5 1645.09
#Mann= 9 ,-1 , 0
  3391.7    .035       0  3467.9    .045       0  4272.1    .035       0
  4587.5     .07       0  4699.4    .035       0  5035.6      .1       0
  5076.6    .035       0    5139      .1       0  5237.1     .07       0
Bank Sta=5076.6,5139
XS Rating Curve= 0 ,0
Exp/Cntr=0.3,0.1

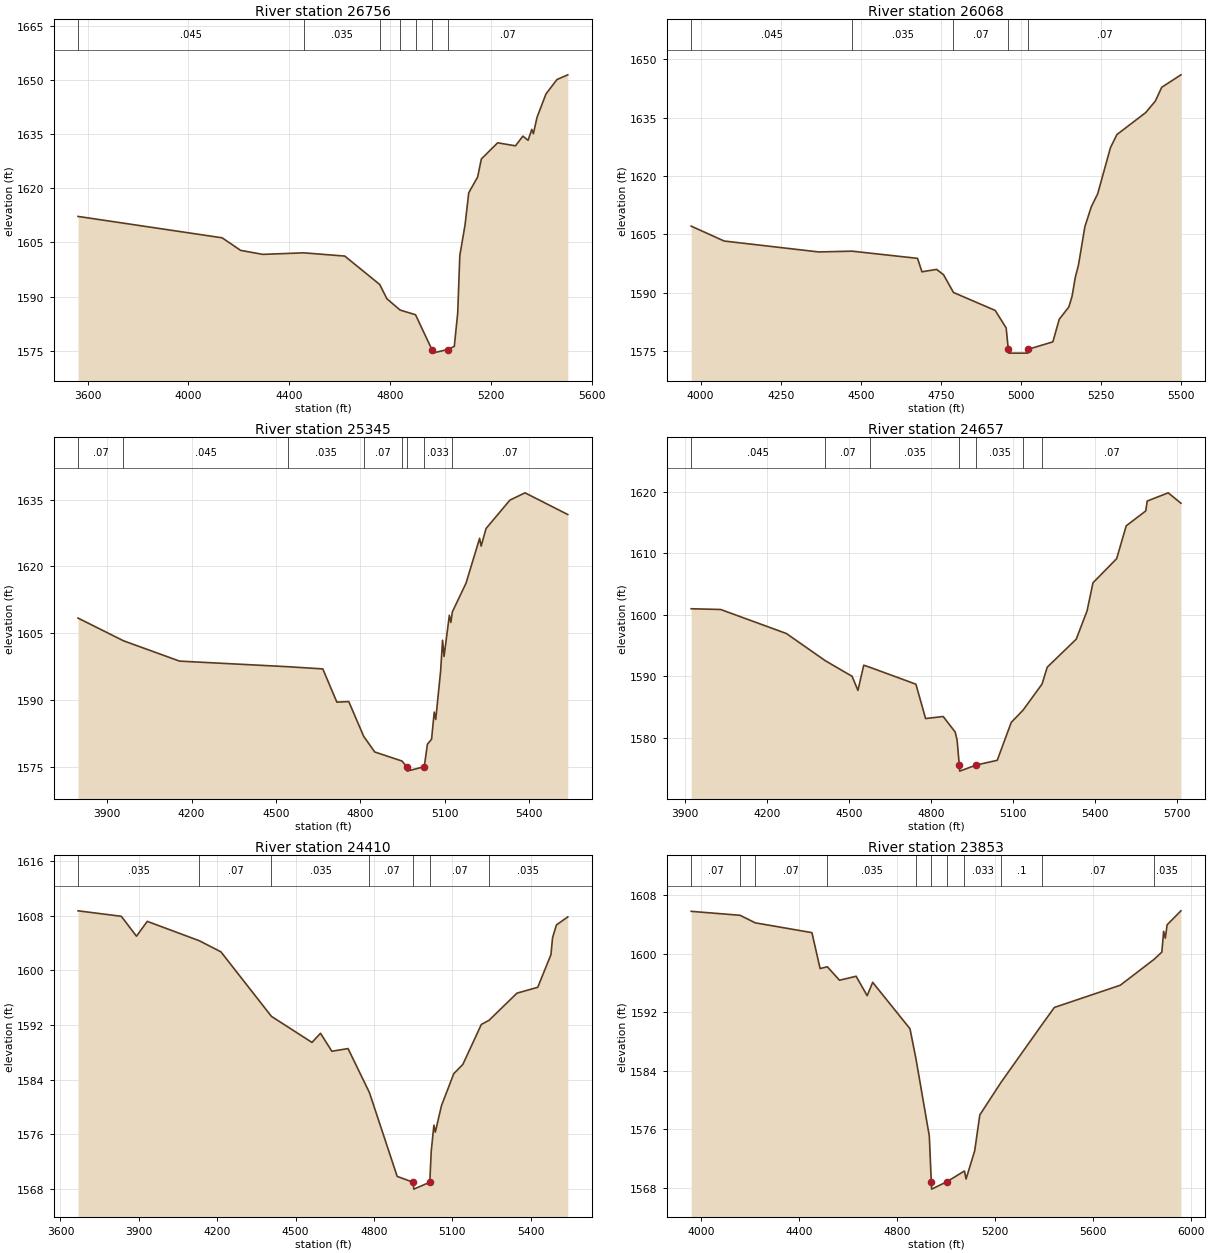
Type RM Length L Ch R = 1 ,26756   ,688,688,688
BEGIN DESCRIPTION:
Turtle Creek 37.0
END DESCRIPTION:
XS GIS Cut Line= 3
      1924856.36     13898145.08        1925625.       13896925.
      1925924.99     13896525.01
#Sta/Elev= 30
  3562.4 1612.21  4133.9 1606.28  4206.9 1602.81  4295.1 1601.69    4457 1602.12
  4620.1 1601.22  4758.7 1593.35  4787.2 1589.39  4839.6 1586.26  4900.7 1584.97
  4965.6 1575.33  4967.1 1574.33    5028 1575.33  5054.4 1576.19    5068  1585.5
  5076.3 1601.38  5097.1 1609.87  5111.7 1618.76  5147.1 1623.15  5161.7 1628.13
  5226.3  1632.6  5297.1 1631.77  5326.3 1634.45  5347.1  1633.3  5361.7 1636.32
    5368 1635.11  5382.5 1639.67    5418 1646.15  5461.7 1650.14  5504.4 1651.44
#Mann= 7 ,-1 , 0
  3562.4    .045       0    4457    .035       0  4758.7     .07       0
  4839.6    .035       0  4900.7     .07       0  4965.6     .05       0
    5028     .07       0
Bank Sta=4965.6,5028
XS Rating Curve= 0 ,0
Exp/Cntr=0.3,0.1

Type RM Length L Ch R = 1 ,26068   ,723,723,723
BEGIN DESCRIPTION:
Turtle Creek 36.0
END DESCRIPTION:
XS GIS Cut Line= 3
      1925274.98     13897725.01        1926175.       13897225.
        1926175.     13896724.98
#Sta/Elev= 30
  3970.4 1607.09  4073.4 1603.26  4368.5 1600.45  4472.7 1600.65  4677.4  1598.8
  4691.1 1595.34  4736.9 1595.96  4758.6 1594.59  4789.6 1590.02  4919.9  1585.4
  4954.2 1580.88  4960.8 1575.41  4962.3 1574.41  5021.7 1574.41  5023.2 1575.41
    5100 1577.31    5120 1583.13    5150  1586.3    5160 1589.05    5170 1593.87
    5180 1597.08    5200 1606.94    5220 1612.06    5240 1615.42    5280 1627.31
    5300 1630.65    5390 1636.31    5420 1639.27    5440 1642.82    5500 1646.03
#Mann= 5 ,-1 , 0
  3970.4    .045       0  4472.7    .035       0  4789.6     .07       0
  4960.8     .05       0  5023.2     .07       0
Bank Sta=4960.8,5023.2
XS Rating Curve= 0 ,0
Exp/Cntr=0.3,0.1

Type RM Length L Ch R = 1 ,25345   ,688,688,688
BEGIN DESCRIPTION:
Turtle Creek 35.0
END DESCRIPTION:
XS GIS Cut Line= 3
      1925924.98     13898325.02        1926725.       13897425.
        1926525.     13896925.01
#Sta/Elev= 30
  3795.8  1608.4  3957.3 1603.31  4157.1 1598.74  4543.6 1597.48  4666.8 1596.99
  4716.9 1589.53  4759.2 1589.66  4812.2 1581.87  4851.6 1578.35  4948.5 1576.32
  4965.4 1575.05  4966.9 1574.05  5027.9 1575.05    5039 1580.09  5053.8 1581.21
  5063.3  1587.3  5068.7 1585.66  5086.2 1596.62  5092.9 1603.43  5098.3 1599.79
  5117.1 1609.03  5122.5 1607.42  5127.8  1609.8  5176.4 1616.23  5224.8  1626.3
  5230.2 1624.55  5247.7  1628.5  5332.5 1634.87  5386.4 1636.51  5538.5 1631.64
#Mann= 8 ,-1 , 0
  3795.8     .07       0  3957.3    .045       0  4543.6    .035       0
  4812.2     .07       0  4948.5    .033       0  4965.4    .033       0
  5027.9    .033       0  5127.8     .07       0
Bank Sta=4965.4,5027.9
XS Rating Curve= 0 ,0
Exp/Cntr=0.3,0.1

Type RM Length L Ch R = 1 ,24657   ,247,247,247
BEGIN DESCRIPTION:
Turtle Creek 35.1
END DESCRIPTION:
XS GIS Cut Line= 4
      1926580.39     13898512.92      1927218.39     13897872.32
      1927270.47      13897609.3      1927031.64     13897038.16
#Sta/Elev= 30
  3922.6 1600.98  4030.5 1600.86  4270.9 1596.95  4413.3 1592.52  4511.3 1589.98
  4532.5 1587.69  4553.7 1591.79  4576.5 1591.45  4744.6  1588.7    4780 1583.11
  4844.4 1583.44  4888.4  1580.9  4895.3  1579.6  4903.2 1575.55  4904.7 1574.55
  4965.7 1575.55    5042 1576.31  5093.3 1582.48  5136.9  1584.5    5206 1588.73
  5224.9 1591.47  5330.9 1596.03  5370.5 1600.62  5392.2  1605.2  5478.9 1609.14
  5513.8 1614.48  5585.2  1616.9  5590.6 1618.51  5667.4 1619.85  5713.9 1618.16
#Mann= 7 ,-1 , 0
  3922.6    .045       0  4413.3     .07       0  4576.5    .035       0
  4903.2    .035       0  4965.7    .035       0  5136.9    .033       0
    5206     .07       0
Bank Sta=4903.2,4965.7
XS Rating Curve= 0 ,0
Exp/Cntr=0.3,0.1

Type RM Length L Ch R = 1 ,24410   ,557,557,557
BEGIN DESCRIPTION:
Turtle Creek 34.0
END DESCRIPTION:
XS GIS Cut Line= 3
      1927966.58     13898918.84      1927355.44     13897486.65
      1927174.98     13897224.97
#Sta/Elev= 30
  3667.3 1608.71    3833 1607.91  3891.1    1605  3932.4 1607.17  4131.9 1604.33
  4214.4 1602.71  4407.8 1593.27    4563 1589.46  4595.6  1590.8  4639.1 1588.17
  4701.1 1588.56    4783 1582.12  4889.2 1569.86    4951    1569  4952.5    1568
    5014    1569  5019.6 1573.57  5029.8 1577.36  5035.2 1576.34  5058.8 1580.22
    5106  1584.9  5140.5 1586.24  5211.4 1592.09  5240.7 1592.69  5347.9 1596.67
  5427.3 1597.52    5478 1602.31  5484.1  1604.8    5499 1606.65  5542.3 1607.82
#Mann= 7 ,-1 , 0
  3667.3    .035       0  4131.9     .07       0  4407.8    .035       0
    4783     .07       0    4951     .05       0    5014     .07       0
  5240.7    .035       0
Bank Sta=4951,5014
XS Rating Curve= 0 ,0
Exp/Cntr=0.3,0.1

Type RM Length L Ch R = 1 ,23853   ,559,559,559
BEGIN DESCRIPTION:
Turtle Creek 33.0
END DESCRIPTION:
XS GIS Cut Line= 3
      1928362.83     13898728.38      1927882.99     13897740.62
      1927225.01     13897125.01
#Sta/Elev= 30
  3959.5  1605.8  4159.2 1605.26  4221.1 1604.23  4452.4 1602.89  4485.8 1597.98
  4515.2 1598.23  4565.1 1596.39  4632.8 1596.93  4677.9 1594.28  4700.4  1596.1
  4852.7 1589.76  4877.2 1585.64  4931.6  1575.1  4939.6 1568.85  4941.1 1567.85
  5002.7 1568.85    5075 1570.33  5081.6 1569.23  5116.8 1573.08  5137.8 1577.99
    5224 1582.42  5390.1 1590.26  5442.1 1592.67  5711.3 1595.71  5847.9 1599.21
  5880.8 1600.23  5888.1 1603.07    5895 1602.13  5902.3 1603.96  5958.7 1605.87
#Mann= 11 ,-1 , 0
  3959.5     .07       0  4159.2    .035       0  4221.1     .07       0
  4515.2    .035       0  4877.2      .1       0  4939.6     .05       0
  5002.7      .1       0    5075    .033       0    5224      .1       0
  5390.1     .07       0  5847.9    .035       0
Bank Sta=4939.6,5002.7
XS Rating Curve= 0 ,0
Exp/Cntr=0.3,0.1

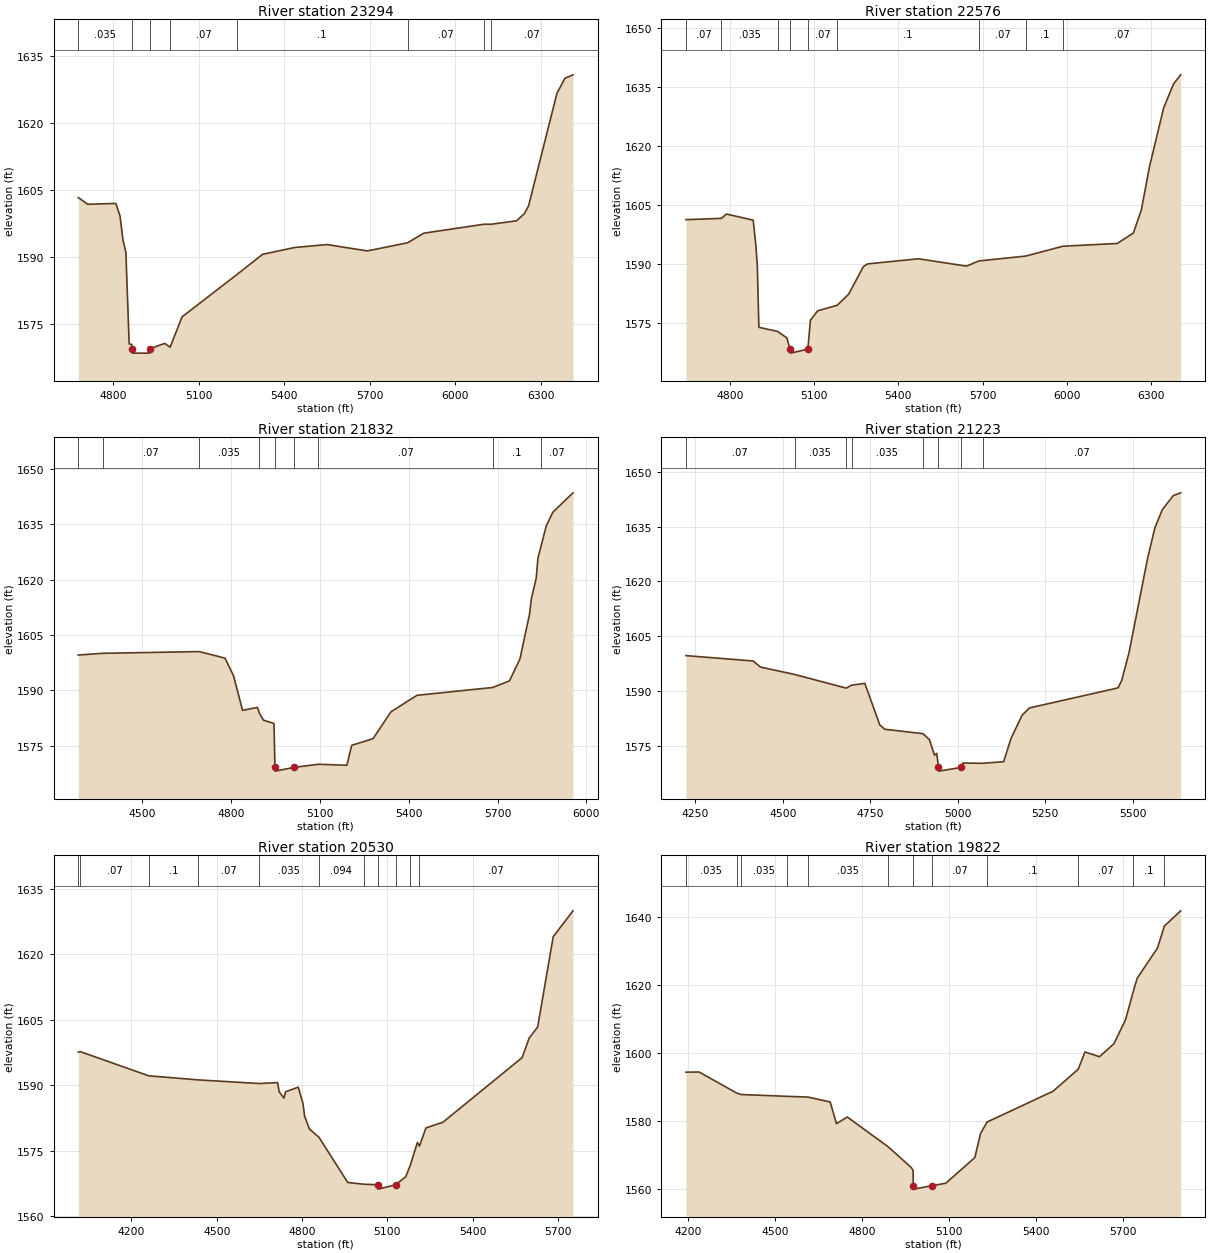
Type RM Length L Ch R = 1 ,23294   ,718,718,718
BEGIN DESCRIPTION:
Turtle Creek 32.0
END DESCRIPTION:
XS GIS Cut Line= 3
      1928587.28     13897651.64        1928275.       13897575.
      1927274.97     13896574.97
#Sta/Elev= 30
  4678.1 1603.41  4711.3  1601.9    4810 1602.09  4824.6 1599.25  4834.9 1593.92
  4845.2 1591.12  4856.7 1570.63  4865.8 1570.52  4866.7 1569.57  4868.2 1568.57
  4928.3 1568.57  4929.8 1569.57  4981.4 1570.75  5000.3 1569.89  5042.1 1576.68
  5233.4  1586.1  5324.9  1590.7  5438.1 1592.23  5551.2 1592.88  5692.6 1591.46
  5833.6 1593.28  5890.6 1595.43  6101.6 1597.43  6126.6 1597.43  6215.9  1598.2
  6244.2 1599.87  6258.3 1601.59  6357.3 1626.68  6385.6 1630.13  6413.9 1630.89
#Mann= 8 ,-1 , 0
  4678.1    .035       0  4866.7    .033       0  4929.8    .035       0
  5000.3     .07       0  5233.4      .1       0  5833.6     .07       0
  6101.6      .1       0  6126.6     .07       0
Bank Sta=4866.7,4929.8
XS Rating Curve= 0 ,0
Exp/Cntr=0.3,0.1

Type RM Length L Ch R = 1 ,22576   ,744,744,744
BEGIN DESCRIPTION:
Turtle Creek 31.0
END DESCRIPTION:
XS GIS Cut Line= 3
      1928869.85     13897186.93      1928064.15     13897035.01
       1927310.1     13896474.75
#Sta/Elev= 30
  4644.5 1601.27  4770.8 1601.59  4788.3  1602.7  4883.5 1601.14  4893.2 1594.73
  4898.3 1589.39  4903.8 1573.93  4970.3 1572.88  5003.1 1571.24  5014.8 1568.37
  5016.3 1567.37  5077.9 1568.37    5087 1575.74    5113 1578.12  5182.7 1579.54
    5223 1582.33  5275.4 1589.34  5290.5 1590.03  5471.2 1591.33  5642.2 1589.47
  5686.2 1590.78  5852.9 1592.02    5985 1594.52  6178.3 1595.22  6235.7 1597.88
  6263.9 1603.74  6293.1  1614.8  6343.2 1629.63  6378.6 1635.77  6403.8 1638.05
#Mann= 9 ,-1 , 0
  4644.5     .07       0  4770.8    .035       0  4970.3     .07       0
  5014.8     .05       0  5077.9     .07       0  5182.7      .1       0
  5686.2     .07       0  5852.9      .1       0    5985     .07       0
Bank Sta=5014.8,5077.9
XS Rating Curve= 0 ,0
Exp/Cntr=0.3,0.1

Type RM Length L Ch R = 1 ,21832   ,609,609,609
BEGIN DESCRIPTION:
Turtle Creek 30.0
END DESCRIPTION:
XS GIS Cut Line= 3
      1929035.69     13896587.97      1928283.48     13896498.62
      1927475.04     13896075.02
#Sta/Elev= 30
  4284.5 1599.55  4367.6 1600.02  4693.2 1600.48  4779.8 1598.71  4808.9 1593.88
  4839.1 1584.58  4889.4 1585.36  4895.9 1583.83  4909.6 1581.91  4945.2 1581.02
  4948.5 1569.11    4950 1568.11  5011.6 1569.11  5095.4 1569.97  5191.3  1569.7
  5207.7 1575.11  5279.5 1576.88  5340.1 1584.17  5428.3 1588.65  5683.5 1590.76
  5740.2 1592.54  5775.7 1598.49    5808  1610.6  5814.2 1614.77  5830.6 1620.38
  5836.2 1625.71  5846.1 1628.82  5864.4 1634.51    5887 1638.25  5954.7 1643.48
#Mann= 9 ,-1 , 0
  4284.5    .035       0  4367.6     .07       0  4693.2    .035       0
  4895.9    .033       0  4948.5    .033       0  5011.6    .033       0
  5095.4     .07       0  5683.5      .1       0  5846.1     .07       0
Bank Sta=4948.5,5011.6
XS Rating Curve= 0 ,0
Exp/Cntr=0.3,0.1

Type RM Length L Ch R = 1 ,21223   ,693,693,693
BEGIN DESCRIPTION:
Turtle Creek 29.0
END DESCRIPTION:
XS GIS Cut Line= 3
      1928825.03     13896425.02        1928225.       13895925.
      1927625.02     13895725.01
#Sta/Elev= 30
  4223.2 1599.68  4415.2 1598.21  4436.1 1596.54  4533.4 1594.53  4681.2 1590.78
  4696.3 1591.58  4734.2 1592.08  4777.1 1580.68  4791.4 1579.52  4900.6  1578.3
    4919 1576.66  4933.3 1572.41  4939.8 1572.91  4944.7 1569.05  4946.2 1568.05
  5007.8 1569.05  5014.8 1570.27  5070.7 1570.19  5130.8 1570.63  5151.8 1576.96
  5183.5 1583.35  5204.5 1585.35  5457.5 1590.84  5468.1 1592.85  5489.1 1600.48
  5541.8 1626.15  5562.9 1634.63    5584 1639.61  5615.6  1643.5  5636.7 1644.26
#Mann= 8 ,-1 , 0
  4223.2     .07       0  4533.4    .035       0  4681.2     .07       0
  4696.3    .035       0  4900.6    .033       0  4944.7    .033       0
  5007.8    .033       0  5070.7     .07       0
Bank Sta=4944.7,5007.8
XS Rating Curve= 0 ,0
Exp/Cntr=0.3,0.1

Type RM Length L Ch R = 1 ,20530   ,708,708,708
BEGIN DESCRIPTION:
Turtle Creek 28.0
END DESCRIPTION:
XS GIS Cut Line= 4
      1928924.99     13896174.98      1928538.49     13895403.78
      1928243.35     13895275.31        1927725.       13895475.
#Sta/Elev= 30
    4013 1597.63    4019 1597.76  4260.9  1592.2  4435.3 1591.26  4650.3 1590.43
    4714 1590.64  4719.6 1588.56  4736.4  1587.1    4742 1588.54  4786.7  1589.6
  4803.4 1585.83    4809 1582.99  4825.8 1580.05  4859.9 1578.09  4960.8 1567.78
  5016.5 1567.38    5066 1567.25  5067.5 1566.25  5129.2 1567.25  5164.6 1569.07
  5181.1 1571.78  5205.8 1576.94  5213.1  1576.1  5235.8 1580.26  5295.8 1581.58
  5574.2 1596.37  5598.8 1600.81  5628.8  1603.4  5683.4 1624.04    5753 1629.98
#Mann= 11 ,-1 , 0
    4013    .035       0    4019     .07       0  4260.9      .1       0
  4435.3     .07       0  4650.3    .035       0  4859.9    .094       0
  5016.5    .033       0    5066     .05       0  5129.2    .033       0
  5181.1    .035       0  5213.1     .07       0
Bank Sta=5066,5129.2
XS Rating Curve= 0 ,0
Exp/Cntr=0.3,0.1

Type RM Length L Ch R = 1 ,19822   ,688,688,688
BEGIN DESCRIPTION:
Turtle Creek 27.0
END DESCRIPTION:
XS GIS Cut Line= 3
      1929274.99     13895574.97        1928875.       13894875.
        1928875.       13893975.
#Sta/Elev= 30
  4193.8 1594.29  4239.1 1594.34  4368.1 1588.17  4384.4 1587.71    4543 1587.18
  4615.1 1586.96  4691.2 1585.52  4712.8 1579.13  4750.2 1581.09  4890.2  1572.4
  4970.5 1566.26    4977  1565.4  4977.8 1560.87  4979.3 1559.87  5042.1 1560.87
    5090 1561.62    5190 1569.15    5210  1576.3  5232.3 1579.61    5460 1588.69
  5546.6 1595.16    5570 1600.24    5620 1598.84    5670 1602.69    5710 1609.76
  5735.5 1617.72    5750 1621.94    5820 1630.83  5844.1 1637.33    5900 1641.78
#Mann= 12 ,-1 , 0
  4193.8    .035       0  4368.1     .07       0  4384.4    .035       0
    4543     .07       0  4615.1    .035       0  4890.2     .07       0
  4977.8     .05       0  5042.1     .07       0  5232.3      .1       0
  5546.6     .07       0  5735.5      .1       0  5844.1     .07       0
Bank Sta=4977.8,5042.1
XS Rating Curve= 0 ,0
Exp/Cntr=0.3,0.1