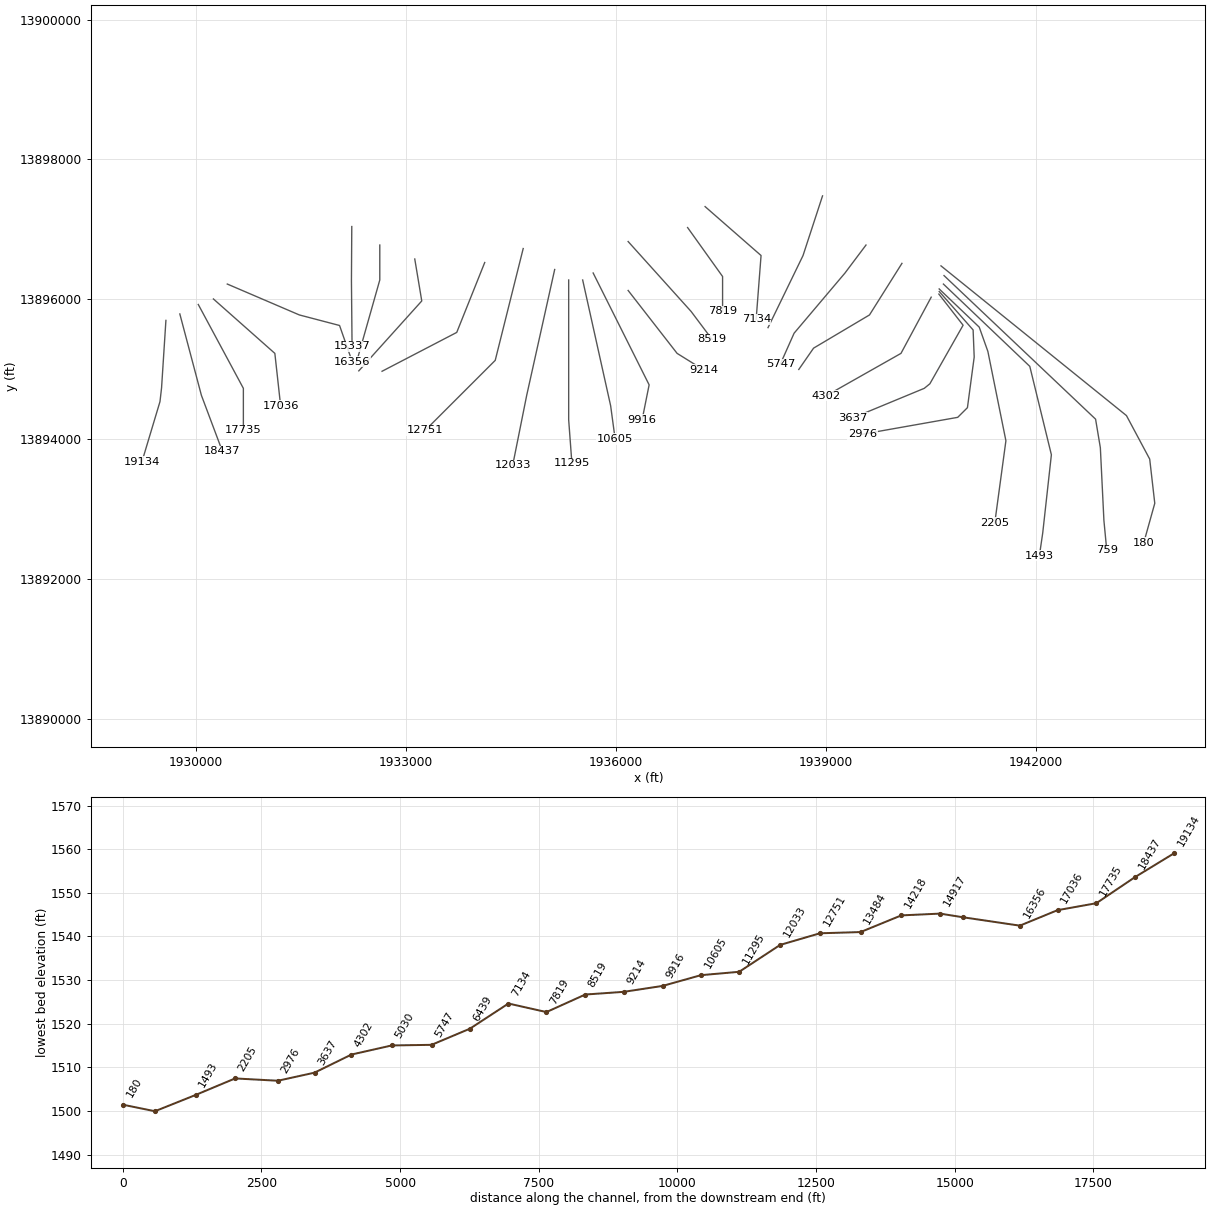
HEC-RAS study Turtle Creek.prj: Turtle Creek Base Level Engineering

--- Turtle Creek.g01 (geometry) --- (continued)

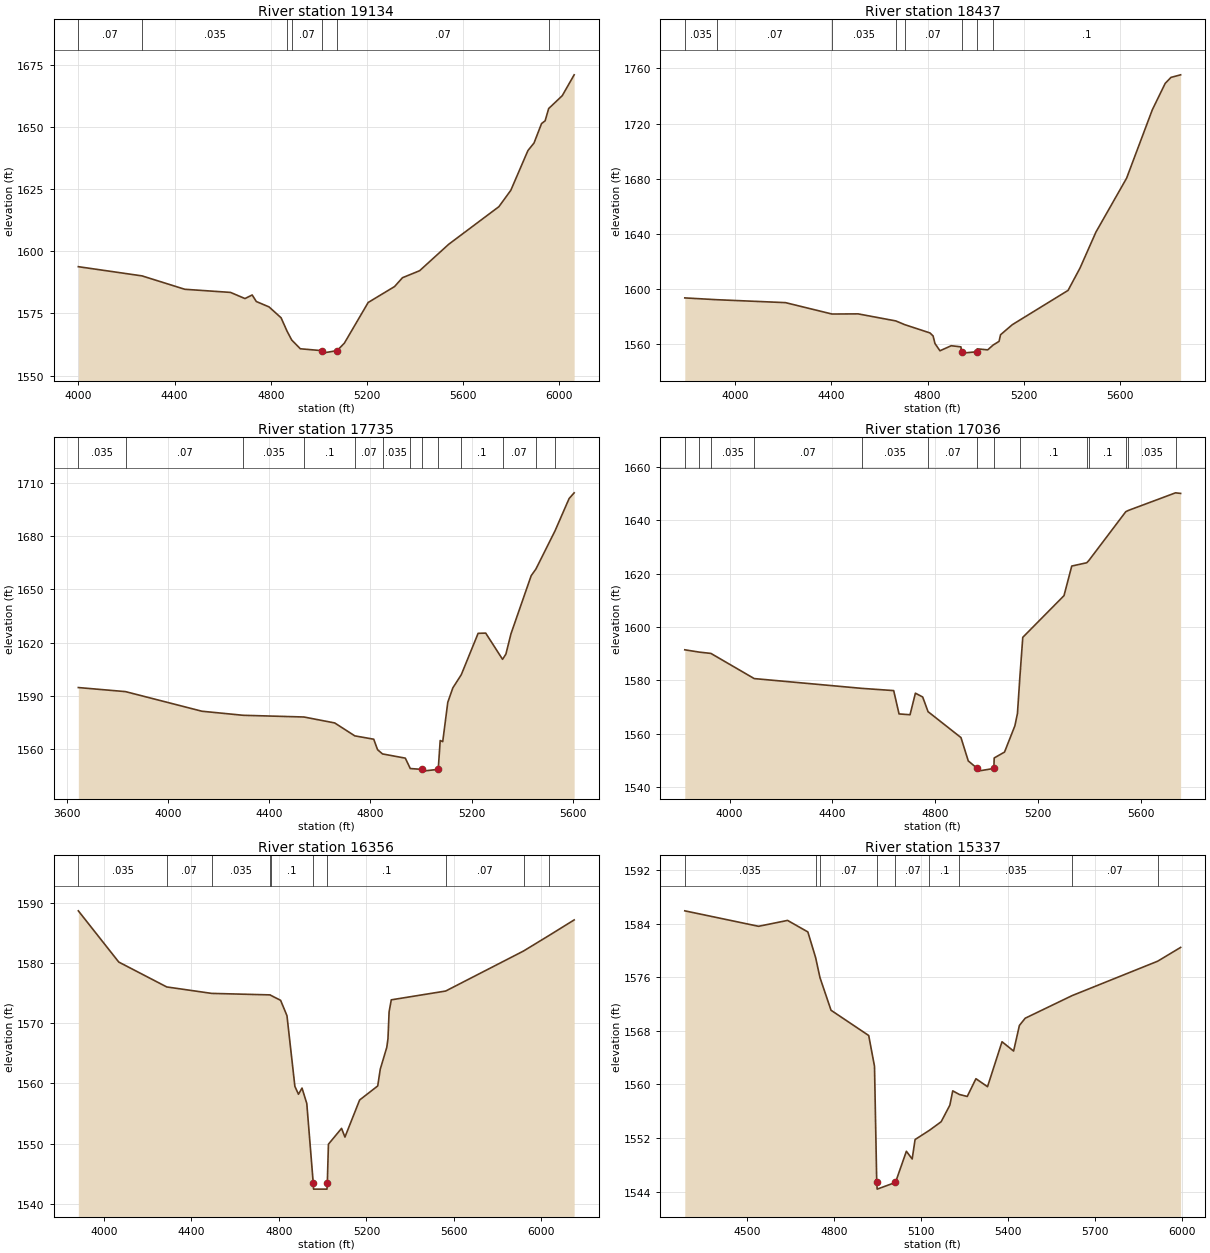
Type RM Length L Ch R = 1 ,19134   ,697,697,697
BEGIN DESCRIPTION:
Turtle Creek 26.0
END DESCRIPTION:
XS GIS Cut Line= 4
      1929567.77     13895696.93      1929505.65     13894733.06
      1929483.08     13894535.25        1929225.       13893675.
#Sta/Elev= 30
  3999.6 1593.77  4264.7 1590.07  4442.5 1584.69  4632.8 1583.43    4693 1580.96
    4723  1582.4  4740.2 1579.77  4793.2  1577.6  4843.3 1573.23    4868 1567.87
  4887.5  1564.3  4923.4 1560.78  5011.9 1560.03  5013.4 1559.03  5076.2 1560.03
  5106.5 1563.03  5205.7 1579.39  5315.3 1585.77  5348.4 1589.34  5419.7 1592.15
  5540.7 1602.77  5749.5 1617.88  5799.1 1624.46  5870.4 1640.44  5895.7 1643.47
    5927 1651.28  5941.8 1652.37  5956.7 1657.32  6013.1 1662.48  6062.7 1670.87
#Mann= 7 ,-1 , 0
  3999.6     .07       0  4264.7    .035       0    4868      .1       0
  4887.5     .07       0  5011.9     .05       0  5076.2     .07       0
  5956.7     .07       0
Bank Sta=5011.9,5076.2
XS Rating Curve= 0 ,0
Exp/Cntr=0.3,0.1

Type RM Length L Ch R = 1 ,18437   ,702,702,702
BEGIN DESCRIPTION:
Turtle Creek 25.0
END DESCRIPTION:
XS GIS Cut Line= 3
       1929766.7     13895788.94        1930075.       13894625.
      1930375.01     13893824.98
#Sta/Elev= 30
  3792.1 1593.66  3927.1 1592.34    4210 1590.24  4403.4 1581.97  4511.6 1582.09
  4668.1 1576.98  4704.9 1574.29    4810 1568.27    4823 1566.07  4830.7 1560.63
  4851.4 1555.33  4898.2 1558.99  4938.4 1558.18  4941.3 1554.63  4942.8 1553.63
  5005.6 1554.63    5006 1556.73  5049.6    1556  5072.6 1559.55  5096.8 1562.16
    5103 1566.97  5151.9 1574.27  5383.3 1599.11  5433.2 1615.42    5499 1641.38
  5626.3 1680.46  5733.1 1730.05  5786.5 1749.17  5810.5 1753.52  5850.6 1755.39
#Mann= 8 ,-1 , 0
  3792.1    .035       0  3927.1     .07       0  4403.4    .035       0
  4668.1      .1       0  4704.9     .07       0  4941.3     .05       0
  5005.6     .07       0  5072.6      .1       0
Bank Sta=4941.3,5005.6
XS Rating Curve= 0 ,0
Exp/Cntr=0.3,0.1

Type RM Length L Ch R = 1 ,17735   ,699,699,699
BEGIN DESCRIPTION:
Turtle Creek 24.0
END DESCRIPTION:
XS GIS Cut Line= 3
      1930030.42     13895924.61        1930675.       13894725.
        1930675.     13894125.02
#Sta/Elev= 30
  3644.1 1594.67  3830.8 1592.38  4133.3 1581.33  4296.2 1579.05  4536.8 1578.09
  4658.5 1574.74  4737.9 1567.47  4812.9 1565.58  4828.1 1559.67  4847.7 1557.29
  4937.8 1554.92  4957.5 1549.06  5003.8 1548.61  5005.3 1547.61  5068.1 1548.61
  5075.9 1564.86  5085.9 1564.21  5105.9 1586.38  5125.9 1594.49  5159.3  1601.9
  5225.9  1625.2  5255.9 1625.33  5322.6 1610.56  5335.9 1613.53  5355.9 1624.94
  5435.9 1657.68  5454.4 1661.36    5530 1682.84  5585.9 1701.09  5605.9 1704.32
#Mann= 13 ,-1 , 0
  3644.1    .035       0  3830.8     .07       0  4296.2    .035       0
  4536.8      .1       0  4737.9     .07       0  4847.7    .035       0
  4957.5     .07       0  5003.8     .05       0  5068.1     .07       0
  5159.3      .1       0  5322.6     .07       0  5454.4      .1       0
    5530    .035       0
Bank Sta=5003.8,5068.1
XS Rating Curve= 0 ,0
Exp/Cntr=0.3,0.1

Type RM Length L Ch R = 1 ,17036   ,680,680,680
BEGIN DESCRIPTION:
Turtle Creek 23.0
END DESCRIPTION:
XS GIS Cut Line= 3
      1930246.77     13896003.65        1931125.       13895225.
      1931207.78     13894473.96
#Sta/Elev= 30
    3826 1591.47  3882.9  1590.6  3927.6 1590.12  4096.1 1580.69  4514.2 1577.03
  4638.8 1576.19  4659.7 1567.45  4702.4 1567.14  4723.3 1575.22  4751.7 1573.79
  4772.5  1568.3  4900.6 1558.59    4929 1549.85  4964.2 1547.02  4965.7 1546.02
  5028.5 1547.02  5029.9 1550.95  5070.1 1553.16  5110.4    1563  5120.4 1567.63
  5129.6 1580.94  5141.1 1596.14  5301.5 1611.76  5331.7 1622.85  5389.9 1624.08
    5398  1624.9  5541.8  1643.2  5551.8 1643.68  5735.5 1650.28  5755.3 1650.06
#Mann= 14 ,-1 , 0
    3826    .035       0  3882.9     .07       0  3927.6    .035       0
  4096.1     .07       0  4514.2    .035       0  4772.5     .07       0
  4964.2     .05       0  5028.5     .07       0  5129.6      .1       0
  5389.9     .07       0    5398      .1       0  5541.8     .07       0
  5551.8    .035       0  5735.5     .07       0
Bank Sta=4964.2,5028.5
XS Rating Curve= 0 ,0
Exp/Cntr=0.3,0.1

Type RM Length L Ch R = 1 ,16356   ,1019,1019,1019
BEGIN DESCRIPTION:
Turtle Creek 22.0
END DESCRIPTION:
XS GIS Cut Line= 4
      1930445.07     13896217.02        1931475.       13895775.
      1932049.94     13895624.12      1932231.95     13895103.08
#Sta/Elev= 30
  3882.9 1588.65  4067.8 1580.15  4287.1 1576.02  4492.4 1574.95  4759.9  1574.7
  4762.7 1574.63  4807.8  1573.8  4836.9 1571.24  4873.1 1559.52  4889.5 1558.21
  4905.7 1559.24  4927.5 1556.68    4957 1543.47  4958.5 1542.47  5019.9 1542.47
  5021.4 1543.47  5026.4 1549.92  5086.4 1552.55    5102 1551.11  5169.1 1557.26
  5251.8 1559.59  5263.5 1562.38  5293.2 1565.99  5298.7 1567.43  5303.9  1571.9
  5313.8 1573.88  5562.5 1575.34  5918.5 1581.98  6036.6 1584.59    6150 1587.14
#Mann= 10 ,-1 , 0
  3882.9    .035       0  4287.1     .07       0  4492.4    .035       0
  4759.9     .07       0  4762.7      .1       0    4957    .035       0
  5021.4      .1       0  5562.5     .07       0  5918.5    .035       0
  6036.6      .1       0
Bank Sta=4957,5021.4
XS Rating Curve= 0 ,0
Exp/Cntr=0.3,0.1

Type RM Length L Ch R = 1 ,15337   ,420,420,420
BEGIN DESCRIPTION:
Turtle Creek 21.1
END DESCRIPTION:
XS GIS Cut Line= 3
      1932224.66      13897039.6      1932219.77     13896263.69
      1932228.65     13895328.76
#Sta/Elev= 30
  4285.8 1585.92  4540.4 1583.61  4640.4 1584.49  4710.4 1582.77  4737.3 1578.93
  4752.2 1575.96  4790.4 1571.08  4920.4 1567.31  4940.4 1562.72  4948.1 1545.38
  4949.6 1544.38  5012.8 1545.38  5050.4 1550.03  5070.4 1548.88  5080.4 1551.78
    5130 1553.16  5170.4 1554.44  5200.4 1556.91  5210.4 1559.05  5233.2 1558.51
  5260.4 1558.21  5290.4 1560.86  5330.4 1559.67  5380.4 1566.38  5420.4 1564.99
  5440.4 1568.81  5460.4 1569.89  5622.5 1573.27  5917.5  1578.4  5996.7 1580.46
#Mann= 9 ,-1 , 0
  4285.8    .035       0  4737.3      .1       0  4752.2     .07       0
  4948.1     .05       0  5012.8     .07       0    5130      .1       0
  5233.2    .035       0  5622.5     .07       0  5917.5    .035       0
Bank Sta=4948.1,5012.8
XS Rating Curve= 0 ,0
Exp/Cntr=0.3,0.1

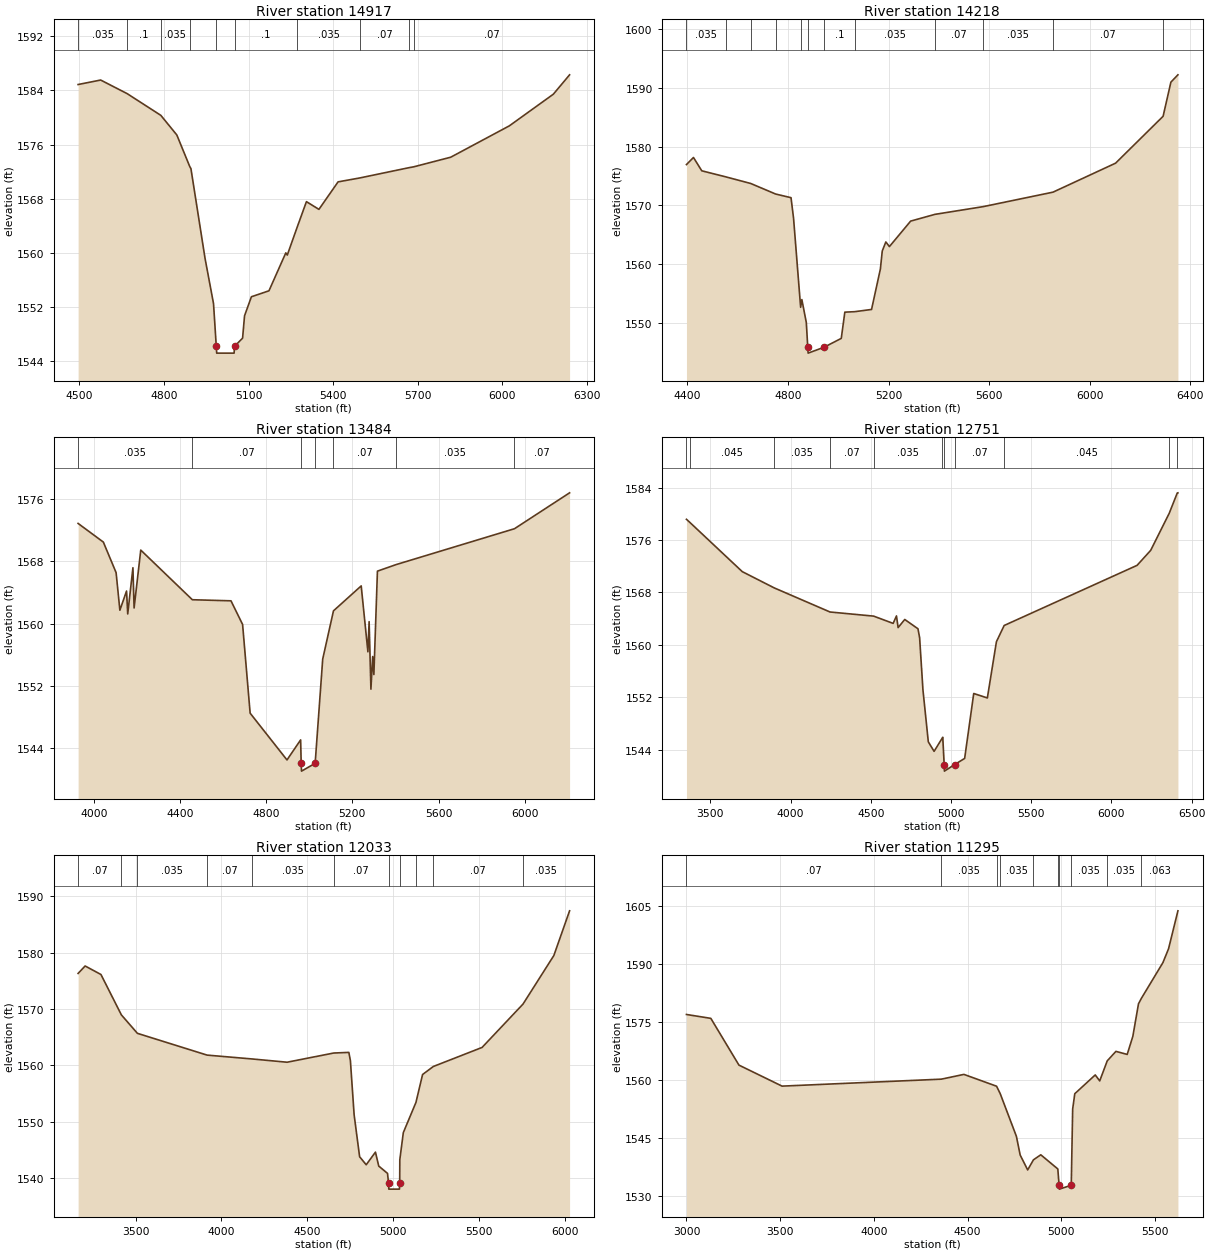
Type RM Length L Ch R = 1 ,14917   ,699,699,699
BEGIN DESCRIPTION:
Turtle Creek 21.0
END DESCRIPTION:
XS GIS Cut Line= 3
        1932625.     13896774.96        1932625.       13896275.
      1932286.77     13895079.59
#Sta/Elev= 30
  4495.8 1584.88  4575.8 1585.54  4669.8 1583.53    4789 1580.33  4845.8 1577.43
  4891.4 1572.79  4895.8 1572.46  4945.8 1559.21  4975.8 1552.55  4985.6 1546.23
  4987.1 1545.23  5048.8 1545.23  5050.3 1546.23  5078.9 1547.44  5085.8 1550.74
  5110.1 1553.55  5172.4 1554.43  5232.1 1560.03  5237.3  1559.7  5272.9 1563.88
  5305.2 1567.59  5349.5 1566.45  5417.4 1570.51  5494.6 1571.09  5669.5 1572.61
  5685.5 1572.73  5816.8 1574.15  6024.6 1578.78  6180.5 1583.45  6238.1 1586.31
#Mann= 10 ,-1 , 0
  4495.8    .035       0  4669.8      .1       0    4789    .035       0
  4891.4      .1       0  4985.6     .05       0  5050.3      .1       0
  5272.9    .035       0  5494.6     .07       0  5669.5    .035       0
  5685.5     .07       0
Bank Sta=4985.6,5050.3
XS Rating Curve= 0 ,0
Exp/Cntr=0.3,0.1

Type RM Length L Ch R = 1 ,14218   ,734,734,734
BEGIN DESCRIPTION:
Turtle Creek 20.0
END DESCRIPTION:
XS GIS Cut Line= 3
      1933124.99     13896575.04        1933225.       13895975.
      1932324.99     13894974.99
#Sta/Elev= 30
  4396.7 1576.94  4424.6 1578.15  4457.6 1575.88    4553 1574.85  4652.2 1573.72
  4751.4 1571.92  4812.4  1571.3  4822.5 1567.78  4850.6 1552.63  4855.5 1553.94
  4873.2 1550.02  4878.9 1545.82  4880.4 1544.82  4943.6 1545.82  5012.1 1547.33
  5026.3  1551.8  5065.4 1551.88  5132.5 1552.26  5167.6 1559.15  5175.1 1562.22
  5189.3 1563.76  5203.5 1562.97  5287.9 1567.31  5384.5 1568.46  5576.9 1569.78
  5853.7 1572.24  6102.6 1577.18  6291.5 1585.17  6322.4 1590.98  6350.4 1592.23
#Mann= 12 ,-1 , 0
  4396.7    .035       0    4553      .1       0  4652.2    .035       0
  4751.4     .07       0  4850.6      .1       0  4878.9     .05       0
  4943.6      .1       0  5065.4    .035       0  5384.5     .07       0
  5576.9    .035       0  5853.7     .07       0  6291.5      .1       0
Bank Sta=4878.9,4943.6
XS Rating Curve= 0 ,0
Exp/Cntr=0.3,0.1

Type RM Length L Ch R = 1 ,13484   ,733,733,733
BEGIN DESCRIPTION:
Turtle Creek 19.0
END DESCRIPTION:
XS GIS Cut Line= 3
      1934124.98     13896524.95        1933725.       13895525.
      1932657.31     13894969.14
#Sta/Elev= 30
  3927.3 1572.88  4044.4 1570.48  4103.6 1566.55  4121.1 1561.71  4152.1 1564.18
  4157.5 1561.23  4181.7 1567.18  4187.1    1562    4218 1569.45  4457.4 1563.06
  4636.7 1562.92  4690.6 1559.88  4725.6 1548.46  4896.6 1542.44  4959.9 1545.02
  4962.5    1542    4964    1541  5027.3    1542  5062.4 1555.43  5112.3 1561.63
    5241 1564.84  5272.1 1556.36  5277.7 1560.24  5286.1 1551.55  5294.2 1555.75
  5299.8 1553.43  5316.3 1566.74  5402.7 1567.58  5952.3  1572.2    6208 1576.82
#Mann= 7 ,-1 , 0
  3927.3    .035       0  4457.4     .07       0  4962.5     .05       0
  5027.3     .07       0  5112.3     .07       0  5402.7    .035       0
  5952.3     .07       0
Bank Sta=4962.5,5027.3
XS Rating Curve= 0 ,0
Exp/Cntr=0.3,0.1

Type RM Length L Ch R = 1 ,12751   ,718,718,718
BEGIN DESCRIPTION:
Turtle Creek 18.0
END DESCRIPTION:
XS GIS Cut Line= 3
      1934675.01     13896725.04        1934275.       13895125.
        1933275.       13894125.
#Sta/Elev= 30
  3351.1 1579.16  3370.4 1578.73    3699 1571.17  3898.1 1568.69  4245.9 1565.01
  4517.9 1564.38  4639.6 1563.27  4660.2 1564.41  4670.5 1562.63  4711.8 1563.87
  4794.2 1562.45  4804.5 1561.09  4825.2 1553.13  4858.7 1545.19  4894.7 1543.74
  4945.6 1545.76  4948.8 1545.89  4957.6 1541.72  4959.1 1540.72  5022.5 1541.72
  5085.2 1542.66  5141.8 1552.57  5226.7 1551.89  5283.2 1560.47  5331.5 1562.95
    6160 1572.13  6244.9 1574.42  6360.1 1580.06  6410.6 1583.18  6414.6  1583.2
#Mann= 11 ,-1 , 0
  3351.1    .035       0  3370.4    .045       0  3898.1    .035       0
  4245.9     .07       0  4517.9    .035       0  4945.6     .07       0
  4957.6     .05       0  5022.5     .07       0  5331.5    .045       0
  6360.1    .035       0  6410.6      .1       0
Bank Sta=4957.6,5022.5
XS Rating Curve= 0 ,0
Exp/Cntr=0.3,0.1

Type RM Length L Ch R = 1 ,12033   ,738,738,738
BEGIN DESCRIPTION:
Turtle Creek 17.0
END DESCRIPTION:
XS GIS Cut Line= 3
      1935124.99     13896424.97        1934725.       13894625.
        1934525.     13893624.99
#Sta/Elev= 30
    3165 1576.29  3205.9 1577.61  3298.1  1576.1  3417.1 1568.94  3510.5 1565.67
  3916.6 1561.81  4177.8 1561.13  4382.7 1560.55  4654.6 1562.18  4742.5 1562.29
  4751.5 1560.85  4773.3 1551.22  4805.3 1543.79  4843.7 1542.37  4897.5 1544.61
  4916.7 1542.14  4967.9 1540.84  4973.9 1539.05  4975.4 1538.05  5037.3 1538.05
  5038.8 1539.05  5039.5 1543.27  5059.9 1548.07  5133.6 1553.43  5172.1 1558.37
  5234.6 1559.79  5518.8 1563.17  5757.4 1570.86  5936.9 1579.46  6028.7 1587.39
#Mann= 11 ,-1 , 0
    3165     .07       0  3417.1    .045       0  3510.5    .035       0
  3916.6     .07       0  4177.8    .035       0  4654.6     .07       0
  4973.9     .05       0  5038.8     .07       0  5133.6      .1       0
  5234.6     .07       0  5757.4    .035       0
Bank Sta=4973.9,5038.8
XS Rating Curve= 0 ,0
Exp/Cntr=0.3,0.1

Type RM Length L Ch R = 1 ,11295   ,690,690,690
BEGIN DESCRIPTION:
Turtle Creek 16.0
END DESCRIPTION:
XS GIS Cut Line= 3
        1935325.     13896274.98        1935325.       13894275.
      1935370.93     13893655.18
#Sta/Elev= 30
    3000 1577.01    3130 1576.01    3280 1563.93    3510  1558.5  4359.5  1560.3
    4480 1561.53  4654.1 1558.48  4673.5 1556.57    4760 1545.52    4780 1540.71
    4820 1536.85  4850.9 1539.46    4890 1540.76  4980.9  1537.1  4987.6 1532.89
  4989.1 1531.89  5052.5 1532.89  5060.1  1552.6  5071.4 1556.54  5180.5 1561.39
  5204.3 1559.85  5244.5 1565.03  5290.8 1567.48  5350.9 1566.69    5381 1571.36
  5411.1 1579.76  5426.5 1581.17  5541.5 1590.41  5571.5 1593.99  5621.5 1603.79
#Mann= 10 ,-1 , 0
    3000     .07       0  4359.5    .035       0  4654.1     .07       0
  4673.5    .035       0  4850.9     .07       0  4980.9    .035       0
  4987.6    .035       0  5052.5    .035       0  5244.5    .035       0
  5426.5    .063       0
Bank Sta=4987.6,5052.5
XS Rating Curve= 0 ,0
Exp/Cntr=0.3,0.1

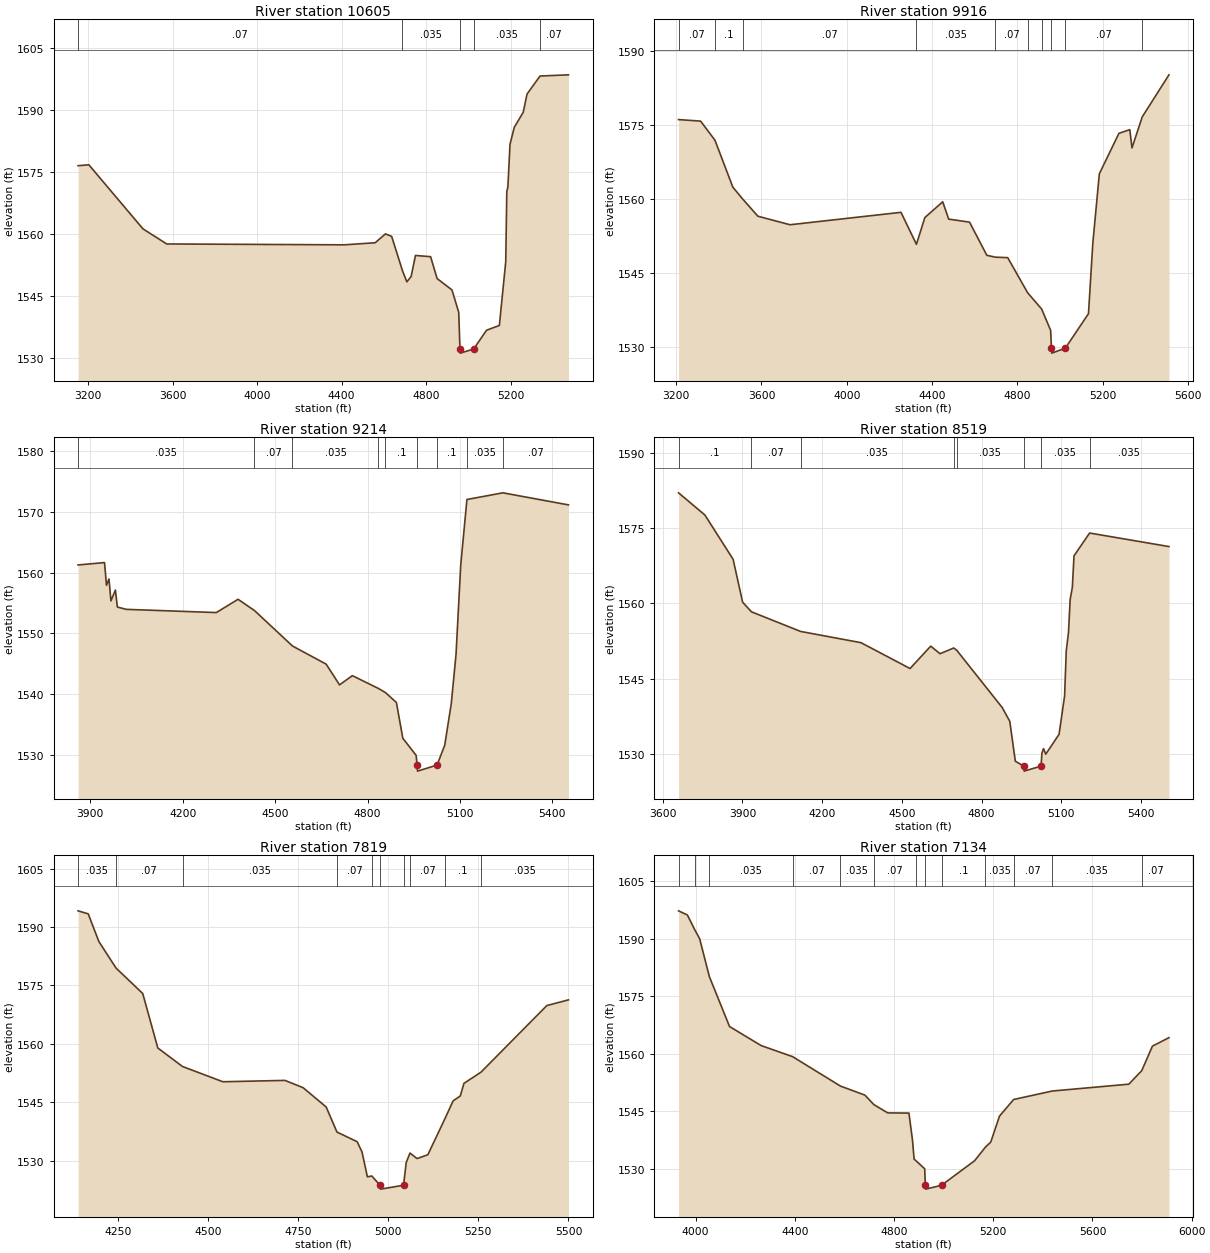
Type RM Length L Ch R = 1 ,10605   ,689,689,689
BEGIN DESCRIPTION:
Turtle Creek 15.0
END DESCRIPTION:
XS GIS Cut Line= 3
        1935525.     13896274.98        1935925.       13894475.
      1935989.05      13894000.6
#Sta/Elev= 30
  3151.8 1576.47    3203 1576.68  3459.1 1561.19  3571.8 1557.53  4411.8 1557.32
    4559 1557.82  4607.7 1559.97  4637.2 1559.35  4688.3 1551.05  4708.9 1548.37
  4729.3 1549.65  4749.8 1554.75  4821.5 1554.45  4852.3 1549.16  4922.7 1546.41
  4954.7 1540.99  4960.6 1532.12  4962.1 1531.12  5025.6 1532.12  5086.5 1536.66
  5147.1 1537.81  5177.3 1553.21  5182.4 1570.23  5187.5 1571.34  5197.5 1581.63
  5217.7 1585.75  5260.2 1589.39  5278.2  1593.8  5339.9 1598.16  5474.4 1598.45
#Mann= 5 ,-1 , 0
  3151.8     .07       0  4688.3    .035       0  4960.6     .05       0
  5025.6    .035       0  5339.9     .07       0
Bank Sta=4960.6,5025.6
XS Rating Curve= 0 ,0
Exp/Cntr=0.3,0.1

Type RM Length L Ch R = 1 ,9916    ,702,702,702
BEGIN DESCRIPTION:
Turtle Creek 14.0
END DESCRIPTION:
XS GIS Cut Line= 3
      1935674.99     13896375.03        1936475.       13894775.
        1936375.     13894274.98
#Sta/Elev= 30
  3211.5 1576.03  3314.9 1575.72  3382.2 1571.84  3465.9 1562.33  3511.6 1559.94
  3583.3 1556.43  3734.2  1554.7  4254.1 1557.22  4326.6 1550.73  4365.9 1556.15
  4449.8 1559.36  4477.7 1555.84  4575.5 1555.23  4656.6  1548.5  4696.8 1548.12
  4754.4 1548.03  4848.1 1540.89  4913.4 1537.61  4955.7 1533.27  4959.5 1529.66
    4961 1528.66  5024.5 1529.66    5133 1536.66  5153.4 1550.96  5183.9 1565.03
  5275.7 1573.24  5326.7 1573.99  5336.9 1570.29  5385.3  1576.6  5510.3 1585.11
#Mann= 10 ,-1 , 0
  3211.5     .07       0  3382.2      .1       0  3511.6     .07       0
  4326.6    .035       0  4696.8     .07       0  4848.1    .035       0
  4913.4     .07       0  4959.5     .05       0  5024.5     .07       0
  5385.3    .035       0
Bank Sta=4959.5,5024.5
XS Rating Curve= 0 ,0
Exp/Cntr=0.3,0.1

Type RM Length L Ch R = 1 ,9214    ,695,695,695
BEGIN DESCRIPTION:
Turtle Creek 13.0
END DESCRIPTION:
XS GIS Cut Line= 3
      1936175.02     13896124.97        1936875.       13895225.
      1937258.55      13894986.3
#Sta/Elev= 30
  3860.3 1561.29  3946.2 1561.68  3952.6 1557.94  3960.7 1558.98    3967 1555.37
  3981.5 1557.15  3987.9 1554.35  4016.8 1553.97  4309.1 1553.44  4379.7 1555.63
    4433 1553.77  4556.3 1547.93  4665.6 1544.94  4709.1 1541.52  4750.7 1543.04
  4835.3 1540.93  4858.1 1540.25  4893.7 1538.61  4914.5 1532.72  4957.9 1529.89
  4960.7  1528.3  4962.2  1527.3  5025.7  1528.3  5050.6 1531.58  5071.8 1538.44
  5087.2 1546.52  5102.5 1561.28  5122.6 1572.08  5239.4 1573.18  5452.2 1571.19
#Mann= 9 ,-1 , 0
  3860.3    .035       0    4433     .07       0  4556.3    .035       0
  4835.3     .07       0  4858.1      .1       0  4960.7     .05       0
  5025.7      .1       0  5122.6    .035       0  5239.4     .07       0
Bank Sta=4960.7,5025.7
XS Rating Curve= 0 ,0
Exp/Cntr=0.3,0.1

Type RM Length L Ch R = 1 ,8519    ,700,700,700
BEGIN DESCRIPTION:
Turtle Creek 12.0
END DESCRIPTION:
XS GIS Cut Line= 3
      1936174.98     13896825.02        1937075.       13895825.
      1937375.01     13895424.99
#Sta/Elev= 30
  3659.8 1581.99  3758.9 1577.58    3865 1568.79  3900.9 1560.25  3934.2 1558.34
  4119.2 1554.44  4346.3 1552.21  4530.9 1547.07  4608.7 1551.52  4643.8 1550.01
  4695.2 1551.15  4706.3 1550.72  4877.8 1539.31  4906.2 1536.58  4927.1 1528.65
  4958.9 1527.68  4960.4 1526.68  5023.9 1527.68  5027.1 1530.25  5033.3 1531.15
  5041.6 1530.05  5091.6 1533.99  5112.5 1541.63  5118.7 1550.57  5127.1 1554.22
  5133.3 1560.75  5141.6 1563.21  5147.9 1569.47  5206.6    1574  5505.2 1571.31
#Mann= 8 ,-1 , 0
  3659.8      .1       0  3934.2     .07       0  4119.2    .035       0
  4695.2     .07       0  4706.3    .035       0  4958.9     .05       0
  5023.9    .035       0  5206.6    .035       0
Bank Sta=4958.9,5023.9
XS Rating Curve= 0 ,0
Exp/Cntr=0.3,0.1

Type RM Length L Ch R = 1 ,7819    ,685,685,685
BEGIN DESCRIPTION:
Turtle Creek 11.0
END DESCRIPTION:
XS GIS Cut Line= 3
      1937025.01     13897024.99        1937525.       13896325.
        1937525.     13895825.02
#Sta/Elev= 30
  4139.8 1594.15    4168 1593.37  4197.5 1586.27  4245.2 1579.44  4319.2 1572.91
    4361 1558.92  4429.5 1554.16  4541.6 1550.24  4713.7 1550.59  4764.1 1548.71
    4828 1543.76  4857.9 1537.32    4914 1534.84  4927.5 1532.16  4942.3 1525.82
  4954.5 1526.03  4977.5 1523.66    4979 1522.66  5042.6 1523.66    5050  1529.5
  5060.5 1531.93    5080 1530.51    5110 1531.49  5158.8 1541.03    5180 1545.32
    5200  1546.6    5210 1549.82  5257.2 1552.69    5440 1569.81    5500 1571.28
#Mann= 10 ,-1 , 0
  4139.8    .035       0  4245.2     .07       0  4429.5    .035       0
  4857.9     .07       0  4954.5    .035       0  4977.5    .035       0
  5042.6    .035       0  5060.5     .07       0  5158.8      .1       0
  5257.2    .035       0
Bank Sta=4977.5,5042.6
XS Rating Curve= 0 ,0
Exp/Cntr=0.3,0.1

Type RM Length L Ch R = 1 ,7134    ,695,695,695
BEGIN DESCRIPTION:
Turtle Creek 10.0
END DESCRIPTION:
XS GIS Cut Line= 3
      1937274.97     13897325.02        1938075.       13896625.
      1938004.86     13895713.75
#Sta/Elev= 30
  3931.5 1597.27  3967.1 1596.18    3998 1592.18  4016.5 1589.99  4055.6 1580.11
    4137 1567.07  4264.2  1562.1  4391.3  1559.2  4584.2 1551.52  4682.8 1549.16
  4718.9 1546.68  4774.8 1544.52  4860.2 1544.47  4874.5 1537.43  4881.1 1532.44
  4890.4 1531.93  4923.8 1529.92  4926.4 1525.62  4927.9 1524.62  4991.5 1525.62
  5124.9 1532.03  5168.3 1535.56  5190.1  1536.9  5225.2 1543.67  5282.4 1548.02
  5438.3 1550.23  5746.8 1552.02  5798.8 1555.55  5841.8 1561.95  5908.5 1564.16
#Mann= 13 ,-1 , 0
  3931.5     .07       0    3998      .1       0  4055.6    .035       0
  4391.3     .07       0  4584.2    .035       0  4718.9     .07       0
  4890.4      .1       0  4926.4     .05       0  4991.5      .1       0
  5168.3    .035       0  5282.4     .07       0  5438.3    .035       0
  5798.8     .07       0
Bank Sta=4926.4,4991.5
XS Rating Curve= 0 ,0
Exp/Cntr=0.3,0.1

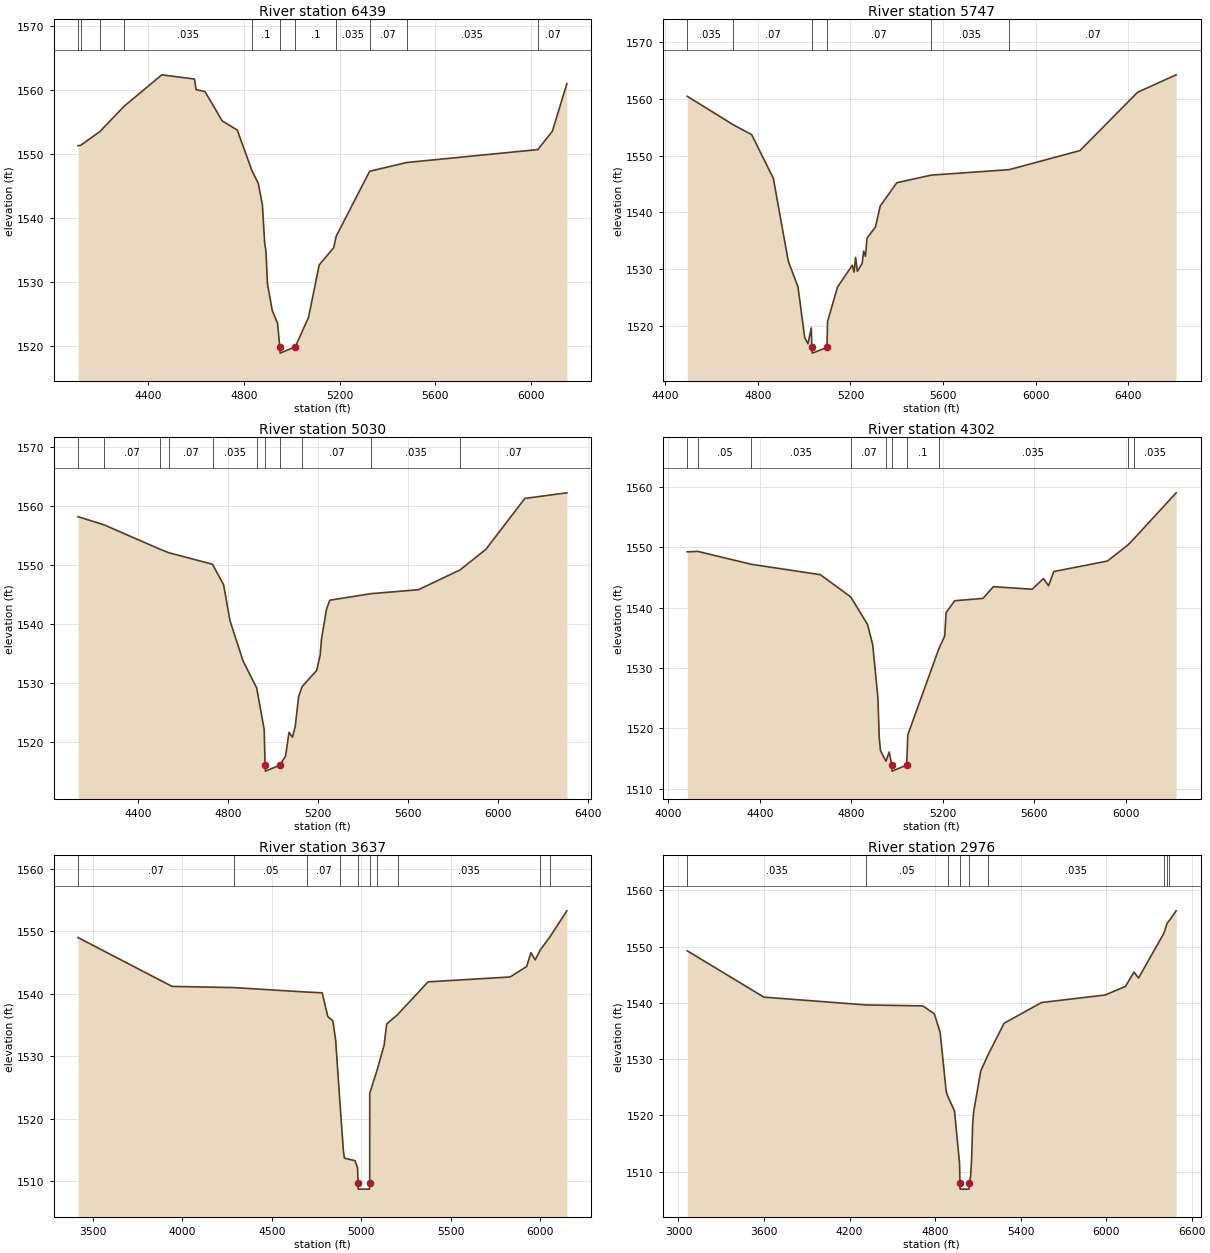
Type RM Length L Ch R = 1 ,6439    ,692,692,692
BEGIN DESCRIPTION:
Turtle Creek 9.0
END DESCRIPTION:
XS GIS Cut Line= 3
      1938953.78     13897478.19        1938675.       13896625.
      1938174.46     13895593.18
#Sta/Elev= 30
  4106.3 1551.26  4117.2 1551.31    4198 1553.47  4299.7 1557.44  4456.8 1562.33
  4593.6 1561.67  4600.1 1560.02  4637.3 1559.72  4709.3 1555.14  4772.4  1553.7
  4833.6 1547.38  4860.4 1545.36  4877.6 1541.98    4887 1535.99  4892.3  1534.8
  4898.7 1529.65  4918.9 1525.48  4940.8 1523.51  4950.1 1519.85  4951.6 1518.85
  5015.2 1519.85  5070.6 1524.47    5115 1532.63  5175.7 1535.33  5185.8 1537.09
  5325.8 1547.26  5480.7 1548.63  6029.3 1550.65  6089.9 1553.52  6150.7 1560.95
#Mann= 11 ,-1 , 0
  4106.3     .05       0  4117.2     .07       0    4198     .05       0
  4299.7    .035       0  4833.6      .1       0  4950.1     .05       0
  5015.2      .1       0  5185.8    .035       0  5325.8     .07       0
  5480.7    .035       0  6029.3     .07       0
Bank Sta=4950.1,5015.2
XS Rating Curve= 0 ,0
Exp/Cntr=0.3,0.1

Type RM Length L Ch R = 1 ,5747    ,717,717,717
BEGIN DESCRIPTION:
Turtle Creek 8.0
END DESCRIPTION:
XS GIS Cut Line= 4
        1939575.     13896775.01        1939275.       13896375.
       1938547.2     13895513.59      1938350.55     13895071.57
#Sta/Elev= 30
    4495 1560.45  4694.2 1555.41  4773.1 1553.69  4866.9 1545.96  4931.5 1531.33
  4973.1 1526.87  5002.2  1517.9  5016.4 1516.81  5030.7 1519.61  5033.3 1516.15
  5034.8 1515.15  5098.4 1516.15    5101 1520.73  5143.9  1526.8  5207.6 1530.64
  5215.3 1529.45  5221.9 1532.03  5229.6 1529.58  5250.5 1530.98    5257 1533.15
  5264.8 1532.22  5271.3 1535.43  5307.7 1537.38  5328.5  1541.1    5400  1545.2
  5548.4 1546.54  5885.5 1547.51    6191 1550.87  6439.8 1561.15  6606.5 1564.23
#Mann= 6 ,-1 , 0
    4495    .035       0  4694.2     .07       0  5033.3     .05       0
  5098.4     .07       0  5548.4    .035       0  5885.5     .07       0
Bank Sta=5033.3,5098.4
XS Rating Curve= 0 ,0
Exp/Cntr=0.3,0.1

Type RM Length L Ch R = 1 ,5030    ,728,728,728
BEGIN DESCRIPTION:
Turtle Creek 7.0
END DESCRIPTION:
XS GIS Cut Line= 4
      1940088.84     13896512.75        1939625.       13895775.
      1938825.64     13895299.96      1938614.44     13894995.19
#Sta/Elev= 30
  4134.1 1558.15  4248.8 1556.78  4496.8 1552.66  4537.3 1552.04  4731.9 1550.08
  4781.1  1546.6  4809.5  1540.5  4867.2 1533.72  4928.1  1529.1  4961.4 1522.07
  4965.3 1516.01  4966.8 1515.01  5030.4 1516.01  5056.2 1517.54  5071.8  1521.6
    5087 1520.75    5099 1522.53  5114.6 1527.68    5130 1529.35  5194.5 1532.08
  5210.1 1534.65  5215.9 1537.39  5238.2 1542.45  5252.9 1543.99  5436.6  1545.1
  5646.4 1545.76  5831.5 1549.12  5946.4 1552.61  6119.4 1561.24  6306.2 1562.19
#Mann= 11 ,-1 , 0
  4134.1    .035       0  4248.8     .07       0  4496.8    .035       0
  4537.3     .07       0  4731.9    .035       0  4928.1      .1       0
  4965.3     .05       0  5030.4      .1       0    5130     .07       0
  5436.6    .035       0  5831.5     .07       0
Bank Sta=4965.3,5030.4
XS Rating Curve= 0 ,0
Exp/Cntr=0.3,0.1

Type RM Length L Ch R = 1 ,4302    ,665,665,665
BEGIN DESCRIPTION:
Turtle Creek 6.0
END DESCRIPTION:
XS GIS Cut Line= 3
      1940507.26      13896029.3        1940075.       13895225.
      1939009.59     13894621.43
#Sta/Elev= 30
  4082.5 1549.22  4127.8  1549.3  4362.8 1547.16  4664.4 1545.44  4797.3 1541.76
  4870.7  1537.2  4893.4 1533.84  4916.1 1525.08  4921.7 1518.58  4927.5  1516.3
  4951.4 1514.58  4965.6 1516.09  4976.7 1513.92  4978.2 1512.92  5041.9 1513.92
  5046.8 1518.92  5182.4 1533.17  5208.4 1535.29  5214.2 1539.15  5251.7 1541.12
  5375.8 1541.52  5420.8 1543.45  5590.8 1543.03  5639.8  1544.8  5662.2 1543.61
  5685.2 1545.96  5919.7  1547.7  6008.5 1550.33  6036.1 1551.41  6220.1 1558.99
#Mann= 10 ,-1 , 0
  4082.5    .035       0  4127.8     .05       0  4362.8    .035       0
  4797.3     .07       0  4951.4      .1       0  4976.7     .05       0
  5041.9      .1       0  5182.4    .035       0  6008.5     .07       0
  6036.1    .035       0
Bank Sta=4976.7,5041.9
XS Rating Curve= 0 ,0
Exp/Cntr=0.3,0.1

Type RM Length L Ch R = 1 ,3637    ,661,661,661
BEGIN DESCRIPTION:
Turtle Creek 5.0
END DESCRIPTION:
XS GIS Cut Line= 5
       1940616.6     13896073.35      1940962.97     13895628.02
      1940488.02     13894790.12      1940408.07       13894725.
      1939392.16     13894304.07
#Sta/Elev= 30
  3417.3 1549.02  3942.5  1541.2  4286.7 1541.01  4698.3 1540.29  4781.1 1540.18
  4812.6 1536.36  4840.3 1535.71  4856.2 1532.62  4878.7 1523.19  4899.4 1514.92
  4905.2 1513.72  4964.3 1513.32  4978.6 1512.15  4981.2 1509.77  4982.7 1508.77
  5044.9 1508.77  5046.4 1509.77  5046.5 1524.09  5088.1 1527.86  5126.8 1531.81
  5141.1 1535.18  5201.7 1536.68  5372.3 1541.93  5830.4 1542.71  5922.7 1544.38
  5946.6  1546.6  5970.4 1545.45  5999.6 1547.07  6051.7 1549.08  6147.4 1553.29
#Mann= 10 ,-1 , 0
  3417.3     .07       0  4286.7     .05       0  4698.3     .07       0
  4878.7    .035       0  4981.2    .035       0  5046.4    .035       0
  5088.1     .07       0  5201.7    .035       0  5999.6     .07       0
  6051.7    .035       0
Bank Sta=4981.2,5046.4
XS Rating Curve= 0 ,0
Exp/Cntr=0.3,0.1

Type RM Length L Ch R = 1 ,2976    ,771,771,771
BEGIN DESCRIPTION:
Turtle Creek 4.0
END DESCRIPTION:
XS GIS Cut Line= 6
      1940621.81     13896109.81       1941106.2     13895560.31
      1941121.71     13895172.39        1941025.     13894448.38
      1940886.08     13894310.03      1939525.12     13894068.95
#Sta/Elev= 30
  3061.9 1549.26  3599.2 1541.03  4316.4 1539.64  4714.7 1539.47  4795.1 1538.07
  4835.8 1534.77  4878.3  1524.3  4887.7 1523.51  4936.7  1520.8    4972 1511.48
  4974.8 1507.92  4976.3 1506.92  5038.5 1506.92    5040 1507.92  5049.8 1509.26
  5056.9 1512.54    5064 1518.51    5071 1520.67  5120.4 1527.88  5169.3 1530.65
  5284.6 1536.39  5546.9 1540.07  5993.8 1541.41    6136 1542.94  6195.2 1545.48
  6227.4 1544.42  6405.8  1552.4  6428.1 1554.18  6443.8 1554.64  6491.3 1556.36
#Mann= 9 ,-1 , 0
  3061.9    .035       0  4316.4     .05       0  4887.7     .07       0
  4974.8     .05       0    5040     .07       0  5169.3    .035       0
  6405.8     .07       0  6428.1    .035       0  6443.8     .07       0
Bank Sta=4974.8,5040
XS Rating Curve= 0 ,0
Exp/Cntr=0.3,0.1

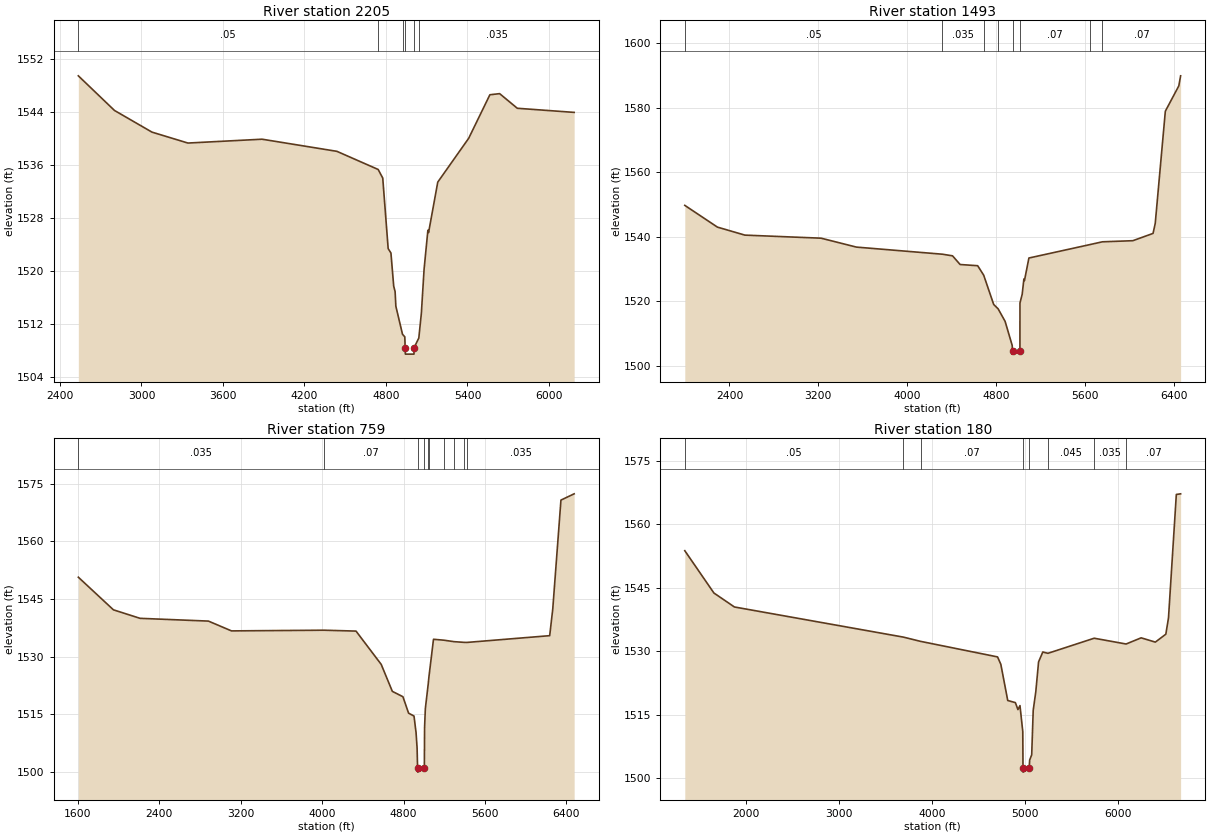
Type RM Length L Ch R = 1 ,2205    ,712,712,712
BEGIN DESCRIPTION:
Turtle Creek 3.0
END DESCRIPTION:
XS GIS Cut Line= 5
      1940620.92     13896147.15      1941193.87     13895600.24
      1941317.23     13895253.09        1941575.       13893975.
      1941415.79     13892800.36
#Sta/Elev= 30
  2535.6 1549.47  2801.8 1544.24  3077.6 1540.97  3342.3 1539.32    3888  1539.9
  4438.8 1538.07  4742.7 1535.33  4776.4 1534.03  4816.3 1523.38  4836.7 1522.72
  4857.1  1517.7  4867.3  1516.9  4872.9 1514.68  4921.8 1510.45  4938.7 1510.06
  4941.3 1508.45  4942.8 1507.45  5006.3 1507.45  5007.8 1508.45  5041.8 1509.88
  5060.5 1513.59  5080.6 1520.25  5108.7 1526.16  5113.8 1525.81  5181.3 1533.42
    5409 1540.04    5565 1546.61  5636.8 1546.78  5766.9 1544.57  6185.3 1543.95
#Mann= 6 ,-1 , 0
  2535.6     .05       0  4742.7    .035       0  4921.8     .05       0
  4941.3     .05       0  5007.8     .05       0  5041.8    .035       0
Bank Sta=4941.3,5007.8
XS Rating Curve= 0 ,0
Exp/Cntr=0.3,0.1

Type RM Length L Ch R = 1 ,1493    ,734,734,734
BEGIN DESCRIPTION:
Turtle Creek 2.0
END DESCRIPTION:
XS GIS Cut Line= 5
      1940681.74     13896216.54       1941916.4     13895039.28
        1942225.       13893775.       1942101.3     13892656.31
      1942053.42     13892328.86
#Sta/Elev= 30
    1998 1549.71  2291.5 1542.98  2539.1  1540.5    3225 1539.55  3543.3 1536.79
  4317.2 1534.59  4408.3 1534.09  4476.7  1531.4  4634.8 1531.03  4688.9  1528.1
  4778.9 1519.03  4818.9 1517.68  4881.8 1513.79  4945.4 1506.37  4948.7 1504.66
  4950.2 1503.66  5015.2 1504.66  5015.4 1519.48  5035.5 1522.19  5050.7 1526.93
  5055.8 1526.41  5095.9 1533.41  5641.5 1537.54  5757.8 1538.43  6031.6 1538.77
  6213.6 1541.03  6233.3 1544.13  6324.2 1578.86  6445.5  1586.7  6461.8 1589.81
#Mann= 8 ,-1 , 0
    1998     .05       0  4317.2    .035       0  4688.9      .1       0
  4818.9     .07       0  4948.7     .05       0  5015.2     .07       0
  5641.5    .035       0  5757.8     .07       0
Bank Sta=4948.7,5015.2
XS Rating Curve= 0 ,0
Exp/Cntr=0.3,0.1

Type RM Length L Ch R = 1 ,759     ,579,579,579
BEGIN DESCRIPTION:
Turtle Creek 1.0
END DESCRIPTION:
XS GIS Cut Line= 5
      1940690.37     13896338.12      1942856.85     13894283.89
        1942925.       13893875.      1942975.97     13892833.91
      1943016.79     13892405.77
#Sta/Elev= 30
    1604 1550.64    1949 1542.15  2210.8 1539.94  2882.7 1539.22  3109.2 1536.67
  4018.1 1536.85  4332.8 1536.62  4580.4 1527.96  4689.8 1520.94  4793.7 1519.55
  4849.5 1515.27  4902.7 1514.52    4923 1510.18  4933.1 1506.17  4937.8 1500.93
  4939.3 1499.93  5004.4 1500.93  5006.6 1511.53  5014.1 1516.43  5042.7 1522.94
  5049.1 1524.65  5094.2 1534.49  5197.7 1534.25  5296.1 1533.87  5394.4 1533.69
  5421.9 1533.67  6236.2 1535.43  6266.3 1542.39  6346.7  1570.7  6476.5 1572.33
#Mann= 10 ,-1 , 0
    1604    .035       0  4018.1     .07       0  4937.8     .05       0
  5004.4     .07       0  5042.7      .1       0  5049.1     .07       0
  5197.7    .045       0  5296.1    .035       0  5394.4    .045       0
  5421.9    .035       0
Bank Sta=4937.8,5004.4
XS Rating Curve= 0 ,0
Exp/Cntr=0.3,0.1

Type RM Length L Ch R = 1 ,180     ,0,0,0
BEGIN DESCRIPTION:
Turtle Creek 0.0
END DESCRIPTION:
XS GIS Cut Line= 5
      1940647.02     13896476.96      1943298.11     13894335.14
      1943630.53     13893712.61      1943702.94     13893080.15
       1943546.5     13892519.35
#Sta/Elev= 30
  1342.1  1553.8    1655  1543.8  1875.7 1540.49  3693.3 1533.36  3877.3 1532.36
    4706 1528.68  4741.2 1526.92  4815.4 1518.37  4897.5 1517.87  4925.1 1516.22
  4947.1 1517.16  4977.2 1511.01  4979.6 1502.43  4981.1 1501.43  5046.2 1502.43
  5051.2 1504.28  5073.1 1505.53  5089.4 1516.06    5117 1520.42  5147.2 1527.51
  5192.6 1529.84  5247.6 1529.53  5745.1  1533.1  6088.2 1531.73  6250.4 1533.19
  6402.7 1532.18  6515.7 1534.05  6544.4 1537.91  6628.6  1567.1  6674.8 1567.25
#Mann= 8 ,-1 , 0
  1342.1     .05       0  3693.3    .035       0  3877.3     .07       0
  4979.6     .05       0  5046.2     .07       0  5247.6    .045       0
  5745.1    .035       0  6088.2     .07       0
Bank Sta=4979.6,5046.2
XS Rating Curve= 0 ,0
Exp/Cntr=0.3,0.1

Chan Stop Cuts=-1
Use User Specified Reach Order=0
Composite Channel Slope=5