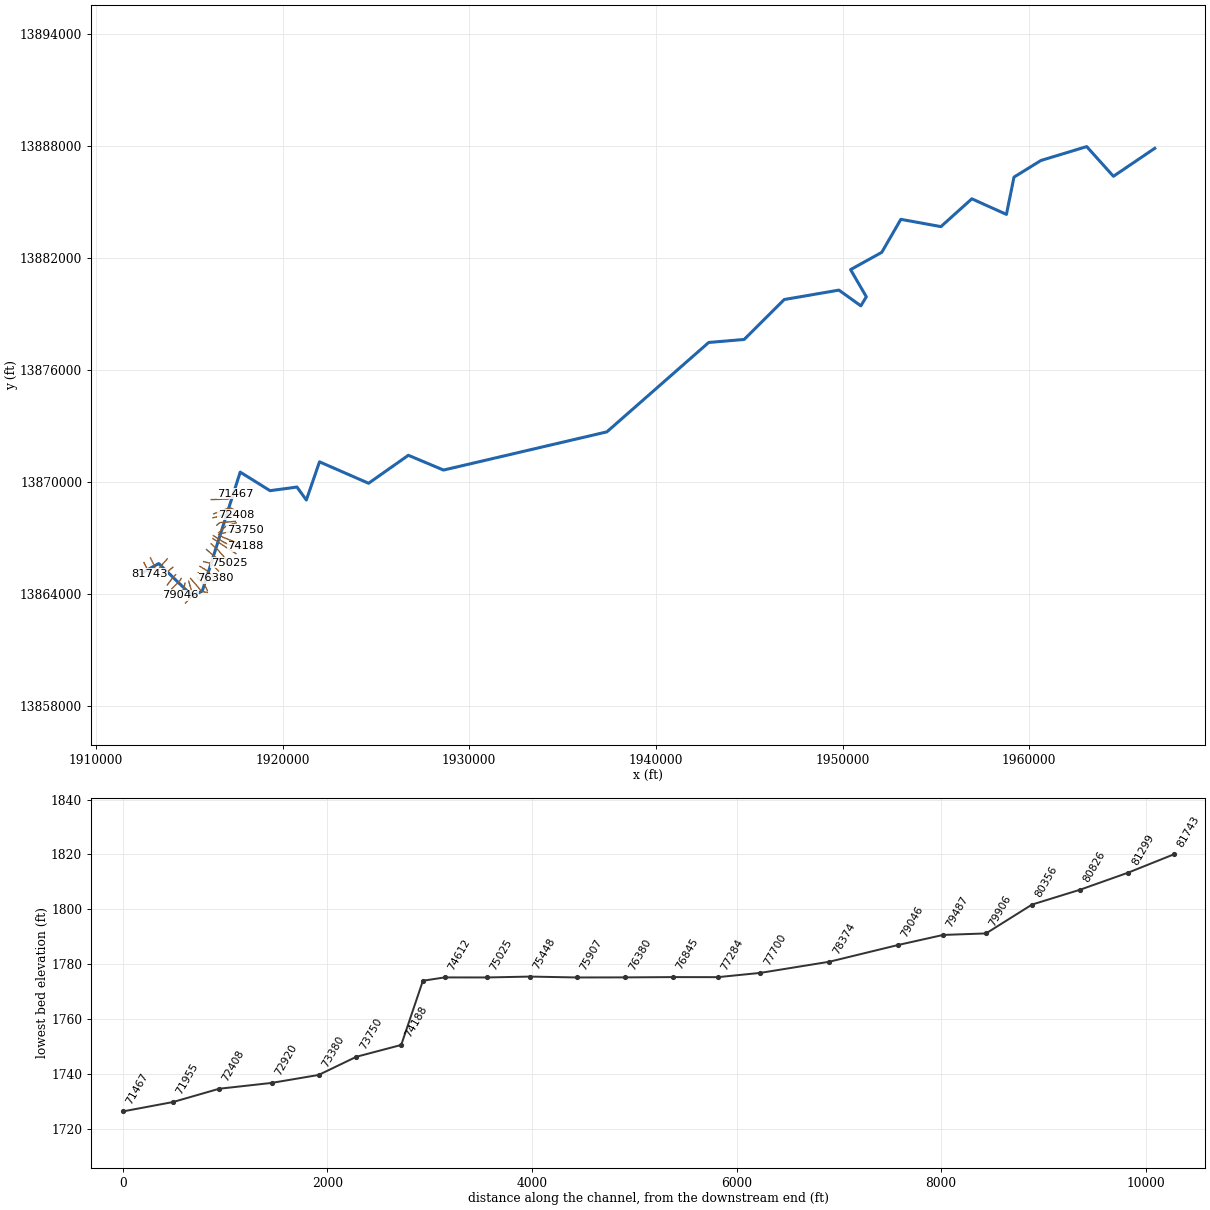
--- Verde Creek.prj (project) ---

Proj Title=Verde Creek Base Level Engineering
Current Plan=p01
Default Exp/Contr=0.3,0.1
English Units
Geom File=g01
Flow File=f01
Plan File=p01
Y Axis Title=Elevation
X Axis Title(PF)=Main Channel Distance
X Axis Title(XS)=Station
BEGIN DESCRIPTION:
Verde Creek
END DESCRIPTION:
DSS Export Rating Curves= 0
DSS Export Rating Curve Sorted= 0
DSS Export Volume Flow Curves= 0
DXF OffsetX= 0
DXF OffsetY= 0
DXF ScaleX= 1
DXF ScaleY= 10

--- Verde Creek.p01 (plan) ---

Plan Title=Multiple Run
Short Identifier=Multiple
Geom File=g01
Flow File=f01
Subcritical Flow
K Sum by GR= 0
Std Step Tol= 0.01
Critical Tol= 0.01
Num of Std Step Trials= 20
Max Error Tol= 0.3
Flow Tol Ratio= 0.001
Split Flow NTrial= 30
Split Flow Tol= 0.02
Split Flow Ratio= 0.02
Log Output Level= 0
Friction Slope Method= 1
Unsteady Friction Slope Method= 2
Unsteady Bridges Friction Slope Method= 1
Parabolic Critical Depth
Global Vel Dist=  1 , 1 , 1
Global Log Level= 0
CheckData=True
Encroach Param= -1, 0, 0, 0
BEGIN DESCRIPTION:
Multiple Run
END DESCRIPTION:

--- Verde Creek.f01 (steady flow) ---

Flow Title=Multiple
Number of Profiles=7
Profile Names=10-year,25-year,50-year,1pct_min,100-year,1pct_plu,500-year
River Rch & RM= Verde Creek,Reach-1,81743
    3130    5582    8022    5559   11092   22131   20941
River Rch & RM= Verde Creek,Reach-1,77700
    3621    6475    9321    6463   12896   25732   24384
River Rch & RM= Verde Creek,Reach-1,71467
    4261    7677   11106    7735   15434   30795   29447
River Rch & RM= Verde Creek,Reach-1,70575
    4494    8122   11772    8210   16381   32684   31350
River Rch & RM= Verde Creek,Reach-1,64701
    5863   10691   15587   10925   21798   43493   42141
River Rch & RM= Verde Creek,Reach-1,57617
    9914   18304   26911   18989   37888   75596   74215
River Rch & RM= Verde Creek,Reach-1,54989
   10793   19982   29435   20805   41512   82828   81590
River Rch & RM= Verde Creek,Reach-1,54448
   11460   21218   31256   22088   44072   87936   86580
River Rch & RM= Verde Creek,Reach-1,48311
   11594   21465   31618   22341   44577   88942   87551
River Rch & RM= Verde Creek,Reach-1,47219
   12922   23989   35402   25057   49996   99755   98512
River Rch & RM= Verde Creek,Reach-1,44484
   13053   24226   35748   25297   50474  100708   99412
River Rch & RM= Verde Creek,Reach-1,42315
   13185   24456   36070   25512   50904  101567  100158
River Rch & RM= Verde Creek,Reach-1,39564
   12844   23872   35251   24960   49802   99369   98251
River Rch & RM= Verde Creek,Reach-1,38497
   13779   25633   37874   26830   53533  106813  105697
River Rch & RM= Verde Creek,Reach-1,33427
   14143   26311   38877   27539   54948  109636  108476
River Rch & RM= Verde Creek,Reach-1,31246
   14177   26373   38968   27602   55074  109887  108711
River Rch & RM= Verde Creek,Reach-1,30249
   14179   26373   38964   27597   55062  109864  108667
River Rch & RM= Verde Creek,Reach-1,29597
   14204   26414   39019   27631   55132  110003  108770
River Rch & RM= Verde Creek,Reach-1,28475
   14170   26335   38886   27524   54918  109575  108247
River Rch & RM= Verde Creek,Reach-1,26274
   15434   28745   42511   30132   60121  119957  118823
River Rch & RM= Verde Creek,Reach-1,25095
   15574   29012   42909   30417   60690  121093  119968
River Rch & RM= Verde Creek,Reach-1,23540
   15571   28970   42810   30319   60494  120702  119358
River Rch & RM= Verde Creek,Reach-1,19194
   15702   29205   43149   30552   60959  121629  120216
River Rch & RM= Verde Creek,Reach-1,16467
   15695   29169   43074   30481   60818  121349  119803
River Rch & RM= Verde Creek,Reach-1,12584
   15839   29432   43456   30746   61346  122402  120799
River Rch & RM= Verde Creek,Reach-1,9763
   15926   29576   43652   30872   61597  122903  121187
River Rch & RM= Verde Creek,Reach-1,3226
   15950   29615   43703   30903   61660  123028  121272
River Rch & RM= Verde Creek,Reach-1,1410
   17519   32597   48176   34112   68063  135803  134211
Boundary for River Rch & Prof#=Verde Creek,Reach-1,1
Up Type=0
Dn Type=3
Dn Slope=0.005
Boundary for River Rch & Prof#=Verde Creek,Reach-1,2
Up Type=0
Dn Type=3
Dn Slope=0.005
Boundary for River Rch & Prof#=Verde Creek,Reach-1,3
Up Type=0
Dn Type=3
Dn Slope=0.005
Boundary for River Rch & Prof#=Verde Creek,Reach-1,4
Up Type=0
Dn Type=3
Dn Slope=0.005
Boundary for River Rch & Prof#=Verde Creek,Reach-1,5
Up Type=0
Dn Type=3
Dn Slope=0.005
Boundary for River Rch & Prof#=Verde Creek,Reach-1,6
Up Type=0
Dn Type=3
Dn Slope=0.005
Boundary for River Rch & Prof#=Verde Creek,Reach-1,7
Up Type=0
Dn Type=3
Dn Slope=0.005

--- Verde Creek.g01 (geometry) ---

Geom Title=Existing Conditions
Program Version=4.10

River Reach=Verde Creek     ,Reach-1
Reach XY= 30
        1912475.       13865125.      1913369.15     13865622.96
      1915168.68     13863883.06      1915702.12     13864151.49
      1917733.28     13870521.94      1919330.93     13869527.24
      1920773.53     13869721.46        1921275.       13869025.
      1921981.03     13871073.38      1924609.58     13869925.03
      1926741.14     13871424.45        1928625.     13870632.56
       1937373.5     13872678.62      1942830.04     13877469.92
      1944727.45     13877630.47      1946876.55     13879771.25
      1949805.01     13880275.06      1950981.19     13879432.81
      1951273.18     13879918.88       1950428.6     13881373.51
      1952098.82     13882298.13      1953122.71     13884069.19
      1955269.07     13883677.25        1956925.     13885167.44
       1958778.3     13884333.08      1959183.14     13886331.06
      1960626.47     13887221.46      1963078.22     13887966.72
      1964509.73     13886375.37        1966725.       13887875.

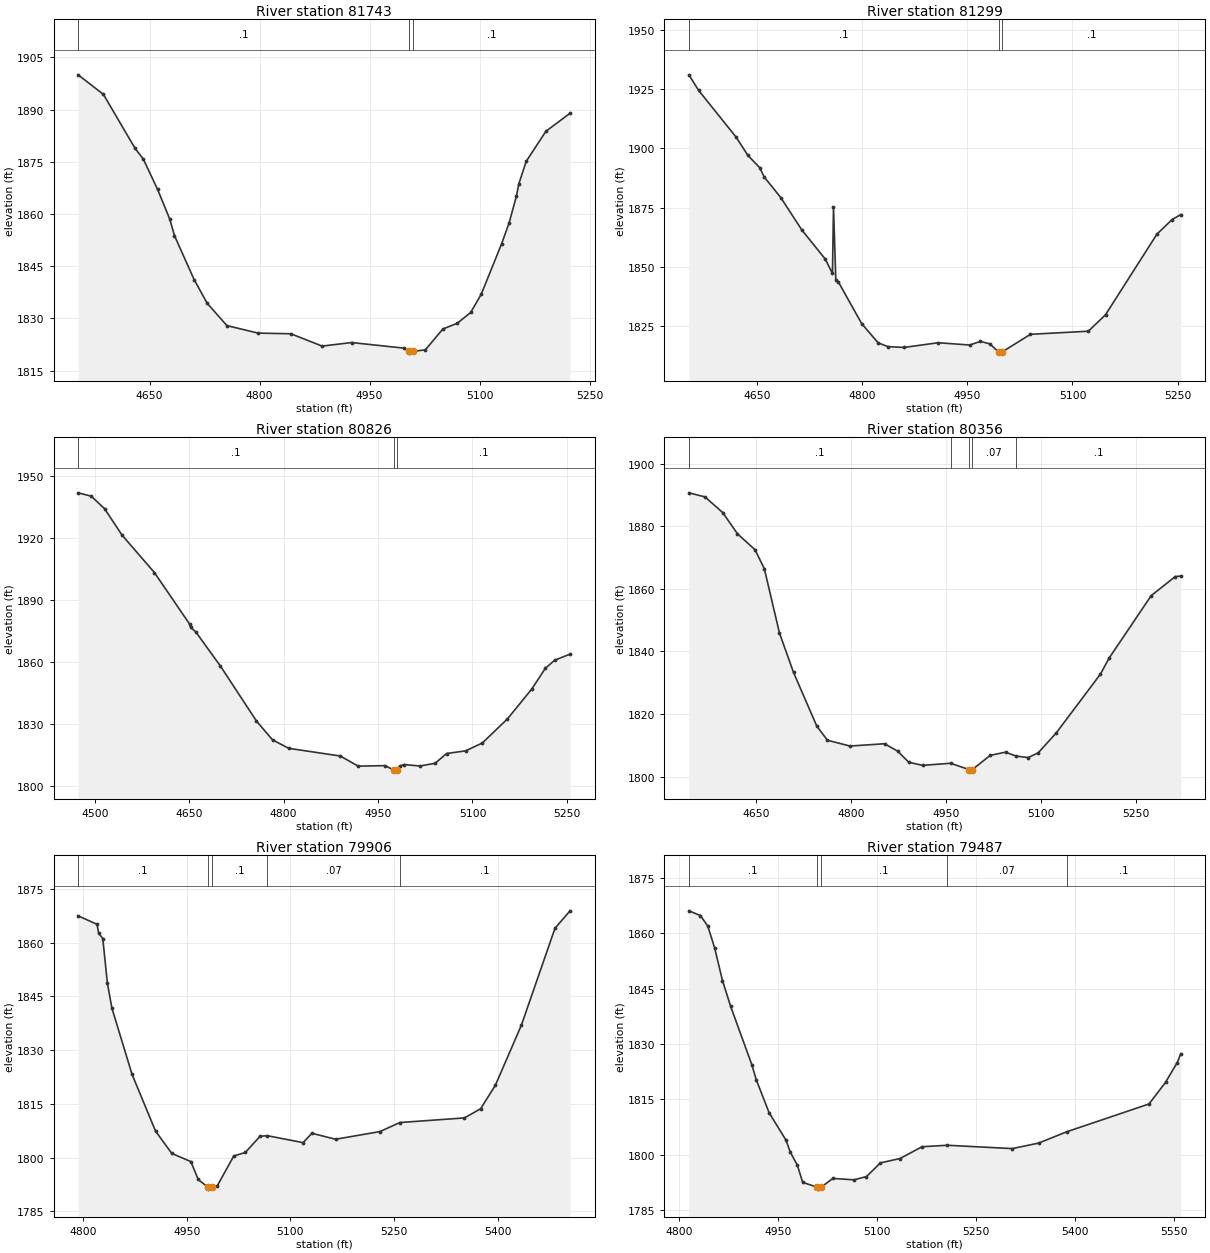
Type RM Length L Ch R = 1 ,81743   ,444,444,444
BEGIN DESCRIPTION:
Verde Creek 151.0
END DESCRIPTION:
XS GIS Cut Line= 3
      1912575.02     13865674.97        1912775.       13865275.
      1912875.01     13865074.98
#Sta/Elev= 30
  4552.6 1899.96  4587.1 1894.34  4630.3 1878.82  4641.4 1875.79  4660.9 1867.08
  4677.3 1858.67    4684 1853.78  4710.8 1841.15  4728.6 1834.36  4755.5 1827.95
    4798  1825.8  4842.7 1825.61  4885.3 1822.07  4925.5 1823.09    4997 1821.48
  5003.5 1820.55  5003.9 1820.05  5008.6 1820.55  5026.1 1820.99  5049.9 1826.97
  5069.7 1828.63    5088 1831.75  5102.3 1836.97  5130.1 1851.46  5140.2 1857.36
  5150.2 1865.09  5153.6 1868.68  5163.6 1875.11  5190.5 1883.75  5223.4 1888.93
#Mann= 3 ,-1 , 0
  4552.6      .1       0  5003.5     .05       0  5008.6      .1       0
Bank Sta=5003.5,5008.6
XS Rating Curve= 0 ,0
Exp/Cntr=0.3,0.1

Type RM Length L Ch R = 1 ,81299   ,473,473,473
BEGIN DESCRIPTION:
Verde Creek 150.0
END DESCRIPTION:
XS GIS Cut Line= 3
        1912925.     13865925.01        1913125.       13865525.
      1913175.01     13865274.97
#Sta/Elev= 30
  4552.5 1931.13  4566.2 1924.62  4619.9 1904.78  4636.6 1897.09  4653.4 1891.92
  4660.1 1887.89  4683.6 1879.23  4713.8 1865.47  4747.3 1853.15  4757.4  1847.1
  4758.9  1875.3  4762.2 1844.51  4765.6 1843.68  4799.1 1825.92  4822.6 1817.78
  4836.7 1816.16  4859.5 1815.82  4908.3 1817.82  4953.4 1816.85  4968.6 1818.38
  4982.1 1817.34  4994.5 1813.92  4994.9 1813.42  4999.6 1813.92  5040.1 1821.38
  5122.7 1822.69  5147.2 1829.65  5220.6 1863.75    5242 1869.85  5254.7 1872.04
#Mann= 3 ,-1 , 0
  4552.5      .1       0  4994.5     .05       0  4999.6      .1       0
Bank Sta=4994.5,4999.6
XS Rating Curve= 0 ,0
Exp/Cntr=0.3,0.1

Type RM Length L Ch R = 1 ,80826   ,470,470,470
BEGIN DESCRIPTION:
Verde Creek 149.0
END DESCRIPTION:
XS GIS Cut Line= 3
      1913824.99     13865874.99        1913475.       13865475.
      1913324.99     13865274.99
#Sta/Elev= 30
  4473.5 1941.95  4494.3 1940.34  4515.6 1934.23  4543.2 1921.48  4594.7 1903.33
  4650.5 1878.41  4652.3 1876.74  4660.3 1874.63  4699.4 1858.12  4756.8 1831.43
  4782.3 1822.31    4808 1818.21    4890 1814.48  4918.4 1809.58  4960.9 1809.82
  4975.3 1807.66  4975.7 1807.16  4980.5 1807.66  4984.3 1809.56  4991.1 1810.35
  5016.3 1809.65  5040.7 1810.95  5058.8 1815.69  5089.2 1816.98  5115.7 1820.81
  5155.6 1832.48  5194.2 1846.92  5215.6  1856.9  5230.6  1860.9    5255 1863.82
#Mann= 3 ,-1 , 0
  4473.5      .1       0  4975.3     .05       0  4980.5      .1       0
Bank Sta=4975.3,4980.5
XS Rating Curve= 0 ,0
Exp/Cntr=0.3,0.1

Type RM Length L Ch R = 1 ,80356   ,450,450,450
BEGIN DESCRIPTION:
Verde Creek 148.0
END DESCRIPTION:
XS GIS Cut Line= 3
      1914124.97     13865424.98        1913775.       13865125.
      1913474.97     13865024.99
#Sta/Elev= 30
  4543.7 1890.68    4569 1889.39  4597.4 1884.32  4620.4 1877.58  4648.1 1872.51
  4662.9 1866.42  4686.8 1845.88    4709 1833.27  4745.8 1816.12  4762.6 1811.62
  4798.2 1809.77  4852.8  1810.5  4873.3 1808.16  4891.1 1804.59  4912.8 1803.59
  4957.2 1804.26  4986.3 1802.25  4986.7 1801.75  4991.5 1802.25  5019.7 1806.78
    5044 1807.81  5060.6 1806.56  5079.8 1806.09  5095.6  1807.6    5124 1813.94
  5193.9 1832.75  5207.7  1837.9  5274.1 1857.83    5312 1863.91  5320.9  1864.1
#Mann= 5 ,-1 , 0
  4543.7      .1       0  4957.2     .07       0  4986.3     .05       0
  4991.5     .07       0  5060.6      .1       0
Bank Sta=4986.3,4991.5
XS Rating Curve= 0 ,0
Exp/Cntr=0.3,0.1

Type RM Length L Ch R = 1 ,79906   ,419,419,419
BEGIN DESCRIPTION:
Verde Creek 147.0
END DESCRIPTION:
XS GIS Cut Line= 3
      1914274.99     13865024.99        1914125.       13864875.
      1913825.01     13864475.02
#Sta/Elev= 30
  4792.7 1867.47  4820.1  1865.1  4822.3 1862.73  4828.4 1861.09    4835 1848.76
  4841.6 1841.71  4870.8 1823.22  4904.8 1807.41  4928.3  1801.2  4955.9 1798.92
  4966.5 1793.94  4980.8 1791.74  4981.2 1791.24  4986.2 1791.74  4994.3 1792.23
    5018 1800.48  5034.7 1801.47  5056.1 1805.99  5066.6 1806.15  5118.3 1804.21
  5131.1 1806.82  5165.4 1805.15  5229.7  1807.3  5258.4 1809.82  5351.9  1811.1
  5375.4 1813.67  5396.8 1820.26  5434.3 1836.95    5483 1864.01  5504.8 1868.87
#Mann= 5 ,-1 , 0
  4792.7      .1       0  4980.8     .05       0  4986.2      .1       0
  5066.6     .07       0  5258.4      .1       0
Bank Sta=4980.8,4986.2
XS Rating Curve= 0 ,0
Exp/Cntr=0.3,0.1

Type RM Length L Ch R = 1 ,79487   ,441,441,441
BEGIN DESCRIPTION:
Verde Creek 146.0
END DESCRIPTION:
XS GIS Cut Line= 3
      1914574.98     13864824.98        1914475.       13864675.
      1914075.02     13864275.02
#Sta/Elev= 30
  4815.1 1866.14  4832.6 1864.86  4843.8 1861.98  4854.2 1856.02    4866 1847.24
  4878.4 1840.23  4910.9 1824.23  4917.3  1820.3  4936.8 1811.38  4962.4 1803.95
  4968.8 1800.73  4979.6 1797.17  4987.6 1792.53    5010 1791.19  5010.4 1790.69
  5015.4 1791.19  5033.4  1793.6  5065.2 1793.21  5084.3 1794.09  5105.5  1797.8
  5135.2 1798.99  5168.7 1802.19  5207.1 1802.58  5305.4 1801.68  5345.2 1803.16
    5388 1806.24  5512.8 1813.78  5537.8 1819.64  5555.3 1824.91    5561  1827.4
#Mann= 5 ,-1 , 0
  4815.1      .1       0    5010     .05       0  5015.4      .1       0
  5207.1     .07       0    5388      .1       0
Bank Sta=5010,5015.4
XS Rating Curve= 0 ,0
Exp/Cntr=0.3,0.1

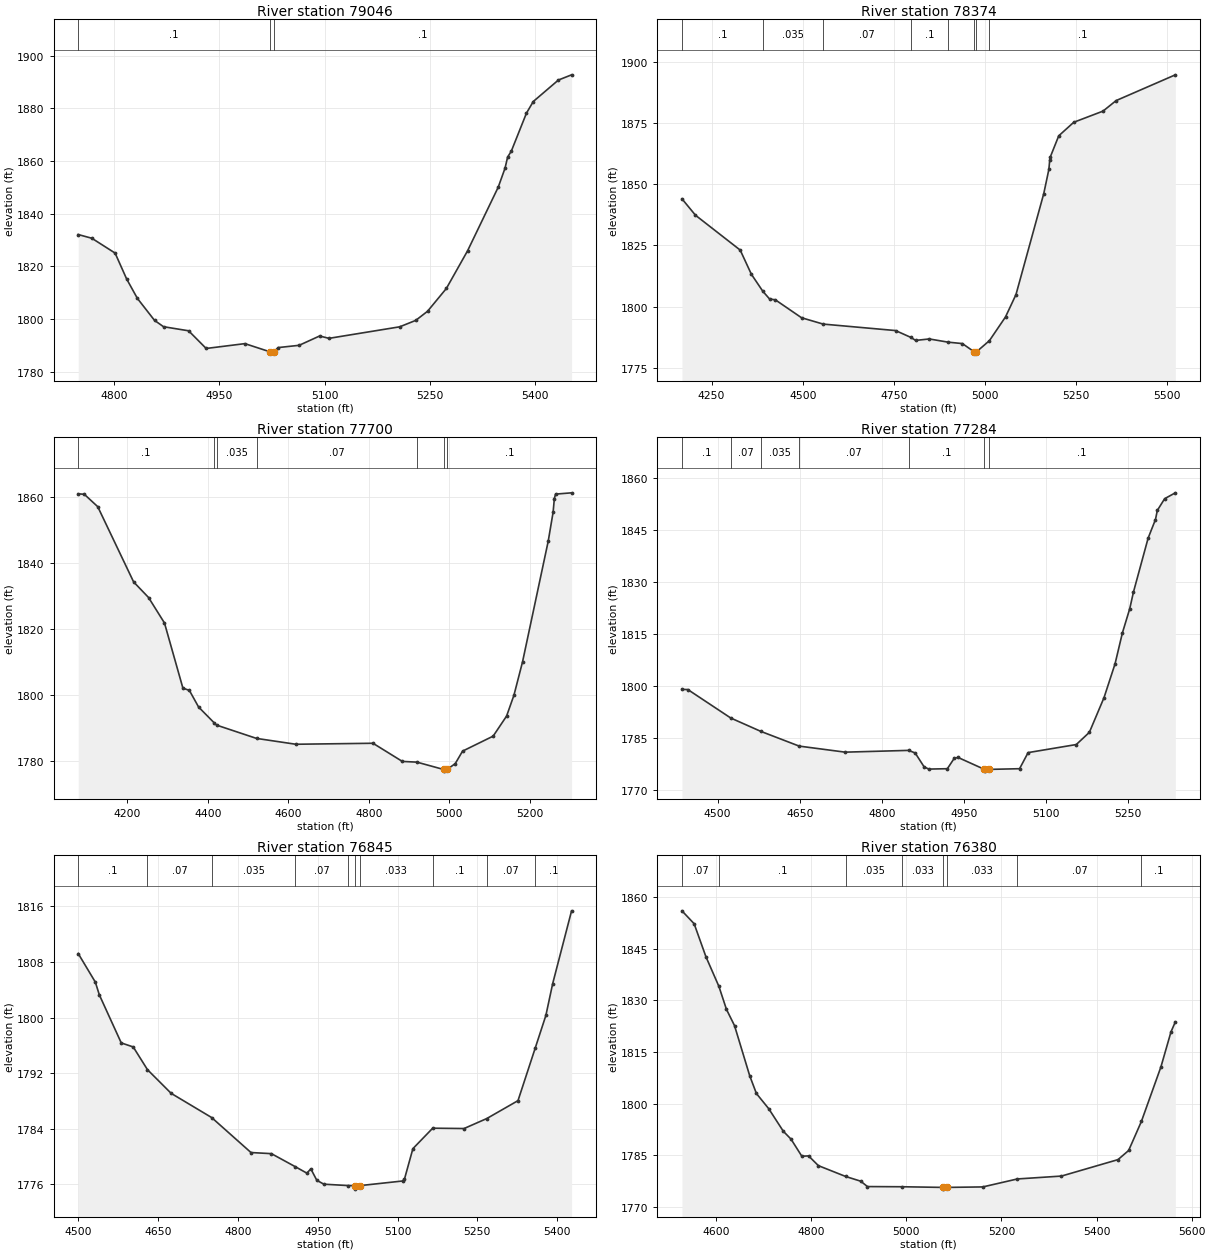
Type RM Length L Ch R = 1 ,79046   ,672,672,672
BEGIN DESCRIPTION:
Verde Creek 145.0
END DESCRIPTION:
XS GIS Cut Line= 3
        1914775.     13864574.98        1914725.       13864325.
      1914525.02     13863925.04
#Sta/Elev= 30
  4749.5 1832.09  4768.9 1830.68    4802 1825.04  4818.4 1815.22  4833.7 1807.83
  4858.1 1799.47  4870.9 1797.06  4906.6 1795.51  4931.6 1788.79  4986.7 1790.63
  5022.4 1787.52  5022.9 1787.02  5027.9 1787.52  5034.1 1789.13  5063.9 1789.99
    5093 1793.53  5106.4 1792.64    5207 1797.02  5229.8 1799.46  5246.6 1802.92
  5273.4 1811.59  5303.6 1825.91  5347.2 1850.08  5356.9 1857.31  5360.6 1861.54
  5365.8 1863.76  5387.4 1878.23  5397.1 1882.65  5432.9 1890.82  5451.6 1892.79
#Mann= 3 ,-1 , 0
  4749.5      .1       0  5022.4     .05       0  5027.9      .1       0
Bank Sta=5022.4,5027.9
XS Rating Curve= 0 ,0
Exp/Cntr=0.3,0.1

Type RM Length L Ch R = 1 ,78374   ,674,674,674
BEGIN DESCRIPTION:
Verde Creek 144.0
END DESCRIPTION:
XS GIS Cut Line= 3
        1914975.     13864675.01      1915195.47     13863927.52
      1914802.27     13863509.53
#Sta/Elev= 30
  4168.9 1844.06    4206 1837.34  4328.6 1823.09  4359.3 1813.19  4390.7 1806.23
  4409.3 1803.06  4424.9 1802.75  4496.9  1795.4  4556.2 1792.81  4754.8 1790.16
  4797.2 1787.33  4809.7 1786.13  4847.2 1786.73  4898.8 1785.42  4937.9 1784.84
  4970.8 1781.43  4971.2 1780.93  4976.4 1781.43  5012.1 1786.02  5056.3 1795.74
    5085 1804.88  5161.2 1846.19  5175.2 1856.08  5177.6 1859.97  5179.4 1861.28
  5202.3 1869.84  5243.5 1875.38  5323.7 1879.94  5359.8 1884.26  5522.1 1894.79
#Mann= 8 ,-1 , 0
  4168.9      .1       0  4390.7    .035       0  4556.2     .07       0
  4797.2      .1       0  4898.8    .035       0  4970.8    .035       0
  4976.4    .035       0  5012.1      .1       0
Bank Sta=4970.8,4976.4
XS Rating Curve= 0 ,0
Exp/Cntr=0.3,0.1

Type RM Length L Ch R = 1 ,77700   ,416,416,416
BEGIN DESCRIPTION:
Verde Creek 143.0
END DESCRIPTION:
XS GIS Cut Line= 3
      1915074.99     13864825.01        1915675.       13864125.
        1915975.       13864075.
#Sta/Elev= 30
  4077.7 1860.88  4092.9 1860.72  4126.2 1856.98  4215.4 1834.18  4252.5 1829.46
  4292.1 1821.74  4337.9 1802.01  4353.9 1801.33  4376.9 1796.28  4415.1 1791.56
  4421.8  1790.8  4520.8 1786.78  4618.5 1785.01  4810.3 1785.31  4883.2 1779.81
  4919.6 1779.59  4985.8 1777.37  4986.3 1776.87  4994.2 1777.37  5014.6 1779.13
  5032.9 1782.93  5108.9 1787.47  5142.3 1793.55  5160.6 1799.88  5181.9 1809.95
  5245.8 1846.55  5257.9 1855.29    5261 1859.45    5264 1860.78  5303.8 1861.17
#Mann= 7 ,-1 , 0
  4077.7      .1       0  4415.1     .07       0  4421.8    .035       0
  4520.8     .07       0  4919.6      .1       0  4985.8     .05       0
  4994.2      .1       0
Bank Sta=4985.8,4994.2
XS Rating Curve= 0 ,0
Exp/Cntr=0.3,0.1

Type RM Length L Ch R = 1 ,77284   ,439,439,439
BEGIN DESCRIPTION:
Verde Creek 142.0
END DESCRIPTION:
XS GIS Cut Line= 3
      1915425.02     13864874.98        1915825.       13864475.
      1915975.02     13864174.97
#Sta/Elev= 30
  4434.8 1798.91  4445.5 1798.87    4524 1790.64    4579 1786.78  4648.8 1782.54
  4732.8 1780.79  4848.7  1781.3  4860.7 1780.56    4877 1776.56  4885.5  1775.9
  4919.5 1776.01  4932.2 1779.04  4939.2 1779.25  4987.3 1775.81  4987.8 1775.31
  4995.8 1775.81  5051.4 1776.01    5067 1780.66    5155 1782.99  5178.9 1786.52
  5205.7 1796.56  5225.8 1806.31  5239.2 1815.23  5252.6 1822.21  5259.4 1827.03
  5286.2  1842.6  5299.6 1847.97    5303 1850.61  5316.4    1854  5335.9 1855.69
#Mann= 7 ,-1 , 0
  4434.8      .1       0    4524     .07       0    4579    .035       0
  4648.8     .07       0  4848.7      .1       0  4987.3     .05       0
  4995.8      .1       0
Bank Sta=4987.3,4995.8
XS Rating Curve= 0 ,0
Exp/Cntr=0.3,0.1

Type RM Length L Ch R = 1 ,76845   ,465,465,465
BEGIN DESCRIPTION:
Verde Creek 141.0
END DESCRIPTION:
XS GIS Cut Line= 3
      1915474.98     13865125.01        1915875.       13864825.
      1916274.98     13864675.01
#Sta/Elev= 30
  4499.9  1809.2  4532.1 1805.09  4539.6 1803.26  4580.8 1796.35  4603.3 1795.77
  4630.1  1792.5  4674.6  1789.1  4750.7 1785.62  4824.6 1780.59    4863 1780.43
    4908 1778.55  4929.6 1777.63  4937.1 1778.24  4948.3  1776.6  4961.6 1776.04
  5007.3 1775.84  5019.9 1775.83  5020.4 1775.33  5028.8 1775.83  5109.6  1776.5
  5112.9 1776.73  5128.9 1781.15  5166.1 1784.09    5225 1784.04  5267.8 1785.48
  5326.4 1788.05    5359 1795.66  5378.8  1800.3  5391.6 1804.88  5427.1 1815.34
#Mann= 10 ,-1 , 0
  4499.9      .1       0  4630.1     .07       0  4750.7    .035       0
    4908     .07       0  5007.3    .033       0  5019.9     .05       0
  5028.8    .033       0  5166.1      .1       0  5267.8     .07       0
    5359      .1       0
Bank Sta=5019.9,5028.8
XS Rating Curve= 0 ,0
Exp/Cntr=0.3,0.1

Type RM Length L Ch R = 1 ,76380   ,473,473,473
BEGIN DESCRIPTION:
Verde Creek 140.0
END DESCRIPTION:
XS GIS Cut Line= 3
        1915575.       13865475.        1915975.       13865225.
      1916375.01     13864824.99
#Sta/Elev= 30
  4528.3 1855.98  4553.9 1852.23  4578.7 1842.65    4606 1834.04  4621.8  1827.4
  4638.8 1822.67  4670.7 1808.14  4684.8 1802.98  4710.7 1798.57  4741.4 1792.02
  4757.7 1789.72  4780.3 1784.78  4794.5 1784.87  4815.2 1782.04  4872.5  1778.9
  4904.2 1777.53  4918.3 1775.97  4991.1 1775.92    5077 1775.73  5077.5 1775.23
  5085.9 1775.73  5160.9 1775.87  5233.5 1778.18  5326.3 1779.02  5445.1 1783.79
  5467.5 1786.44  5494.3 1794.86  5535.4  1810.7  5556.6 1820.88  5565.7 1823.76
#Mann= 8 ,-1 , 0
  4528.3     .07       0    4606      .1       0  4872.5    .035       0
  4991.1    .033       0    5077    .033       0  5085.9    .033       0
  5233.5     .07       0  5494.3      .1       0
Bank Sta=5077,5085.9
XS Rating Curve= 0 ,0
Exp/Cntr=0.3,0.1

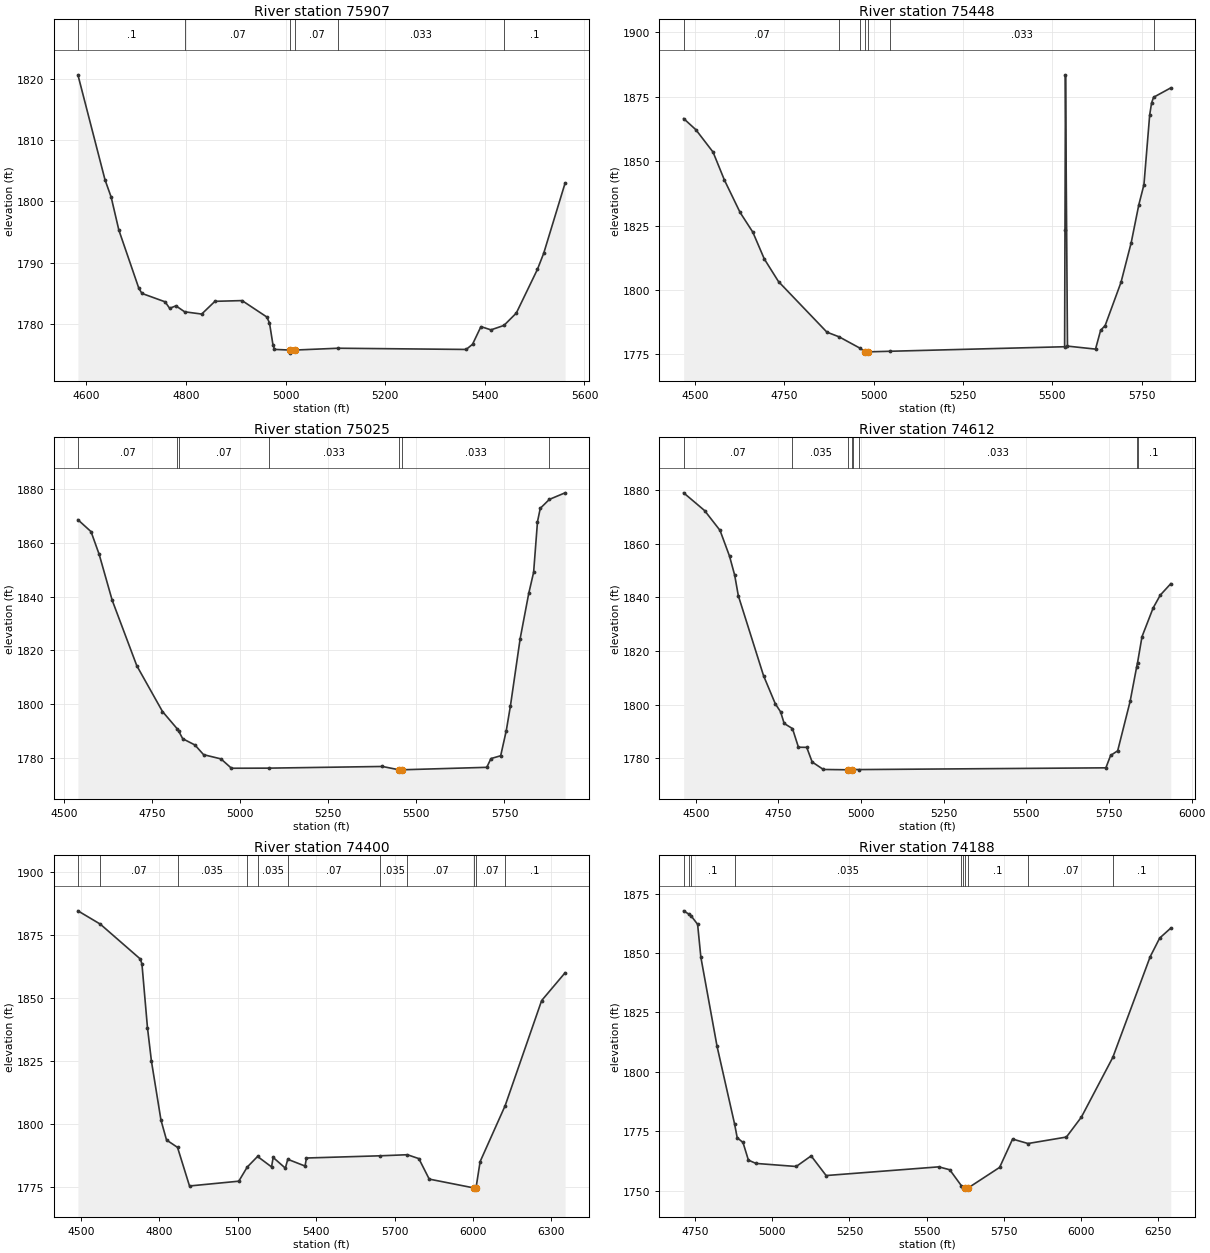
Type RM Length L Ch R = 1 ,75907   ,459,459,459
BEGIN DESCRIPTION:
Verde Creek 139.0
END DESCRIPTION:
XS GIS Cut Line= 3
      1915774.96     13865725.01        1916175.       13865625.
      1916574.97     13865225.03
#Sta/Elev= 30
  4583.1 1820.65  4637.5 1803.51  4649.9 1800.67  4665.3  1795.3  4705.5 1785.77
  4711.7 1784.95  4758.1 1783.58  4767.3 1782.52  4779.9 1782.92  4797.4 1781.95
  4831.6 1781.58  4858.2 1783.66  4912.7 1783.78  4962.2 1781.11  4967.7 1780.14
  4974.6  1776.6  4977.7 1775.81  5008.9  1775.7  5009.4  1775.2    5018  1775.7
  5105.7    1776  5362.5  1775.8  5375.3 1776.64  5392.2 1779.53  5412.3    1779
  5438.3 1779.72  5463.2 1781.74  5505.6 1788.88  5518.3 1791.53  5561.1 1802.96
#Mann= 6 ,-1 , 0
  4583.1      .1       0  4797.4     .07       0  5008.9     .05       0
    5018     .07       0  5105.7    .033       0  5438.3      .1       0
Bank Sta=5008.9,5018
XS Rating Curve= 0 ,0
Exp/Cntr=0.3,0.1

Type RM Length L Ch R = 1 ,75448   ,423,423,423
BEGIN DESCRIPTION:
Verde Creek 138.0
END DESCRIPTION:
XS GIS Cut Line= 3
      1915925.02     13866374.98        1916325.       13866025.
      1917024.96     13865575.03
#Sta/Elev= 30
  4468.3 1866.52  4502.7 1862.17  4550.7  1853.5  4582.5 1842.65  4626.3 1830.11
  4662.1 1822.42    4694 1812.08  4733.9 1803.27  4869.4 1783.65  4903.4 1781.85
  4960.6 1777.54  4976.4 1776.02  4976.9 1775.52  4985.7 1776.02  5045.2 1776.24
  5534.7    1778  5535.7 1823.43  5537.1 1883.48  5542.7 1778.24  5621.2 1777.08
  5635.5 1784.38  5648.1  1786.2  5692.5 1802.98  5721.1 1818.39  5742.4 1833.09
  5756.7 1840.84  5772.8 1867.91  5778.1 1872.56  5783.6 1874.77  5831.9 1878.42
#Mann= 7 ,-1 , 0
  4468.3     .07       0  4903.4    .035       0  4960.6     .07       0
  4976.4     .05       0  4985.7     .07       0  5045.2    .033       0
  5783.6      .1       0
Bank Sta=4976.4,4985.7
XS Rating Curve= 0 ,0
Exp/Cntr=0.3,0.1

Type RM Length L Ch R = 1 ,75025   ,413,413,413
BEGIN DESCRIPTION:
Verde Creek 137.0
END DESCRIPTION:
XS GIS Cut Line= 3
      1916174.97     13866675.03        1916525.       13866375.
      1917125.02     13865674.98
#Sta/Elev= 30
    4539 1868.52  4576.3 1864.09  4599.4 1855.65  4636.2 1838.68  4706.2 1814.32
  4779.1 1797.33  4821.7 1790.79  4824.8 1790.13  4836.6 1787.22  4871.3  1784.9
  4895.8 1781.31  4945.1 1779.74  4974.9 1776.27    5081 1776.31  5403.4 1776.93
  5450.4  1775.7  5450.9  1775.2  5459.8  1775.7  5699.7 1776.61  5711.6 1779.86
  5739.2 1780.91    5755 1790.17  5766.9 1799.43  5794.5 1824.38  5818.9 1841.19
  5832.7 1848.99  5843.7 1867.79  5851.6 1872.75  5877.4 1876.06    5922  1878.5
#Mann= 7 ,-1 , 0
    4539     .07       0  4821.7    .035       0  4824.8     .07       0
    5081    .033       0  5450.4     .05       0  5459.8    .033       0
  5877.4      .1       0
Bank Sta=5450.4,5459.8
XS Rating Curve= 0 ,0
Exp/Cntr=0.3,0.1

Type RM Length L Ch R = 1 ,74612   ,212,212,212
BEGIN DESCRIPTION:
Verde Creek 136.0
END DESCRIPTION:
XS GIS Cut Line= 3
        1916267.     13866960.81      1916723.55     13866659.67
      1917501.79     13866156.43
#Sta/Elev= 30
  4463.2 1878.96  4526.6 1872.35  4573.3 1864.96    4602 1855.37  4617.7 1848.24
  4628.6 1840.64  4704.9 1810.82  4740.6  1800.3  4756.6 1797.31  4767.3    1793
  4792.5 1791.07  4810.5 1784.13  4835.6 1784.08    4852 1778.63  4885.9 1775.84
  4961.7 1775.72  4962.2 1775.22  4971.1 1775.72  4974.1 1775.85  4993.7  1775.8
  5740.5 1776.45  5754.8 1781.06  5776.2  1782.8  5813.8 1801.21  5833.7 1814.11
  5836.3 1815.64  5849.8 1825.34  5883.4 1836.03    5905 1840.82  5936.9  1845.1
#Mann= 8 ,-1 , 0
  4463.2     .07       0  4792.5    .035       0  4961.7    .033       0
  4971.1    .035       0  4974.1     .07       0  4993.7    .033       0
  5833.7     .07       0  5836.3      .1       0
Bank Sta=4961.7,4971.1
XS Rating Curve= 0 ,0
Exp/Cntr=0.3,0.1

Type RM Length L Ch R = 1 ,74400   ,212,212,212
BEGIN DESCRIPTION:
Verde Creek D5
END DESCRIPTION:
XS GIS Cut Line= 6
      1916292.47      13867121.1      1916804.63     13866795.58
      1916926.16     13866730.47      1917299.42     13866565.54
      1917442.65     13866526.48      1917991.95     13866401.05
#Sta/Elev= 30
    4488 1884.44  4573.7 1879.16  4727.2 1865.29  4733.2 1863.27  4754.3 1838.03
  4769.6 1824.68    4806 1801.37  4827.2  1793.5  4869.3 1790.57  4915.2 1775.25
  5103.8 1777.15    5136 1782.74  5175.7 1786.96  5229.2 1782.82  5235.4 1786.57
    5282 1782.33  5291.3 1785.84  5357.4 1783.16  5362.9 1786.35    5646 1787.23
  5749.1 1787.65    5793 1786.11  5832.7 1777.98  6002.4  1774.5  6002.9    1774
  6011.8  1774.5  6027.6 1784.93  6123.4 1807.14    6263 1848.83  6352.7 1859.85
#Mann= 11 ,-1 , 0
    4488      .1       0  4573.7     .07       0  4869.3    .035       0
    5136     .07       0  5175.7    .035       0  5291.3     .07       0
    5646    .035       0  5749.1     .07       0  6002.4    .035       0
  6011.8     .07       0  6123.4      .1       0
Bank Sta=6002.4,6011.8
XS Rating Curve= 0 ,0
Exp/Cntr=0.3,0.1

Type RM Length L Ch R = 1 ,74188   ,438,438,438
BEGIN DESCRIPTION:
Verde Creek 135.0
END DESCRIPTION:
XS GIS Cut Line= 3
      1916575.01     13867174.99        1916825.       13867025.
      1918019.96     13866549.02
#Sta/Elev= 30
  4713.1 1867.77  4731.1 1866.29    4737 1865.71  4758.4 1862.09  4768.9 1848.26
  4821.4  1810.7  4878.3 1777.95  4886.6 1772.27  4905.4 1770.25  4922.9 1762.83
  4947.4 1761.44  5077.7 1760.15  5126.1 1764.61  5174.6 1756.34  5539.5    1760
    5575 1758.77  5612.4  1752.1  5618.8 1751.21  5625.2 1751.12  5625.7 1750.62
  5634.6 1751.12  5736.5 1759.77  5778.5 1771.69  5828.5 1769.82  5952.8 1772.54
  6001.3 1780.93  6103.1 1806.08  6224.1 1848.45  6254.9  1856.3  6290.9 1860.51
#Mann= 10 ,-1 , 0
  4713.1      .1       0  4731.1     .07       0    4737      .1       0
  4878.3    .035       0  5612.4     .07       0  5618.8      .1       0
  5625.2    .035       0  5634.6      .1       0  5828.5     .07       0
  6103.1      .1       0
Bank Sta=5625.2,5634.6
XS Rating Curve= 0 ,0
Exp/Cntr=0.3,0.1

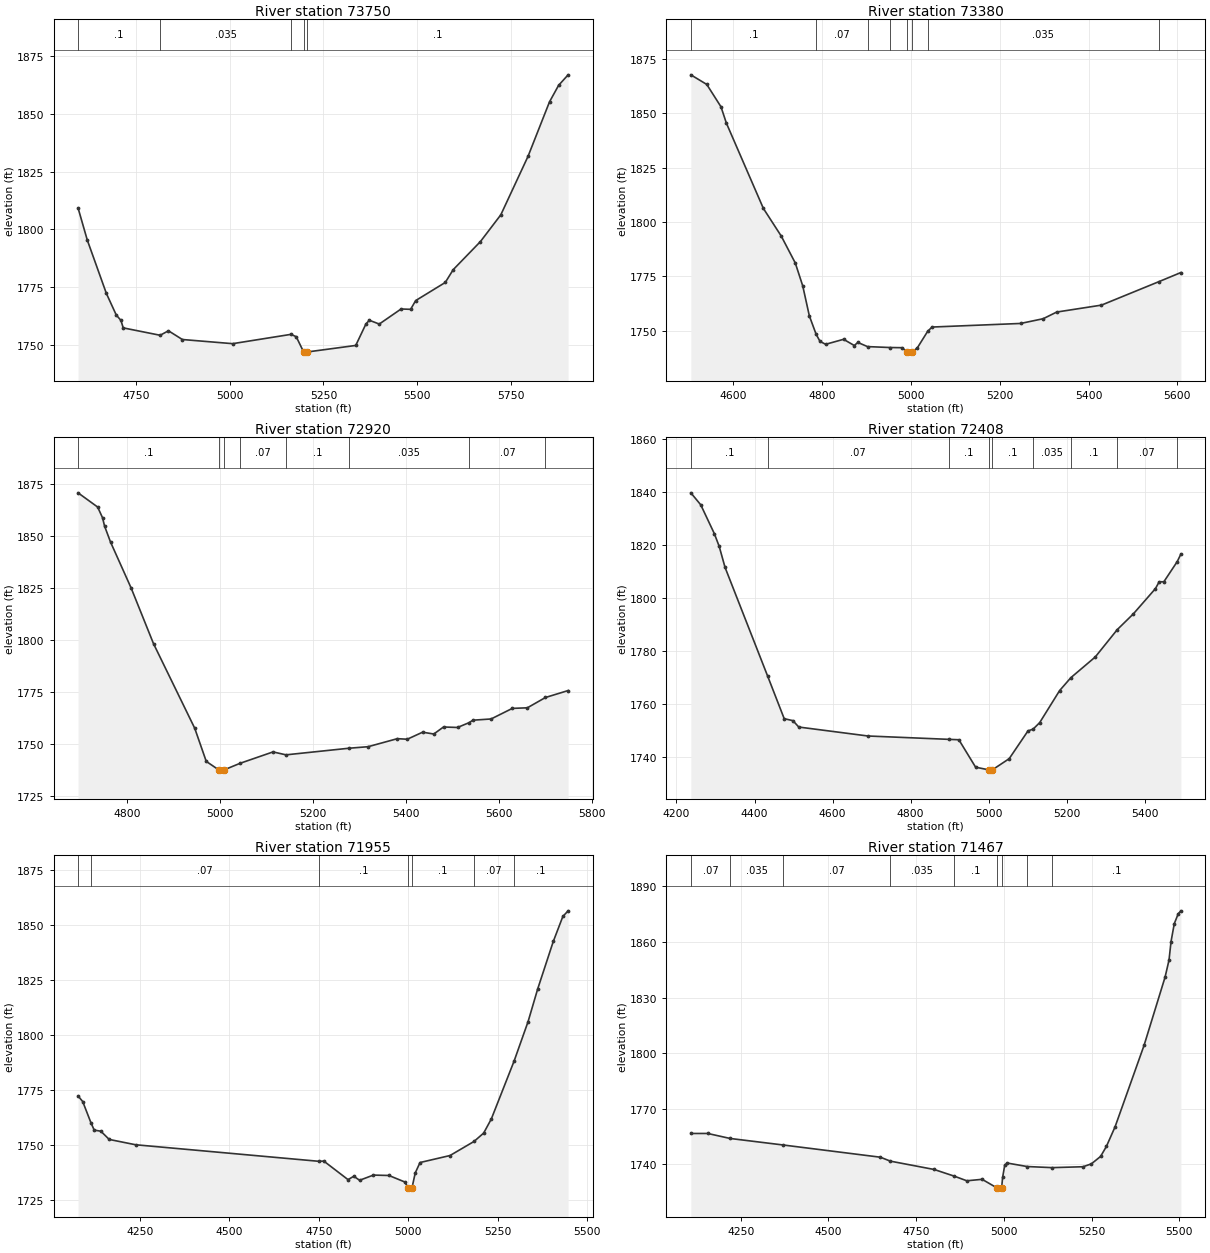
Type RM Length L Ch R = 1 ,73750   ,370,370,370
BEGIN DESCRIPTION:
Verde Creek 134.0
END DESCRIPTION:
XS GIS Cut Line= 3
      1916725.01       13867225.        1917125.       13867325.
      1918013.13     13867431.57
#Sta/Elev= 30
  4595.5 1809.25  4620.1 1795.34  4671.1 1772.16  4697.4 1762.84  4709.8 1760.51
    4716 1757.26  4814.4 1754.06  4836.6    1756  4873.7 1752.22  5007.8 1750.42
  5163.5 1754.46  5177.4 1753.41    5197 1746.82  5197.5 1746.32  5206.5 1746.82
    5336 1749.65  5363.2 1758.97  5372.3 1760.56  5398.7 1758.92  5456.9 1765.45
  5482.3  1765.3  5495.8 1769.09  5574.7 1776.94  5595.9 1782.49  5668.4 1794.65
  5722.8 1806.25  5795.3 1831.56  5852.7 1855.22  5876.9 1862.36  5902.3 1866.92
#Mann= 5 ,-1 , 0
  4595.5      .1       0  4814.4    .035       0  5163.5      .1       0
    5197    .035       0  5206.5      .1       0
Bank Sta=5197,5206.5
XS Rating Curve= 0 ,0
Exp/Cntr=0.3,0.1

Type RM Length L Ch R = 1 ,73380   ,460,460,460
BEGIN DESCRIPTION:
Verde Creek 133.0
END DESCRIPTION:
XS GIS Cut Line= 3
      1916574.97     13867274.97      1916984.99     13867637.15
      1917517.27       13867801.
#Sta/Elev= 30
  4503.9 1867.62  4539.8  1863.2  4571.8 1852.93  4583.9 1845.46  4667.3 1806.21
  4707.5 1793.52  4739.2 1781.12    4756 1770.59  4770.9 1756.79  4786.1 1748.39
  4794.9 1745.07  4807.6 1743.75    4848 1746.04  4872.1 1743.19  4880.1  1744.6
  4901.9 1742.69  4952.4 1742.27  4979.4 1742.19  4991.9 1740.19  4992.4 1739.69
  5001.6 1740.19  5013.8    1742  5037.4 1749.71  5047.3 1751.68  5246.8 1753.33
  5297.7 1755.51  5328.1 1758.57    5429 1761.76  5558.6 1772.57  5607.9 1776.74
#Mann= 8 ,-1 , 0
  4503.9      .1       0  4786.1     .07       0  4901.9      .1       0
  4952.4     .07       0  4991.9     .05       0  5001.6     .07       0
  5037.4    .035       0  5558.6      .1       0
Bank Sta=4991.9,5001.6
XS Rating Curve= 0 ,0
Exp/Cntr=0.3,0.1

Type RM Length L Ch R = 1 ,72920   ,512,512,512
BEGIN DESCRIPTION:
Verde Creek 132.0
END DESCRIPTION:
XS GIS Cut Line= 3
      1916475.03     13867675.03      1916635.66     13867814.86
      1917475.25       13867884.
#Sta/Elev= 30
  4694.2 1870.77  4736.4 1863.93    4747 1858.73  4751.3 1854.77  4764.1  1847.1
  4808.7 1824.86  4856.7 1798.16  4945.5 1757.42  4970.3 1741.48  4997.9 1737.29
  4998.4 1736.79  5007.6 1737.29  5043.4 1740.58  5114.1 1746.04    5142 1744.63
  5277.5 1747.81  5318.8 1748.55  5381.9 1752.42  5403.1 1752.14  5436.2 1755.53
  5460.3 1754.66  5481.3 1758.04  5511.4 1757.81  5536.5 1760.14  5544.5 1761.31
  5583.7  1761.9  5629.4 1766.99  5661.9 1767.28  5700.8 1772.24  5749.6 1775.58
#Mann= 8 ,-1 , 0
  4694.2      .1       0  4997.9     .05       0  5007.6      .1       0
  5043.4     .07       0    5142      .1       0  5277.5    .035       0
  5536.5     .07       0  5700.8      .1       0
Bank Sta=4997.9,5007.6
XS Rating Curve= 0 ,0
Exp/Cntr=0.3,0.1

Type RM Length L Ch R = 1 ,72408   ,453,453,453
BEGIN DESCRIPTION:
Verde Creek 131.0
END DESCRIPTION:
XS GIS Cut Line= 4
      1916274.95     13868074.99      1916893.69     13868224.39
        1917025.       13868225.      1917512.53     13868240.43
#Sta/Elev= 30
  4236.8 1839.77  4262.2 1835.24    4297 1824.36  4309.5 1819.53  4324.4 1811.63
  4433.7 1770.51    4476 1754.48  4498.4 1753.73  4513.3 1751.32  4690.4 1747.94
  4897.6 1746.67  4923.5 1746.52  4966.4 1736.16  4999.6 1735.17  5000.1 1734.67
  5009.4 1735.17  5052.5 1739.38  5100.6 1749.86  5113.7 1750.53  5130.6 1752.99
  5181.6 1765.08  5210.4 1769.96  5272.9 1777.77  5329.4 1788.12  5370.7 1794.08
  5427.1 1803.59  5436.7 1806.17  5448.7 1806.18  5482.9 1813.78  5492.4 1816.66
#Mann= 9 ,-1 , 0
  4236.8      .1       0  4433.7     .07       0  4897.6      .1       0
  4999.6     .05       0  5009.4      .1       0  5113.7    .035       0
  5210.4      .1       0  5329.4     .07       0  5482.9      .1       0
Bank Sta=4999.6,5009.4
XS Rating Curve= 0 ,0
Exp/Cntr=0.3,0.1

Type RM Length L Ch R = 1 ,71955   ,488,488,488
BEGIN DESCRIPTION:
Verde Creek 130.0
END DESCRIPTION:
XS GIS Cut Line= 3
      1916316.81     13868287.22        1917175.       13868625.
      1917575.01       13868425.
#Sta/Elev= 30
  4076.8 1772.16  4089.8 1769.63  4112.9 1759.96    4122 1756.64  4140.5 1756.14
  4163.9  1752.4  4237.7 1749.98    4750 1742.46  4763.6 1742.56  4831.3 1734.13
  4847.4 1735.68  4863.5 1733.84  4902.2  1736.2  4945.6 1736.02  4989.3 1733.11
  5000.1 1730.32  5000.6 1729.82  5009.9 1730.32  5019.1 1737.19  5032.5 1741.91
  5116.3 1745.09  5183.3 1751.48  5210.3 1755.29  5231.7 1761.71  5295.3 1787.99
  5334.4 1805.93  5361.2 1820.75  5404.8 1842.35  5431.6 1853.73  5446.3 1856.28
#Mann= 7 ,-1 , 0
  4076.8    .035       0  4112.9     .07       0    4750      .1       0
  5000.1     .05       0  5009.9      .1       0  5183.3     .07       0
  5295.3      .1       0
Bank Sta=5000.1,5009.9
XS Rating Curve= 0 ,0
Exp/Cntr=0.3,0.1

Type RM Length L Ch R = 1 ,71467   ,444,444,444
BEGIN DESCRIPTION:
Verde Creek 129.0
END DESCRIPTION:
XS GIS Cut Line= 3
      1916178.76     13869049.33        1917075.       13869075.
        1917475.       13869375.
#Sta/Elev= 30
  4107.9  1756.5    4156 1756.51    4220  1753.8  4370.5 1750.29  4648.2 1743.67
  4676.4 1741.55  4801.3 1737.04  4858.2 1733.46  4894.3 1730.93    4938 1731.72
  4981.8 1726.92  4982.3 1726.42  4993.5 1726.92  4996.4 1732.72  5002.4 1739.34
  5009.4 1740.52  5066.4 1738.63  5137.3 1738.04  5225.7 1738.52  5249.4 1740.09
  5275.6 1744.09  5292.1 1749.47  5316.9 1760.11  5399.4 1804.07  5459.4 1841.04
  5470.6 1850.22  5476.4 1860.27  5485.6 1869.91  5496.9 1875.28  5504.5 1876.85
#Mann= 9 ,-1 , 0
  4107.9     .07       0    4220    .035       0  4370.5     .07       0
  4676.4    .035       0  4858.2      .1       0  4981.8     .05       0
  4993.5      .1       0  5066.4     .07       0  5137.3      .1       0
Bank Sta=4981.8,4993.5
XS Rating Curve= 0 ,0
Exp/Cntr=0.3,0.1