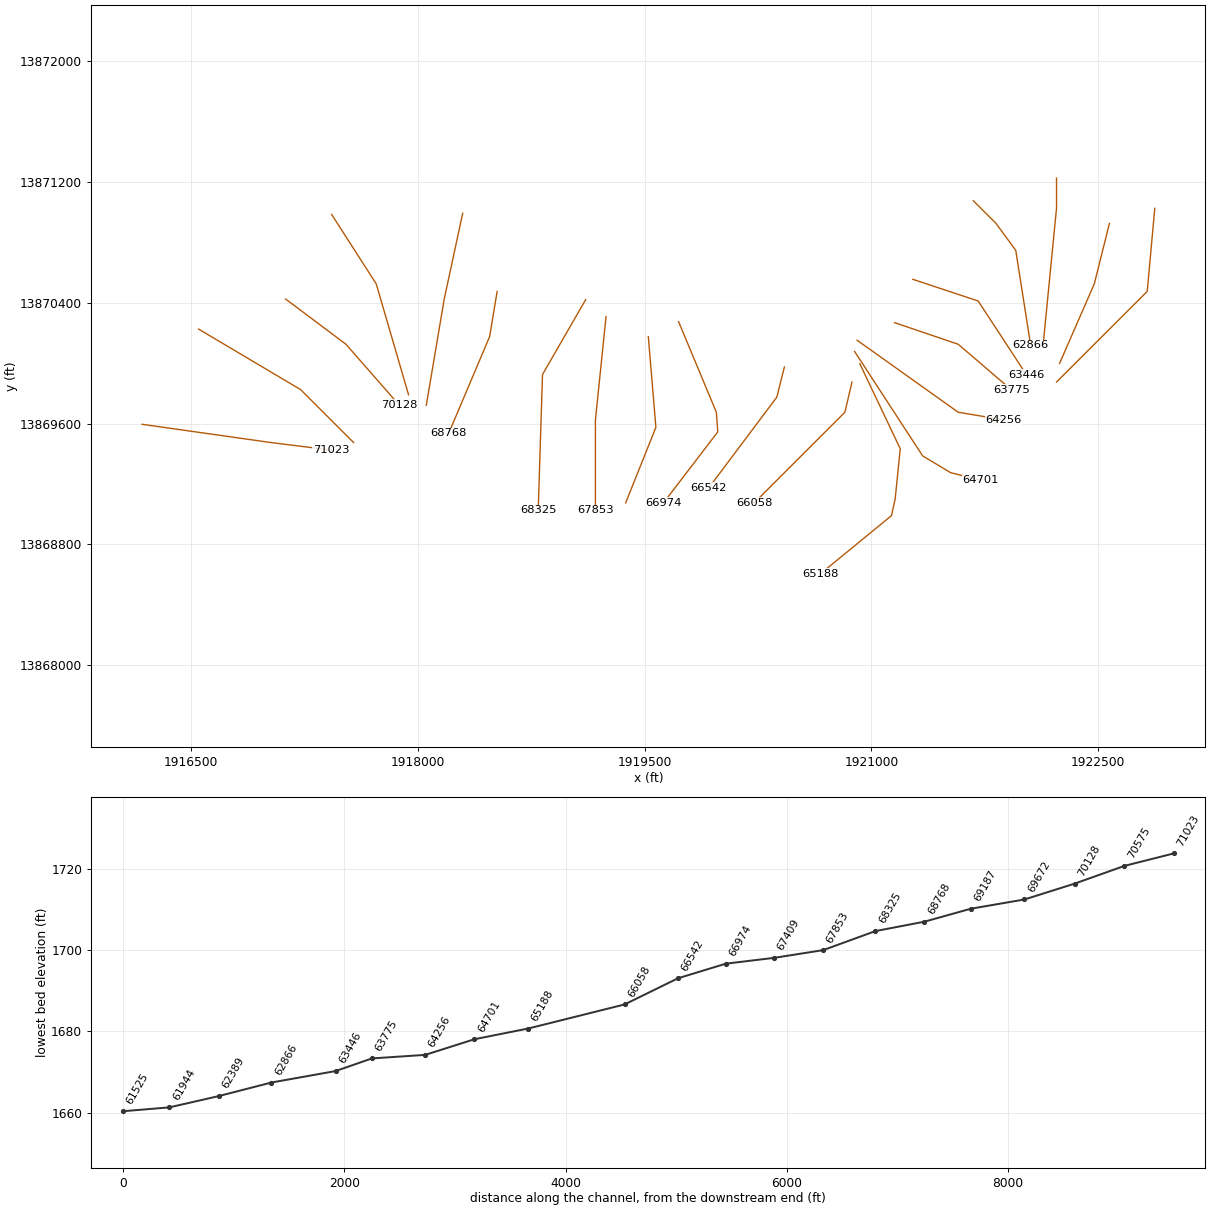
HEC-RAS study Verde Creek.prj: Verde Creek Base Level Engineering

--- Verde Creek.g01 (geometry) --- (continued)

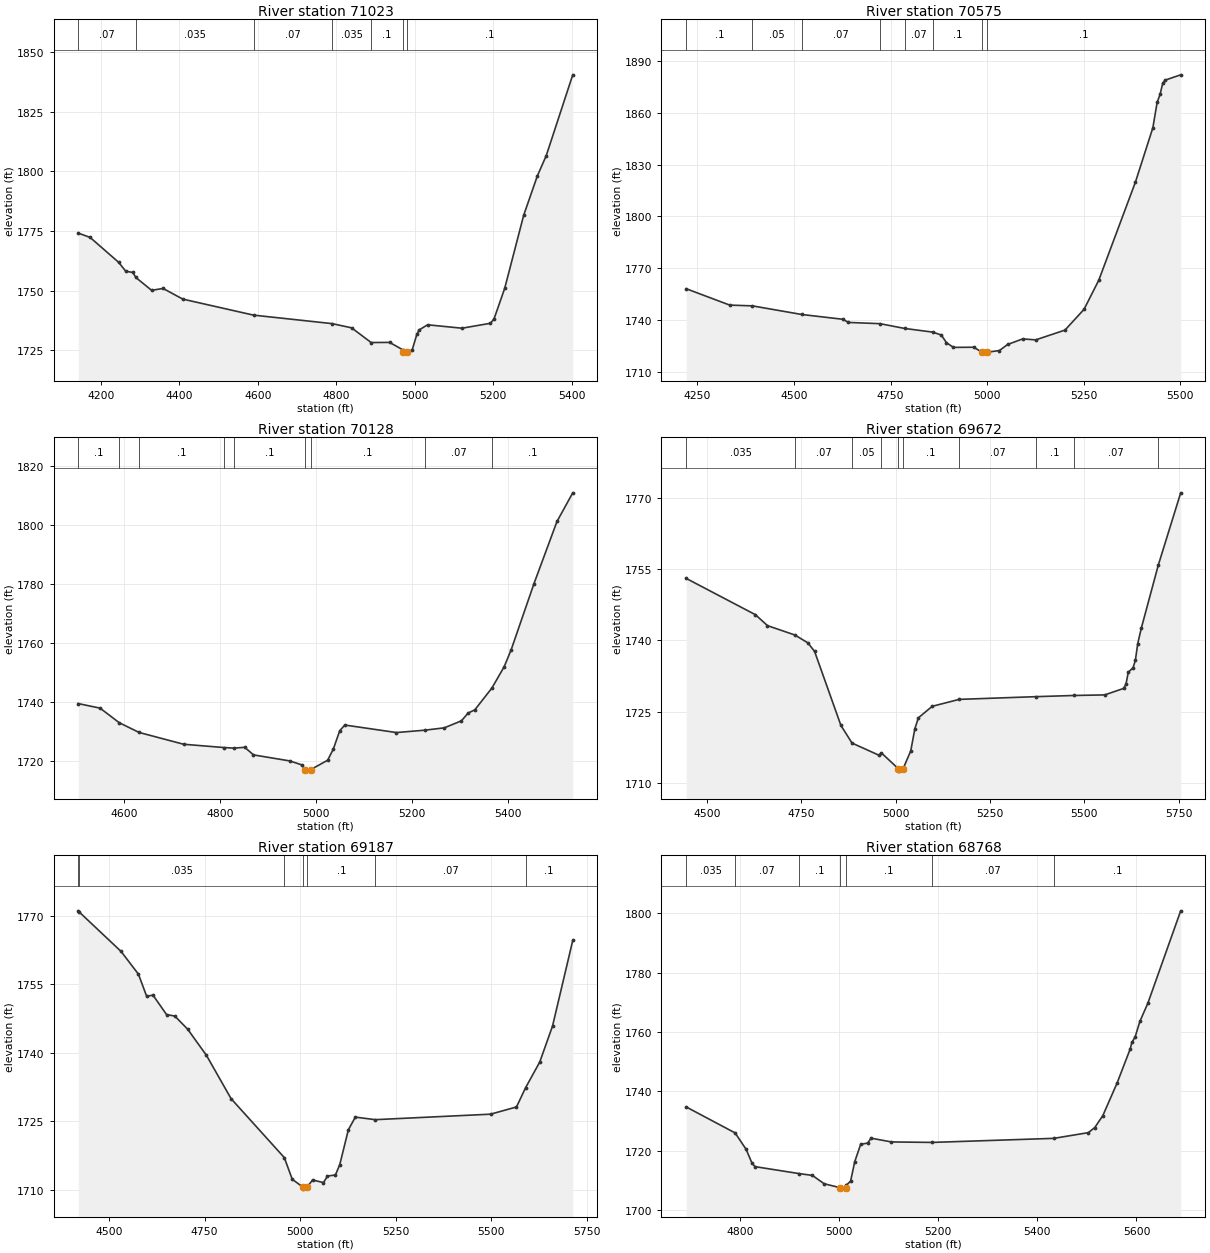
Type RM Length L Ch R = 1 ,71023   ,448,448,448
BEGIN DESCRIPTION:
Verde Creek 128.0
END DESCRIPTION:
XS GIS Cut Line= 3
      1916176.09     13869595.39        1917025.       13869475.
      1917424.98       13869425.
#Sta/Elev= 30
  4142.6 1774.12  4172.7 1772.33  4245.4 1761.92  4263.6 1758.17  4281.8 1757.64
  4289.3 1755.55  4329.6 1750.15  4358.8 1750.95    4409 1746.48  4589.3 1739.77
  4789.2 1736.22  4839.3 1734.45  4889.2 1728.29  4936.3 1728.34  4969.6 1725.27
  4969.8 1724.35  4970.3 1723.85  4981.5 1724.35  4993.8  1725.2  5005.9 1731.81
    5012 1733.61    5033 1735.72  5120.8 1734.29  5193.4 1736.36  5202.5  1738.2
  5229.7 1751.02    5278 1781.58  5312.9 1798.09  5335.5 1806.55  5403.1 1840.43
#Mann= 7 ,-1 , 0
  4142.6     .07       0  4289.3    .035       0  4589.3     .07       0
  4789.2    .035       0  4889.2      .1       0  4969.8     .05       0
  4981.5      .1       0
Bank Sta=4969.8,4981.5
XS Rating Curve= 0 ,0
Exp/Cntr=0.3,0.1

Type RM Length L Ch R = 1 ,70575   ,447,447,447
BEGIN DESCRIPTION:
Verde Creek 127.0
END DESCRIPTION:
XS GIS Cut Line= 3
      1916550.03     13870225.64        1917225.       13869825.
        1917575.       13869475.
#Sta/Elev= 30
  4220.8 1758.11  4333.4 1748.62  4392.3 1748.17  4519.9 1743.17  4626.5 1740.39
  4640.4 1738.57  4722.4 1737.85    4786 1735.09  4859.6 1732.93  4881.2 1731.24
  4894.5 1726.79  4912.6 1724.09  4964.9 1724.19  4986.8 1721.27  4987.3 1720.77
  4998.8 1721.27  5031.5 1722.27  5052.7 1725.79  5091.8 1729.02  5125.3 1728.45
  5201.2 1734.13  5250.5 1746.16  5288.7 1763.06  5383.7 1820.04  5428.7 1851.47
  5439.7 1866.14  5447.3 1870.79  5454.1 1877.13    5460 1879.03  5500.7 1882.14
#Mann= 8 ,-1 , 0
  4220.8      .1       0  4392.3     .05       0  4519.9     .07       0
  4722.4     .05       0    4786     .07       0  4859.6      .1       0
  4986.8     .05       0  4998.8      .1       0
Bank Sta=4986.8,4998.8
XS Rating Curve= 0 ,0
Exp/Cntr=0.3,0.1

Type RM Length L Ch R = 1 ,70128   ,456,456,456
BEGIN DESCRIPTION:
Verde Creek 126.0
END DESCRIPTION:
XS GIS Cut Line= 3
      1917124.97     13870425.03        1917525.       13870125.
      1917875.03     13869724.96
#Sta/Elev= 30
  4504.3 1739.32  4549.8 1737.78  4589.9 1732.82  4631.3 1729.53  4724.2 1725.53
  4807.9 1724.42  4828.6 1724.22  4851.7 1724.49  4869.8 1721.93  4945.5 1719.88
  4971.7 1718.49  4976.9 1716.92  4977.4 1716.42  4989.1 1716.92  5024.6 1720.12
  5036.6 1723.97  5049.8 1730.12  5060.4 1732.05  5168.1  1729.5  5227.1  1730.3
  5267.8 1731.09  5303.6 1733.47  5317.7 1736.12  5331.6  1737.2  5367.3 1744.61
  5392.9 1751.84  5407.3 1757.51  5455.1 1780.03    5503 1801.06  5535.9 1810.78
#Mann= 9 ,-1 , 0
  4504.3      .1       0  4589.9     .05       0  4631.3      .1       0
  4807.9     .05       0  4828.6      .1       0  4976.9     .05       0
  4989.1      .1       0  5227.1     .07       0  5367.3      .1       0
Bank Sta=4976.9,4989.1
XS Rating Curve= 0 ,0
Exp/Cntr=0.3,0.1

Type RM Length L Ch R = 1 ,69672   ,485,485,485
BEGIN DESCRIPTION:
Verde Creek 125.0
END DESCRIPTION:
XS GIS Cut Line= 3
      1917430.42     13870984.08        1917725.       13870525.
      1917939.01      13869790.4
#Sta/Elev= 30
  4444.6 1753.03    4628  1745.4    4660  1743.1  4732.6 1741.13    4767 1739.48
  4784.8 1737.69  4854.7  1722.1  4884.1  1718.4  4955.9 1715.83  4961.7 1716.35
    5007    1713  5007.5  1712.5  5019.4    1713  5039.7 1716.74  5050.7 1721.45
  5060.1 1723.72  5096.6 1726.13    5168 1727.59    5371 1728.16  5472.6 1728.41
  5553.8 1728.53  5603.8 1729.89  5610.1 1730.76  5616.3  1733.3  5628.8 1734.22
  5635.1 1735.81  5641.3  1739.3  5650.7 1742.52  5695.7 1755.79  5755.2 1771.03
#Mann= 10 ,-1 , 0
  4444.6    .035       0  4732.6     .07       0  4884.1     .05       0
  4961.7      .1       0    5007     .05       0  5019.4      .1       0
    5168     .07       0    5371      .1       0  5472.6     .07       0
  5695.7      .1       0
Bank Sta=5007,5019.4
XS Rating Curve= 0 ,0
Exp/Cntr=0.3,0.1

Type RM Length L Ch R = 1 ,69187   ,419,419,419
BEGIN DESCRIPTION:
Verde Creek 124.0
END DESCRIPTION:
XS GIS Cut Line= 3
      1918297.15      13870992.7        1918175.       13870425.
      1918056.36     13869721.63
#Sta/Elev= 30
  4419.6 1771.04  4421.5 1770.83  4531.7 1762.16  4577.1 1757.19  4598.6 1752.36
  4615.1 1752.62  4650.7 1748.36  4672.2 1748.05  4705.9 1745.17  4755.1 1739.45
  4819.5 1729.99  4958.8 1717.11  4979.6 1712.37  5006.5 1710.72    5007 1710.22
    5019 1710.72  5032.7 1712.22  5061.3 1711.65  5071.8 1713.08  5092.6 1713.31
    5104  1715.6  5126.4 1723.19  5144.7 1725.96  5196.6  1725.4  5498.7  1726.6
  5566.4 1728.18  5590.2 1732.38  5627.3 1738.01  5660.7 1745.86  5713.6 1764.56
#Mann= 7 ,-1 , 0
  4419.6     .07       0  4421.5    .035       0  4958.8      .1       0
  5006.5     .05       0    5019      .1       0  5196.6     .07       0
  5590.2      .1       0
Bank Sta=5006.5,5019
XS Rating Curve= 0 ,0
Exp/Cntr=0.3,0.1

Type RM Length L Ch R = 1 ,68768   ,443,443,443
BEGIN DESCRIPTION:
Verde Creek 123.0
END DESCRIPTION:
XS GIS Cut Line= 3
      1918524.99     13870474.96        1918475.       13870175.
      1918204.64     13869536.04
#Sta/Elev= 30
  4691.4 1734.72  4790.1 1725.97  4812.3 1720.44  4824.4 1715.69  4830.5  1714.6
  4919.9 1712.25  4946.1 1711.65  4969.7 1708.85  5001.5 1707.53    5002 1707.03
    5014 1707.53  5014.1 1708.29  5023.2 1709.73  5031.5 1716.29  5043.5 1722.13
  5057.6 1722.55  5064.4  1724.2  5105.6 1722.93  5187.9 1722.77  5433.3 1724.14
  5502.9 1726.06  5515.9 1727.78  5532.2 1731.81  5561.1 1742.84  5587.5  1754.3
  5590.8 1756.49  5597.3 1758.27  5606.9 1763.54  5622.9 1769.61  5689.3  1800.8
#Mann= 7 ,-1 , 0
  4691.4    .035       0  4790.1     .07       0  4919.9      .1       0
  5001.5     .05       0    5014      .1       0  5187.9     .07       0
  5433.3      .1       0
Bank Sta=5001.5,5014
XS Rating Curve= 0 ,0
Exp/Cntr=0.3,0.1

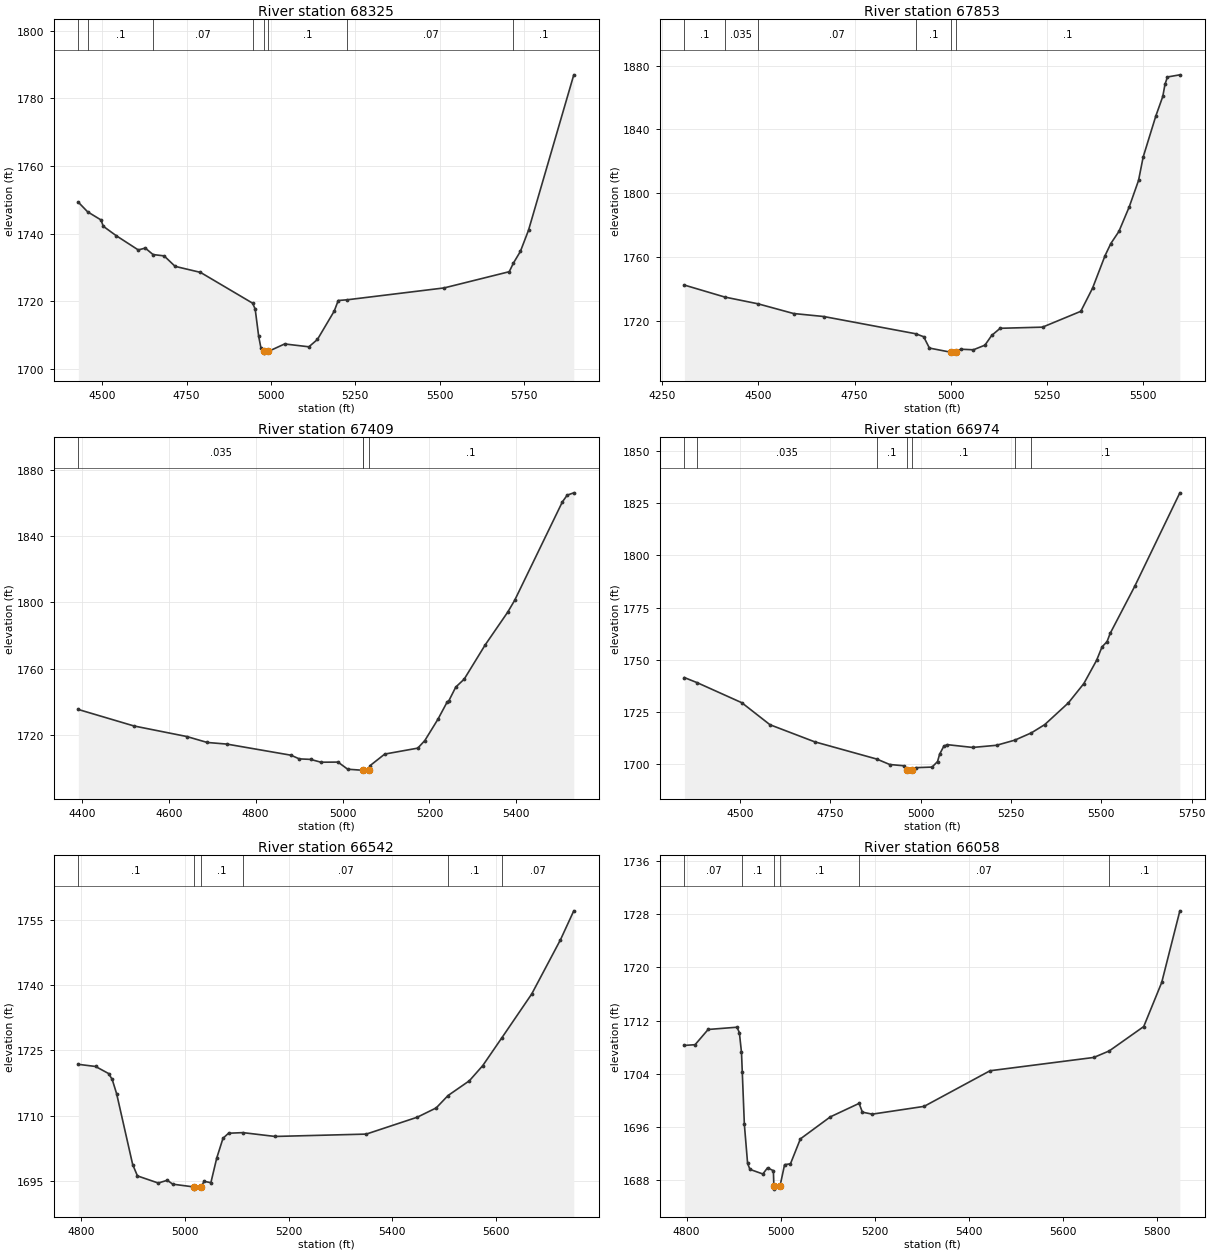
Type RM Length L Ch R = 1 ,68325   ,472,472,472
BEGIN DESCRIPTION:
Verde Creek 122.0
END DESCRIPTION:
XS GIS Cut Line= 3
      1919110.42     13870420.27        1918825.       13869925.
      1918796.55     13869027.48
#Sta/Elev= 30
  4428.6 1749.29  4456.3 1746.44    4496 1744.04  4502.5 1742.19  4540.6 1739.43
  4606.4 1735.19  4627.2 1735.74  4650.1 1733.83  4683.1 1733.43  4715.7 1730.34
  4790.9 1728.56  4945.6 1719.46  4953.2 1717.72  4963.6 1709.66  4970.4 1706.15
  4979.5 1705.21    4980 1704.71  4992.2 1705.21  5040.5 1707.42  5112.5 1706.58
  5137.8 1708.74  5187.6 1717.12  5199.6 1720.25  5226.6 1720.47  5513.6 1723.97
  5706.8 1728.76  5719.3 1731.34  5739.8 1734.75  5763.9    1741  5898.2 1786.91
#Mann= 8 ,-1 , 0
  4428.6     .07       0  4456.3      .1       0  4650.1     .07       0
  4945.6      .1       0  4979.5     .05       0  4992.2      .1       0
  5226.6     .07       0  5719.3      .1       0
Bank Sta=4979.5,4992.2
XS Rating Curve= 0 ,0
Exp/Cntr=0.3,0.1

Type RM Length L Ch R = 1 ,67853   ,444,444,444
BEGIN DESCRIPTION:
Verde Creek 121.0
END DESCRIPTION:
XS GIS Cut Line= 3
      1919245.33     13870308.25        1919175.       13869625.
        1919175.     13869024.96
#Sta/Elev= 30
  4308.1 1742.61    4413 1735.12  4499.2 1730.89  4591.6 1724.81  4669.8 1722.94
  4909.2 1712.13  4929.6 1710.28  4944.5 1703.19  5001.3 1700.52  5001.8 1700.02
  5014.2 1700.52  5025.7 1702.48  5058.7 1702.11  5088.7 1705.01  5106.3  1711.1
  5128.2 1715.56  5238.3 1716.28  5337.7 1726.19  5368.2 1740.66  5400.7 1761.02
  5415.7 1768.61  5436.7 1776.18  5463.7 1791.69  5487.7 1808.11  5499.7 1822.75
  5532.7 1848.51  5550.7 1860.68  5556.3 1868.15  5562.7 1872.84    5595 1874.19
#Mann= 6 ,-1 , 0
  4308.1      .1       0    4413    .035       0  4499.2     .07       0
  4909.2      .1       0  5001.3     .05       0  5014.2      .1       0
Bank Sta=5001.3,5014.2
XS Rating Curve= 0 ,0
Exp/Cntr=0.3,0.1

Type RM Length L Ch R = 1 ,67409   ,435,435,435
BEGIN DESCRIPTION:
Verde Creek 120.0
END DESCRIPTION:
XS GIS Cut Line= 3
        1919525.     13870174.95        1919575.       13869575.
      1919374.98     13869074.95
#Sta/Elev= 30
  4391.8  1735.3    4520 1725.35  4641.7 1718.98  4688.5 1715.41  4733.7 1714.43
  4881.4 1707.72  4900.5 1705.51  4926.4  1705.2  4950.4  1703.5  4989.6 1703.57
  5011.9 1699.28  5047.2 1698.62  5047.4 1698.62  5047.9 1698.12  5060.3 1698.62
  5063.6 1701.47  5097.2  1708.4  5173.3 1711.99  5189.5 1716.57  5219.5 1729.34
  5241.3    1740  5244.5 1740.41  5260.7  1748.8  5280.1  1753.6  5328.5 1774.27
  5380.2 1793.96  5396.4 1801.18  5506.2 1860.53  5517.2 1864.56  5532.4 1865.96
#Mann= 4 ,-1 , 0
  4391.8    .035       0  5047.2      .1       0  5047.4    .035       0
  5060.3      .1       0
Bank Sta=5047.4,5060.3
XS Rating Curve= 0 ,0
Exp/Cntr=0.3,0.1

Type RM Length L Ch R = 1 ,66974   ,432,432,432
BEGIN DESCRIPTION:
Verde Creek 119.0
END DESCRIPTION:
XS GIS Cut Line= 4
      1919724.99     13870275.03        1919975.       13869675.
      1919984.25     13869544.96      1919625.03     13869075.03
#Sta/Elev= 30
  4345.5 1741.48  4381.3 1739.01  4504.5 1729.44  4582.5  1718.9    4706 1710.74
  4878.2 1702.47    4914 1699.86    4953 1699.26  4962.4 1697.19  4962.9 1696.69
  4975.4 1697.19  4985.5 1698.34  5031.4 1698.63  5046.4 1701.28  5052.4 1704.87
  5064.1 1708.71  5073.5 1709.36  5143.7 1708.03  5209.7 1709.06  5260.4 1711.53
  5306.5 1715.03  5343.3 1718.97  5408.8 1729.38  5451.6 1738.63  5486.8 1749.73
  5501.9 1756.18  5515.8 1758.69  5524.3 1762.59  5592.5  1785.2  5717.4 1829.93
#Mann= 7 ,-1 , 0
  4345.5      .1       0  4381.3    .035       0  4878.2      .1       0
  4962.4     .05       0  4975.4      .1       0  5260.4     .07       0
  5306.5      .1       0
Bank Sta=4962.4,4975.4
XS Rating Curve= 0 ,0
Exp/Cntr=0.3,0.1

Type RM Length L Ch R = 1 ,66542   ,484,484,484
BEGIN DESCRIPTION:
Verde Creek 118.0
END DESCRIPTION:
XS GIS Cut Line= 3
      1920424.99     13869974.97        1920375.       13869775.
      1919925.02     13869175.02
#Sta/Elev= 30
  4793.9 1721.79  4827.1  1721.3  4852.4 1719.67  4859.3 1718.31  4867.8 1715.05
  4898.8 1698.75    4908 1696.14  4948.2  1694.5  4965.6 1695.14  4976.1 1694.24
  5017.2  1693.6  5017.7  1693.1  5030.4  1693.6  5036.7 1694.89  5049.7 1694.58
    5061 1700.24  5073.1 1704.79  5083.8 1705.95  5111.5 1706.09  5173.5 1705.21
  5349.5 1705.75  5448.1 1709.64  5484.5 1711.77  5507.4 1714.62  5548.5 1718.01
  5574.3 1721.49  5611.3 1727.91  5668.8 1737.96  5724.3 1750.43    5750 1757.08
#Mann= 6 ,-1 , 0
  4793.9      .1       0  5017.2     .05       0  5030.4      .1       0
  5111.5     .07       0  5507.4      .1       0  5611.3     .07       0
Bank Sta=5017.2,5030.4
XS Rating Curve= 0 ,0
Exp/Cntr=0.3,0.1

Type RM Length L Ch R = 1 ,66058   ,870,870,870
BEGIN DESCRIPTION:
Verde Creek 117.0
END DESCRIPTION:
XS GIS Cut Line= 3
      1920871.96     13869874.36        1920825.       13869675.
      1920225.03     13869075.03
#Sta/Elev= 30
  4795.5 1708.26  4818.2 1708.37    4846 1710.66  4907.4    1711  4912.4 1710.17
  4916.9  1707.2  4918.6 1704.21    4923 1696.37  4929.9  1690.5  4934.9 1689.61
  4962.3 1688.92  4972.3 1689.85  4984.7 1689.41  4985.7 1687.14  4986.2 1686.64
  4998.9 1687.14  5008.5 1690.32    5021 1690.45  5042.1  1694.2  5105.7 1697.51
  5166.9 1699.54  5173.9 1698.22  5194.8 1697.92  5305.1 1699.09  5445.3 1704.45
  5665.8 1706.45  5698.6 1707.43    5772  1711.1  5810.2 1717.73  5848.8 1728.51
#Mann= 6 ,-1 , 0
  4795.5     .07       0  4918.6      .1       0  4985.7     .05       0
  4998.9      .1       0  5166.9     .07       0  5698.6      .1       0
Bank Sta=4985.7,4998.9
XS Rating Curve= 0 ,0
Exp/Cntr=0.3,0.1

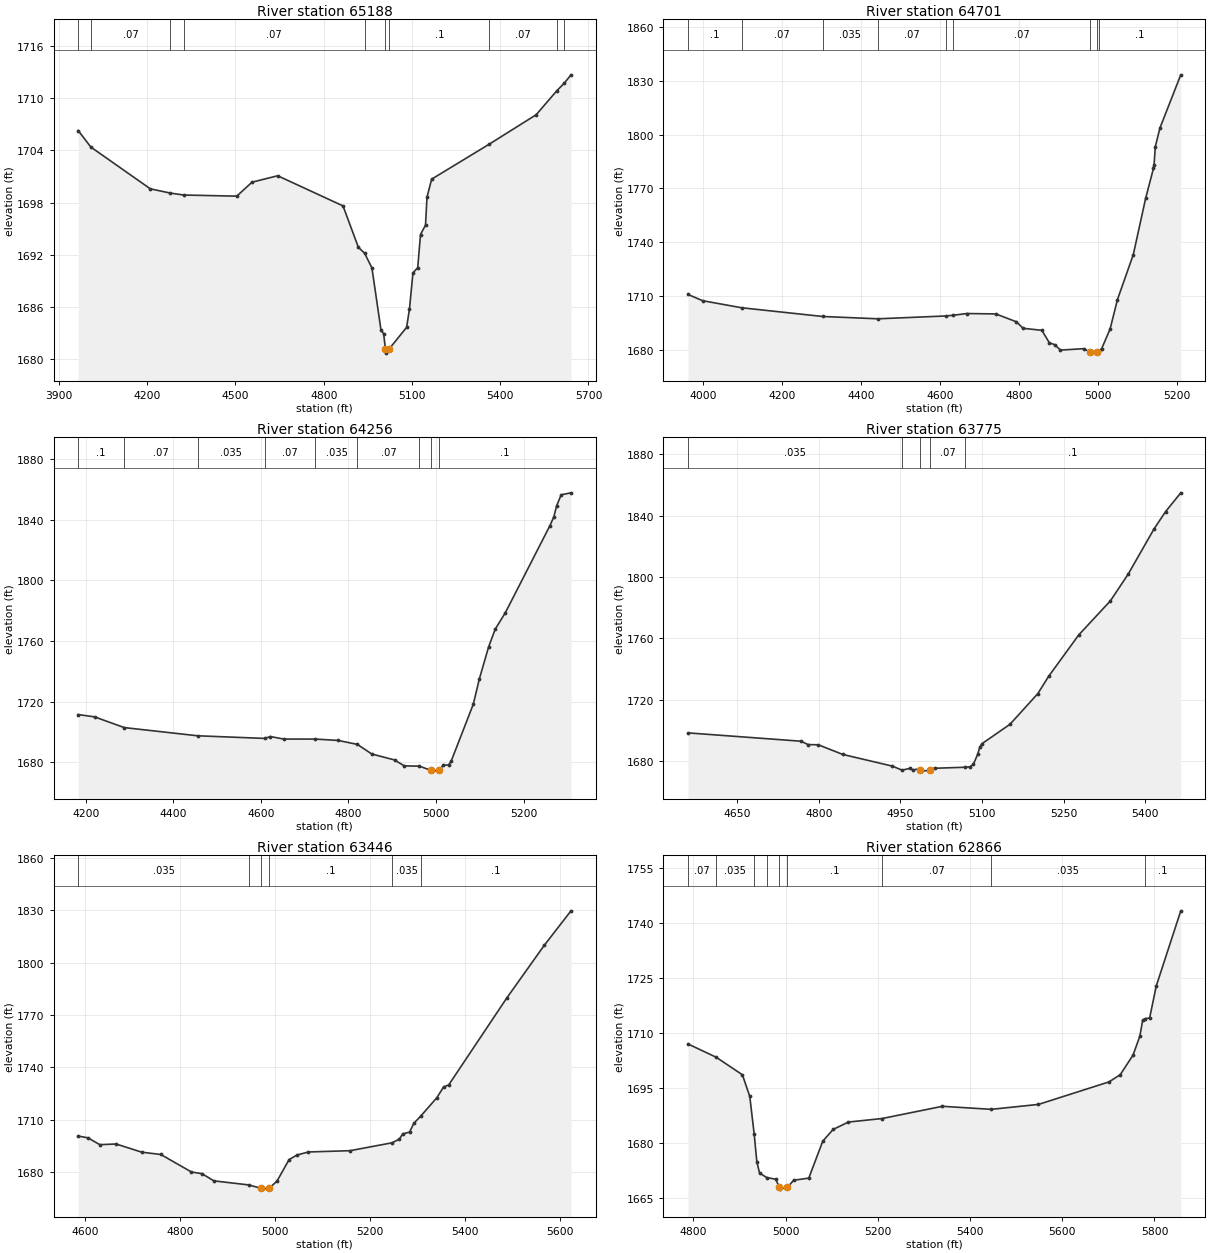
Type RM Length L Ch R = 1 ,65188   ,487,487,487
BEGIN DESCRIPTION:
Verde Creek 116.0
END DESCRIPTION:
XS GIS Cut Line= 5
      1920924.11     13869995.78      1921191.24     13869433.67
      1921157.87     13869101.22      1921133.45     13868990.95
      1920664.93     13868606.95
#Sta/Elev= 30
  3965.4 1706.26  4008.5 1704.36  4210.7 1699.57  4277.5 1699.09  4323.6 1698.86
  4504.4 1698.73  4556.1 1700.33  4643.5 1701.07  4865.6 1697.61  4917.8 1692.86
  4939.1 1692.18  4963.9 1690.49  4994.6 1683.39  5003.8 1682.94  5009.6 1681.22
  5010.1 1680.72  5022.9 1681.22  5081.7 1683.67  5091.5 1685.77  5103.3 1689.92
  5119.6 1690.53    5129 1694.33    5146  1695.4  5151.1 1698.61  5166.9 1700.68
  5362.9  1704.7  5522.1 1708.07  5592.8 1710.84  5618.4 1711.72  5640.6 1712.65
#Mann= 10 ,-1 , 0
  3965.4      .1       0  4008.5     .07       0  4277.5    .035       0
  4323.6     .07       0  4939.1      .1       0  5009.6     .05       0
  5022.9      .1       0  5362.9     .07       0  5592.8      .1       0
  5618.4     .07       0
Bank Sta=5009.6,5022.9
XS Rating Curve= 0 ,0
Exp/Cntr=0.3,0.1

Type RM Length L Ch R = 1 ,64701   ,445,445,445
BEGIN DESCRIPTION:
Verde Creek 115.0
END DESCRIPTION:
XS GIS Cut Line= 4
      1920889.06     13870077.92      1921339.49     13869386.31
        1921525.       13869275.      1921725.04     13869224.99
#Sta/Elev= 30
  3961.9  1710.8  3999.3 1707.31  4098.1 1703.37  4303.4 1698.51  4443.2 1697.22
  4614.5  1698.8    4633 1699.18    4668 1700.16  4741.4 1699.94  4793.1  1695.6
  4810.6 1691.92    4858  1690.8    4877 1683.84    4891 1682.75    4905 1679.76
  4964.5 1680.56  4980.4 1678.57  4980.9 1678.07  4997.5 1678.57  5003.9 1679.31
  5009.6 1680.64  5030.9 1691.57  5049.4  1707.9  5089.6 1733.05  5120.9 1764.49
  5140.6  1781.1  5142.2 1783.17  5145.3 1793.24  5157.1 1803.71  5209.8 1833.33
#Mann= 9 ,-1 , 0
  3961.9      .1       0  4098.1     .07       0  4303.4    .035       0
  4443.2     .07       0  4614.5    .035       0    4633     .07       0
  4980.4     .05       0  4997.5     .07       0  5003.9      .1       0
Bank Sta=4980.4,4997.5
XS Rating Curve= 0 ,0
Exp/Cntr=0.3,0.1

Type RM Length L Ch R = 1 ,64256   ,481,481,481
BEGIN DESCRIPTION:
Verde Creek 114.0
END DESCRIPTION:
XS GIS Cut Line= 3
      1920906.01     13870151.71        1921575.       13869675.
      1921875.01       13869625.
#Sta/Elev= 30
  4182.8 1711.49  4220.2 1709.98    4288 1702.91  4455.5 1697.51    4609 1695.77
  4621.7 1697.01  4652.3 1695.35  4724.8 1695.34  4776.4 1694.45  4820.6 1691.82
  4853.4 1685.49  4905.4 1681.58  4927.5 1677.68  4961.8 1677.51  4988.9 1674.72
  4989.4 1674.22  5006.1 1674.72  5016.9 1678.04  5029.1 1678.34  5035.1 1681.09
  5085.3 1718.37    5099 1734.94  5120.3 1756.15  5135.5 1767.89  5158.3 1778.53
  5260.2 1835.96  5269.3 1841.84  5275.4 1848.95    5286 1856.32  5308.4  1857.6
#Mann= 9 ,-1 , 0
  4182.8      .1       0    4288     .07       0  4455.5    .035       0
    4609     .07       0  4724.8    .035       0  4820.6     .07       0
  4961.8      .1       0  4988.9     .05       0  5006.1      .1       0
Bank Sta=4988.9,5006.1
XS Rating Curve= 0 ,0
Exp/Cntr=0.3,0.1

Type RM Length L Ch R = 1 ,63775   ,329,329,329
BEGIN DESCRIPTION:
Verde Creek 113.0
END DESCRIPTION:
XS GIS Cut Line= 3
      1921153.46     13870268.41        1921575.       13870125.
      1921924.97     13869825.03
#Sta/Elev= 30
  4559.3 1698.29  4767.4 1692.85  4780.1 1690.67  4799.1 1690.51    4844 1684.23
  4935.3 1676.61  4953.1 1673.96    4967 1675.14  4973.4 1674.13    4986    1675
  4986.9 1673.85  4987.4 1673.35  5004.1 1673.85  5004.6 1674.82  5013.4 1675.23
  5068.9 1675.88    5078 1676.15  5084.2 1677.82  5092.1 1684.38    5096 1688.99
    5100 1691.26  5151.4 1703.87  5202.7 1723.91  5222.5 1735.15  5277.8 1762.13
  5336.1 1784.39  5368.7 1801.75  5416.1 1831.15  5437.5 1842.56  5465.5 1854.83
#Mann= 5 ,-1 , 0
  4559.3    .035       0  4953.1     .07       0  4986.9     .05       0
  5004.1     .07       0  5068.9      .1       0
Bank Sta=4986.9,5004.1
XS Rating Curve= 0 ,0
Exp/Cntr=0.3,0.1

Type RM Length L Ch R = 1 ,63446   ,580,580,580
BEGIN DESCRIPTION:
Verde Creek 112.0
END DESCRIPTION:
XS GIS Cut Line= 3
      1921274.32     13870555.03      1921706.66     13870411.54
      1922025.03     13869924.96
#Sta/Elev= 30
  4585.9 1700.64  4606.4 1699.61  4631.4 1695.69  4665.7 1696.08  4719.9 1691.38
  4759.8 1690.06  4824.2 1680.05  4846.3 1679.07  4871.6 1674.95  4945.1 1672.63
  4970.4 1670.73  4970.9 1670.23  4987.6 1670.73  5004.3 1674.82  5029.6 1687.13
  5046.6 1689.78  5070.3 1691.51    5158 1692.24  5246.2 1696.76  5261.7 1698.85
  5268.8 1701.87  5283.2 1702.88  5292.2 1707.93  5307.6 1712.32  5340.5 1722.56
  5354.9 1728.76  5365.6 1729.92  5487.5 1779.59  5566.4 1809.77  5622.9  1829.6
#Mann= 6 ,-1 , 0
  4585.9    .035       0  4945.1      .1       0  4970.4     .05       0
  4987.6      .1       0  5246.2    .035       0  5307.6      .1       0
Bank Sta=4970.4,4987.6
XS Rating Curve= 0 ,0
Exp/Cntr=0.3,0.1

Type RM Length L Ch R = 1 ,62866   ,477,477,477
BEGIN DESCRIPTION:
Verde Creek 111.0
END DESCRIPTION:
XS GIS Cut Line= 4
      1921674.97     13871075.03        1921825.       13870925.
      1921955.52     13870746.47      1922053.94     13870118.57
#Sta/Elev= 30
  4788.1 1707.04  4849.5  1703.4  4906.2 1698.62  4922.2 1692.71  4931.7 1682.52
  4937.5 1674.93  4943.4 1671.79  4959.2 1670.56  4978.3 1670.12  4986.6 1667.91
  4987.1 1667.41  5003.9 1667.91  5017.3 1669.83  5050.2 1670.42  5080.5 1680.49
  5102.8 1683.69  5136.2 1685.72  5209.2 1686.68  5340.1 1690.02  5445.9 1689.19
  5548.3 1690.53  5701.4 1696.68  5725.7 1698.64  5753.5    1704  5768.3 1709.18
  5774.3 1713.48  5779.8 1713.91  5789.5 1714.15  5803.9 1722.88    5857 1743.37
#Mann= 9 ,-1 , 0
  4788.1     .07       0  4849.5    .035       0  4931.7     .07       0
  4959.2      .1       0  4986.6     .05       0  5003.9      .1       0
  5209.2     .07       0  5445.9    .035       0  5779.8      .1       0
Bank Sta=4986.6,5003.9
XS Rating Curve= 0 ,0
Exp/Cntr=0.3,0.1

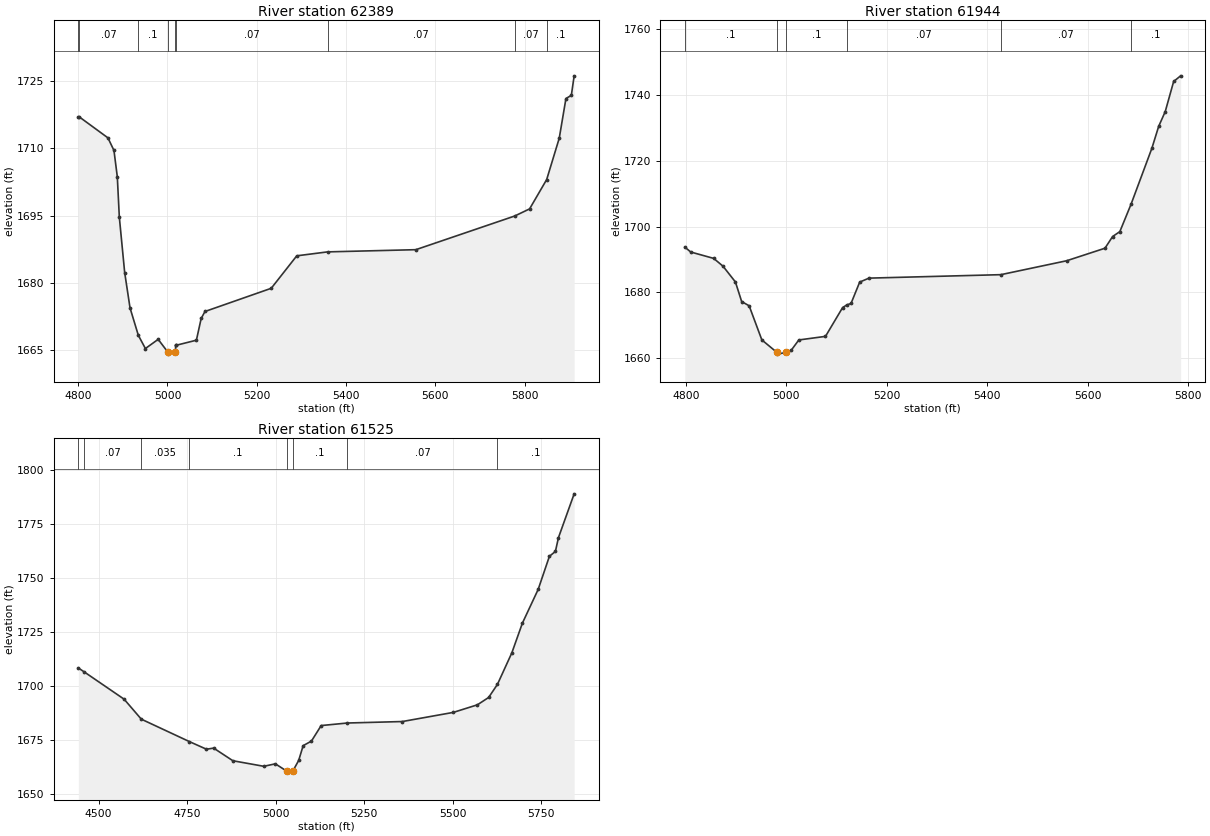
Type RM Length L Ch R = 1 ,62389   ,445,445,445
BEGIN DESCRIPTION:
Verde Creek 110.0
END DESCRIPTION:
XS GIS Cut Line= 3
        1922225.     13871225.03        1922225.       13871025.
      1922136.29     13870118.96
#Sta/Elev= 30
  4800.4    1717  4802.8 1717.01  4866.7 1712.35  4880.2 1709.53  4887.7 1703.65
  4892.2 1694.65  4904.2 1682.27  4916.2 1674.37  4934.8 1668.25  4950.6 1665.31
  4979.2 1667.36  5000.5 1664.56    5001 1664.06    5018 1664.56  5018.3 1666.05
  5019.7 1666.04  5064.8 1667.17  5075.5 1672.02    5084 1673.58  5232.4 1678.76
  5289.6 1686.01  5358.6 1686.89  5556.2 1687.38  5777.7  1694.9    5811 1696.49
  5849.3 1703.05  5877.4 1712.27  5892.4 1721.13  5904.5 1721.84  5910.8  1726.2
#Mann= 9 ,-1 , 0
  4800.4     .07       0  4802.8     .07       0  4934.8      .1       0
  5000.5     .05       0    5018      .1       0  5019.7     .07       0
  5358.6     .07       0  5777.7     .07       0  5849.3      .1       0
Bank Sta=5000.5,5018
XS Rating Curve= 0 ,0
Exp/Cntr=0.3,0.1

Type RM Length L Ch R = 1 ,61944   ,419,419,419
BEGIN DESCRIPTION:
Verde Creek 109.0
END DESCRIPTION:
XS GIS Cut Line= 4
      1922575.01     13870925.02        1922525.       13870725.
        1922475.       13870525.      1922245.24     13869998.15
#Sta/Elev= 30
  4798.2 1693.79    4810 1692.29  4855.7 1690.35  4874.3 1687.98    4899 1683.19
  4911.4 1677.25  4926.3 1675.96  4951.6  1665.6  4981.8 1661.79  4982.3 1661.29
  4999.4 1661.79  5010.3 1662.51  5025.2 1665.59  5078.3 1666.68  5112.4 1675.43
  5120.9 1676.24  5129.1 1676.66  5146.4 1683.16  5164.9 1684.36  5427.4 1685.41
  5558.3 1689.63  5634.7 1693.44  5649.9 1696.99  5664.3 1698.48  5686.7 1706.83
  5728.1 1723.79  5741.6 1730.43  5754.7 1734.93  5771.4 1744.05  5785.3 1745.77
#Mann= 6 ,-1 , 0
  4798.2      .1       0  4981.8     .05       0  4999.4      .1       0
  5120.9     .07       0  5427.4     .07       0  5686.7      .1       0
Bank Sta=4981.8,4999.4
XS Rating Curve= 0 ,0
Exp/Cntr=0.3,0.1

Type RM Length L Ch R = 1 ,61525   ,490,490,490
BEGIN DESCRIPTION:
Verde Creek 108.0
END DESCRIPTION:
XS GIS Cut Line= 3
        1922875.     13871025.01        1922825.       13870475.
        1922225.       13869875.
#Sta/Elev= 30
  4442.9 1708.55  4459.6 1706.71  4572.2  1694.1  4620.8 1684.85  4756.8 1674.46
  4804.9 1670.94  4825.2 1671.46  4879.5 1665.61  4966.8 1663.04  4999.6 1664.18
  5031.3 1660.84  5031.8 1660.34  5048.9 1660.84  5065.4 1665.74  5078.1 1672.59
  5101.5 1674.71    5129 1681.89    5203 1683.07  5358.1 1683.75  5502.5 1687.99
  5570.3 1691.49  5602.1 1694.89  5626.9 1700.93  5667.7 1715.56  5697.5  1729.3
  5742.1 1744.92  5773.8 1760.23  5790.7 1762.46  5799.4 1768.88  5843.7 1789.13
#Mann= 8 ,-1 , 0
  4442.9    .035       0  4459.6     .07       0  4620.8    .035       0
  4756.8      .1       0  5031.3     .05       0  5048.9      .1       0
    5203     .07       0  5626.9      .1       0
Bank Sta=5031.3,5048.9
XS Rating Curve= 0 ,0
Exp/Cntr=0.3,0.1