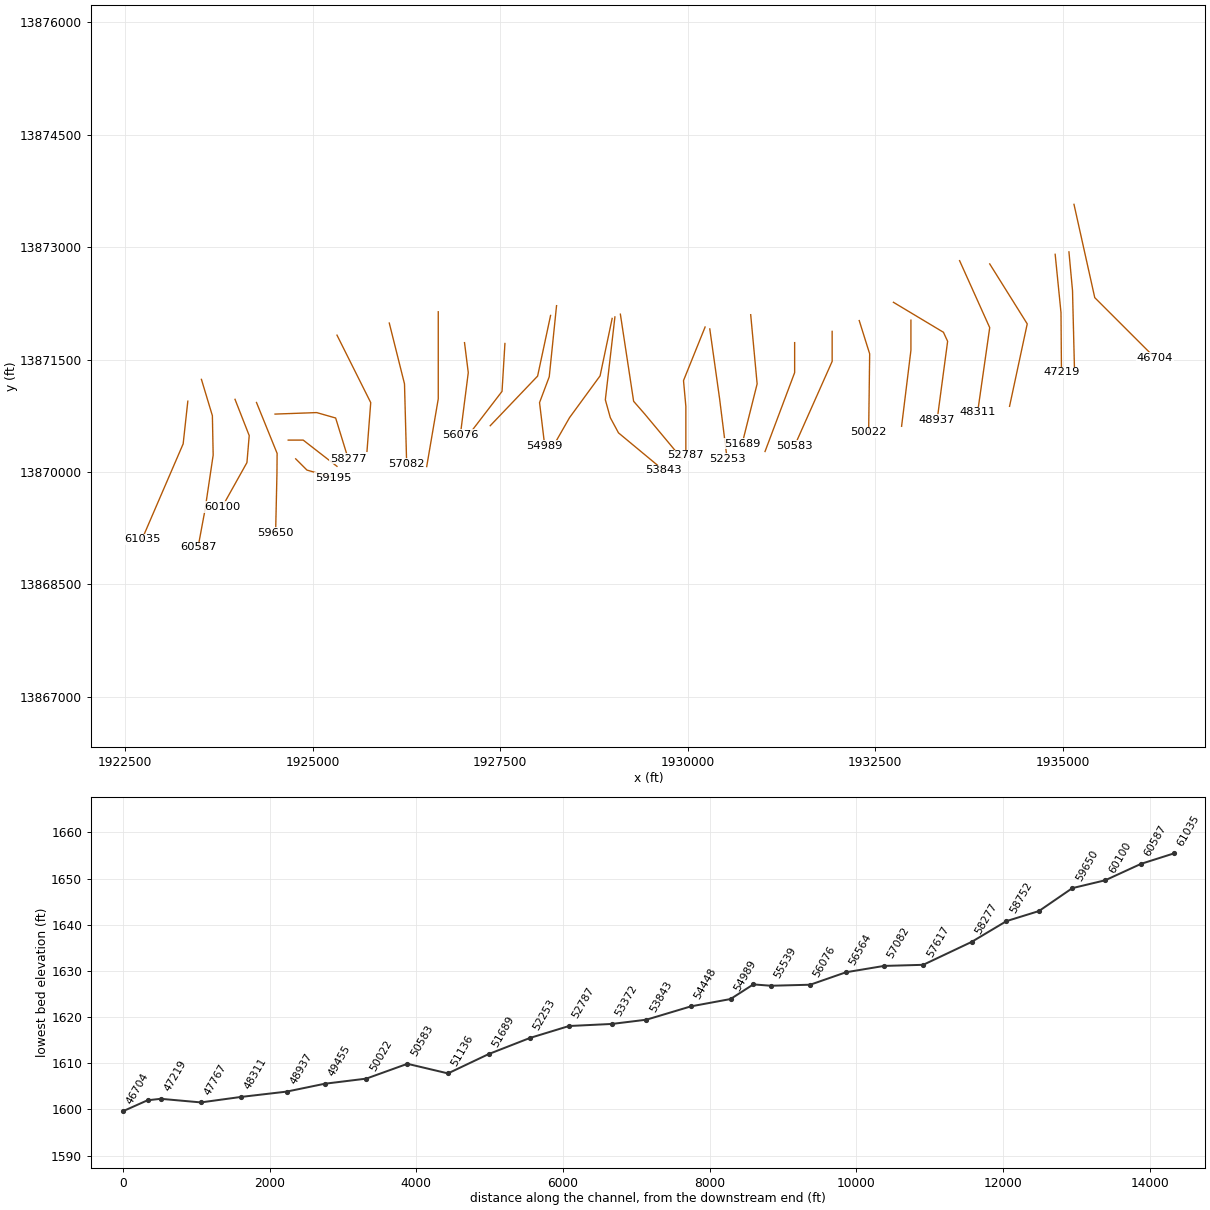
HEC-RAS study Verde Creek.prj: Verde Creek Base Level Engineering

--- Verde Creek.g01 (geometry) --- (continued)

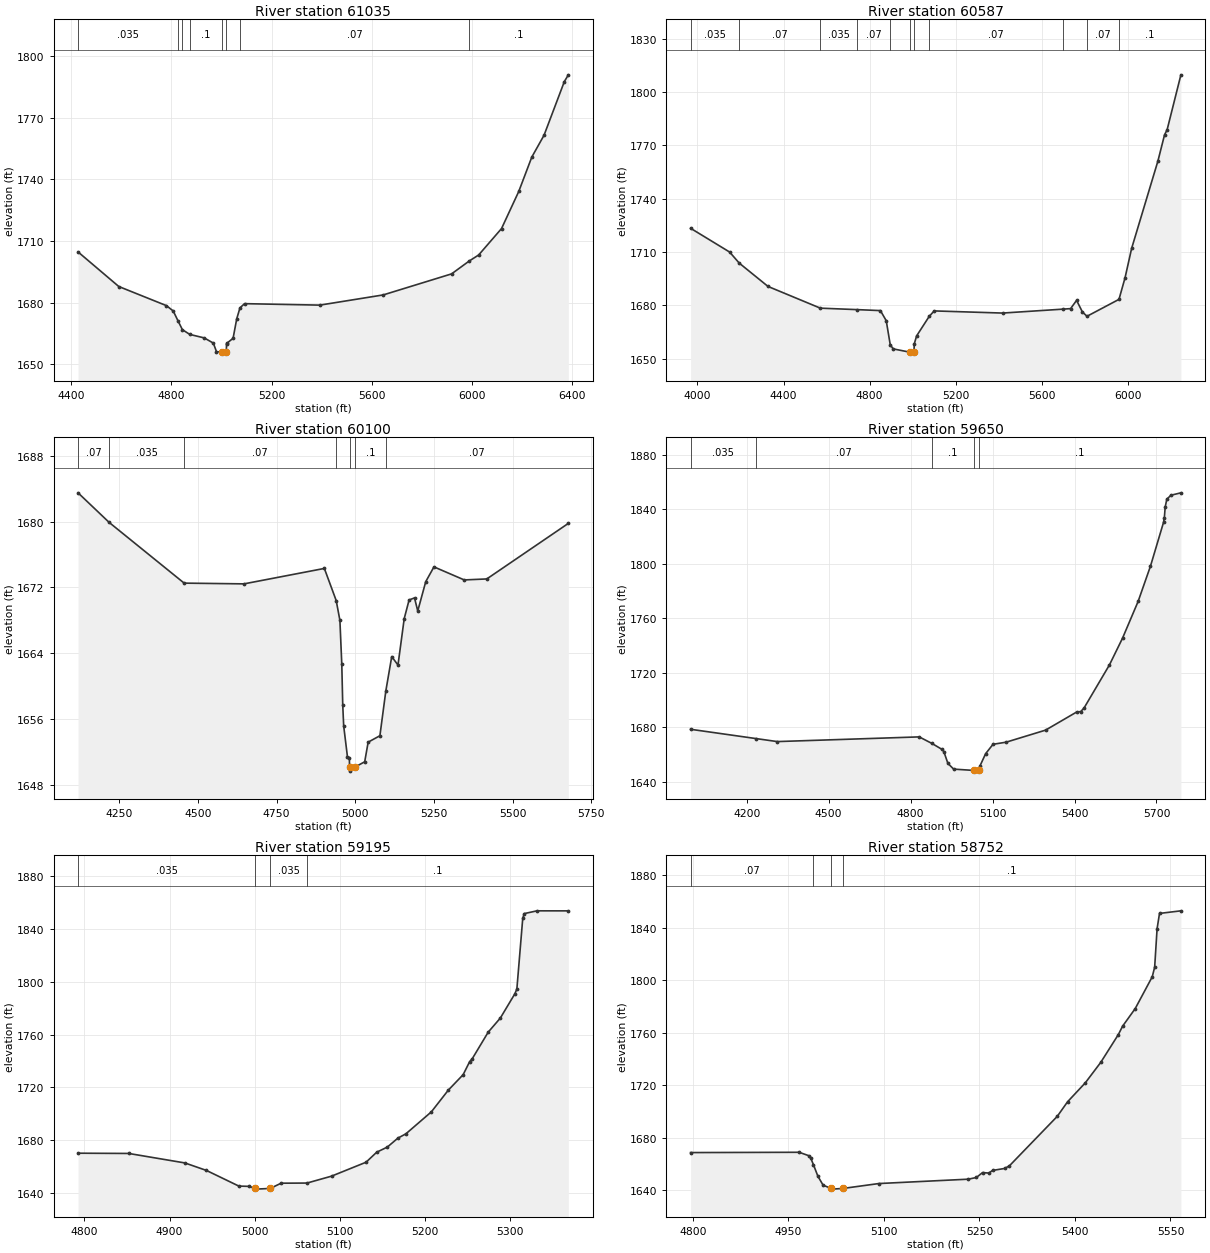
Type RM Length L Ch R = 1 ,61035   ,448,448,448
BEGIN DESCRIPTION:
Verde Creek 107.0
END DESCRIPTION:
XS GIS Cut Line= 3
      1923337.09     13870943.91        1923275.       13870375.
       1922727.1     13869103.19
#Sta/Elev= 30
  4427.8  1704.7  4590.4 1687.87  4780.6 1678.56  4807.7 1675.95  4827.7 1670.91
  4844.4 1666.84  4873.8 1664.55  4931.4 1662.85  4967.7 1660.33  4980.4 1656.15
  5001.9 1655.94  5002.4 1655.44  5019.5 1655.94  5020.5 1659.81  5022.4 1660.31
  5046.6 1662.65  5061.2 1672.16  5074.1 1677.48  5092.4 1679.52  5392.9 1678.81
  5645.7 1683.77  5918.8 1694.02  5988.9 1700.26  6026.9 1703.22  6118.1 1716.07
  6186.9 1734.15  6238.9 1750.86  6287.9 1761.53  6368.8 1787.62  6384.9 1790.92
#Mann= 8 ,-1 , 0
  4427.8    .035       0  4827.7      .1       0  4844.4     .07       0
  4873.8      .1       0  5001.9     .05       0  5019.5      .1       0
  5074.1     .07       0  5988.9      .1       0
Bank Sta=5001.9,5019.5
XS Rating Curve= 0 ,0
Exp/Cntr=0.3,0.1

Type RM Length L Ch R = 1 ,60587   ,487,487,487
BEGIN DESCRIPTION:
Verde Creek 106.0
END DESCRIPTION:
XS GIS Cut Line= 5
      1923518.44     13871234.96      1923664.47     13870750.39
        1923675.       13870225.      1923565.25     13869488.84
      1923473.07     13868994.14
#Sta/Elev= 30
    3968 1723.42  4149.4 1710.05  4194.2 1703.81    4328 1690.69  4571.2 1678.48
  4742.5 1677.65  4850.3 1677.11  4877.4 1671.43  4896.2 1657.77  4910.3 1655.55
  4988.6 1653.68  4989.1 1653.18  5006.2 1653.68  5007.8 1658.41  5018.6 1662.86
  5077.4  1673.9  5100.5 1676.93  5418.1 1675.72  5696.8 1677.91  5734.4 1678.22
  5762.2 1682.87  5789.3 1676.34  5810.6 1673.91  5959.3 1683.43  5987.6 1695.63
  6018.1 1712.11  6140.2 1761.23  6171.2 1776.05  6182.9 1778.77  6247.1 1809.75
#Mann= 11 ,-1 , 0
    3968    .035       0  4194.2     .07       0  4571.2    .035       0
  4742.5     .07       0  4896.2      .1       0  4988.6     .05       0
  5006.2      .1       0  5077.4     .07       0  5696.8      .1       0
  5810.6     .07       0  5959.3      .1       0
Bank Sta=4988.6,5006.2
XS Rating Curve= 0 ,0
Exp/Cntr=0.3,0.1

Type RM Length L Ch R = 1 ,60100   ,450,450,450
BEGIN DESCRIPTION:
Verde Creek 105.0
END DESCRIPTION:
XS GIS Cut Line= 4
      1923966.14     13870968.48      1924155.47     13870484.74
        1924125.       13870125.      1923794.75     13869533.33
#Sta/Elev= 30
  4119.1 1683.53  4218.1 1679.92  4456.3 1672.53  4646.4 1672.44  4901.8 1674.32
  4939.4 1670.41  4951.2    1668  4957.2 1662.63  4960.2 1657.72  4963.2 1655.14
  4975.3 1651.34  4981.3 1651.29  4981.8 1650.13  4982.3 1649.63  4999.5 1650.13
    5030 1650.77    5041 1653.16  5078.3 1653.94  5097.2 1659.41  5115.9 1663.58
  5135.8 1662.55  5155.6 1668.21  5171.1 1670.48  5188.3 1670.73  5198.6 1669.14
    5224 1672.71  5250.1 1674.51  5346.3 1672.92    5418 1673.04  5677.2 1679.81
#Mann= 7 ,-1 , 0
  4119.1     .07       0  4218.1    .035       0  4456.3     .07       0
  4939.4      .1       0  4981.8     .05       0  4999.5      .1       0
  5097.2     .07       0
Bank Sta=4981.8,4999.5
XS Rating Curve= 0 ,0
Exp/Cntr=0.3,0.1

Type RM Length L Ch R = 1 ,59650   ,455,455,455
BEGIN DESCRIPTION:
Verde Creek 104.0
END DESCRIPTION:
XS GIS Cut Line= 4
       1924252.4     13870926.52      1924527.27      13870247.6
        1924525.       13869975.      1924507.21     13869185.76
#Sta/Elev= 30
  3994.9 1678.59  4233.2 1671.82  4312.2 1669.58  4831.7 1673.02  4878.3  1668.2
  4915.7 1663.78  4921.7 1662.28  4936.7 1653.57  4957.7 1649.39  5032.7 1648.42
  5033.2 1647.92  5050.7 1648.42  5053.1 1651.34  5074.7  1660.7  5101.7 1667.59
  5149.8 1669.14  5293.9 1677.96  5407.5 1691.21  5422.8 1691.57  5434.8 1694.15
  5527.9  1725.8  5575.9 1745.45  5632.9 1772.36  5677.9  1798.1  5725.9 1830.33
  5728.9 1833.77  5731.9 1841.52  5737.9 1847.29  5752.9 1850.17  5789.4 1851.94
#Mann= 5 ,-1 , 0
  3994.9    .035       0  4233.2     .07       0  4878.3      .1       0
  5032.7     .05       0  5050.7      .1       0
Bank Sta=5032.7,5050.7
XS Rating Curve= 0 ,0
Exp/Cntr=0.3,0.1

Type RM Length L Ch R = 1 ,59195   ,443,443,443
BEGIN DESCRIPTION:
Verde Creek 103.0
END DESCRIPTION:
XS GIS Cut Line= 3
      1924775.03     13870174.97        1924925.       13870025.
      1925275.01       13869925.
#Sta/Elev= 30
  4792.5 1670.17    4852 1669.98    4918  1662.8  4943.4  1657.1  4981.4 1645.27
  4993.9 1645.04  5000.2 1643.46  5000.7 1642.96  5018.2 1643.46  5031.1 1647.45
  5061.5 1647.56  5090.3 1652.78  5130.9 1663.34  5143.4 1670.93  5155.9 1674.82
  5168.3 1681.59  5177.7 1684.85  5207.6 1701.47  5227.6 1717.98    5245 1729.68
  5252.6 1739.49  5255.7 1741.76  5274.4 1761.84  5288.7 1772.56  5305.8 1790.99
  5308.1 1794.57    5315 1848.03  5316.8 1851.66  5331.8 1853.75  5368.6 1853.72
#Mann= 4 ,-1 , 0
  4792.5    .035       0  5000.2    .035       0  5018.2    .035       0
  5061.5      .1       0
Bank Sta=5000.2,5018.2
XS Rating Curve= 0 ,0
Exp/Cntr=0.3,0.1

Type RM Length L Ch R = 1 ,58752   ,475,475,475
BEGIN DESCRIPTION:
Verde Creek 102.0
END DESCRIPTION:
XS GIS Cut Line= 3
      1924674.98       13870425.        1924875.       13870425.
        1925325.       13870075.
#Sta/Elev= 30
  4796.3 1668.63  4966.8 1668.85  4981.8 1666.28  4984.8 1664.67  4989.2 1659.45
  4996.3 1650.55  5004.5 1643.75  5017.4 1641.28  5017.9 1640.78  5035.4 1641.28
  5091.9 1645.03  5232.5 1648.36  5245.1 1649.64  5254.9 1653.39  5264.7 1653.01
  5270.5 1655.02  5289.5 1656.52  5297.1 1658.55  5372.2 1696.22  5388.4 1707.32
  5416.2 1721.73  5440.6 1737.41  5468.2 1758.57  5474.8 1764.91  5494.6 1778.29
  5521.4 1802.56  5525.2  1809.9    5529 1839.15  5532.8 1850.82  5566.4  1852.8
#Mann= 4 ,-1 , 0
  4796.3     .07       0  4989.2      .1       0  5017.4     .05       0
  5035.4      .1       0
Bank Sta=5017.4,5035.4
XS Rating Curve= 0 ,0
Exp/Cntr=0.3,0.1

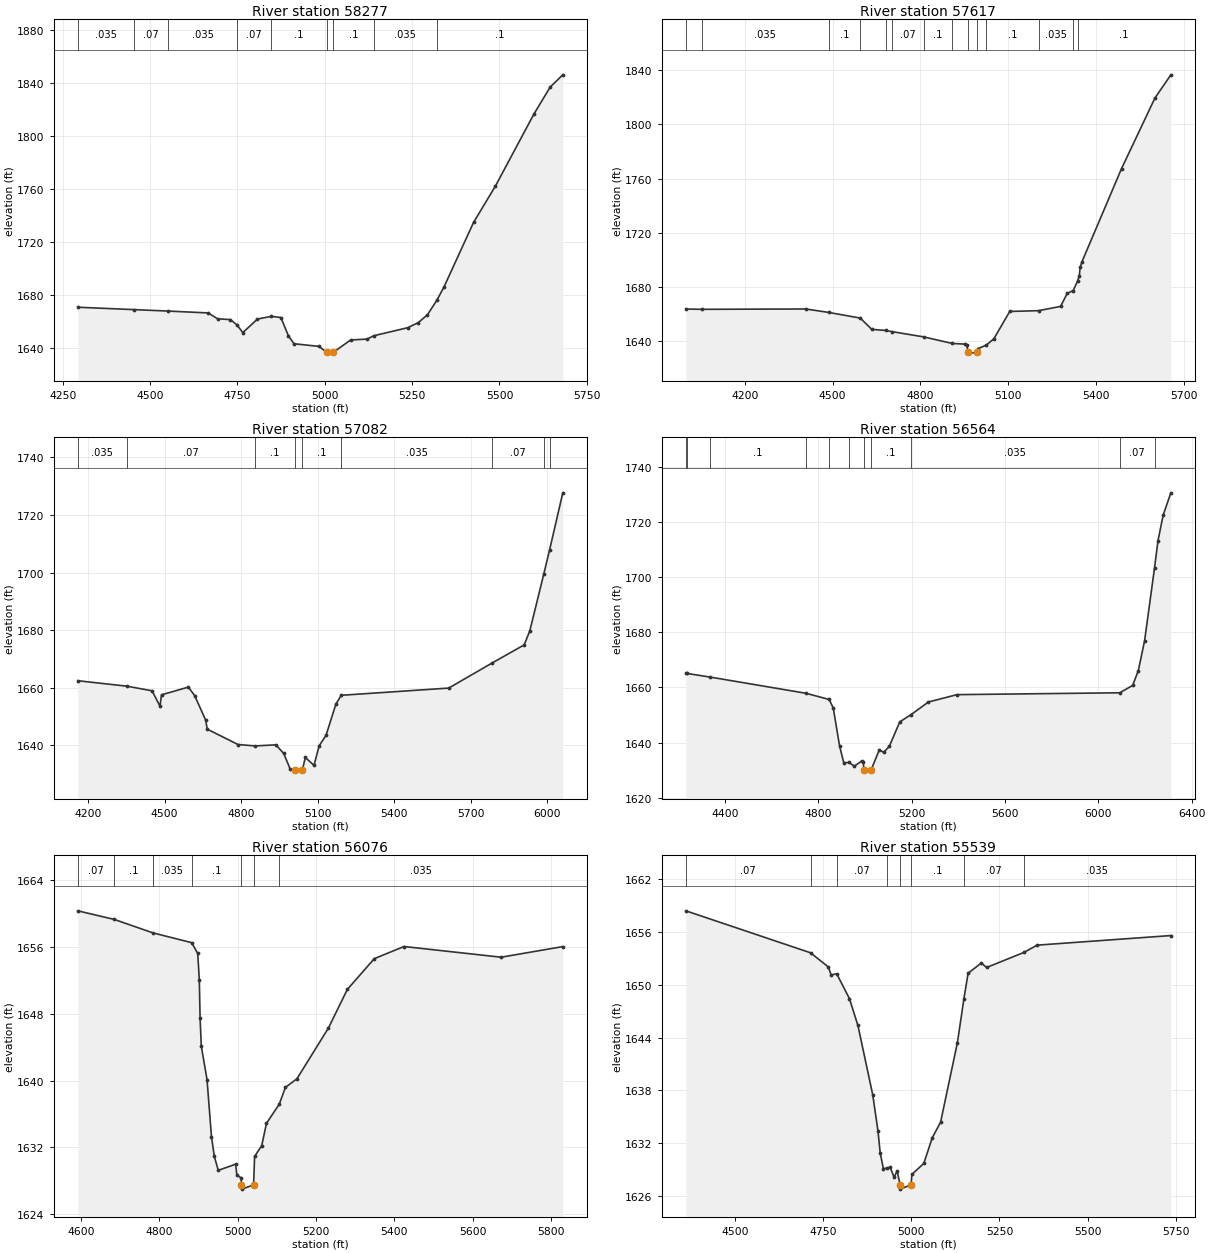
Type RM Length L Ch R = 1 ,58277   ,660,660,660
BEGIN DESCRIPTION:
Verde Creek 101.0
END DESCRIPTION:
XS GIS Cut Line= 4
      1924499.45     13870771.94       1925054.1     13870791.98
      1925307.39     13870719.73      1925474.99     13870175.03
#Sta/Elev= 30
    4293 1670.85  4453.2 1669.06  4551.7 1667.96  4666.2 1666.56  4693.3 1662.11
  4729.8 1661.55  4748.7 1657.53  4765.3 1651.74  4807.3 1661.93  4847.2    1664
  4874.4 1663.11  4895.7 1649.43  4911.8 1643.34  4983.6 1641.36  5005.7 1636.78
  5006.2 1636.28  5023.8 1636.78    5074 1646.19  5121.3 1646.86  5139.9 1649.35
  5237.5 1655.44  5267.9 1659.32    5294  1665.2  5320.8 1676.12    5341 1685.99
  5425.8  1734.7  5488.6 1762.19  5598.4 1816.25  5645.5 1836.81  5681.3 1845.91
#Mann= 9 ,-1 , 0
    4293    .035       0  4453.2     .07       0  4551.7    .035       0
  4748.7     .07       0  4847.2      .1       0  5005.7     .05       0
  5023.8      .1       0  5139.9    .035       0  5320.8      .1       0
Bank Sta=5005.7,5023.8
XS Rating Curve= 0 ,0
Exp/Cntr=0.3,0.1

Type RM Length L Ch R = 1 ,57617   ,535,535,535
BEGIN DESCRIPTION:
Verde Creek 100.0
END DESCRIPTION:
XS GIS Cut Line= 4
      1925325.09     13871824.82        1925575.       13871325.
        1925775.       13870925.        1925725.     13870275.05
#Sta/Elev= 30
  3998.1 1663.82  4052.9  1663.6  4408.1 1663.85    4486 1661.32  4594.3 1657.15
  4633.8  1648.8  4682.4 1648.01  4702.6 1647.16  4810.8  1643.3  4909.1 1638.42
  4952.4 1637.97  4958.2 1636.96  4963.9 1631.82  4964.4 1631.32  4994.6 1631.82
    4996 1634.56  5025.4 1637.27    5051 1641.91  5105.2 1662.03  5204.5 1662.62
  5279.1 1665.76  5301.5 1675.28  5322.1 1677.47  5337.1  1684.4  5342.9 1688.14
  5345.9 1694.52  5351.8  1698.5  5487.3 1767.26  5601.6 1819.32    5656  1836.4
#Mann= 14 ,-1 , 0
  3998.1      .1       0  4052.9    .035       0    4486      .1       0
  4594.3     .07       0  4682.4    .035       0  4702.6     .07       0
  4810.8      .1       0  4909.1     .07       0  4963.9     .05       0
  4994.6     .07       0  5025.4      .1       0  5204.5    .035       0
  5322.1     .07       0  5337.1      .1       0
Bank Sta=4963.9,4994.6
XS Rating Curve= 0 ,0
Exp/Cntr=0.3,0.1

Type RM Length L Ch R = 1 ,57082   ,518,518,518
BEGIN DESCRIPTION:
Verde Creek 99.0
END DESCRIPTION:
XS GIS Cut Line= 4
      1926022.28     13871985.87        1926125.       13871575.
        1926225.       13871175.      1926253.92     13870108.82
#Sta/Elev= 30
  4159.2 1662.47  4352.2 1660.57  4450.5 1658.97  4481.5 1653.65  4487.6 1657.57
  4592.8 1660.25  4617.5 1657.32  4660.8  1648.8    4667 1645.65  4787.6 1640.32
  4855.2 1639.83    4936 1640.21    4967 1637.22  4992.7  1631.7  5009.4 1631.58
  5009.9 1631.08  5040.2 1631.58  5051.8 1635.82  5085.8 1633.07  5105.8 1639.85
  5132.8 1643.49  5171.9 1654.43  5192.8 1657.41  5614.3 1659.92  5783.7  1668.6
  5910.1 1674.91  5932.1 1679.75  5986.6 1699.36  6009.8  1707.9  6061.6 1727.71
#Mann= 9 ,-1 , 0
  4159.2    .035       0  4352.2     .07       0  4855.2      .1       0
  5009.4     .05       0  5040.2      .1       0  5192.8    .035       0
  5783.7     .07       0  5986.6      .1       0  6009.8     .07       0
Bank Sta=5009.4,5040.2
XS Rating Curve= 0 ,0
Exp/Cntr=0.3,0.1

Type RM Length L Ch R = 1 ,56564   ,488,488,488
BEGIN DESCRIPTION:
Verde Creek 98.0
END DESCRIPTION:
XS GIS Cut Line= 5
        1926675.      13872136.6        1926675.       13871775.
        1926675.       13871375.        1926675.       13870975.
      1926521.07     13870071.82
#Sta/Elev= 30
  4233.1 1665.11  4238.1 1665.09  4337.3 1663.77  4748.6 1657.89  4846.9 1655.66
  4864.5 1652.62  4891.5 1638.89  4909.5 1632.75  4932.8 1632.85  4954.5 1631.48
  4987.5 1633.42  4993.5 1632.94    4996 1630.21  4996.5 1629.71    5027 1630.21
    5062 1637.46  5080.5 1636.51  5104.9 1638.72  5149.5 1647.55    5197 1650.13
  5272.5 1654.75  5394.7 1657.41  6091.7 1658.08  6147.2 1660.75  6171.5 1666.14
  6198.4 1676.96  6240.8 1703.21  6255.6 1713.09    6278 1722.45  6310.9  1730.5
#Mann= 11 ,-1 , 0
  4233.1     .07       0  4238.1    .035       0  4337.3      .1       0
  4748.6    .035       0  4846.9     .07       0  4932.8      .1       0
    4996     .05       0    5027      .1       0    5197    .035       0
  6091.7     .07       0  6240.8      .1       0
Bank Sta=4996,5027
XS Rating Curve= 0 ,0
Exp/Cntr=0.3,0.1

Type RM Length L Ch R = 1 ,56076   ,537,537,537
BEGIN DESCRIPTION:
Verde Creek 97.0
END DESCRIPTION:
XS GIS Cut Line= 3
        1927025.     13871724.98        1927075.       13871325.
      1926969.73     13870497.06
#Sta/Elev= 30
  4592.4 1660.31  4685.5 1659.28  4784.2 1657.67    4883  1656.5  4898.5 1655.21
  4902.5 1652.05  4904.5 1647.44  4907.6 1644.11  4922.2 1640.12  4933.6 1633.26
  4940.8 1630.93  4950.9 1629.26  4995.3 1629.99  4998.3 1628.68  5009.2 1628.36
    5010 1627.51  5010.5 1627.01    5041 1627.51  5043.6 1630.92  5061.8 1632.22
  5073.9 1634.88  5106.5 1637.17  5122.3 1639.19  5151.4  1640.2  5231.9 1646.28
  5280.2  1650.9  5349.1 1654.59    5425 1656.04  5672.7 1654.76  5830.1 1656.03
#Mann= 7 ,-1 , 0
  4592.4     .07       0  4685.5      .1       0  4784.2    .035       0
    4883      .1       0    5010     .05       0    5041      .1       0
  5106.5    .035       0
Bank Sta=5010,5041
XS Rating Curve= 0 ,0
Exp/Cntr=0.3,0.1

Type RM Length L Ch R = 1 ,55539   ,239,239,239
BEGIN DESCRIPTION:
Verde Creek 96.0
END DESCRIPTION:
XS GIS Cut Line= 3
      1927563.61     13871713.44        1927525.       13871075.
      1927077.23     13870490.63
#Sta/Elev= 30
  4360.4 1658.42  4714.1 1653.65  4764.3 1652.05  4772.6 1651.13  4788.3 1651.27
  4824.4 1648.44  4848.5 1645.39  4890.6 1637.49  4905.6 1633.34  4911.6 1630.92
  4920.6 1629.13  4930.1 1629.17  4939.8 1629.28  4951.2 1628.13  4959.7 1628.87
  4968.2 1627.29  4968.7 1626.79  4999.3 1627.29  5001.6 1628.46  5035.4 1629.72
  5059.4 1632.63    5083  1634.4  5130.7 1643.44  5149.2 1648.44    5161 1651.32
  5198.5 1652.49  5213.5 1651.98  5319.2 1653.69  5356.9 1654.52  5736.2 1655.61
#Mann= 8 ,-1 , 0
  4360.4     .07       0  4714.1    .035       0  4788.3     .07       0
  4930.1      .1       0  4968.2     .05       0  4999.3      .1       0
  5149.2     .07       0  5319.2    .035       0
Bank Sta=4968.2,4999.3
XS Rating Curve= 0 ,0
Exp/Cntr=0.3,0.1

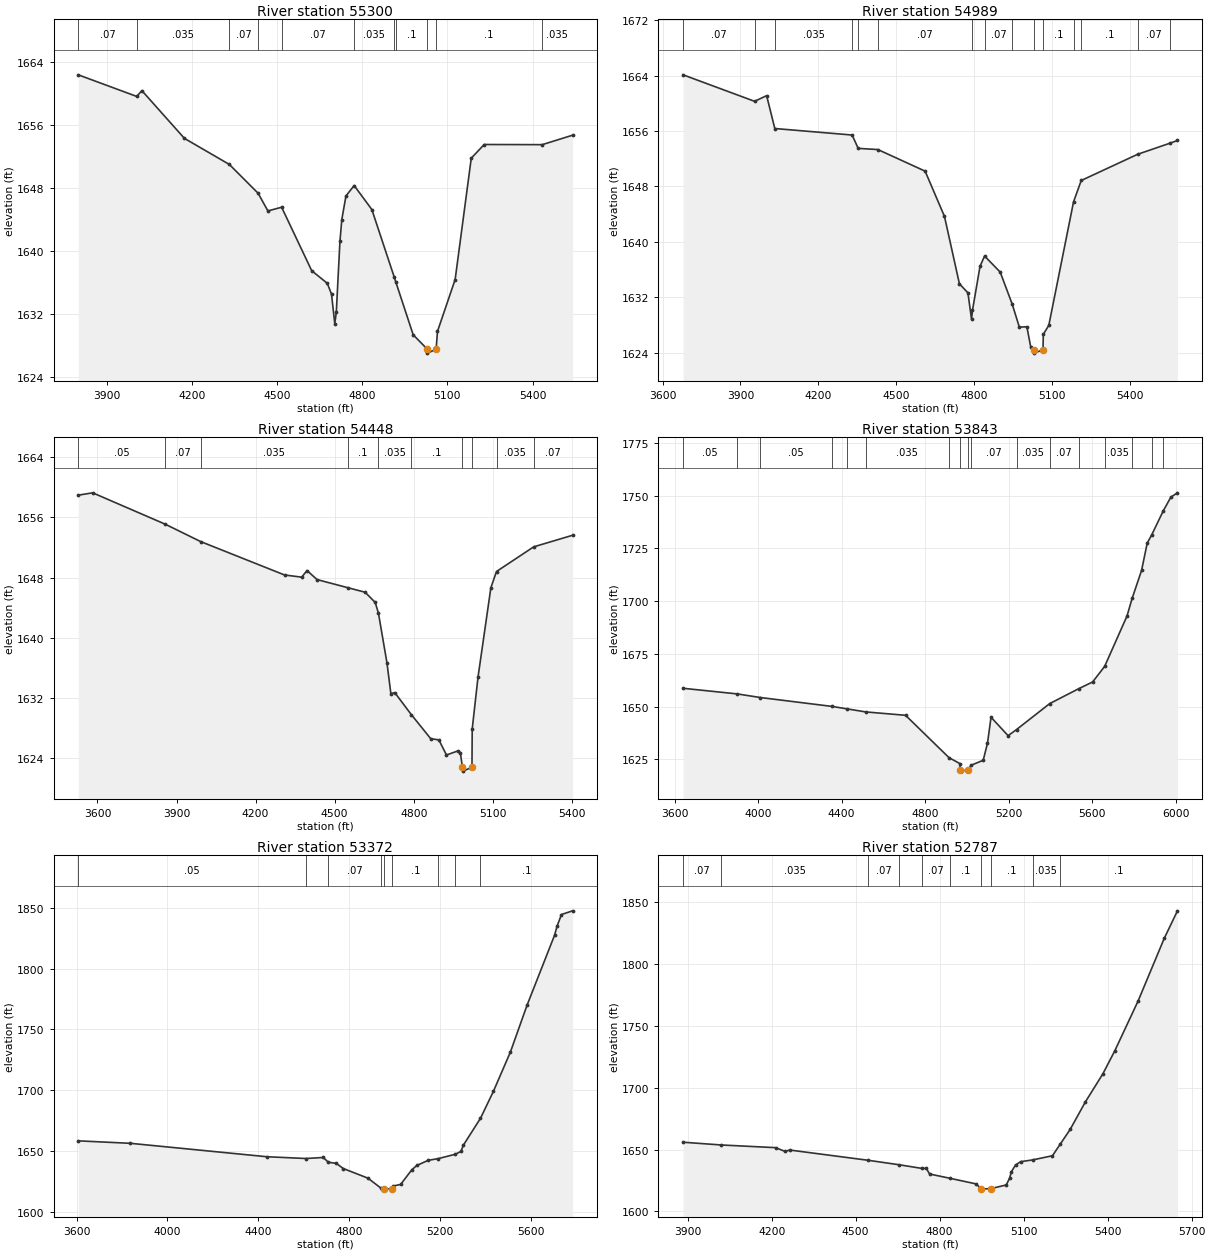
Type RM Length L Ch R = 1 ,55300   ,311,311,311
BEGIN DESCRIPTION:
Verde Creek 95.1
END DESCRIPTION:
XS GIS Cut Line= 3
      1928172.01     13872087.44      1927999.13     13871278.73
      1927367.87     13870616.88
#Sta/Elev= 30
  3799.5 1662.35  4005.6 1659.61  4023.6 1660.35  4173.4  1654.3  4331.9 1650.99
  4433.2 1647.34  4467.6  1645.1    4516 1645.57  4621.9 1637.53  4676.8 1635.93
  4691.7 1634.56  4703.2 1630.82  4708.6 1632.25  4721.4 1641.23    4728 1644.01
  4742.6    1647  4771.5 1648.32  4833.8 1645.28  4913.1 1636.67  4918.1 1636.11
  4979.5  1629.4  5029.2 1627.58  5029.7 1627.08  5060.3 1627.58  5065.1 1629.84
  5127.3 1636.41  5184.1 1651.79  5229.7 1653.52  5434.1  1653.5  5541.1  1654.7
#Mann= 11 ,-1 , 0
  3799.5     .07       0  4005.6    .035       0  4331.9     .07       0
  4433.2    .035       0    4516     .07       0  4771.5    .035       0
  4913.1     .07       0  4918.1      .1       0  5029.2     .05       0
  5060.3      .1       0  5434.1    .035       0
Bank Sta=5029.2,5060.3
XS Rating Curve= 0 ,0
Exp/Cntr=0.3,0.1

Type RM Length L Ch R = 1 ,54989   ,541,541,541
BEGIN DESCRIPTION:
Verde Creek 95.0
END DESCRIPTION:
XS GIS Cut Line= 4
      1928251.57     13872218.16      1928154.21     13871269.55
        1928025.       13870925.       1928094.4     13870347.43
#Sta/Elev= 30
  3679.1 1664.13  3954.4  1660.3  4000.7 1661.12  4032.2 1656.37  4329.9 1655.43
  4353.2  1653.5  4429.1 1653.33  4610.9 1650.21  4685.4 1643.67    4743 1633.92
  4775.7 1632.63  4789.6 1628.82  4793.2 1630.08  4822.3 1636.46  4839.9 1637.94
    4900 1635.62  4946.2 1630.99  4973.7 1627.67  5002.7 1627.72  5017.6 1624.78
  5030.8 1624.41  5031.4 1623.91  5064.8 1624.41  5065.9 1626.63  5087.1 1627.92
  5182.4 1645.78    5212 1648.86  5429.4 1652.65  5554.4 1654.26  5582.4 1654.64
#Mann= 15 ,-1 , 0
  3679.1     .07       0  3954.4      .1       0  4032.2    .035       0
  4329.9     .07       0  4353.2    .035       0  4429.1     .07       0
  4793.2    .035       0  4839.9     .07       0  4946.2      .1       0
  5030.8     .05       0  5064.8      .1       0  5182.4    .035       0
    5212      .1       0  5429.4     .07       0  5554.4      .1       0
Bank Sta=5030.8,5064.8
XS Rating Curve= 0 ,0
Exp/Cntr=0.3,0.1

Type RM Length L Ch R = 1 ,54448   ,605,605,605
BEGIN DESCRIPTION:
Verde Creek 94.0
END DESCRIPTION:
XS GIS Cut Line= 4
      1928992.83     13872047.81      1928831.87     13871282.06
        1928425.       13870725.      1928225.01     13870375.02
#Sta/Elev= 30
  3527.2 1658.94  3581.9 1659.25    3857 1655.09  3991.6 1652.78  4309.7 1648.35
  4374.8 1648.06  4395.2 1648.94  4432.9 1647.74    4550 1646.66  4615.4 1646.06
  4653.7 1644.71    4666 1643.28  4698.3 1636.69  4713.2 1632.59    4728 1632.74
  4790.7 1629.82  4864.5 1626.62  4895.2 1626.47  4924.1 1624.46  4969.7 1625.03
  4976.9 1624.73  4984.6 1622.82  4985.4 1622.32  5020.8 1622.82  5021.7 1627.89
  5043.7 1634.78  5092.5 1646.65  5113.9 1648.81  5254.8 1652.08  5402.6 1653.62
#Mann= 10 ,-1 , 0
  3527.2     .05       0    3857     .07       0  3991.6    .035       0
    4550      .1       0    4666    .035       0  4790.7      .1       0
  4984.6     .05       0  5020.8      .1       0  5113.9    .035       0
  5254.8     .07       0
Bank Sta=4984.6,5020.8
XS Rating Curve= 0 ,0
Exp/Cntr=0.3,0.1

Type RM Length L Ch R = 1 ,53843   ,471,471,471
BEGIN DESCRIPTION:
Verde Creek 93.0
END DESCRIPTION:
XS GIS Cut Line= 5
      1929029.56     13872067.87      1928901.85     13870962.48
      1928968.02     13870724.43      1929077.36     13870521.27
      1929675.03     13870024.97
#Sta/Elev= 30
  3640.9 1658.68    3899 1656.03  4010.7 1654.31  4354.4 1650.09  4425.6 1648.94
  4515.9 1647.48  4706.2 1645.89  4914.2 1625.83  4965.6 1623.05  4969.2 1619.94
  4970.1 1619.44  5005.5 1619.94  5020.4 1622.23  5078.1 1624.59  5098.6 1632.66
  5115.6 1644.96  5197.4 1636.23    5238 1639.15  5396.4 1651.42  5534.7 1658.45
  5602.2 1661.69  5659.6 1669.04  5766.8 1692.93  5791.2 1701.23  5836.6 1714.54
  5863.5 1727.45  5884.7 1731.28  5939.6 1742.57  5976.6 1749.21  6008.3 1751.27
#Mann= 17 ,-1 , 0
  3640.9     .05       0    3899     .07       0  4010.7     .05       0
  4354.4    .035       0  4425.6     .05       0  4515.9    .035       0
  4914.2      .1       0  4969.2     .05       0  5005.5      .1       0
  5020.4     .07       0    5238    .035       0  5396.4     .07       0
  5534.7      .1       0  5659.6    .035       0  5791.2      .1       0
  5884.7    .035       0  5939.6      .1       0
Bank Sta=4969.2,5005.5
XS Rating Curve= 0 ,0
Exp/Cntr=0.3,0.1

Type RM Length L Ch R = 1 ,53372   ,585,585,585
BEGIN DESCRIPTION:
Verde Creek 92.0
END DESCRIPTION:
XS GIS Cut Line= 4
       1929102.2     13872104.67        1929279.     13870942.65
        1929425.       13870775.      1929924.98     13870175.02
#Sta/Elev= 30
  3606.7 1658.26  3836.7 1656.22  4437.5 1645.19    4610 1643.72  4686.4 1644.56
    4709 1640.66    4744 1639.71  4774.4 1635.49  4883.4 1627.55  4942.4  1619.1
  4955.2 1619.02    4956 1618.52  4991.6 1619.02  4995.4  1621.1  5027.4 1622.38
  5076.9 1634.47  5099.1 1638.03  5148.8 1642.21    5193 1643.63  5267.6 1647.17
  5293.6 1649.55  5303.4 1654.54  5379.4 1676.83  5436.2 1698.93  5511.5 1731.47
  5584.6 1769.88  5705.7 1827.38  5717.4 1835.18  5736.4 1844.54  5785.4 1847.57
#Mann= 9 ,-1 , 0
  3606.7     .05       0    4610    .035       0    4709     .07       0
  4942.4      .1       0  4955.2     .05       0  4991.6      .1       0
    5193     .07       0  5267.6    .035       0  5379.4      .1       0
Bank Sta=4955.2,4991.6
XS Rating Curve= 0 ,0
Exp/Cntr=0.3,0.1

Type RM Length L Ch R = 1 ,52787   ,534,534,534
BEGIN DESCRIPTION:
Verde Creek 91.0
END DESCRIPTION:
XS GIS Cut Line= 4
      1930231.59      13871933.3      1929943.74     13871218.82
        1929975.       13870875.        1929975.     13870225.03
#Sta/Elev= 30
  3883.8 1656.01  4020.7 1653.77  4214.3 1651.61  4248.2 1648.56  4264.4  1649.7
  4545.1 1641.39  4653.1 1637.86  4738.3 1634.77    4752    1635  4764.1 1630.31
  4836.8 1626.84  4929.8 1622.31  4947.5 1618.57  4948.4 1618.07  4984.4 1618.57
    5038 1621.44    5050 1627.05    5056 1632.04    5071 1637.56    5089 1640.27
  5132.2  1641.7    5203 1645.08  5230.5 1654.38  5266.4 1666.45    5320 1688.43
    5383 1711.35    5425 1729.69    5509 1770.36    5602 1820.83  5649.3 1843.17
#Mann= 10 ,-1 , 0
  3883.8     .07       0  4020.7    .035       0  4545.1     .07       0
  4653.1    .035       0  4738.3     .07       0  4836.8      .1       0
  4947.5     .05       0  4984.4      .1       0  5132.2    .035       0
  5230.5      .1       0
Bank Sta=4947.5,4984.4
XS Rating Curve= 0 ,0
Exp/Cntr=0.3,0.1

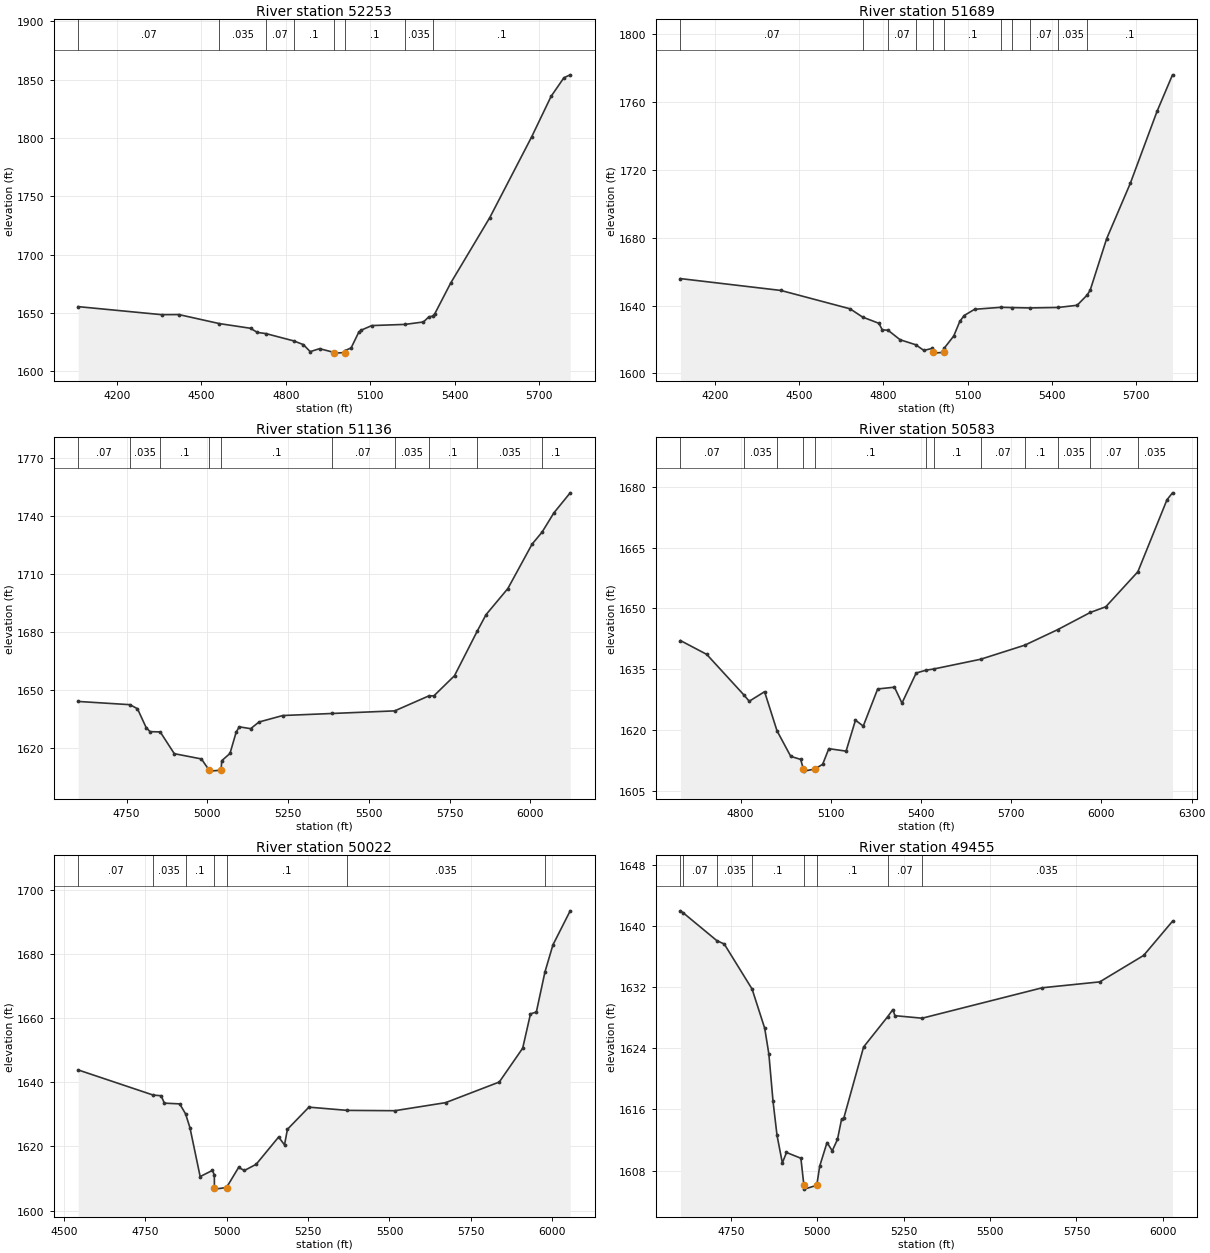
Type RM Length L Ch R = 1 ,52253   ,564,564,564
BEGIN DESCRIPTION:
Verde Creek 90.0
END DESCRIPTION:
XS GIS Cut Line= 3
      1930294.15     13871907.65        1930425.       13870975.
        1930525.     13870175.01
#Sta/Elev= 30
  4062.6 1655.34  4359.1 1648.45  4420.4 1648.54  4564.2  1640.8  4674.9 1636.79
  4699.1 1633.25  4729.6 1632.23  4828.5 1625.97  4862.7 1622.77    4887 1616.76
  4920.3 1619.31  4973.1 1615.98    4974 1615.48    5010 1615.98  5011.2 1617.73
  5032.3 1619.94  5059.5 1633.44  5067.8 1635.13  5105.9 1639.11  5223.8 1640.11
  5289.3 1642.21  5308.4 1646.54  5322.5 1647.24  5329.9 1649.38  5385.7  1675.4
  5525.1 1731.73  5673.3 1800.69  5742.8 1835.64  5788.2 1851.55  5810.6 1854.07
#Mann= 8 ,-1 , 0
  4062.6     .07       0  4564.2    .035       0  4729.6     .07       0
  4828.5      .1       0  4973.1     .05       0    5010      .1       0
  5223.8    .035       0  5322.5      .1       0
Bank Sta=4973.1,5010
XS Rating Curve= 0 ,0
Exp/Cntr=0.3,0.1

Type RM Length L Ch R = 1 ,51689   ,553,553,553
BEGIN DESCRIPTION:
Verde Creek 89.0
END DESCRIPTION:
XS GIS Cut Line= 3
      1930839.31     13872097.51        1930925.       13871175.
        1930725.     13870375.01
#Sta/Elev= 30
  4077.7 1655.92  4435.2 1648.93  4681.5  1638.1  4725.8 1633.24    4784 1629.56
    4796 1625.69  4816.3  1625.5  4859.3 1619.88  4914.8 1616.93  4943.8  1613.6
  4973.8 1614.74  4978.1 1612.48    4979 1611.98    5015 1612.48  5015.8 1614.77
  5050.3 1622.09  5071.9  1630.7  5087.4 1634.15  5124.5 1637.82  5218.1    1639
  5258.6 1638.83  5320.3 1638.62  5422.6 1638.91  5489.4  1640.2  5524.8 1646.18
  5535.8 1649.06  5594.5 1679.47  5678.8 1712.16  5773.9 1754.58  5828.8 1776.06
#Mann= 11 ,-1 , 0
  4077.7     .07       0  4725.8    .035       0  4816.3     .07       0
  4914.8      .1       0  4978.1     .05       0    5015      .1       0
  5218.1     .07       0  5258.6      .1       0  5320.3     .07       0
  5422.6    .035       0  5524.8      .1       0
Bank Sta=4978.1,5015
XS Rating Curve= 0 ,0
Exp/Cntr=0.3,0.1

Type RM Length L Ch R = 1 ,51136   ,553,553,553
BEGIN DESCRIPTION:
Verde Creek 88.0
END DESCRIPTION:
XS GIS Cut Line= 4
        1931425.     13871724.98        1931425.       13871325.
        1931125.       13870525.      1931030.47     13870272.92
#Sta/Elev= 30
    4600 1643.94  4760.3 1642.26  4783.7 1640.16  4810.7 1630.36  4822.7 1628.28
  4854.2 1628.14  4897.7 1616.86  4981.7 1614.13  5005.6 1608.31  5006.5 1607.81
  5042.7 1608.31  5044.5 1613.18  5070.2 1616.99  5089.4 1628.07    5099 1630.78
  5134.2 1629.82  5159.9 1633.27  5233.6 1636.64  5385.4 1637.69  5580.2 1639.05
  5686.5 1646.86  5701.4 1646.82  5765.4 1657.29  5836.4  1680.6    5863 1688.93
  5930.6 1702.48  6005.7 1725.53  6036.4 1731.69    6073 1741.68  6123.6  1752.1
#Mann= 10 ,-1 , 0
    4600     .07       0  4760.3    .035       0  4854.2      .1       0
  5005.6     .05       0  5042.7      .1       0  5385.4     .07       0
  5580.2    .035       0  5686.5      .1       0  5836.4    .035       0
  6036.4      .1       0
Bank Sta=5005.6,5042.7
XS Rating Curve= 0 ,0
Exp/Cntr=0.3,0.1

Type RM Length L Ch R = 1 ,50583   ,561,561,561
BEGIN DESCRIPTION:
Verde Creek 87.0
END DESCRIPTION:
XS GIS Cut Line= 4
        1931925.     13871875.02        1931925.       13871475.
        1931725.       13871025.      1931423.02     13870345.54
#Sta/Elev= 30
  4600.3 1642.08  4687.7 1638.67  4811.4 1628.66    4829 1627.12    4880 1629.47
  4921.3 1619.84    4967 1613.53    5000 1612.78  5009.1 1610.39    5010 1609.89
  5046.2 1610.39  5073.1 1611.57  5093.6 1615.43    5151 1614.82  5182.2 1622.45
  5208.1    1621  5256.1 1630.15  5311.9 1630.58  5336.8 1626.66  5384.1 1634.08
  5417.4 1634.79  5441.9 1635.06  5598.3 1637.47    5745 1640.94  5854.2 1644.76
  5963.4 1649.02  6014.4 1650.41  6121.1 1659.04    6218  1676.8  6236.3  1678.5
#Mann= 12 ,-1 , 0
  4600.3     .07       0  4811.4    .035       0  4921.3      .1       0
  5009.1     .05       0  5046.2      .1       0  5417.4     .07       0
  5441.9      .1       0  5598.3     .07       0    5745      .1       0
  5854.2    .035       0  5963.4     .07       0  6121.1    .035       0
Bank Sta=5009.1,5046.2
XS Rating Curve= 0 ,0
Exp/Cntr=0.3,0.1

Type RM Length L Ch R = 1 ,50022   ,567,567,567
BEGIN DESCRIPTION:
Verde Creek 86.0
END DESCRIPTION:
XS GIS Cut Line= 4
      1932285.88     13872019.14        1932425.       13871575.
       1932416.8     13870944.94      1932411.38     13870528.31
#Sta/Elev= 30
  4543.2 1643.89  4773.8 1636.04  4798.2 1635.83  4808.2 1633.52  4855.3 1633.29
  4873.3 1630.19  4886.8 1625.86  4918.2  1610.6  4955.9 1612.53  4961.8 1611.08
    4962 1607.18  4962.9 1606.68  4999.2 1607.18  5036.3 1613.44  5054.3  1612.5
  5090.3 1614.43  5159.4 1622.95  5177.4 1620.48  5186.4 1625.35  5252.4 1632.27
  5370.3 1631.26  5516.4 1631.16  5672.4 1633.67  5837.4 1640.11  5909.4 1650.67
  5933.4 1661.39  5951.4 1661.96  5977.9  1674.5  6002.4 1682.93  6055.4 1693.55
#Mann= 7 ,-1 , 0
  4543.2     .07       0  4773.8    .035       0  4873.3      .1       0
    4962     .05       0  4999.2      .1       0  5370.3    .035       0
  5977.9     .07       0
Bank Sta=4962,4999.2
XS Rating Curve= 0 ,0
Exp/Cntr=0.3,0.1

Type RM Length L Ch R = 1 ,49455   ,518,518,518
BEGIN DESCRIPTION:
Verde Creek 85.0
END DESCRIPTION:
XS GIS Cut Line= 4
        1932975.     13872024.97        1932975.       13871625.
      1932918.48     13871164.08      1932850.47     13870609.48
#Sta/Elev= 30
  4604.6 1641.96  4611.5 1641.74  4709.9 1638.06  4731.3 1637.62  4811.8 1631.73
  4848.3  1626.6  4860.3 1623.24  4872.3 1617.07  4883.9  1612.6  4899.3    1609
  4911.3 1610.36  4952.9 1609.61  4961.6 1606.07  4962.6 1605.57  4998.9 1606.07
  5007.3 1608.57  5028.5 1611.66  5043.6 1610.58  5058.7 1612.07  5070.8 1614.76
  5076.8 1614.82  5134.3 1624.16  5204.1 1628.13  5218.9 1629.05  5224.9 1628.25
  5303.6 1627.92  5651.1  1631.9  5817.3 1632.67  5944.3 1636.13  6027.7  1640.6
#Mann= 8 ,-1 , 0
  4604.6      .1       0  4611.5     .07       0  4709.9    .035       0
  4811.8      .1       0  4961.6     .05       0  4998.9      .1       0
  5204.1     .07       0  5303.6    .035       0
Bank Sta=4961.6,4998.9
XS Rating Curve= 0 ,0
Exp/Cntr=0.3,0.1

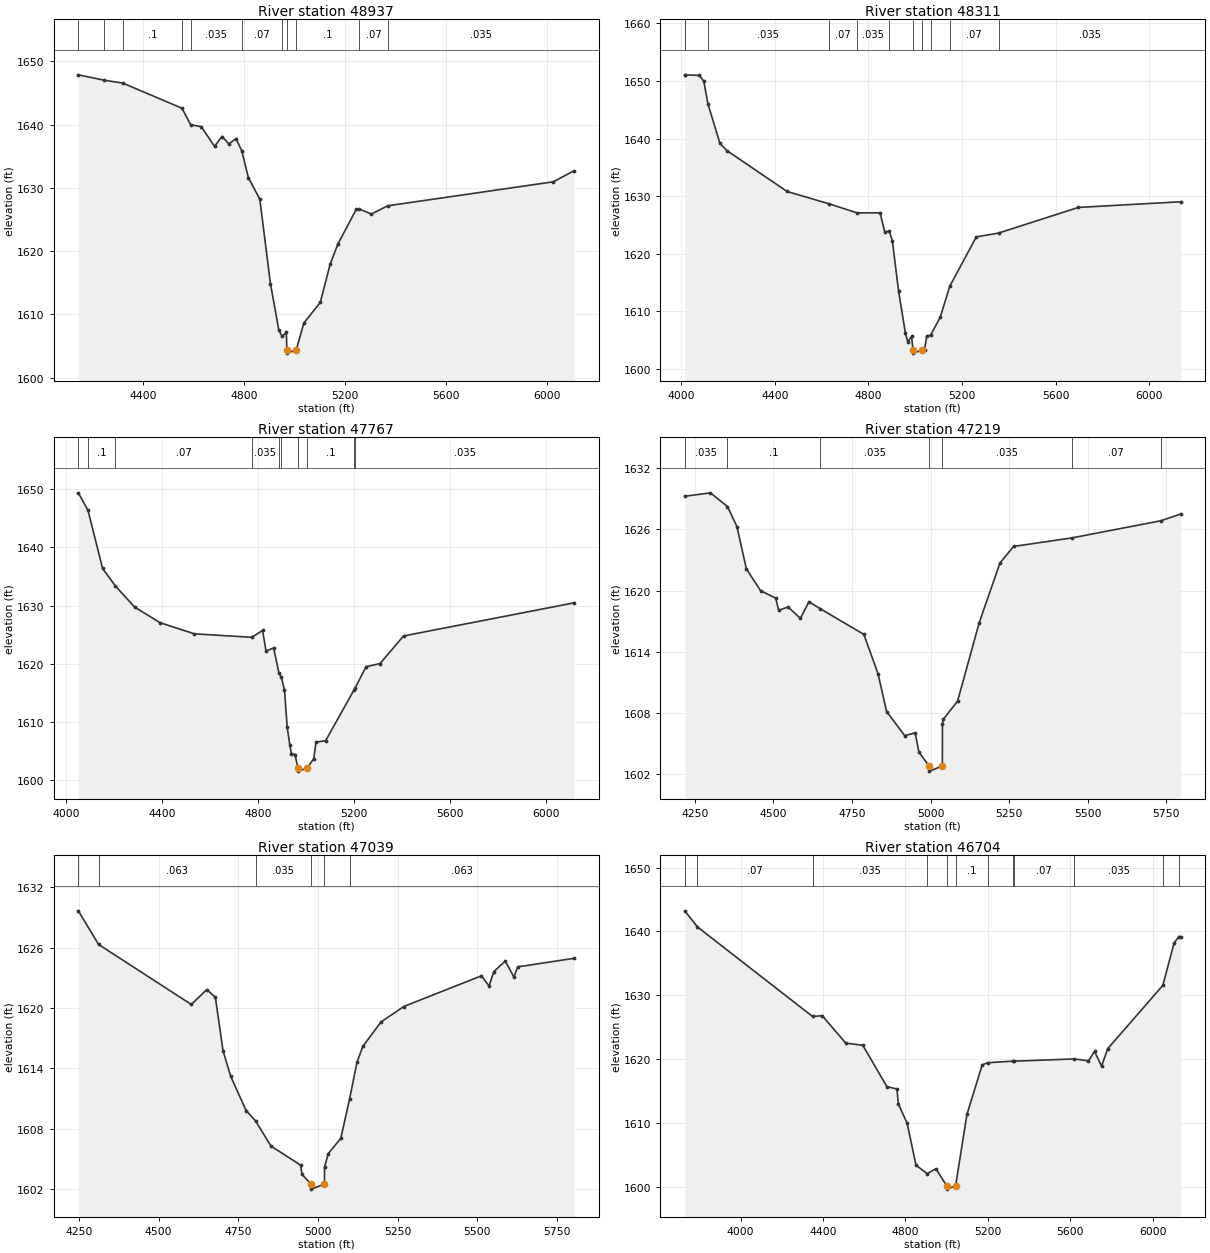
Type RM Length L Ch R = 1 ,48937   ,626,626,626
BEGIN DESCRIPTION:
Verde Creek 84.0
END DESCRIPTION:
XS GIS Cut Line= 5
      1932741.98     13872262.84      1933408.11     13871863.23
      1933463.98     13871742.38        1933375.       13871075.
      1933324.62     13870697.17
#Sta/Elev= 30
  4144.5 1647.86  4246.9 1647.01  4320.8 1646.55  4555.2 1642.58  4589.3 1639.98
  4631.6 1639.67    4684 1636.55  4713.2 1638.11  4741.1 1636.95  4769.1 1637.77
  4791.8 1635.88  4818.1 1631.63  4863.6 1628.18  4905.6 1614.87  4938.9  1607.5
  4951.9 1606.52  4968.6 1607.14  4970.6 1604.37  4971.5 1603.87  5007.9 1604.37
    5038 1608.63    5103 1611.88  5142.3 1617.94  5172.6 1621.09  5246.2 1626.64
  5257.8 1626.64  5305.7 1625.86  5370.4 1627.16  6026.1 1630.95  6108.9 1632.71
#Mann= 11 ,-1 , 0
  4144.5      .1       0  4246.9     .07       0  4320.8      .1       0
  4555.2     .07       0  4589.3    .035       0  4791.8     .07       0
  4951.9      .1       0  4970.6     .05       0  5007.9      .1       0
  5257.8     .07       0  5370.4    .035       0
Bank Sta=4970.6,5007.9
XS Rating Curve= 0 ,0
Exp/Cntr=0.3,0.1

Type RM Length L Ch R = 1 ,48311   ,544,544,544
BEGIN DESCRIPTION:
Verde Creek 83.0
END DESCRIPTION:
XS GIS Cut Line= 4
      1933623.42     13872818.42        1934025.       13871925.
        1933925.       13871225.      1933863.84     13870796.88
#Sta/Elev= 30
  4015.5 1651.07  4015.8 1651.07  4077.8 1650.97  4096.8 1649.95  4114.2 1646.04
  4165.9 1639.14  4196.5 1637.87  4452.6  1630.8  4631.6 1628.66  4752.1 1627.08
    4850 1627.09  4869.7 1623.82  4890.3 1623.85  4902.6 1622.22  4928.9 1613.58
  4958.5 1606.13  4968.4 1604.69  4984.9  1605.6  4990.9 1603.21  4991.9 1602.71
  5028.9 1603.21  5040.1 1603.33  5049.3 1605.63  5066.5 1605.87  5107.4 1608.96
    5148 1614.34  5261.4 1622.91  5356.3 1623.57  5697.7 1628.03  6134.6 1629.01
#Mann= 11 ,-1 , 0
  4015.5     .07       0  4015.8      .1       0  4114.2    .035       0
  4631.6     .07       0  4752.1    .035       0  4890.3     .07       0
  4990.9     .05       0  5028.9     .07       0  5066.5      .1       0
    5148     .07       0  5356.3    .035       0
Bank Sta=4990.9,5028.9
XS Rating Curve= 0 ,0
Exp/Cntr=0.3,0.1

Type RM Length L Ch R = 1 ,47767   ,548,548,548
BEGIN DESCRIPTION:
Verde Creek 82.0
END DESCRIPTION:
XS GIS Cut Line= 4
        1934025.     13872774.99        1934525.       13871975.
        1934375.       13871275.       1934289.4     13870875.55
#Sta/Elev= 30
  4051.5  1649.4  4091.9 1646.37  4152.7 1636.39  4205.7  1633.4  4285.8 1629.76
    4392 1627.07  4535.1 1625.15  4774.5 1624.55    4820 1625.72  4834.2 1622.19
    4866 1622.71  4888.3 1618.39    4898 1617.69  4911.2 1615.52  4922.6 1609.06
  4933.8 1605.96  4940.3 1604.53  4955.2 1604.38  4967.3 1602.03  4968.3 1601.53
  5005.4 1602.03  5033.5  1603.7  5042.7 1606.53  5082.6 1606.75  5201.7 1615.53
  5204.8 1615.75  5251.3 1619.48  5309.6 1620.04  5407.8 1624.78  6119.3 1630.48
#Mann= 10 ,-1 , 0
  4051.5    .035       0  4091.9      .1       0  4205.7     .07       0
  4774.5    .035       0  4888.3     .07       0    4898      .1       0
  4967.3     .05       0  5005.4      .1       0  5201.7     .07       0
  5204.8    .035       0
Bank Sta=4967.3,5005.4
XS Rating Curve= 0 ,0
Exp/Cntr=0.3,0.1

Type RM Length L Ch R = 1 ,47219   ,180,180,180
BEGIN DESCRIPTION:
Verde Creek 81.0
END DESCRIPTION:
XS GIS Cut Line= 3
      1934897.32     13872903.25        1934975.       13872125.
      1934981.25     13871329.54
#Sta/Elev= 30
  4217.9 1629.23  4299.3 1629.57  4353.7 1628.23  4383.7 1626.27  4413.8 1622.12
  4459.1 1619.98  4507.3 1619.25  4516.3 1618.06  4546.5 1618.39  4585.7 1617.27
  4612.9  1618.9  4649.4 1618.21  4787.7  1615.7  4832.9 1611.83    4860 1608.15
  4917.5 1605.79    4951 1606.06  4962.6 1604.19  4995.1 1602.81  4996.1 1602.31
  5037.4 1602.81  5037.7 1606.96  5040.7  1607.4  5085.7 1609.16  5154.7 1616.85
  5220.7  1622.7  5264.2 1624.32  5448.6 1625.15    5732 1626.83  5795.5 1627.49
#Mann= 7 ,-1 , 0
  4217.9    .035       0  4353.7      .1       0  4649.4    .035       0
  4995.1    .035       0  5037.4    .035       0  5448.6     .07       0
    5732    .035       0
Bank Sta=4995.1,5037.4
XS Rating Curve= 0 ,0
Exp/Cntr=0.3,0.1

Type RM Length L Ch R = 1 ,47039   ,335,335,335
BEGIN DESCRIPTION:
Verde Creek 80.1
END DESCRIPTION:
XS GIS Cut Line= 3
      1935080.92     13872935.33      1935128.51     13872418.92
      1935154.35     13871382.34
#Sta/Elev= 30
    4248 1629.65  4311.5 1626.31  4602.4 1620.34  4650.8 1621.82  4677.9 1621.06
  4701.9 1615.75  4726.1 1613.19  4774.3  1609.8    4804 1608.77  4852.3 1606.27
  4945.3 1604.38  4949.8 1603.45  4977.8 1602.49  4978.8 1601.99  5020.2 1602.49
  5020.3 1604.15  5031.8 1605.51  5071.3 1607.03    5099 1610.95  5122.1 1614.59
  5140.4 1616.17  5197.4  1618.6    5269 1620.14  5512.5 1623.19  5536.5 1622.18
  5551.5 1623.61  5587.5 1624.66  5614.5 1623.07  5626.5 1624.08  5803.5 1624.93
#Mann= 6 ,-1 , 0
    4248    .035       0  4311.5    .063       0    4804    .035       0
  4977.8    .035       0  5020.2    .035       0    5099    .063       0
Bank Sta=4977.8,5020.2
XS Rating Curve= 0 ,0
Exp/Cntr=0.3,0.1

Type RM Length L Ch R = 1 ,46704   ,531,531,531
BEGIN DESCRIPTION:
Verde Creek 80.0
END DESCRIPTION:
XS GIS Cut Line= 3
      1935148.15      13873569.6        1935425.       13872325.
        1936225.       13871525.
#Sta/Elev= 30
  3729.6 1643.23  3790.9 1640.71  4349.4 1626.68  4396.8  1626.8  4510.6  1622.5
  4593.5 1622.16  4710.3 1615.69  4759.5  1615.3  4765.6    1613  4808.7 1609.94
  4851.7 1603.37  4906.2 1602.04  4947.9 1602.81  5001.4 1600.12  5002.4 1599.62
  5043.8 1600.12    5099 1611.34  5173.2 1619.09  5199.4 1619.43  5320.6 1619.67
  5326.1 1619.67  5619.2 1620.02  5688.7 1619.73  5718.3 1621.19  5752.3 1618.89
    5782 1621.62  6049.7 1631.55  6104.5 1638.21    6128  1639.2    6136 1639.17
#Mann= 12 ,-1 , 0
  3729.6    .035       0  3790.9     .07       0  4349.4    .035       0
  4906.2      .1       0  5001.4     .05       0  5043.8      .1       0
  5199.4     .07       0  5320.6    .035       0  5326.1     .07       0
  5619.2    .035       0  6049.7      .1       0    6128    .035       0
Bank Sta=5001.4,5043.8
XS Rating Curve= 0 ,0
Exp/Cntr=0.3,0.1