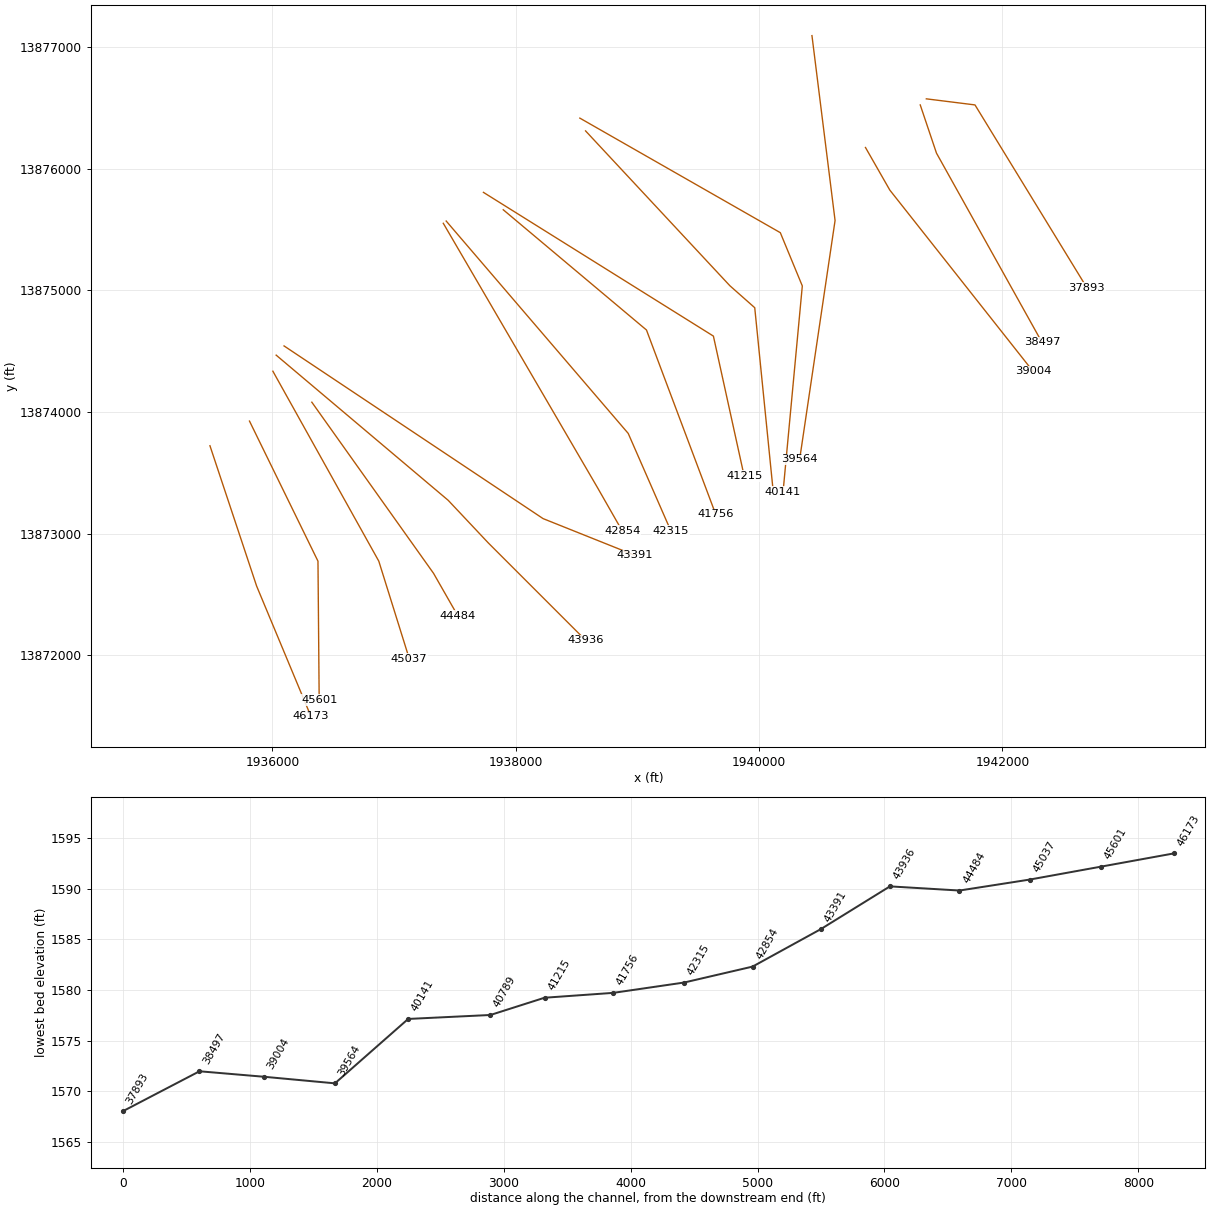
HEC-RAS study Verde Creek.prj: Verde Creek Base Level Engineering

--- Verde Creek.g01 (geometry) --- (continued)

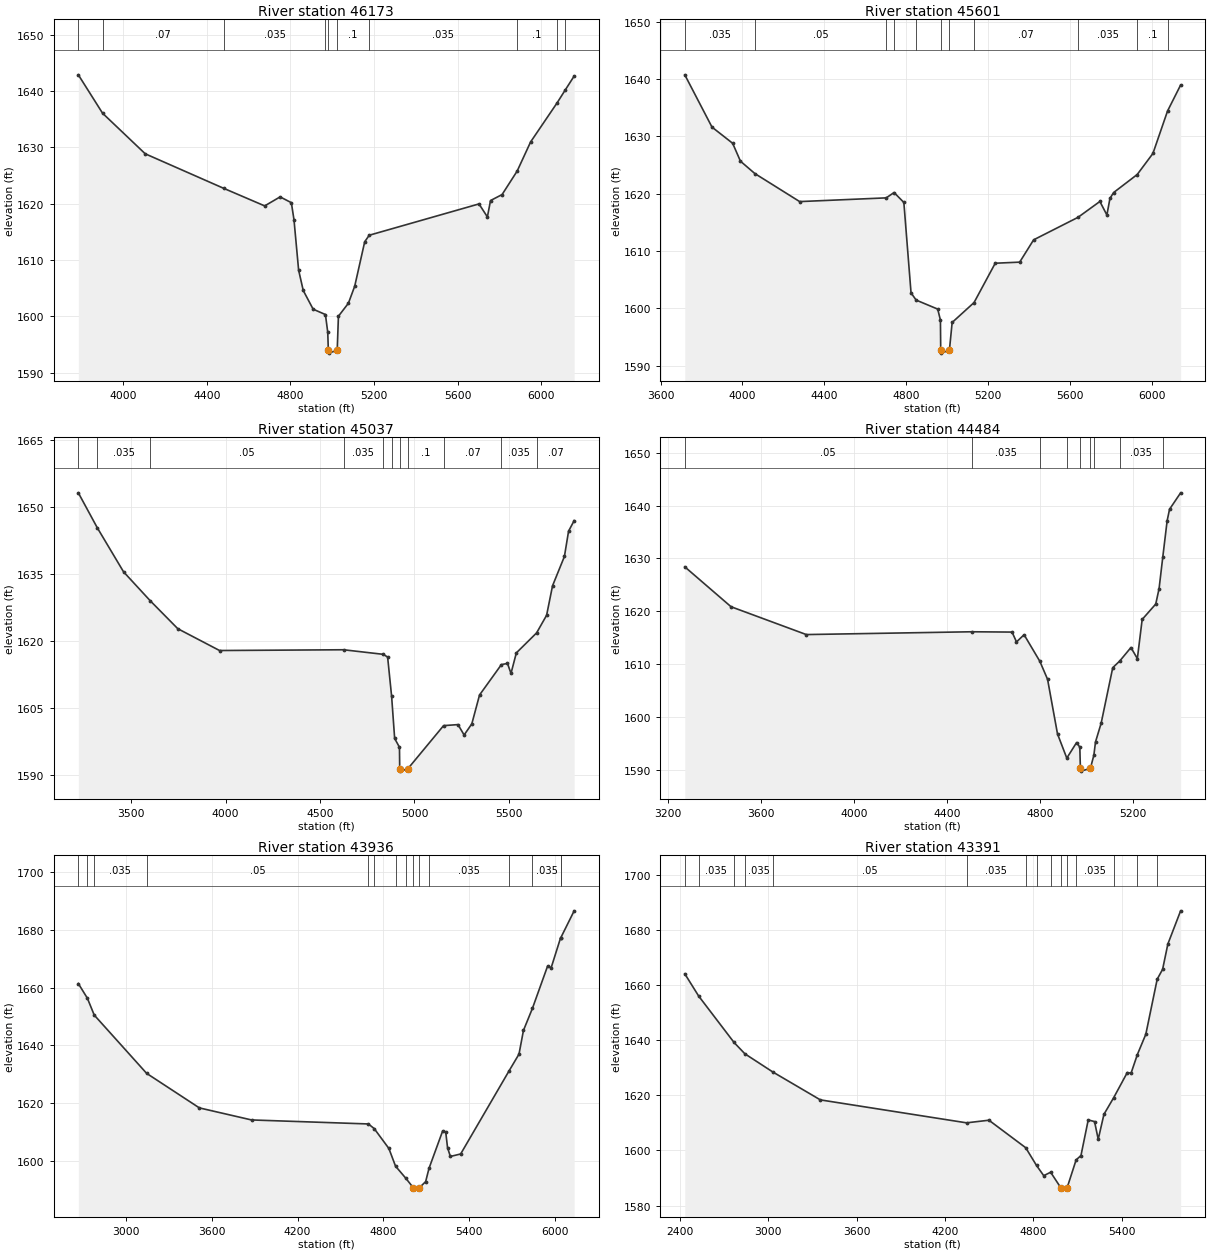
Type RM Length L Ch R = 1 ,46173   ,572,572,572
BEGIN DESCRIPTION:
Verde Creek 79.0
END DESCRIPTION:
XS GIS Cut Line= 3
      1935487.19     13873723.78      1935870.69     13872570.65
      1936316.26     13871501.83
#Sta/Elev= 30
  3784.7 1642.87  3900.8 1636.05  4104.9 1628.85  4479.8 1622.73  4676.7  1619.6
  4750.5  1621.2  4804.3 1620.17  4816.9 1617.15  4839.1 1608.19  4861.2 1604.58
  4908.6 1601.26  4967.4 1600.31  4978.5 1597.16  4981.3 1593.96  4982.3 1593.46
  5023.8 1593.96  5029.6 1600.01  5077.4 1602.32  5107.6 1605.35  5155.4 1613.23
    5177 1614.39  5702.4 1619.95  5742.6 1617.64  5757.6 1620.55  5812.9 1621.61
  5885.2 1625.79  5949.4 1630.95  6076.8 1637.92  6114.4 1640.13  6157.9 1642.65
#Mann= 10 ,-1 , 0
  3784.7    .035       0  3900.8     .07       0  4479.8    .035       0
  4967.4      .1       0  4981.3     .05       0  5023.8      .1       0
    5177    .035       0  5885.2      .1       0  6076.8    .035       0
  6114.4      .1       0
Bank Sta=4981.3,5023.8
XS Rating Curve= 0 ,0
Exp/Cntr=0.3,0.1

Type RM Length L Ch R = 1 ,45601   ,564,564,564
BEGIN DESCRIPTION:
Verde Creek 78.0
END DESCRIPTION:
XS GIS Cut Line= 3
      1935812.11     13873926.49        1936375.       13872775.
      1936384.95     13871633.95
#Sta/Elev= 30
  3718.3  1640.7  3851.2 1631.58  3952.1 1628.76  3990.2 1625.64  4060.6 1623.48
  4279.6 1618.59  4702.5 1619.24  4740.9 1620.17  4788.7 1618.44  4823.8 1602.67
  4848.8 1601.41  4954.1 1599.84  4967.4 1597.92  4968.8 1592.66  4969.8 1592.16
  5011.3 1592.66  5024.7 1597.51  5131.7 1600.98  5235.2 1607.84  5354.7 1608.03
  5422.8 1611.92  5639.5 1615.84  5746.6 1618.61  5780.8 1616.25  5795.8 1619.15
  5813.8 1620.17  5928.9 1623.31  6005.8 1626.99  6077.2 1634.39  6141.1 1638.92
#Mann= 11 ,-1 , 0
  3718.3    .035       0  4060.6     .05       0  4702.5    .035       0
  4740.9     .05       0  4848.8      .1       0  4968.8     .05       0
  5011.3      .1       0  5131.7     .07       0  5639.5    .035       0
  5928.9      .1       0  6077.2    .035       0
Bank Sta=4968.8,5011.3
XS Rating Curve= 0 ,0
Exp/Cntr=0.3,0.1

Type RM Length L Ch R = 1 ,45037   ,553,553,553
BEGIN DESCRIPTION:
Verde Creek 77.0
END DESCRIPTION:
XS GIS Cut Line= 3
      1936004.31     13874336.49        1936875.       13872775.
        1937125.     13871974.99
#Sta/Elev= 30
  3219.9 1653.09    3320  1645.3  3459.4 1635.43  3600.3 1628.98  3746.6 1622.72
  3967.8 1617.84  4624.6 1618.01  4834.7 1616.99    4858 1616.38  4879.2 1607.57
  4895.2 1598.18  4920.7 1596.22    4922 1591.38    4923 1590.88  4964.5 1591.38
  5154.3 1601.05  5230.7 1601.28  5263.1 1598.96  5303.9 1601.45  5344.8  1607.9
  5460.5 1614.69  5492.5 1614.96  5511.4 1612.73  5539.7 1617.31    5647 1621.78
    5700 1625.72  5731.4 1632.31  5794.3 1638.86  5816.3 1644.52  5845.9 1646.88
#Mann= 11 ,-1 , 0
  3219.9     .07       0    3320    .035       0  3600.3     .05       0
  4624.6    .035       0  4834.7      .1       0  4879.2      .1       0
    4922     .05       0  4964.5      .1       0  5154.3     .07       0
  5460.5    .035       0    5647     .07       0
Bank Sta=4922,4964.5
XS Rating Curve= 0 ,0
Exp/Cntr=0.3,0.1

Type RM Length L Ch R = 1 ,44484   ,548,548,548
BEGIN DESCRIPTION:
Verde Creek 76.0
END DESCRIPTION:
XS GIS Cut Line= 3
      1936324.51     13874081.52        1937325.       13872675.
      1937525.02     13872324.97
#Sta/Elev= 30
  3273.9 1628.41  3472.5 1620.87  3795.7 1615.61  4506.4 1616.14  4679.3 1616.08
  4698.3 1614.22  4730.9 1615.58  4798.4 1610.57  4831.7 1607.16  4874.4 1596.83
  4914.3 1592.26  4956.5 1595.21  4970.2 1594.32  4972.7  1590.3  4973.7  1589.8
  5015.5  1590.3  5030.5  1592.8  5037.6 1595.32  5061.8 1598.85  5111.6 1609.35
  5141.8 1610.62  5189.7 1613.16  5217.3 1611.07    5238 1618.47  5296.3 1621.38
  5310.6  1624.3  5326.6  1630.3  5345.2 1637.12  5355.5 1639.29  5403.1  1642.4
#Mann= 9 ,-1 , 0
  3273.9     .05       0  4506.4    .035       0  4798.4     .07       0
  4914.3    .035       0  4972.7    .035       0  5015.5    .035       0
  5030.5      .1       0  5141.8    .035       0  5326.6     .07       0
Bank Sta=4972.7,5015.5
XS Rating Curve= 0 ,0
Exp/Cntr=0.3,0.1

Type RM Length L Ch R = 1 ,43936   ,545,545,545
BEGIN DESCRIPTION:
Verde Creek 75.0
END DESCRIPTION:
XS GIS Cut Line= 4
      1936031.37     13874468.43      1937444.88     13873275.61
        1937775.       13872925.      1938575.01     13872124.99
#Sta/Elev= 30
  2669.1  1661.4  2732.2 1656.33  2780.1 1650.49  3146.1  1630.3  3514.4 1618.34
  3878.5 1614.17  4694.6 1612.78  4735.4 1611.17  4837.7 1604.29  4884.2 1598.17
    4957 1593.91    5008 1590.71    5009 1590.21  5050.8 1590.71  5094.6 1592.81
  5117.8 1597.38  5213.4 1610.37  5234.6 1610.04  5247.3 1604.61    5267 1601.52
  5339.1 1602.39  5677.1 1631.17  5746.4 1636.96  5777.6 1645.18  5840.2 1652.81
  5945.8 1667.41  5971.2 1666.91  6036.3 1677.14  6038.6  1677.3  6131.6 1686.59
#Mann= 15 ,-1 , 0
  2669.1    .035       0  2732.2     .07       0  2780.1    .035       0
  3146.1     .05       0  4694.6    .035       0  4735.4     .05       0
  4884.2     .07       0    4957      .1       0    5008     .05       0
  5050.8      .1       0  5117.8    .035       0  5677.1     .07       0
  5840.2    .035       0  6036.3     .07       0  6038.6    .035       0
Bank Sta=5008,5050.8
XS Rating Curve= 0 ,0
Exp/Cntr=0.3,0.1

Type RM Length L Ch R = 1 ,43391   ,537,537,537
BEGIN DESCRIPTION:
Verde Creek 74.0
END DESCRIPTION:
XS GIS Cut Line= 4
      1936096.18      13874544.2        1937775.       13873425.
        1938225.       13873125.      1938975.01       13872825.
#Sta/Elev= 30
  2434.1 1664.04  2528.2 1655.98  2768.2 1639.17  2841.9 1635.05  3031.2 1628.47
  3354.5 1618.34    4347 1610.02  4498.9 1610.97  4748.6    1601  4821.9 1594.58
    4871 1590.87  4917.9 1592.11  4986.9 1586.49  4987.9 1585.99  5029.8 1586.49
    5091  1596.6  5123.7 1598.15  5173.1 1611.07    5216 1610.48    5241 1604.05
  5279.8 1613.11  5346.3 1619.17  5438.1 1628.24  5463.9 1628.02  5506.8 1634.78
  5564.1 1642.13  5641.4  1662.1  5678.1 1665.66  5713.7 1674.83  5800.4 1686.87
#Mann= 15 ,-1 , 0
  2434.1     .07       0  2528.2    .035       0  2768.2     .05       0
  2841.9    .035       0  3031.2     .05       0    4347    .035       0
  4748.6     .05       0  4821.9     .07       0  4917.9      .1       0
  4986.9     .05       0  5029.8      .1       0    5091    .035       0
  5346.3     .07       0  5506.8    .035       0  5641.4     .07       0
Bank Sta=4986.9,5029.8
XS Rating Curve= 0 ,0
Exp/Cntr=0.3,0.1

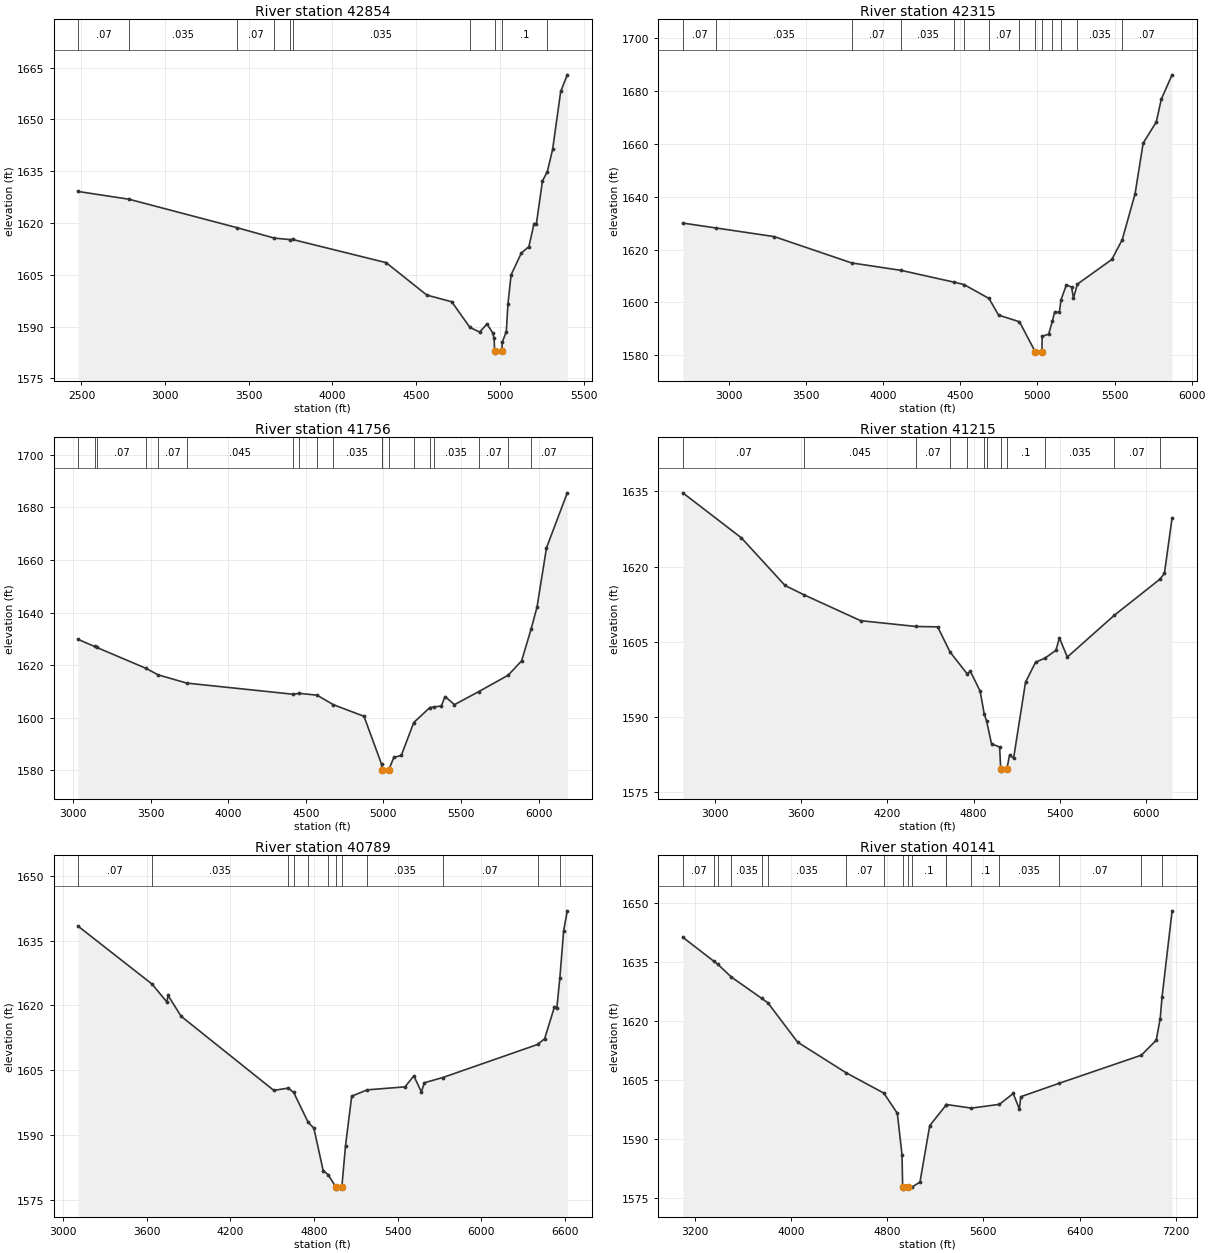
Type RM Length L Ch R = 1 ,42854   ,539,539,539
BEGIN DESCRIPTION:
Verde Creek 73.0
END DESCRIPTION:
XS GIS Cut Line= 4
      1937405.01     13875552.12        1938325.       13873975.
        1938675.       13873375.      1938875.01     13873024.98
#Sta/Elev= 30
  2479.3 1629.11  2783.9 1626.86  3429.1 1618.63  3652.8  1615.6  3746.7 1615.17
    3761 1615.21  4320.3  1608.5  4563.5 1599.11  4712.7 1597.17  4820.7 1589.77
  4879.4  1588.4  4923.2 1590.74  4957.3 1588.17  4965.9 1586.57  4968.6  1582.8
  4969.6  1582.3  5011.8  1582.8  5014.4 1585.47  5038.6 1588.55  5048.4 1596.55
  5067.2 1604.97  5128.4 1611.29  5173.4 1613.13  5204.4 1619.81  5218.3 1619.77
  5254.7 1632.17  5283.5 1634.82  5315.4 1641.31  5363.7 1658.08  5402.9 1662.88
#Mann= 10 ,-1 , 0
  2479.3     .07       0  2783.9    .035       0  3429.1     .07       0
  3652.8    .035       0  3746.7     .07       0    3761    .035       0
  4820.7     .07       0  4968.6    .035       0  5011.8      .1       0
  5283.5     .07       0
Bank Sta=4968.6,5011.8
XS Rating Curve= 0 ,0
Exp/Cntr=0.3,0.1

Type RM Length L Ch R = 1 ,42315   ,559,559,559
BEGIN DESCRIPTION:
Verde Creek 72.0
END DESCRIPTION:
XS GIS Cut Line= 4
      1937428.81     13875570.55        1938625.       13874175.
        1938925.       13873825.      1939274.99     13873025.03
#Sta/Elev= 30
    2701 1630.02    2917 1628.16    3294 1624.89  3795.1 1614.92  4116.1  1612.1
  4462.3 1607.59  4523.2 1606.74    4686 1601.45  4748.1 1595.14  4883.7 1592.62
    4986 1581.23    4987 1580.73  5029.3 1581.23  5030.6 1587.07  5073.2 1587.94
  5097.4 1592.98    5112 1596.39  5141.9  1596.2  5153.4 1601.01  5187.8  1606.6
  5221.4 1605.76  5233.6 1601.64  5259.3 1606.89  5482.5 1616.23  5549.9 1623.72
  5633.1 1641.09  5685.5 1660.31  5770.6 1668.32  5803.4 1677.01  5873.2 1686.21
#Mann= 14 ,-1 , 0
    2701     .07       0    2917    .035       0  3795.1     .07       0
  4116.1    .035       0  4462.3     .07       0  4523.2    .035       0
    4686     .07       0  4883.7      .1       0    4986     .05       0
  5029.3      .1       0  5097.4    .035       0  5153.4      .1       0
  5259.3    .035       0  5549.9     .07       0
Bank Sta=4986,5029.3
XS Rating Curve= 0 ,0
Exp/Cntr=0.3,0.1

Type RM Length L Ch R = 1 ,41756   ,541,541,541
BEGIN DESCRIPTION:
Verde Creek 71.0
END DESCRIPTION:
XS GIS Cut Line= 4
      1937897.87     13875663.29        1939075.       13874675.
        1939225.       13874275.      1939643.64     13873161.49
#Sta/Elev= 30
  3031.5 1629.85  3138.4 1627.12  3151.1  1626.8  3471.9 1618.76  3546.2 1616.37
  3732.8 1613.19  4419.6 1608.95  4456.3  1609.3  4572.6  1608.6  4676.5 1605.01
    4875 1600.56    4988 1582.38  4991.2 1580.21  4992.2 1579.71  5034.5 1580.21
  5067.3 1584.92  5115.4 1585.68  5195.7 1598.19  5299.6 1603.91  5323.4  1604.1
  5373.4  1604.5  5397.4 1608.09  5458.3    1605  5615.3 1609.99  5803.9 1616.17
    5891 1621.66  5952.4 1633.82  5990.3 1642.12  6051.3 1664.64  6185.3 1685.57
#Mann= 19 ,-1 , 0
  3031.5     .07       0  3138.4    .035       0  3151.1     .07       0
  3471.9    .035       0  3546.2     .07       0  3732.8    .045       0
  4419.6     .07       0  4456.3    .045       0  4572.6     .07       0
  4676.5    .035       0    4988      .1       0  4991.2     .05       0
  5034.5      .1       0  5195.7    .035       0  5299.6     .07       0
  5323.4    .035       0  5615.3     .07       0  5803.9    .035       0
  5952.4     .07       0
Bank Sta=4991.2,5034.5
XS Rating Curve= 0 ,0
Exp/Cntr=0.3,0.1

Type RM Length L Ch R = 1 ,41215   ,426,426,426
BEGIN DESCRIPTION:
Verde Creek 70.0
END DESCRIPTION:
XS GIS Cut Line= 4
      1937734.96     13875806.27        1939225.       13874875.
        1939625.       13874625.      1939877.89     13873474.69
#Sta/Elev= 30
  2775.6  1634.7  3183.2 1625.73  3487.5 1616.23  3618.7 1614.38  4013.3 1609.22
  4399.6 1608.06  4549.8 1607.99    4636 1602.98  4755.3 1598.63    4778 1599.11
  4845.9 1595.16  4873.9 1590.64  4890.3 1589.25  4924.8 1584.68  4981.4 1584.03
  4988.9 1579.73  4989.9 1579.23  5032.2 1579.73  5050.5 1582.42  5078.7 1581.82
  5161.8 1596.97  5231.7 1600.94  5297.7 1601.76    5373 1603.31  5397.6 1605.76
  5452.9 1601.97    5778 1610.25  6097.1 1617.48  6128.7 1618.63  6182.2 1629.73
#Mann= 12 ,-1 , 0
  2775.6     .07       0  3618.7    .045       0  4399.6     .07       0
    4636    .035       0  4755.3      .1       0  4873.9     .07       0
  4890.3      .1       0  4988.9     .05       0  5032.2      .1       0
  5297.7    .035       0    5778     .07       0  6097.1    .035       0
Bank Sta=4988.9,5032.2
XS Rating Curve= 0 ,0
Exp/Cntr=0.3,0.1

Type RM Length L Ch R = 1 ,40789   ,648,648,648
BEGIN DESCRIPTION:
Verde Creek 69.0
END DESCRIPTION:
XS GIS Cut Line= 4
      1938574.33     13876311.46      1939759.93     13875039.38
      1939964.79     13874858.25      1940114.17      13873371.8
#Sta/Elev= 30
  3109.1 1638.36  3639.8 1624.95  3745.4 1620.83  3754.7 1622.31  3847.9 1617.51
  4512.3 1600.36  4615.7  1600.9    4655 1599.88  4757.7 1593.03  4799.3 1591.63
  4866.1 1581.82  4901.7 1580.87  4956.6 1578.03  4957.6 1577.53  4999.9 1578.03
  5026.3 1587.61  5070.5 1599.03  5182.1 1600.49  5452.4 1601.18  5515.7 1603.72
    5570 1600.01  5591.1 1602.13  5722.5 1603.33  6402.2 1610.98  6453.4 1612.32
  6522.7 1619.61  6540.8 1619.53    6562 1626.27  6589.1 1637.21  6615.4 1641.89
#Mann= 12 ,-1 , 0
  3109.1     .07       0  3639.8    .035       0  4615.7     .07       0
    4655    .035       0  4757.7     .07       0  4901.7      .1       0
  4956.6     .05       0  4999.9      .1       0  5182.1    .035       0
  5722.5     .07       0  6402.2    .035       0    6562      .1       0
Bank Sta=4956.6,4999.9
XS Rating Curve= 0 ,0
Exp/Cntr=0.3,0.1

Type RM Length L Ch R = 1 ,40141   ,577,577,577
BEGIN DESCRIPTION:
Verde Creek 68.0
END DESCRIPTION:
XS GIS Cut Line= 5
      1938527.32     13876416.52        1939825.       13875675.
        1940175.       13875475.      1940355.74     13875037.21
      1940197.52     13873344.43
#Sta/Elev= 30
  3098.6 1641.37  3359.4 1635.19  3390.3 1634.46  3502.9 1631.21  3755.9 1625.77
  3806.9 1624.64  4053.6 1614.63  4453.6 1606.88  4771.1 1601.63  4883.5 1596.48
  4922.7 1585.92  4927.9 1577.64  4928.9 1577.14    4972 1577.64  5008.6 1577.71
  5072.1 1578.95  5153.2 1593.34  5288.4 1598.53  5292.3 1598.72  5500.5  1597.8
  5733.2 1598.76  5847.8 1601.53    5899 1597.58  5911.1 1600.71  6228.4 1604.11
  6915.1 1611.31    7038 1615.12  7071.1 1620.63  7086.2 1626.05  7170.1 1648.11
#Mann= 18 ,-1 , 0
  3098.6     .07       0  3359.4    .035       0  3390.3     .07       0
  3502.9    .035       0  3755.9     .07       0  3806.9    .035       0
  4453.6     .07       0  4771.1      .1       0  4927.9     .05       0
    4972      .1       0  5008.6      .1       0  5288.4     .07       0
  5292.3    .035       0  5500.5      .1       0  5733.2    .035       0
  6228.4     .07       0  6915.1    .035       0  7086.2      .1       0
Bank Sta=4927.9,4972
XS Rating Curve= 0 ,0
Exp/Cntr=0.3,0.1

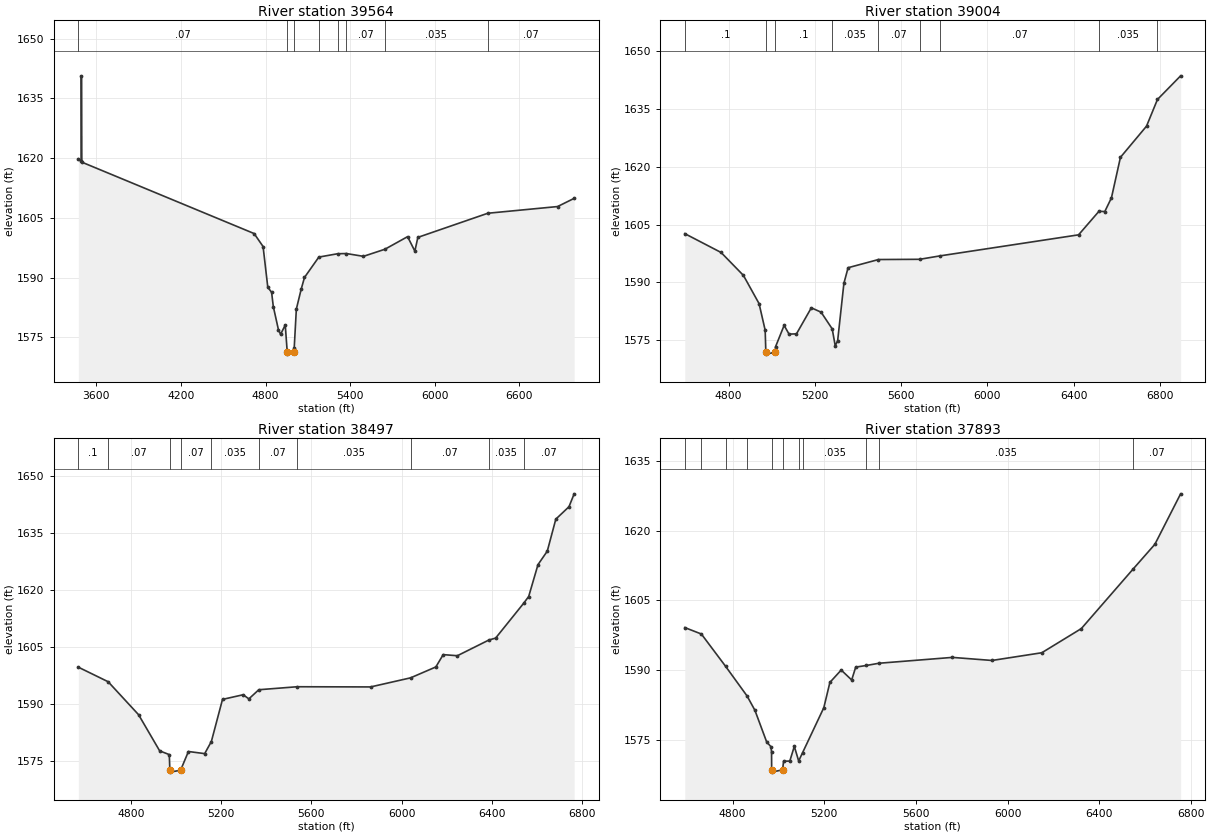
Type RM Length L Ch R = 1 ,39564   ,560,560,560
BEGIN DESCRIPTION:
Verde Creek 67.0
END DESCRIPTION:
XS GIS Cut Line= 4
      1940435.06     13877094.55        1940575.       13875975.
        1940625.       13875575.      1940334.04     13873612.93
#Sta/Elev= 30
  3472.9 1619.82  3492.6  1619.2  3494.6 1640.68  3497.7    1619  4719.1 1601.07
  4782.6 1597.81    4816 1587.57    4843 1586.32  4855.1 1582.73  4891.4 1576.92
  4906.5 1575.76  4939.8  1578.1  4953.8 1571.29  4954.8 1570.79  4998.4 1571.29
  5003.3 1572.33  5018.4  1582.1  5053.1 1587.15  5076.1 1590.05  5177.8 1595.16
  5310.9    1596  5372.8 1596.05  5494.2 1595.35  5646.2 1597.13    5807 1600.29
  5858.5 1596.66  5879.8 1600.11  6375.9 1606.17  6870.3 1607.85  6987.8 1609.91
#Mann= 8 ,-1 , 0
  3472.9     .07       0  4953.8     .05       0  4998.4     .07       0
  5177.8     .07       0  5310.9    .035       0  5372.8     .07       0
  5646.2    .035       0  6375.9     .07       0
Bank Sta=4953.8,4998.4
XS Rating Curve= 0 ,0
Exp/Cntr=0.3,0.1

Type RM Length L Ch R = 1 ,39004   ,507,507,507
BEGIN DESCRIPTION:
Verde Creek 66.0
END DESCRIPTION:
XS GIS Cut Line= 3
        1940875.       13876175.        1941075.       13875825.
      1942250.54      13874337.3
#Sta/Elev= 30
  4596.9 1602.66  4765.1 1597.78  4868.7 1591.84  4941.3 1584.53  4969.6 1577.63
  4972.7 1571.94  4973.7 1571.44  5017.3 1571.94  5017.5 1573.32  5057.4 1578.88
  5080.3 1576.63  5114.7 1576.69  5183.6 1583.44  5228.9 1582.31  5280.5 1577.98
  5294.4  1573.6  5305.7 1574.91  5334.7 1589.79  5354.1 1593.83    5495 1595.95
  5686.2 1596.01  5780.7  1596.9  6422.9 1602.35  6517.4 1608.45  6544.4 1608.38
  6575.3 1611.93    6617 1622.43    6738 1630.51  6788.6 1637.42  6896.1 1643.55
#Mann= 9 ,-1 , 0
  4596.9      .1       0  4972.7     .05       0  5017.3      .1       0
  5280.5    .035       0    5495     .07       0  5686.2    .035       0
  5780.7     .07       0  6517.4    .035       0  6788.6     .07       0
Bank Sta=4972.7,5017.3
XS Rating Curve= 0 ,0
Exp/Cntr=0.3,0.1

Type RM Length L Ch R = 1 ,38497   ,604,604,604
BEGIN DESCRIPTION:
Verde Creek 65.0
END DESCRIPTION:
XS GIS Cut Line= 3
      1941324.99     13876525.03      1941458.41       13876129.
        1942325.     13874574.99
#Sta/Elev= 30
  4567.2 1599.66  4699.3 1595.82  4834.2 1587.12  4927.6 1577.59  4970.3  1576.6
  4972.8 1572.48  4973.8 1571.98  5020.3 1572.48  5055.1 1577.42  5127.1 1576.86
  5156.7 1580.05  5206.1 1591.16  5297.6 1592.39  5322.9  1591.3  5366.9 1593.71
  5537.1  1594.5  5862.4 1594.45  6039.7 1596.85  6151.5 1599.72  6184.1 1602.97
  6246.9 1602.68  6386.4 1606.82  6416.4 1607.33  6540.4  1616.5  6562.9  1618.3
  6604.1  1626.7  6645.3 1630.26  6683.1  1638.7  6741.5 1641.98  6764.4 1645.38
#Mann= 10 ,-1 , 0
  4567.2      .1       0  4699.3     .07       0  4972.8     .05       0
  5020.3     .07       0  5156.7    .035       0  5366.9     .07       0
  5537.1    .035       0  6039.7     .07       0  6386.4    .035       0
  6540.4     .07       0
Bank Sta=4972.8,5020.3
XS Rating Curve= 0 ,0
Exp/Cntr=0.3,0.1

Type RM Length L Ch R = 1 ,37893   ,588,588,588
BEGIN DESCRIPTION:
Verde Creek 64.0
END DESCRIPTION:
XS GIS Cut Line= 3
        1941375.       13876575.        1941775.       13876525.
      1942693.61     13875024.24
#Sta/Elev= 30
  4591.3 1599.15  4663.6 1597.76  4769.1 1590.82    4863 1584.42  4897.2 1581.34
  4948.6 1574.51  4966.7 1573.53  4969.7 1572.44  4970.2 1568.54  4971.2 1568.04
  5017.7 1568.54  5022.2 1570.39  5049.3 1570.42    5069 1573.58    5088 1570.44
  5104.7 1572.19  5197.7 1581.91  5224.2 1587.35  5273.5 1590.01  5319.2 1587.87
  5336.8 1590.64  5383.3 1590.99  5437.9 1591.47  5758.4 1592.73  5931.2 1592.07
  6148.5 1593.73  6320.9 1598.93  6546.7 1611.74  6641.7 1617.07    6754 1627.93
#Mann= 11 ,-1 , 0
  4591.3      .1       0  4663.6     .07       0  4769.1      .1       0
    4863     .07       0  4970.2     .05       0  5017.7     .07       0
    5088      .1       0  5104.7    .035       0  5383.3     .07       0
  5437.9    .035       0  6546.7     .07       0
Bank Sta=4970.2,5017.7
XS Rating Curve= 0 ,0
Exp/Cntr=0.3,0.1