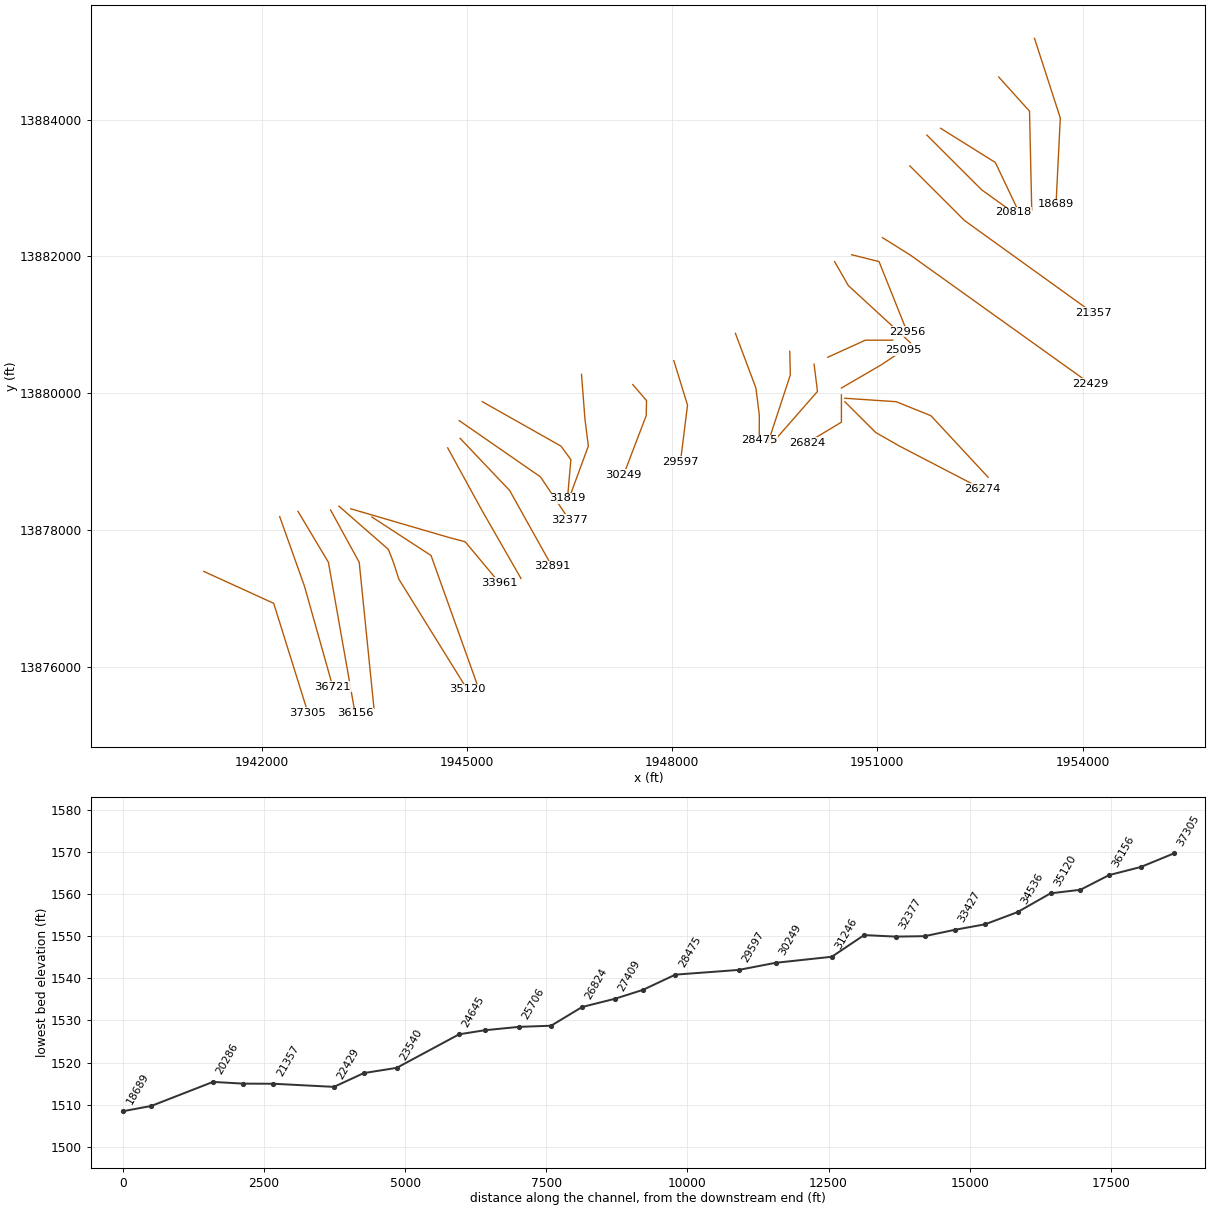
HEC-RAS study Verde Creek.prj: Verde Creek Base Level Engineering

--- Verde Creek.g01 (geometry) --- (continued)

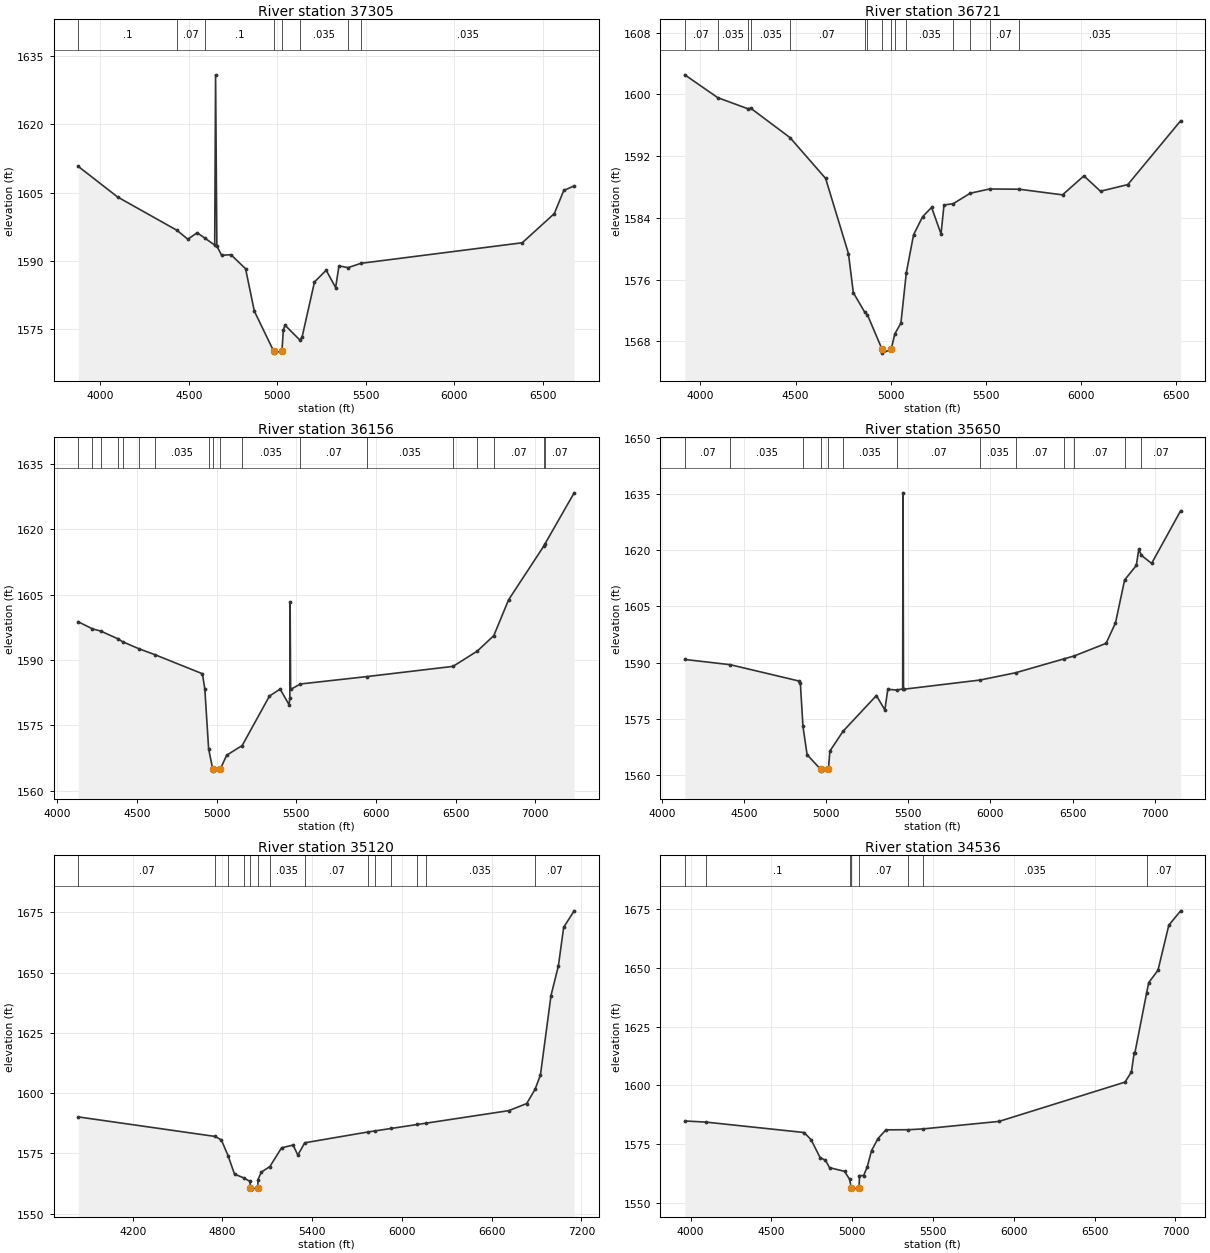
Type RM Length L Ch R = 1 ,37305   ,584,584,584
BEGIN DESCRIPTION:
Verde Creek 63.0
END DESCRIPTION:
XS GIS Cut Line= 3
      1941152.19     13877391.88        1942175.       13876925.
      1942674.99     13875325.03
#Sta/Elev= 30
  3875.4 1610.74  4097.9 1604.01  4432.8 1596.69    4494 1594.74  4546.4 1596.16
    4591 1594.96  4645.7 1593.45  4650.6 1630.89  4657.8 1593.25  4684.8 1591.21
  4737.6 1591.33    4820 1588.25  4869.5 1578.93    4978 1570.19    4979 1569.69
  5025.6 1570.19  5033.3 1574.76  5042.7 1575.83  5126.9 1572.56    5139 1573.18
  5209.3 1585.34  5275.3 1587.92  5328.7 1584.11  5347.6 1588.88  5398.9 1588.49
  5471.4 1589.44  6382.7 1593.96  6563.9 1600.37  6617.4 1605.47    6676 1606.46
#Mann= 8 ,-1 , 0
  3875.4      .1       0  4432.8     .07       0    4591      .1       0
    4978     .05       0  5025.6      .1       0  5126.9    .035       0
  5398.9     .07       0  5471.4    .035       0
Bank Sta=4978,5025.6
XS Rating Curve= 0 ,0
Exp/Cntr=0.3,0.1

Type RM Length L Ch R = 1 ,36721   ,565,565,565
BEGIN DESCRIPTION:
Verde Creek 62.0
END DESCRIPTION:
XS GIS Cut Line= 3
      1942262.18      13878194.7        1942625.       13877175.
      1943038.05     13875707.55
#Sta/Elev= 30
  3917.6 1602.55  4090.9 1599.59  4247.3 1598.17    4265 1598.21  4470.8 1594.41
  4657.9 1589.12  4778.1 1579.37  4803.6 1574.31  4862.5 1571.83  4877.6 1571.45
  4954.8 1566.97  4955.8 1566.47  5002.6 1566.97  5021.8 1568.96  5053.9 1570.38
  5082.2 1576.88  5120.3 1581.81  5168.2 1584.17  5215.2 1585.36  5264.8 1581.92
  5280.4 1585.68  5328.5 1585.84  5418.4  1587.2  5519.6 1587.75  5675.2 1587.72
  5903.4 1586.99  6015.9 1589.45  6103.2 1587.46  6246.6 1588.32  6524.4 1596.59
#Mann= 15 ,-1 , 0
  3917.6     .07       0  4090.9    .035       0  4247.3     .07       0
    4265    .035       0  4470.8     .07       0  4862.5    .035       0
  4877.6     .07       0  4954.8     .05       0  5002.6     .07       0
  5021.8      .1       0  5082.2    .035       0  5328.5     .07       0
  5418.4    .035       0  5519.6     .07       0  5675.2    .035       0
Bank Sta=4954.8,5002.6
XS Rating Curve= 0 ,0
Exp/Cntr=0.3,0.1

Type RM Length L Ch R = 1 ,36156   ,506,506,506
BEGIN DESCRIPTION:
Verde Creek 61.0
END DESCRIPTION:
XS GIS Cut Line= 3
      1942530.55     13878269.65        1942975.       13877525.
        1943365.     13875314.74
#Sta/Elev= 30
  4132.8 1598.77  4220.6 1597.16  4273.4 1596.64  4384.8 1594.81    4410 1594.21
    4514 1592.57  4612.1 1591.25  4911.4 1586.86  4926.6 1583.37  4950.5 1569.63
  4976.1 1565.03  4977.1 1564.53  5023.9 1565.03    5064 1568.19  5161.1  1570.4
  5332.1 1581.74  5399.1 1583.34  5455.4 1579.75    5460  1581.3    5462 1603.26
  5465.1 1583.26  5526.1 1584.51  5946.6 1586.22  6484.3 1588.55  6636.4 1592.05
    6740 1595.59  6832.9 1603.81  7055.4 1616.22  7061.6 1616.66  7244.4 1628.34
#Mann= 18 ,-1 , 0
  4132.8    .035       0  4220.6     .07       0  4273.4    .035       0
  4384.8     .07       0    4410    .035       0    4514     .07       0
  4612.1    .035       0  4950.5      .1       0  4976.1     .05       0
  5023.9      .1       0  5161.1    .035       0  5526.1     .07       0
  5946.6    .035       0  6484.3     .07       0  6636.4    .035       0
    6740     .07       0  7055.4    .035       0  7061.6     .07       0
Bank Sta=4976.1,5023.9
XS Rating Curve= 0 ,0
Exp/Cntr=0.3,0.1

Type RM Length L Ch R = 1 ,35650   ,530,530,530
BEGIN DESCRIPTION:
Verde Creek 60.0
END DESCRIPTION:
XS GIS Cut Line= 3
       1943007.2      13878289.3        1943425.       13877525.
      1943640.99     13875388.53
#Sta/Elev= 30
  4139.1 1590.84  4415.9 1589.44  4835.8 1585.07  4842.6  1584.5  4858.4    1573
  4883.6 1565.44  4965.7 1561.55  4966.7 1561.05  5013.5 1561.55  5022.2 1566.39
  5102.3 1571.67  5305.6 1581.22  5356.9 1577.37    5375 1582.89  5428.7 1582.68
  5465.5 1582.98  5467.5 1635.29  5470.5 1582.89  5936.9 1585.35  6154.3 1587.31
    6450 1591.03  6511.3  1591.8  6703.7 1595.14    6761 1600.59  6816.5 1612.04
  6887.7 1615.92  6902.8 1620.21  6919.2 1618.59  6981.1 1616.47  7157.5  1630.5
#Mann= 13 ,-1 , 0
  4139.1     .07       0  4415.9    .035       0  4858.4      .1       0
  4965.7     .05       0  5013.5      .1       0  5102.3    .035       0
  5428.7     .07       0  5936.9    .035       0  6154.3     .07       0
    6450    .035       0  6511.3     .07       0  6816.5      .1       0
  6919.2     .07       0
Bank Sta=4965.7,5013.5
XS Rating Curve= 0 ,0
Exp/Cntr=0.3,0.1

Type RM Length L Ch R = 1 ,35120   ,584,584,584
BEGIN DESCRIPTION:
Verde Creek 59.0
END DESCRIPTION:
XS GIS Cut Line= 5
      1943128.29     13878346.24      1943851.81     13877713.85
        1943925.       13877525.      1944005.62     13877276.85
      1945001.57     13875669.37
#Sta/Elev= 30
  3836.5 1590.15  4751.8 1582.05  4792.7 1580.62  4838.1 1574.03  4880.9  1566.4
  4942.3 1564.88  4983.9 1563.39  4987.5  1560.7  4988.5  1560.2  5035.7  1560.7
  5037.8 1564.15    5060 1567.25  5117.2 1569.57  5195.5 1577.34  5272.5 1578.48
  5304.2 1574.34  5350.6 1579.42  5772.5  1583.9  5816.9 1584.32  5930.4 1585.39
  6103.2 1587.01    6159 1587.53  6714.7 1592.76  6834.7 1595.71  6890.5  1601.6
  6926.5 1607.56  6997.1 1640.51  7046.5 1652.82  7081.8 1668.82  7151.9 1675.64
#Mann= 14 ,-1 , 0
  3836.5     .07       0  4751.8      .1       0  4838.1     .07       0
  4942.3      .1       0  4987.5     .05       0  5035.7      .1       0
  5117.2    .035       0  5350.6     .07       0  5772.5    .035       0
  5816.9     .07       0  5930.4    .035       0  6103.2     .07       0
    6159    .035       0  6890.5     .07       0
Bank Sta=4987.5,5035.7
XS Rating Curve= 0 ,0
Exp/Cntr=0.3,0.1

Type RM Length L Ch R = 1 ,34536   ,575,575,575
BEGIN DESCRIPTION:
Verde Creek 58.0
END DESCRIPTION:
XS GIS Cut Line= 3
      1943610.13     13878188.21        1944475.       13877625.
      1945160.67     13875708.02
#Sta/Elev= 30
  3963.8  1584.8    4093 1584.33  4701.8 1579.88  4744.8 1576.87  4801.2 1569.16
  4834.3 1568.06  4859.3  1564.9  4952.4 1563.32  4983.8  1559.9  4993.9 1556.24
  4994.9 1555.74  5042.2 1556.24  5044.7 1561.52  5070.2 1561.51  5092.6 1565.18
  5119.3 1572.17  5159.4 1577.31  5208.4 1581.02  5346.6 1581.07  5438.7 1581.42
  5908.4 1584.62  6687.7 1601.37  6727.4 1605.71  6743.8 1613.57  6749.2 1613.97
    6821 1639.23  6834.3 1643.77  6891.7 1649.07  6958.6 1668.25  7031.8  1674.4
#Mann= 8 ,-1 , 0
  3963.8     .07       0    4093      .1       0  4983.8     .07       0
  4993.9     .05       0  5042.2     .07       0  5346.6     .07       0
  5438.7    .035       0    6821     .07       0
Bank Sta=4993.9,5042.2
XS Rating Curve= 0 ,0
Exp/Cntr=0.3,0.1

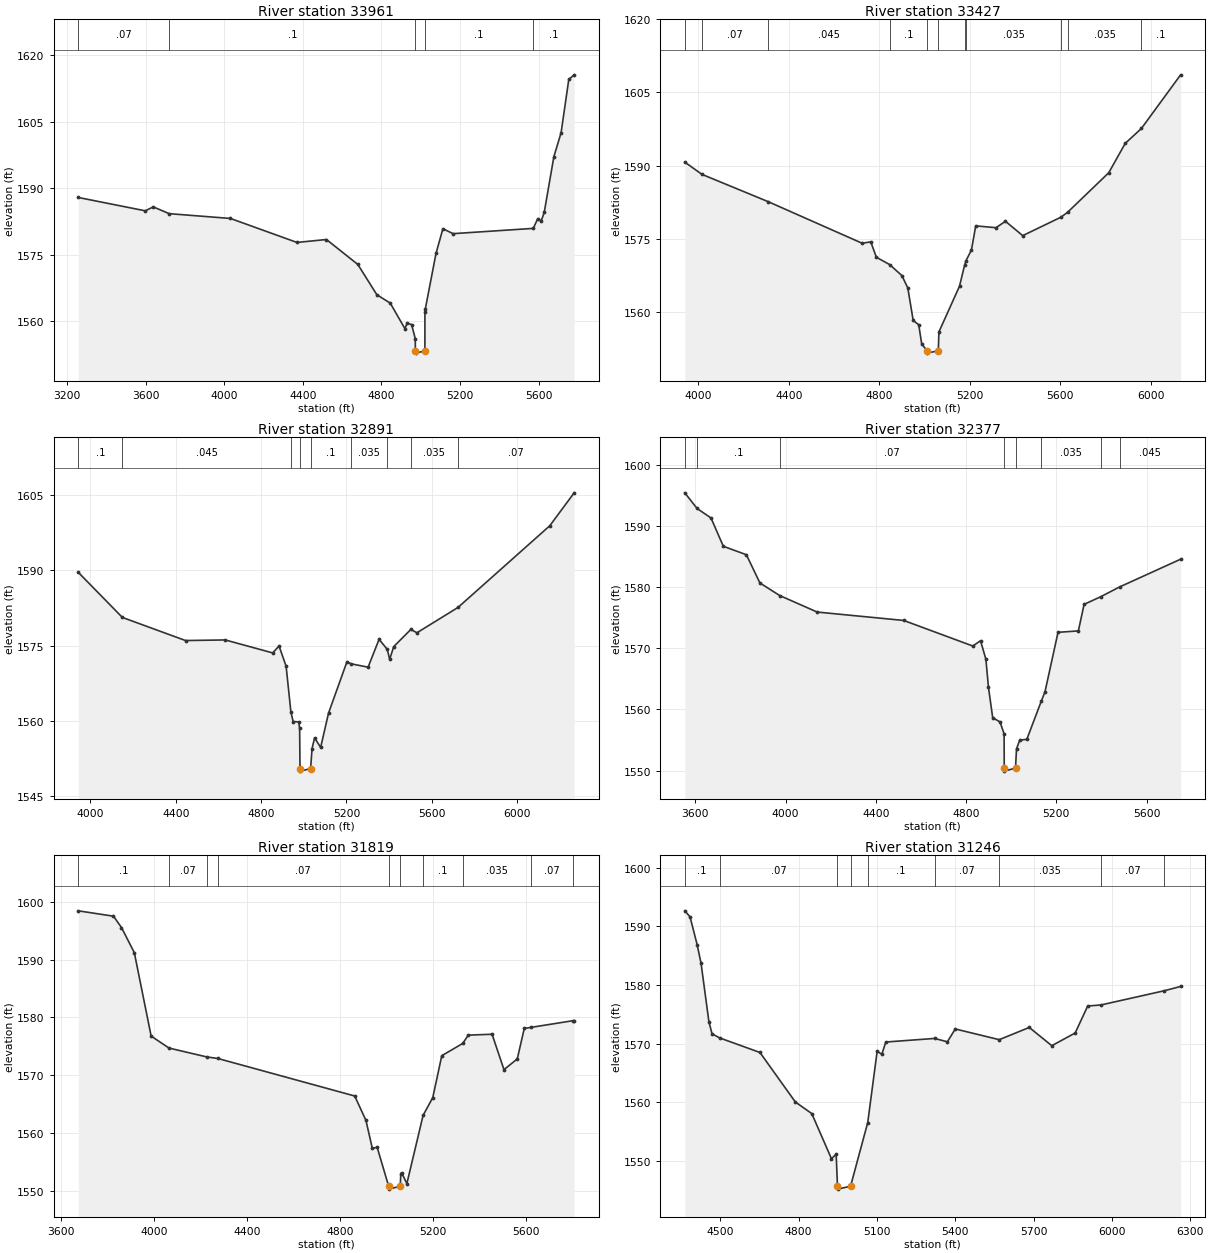
Type RM Length L Ch R = 1 ,33961   ,534,534,534
BEGIN DESCRIPTION:
Verde Creek 57.0
END DESCRIPTION:
XS GIS Cut Line= 4
      1943301.82     13878308.09      1944726.44     13877891.44
        1944975.       13877825.        1945475.     13877225.01
#Sta/Elev= 30
  3258.2 1587.95  3599.1 1584.94  3639.3 1585.83  3720.6  1584.3    4032 1583.22
  4370.5 1577.81  4520.5 1578.47  4680.1 1572.85  4776.8 1566.02  4845.1 1564.12
  4919.6 1558.38  4931.6 1559.61  4953.7 1559.28  4972.4 1556.12  4973.1 1553.34
  4974.1 1552.84  5021.4 1553.34  5021.5 1562.15  5023.2 1562.72  5077.9 1575.32
    5113 1580.91  5164.7 1579.79  5572.9 1580.98  5595.8  1583.2  5612.9 1582.61
  5628.5 1584.58  5677.6 1597.15  5714.4 1602.57  5753.5 1614.59  5780.8 1615.62
#Mann= 5 ,-1 , 0
  3258.2     .07       0  3720.6      .1       0  4973.1     .05       0
  5021.4      .1       0  5572.9      .1       0
Bank Sta=4973.1,5021.4
XS Rating Curve= 0 ,0
Exp/Cntr=0.3,0.1

Type RM Length L Ch R = 1 ,33427   ,536,536,536
BEGIN DESCRIPTION:
Verde Creek 56.0
END DESCRIPTION:
XS GIS Cut Line= 3
      1944719.11     13879199.06        1945225.       13878275.
      1945790.16     13877288.61
#Sta/Elev= 30
  3940.8  1590.7  4016.7 1588.19  4309.9 1582.58  4724.1 1574.07  4762.3 1574.35
  4787.2 1571.19  4845.6  1569.7  4899.7 1567.44  4925.9  1564.9  4949.8 1558.23
  4974.1 1557.36  4987.4 1553.42  5010.8 1552.04  5011.8 1551.54  5060.6 1552.04
  5063.4 1555.89  5154.4 1565.27  5176.5 1569.52  5182.9 1570.48  5207.2  1572.7
  5225.9 1577.63  5315.8 1577.26  5357.3 1578.57  5433.6 1575.63  5602.7 1579.42
  5631.4  1580.4  5813.7 1588.53  5886.3 1594.54  5957.8  1597.6  6131.1  1608.6
#Mann= 11 ,-1 , 0
  3940.8      .1       0  4016.7     .07       0  4309.9    .045       0
  4845.6      .1       0  5010.8     .05       0  5060.6      .1       0
  5176.5      .1       0  5182.9    .035       0  5602.7     .07       0
  5631.4    .035       0  5957.8      .1       0
Bank Sta=5010.8,5060.6
XS Rating Curve= 0 ,0
Exp/Cntr=0.3,0.1

Type RM Length L Ch R = 1 ,32891   ,514,514,514
BEGIN DESCRIPTION:
Verde Creek 55.0
END DESCRIPTION:
XS GIS Cut Line= 3
      1944900.46     13879338.65        1945625.       13878575.
      1946244.39     13877464.18
#Sta/Elev= 30
  3943.1 1589.56  4149.5  1580.6  4445.8    1576  4631.9 1576.12  4854.2 1573.54
  4884.1 1574.91  4917.2  1570.9  4939.5 1561.84  4950.1 1559.89  4976.3 1559.81
  4980.6 1558.51  4982.3 1550.52  4983.3 1550.02  5032.1 1550.52  5038.8 1554.52
  5050.7 1556.64  5079.1 1554.73    5116 1561.55  5202.3 1571.77    5222 1571.37
  5301.5  1570.7    5353 1576.24  5391.2 1574.26  5402.7 1572.27  5421.7 1574.79
  5501.9 1578.21  5530.6 1577.55  5723.2 1582.59  6153.3 1598.84  6267.6 1605.39
#Mann= 9 ,-1 , 0
  3943.1      .1       0  4149.5    .045       0  4939.5      .1       0
  4982.3     .05       0  5032.1      .1       0    5222    .035       0
  5391.2     .07       0  5501.9    .035       0  5723.2     .07       0
Bank Sta=4982.3,5032.1
XS Rating Curve= 0 ,0
Exp/Cntr=0.3,0.1

Type RM Length L Ch R = 1 ,32377   ,558,558,558
BEGIN DESCRIPTION:
Verde Creek 54.0
END DESCRIPTION:
XS GIS Cut Line= 3
      1944886.19     13879598.64        1946075.       13878775.
      1946492.44     13878150.18
#Sta/Elev= 30
  3553.5 1595.41    3608 1592.85  3669.6  1591.3  3724.3 1586.67  3826.5 1585.29
  3886.5 1580.67  3974.3 1578.62  4140.4 1575.92  4523.6 1574.55  4830.1 1570.37
  4864.4 1571.24  4888.1  1568.2  4899.5  1563.6  4918.3 1558.64  4950.6 1557.97
  4968.8 1556.01  4969.4 1550.42  4970.4 1549.92  5019.3 1550.42  5023.8 1553.56
  5038.2    1555  5069.4 1555.11  5133.5 1561.34  5150.1  1562.9  5207.8 1572.61
    5298 1572.84  5323.3 1577.18  5397.2 1578.43  5480.3 1580.02  5751.2 1584.56
#Mann= 8 ,-1 , 0
  3553.5     .07       0    3608      .1       0  3974.3     .07       0
  4969.4     .05       0  5019.3     .07       0  5133.5    .035       0
  5397.2     .07       0  5480.3    .045       0
Bank Sta=4969.4,5019.3
XS Rating Curve= 0 ,0
Exp/Cntr=0.3,0.1

Type RM Length L Ch R = 1 ,31819   ,573,573,573
BEGIN DESCRIPTION:
Verde Creek 53.0
END DESCRIPTION:
XS GIS Cut Line= 4
      1945224.97     13879875.01        1946375.       13879225.
       1946519.6     13879026.96      1946470.32     13878463.34
#Sta/Elev= 30
  3673.7 1598.42  3824.9 1597.49  3859.3 1595.53  3914.5 1591.18  3986.8 1576.75
  4063.7 1574.68  4225.7 1573.15  4273.4 1572.88  4862.1 1566.39  4910.4 1562.17
  4937.9 1557.31  4958.6 1557.52  5008.1 1550.78  5009.1 1550.28    5058 1550.78
  5060.3 1552.97  5064.1 1553.11  5086.3 1551.23  5156.1 1563.03  5197.8 1566.12
  5236.5 1573.36  5326.9 1575.49  5350.3 1576.92  5452.7 1577.07  5503.9 1570.95
  5561.1  1572.8  5591.2 1578.07  5620.3 1578.26  5801.4 1579.42  5805.7  1579.4
#Mann= 10 ,-1 , 0
  3673.7      .1       0  4063.7     .07       0  4225.7      .1       0
  4273.4     .07       0  5008.1     .05       0    5058     .07       0
  5156.1      .1       0  5326.9    .035       0  5620.3     .07       0
  5801.4    .045       0
Bank Sta=5008.1,5058
XS Rating Curve= 0 ,0
Exp/Cntr=0.3,0.1

Type RM Length L Ch R = 1 ,31246   ,997,997,997
BEGIN DESCRIPTION:
Verde Creek 52.0
END DESCRIPTION:
XS GIS Cut Line= 4
        1946675.     13880275.01        1946725.       13879625.
        1946775.       13879225.      1946483.46       13878433.
#Sta/Elev= 30
    4364 1592.67    4384 1591.65  4411.2  1586.9  4426.2 1583.73  4456.3 1573.73
  4468.3 1571.67  4497.4 1570.96  4651.9 1568.47  4787.3 1560.02  4850.4 1558.03
  4925.7 1550.32  4943.7  1551.1  4948.8 1545.63  4949.8 1545.13  4998.9 1545.63
  5064.7 1556.51  5100.6 1568.66  5118.7 1568.18  5133.8 1570.26  5320.6 1570.87
  5369.7  1570.3  5399.9 1572.49  5568.3 1570.66  5683.3 1572.75  5769.6 1569.63
  5859.1  1571.8  5907.1 1576.41    5958 1576.59  6199.6 1579.01    6263 1579.75
#Mann= 9 ,-1 , 0
    4364      .1       0  4497.4     .07       0  4948.8     .05       0
  4998.9     .07       0  5064.7      .1       0  5320.6     .07       0
  5568.3    .035       0    5958     .07       0  6199.6    .045       0
Bank Sta=4948.8,4998.9
XS Rating Curve= 0 ,0
Exp/Cntr=0.3,0.1

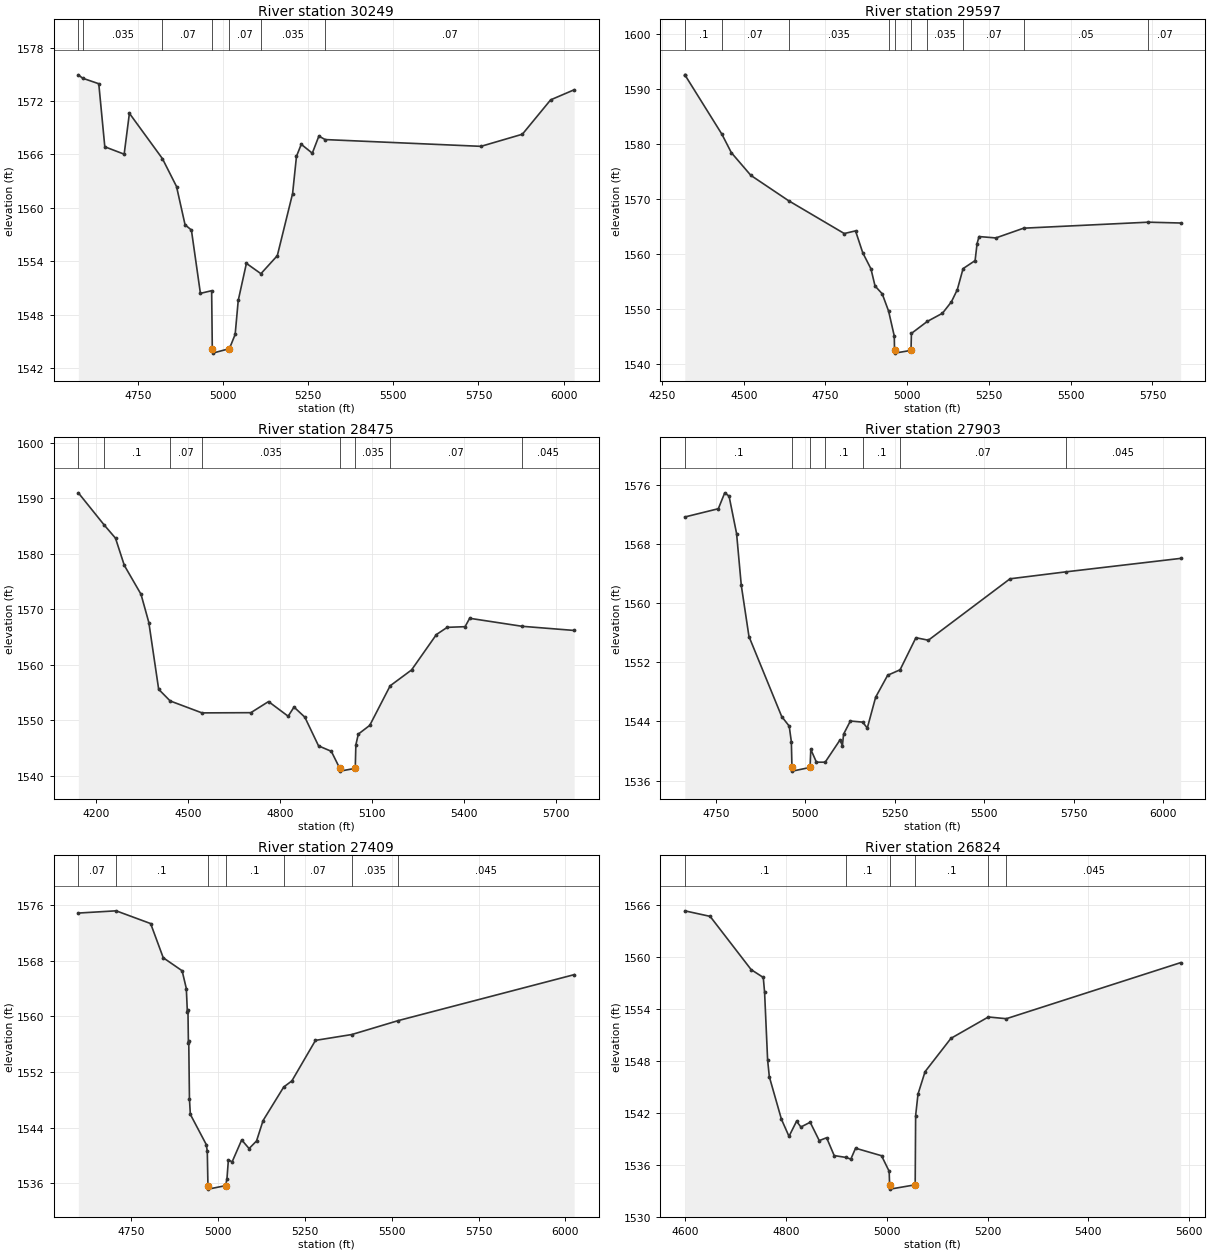
Type RM Length L Ch R = 1 ,30249   ,652,652,652
BEGIN DESCRIPTION:
Verde Creek 50.0
END DESCRIPTION:
XS GIS Cut Line= 4
      1947424.99     13880125.01      1947625.73     13879890.82
      1947621.25     13879671.25      1947290.52     13878804.99
#Sta/Elev= 30
  4575.6 1574.94  4588.2 1574.56  4635.6 1573.94  4653.3 1566.86  4710.1 1566.03
  4725.5 1570.62  4822.4 1565.53  4863.8  1562.4  4888.9  1558.1  4907.5 1557.51
  4933.9  1550.4  4966.9  1550.7  4968.8 1544.19  4969.8 1543.69    5019 1544.19
  5035.9 1545.79  5044.9  1549.6  5068.9 1553.77  5111.5 1552.61  5159.6 1554.63
  5204.5 1561.61  5215.9 1565.79  5229.9 1567.14  5262.3 1566.14  5281.6 1568.06
    5300 1567.67  5757.4 1566.91  5878.9 1568.27  5961.9 1572.13  6030.9 1573.26
#Mann= 7 ,-1 , 0
  4575.6      .1       0  4588.2    .035       0  4822.4     .07       0
  4968.8     .05       0    5019     .07       0  5111.5    .035       0
    5300     .07       0
Bank Sta=4968.8,5019
XS Rating Curve= 0 ,0
Exp/Cntr=0.3,0.1

Type RM Length L Ch R = 1 ,29597   ,1122,1122,1122
BEGIN DESCRIPTION:
Verde Creek 49.0
END DESCRIPTION:
XS GIS Cut Line= 3
      1948024.99     13880475.04        1948225.       13879825.
      1948121.74     13878995.32
#Sta/Elev= 30
  4319.9 1592.54  4320.2 1592.53  4433.4 1581.75  4462.2 1578.41  4521.9 1574.28
  4637.3 1569.68  4807.5 1563.72    4842  1564.2    4864 1560.24  4889.1 1557.31
  4901.7 1554.19  4923.6 1552.77  4943.1 1549.63  4960.5  1545.1  4961.2  1542.5
  4962.2    1542  5011.6  1542.5  5012.9 1545.58  5061.5 1547.76  5107.8 1549.24
  5135.1 1551.31  5153.2 1553.52  5170.9 1557.35  5207.6  1558.8  5213.7  1561.9
  5219.7 1563.17    5271 1562.92    5356 1564.69    5737 1565.78  5836.1 1565.63
#Mann= 11 ,-1 , 0
  4319.9    .035       0  4320.2      .1       0  4433.4     .07       0
  4637.3    .035       0  4943.1     .07       0  4961.2     .05       0
  5011.6     .07       0  5061.5    .035       0  5170.9     .07       0
    5356     .05       0    5737     .07       0
Bank Sta=4961.2,5011.6
XS Rating Curve= 0 ,0
Exp/Cntr=0.3,0.1

Type RM Length L Ch R = 1 ,28475   ,572,572,572
BEGIN DESCRIPTION:
Verde Creek 48.0
END DESCRIPTION:
XS GIS Cut Line= 4
        1948925.     13880874.99        1949225.       13880075.
        1949275.       13879675.      1949273.09     13879313.01
#Sta/Elev= 30
  4141.1 1591.01  4225.5 1585.22  4262.5 1582.84  4291.3 1577.94  4345.8 1572.74
  4371.4 1567.65  4403.5 1555.62  4441.1 1553.52    4545 1551.37  4704.6 1551.41
  4762.3 1553.41  4826.4 1550.77  4845.6 1552.42  4880.9  1550.6  4925.7 1545.43
  4967.4 1544.45    4995 1541.38    4996 1540.88  5045.6 1541.38  5047.6 1545.61
  5055.6 1547.55  5092.9 1549.12  5159.6 1556.25  5229.4  1559.1  5310.6 1565.48
  5345.9 1566.78  5404.3  1566.9  5419.3 1568.41  5590.4 1566.97  5760.6 1566.22
#Mann= 8 ,-1 , 0
  4141.1    .035       0  4225.5      .1       0  4441.1     .07       0
    4545    .035       0    4995    .035       0  5045.6    .035       0
  5159.6     .07       0  5590.4    .045       0
Bank Sta=4995,5045.6
XS Rating Curve= 0 ,0
Exp/Cntr=0.3,0.1

Type RM Length L Ch R = 1 ,27903   ,494,494,494
BEGIN DESCRIPTION:
Verde Creek 47.0
END DESCRIPTION:
XS GIS Cut Line= 3
      1949719.85     13880611.97      1949728.02     13880266.17
      1949403.34     13879278.78
#Sta/Elev= 30
  4663.4 1571.65  4757.1 1572.77    4775 1574.92  4787.1 1574.47  4808.1  1569.4
  4821.2 1562.41  4842.7 1555.48  4934.1 1544.66  4955.1 1543.36  4961.1 1541.25
  4962.8 1537.77  4963.8 1537.27  5013.4 1537.77  5015.4 1540.21  5031.2 1538.48
  5055.6 1538.48  5096.8 1541.47  5103.8 1540.73    5107 1542.27    5126 1544.05
  5160.3  1543.9  5173.3  1543.1  5196.6 1547.27  5230.2 1550.24  5264.9 1550.98
  5309.1 1555.32  5343.9 1554.98  5572.1 1563.29  5728.1 1564.23  6048.7 1566.05
#Mann= 7 ,-1 , 0
  4663.4      .1       0  4962.8     .05       0  5013.4      .1       0
  5055.6      .1       0  5160.3      .1       0  5264.9     .07       0
  5728.1    .045       0
Bank Sta=4962.8,5013.4
XS Rating Curve= 0 ,0
Exp/Cntr=0.3,0.1

Type RM Length L Ch R = 1 ,27409   ,585,585,585
BEGIN DESCRIPTION:
Verde Creek 46.0
END DESCRIPTION:
XS GIS Cut Line= 3
        1950075.       13880425.        1950125.       13880025.
      1949450.28       13879253.
#Sta/Elev= 30
  4596.9 1574.82  4705.8 1575.14  4805.2 1573.31  4841.5  1568.4  4895.9 1566.53
    4908 1563.98    4911 1560.61  4912.7 1560.89    4914 1556.09    4915 1556.37
    4917 1548.14  4919.6  1545.9  4965.4 1541.57  4968.4 1540.59  4970.3 1535.66
  4971.3 1535.16  5020.9 1535.66    5025  1536.6  5029.2 1539.38  5039.9 1539.07
  5067.5 1542.23  5088.8 1540.99  5110.3 1542.08  5129.1 1545.01  5188.6 1549.83
  5212.1 1550.71  5280.1 1556.53  5384.8 1557.37  5519.2 1559.38  6025.3 1565.97
#Mann= 7 ,-1 , 0
  4596.9     .07       0  4705.8      .1       0  4970.3     .05       0
  5020.9      .1       0  5188.6     .07       0  5384.8    .035       0
  5519.2    .045       0
Bank Sta=4970.3,5020.9
XS Rating Curve= 0 ,0
Exp/Cntr=0.3,0.1

Type RM Length L Ch R = 1 ,26824   ,550,550,550
BEGIN DESCRIPTION:
Verde Creek 45.0
END DESCRIPTION:
XS GIS Cut Line= 3
        1950475.     13879974.97        1950475.       13879575.
      1949974.97     13879274.98
#Sta/Elev= 30
  4599.8 1565.36    4650 1564.72  4731.4 1558.56  4755.4 1557.66    4758 1555.95
    4764 1548.13  4767.4 1546.18  4791.4 1541.27  4806.4 1539.29  4821.4 1541.04
    4830 1540.37  4848.4 1540.92  4866.4  1538.8    4881 1539.13    4896 1537.07
  4918.8 1536.86    4929 1536.66  4938.4 1537.92  4989.9 1537.05    5005 1535.25
  5005.9 1533.69  5006.9 1533.19  5056.6 1533.69  5057.5 1541.69  5062.2 1544.18
  5076.2 1546.77  5127.5 1550.62  5201.7 1553.09  5237.3 1552.89  5582.9 1559.37
#Mann= 6 ,-1 , 0
  4599.8      .1       0  4918.8      .1       0  5005.9     .05       0
  5056.6      .1       0  5201.7    .035       0  5237.3    .045       0
Bank Sta=5005.9,5056.6
XS Rating Curve= 0 ,0
Exp/Cntr=0.3,0.1

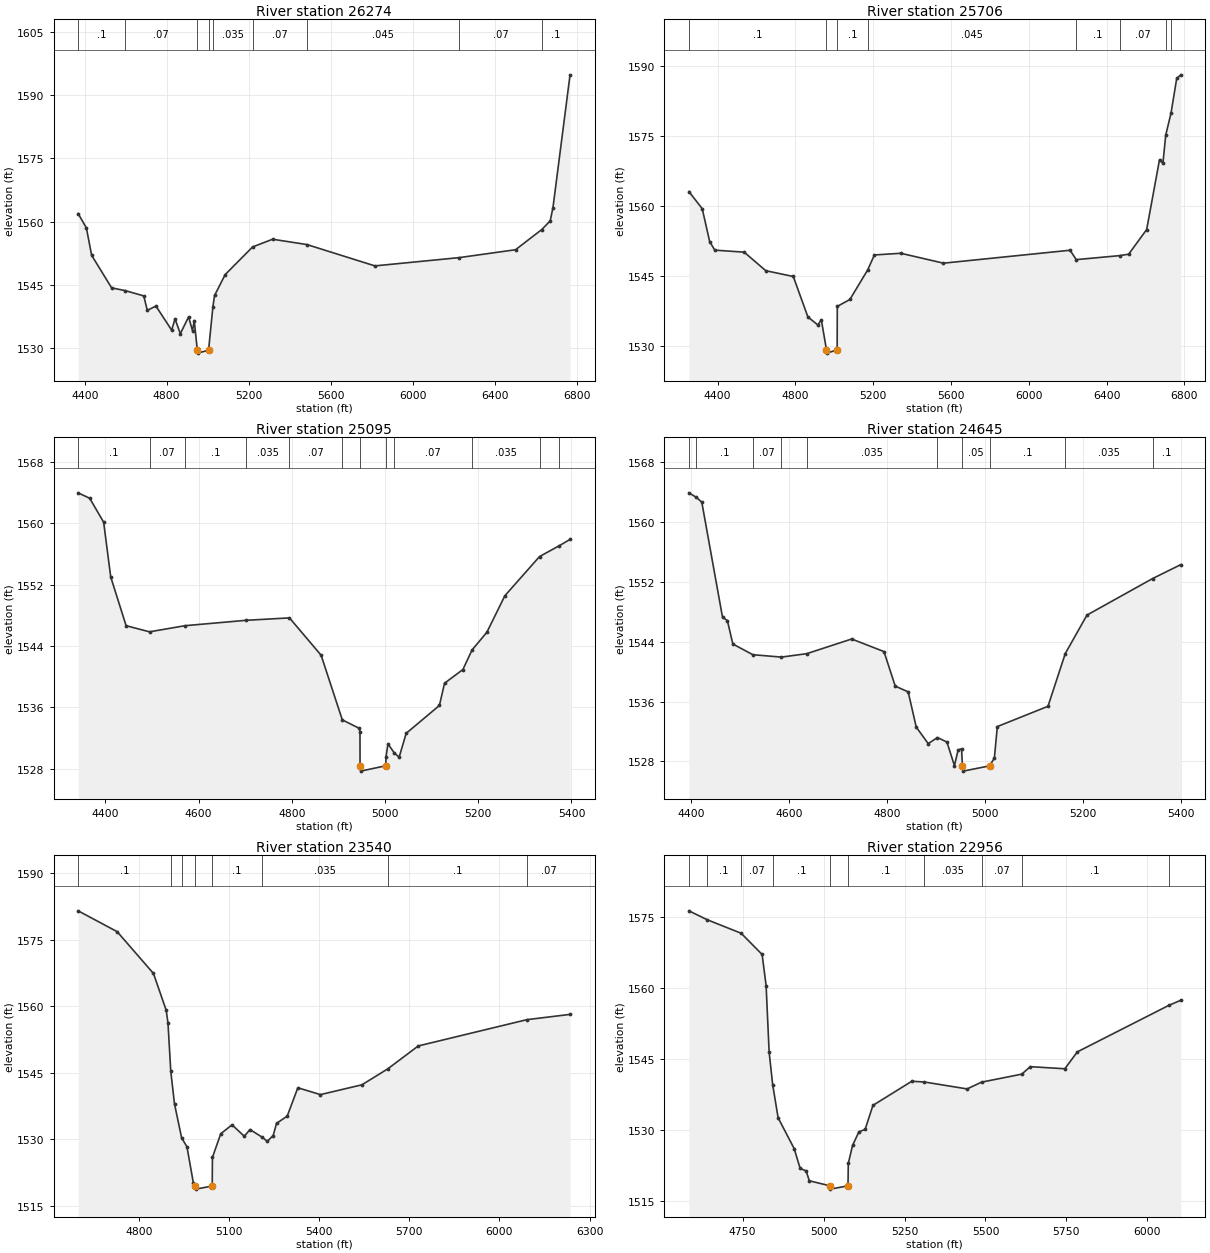
Type RM Length L Ch R = 1 ,26274   ,568,568,568
BEGIN DESCRIPTION:
Verde Creek 44.0
END DESCRIPTION:
XS GIS Cut Line= 4
      1950525.03     13879874.97        1950975.       13879425.
        1951325.       13879225.      1952532.33     13878596.93
#Sta/Elev= 30
  4367.9 1561.89  4408.1 1558.48  4433.9 1551.96  4531.4 1544.24  4596.9  1543.6
  4688.1 1542.33  4705.4  1538.9  4747.5 1539.92  4824.2 1534.21  4840.8 1536.86
  4866.6 1533.35  4906.8 1537.35    4926 1534.05  4934.5 1536.48  4949.5 1529.44
  4950.7 1528.74  5004.4 1529.44  5025.5 1539.72  5033.6 1542.43  5085.4 1547.39
  5219.2 1553.96  5316.9 1555.79  5484.1 1554.53  5815.9 1549.46  6226.6 1551.42
  6502.4  1553.3  6630.5  1558.1  6671.5 1560.16    6685 1563.31  6768.3 1594.84
#Mann= 9 ,-1 , 0
  4367.9      .1       0  4596.9     .07       0  4949.5     .05       0
  5004.4     .07       0  5025.5    .035       0  5219.2     .07       0
  5484.1    .045       0  6226.6     .07       0  6630.5      .1       0
Bank Sta=4949.5,5004.4
XS Rating Curve= 0 ,0
Exp/Cntr=0.3,0.1

Type RM Length L Ch R = 1 ,25706   ,611,611,611
BEGIN DESCRIPTION:
Verde Creek 43.0
END DESCRIPTION:
XS GIS Cut Line= 4
      1950525.04       13879925.        1951275.       13879875.
      1951783.48     13879669.89      1952619.96     13878768.96
#Sta/Elev= 30
  4252.5 1563.05    4321 1559.38  4359.2 1552.35  4385.4 1550.51  4536.5 1550.08
  4647.8 1546.11  4789.1 1544.87  4864.3 1536.21  4915.4  1534.5  4933.4  1535.6
  4959.9 1529.17  4961.1 1528.47  5014.8 1529.17  5015.4 1538.47  5080.1 1539.95
  5171.5 1546.26  5206.3 1549.48  5342.1 1549.84  5561.4 1547.72  6212.3 1550.49
  6244.2 1548.48  6467.9 1549.34  6513.6 1549.64  6606.2 1554.92  6672.3 1569.88
  6689.9 1569.14  6704.3 1575.14  6731.5 1579.86  6760.7 1587.26  6781.8 1588.03
#Mann= 8 ,-1 , 0
  4252.5      .1       0  4959.9     .05       0  5014.8      .1       0
  5171.5    .045       0  6244.2      .1       0  6467.9     .07       0
  6704.3      .1       0  6731.5     .07       0
Bank Sta=4959.9,5014.8
XS Rating Curve= 0 ,0
Exp/Cntr=0.3,0.1

Type RM Length L Ch R = 1 ,25095   ,450,450,450
BEGIN DESCRIPTION:
Verde Creek 42.0
END DESCRIPTION:
XS GIS Cut Line= 3
      1950475.02     13880075.01      1951053.51     13880411.85
      1951374.97     13880624.98
#Sta/Elev= 30
  4341.8 1563.98  4366.6 1563.27  4396.5 1560.15  4411.7    1553  4444.7 1546.64
  4494.9 1545.84  4571.1 1546.64  4701.6 1547.34  4795.1 1547.66    4863 1542.78
  4908.4 1534.35    4945 1533.24  4946.3  1532.8  4946.5 1528.36  4947.7 1527.66
  5001.8 1528.36  5001.9 1529.45  5006.4 1531.21  5019.3 1530.09  5030.3 1529.47
  5045.4 1532.59  5116.7 1536.23  5127.7 1539.13  5167.1 1540.92  5186.7 1543.47
  5218.6 1545.79  5257.1 1550.55  5331.4 1555.66    5373 1557.05  5396.9  1557.9
#Mann= 12 ,-1 , 0
  4341.8      .1       0  4494.9     .07       0  4571.1      .1       0
  4701.6    .035       0  4795.1     .07       0  4908.4      .1       0
  4946.5     .05       0  5001.8      .1       0  5019.3     .07       0
  5186.7    .035       0  5331.4      .1       0    5373     .07       0
Bank Sta=4946.5,5001.8
XS Rating Curve= 0 ,0
Exp/Cntr=0.3,0.1

Type RM Length L Ch R = 1 ,24645   ,1105,1105,1105
BEGIN DESCRIPTION:
Verde Creek 41.0
END DESCRIPTION:
XS GIS Cut Line= 3
      1950274.97     13880524.99        1950825.       13880775.
      1951225.02       13880775.
#Sta/Elev= 30
  4395.1 1563.92  4410.4 1563.31  4421.4 1562.67  4463.7 1547.28  4473.6 1546.84
  4484.8  1543.7  4525.6 1542.27  4584.1 1541.95  4635.7 1542.41  4727.4 1544.37
  4793.3 1542.69  4816.3 1538.07  4842.7  1537.3  4859.2 1532.59  4883.6 1530.38
  4902.5 1531.19  4921.8 1530.59  4937.2 1527.43  4944.7 1529.54  4951.7 1529.68
  4953.5  1527.4  4954.7  1526.7  5008.8  1527.4  5018.7 1528.45  5024.7 1532.66
  5128.1 1535.37  5163.4 1542.42  5207.7 1547.57  5341.8 1552.46  5399.3 1554.32
#Mann= 10 ,-1 , 0
  4395.1     .07       0  4410.4      .1       0  4525.6     .07       0
  4584.1      .1       0  4635.7    .035       0  4902.5      .1       0
  4953.5     .05       0  5008.8      .1       0  5163.4    .035       0
  5341.8      .1       0
Bank Sta=4953.5,5008.8
XS Rating Curve= 0 ,0
Exp/Cntr=0.3,0.1

Type RM Length L Ch R = 1 ,23540   ,584,584,584
BEGIN DESCRIPTION:
Verde Creek 40.0
END DESCRIPTION:
XS GIS Cut Line= 3
      1950375.02     13881924.96        1950575.       13881575.
       1951483.1      13880738.1
#Sta/Elev= 30
  4597.2 1581.53  4727.1 1576.83    4848  1567.4  4890.5 1559.08  4896.4  1556.2
  4905.7 1545.29  4918.1 1537.96  4941.8  1530.3  4959.6 1528.28    4981 1520.08
  4987.9 1519.43  4989.2 1518.73  5043.7 1519.43  5044.4 1525.88  5072.1 1531.23
  5109.7 1533.24  5150.5 1530.66  5169.5 1532.18  5210.2 1530.44    5227 1529.51
  5246.6 1530.82    5258 1533.58  5293.4  1535.2  5328.8  1541.6  5404.1 1540.06
  5542.1 1542.27  5628.5 1545.88  5729.8 1551.04  6091.5 1556.97  6235.2 1558.16
#Mann= 8 ,-1 , 0
  4597.2      .1       0  4905.7     .07       0  4941.8      .1       0
  4987.9     .05       0  5043.7      .1       0  5210.2    .035       0
  5628.5      .1       0  6091.5     .07       0
Bank Sta=4987.9,5043.7
XS Rating Curve= 0 ,0
Exp/Cntr=0.3,0.1

Type RM Length L Ch R = 1 ,22956   ,527,527,527
BEGIN DESCRIPTION:
Verde Creek 39.0
END DESCRIPTION:
XS GIS Cut Line= 3
      1950625.03     13882024.99        1951025.       13881925.
      1951435.56     13880896.49
#Sta/Elev= 30
  4583.9 1576.25  4640.7 1574.36  4745.4 1571.51  4810.1 1567.03  4822.4 1560.47
  4831.7 1546.46  4842.6 1539.57  4859.5 1532.54    4909 1526.05  4927.6 1521.86
  4946.1 1521.32  4955.9 1519.24  5019.6 1518.18  5020.9 1517.48  5075.4 1518.18
  5076.3 1522.91  5089.5 1526.71  5108.9 1529.56  5128.3  1530.1  5152.5 1535.17
  5272.5 1540.26  5311.7  1540.1  5443.4 1538.64  5487.9 1540.07  5612.1 1541.76
  5638.6 1543.34  5745.2  1542.9    5784 1546.47  6065.8 1556.26  6103.6 1557.37
#Mann= 10 ,-1 , 0
  4583.9     .07       0  4640.7      .1       0  4745.4     .07       0
  4842.6      .1       0  5019.6     .05       0  5075.4      .1       0
  5311.7    .035       0  5487.9     .07       0  5612.1      .1       0
  6065.8     .07       0
Bank Sta=5019.6,5075.4
XS Rating Curve= 0 ,0
Exp/Cntr=0.3,0.1

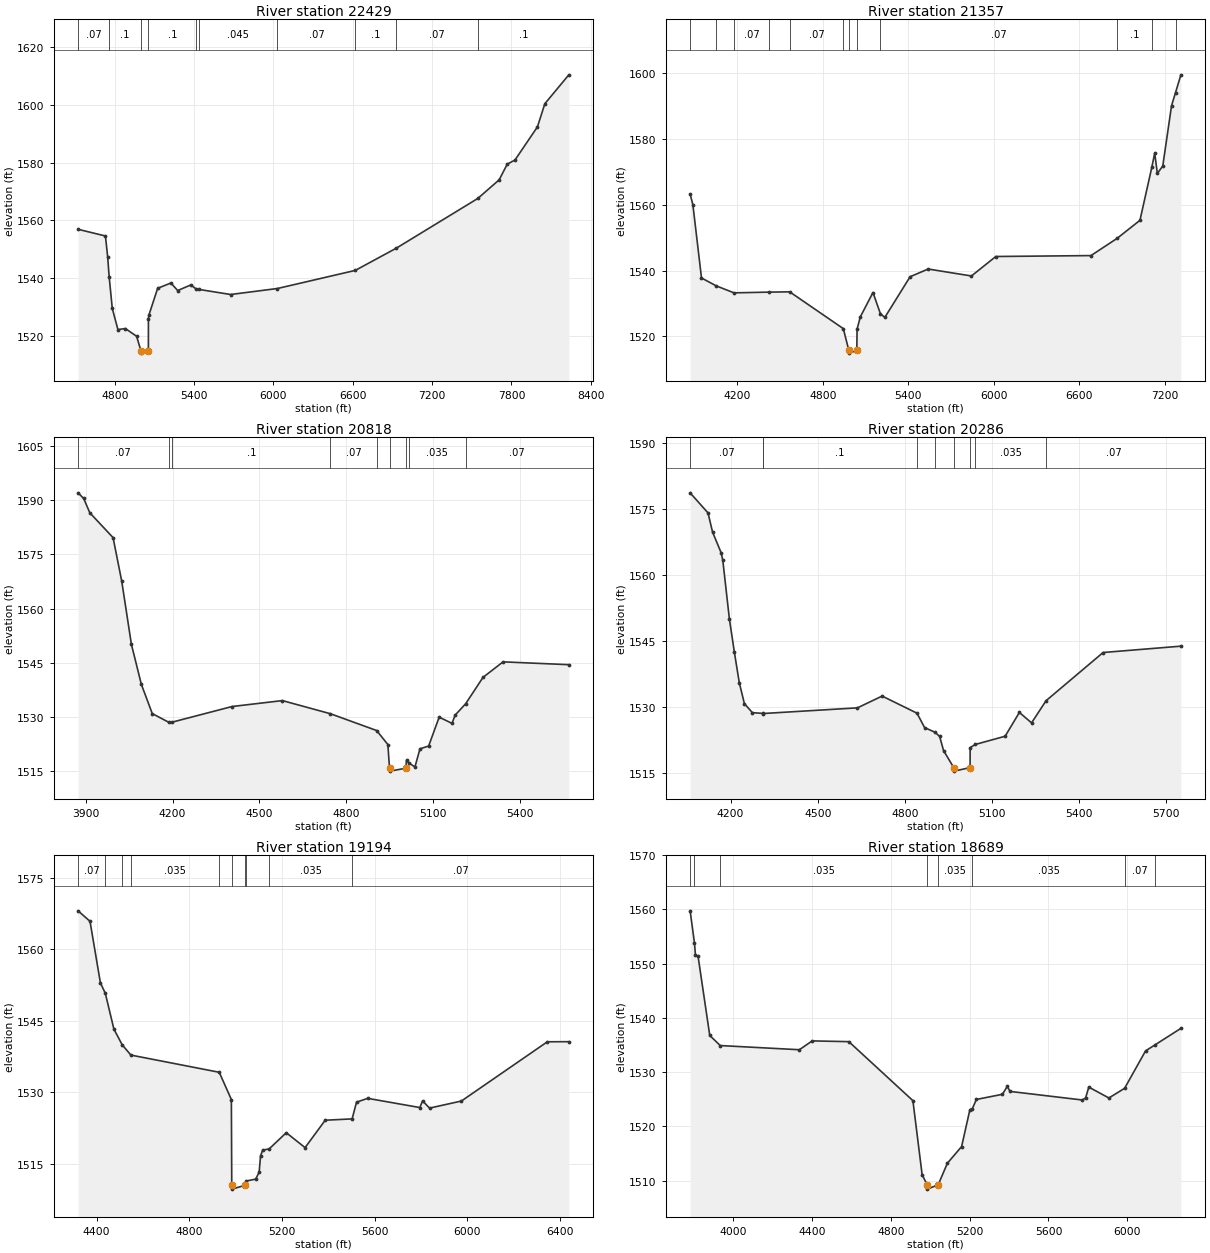
Type RM Length L Ch R = 1 ,22429   ,1072,1072,1072
BEGIN DESCRIPTION:
Verde Creek 38.0
END DESCRIPTION:
XS GIS Cut Line= 3
      1951075.03     13882274.98        1951475.       13882025.
        1954109.      13880139.6
#Sta/Elev= 30
  4523.1 1556.96    4730 1554.65    4747 1547.37    4758 1540.61  4781.8 1529.62
  4824.3 1522.34  4880.9  1522.7  4965.8 1520.03  4998.9 1514.91  5000.2 1514.21
  5054.7 1514.91  5055.1 1525.94  5057.8 1527.22  5124.8 1536.59  5224.9 1538.42
  5276.5 1535.82  5375.4 1537.75  5416.2 1536.35  5434.5 1536.22  5676.6 1534.45
  6030.3 1536.52  6619.3 1542.77  6929.8 1550.45  7545.7 1567.61    7707 1574.03
  7768.5 1579.46  7826.7 1580.87  7996.6 1592.32  8052.6 1600.31    8234 1610.29
#Mann= 10 ,-1 , 0
  4523.1     .07       0    4758      .1       0  4998.9     .05       0
  5054.7      .1       0  5416.2     .07       0  5434.5    .045       0
  6030.3     .07       0  6619.3      .1       0  6929.8     .07       0
  7545.7      .1       0
Bank Sta=4998.9,5054.7
XS Rating Curve= 0 ,0
Exp/Cntr=0.3,0.1

Type RM Length L Ch R = 1 ,21357   ,539,539,539
BEGIN DESCRIPTION:
Verde Creek 37.0
END DESCRIPTION:
XS GIS Cut Line= 3
      1951475.01     13883324.99        1952275.       13882525.
      1954152.57     13881173.07
#Sta/Elev= 30
  3868.4 1563.22  3887.7 1559.98  3948.2 1537.76  4051.6 1535.36  4176.4 1533.24
  4423.2 1533.46  4567.2 1533.55  4943.8 1522.38  4982.6 1515.75  4983.8 1514.95
  5038.6 1515.75  5040.3 1522.21  5063.1 1525.95  5151.9 1533.34  5204.7 1526.85
  5235.4  1525.8  5412.5 1538.13  5539.3 1540.47  5843.2 1538.36  6014.3 1544.27
  6682.3 1544.55  6866.3 1549.79  7026.1 1555.25  7110.2  1571.5  7129.8 1575.64
  7148.1 1569.49  7186.3 1571.72  7247.9 1590.04  7275.7 1593.98  7313.4  1599.4
#Mann= 12 ,-1 , 0
  3868.4     .07       0  4051.6      .1       0  4176.4     .07       0
  4423.2      .1       0  4567.2     .07       0  4943.8      .1       0
  4982.6     .05       0  5038.6      .1       0  5204.7     .07       0
  6866.3      .1       0  7110.2    .035       0  7275.7     .07       0
Bank Sta=4982.6,5038.6
XS Rating Curve= 0 ,0
Exp/Cntr=0.3,0.1

Type RM Length L Ch R = 1 ,20818   ,532,532,532
BEGIN DESCRIPTION:
Verde Creek 36.0
END DESCRIPTION:
XS GIS Cut Line= 3
      1951724.97     13883775.03        1952525.       13882975.
      1952984.49     13882644.52
#Sta/Elev= 30
  3873.2 1592.08  3892.6 1590.51  3913.8 1586.55  3994.2 1579.67  4024.1 1567.64
  4057.7 1550.08    4092 1539.04  4129.8 1530.92    4186 1528.55  4199.6 1528.57
  4405.9 1532.88  4579.9 1534.52    4746 1530.88  4905.8 1526.23  4944.7 1522.35
  4950.4 1515.78  4951.7 1514.98  5006.6 1515.78  5009.2 1518.04  5017.3 1517.23
  5038.4 1516.14  5055.7 1521.16  5085.7 1521.93  5122.2 1529.94  5166.5 1528.21
  5177.6 1530.52  5213.6 1533.63  5273.7 1540.95  5343.1 1545.25  5570.6 1544.47
#Mann= 9 ,-1 , 0
  3873.2     .07       0    4186    .035       0  4199.6      .1       0
    4746     .07       0  4905.8      .1       0  4950.4     .05       0
  5006.6      .1       0  5017.3    .035       0  5213.6     .07       0
Bank Sta=4950.4,5006.6
XS Rating Curve= 0 ,0
Exp/Cntr=0.3,0.1

Type RM Length L Ch R = 1 ,20286   ,1092,1092,1092
BEGIN DESCRIPTION:
Verde Creek 35.0
END DESCRIPTION:
XS GIS Cut Line= 3
      1951925.03     13883874.98        1952725.       13883375.
      1953044.89     13882701.14
#Sta/Elev= 30
  4060.9 1578.64  4122.5 1574.07  4138.1 1569.72  4167.8    1565  4173.4 1563.28
  4196.1 1549.95  4213.1 1542.46    4230 1535.53  4247.7 1530.72  4275.3 1528.68
  4311.2 1528.51  4311.8 1528.48  4636.9 1529.77  4721.8 1532.45  4841.8 1528.56
  4867.9  1525.3  4904.1 1524.21  4919.9 1523.27  4933.2 1520.07  4968.3 1516.19
  4969.5 1515.39  5024.5 1516.19  5024.9 1520.74  5042.5 1521.45  5145.2 1523.32
  5194.3 1528.73  5236.2 1526.36  5286.2  1531.4  5482.5 1542.35  5750.2 1543.79
#Mann= 9 ,-1 , 0
  4060.9     .07       0  4311.2    .035       0  4311.8      .1       0
  4841.8     .07       0  4904.1      .1       0  4968.3     .05       0
  5024.5      .1       0  5042.5    .035       0  5286.2     .07       0
Bank Sta=4968.3,5024.5
XS Rating Curve= 0 ,0
Exp/Cntr=0.3,0.1

Type RM Length L Ch R = 1 ,19194   ,505,505,505
BEGIN DESCRIPTION:
Verde Creek 34.0
END DESCRIPTION:
XS GIS Cut Line= 3
      1952775.03     13884624.97        1953225.       13884125.
      1953257.34      13882680.5
#Sta/Elev= 30
  4319.8 1568.08  4371.3 1565.88  4416.1 1552.97  4437.4 1550.76  4474.4 1543.25
    4510 1539.98  4547.6 1537.81  4928.9  1534.2  4981.2 1528.48  4982.9 1510.48
  4984.2 1509.68  5039.3 1510.48  5045.9 1511.39  5086.1 1511.78  5101.1 1513.25
  5107.1 1516.65  5116.1 1517.86  5144.2 1518.12  5218.2 1521.52  5299.2 1518.39
  5386.2 1524.14  5502.2 1524.42  5521.2 1527.92  5569.3 1528.73  5794.3  1526.8
  5806.3  1528.2  5836.3 1526.68  5973.9 1528.17  6344.6  1540.6  6437.3 1540.62
#Mann= 10 ,-1 , 0
  4319.8     .07       0  4437.4    .035       0    4510     .07       0
  4547.6    .035       0  4928.9     .07       0  4982.9     .05       0
  5039.3     .07       0  5045.9      .1       0  5144.2    .035       0
  5502.2     .07       0
Bank Sta=4982.9,5039.3
XS Rating Curve= 0 ,0
Exp/Cntr=0.3,0.1

Type RM Length L Ch R = 1 ,18689   ,546,546,546
BEGIN DESCRIPTION:
Verde Creek 33.0
END DESCRIPTION:
XS GIS Cut Line= 3
      1953297.65     13885191.08        1953675.       13884025.
      1953612.36     13882760.26
#Sta/Elev= 30
  3780.4 1559.75  3802.2 1553.89  3807.5 1551.58  3820.5 1551.42    3880 1536.77
  3933.2  1534.9  4335.1 1534.13  4400.3 1535.76  4586.3 1535.62  4911.6 1524.74
  4958.4  1511.1  4983.5 1509.22  4984.7 1508.42  5039.9 1509.22  5086.8  1513.2
  5158.9 1516.27  5200.9 1523.06  5213.2 1523.24    5234 1524.96  5366.1 1525.91
  5390.7 1527.36  5405.2 1526.44  5771.6 1524.86  5788.5 1525.24  5804.7 1527.24
  5906.8 1525.23  5986.6 1527.02    6093 1533.92  6141.6 1535.04  6272.3 1538.07
#Mann= 8 ,-1 , 0
  3780.4    .035       0  3802.2     .07       0  3933.2    .035       0
  4983.5     .05       0  5039.9    .035       0  5213.2    .035       0
  5986.6     .07       0  6141.6    .035       0
Bank Sta=4983.5,5039.9
XS Rating Curve= 0 ,0
Exp/Cntr=0.3,0.1