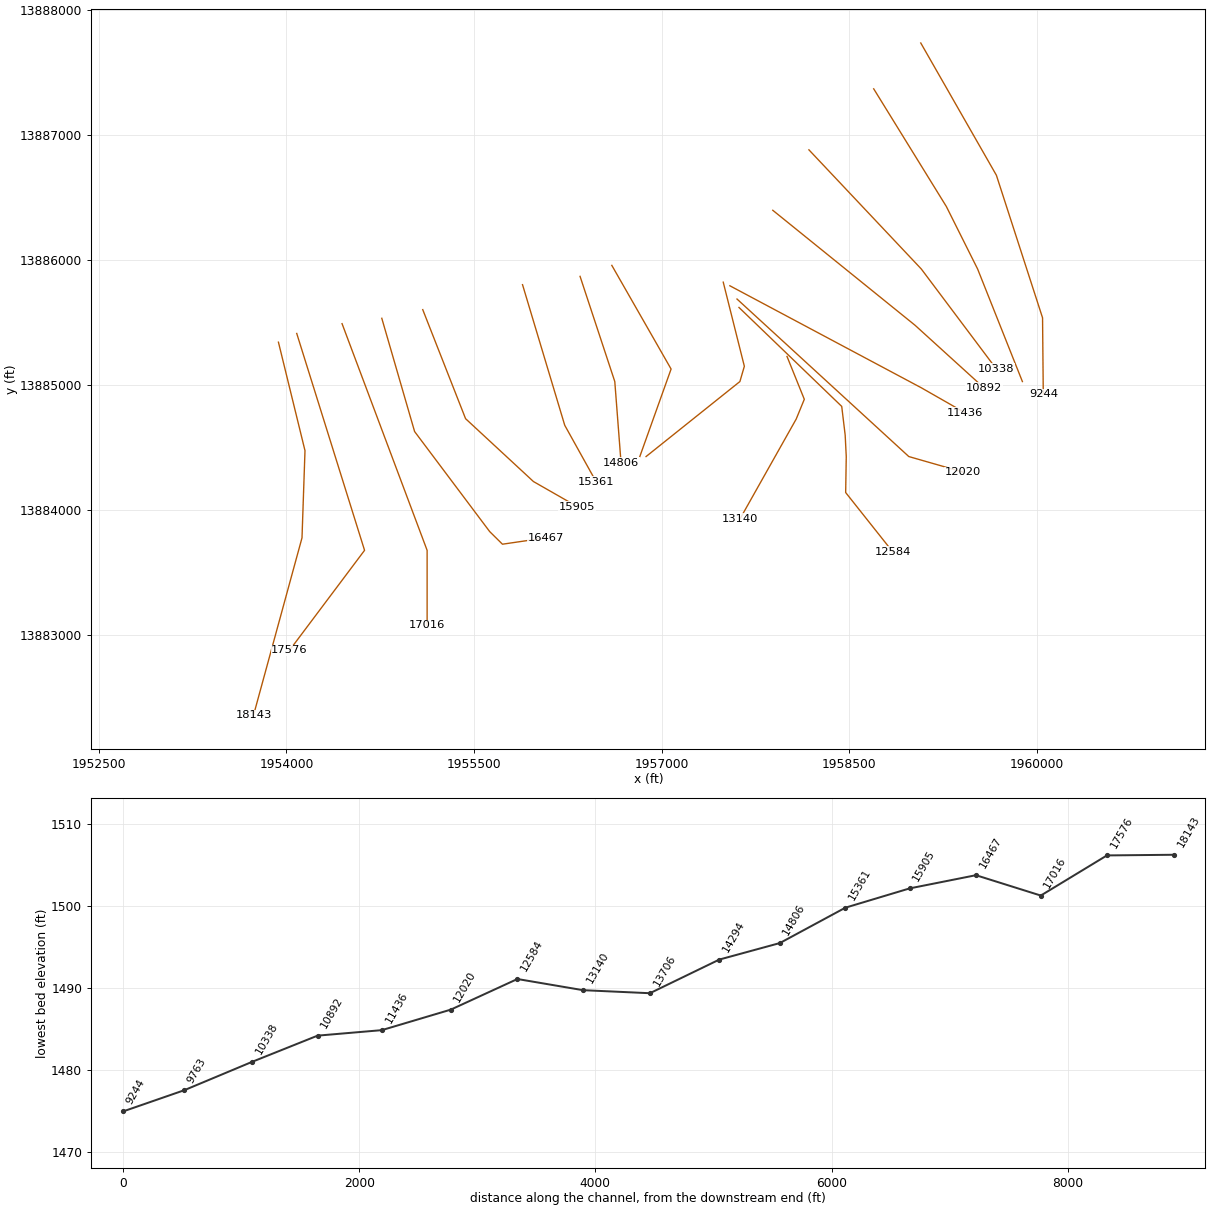
HEC-RAS study Verde Creek.prj: Verde Creek Base Level Engineering

--- Verde Creek.g01 (geometry) --- (continued)

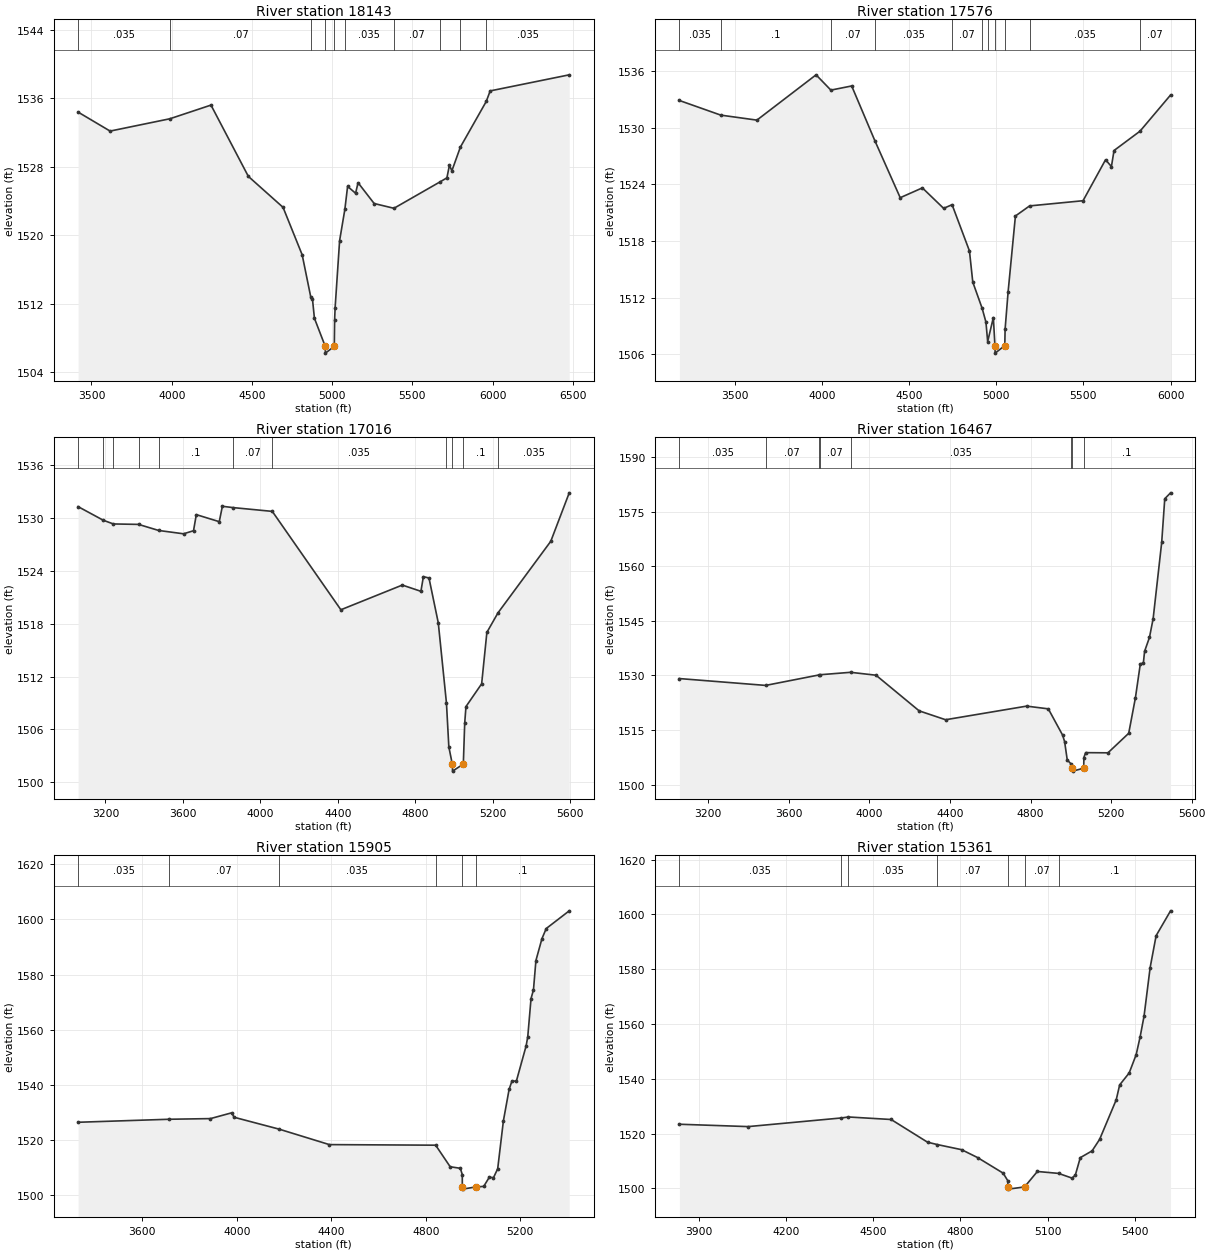
Type RM Length L Ch R = 1 ,18143   ,567,567,567
BEGIN DESCRIPTION:
Verde Creek 32.0
END DESCRIPTION:
XS GIS Cut Line= 4
      1953936.68      13885339.7      1954148.88     13884472.18
        1954125.       13883775.      1953737.77      13882356.9
#Sta/Elev= 30
  3416.7  1534.4  3616.2 1532.18  3988.5 1533.62  4244.8 1535.22  4477.7 1526.88
  4693.9 1523.26  4813.1 1517.71  4867.2 1512.72    4877 1512.58  4889.4 1510.29
  4956.7 1507.01    4958 1506.21  5013.3 1507.01  5015.3 1510.09  5018.4 1511.51
  5046.4 1519.37    5079 1523.01  5096.2 1525.71  5145.9 1524.91  5161.5 1526.14
  5261.6 1523.71    5385 1523.15  5670.4 1526.22    5715 1526.71  5730.6 1528.17
  5746.1 1527.54  5799.1 1530.31  5960.3 1535.65  5984.7 1536.88  6477.4 1538.76
#Mann= 10 ,-1 , 0
  3416.7    .035       0  3988.5     .07       0  4867.2      .1       0
  4956.7     .05       0  5013.3      .1       0    5079    .035       0
    5385     .07       0  5670.4    .035       0  5799.1     .07       0
  5960.3    .035       0
Bank Sta=4956.7,5013.3
XS Rating Curve= 0 ,0
Exp/Cntr=0.3,0.1

Type RM Length L Ch R = 1 ,17576   ,560,560,560
BEGIN DESCRIPTION:
Verde Creek 31.0
END DESCRIPTION:
XS GIS Cut Line= 4
      1954082.95     13885409.55        1954375.       13884475.
        1954625.       13883675.      1954024.99     13882874.98
#Sta/Elev= 30
  3182.6  1532.9  3419.9 1531.35  3627.1 1530.82  3966.5 1535.62  4051.4    1534
  4170.8 1534.44  4303.7 1528.64  4449.2  1522.6  4576.3 1523.64  4698.2 1521.47
  4746.7 1521.86  4846.3 1516.96  4865.4 1513.66  4919.1 1510.88  4940.9 1509.42
  4950.8 1507.35  4983.4  1509.9  4992.5 1506.93  4993.8 1506.13  5049.1 1506.93
  5050.8 1508.65  5068.2 1512.65    5110 1520.66  5191.3 1521.73  5497.9 1522.28
    5627 1526.62  5660.7  1525.9  5675.7  1527.6  5824.8 1529.65  5999.9 1533.48
#Mann= 11 ,-1 , 0
  3182.6    .035       0  3419.9      .1       0  4051.4     .07       0
  4303.7    .035       0  4746.7     .07       0  4919.1    .035       0
  4950.8      .1       0  4992.5     .05       0  5049.1      .1       0
  5191.3    .035       0  5824.8     .07       0
Bank Sta=4992.5,5049.1
XS Rating Curve= 0 ,0
Exp/Cntr=0.3,0.1

Type RM Length L Ch R = 1 ,17016   ,549,549,549
BEGIN DESCRIPTION:
Verde Creek 30.0
END DESCRIPTION:
XS GIS Cut Line= 4
      1954445.18     13885487.85        1954825.       13884475.
        1955125.       13883675.        1955125.     13883075.03
#Sta/Elev= 30
  3059.1 1531.32  3189.3 1529.77  3241.2 1529.35  3371.1  1529.3    3475 1528.61
  3603.8 1528.23  3655.1 1528.58  3669.5 1530.41    3788 1529.61  3804.1 1531.36
  3859.3 1531.21  4061.9 1530.78    4416 1519.59  4733.2  1522.4  4829.3 1521.69
  4842.1 1523.36    4871  1523.2    4919  1518.1  4961.2 1508.98  4973.5 1503.99
  4991.4 1502.04  4992.7 1501.24  5048.3 1502.04  5055.4 1506.68  5061.9 1508.58
  5142.9 1511.17  5169.9 1517.02  5227.3 1519.24  5499.9 1527.38  5595.2 1532.89
#Mann= 11 ,-1 , 0
  3059.1    .035       0  3189.3     .07       0  3241.2    .035       0
  3371.1     .07       0    3475      .1       0  3859.3     .07       0
  4061.9    .035       0  4961.2      .1       0  4991.4     .05       0
  5048.3      .1       0  5227.3    .035       0
Bank Sta=4991.4,5048.3
XS Rating Curve= 0 ,0
Exp/Cntr=0.3,0.1

Type RM Length L Ch R = 1 ,16467   ,562,562,562
BEGIN DESCRIPTION:
Verde Creek 29.0
END DESCRIPTION:
XS GIS Cut Line= 5
      1954762.72     13885530.92        1955025.       13884625.
        1955625.       13883825.      1955727.13     13883723.92
      1956074.98       13883775.
#Sta/Elev= 30
  3056.8 1529.15    3485 1527.27  3749.3 1530.14    3755  1530.2  3906.6 1530.87
  4032.9 1530.07    4247 1520.28  4378.3 1517.84  4780.7 1521.58  4888.3 1520.83
  4959.5 1513.59  4969.3 1511.81  4982.3  1506.8  5001.7 1505.66  5007.2 1504.52
  5008.5 1503.72  5064.2 1504.52  5064.8 1507.44  5073.7  1508.8  5184.4 1508.75
  5287.5 1514.12  5320.8 1523.88  5345.1 1533.18  5360.2 1533.41  5366.3 1536.64
  5390.6 1540.47  5408.8 1545.62  5451.2 1566.55  5466.4 1578.55  5495.2 1580.18
#Mann= 8 ,-1 , 0
  3056.8    .035       0    3485     .07       0  3749.3      .1       0
    3755     .07       0  3906.6    .035       0  5001.7      .1       0
  5007.2    .035       0  5064.2      .1       0
Bank Sta=5007.2,5064.2
XS Rating Curve= 0 ,0
Exp/Cntr=0.3,0.1

Type RM Length L Ch R = 1 ,15905   ,544,544,544
BEGIN DESCRIPTION:
Verde Creek 28.0
END DESCRIPTION:
XS GIS Cut Line= 4
      1955090.05     13885600.13       1955432.3     13884727.99
        1955975.       13884225.      1956324.96     13884025.02
#Sta/Elev= 30
  3327.9 1526.38  3712.7 1527.47  3888.4 1527.71  3978.7 1529.82  3988.3  1528.2
  4178.5  1523.9    4392 1518.27  4842.1 1518.06  4903.6 1510.23  4946.7 1509.67
  4954.9 1507.38    4955 1502.91  4956.3 1502.11  5012.1 1502.91  5045.6  1503.1
  5069.3 1506.43    5087 1506.27  5104.8  1509.5    5129 1526.92  5153.2 1538.33
  5165.3 1541.37  5183.8 1541.28  5225.2 1554.09  5232.1  1557.4    5246 1571.27
  5256.3 1574.44  5266.7 1585.09  5292.3 1593.05  5310.4 1596.71  5407.8 1603.13
#Mann= 6 ,-1 , 0
  3327.9    .035       0  3712.7     .07       0  4178.5    .035       0
  4842.1      .1       0    4955     .05       0  5012.1      .1       0
Bank Sta=4955,5012.1
XS Rating Curve= 0 ,0
Exp/Cntr=0.3,0.1

Type RM Length L Ch R = 1 ,15361   ,555,555,555
BEGIN DESCRIPTION:
Verde Creek 27.0
END DESCRIPTION:
XS GIS Cut Line= 4
       1955887.6     13885799.68        1956075.       13885175.
        1956225.       13884675.      1956475.01     13884224.98
#Sta/Elev= 30
  3833.6 1523.43  4069.9 1522.57  4390.3 1525.72  4414.7 1526.08  4561.7 1525.16
  4686.9 1516.88  4719.9 1516.03    4804 1514.15  4859.2 1511.26  4946.9 1505.59
  4962.6 1502.87  4963.4 1500.56  4964.7 1499.76  5020.5 1500.56  5064.6  1506.2
  5137.3  1505.5  5183.7 1503.79    5195 1504.83  5212.2 1511.24  5252.8 1513.72
  5278.6  1517.9  5335.7 1532.32  5347.6 1537.78  5380.3 1542.13  5404.4 1548.83
  5418.1 1555.37  5431.5 1562.89  5452.4 1580.58    5473 1592.22  5522.6 1601.28
#Mann= 7 ,-1 , 0
  3833.6    .035       0  4390.3     .07       0  4414.7    .035       0
  4719.9     .07       0  4963.4     .05       0  5020.5     .07       0
  5137.3      .1       0
Bank Sta=4963.4,5020.5
XS Rating Curve= 0 ,0
Exp/Cntr=0.3,0.1

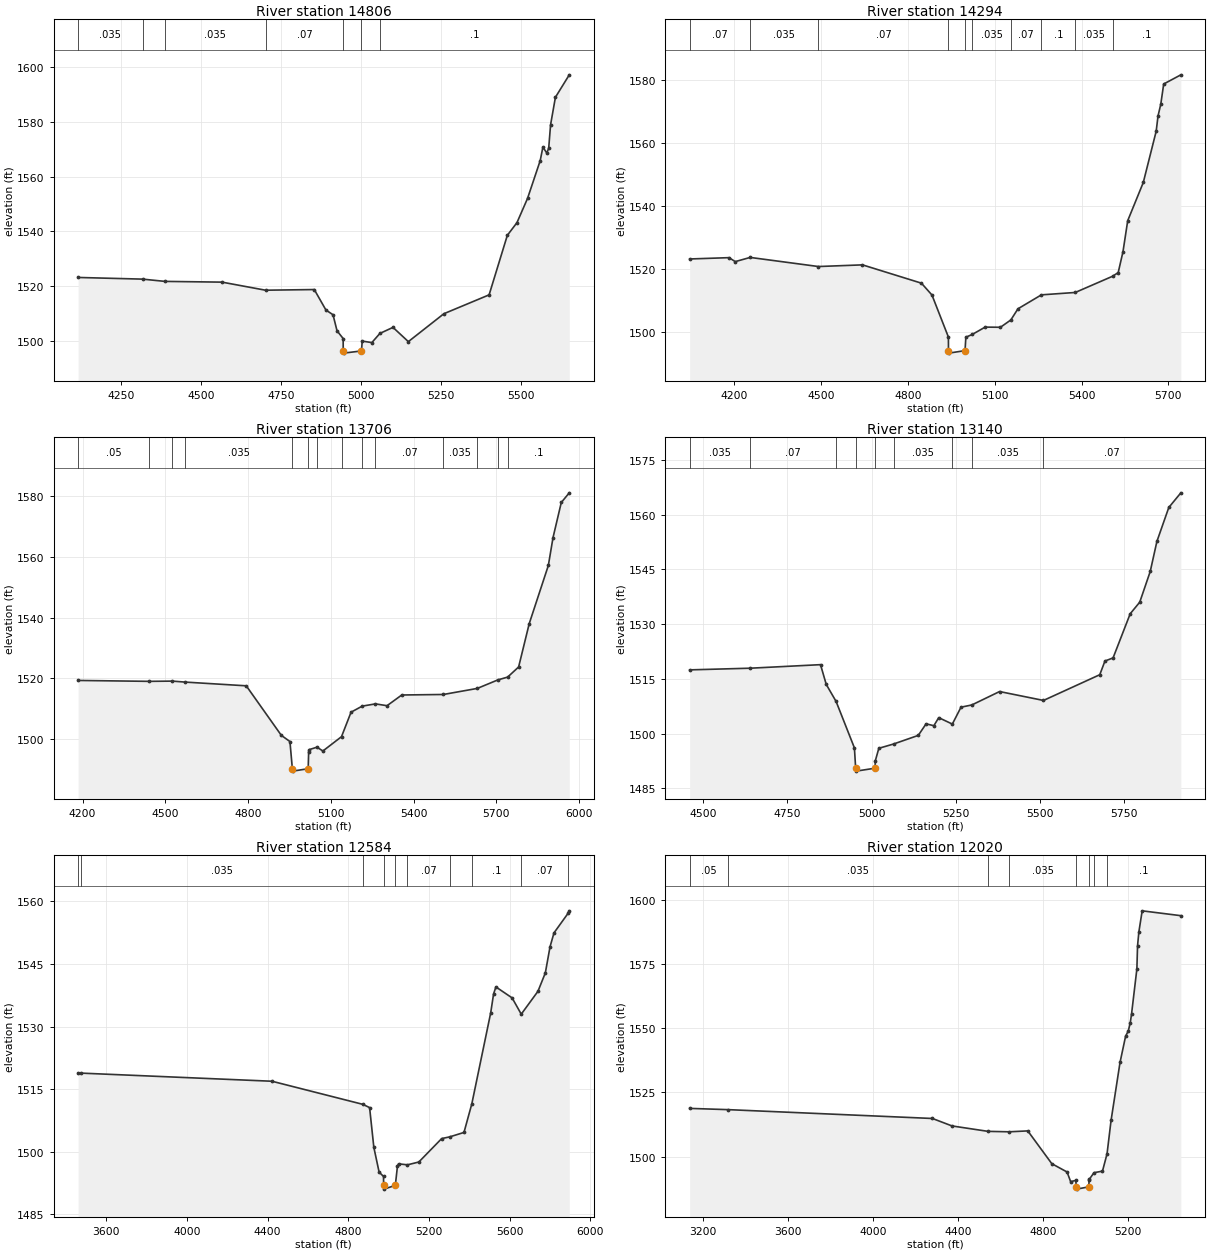
Type RM Length L Ch R = 1 ,14806   ,512,512,512
BEGIN DESCRIPTION:
Verde Creek 26.0
END DESCRIPTION:
XS GIS Cut Line= 3
      1956347.43     13885866.19        1956625.       13885025.
        1956675.     13884375.02
#Sta/Elev= 30
  4114.2 1523.11  4316.1  1522.5  4386.4 1521.67  4564.8  1521.4  4700.9 1518.45
  4853.6 1518.69  4890.1  1511.2  4912.3 1509.47  4924.8 1503.61    4944 1500.78
  4944.2 1496.25  4945.5 1495.45  5001.3 1496.25  5003.7 1499.85  5033.8  1499.3
  5059.1 1502.66    5100 1504.86  5148.1 1499.65  5259.4 1509.86  5400.9 1516.75
    5458 1538.52  5488.1 1543.14  5521.2    1552  5560.9 1565.83  5569.3 1570.76
  5581.4 1568.61  5587.4 1570.29  5593.4 1578.96  5608.5 1588.97  5651.9 1597.18
#Mann= 7 ,-1 , 0
  4114.2    .035       0  4316.1     .07       0  4386.4    .035       0
  4700.9     .07       0  4944.2     .05       0  5001.3     .07       0
  5059.1      .1       0
Bank Sta=4944.2,5001.3
XS Rating Curve= 0 ,0
Exp/Cntr=0.3,0.1

Type RM Length L Ch R = 1 ,14294   ,588,588,588
BEGIN DESCRIPTION:
Verde Creek 25.0
END DESCRIPTION:
XS GIS Cut Line= 4
      1956601.29       13885954.        1956875.       13885475.
        1957075.       13885125.        1956825.     13884425.01
#Sta/Elev= 30
  4045.1 1523.33  4181.3 1523.75  4202.6 1522.49  4254.3 1523.82  4490.3 1520.93
  4642.5 1521.46  4846.3 1515.65  4882.7 1511.89  4939.6 1498.53  4939.8 1494.24
  4941.2 1493.44  4997.1 1494.24  4999.9 1498.49  5022.2 1499.38  5066.6  1501.7
  5119.5 1501.65  5155.4 1503.97  5180.1 1507.52  5261.1 1511.94  5378.2  1512.7
  5507.1 1517.84  5526.6 1519.01  5543.1 1525.63  5559.5 1535.49  5613.3 1547.61
  5657.9 1563.88  5664.3 1568.75  5673.8 1572.47  5683.9 1578.88  5743.2 1581.79
#Mann= 10 ,-1 , 0
  4045.1     .07       0  4254.3    .035       0  4490.3     .07       0
  4939.8     .05       0  4997.1     .07       0  5022.2    .035       0
  5155.4     .07       0  5261.1      .1       0  5378.2    .035       0
  5507.1      .1       0
Bank Sta=4939.8,4997.1
XS Rating Curve= 0 ,0
Exp/Cntr=0.3,0.1

Type RM Length L Ch R = 1 ,13706   ,566,566,566
BEGIN DESCRIPTION:
Verde Creek 24.0
END DESCRIPTION:
XS GIS Cut Line= 4
      1957491.87     13885819.68      1957660.52       13885147.
        1957625.       13885025.      1956875.03     13884425.02
#Sta/Elev= 30
  4183.8 1519.25    4442 1518.95  4525.9 1519.03  4569.7 1518.72  4793.5 1517.48
  4920.7 1501.14  4951.9  1499.1  4960.7 1490.14  4962.1 1489.34  5018.1 1490.14
  5019.8 1495.69  5022.3 1496.45  5050.1 1497.24  5071.4 1495.98  5138.9  1500.7
  5173.5 1508.78    5214 1510.78    5262 1511.52    5304 1510.92  5357.4 1514.45
  5508.2 1514.62  5631.3 1516.62  5705.9 1519.43  5741.2 1520.35  5781.1 1523.69
  5819.5 1537.97  5888.9 1557.17  5905.9 1566.39  5935.8 1577.94  5964.8 1581.13
#Mann= 14 ,-1 , 0
  4183.8     .05       0    4442    .035       0  4525.9     .05       0
  4569.7    .035       0  4960.7    .035       0  5018.1    .035       0
  5050.1      .1       0  5138.9    .035       0    5214      .1       0
    5262     .07       0  5508.2    .035       0  5631.3      .1       0
  5705.9    .035       0  5741.2      .1       0
Bank Sta=4960.7,5018.1
XS Rating Curve= 0 ,0
Exp/Cntr=0.3,0.1

Type RM Length L Ch R = 1 ,13140   ,556,556,556
BEGIN DESCRIPTION:
Verde Creek 23.0
END DESCRIPTION:
XS GIS Cut Line= 4
      1958001.59     13885225.54      1958139.77     13884882.91
        1958075.       13884725.        1957625.     13883924.99
#Sta/Elev= 30
  4459.9 1517.47  4640.3 1517.93  4848.3  1518.9  4865.3 1513.48  4894.6  1508.8
  4948.9 1496.08  4952.6 1490.51  4953.9 1489.71    5010 1490.51  5011.1 1492.59
  5021.4 1495.97    5065 1497.14  5138.5 1499.51  5161.7 1502.68  5184.7 1502.16
  5199.2 1504.37  5239.6 1502.61  5265.3 1507.24  5297.4 1507.85  5379.8 1511.53
  5510.1 1509.09  5677.2 1516.14  5692.6  1519.9  5716.7 1520.75  5767.5 1532.85
  5795.9 1536.04    5827 1544.45  5846.8 1552.69  5882.1 1561.99  5917.9 1566.01
#Mann= 9 ,-1 , 0
  4459.9    .035       0  4640.3     .07       0  4894.6      .1       0
  4952.6     .05       0    5010      .1       0    5065    .035       0
  5239.6     .07       0  5297.4    .035       0  5510.1     .07       0
Bank Sta=4952.6,5010
XS Rating Curve= 0 ,0
Exp/Cntr=0.3,0.1

Type RM Length L Ch R = 1 ,12584   ,564,564,564
BEGIN DESCRIPTION:
Verde Creek 22.0
END DESCRIPTION:
XS GIS Cut Line= 6
      1957617.67     13885617.44      1958438.84     13884826.08
      1958466.48     13884595.22        1958475.       13884425.
      1958470.32      13884137.1      1958845.27     13883664.36
#Sta/Elev= 30
  3461.1 1518.84  3473.2 1518.85  4422.1  1516.9  4872.4 1511.37    4906 1510.59
    4927 1501.08  4953.1 1495.15  4975.1  1494.1  4975.4 1491.97  4976.8 1491.07
  5033.5 1491.97  5044.1 1496.58  5049.3 1497.12  5093.7 1496.89    5150 1497.56
  5263.2 1503.17  5302.9 1503.58  5373.8 1504.64  5412.7 1511.49  5506.3 1533.28
  5520.6 1537.81  5532.1 1539.48  5612.5 1536.85  5657.7 1532.96  5740.6 1538.44
  5777.1 1542.84  5800.4 1549.09    5820 1552.42  5889.7  1557.1  5895.8  1557.7
#Mann= 10 ,-1 , 0
  3461.1     .05       0  3473.2    .035       0  4872.4      .1       0
  4975.4     .05       0  5033.5      .1       0  5093.7     .07       0
  5302.9    .035       0  5412.7      .1       0  5657.7     .07       0
  5889.7      .1       0
Bank Sta=4975.4,5033.5
XS Rating Curve= 0 ,0
Exp/Cntr=0.3,0.1

Type RM Length L Ch R = 1 ,12020   ,584,584,584
BEGIN DESCRIPTION:
Verde Creek 21.0
END DESCRIPTION:
XS GIS Cut Line= 3
      1957601.72       13885685.        1958975.       13884425.
      1959408.39     13884300.68
#Sta/Elev= 30
  3135.7  1518.8  3318.2 1518.31  4279.7 1514.87  4371.7 1511.97  4541.7 1509.85
  4641.5 1509.68    4729 1510.03  4842.1 1497.26  4914.2 1494.01  4930.9 1490.25
  4954.9 1490.73  4958.4 1488.24  4959.8 1487.34  5016.6 1488.24  5017.9 1490.91
  5019.2 1491.21    5041 1493.75    5081 1494.35  5102.5 1501.11  5121.4 1514.09
  5163.6 1536.69    5190 1546.97  5202.5 1548.94  5211.9 1552.16  5218.1 1555.68
  5243.1 1573.18  5246.2 1582.12  5252.4 1587.54    5268 1595.79  5450.3  1593.9
#Mann= 8 ,-1 , 0
  3135.7     .05       0  3318.2    .035       0  4541.7     .07       0
  4641.5    .035       0  4958.4    .035       0  5016.6    .035       0
    5041     .07       0  5102.5      .1       0
Bank Sta=4958.4,5016.6
XS Rating Curve= 0 ,0
Exp/Cntr=0.3,0.1

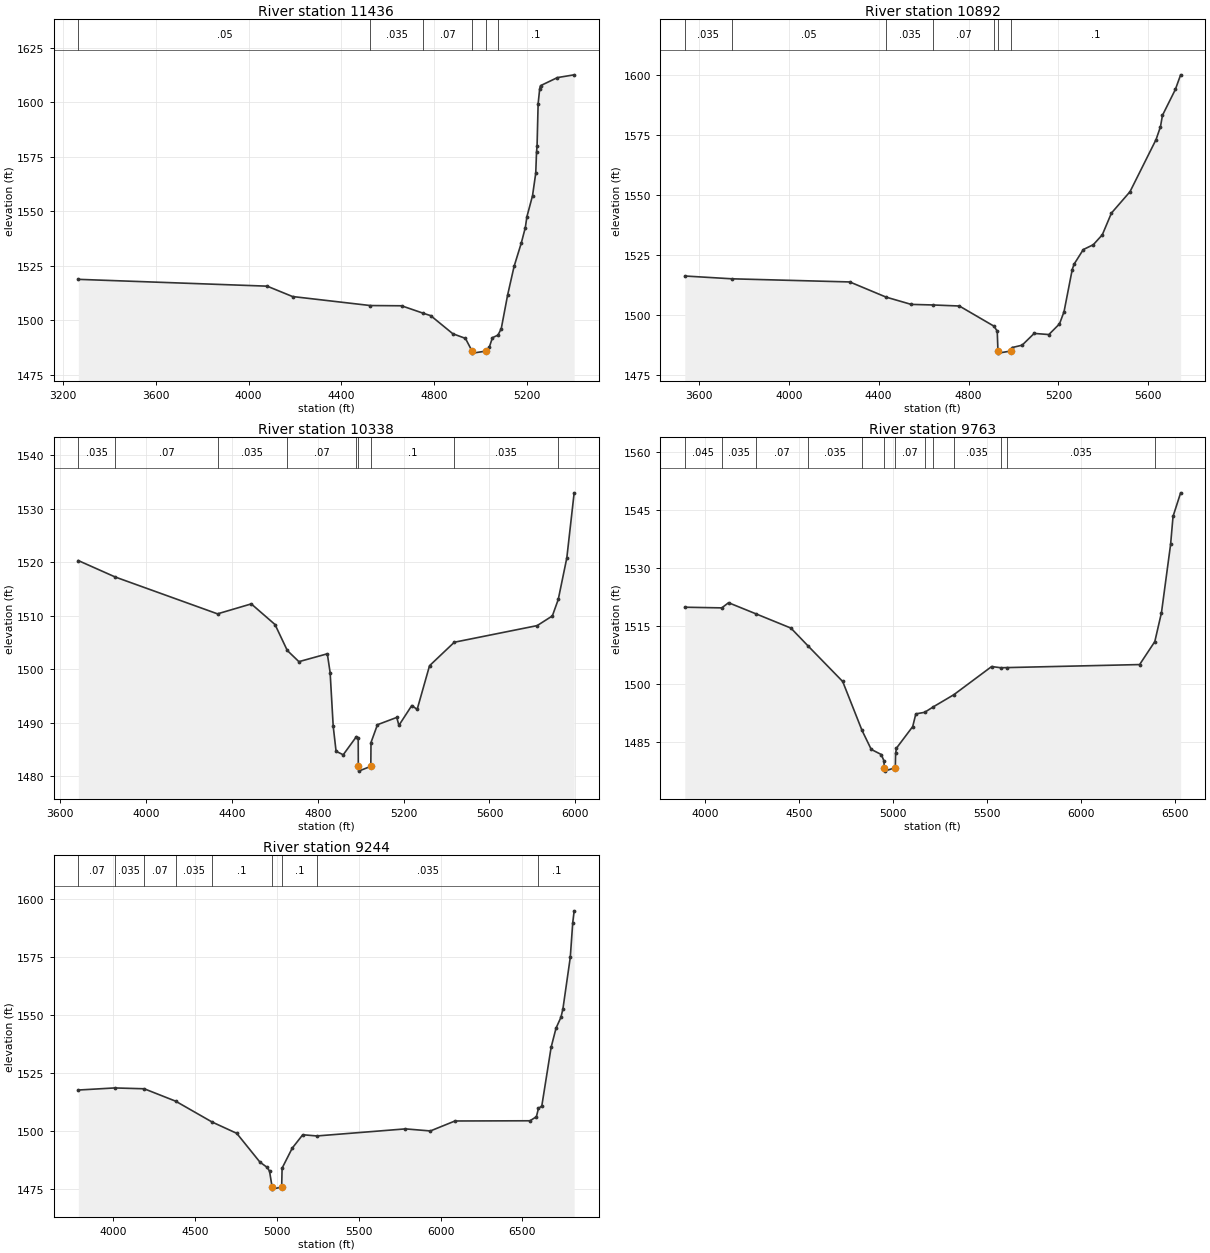
Type RM Length L Ch R = 1 ,11436   ,544,544,544
BEGIN DESCRIPTION:
Verde Creek 20.0
END DESCRIPTION:
XS GIS Cut Line= 3
      1957544.86     13885790.91        1959075.       13884975.
      1959425.01       13884775.
#Sta/Elev= 30
  3265.9 1518.72  4079.8 1515.59  4189.1 1510.83  4524.4 1506.69  4659.1 1506.58
  4753.4 1503.13  4784.9 1502.04  4880.1 1493.74  4934.5 1491.61  4963.2 1485.74
  4964.6 1484.84  5021.4 1485.74  5037.1 1487.48  5050.9 1491.93  5074.7 1493.11
  5088.9  1496.1  5116.5 1511.63  5144.2 1524.67  5175.3 1535.42  5192.6  1542.5
  5199.5 1547.51  5223.6  1557.1  5237.5 1567.45  5240.9 1577.15  5243.2 1579.88
  5247.8 1599.36  5254.7 1606.32  5258.2 1607.65  5330.8 1611.36  5403.1 1612.63
#Mann= 6 ,-1 , 0
  3265.9     .05       0  4524.4    .035       0  4753.4     .07       0
  4963.2     .05       0  5021.4     .07       0  5074.7      .1       0
Bank Sta=4963.2,5021.4
XS Rating Curve= 0 ,0
Exp/Cntr=0.3,0.1

Type RM Length L Ch R = 1 ,10892   ,554,554,554
BEGIN DESCRIPTION:
Verde Creek 19.0
END DESCRIPTION:
XS GIS Cut Line= 3
      1957887.77     13886394.78        1959025.       13885475.
      1959574.98     13884975.02
#Sta/Elev= 30
  3537.5  1516.3    3747 1515.13  4271.5 1513.82  4433.1  1507.5  4544.8 1504.47
    4642 1504.23    4759  1503.8    4913  1495.4  4927.5 1493.33  4930.7 1485.07
  4932.1 1484.17  4988.9 1485.07    4994  1486.5  5038.2 1487.48  5091.8 1492.38
  5157.2 1491.91  5204.5 1496.35  5224.7 1501.43  5261.2    1519  5269.3 1521.21
  5310.3 1527.31  5354.9 1529.33    5395 1533.47  5435.6 1542.51  5518.2 1551.42
  5634.2 1573.15  5653.7 1578.48  5662.6 1583.23    5720 1594.01  5743.4  1600.1
#Mann= 7 ,-1 , 0
  3537.5    .035       0    3747     .05       0  4433.1    .035       0
    4642     .07       0    4913      .1       0  4930.7     .05       0
  4988.9      .1       0
Bank Sta=4930.7,4988.9
XS Rating Curve= 0 ,0
Exp/Cntr=0.3,0.1

Type RM Length L Ch R = 1 ,10338   ,575,575,575
BEGIN DESCRIPTION:
Verde Creek 18.0
END DESCRIPTION:
XS GIS Cut Line= 3
      1958176.68     13886878.16        1959075.       13885925.
      1959675.02     13885124.98
#Sta/Elev= 30
  3684.7 1520.35  3857.8 1517.26  4333.1 1510.39  4490.3 1512.25    4601 1508.39
  4658.1 1503.54  4712.3 1501.45  4844.6 1502.92  4857.7 1499.41    4872 1489.39
  4885.4 1484.69  4918.7 1484.04  4980.3 1487.44  4988.5 1487.18    4989 1481.88
  4990.4 1480.98  5047.2 1481.88  5048.1 1486.33  5078.1 1489.66  5168.1 1491.02
  5178.1 1489.54  5238.1 1493.25  5263.1 1492.52  5320.8 1500.69  5436.1 1505.08
  5822.2 1508.19  5892.9    1510  5920.4 1513.08  5960.3 1520.85  5994.5 1533.02
#Mann= 9 ,-1 , 0
  3684.7    .035       0  3857.8     .07       0  4333.1    .035       0
  4658.1     .07       0  4980.3      .1       0    4989     .05       0
  5047.2      .1       0  5436.1    .035       0  5920.4      .1       0
Bank Sta=4989,5047.2
XS Rating Curve= 0 ,0
Exp/Cntr=0.3,0.1

Type RM Length L Ch R = 1 ,9763    ,519,519,519
BEGIN DESCRIPTION:
Verde Creek 17.0
END DESCRIPTION:
XS GIS Cut Line= 4
      1958694.44      13887366.1        1959275.       13886425.
        1959525.       13885925.      1959882.82      13885024.9
#Sta/Elev= 30
    3894 1519.82  4090.5 1519.65  4126.4 1520.98  4269.5 1518.16  4457.7 1514.43
  4547.6 1509.88  4732.6 1500.65  4835.1 1488.05  4884.2 1483.13  4937.3 1481.81
  4951.2 1480.24  4953.8 1478.42  4955.2 1477.52    5012 1478.42  5013.6 1482.11
  5018.3 1483.46  5104.5 1489.02    5121 1492.29    5168  1492.7  5214.2 1494.12
  5322.5 1497.23  5523.7 1504.51  5572.3  1504.2  5605.8 1504.24  6309.6 1505.02
  6390.3 1510.95  6425.7 1518.43  6474.2 1536.04  6487.1 1543.25  6527.4 1549.34
#Mann= 13 ,-1 , 0
    3894    .045       0  4090.5    .035       0  4269.5     .07       0
  4547.6    .035       0  4835.1     .07       0  4953.8     .05       0
    5012     .07       0    5168      .1       0  5214.2     .07       0
  5322.5    .035       0  5572.3     .07       0  5605.8    .035       0
  6390.3      .1       0
Bank Sta=4953.8,5012
XS Rating Curve= 0 ,0
Exp/Cntr=0.3,0.1

Type RM Length L Ch R = 1 ,9244    ,574,574,574
BEGIN DESCRIPTION:
Verde Creek 16.0
END DESCRIPTION:
XS GIS Cut Line= 5
      1959070.53     13887732.82        1959475.       13887025.
        1959675.       13886675.      1960043.96     13885534.62
      1960049.76     13884921.67
#Sta/Elev= 30
  3785.9  1517.7  4007.8  1518.6  4188.5 1518.24  4380.2  1512.9  4602.8 1503.91
  4753.9 1499.01  4895.6  1486.6  4940.5 1484.28  4954.3 1482.68  4970.1 1475.83
  4971.5 1474.93  5028.4 1475.83  5031.1 1483.99  5093.1 1492.63  5157.3  1498.4
  5243.7 1497.88  5784.8 1500.93  5937.2 1500.04  6087.5 1504.34  6546.1 1504.43
  6585.1 1506.19  6597.5 1509.73  6618.1 1510.83  6675.1 1536.16  6705.1 1544.42
  6735.1 1549.09  6747.1 1552.71  6792.1 1574.96  6807.1 1589.89  6815.8 1595.04
#Mann= 9 ,-1 , 0
  3785.9     .07       0  4007.8    .035       0  4188.5     .07       0
  4380.2    .035       0  4602.8      .1       0  4970.1     .05       0
  5028.4      .1       0  5243.7    .035       0  6597.5      .1       0
Bank Sta=4970.1,5028.4
XS Rating Curve= 0 ,0
Exp/Cntr=0.3,0.1