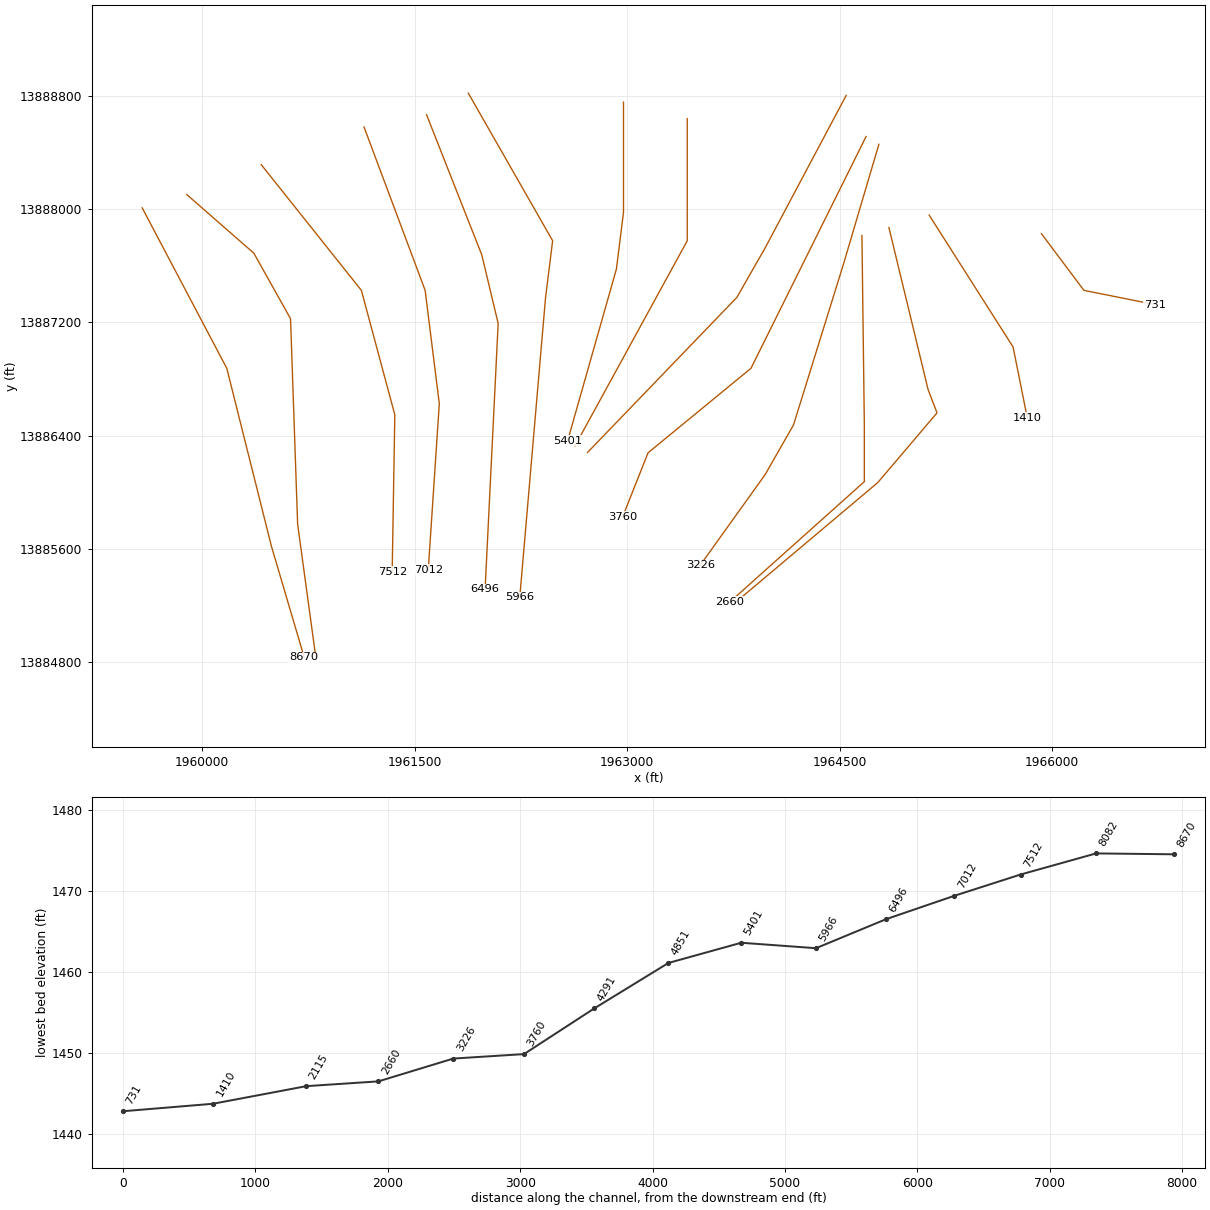
HEC-RAS study Verde Creek.prj: Verde Creek Base Level Engineering

--- Verde Creek.g01 (geometry) --- (continued)

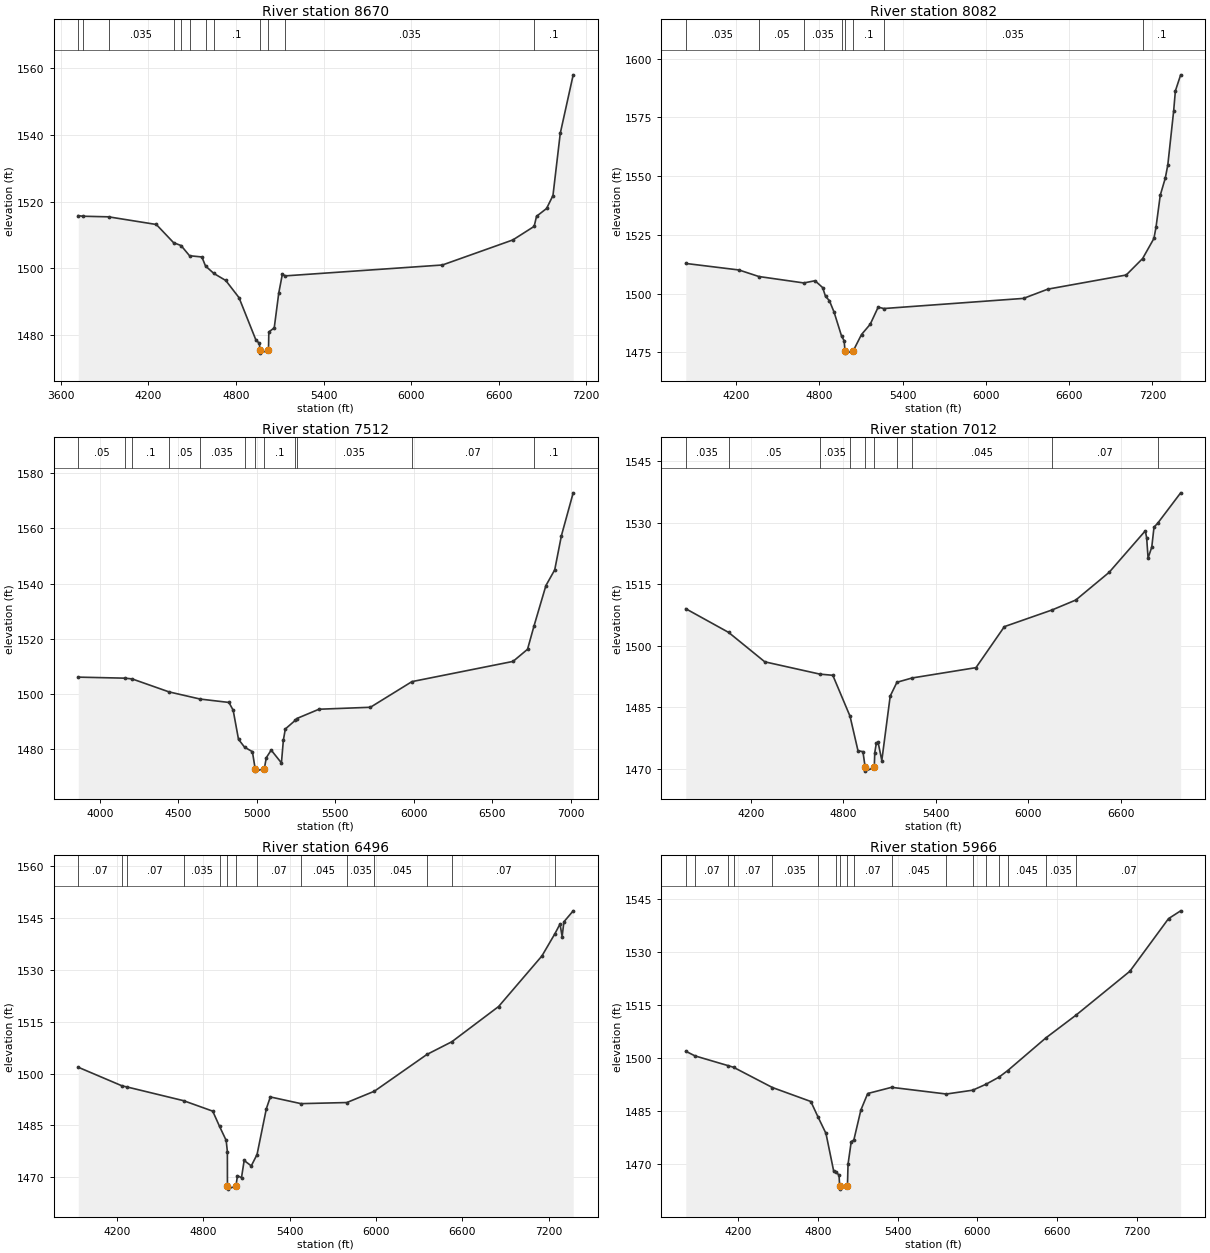
Type RM Length L Ch R = 1 ,8670    ,588,588,588
BEGIN DESCRIPTION:
Verde Creek 15.0
END DESCRIPTION:
XS GIS Cut Line= 5
      1959577.76     13888007.35      1959878.83     13887436.54
        1960175.       13886875.      1960489.98      13885619.1
      1960721.11     13884836.41
#Sta/Elev= 30
  3719.5 1515.79  3749.6 1515.61  3926.8 1515.43  4254.2 1513.13  4372.4 1507.67
  4423.9  1506.8  4481.8 1503.75  4566.3 1503.38  4591.2 1500.67  4648.7 1498.42
    4730 1496.32  4820.7 1491.17    4936 1478.51  4960.4 1477.43  4964.5 1475.41
  4965.9 1474.51  5022.8 1475.41  5025.1 1480.86  5062.2  1482.1  5093.2 1492.57
  5117.9 1498.22  5136.6  1497.7  6214.5 1500.97    6697 1508.49  6843.1 1512.56
  6859.4 1515.59  6928.2 1517.93    6972 1521.83    7022  1540.5  7110.6 1558.06
#Mann= 12 ,-1 , 0
  3719.5    .035       0  3749.6     .07       0  3926.8    .035       0
  4372.4     .07       0  4423.9    .035       0  4481.8      .1       0
  4591.2    .035       0  4648.7      .1       0  4964.5     .05       0
  5022.8      .1       0  5136.6    .035       0  6843.1      .1       0
Bank Sta=4964.5,5022.8
XS Rating Curve= 0 ,0
Exp/Cntr=0.3,0.1

Type RM Length L Ch R = 1 ,8082    ,570,570,570
BEGIN DESCRIPTION:
Verde Creek 14.0
END DESCRIPTION:
XS GIS Cut Line= 5
      1959892.35     13888101.42      1960365.93     13887687.57
        1960625.       13887225.        1960675.       13885775.
      1960804.36     13884826.45
#Sta/Elev= 30
  3836.7 1512.81  4220.3 1510.03  4363.3 1507.25  4687.6 1504.51  4768.5 1505.45
  4823.5 1502.52  4844.1 1498.78  4871.6 1497.02    4906 1492.04  4960.3 1481.77
  4978.2 1479.94  4984.7 1475.52  4986.1 1474.62  5043.1 1475.52  5103.5 1482.55
  5166.2 1486.91  5223.6  1494.2  5264.3 1493.61  6271.2 1497.93  6446.7 1501.87
  7011.5 1507.89  7129.7  1514.9  7211.3 1523.47  7226.5 1528.33  7256.8 1541.84
  7293.1 1549.15  7311.3 1554.74  7353.6 1577.84  7365.8 1586.28    7404 1593.14
#Mann= 8 ,-1 , 0
  3836.7    .035       0  4363.3     .05       0  4687.6    .035       0
  4960.3      .1       0  4984.7     .05       0  5043.1      .1       0
  5264.3    .035       0  7129.7      .1       0
Bank Sta=4984.7,5043.1
XS Rating Curve= 0 ,0
Exp/Cntr=0.3,0.1

Type RM Length L Ch R = 1 ,7512    ,500,500,500
BEGIN DESCRIPTION:
Verde Creek 13.0
END DESCRIPTION:
XS GIS Cut Line= 4
      1960418.43     13888311.93        1961125.       13887425.
      1961361.05     13886546.45      1961342.35     13885437.48
#Sta/Elev= 30
  3861.9 1506.08  4157.7 1505.71  4204.8 1505.44  4439.5 1500.74  4638.8 1498.13
  4821.6 1496.91  4848.5  1494.1  4882.6 1483.54  4921.4 1480.69  4971.1 1479.07
  4988.6 1472.92    4990 1472.02    5047 1472.92  5059.7 1476.89  5090.8 1479.64
    5156 1474.99  5168.4 1483.26  5180.9  1487.3  5244.4 1490.44  5254.2 1491.09
  5395.2 1494.45  5722.9 1495.16  5987.5 1504.46  6631.4 1511.78  6723.8 1516.17
  6764.6 1524.53  6840.9 1539.26    6897 1544.96  6939.8 1557.38  7014.7 1572.87
#Mann= 12 ,-1 , 0
  3861.9     .05       0  4157.7    .035       0  4204.8      .1       0
  4439.5     .05       0  4638.8    .035       0  4921.4      .1       0
  4988.6     .05       0    5047      .1       0  5244.4      .1       0
  5254.2    .035       0  5987.5     .07       0  6764.6      .1       0
Bank Sta=4988.6,5047
XS Rating Curve= 0 ,0
Exp/Cntr=0.3,0.1

Type RM Length L Ch R = 1 ,7012    ,516,516,516
BEGIN DESCRIPTION:
Verde Creek 12.0
END DESCRIPTION:
XS GIS Cut Line= 5
      1961143.84     13888577.66      1961323.29     13888097.91
        1961575.       13887425.        1961675.       13886625.
      1961597.12     13885454.37
#Sta/Elev= 30
  3778.2 1509.04  4056.2 1503.26  4290.8 1496.08  4647.9 1493.08    4732 1492.79
  4843.6 1482.81  4895.3 1474.38  4927.4 1474.15  4942.1  1470.3  4943.5  1469.4
  5000.9  1470.3  5004.2 1473.93  5014.1 1476.17  5025.7 1476.45  5049.8 1471.99
  5104.3 1487.72  5147.9 1491.09  5246.6 1492.14  5660.6 1494.66  5844.8 1504.67
  6153.4 1508.73  6307.8 1511.16  6524.3 1517.92    6759 1528.06  6767.8 1526.31
  6776.9 1521.39  6800.9  1524.1  6815.4 1528.96  6838.1 1529.85  6988.3 1537.33
#Mann= 10 ,-1 , 0
  3778.2    .035       0  4056.2     .05       0  4647.9    .035       0
  4843.6     .07       0  4942.1     .05       0  5000.9     .07       0
  5147.9    .035       0  5246.6    .045       0  6153.4     .07       0
  6838.1      .1       0
Bank Sta=4942.1,5000.9
XS Rating Curve= 0 ,0
Exp/Cntr=0.3,0.1

Type RM Length L Ch R = 1 ,6496    ,530,530,530
BEGIN DESCRIPTION:
Verde Creek 11.0
END DESCRIPTION:
XS GIS Cut Line= 4
      1961585.24     13888664.25        1961975.       13887675.
      1962090.44      13887191.4      1961998.26     13885315.81
#Sta/Elev= 30
  3932.5 1501.82  4237.8 1496.41  4271.3 1496.11  4663.7 1492.14  4866.4 1489.11
  4913.6 1484.72  4959.9 1480.63  4968.2 1477.41  4968.7 1467.42  4970.1 1466.52
  5027.5 1467.42  5038.6 1470.41  5066.4 1469.83  5084.9 1474.82  5134.2 1473.25
  5174.4 1476.54  5239.1 1489.83  5266.8 1493.22  5479.7 1491.28  5798.2  1491.6
  5989.6 1494.88  6354.7 1505.53  6527.7 1509.21  6852.6 1519.41  7153.7 1534.07
  7244.2 1540.53  7279.2 1543.31    7294 1539.69  7306.2 1543.94  7370.8 1547.13
#Mann= 14 ,-1 , 0
  3932.5     .07       0  4237.8    .035       0  4271.3     .07       0
  4663.7    .035       0  4913.6      .1       0  4968.7     .05       0
  5027.5      .1       0  5174.4     .07       0  5479.7    .045       0
  5798.2    .035       0  5989.6    .045       0  6354.7    .035       0
  6527.7     .07       0  7244.2      .1       0
Bank Sta=4968.7,5027.5
XS Rating Curve= 0 ,0
Exp/Cntr=0.3,0.1

Type RM Length L Ch R = 1 ,5966    ,565,565,565
BEGIN DESCRIPTION:
Verde Creek 10.0
END DESCRIPTION:
XS GIS Cut Line= 5
      1961879.72     13888816.74        1962275.       13888125.
        1962475.       13887775.        1962425.       13887375.
      1962242.97     13885259.75
#Sta/Elev= 30
  3804.3 1501.94    3874 1500.62  4125.5 1497.84  4163.8  1497.4    4457 1491.67
    4746 1487.72  4798.5 1483.47  4859.8  1478.7  4918.5 1467.95  4935.5 1467.69
  4958.2 1466.94  4962.8 1463.84  4964.3 1462.94  5021.7 1463.84    5026 1469.99
  5050.1 1476.37  5069.8 1476.84  5122.7 1485.32  5174.1 1489.98  5353.8 1491.73
  5766.3 1489.84  5964.3 1490.92  6063.3 1492.58  6162.3 1494.61  6228.3 1496.47
  6515.4 1505.71  6742.1 1512.14  7147.9 1524.56    7439 1539.45  7530.3 1541.65
#Mann= 18 ,-1 , 0
  3804.3    .035       0    3874     .07       0  4125.5    .035       0
  4163.8     .07       0    4457    .035       0  4798.5     .07       0
  4935.5      .1       0  4962.8     .05       0  5021.7      .1       0
  5069.8     .07       0  5353.8    .045       0  5766.3     .07       0
  5964.3    .035       0  6063.3    .045       0  6162.3    .035       0
  6228.3    .045       0  6515.4    .035       0  6742.1     .07       0
Bank Sta=4962.8,5021.7
XS Rating Curve= 0 ,0
Exp/Cntr=0.3,0.1

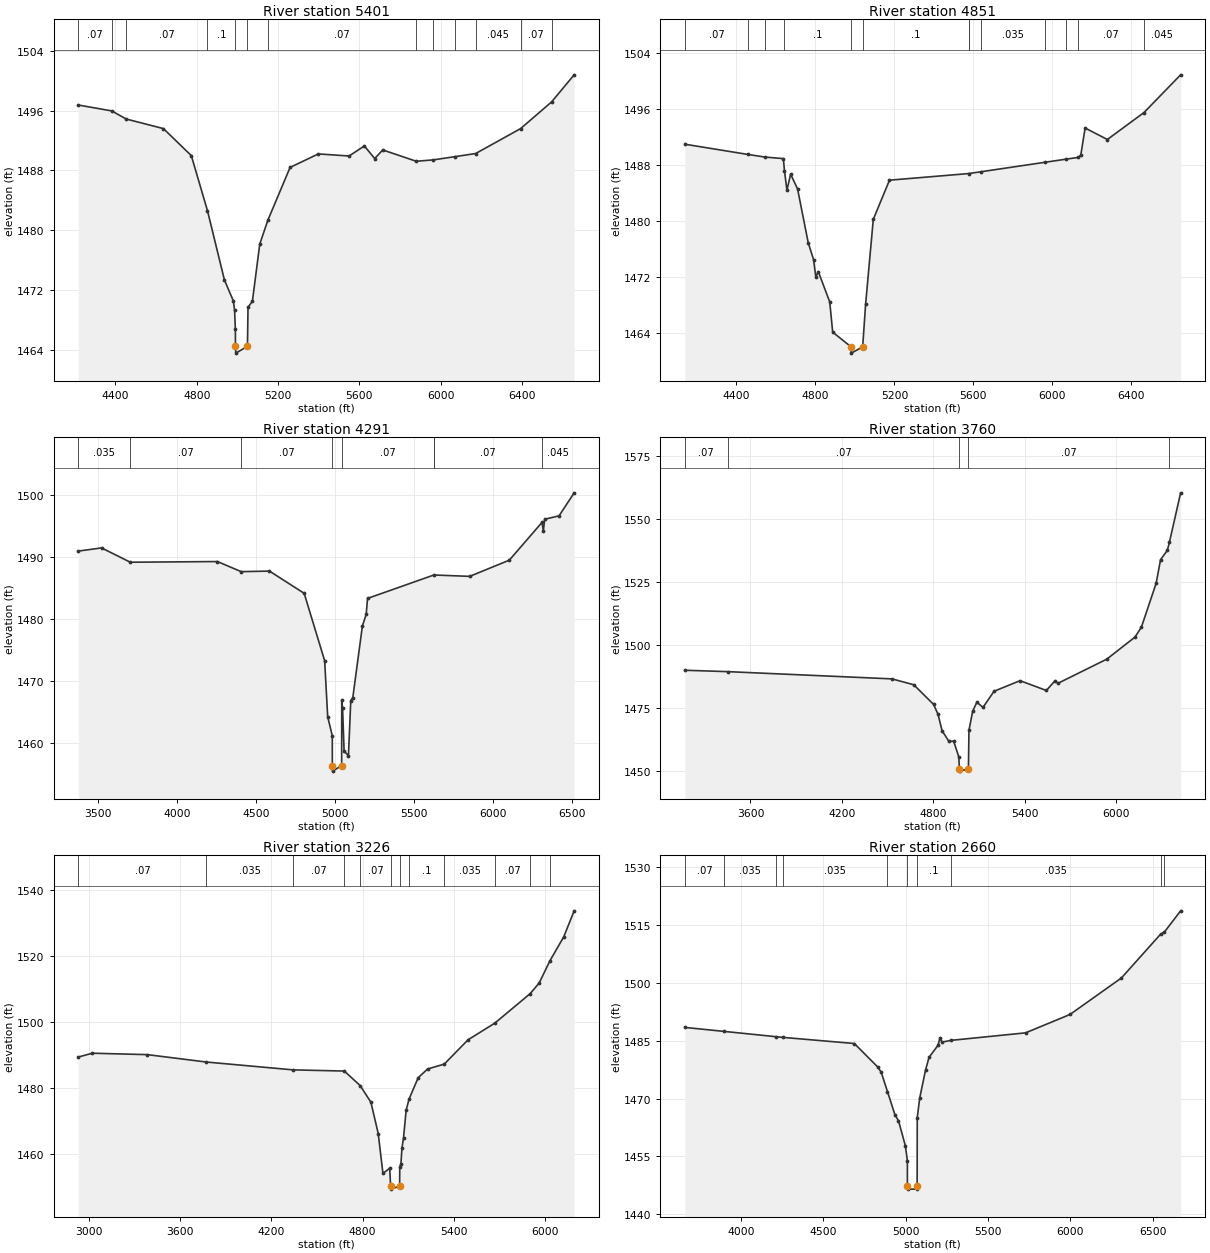
Type RM Length L Ch R = 1 ,5401    ,550,550,550
BEGIN DESCRIPTION:
Verde Creek 9.0
END DESCRIPTION:
XS GIS Cut Line= 5
        1962975.      13888753.4        1962975.       13888375.
        1962975.       13887975.        1962925.       13887575.
      1962580.96     13886364.03
#Sta/Elev= 30
  4217.4 1496.74  4382.2 1495.95  4452.8 1494.87  4636.3 1493.59  4773.5 1489.98
  4853.1 1482.62  4936.3 1473.39  4980.5 1470.57  4986.5 1469.31  4990.3 1466.77
  4990.9 1464.51  4992.4 1463.61  5049.8 1464.51  5052.6 1469.74  5074.1 1470.53
  5110.3 1478.16    5150 1481.34  5259.6 1488.41  5398.9 1490.21  5549.9 1489.93
  5625.2 1491.27  5676.2 1489.59  5715.6 1490.74  5880.7 1489.23  5963.7 1489.41
  6069.6 1489.84  6172.8 1490.26  6394.3 1493.59  6546.9 1497.16  6657.8 1500.77
#Mann= 13 ,-1 , 0
  4217.4     .07       0  4382.2    .035       0  4452.8     .07       0
  4853.1      .1       0  4990.9     .05       0  5049.8      .1       0
    5150     .07       0  5880.7    .045       0  5963.7    .035       0
  6069.6     .07       0  6172.8    .045       0  6394.3     .07       0
  6546.9    .045       0
Bank Sta=4990.9,5049.8
XS Rating Curve= 0 ,0
Exp/Cntr=0.3,0.1

Type RM Length L Ch R = 1 ,4851    ,560,560,560
BEGIN DESCRIPTION:
Verde Creek 8.0
END DESCRIPTION:
XS GIS Cut Line= 4
        1963425.     13888636.51        1963425.       13888175.
        1963425.       13887775.      1962633.16     13886327.89
#Sta/Elev= 30
  4138.5 1490.97  4459.2  1489.5  4544.7 1489.13  4637.7 1488.91  4643.1  1487.2
  4655.7  1484.4  4674.5 1486.69  4709.7 1484.57  4763.7 1476.88  4790.7 1474.48
  4801.9 1472.01  4814.7 1472.76  4872.5 1468.44  4887.5 1464.12  4980.5 1462.02
  4981.9 1461.12  5039.4 1462.02  5054.1 1468.07  5093.1 1480.23  5175.2 1485.83
  5575.4 1486.77  5640.3 1487.04  5961.2 1488.38  6069.4 1488.83  6130.8 1489.08
  6143.8 1489.38  6165.9 1493.28  6278.6 1491.64    6464 1495.49  6649.6 1500.88
#Mann= 13 ,-1 , 0
  4138.5     .07       0  4459.2    .035       0  4544.7     .07       0
  4643.1      .1       0  4980.5     .05       0  5039.4      .1       0
  5575.4    .035       0  5575.4     .07       0  5640.3    .035       0
  5961.2     .07       0  6069.4    .035       0  6130.8     .07       0
    6464    .045       0
Bank Sta=4980.5,5039.4
XS Rating Curve= 0 ,0
Exp/Cntr=0.3,0.1

Type RM Length L Ch R = 1 ,4291    ,531,531,531
BEGIN DESCRIPTION:
Verde Creek 7.0
END DESCRIPTION:
XS GIS Cut Line= 4
      1964547.03     13888801.37        1963975.       13887725.
        1963775.       13887375.      1962721.77     13886281.47
#Sta/Elev= 30
  3372.9 1491.03  3519.8 1491.54  3702.3 1489.23    4254 1489.34  4404.6 1487.71
  4583.5  1487.8  4803.3 1484.21    4933 1473.33  4952.2 1464.29  4981.4 1461.23
  4981.6 1456.42  4983.1 1455.52  5040.6 1456.42  5041.2 1466.92  5046.5 1465.68
  5056.1 1458.77  5083.7 1458.01  5098.4  1466.9  5111.3 1467.39    5172 1478.94
  5196.1 1480.81  5204.6 1483.39  5624.7 1487.17  5851.7 1486.95  6102.4 1489.56
  6309.3 1495.65    6318 1494.29  6326.6 1496.17  6417.4 1496.71  6513.2 1500.43
#Mann= 8 ,-1 , 0
  3372.9    .035       0  3702.3     .07       0  4404.6     .07       0
  4981.6     .05       0  5040.6     .07       0  5624.7    .035       0
  5624.7     .07       0  6309.3    .045       0
Bank Sta=4981.6,5040.6
XS Rating Curve= 0 ,0
Exp/Cntr=0.3,0.1

Type RM Length L Ch R = 1 ,3760    ,534,534,534
BEGIN DESCRIPTION:
Verde Creek 6.0
END DESCRIPTION:
XS GIS Cut Line= 4
      1964687.11     13888510.76        1963875.       13886875.
      1963148.29     13886278.32      1962968.41     13885824.95
#Sta/Elev= 30
  3168.9 1489.89  3449.8 1489.34  4528.5 1486.47  4671.7 1484.14  4801.5 1476.37
  4830.6  1472.5  4857.5 1465.92  4902.5 1461.66  4933.6 1461.77  4967.2 1455.53
  4971.4 1450.79  4972.9 1449.89  5030.4 1450.79    5034 1466.05  5058.3 1473.63
  5085.5 1477.18  5126.2 1475.19  5198.7 1481.56  5369.2 1485.75  5541.9 1481.87
  5599.4 1485.76  5617.3 1484.69  5938.6 1494.29  6123.7 1503.04  6165.7 1506.97
  6262.5 1524.36  6291.5 1533.74    6336 1537.41  6349.6 1540.61  6423.2 1560.24
#Mann= 5 ,-1 , 0
  3168.9     .07       0  3449.8     .07       0  4971.4     .05       0
  5030.4     .07       0  6349.6     .07       0
Bank Sta=4971.4,5030.4
XS Rating Curve= 0 ,0
Exp/Cntr=0.3,0.1

Type RM Length L Ch R = 1 ,3226    ,566,566,566
BEGIN DESCRIPTION:
Verde Creek 5.0
END DESCRIPTION:
XS GIS Cut Line= 5
      1964777.56      13888455.8      1964528.15      13887611.9
        1964175.       13886475.        1963975.       13886125.
      1963516.16     13885484.34
#Sta/Elev= 30
  2929.5 1489.33  3021.9 1490.48  3383.6 1490.05  3772.1 1487.81  4341.7 1485.44
    4679 1485.08  4783.2 1480.69  4854.1 1475.65  4902.2 1466.16  4933.2  1454.1
  4977.6 1455.64  4983.9 1450.24  4985.4 1449.34    5043 1450.24  5043.9 1456.08
  5051.4 1456.88  5058.3 1461.76  5068.7 1464.92    5086 1473.25  5105.7 1476.68
  5165.2 1483.07  5226.8  1485.7  5336.5 1487.18  5492.5 1494.52    5669 1499.58
  5901.7 1508.51  5961.1 1511.74  6031.5 1518.44    6123 1525.75  6191.1 1533.58
#Mann= 12 ,-1 , 0
  2929.5     .07       0  3772.1    .035       0  4341.7     .07       0
    4679    .035       0  4783.2     .07       0  4983.9     .05       0
    5043      .1       0  5105.7      .1       0  5336.5    .035       0
    5669     .07       0  5901.7      .1       0  6031.5    .035       0
Bank Sta=4983.9,5043
XS Rating Curve= 0 ,0
Exp/Cntr=0.3,0.1

Type RM Length L Ch R = 1 ,2660    ,545,545,545
BEGIN DESCRIPTION:
Verde Creek 4.0
END DESCRIPTION:
XS GIS Cut Line= 4
      1964657.94     13887812.05        1964675.       13886475.
        1964675.       13886075.      1963725.44     13885225.28
#Sta/Elev= 30
  3658.3 1488.42  3898.6 1487.38  4213.9 1486.01  4253.7 1485.84    4688 1484.25
  4830.1 1478.17  4851.1 1476.82  4889.2  1471.8  4935.1 1465.73  4956.1 1464.27
  4998.1 1457.72  5010.1  1453.9  5010.3 1447.43  5011.8 1446.53  5068.1 1446.53
  5069.5 1447.43  5070.1 1465.04  5085.1 1470.14  5121.1 1477.49  5141.9 1480.68
  5196.1 1483.78  5208.1 1485.68  5220.1 1484.61  5276.3 1485.07  5727.9 1487.01
  5997.8 1491.77  6310.1 1501.23  6548.2 1512.58  6571.4 1513.14  6669.7 1518.62
#Mann= 10 ,-1 , 0
  3658.3     .07       0  3898.6    .035       0  4213.9     .07       0
  4253.7    .035       0  4889.2      .1       0  5010.3     .05       0
  5069.5      .1       0  5276.3    .035       0  6548.2     .07       0
  6571.4    .035       0
Bank Sta=5010.3,5069.5
XS Rating Curve= 0 ,0
Exp/Cntr=0.3,0.1

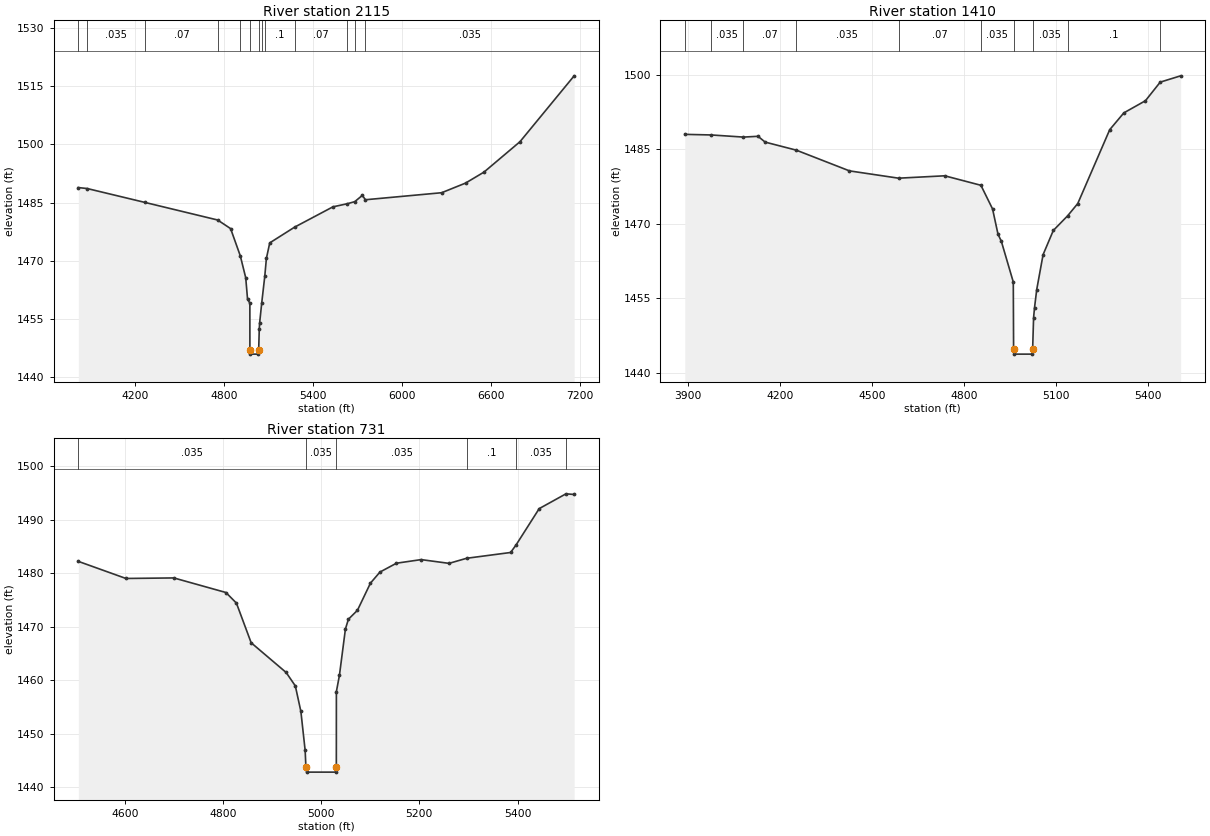
Type RM Length L Ch R = 1 ,2115    ,705,705,705
BEGIN DESCRIPTION:
Verde Creek 3.0
END DESCRIPTION:
XS GIS Cut Line= 5
      1964848.37      13887868.5        1965125.       13886725.
      1965188.08     13886560.39        1964770.     13886068.63
      1963743.42     13885203.85
#Sta/Elev= 30
  3819.6 1488.87  3879.4 1488.62  4269.5 1485.03  4758.2 1480.51  4845.5 1478.29
    4911 1471.25  4947.4 1465.62  4959.7 1460.08  4975.2 1459.09  4975.4 1446.94
  4976.9 1445.94  5033.2 1445.94  5034.6 1446.94  5038.6 1452.31  5040.9 1453.89
  5055.3 1459.18  5075.6 1465.96  5086.7 1470.63  5109.2 1474.61  5277.2 1478.68
  5534.8  1483.9  5631.4  1484.7  5681.9 1485.24  5732.9 1486.85  5753.9 1485.73
  6267.3 1487.54  6428.2 1490.02  6552.4 1492.85  6795.1 1500.69  7160.1 1517.67
#Mann= 13 ,-1 , 0
  3819.6     .07       0  3879.4    .035       0  4269.5     .07       0
  4758.2    .035       0    4911      .1       0  4975.4     .05       0
  5034.6      .1       0  5055.3     .07       0  5075.6      .1       0
  5277.2     .07       0  5631.4    .035       0  5681.9     .07       0
  5753.9    .035       0
Bank Sta=4975.4,5034.6
XS Rating Curve= 0 ,0
Exp/Cntr=0.3,0.1

Type RM Length L Ch R = 1 ,1410    ,679,679,679
BEGIN DESCRIPTION:
Verde Creek 2.0
END DESCRIPTION:
XS GIS Cut Line= 3
      1965132.27     13887956.53        1965725.       13887025.
        1965825.     13886525.02
#Sta/Elev= 30
  3891.2    1488  3977.2 1487.88  4082.1 1487.45  4129.5 1487.61  4152.8 1486.44
  4254.2 1484.82  4427.2 1480.65    4587 1479.18  4737.3 1479.66  4855.1 1477.75
    4893 1472.99  4910.8 1467.89  4921.4 1466.52  4960.5 1458.28  4961.5 1444.77
    4963 1443.77    5022 1443.77  5023.5 1444.77  5026.6 1451.13  5029.6 1453.09
  5036.8 1456.77  5057.5 1463.79  5090.8 1468.66  5137.3  1471.6  5170.4 1474.08
  5274.4 1488.94  5320.3 1492.32  5390.7 1494.77  5438.8 1498.51  5505.2 1499.78
#Mann= 10 ,-1 , 0
  3891.2      .1       0  3977.2    .035       0  4082.1     .07       0
  4254.2    .035       0    4587     .07       0  4855.1    .035       0
  4961.5    .035       0  5023.5    .035       0  5137.3      .1       0
  5438.8     .07       0
Bank Sta=4961.5,5023.5
XS Rating Curve= 0 ,0
Exp/Cntr=0.3,0.1

Type RM Length L Ch R = 1 ,731     ,0,0,0
BEGIN DESCRIPTION:
Verde Creek 1.0
END DESCRIPTION:
XS GIS Cut Line= 3
      1965925.03     13887824.96        1966225.       13887425.
      1966725.05     13887324.99
#Sta/Elev= 30
  4505.5 1482.19  4602.5    1479    4700  1479.1  4806.1 1476.38  4827.5  1474.4
  4857.5    1467  4928.8 1461.45  4947.5 1458.94  4958.8 1454.17  4967.5 1446.89
    4969 1443.85  4970.5 1442.85  5029.5 1442.85    5031 1443.85  5031.1 1457.88
  5037.3 1460.91  5049.5 1469.56  5055.6 1471.39    5074 1473.06  5100.5 1478.13
  5119.9  1480.2  5153.5 1481.85  5203.7 1482.52  5260.6 1481.82  5296.4 1482.77
    5386 1483.85  5397.6 1485.33  5444.2 1492.04  5498.7  1494.8  5515.4 1494.68
#Mann= 6 ,-1 , 0
  4505.5    .035       0    4969    .035       0    5031    .035       0
  5296.4      .1       0  5397.6    .035       0  5498.7     .07       0
Bank Sta=4969,5031
XS Rating Curve= 0 ,0
Exp/Cntr=0.3,0.1

Chan Stop Cuts=-1
Use User Specified Reach Order=0
Composite Channel Slope=5