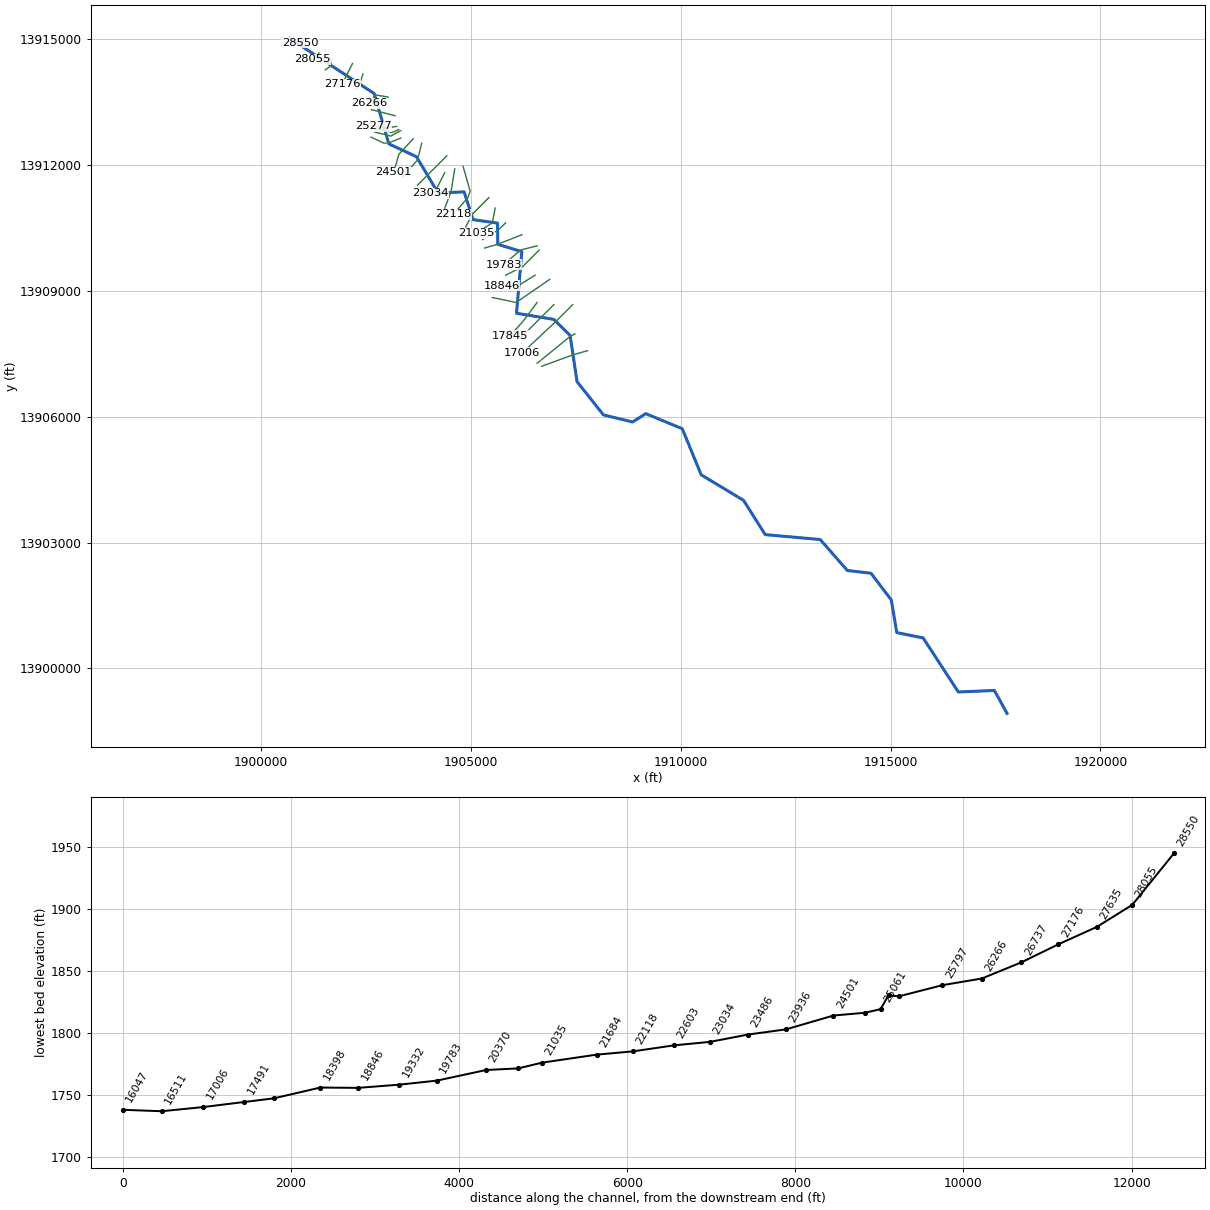
--- West Creek.prj (project) ---

Proj Title=West Creek Base Level Engineering
Current Plan=p01
Default Exp/Contr=0.3,0.1
English Units
Geom File=g01
Flow File=f01
Plan File=p01
BEGIN DESCRIPTION:
West Creek
END DESCRIPTION:

--- West Creek.p01 (plan) ---

Plan Title=Multiple Run
Short Identifier=Multiple
Geom File=g01
Flow File=f01
Subcritical Flow
K Sum by GR= 0
Std Step Tol= 0.01
Critical Tol= 0.01
Num of Std Step Trials= 20
Max Error Tol= 0.3
Flow Tol Ratio= 0.001
Split Flow NTrial= 30
Split Flow Tol= 0.02
Split Flow Ratio= 0.02
Log Output Level= 0
Friction Slope Method= 1
Unsteady Friction Slope Method= 2
Unsteady Bridges Friction Slope Method= 1
Parabolic Critical Depth
Global Vel Dist=  1 , 1 , 1
Global Log Level= 0
CheckData=True
Encroach Param= -1, 0, 0, 0
BEGIN DESCRIPTION:
Multiple Run
END DESCRIPTION:

--- West Creek.f01 (steady flow) ---

Flow Title=Multiple
Number of Profiles=7
Profile Names=10-year,25-year,50-year,1pct_min,100-year,1pct_plu,500-year
River Rch & RM= West Creek,Reach-1,28550
     724    1204    1650    1097    2189    4367    3794
River Rch & RM= West Creek,Reach-1,23936
    1683    2949    4186    2871    5729   11431   10603
River Rch & RM= West Creek,Reach-1,21035
    2159    3825    5469    3774    7531   15025   14113
River Rch & RM= West Creek,Reach-1,17845
    2988    5371    7754    5395   10764   21478   20516
River Rch & RM= West Creek,Reach-1,14179
    3437    6197    8965    6245   12460   24861   23811
River Rch & RM= West Creek,Reach-1,7446
    4264    7766   11310    7927   15817   31559   30603
River Rch & RM= West Creek,Reach-1,6878
    4569    8332   12145    8517   16993   33905   32911
River Rch & RM= West Creek,Reach-1,2814
    5449    9964   14554   10223   20398   40698   39618
Boundary for River Rch & Prof#=West Creek,Reach-1,1
Up Type=0
Dn Type=3
Dn Slope=0.005
Boundary for River Rch & Prof#=West Creek,Reach-1,2
Up Type=0
Dn Type=3
Dn Slope=0.005
Boundary for River Rch & Prof#=West Creek,Reach-1,3
Up Type=0
Dn Type=3
Dn Slope=0.005
Boundary for River Rch & Prof#=West Creek,Reach-1,4
Up Type=0
Dn Type=3
Dn Slope=0.005
Boundary for River Rch & Prof#=West Creek,Reach-1,5
Up Type=0
Dn Type=3
Dn Slope=0.005
Boundary for River Rch & Prof#=West Creek,Reach-1,6
Up Type=0
Dn Type=3
Dn Slope=0.005
Boundary for River Rch & Prof#=West Creek,Reach-1,7
Up Type=0
Dn Type=3
Dn Slope=0.005

--- West Creek.g01 (geometry) ---

Geom Title=Existing Conditions

River Reach=West Creek,Reach-1
Reach XY= 30
      1900675.00     13915025.00      1902691.79     13913708.56
      1903041.43     13912508.23      1903698.91     13912202.30
      1904218.52     13911332.69      1904835.12     13911364.66
      1905047.86     13910701.43      1905631.52     13910617.33
      1905638.19     13910111.26      1906211.39     13909938.24
      1906084.29     13908468.34      1906973.54     13908321.46
      1907361.60     13907938.30      1907526.92     13906836.95
      1908154.91     13906044.78      1908850.12     13905874.70
      1909164.49     13906073.80      1910034.68     13905714.22
      1910485.52     13904615.21      1911495.47     13904005.37
      1912011.66     13903188.36      1913323.48     13903071.26
      1913968.83     13902332.86      1914531.06     13902267.52
      1915015.87     13901631.74      1915147.85     13900851.16
      1915775.00     13900725.00      1916614.88     13899435.35
      1917473.55     13899471.47      1917775.00     13898925.00

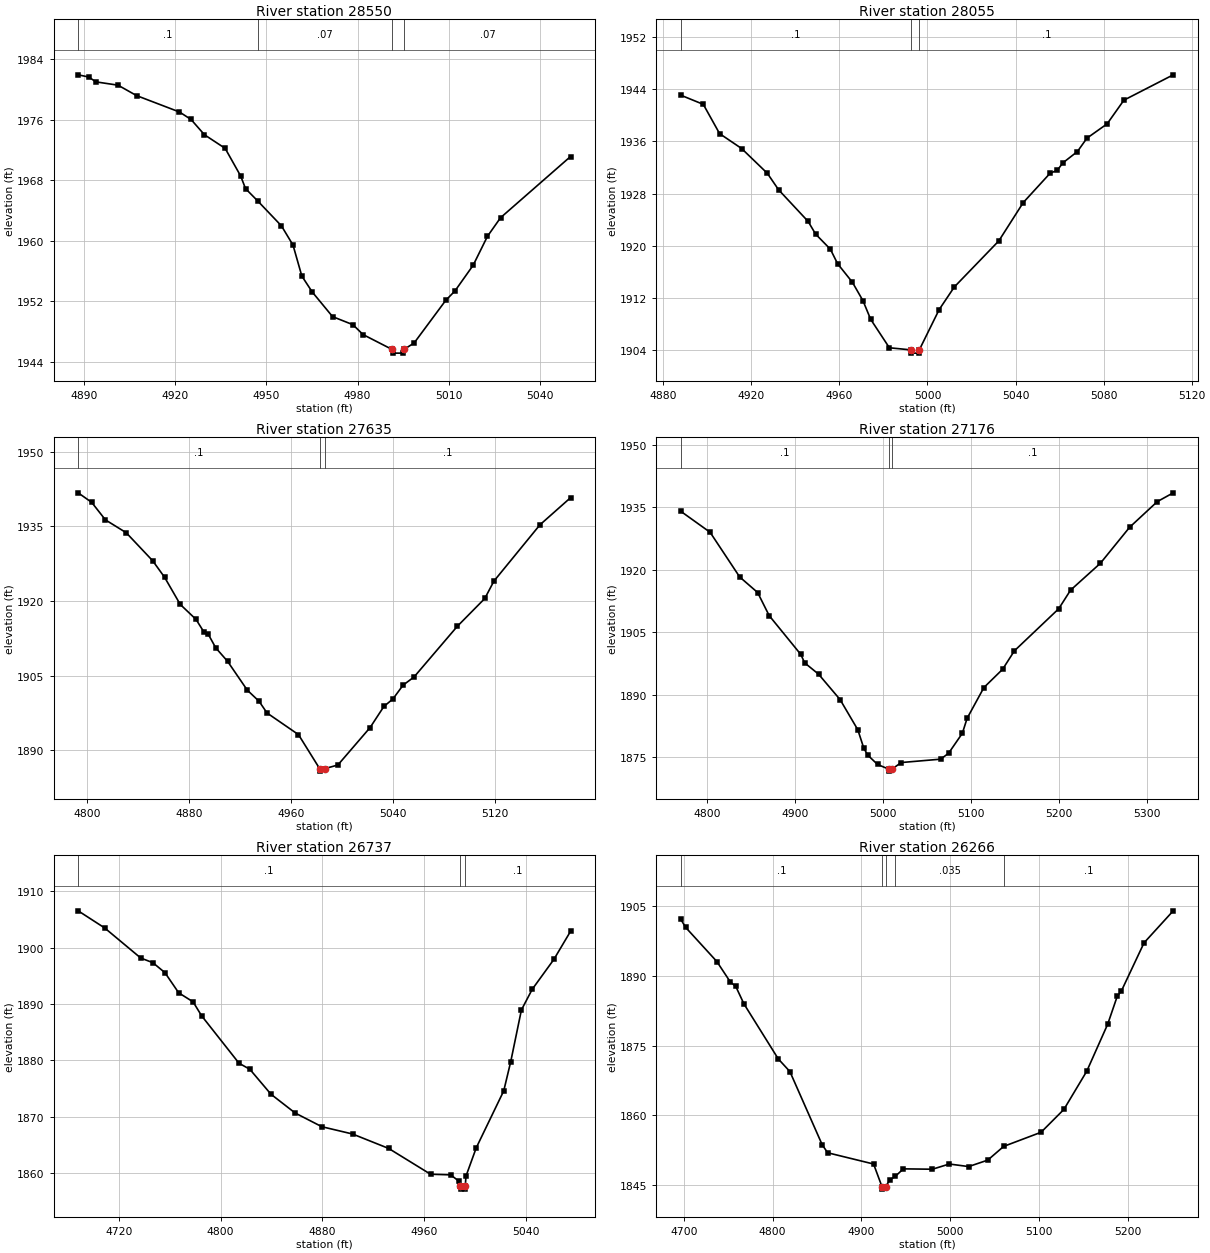
Type RM Length L Ch R = 1,28550,495,495,495
BEGIN DESCRIPTION:
West Creek 61.0
END DESCRIPTION:
XS GIS Cut Line= 3
      1901025.01     13915025.01      1900975.00     13914925.00
      1900925.02     13914925.00
#Sta/Elev= 30
  4888.2 1981.95  4891.7 1981.66  4894.0 1981.02  4901.3 1980.58  4907.4 1979.20
  4921.5 1977.03  4925.3 1976.04  4929.7 1974.02  4936.5 1972.22  4941.6 1968.56
  4943.2 1966.89  4947.2 1965.26  4955.0 1961.96  4958.8 1959.42  4961.7 1955.32
  4965.1 1953.22  4971.8 1949.95  4978.5 1948.88  4981.8 1947.58  4991.3 1945.62
  4991.5 1945.12  4995.0 1945.12  4995.3 1945.62  4998.6 1946.46  5009.0 1952.11
  5012.0 1953.34  5018.0 1956.75  5022.7 1960.58  5027.0 1963.04  5050.0 1971.14
#Mann=4,-1,0
  4888.2     0.1       0  4947.2    0.07       0  4991.3    0.05       0
  4995.3    0.07       0
Bank Sta=4991.3,4995.3
Exp/Cntr=0.3,0.1

Type RM Length L Ch R = 1,28055,420,420,420
BEGIN DESCRIPTION:
West Creek 60.0
END DESCRIPTION:
XS GIS Cut Line= 3
      1901374.99     13914674.97      1901325.00     13914575.00
      1901224.98     13914524.99
#Sta/Elev= 30
  4888.0 1943.06  4898.2 1941.66  4905.6 1937.18  4915.6 1934.90  4927.3 1931.10
  4932.4 1928.58  4945.8 1923.74  4949.2 1921.80  4955.9 1919.49  4959.2 1917.26
  4965.9 1914.43  4970.7 1911.61  4974.2 1908.76  4982.7 1904.40  4992.3 1904.08
  4992.6 1903.58  4996.1 1903.58  4996.3 1904.08  5005.3 1910.24  5012.2 1913.71
  5032.4 1920.76  5043.5 1926.63  5055.7 1931.12  5059.0 1931.57  5061.4 1932.68
  5068.1 1934.44  5072.4 1936.48  5081.6 1938.68  5089.2 1942.30  5111.6 1946.18
#Mann=3,-1,0
  4888.0     0.1       0  4992.3    0.05       0  4996.3     0.1       0
Bank Sta=4992.3,4996.3
Exp/Cntr=0.3,0.1

Type RM Length L Ch R = 1,27635,459,459,459
BEGIN DESCRIPTION:
West Creek 59.0
END DESCRIPTION:
XS GIS Cut Line= 3
      1901625.00     13914575.01      1901675.00     13914375.00
      1901525.03     13914275.02
#Sta/Elev= 30
  4793.1 1941.73  4803.7 1939.82  4814.5 1936.30  4830.8 1933.72  4851.6 1928.08
  4860.9 1924.78  4873.2 1919.32  4885.6 1916.31  4891.8 1913.77  4894.9 1913.46
  4901.1 1910.59  4910.3 1907.91  4925.8 1902.11  4935.1 1899.86  4941.3 1897.52
  4966.0 1893.17  4982.6 1886.34  4982.8 1885.84  4986.6 1886.34  4996.9 1887.07
  5022.2 1894.59  5033.0 1898.82  5040.1 1900.33  5048.1 1903.11  5056.7 1904.75
  5090.6 1914.91  5112.2 1920.51  5119.4 1924.01  5155.5 1935.31  5179.5 1940.75
#Mann=3,-1,0
  4793.1     0.1       0  4982.6    0.05       0  4986.6     0.1       0
Bank Sta=4982.6,4986.6
Exp/Cntr=0.3,0.1

Type RM Length L Ch R = 1,27176,439,439,439
BEGIN DESCRIPTION:
West Creek 58.0
END DESCRIPTION:
XS GIS Cut Line= 3
      1902175.00     13914425.00      1902075.00     13914225.00
      1901925.01     13913925.02
#Sta/Elev= 30
  4770.3 1934.05  4803.5 1929.03  4837.1 1918.31  4857.5 1914.57  4870.6 1909.03
  4906.5 1899.72  4910.9 1897.70  4926.6 1895.00  4951.1 1888.89  4971.2 1881.66
  4978.0 1877.24  4982.5 1875.56  4993.7 1873.32  5006.1 1872.23  5006.4 1871.73
  5010.1 1872.23  5020.5 1873.79  5065.2 1874.60  5074.2 1876.00  5089.9 1880.81
  5095.3 1884.40  5114.4 1891.79  5135.6 1896.16  5149.0 1900.59  5199.3 1910.68
  5212.7 1915.13  5246.6 1921.59  5279.8 1930.23  5311.2 1936.38  5329.3 1938.49
#Mann=3,-1,0
  4770.3     0.1       0  5006.1    0.05       0  5010.1     0.1       0
Bank Sta=5006.1,5010.1
Exp/Cntr=0.3,0.1

Type RM Length L Ch R = 1,26737,471,471,471
BEGIN DESCRIPTION:
West Creek 57.0
END DESCRIPTION:
XS GIS Cut Line= 3
      1902424.99     13914174.97      1902325.00     13913875.00
      1902275.01     13913825.01
#Sta/Elev= 30
  4688.1 1906.52  4708.9 1903.49  4737.3 1898.15  4746.8 1897.33  4756.3 1895.56
  4767.1 1891.99  4778.4 1890.39  4785.1 1887.92  4814.5 1879.51  4823.0 1878.44
  4839.6 1874.02  4858.6 1870.69  4879.6 1868.26  4903.7 1866.97  4932.1 1864.41
  4965.0 1859.84  4980.8 1859.73  4987.1 1858.64  4988.3 1857.70  4988.6 1857.20
  4992.1 1857.20  4992.3 1857.70  4992.8 1859.48  5000.9 1864.52  5022.5 1874.61
  5028.0 1879.79  5036.4 1888.96  5044.9 1892.62  5061.9 1897.91  5075.0 1902.89
#Mann=3,-1,0
  4688.1     0.1       0  4988.3    0.05       0  4992.3     0.1       0
Bank Sta=4988.3,4992.3
Exp/Cntr=0.3,0.1

Type RM Length L Ch R = 1,26266,469,469,469
BEGIN DESCRIPTION:
West Creek 56.0
END DESCRIPTION:
XS GIS Cut Line= 3
      1903025.00     13913625.00      1902725.00     13913675.00
      1902575.02     13913475.03
#Sta/Elev= 30
  4696.7 1902.13  4702.1 1900.41  4737.2 1893.07  4752.4 1888.67  4758.5 1887.72
  4767.7 1883.96  4806.4 1872.11  4819.4 1869.41  4855.7 1853.69  4861.9 1851.94
  4913.6 1849.52  4923.1 1844.62  4923.3 1844.12  4927.1 1844.62  4931.9 1846.11
  4938.1 1846.88  4947.1 1848.48  4979.8 1848.40  4998.8 1849.52  5020.6 1848.97
  5042.1 1850.36  5060.0 1853.31  5102.1 1856.35  5127.8 1861.27  5153.5 1869.48
  5177.1 1879.61  5187.8 1885.59  5192.5 1886.75  5218.0 1897.10  5250.8 1903.97
#Mann=5,-1,0
  4696.7     0.1       0  4923.1   0.035       0  4927.1     0.1       0
  4938.1   0.035       0  5060.0     0.1       0
Bank Sta=4923.1,4927.1
Exp/Cntr=0.3,0.1

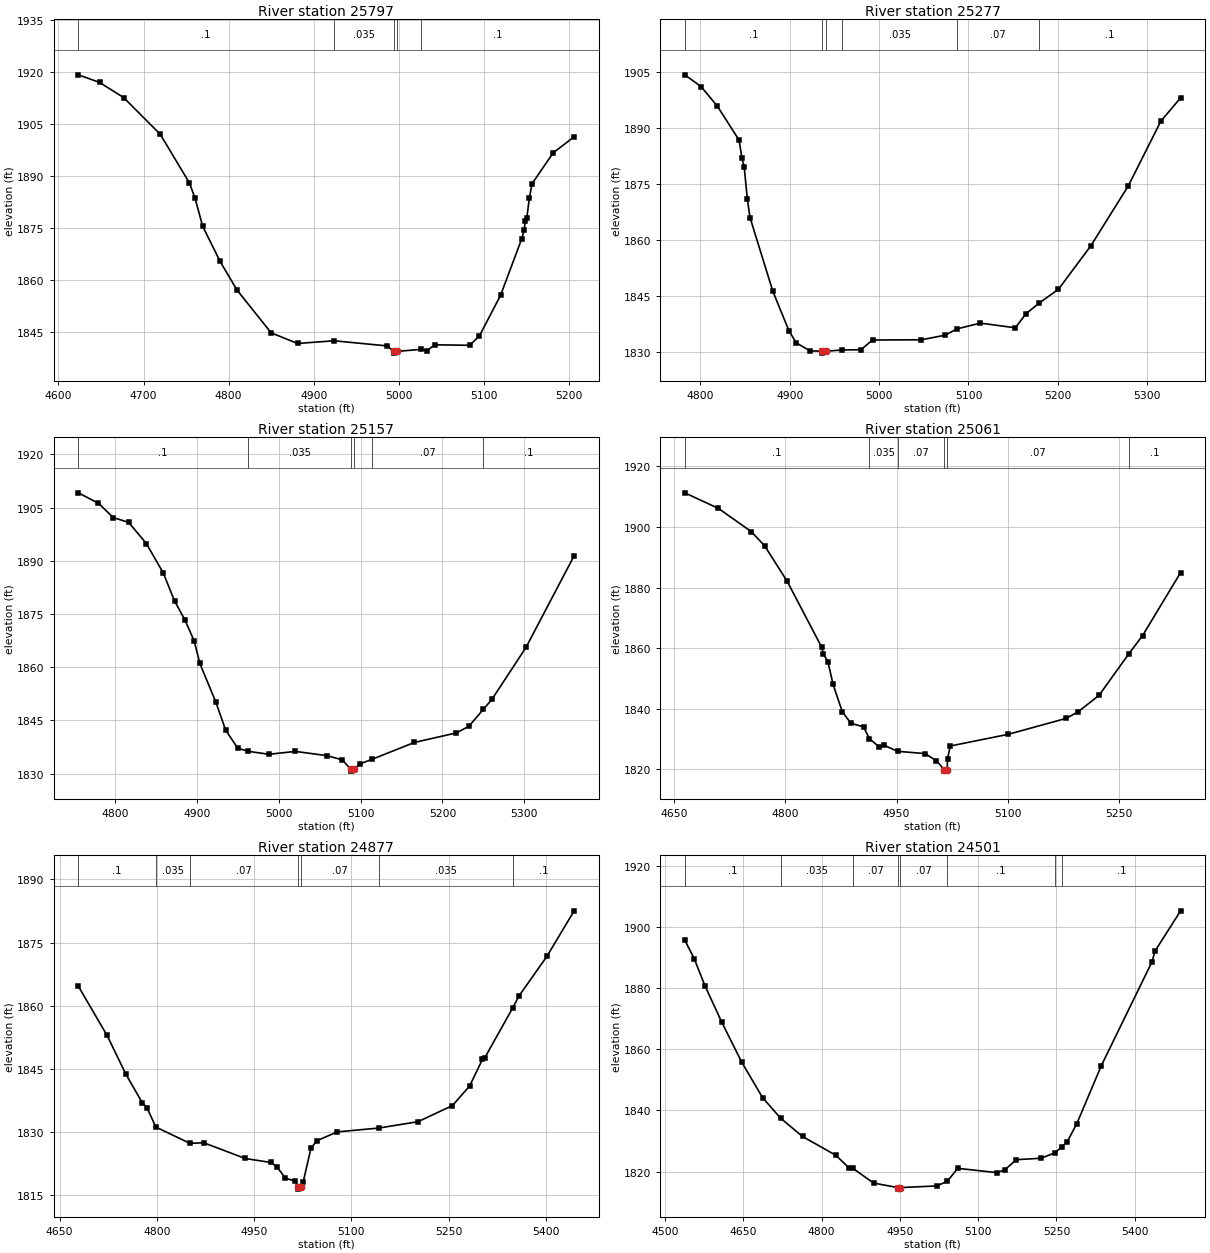
Type RM Length L Ch R = 1,25797,520,520,520
BEGIN DESCRIPTION:
West Creek 55.0
END DESCRIPTION:
XS GIS Cut Line= 3
      1903189.06     13913178.66      1902825.00     13913275.00
      1902625.05     13913324.99
#Sta/Elev= 30
  4623.4 1919.20  4648.3 1917.01  4676.6 1912.64  4719.7 1902.00  4753.8 1888.01
  4760.5 1883.58  4769.5 1875.44  4790.0 1865.27  4809.7 1857.04  4850.0 1844.62
  4881.0 1841.54  4923.9 1842.32  4986.5 1840.83  4993.8 1839.25  4994.1 1838.75
  4997.8 1839.25  5026.6 1839.85  5033.0 1839.46  5042.3 1841.15  5083.4 1841.02
  5094.8 1843.76  5119.6 1855.45  5144.3 1871.68  5147.4 1874.32  5148.6 1876.86
  5150.5 1877.90  5153.5 1883.65  5156.7 1887.76  5181.4 1896.64  5206.1 1901.30
#Mann=5,-1,0
  4623.4     0.1       0  4923.9   0.035       0  4993.8   0.035       0
  4997.8   0.035       0  5026.6     0.1       0
Bank Sta=4993.8,4997.8
Exp/Cntr=0.3,0.1

Type RM Length L Ch R = 1,25277,120,120,120
BEGIN DESCRIPTION:
West Creek 54.0
END DESCRIPTION:
XS GIS Cut Line= 3
      1903224.98     13912925.00      1903016.27     13912889.12
      1902675.02     13912925.00
#Sta/Elev= 30
  4782.5 1904.17  4800.7 1901.03  4819.0 1895.77  4843.3 1886.66  4846.4 1881.88
  4849.0 1879.49  4852.5 1870.88  4855.5 1865.96  4880.9 1846.33  4899.1 1835.65
  4907.3 1832.43  4922.5 1830.32  4936.1 1830.19  4936.3 1829.69  4940.1 1830.19
  4958.8 1830.53  4979.6 1830.60  4992.6 1833.20  5047.4 1833.26  5074.0 1834.50
  5087.0 1836.17  5113.2 1837.72  5152.4 1836.47  5164.5 1840.28  5179.2 1843.09
  5200.7 1846.79  5236.9 1858.41  5278.7 1874.39  5315.3 1891.78  5337.4 1898.02
#Mann=6,-1,0
  4782.5     0.1       0  4936.1   0.035       0  4940.1     0.1       0
  4958.8   0.035       0  5087.0    0.07       0  5179.2     0.1       0
Bank Sta=4936.1,4940.1
Exp/Cntr=0.3,0.1

Type RM Length L Ch R = 1,25157,96,96,96
BEGIN DESCRIPTION:
West Creek 53.2
END DESCRIPTION:
XS GIS Cut Line= 5
      1903276.53     13912849.54      1903138.52     13912784.44
      1903081.23     13912784.44      1902995.29     13912820.90
      1902695.77     13912867.78
#Sta/Elev= 30
  4754.7 1909.19  4779.3 1906.25  4797.4 1902.21  4816.3 1900.85  4837.9 1894.88
  4858.5 1886.62  4872.5 1878.64  4885.3 1873.24  4896.5 1867.33  4903.3 1861.06
  4922.8 1850.22  4934.8 1842.31  4949.6 1837.18  4962.3 1836.30  4987.6 1835.45
  5020.2 1836.26  5059.2 1835.05  5077.5 1833.88  5088.0 1831.20  5088.3 1830.70
  5092.0 1831.20  5098.7 1832.70  5113.5 1833.99  5165.5 1838.78  5217.1 1841.48
  5232.3 1843.34  5250.0 1848.11  5260.7 1851.00  5302.2 1865.59  5361.1 1891.45
#Mann=6,-1,0
  4754.7     0.1       0  4962.3   0.035       0  5088.0   0.035       0
  5092.0   0.035       0  5113.5    0.07       0  5250.0     0.1       0
Bank Sta=5088,5092
Exp/Cntr=0.3,0.1

Type RM Length L Ch R = 1,25061,184,184,184
BEGIN DESCRIPTION:
West Creek 53.1
END DESCRIPTION:
XS GIS Cut Line= 3
      1903325.22     13912823.76      1903090.04     13912694.27
      1902701.19     13912789.44
#Sta/Elev= 30
  4664.3 1911.28  4709.7 1906.12  4753.9 1898.49  4771.9 1893.81  4802.2 1882.15
  4848.9 1860.32  4851.1 1858.20  4857.5 1855.35  4864.3 1848.02  4876.8 1838.93
  4888.3 1835.20  4905.4 1833.97  4913.4 1830.07  4926.0 1827.47  4932.8 1827.96
  4951.3 1825.91  4988.4 1825.16  5003.8 1822.78  5014.2 1819.87  5014.4 1819.37
  5018.2 1819.87  5018.7 1823.53  5022.4 1827.67  5100.5 1831.52  5178.4 1836.77
  5194.5 1838.91  5223.1 1844.40  5262.8 1857.97  5281.8 1864.15  5333.1 1884.94
#Mann=6,-1,0
  4664.3     0.1       0  4913.4   0.035       0  4951.3    0.07       0
  5014.2    0.05       0  5018.2    0.07       0  5262.8     0.1       0
Bank Sta=5014.2,5018.2
Exp/Cntr=0.3,0.1

Type RM Length L Ch R = 1,24877,376,376,376
BEGIN DESCRIPTION:
West Creek 53.0
END DESCRIPTION:
XS GIS Cut Line= 4
      1903326.09     13912646.90      1903025.00     13912525.00
      1902925.00     13912525.00      1902616.88     13912668.67
#Sta/Elev= 30
  4679.0 1864.66  4723.3 1852.97  4752.4 1843.75  4777.8 1836.95  4784.8 1835.82
  4798.6 1831.22  4850.9 1827.37  4872.5 1827.49  4936.5 1823.76  4975.8 1822.82
  4985.2 1821.83  4998.4 1819.08  5013.8 1818.39  5017.8 1816.99  5018.1 1816.49
  5021.8 1816.99  5025.8 1818.17  5037.8 1826.17  5046.8 1827.97  5078.5 1830.08
  5142.1 1830.98  5203.1 1832.50  5256.1 1836.33  5282.6 1840.97  5302.4 1847.31
  5305.7 1847.60  5349.2 1859.55  5358.7 1862.33  5401.7 1871.72  5443.8 1882.54
#Mann=7,-1,0
  4679.0     0.1       0  4798.6   0.035       0  4850.9    0.07       0
  5017.8    0.05       0  5021.8    0.07       0  5142.1   0.035       0
  5349.2     0.1       0
Bank Sta=5017.8,5021.8
Exp/Cntr=0.3,0.1

Type RM Length L Ch R = 1,24501,565,565,565
BEGIN DESCRIPTION:
West Creek 52.0
END DESCRIPTION:
XS GIS Cut Line= 3
      1903623.51     13912629.44      1903282.06     13912261.06
      1903156.76     13911831.34
#Sta/Elev= 30
  4538.1 1895.80  4556.1 1889.77  4576.5 1880.95  4608.6 1869.04  4646.8 1855.94
  4687.0 1844.24  4721.9 1837.43  4763.6 1831.48  4827.3 1825.34  4852.8 1821.19
  4860.2 1821.04  4899.7 1816.22  4946.3 1814.73  4946.5 1814.23  4950.3 1814.73
  5020.5 1815.28  5040.8 1816.74  5061.0 1821.05  5136.0 1819.63  5150.7 1820.52
  5173.5 1823.88  5220.9 1824.36  5247.3 1826.14  5260.7 1828.15  5270.4 1829.65
  5289.1 1835.68  5336.0 1854.66  5432.9 1888.63  5439.1 1892.28  5488.0 1905.42
#Mann=8,-1,0
  4538.1     0.1       0  4721.9   0.035       0  4860.2    0.07       0
  4946.3    0.05       0  4950.3    0.07       0  5040.8     0.1       0
  5247.3    0.07       0  5260.7     0.1       0
Bank Sta=4946.3,4950.3
Exp/Cntr=0.3,0.1

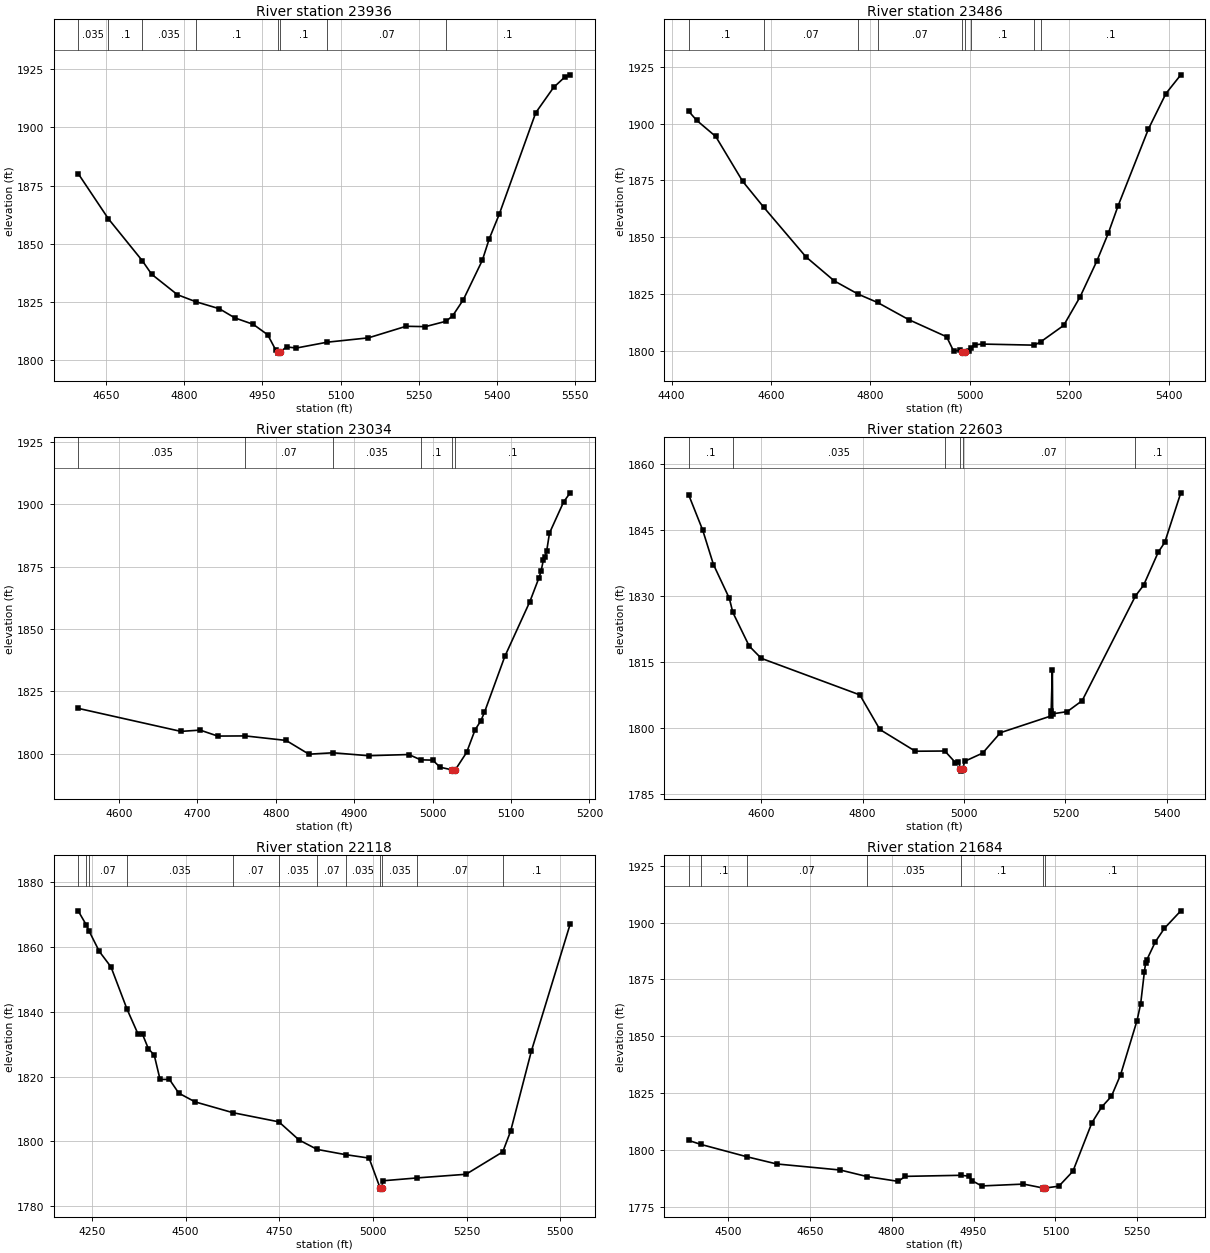
Type RM Length L Ch R = 1,23936,450,450,450
BEGIN DESCRIPTION:
West Creek 51.0
END DESCRIPTION:
XS GIS Cut Line= 3
      1903825.00     13912525.02      1903725.00     13912125.00
      1903375.02     13911725.03
#Sta/Elev= 30
  4596.6 1880.17  4654.5 1860.77  4719.6 1842.75  4737.6 1836.93  4787.0 1828.15
  4821.8 1825.17  4867.4 1822.12  4897.4 1818.16  4932.4 1815.43  4960.2 1810.94
  4975.7 1804.36  4979.9 1803.56  4980.1 1803.06  4983.9 1803.56  4996.3 1805.73
  5015.1 1805.25  5074.5 1807.76  5153.4 1809.62  5225.6 1814.59  5262.5 1814.43
  5302.3 1816.75  5314.9 1819.07  5335.4 1825.98  5371.9 1842.93  5385.0 1852.07
  5404.2 1862.62  5474.3 1906.27  5508.5 1917.13  5529.6 1921.50  5540.4 1922.55
#Mann=8,-1,0
  4596.6   0.035       0  4654.5     0.1       0  4719.6   0.035       0
  4821.8     0.1       0  4979.9    0.05       0  4983.9     0.1       0
  5074.5    0.07       0  5302.3     0.1       0
Bank Sta=4979.9,4983.9
Exp/Cntr=0.3,0.1

Type RM Length L Ch R = 1,23486,452,452,452
BEGIN DESCRIPTION:
West Creek 50.0
END DESCRIPTION:
XS GIS Cut Line= 3
      1904425.02     13912225.02      1904025.00     13911825.00
      1903724.98     13911524.98
#Sta/Elev= 30
  4434.5 1905.38  4450.6 1901.39  4488.8 1894.31  4543.0 1874.56  4585.2 1863.19
  4670.3 1841.29  4727.3 1830.71  4775.8 1824.82  4814.4 1821.20  4877.0 1813.66
  4953.3 1806.10  4967.3 1799.84  4980.9 1800.20  4985.2 1799.40  4985.5 1798.90
  4989.4 1799.40  4997.9 1799.67  5003.3 1801.34  5009.7 1802.60  5025.5 1802.89
  5130.1 1802.41  5143.4 1804.00  5188.8 1811.10  5221.9 1823.70  5255.8 1839.58
  5278.8 1851.83  5298.2 1863.72  5359.4 1897.64  5394.6 1913.24  5424.5 1921.47
#Mann=9,-1,0
  4434.5     0.1       0  4585.2    0.07       0  4775.8   0.035       0
  4814.4    0.07       0  4985.2    0.05       0  4989.4    0.07       0
  5003.3     0.1       0  5130.1    0.07       0  5143.4     0.1       0
Bank Sta=4985.2,4989.4
Exp/Cntr=0.3,0.1

Type RM Length L Ch R = 1,23034,431,431,431
BEGIN DESCRIPTION:
West Creek 49.0
END DESCRIPTION:
XS GIS Cut Line= 3
      1904375.02     13911825.04      1904175.00     13911425.00
      1904025.03     13911325.02
#Sta/Elev= 30
  4548.0 1818.16  4679.0 1808.92  4703.6 1809.43  4726.0 1807.04  4761.3 1807.10
  4813.2 1805.29  4842.3 1799.77  4873.0 1800.34  4918.3 1799.16  4969.7 1799.64
  4984.8 1797.51  5000.2 1797.39  5009.5 1794.56  5024.7 1793.48  5025.0 1792.98
  5028.9 1793.48  5043.4 1800.47  5054.3 1809.63  5061.4 1813.06  5066.2 1816.61
  5092.1 1838.96  5124.1 1861.00  5135.4 1870.30  5138.3 1873.06  5141.4 1877.85
  5143.6 1879.04  5145.5 1881.24  5149.1 1888.46  5167.1 1900.95  5175.5 1904.60
#Mann=6,-1,0
  4548.0   0.035       0  4761.3    0.07       0  4873.0   0.035       0
  4984.8     0.1       0  5024.7    0.05       0  5028.9     0.1       0
Bank Sta=5024.7,5028.9
Exp/Cntr=0.3,0.1

Type RM Length L Ch R = 1,22603,485,485,485
BEGIN DESCRIPTION:
West Creek 48.0
END DESCRIPTION:
XS GIS Cut Line= 3
      1904612.76     13911911.36      1904525.00     13911375.00
      1904375.00     13910974.99
#Sta/Elev= 30
  4456.9 1852.88  4484.4 1844.92  4505.6 1837.10  4536.9 1829.43  4543.8 1826.23
  4576.1 1818.58  4599.9 1815.79  4794.4 1807.48  4833.9 1799.62  4903.9 1794.68
  4962.1 1794.73  4982.9 1792.10  4989.0 1792.30  4992.9 1790.66  4993.2 1790.16
  4997.2 1790.66  5001.2 1792.39  5036.7 1794.26  5071.7 1798.89  5171.0 1802.67
  5171.8 1803.75  5174.2 1813.11  5174.8 1803.18  5203.6 1803.68  5233.0 1806.17
  5338.2 1829.97  5354.2 1832.40  5383.1 1839.91  5395.9 1842.13  5427.6 1853.39
#Mann=6,-1,0
  4456.9     0.1       0  4543.8   0.035       0  4962.1    0.07       0
  4992.9    0.05       0  4997.2    0.07       0  5338.2     0.1       0
Bank Sta=4992.9,4997.2
Exp/Cntr=0.3,0.1

Type RM Length L Ch R = 1,22118,434,434,434
BEGIN DESCRIPTION:
West Creek 47.0
END DESCRIPTION:
XS GIS Cut Line= 4
      1904810.10     13911974.55      1904979.46     13911382.47
      1904925.00     13911225.00      1904574.97     13910824.97
#Sta/Elev= 30
  4212.9 1871.09  4234.6 1866.75  4242.0 1864.88  4269.4 1858.58  4300.6 1853.80
  4343.4 1840.79  4372.3 1833.26  4384.8 1833.04  4400.4 1828.61  4416.1 1826.62
  4431.6 1819.11  4456.6 1819.14  4481.7 1814.89  4525.2 1812.20  4626.6 1808.86
  4748.9 1806.05  4802.9 1800.45  4851.2 1797.55  4926.9 1795.94  4989.8 1794.88
  5018.8 1785.81  5019.1 1785.31  5023.1 1785.81  5027.6 1787.89  5118.8 1788.77
  5248.7 1789.89  5346.8 1796.79  5367.8 1803.17  5423.0 1827.77  5526.9 1867.03
#Mann=12,-1,0
  4212.9    0.07       0  4234.6     0.1       0  4242.0    0.07       0
  4343.4   0.035       0  4626.6    0.07       0  4748.9   0.035       0
  4851.2    0.07       0  4926.9   0.035       0  5018.8   0.035       0
  5023.1   0.035       0  5118.8    0.07       0  5346.8     0.1       0
Bank Sta=5018.8,5023.1
Exp/Cntr=0.3,0.1

Type RM Length L Ch R = 1,21684,649,649,649
BEGIN DESCRIPTION:
West Creek 46.0
END DESCRIPTION:
XS GIS Cut Line= 3
      1905425.00     13911225.00      1905025.00     13910825.00
      1904875.00     13910525.00
#Sta/Elev= 30
  4428.5 1804.10  4450.4 1802.37  4535.5 1796.88  4589.4 1793.75  4706.1 1791.07
  4754.7 1788.21  4812.2 1786.07  4824.7 1788.28  4926.8 1788.75  4941.5 1788.38
  4947.9 1786.31  4964.9 1784.06  5041.5 1784.88  5077.3 1783.16  5077.6 1782.66
  5081.7 1783.16  5106.3 1783.96  5132.0 1790.53  5166.7 1811.85  5184.6 1818.79
  5202.5 1823.53  5219.3 1833.02  5249.4 1856.86  5256.1 1864.31  5262.9 1878.41
  5265.1 1882.11  5267.3 1883.60  5283.0 1891.59  5299.7 1897.56  5329.6 1905.22
#Mann=7,-1,0
  4428.5    0.07       0  4450.4     0.1       0  4535.5    0.07       0
  4754.7   0.035       0  4926.8     0.1       0  5077.3    0.05       0
  5081.7     0.1       0
Bank Sta=5077.3,5081.7
Exp/Cntr=0.3,0.1

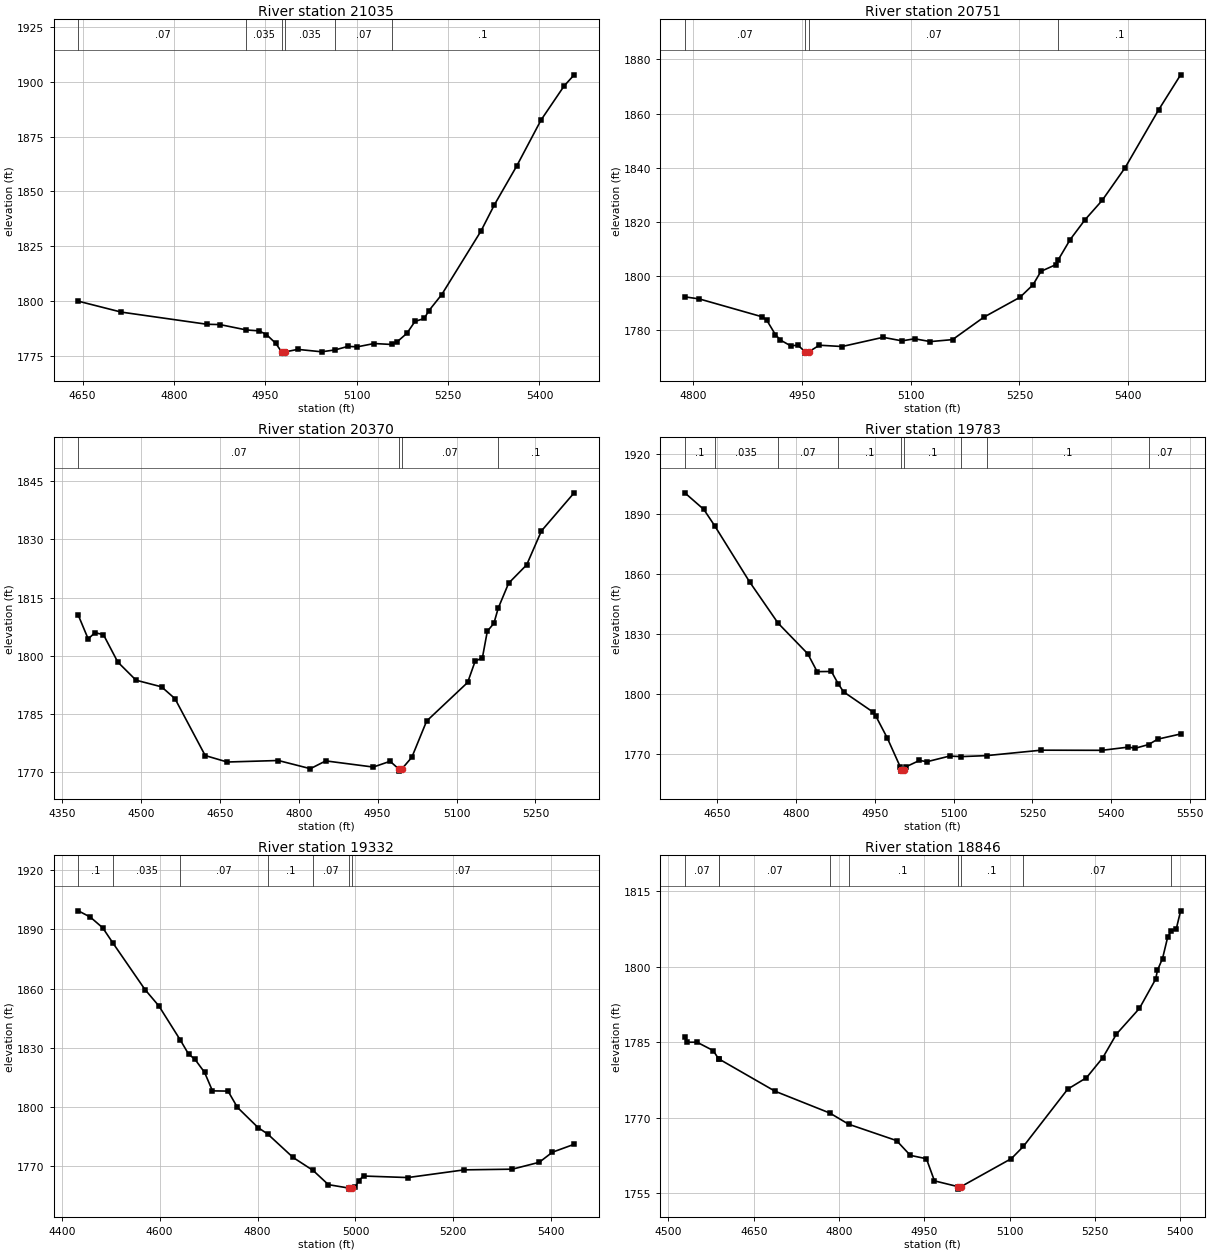
Type RM Length L Ch R = 1,21035,284,284,284
BEGIN DESCRIPTION:
West Creek 45.0
END DESCRIPTION:
XS GIS Cut Line= 3
      1905575.01     13910975.04      1905508.57     13910625.84
      1905124.98     13910374.98
#Sta/Elev= 30
  4643.1 1799.91  4713.6 1794.93  4854.2 1789.38  4875.5 1789.24  4919.0 1786.78
  4939.7 1786.37  4951.9 1784.68  4967.1 1780.68  4976.9 1776.71  4977.3 1776.21
  4981.9 1776.71  5003.0 1777.92  5042.5 1776.82  5064.6 1777.68  5085.5 1779.28
  5101.1 1779.09  5128.5 1780.59  5157.5 1780.16  5165.4 1781.15  5182.3 1785.23
  5195.7 1790.69  5210.9 1792.02  5218.1 1795.45  5239.6 1802.95  5303.9 1831.89
  5325.9 1843.86  5362.6 1861.59  5402.6 1882.61  5440.3 1898.08  5456.9 1903.21
#Mann=6,-1,0
  4643.1    0.07       0  4919.0   0.035       0  4976.9   0.035       0
  4981.9   0.035       0  5064.6    0.07       0  5157.5     0.1       0
Bank Sta=4976.9,4981.9
Exp/Cntr=0.3,0.1

Type RM Length L Ch R = 1,20751,381,381,381
BEGIN DESCRIPTION:
West Creek 44.0
END DESCRIPTION:
XS GIS Cut Line= 3
      1905825.03     13910625.03      1905675.00     13910475.00
      1905274.98     13910224.99
#Sta/Elev= 30
  4788.5 1792.34  4808.6 1791.56  4894.9 1784.99  4901.3 1783.82  4913.4 1778.42
  4920.4 1776.38  4934.6 1774.23  4944.4 1774.51  4954.5 1772.05  4954.9 1771.55
  4959.6 1772.05  4974.1 1774.47  5005.4 1773.99  5062.0 1777.39  5088.1 1776.08
  5105.5 1776.85  5127.1 1775.81  5157.8 1776.54  5201.2 1784.86  5250.9 1792.19
  5268.8 1796.78  5279.7 1801.75  5300.4 1804.24  5303.7 1806.06  5320.1 1813.51
  5340.6 1820.83  5364.1 1827.93  5395.9 1840.06  5441.9 1861.32  5472.4 1874.33
#Mann=4,-1,0
  4788.5    0.07       0  4954.5    0.05       0  4959.6    0.07       0
  5303.7     0.1       0
Bank Sta=4954.5,4959.6
Exp/Cntr=0.3,0.1

Type RM Length L Ch R = 1,20370,587,587,587
BEGIN DESCRIPTION:
West Creek 43.0
END DESCRIPTION:
XS GIS Cut Line= 3
      1906212.18     13910340.65      1905638.54     13910114.15
      1905325.00     13910025.00
#Sta/Elev= 30
  4381.0 1810.44  4399.7 1804.36  4412.6 1805.96  4428.7 1805.46  4456.0 1798.39
  4490.7 1793.71  4539.2 1792.00  4564.7 1788.96  4622.2 1774.28  4664.0 1772.61
  4761.2 1773.00  4822.2 1770.89  4851.4 1772.90  4941.8 1771.31  4973.8 1772.80
  4990.6 1770.76  4991.0 1770.26  4995.7 1770.76  5015.1 1773.84  5043.2 1783.17
  5121.2 1793.13  5135.5 1798.63  5149.2 1799.46  5158.6 1806.34  5171.1 1808.38
  5179.3 1812.28  5199.1 1818.72  5233.4 1823.45  5261.5 1832.21  5323.7 1842.03
#Mann=4,-1,0
  4381.0    0.07       0  4990.6    0.05       0  4995.7    0.07       0
  5179.3     0.1       0
Bank Sta=4990.6,4995.7
Exp/Cntr=0.3,0.1

Type RM Length L Ch R = 1,19783,451,451,451
BEGIN DESCRIPTION:
West Creek 42.0
END DESCRIPTION:
XS GIS Cut Line= 3
      1906574.98     13910074.99      1906175.00     13909975.00
      1905775.00     13909625.00
#Sta/Elev= 30
  4588.3 1900.64  4624.5 1892.35  4645.1 1884.22  4711.5 1856.23  4765.9 1835.55
  4822.4 1820.26  4840.2 1811.36  4867.4 1811.44  4880.2 1805.34  4890.5 1801.27
  4946.1 1791.26  4951.5 1789.38  4973.8 1778.18  4998.7 1763.64  4999.4 1762.18
  4999.8 1761.68  5004.8 1762.18  5009.4 1763.86  5034.9 1767.00  5049.6 1766.40
  5092.3 1769.20  5114.2 1768.93  5162.7 1769.42  5266.7 1772.14  5382.2 1772.07
  5432.7 1773.67  5446.0 1773.13  5471.0 1774.94  5488.5 1777.64  5532.1 1780.23
#Mann=9,-1,0
  4588.3     0.1       0  4645.1   0.035       0  4765.9    0.07       0
  4880.2     0.1       0  4999.4    0.05       0  5004.8     0.1       0
  5114.2    0.07       0  5162.7     0.1       0  5471.0    0.07       0
Bank Sta=4999.4,5004.8
Exp/Cntr=0.3,0.1

Type RM Length L Ch R = 1,19332,486,486,486
BEGIN DESCRIPTION:
West Creek 41.0
END DESCRIPTION:
XS GIS Cut Line= 3
      1906625.00     13909975.00      1906225.00     13909575.00
      1905825.00     13909375.00
#Sta/Elev= 30
  4433.9 1899.40  4458.4 1896.22  4483.8 1890.77  4504.8 1883.00  4570.0 1859.53
  4598.4 1851.22  4642.6 1833.78  4659.1 1826.80  4671.8 1824.26  4691.7 1817.59
  4707.9 1808.17  4739.7 1808.06  4758.8 1799.84  4801.2 1789.54  4820.6 1786.34
  4872.5 1774.45  4913.5 1767.85  4944.7 1760.66  4987.3 1758.89  4987.7 1758.39
  4992.7 1758.89  4999.8 1759.28  5006.5 1762.72  5016.5 1765.03  5107.1 1764.25
  5222.1 1768.15  5320.4 1768.50  5375.4 1771.98  5402.3 1777.09  5446.8 1781.11
#Mann=7,-1,0
  4433.9     0.1       0  4504.8   0.035       0  4642.6    0.07       0
  4820.6     0.1       0  4913.5    0.07       0  4987.3    0.05       0
  4992.7    0.07       0
Bank Sta=4987.3,4992.7
Exp/Cntr=0.3,0.1

Type RM Length L Ch R = 1,18846,448,448,448
BEGIN DESCRIPTION:
West Creek 40.0
END DESCRIPTION:
XS GIS Cut Line= 3
      1906525.04     13909375.03      1906125.00     13909125.00
      1905725.05     13909125.00
#Sta/Elev= 30
  4528.7 1785.97  4532.5 1784.98  4550.2 1784.98  4578.5 1783.33  4588.0 1781.71
  4588.8 1781.65  4687.3 1775.26  4783.6 1770.93  4816.7 1768.71  4901.0 1765.46
  4925.2 1762.53  4953.5 1761.86  4967.6 1757.47  5008.8 1756.33  5009.3 1755.83
  5014.4 1756.33  5102.9 1761.89  5123.9 1764.30  5201.9 1775.67  5234.9 1777.94
  5263.6 1781.91  5287.6 1786.60  5327.9 1791.68  5356.6 1797.51  5359.6 1799.24
  5368.6 1801.59  5377.6 1805.81  5384.1 1807.09  5392.6 1807.40  5400.4 1811.05
#Mann=9,-1,0
  4528.7    0.07       0  4588.0   0.035       0  4588.8    0.07       0
  4783.6   0.035       0  4816.7     0.1       0  5008.8    0.05       0
  5014.4     0.1       0  5123.9    0.07       0  5384.1     0.1       0
Bank Sta=5008.8,5014.4
Exp/Cntr=0.3,0.1

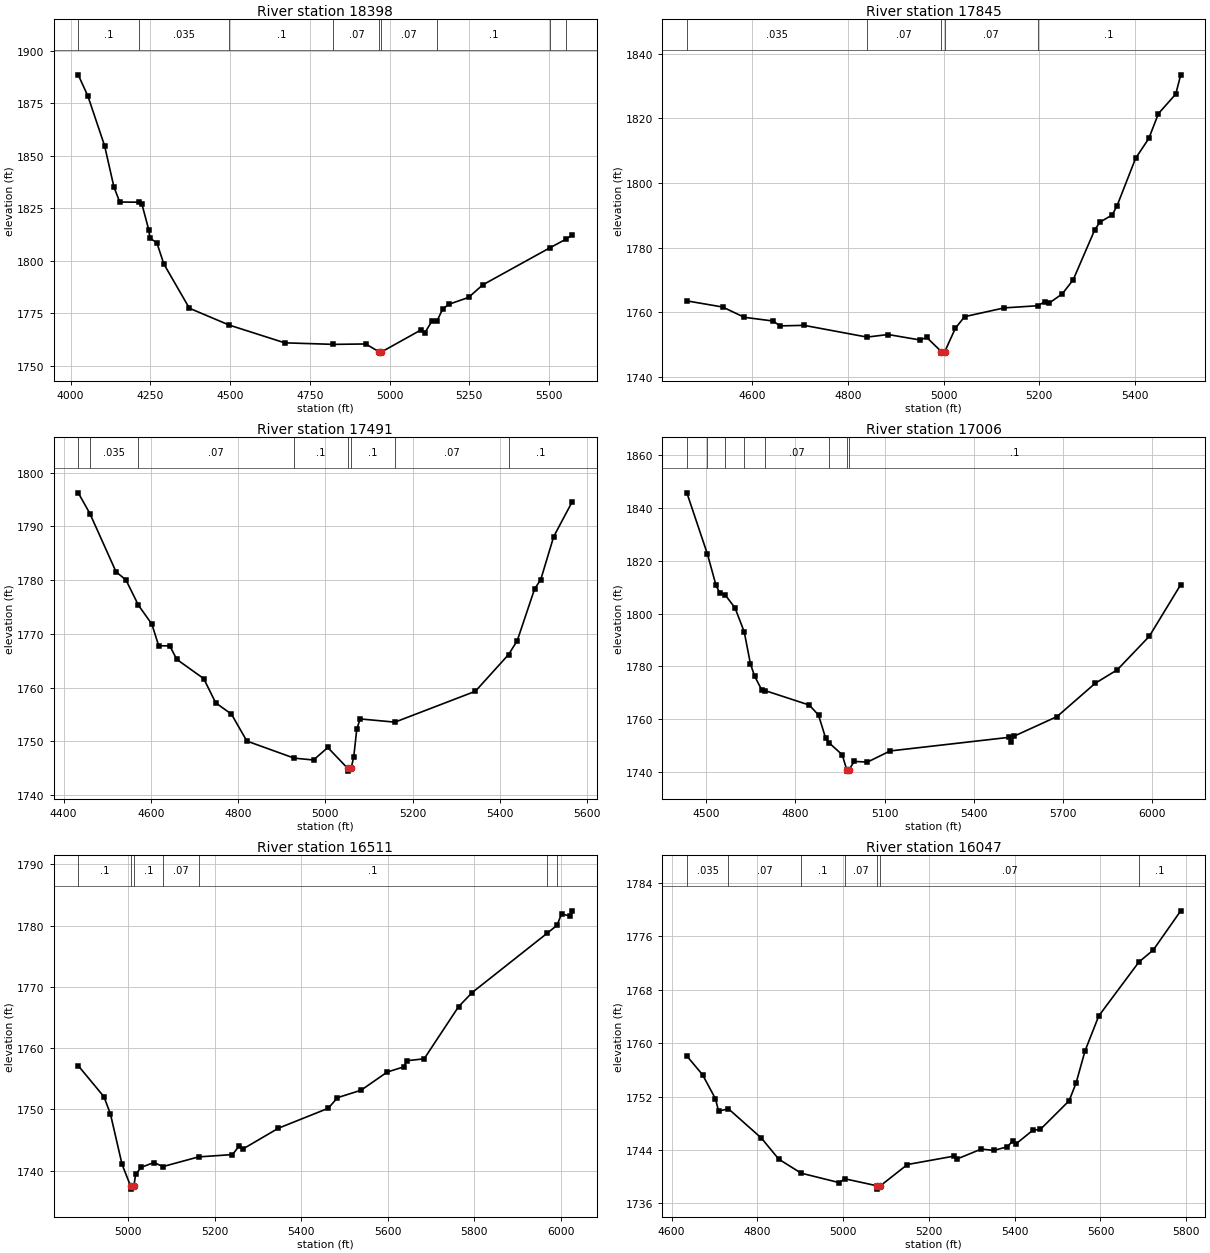
Type RM Length L Ch R = 1,18398,553,553,553
BEGIN DESCRIPTION:
West Creek 39.0
END DESCRIPTION:
XS GIS Cut Line= 3
      1906875.01     13909275.00      1906075.00     13908725.00
      1905509.59     13908844.36
#Sta/Elev= 30
  4023.9 1888.60  4054.4 1878.38  4106.6 1854.81  4135.8 1835.23  4154.0 1828.04
  4213.0 1827.96  4223.1 1827.32  4245.0 1814.82  4248.6 1810.84  4270.5 1808.62
  4292.3 1798.56  4372.4 1777.48  4497.4 1769.45  4671.5 1761.00  4824.1 1760.27
  4925.8 1760.46  4968.5 1756.60  4969.0 1756.10  4974.1 1756.60  5099.2 1767.18
  5111.4 1765.91  5132.9 1771.33  5149.3 1771.52  5166.6 1777.04  5185.8 1779.33
  5247.8 1782.61  5292.3 1788.59  5503.1 1806.26  5552.8 1810.31  5572.6 1812.31
#Mann=9,-1,0
  4023.9     0.1       0  4213.0   0.035       0  4497.4     0.1       0
  4824.1    0.07       0  4968.5    0.05       0  4974.1    0.07       0
  5149.3     0.1       0  5503.1    0.07       0  5552.8     0.1       0
Bank Sta=4968.5,4974.1
Exp/Cntr=0.3,0.1

Type RM Length L Ch R = 1,17845,354,354,354
BEGIN DESCRIPTION:
West Creek 38.0
END DESCRIPTION:
XS GIS Cut Line= 3
      1906575.02     13908725.03      1906248.35     13908286.27
      1905924.97     13907924.97
#Sta/Elev= 30
  4463.7 1763.53  4538.4 1761.64  4583.8 1758.45  4643.5 1757.32  4658.6 1755.80
  4708.5 1755.97  4840.2 1752.34  4884.3 1753.13  4950.3 1751.46  4965.0 1752.22
  4995.2 1747.88  4995.7 1747.38  5002.7 1747.88  5024.9 1755.11  5044.1 1758.66
  5126.9 1761.37  5196.7 1762.03  5212.4 1763.33  5220.4 1762.82  5248.0 1765.68
  5270.9 1770.05  5316.1 1785.55  5326.6 1787.85  5352.4 1790.10  5362.8 1793.02
  5401.3 1807.61  5428.9 1813.75  5449.0 1821.44  5485.2 1827.47  5495.6 1833.43
#Mann=5,-1,0
  4463.7   0.035       0  4840.2    0.07       0  4995.2    0.05       0
  5002.7    0.07       0  5196.7     0.1       0
Bank Sta=4995.2,5002.7
Exp/Cntr=0.3,0.1

Type RM Length L Ch R = 1,17491,485,485,485
BEGIN DESCRIPTION:
West Creek 37.0
END DESCRIPTION:
XS GIS Cut Line= 3
      1906974.99     13908674.99      1906575.00     13908275.00
      1906174.97     13907874.97
#Sta/Elev= 30
  4433.7 1796.25  4460.4 1792.39  4520.4 1781.53  4542.9 1780.04  4571.7 1775.31
  4602.3 1771.81  4618.0 1767.78  4643.4 1767.74  4659.6 1765.23  4721.1 1761.66
  4748.7 1757.14  4784.7 1755.04  4820.0 1750.03  4928.3 1746.85  4972.7 1746.50
  5005.4 1748.83  5051.2 1744.93  5051.7 1744.43  5058.7 1744.93  5064.8 1747.04
  5071.9 1752.29  5079.6 1754.15  5159.2 1753.55  5343.5 1759.30  5419.6 1766.14
  5439.4 1768.72  5479.2 1778.35  5493.3 1780.10  5523.0 1788.11  5565.1 1794.55
#Mann=8,-1,0
  4433.7    0.07       0  4460.4   0.035       0  4571.7    0.07       0
  4928.3     0.1       0  5051.2    0.05       0  5058.7     0.1       0
  5159.2    0.07       0  5419.6     0.1       0
Bank Sta=5051.2,5058.7
Exp/Cntr=0.3,0.1

Type RM Length L Ch R = 1,17006,495,495,495
BEGIN DESCRIPTION:
West Creek 36.0
END DESCRIPTION:
XS GIS Cut Line= 3
      1907425.00     13908675.00      1907025.00     13908275.00
      1906224.98     13907524.98
#Sta/Elev= 30
  4434.6 1845.70  4503.9 1822.49  4532.4 1810.82  4545.1 1807.80  4563.2 1807.13
  4596.9 1802.10  4627.8 1793.03  4648.6 1780.95  4662.6 1776.33  4686.0 1771.22
  4697.5 1770.85  4846.4 1765.37  4877.7 1761.59  4901.5 1752.92  4914.1 1750.99
  4957.5 1746.54  4972.8 1740.85  4973.3 1740.35  4980.4 1740.85  4997.8 1744.03
  5042.4 1743.77  5118.8 1747.99  5518.3 1753.13  5527.1 1751.42  5534.8 1753.52
  5680.6 1761.00  5809.2 1773.61  5883.3 1778.70  5991.1 1791.39  6096.9 1810.94
#Mann=8,-1,0
  4434.6    0.07       0  4503.9     0.1       0  4563.2    0.07       0
  4627.8   0.035       0  4697.5    0.07       0  4914.1     0.1       0
  4972.8    0.05       0  4980.4     0.1       0
Bank Sta=4972.8,4980.4
Exp/Cntr=0.3,0.1

Type RM Length L Ch R = 1,16511,464,464,464
BEGIN DESCRIPTION:
West Creek 35.0
END DESCRIPTION:
XS GIS Cut Line= 3
      1907475.03     13907975.01      1907375.00     13907925.00
      1906575.01     13907275.01
#Sta/Elev= 30
  4884.0 1757.12  4943.5 1752.05  4958.5 1749.24  4985.3 1741.03  5005.1 1737.47
  5005.6 1736.97  5012.8 1737.47  5016.7 1739.36  5029.6 1740.53  5059.2 1741.31
  5079.9 1740.65  5162.4 1742.23  5240.9 1742.61  5256.3 1744.01  5264.2 1743.49
  5347.3 1746.92  5462.5 1750.17  5483.8 1751.90  5538.5 1753.12  5599.0 1756.09
  5637.4 1756.93  5643.8 1757.93  5684.3 1758.24  5763.8 1766.74  5795.2 1769.05
  5968.5 1778.72  5991.8 1780.04  6002.1 1781.91  6021.7 1781.54  6026.6 1782.40
#Mann=7,-1,0
  4884.0     0.1       0  5005.1    0.05       0  5012.8     0.1       0
  5079.9    0.07       0  5162.4     0.1       0  5968.5    0.07       0
  5991.8     0.1       0
Bank Sta=5005.1,5012.8
Exp/Cntr=0.3,0.1

Type RM Length L Ch R = 1,16047,481,481,481
BEGIN DESCRIPTION:
West Creek 34.0
END DESCRIPTION:
XS GIS Cut Line= 3
      1907774.98     13907574.99      1907425.00     13907475.00
      1906685.39     13907203.94
#Sta/Elev= 30
  4635.5 1758.06  4672.1 1755.26  4702.2 1751.66  4709.5 1749.82  4732.5 1750.16
  4809.3 1745.78  4849.9 1742.62  4902.0 1740.53  4991.0 1739.11  5003.6 1739.69
  5078.7 1738.64  5079.2 1738.14  5086.8 1738.64  5149.8 1741.82  5258.5 1743.08
  5264.8 1742.63  5322.4 1744.14  5351.1 1743.93  5383.1 1744.48  5395.9 1745.40
  5402.8 1744.90  5442.5 1746.96  5459.8 1747.07  5526.9 1751.36  5543.1 1754.00
  5564.1 1758.84  5596.1 1764.06  5689.7 1772.13  5723.1 1773.92  5787.2 1779.79
#Mann=7,-1,0
  4635.5   0.035       0  4732.5    0.07       0  4902.0     0.1       0
  5003.6    0.07       0  5078.7    0.05       0  5086.8    0.07       0
  5689.7     0.1       0
Bank Sta=5078.7,5086.8
Exp/Cntr=0.3,0.1