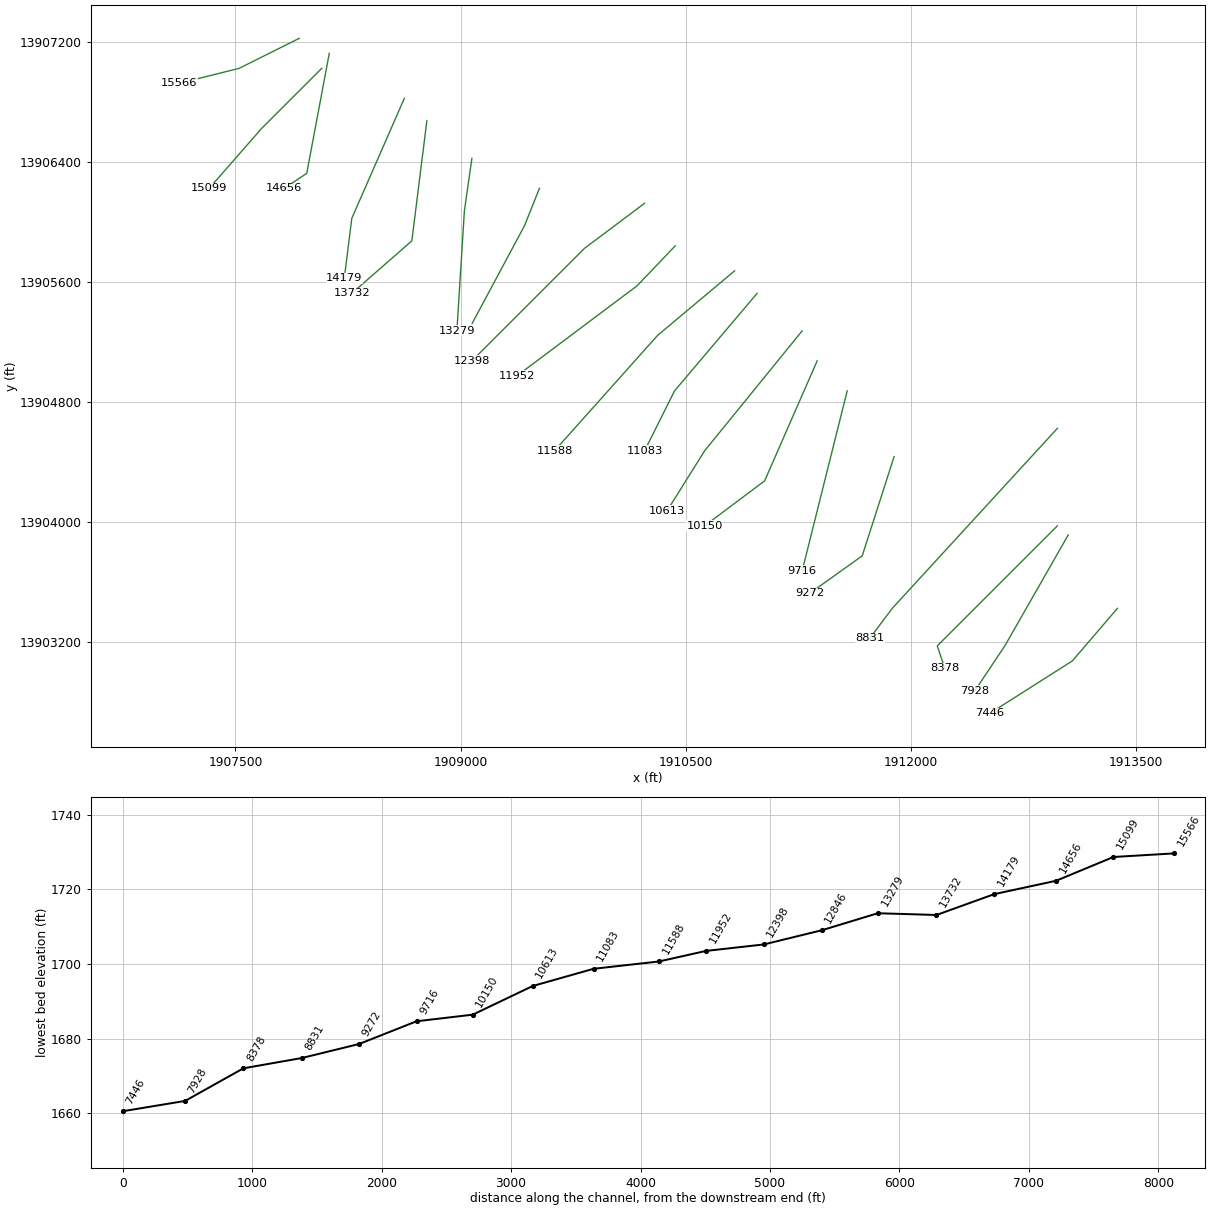
HEC-RAS study West Creek.prj: West Creek Base Level Engineering

--- West Creek.g01 (geometry) --- (continued)

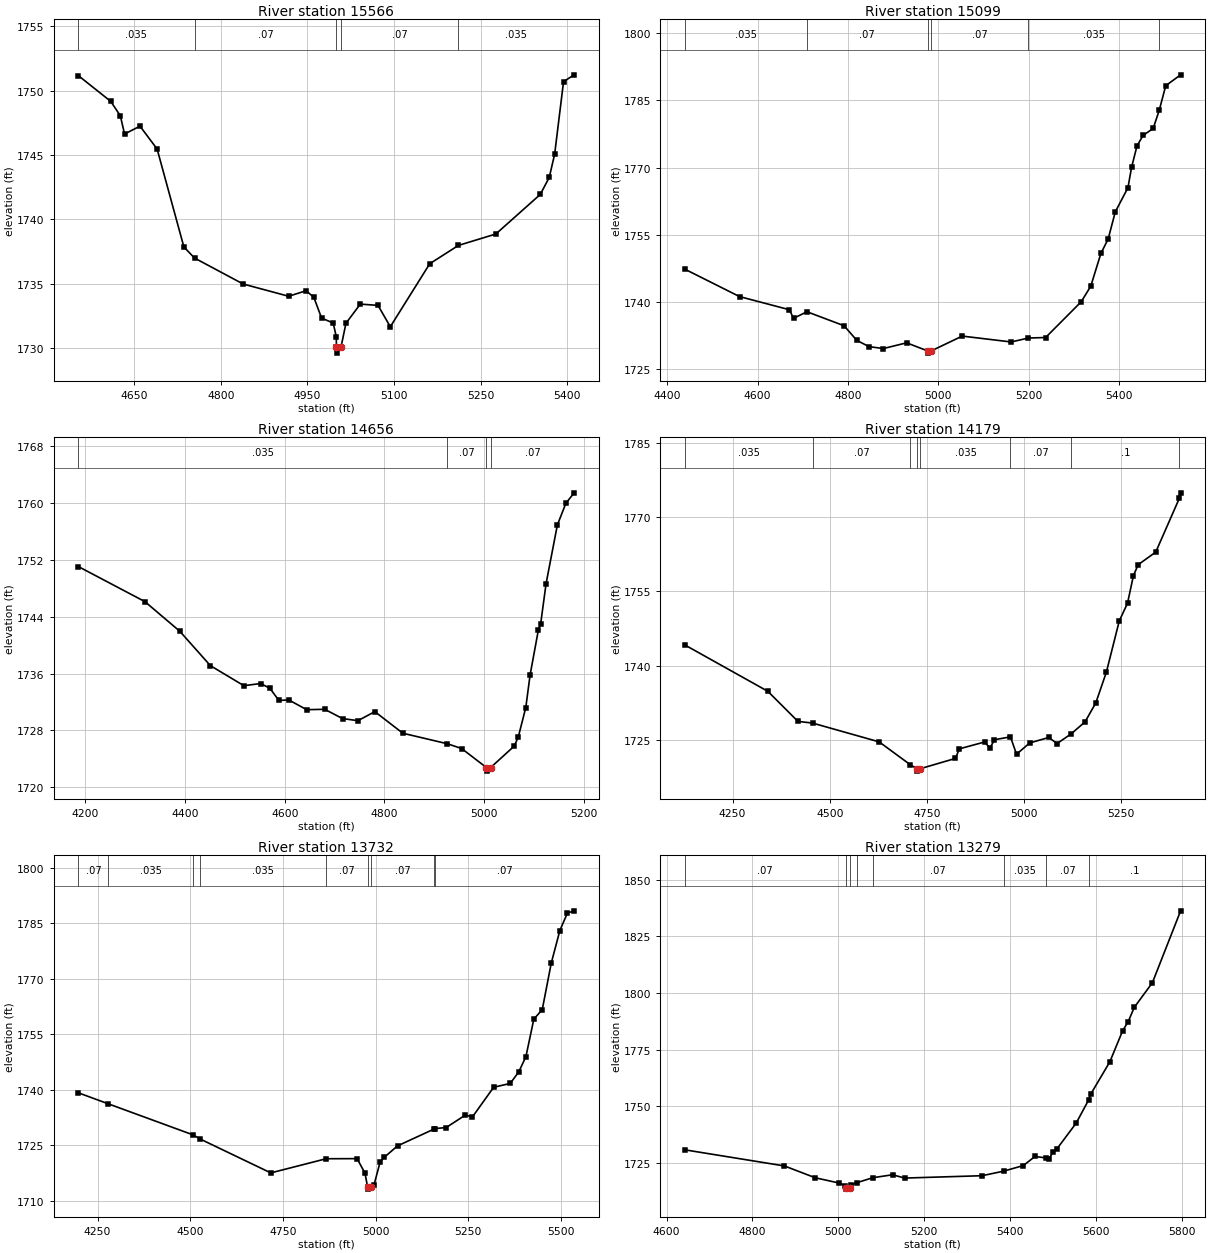
Type RM Length L Ch R = 1,15566,467,467,467
BEGIN DESCRIPTION:
West Creek 33.0
END DESCRIPTION:
XS GIS Cut Line= 3
      1907924.97     13907224.99      1907525.00     13907025.00
      1907124.99     13906925.00
#Sta/Elev= 30
  4552.8 1751.17  4608.9 1749.17  4625.6 1748.05  4632.9 1746.63  4659.7 1747.24
  4689.4 1745.46  4735.7 1737.86  4754.2 1736.99  4838.6 1734.97  4917.4 1734.02
  4947.6 1734.45  4961.0 1733.94  4974.5 1732.32  4994.6 1731.94  5000.0 1730.87
  5000.2 1730.10  5000.7 1729.60  5008.3 1730.10  5016.7 1731.92  5041.6 1733.41
  5072.3 1733.31  5093.6 1731.65  5162.0 1736.55  5211.6 1737.97  5276.6 1738.86
  5353.7 1741.94  5369.2 1743.27  5378.5 1745.07  5393.9 1750.70  5412.3 1751.23
#Mann=5,-1,0
  4552.8   0.035       0  4754.2    0.07       0  5000.2    0.05       0
  5008.3    0.07       0  5211.6   0.035       0
Bank Sta=5000.2,5008.3
Exp/Cntr=0.3,0.1

Type RM Length L Ch R = 1,15099,443,443,443
BEGIN DESCRIPTION:
West Creek 32.0
END DESCRIPTION:
XS GIS Cut Line= 3
      1908074.98     13907024.98      1907675.00     13906625.00
      1907324.97     13906224.97
#Sta/Elev= 30
  4439.0 1747.37  4560.2 1741.25  4670.5 1738.32  4679.6 1736.40  4709.3 1737.87
  4791.4 1734.75  4819.6 1731.49  4846.6 1730.09  4878.4 1729.66  4929.9 1730.94
  4976.1 1729.14  4976.6 1728.64  4984.4 1729.14  5052.9 1732.44  5161.3 1731.13
  5199.5 1732.01  5237.4 1732.12  5316.2 1740.10  5337.4 1743.58  5359.8 1750.89
  5375.8 1754.08  5391.7 1760.18  5419.6 1765.53  5427.6 1770.06  5439.6 1774.84
  5452.9 1777.19  5475.4 1778.75  5488.8 1782.79  5503.3 1788.30  5536.2 1790.72
#Mann=6,-1,0
  4439.0   0.035       0  4709.3    0.07       0  4976.1    0.05       0
  4984.4    0.07       0  5199.5   0.035       0  5488.8    0.07       0
Bank Sta=4976.1,4984.4
Exp/Cntr=0.3,0.1

Type RM Length L Ch R = 1,14656,477,477,477
BEGIN DESCRIPTION:
West Creek 31.0
END DESCRIPTION:
XS GIS Cut Line= 3
      1908125.00     13907124.99      1907975.00     13906325.00
      1907825.01     13906225.00
#Sta/Elev= 30
  4186.1 1751.05  4319.7 1746.11  4389.5 1741.95  4450.9 1737.11  4518.0 1734.29
  4551.5 1734.59  4570.0 1733.94  4588.3 1732.21  4608.0 1732.29  4644.0 1730.91
  4680.0 1730.97  4716.0 1729.66  4746.8 1729.37  4780.6 1730.64  4836.8 1727.60
  4926.1 1726.12  4954.6 1725.45  5004.5 1722.77  5005.0 1722.27  5012.8 1722.77
  5060.1 1725.79  5068.2 1727.06  5083.3 1731.21  5091.9 1735.78  5108.7 1742.19
  5113.2 1743.03  5124.0 1748.65  5146.6 1756.89  5163.7 1759.95  5180.3 1761.42
#Mann=4,-1,0
  4186.1   0.035       0  4926.1    0.07       0  5004.5    0.05       0
  5012.8    0.07       0
Bank Sta=5004.5,5012.8
Exp/Cntr=0.3,0.1

Type RM Length L Ch R = 1,14179,447,447,447
BEGIN DESCRIPTION:
West Creek 30.0
END DESCRIPTION:
XS GIS Cut Line= 3
      1908625.01     13906825.02      1908275.00     13906025.00
      1908225.01     13905625.05
#Sta/Elev= 30
  4126.9 1744.20  4340.6 1734.83  4418.1 1728.75  4455.7 1728.41  4627.2 1724.61
  4707.8 1719.97  4724.0 1719.20  4724.5 1718.70  4733.4 1719.20  4823.6 1721.27
  4833.5 1723.20  4898.7 1724.59  4912.4 1723.33  4923.8 1725.04  4965.2 1725.62
  4980.8 1722.12  5014.9 1724.40  5063.9 1725.50  5085.1 1724.27  5121.7 1726.24
  5157.3 1728.67  5184.9 1732.49  5212.1 1738.71  5245.3 1749.06  5266.5 1752.63
  5281.6 1758.16  5293.7 1760.40  5339.1 1762.95  5400.1 1773.86  5403.2 1774.93
#Mann=8,-1,0
  4126.9   0.035       0  4455.7    0.07       0  4707.8   0.035       0
  4724.0    0.05       0  4733.4   0.035       0  4965.2    0.07       0
  5121.7     0.1       0  5400.1    0.07       0
Bank Sta=4724,4733.4
Exp/Cntr=0.3,0.1

Type RM Length L Ch R = 1,13732,453,453,453
BEGIN DESCRIPTION:
West Creek 29.0
END DESCRIPTION:
XS GIS Cut Line= 3
      1908775.00     13906675.00      1908675.00     13905875.00
      1908275.03     13905525.02
#Sta/Elev= 30
  4198.1 1739.17  4279.1 1736.18  4508.1 1727.77  4526.9 1726.66  4717.4 1717.50
  4866.7 1721.33  4950.1 1721.36  4971.4 1717.45  4978.7 1713.61  4979.2 1713.11
  4988.2 1713.61  4995.6 1714.16  5012.5 1720.53  5023.2 1721.69  5059.2 1724.81
  5158.5 1729.39  5161.0 1729.49  5190.6 1729.78  5242.4 1733.15  5261.2 1732.62
  5318.6 1740.67  5363.3 1741.70  5386.6 1744.87  5405.7 1748.98  5427.0 1759.10
  5449.7 1761.67  5474.0 1774.25  5497.2 1783.07  5517.5 1787.78  5535.8 1788.40
#Mann=9,-1,0
  4198.1    0.07       0  4279.1   0.035       0  4508.1    0.07       0
  4526.9   0.035       0  4866.7    0.07       0  4978.7    0.05       0
  4988.2    0.07       0  5158.5   0.035       0  5161.0    0.07       0
Bank Sta=4978.7,4988.2
Exp/Cntr=0.3,0.1

Type RM Length L Ch R = 1,13279,433,433,433
BEGIN DESCRIPTION:
West Creek 28.0
END DESCRIPTION:
XS GIS Cut Line= 3
      1909075.00     13906424.97      1909025.00     13906075.00
      1908975.00     13905274.98
#Sta/Elev= 30
  4642.3 1730.90  4874.3 1723.80  4946.6 1718.56  5001.1 1716.30  5016.2 1715.13
  5017.3 1714.08  5017.8 1713.58  5027.1 1714.08  5029.1 1715.46  5042.9 1716.40
  5080.0 1718.60  5126.4 1719.91  5154.4 1718.45  5334.8 1719.49  5385.3 1721.51
  5431.0 1723.97  5458.0 1727.96  5484.1 1727.33  5491.1 1726.85  5500.1 1730.09
  5509.1 1731.29  5554.2 1742.70  5582.8 1752.78  5587.5 1755.28  5632.4 1769.64
  5662.4 1783.40  5675.2 1787.35  5689.5 1793.69  5731.6 1804.52  5797.4 1836.20
#Mann=8,-1,0
  4642.3    0.07       0  5017.3    0.05       0  5027.1    0.07       0
  5042.9   0.035       0  5080.0    0.07       0  5385.3   0.035       0
  5484.1    0.07       0  5582.8     0.1       0
Bank Sta=5017.3,5027.1
Exp/Cntr=0.3,0.1

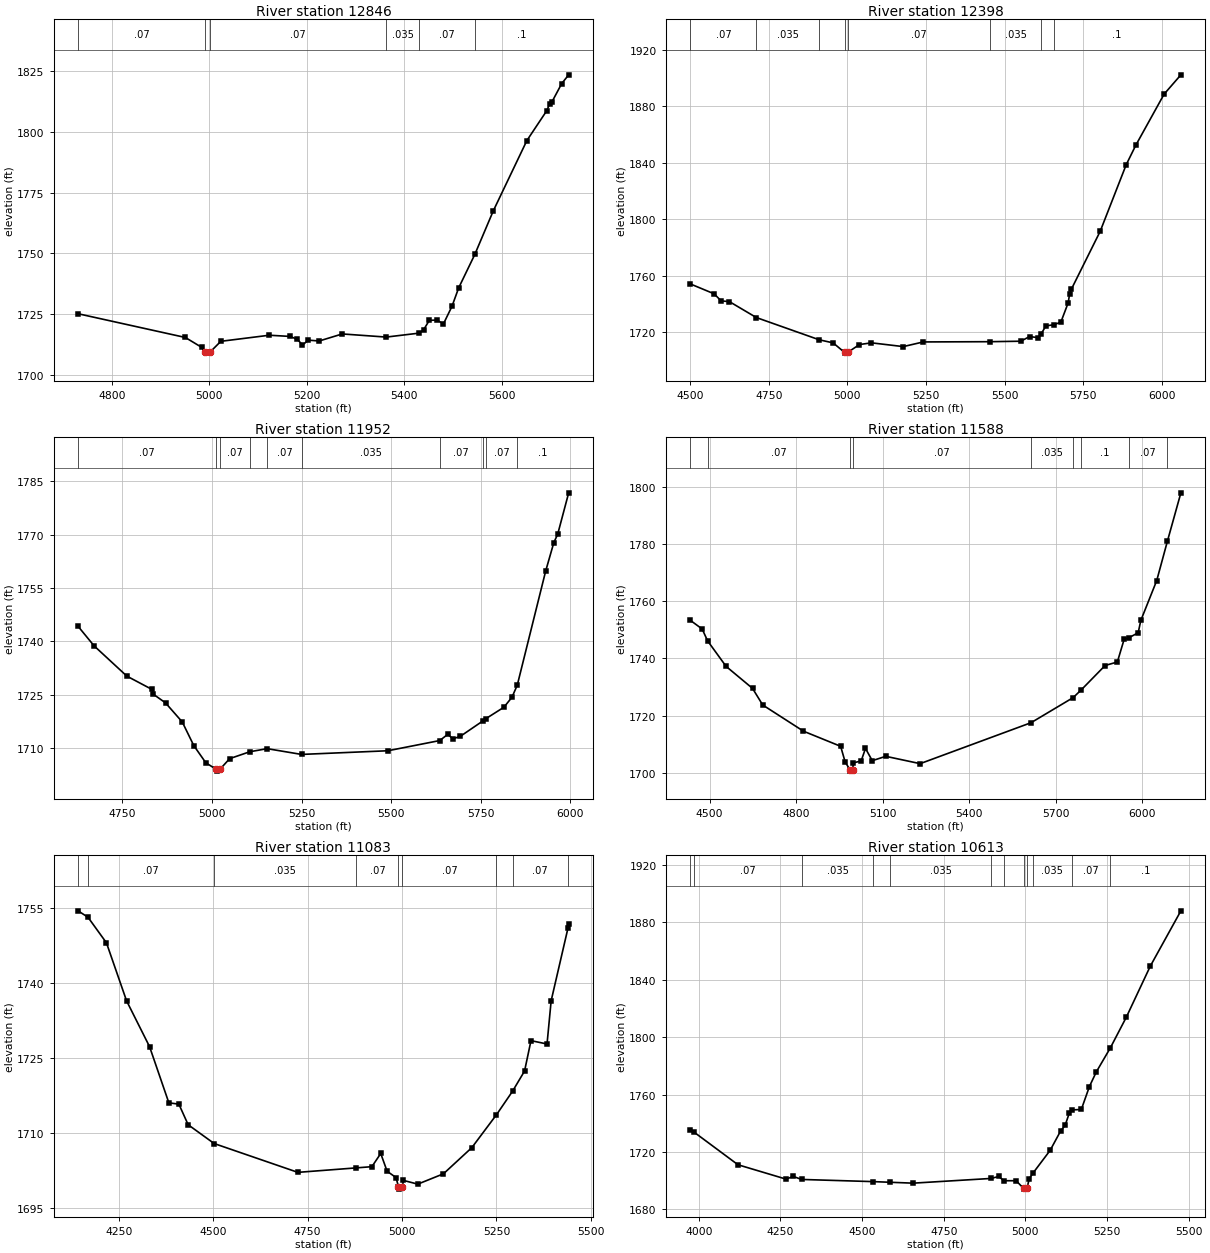
Type RM Length L Ch R = 1,12846,448,448,448
BEGIN DESCRIPTION:
West Creek 27.0
END DESCRIPTION:
XS GIS Cut Line= 3
      1909524.99     13906224.96      1909425.00     13905975.00
      1909076.92     13905325.06
#Sta/Elev= 30
  4730.8 1725.22  4950.8 1715.46  4984.4 1711.40  4992.1 1709.52  4992.6 1709.02
  5001.9 1709.52  5023.7 1713.88  5123.1 1716.38  5165.5 1715.89  5180.9 1714.67
  5191.2 1712.35  5203.2 1714.36  5225.4 1714.01  5272.8 1716.91  5363.0 1715.62
  5431.2 1717.26  5439.6 1718.59  5451.4 1722.51  5466.9 1722.61  5480.4 1721.05
  5498.0 1728.33  5511.6 1735.85  5544.7 1749.59  5582.5 1767.47  5651.5 1796.43
  5692.3 1808.71  5698.5 1811.66  5702.9 1812.32  5723.0 1819.87  5737.3 1823.47
#Mann=6,-1,0
  4730.8    0.07       0  4992.1    0.05       0  5001.9    0.07       0
  5363.0   0.035       0  5431.2    0.07       0  5544.7     0.1       0
Bank Sta=4992.1,5001.9
Exp/Cntr=0.3,0.1

Type RM Length L Ch R = 1,12398,446,446,446
BEGIN DESCRIPTION:
West Creek 26.0
END DESCRIPTION:
XS GIS Cut Line= 3
      1910224.98     13906124.99      1909825.00     13905825.00
      1909075.03     13905075.03
#Sta/Elev= 30
  4500.1 1754.20  4575.9 1747.19  4598.3 1742.18  4624.5 1741.67  4710.3 1730.39
  4910.2 1714.66  4954.5 1712.47  4990.9 1705.72  4991.4 1705.22  5000.8 1705.72
  5038.3 1711.30  5076.5 1712.50  5177.6 1709.84  5241.3 1713.14  5452.9 1713.31
  5551.6 1713.65  5579.2 1716.93  5606.8 1716.17  5616.4 1718.95  5631.6 1724.55
  5655.5 1725.23  5678.9 1727.12  5702.3 1740.89  5706.5 1746.75  5712.2 1750.37
  5804.1 1791.46  5886.8 1838.55  5917.2 1852.27  6007.4 1888.49  6060.7 1902.13
#Mann=8,-1,0
  4500.1    0.07       0  4710.3   0.035       0  4910.2    0.07       0
  4990.9    0.05       0  5000.8    0.07       0  5452.9   0.035       0
  5616.4    0.07       0  5655.5     0.1       0
Bank Sta=4990.9,5000.8
Exp/Cntr=0.3,0.1

Type RM Length L Ch R = 1,11952,364,364,364
BEGIN DESCRIPTION:
West Creek 25.0
END DESCRIPTION:
XS GIS Cut Line= 3
      1910429.34     13905841.51      1910175.00     13905575.00
      1909375.00     13904975.00
#Sta/Elev= 30
  4626.8 1744.23  4671.5 1738.73  4762.8 1730.22  4832.8 1726.48  4836.9 1725.11
  4870.7 1722.69  4917.4 1717.32  4949.6 1710.67  4983.2 1705.83  5012.4 1703.99
  5012.9 1703.49  5022.4 1703.99  5049.6 1707.00  5105.7 1708.94  5154.2 1709.81
  5250.0 1708.19  5490.9 1709.22  5635.5 1712.09  5658.1 1713.85  5672.1 1712.58
  5692.4 1713.24  5755.8 1717.60  5763.7 1718.21  5814.5 1721.46  5837.1 1724.28
  5851.9 1727.71  5930.9 1759.73  5953.8 1767.80  5964.5 1770.12  5995.2 1781.78
#Mann=10,-1,0
  4626.8    0.07       0  5012.4    0.05       0  5022.4    0.07       0
  5105.7   0.035       0  5154.2    0.07       0  5250.0   0.035       0
  5635.5    0.07       0  5755.8     0.1       0  5763.7    0.07       0
  5851.9     0.1       0
Bank Sta=5012.4,5022.4
Exp/Cntr=0.3,0.1

Type RM Length L Ch R = 1,11588,505,505,505
BEGIN DESCRIPTION:
West Creek 24.0
END DESCRIPTION:
XS GIS Cut Line= 3
      1910825.01     13905675.00      1910312.65     13905245.36
      1909624.99     13904474.99
#Sta/Elev= 30
  4432.9 1753.33  4474.1 1750.29  4493.0 1746.14  4557.1 1737.24  4648.7 1729.56
  4684.2 1723.75  4825.5 1714.60  4954.3 1709.33  4970.0 1703.85  4986.6 1701.16
  4987.1 1700.66  4996.6 1701.16  4998.0 1703.51  5025.6 1704.25  5040.5 1708.58
  5064.0 1704.31  5110.8 1705.83  5230.0 1703.27  5614.6 1717.57  5760.4 1726.32
  5787.9 1728.95  5871.4 1737.54  5913.9 1738.77  5937.3 1746.66  5954.5 1747.27
  5986.1 1748.98  5995.3 1753.28  6050.4 1767.20  6087.7 1781.04  6134.2 1797.84
#Mann=9,-1,0
  4432.9   0.035       0  4493.0    0.07       0  4986.6    0.05       0
  4996.6    0.07       0  5614.6   0.035       0  5760.4    0.07       0
  5787.9     0.1       0  5954.5    0.07       0  6087.7     0.1       0
Bank Sta=4986.6,4996.6
Exp/Cntr=0.3,0.1

Type RM Length L Ch R = 1,11083,470,470,470
BEGIN DESCRIPTION:
West Creek 23.0
END DESCRIPTION:
XS GIS Cut Line= 3
      1910974.97     13905524.97      1910425.00     13904875.00
      1910225.02     13904475.04
#Sta/Elev= 30
  4142.5 1754.46  4168.8 1753.17  4217.6 1748.05  4270.9 1736.42  4331.7 1727.25
  4382.8 1715.99  4409.3 1715.73  4433.9 1711.60  4502.8 1707.83  4724.3 1702.06
  4879.3 1702.96  4920.2 1703.20  4943.6 1705.84  4960.5 1702.28  4984.1 1701.02
  4990.5 1699.20  4991.0 1698.70  5000.7 1699.20  5003.6 1700.45  5041.7 1699.70
  5109.6 1701.77  5184.8 1707.02  5250.0 1713.61  5292.4 1718.30  5324.3 1722.36
  5341.3 1728.45  5383.8 1727.78  5394.7 1736.44  5439.2 1750.99  5441.1 1751.77
#Mann=9,-1,0
  4142.5     0.1       0  4168.8    0.07       0  4502.8   0.035       0
  4879.3    0.07       0  4990.5    0.05       0  5000.7    0.07       0
  5250.0   0.035       0  5292.4    0.07       0  5439.2     0.1       0
Bank Sta=4990.5,5000.7
Exp/Cntr=0.3,0.1

Type RM Length L Ch R = 1,10613,463,463,463
BEGIN DESCRIPTION:
West Creek 22.0
END DESCRIPTION:
XS GIS Cut Line= 3
      1911274.99     13905274.99      1910625.00     13904475.00
      1910374.98     13904074.96
#Sta/Elev= 30
  3973.8 1735.48  3984.5 1733.96  4120.0 1711.07  4266.9 1701.08  4289.4 1702.93
  4314.6 1700.84  4534.6 1699.32  4586.9 1698.86  4656.2 1698.25  4895.2 1701.54
  4918.6 1702.92  4933.8 1699.95  4971.9 1699.94  4994.5 1694.59  4995.0 1694.09
  5004.7 1694.59  5012.2 1701.48  5023.5 1705.30  5075.9 1721.12  5107.7 1734.49
  5121.9 1738.64  5134.5 1747.07  5141.8 1749.30  5171.4 1749.61  5196.2 1765.63
  5217.4 1775.85  5260.2 1792.52  5309.4 1814.04  5382.7 1849.56  5476.3 1888.09
#Mann=12,-1,0
  3973.8     0.1       0  3984.5    0.07       0  4314.6   0.035       0
  4534.6    0.07       0  4586.9   0.035       0  4895.2    0.07       0
  4933.8     0.1       0  4994.5    0.05       0  5004.7     0.1       0
  5023.5   0.035       0  5141.8    0.07       0  5260.2     0.1       0
Bank Sta=4994.5,5004.7
Exp/Cntr=0.3,0.1

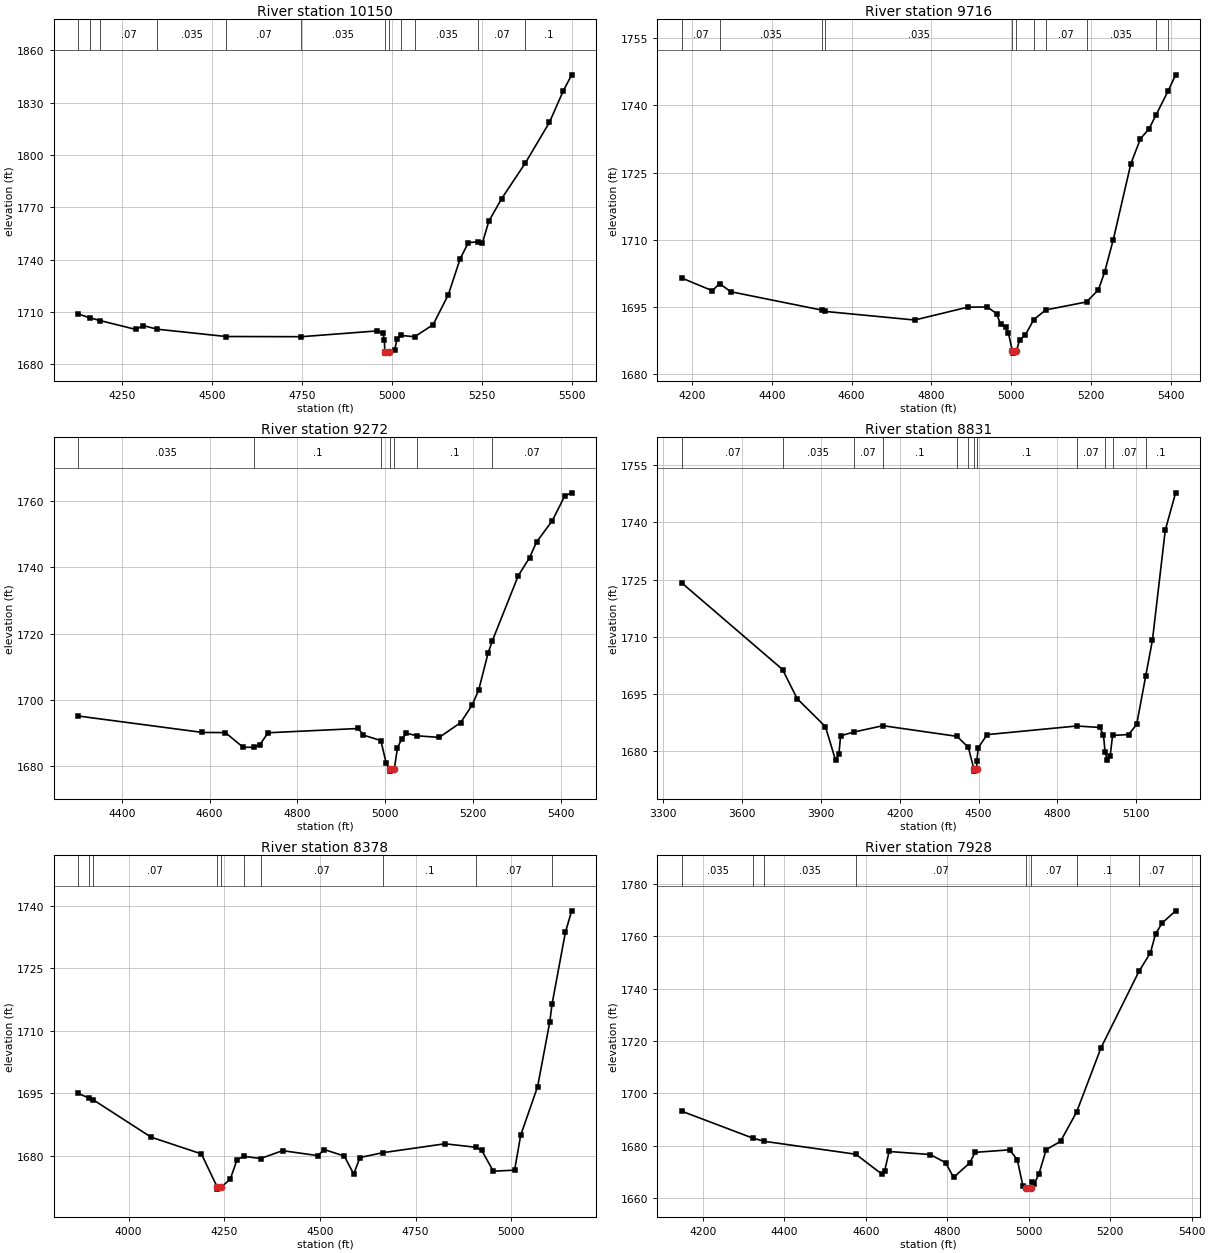
Type RM Length L Ch R = 1,10150,434,434,434
BEGIN DESCRIPTION:
West Creek 21.0
END DESCRIPTION:
XS GIS Cut Line= 3
      1911374.98     13905074.96      1911025.00     13904275.00
      1910624.98     13903974.98
#Sta/Elev= 30
  4126.8 1708.85  4160.1 1706.60  4187.7 1705.07  4287.7 1699.97  4307.4 1702.21
  4346.3 1700.14  4538.5 1695.94  4747.4 1695.83  4957.5 1699.13  4975.4 1697.74
  4978.7 1693.68  4980.1 1686.92  4980.6 1686.42  4990.3 1686.92  5007.1 1688.30
  5014.4 1694.63  5025.9 1696.53  5062.9 1695.80  5114.3 1702.71  5156.9 1720.01
  5189.3 1740.34  5212.5 1749.78  5240.0 1750.18  5251.4 1749.52  5269.4 1762.02
  5305.0 1774.95  5371.4 1795.50  5438.1 1818.71  5476.4 1836.65  5500.0 1845.91
#Mann=12,-1,0
  4126.8    0.07       0  4160.1   0.035       0  4187.7    0.07       0
  4346.3   0.035       0  4538.5    0.07       0  4747.4   0.035       0
  4980.1   0.035       0  4990.3   0.035       0  5025.9     0.1       0
  5062.9   0.035       0  5240.0    0.07       0  5371.4     0.1       0
Bank Sta=4980.1,4990.3
Exp/Cntr=0.3,0.1

Type RM Length L Ch R = 1,9716,444,444,444
BEGIN DESCRIPTION:
West Creek 20.0
END DESCRIPTION:
XS GIS Cut Line= 3
      1911574.99     13904874.97      1911375.00     13904075.00
      1911275.00     13903675.00
#Sta/Elev= 30
  4175.4 1701.40  4251.1 1698.60  4269.2 1700.19  4297.5 1698.37  4524.8 1694.28
  4534.0 1693.97  4758.3 1692.05  4891.2 1694.92  4940.7 1694.96  4963.7 1693.46
  4973.6 1691.06  4986.0 1690.43  4993.3 1689.17  5003.0 1685.15  5003.5 1684.65
  5013.5 1685.15  5021.1 1687.58  5035.5 1688.69  5056.8 1692.14  5086.9 1694.31
  5189.1 1696.09  5219.0 1698.84  5234.5 1702.80  5256.1 1710.02  5300.2 1727.00
  5324.2 1732.56  5345.8 1734.80  5363.3 1737.89  5393.5 1743.24  5412.3 1746.85
#Mann=11,-1,0
  4175.4    0.07       0  4269.2   0.035       0  4524.8    0.07       0
  4534.0   0.035       0  5003.0   0.035       0  5013.5   0.035       0
  5056.8     0.1       0  5086.9    0.07       0  5189.1   0.035       0
  5363.3    0.07       0  5393.5   0.035       0
Bank Sta=5003,5013.5
Exp/Cntr=0.3,0.1

Type RM Length L Ch R = 1,9272,441,441,441
BEGIN DESCRIPTION:
West Creek 19.0
END DESCRIPTION:
XS GIS Cut Line= 3
      1911887.45     13904436.56      1911675.00     13903775.00
      1911324.96     13903524.97
#Sta/Elev= 30
  4300.4 1695.17  4583.5 1690.22  4635.9 1690.17  4676.4 1685.74  4701.4 1685.74
  4714.6 1686.54  4733.2 1690.12  4938.8 1691.41  4950.7 1689.41  4990.3 1687.77
  5002.4 1680.98  5010.3 1679.06  5010.8 1678.56  5020.8 1679.06  5028.2 1685.58
  5037.7 1688.21  5048.7 1689.98  5073.2 1689.20  5123.4 1688.73  5172.3 1693.19
  5198.1 1698.42  5213.2 1702.92  5234.7 1714.09  5244.6 1717.88  5303.5 1737.43
  5329.3 1742.89  5345.3 1747.61  5380.9 1753.99  5410.0 1761.58  5425.4 1762.43
#Mann=7,-1,0
  4300.4   0.035       0  4701.4     0.1       0  4990.3    0.07       0
  5010.3    0.05       0  5020.8    0.07       0  5073.2     0.1       0
  5244.6    0.07       0
Bank Sta=5010.3,5020.8
Exp/Cntr=0.3,0.1

Type RM Length L Ch R = 1,8831,453,453,453
BEGIN DESCRIPTION:
West Creek 18.0
END DESCRIPTION:
XS GIS Cut Line= 3
      1912975.02     13904625.02      1911875.00     13903425.00
      1911725.01     13903225.01
#Sta/Elev= 30
  3371.6 1724.04  3753.9 1701.43  3809.1 1693.82  3917.0 1686.47  3955.6 1677.64
  3968.3 1679.32  3974.7 1684.08  4024.5 1685.04  4135.5 1686.72  4417.4 1683.93
  4460.7 1681.07  4482.1 1675.32  4482.6 1674.82  4492.6 1675.32  4492.8 1677.35
  4498.6 1680.94  4532.2 1684.38  4873.1 1686.64  4960.4 1686.26  4974.8 1684.35
  4981.2 1679.77  4989.6 1677.71  5000.4 1678.69  5009.6 1684.17  5071.0 1684.40
  5101.4 1687.08  5135.6 1699.67  5161.4 1709.17  5210.2 1737.94  5249.5 1747.71
#Mann=12,-1,0
  3371.6    0.07       0  3753.9   0.035       0  4024.5    0.07       0
  4135.5     0.1       0  4417.4   0.035       0  4460.7     0.1       0
  4482.1    0.05       0  4492.6     0.1       0  4873.1    0.07       0
  4981.2     0.1       0  5009.6    0.07       0  5135.6     0.1       0
Bank Sta=4482.1,4492.6
Exp/Cntr=0.3,0.1

Type RM Length L Ch R = 1,8378,450,450,450
BEGIN DESCRIPTION:
West Creek 17.0
END DESCRIPTION:
XS GIS Cut Line= 3
      1912975.01     13903975.01      1912175.00     13903175.00
      1912225.00     13903025.00
#Sta/Elev= 30
  3868.6 1695.00  3896.7 1693.90  3907.9 1693.46  4058.9 1684.52  4190.4 1680.50
  4231.8 1672.55  4232.3 1672.05  4242.4 1672.55  4266.0 1674.45  4283.7 1679.13
  4302.0 1679.91  4345.0 1679.39  4402.5 1681.27  4495.1 1680.08  4511.4 1681.54
  4563.8 1679.99  4588.5 1675.65  4604.7 1679.63  4664.7 1680.79  4826.8 1682.92
  4907.1 1682.09  4922.9 1681.35  4953.3 1676.35  5008.9 1676.60  5024.7 1684.94
  5069.0 1696.63  5100.6 1712.04  5106.7 1716.39  5141.7 1733.68  5158.1 1738.78
#Mann=10,-1,0
  3868.6    0.07       0  3896.7   0.035       0  3907.9    0.07       0
  4231.8    0.05       0  4242.4    0.07       0  4302.0   0.035       0
  4345.0    0.07       0  4664.7     0.1       0  4907.1    0.07       0
  5106.7     0.1       0
Bank Sta=4231.8,4242.4
Exp/Cntr=0.3,0.1

Type RM Length L Ch R = 1,7928,482,482,482
BEGIN DESCRIPTION:
West Creek 16.0
END DESCRIPTION:
XS GIS Cut Line= 3
      1913047.31     13903914.32      1912625.00     13903175.00
      1912424.99     13902874.99
#Sta/Elev= 30
  4148.6 1693.08  4322.1 1682.84  4350.8 1681.60  4575.3 1676.67  4640.1 1668.95
  4646.0 1670.32  4657.0 1677.72  4758.2 1676.55  4795.6 1673.44  4815.3 1667.81
  4854.9 1673.34  4868.2 1677.39  4952.7 1678.35  4971.7 1674.63  4985.6 1664.54
  4994.1 1663.82  4994.6 1663.32  5004.7 1663.82  5008.7 1666.02  5013.8 1665.42
  5024.7 1669.02  5042.7 1678.42  5077.9 1681.58  5117.6 1692.87  5177.4 1717.40
  5270.7 1746.67  5298.6 1753.67  5311.6 1761.05  5327.5 1765.13  5360.6 1769.80
#Mann=8,-1,0
  4148.6   0.035       0  4322.1    0.07       0  4350.8   0.035       0
  4575.3    0.07       0  4994.1    0.05       0  5004.7    0.07       0
  5117.6     0.1       0  5270.7    0.07       0
Bank Sta=4994.1,5004.7
Exp/Cntr=0.3,0.1

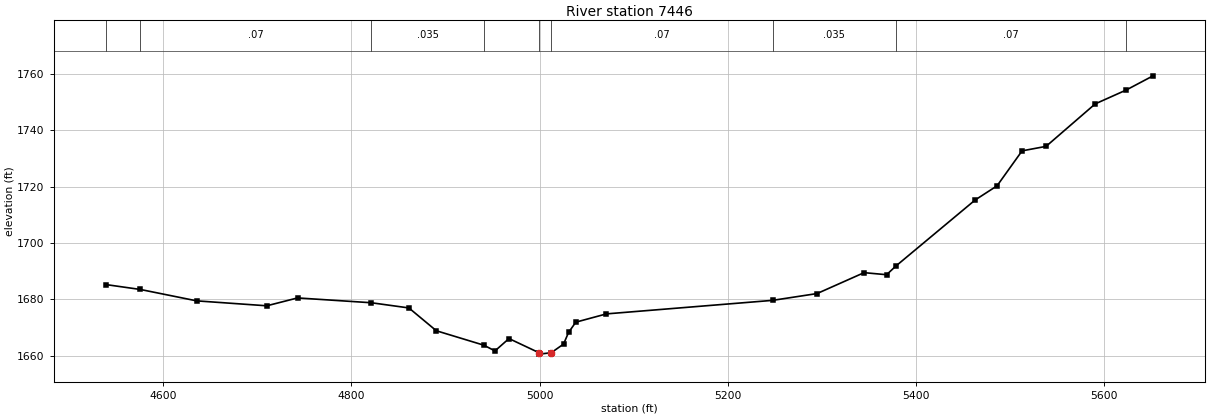
Type RM Length L Ch R = 1,7446,568,568,568
BEGIN DESCRIPTION:
West Creek 15.0
END DESCRIPTION:
XS GIS Cut Line= 3
      1913375.02     13903425.03      1913075.00     13903075.00
      1912525.03     13902725.02
#Sta/Elev= 30
  4539.0 1685.24  4575.5 1683.51  4635.5 1679.46  4710.0 1677.71  4742.7 1680.50
  4821.1 1678.79  4861.0 1676.95  4890.2 1668.85  4940.6 1663.74  4952.5 1661.70
  4967.4 1666.08  4999.3 1661.06  4999.8 1660.56  5012.3 1661.06  5025.4 1664.13
  5030.7 1668.26  5038.4 1671.90  5071.0 1674.84  5247.6 1679.64  5294.8 1682.05
  5344.8 1689.47  5368.7 1688.74  5378.5 1691.79  5462.9 1715.27  5486.1 1720.28
  5512.7 1732.69  5538.2 1734.28  5590.4 1749.35  5623.4 1754.28  5651.9 1759.31
#Mann=9,-1,0
  4539.0   0.035       0  4575.5    0.07       0  4821.1   0.035       0
  4940.6    0.07       0  4999.3    0.05       0  5012.3    0.07       0
  5247.6   0.035       0  5378.5    0.07       0  5623.4   0.035       0
Bank Sta=4999.3,5012.3
Exp/Cntr=0.3,0.1