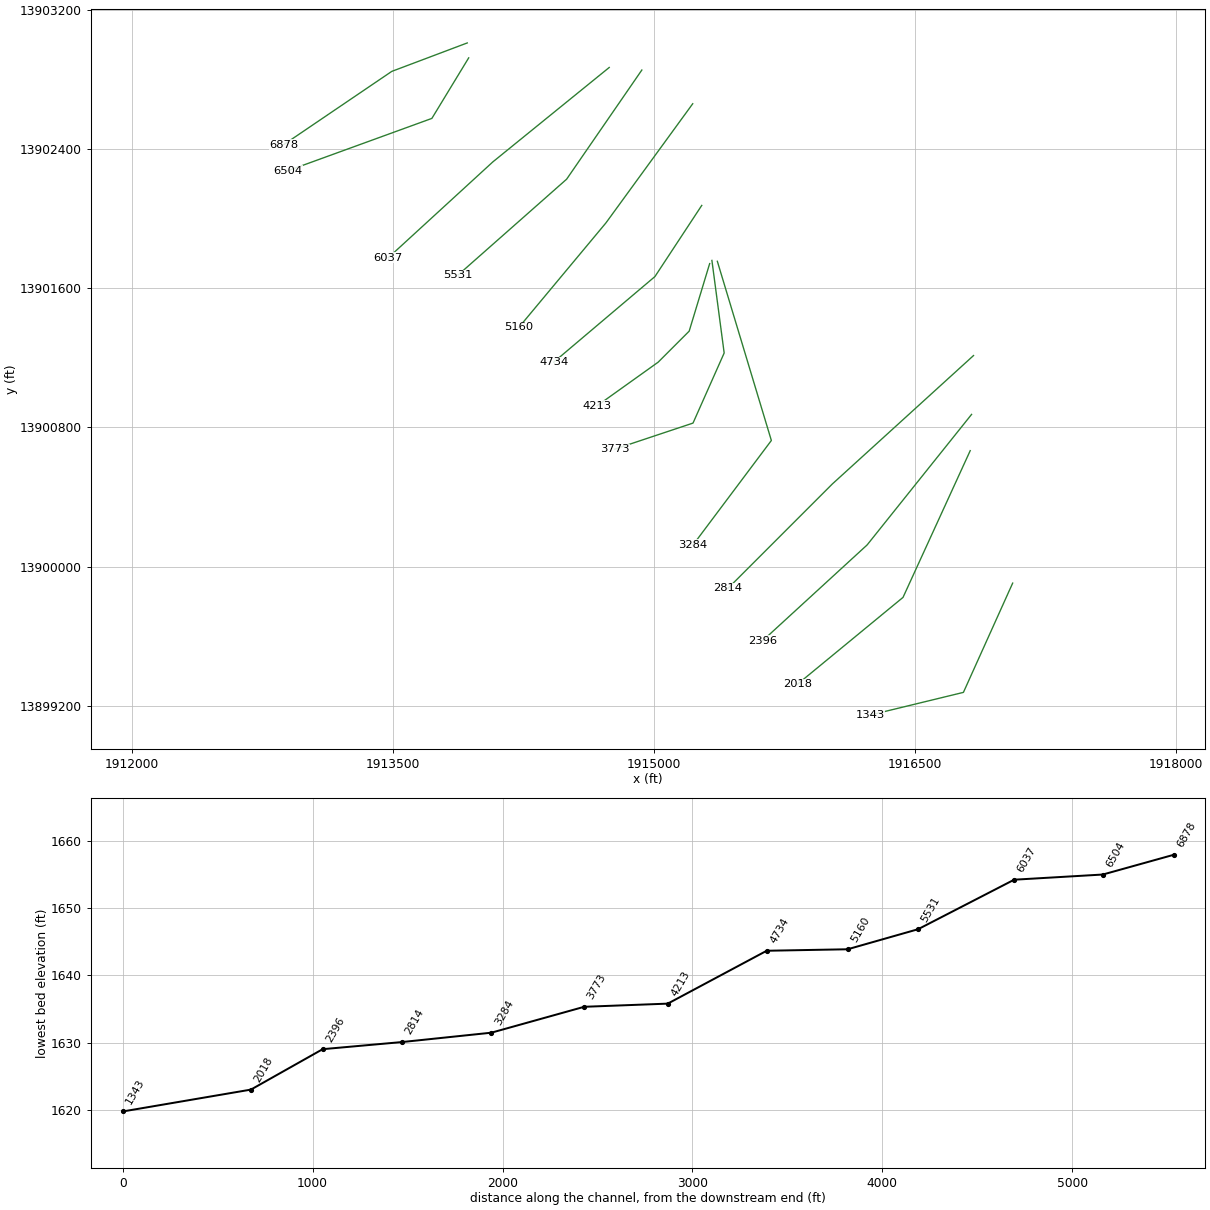
HEC-RAS study West Creek.prj: West Creek Base Level Engineering

--- West Creek.g01 (geometry) --- (continued)

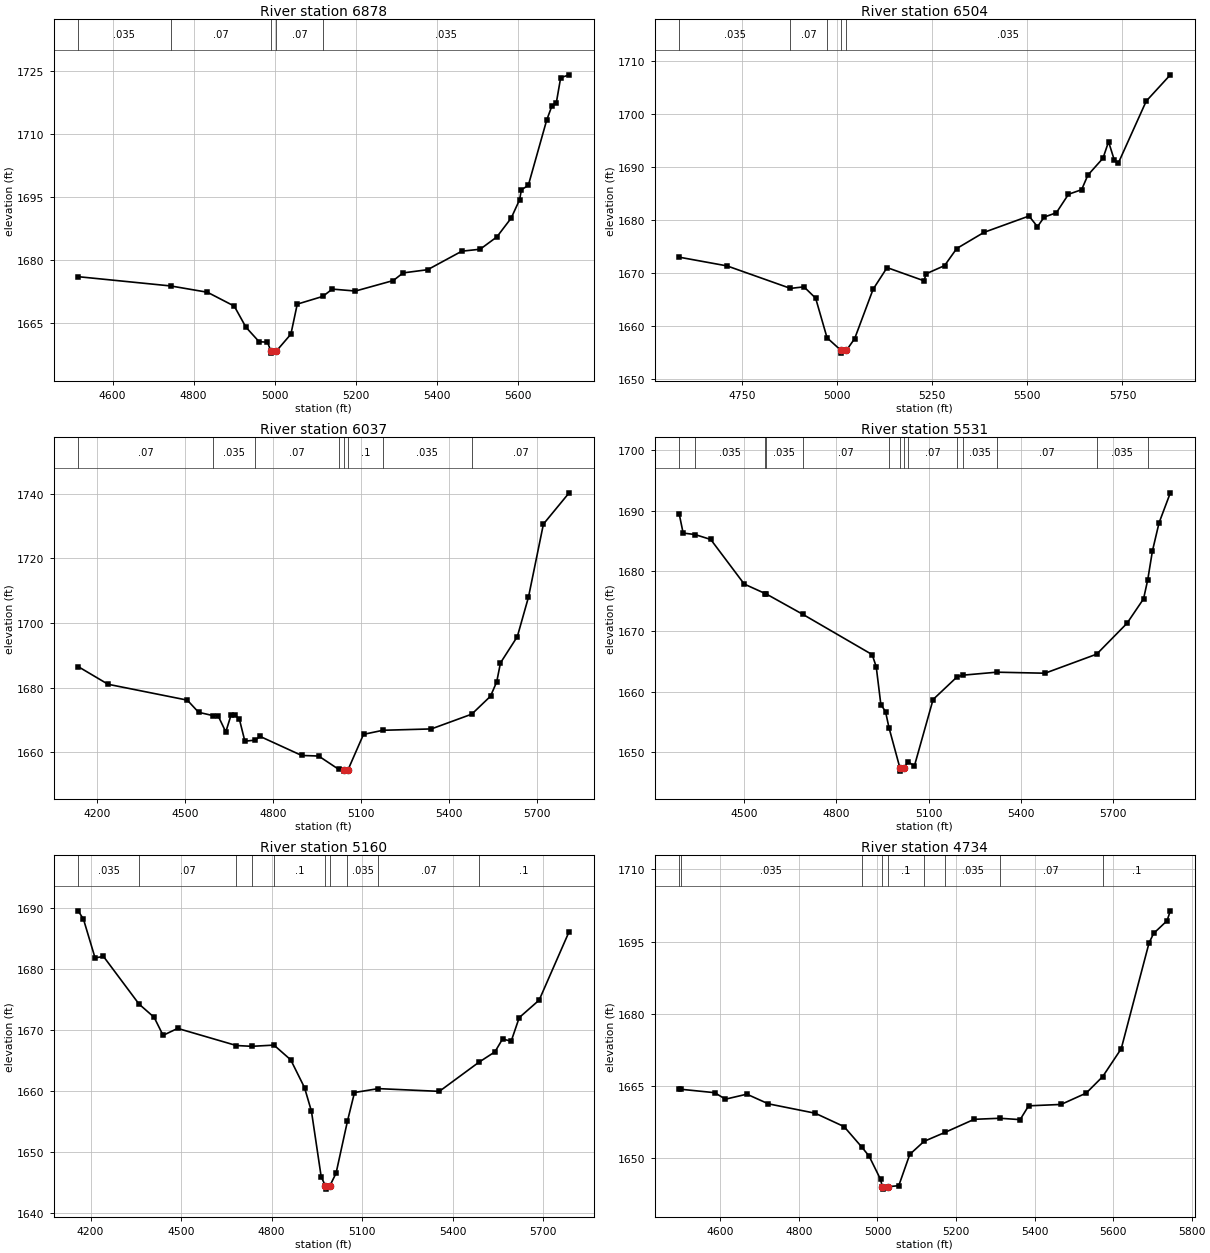
Type RM Length L Ch R = 1,6878,374,374,374
BEGIN DESCRIPTION:
West Creek 14.0
END DESCRIPTION:
XS GIS Cut Line= 3
      1913928.19     13903008.42      1913494.69     13902845.05
      1912875.00     13902425.00
#Sta/Elev= 30
  4514.9 1676.12  4743.5 1673.91  4834.1 1672.41  4900.3 1669.11  4929.1 1664.09
  4961.7 1660.62  4982.3 1660.52  4990.6 1658.41  4991.1 1657.91  5004.3 1658.41
  5040.1 1662.43  5055.8 1669.58  5118.8 1671.42  5142.2 1673.16  5199.5 1672.70
  5292.8 1675.20  5317.1 1677.02  5377.6 1677.78  5461.9 1682.19  5507.2 1682.66
  5548.3 1685.58  5583.7 1690.06  5604.4 1694.42  5609.1 1696.84  5626.0 1697.85
  5671.4 1713.41  5684.3 1716.79  5695.1 1717.50  5705.9 1723.51  5726.8 1724.20
#Mann=5,-1,0
  4514.9   0.035       0  4743.5    0.07       0  4990.6    0.05       0
  5004.3    0.07       0  5118.8   0.035       0
Bank Sta=4990.6,5004.3
Exp/Cntr=0.3,0.1

Type RM Length L Ch R = 1,6504,467,467,467
BEGIN DESCRIPTION:
West Creek 13.0
END DESCRIPTION:
XS GIS Cut Line= 3
      1913936.44     13902922.68      1913725.00     13902575.00
      1912894.97     13902273.25
#Sta/Elev= 30
  4585.7 1673.05  4711.1 1671.41  4877.8 1667.17  4913.3 1667.46  4943.9 1665.33
  4973.9 1657.86  5010.8 1655.47  5011.3 1654.97  5024.6 1655.47  5046.4 1657.70
  5094.9 1667.01  5131.6 1671.09  5228.3 1668.61  5234.7 1669.94  5282.6 1671.46
  5314.5 1674.68  5386.2 1677.73  5504.5 1680.81  5526.7 1678.80  5544.4 1680.61
  5576.3 1681.42  5608.2 1684.91  5642.7 1685.77  5659.1 1688.51  5698.9 1691.71
  5713.5 1694.81  5728.7 1691.33  5739.1 1690.78  5812.5 1702.47  5875.8 1707.42
#Mann=5,-1,0
  4585.7   0.035       0  4877.8    0.07       0  4973.9   0.035       0
  5010.8   0.035       0  5024.6   0.035       0
Bank Sta=5010.8,5024.6
Exp/Cntr=0.3,0.1

Type RM Length L Ch R = 1,6037,506,506,506
BEGIN DESCRIPTION:
West Creek 12.0
END DESCRIPTION:
XS GIS Cut Line= 3
      1914743.71     13902867.49      1914075.00     13902325.00
      1913475.02     13901775.02
#Sta/Elev= 30
  4134.2 1686.56  4236.3 1681.08  4506.7 1676.17  4545.3 1672.40  4595.4 1671.36
  4611.4 1671.40  4638.0 1666.32  4656.2 1671.62  4671.1 1671.52  4684.4 1670.26
  4703.1 1663.46  4738.1 1663.79  4754.8 1664.95  4896.8 1659.05  4954.8 1658.87
  5023.2 1654.75  5041.4 1654.70  5041.9 1654.20  5055.4 1654.70  5107.8 1665.58
  5174.1 1666.84  5339.2 1667.26  5477.0 1671.83  5541.0 1677.38  5562.2 1681.84
  5575.0 1687.69  5632.4 1695.81  5670.5 1708.04  5721.5 1730.65  5809.2 1740.32
#Mann=8,-1,0
  4134.2    0.07       0  4595.4   0.035       0  4738.1    0.07       0
  5023.2     0.1       0  5041.4    0.05       0  5055.4     0.1       0
  5174.1   0.035       0  5477.0    0.07       0
Bank Sta=5041.4,5055.4
Exp/Cntr=0.3,0.1

Type RM Length L Ch R = 1,5531,371,371,371
BEGIN DESCRIPTION:
West Creek 11.0
END DESCRIPTION:
XS GIS Cut Line= 3
      1914931.04     13902852.80      1914498.99     13902225.84
      1913874.96     13901674.97
#Sta/Elev= 30
  4291.0 1689.40  4303.5 1686.30  4341.6 1686.06  4393.0 1685.24  4501.7 1677.85
  4569.6 1676.28  4571.3 1676.26  4690.9 1672.86  4917.1 1666.15  4930.2 1664.13
  4945.2 1657.88  4960.3 1656.72  4971.5 1654.07  5007.2 1647.34  5007.7 1646.84
  5021.2 1647.34  5032.5 1648.36  5054.4 1647.75  5114.7 1658.71  5193.3 1662.50
  5212.8 1662.75  5321.2 1663.24  5478.1 1663.07  5645.8 1666.23  5744.1 1671.34
  5797.9 1675.40  5811.4 1678.55  5826.7 1683.34  5848.1 1687.98  5884.8 1692.97
#Mann=14,-1,0
  4291.0    0.07       0  4341.6   0.035       0  4569.6    0.07       0
  4571.3   0.035       0  4690.9    0.07       0  4971.5   0.035       0
  5007.2   0.035       0  5021.2   0.035       0  5032.5    0.07       0
  5193.3     0.1       0  5212.8   0.035       0  5321.2    0.07       0
  5645.8   0.035       0  5811.4    0.07       0
Bank Sta=5007.2,5021.2
Exp/Cntr=0.3,0.1

Type RM Length L Ch R = 1,5160,426,426,426
BEGIN DESCRIPTION:
West Creek 10.0
END DESCRIPTION:
XS GIS Cut Line= 3
      1915223.30     13902659.24      1914725.00     13901975.00
      1914224.99     13901374.98
#Sta/Elev= 30
  4158.6 1689.52  4176.2 1688.18  4214.8 1681.80  4242.8 1682.03  4360.6 1674.22
  4410.6 1672.05  4440.3 1669.09  4488.6 1670.23  4683.3 1667.42  4734.5 1667.29
  4807.8 1667.49  4863.4 1665.07  4909.1 1660.51  4932.1 1656.62  4964.3 1645.89
  4978.6 1644.36  4979.1 1643.86  4992.6 1644.36  5013.6 1646.47  5051.5 1655.05
  5074.7 1659.71  5153.7 1660.35  5355.9 1659.90  5487.1 1664.68  5540.1 1666.38
  5565.3 1668.48  5594.1 1668.14  5620.7 1672.00  5686.7 1674.87  5786.1 1686.11
#Mann=10,-1,0
  4158.6   0.035       0  4360.6    0.07       0  4683.3     0.1       0
  4734.5    0.07       0  4807.8     0.1       0  4978.6    0.05       0
  4992.6     0.1       0  5051.5   0.035       0  5153.7    0.07       0
  5487.1     0.1       0
Bank Sta=4978.6,4992.6
Exp/Cntr=0.3,0.1

Type RM Length L Ch R = 1,4734,521,521,521
BEGIN DESCRIPTION:
West Creek 9.0
END DESCRIPTION:
XS GIS Cut Line= 3
      1915275.03     13902075.04      1915006.27     13901666.60
      1914425.00     13901175.00
#Sta/Elev= 30
  4495.5 1664.39  4500.5 1664.36  4585.7 1663.66  4613.0 1662.31  4667.5 1663.35
  4722.1 1661.35  4841.4 1659.40  4915.0 1656.62  4959.5 1652.43  4978.6 1650.51
  5007.8 1645.68  5012.4 1644.14  5012.9 1643.64  5026.6 1644.14  5054.3 1644.36
  5082.3 1650.85  5118.5 1653.55  5172.9 1655.45  5246.2 1658.13  5311.2 1658.35
  5363.3 1658.07  5384.9 1660.93  5467.5 1661.22  5531.4 1663.57  5573.4 1666.99
  5620.7 1672.79  5691.4 1694.72  5703.2 1696.73  5737.2 1699.34  5745.7 1701.41
#Mann=9,-1,0
  4495.5     0.1       0  4500.5   0.035       0  4959.5     0.1       0
  5012.4    0.05       0  5026.6     0.1       0  5118.5    0.07       0
  5172.9   0.035       0  5311.2    0.07       0  5573.4     0.1       0
Bank Sta=5012.4,5026.6
Exp/Cntr=0.3,0.1

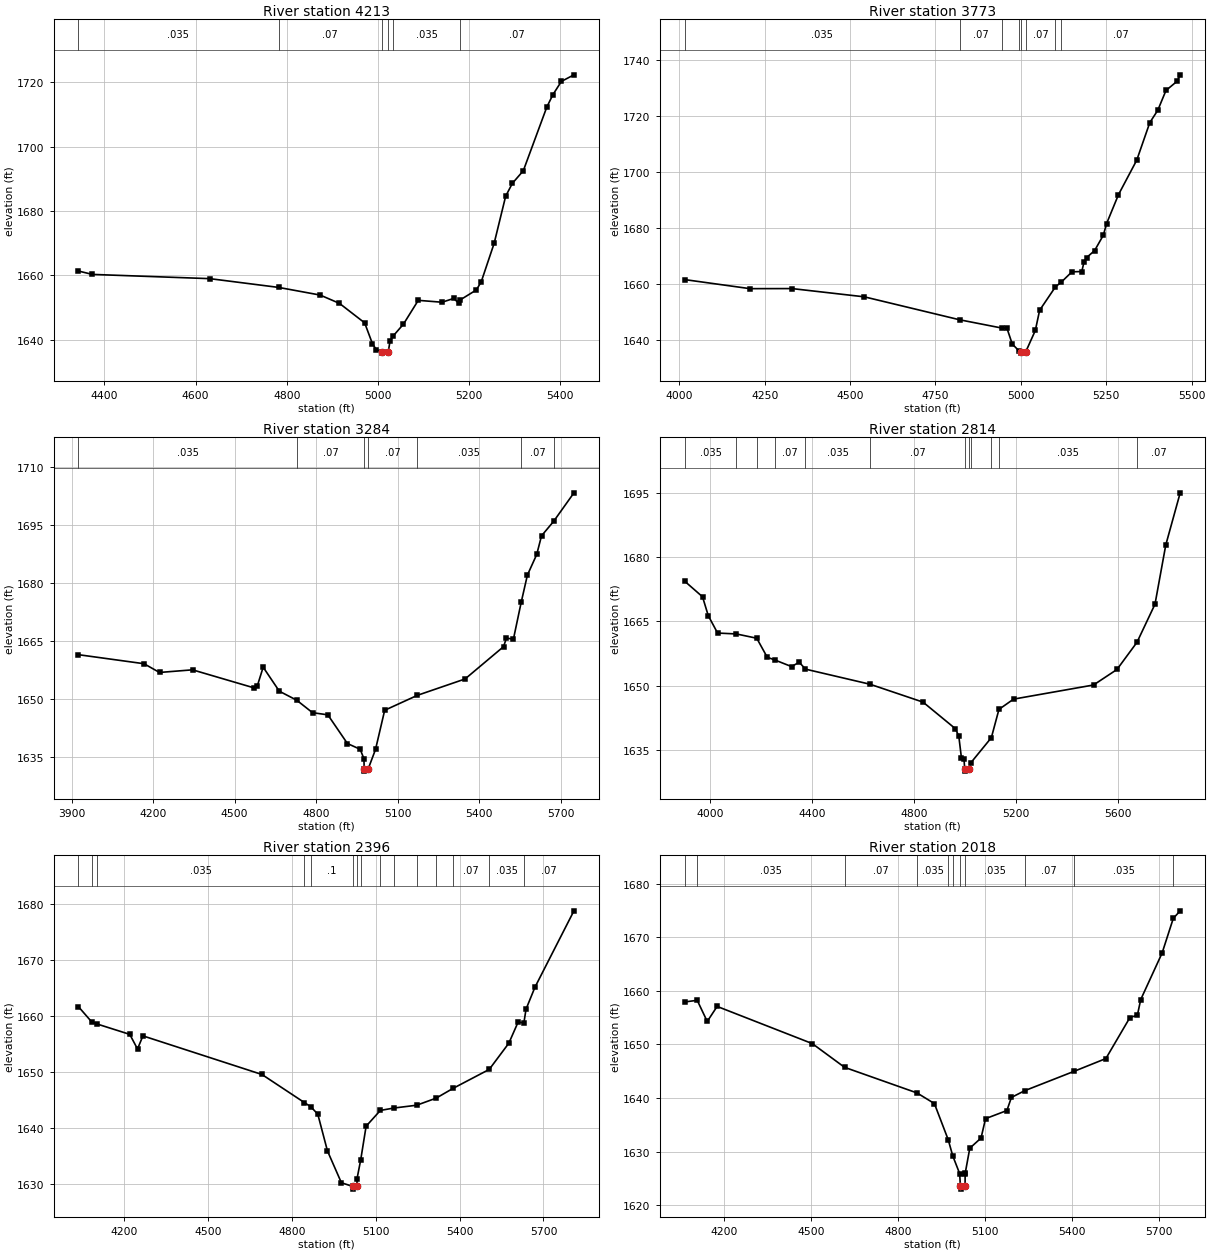
Type RM Length L Ch R = 1,4213,440,440,440
BEGIN DESCRIPTION:
West Creek 8.0
END DESCRIPTION:
XS GIS Cut Line= 4
      1915320.58     13901740.97      1915202.87     13901352.87
      1915025.00     13901175.00      1914675.02     13900925.01
#Sta/Elev= 30
  4342.8 1661.31  4373.6 1660.25  4631.3 1658.93  4782.0 1656.21  4873.3 1653.83
  4915.7 1651.24  4970.9 1645.19  4987.9 1638.74  4996.4 1636.85  5008.6 1636.28
  5009.1 1635.78  5022.8 1636.28  5026.6 1639.57  5033.0 1641.04  5055.9 1644.77
  5088.5 1652.19  5140.7 1651.60  5166.2 1652.78  5177.0 1651.34  5180.9 1652.36
  5215.7 1655.40  5226.5 1657.90  5255.0 1669.94  5280.2 1684.55  5294.9 1688.56
  5318.9 1692.47  5370.5 1712.28  5384.0 1716.16  5402.4 1720.24  5430.0 1722.29
#Mann=6,-1,0
  4342.8   0.035       0  4782.0    0.07       0  5008.6    0.05       0
  5022.8    0.07       0  5033.0   0.035       0  5180.9    0.07       0
Bank Sta=5008.6,5022.8
Exp/Cntr=0.3,0.1

Type RM Length L Ch R = 1,3773,489,489,489
BEGIN DESCRIPTION:
West Creek 7.0
END DESCRIPTION:
XS GIS Cut Line= 4
      1915333.49     13901759.26      1915403.91     13901227.54
      1915225.00     13900825.00      1914775.01     13900675.00
#Sta/Elev= 30
  4015.3 1661.62  4206.9 1658.37  4329.8 1658.40  4541.6 1655.45  4820.6 1647.24
  4944.6 1644.27  4958.9 1644.35  4974.8 1638.56  4993.5 1636.25  5000.1 1635.81
  5000.6 1635.31  5014.4 1635.81  5042.3 1643.41  5054.9 1650.63  5101.4 1659.04
  5118.2 1660.68  5149.5 1664.39  5178.3 1664.50  5185.1 1667.96  5192.2 1669.46
  5215.9 1671.99  5241.5 1677.50  5251.0 1681.65  5285.8 1692.00  5339.3 1704.34
  5377.5 1717.77  5400.9 1722.19  5424.9 1729.27  5457.8 1732.60  5466.5 1734.86
#Mann=8,-1,0
  4015.3   0.035       0  4820.6    0.07       0  4944.6   0.035       0
  4993.5    0.07       0  5000.1    0.05       0  5014.4    0.07       0
  5101.4   0.035       0  5118.2    0.07       0
Bank Sta=5000.1,5014.4
Exp/Cntr=0.3,0.1

Type RM Length L Ch R = 1,3284,470,470,470
BEGIN DESCRIPTION:
West Creek 6.0
END DESCRIPTION:
XS GIS Cut Line= 3
      1915364.74     13901754.14      1915675.00     13900725.00
      1915225.00     13900124.99
#Sta/Elev= 30
  3924.5 1661.58  4166.4 1659.24  4223.4 1656.98  4345.0 1657.66  4570.6 1653.01
  4583.2 1653.42  4605.1 1658.34  4664.6 1652.13  4728.5 1649.81  4786.8 1646.58
  4843.2 1646.02  4915.3 1638.60  4962.3 1637.11  4976.1 1634.67  4977.1 1631.96
  4977.6 1631.46  4991.4 1631.96  5018.8 1637.07  5052.5 1647.20  5173.1 1651.07
  5348.6 1655.30  5490.1 1663.65  5500.8 1665.85  5526.6 1665.61  5555.1 1675.10
  5578.0 1682.16  5612.3 1687.49  5630.0 1692.32  5674.7 1696.07  5749.4 1703.44
#Mann=7,-1,0
  3924.5   0.035       0  4728.5    0.07       0  4977.1    0.05       0
  4991.4    0.07       0  5173.1   0.035       0  5555.1    0.07       0
  5674.7     0.1       0
Bank Sta=4977.1,4991.4
Exp/Cntr=0.3,0.1

Type RM Length L Ch R = 1,2814,418,418,418
BEGIN DESCRIPTION:
West Creek 5.0
END DESCRIPTION:
XS GIS Cut Line= 3
      1916836.31     13901212.94      1916025.00     13900475.00
      1915425.03     13899875.03
#Sta/Elev= 30
  3898.6 1674.41  3969.1 1670.75  3991.7 1666.33  4028.2 1662.29  4102.1 1662.08
  4181.9 1661.08  4223.0 1656.65  4253.6 1655.99  4318.6 1654.46  4348.5 1655.49
  4373.1 1653.87  4626.8 1650.34  4834.6 1646.17  4960.9 1640.00  4974.8 1638.28
  4985.2 1633.16  4995.3 1632.92  4998.0 1630.57  4998.5 1630.07  5014.0 1630.57
  5021.1 1631.94  5102.7 1637.88  5132.5 1644.48  5189.8 1646.87  5503.7 1650.17
  5595.7 1653.79  5674.3 1660.14  5744.9 1669.02  5787.3 1682.86  5843.8 1695.01
#Mann=12,-1,0
  3898.6   0.035       0  4102.1    0.07       0  4181.9   0.035       0
  4253.6    0.07       0  4373.1   0.035       0  4626.8    0.07       0
  4998.0    0.05       0  5014.0    0.07       0  5021.1     0.1       0
  5102.7    0.07       0  5132.5   0.035       0  5674.3    0.07       0
Bank Sta=4998,5014
Exp/Cntr=0.3,0.1

Type RM Length L Ch R = 1,2396,378,378,378
BEGIN DESCRIPTION:
West Creek 4.0
END DESCRIPTION:
XS GIS Cut Line= 3
      1916824.97     13900874.81      1916225.00     13900125.00
      1915625.03     13899575.03
#Sta/Elev= 30
  4034.8 1661.63  4082.3 1658.91  4100.1 1658.54  4218.9 1656.66  4246.7 1654.05
  4266.1 1656.39  4692.2 1649.49  4843.9 1644.48  4867.3 1643.71  4892.0 1642.41
  4926.6 1635.84  4976.5 1630.15  5016.3 1629.51  5016.8 1629.01  5032.4 1629.51
  5032.5 1630.87  5045.7 1634.25  5065.0 1640.25  5116.0 1643.07  5164.7 1643.50
  5246.0 1644.00  5315.5 1645.26  5375.9 1647.00  5505.8 1650.40  5575.9 1655.08
  5609.1 1658.85  5629.8 1658.71  5637.5 1661.16  5669.4 1665.08  5809.0 1678.73
#Mann=15,-1,0
  4034.8   0.035       0  4082.3    0.07       0  4100.1   0.035       0
  4843.9    0.07       0  4867.3     0.1       0  5016.3    0.05       0
  5032.4     0.1       0  5045.7   0.035       0  5116.0    0.07       0
  5164.7   0.035       0  5246.0    0.07       0  5315.5   0.035       0
  5375.9    0.07       0  5505.8   0.035       0  5629.8    0.07       0
Bank Sta=5016.3,5032.4
Exp/Cntr=0.3,0.1

Type RM Length L Ch R = 1,2018,675,675,675
BEGIN DESCRIPTION:
West Creek 3.0
END DESCRIPTION:
XS GIS Cut Line= 3
      1916817.29     13900666.67      1916431.36     13899823.93
      1915825.04     13899325.03
#Sta/Elev= 30
  4062.6 1657.93  4106.3 1658.24  4140.9 1654.29  4175.1 1657.10  4503.8 1650.16
  4615.4 1645.73  4865.7 1640.95  4925.6 1638.97  4973.3 1632.23  4989.2 1629.18
  5012.9 1625.90  5015.5 1623.50  5016.0 1623.00  5031.6 1623.50  5031.8 1625.79
  5032.4 1626.07  5047.9 1630.64  5086.7 1632.53  5102.3 1636.15  5176.1 1637.67
  5191.6 1640.11  5237.1 1641.36  5407.4 1644.97  5518.0 1647.37  5601.1 1655.03
  5626.8 1655.46  5638.4 1658.38  5712.2 1667.06  5750.9 1673.54  5774.7 1674.94
#Mann=11,-1,0
  4062.6    0.07       0  4106.3   0.035       0  4615.4    0.07       0
  4865.7   0.035       0  4973.3     0.1       0  4989.2   0.035       0
  5015.5   0.035       0  5031.6   0.035       0  5237.1    0.07       0
  5407.4   0.035       0  5750.9    0.07       0
Bank Sta=5015.5,5031.6
Exp/Cntr=0.3,0.1

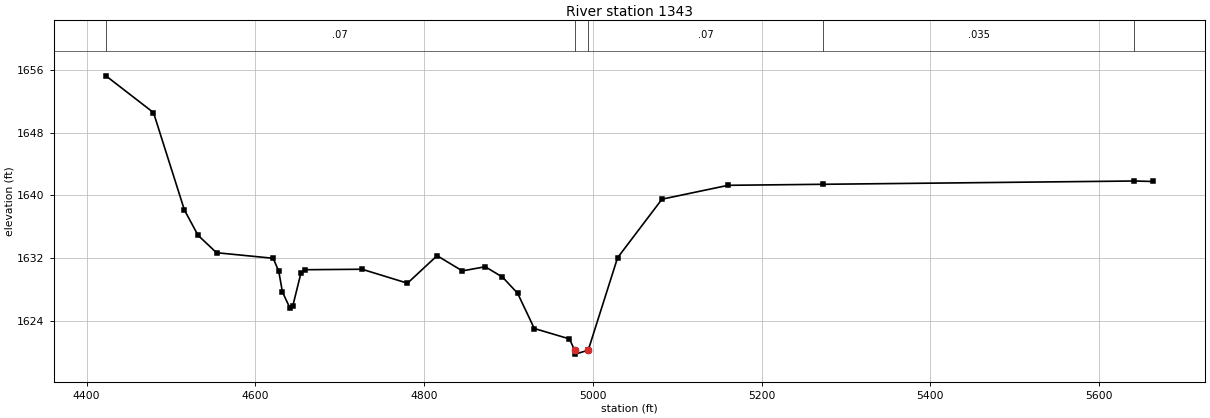
Type RM Length L Ch R = 1,1343,0,0,0
BEGIN DESCRIPTION:
West Creek 2.0
END DESCRIPTION:
XS GIS Cut Line= 3
      1917061.16     13899905.89      1916778.19     13899278.21
      1916241.35     13899147.70
#Sta/Elev= 30
  4422.9 1655.26  4479.3 1650.57  4515.9 1638.15  4532.1 1634.91  4554.0 1632.69
  4621.2 1631.98  4627.8 1630.30  4632.1 1627.68  4641.0 1625.63  4644.3 1625.86
  4654.1 1630.12  4659.3 1630.52  4726.5 1630.58  4780.3 1628.80  4815.4 1632.31
  4845.3 1630.37  4872.5 1630.90  4892.9 1629.58  4910.8 1627.52  4930.6 1623.02
  4972.3 1621.69  4978.4 1620.25  4978.9 1619.75  4994.5 1620.25  5029.3 1632.05
  5081.9 1639.52  5160.3 1641.29  5272.9 1641.42  5641.7 1641.84  5663.9 1641.78
#Mann=5,-1,0
  4422.9    0.07       0  4978.4    0.05       0  4994.5    0.07       0
  5272.9   0.035       0  5641.7    0.07       0
Bank Sta=4978.4,4994.5
Exp/Cntr=0.3,0.1

Chan Stop Cuts=-1