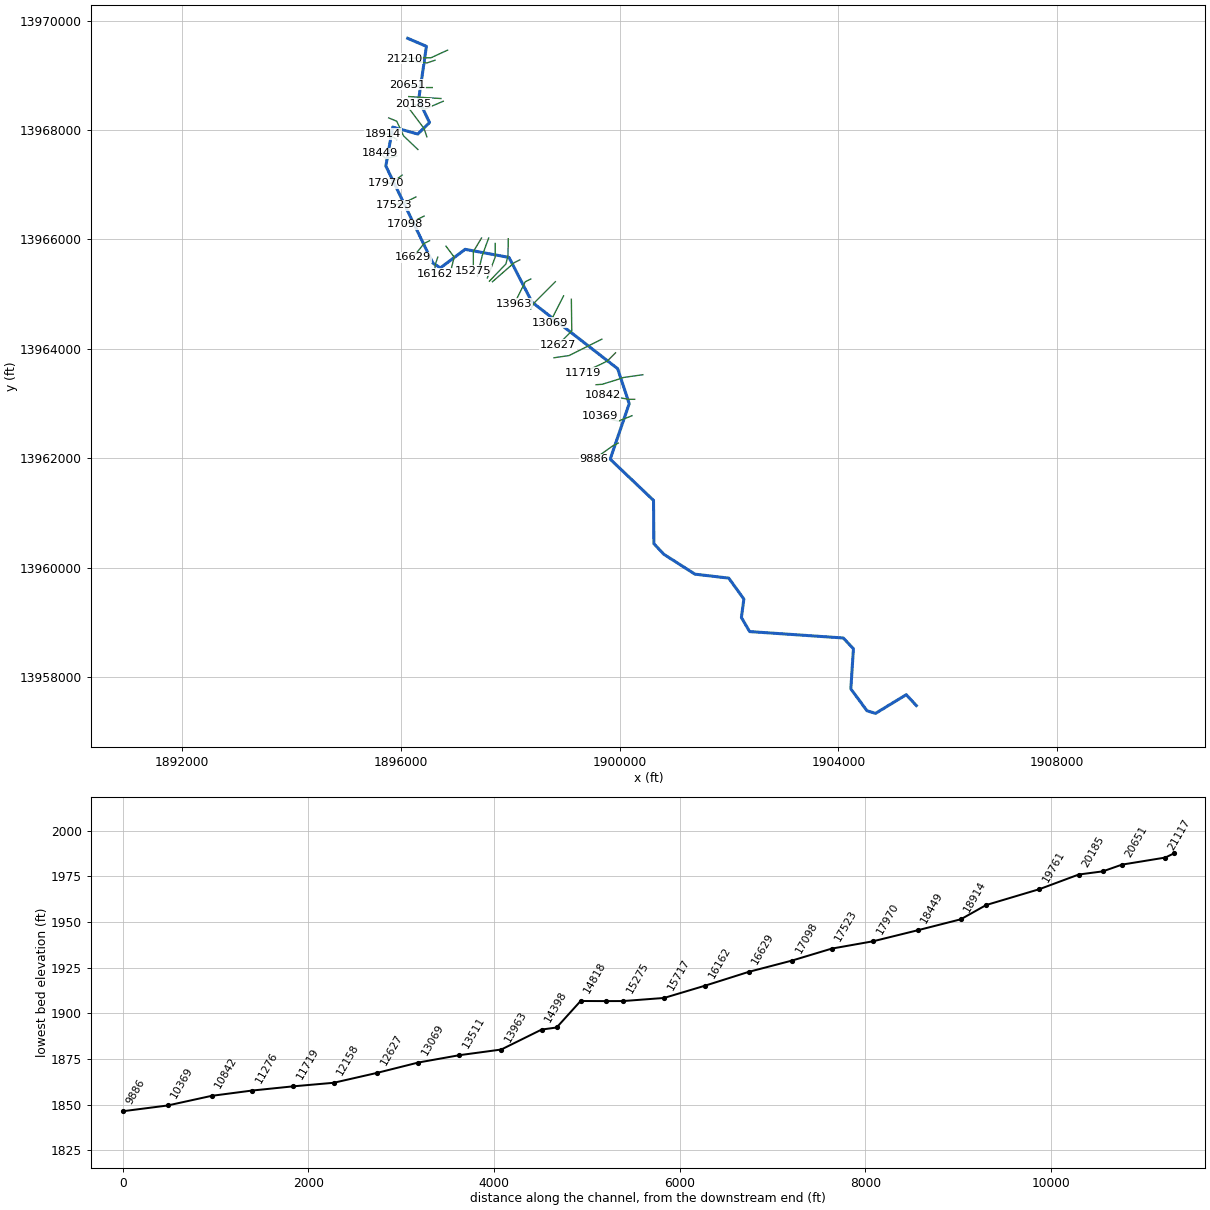
--- West Goat Creek.prj (project) ---

Proj Title=West Goat Creek Base Level Engineering
Current Plan=p01
Default Exp/Contr=0.3,0.1
English Units
Geom File=g01
Flow File=f01
Plan File=p01
Y Axis Title=Elevation
X Axis Title(PF)=Main Channel Distance
X Axis Title(XS)=Station
BEGIN DESCRIPTION:
West Goat Creek
END DESCRIPTION:
DSS Export Rating Curves= 0
DSS Export Rating Curve Sorted= 0
DSS Export Volume Flow Curves= 0
DXF OffsetX= 0
DXF OffsetY= 0
DXF ScaleX= 1
DXF ScaleY= 10

--- West Goat Creek.p01 (plan) ---

Plan Title=Multiple Run
Short Identifier=Multiple
Geom File=g01
Flow File=f01
Subcritical Flow
K Sum by GR= 0
Std Step Tol= 0.01
Critical Tol= 0.01
Num of Std Step Trials= 20
Max Error Tol= 0.3
Flow Tol Ratio= 0.001
Split Flow NTrial= 30
Split Flow Tol= 0.02
Split Flow Ratio= 0.02
Log Output Level= 0
Friction Slope Method= 1
Unsteady Friction Slope Method= 2
Unsteady Bridges Friction Slope Method= 1
Parabolic Critical Depth
Global Vel Dist=  1 , 1 , 1
Global Log Level= 0
CheckData=True
Encroach Param= -1, 0, 0, 0
BEGIN DESCRIPTION:
Multiple Run
END DESCRIPTION:

--- West Goat Creek.f01 (steady flow) ---

Flow Title=Multiple
Number of Profiles=7
Profile Names=10-year,25-year,50-year,1pct_min,100-year,1pct_plu,500-year
River Rch & RM= West Goat Creek,Reach-1,21210
    2101    3721    5317    3665    7313   14592   13680
River Rch & RM= West Goat Creek,Reach-1,12158
    2780    4991    7196    4999    9974   19901   18957
River Rch & RM= West Goat Creek,Reach-1,9886
    3306    5981    8669    6050   12071   24085   23157
River Rch & RM= West Goat Creek,Reach-1,8110
    3662    6645    9648    6743   13454   26844   25884
River Rch & RM= West Goat Creek,Reach-1,4853
    3977    7225   10499    7340   14645   29221   28195
Boundary for River Rch & Prof#=West Goat Creek,Reach-1,1
Up Type=0
Dn Type=3
Dn Slope=0.005
Boundary for River Rch & Prof#=West Goat Creek,Reach-1,2
Up Type=0
Dn Type=3
Dn Slope=0.005
Boundary for River Rch & Prof#=West Goat Creek,Reach-1,3
Up Type=0
Dn Type=3
Dn Slope=0.005
Boundary for River Rch & Prof#=West Goat Creek,Reach-1,4
Up Type=0
Dn Type=3
Dn Slope=0.005
Boundary for River Rch & Prof#=West Goat Creek,Reach-1,5
Up Type=0
Dn Type=3
Dn Slope=0.005
Boundary for River Rch & Prof#=West Goat Creek,Reach-1,6
Up Type=0
Dn Type=3
Dn Slope=0.005
Boundary for River Rch & Prof#=West Goat Creek,Reach-1,7
Up Type=0
Dn Type=3
Dn Slope=0.005

--- West Goat Creek.g01 (geometry) ---

Geom Title=Existing Conditions
Program Version=4.10

River Reach=West Goat Creek ,Reach-1
Reach XY= 30
        1896125.       13969675.      1896467.11     13969528.66
      1896324.59       13968550.       1896524.4     13968135.62
      1896309.78     13967925.24      1895851.09      13968052.3
      1895725.52     13967340.22      1896585.75     13965565.29
      1896723.35      13965478.1      1897175.09     13965817.25
      1897977.43     13965669.48      1898397.87     13964851.48
      1899964.22     13963634.68      1900174.94     13962995.03
      1899827.14     13961980.96      1900619.27     13961227.55
      1900626.05     13960435.43      1900808.32     13960241.64
      1901376.47     13959878.55      1901995.04     13959805.64
      1902271.33     13959423.42      1902226.12     13959085.46
      1902376.45     13958828.52      1904088.38     13958711.46
      1904274.45     13958514.36      1904226.82     13957781.12
      1904522.57     13957380.52      1904678.35     13957333.02
      1905240.28     13957674.63        1905425.       13957475.

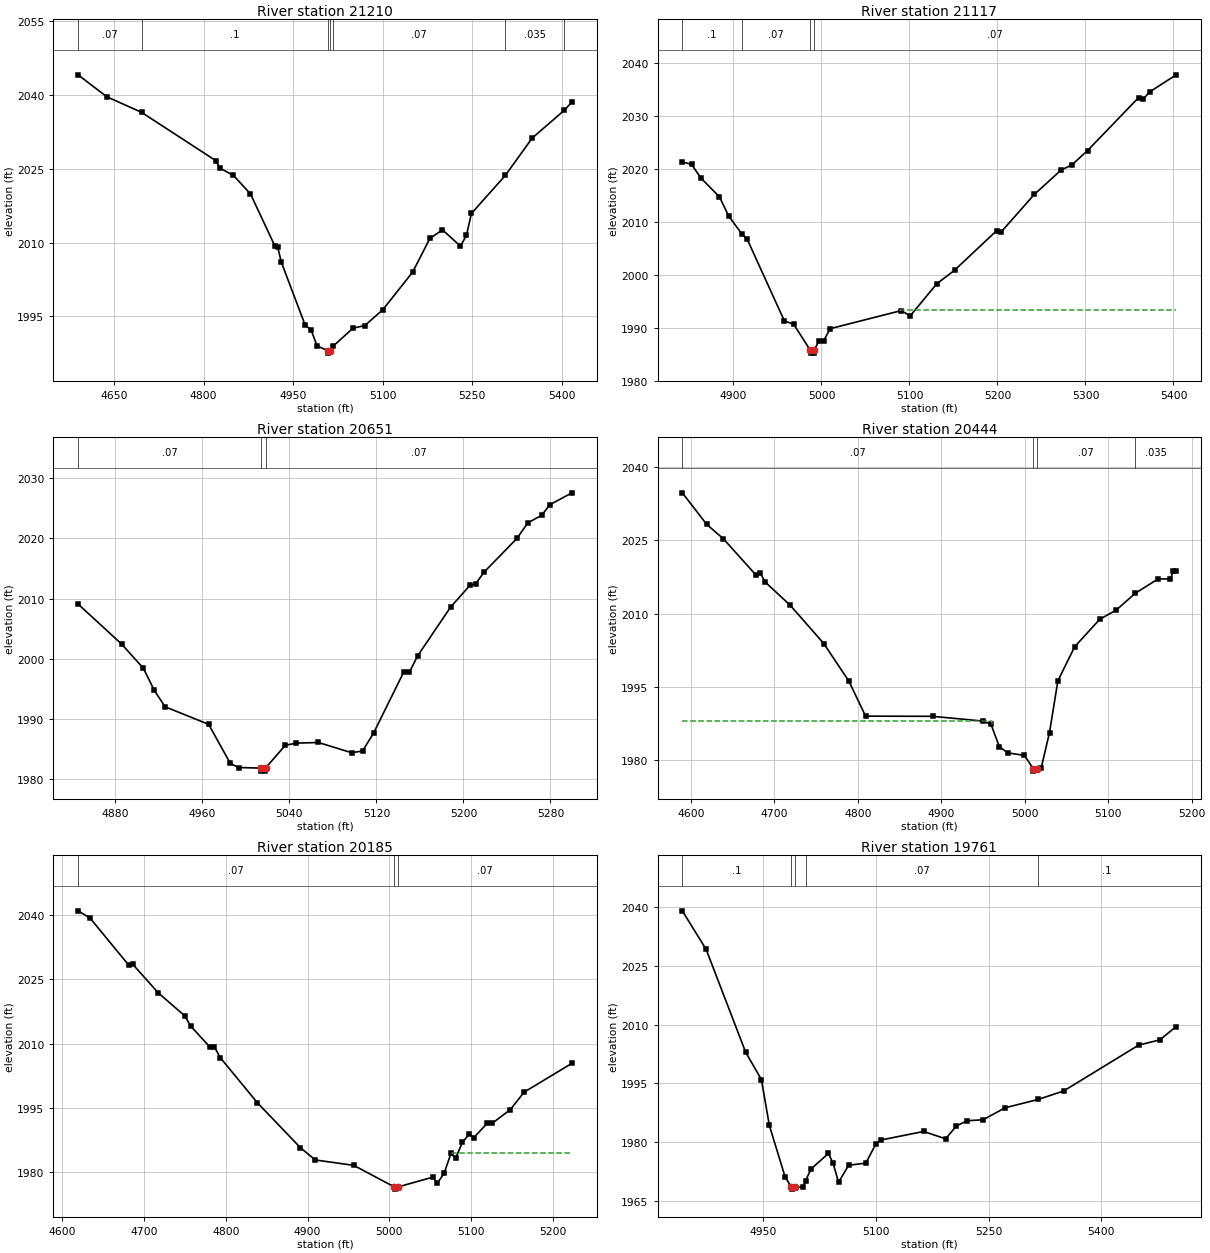
Type RM Length L Ch R = 1 ,21210   ,93,93,93
BEGIN DESCRIPTION:
West Goat Creek 47.0
END DESCRIPTION:
XS GIS Cut Line= 4
      1896854.68      13969459.4      1896550.99       13969320.
      1896296.11     13969313.53       1896058.4     13969302.01
#Sta/Elev= 30
  4589.9 2044.08  4637.7 2039.64  4696.1 2036.46  4820.6 2026.63  4827.1 2025.14
  4850.1 2023.63  4878.6 2019.88  4919.1 2009.37    4924 2009.18    4930 2006.08
  4970.1 1993.22  4980.1 1992.23  4990.1 1988.99  5008.1 1988.02  5008.3 1987.52
  5012.1 1988.02  5016.8 1988.91  5050.1 1992.58  5070.1 1993.13  5100.1 1996.33
  5150.1 2003.98    5179 2010.83  5200.1 2012.57  5230.2 2009.27  5240.2 2011.44
  5248.6 2015.91  5305.3 2023.62  5350.3 2031.22  5403.9 2036.85    5417 2038.57
#Mann= 7 ,-1 , 0
  4589.9     .07       0  4696.1      .1       0  5008.1     .05       0
  5012.1      .1       0  5016.8     .07       0  5305.3    .035       0
  5403.9     .07       0
Bank Sta=5008.1,5012.1
XS Rating Curve= 0 ,0
Exp/Cntr=0.3,0.1

Type RM Length L Ch R = 1 ,21117   ,466,466,466
BEGIN DESCRIPTION:
West Goat Creek 46.0
END DESCRIPTION:
XS GIS Cut Line= 3
      1896625.01       13969275.        1896475.       13969225.
      1896075.03       13969275.
#Sta/Elev= 30
  4841.9 2021.28  4852.4 2020.82    4863 2018.25  4884.1  2014.7  4894.6 2011.08
  4909.4 2007.74  4915.7 2006.69  4957.9  1991.3  4968.4 1990.69  4987.5 1985.74
  4987.7 1985.24  4991.2 1985.24  4991.5 1985.74  4997.4  1987.6  5002.5  1987.6
  5010.1 1989.86  5090.7 1993.26  5100.8 1992.25    5131  1998.3  5151.2 2000.86
  5199.1 2008.33  5204.1 2008.06  5241.9 2015.16  5272.1 2019.72  5284.7 2020.74
  5302.4 2023.43  5360.3 2033.39  5365.3 2033.06  5372.9 2034.48  5403.1  2037.7
#Mann= 4 ,-1 , 0
  4841.9      .1       0  4909.4     .07       0  4987.5     .05       0
  4991.5     .07       0
#XS Ineff= 2 , 0
                         5088.79         1993.42
Permanent Ineff=
       F       F
Bank Sta=4987.5,4991.5
XS Rating Curve= 0 ,0
Exp/Cntr=0.3,0.1

Type RM Length L Ch R = 1 ,20651   ,207,207,207
BEGIN DESCRIPTION:
West Goat Creek 45.0
END DESCRIPTION:
XS GIS Cut Line= 3
      1896574.98       13968775.        1896425.       13968775.
      1896125.02       13968825.
#Sta/Elev= 30
  4845.7 2009.08  4885.7 2002.45  4905.7 1998.44  4915.7 1994.78  4925.7 1992.05
  4965.7 1989.14  4985.7 1982.65  4993.2 1981.98  5013.9 1981.88  5014.2 1981.38
  5017.8 1981.38    5018 1981.88  5036.2 1985.67  5046.4 1986.02  5066.6 1986.13
  5097.1 1984.44  5107.2 1984.71  5117.3 1987.67  5145.2 1997.85  5150.3 1997.79
  5157.9  2000.5  5188.3 2008.61    5206 2012.19  5211.1 2012.39  5218.7 2014.33
  5249.1 2019.96  5259.3 2022.57  5271.9  2023.8  5279.5 2025.57  5299.8 2027.53
#Mann= 3 ,-1 , 0
  4845.7     .07       0  5013.9     .05       0    5018     .07       0
Bank Sta=5013.9,5018
XS Rating Curve= 0 ,0
Exp/Cntr=0.3,0.1

Type RM Length L Ch R = 1 ,20444   ,259,259,259
BEGIN DESCRIPTION:
Mapping XS fb677e36
END DESCRIPTION:
XS GIS Cut Line= 2
       1896734.2     13968574.38      1896143.51     13968610.46
#Sta/Elev= 30
  4589.6 2034.77  4618.9 2028.29  4638.9 2025.33  4677.9  2017.9  4682.9 2018.35
    4689 2016.46    4719 2011.69  4759.1 2003.86  4789.2 1996.14  4809.2 1988.97
  4889.4 1988.93  4949.5 1987.96  4959.5 1987.28  4969.5  1982.7  4979.5 1981.44
  4999.6 1980.91  5010.1 1978.19  5010.4 1977.69  5014.3 1978.19  5019.6 1978.31
  5029.6 1985.61  5039.6 1996.19  5059.7 2003.19  5089.7 2008.82  5109.8 2010.75
  5132.4 2014.17  5159.9 2017.13  5174.4 2017.09  5178.1 2018.76  5181.4 2018.76
#Mann= 4 ,-1 , 0
  4589.6     .07       0  5010.1     .05       0  5014.3     .07       0
  5132.4    .035       0
#XS Ineff= 2 , 0
         4960.65 1988.05
Permanent Ineff=
       F       F
Bank Sta=5010.1,5014.3
XS Rating Curve= 0 ,0
Exp/Cntr=0.3,0.1

Type RM Length L Ch R = 1 ,20185   ,424,424,424
BEGIN DESCRIPTION:
West Goat Creek 44.0
END DESCRIPTION:
XS GIS Cut Line= 3
      1896775.03     13968525.01        1896425.       13968375.
      1896225.03     13968474.99
#Sta/Elev= 30
  4619.2 2041.04  4633.7 2039.37  4680.9  2028.4  4686.3 2028.49  4717.2 2021.87
  4749.8 2016.47    4757 2014.09  4780.6 2009.15  4786.1 2009.16  4793.3 2006.68
  4838.6 1996.16  4891.2 1985.66  4909.4 1982.78  4956.5 1981.52  5006.3 1976.46
  5006.6 1975.96  5010.5 1976.46  5053.1 1978.75  5058.7 1977.31  5067.1 1979.66
  5075.5 1984.31  5081.1  1983.2  5089.5 1986.87  5097.9 1988.86  5103.4    1988
  5120.2 1991.41  5125.8 1991.34  5148.2 1994.56  5164.9 1998.62  5223.6 2005.39
#Mann= 3 ,-1 , 0
  4619.2     .07       0  5006.3     .05       0  5010.5     .07       0
#XS Ineff= 2 , 0
                         5076.35         1984.32
Permanent Ineff=
       F       F
Bank Sta=5006.3,5010.5
XS Rating Curve= 0 ,0
Exp/Cntr=0.3,0.1

Type RM Length L Ch R = 1 ,19761   ,574,574,574
BEGIN DESCRIPTION:
West Goat Creek 43.0
END DESCRIPTION:
XS GIS Cut Line= 3
      1896475.01     13967874.96        1896425.       13968025.
      1896124.97     13968425.04
#Sta/Elev= 30
  4841.9 2039.07  4873.6 2029.24  4926.3 2002.94  4947.3 1995.95  4957.9 1984.21
    4979 1971.02  4987.4 1968.44  4987.7 1967.94  4991.6 1968.44  5003.2 1968.48
  5006.1 1970.09  5013.6 1973.12  5036.5 1977.05  5042.8 1974.63  5050.1 1969.69
  5063.6 1974.03  5086.5  1974.6  5100.1 1979.56  5107.3 1980.52  5163.6 1982.68
  5192.8 1980.79  5207.3 1984.12  5221.9 1985.43  5242.8 1985.66  5271.9 1988.72
  5316.1 1990.86  5350.1 1993.02  5450.1 2004.75  5478.2 2006.08  5500.1 2009.49
#Mann= 5 ,-1 , 0
  4841.9      .1       0  4987.4     .05       0  4991.6      .1       0
  5006.1     .07       0  5316.1      .1       0
Bank Sta=4987.4,4991.6
XS Rating Curve= 0 ,0
Exp/Cntr=0.3,0.1

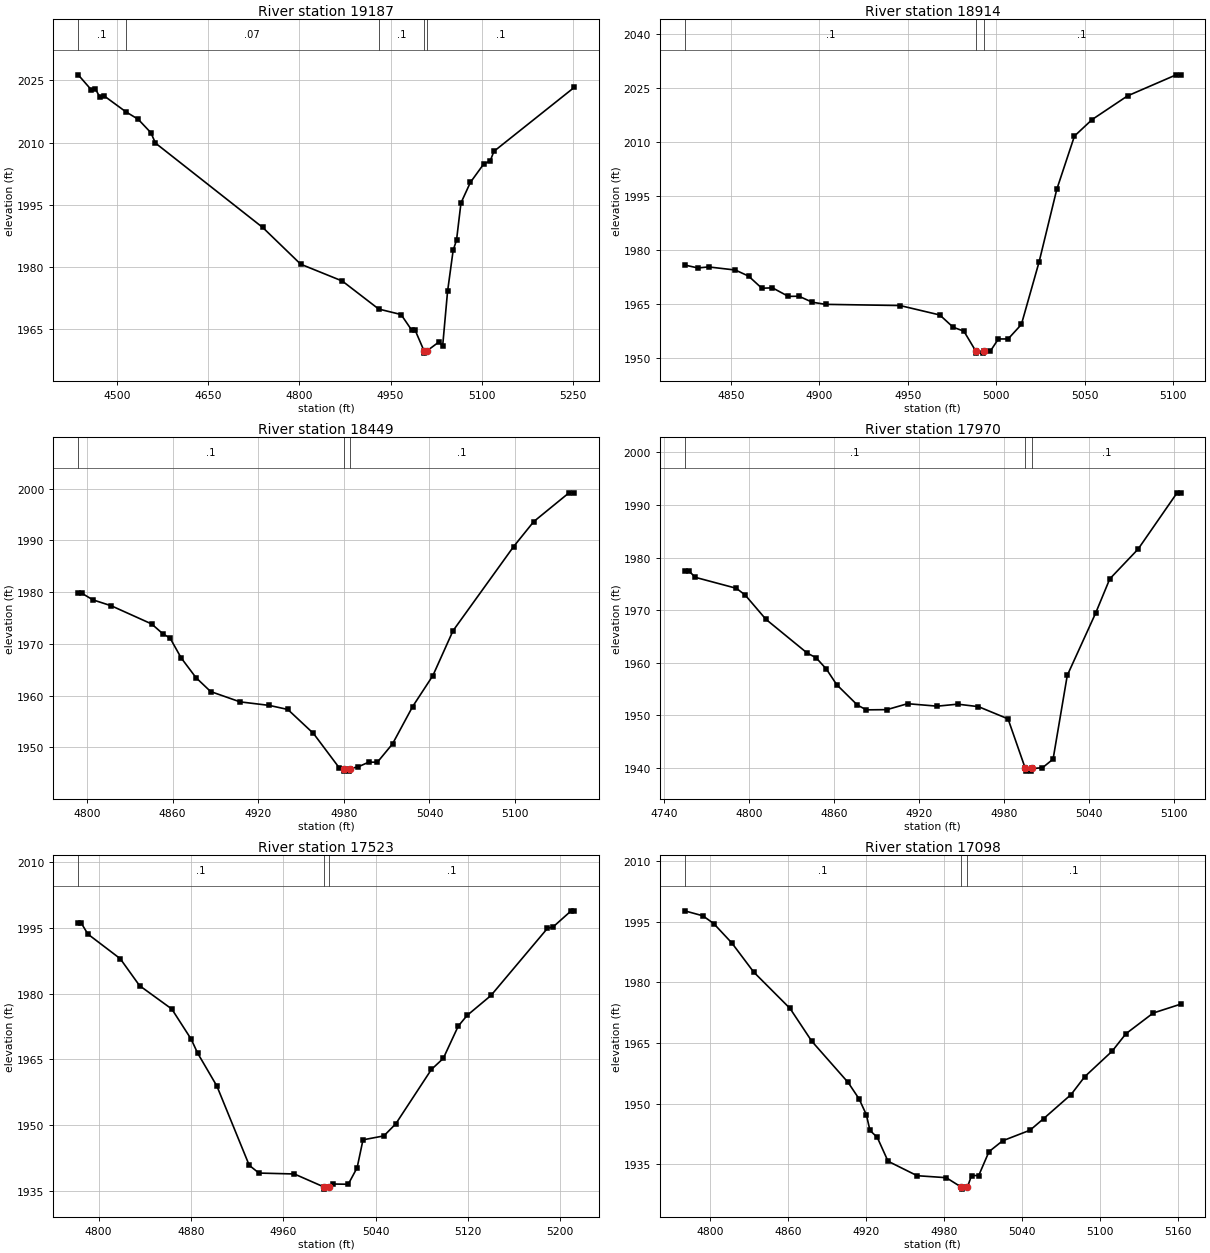
Type RM Length L Ch R = 1 ,19187   ,273,273,273
BEGIN DESCRIPTION:
West Goat Creek 42.0
END DESCRIPTION:
XS GIS Cut Line= 4
      1896311.85     13967642.19      1896050.52     13967890.58
      1895924.69     13968159.36       1895777.4     13968220.52
#Sta/Elev= 30
  4435.6 2026.36  4456.7 2022.82  4463.6 2023.05  4470.9 2021.06  4477.8 2021.33
  4514.1 2017.44  4534.4 2015.64  4555.4 2012.38  4562.7 2009.91  4739.5 1989.54
    4802 1980.69  4870.5 1976.63  4930.5 1969.87  4967.3 1968.55  4984.6 1964.84
  4990.1 1964.91  5005.3 1959.74  5005.6 1959.24  5009.6 1959.74  5030.3    1962
  5035.8 1960.91  5043.9 1974.12  5053.1 1984.02  5058.7 1986.52    5066 1995.46
  5081.5 2000.42  5103.4 2004.84  5114.2  2005.6  5120.2  2007.9  5252.4 2023.31
#Mann= 5 ,-1 , 0
  4435.6      .1       0  4514.1     .07       0  4930.5      .1       0
  5005.3     .05       0  5009.6      .1       0
Bank Sta=5005.3,5009.6
XS Rating Curve= 0 ,0
Exp/Cntr=0.3,0.1

Type RM Length L Ch R = 1 ,18914   ,465,465,465
BEGIN DESCRIPTION:
West Goat Creek 41.0
END DESCRIPTION:
XS GIS Cut Line= 3
      1895925.01       13967825.        1895775.       13967925.
      1895674.99       13967925.
#Sta/Elev= 30
  4823.9 1975.89  4831.4 1975.07  4837.4 1975.36  4852.5  1974.5    4860 1972.82
  4867.5 1969.45  4873.5 1969.56  4882.5 1967.19  4888.5 1967.23    4896 1965.57
  4903.5 1964.98  4945.6 1964.65  4968.1 1962.03  4975.6 1958.64  4981.7 1957.54
  4988.5 1951.95  4988.8 1951.45  4992.5 1951.45  4992.8 1951.95  4996.7 1952.03
  5001.2 1955.38  5006.7 1955.38  5014.2  1959.4  5024.2 1976.73  5034.2 1996.86
  5044.2 2011.66  5054.2 2016.24  5074.2  2022.8  5101.7 2028.64  5104.2 2028.64
#Mann= 3 ,-1 , 0
  4823.9      .1       0  4988.5     .05       0  4992.8      .1       0
Bank Sta=4988.5,4992.8
XS Rating Curve= 0 ,0
Exp/Cntr=0.3,0.1

Type RM Length L Ch R = 1 ,18449   ,479,479,479
BEGIN DESCRIPTION:
West Goat Creek 40.0
END DESCRIPTION:
XS GIS Cut Line= 3
        1895925.       13967525.        1895725.       13967475.
      1895624.99     13967575.01
#Sta/Elev= 30
  4793.8 1979.77  4796.4 1979.77  4804.1 1978.51    4817 1977.36  4845.3 1973.85
  4853.1 1971.96  4858.2 1971.12    4866 1967.28  4876.3  1963.5  4886.6  1960.8
  4907.2 1958.81  4927.8 1958.12  4940.7 1957.34  4958.7  1952.7  4976.8 1946.05
  4979.8 1945.93  4980.1 1945.43  4983.8 1945.43  4984.1 1945.93  4989.7 1946.22
  4997.4 1947.16  5003.5 1947.16  5014.1 1950.69  5028.2  1957.9  5042.4 1963.89
  5056.5 1972.54    5099 1988.81  5113.1 1993.63  5137.8 1999.18  5141.4 1999.18
#Mann= 3 ,-1 , 0
  4793.8      .1       0  4979.8     .05       0  4984.1      .1       0
Bank Sta=4979.8,4984.1
XS Rating Curve= 0 ,0
Exp/Cntr=0.3,0.1

Type RM Length L Ch R = 1 ,17970   ,447,447,447
BEGIN DESCRIPTION:
West Goat Creek 39.0
END DESCRIPTION:
XS GIS Cut Line= 3
      1896025.02     13967175.02        1895825.       13967025.
      1895725.03       13967025.
#Sta/Elev= 30
  4754.7 1977.42  4757.9 1977.42    4762 1976.25  4791.2 1974.15  4797.4 1972.87
    4812 1968.27  4841.2 1961.84  4847.4 1960.97  4854.7 1958.81    4862 1955.84
  4876.6 1951.97  4882.9 1951.06  4897.4  1951.1    4912 1952.23  4932.9 1951.76
  4947.4 1952.14    4962 1951.67  4982.9 1949.35  4995.1 1939.92  4995.4 1939.42
  4999.4 1939.42  4999.8 1939.92  5007.2 1940.06  5014.7  1941.7  5024.7  1957.6
  5044.7 1969.42  5054.7 1975.94  5074.7  1981.6  5102.2 1992.29  5104.7 1992.29
#Mann= 3 ,-1 , 0
  4754.7      .1       0  4995.1     .05       0  4999.8      .1       0
#XS Ineff= 2 , 0
         4911.88 1951.92
Permanent Ineff=
       F       F
Bank Sta=4995.1,4999.8
XS Rating Curve= 0 ,0
Exp/Cntr=0.3,0.1

Type RM Length L Ch R = 1 ,17523   ,425,425,425
BEGIN DESCRIPTION:
West Goat Creek 38.0
END DESCRIPTION:
XS GIS Cut Line= 3
      1896275.04     13966775.02        1896075.       13966675.
      1895875.01       13966625.
#Sta/Elev= 30
  4782.3 1996.08  4785.1 1996.08  4790.7 1993.64  4818.7 1988.03  4835.5 1981.86
  4863.4 1976.53  4880.2 1969.64  4885.8 1966.45  4902.5 1958.92  4930.5 1940.84
  4938.9 1939.06  4969.6 1938.85  4995.2 1935.89  4995.6 1935.39  4999.9 1935.89
  5003.2 1936.56  5016.3  1936.5    5024 1940.27  5029.1 1946.65  5047.2 1947.55
  5057.5  1950.3  5088.4 1962.73  5098.7 1965.26  5111.6  1972.6  5119.3 1975.06
    5140 1979.62  5188.9 1994.94  5194.1 1995.34  5209.5 1998.96  5212.1 1998.96
#Mann= 3 ,-1 , 0
  4782.3      .1       0  4995.2     .05       0  4999.9      .1       0
Bank Sta=4995.2,4999.9
XS Rating Curve= 0 ,0
Exp/Cntr=0.3,0.1

Type RM Length L Ch R = 1 ,17098   ,469,469,469
BEGIN DESCRIPTION:
West Goat Creek 37.0
END DESCRIPTION:
XS GIS Cut Line= 3
      1896425.01       13966425.        1896225.       13966325.
      1896075.03     13966275.01
#Sta/Elev= 30
  4780.5 1997.69  4794.5 1996.46  4802.9 1994.52  4816.8 1989.74  4833.6 1982.56
  4861.6 1973.55  4878.3 1965.46  4906.3 1955.25  4914.7 1951.21  4920.3  1947.3
  4923.1 1943.39  4928.7 1941.69    4937 1935.78  4959.4  1932.2  4981.8 1931.71
  4993.4 1929.38  4993.7 1928.88  4998.1 1929.38  5001.3 1932.24  5006.8 1932.24
  5014.7 1938.14  5025.2 1940.83  5046.3 1943.45  5056.8 1946.32  5077.9 1952.27
  5088.4 1956.68  5109.5 1962.99  5120.1  1967.3  5141.1 1972.42  5162.2 1974.61
#Mann= 3 ,-1 , 0
  4780.5      .1       0  4993.4     .05       0  4998.1      .1       0
Bank Sta=4993.4,4998.1
XS Rating Curve= 0 ,0
Exp/Cntr=0.3,0.1

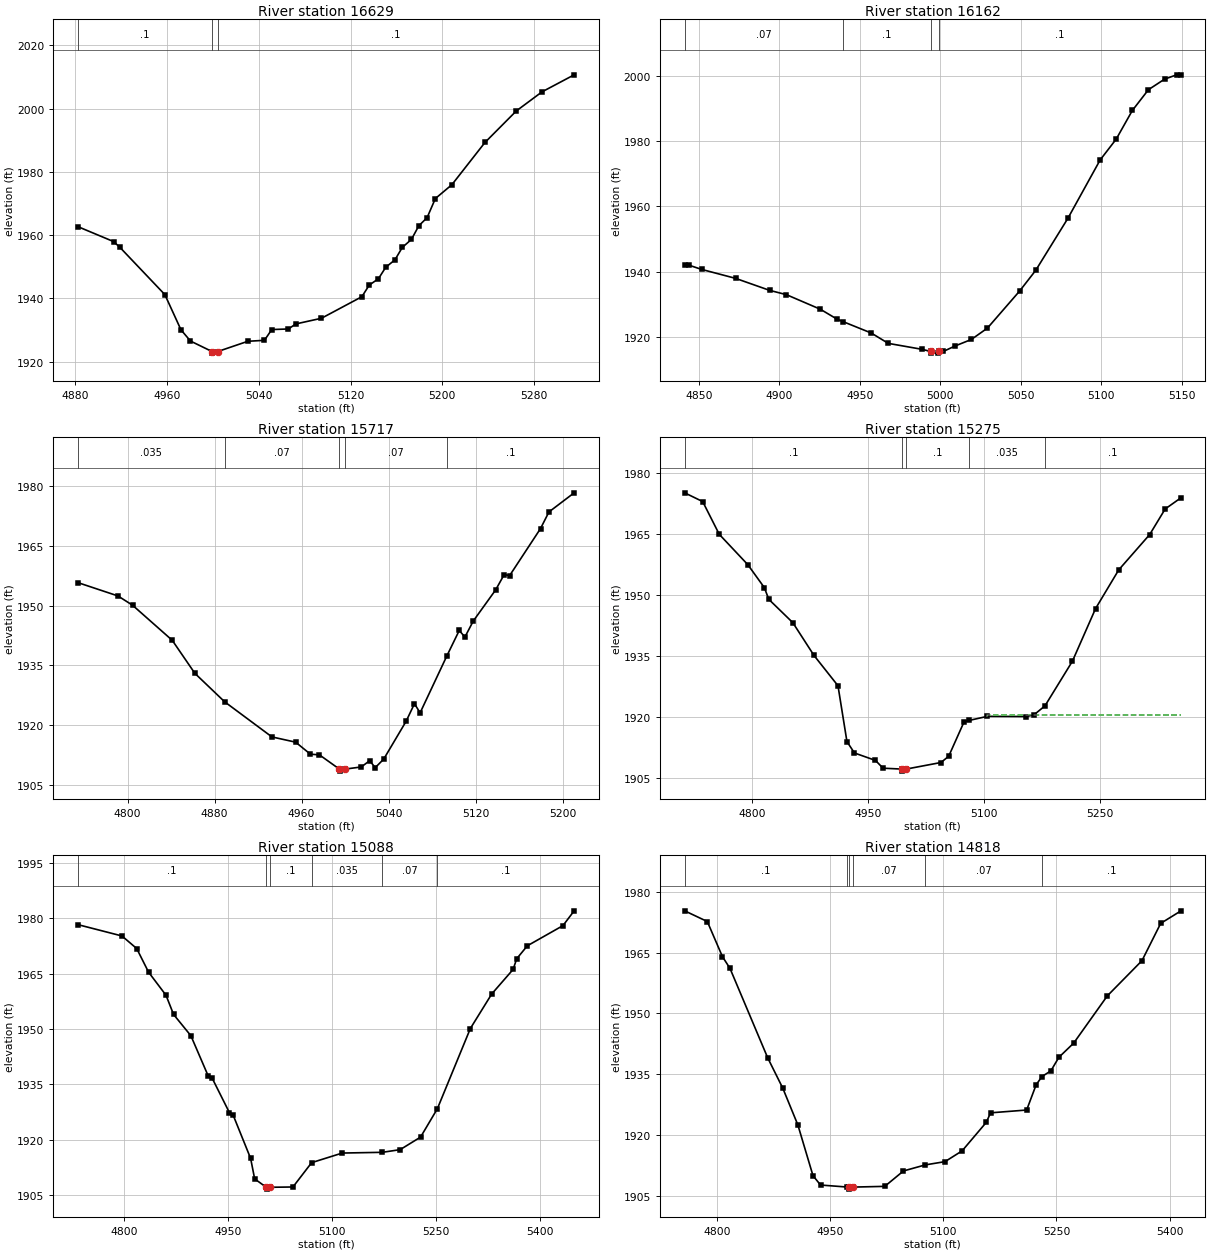
Type RM Length L Ch R = 1 ,16629   ,467,467,467
BEGIN DESCRIPTION:
West Goat Creek 36.0
END DESCRIPTION:
XS GIS Cut Line= 3
      1896525.01     13965975.01        1896425.       13965925.
      1896224.99     13965674.98
#Sta/Elev= 30
  4882.8 1962.63  4913.6 1957.95  4919.2 1956.09  4958.3 1941.16  4972.3 1930.04
  4980.6 1926.48  4999.4 1923.16  4999.7 1922.66  5004.3 1923.16  5030.6 1926.41
    5045 1926.71  5051.4 1930.12  5065.9  1930.3  5072.3 1931.89  5094.7 1933.69
  5129.9 1940.51  5136.3 1944.18  5144.3 1946.19  5150.7 1949.83  5158.7 1952.17
  5165.1  1956.1  5173.1 1958.65  5179.5 1962.96  5186.7 1965.51  5193.9 1971.56
  5208.3 1975.94  5237.1  1989.3  5264.4 1999.27  5286.8 2005.31  5314.8  2010.7
#Mann= 3 ,-1 , 0
  4882.8      .1       0  4999.4     .05       0  5004.3      .1       0
Bank Sta=4999.4,5004.3
XS Rating Curve= 0 ,0
Exp/Cntr=0.3,0.1

Type RM Length L Ch R = 1 ,16162   ,445,445,445
BEGIN DESCRIPTION:
West Goat Creek 35.0
END DESCRIPTION:
XS GIS Cut Line= 3
      1896674.99     13965674.96        1896625.       13965525.
        1896625.     13965374.97
#Sta/Elev= 30
  4841.2 1942.06  4843.8 1942.06  4851.7 1940.76  4872.8 1938.02  4893.9 1934.36
  4904.4 1933.03  4925.5 1928.57    4936  1925.5  4939.6 1924.78  4957.1  1921.3
  4967.7 1918.13  4988.7 1916.31  4994.1 1915.65  4994.5 1915.15  4998.7 1915.15
  4999.1 1915.65  5001.8 1915.65  5009.3 1917.36  5019.3 1919.33  5029.3 1922.81
  5049.3 1934.15  5059.3 1940.48  5079.3 1956.41  5099.3 1974.23  5109.3 1980.62
  5119.3 1989.36  5129.3 1995.72  5139.3 1998.94  5146.8 2000.27  5149.3 2000.27
#Mann= 4 ,-1 , 0
  4841.2     .07       0  4939.6      .1       0  4994.1     .05       0
  4999.1      .1       0
Bank Sta=4994.1,4999.1
XS Rating Curve= 0 ,0
Exp/Cntr=0.3,0.1

Type RM Length L Ch R = 1 ,15717   ,442,442,442
BEGIN DESCRIPTION:
West Goat Creek 34.0
END DESCRIPTION:
XS GIS Cut Line= 3
      1896824.97     13965875.03        1896975.       13965675.
        1896925.       13965475.
#Sta/Elev= 30
  4754.5 1955.75    4791 1952.43  4804.5 1950.09    4841 1941.27  4861.8 1932.97
  4889.2 1925.81  4932.7 1916.98  4954.5 1915.66  4968.1 1912.64  4976.4 1912.47
  4994.8 1908.88  4995.2 1908.38  4999.8 1908.88  5014.9 1909.43  5022.6 1911.01
  5027.7 1909.26  5035.5 1911.39  5056.1  1920.9  5063.8 1925.33    5069 1923.04
  5093.4 1937.23    5105 1943.75  5110.2 1942.09  5117.9 1946.12  5138.5 1953.95
  5146.3 1957.78  5151.4 1957.56  5179.8 1969.38  5187.5 1973.54  5210.7 1978.35
#Mann= 5 ,-1 , 0
  4754.5    .035       0  4889.2     .07       0  4994.8     .05       0
  4999.8     .07       0  5093.4      .1       0
Bank Sta=4994.8,4999.8
XS Rating Curve= 0 ,0
Exp/Cntr=0.3,0.1

Type RM Length L Ch R = 1 ,15275   ,187,187,187
BEGIN DESCRIPTION:
West Goat Creek 33.0
END DESCRIPTION:
XS GIS Cut Line= 3
        1897475.       13966025.        1897325.       13965775.
        1897325.     13965425.05
#Sta/Elev= 30
  4712.8 1975.07  4736.1 1972.92  4757.5 1964.88  4794.4 1957.43  4815.8 1951.79
  4821.6  1948.9  4852.7 1943.16    4880 1935.13  4911.1 1927.66  4922.7 1913.93
  4932.4 1911.14  4959.6 1909.31  4969.4  1907.4    4994 1907.18  4994.4 1906.68
  4999.2 1907.18  5044.3  1908.8  5054.3 1910.33  5074.3 1918.84  5080.5 1919.13
  5104.3 1920.14  5154.3  1920.1  5164.3 1920.47  5178.8 1922.71  5214.3 1933.68
  5244.3 1946.63  5274.3 1956.15  5314.3 1964.82  5334.3  1971.1  5354.3 1973.79
#Mann= 5 ,-1 , 0
  4712.8      .1       0    4994     .05       0  4999.2      .1       0
  5080.5    .035       0  5178.8      .1       0
#XS Ineff= 2 , 0
                         5103.36         1920.42
Permanent Ineff=
       F       F
Bank Sta=4994,4999.2
XS Rating Curve= 0 ,0
Exp/Cntr=0.3,0.1

Type RM Length L Ch R = 1 ,15088   ,270,270,270
BEGIN DESCRIPTION:
Mapping XS 56d2ab27
END DESCRIPTION:
XS GIS Cut Line= 3
      1897605.26     13966024.36      1897487.22     13965701.24
      1897400.79     13965339.22
#Sta/Elev= 30
  4733.2 1978.27  4796.4 1975.22  4817.7 1971.81  4834.8 1965.42    4860 1959.16
  4870.9 1953.97  4895.9 1948.21  4921.1 1937.23  4926.4  1936.8  4951.6 1927.36
    4957 1926.68  4982.2 1914.97    4988 1909.44  5004.8 1907.16  5005.2 1906.66
    5010 1907.16  5043.3 1907.24  5070.3 1913.83  5114.5 1916.43  5172.4 1916.63
  5198.1 1917.35  5227.6 1920.75  5251.9 1928.45  5299.5 1950.16  5330.4 1959.52
  5361.2 1966.15  5366.5 1969.07  5381.8 1972.56  5433.2 1978.02  5449.4 1982.03
#Mann= 6 ,-1 , 0
  4733.2      .1       0  5004.8     .05       0    5010      .1       0
  5070.3    .035       0  5172.4     .07       0  5251.9      .1       0
Bank Sta=5004.8,5010
XS Rating Curve= 0 ,0
Exp/Cntr=0.3,0.1

Type RM Length L Ch R = 1 ,14818   ,258,258,258
BEGIN DESCRIPTION:
West Goat Creek 32.0
END DESCRIPTION:
XS GIS Cut Line= 3
        1897725.     13965924.99        1897725.       13965675.
      1897581.14     13965294.15
#Sta/Elev= 30
  4757.4 1975.28  4787.4 1972.64  4807.4    1964  4817.4 1961.11  4867.4 1939.06
  4887.4 1931.58  4907.4 1922.51  4927.4 1910.03  4937.4 1907.72    4973 1907.22
  4974.8 1907.21  4975.2 1906.71    4980 1907.21  5022.5 1907.39  5047.3 1911.19
  5076.2 1912.68  5102.3 1913.48    5125 1916.14    5157 1923.16  5162.7 1925.51
  5210.5  1926.2  5223.1 1932.43  5230.8 1934.45  5242.6 1935.86  5253.3 1939.21
  5272.8 1942.68  5317.4 1954.33  5363.3    1963  5388.1 1972.19  5414.5 1975.22
#Mann= 6 ,-1 , 0
  4757.4      .1       0    4973     .07       0  4974.8     .05       0
    4980     .07       0  5076.2     .07       0  5230.8      .1       0
Bank Sta=4974.8,4980
XS Rating Curve= 0 ,0
Exp/Cntr=0.3,0.1

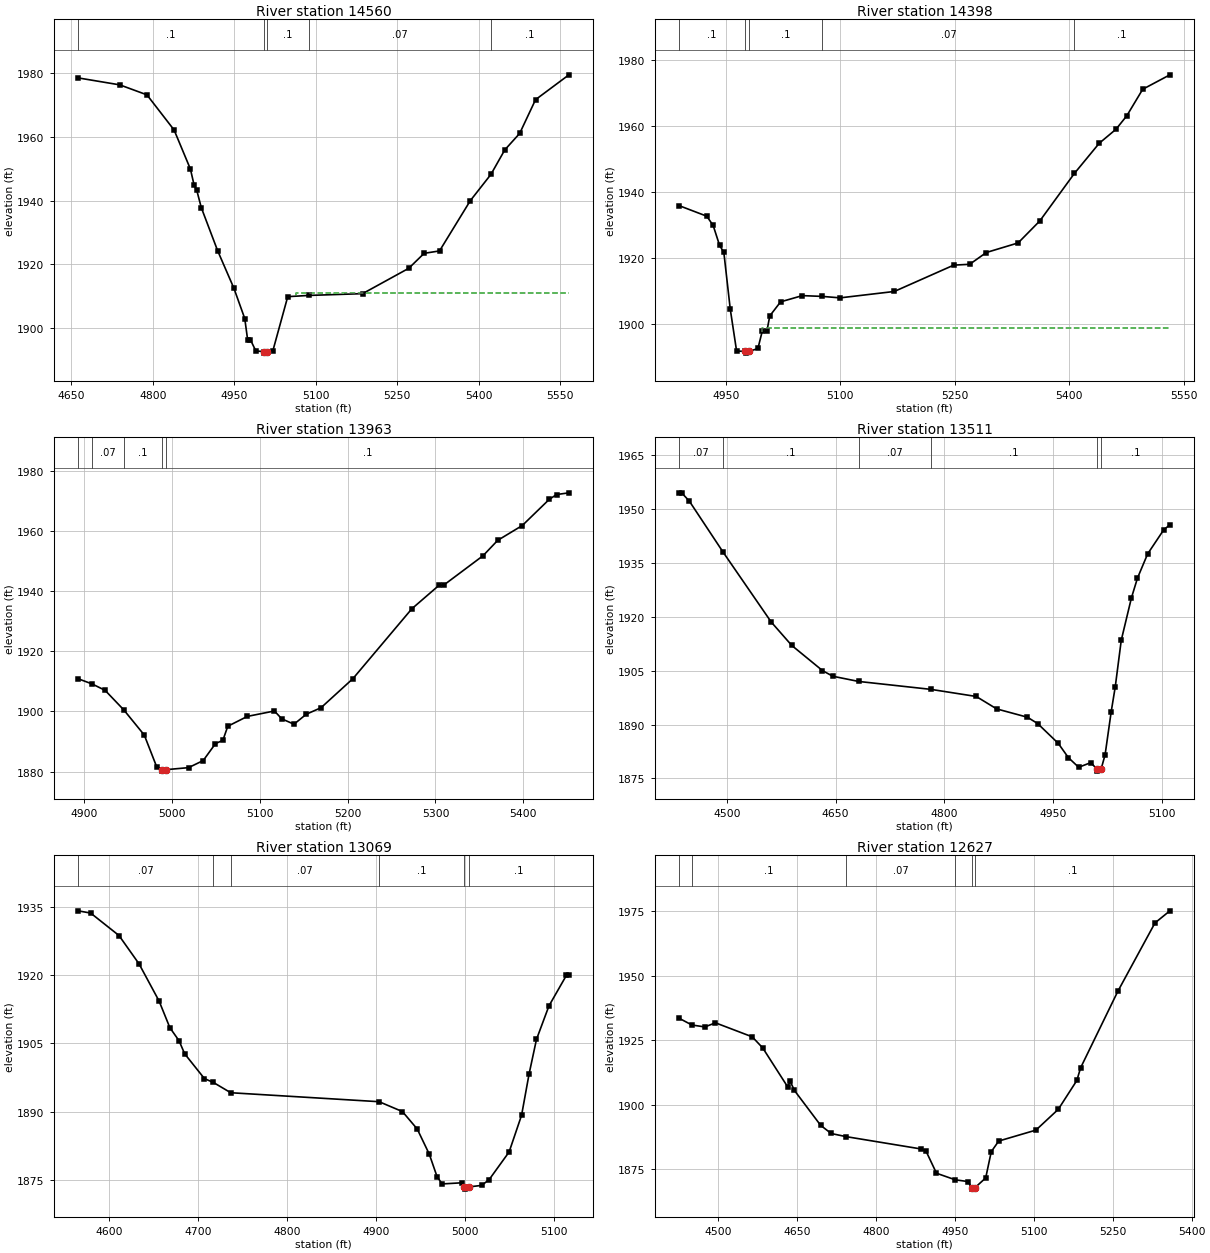
Type RM Length L Ch R = 1 ,14560   ,162,162,162
BEGIN DESCRIPTION:
Mapping XS b8365dc0
END DESCRIPTION:
XS GIS Cut Line= 4
      1897963.71     13966011.69      1897958.33     13965699.54
      1897920.92     13965550.22      1897618.66     13965234.53
#Sta/Elev= 30
  4662.5 1978.42  4739.2 1976.24  4789.2 1973.11  4839.2  1962.1  4869.2 1949.86
  4875.9 1944.93  4880.9 1943.21  4889.2  1937.8  4919.2 1924.33  4949.2 1912.55
  4969.2 1903.05  4974.5  1896.4  4979.6  1896.4  4989.7 1892.86  5004.5 1892.71
  5004.9 1892.21  5009.7 1892.71  5020.6 1892.74  5048.3  1909.9  5086.7 1910.28
  5186.1 1910.84    5271 1918.78  5299.3 1923.47  5327.6 1924.22  5384.2 1939.95
  5422.3 1948.22  5447.7 1955.87  5475.1 1961.03  5504.3  1971.6  5565.7 1979.38
#Mann= 5 ,-1 , 0
  4662.5      .1       0  5004.5     .05       0  5009.7      .1       0
  5086.7     .07       0  5422.3      .1       0
#XS Ineff= 2 , 0
                         5064.13         1911.05
Permanent Ineff=
       F       F
Bank Sta=5004.5,5009.7
XS Rating Curve= 0 ,0
Exp/Cntr=0.3,0.1

Type RM Length L Ch R = 1 ,14398   ,435,435,435
BEGIN DESCRIPTION:
West Goat Creek 31.0
END DESCRIPTION:
XS GIS Cut Line= 3
      1898174.98     13965624.99        1898075.       13965575.
      1897674.99     13965224.99
#Sta/Elev= 30
  4888.5 1935.86  4924.8 1932.65  4933.2 1929.84  4941.6  1923.8  4947.2 1921.67
  4955.6 1904.46  4963.9 1891.73  4975.3 1891.57  4975.7 1891.07  4980.5 1891.57
  4991.9  1892.5  4997.5 1897.69  5003.6 1897.69  5007.4 1902.37  5021.6 1906.64
  5050.1 1908.53  5076.5 1908.29  5099.5 1907.85  5170.6 1909.79  5248.5 1917.79
  5269.4 1918.04  5291.2 1921.62  5332.9 1924.53  5361.4 1931.23  5406.7 1945.65
  5439.2 1954.79  5461.1 1959.03  5475.3 1963.12  5496.2 1971.19  5531.8 1975.57
#Mann= 5 ,-1 , 0
  4888.5      .1       0  4975.3     .05       0  4980.5      .1       0
  5076.5     .07       0  5406.7      .1       0
#XS Ineff= 2 , 0
                         4997.31         1898.68
Permanent Ineff=
       F       F
Bank Sta=4975.3,4980.5
XS Rating Curve= 0 ,0
Exp/Cntr=0.3,0.1

Type RM Length L Ch R = 1 ,13963   ,452,452,452
BEGIN DESCRIPTION:
West Goat Creek 30.0
END DESCRIPTION:
XS GIS Cut Line= 3
      1898374.98     13965274.99        1898275.       13965225.
        1898075.       13964825.
#Sta/Elev= 30
    4893  1910.9  4908.7 1909.19  4923.7 1907.05  4945.1 1900.51  4968.4 1892.15
  4982.4 1881.66  4988.1 1880.64  4988.5 1880.14  4993.6 1880.64  5018.8  1881.3
  5035.5 1883.66  5049.5 1889.31  5057.9 1890.39  5063.5 1895.08  5085.8 1898.36
  5116.6 1900.16    5125 1897.54  5138.9 1895.76  5152.9 1899.08  5169.7 1901.25
    5206 1910.92  5273.1 1934.18  5303.9 1941.95  5309.4 1942.05  5354.2 1951.84
  5370.9 1956.96  5398.9  1961.9  5429.6  1970.6    5438 1972.21    5452 1972.78
#Mann= 5 ,-1 , 0
    4893      .1       0  4908.7     .07       0  4945.1      .1       0
  4988.1     .05       0  4993.6      .1       0
#XS Ineff= 2 , 0
                         5112.33         1899.74
Permanent Ineff=
       F       F
Bank Sta=4988.1,4993.6
XS Rating Curve= 0 ,0
Exp/Cntr=0.3,0.1

Type RM Length L Ch R = 1 ,13511   ,442,442,442
BEGIN DESCRIPTION:
West Goat Creek 29.0
END DESCRIPTION:
XS GIS Cut Line= 3
      1898825.03     13965225.03        1898425.       13964825.
      1898375.01     13964725.02
#Sta/Elev= 30
    4434  1954.5  4437.6  1954.5  4448.2 1952.19  4494.9 1937.96  4561.3 1918.52
  4589.6 1912.02    4632 1905.02  4646.2 1903.45  4681.9    1902  4781.5  1899.8
  4844.2 1897.82  4872.4 1894.36  4914.9 1892.04    4929 1890.28  4957.3  1884.8
  4971.4  1880.8  4985.6 1878.11  5002.5 1879.42  5010.9 1877.54  5011.3 1877.04
  5016.5 1877.54  5022.1 1881.62  5030.5 1893.58  5036.1 1900.51  5044.4 1913.48
  5058.4 1925.25  5066.8 1930.78  5080.8  1937.5  5103.1 1944.23  5111.5 1945.59
#Mann= 6 ,-1 , 0
    4434     .07       0  4494.9      .1       0  4681.9     .07       0
  4781.5      .1       0  5010.9     .05       0  5016.5      .1       0
Bank Sta=5010.9,5016.5
XS Rating Curve= 0 ,0
Exp/Cntr=0.3,0.1

Type RM Length L Ch R = 1 ,13069   ,442,442,442
BEGIN DESCRIPTION:
West Goat Creek 28.0
END DESCRIPTION:
XS GIS Cut Line= 3
      1898974.71     13964965.91        1898775.       13964575.
      1898724.99     13964474.98
#Sta/Elev= 30
  4565.6 1934.11  4579.7 1933.62  4611.5 1928.69    4634 1922.47  4656.5 1914.31
  4668.6 1908.46  4678.9 1905.59  4685.2 1902.73  4707.4 1897.28  4717.5 1896.43
  4736.9 1894.18  4903.4 1892.21  4929.6 1890.04  4946.2 1886.21  4959.7  1880.7
  4968.4 1875.78  4974.1 1874.16  4996.3 1874.41  4998.9 1873.52  4999.4 1873.02
  5004.6 1873.52  5018.5 1873.84  5026.9 1875.11  5049.3 1881.18  5063.3 1889.25
  5071.7  1898.3    5080 1905.88    5094 1913.24  5113.6 1919.95  5116.4 1919.95
#Mann= 6 ,-1 , 0
  4565.6     .07       0  4717.5      .1       0  4736.9     .07       0
  4903.4      .1       0  4998.9     .05       0  5004.6      .1       0
Bank Sta=4998.9,5004.6
XS Rating Curve= 0 ,0
Exp/Cntr=0.3,0.1

Type RM Length L Ch R = 1 ,12627   ,469,469,469
BEGIN DESCRIPTION:
West Goat Creek 27.0
END DESCRIPTION:
XS GIS Cut Line= 3
      1899117.19     13964904.12        1899125.       13964325.
      1898875.02     13964075.02
#Sta/Elev= 30
  4425.9 1933.62  4450.3 1930.99    4475 1930.24    4495 1931.84    4565  1926.4
    4585 1922.08  4632.1 1907.08  4637.1 1909.19    4645 1905.66    4695  1892.1
    4715 1888.94  4742.9 1887.74  4885.1 1882.97  4895.1 1882.16  4915.1 1873.54
  4950.8 1870.99  4975.1 1870.31  4982.2 1867.88  4982.7 1867.38  4987.9 1867.88
  5008.6 1871.72  5019.2 1881.91  5033.4 1886.02  5104.1 1890.26  5146.5  1898.3
  5181.8 1909.49  5188.9 1914.37  5259.6 1944.01  5330.3 1970.55  5358.6 1975.24
#Mann= 6 ,-1 , 0
  4425.9     .07       0  4450.3      .1       0  4742.9     .07       0
  4950.8      .1       0  4982.2     .05       0  4987.9      .1       0
Bank Sta=4982.2,4987.9
XS Rating Curve= 0 ,0
Exp/Cntr=0.3,0.1

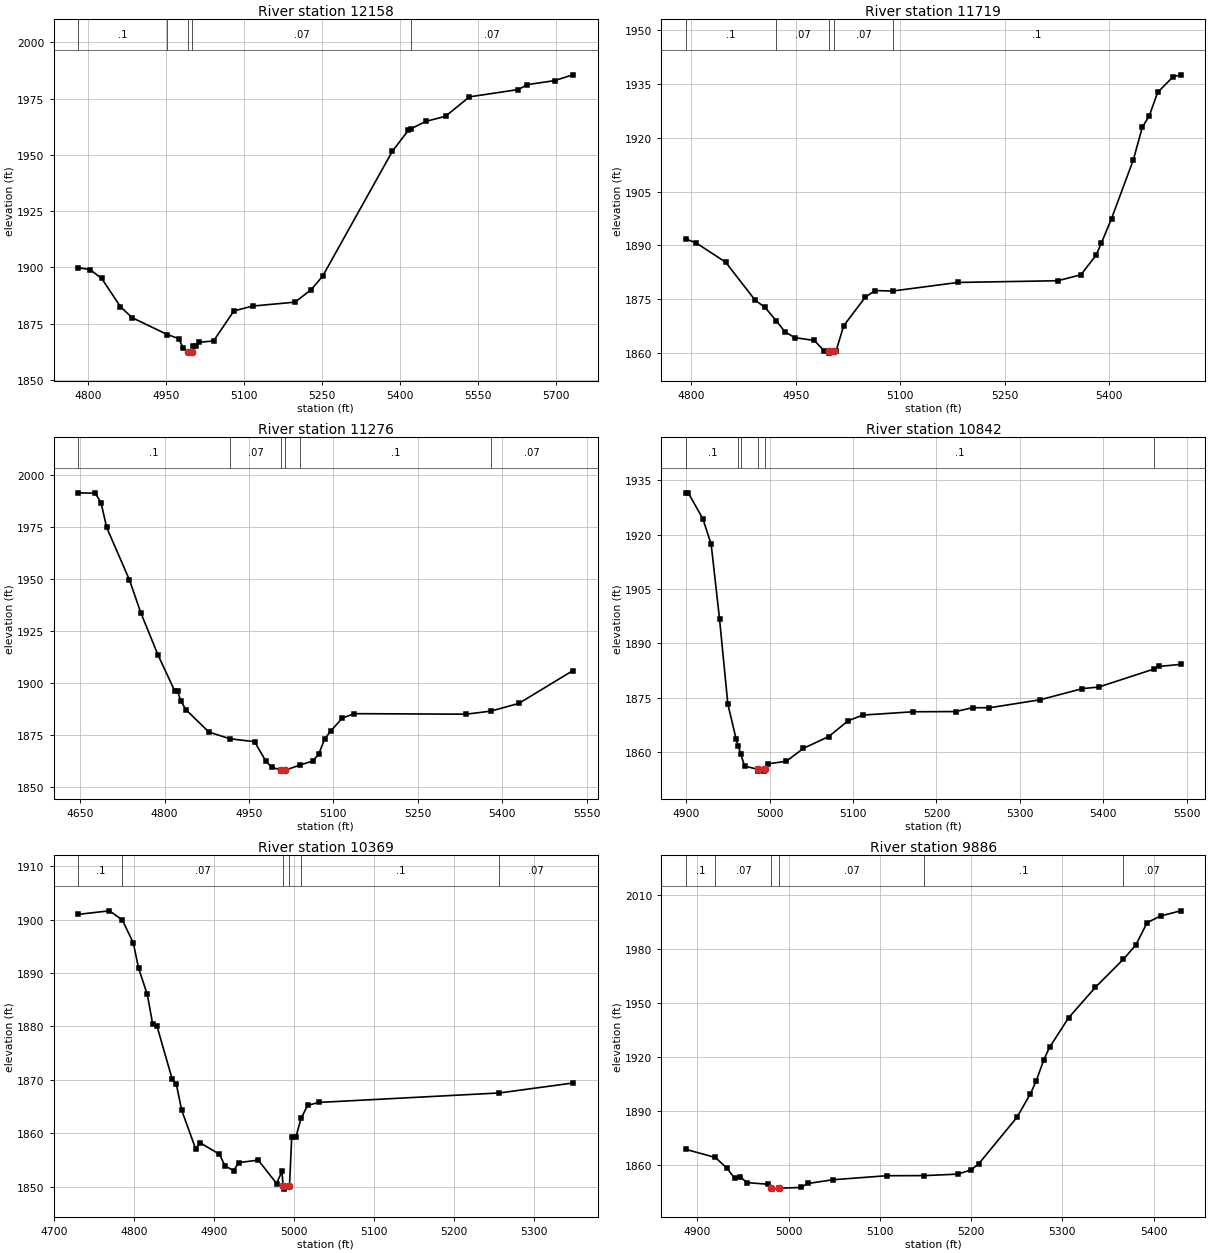
Type RM Length L Ch R = 1 ,12158   ,439,439,439
BEGIN DESCRIPTION:
West Goat Creek 26.0
END DESCRIPTION:
XS GIS Cut Line= 4
      1899675.03     13964175.02        1899475.       13964075.
        1899075.       13963875.      1898798.29     13963834.62
#Sta/Elev= 30
    4781 1899.89  4803.4 1899.05  4825.8 1895.18  4862.1 1882.57  4884.5 1877.68
  4952.2  1870.2  4973.9  1868.4  4982.3 1864.36  4992.4 1862.44  4992.9 1861.94
  5000.1 1862.44  5001.9 1864.89  5007.4 1864.89    5013 1866.77    5041 1867.33
  5080.1 1880.69  5116.4 1882.85  5197.5 1884.58  5228.3 1890.06  5250.6 1896.08
  5384.8 1951.65  5415.5 1960.91  5421.3 1961.71  5449.1 1964.86  5486.9 1967.15
  5532.7 1975.76  5626.8 1979.01  5643.9 1981.18  5696.8 1982.99  5731.5 1985.55
#Mann= 5 ,-1 , 0
    4781      .1       0  4952.2     .07       0  4992.4     .05       0
  5000.1     .07       0  5421.3     .07       0
Bank Sta=4992.4,5000.1
XS Rating Curve= 0 ,0
Exp/Cntr=0.3,0.1

Type RM Length L Ch R = 1 ,11719   ,443,443,443
BEGIN DESCRIPTION:
West Goat Creek 25.0
END DESCRIPTION:
XS GIS Cut Line= 4
        1899925.       13963925.        1899775.       13963775.
        1899675.       13963725.      1899325.01       13963563.
#Sta/Elev= 30
  4792.9 1891.75    4807 1890.71  4849.5 1885.33  4891.9 1874.72    4906 1872.73
  4922.2 1868.99  4934.3 1865.99  4948.5  1864.3  4976.7 1863.52  4990.9 1860.63
  4997.6 1860.48  4998.1 1859.98  5005.4 1860.48  5007.8 1860.48    5019 1867.61
  5049.8 1875.53  5063.7  1877.4  5089.4 1877.29    5183 1879.67  5326.2 1880.15
  5359.3  1881.8  5381.3 1887.34  5388.7 1890.65  5403.3 1897.48  5434.5 1913.79
  5447.4 1922.89  5457.5 1926.13  5469.5 1932.64  5491.5 1936.95  5502.5 1937.51
#Mann= 5 ,-1 , 0
  4792.9      .1       0  4922.2     .07       0  4997.6     .05       0
  5005.4     .07       0  5089.4      .1       0
Bank Sta=4997.6,5005.4
XS Rating Curve= 0 ,0
Exp/Cntr=0.3,0.1

Type RM Length L Ch R = 1 ,11276   ,434,434,434
BEGIN DESCRIPTION:
West Goat Creek 24.0
END DESCRIPTION:
XS GIS Cut Line= 5
      1900425.03       13963525.        1900075.       13963475.
        1899925.       13963425.      1899679.83     13963349.73
      1899569.44     13963342.28
#Sta/Elev= 30
  4646.7 1991.48    4677 1991.29  4687.1 1986.74  4697.2 1974.82  4737.6 1949.63
  4757.8 1933.84  4788.2 1913.62  4818.5 1896.02  4823.5 1896.07  4828.6 1891.47
  4838.7 1887.01  4879.1  1876.4  4916.5 1873.21  4959.9 1871.84  4980.1 1862.47
  4990.2 1859.58  5006.9 1858.17  5007.4 1857.67  5014.8 1858.17  5040.4 1860.56
  5063.5 1862.54  5074.1 1865.93  5084.6 1873.15  5095.2  1876.9  5116.2 1883.25
  5137.3  1885.3  5336.2 1885.05  5379.7 1886.52  5429.7 1890.24  5525.5 1905.99
#Mann= 6 ,-1 , 0
  4646.7      .1       0  4916.5     .07       0  5006.9     .05       0
  5014.8     .07       0  5040.4      .1       0  5379.7     .07       0
Bank Sta=5006.9,5014.8
XS Rating Curve= 0 ,0
Exp/Cntr=0.3,0.1

Type RM Length L Ch R = 1 ,10842   ,473,473,473
BEGIN DESCRIPTION:
West Goat Creek 23.0
END DESCRIPTION:
XS GIS Cut Line= 3
      1900274.98       13963075.        1900175.       13963075.
      1899688.87     13963155.37
#Sta/Elev= 30
  4900.1 1931.57  4902.6 1931.57  4920.1 1924.43  4930.1 1917.34  4940.1 1896.78
  4950.1 1873.23  4960.1 1863.54  4962.7 1861.62  4965.4 1859.63  4970.1 1856.17
  4986.1 1855.28  4986.6 1854.78  4993.5 1854.78    4994 1855.28  4997.6 1856.77
  5020.3 1857.51  5040.6 1861.06    5071 1864.32  5094.2 1868.67  5111.6 1870.24
  5172.4 1871.16  5223.1 1871.21  5243.3 1872.29  5263.6 1872.26  5324.4 1874.47
  5375.1 1877.55  5394.4 1877.97  5460.9 1882.96  5466.3 1883.66  5492.8 1884.23
#Mann= 6 ,-1 , 0
  4900.1      .1       0  4962.7     .07       0  4965.4      .1       0
  4986.1     .05       0    4994      .1       0  5460.9     .07       0
Bank Sta=4986.1,4994
XS Rating Curve= 0 ,0
Exp/Cntr=0.3,0.1

Type RM Length L Ch R = 1 ,10369   ,483,483,483
BEGIN DESCRIPTION:
West Goat Creek 22.0
END DESCRIPTION:
XS GIS Cut Line= 3
        1900225.       13962775.        1899975.       13962675.
       1899638.8     13962766.56
#Sta/Elev= 30
  4730.3 1901.02  4769.3 1901.68  4785.3 1899.96    4799 1895.69  4805.7 1890.89
  4816.5 1886.01  4823.2 1880.49  4828.6 1880.08  4847.4 1870.24  4852.8 1869.16
  4859.5 1864.28    4877 1857.03  4882.4  1858.2  4906.7 1856.05  4913.4 1853.91
  4924.2 1852.97  4930.9 1854.48  4955.1 1854.95    4978 1850.56  4984.7 1852.85
  4986.2 1850.01  4986.7 1849.51  4994.1 1850.01  4996.9 1859.26  5002.1 1859.26
  5008.6 1862.77  5016.8 1865.21  5030.6 1865.76  5256.4 1867.54    5348  1869.4
#Mann= 6 ,-1 , 0
  4730.3      .1       0  4785.3     .07       0  4986.2     .05       0
  4994.1     .07       0  5008.6      .1       0  5256.4     .07       0
Bank Sta=4986.2,4994.1
XS Rating Curve= 0 ,0
Exp/Cntr=0.3,0.1

Type RM Length L Ch R = 1 ,9886    ,454,454,454
BEGIN DESCRIPTION:
West Goat Creek 21.0
END DESCRIPTION:
XS GIS Cut Line= 3
      1899975.02     13962275.01        1899875.       13962225.
      1899525.03     13961975.02
#Sta/Elev= 30
  4887.8 1868.45  4919.8    1864  4932.5 1858.01  4940.9 1852.43  4946.5 1853.25
  4954.9 1849.97  4977.3 1849.09  4981.3 1846.86  4981.8 1846.36    4990 1846.86
  5013.1 1847.28  5021.7 1849.53  5048.8 1851.59  5107.8 1853.83  5148.9 1853.88
  5185.2 1854.71  5199.9 1857.03  5208.5 1860.53  5250.3 1886.35  5265.1 1899.52
  5271.2 1906.33  5279.8 1918.51    5286 1925.28  5306.8 1941.71  5336.3 1958.75
  5366.7 1974.24  5380.6 1982.32  5392.9 1994.74  5407.6 1998.42  5429.7 2001.31
#Mann= 6 ,-1 , 0
  4887.8      .1       0  4919.8     .07       0  4981.3     .05       0
    4990     .07       0  5148.9      .1       0  5366.7     .07       0
Bank Sta=4981.3,4990
XS Rating Curve= 0 ,0
Exp/Cntr=0.3,0.1