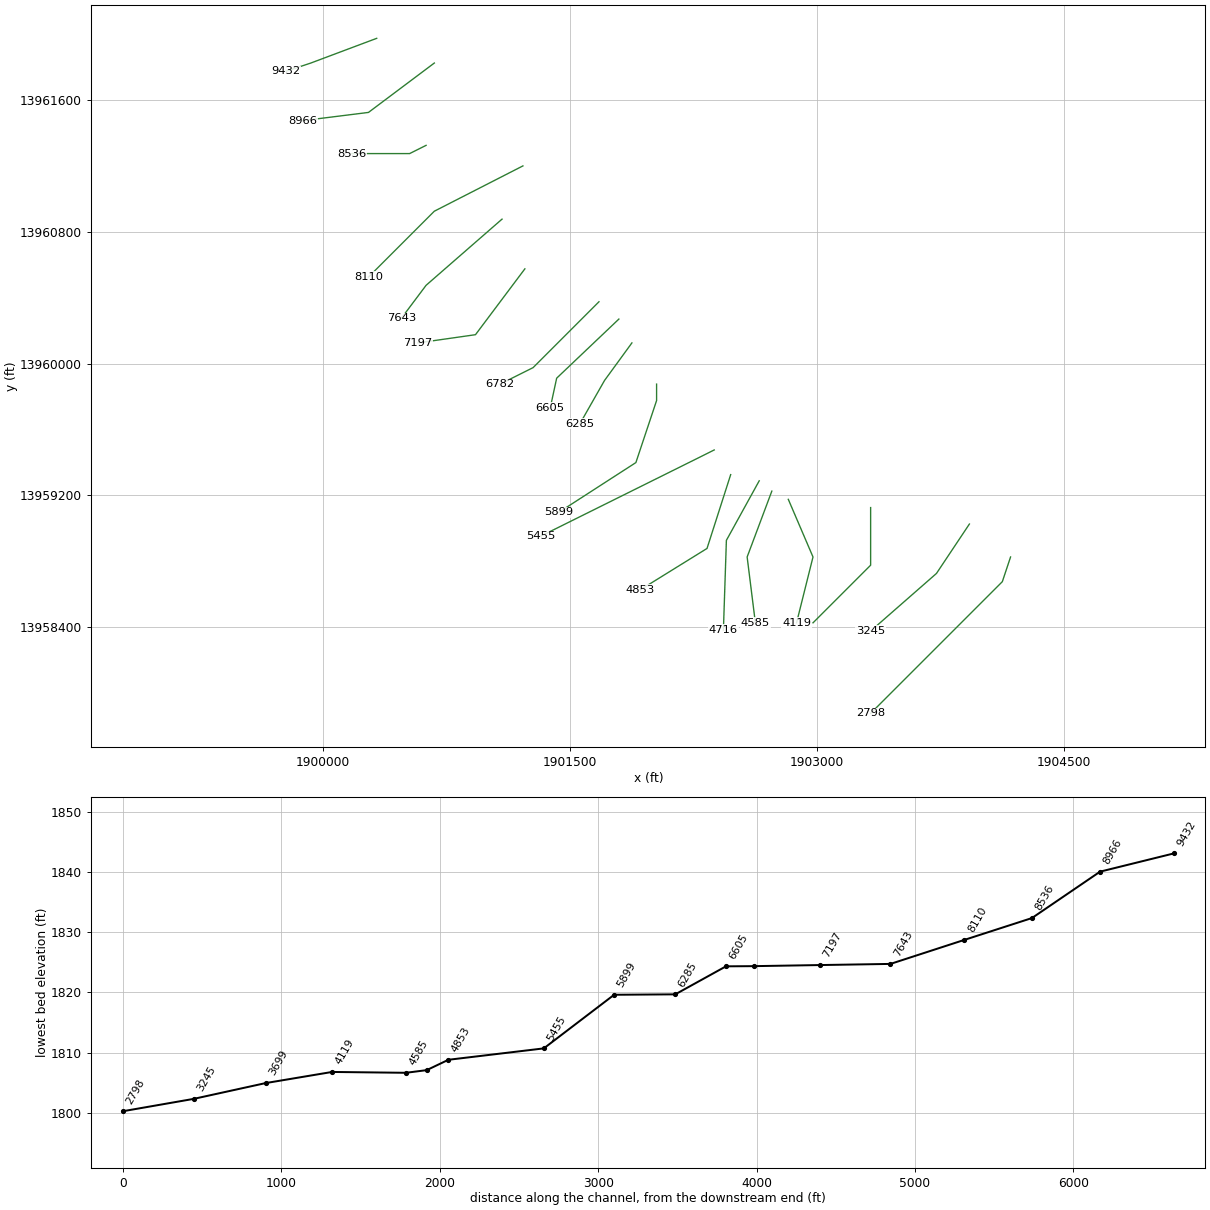
HEC-RAS study West Goat Creek.prj: West Goat Creek Base Level Engineering

--- West Goat Creek.g01 (geometry) --- (continued)

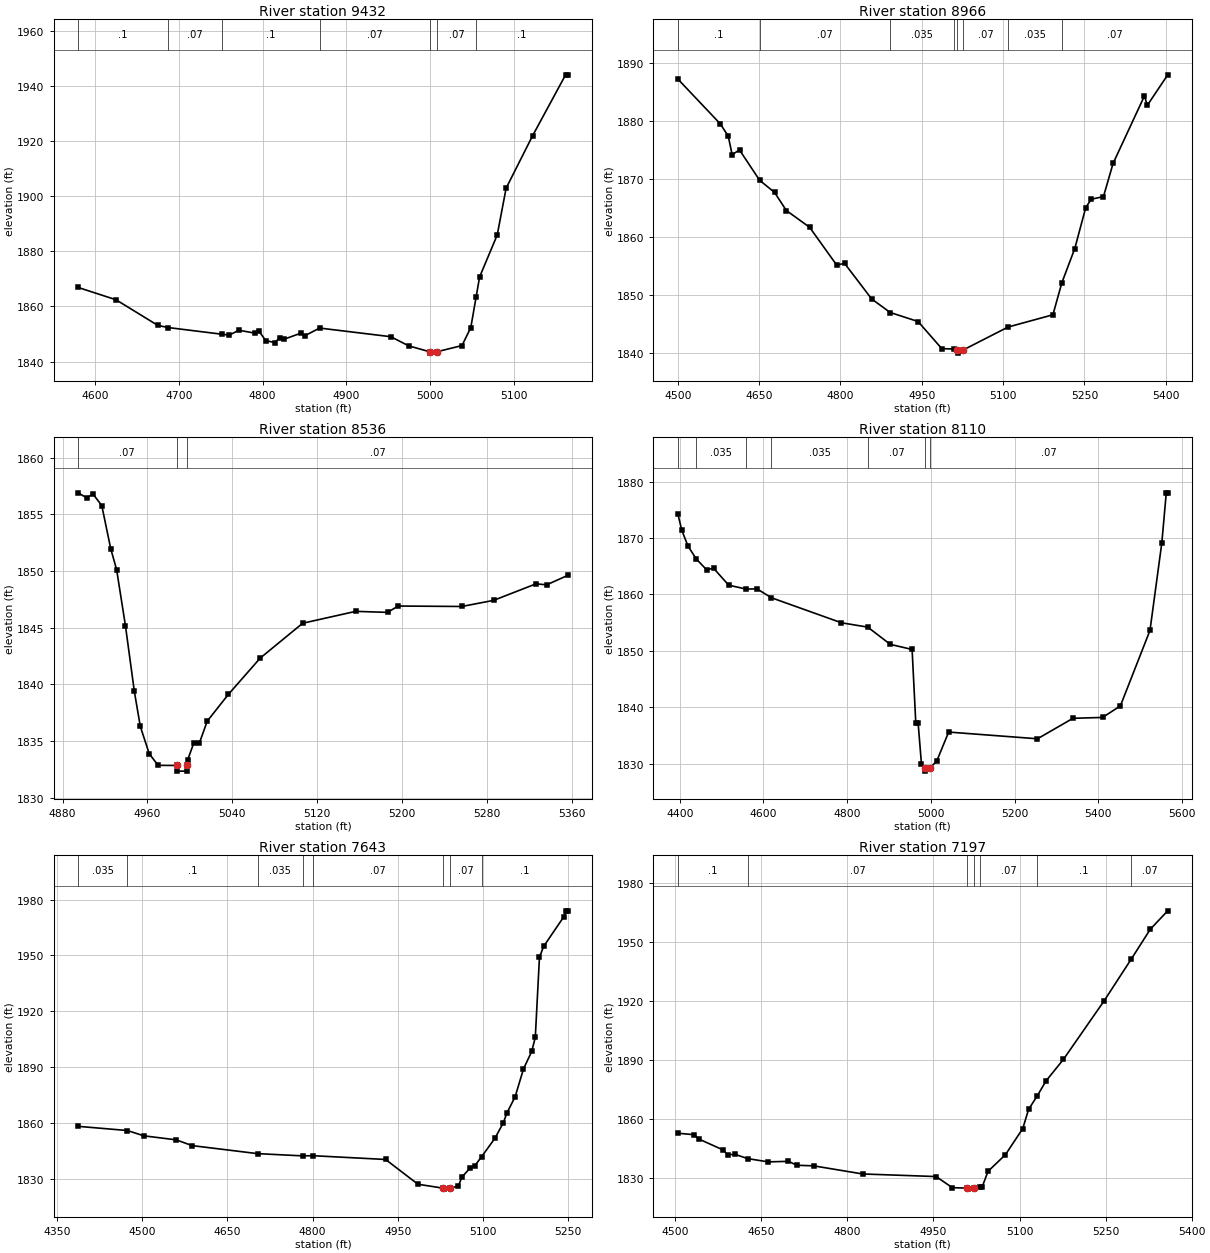
Type RM Length L Ch R = 1 ,9432    ,466,466,466
BEGIN DESCRIPTION:
West Goat Creek 20.0
END DESCRIPTION:
XS GIS Cut Line= 3
      1900325.04     13961975.01        1899925.       13961825.
      1899774.96     13961774.99
#Sta/Elev= 30
  4579.5 1866.91  4624.9 1862.43  4674.8 1853.13  4687.3 1852.34  4751.9  1849.9
  4760.2  1849.6  4771.8 1851.36  4790.5 1850.34  4795.8 1851.01  4803.8 1847.61
  4814.5  1846.9  4820.7 1848.63  4826.1 1848.14  4845.6 1850.28    4851 1849.44
  4868.2 1852.16  4953.3 1849.02  4974.7  1845.7  4999.7 1843.56  5000.2 1843.06
  5008.4 1843.56  5038.4 1845.81  5048.9 1852.35  5055.2 1863.35  5059.4 1870.68
  5080.5 1885.97  5091.1 1902.92  5122.7 1921.93  5162.2 1944.07  5164.9 1944.07
#Mann= 7 ,-1 , 0
  4579.5      .1       0  4687.3     .07       0  4751.9      .1       0
  4868.2     .07       0  4999.7     .05       0  5008.4     .07       0
  5055.2      .1       0
Bank Sta=4999.7,5008.4
XS Rating Curve= 0 ,0
Exp/Cntr=0.3,0.1

Type RM Length L Ch R = 1 ,8966    ,430,430,430
BEGIN DESCRIPTION:
West Goat Creek 19.0
END DESCRIPTION:
XS GIS Cut Line= 3
      1900675.03     13961825.03        1900275.       13961525.
      1899874.96     13961474.99
#Sta/Elev= 30
  4500.3 1887.18  4578.5 1879.48  4593.1 1877.37  4600.3 1874.19  4613.9 1874.99
  4651.1 1869.76  4678.5 1867.69  4700.3 1864.57  4743.1 1861.69  4793.1 1855.18
  4807.6 1855.48  4857.6 1849.35  4891.8 1847.02  4943.1 1845.47  4986.8 1840.81
  5010.2 1840.73  5015.6 1840.53  5016.1 1840.03  5025.4 1840.53  5109.1 1844.52
  5191.8 1846.63  5208.1  1852.1  5232.1 1858.03  5252.3 1865.08  5262.4 1866.51
    5285 1866.97  5302.7 1872.67  5360.6  1884.3  5365.7 1882.65  5403.5 1887.92
#Mann= 8 ,-1 , 0
  4500.3      .1       0  4651.1     .07       0  4891.8    .035       0
  5010.2     .07       0  5015.6     .05       0  5025.4     .07       0
  5109.1    .035       0  5208.1     .07       0
Bank Sta=5015.6,5025.4
XS Rating Curve= 0 ,0
Exp/Cntr=0.3,0.1

Type RM Length L Ch R = 1 ,8536    ,426,426,426
BEGIN DESCRIPTION:
West Goat Creek 18.0
END DESCRIPTION:
XS GIS Cut Line= 3
      1900625.01     13961325.01        1900525.       13961275.
      1900175.02       13961275.
#Sta/Elev= 30
  4894.6 1856.89    4903 1856.44  4908.6  1856.8    4917 1855.76  4925.4 1851.97
    4931  1850.1  4939.3 1845.16  4947.7 1839.36  4953.3 1836.28  4961.7 1833.87
  4970.1 1832.84  4987.5 1832.83    4988 1832.33  4996.9 1832.33  4997.4 1832.83
    4998 1833.33  5003.6 1834.78  5008.9 1834.78  5016.4 1836.74  5036.4 1839.11
  5066.4 1842.31  5106.4 1845.38  5156.4 1846.43  5186.4 1846.34  5196.4  1846.9
  5256.4 1846.86  5286.4  1847.4  5326.4 1848.86  5336.4 1848.77  5356.4 1849.61
#Mann= 3 ,-1 , 0
  4894.6     .07       0  4987.5     .05       0  4997.4     .07       0
Bank Sta=4987.5,4997.4
XS Rating Curve= 0 ,0
Exp/Cntr=0.3,0.1

Type RM Length L Ch R = 1 ,8110    ,467,467,467
BEGIN DESCRIPTION:
West Goat Creek 17.0
END DESCRIPTION:
XS GIS Cut Line= 3
      1901213.03     13961200.15        1900675.       13960925.
        1900275.       13960525.
#Sta/Elev= 30
  4395.7 1874.27  4404.7 1871.43  4419.8 1868.58  4439.6 1866.29  4464.2 1864.38
  4480.8 1864.66    4517 1861.65  4559.4 1860.95  4584.4 1861.01  4618.8 1859.43
  4786.2 1854.99  4849.2 1854.22  4902.9 1851.17  4955.1 1850.26  4963.9 1837.24
  4969.5 1837.22  4977.5 1829.92  4986.1 1829.21  4986.6 1828.71  4997.3 1829.21
  5014.2 1830.54  5042.4 1835.63  5254.6 1834.44  5339.4 1838.07  5410.1 1838.22
  5452.6 1840.27  5523.3 1853.64  5551.6 1869.16  5562.2 1878.01  5565.7 1878.01
#Mann= 7 ,-1 , 0
  4395.7      .1       0  4439.6    .035       0  4559.4     .07       0
  4618.8    .035       0  4849.2     .07       0  4986.1     .05       0
  4997.3     .07       0
Bank Sta=4986.1,4997.3
XS Rating Curve= 0 ,0
Exp/Cntr=0.3,0.1

Type RM Length L Ch R = 1 ,7643    ,446,446,446
BEGIN DESCRIPTION:
West Goat Creek 16.0
END DESCRIPTION:
XS GIS Cut Line= 3
      1901086.31     13960876.98        1900625.       13960475.
      1900474.99     13960274.99
#Sta/Elev= 30
  4387.4 1858.39  4474.2 1856.14  4503.2  1853.3  4560.2 1851.14  4588.1 1848.06
  4703.2 1843.75  4782.7 1842.55  4801.1 1842.64  4928.6 1840.62  4985.5 1827.34
  5030.1 1825.22  5030.6 1824.72  5041.3 1825.22  5056.6 1826.37  5062.8 1831.14
  5077.4 1836.08  5085.7 1837.32  5097.5  1842.1  5121.2  1852.1  5135.7 1860.28
    5142 1865.51  5156.6 1874.32  5171.2 1889.15  5185.7 1898.55    5192 1906.11
  5199.3 1948.99  5206.6 1954.83    5242 1970.69  5246.2 1973.94  5249.3 1973.94
#Mann= 8 ,-1 , 0
  4387.4    .035       0  4474.2      .1       0  4703.2    .035       0
  4782.7      .1       0  4801.1     .07       0  5030.1     .05       0
  5041.3     .07       0  5097.5      .1       0
Bank Sta=5030.1,5041.3
XS Rating Curve= 0 ,0
Exp/Cntr=0.3,0.1

Type RM Length L Ch R = 1 ,7197    ,415,415,415
BEGIN DESCRIPTION:
West Goat Creek 15.0
END DESCRIPTION:
XS GIS Cut Line= 3
      1901225.02     13960575.02        1900925.       13960175.
      1900574.98       13960125.
#Sta/Elev= 30
  4504.7 1852.87  4532.9 1852.13  4541.2 1849.92  4582.9 1844.48  4591.2 1842.04
  4604.7 1842.13    4626 1840.02    4662 1838.35  4697.4 1838.62    4712 1836.63
  4741.2 1836.34  4826.6 1832.22  4954.7  1830.9  4982.9 1825.28  5009.2 1825.03
  5009.7 1824.53  5020.4 1825.03  5031.5 1825.49    5035 1825.68  5045.1 1833.55
  5075.4 1841.97  5105.7 1855.26  5115.8 1864.97  5130.6 1871.65  5146.2  1879.4
  5176.5  1890.3  5247.2  1919.9  5294.9 1941.24    5328 1956.35  5358.3 1965.64
#Mann= 7 ,-1 , 0
  4504.7      .1       0    4626     .07       0  5009.2     .05       0
  5020.4     .07       0  5031.5     .07       0  5130.6      .1       0
  5294.9     .07       0
Bank Sta=5009.2,5020.4
XS Rating Curve= 0 ,0
Exp/Cntr=0.3,0.1

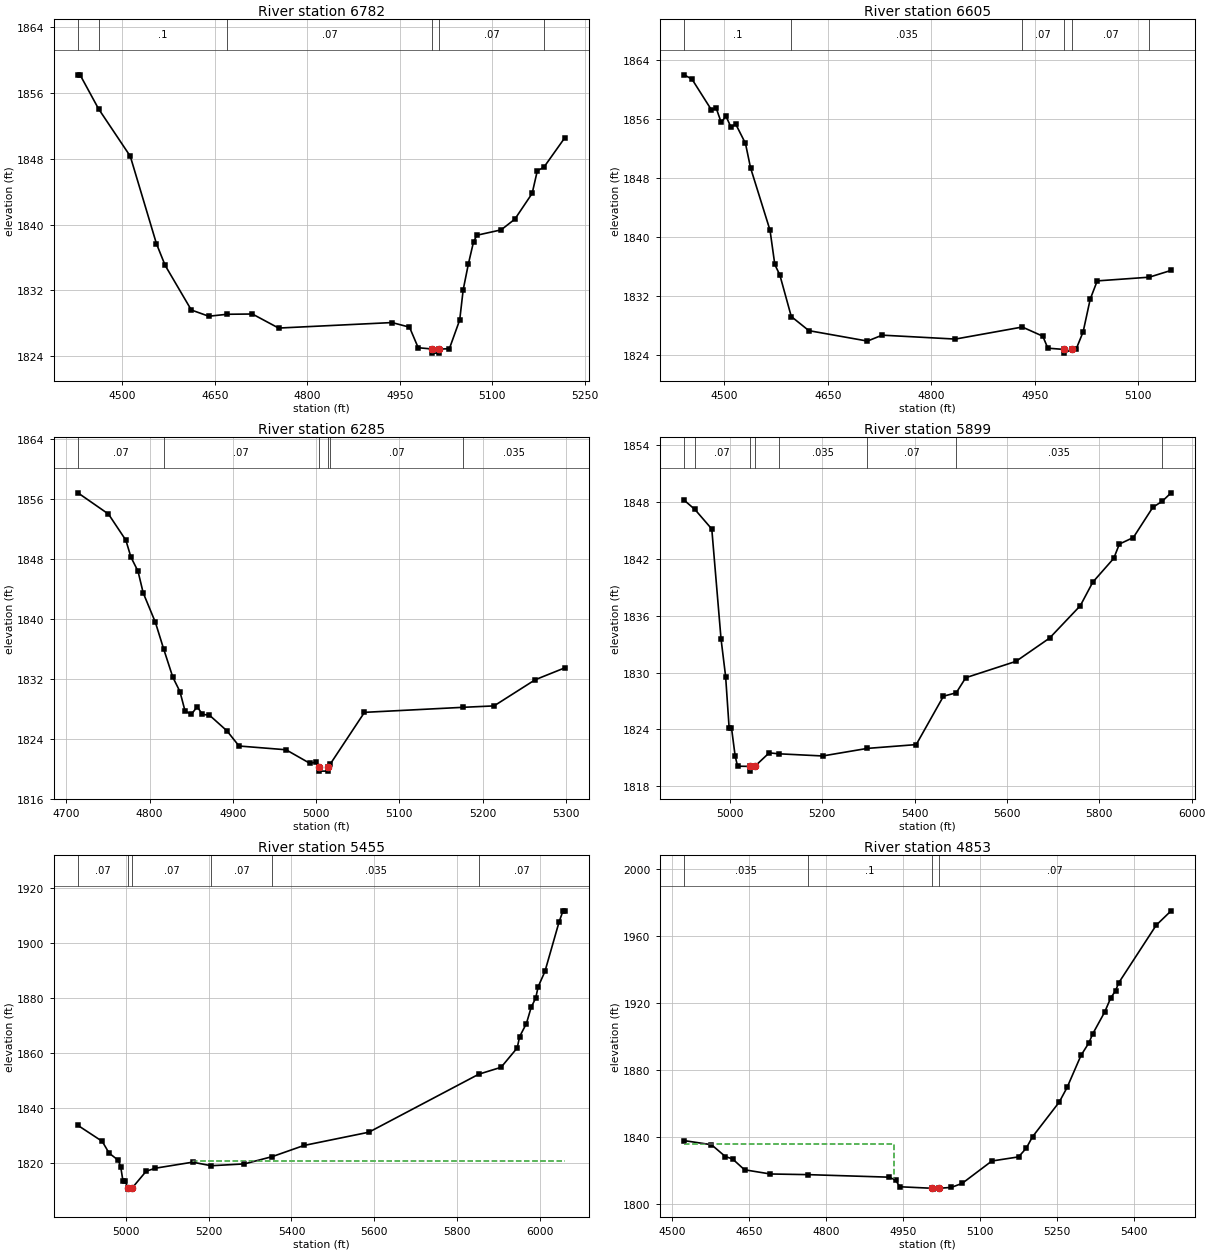
Type RM Length L Ch R = 1 ,6782    ,177,177,177
BEGIN DESCRIPTION:
West Goat Creek 14.0
END DESCRIPTION:
XS GIS Cut Line= 3
        1901675.       13960375.        1901275.       13959975.
      1901074.99       13959875.
#Sta/Elev= 30
  4428.2 1858.22  4431.7 1858.22  4461.6 1854.09  4513.1 1848.31  4555.5 1837.67
  4569.6 1835.03    4612  1829.6  4640.3 1828.84  4670.4 1829.08    4711 1829.11
  4753.5  1827.4  4937.3 1828.07  4965.6 1827.51  4979.7 1825.01  5002.3 1824.85
  5002.8 1824.35    5013 1824.35  5013.5 1824.85  5030.2 1824.88    5047 1828.39
  5052.6 1832.05    5061 1835.19  5069.4  1837.9  5074.9  1838.7  5114.1 1839.35
  5136.4 1840.66  5164.4 1843.79  5172.8 1846.56  5183.2 1846.95  5217.5 1850.58
#Mann= 6 ,-1 , 0
  4428.2     .07       0  4461.6      .1       0  4670.4     .07       0
  5002.3     .05       0  5013.5     .07       0  5183.2     .07       0
Bank Sta=5002.3,5013.5
XS Rating Curve= 0 ,0
Exp/Cntr=0.3,0.1

Type RM Length L Ch R = 1 ,6605    ,320,320,320
BEGIN DESCRIPTION:
West Goat Creek 13.1
END DESCRIPTION:
XS GIS Cut Line= 3
      1901796.03     13960269.93      1901418.06     13959910.85
      1901379.09     13959730.36
#Sta/Elev= 30
  4441.5 1861.96  4452.9 1861.38  4481.2 1857.21  4488.1 1857.45  4495.3 1855.52
  4502.2 1856.37  4509.5 1854.88  4516.4 1855.29  4530.5 1852.68  4537.8  1849.4
  4566.1 1840.93    4573 1836.31  4580.3 1834.89  4596.9 1829.27  4622.4 1827.36
  4707.3 1825.95  4728.7 1826.75  4834.7 1826.22  4931.8 1827.85  4961.5 1826.61
  4968.8 1824.99  4992.1 1824.82  4992.6 1824.32  5003.3 1824.82  5009.8 1824.85
    5020 1827.21  5030.2 1831.61  5040.4 1834.09  5115.8 1834.59  5147.5 1835.51
#Mann= 6 ,-1 , 0
  4441.5      .1       0  4596.9    .035       0  4931.8     .07       0
  4992.1     .05       0  5003.3     .07       0  5115.8    .035       0
Bank Sta=4992.1,5003.3
XS Rating Curve= 0 ,0
Exp/Cntr=0.3,0.1

Type RM Length L Ch R = 1 ,6285    ,386,386,386
BEGIN DESCRIPTION:
West Goat Creek 13.0
END DESCRIPTION:
XS GIS Cut Line= 3
        1901875.       13960125.      1901708.72     13959896.82
      1901559.09     13959633.97
#Sta/Elev= 30
    4714 1856.79  4750.7 1853.96  4771.6 1850.47  4777.7 1848.21  4786.2 1846.33
  4792.4 1843.45  4807.1  1839.5    4817 1835.96    4828 1832.19  4836.5 1830.29
  4842.6 1827.71  4850.1 1827.23  4857.3 1828.26  4863.5 1827.24    4872 1827.13
  4892.9 1825.05  4907.5 1823.02  4963.9 1822.52  4992.4 1820.72  5000.3 1820.87
  5003.4 1820.17  5003.9 1819.67  5014.3 1819.67  5014.8 1820.17  5016.9 1820.59
  5058.1 1827.51  5176.2 1828.18  5213.7 1828.37  5263.1 1831.86  5298.8 1833.45
#Mann= 6 ,-1 , 0
    4714     .07       0    4817     .07       0  5003.4     .05       0
  5014.8     .07       0  5016.9     .07       0  5176.2    .035       0
Bank Sta=5003.4,5014.8
XS Rating Curve= 0 ,0
Exp/Cntr=0.3,0.1

Type RM Length L Ch R = 1 ,5899    ,444,444,444
BEGIN DESCRIPTION:
West Goat Creek 12.0
END DESCRIPTION:
XS GIS Cut Line= 4
        1902025.     13959874.97        1902025.       13959775.
      1901899.21     13959398.22      1901430.79     13959095.91
#Sta/Elev= 30
  4900.8 1848.21  4924.3 1847.22  4960.8 1845.16  4980.8 1833.57  4990.8 1829.57
  4998.3  1824.2  5003.4  1824.2  5011.3 1821.23  5016.6 1820.12  5042.5  1820.1
    5043  1819.6  5053.9  1820.1  5085.1 1821.53  5105.7 1821.43  5200.9  1821.2
  5297.7    1822  5403.5  1822.4  5462.5 1827.51  5490.2 1827.87  5510.7 1829.46
  5619.6 1831.19  5692.2 1833.64  5758.8 1837.06  5785.9 1839.55  5831.4 1842.07
  5843.4 1843.57  5873.7 1844.26  5915.9 1847.45  5936.3 1848.09  5955.5 1848.98
#Mann= 8 ,-1 , 0
  4900.8    .035       0  4924.3     .07       0  5042.5     .05       0
  5053.9     .07       0  5105.7    .035       0  5297.7     .07       0
  5490.2    .035       0  5936.3     .07       0
Bank Sta=5042.5,5053.9
XS Rating Curve= 0 ,0
Exp/Cntr=0.3,0.1

Type RM Length L Ch R = 1 ,5455    ,602,602,602
BEGIN DESCRIPTION:
West Goat Creek 11.0
END DESCRIPTION:
XS GIS Cut Line= 3
      1902374.98     13959474.99        1902275.       13959425.
      1901321.72     13958951.45
#Sta/Elev= 30
  4884.2 1833.83  4942.9 1828.04  4959.6 1823.76    4982 1821.14  4987.6 1818.77
  4993.2 1813.51  4998.8 1813.51  5004.2  1811.2  5004.7  1810.7  5015.7  1811.2
  5049.2 1817.21  5071.6  1818.3  5161.2 1820.48    5206 1819.19  5286.3 1819.85
  5353.9 1822.51  5430.1 1826.54  5586.9 1831.35  5852.4  1852.4  5906.2  1854.9
  5945.1 1861.91    5951 1866.03  5967.4 1870.79    5979 1876.71  5989.7 1879.96
  5995.8 1884.13  6012.1 1889.66  6046.2 1907.59  6055.8 1911.67  6060.4 1911.67
#Mann= 6 ,-1 , 0
  4884.2     .07       0  5004.2     .05       0  5015.7     .07       0
    5206     .07       0  5353.9    .035       0  5852.4     .07       0
#XS Ineff= 2 , 0
                         5160.99         1820.84
Permanent Ineff=
       F       F
Bank Sta=5004.2,5015.7
XS Rating Curve= 0 ,0
Exp/Cntr=0.3,0.1

Type RM Length L Ch R = 1 ,4853    ,137,137,137
BEGIN DESCRIPTION:
West Goat Creek 10.0
END DESCRIPTION:
XS GIS Cut Line= 3
      1902474.99     13959324.98      1902331.27     13958876.67
      1901924.99     13958624.99
#Sta/Elev= 30
    4523 1837.77  4576.4 1835.31  4603.3 1828.27  4617.5  1826.8  4640.7 1820.36
    4691 1817.85    4764 1817.46    4922 1815.95  4935.1 1814.25    4943 1810.22
  5006.9 1809.31  5007.4 1808.81  5018.9 1809.31  5043.4 1809.83  5064.6 1812.23
  5122.5 1825.59  5174.5 1828.05  5189.4 1833.17  5201.7 1840.05  5253.7 1860.72
  5269.1  1869.5  5296.2 1888.65  5311.6 1896.13  5318.8 1901.35  5342.3  1914.5
  5354.1 1922.93  5363.6 1927.28  5369.5 1931.87  5442.7 1966.34  5471.7 1974.91
#Mann= 4 ,-1 , 0
    4523    .035       0    4764      .1       0  5006.9     .05       0
  5018.9     .07       0
#XS Ineff= 2 , 0
         4931.39    1836
Permanent Ineff=
       F       F
Bank Sta=5006.9,5018.9
XS Rating Curve= 0 ,0
Exp/Cntr=0.3,0.1

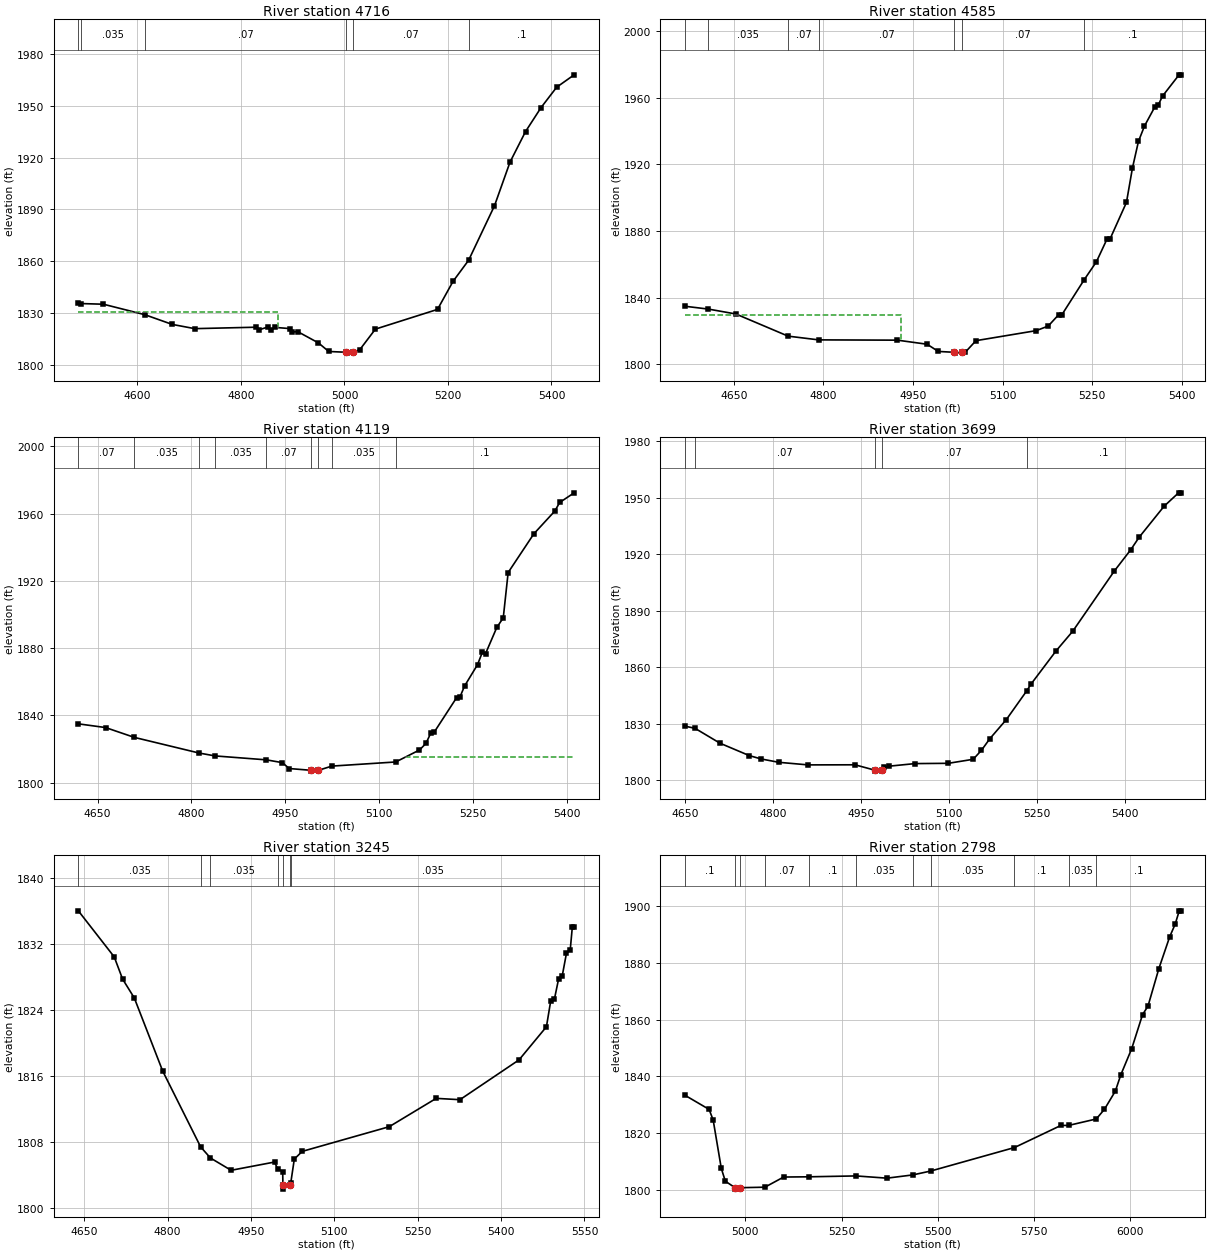
Type RM Length L Ch R = 1 ,4716    ,131,131,131
BEGIN DESCRIPTION:
Mapping XS 59d10ab2
END DESCRIPTION:
XS GIS Cut Line= 3
       1902648.3     13959287.48      1902448.94     13958925.81
      1902430.84     13958381.19
#Sta/Elev= 30
  4485.9 1835.78  4491.7  1835.7  4534.4 1835.32  4614.3 1829.28  4667.3 1823.67
  4710.8 1821.22  4830.1 1822.06  4835.8  1820.6  4851.8 1822.17  4857.5 1820.16
  4865.5 1821.95  4895.4 1821.24  4897.8 1819.27  4909.7 1819.51  4949.7    1813
  4969.7 1808.04  5003.7 1807.59  5004.2 1807.09  5015.8 1807.59  5029.8 1809.13
  5059.8 1820.95  5179.8 1832.33  5209.9 1848.56  5239.9  1860.7  5289.9 1892.17
  5319.9 1917.37  5349.9 1935.01  5379.9 1948.86    5410 1960.59  5443.8 1967.74
#Mann= 6 ,-1 , 0
  4485.9     .07       0  4491.7    .035       0  4614.3     .07       0
  5003.7     .05       0  5015.8     .07       0  5239.9      .1       0
#XS Ineff= 2 , 0
         4870.85 1830.79
Permanent Ineff=
       F       F
Bank Sta=5003.7,5015.8
XS Rating Curve= 0 ,0
Exp/Cntr=0.3,0.1

Type RM Length L Ch R = 1 ,4585    ,466,466,466
BEGIN DESCRIPTION:
West Goat Creek 9.0
END DESCRIPTION:
XS GIS Cut Line= 3
      1902724.98     13959224.96        1902575.       13958825.
        1902625.     13958424.97
#Sta/Elev= 30
  4567.9 1834.79  4607.3 1833.08  4653.3 1830.15  4740.9 1816.84  4792.1  1814.6
  4923.9 1814.43  4973.7 1811.98  4992.4 1807.66  5019.2 1807.15  5019.7 1806.65
  5031.3 1807.15  5037.9 1807.32  5055.5 1814.13  5156.3 1820.14  5176.5 1822.91
  5194.1 1829.76  5199.1 1829.54  5236.9 1850.79  5257.1 1861.41  5274.7 1874.92
  5279.8 1874.99  5307.5  1897.1  5317.5  1917.7  5327.6 1933.73  5337.7 1942.94
  5355.3 1954.59  5360.4 1955.29  5367.9 1960.89  5395.6 1973.64  5398.2 1973.64
#Mann= 7 ,-1 , 0
  4567.9     .07       0  4607.3    .035       0  4740.9     .07       0
  4792.1     .07       0  5019.2     .05       0  5031.3     .07       0
  5236.9      .1       0
#XS Ineff= 2 , 0
         4929.15 1829.37
Permanent Ineff=
       F       F
Bank Sta=5019.2,5031.3
XS Rating Curve= 0 ,0
Exp/Cntr=0.3,0.1

Type RM Length L Ch R = 1 ,4119    ,420,420,420
BEGIN DESCRIPTION:
West Goat Creek 8.0
END DESCRIPTION:
XS GIS Cut Line= 3
      1902824.99     13959175.02        1902975.       13958825.
      1902875.01     13958425.02
#Sta/Elev= 30
  4619.1 1834.92  4662.6 1832.71  4708.8 1826.85  4812.4 1817.54  4837.8 1815.84
  4919.9  1813.5  4945.5 1811.83  4956.4 1808.33  4991.1 1807.29  4991.6 1806.79
  5003.2 1807.29  5024.6 1809.78  5126.8 1812.24  5164.8 1819.36  5175.1 1823.26
  5182.9 1829.44    5188 1829.77  5224.1 1850.45  5229.3 1850.71    5237 1857.48
  5257.6  1870.1  5265.3 1877.45  5270.5  1876.7  5288.5  1892.3  5298.8 1897.96
  5306.6 1924.92  5347.8 1947.99  5381.3 1961.51    5389 1966.59  5412.2 1972.34
#Mann= 9 ,-1 , 0
  4619.1     .07       0  4708.8    .035       0  4812.4     .07       0
  4837.8    .035       0  4919.9     .07       0  4991.1     .05       0
  5003.2     .07       0  5024.6    .035       0  5126.8      .1       0
#XS Ineff= 2 , 0
                         5141.87         1815.34
Permanent Ineff=
       F       F
Bank Sta=4991.1,5003.2
XS Rating Curve= 0 ,0
Exp/Cntr=0.3,0.1

Type RM Length L Ch R = 1 ,3699    ,454,454,454
BEGIN DESCRIPTION:
West Goat Creek 7.0
END DESCRIPTION:
XS GIS Cut Line= 3
        1903325.     13959124.96        1903325.       13958775.
      1902975.03     13958425.03
#Sta/Elev= 30
  4649.4 1828.83  4666.7 1827.69  4709.4 1819.76  4759.4 1813.17  4779.4 1811.41
  4809.4 1809.63  4859.4 1808.25  4939.4  1808.3  4973.3 1805.44  4973.8 1804.94
  4984.9 1804.94  4985.4 1805.44  4989.4 1806.99  4996.9 1807.55  5041.8 1808.94
  5098.4 1809.09  5140.8 1811.22  5154.9 1815.99  5169.1 1822.12  5197.4 1832.34
  5231.9 1847.49  5239.8 1851.32  5282.2 1868.84  5310.5 1879.22  5381.2 1911.13
  5409.5 1922.55  5423.6  1929.1  5466.1 1945.56  5490.8 1952.69  5494.3 1952.69
#Mann= 5 ,-1 , 0
  4649.4     .07       0  4666.7     .07       0  4973.3     .05       0
  4985.4     .07       0  5231.9      .1       0
Bank Sta=4973.3,4985.4
XS Rating Curve= 0 ,0
Exp/Cntr=0.3,0.1

Type RM Length L Ch R = 1 ,3245    ,447,447,447
BEGIN DESCRIPTION:
West Goat Creek 6.0
END DESCRIPTION:
XS GIS Cut Line= 3
      1903925.01     13959025.01        1903725.       13958725.
      1903324.98     13958374.98
#Sta/Elev= 30
  4639.3 1836.02  4703.9 1830.44  4718.9 1827.76    4740 1825.47    4791 1816.63
  4859.3 1807.44    4877 1806.09  4914.2  1804.6  4992.4  1805.6  4997.7 1804.79
    5007 1804.44  5007.4 1802.82  5007.9 1802.32  5019.9 1802.82  5021.6 1803.11
  5027.9 1805.96  5042.1 1806.89  5198.7 1809.88  5283.2 1813.31  5325.9 1813.15
  5432.2 1817.97  5481.5 1821.98  5489.1 1825.06  5495.8  1825.3  5503.4 1827.77
    5510 1828.17  5517.6  1830.9  5524.3 1831.27  5528.1 1834.06  5531.4 1834.06
#Mann= 7 ,-1 , 0
  4639.3    .035       0  4859.3     .07       0    4877    .035       0
  4997.7     .07       0  5007.4     .05       0  5019.9     .07       0
  5021.6    .035       0
Bank Sta=5007.4,5019.9
XS Rating Curve= 0 ,0
Exp/Cntr=0.3,0.1

Type RM Length L Ch R = 1 ,2798    ,465,465,465
BEGIN DESCRIPTION:
West Goat Creek 5.0
END DESCRIPTION:
XS GIS Cut Line= 3
      1904174.99     13958824.98        1904125.       13958675.
      1903324.98     13957874.98
#Sta/Elev= 30
  4842.3 1833.36  4905.5 1828.35  4916.1 1824.59  4937.2 1807.59  4947.7 1803.06
  4973.1 1800.77  4973.6 1800.27  4985.6 1800.77  5050.6 1800.95  5099.4 1804.53
  5164.7 1804.61  5287.6 1804.92  5368.1 1804.13    5435 1805.27  5481.5 1806.63
  5699.6 1814.91  5820.6 1822.71  5840.3  1822.7  5912.5 1824.98  5933.8 1828.41
  5962.1  1834.8  5976.2 1840.52  6004.5 1849.71  6032.8 1861.73  6046.9 1864.72
  6075.2 1877.94  6103.5 1889.19  6117.6 1893.57  6128.2 1898.28  6131.8 1898.28
#Mann= 11 ,-1 , 0
  4842.3      .1       0  4973.1     .05       0  4985.6      .1       0
  5050.6     .07       0  5164.7      .1       0  5287.6    .035       0
    5435      .1       0  5481.5    .035       0  5699.6      .1       0
  5840.3    .035       0  5912.5      .1       0
Bank Sta=4973.1,4985.6
XS Rating Curve= 0 ,0
Exp/Cntr=0.3,0.1