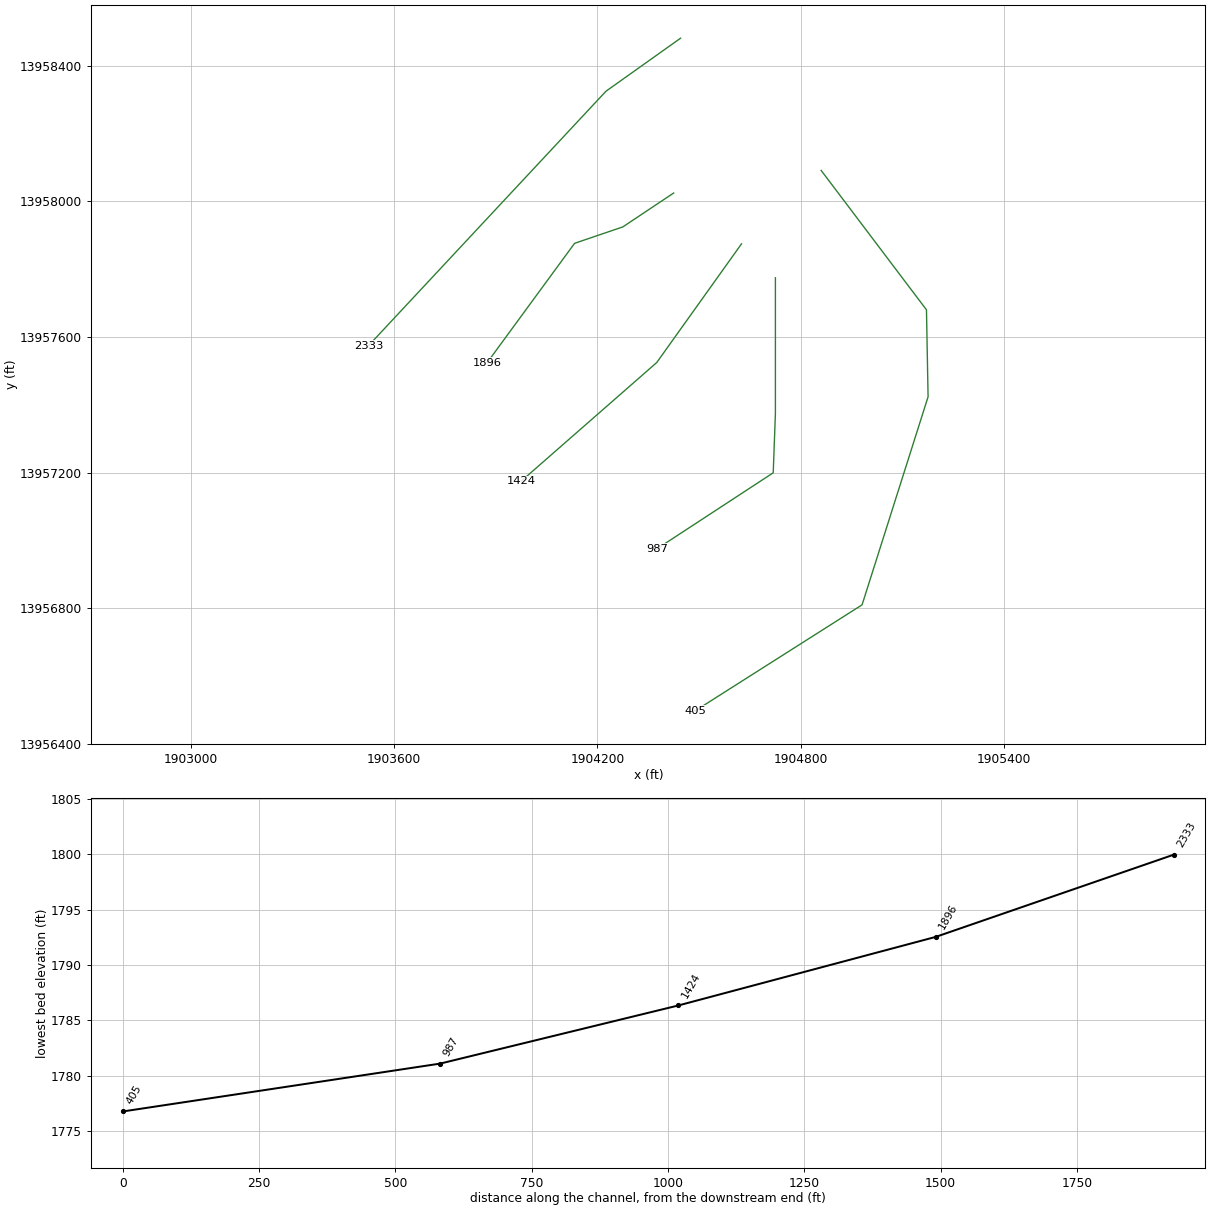
HEC-RAS study West Goat Creek.prj: West Goat Creek Base Level Engineering

--- West Goat Creek.g01 (geometry) --- (continued)

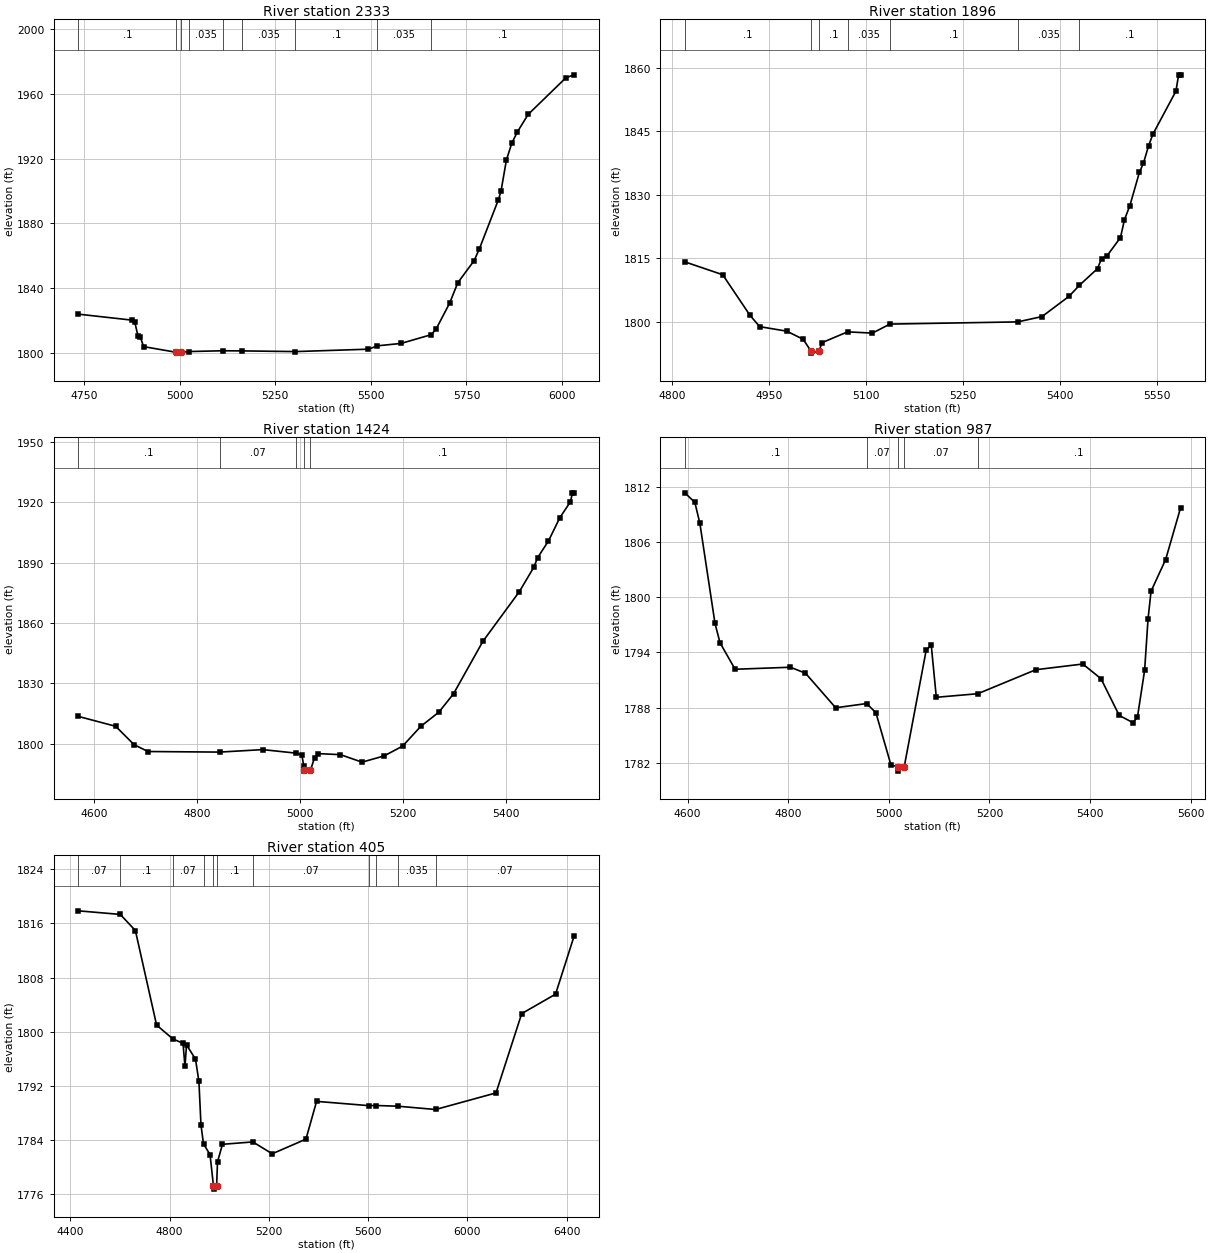
Type RM Length L Ch R = 1 ,2333    ,437,437,437
BEGIN DESCRIPTION:
West Goat Creek 4.0
END DESCRIPTION:
XS GIS Cut Line= 3
       1904445.2     13958481.55        1904225.       13958325.
      1903524.99     13957574.99
#Sta/Elev= 30
  4735.4 1824.01  4876.4  1820.3  4882.9 1819.12  4891.2 1810.67  4897.3    1810
    4906 1803.97  4991.9 1800.46  4992.4 1799.96  5004.5 1800.46  5023.6 1800.93
  5112.4 1801.42  5163.3 1801.34    5303 1800.91  5493.9  1802.4  5517.3 1804.47
  5578.9 1805.94  5658.1 1811.36  5670.7 1814.85  5705.9 1830.76  5727.4 1843.42
  5769.9 1856.99    5784 1864.46  5833.4  1894.6  5840.2 1899.78  5854.4 1919.12
  5868.6 1929.58  5882.7  1936.3  5911.1 1947.23  6010.2 1969.94  6031.5 1971.69
#Mann= 9 ,-1 , 0
  4735.4      .1       0  4991.9     .05       0  5004.5      .1       0
  5023.6    .035       0  5112.4      .1       0  5163.3    .035       0
    5303      .1       0  5517.3    .035       0  5658.1      .1       0
Bank Sta=4991.9,5004.5
XS Rating Curve= 0 ,0
Exp/Cntr=0.3,0.1

Type RM Length L Ch R = 1 ,1896    ,472,472,472
BEGIN DESCRIPTION:
West Goat Creek 3.0
END DESCRIPTION:
XS GIS Cut Line= 4
      1904424.98     13958024.99        1904275.       13957925.
      1904132.56     13957876.52        1903875.       13957525.
#Sta/Elev= 30
  4820.2 1814.09  4878.8 1811.05  4920.8  1801.5  4935.9 1798.79  4977.9 1797.71
  5003.1 1795.81  5015.2 1793.03  5015.7 1792.53  5027.9 1793.03  5032.1 1794.99
  5071.8 1797.55  5110.2 1797.26  5137.3 1799.39  5334.9 1799.91  5372.5 1801.17
  5414.2 1805.95  5430.3 1808.57  5458.2 1812.49  5464.4 1814.85  5472.8  1815.5
  5493.7 1819.82  5499.9 1824.05  5508.3  1827.4    5523 1835.25  5529.2 1837.39
  5537.1 1841.47  5543.9 1844.27  5579.4  1854.4  5583.6 1858.27  5586.7 1858.27
#Mann= 7 ,-1 , 0
  4820.2      .1       0  5015.2     .05       0  5027.9      .1       0
  5071.8    .035       0  5137.3      .1       0  5334.9    .035       0
  5430.3      .1       0
Bank Sta=5015.2,5027.9
XS Rating Curve= 0 ,0
Exp/Cntr=0.3,0.1

Type RM Length L Ch R = 1 ,1424    ,437,437,437
BEGIN DESCRIPTION:
West Goat Creek 2.0
END DESCRIPTION:
XS GIS Cut Line= 3
      1904624.98     13957874.97        1904375.       13957525.
      1903974.99     13957174.99
#Sta/Elev= 30
  4569.9 1813.54  4642.4 1808.61    4678 1799.48    4705 1796.08    4844  1795.8
  4927.5 1797.03  4992.2 1795.28  5003.3 1794.42  5007.1 1788.99  5007.4 1786.84
  5007.9 1786.34  5020.1 1786.84    5028 1792.97  5035.6 1795.04  5078.3 1794.52
    5120  1790.8  5162.8 1793.88  5198.8 1798.77  5233.9 1808.55  5269.1 1815.64
  5297.5 1824.75  5354.5 1850.83  5425.2 1875.52  5453.2 1887.64  5460.8 1892.47
  5481.7 1900.72  5503.5 1912.17  5524.4 1920.24  5528.2 1924.63  5531.5 1924.63
#Mann= 5 ,-1 , 0
  4569.9      .1       0    4844     .07       0  4992.2      .1       0
  5007.4     .05       0  5020.1      .1       0
Bank Sta=5007.4,5020.1
XS Rating Curve= 0 ,0
Exp/Cntr=0.3,0.1

Type RM Length L Ch R = 1 ,987     ,582,582,582
BEGIN DESCRIPTION:
West Goat Creek 1.0
END DESCRIPTION:
XS GIS Cut Line= 4
        1904725.       13957775.        1904725.       13957375.
      1904718.56     13957199.67      1904375.04     13956975.02
#Sta/Elev= 30
  4594.3 1811.36  4614.3 1810.32  4624.3 1808.03  4654.3 1797.17  4664.3 1795.05
  4694.3 1792.17  4804.3 1792.39  4834.3 1791.74  4894.3 1787.98  4955.9 1788.44
  4974.3 1787.44  5004.3 1781.74    5018 1781.59  5018.5 1781.09  5030.7 1781.59
  5074.4 1794.28  5084.4 1794.76  5094.4 1789.12  5176.9 1789.51  5292.3 1792.12
  5385.7 1792.74  5421.9 1791.14  5458.1 1787.15  5485.2 1786.37  5494.3 1786.95
  5508.6 1792.05  5515.4 1797.64  5521.4 1800.66  5550.4  1804.1  5580.2 1809.75
#Mann= 5 ,-1 , 0
  4594.3      .1       0  4955.9     .07       0    5018     .05       0
  5030.7     .07       0  5176.9      .1       0
Bank Sta=5018,5030.7
XS Rating Curve= 0 ,0
Exp/Cntr=0.3,0.1

Type RM Length L Ch R = 1 ,405     ,0,0,0
BEGIN DESCRIPTION:
West Goat Creek 0.0
END DESCRIPTION:
XS GIS Cut Line= 5
      1904859.95     13958091.55      1905170.66     13957680.38
       1905175.4     13957423.76      1904980.67      13956810.2
      1904489.21     13956498.16
#Sta/Elev= 30
  4432.4 1817.87  4601.4 1817.34  4662.3 1814.96  4747.7    1801  4813.3 1798.95
  4854.2 1798.31  4862.1 1794.89  4868.4 1798.06  4904.4 1795.98  4918.3 1792.67
  4926.6 1786.22  4936.8 1783.45  4963.1 1781.87  4976.8 1777.27  4977.3 1776.77
  4989.6 1777.27  4993.2  1780.8  5013.2 1783.39  5135.7 1783.74  5213.6 1781.99
  5349.6 1784.15  5392.4 1789.73  5602.9  1789.1  5631.3 1789.12  5718.5 1789.02
    5872 1788.53  6115.5 1790.98  6218.9 1802.69  6355.3 1805.56  6430.3 1814.17
#Mann= 11 ,-1 , 0
  4432.4     .07       0  4601.4      .1       0  4813.3     .07       0
  4936.8      .1       0  4976.8     .05       0  4989.6      .1       0
  5135.7     .07       0  5602.9    .035       0  5631.3      .1       0
  5718.5    .035       0    5872     .07       0
Bank Sta=4976.8,4989.6
XS Rating Curve= 0 ,0
Exp/Cntr=0.3,0.1

Chan Stop Cuts=-1
Use User Specified Reach Order=0
Composite Channel Slope=5