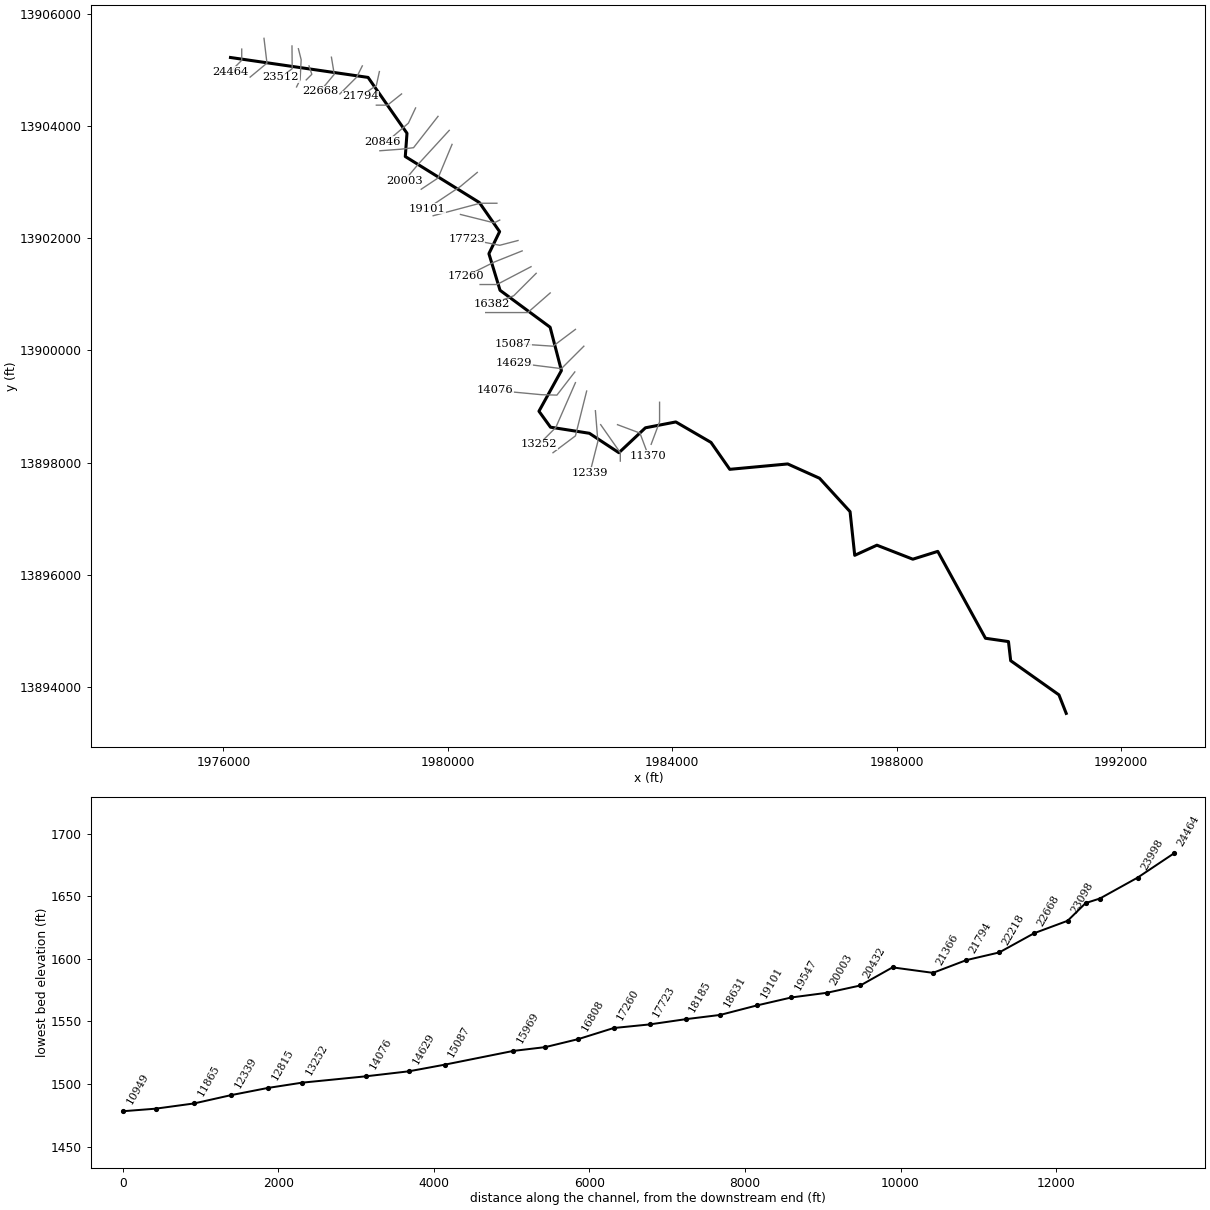
--- Wilson Creek.prj (project) ---

Proj Title=Wilson Creek Base Level Engineering
Current Plan=p01
Default Exp/Contr=0.3,0.1
English Units
Geom File=g01
Flow File=f01
Plan File=p01
Y Axis Title=Elevation
X Axis Title(PF)=Main Channel Distance
X Axis Title(XS)=Station
BEGIN DESCRIPTION:
Wilson Creek
END DESCRIPTION:
DSS Export Rating Curves= 0
DSS Export Rating Curve Sorted= 0
DSS Export Volume Flow Curves= 0
DXF OffsetX= 0
DXF OffsetY= 0
DXF ScaleX= 1
DXF ScaleY= 10

--- Wilson Creek.p01 (plan) ---

Plan Title=Multiple Run
Short Identifier=Multiple
Geom File=g01
Flow File=f01
Subcritical Flow
K Sum by GR= 0
Std Step Tol= 0.01
Critical Tol= 0.01
Num of Std Step Trials= 20
Max Error Tol= 0.3
Flow Tol Ratio= 0.001
Split Flow NTrial= 30
Split Flow Tol= 0.02
Split Flow Ratio= 0.02
Log Output Level= 0
Friction Slope Method= 1
Unsteady Friction Slope Method= 2
Unsteady Bridges Friction Slope Method= 1
Parabolic Critical Depth
Global Vel Dist=  1 , 1 , 1
Global Log Level= 0
CheckData=True
Encroach Param= -1, 0, 0, 0
BEGIN DESCRIPTION:
Multiple Run
END DESCRIPTION:

--- Wilson Creek.f01 (steady flow) ---

Flow Title=Multiple
Program Version=4.10
Number of Profiles= 7
Profile Names=10-year,25-year,50-year,1pct_min,100-year,1pct_plu,500-year
River Rch & RM=Wilson Creek,Reach-1         ,24464
     363     585     787     517    1032    2058    1745
River Rch & RM=Wilson Creek,Reach-1         ,23098
    1331    2312    3268    2240    4469    8918    8272
River Rch & RM=Wilson Creek,Reach-1         ,16808
    2040    3615    5177    3587    7157   14280   13549
River Rch & RM=Wilson Creek,Reach-1         ,12339
    2177    3860    5528    3828    7639   15241   14450
River Rch & RM=Wilson Creek,Reach-1         ,8288
    2808    5040    7278    5077   10130   20213   19452
River Rch & RM=Wilson Creek,Reach-1         ,7421
    3013    5405    7801    5436   10847   21642   20785
River Rch & RM=Wilson Creek,Reach-1         ,1331
    3948    7166   10426    7318   14601   29134   28387
Boundary for River Rch & Prof#=Wilson Creek,Reach-1         , 1
Up Type= 0
Dn Type= 3
Dn Slope=0.006
Boundary for River Rch & Prof#=Wilson Creek,Reach-1         , 2
Up Type= 0
Dn Type= 3
Dn Slope=0.006
Boundary for River Rch & Prof#=Wilson Creek,Reach-1         , 3
Up Type= 0
Dn Type= 3
Dn Slope=0.006
Boundary for River Rch & Prof#=Wilson Creek,Reach-1         , 4
Up Type= 0
Dn Type= 3
Dn Slope=0.006
Boundary for River Rch & Prof#=Wilson Creek,Reach-1         , 5
Up Type= 0
Dn Type= 3
Dn Slope=0.006
Boundary for River Rch & Prof#=Wilson Creek,Reach-1         , 6
Up Type= 0
Dn Type= 3
Dn Slope=0.006
Boundary for River Rch & Prof#=Wilson Creek,Reach-1         , 7
Up Type= 0
Dn Type= 3
Dn Slope=0.006
DSS Import GetInterval= 0
DSS Import GetPeak= 0
DSS Import FillOption= 0

--- Wilson Creek.g01 (geometry) ---

Geom Title=Existing Conditions
Program Version=4.10

River Reach=Wilson Creek    ,Reach-1
Reach XY= 30
        1976125.       13905225.      1978577.68     13904869.61
      1979271.47     13903873.54      1979241.41      13903458.2
      1980561.38     13902638.21      1980923.16     13902118.88
      1980732.19     13901725.33      1980930.73     13901072.45
      1981823.52     13900413.51      1982024.98     13899640.41
      1981624.49     13898914.83      1981830.44     13898630.18
      1982523.53     13898521.47      1983050.11     13898174.68
       1983522.7     13898619.17       1984064.5      13898723.8
      1984692.05     13898358.51      1985026.47     13897878.53
      1986059.78      13897974.5       1986627.3     13897719.17
      1987171.39      13897123.5      1987254.36     13896344.38
      1987649.91     13896525.21      1988290.27     13896275.38
        1988735.     13896414.95      1989585.62     13894864.94
      1989995.65      13894805.6      1990034.99     13894465.05
      1990895.48     13893855.37        1991025.       13893525.

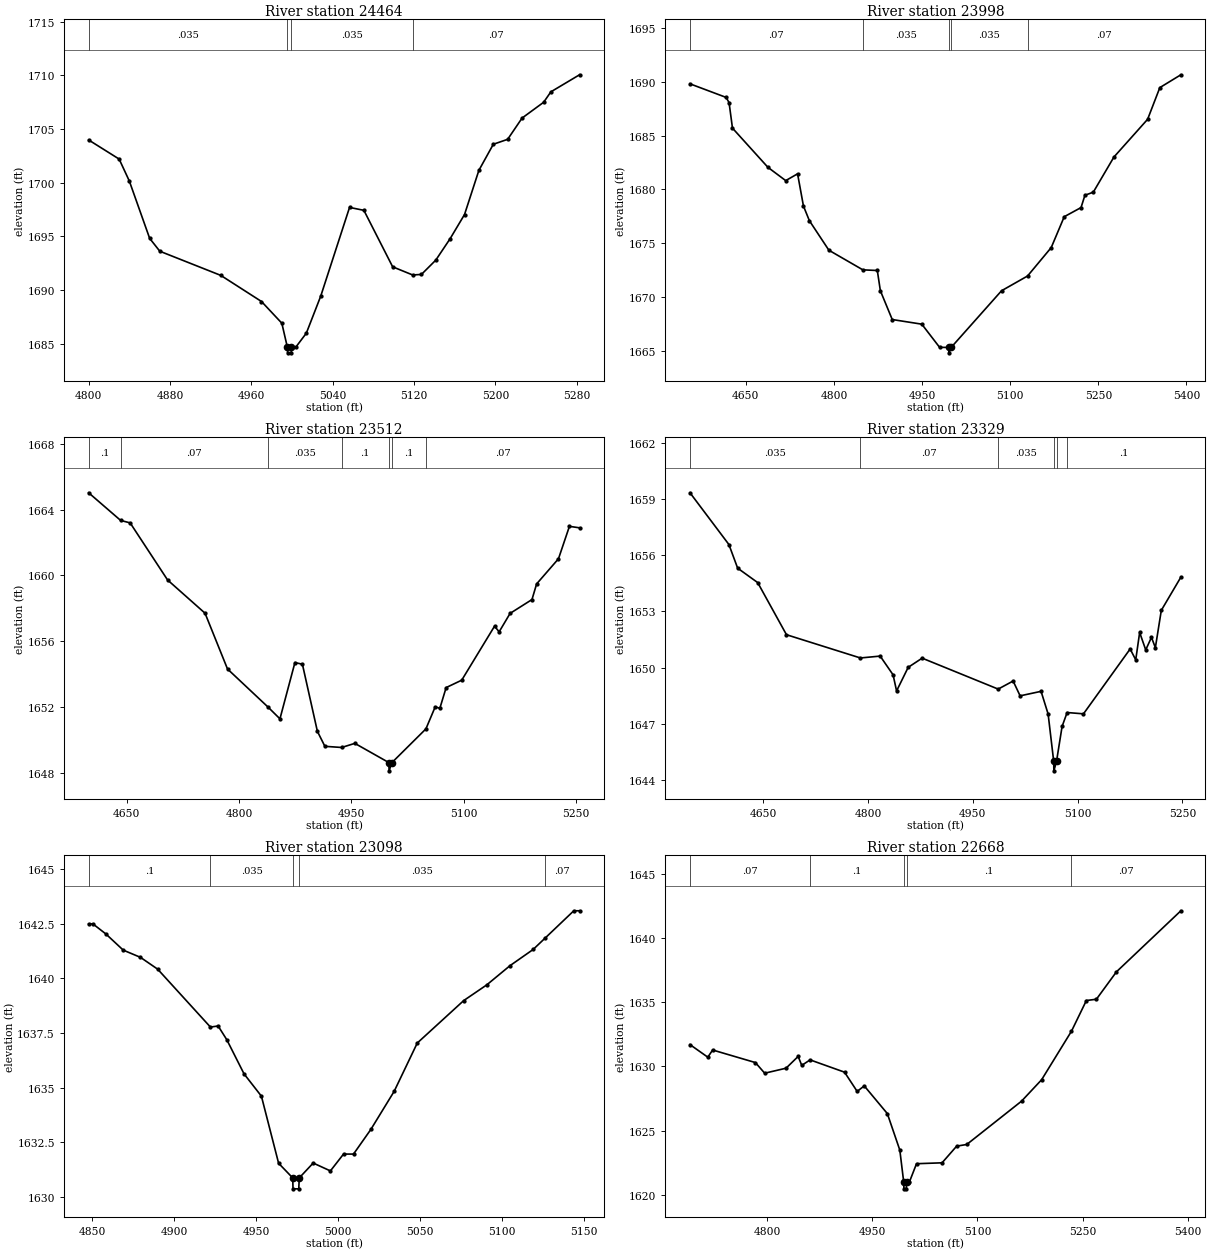
Type RM Length L Ch R = 1 ,24464   ,466,466,466
BEGIN DESCRIPTION:
Wilson Creek 50.0
END DESCRIPTION:
XS GIS Cut Line= 3
        1976325.     13905374.99        1976325.       13905175.
      1976125.03     13904975.03
#Sta/Elev= 30
    4800 1703.98    4830  1702.2    4840 1700.16    4860 1694.82    4870 1693.62
    4930 1691.37    4970 1688.94    4990 1686.92  4995.5 1684.66  4995.7 1684.16
  4999.2 1684.16  4999.5 1684.66  5003.5 1684.66  5014.1 1685.99  5028.3 1689.45
  5056.6  1697.7  5070.7 1697.43    5099 1692.17  5118.7 1691.41  5127.3 1691.46
  5141.4 1692.79  5155.6  1694.8  5169.7 1697.04  5183.8 1701.15    5198 1703.58
  5212.1 1704.04  5226.3 1706.02  5247.5 1707.49  5254.6 1708.46  5282.8 1710.05
#Mann= 4 ,-1 , 0
    4800    .035       0  4995.5    .035       0  4999.5    .035       0
  5118.7     .07       0
Bank Sta=4995.5,4999.5
XS Rating Curve= 0 ,0
Exp/Cntr=0.3,0.1

Type RM Length L Ch R = 1 ,23998   ,486,486,486
BEGIN DESCRIPTION:
Wilson Creek 49.0
END DESCRIPTION:
XS GIS Cut Line= 3
       1976722.2     13905566.76        1976775.       13905125.
      1976475.01     13904875.01
#Sta/Elev= 30
  4555.1  1689.8  4616.6 1688.54  4621.6 1688.06  4627.4 1685.69  4687.8 1682.05
    4718 1680.82  4738.2 1681.45  4748.2 1678.46  4758.3  1677.1  4791.5 1674.36
  4849.3 1672.54  4873.9 1672.48  4879.1  1670.6  4899.3 1667.93  4949.6  1667.5
  4979.9 1665.35  4995.5 1665.34  4995.7 1664.84  4999.5 1665.34  5085.3  1670.6
  5129.6 1671.97  5169.9 1674.61    5192 1677.47  5220.6 1678.32  5227.2 1679.46
  5241.5 1679.75  5276.6 1683.01  5333.9 1686.51  5354.7 1689.45  5390.5 1690.64
#Mann= 5 ,-1 , 0
  4555.1     .07       0  4849.3    .035       0  4995.5    .035       0
  4999.5    .035       0  5129.6     .07       0
Bank Sta=4995.5,4999.5
XS Rating Curve= 0 ,0
Exp/Cntr=0.3,0.1

Type RM Length L Ch R = 1 ,23512   ,183,183,183
BEGIN DESCRIPTION:
Wilson Creek 48.0
END DESCRIPTION:
XS GIS Cut Line= 3
      1977221.31     13905430.38        1977225.       13905025.
        1977025.       13904875.
#Sta/Elev= 30
  4599.4 1665.02  4642.1 1663.34  4654.8 1663.19  4704.8 1659.72  4754.8  1657.7
  4784.8 1654.31  4838.8    1652  4854.8 1651.28  4874.8  1654.7  4884.8  1654.6
  4904.8 1650.52  4914.8 1649.61  4937.2 1649.54  4954.8 1649.79  5000.3 1648.62
  5000.5 1648.12  5004.3 1648.62  5049.7 1650.67  5062.1 1652.01  5068.3 1651.92
  5076.7 1653.18  5097.5 1653.63  5141.3 1656.91  5147.5 1656.57  5162.1 1657.69
  5191.3 1658.53  5197.5 1659.48  5226.7 1661.01  5241.3 1662.98  5254.8 1662.89
#Mann= 7 ,-1 , 0
  4599.4      .1       0  4642.1     .07       0  4838.8    .035       0
  4937.2      .1       0  5000.3     .05       0  5004.3      .1       0
  5049.7     .07       0
#XS Ineff= 2 , 0
         4878.48 1654.06
Permanent Ineff=
       F       F
Bank Sta=5000.3,5004.3
XS Rating Curve= 0 ,0
Exp/Cntr=0.3,0.1

Type RM Length L Ch R = 1 ,23329   ,231,231,231
BEGIN DESCRIPTION:
Mapping XS 6408c18a
END DESCRIPTION:
XS GIS Cut Line= 4
      1977335.74     13905381.11      1977384.73     13905185.49
       1977366.5     13904830.02      1977302.67     13904699.82
#Sta/Elev= 30
  4545.3 1659.32    4601 1656.56  4613.5  1655.3  4642.2 1654.53  4683.4 1651.75
  4789.2 1650.51  4817.5 1650.61    4836 1649.61    4841 1648.75  4857.6 1650.01
  4877.6  1650.5  4986.4 1648.85  5007.8 1649.28  5017.8 1648.49  5047.8 1648.73
  5057.9 1647.52  5065.9 1644.99  5066.1 1644.49  5069.9 1644.99  5077.9 1646.86
  5085.1  1647.6  5108.5 1647.53  5175.3 1650.99  5183.3 1650.41  5188.9 1651.87
  5197.6 1650.94  5205.8 1651.61  5211.4 1651.06  5219.9 1653.05  5247.9 1654.82
#Mann= 6 ,-1 , 0
  4545.3    .035       0  4789.2     .07       0  4986.4    .035       0
  5065.9    .035       0  5069.9    .035       0  5085.1      .1       0
#XS Ineff= 2 , 0
         4874.89 1650.36
Permanent Ineff=
       F       F
Bank Sta=5065.9,5069.9
XS Rating Curve= 0 ,0
Exp/Cntr=0.3,0.1

Type RM Length L Ch R = 1 ,23098   ,430,430,430
BEGIN DESCRIPTION:
Wilson Creek 47.0
END DESCRIPTION:
XS GIS Cut Line= 3
      1977525.01     13905074.98        1977575.       13904925.
      1977475.01     13904825.01
#Sta/Elev= 30
  4847.8 1642.49  4850.4 1642.49  4858.3 1642.03  4868.9 1641.29  4879.4 1640.96
  4889.9 1640.42  4922.1 1637.77  4926.8 1637.82  4932.1 1637.19  4942.6 1635.63
  4953.2 1634.61  4963.7 1631.54  4972.3 1630.87  4972.5 1630.37    4976 1630.37
  4976.3 1630.87  4984.8 1631.55  4995.3 1631.19  5003.3 1631.96  5009.4 1631.96
    5020 1633.09  5034.2 1634.83  5048.3 1637.04  5076.6 1638.98  5090.7  1639.7
  5104.9 1640.58    5119 1641.32  5126.3 1641.84  5143.8 1643.09  5147.3 1643.09
#Mann= 5 ,-1 , 0
  4847.8      .1       0  4922.1    .035       0  4972.3    .035       0
  4976.3    .035       0  5126.3     .07       0
Bank Sta=4972.3,4976.3
XS Rating Curve= 0 ,0
Exp/Cntr=0.3,0.1

Type RM Length L Ch R = 1 ,22668   ,450,450,450
BEGIN DESCRIPTION:
Wilson Creek 46.0
END DESCRIPTION:
XS GIS Cut Line= 3
      1977924.43     13905230.04        1977975.       13904925.
      1977725.01     13904625.01
#Sta/Elev= 30
  4690.3  1631.7  4715.7 1630.72  4722.6 1631.28  4783.5  1630.3  4796.8 1629.47
  4827.2 1629.86  4844.5 1630.78  4849.6 1630.08  4861.5 1630.51  4910.6 1629.55
  4928.6 1628.05  4938.7 1628.48  4971.6 1626.32  4989.4 1623.47    4995 1620.95
  4995.2 1620.45  4998.7 1620.45    4999 1620.95  5002.8 1620.95  5013.2 1622.41
  5049.6 1622.48  5070.4 1623.78  5084.8 1623.91  5162.9 1627.29  5191.5 1628.96
  5234.1 1632.75  5255.3 1635.14  5269.6 1635.24  5298.2 1637.38    5390 1642.14
#Mann= 5 ,-1 , 0
  4690.3     .07       0  4861.5      .1       0    4995     .05       0
    4999      .1       0  5234.1     .07       0
Bank Sta=4995,4999
XS Rating Curve= 0 ,0
Exp/Cntr=0.3,0.1

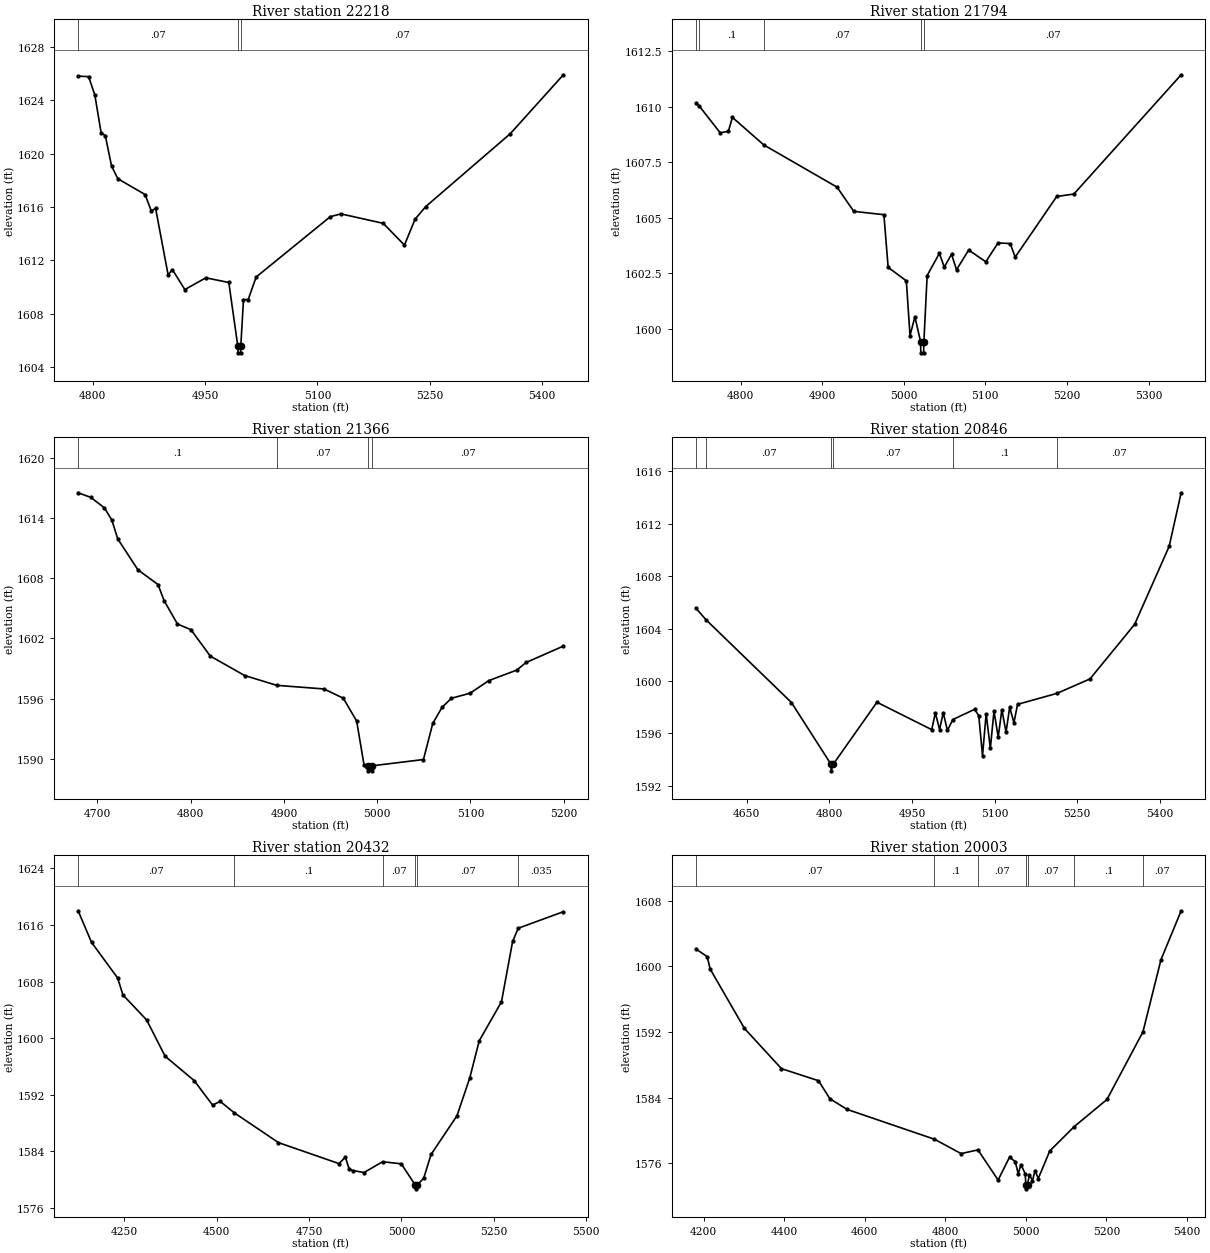
Type RM Length L Ch R = 1 ,22218   ,424,424,424
BEGIN DESCRIPTION:
Wilson Creek 45.0
END DESCRIPTION:
XS GIS Cut Line= 3
      1978474.99     13905074.98        1978375.       13904875.
      1978074.97     13904574.97
#Sta/Elev= 30
  4780.5  1625.8  4794.5 1625.76  4802.8 1624.39  4811.2 1621.56  4816.8 1621.34
  4825.2 1619.05  4833.6 1618.11  4869.9 1616.93  4878.3 1615.68  4883.9 1615.91
  4900.7  1610.9  4906.3 1611.31    4923 1609.81    4951 1610.69  4981.7 1610.34
  4993.7 1605.57    4994 1605.07  4997.5 1605.07  4997.7 1605.57  5001.3 1609.06
  5007.6 1609.06  5018.2 1610.75  5117.2 1615.27  5131.4 1615.48  5187.9 1614.77
  5216.2 1613.14  5230.4 1615.08  5244.5 1616.02  5357.6 1621.49  5428.4  1625.9
#Mann= 3 ,-1 , 0
  4780.5     .07       0  4993.7     .05       0  4997.7     .07       0
Bank Sta=4993.7,4997.7
XS Rating Curve= 0 ,0
Exp/Cntr=0.3,0.1

Type RM Length L Ch R = 1 ,21794   ,428,428,428
BEGIN DESCRIPTION:
Wilson Creek 44.0
END DESCRIPTION:
XS GIS Cut Line= 3
      1978779.53     13904974.01        1978725.       13904725.
      1978443.54     13904534.64
#Sta/Elev= 30
  4745.3 1610.15  4749.5 1610.03    4775 1608.83    4785 1608.89  4790.1 1609.52
  4828.6 1608.28  4918.3 1606.38  4938.8 1605.29  4975.7 1605.14  4980.9 1602.77
  5003.2 1602.16  5007.7  1599.7  5013.7 1600.54  5020.7 1599.42  5020.9 1598.92
  5024.4 1598.92  5024.7 1599.42  5028.7  1602.4  5043.7  1603.4  5049.7 1602.78
  5058.6 1603.36  5064.7 1602.66  5079.6 1603.55  5100.6 1603.02  5115.6 1603.87
  5130.5 1603.84  5136.6 1603.23  5187.5 1605.96  5208.5 1606.07    5340 1611.44
#Mann= 5 ,-1 , 0
  4745.3     .07       0  4749.5      .1       0  4828.6     .07       0
  5020.7     .05       0  5024.7     .07       0
Bank Sta=5020.7,5024.7
XS Rating Curve= 0 ,0
Exp/Cntr=0.3,0.1

Type RM Length L Ch R = 1 ,21366   ,520,520,520
BEGIN DESCRIPTION:
Wilson Creek 43.0
END DESCRIPTION:
XS GIS Cut Line= 3
      1979175.03     13904575.02        1978925.       13904375.
      1978724.99       13904375.
#Sta/Elev= 30
  4679.4 1616.55    4693 1616.09  4707.5 1615.05  4715.5 1613.84  4721.9 1611.94
  4743.5 1608.86  4765.1 1607.38  4771.5 1605.79  4785.9 1603.44  4800.3 1602.88
  4821.1 1600.24  4857.9  1598.3  4892.3 1597.32  4942.8 1596.96  4963.6 1596.04
    4978 1593.75    4986 1589.32  4990.4 1589.28  4990.6 1588.78  4994.1 1588.78
  4994.4 1589.28  5049.6 1589.91  5059.6 1593.52  5069.6 1595.13  5079.6 1596.03
  5099.6 1596.53  5119.6 1597.79  5149.6 1598.84  5159.6  1599.6  5199.6 1601.24
#Mann= 4 ,-1 , 0
  4679.4      .1       0  4892.3     .07       0  4990.4     .05       0
  4994.4     .07       0
Bank Sta=4990.4,4994.4
XS Rating Curve= 0 ,0
Exp/Cntr=0.3,0.1

Type RM Length L Ch R = 1 ,20846   ,414,414,414
BEGIN DESCRIPTION:
Wilson Creek 42.0
END DESCRIPTION:
XS GIS Cut Line= 4
      1979424.98     13904324.97      1979296.84     13904053.98
      1979008.65     13903805.72      1978825.04     13903725.02
#Sta/Elev= 30
  4557.9 1605.56  4576.2 1604.67  4731.3 1598.36  4803.1 1593.65  4803.4 1593.15
  4807.1 1593.65  4886.5 1598.38  4985.9 1596.29  4992.5 1597.56  5000.2  1596.3
  5006.8 1597.59  5014.4 1596.23  5024.2 1597.06  5063.8 1597.84  5071.3 1597.35
  5078.1 1594.31  5084.7  1597.5  5092.3 1594.87  5098.9  1597.7  5106.6 1595.72
  5113.2 1597.82  5120.8 1596.09  5127.4    1598  5135.1 1596.82  5141.7 1598.22
  5213.5 1599.06  5273.2 1600.16  5354.2 1604.32  5416.8 1610.26  5438.6 1614.35
#Mann= 6 ,-1 , 0
  4557.9      .1       0  4576.2     .07       0  4803.1     .05       0
  4807.1     .07       0  5024.2      .1       0  5213.5     .07       0
Bank Sta=4803.1,4807.1
XS Rating Curve= 0 ,0
Exp/Cntr=0.3,0.1

Type RM Length L Ch R = 1 ,20432   ,429,429,429
BEGIN DESCRIPTION:
Wilson Creek 41.0
END DESCRIPTION:
XS GIS Cut Line= 4
      1979825.02     13904175.02      1979388.43     13903615.86
      1979158.84     13903588.77      1978788.07     13903561.14
#Sta/Elev= 30
  4125.7 1618.01  4161.9 1613.55  4232.5 1608.51  4246.9 1606.11  4311.1 1602.56
  4360.9 1597.44  4439.6 1593.99  4489.3 1590.53  4510.1 1591.05  4548.1 1589.43
  4667.5 1585.22  4831.2 1582.25  4848.6 1583.17  4858.7 1581.47  4868.8 1581.27
    4899 1580.99  4949.1 1582.51  4999.7 1582.22    5038 1579.18  5038.2 1578.68
    5042 1579.18  5060.5  1580.2  5080.2 1583.54  5150.4 1589.02  5184.9 1594.36
  5210.5 1599.61  5270.7 1605.14  5300.8 1613.67    5316 1615.54  5438.1 1617.88
#Mann= 6 ,-1 , 0
  4125.7     .07       0  4548.1      .1       0  4949.1     .07       0
    5038     .05       0    5042     .07       0    5316    .035       0
Bank Sta=5038,5042
XS Rating Curve= 0 ,0
Exp/Cntr=0.3,0.1

Type RM Length L Ch R = 1 ,20003   ,456,456,456
BEGIN DESCRIPTION:
Wilson Creek 40.0
END DESCRIPTION:
XS GIS Cut Line= 3
      1980024.98     13903924.98        1979475.       13903325.
      1979225.02     13903025.02
#Sta/Elev= 30
  4180.9 1602.12  4208.9 1601.19  4216.3 1599.67  4301.4 1592.43  4393.3 1587.52
  4485.2 1586.05  4513.5 1583.85  4556.1 1582.55  4773.1 1578.91  4839.1 1577.16
    4881 1577.61    4931 1573.93  4959.4 1576.73  4973.5 1576.18  4980.9 1574.71
  4987.7 1575.82  4998.1 1574.72    5000 1573.36  5000.2 1572.86    5004 1573.36
  5008.5 1574.58  5016.3 1573.87  5022.8 1575.08  5030.6 1574.11  5059.2 1577.48
  5119.7 1580.44  5201.1 1583.76  5290.4    1592  5335.2 1600.81  5385.3 1606.78
#Mann= 7 ,-1 , 0
  4180.9     .07       0  4773.1      .1       0    4881     .07       0
    5000     .05       0    5004     .07       0  5119.7      .1       0
  5290.4     .07       0
Bank Sta=5000,5004
XS Rating Curve= 0 ,0
Exp/Cntr=0.3,0.1

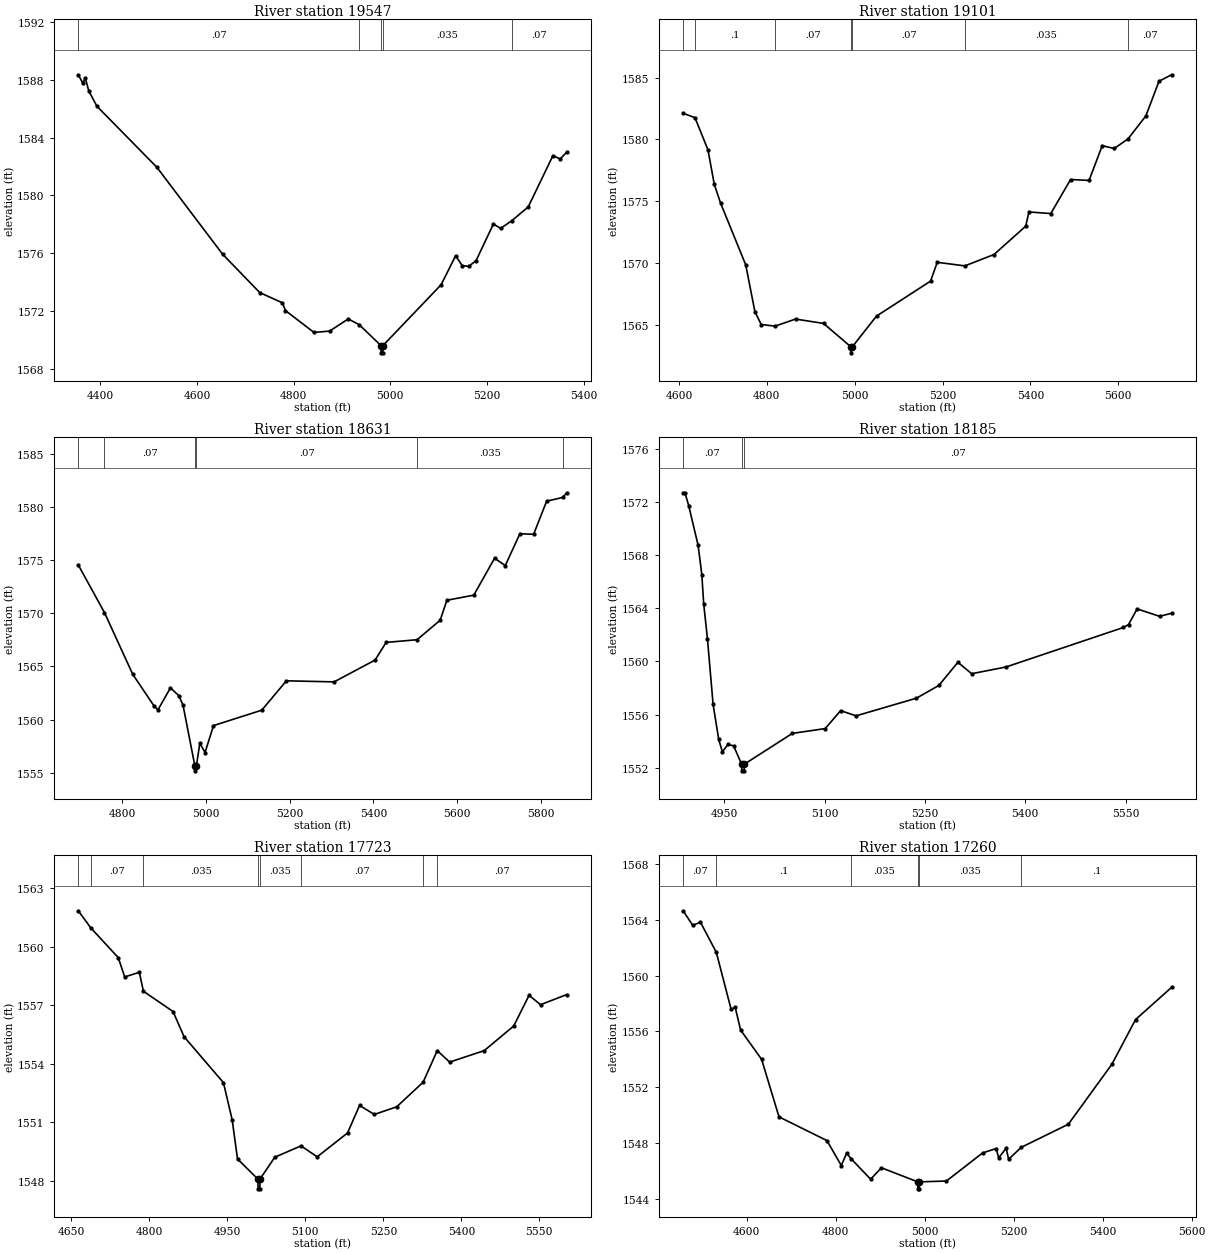
Type RM Length L Ch R = 1 ,19547   ,446,446,446
BEGIN DESCRIPTION:
Wilson Creek 39.0
END DESCRIPTION:
XS GIS Cut Line= 3
        1980075.       13903675.        1979825.       13903075.
      1979524.97     13902874.98
#Sta/Elev= 30
  4354.5 1588.33  4363.7 1587.76  4369.1  1588.1  4376.2 1587.22    4393 1586.16
    4517 1581.95    4653 1575.95  4729.9  1573.3    4777 1572.59    4783 1572.06
    4842 1570.55  4874.5 1570.64    4913 1571.48  4935.8 1571.08  4980.8 1569.64
  4981.1 1569.14  4984.6 1569.14  4984.8 1569.64  5105.2 1573.84  5135.2 1575.84
  5148.7 1575.16  5162.2 1575.11  5177.3 1575.49  5213.3 1578.03  5228.3 1577.73
  5251.1 1578.25  5285.4 1579.21  5336.5 1582.75  5351.5 1582.52  5365.1 1582.99
#Mann= 5 ,-1 , 0
  4354.5     .07       0  4935.8    .035       0  4980.8    .035       0
  4984.8    .035       0  5251.1     .07       0
Bank Sta=4980.8,4984.8
XS Rating Curve= 0 ,0
Exp/Cntr=0.3,0.1

Type RM Length L Ch R = 1 ,19101   ,470,470,470
BEGIN DESCRIPTION:
Wilson Creek 38.0
END DESCRIPTION:
XS GIS Cut Line= 3
      1980524.98     13903174.98        1980225.       13902925.
      1979624.99       13902525.
#Sta/Elev= 30
  4609.6 1582.11  4636.6 1581.75  4666.2 1579.15  4680.5 1576.37  4694.8 1574.85
  4752.1 1569.85  4772.9 1566.08  4787.3 1565.03    4819  1564.9  4865.4 1565.47
  4929.1 1565.12  4990.9 1563.24  4991.2 1562.74  4994.9 1563.24  5049.7 1565.71
  5172.8 1568.54  5187.9 1570.06  5250.8 1569.77  5317.1 1570.69  5389.2 1572.98
  5396.7 1574.13  5446.3    1574  5491.3 1576.75  5533.4 1576.68  5563.4 1579.49
  5590.5 1579.26  5621.9 1580.03  5662.6 1581.89  5692.6  1584.7  5721.2 1585.22
#Mann= 7 ,-1 , 0
  4609.6     .07       0  4636.6      .1       0    4819     .07       0
  4990.9     .05       0  4994.9     .07       0  5250.8    .035       0
  5621.9     .07       0
Bank Sta=4990.9,4994.9
XS Rating Curve= 0 ,0
Exp/Cntr=0.3,0.1

Type RM Length L Ch R = 1 ,18631   ,446,446,446
BEGIN DESCRIPTION:
Wilson Creek 37.0
END DESCRIPTION:
XS GIS Cut Line= 3
      1980874.96       13902625.        1980575.       13902625.
      1979738.65      13902402.1
#Sta/Elev= 30
  4695.7 1574.54  4758.2 1570.06  4825.7 1564.26  4875.7 1561.33  4885.7 1560.92
  4915.7 1562.99  4935.7 1562.25  4945.7 1561.35  4973.7 1555.69  4973.9 1555.19
  4977.7 1555.69  4985.7 1557.78  4998.2 1556.91  5018.3 1559.44  5133.5 1560.89
  5192.3 1563.65  5306.1 1563.55  5403.9  1565.6  5430.3 1567.26    5504 1567.51
  5559.2 1569.34  5575.2 1571.22  5639.4  1571.7    5689 1575.17  5714.5 1574.48
  5749.4 1577.47  5782.2 1577.42  5813.2 1580.53  5851.4 1580.88  5861.2 1581.32
#Mann= 6 ,-1 , 0
  4695.7      .1       0  4758.2     .07       0  4973.7     .05       0
  4977.7     .07       0    5504    .035       0  5851.4     .07       0
Bank Sta=4973.7,4977.7
XS Rating Curve= 0 ,0
Exp/Cntr=0.3,0.1

Type RM Length L Ch R = 1 ,18185   ,462,462,462
BEGIN DESCRIPTION:
Wilson Creek 36.0
END DESCRIPTION:
XS GIS Cut Line= 3
      1980925.04     13902325.02        1980825.       13902275.
      1980225.02       13902425.
#Sta/Elev= 30
  4888.4 1572.69  4891.2 1572.69  4896.8 1571.71  4910.8 1568.74  4916.4 1566.52
  4919.2  1564.3  4924.8  1561.7  4933.2 1556.77  4941.6 1554.13  4947.1 1553.19
  4955.5 1553.75  4963.9 1553.64  4975.9 1552.26  4976.1 1551.76  4979.6 1551.76
  4979.9 1552.26  5051.8 1554.58  5100.8 1554.94  5123.9 1556.29  5147.1  1555.9
  5237.3 1557.23  5270.8 1558.19  5299.2 1559.93  5319.8 1559.07  5371.3 1559.58
  5546.6 1562.55  5554.3 1562.77  5567.2 1563.95  5600.7 1563.39  5618.7 1563.62
#Mann= 3 ,-1 , 0
  4888.4     .07       0  4975.9     .05       0  4979.9     .07       0
Bank Sta=4975.9,4979.9
XS Rating Curve= 0 ,0
Exp/Cntr=0.3,0.1

Type RM Length L Ch R = 1 ,17723   ,463,463,463
BEGIN DESCRIPTION:
Wilson Creek 35.0
END DESCRIPTION:
XS GIS Cut Line= 3
      1981251.39     13901960.25        1980925.       13901875.
      1980333.87     13901990.28
#Sta/Elev= 30
  4663.2 1561.84  4687.4 1560.96  4740.1 1559.44  4752.5 1558.45  4780.6 1558.69
  4788.5 1557.72  4845.5 1556.68  4866.7 1555.39  4942.4 1553.04  4959.2 1551.14
  4969.5 1549.13  5008.7  1548.1    5009  1547.6  5012.5  1547.6  5012.7  1548.1
  5041.3 1549.22  5091.6  1549.8  5122.8 1549.24  5181.1 1550.46  5204.3 1551.87
  5232.7 1551.41  5275.6  1551.8  5326.5 1553.06  5353.7 1554.68  5377.5 1554.09
  5444.2 1554.68  5500.8 1555.94  5530.3 1557.51  5552.4 1557.03  5602.8 1557.55
#Mann= 8 ,-1 , 0
  4663.2      .1       0  4687.4     .07       0  4788.5    .035       0
  5008.7    .035       0  5012.7    .035       0  5091.6     .07       0
  5326.5    .035       0  5353.7     .07       0
Bank Sta=5008.7,5012.7
XS Rating Curve= 0 ,0
Exp/Cntr=0.3,0.1

Type RM Length L Ch R = 1 ,17260   ,452,452,452
BEGIN DESCRIPTION:
Wilson Creek 34.0
END DESCRIPTION:
XS GIS Cut Line= 3
      1981324.99       13901775.        1980825.       13901575.
      1980325.02     13901325.01
#Sta/Elev= 30
  4457.4 1564.64  4478.9  1563.6  4496.4 1563.82    4532 1561.66  4565.1 1557.59
  4574.5 1557.71  4586.6 1556.09  4633.8 1553.99  4672.8 1549.87  4780.5 1548.17
  4812.8 1546.38  4824.9 1547.27  4834.7 1546.87  4878.8  1545.4    4903 1546.22
  4984.5 1545.21  4984.7 1544.71  4988.2 1544.71  4988.5 1545.21    5049 1545.27
  5130.1 1547.28  5160.8  1547.6  5166.4 1546.93  5183.2 1547.62  5188.8 1546.83
  5216.9 1547.68  5322.9 1549.34  5420.8 1553.64  5473.9 1556.84  5554.9 1559.15
#Mann= 6 ,-1 , 0
  4457.4     .07       0    4532      .1       0  4834.7    .035       0
  4984.5    .035       0  4988.5    .035       0  5216.9      .1       0
Bank Sta=4984.5,4988.5
XS Rating Curve= 0 ,0
Exp/Cntr=0.3,0.1

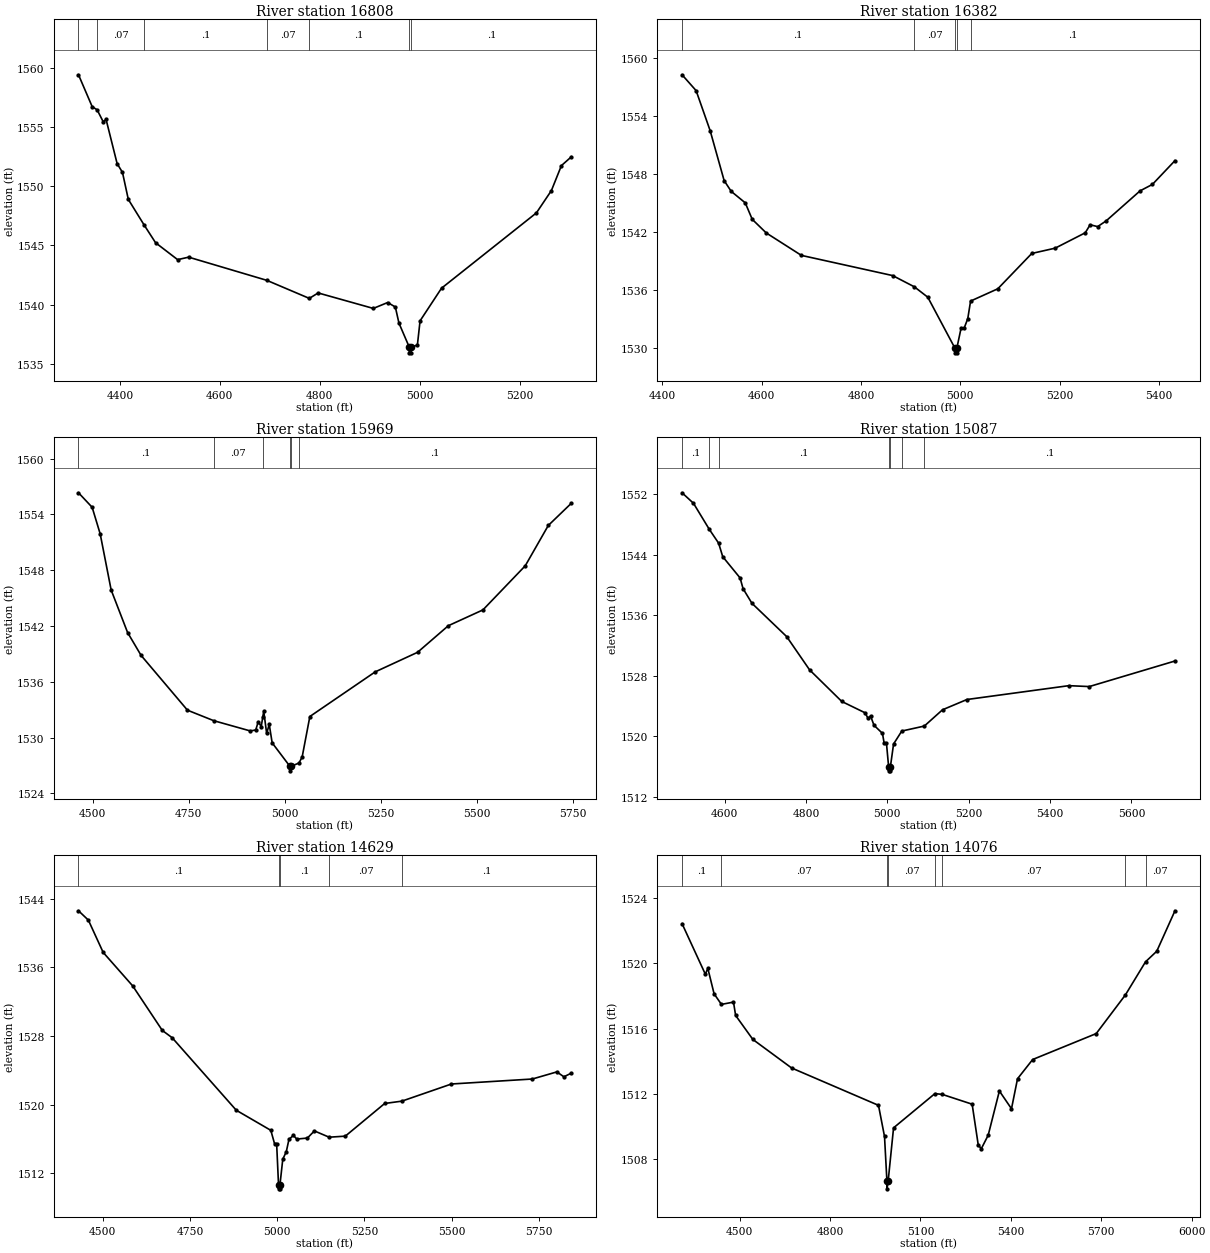
Type RM Length L Ch R = 1 ,16808   ,426,426,426
BEGIN DESCRIPTION:
Wilson Creek 33.0
END DESCRIPTION:
XS GIS Cut Line= 3
      1981483.35     13901493.25        1980875.       13901175.
      1980574.96       13901175.
#Sta/Elev= 30
  4317.2 1559.45  4344.7 1556.74  4354.4 1556.49  4366.7 1555.47  4372.4 1555.67
  4394.5 1551.93  4405.2 1551.19  4416.9  1548.9  4448.3 1546.75  4471.5 1545.23
  4515.6  1543.8  4537.7 1544.01    4694 1542.05  4779.2 1540.52  4796.9 1540.98
  4907.3 1539.67  4936.1 1540.17  4951.4 1539.79  4958.6 1538.43  4979.1 1536.41
  4979.4 1535.91  4982.9 1535.91  4983.2 1536.41  4995.5 1536.56  5000.9 1538.62
  5043.8 1541.38  5233.8 1547.76  5263.8 1549.65  5283.8 1551.76  5303.8 1552.51
#Mann= 7 ,-1 , 0
  4317.2      .1       0  4354.4     .07       0  4448.3      .1       0
    4694     .07       0  4779.2      .1       0  4979.1     .05       0
  4983.2      .1       0
Bank Sta=4979.1,4983.2
XS Rating Curve= 0 ,0
Exp/Cntr=0.3,0.1

Type RM Length L Ch R = 1 ,16382   ,413,413,413
BEGIN DESCRIPTION:
Wilson Creek 32.0
END DESCRIPTION:
XS GIS Cut Line= 3
      1981574.99     13901374.99        1981175.       13900975.
      1980774.97     13900824.99
#Sta/Elev= 30
  4439.6 1558.27  4467.9 1556.63  4496.2 1552.48  4524.4 1547.31  4538.6  1546.2
  4566.9 1545.01    4581  1543.3  4609.3 1541.89    4680 1539.57  4863.8 1537.48
  4907.4 1536.32  4934.6 1535.24  4989.1 1529.98  4989.3 1529.48  4992.9 1529.48
  4993.2 1529.98  5001.7 1532.05  5007.9 1532.05  5015.1 1533.01  5020.8 1534.84
  5075.6 1536.11  5144.1 1539.77  5191.3 1540.32  5251.8 1541.91  5261.6 1542.74
  5276.7 1542.55  5293.6 1543.13  5362.2 1546.25  5387.1 1546.92  5432.5 1549.38
#Mann= 5 ,-1 , 0
  4439.6      .1       0  4907.4     .07       0  4989.1     .05       0
  4993.2     .07       0  5020.8      .1       0
Bank Sta=4989.1,4993.2
XS Rating Curve= 0 ,0
Exp/Cntr=0.3,0.1

Type RM Length L Ch R = 1 ,15969   ,882,882,882
BEGIN DESCRIPTION:
Wilson Creek 31.0
END DESCRIPTION:
XS GIS Cut Line= 3
      1981824.97     13901024.97        1981425.       13900675.
      1980674.96       13900675.
#Sta/Elev= 30
  4463.5 1556.32    4499 1554.76  4519.9  1551.9  4548.4 1545.87  4591.1  1541.3
  4626.2 1538.84  4746.8 1532.95  4815.2 1531.82    4910 1530.72  4924.3 1530.82
  4930.9 1531.72  4938.5 1531.18  4942.6 1532.21  4945.1 1532.84  4952.7 1530.45
  4959.4 1531.43    4967 1529.44  5012.9 1526.93  5013.2 1526.43    5017 1526.93
  5036.7 1527.27    5045 1527.92    5065 1532.27    5235 1537.07    5345 1539.17
    5425 1542.03    5515 1543.73    5625 1548.47    5685 1552.81    5745  1555.2
#Mann= 6 ,-1 , 0
  4463.5      .1       0  4815.2     .07       0  4942.6     .07       0
  5012.9     .05       0    5017     .07       0  5036.7      .1       0
Bank Sta=5012.9,5017
XS Rating Curve= 0 ,0
Exp/Cntr=0.3,0.1

Type RM Length L Ch R = 1 ,15087   ,458,458,458
BEGIN DESCRIPTION:
Wilson Creek 30.0
END DESCRIPTION:
XS GIS Cut Line= 3
      1982274.97     13900374.98        1981875.       13900075.
      1981164.72     13900122.05
#Sta/Elev= 30
  4495.3  1552.2  4523.4 1550.81  4562.1 1547.38  4585.2 1545.54  4595.3 1543.75
    4638 1540.94  4645.3 1539.52  4667.1 1537.59  4752.6 1533.18  4808.8 1528.79
    4888 1524.61  4945.3 1523.11  4952.6 1522.37  4958.8 1522.69  4967.1 1521.47
    4988 1520.39  4992.1 1519.11  4997.8 1519.11  5003.2 1515.94  5003.4 1515.44
  5007.1 1515.44  5007.4 1515.94  5015.3 1518.99  5035.5  1520.7  5090.9 1521.36
  5135.6 1523.51  5195.7 1524.87  5446.2  1526.7  5496.4 1526.58  5707.1 1529.96
#Mann= 7 ,-1 , 0
  4495.3      .1       0  4562.1     .07       0  4585.2      .1       0
  5003.2     .05       0  5007.4      .1       0  5035.5     .07       0
  5090.9      .1       0
Bank Sta=5003.2,5007.4
XS Rating Curve= 0 ,0
Exp/Cntr=0.3,0.1

Type RM Length L Ch R = 1 ,14629   ,553,553,553
BEGIN DESCRIPTION:
Wilson Creek 29.0
END DESCRIPTION:
XS GIS Cut Line= 3
      1982424.99     13900074.99        1982025.       13899675.
      1981183.66     13899779.73
#Sta/Elev= 30
  4430.1 1542.58  4458.4 1541.49  4500.8 1537.73  4585.6 1533.82  4670.5 1528.63
  4698.8 1527.78  4882.6 1519.33  4981.6 1516.99  4992.2 1515.45  4998.3 1515.45
  5003.7 1510.67    5004 1510.17  5007.7 1510.17  5007.9 1510.67  5015.9 1513.62
    5026  1514.5  5033.6 1515.93  5046.2  1516.4  5056.2 1515.97  5086.5 1516.09
  5106.6 1516.92  5148.8 1516.19  5195.2 1516.31  5308.2 1520.12  5357.3 1520.39
  5499.6 1522.39  5731.4 1522.97  5801.9  1523.8  5822.1 1523.23  5843.6 1523.66
#Mann= 5 ,-1 , 0
  4430.1      .1       0  5003.7     .05       0  5007.9      .1       0
  5148.8     .07       0  5357.3      .1       0
Bank Sta=5003.7,5007.9
XS Rating Curve= 0 ,0
Exp/Cntr=0.3,0.1

Type RM Length L Ch R = 1 ,14076   ,824,824,824
BEGIN DESCRIPTION:
Wilson Creek 28.1
END DESCRIPTION:
XS GIS Cut Line= 4
      1982263.71     13899615.81       1981944.9     13899202.52
      1981667.46     13899209.88      1980834.85      13899288.3
#Sta/Elev= 30
  4308.8 1522.43  4386.1 1519.33  4394.3 1519.69  4415.1 1518.13  4439.4 1517.48
  4479.5 1517.62  4486.6  1516.8  4543.8 1515.33  4672.4 1513.58  4960.7 1511.29
  4980.7 1509.38  4988.6 1506.67  4988.9 1506.17  4992.9 1506.67  5010.7 1509.91
    5148 1512.01  5172.5 1511.96  5271.5 1511.36  5291.6 1508.88  5301.6 1508.62
  5324.8 1509.46  5361.9 1512.17  5402.1 1511.08  5422.1 1512.92  5472.4  1514.1
  5683.3 1515.69  5780.1 1518.06  5846.9 1520.09  5884.2 1520.74  5944.6 1523.22
#Mann= 8 ,-1 , 0
  4308.8      .1       0  4439.4     .07       0  4988.6     .05       0
  4992.9     .07       0    5148      .1       0  5172.5     .07       0
  5780.1      .1       0  5846.9     .07       0
Bank Sta=4988.6,4992.9
XS Rating Curve= 0 ,0
Exp/Cntr=0.3,0.1

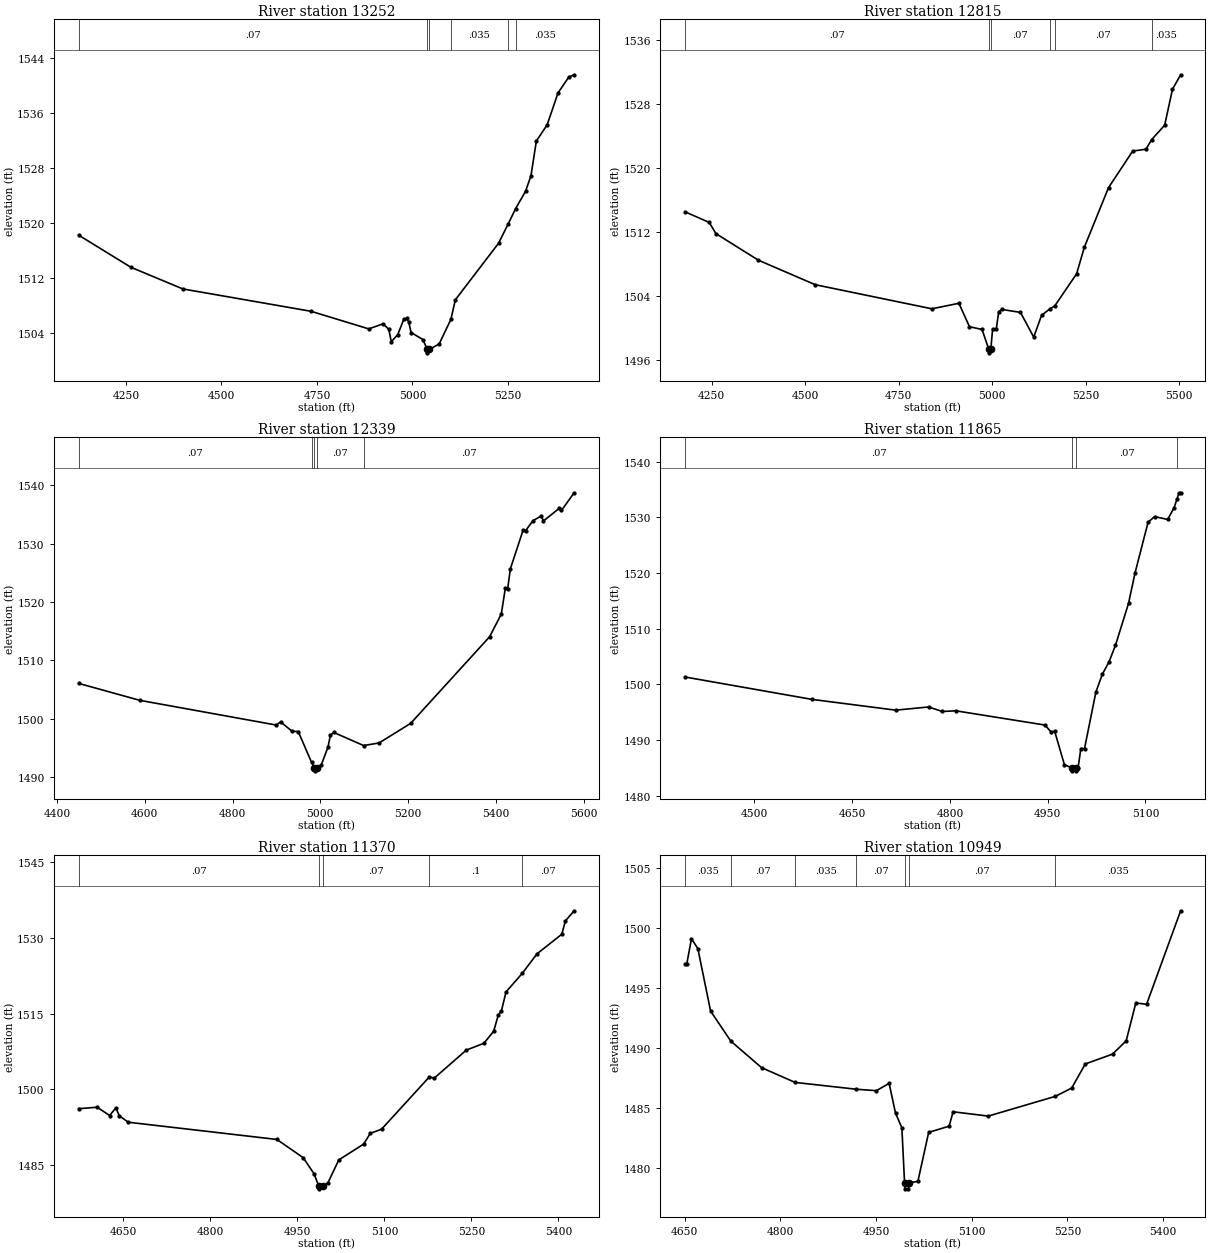
Type RM Length L Ch R = 1 ,13252   ,437,437,437
BEGIN DESCRIPTION:
Wilson Creek 28.0
END DESCRIPTION:
XS GIS Cut Line= 3
      1982274.98     13899424.96        1981925.       13898625.
      1981625.02     13898325.02
#Sta/Elev= 30
  4126.2 1518.18    4263 1513.51    4399 1510.36  4734.7 1507.11  4885.9 1504.55
    4923 1505.29  4938.2  1504.5  4944.8 1502.68  4961.6 1503.71  4977.5 1505.94
  4984.9 1506.07  4990.4 1505.57  4996.6 1504.02  5027.7    1503  5038.8 1501.57
  5039.3 1501.07  5044.7 1501.57  5070.1 1502.36  5100.8 1505.93  5112.5 1508.78
  5225.6    1517  5250.2 1519.73  5270.4 1522.05  5296.4 1524.56  5310.5 1526.82
  5324.6 1531.86  5352.9 1534.22  5381.2 1538.84  5409.5 1541.16  5423.6 1541.49
#Mann= 6 ,-1 , 0
  4126.2     .07       0  5038.8     .05       0  5044.7     .07       0
  5100.8    .035       0  5250.2     .07       0  5270.4    .035       0
Bank Sta=5038.8,5044.7
XS Rating Curve= 0 ,0
Exp/Cntr=0.3,0.1

Type RM Length L Ch R = 1 ,12815   ,476,476,476
BEGIN DESCRIPTION:
Wilson Creek 27.0
END DESCRIPTION:
XS GIS Cut Line= 3
        1982475.       13899275.        1982275.       13898475.
      1981875.02     13898175.02
#Sta/Elev= 30
    4179 1514.49  4243.4 1513.17  4261.5 1511.77  4374.9 1508.45  4526.9 1505.39
  4838.7 1502.38  4910.9 1503.07  4939.2 1500.14  4972.7  1499.8  4990.4 1497.38
  4990.8 1496.88  4996.3 1497.38    5001 1499.87  5010.9 1499.87  5017.2    1502
  5025.5  1502.3  5075.5 1501.93  5110.9 1498.84  5131.8 1501.56  5153.7 1502.36
  5167.1 1502.74  5225.5 1506.75  5246.3 1510.08  5310.9 1517.52  5375.5 1522.08
  5410.9 1522.31  5425.9  1523.5  5460.9 1525.31  5481.8  1529.8  5503.6 1531.61
#Mann= 6 ,-1 , 0
    4179     .07       0  4990.4     .05       0  4996.3     .07       0
  5153.7    .035       0  5167.1     .07       0  5425.9    .035       0
Bank Sta=4990.4,4996.3
XS Rating Curve= 0 ,0
Exp/Cntr=0.3,0.1

Type RM Length L Ch R = 1 ,12339   ,474,474,474
BEGIN DESCRIPTION:
Wilson Creek 26.0
END DESCRIPTION:
XS GIS Cut Line= 3
      1982631.04     13898923.98        1982675.       13898375.
      1982532.26     13897814.01
#Sta/Elev= 30
    4449 1506.07  4588.4 1503.17  4899.4 1498.94  4909.4 1499.48  4935.8 1497.86
  4949.6 1497.83    4980 1492.55  4986.6  1491.6  4987.1  1491.1  4992.9  1491.6
  5002.3 1492.15  5017.6 1495.21  5022.8 1497.19  5030.7 1497.67  5098.5 1495.43
  5133.9 1495.87  5206.1 1499.24  5385.8 1514.05  5412.5 1517.94  5421.6 1522.34
  5426.8 1522.16  5433.1 1525.67  5462.5 1532.38  5467.7  1532.2  5484.7 1533.92
  5503.4 1534.72  5508.6 1533.88  5544.3 1536.02  5549.5 1535.67  5578.6  1538.7
#Mann= 5 ,-1 , 0
    4449     .07       0    4980     .07       0  4986.6     .05       0
  4992.9     .07       0  5098.5     .07       0
Bank Sta=4986.6,4992.9
XS Rating Curve= 0 ,0
Exp/Cntr=0.3,0.1

Type RM Length L Ch R = 1 ,11865   ,495,495,495
BEGIN DESCRIPTION:
Wilson Creek 25.0
END DESCRIPTION:
XS GIS Cut Line= 3
      1982724.97     13898675.04        1983075.       13898175.
        1983075.     13898024.97
#Sta/Elev= 30
  4393.6 1501.34  4588.5 1497.32  4716.7 1495.39  4767.3 1495.96  4788.2 1495.15
  4809.1 1495.27    4946 1492.71  4954.7 1491.52  4960.8 1491.56  4975.6 1485.61
  4987.3 1484.99  4987.8 1484.49  4993.2 1484.49  4993.7 1484.99  4996.6 1485.04
  5000.9 1488.49  5006.5 1488.49    5024 1498.66    5034 1501.88    5044 1504.02
    5054 1507.04    5074 1514.55    5084 1520.02    5104 1529.12    5114 1530.16
    5134 1529.64    5144 1531.74  5148.5 1533.35  5151.5 1534.43    5154 1534.43
#Mann= 4 ,-1 , 0
  4393.6     .07       0  4987.3     .05       0  4993.7     .07       0
  5148.5      .1       0
Bank Sta=4987.3,4993.7
XS Rating Curve= 0 ,0
Exp/Cntr=0.3,0.1

Type RM Length L Ch R = 1 ,11370   ,421,421,421
BEGIN DESCRIPTION:
Wilson Creek 24.0
END DESCRIPTION:
XS GIS Cut Line= 3
      1983024.98     13898675.01        1983425.       13898525.
      1983574.99     13898125.02
#Sta/Elev= 30
  4572.8 1496.18  4604.9 1496.47  4626.2 1494.83  4636.9 1496.33  4643.1 1494.76
  4658.3  1493.5  4914.6 1490.09    4960 1486.48  4978.7 1483.29    4987 1480.81
  4987.5 1480.31  4993.4 1480.81  5002.7 1481.52  5021.4 1486.04  5064.1 1489.16
  5075.7 1491.29  5095.2 1492.13  5177.4 1502.46    5186 1502.24  5241.2 1507.78
  5271.5 1509.13  5288.4 1511.52  5296.4 1514.75  5301.7 1515.51  5309.7  1519.3
  5337.6 1522.97  5363.1 1526.84  5405.9 1530.73  5412.1 1533.37  5427.2 1535.37
#Mann= 5 ,-1 , 0
  4572.8     .07       0    4987     .05       0  4993.4     .07       0
  5177.4      .1       0  5337.6     .07       0
Bank Sta=4987,4993.4
XS Rating Curve= 0 ,0
Exp/Cntr=0.3,0.1

Type RM Length L Ch R = 1 ,10949   ,484,484,484
BEGIN DESCRIPTION:
Wilson Creek 23.0
END DESCRIPTION:
XS GIS Cut Line= 3
        1983775.     13899074.99        1983775.       13898725.
        1983625.     13898324.99
#Sta/Elev= 30
  4650.4 1496.99  4652.9 1496.99  4660.4 1499.15  4670.4 1498.31  4690.4  1493.1
  4722.2 1490.59  4770.4 1488.38  4822.9 1487.15    4919 1486.58  4950.4 1486.46
  4970.4 1487.07  4980.4 1484.59  4990.4 1483.36  4994.6 1478.77  4995.1 1478.27
  5000.7 1478.27  5001.2 1478.77  5015.5 1478.89  5032.4 1482.98  5064.5  1483.5
  5070.7  1484.7  5125.9 1484.34  5231.3 1485.99  5256.7 1486.68  5278.1 1488.69
  5320.8 1489.51  5342.2 1490.62  5357.3 1493.78  5374.2 1493.67  5427.6 1501.47
#Mann= 7 ,-1 , 0
  4650.4    .035       0  4722.2     .07       0  4822.9    .035       0
    4919     .07       0  4994.6     .05       0  5001.2     .07       0
  5231.3    .035       0
Bank Sta=4994.6,5001.2
XS Rating Curve= 0 ,0
Exp/Cntr=0.3,0.1