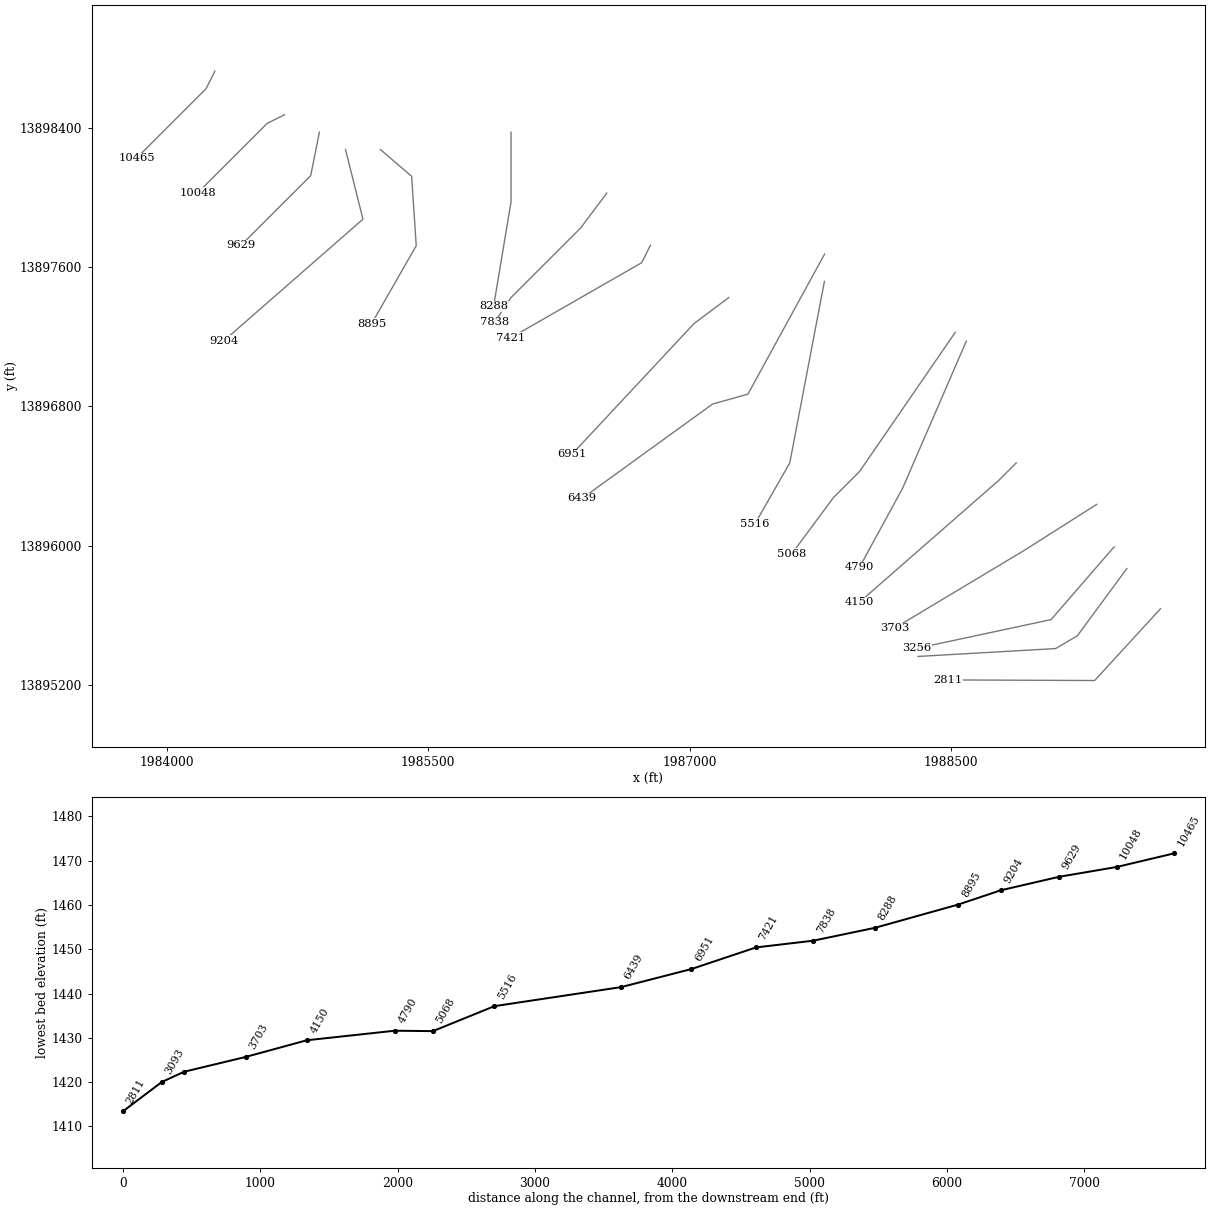
HEC-RAS study Wilson Creek.prj: Wilson Creek Base Level Engineering

--- Wilson Creek.g01 (geometry) --- (continued)

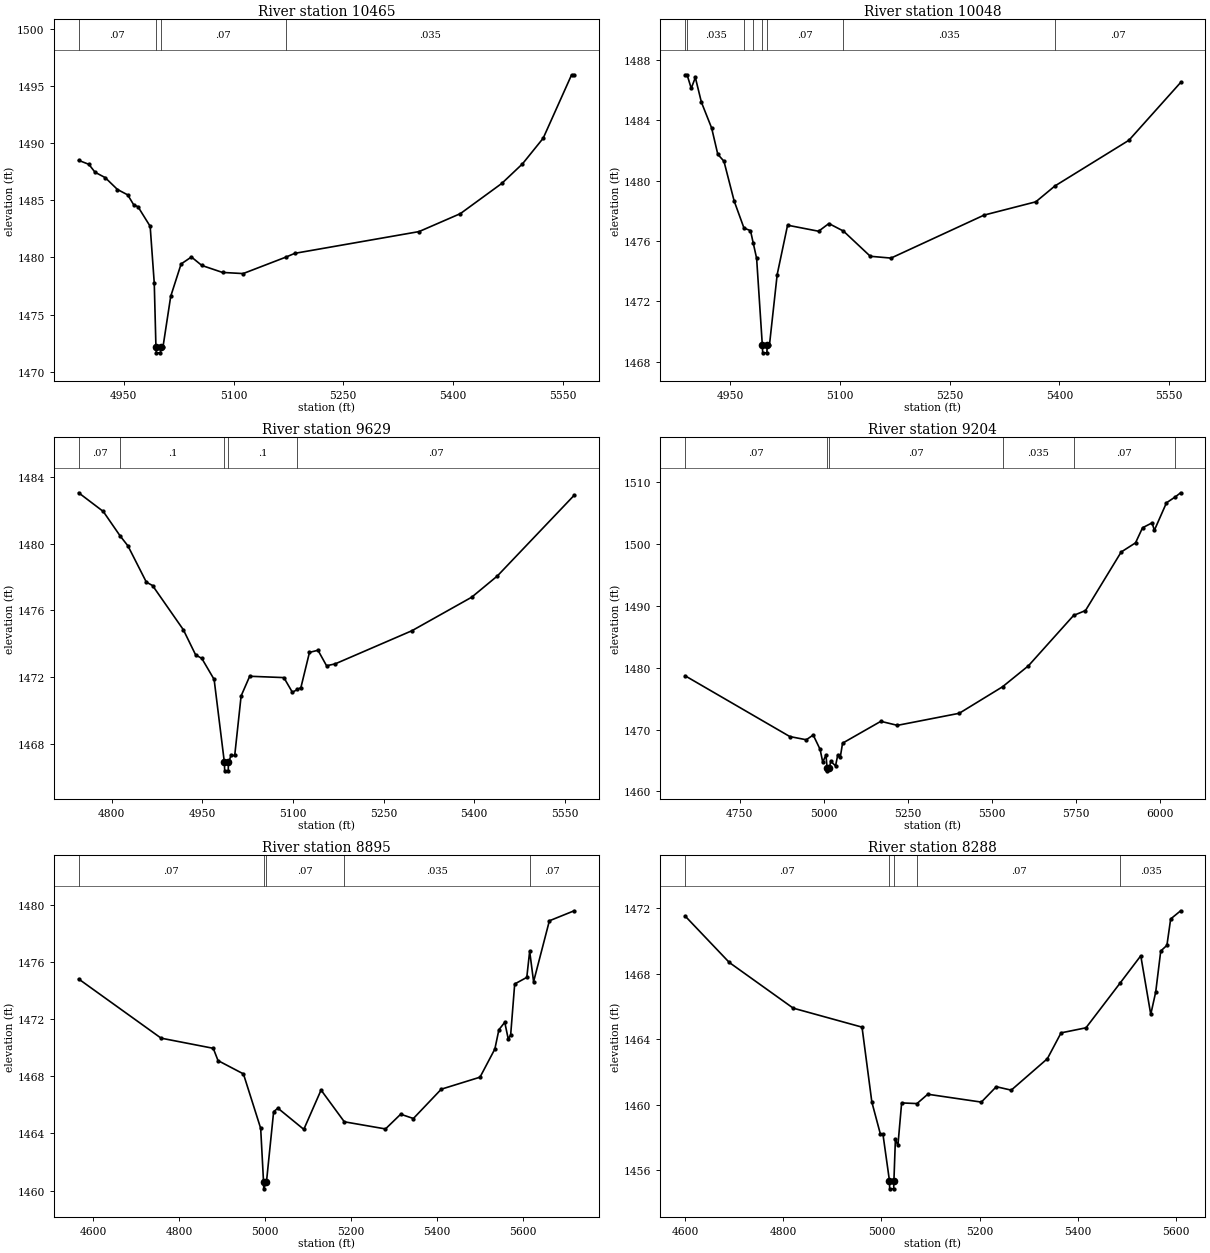
Type RM Length L Ch R = 1 ,10465   ,417,417,417
BEGIN DESCRIPTION:
Wilson Creek 22.0
END DESCRIPTION:
XS GIS Cut Line= 3
        1984275.       13898725.        1984225.       13898625.
      1983824.99     13898224.99
#Sta/Elev= 30
  4888.2 1488.49  4902.2 1488.14  4910.6 1487.45  4924.5 1486.98  4941.3 1485.94
  4955.3 1485.47  4963.7 1484.58  4969.3 1484.44    4986 1482.72  4991.6 1477.75
  4993.9 1472.16  4994.4 1471.66  5000.1 1471.66  5000.6 1472.16  5003.5 1472.16
  5014.1  1476.6  5028.3 1479.43  5042.4 1480.04  5056.6  1479.3  5084.9 1478.69
  5113.1 1478.59  5171.2 1480.02  5183.8 1480.36  5353.6 1482.26  5410.1 1483.83
  5466.7 1486.47    5495 1488.18  5523.3 1490.42  5562.2 1495.97  5565.7 1495.97
#Mann= 4 ,-1 , 0
  4888.2     .07       0  4993.9     .05       0  5000.6     .07       0
  5171.2    .035       0
Bank Sta=4993.9,5000.6
XS Rating Curve= 0 ,0
Exp/Cntr=0.3,0.1

Type RM Length L Ch R = 1 ,10048   ,419,419,419
BEGIN DESCRIPTION:
Wilson Creek 21.0
END DESCRIPTION:
XS GIS Cut Line= 3
      1984674.99     13898474.99        1984575.       13898425.
      1984174.98     13898024.98
#Sta/Elev= 30
  4888.2 1487.02  4890.9 1487.02  4896.6 1486.12  4902.2 1486.84  4910.5  1485.2
  4924.5 1483.49  4932.9 1481.75  4941.3 1481.29  4955.3 1478.65  4968.7 1476.86
  4977.6 1476.69  4981.3 1475.88    4986 1474.85  4993.8 1469.09  4994.3 1468.59
    5000 1468.59  5000.5 1469.09  5003.5 1469.09  5014.1 1473.78  5028.3 1477.05
  5070.7 1476.65  5084.8 1477.16  5104.7 1476.66  5141.4 1474.99  5169.7 1474.87
    5297 1477.72  5367.7  1478.6  5393.8 1479.65    5495 1482.68  5565.7 1486.51
#Mann= 8 ,-1 , 0
  4888.2     .07       0  4890.9    .035       0  4968.7      .1       0
  4981.3     .07       0  4993.8     .05       0  5000.5     .07       0
  5104.7    .035       0  5393.8     .07       0
Bank Sta=4993.8,5000.5
XS Rating Curve= 0 ,0
Exp/Cntr=0.3,0.1

Type RM Length L Ch R = 1 ,9629    ,425,425,425
BEGIN DESCRIPTION:
Wilson Creek 20.0
END DESCRIPTION:
XS GIS Cut Line= 3
      1984875.01     13898375.05        1984825.       13898125.
      1984424.99     13897724.99
#Sta/Elev= 30
    4745 1483.05  4785.8 1481.93    4814 1480.45  4826.6 1479.87  4857.2 1477.69
  4867.4 1477.49  4918.4 1474.84  4938.8 1473.33    4949 1473.12  4969.4 1471.86
  4986.4 1466.88  4986.9 1466.38  4992.7 1466.38  4993.2 1466.88  4997.4  1467.3
  5003.5  1467.3  5014.1 1470.87  5028.3 1472.05  5084.9 1471.97    5099 1471.09
  5107.4 1471.26  5113.1 1471.37  5127.3 1473.48  5141.4 1473.61  5155.6 1472.68
  5169.7 1472.79    5297 1474.78    5396 1476.79  5438.4 1478.06  5565.7  1482.9
#Mann= 5 ,-1 , 0
    4745     .07       0    4814      .1       0  4986.4     .05       0
  4993.2      .1       0  5107.4     .07       0
Bank Sta=4986.4,4993.2
XS Rating Curve= 0 ,0
Exp/Cntr=0.3,0.1

Type RM Length L Ch R = 1 ,9204    ,309,309,309
BEGIN DESCRIPTION:
Wilson Creek 19.0
END DESCRIPTION:
XS GIS Cut Line= 3
        1985025.     13898275.01        1985125.       13897875.
      1984325.03     13897175.02
#Sta/Elev= 30
    4587 1478.69  4898.8 1468.87  4947.8 1468.35  4968.4 1469.12    4989 1466.79
  4996.7 1464.74  5006.4 1465.88  5009.7 1463.83  5010.2 1463.33  5016.5 1463.83
  5020.7 1464.87  5034.9 1464.13  5041.6 1465.92  5049.1 1465.58  5055.8  1467.8
  5169.7 1471.33    5219 1470.68  5403.2 1472.63    5532 1476.91  5609.1  1480.3
  5743.6 1488.44    5779 1489.23  5885.3 1498.69    5928 1500.17  5948.9 1502.61
  5977.4  1503.4    5984 1502.19  6020.1 1506.64  6045.9 1507.58  6062.3 1508.26
#Mann= 6 ,-1 , 0
    4587     .07       0  5009.7     .05       0  5016.5     .07       0
    5532    .035       0  5743.6     .07       0  6045.9    .035       0
Bank Sta=5009.7,5016.5
XS Rating Curve= 0 ,0
Exp/Cntr=0.3,0.1

Type RM Length L Ch R = 1 ,8895    ,607,607,607
BEGIN DESCRIPTION:
Wilson Creek 18.0
END DESCRIPTION:
XS GIS Cut Line= 4
      1985224.96     13898275.03      1985404.52     13898121.13
      1985430.76     13897722.57        1985175.       13897275.
#Sta/Elev= 30
  4566.9  1474.8  4758.5 1470.66  4879.7 1469.95  4890.8 1469.09  4949.8 1468.16
  4989.9 1464.35  4996.5 1460.62    4997 1460.12  5003.4 1460.62    5020 1465.52
    5030 1465.76  5090.1 1464.28  5130.2 1467.03  5184.2 1464.81  5279.9 1464.31
  5315.2 1465.34  5344.7 1465.04  5409.5 1467.09  5499.5 1467.93    5534  1469.9
  5543.4 1471.25    5557 1471.77    5565 1470.62  5570.7 1470.87  5580.1 1474.45
  5608.2 1474.91  5614.9 1476.74    5624 1474.61  5660.7 1478.87  5718.3 1479.57
#Mann= 5 ,-1 , 0
  4566.9     .07       0  4996.5     .05       0  5003.4     .07       0
  5184.2    .035       0  5614.9     .07       0
Bank Sta=4996.5,5003.4
XS Rating Curve= 0 ,0
Exp/Cntr=0.3,0.1

Type RM Length L Ch R = 1 ,8288    ,450,450,450
BEGIN DESCRIPTION:
Wilson Creek 17.0
END DESCRIPTION:
XS GIS Cut Line= 3
        1985975.     13898375.04        1985975.       13897975.
        1985875.     13897375.02
#Sta/Elev= 30
  4600.4 1471.53  4690.4 1468.69  4820.4  1465.9  4960.4 1464.74  4980.4 1460.16
  4997.9 1458.19    5003 1458.19  5016.2 1455.36  5016.7 1454.86  5024.8 1454.86
  5025.3 1455.36  5028.3 1457.88  5033.4 1457.51    5041 1460.11  5072.2 1460.07
  5094.2 1460.64  5203.2 1460.16  5233.6  1461.1    5264 1460.89  5337.5 1462.81
  5365.4 1464.39  5416.1  1464.7  5486.2 1467.46  5527.6  1469.1  5547.9 1465.52
    5558 1466.89  5568.2 1469.39  5580.8 1469.74  5588.4 1471.35  5608.7 1471.85
#Mann= 5 ,-1 , 0
  4600.4     .07       0  5016.2     .05       0  5025.3     .07       0
  5072.2     .07       0  5486.2    .035       0
Bank Sta=5016.2,5025.3
XS Rating Curve= 0 ,0
Exp/Cntr=0.3,0.1

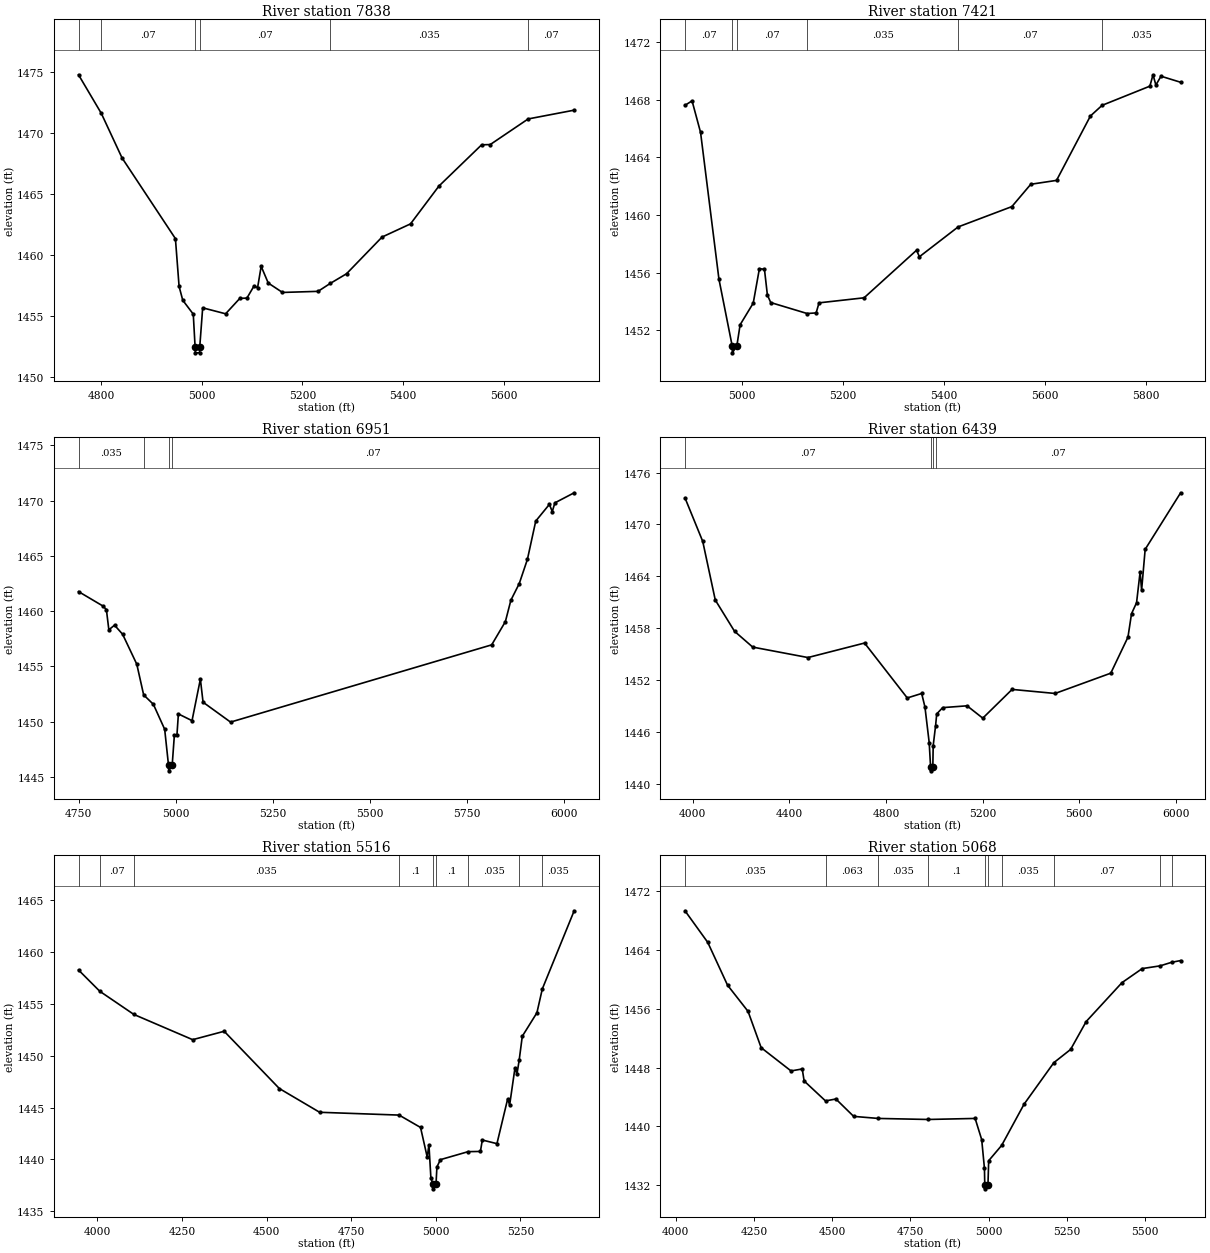
Type RM Length L Ch R = 1 ,7838    ,417,417,417
BEGIN DESCRIPTION:
Wilson Creek 16.0
END DESCRIPTION:
XS GIS Cut Line= 4
      1986525.02     13898025.02        1986375.       13897825.
        1985975.       13897425.      1985880.85     13897283.59
#Sta/Elev= 30
  4754.7 1474.74    4800 1471.58  4841.2 1467.93  4947.4 1461.31  4954.7 1457.39
    4962 1456.26  4982.9 1455.12  4986.5 1452.45    4987 1451.95  4995.3 1451.95
  4995.8 1452.45  5001.6 1455.64  5047.2 1455.15  5075.4 1456.41  5089.6 1456.44
  5103.7 1457.43  5110.8 1457.29  5117.9 1459.04    5132 1457.67  5160.3  1456.9
    5231 1456.99  5255.3 1457.64  5287.6 1458.43  5358.3 1461.44  5414.9 1462.52
  5471.4 1465.62  5556.3    1469  5573.4 1469.02  5648.8 1471.12  5740.3 1471.84
#Mann= 6 ,-1 , 0
  4754.7    .035       0    4800     .07       0  4986.5     .05       0
  4995.8     .07       0  5255.3    .035       0  5648.8     .07       0
Bank Sta=4986.5,4995.8
XS Rating Curve= 0 ,0
Exp/Cntr=0.3,0.1

Type RM Length L Ch R = 1 ,7421    ,470,470,470
BEGIN DESCRIPTION:
Wilson Creek 15.0
END DESCRIPTION:
XS GIS Cut Line= 3
      1986775.01     13897725.02        1986725.       13897625.
      1985972.28     13897193.01
#Sta/Elev= 30
  4888.2 1467.61  4902.2 1467.92    4919 1465.73  4955.3 1455.55  4981.4 1450.93
  4981.9 1450.43  4990.8 1450.93  4997.2 1452.38  5023.1 1453.88  5035.3 1456.27
  5045.3 1456.23  5051.1 1454.44  5057.7 1453.92  5129.6 1453.16  5147.4  1453.2
  5153.2  1453.9  5242.2 1454.25  5345.9 1457.55  5351.6  1457.1  5428.1 1459.17
  5534.3 1460.58  5571.7 1462.13  5622.6  1462.4  5689.6 1466.87  5712.7 1467.61
  5807.1 1468.94  5813.3 1469.73    5819 1469.02  5829.1 1469.63  5867.9 1469.21
#Mann= 6 ,-1 , 0
  4888.2     .07       0  4981.4     .05       0  4990.8     .07       0
  5129.6    .035       0  5428.1     .07       0  5712.7    .035       0
Bank Sta=4981.4,4990.8
XS Rating Curve= 0 ,0
Exp/Cntr=0.3,0.1

Type RM Length L Ch R = 1 ,6951    ,512,512,512
BEGIN DESCRIPTION:
Wilson Creek 14.0
END DESCRIPTION:
XS GIS Cut Line= 3
      1987224.98     13897424.98        1987025.       13897275.
      1986324.99     13896524.99
#Sta/Elev= 30
  4749.8 1461.77  4813.3 1460.45  4821.6 1460.13  4827.9 1458.31  4842.5 1458.73
  4863.3 1457.91  4899.8  1455.2  4917.5 1452.42  4942.5 1451.57  4971.6 1449.31
  4981.5 1446.05    4982 1445.55  4990.9 1446.05  4996.6  1448.8  5003.2  1448.8
  5006.9  1450.7    5042 1450.09  5063.5 1453.85  5070.4 1451.76  5141.2 1449.96
  5813.4 1456.95  5848.6 1459.05  5862.8 1460.99  5884.3 1462.49  5905.3 1464.68
  5926.8 1468.15  5961.9 1469.66  5969.3 1469.01  5976.1  1469.8  6025.7 1470.71
#Mann= 4 ,-1 , 0
  4749.8    .035       0  4917.5     .07       0  4981.5     .05       0
  4990.9     .07       0
Bank Sta=4981.5,4990.9
XS Rating Curve= 0 ,0
Exp/Cntr=0.3,0.1

Type RM Length L Ch R = 1 ,6439    ,923,923,923
BEGIN DESCRIPTION:
Wilson Creek 13.0
END DESCRIPTION:
XS GIS Cut Line= 4
      1987774.99     13897674.98      1987334.81     13896870.02
      1987131.36     13896812.72      1986384.04     13896271.73
#Sta/Elev= 30
  3968.5 1473.08    4042 1468.04  4093.9 1461.25  4173.6 1457.63  4248.8  1455.8
  4477.4 1454.59  4711.7 1456.27  4888.5 1449.91  4948.1 1450.43  4961.7 1448.86
  4979.3 1444.73  4984.9 1441.97  4985.4 1441.47  4994.3 1441.97  4995.8 1444.39
  5005.8 1446.72  5010.4 1448.06    5035 1448.79    5136    1449    5201 1447.57
  5322.4  1450.9  5500.3 1450.43  5730.8 1452.78  5801.9 1456.95  5816.6 1459.66
  5837.5 1460.94  5852.2 1464.51  5858.4  1462.4  5873.1 1467.12  6019.9 1473.67
#Mann= 4 ,-1 , 0
  3968.5     .07       0  4984.9     .05       0  4994.3     .07       0
  5005.8     .07       0
Bank Sta=4984.9,4994.3
XS Rating Curve= 0 ,0
Exp/Cntr=0.3,0.1

Type RM Length L Ch R = 1 ,5516    ,448,448,448
BEGIN DESCRIPTION:
Wilson Creek 12.0
END DESCRIPTION:
XS GIS Cut Line= 3
      1987773.87     13897517.91        1987575.       13896475.
      1987375.01     13896125.01
#Sta/Elev= 30
    3944 1458.24  4006.9 1456.19  4107.6 1453.96  4281.4 1451.53  4374.5 1452.34
  4537.4 1446.83  4656.6 1444.54  4891.5 1444.27  4954.8 1443.08  4974.5 1440.23
  4979.6 1441.41  4985.3 1438.26  4990.5 1437.67    4991 1437.17  5000.6 1437.67
  5003.2 1439.28  5013.6 1439.98  5095.5 1440.75  5131.7 1440.77  5137.4 1441.87
  5180.6 1441.52  5212.3 1445.83  5218.1 1445.24  5233.9 1448.82  5239.7 1448.21
  5246.3 1449.56  5255.5 1451.86  5298.7 1454.12  5314.7 1456.42  5408.8 1463.94
#Mann= 9 ,-1 , 0
    3944    .035       0  4006.9     .07       0  4107.6    .035       0
  4891.5      .1       0  4990.5     .05       0  5000.6      .1       0
  5095.5    .035       0  5246.3     .07       0  5314.7    .035       0
Bank Sta=4990.5,5000.6
XS Rating Curve= 0 ,0
Exp/Cntr=0.3,0.1

Type RM Length L Ch R = 1 ,5068    ,278,278,278
BEGIN DESCRIPTION:
Wilson Creek 11.0
END DESCRIPTION:
XS GIS Cut Line= 4
      1988524.99     13897224.99        1987975.       13896425.
        1987825.       13896275.      1987586.17     13895952.31
#Sta/Elev= 30
  4029.2 1469.29    4102    1465  4165.2 1459.19  4230.8 1455.63  4272.7  1450.7
  4368.2 1447.54    4404 1447.81  4410.1 1446.18  4478.4 1443.47  4511.6 1443.73
  4568.4 1441.37  4647.1 1441.09  4806.3 1440.95  4956.7 1441.09  4977.7 1438.21
  4986.5  1434.3  4987.5 1432.03    4988 1431.53  4997.7 1432.03    5000 1435.35
  5041.5 1437.43  5113.2 1443.03  5208.2 1448.66  5261.9 1450.46  5311.7 1454.25
  5426.1 1459.53  5490.8 1461.44    5548 1461.81  5584.6 1462.29  5613.6 1462.53
#Mann= 10 ,-1 , 0
  4029.2    .035       0  4478.4    .063       0  4647.1    .035       0
  4806.3      .1       0  4987.5     .05       0  4997.7      .1       0
  5041.5    .035       0  5208.2     .07       0    5548    .035       0
  5584.6     .07       0
Bank Sta=4987.5,4997.7
XS Rating Curve= 0 ,0
Exp/Cntr=0.3,0.1

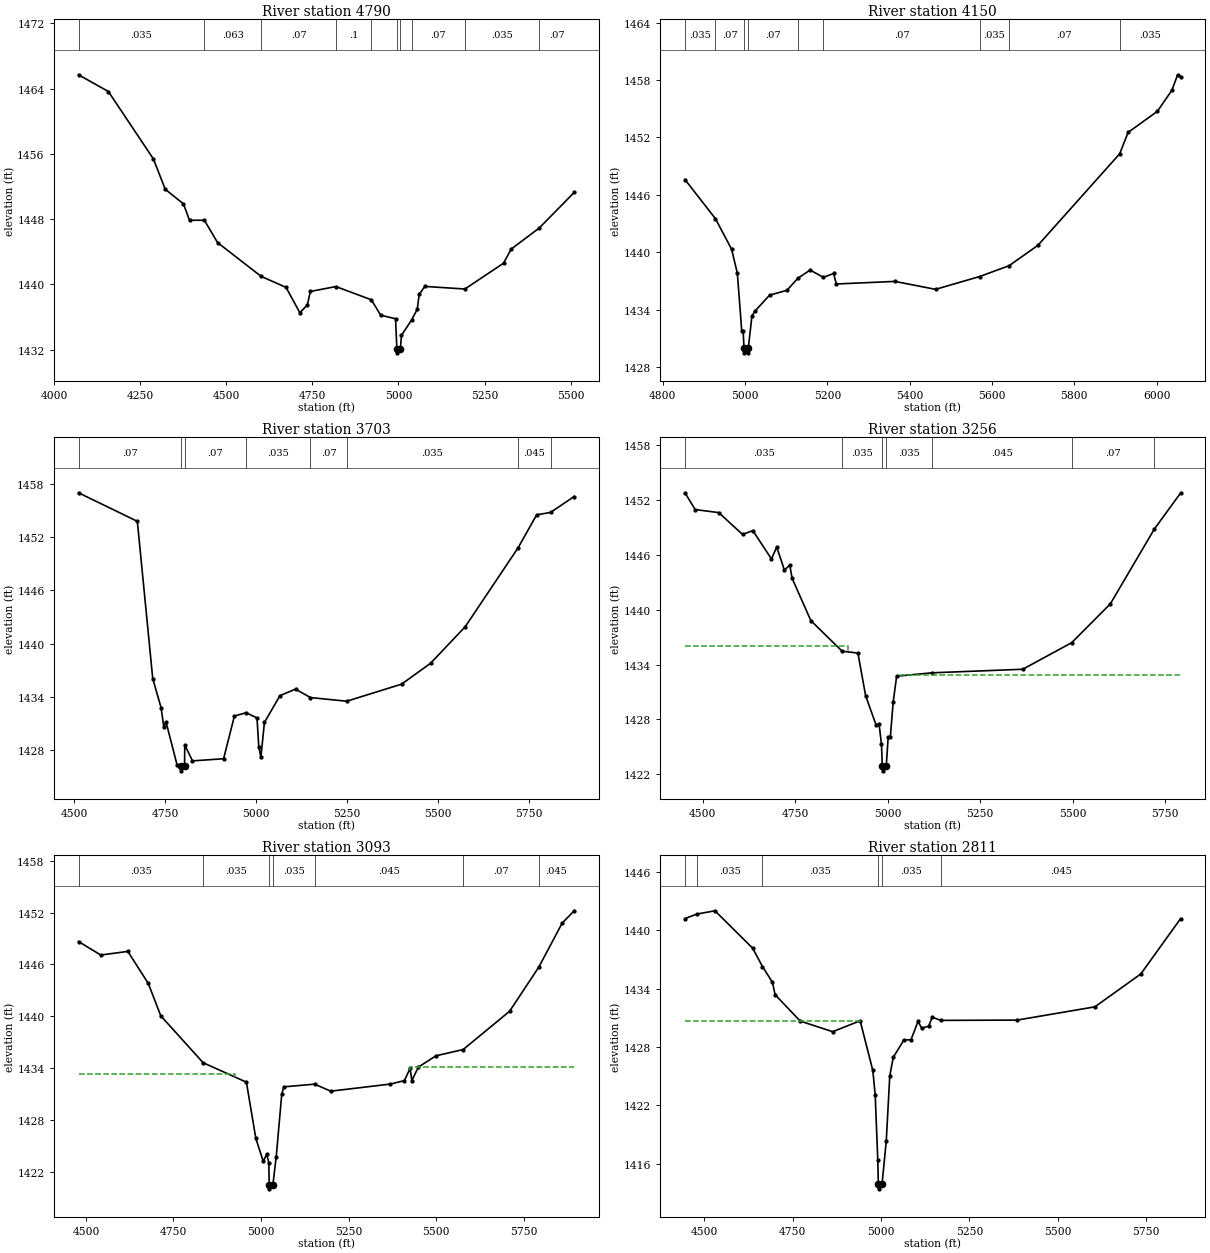
Type RM Length L Ch R = 1 ,4790    ,640,640,640
BEGIN DESCRIPTION:
Wilson Creek 10.0
END DESCRIPTION:
XS GIS Cut Line= 3
      1988588.37     13897174.57      1988223.05     13896330.25
        1987975.       13895875.
#Sta/Elev= 30
  4071.4 1465.69  4158.1 1463.64  4288.7 1455.38  4323.1 1451.66    4376 1449.87
  4393.5 1447.86  4436.6 1447.87  4474.9 1445.13    4601    1441  4673.7 1439.64
  4713.8 1436.53  4735.6  1437.5  4744.1 1439.14  4818.3 1439.74  4921.2 1438.12
  4948.4 1436.23  4991.4  1435.8  4995.3 1432.12  4995.8 1431.62  5005.5 1432.12
  5008.7 1433.77  5037.8 1435.63  5054.3 1436.94  5060.2 1438.79  5076.4 1439.76
  5192.6 1439.44  5304.8  1442.6    5327 1444.33  5408.6 1446.92  5509.8 1451.27
#Mann= 10 ,-1 , 0
  4071.4    .035       0  4436.6    .063       0    4601     .07       0
  4818.3      .1       0  4921.2     .07       0  4995.3     .05       0
  5005.5     .07       0  5037.8     .07       0  5192.6    .035       0
  5408.6     .07       0
Bank Sta=4995.3,5005.5
XS Rating Curve= 0 ,0
Exp/Cntr=0.3,0.1

Type RM Length L Ch R = 1 ,4150    ,447,447,447
BEGIN DESCRIPTION:
Wilson Creek 9.0
END DESCRIPTION:
XS GIS Cut Line= 3
      1988875.02     13896475.02        1988775.       13896375.
      1987974.97     13895674.98
#Sta/Elev= 30
  4854.1 1447.59  4928.1  1443.5  4967.3 1440.32  4981.4 1437.79    4992 1431.78
  4995.5 1431.78  4997.5 1429.97    4998 1429.47  5007.4 1429.47  5007.9 1429.97
  5016.9 1433.33  5023.5  1433.8  5059.6  1435.5  5101.8 1436.01  5128.8 1437.28
  5158.3 1438.13  5190.5 1437.36  5215.3 1437.77  5221.9 1436.67  5364.3 1436.94
    5463 1436.11  5570.1 1437.45  5641.6 1438.58  5711.7 1440.71  5910.5 1450.29
  5930.9 1452.52  6002.1 1454.73  6037.2 1456.92  6051.4 1458.55  6058.6 1458.36
#Mann= 9 ,-1 , 0
  4854.1    .035       0  4928.1     .07       0  4997.5     .05       0
  5007.9     .07       0  5128.8    .035       0  5190.5     .07       0
  5570.1    .035       0  5641.6     .07       0  5910.5    .035       0
Bank Sta=4997.5,5007.9
XS Rating Curve= 0 ,0
Exp/Cntr=0.3,0.1

Type RM Length L Ch R = 1 ,3703    ,447,447,447
BEGIN DESCRIPTION:
Wilson Creek 8.0
END DESCRIPTION:
XS GIS Cut Line= 3
      1989336.57     13896236.67        1988925.       13895975.
      1988174.96     13895524.98
#Sta/Elev= 30
  4512.3 1456.96    4674 1453.75  4716.3 1436.07  4739.3 1432.79  4746.8 1430.59
  4752.7 1431.21  4783.2 1426.36  4793.3 1426.19  4793.8 1425.69  4803.7 1426.19
  4804.4  1428.6  4825.6 1426.81  4911.1 1427.05  4940.8 1431.85  4973.3 1432.23
  5002.9 1431.63  5007.8 1428.41  5013.6 1427.21  5023.3 1431.13  5066.1 1434.15
  5108.9 1434.88  5149.7 1433.93  5249.5 1433.52  5400.4 1435.44  5480.1 1437.79
  5575.3  1441.9  5720.6 1450.78  5771.6 1454.48  5809.8 1454.75  5874.7 1456.54
#Mann= 8 ,-1 , 0
  4512.3     .07       0  4793.3    .035       0  4803.7     .07       0
  4973.3    .035       0  5149.7     .07       0  5249.5    .035       0
  5720.6    .045       0  5809.8    .035       0
Bank Sta=4793.3,4803.7
XS Rating Curve= 0 ,0
Exp/Cntr=0.3,0.1

Type RM Length L Ch R = 1 ,3256    ,163,163,163
BEGIN DESCRIPTION:
Wilson Creek 7.0
END DESCRIPTION:
XS GIS Cut Line= 3
      1989436.49     13895992.65        1989075.       13895575.
      1988305.35     13895410.02
#Sta/Elev= 30
  4452.6  1452.8  4480.2 1450.96  4543.8 1450.63  4608.2 1448.24  4635.9 1448.66
  4686.3 1445.56  4700.6 1446.86  4721.4 1444.32  4735.7 1444.89  4742.3 1443.42
  4792.7 1438.81  4877.2 1435.46    4920 1435.25  4940.8 1430.58  4969.3 1427.35
    4977 1427.54  4983.6 1425.26    4986 1422.86  4986.5 1422.36  4996.5 1422.86
  5001.7 1426.03  5007.5 1426.03  5015.2 1429.85  5024.6 1432.72  5119.8 1433.09
  5365.4 1433.48  5497.7 1436.39  5602.3 1440.65  5720.9 1448.82  5792.1 1452.78
#Mann= 7 ,-1 , 0
  4452.6    .035       0  4877.2    .035       0    4986    .035       0
  4996.5    .035       0  5119.8    .045       0  5497.7     .07       0
  5720.9    .045       0
#XS Ineff= 2 , 0
         4894.39 1436.03 5032.51          1432.8
Permanent Ineff=
       F       F
Bank Sta=4986,4996.5
XS Rating Curve= 0 ,0
Exp/Cntr=0.3,0.1

Type RM Length L Ch R = 1 ,3093    ,282,282,282
BEGIN DESCRIPTION:
Mapping XS df8fdff5
END DESCRIPTION:
XS GIS Cut Line= 4
      1989509.93     13895868.21      1989225.66     13895481.96
      1989101.18     13895408.56      1988310.77     13895363.24
#Sta/Elev= 30
  4478.7 1448.65  4542.3 1447.09  4619.5 1447.51  4678.1  1443.8  4713.6 1440.06
  4834.7 1434.63  4958.3 1432.38  4985.2 1425.87  5006.4 1423.22  5016.3 1424.05
  5022.1 1423.08  5023.5 1420.54    5024 1420.04    5034 1420.54  5043.5 1423.77
  5059.2 1430.97    5065 1431.84  5153.2 1432.15  5199.1 1431.34  5369.4 1432.16
  5409.5 1432.56  5425.8 1433.97  5430.8 1432.57  5449.5 1434.12  5499.6 1435.43
  5577.5 1436.16    5710 1440.58  5793.3 1445.68  5860.2 1450.78  5894.5 1452.21
#Mann= 7 ,-1 , 0
  4478.7    .035       0  4834.7    .035       0  5023.5    .035       0
    5034    .035       0  5153.2    .045       0  5577.5     .07       0
  5793.3    .045       0
#XS Ineff= 2 , 0
         4925.56 1433.36 5424.22         1434.09
Permanent Ineff=
       F       F
Bank Sta=5023.5,5034
XS Rating Curve= 0 ,0
Exp/Cntr=0.3,0.1

Type RM Length L Ch R = 1 ,2811    ,506,506,506
BEGIN DESCRIPTION:
Wilson Creek 6.0
END DESCRIPTION:
XS GIS Cut Line= 3
      1989702.83     13895637.22        1989325.       13895225.
      1988482.49     13895228.37
#Sta/Elev= 30
  4445.4 1441.18  4478.8 1441.64  4530.1 1441.98  4636.8 1438.14  4664.5 1436.26
  4692.9 1434.63  4700.3 1433.37  4771.2 1430.66  4863.1 1429.57  4940.8 1430.69
  4976.5  1425.6  4983.3 1423.12  4990.7 1416.37  4992.2 1413.94  4992.7 1413.44
  5002.7 1413.94  5014.6 1418.33  5024.6 1425.05  5034.6 1426.96  5064.6 1428.72
  5084.6 1428.74  5104.6 1430.64  5114.6 1429.93  5134.6 1430.14  5144.6 1431.06
  5168.9 1430.73  5384.6 1430.76  5604.6 1432.12  5734.6  1435.5  5847.1 1441.18
#Mann= 6 ,-1 , 0
  4445.4     .07       0  4478.8    .035       0  4664.5    .035       0
  4992.2    .035       0  5002.7    .035       0  5168.9    .045       0
#XS Ineff= 2 , 0
          4941.7 1430.63
Permanent Ineff=
       F       F
Bank Sta=4992.2,5002.7
XS Rating Curve= 0 ,0
Exp/Cntr=0.3,0.1