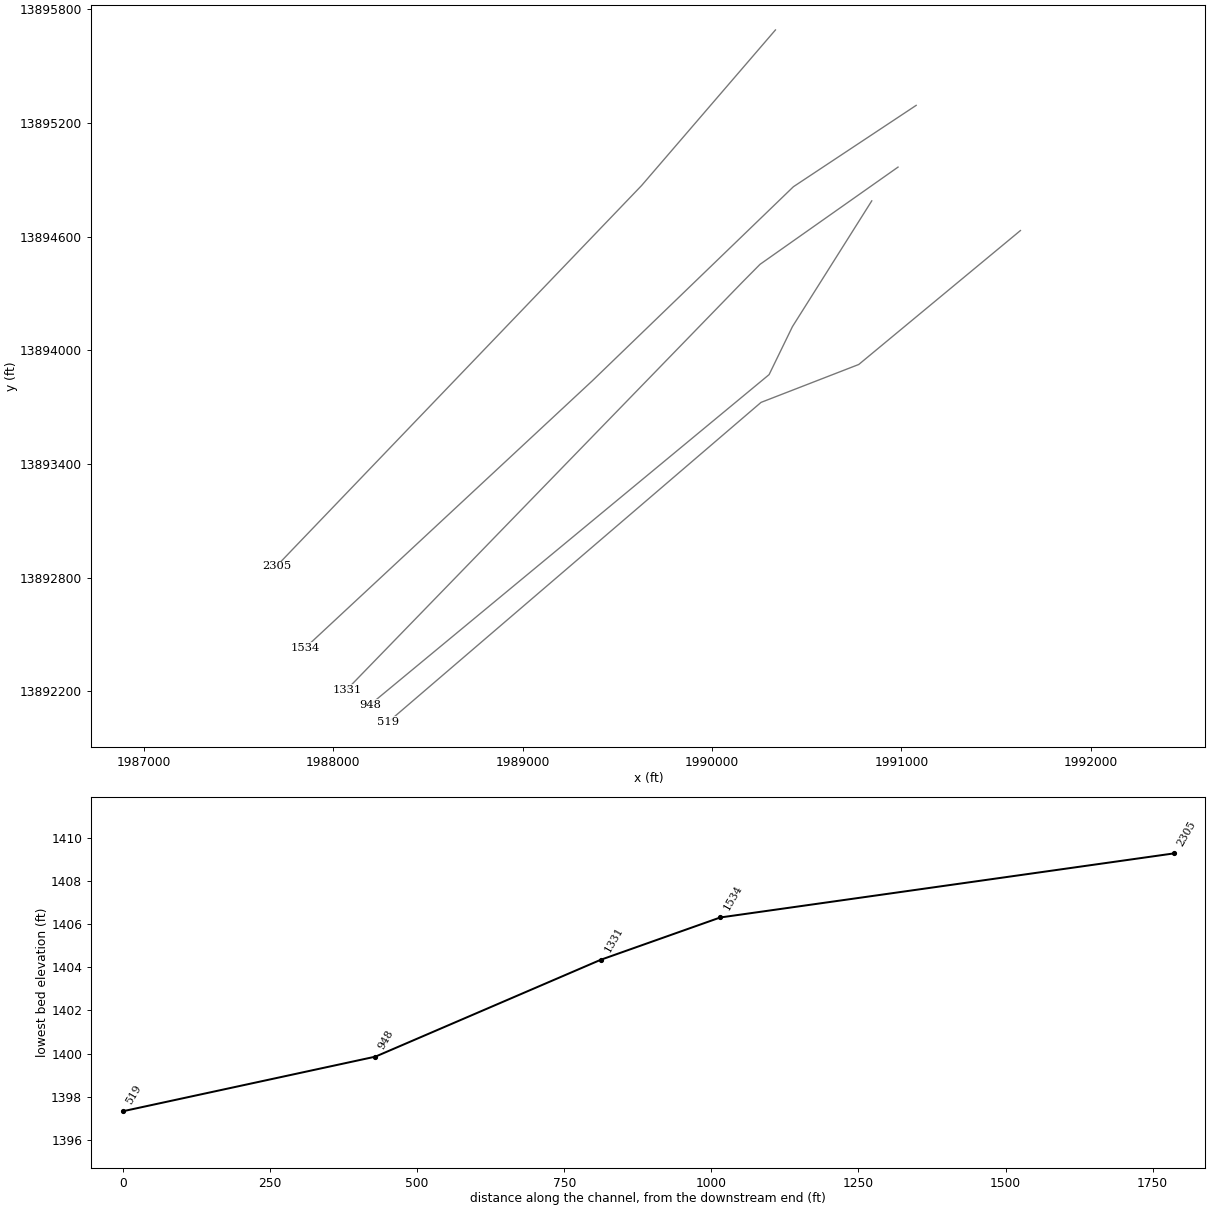
HEC-RAS study Wilson Creek.prj: Wilson Creek Base Level Engineering

--- Wilson Creek.g01 (geometry) --- (continued)

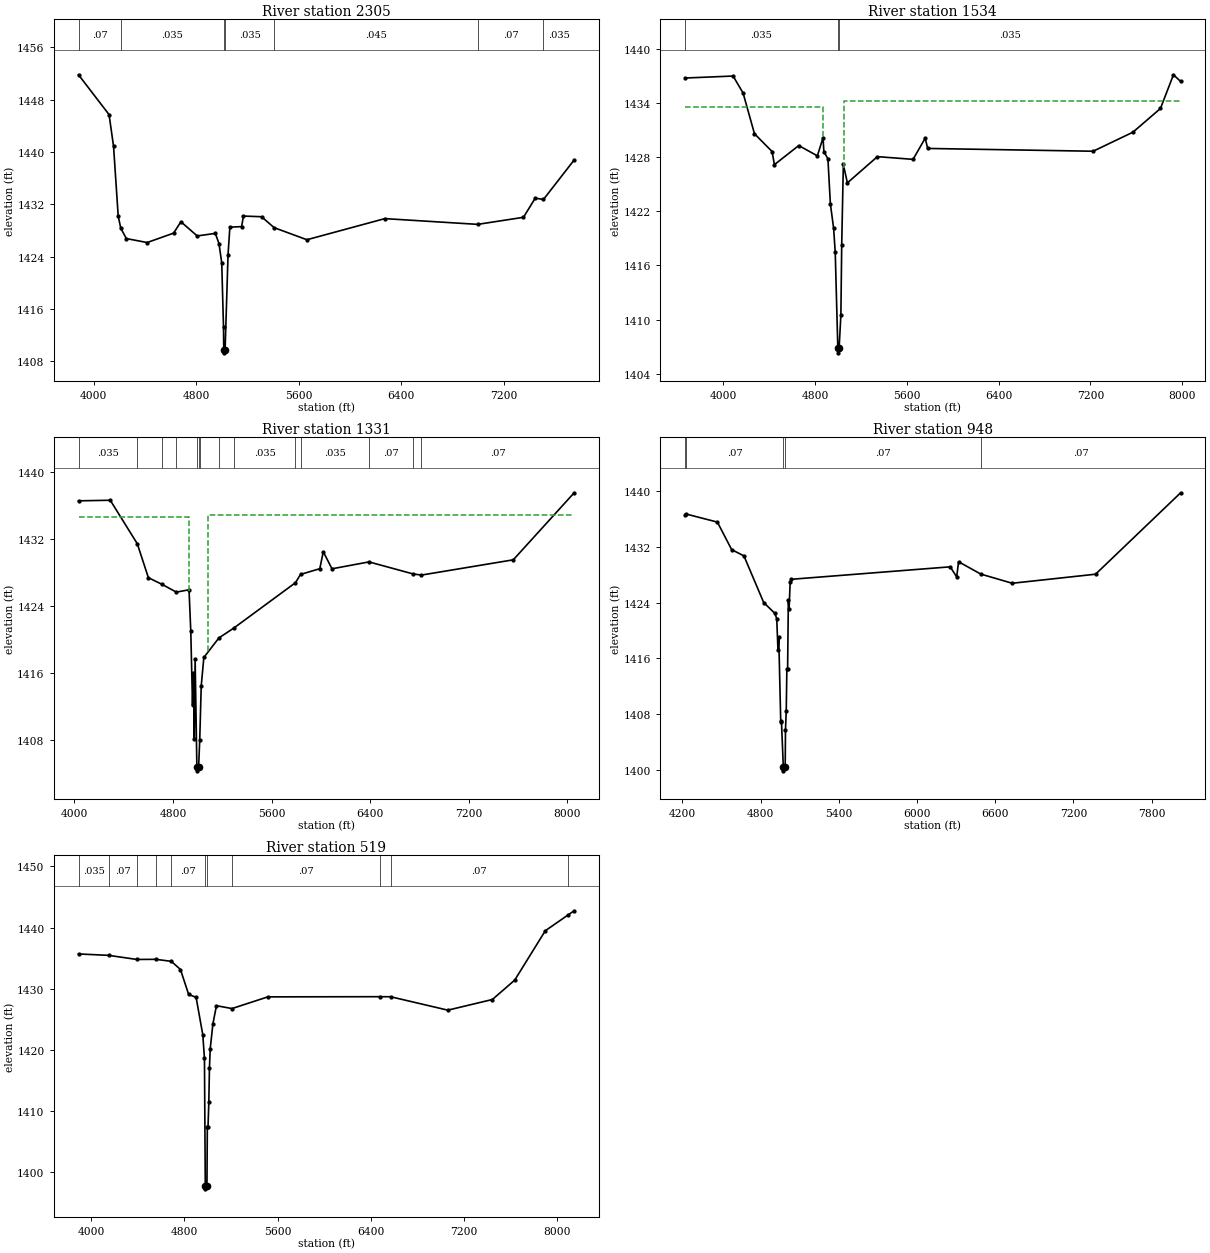
Type RM Length L Ch R = 1 ,2305    ,771,771,771
BEGIN DESCRIPTION:
Wilson Creek 5.0
END DESCRIPTION:
XS GIS Cut Line= 3
      1990335.18      13895691.2      1989628.61     13894869.82
      1987700.54     13892859.69
#Sta/Elev= 30
  3881.5 1451.81    4120 1445.72  4155.1 1440.85  4191.3 1430.19  4211.6 1428.33
  4254.9 1426.76  4417.4 1426.15  4623.6 1427.59  4680.7 1429.33    4808 1427.16
  4949.5 1427.55    4978 1425.99  4999.4 1423.04  5013.2  1413.2  5015.1 1409.78
  5015.6 1409.28  5025.7 1409.78  5048.7 1424.32  5062.9  1428.5  5154.7 1428.59
  5168.9  1430.2  5310.4  1430.1  5407.9 1428.43  5664.2 1426.58  6272.4 1429.81
  6997.1 1428.93  7354.5 1430.01  7446.4 1432.94  7510.6 1432.74  7750.3 1438.78
#Mann= 7 ,-1 , 0
  3881.5     .07       0  4211.6    .035       0  5015.1    .035       0
  5025.7    .035       0  5407.9    .045       0  6997.1     .07       0
  7510.6    .035       0
#XS Ineff= 2 , 0
                          5186.1            1430
Permanent Ineff=
       F       F
Bank Sta=5015.1,5025.7
XS Rating Curve= 0 ,0
Exp/Cntr=0.3,0.1

Type RM Length L Ch R = 1 ,1534    ,203,203,203
BEGIN DESCRIPTION:
Wilson Creek 4.0
END DESCRIPTION:
XS GIS Cut Line= 4
      1991078.19     13895293.03      1990430.04     13894863.48
      1989368.61     13893839.07      1987852.54     13892428.79
#Sta/Elev= 30
  3664.3 1436.79  4084.1 1437.01  4171.3 1435.12  4270.5 1430.61  4423.9 1428.64
  4444.4 1427.18  4656.6  1429.3  4819.2 1428.16  4868.6 1430.18  4875.8 1428.62
  4911.1 1427.83  4932.4 1422.84  4960.7 1420.14  4974.9 1417.47  4997.6 1406.81
  4998.1 1406.31  5008.6 1406.81  5024.2 1410.51  5031.4 1418.29  5045.6  1427.2
  5080.8 1425.16  5342.5 1428.07  5653.7 1427.77  5759.7 1430.12  5781.1 1428.98
  7224.3 1428.67  7571.2 1430.78  7811.6 1433.41  7924.9 1437.15  7987.6 1436.41
#Mann= 3 ,-1 , 0
  3664.3    .035       0  4997.6    .035       0  5008.6    .035       0
#XS Ineff= 2 , 0
         4866.59 1433.55 5051.57         1434.29
Permanent Ineff=
       F       F
Bank Sta=4997.6,5008.6
XS Rating Curve= 0 ,0
Exp/Cntr=0.3,0.1

Type RM Length L Ch R = 1 ,1331    ,383,383,383
BEGIN DESCRIPTION:
Wilson Creek 3.0
END DESCRIPTION:
XS GIS Cut Line= 4
      1990982.42     13894967.08      1990254.03     13894453.93
      1990160.85     13894359.87      1988072.61     13892209.04
#Sta/Elev= 30
  4032.9 1436.53  4290.5  1436.6    4510 1431.41  4599.7 1427.37  4708.7 1426.59
  4826.7 1425.65  4929.5 1425.93  4943.7 1421.02  4957.8  1412.2  4964.9 1415.96
    4972 1408.15    4979 1417.65  4993.1 1404.85  4993.6 1404.35  5007.3 1404.85
  5016.4 1408.05  5028.5 1414.48  5049.7 1417.86  5171.8 1420.19  5291.3 1421.35
  5792.9 1426.77  5834.4 1427.76  5990.3 1428.44  6018.6 1430.46  6089.3 1428.43
  6389.6 1429.25  6746.8 1427.82  6814.4 1427.68  7560.2  1429.5  8054.1 1437.49
#Mann= 14 ,-1 , 0
  4032.9    .035       0    4510     .07       0  4708.7    .035       0
  4826.7     .07       0  4993.1     .05       0  5007.3     .07       0
  5016.4    .035       0  5171.8     .07       0  5291.3    .035       0
  5792.9     .07       0  5834.4    .035       0  6389.6     .07       0
  6746.8    .035       0  6814.4     .07       0
#XS Ineff= 2 , 0
         4930.49 1434.63 5087.44         1434.84
Permanent Ineff=
       F       F
Bank Sta=4993.1,5007.3
XS Rating Curve= 0 ,0
Exp/Cntr=0.3,0.1

Type RM Length L Ch R = 1 ,948     ,429,429,429
BEGIN DESCRIPTION:
Wilson Creek 2.0
END DESCRIPTION:
XS GIS Cut Line= 4
      1990843.67     13894788.72        1990425.       13894125.
      1990301.67     13893871.49      1988193.15     13892127.12
#Sta/Elev= 30
  4219.2 1436.63  4227.8 1436.73  4467.9 1435.57  4577.3 1431.62  4671.5 1430.72
  4823.3 1424.02  4909.4 1422.46  4923.3  1421.7  4932.7 1417.23  4938.6  1419.1
  4953.9 1406.96  4959.8 1406.81  4973.9 1400.36  4974.4 1399.86  4988.1 1400.36
  4990.4 1405.71  4996.3 1408.51    5001 1414.52  5006.7 1414.52  5012.4 1424.32
    5018 1423.13  5026.2  1426.9    5035 1427.36  6254.6 1429.15  6304.1  1427.7
  6318.5 1429.88  6488.5 1428.11  6730.1 1426.79  7369.6 1428.09  8022.4 1439.78
#Mann= 5 ,-1 , 0
  4219.2    .035       0  4227.8     .07       0  4973.9     .05       0
  4988.1     .07       0  6488.5     .07       0
Bank Sta=4973.9,4988.1
XS Rating Curve= 0 ,0
Exp/Cntr=0.3,0.1

Type RM Length L Ch R = 1 ,519     ,0,0,0
BEGIN DESCRIPTION:
Wilson Creek 1.0
END DESCRIPTION:
XS GIS Cut Line= 4
       1991628.6     13894632.11        1990775.       13893925.
      1990259.19     13893724.92       1988292.2     13892038.74
#Sta/Elev= 30
  3891.3 1435.69  4149.9 1435.46  4392.5 1434.79    4556 1434.81  4687.8 1434.48
    4766 1433.15  4836.3 1429.07  4900.1 1428.61  4957.4 1422.51  4971.8 1418.68
    4979 1397.83  4979.5 1397.33  4993.2 1397.83  4996.5 1407.41  5002.4 1407.41
  5009.3  1411.5  5014.7 1417.07  5021.2 1420.19  5044.6 1424.31  5074.8 1427.24
    5208 1426.77  5515.6 1428.68    6481 1428.71  6569.2  1428.7  7059.9 1426.51
    7442 1428.25  7633.9 1431.42  7896.2 1439.48  8088.6 1442.02  8143.8 1442.74
#Mann= 11 ,-1 , 0
  3891.3    .035       0  4149.9     .07       0  4392.5    .035       0
    4556     .07       0  4687.8     .07       0    4979     .05       0
  4993.2     .07       0    5208     .07       0    6481    .035       0
  6569.2     .07       0  8088.6    .035       0
Bank Sta=4979,4993.2
XS Rating Curve= 0 ,0
Exp/Cntr=0.3,0.1

Chan Stop Cuts=-1
Use User Specified Reach Order=0
Composite Channel Slope=5