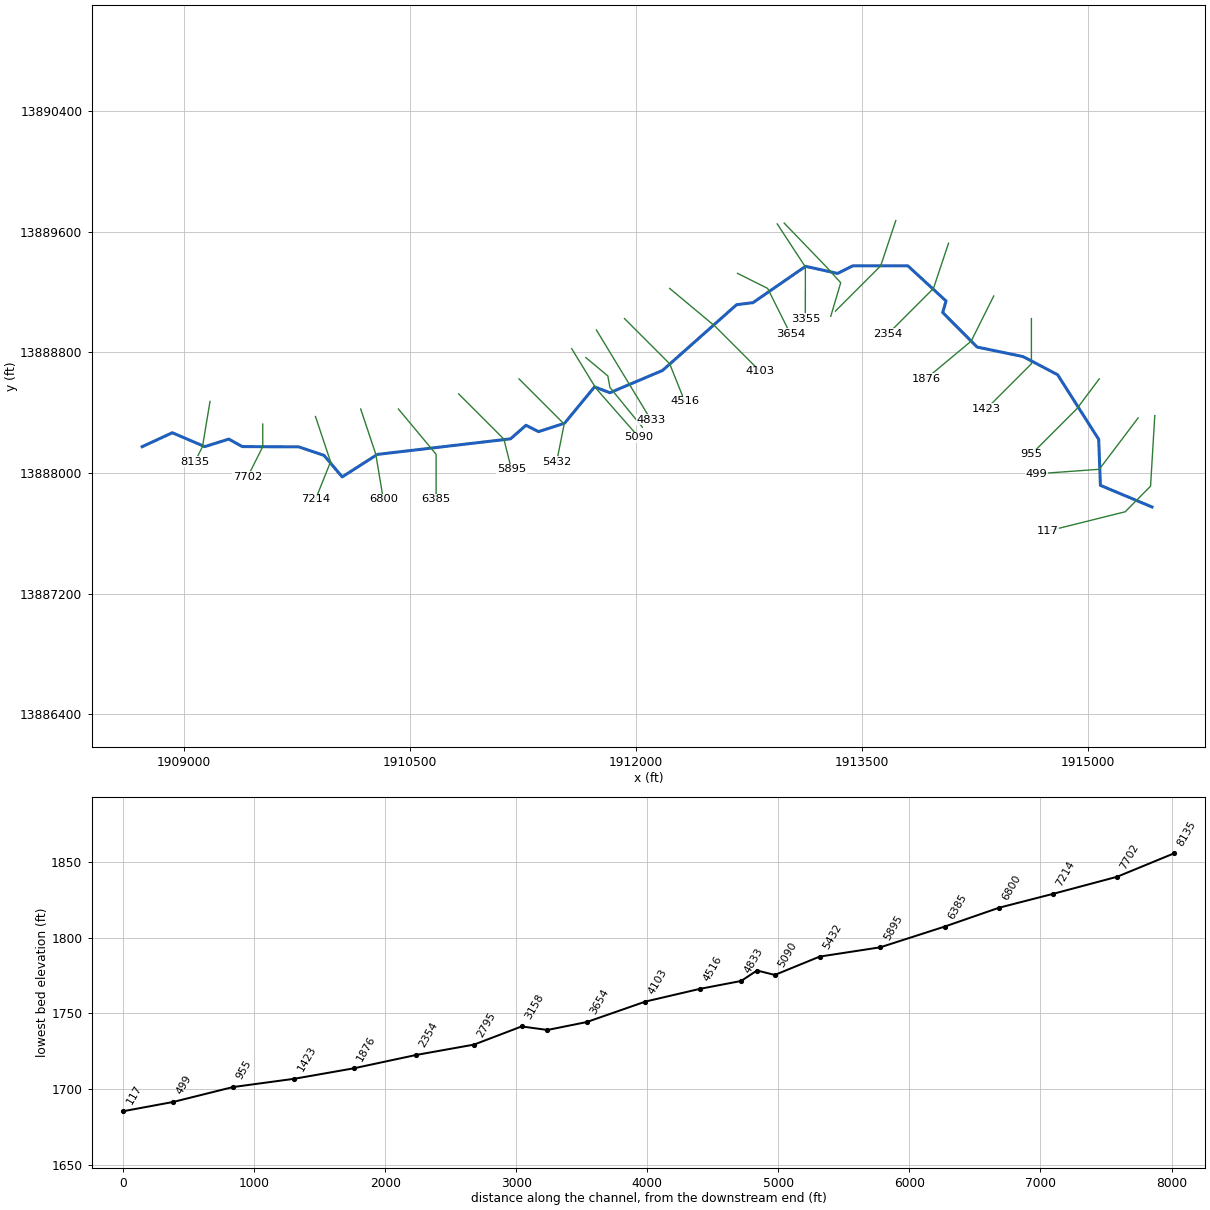
--- Wolf Creek.prj (project) ---

Proj Title=Wolf Creek Base Level Engineering
Current Plan=p01
Default Exp/Contr=0.3,0.1
English Units
Geom File=g01
Flow File=f01
Plan File=p01
BEGIN DESCRIPTION:
Wolf Creek
END DESCRIPTION:

--- Wolf Creek.p01 (plan) ---

Plan Title=Multiple Run
Short Identifier=Multiple
Geom File=g01
Flow File=f01
Subcritical Flow
K Sum by GR= 0
Std Step Tol= 0.01
Critical Tol= 0.01
Num of Std Step Trials= 20
Max Error Tol= 0.3
Flow Tol Ratio= 0.001
Split Flow NTrial= 30
Split Flow Tol= 0.02
Split Flow Ratio= 0.02
Log Output Level= 0
Friction Slope Method= 1
Unsteady Friction Slope Method= 2
Unsteady Bridges Friction Slope Method= 1
Parabolic Critical Depth
Global Vel Dist=  1 , 1 , 1
Global Log Level= 0
CheckData=True
Encroach Param= -1, 0, 0, 0
BEGIN DESCRIPTION:
Multiple Run
END DESCRIPTION:

--- Wolf Creek.f01 (steady flow) ---

Flow Title=Multiple
Number of Profiles=7
Profile Names=10-year,25-year,50-year,1pct_min,100-year,1pct_plu,500-year
River Rch & RM= Wolf Creek,Reach-1,8135
    1548    2696    3813    2608    5205   10384    9571
Boundary for River Rch & Prof#=Wolf Creek,Reach-1,1
Up Type=0
Dn Type=3
Dn Slope=0.005
Boundary for River Rch & Prof#=Wolf Creek,Reach-1,2
Up Type=0
Dn Type=3
Dn Slope=0.005
Boundary for River Rch & Prof#=Wolf Creek,Reach-1,3
Up Type=0
Dn Type=3
Dn Slope=0.005
Boundary for River Rch & Prof#=Wolf Creek,Reach-1,4
Up Type=0
Dn Type=3
Dn Slope=0.005
Boundary for River Rch & Prof#=Wolf Creek,Reach-1,5
Up Type=0
Dn Type=3
Dn Slope=0.005
Boundary for River Rch & Prof#=Wolf Creek,Reach-1,6
Up Type=0
Dn Type=3
Dn Slope=0.005
Boundary for River Rch & Prof#=Wolf Creek,Reach-1,7
Up Type=0
Dn Type=3
Dn Slope=0.005

--- Wolf Creek.g01 (geometry) ---

Geom Title=Existing Conditions

River Reach=Wolf Creek,Reach-1
Reach XY= 30
      1908725.00     13888175.00      1908925.00     13888267.45
      1909140.27     13888175.38      1909300.00     13888225.40
      1909388.91     13888175.70      1909764.50     13888173.78
      1909931.45     13888117.25      1910052.12     13887974.40
      1910285.50     13888123.80      1911169.15     13888227.07
      1911271.60     13888317.17      1911354.79     13888274.79
      1911527.44     13888330.52      1911726.44     13888571.90
      1911828.31     13888533.07      1912177.53     13888680.76
      1912668.83     13889117.14      1912777.42     13889130.54
      1913126.72     13889371.66      1913338.80     13889324.52
      1913439.13     13889374.70      1913804.94     13889375.20
      1914058.61     13889141.67      1914036.24     13889065.00
      1914265.32     13888835.76      1914569.55     13888772.82
      1914798.89     13888652.28      1915071.45     13888223.53
      1915082.67     13887918.48      1915425.00     13887775.00

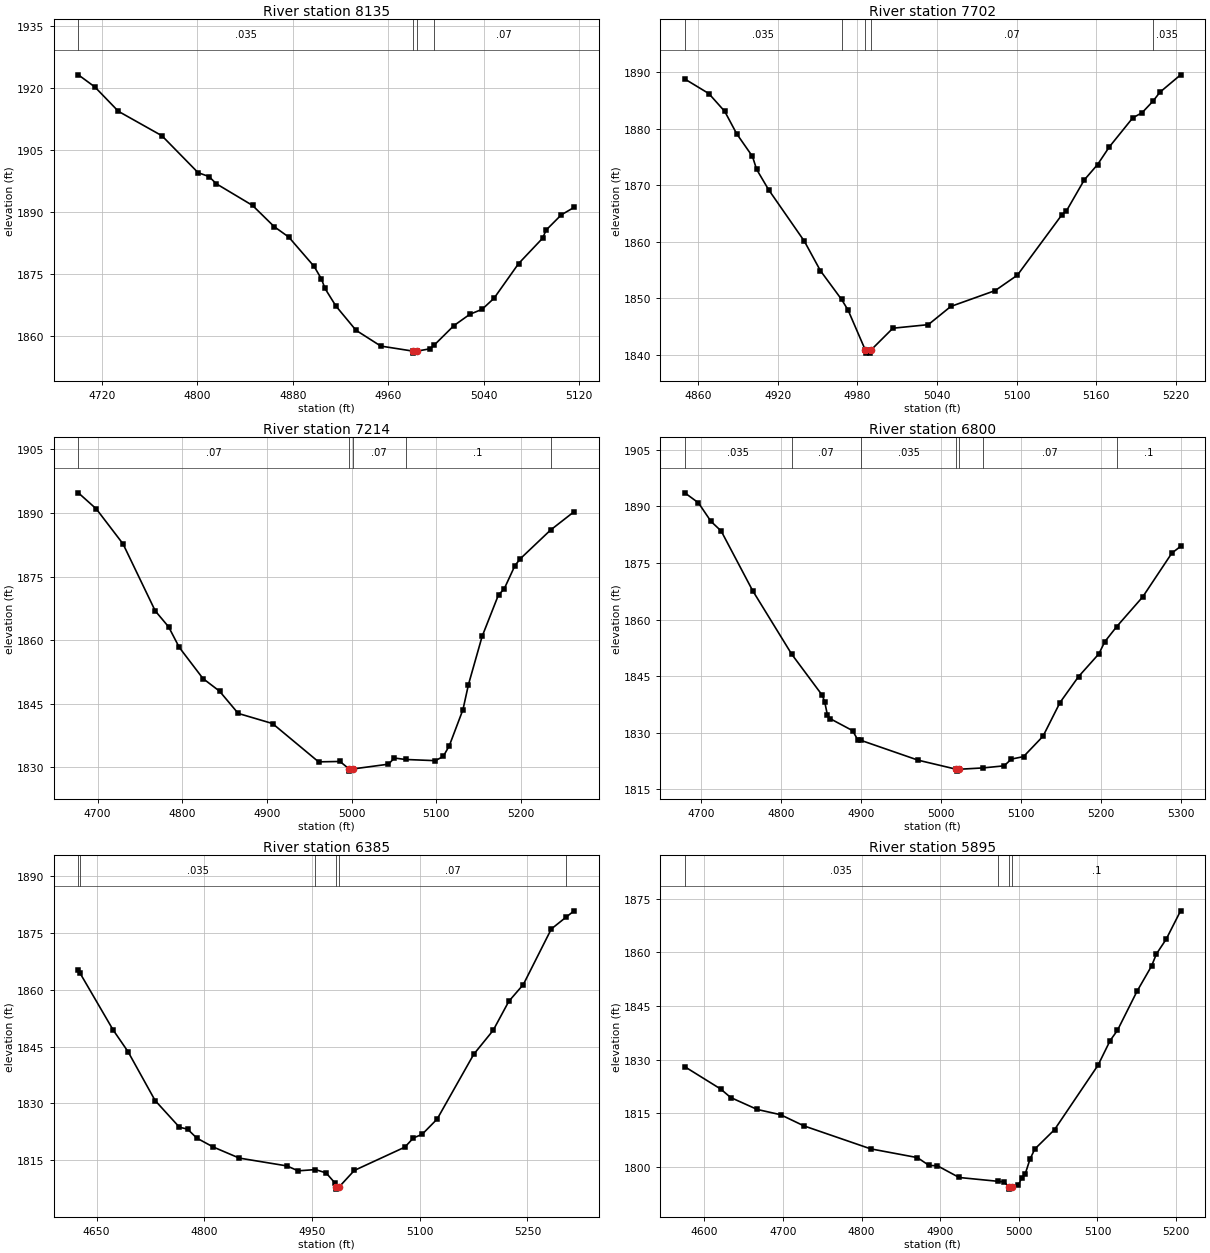
Type RM Length L Ch R = 1,8135,433,433,433
BEGIN DESCRIPTION:
Wolf Creek 18.0
END DESCRIPTION:
XS GIS Cut Line= 3
      1909175.00     13888474.98      1909125.00     13888175.00
      1909075.01     13888075.02
#Sta/Elev= 30
  4700.1 1923.22  4714.0 1920.27  4733.7 1914.38  4770.2 1908.46  4800.6 1899.50
  4809.7 1898.58  4815.8 1896.83  4846.2 1891.58  4864.4 1886.43  4876.6 1883.91
  4897.9 1876.79  4904.0 1873.77  4907.0 1871.46  4916.1 1867.22  4933.0 1861.33
  4953.8 1857.50  4980.5 1856.29  4980.7 1855.79  4984.5 1856.29  4995.2 1856.85
  4998.8 1857.79  5015.1 1862.45  5028.5 1865.20  5038.8 1866.41  5048.8 1869.09
  5069.4 1877.49  5089.6 1883.65  5092.4 1885.58  5105.2 1889.29  5116.0 1891.11
#Mann=4,-1,0
  4700.1   0.035       0  4980.5    0.05       0  4984.5   0.035       0
  4998.8    0.07       0
Bank Sta=4980.5,4984.5
Exp/Cntr=0.3,0.1

Type RM Length L Ch R = 1,7702,488,488,488
BEGIN DESCRIPTION:
Wolf Creek 17.0
END DESCRIPTION:
XS GIS Cut Line= 3
      1909525.00     13888324.96      1909525.00     13888175.00
      1909424.98     13887974.97
#Sta/Elev= 30
  4850.0 1888.76  4868.1 1886.19  4880.1 1883.04  4889.1 1879.09  4901.0 1875.08
  4904.1 1872.81  4913.1 1869.23  4940.1 1860.11  4952.2 1854.90  4968.1 1849.84
  4973.0 1847.96  4986.1 1840.85  4986.3 1840.35  4989.8 1840.35  4990.1 1840.85
  5006.8 1844.75  5033.5 1845.38  5050.4 1848.59  5083.9 1851.40  5100.6 1854.12
  5134.1 1864.77  5137.6 1865.48  5151.0 1870.94  5161.0 1873.65  5169.9 1876.78
  5187.5 1881.89  5194.6 1882.82  5202.9 1884.88  5208.0 1886.43  5223.6 1889.50
#Mann=5,-1,0
  4850.0   0.035       0  4968.1    0.07       0  4986.1    0.05       0
  4990.1    0.07       0  5202.9   0.035       0
Bank Sta=4986.1,4990.1
Exp/Cntr=0.3,0.1

Type RM Length L Ch R = 1,7214,414,414,414
BEGIN DESCRIPTION:
Wolf Creek 16.0
END DESCRIPTION:
XS GIS Cut Line= 3
      1909875.00     13888375.01      1909975.00     13888075.00
      1909875.00     13887825.00
#Sta/Elev= 30
  4677.2 1894.75  4698.4 1890.96  4730.0 1882.69  4768.0 1866.89  4783.8 1863.12
  4796.4 1858.27  4824.4 1850.92  4843.9 1847.95  4866.0 1842.69  4906.5 1840.30
  4960.9 1831.26  4986.2 1831.35  4997.0 1829.57  4997.2 1829.07  5001.0 1829.57
  5043.4 1830.71  5050.4 1832.16  5063.6 1831.82  5098.8 1831.54  5108.1 1832.53
  5115.3 1835.08  5131.4 1843.59  5137.9 1849.51  5154.0 1860.85  5173.4 1870.70
  5179.9 1872.00  5192.8 1877.59  5199.3 1879.23  5234.8 1885.96  5262.7 1890.31
#Mann=5,-1,0
  4677.2    0.07       0  4997.0    0.05       0  5001.0    0.07       0
  5063.6     0.1       0  5234.8   0.035       0
Bank Sta=4997,5001
Exp/Cntr=0.3,0.1

Type RM Length L Ch R = 1,6800,415,415,415
BEGIN DESCRIPTION:
Wolf Creek 15.0
END DESCRIPTION:
XS GIS Cut Line= 3
      1910174.99     13888425.03      1910275.00     13888125.00
      1910325.00     13887825.00
#Sta/Elev= 30
  4679.5 1893.58  4696.5 1890.94  4712.3 1886.00  4725.0 1883.47  4764.3 1867.70
  4813.3 1850.82  4851.5 1839.94  4854.6 1838.17  4857.8 1834.85  4861.0 1833.79
  4889.4 1830.58  4895.8 1828.20  4899.8 1828.01  4971.6 1822.74  5019.2 1820.35
  5019.5 1819.85  5023.2 1820.35  5052.6 1820.70  5079.0 1821.25  5088.2 1823.04
  5103.3 1823.69  5127.7 1829.09  5149.0 1838.03  5172.2 1844.90  5197.6 1850.92
  5205.0 1854.13  5220.0 1858.16  5252.4 1865.99  5288.9 1877.60  5299.9 1879.41
#Mann=7,-1,0
  4679.5   0.035       0  4813.3    0.07       0  4899.8   0.035       0
  5019.2   0.035       0  5023.2   0.035       0  5052.6    0.07       0
  5220.0     0.1       0
Bank Sta=5019.2,5023.2
Exp/Cntr=0.3,0.1

Type RM Length L Ch R = 1,6385,490,490,490
BEGIN DESCRIPTION:
Wolf Creek 14.0
END DESCRIPTION:
XS GIS Cut Line= 3
      1910424.98     13888425.02      1910675.00     13888125.00
      1910675.00     13887825.04
#Sta/Elev= 30
  4624.5 1865.19  4626.4 1864.57  4672.9 1849.43  4693.6 1843.71  4731.4 1830.78
  4765.3 1823.72  4776.6 1823.22  4789.4 1820.86  4812.2 1818.51  4848.6 1815.57
  4915.0 1813.50  4930.6 1812.20  4954.7 1812.53  4969.6 1811.65  4981.4 1809.09
  4983.3 1807.87  4983.5 1807.37  4987.3 1807.87  5008.8 1812.30  5079.2 1818.46
  5091.2 1820.90  5103.2 1821.83  5124.2 1825.88  5175.2 1843.00  5202.2 1849.31
  5224.0 1856.98  5244.2 1861.41  5283.2 1876.09  5303.8 1879.22  5315.0 1880.88
#Mann=6,-1,0
  4624.5    0.07       0  4626.4   0.035       0  4954.7    0.07       0
  4983.3    0.05       0  4987.3    0.07       0  5303.8     0.1       0
Bank Sta=4983.3,4987.3
Exp/Cntr=0.3,0.1

Type RM Length L Ch R = 1,5895,463,463,463
BEGIN DESCRIPTION:
Wolf Creek 13.0
END DESCRIPTION:
XS GIS Cut Line= 3
      1910825.01     13888524.99      1911125.00     13888225.00
      1911175.00     13888025.00
#Sta/Elev= 30
  4575.3 1827.99  4620.9 1821.75  4633.6 1819.37  4667.4 1816.02  4697.1 1814.55
  4726.8 1811.42  4811.6 1804.99  4871.0 1802.54  4885.9 1800.34  4896.5 1800.25
  4924.1 1796.97  4973.4 1795.90  4981.3 1795.72  4987.8 1794.21  4988.1 1793.71
  4991.8 1794.21  4999.5 1794.85  5003.7 1796.93  5007.9 1797.82  5014.1 1802.05
  5020.3 1804.94  5045.4 1810.37  5100.7 1828.42  5116.1 1835.32  5125.4 1838.19
  5150.2 1849.10  5168.7 1856.17  5174.9 1859.56  5187.3 1863.69  5205.7 1871.65
#Mann=4,-1,0
  4575.3   0.035       0  4973.4     0.1       0  4987.8    0.05       0
  4991.8     0.1       0
Bank Sta=4987.8,4991.8
Exp/Cntr=0.3,0.1

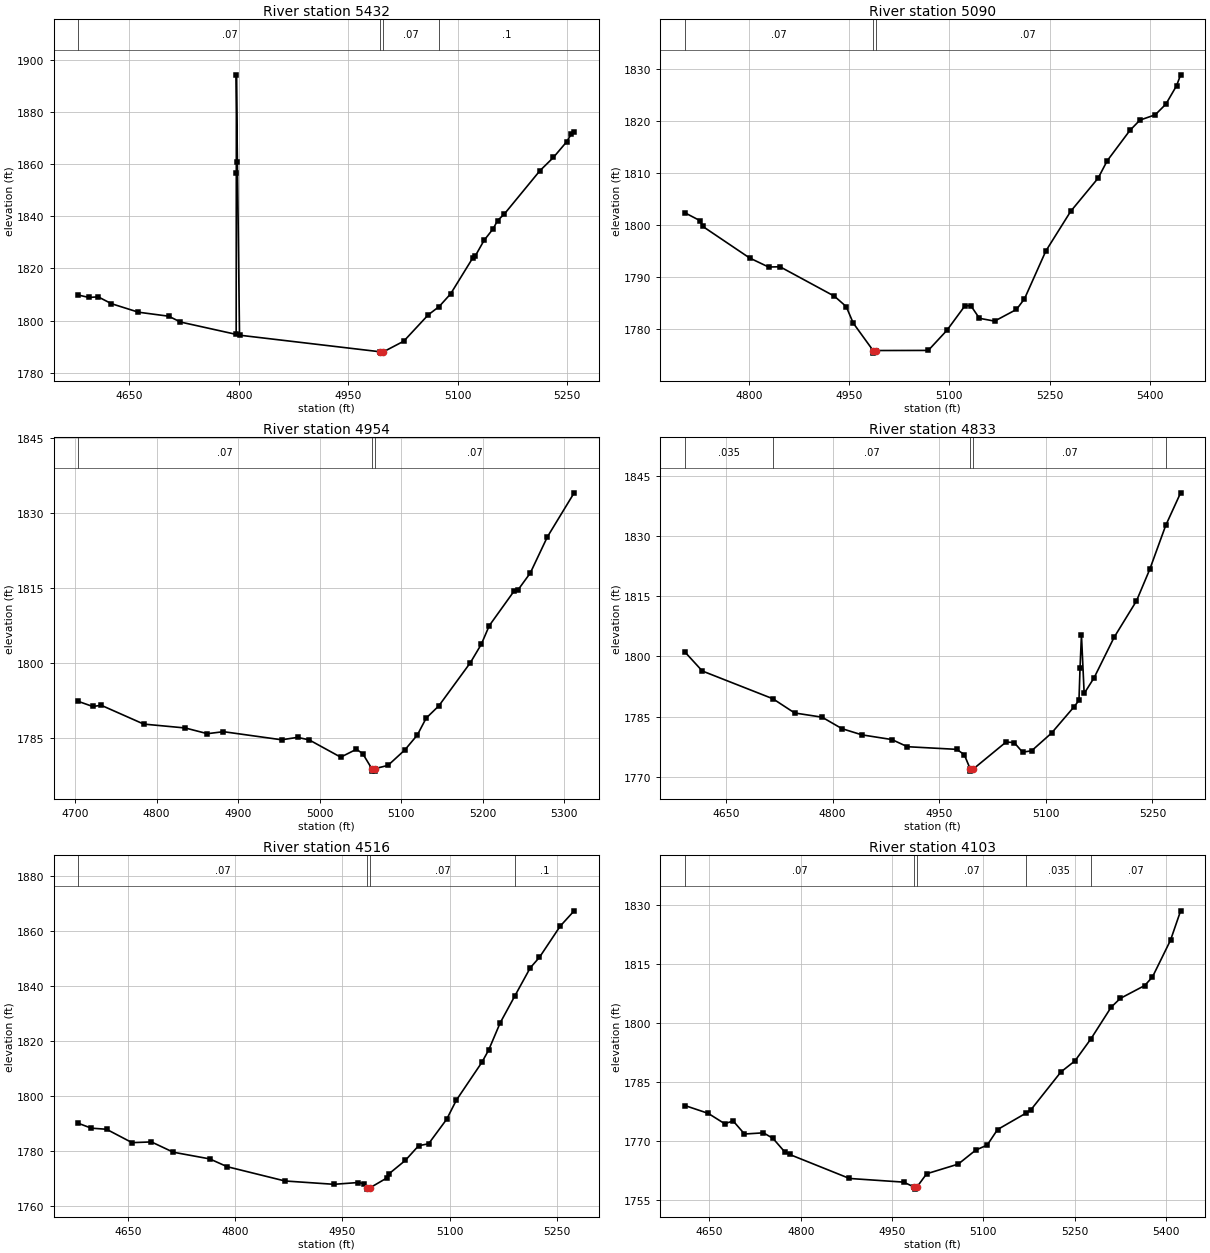
Type RM Length L Ch R = 1,5432,342,342,342
BEGIN DESCRIPTION:
Wolf Creek 12.0
END DESCRIPTION:
XS GIS Cut Line= 3
      1911225.02     13888624.98      1911525.00     13888325.00
      1911475.00     13888074.99
#Sta/Elev= 30
  4580.1 1809.79  4594.6 1808.88  4607.3 1809.10  4625.5 1806.48  4662.5 1803.22
  4703.9 1801.69  4720.0 1799.46  4796.3 1794.73  4796.5 1856.38  4796.6 1894.14
  4798.0 1860.75  4800.9 1794.42  4994.0 1788.05  4994.3 1787.55  4998.0 1788.05
  5025.9 1792.13  5059.5 1802.23  5074.3 1805.37  5090.1 1810.26  5120.7 1824.14
  5123.8 1824.74  5136.0 1830.79  5148.3 1835.15  5154.4 1838.33  5163.6 1840.81
  5212.4 1857.42  5230.9 1862.50  5249.2 1868.55  5255.3 1871.45  5259.3 1872.29
#Mann=4,-1,0
  4580.1    0.07       0  4994.0    0.05       0  4998.0    0.07       0
  5074.3     0.1       0
Bank Sta=4994,4998
Exp/Cntr=0.3,0.1

Type RM Length L Ch R = 1,5090,136,136,136
BEGIN DESCRIPTION:
Wolf Creek 11.0
END DESCRIPTION:
XS GIS Cut Line= 3
      1911574.99     13888825.01      1911735.56     13888562.51
      1912021.47     13888236.28
#Sta/Elev= 30
  4704.4 1802.40  4727.1 1800.88  4731.3 1799.77  4801.3 1793.71  4829.7 1791.97
  4846.8 1792.02  4928.2 1786.36  4945.8 1784.37  4956.3 1781.20  4986.0 1775.93
  4986.2 1775.43  4990.0 1775.93  5068.5 1775.95  5096.4 1779.81  5123.5 1784.55
  5132.3 1784.52  5145.0 1782.12  5167.7 1781.58  5200.4 1783.82  5212.4 1785.86
  5244.3 1795.04  5281.5 1802.67  5322.5 1809.04  5336.1 1812.38  5370.1 1818.22
  5385.0 1820.19  5407.9 1821.21  5423.8 1823.25  5439.8 1826.79  5445.9 1828.89
#Mann=3,-1,0
  4704.4    0.07       0  4986.0    0.05       0  4990.0    0.07       0
Bank Sta=4986,4990
Exp/Cntr=0.3,0.1

Type RM Length L Ch R = 1,4954,121,121,121
BEGIN DESCRIPTION:
Wolf Creek 11.1
END DESCRIPTION:
XS GIS Cut Line= 4
      1911668.69     13888766.07      1911814.56     13888644.51
      1911828.45     13888568.12      1912043.74     13888304.22
#Sta/Elev= 30
  4704.1 1792.31  4721.8 1791.29  4732.2 1791.53  4784.3 1787.77  4835.3 1786.99
  4862.4 1785.85  4882.1 1786.25  4953.4 1784.63  4972.9 1785.11  4987.1 1784.62
  5025.9 1781.15  5045.2 1782.74  5053.0 1781.83  5064.0 1778.86  5064.3 1778.36
  5067.8 1778.36  5068.0 1778.86  5083.9 1779.51  5104.5 1782.59  5119.8 1785.57
  5130.7 1788.96  5146.2 1791.41  5184.9 1800.05  5198.3 1803.73  5208.1 1807.46
  5238.4 1814.35  5243.2 1814.58  5258.4 1817.99  5279.3 1825.20  5312.2 1834.03
#Mann=3,-1,0
  4704.1    0.07       0  5064.0    0.05       0  5068.0    0.07       0
Bank Sta=5064,5068
Exp/Cntr=0.3,0.1

Type RM Length L Ch R = 1,4833,317,317,317
BEGIN DESCRIPTION:
Mapping XS cf2538a1
END DESCRIPTION:
XS GIS Cut Line= 2
      1911738.84     13888949.15      1912100.65     13888352.82
#Sta/Elev= 30
  4592.2 1801.13  4616.8 1796.37  4716.1 1789.46  4746.7 1785.92  4785.3 1784.87
  4813.3 1782.01  4841.4 1780.47  4883.5 1779.30  4905.3 1777.52  4974.7 1776.86
  4985.3 1775.56  4993.8 1771.94  4994.1 1771.44  4997.8 1771.94  5044.1 1778.68
  5055.5 1778.56  5067.3 1776.17  5080.0 1776.49  5108.1 1780.91  5139.7 1787.44
  5146.7 1789.05  5148.2 1797.14  5150.2 1805.34  5154.0 1790.77  5168.0 1794.69
  5196.1 1804.74  5227.6 1813.82  5246.3 1821.69  5268.7 1832.60  5289.7 1840.73
#Mann=5,-1,0
  4592.2   0.035       0  4716.1    0.07       0  4993.8    0.05       0
  4997.8    0.07       0  5268.7     0.1       0
Bank Sta=4993.8,4997.8
Exp/Cntr=0.3,0.1

Type RM Length L Ch R = 1,4516,413,413,413
BEGIN DESCRIPTION:
Wolf Creek 10.0
END DESCRIPTION:
XS GIS Cut Line= 3
      1911925.02     13889024.98      1912225.00     13888725.00
      1912324.97     13888475.09
#Sta/Elev= 30
  4580.7 1790.08  4598.9 1788.31  4620.1 1787.92  4655.8 1783.06  4682.9 1783.32
  4713.5 1779.58  4764.4 1777.16  4788.9 1774.32  4869.6 1769.14  4938.3 1767.93
  4972.3 1768.58  4980.3 1768.12  4984.7 1766.68  4984.9 1766.18  4988.7 1766.68
  5012.4 1770.27  5015.6 1771.84  5038.0 1776.61  5056.6 1781.95  5070.5 1782.64
  5095.9 1791.58  5109.3 1798.46  5144.9 1812.16  5154.5 1816.66  5170.7 1826.59
  5191.2 1836.35  5212.7 1846.53  5225.6 1850.36  5254.7 1861.70  5274.1 1867.23
#Mann=4,-1,0
  4580.7    0.07       0  4984.7    0.05       0  4988.7    0.07       0
  5191.2     0.1       0
Bank Sta=4984.7,4988.7
Exp/Cntr=0.3,0.1

Type RM Length L Ch R = 1,4103,449,449,449
BEGIN DESCRIPTION:
Wolf Creek 9.0
END DESCRIPTION:
XS GIS Cut Line= 3
      1912225.01     13889225.00      1912525.00     13888975.00
      1912825.02     13888674.98
#Sta/Elev= 30
  4609.5 1779.08  4648.0 1777.08  4675.0 1774.45  4689.0 1775.15  4707.6 1771.83
  4738.7 1772.13  4754.3 1770.74  4773.4 1767.34  4781.7 1766.64  4880.1 1760.53
  4969.1 1759.60  4986.8 1758.32  4987.0 1757.82  4990.8 1758.32  5006.9 1761.72
  5058.8 1764.18  5087.6 1767.74  5106.5 1769.02  5123.4 1772.96  5170.9 1777.20
  5178.6 1778.05  5227.6 1787.61  5250.7 1790.43  5277.0 1796.04  5310.1 1804.06
  5325.1 1806.30  5365.3 1809.58  5378.0 1811.75  5407.7 1821.10  5424.3 1828.57
#Mann=5,-1,0
  4609.5    0.07       0  4986.8    0.05       0  4990.8    0.07       0
  5170.9   0.035       0  5277.0    0.07       0
Bank Sta=4986.8,4990.8
Exp/Cntr=0.3,0.1

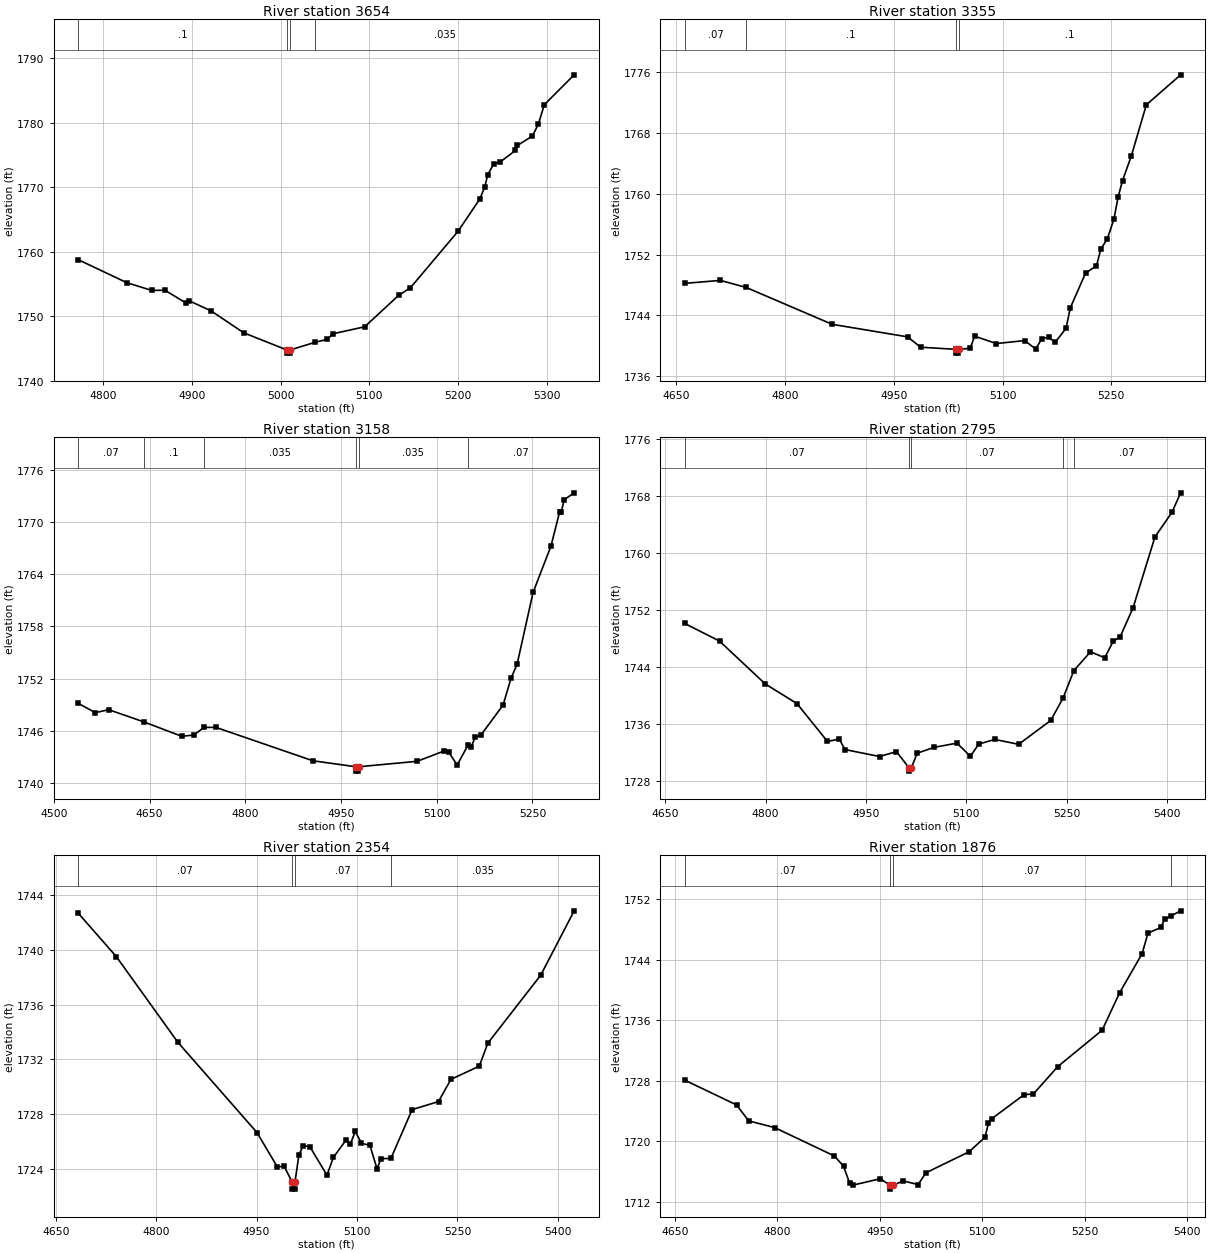
Type RM Length L Ch R = 1,3654,299,299,299
BEGIN DESCRIPTION:
Wolf Creek 8.0
END DESCRIPTION:
XS GIS Cut Line= 3
      1912674.96     13889325.02      1912875.00     13889225.00
      1913025.02     13888924.96
#Sta/Elev= 30
  4772.0 1758.75  4826.6 1755.19  4854.6 1753.99  4869.6 1754.01  4893.1 1752.06
  4896.4 1752.41  4921.7 1750.81  4958.4 1747.41  5007.0 1744.75  5007.2 1744.25
  5010.7 1744.25  5011.0 1744.75  5039.4 1745.95  5052.6 1746.38  5059.3 1747.26
  5094.9 1748.34  5133.1 1753.21  5146.5 1754.40  5200.2 1763.17  5224.6 1768.15
  5230.3 1770.04  5233.7 1771.96  5240.4 1773.61  5247.1 1773.86  5264.9 1775.71
  5267.2 1776.49  5284.0 1777.95  5290.7 1779.78  5297.4 1782.80  5331.1 1787.45
#Mann=4,-1,0
  4772.0     0.1       0  5007.0    0.05       0  5011.0     0.1       0
  5039.4   0.035       0
Bank Sta=5007,5011
Exp/Cntr=0.3,0.1

Type RM Length L Ch R = 1,3355,197,197,197
BEGIN DESCRIPTION:
Wolf Creek 7.0
END DESCRIPTION:
XS GIS Cut Line= 3
      1912938.36     13889653.11      1913125.24     13889368.01
      1913125.00     13889025.01
#Sta/Elev= 30
  4661.7 1748.22  4710.8 1748.61  4746.4 1747.68  4865.0 1742.83  4969.0 1741.18
  4987.0 1739.82  5035.5 1739.54  5035.7 1739.04  5039.2 1739.04  5039.5 1739.54
  5055.5 1739.68  5061.4 1741.27  5091.4 1740.30  5130.5 1740.69  5145.5 1739.59
  5154.4 1740.95  5163.5 1741.13  5172.5 1740.45  5187.5 1742.30  5193.5 1745.01
  5214.5 1749.58  5229.5 1750.53  5235.5 1752.70  5244.5 1754.09  5253.5 1756.63
  5259.5 1759.64  5265.5 1761.75  5277.5 1764.95  5298.3 1771.71  5345.6 1775.66
#Mann=4,-1,0
  4661.7    0.07       0  4746.4     0.1       0  5035.5    0.05       0
  5039.5     0.1       0
Bank Sta=5035.5,5039.5
Exp/Cntr=0.3,0.1

Type RM Length L Ch R = 1,3158,363,363,363
BEGIN DESCRIPTION:
Wolf Creek 6.1
END DESCRIPTION:
XS GIS Cut Line= 4
      1912984.73     13889658.37      1913262.48     13889370.21
      1913359.70     13889262.57      1913293.73     13889040.33
#Sta/Elev= 30
  4538.3 1749.15  4565.1 1748.09  4585.9 1748.43  4640.9 1747.03  4700.1 1745.38
  4719.2 1745.51  4735.1 1746.39  4753.8 1746.40  4905.9 1742.56  4973.5 1741.87
  4973.8 1741.37  4977.3 1741.37  4977.5 1741.87  5069.4 1742.50  5111.7 1743.69
  5118.9 1743.54  5132.1 1742.07  5148.7 1744.32  5154.0 1744.14  5160.2 1745.26
  5169.6 1745.55  5204.0 1748.96  5216.6 1752.07  5225.9 1753.63  5251.0 1761.90
  5279.1 1767.24  5292.6 1771.16  5295.1 1771.16  5299.9 1772.56  5315.4 1773.35
#Mann=6,-1,0
  4538.3    0.07       0  4640.9     0.1       0  4735.1   0.035       0
  4973.5   0.035       0  4977.5   0.035       0  5148.7    0.07       0
Bank Sta=4973.5,4977.5
Exp/Cntr=0.3,0.1

Type RM Length L Ch R = 1,2795,441,441,441
BEGIN DESCRIPTION:
Wolf Creek 6.0
END DESCRIPTION:
XS GIS Cut Line= 3
      1913724.99     13889674.98      1913625.00     13889375.00
      1913324.98     13889074.98
#Sta/Elev= 30
  4679.4 1750.08  4731.3 1747.61  4799.5 1741.60  4846.9 1738.84  4892.5 1733.52
  4910.1 1733.87  4918.6 1732.39  4970.2 1731.41  4995.5 1732.10  5013.9 1729.86
  5014.1 1729.36  5017.9 1729.86  5026.5 1731.88  5051.9 1732.70  5085.9 1733.29
  5105.8 1731.45  5118.5 1733.16  5142.3 1733.81  5177.9 1733.12  5225.9 1736.47
  5244.3 1739.61  5260.4 1743.46  5285.3 1746.11  5306.5 1745.27  5319.2 1747.57
  5329.8 1748.24  5348.9 1752.30  5381.6 1762.24  5407.0 1765.69  5419.9 1768.42
#Mann=5,-1,0
  4679.4    0.07       0  5013.9    0.05       0  5017.9    0.07       0
  5244.3   0.035       0  5260.4    0.07       0
Bank Sta=5013.9,5017.9
Exp/Cntr=0.3,0.1

Type RM Length L Ch R = 1,2354,478,478,478
BEGIN DESCRIPTION:
Wolf Creek 5.0
END DESCRIPTION:
XS GIS Cut Line= 3
      1914075.00     13889525.01      1913975.00     13889225.00
      1913675.00     13888925.00
#Sta/Elev= 30
  4683.8 1742.68  4740.6 1739.51  4832.3 1733.26  4950.7 1726.65  4981.0 1724.14
  4991.1 1724.20  5003.3 1723.02  5003.6 1722.52  5007.1 1722.52  5007.3 1723.02
  5013.2 1725.02  5019.6 1725.69  5029.6 1725.62  5055.1 1723.54  5064.7 1724.84
  5083.2 1726.08  5090.2 1725.84  5097.5 1726.74  5106.6 1725.87  5119.3 1725.72
  5129.9 1724.00  5135.7 1724.75  5150.6 1724.76  5182.3 1728.33  5221.7 1728.92
  5240.2 1730.54  5282.6 1731.51  5295.4 1733.19  5374.4 1738.16  5424.3 1742.86
#Mann=4,-1,0
  4683.8    0.07       0  5003.3    0.05       0  5007.3    0.07       0
  5150.6   0.035       0
Bank Sta=5003.3,5007.3
Exp/Cntr=0.3,0.1

Type RM Length L Ch R = 1,1876,453,453,453
BEGIN DESCRIPTION:
Wolf Creek 4.0
END DESCRIPTION:
XS GIS Cut Line= 3
      1914374.98     13889174.97      1914225.00     13888875.00
      1913924.99     13888624.99
#Sta/Elev= 30
  4664.4 1728.06  4740.1 1724.79  4758.0 1722.68  4796.0 1721.79  4883.4 1718.04
  4896.8 1716.69  4905.6 1714.47  4910.2 1714.18  4950.5 1715.03  4965.3 1714.16
  4965.5 1713.66  4969.3 1714.16  4984.0 1714.75  5005.9 1714.26  5017.6 1715.83
  5080.5 1718.59  5103.9 1720.52  5109.0 1722.39  5113.7 1722.96  5161.4 1726.16
  5174.6 1726.22  5210.4 1729.85  5275.4 1734.66  5301.1 1739.63  5333.9 1744.78
  5342.5 1747.49  5361.6 1748.25  5366.7 1749.30  5376.8 1749.80  5390.3 1750.44
#Mann=4,-1,0
  4664.4    0.07       0  4965.3    0.05       0  4969.3    0.07       0
  5376.8   0.035       0
Bank Sta=4965.3,4969.3
Exp/Cntr=0.3,0.1

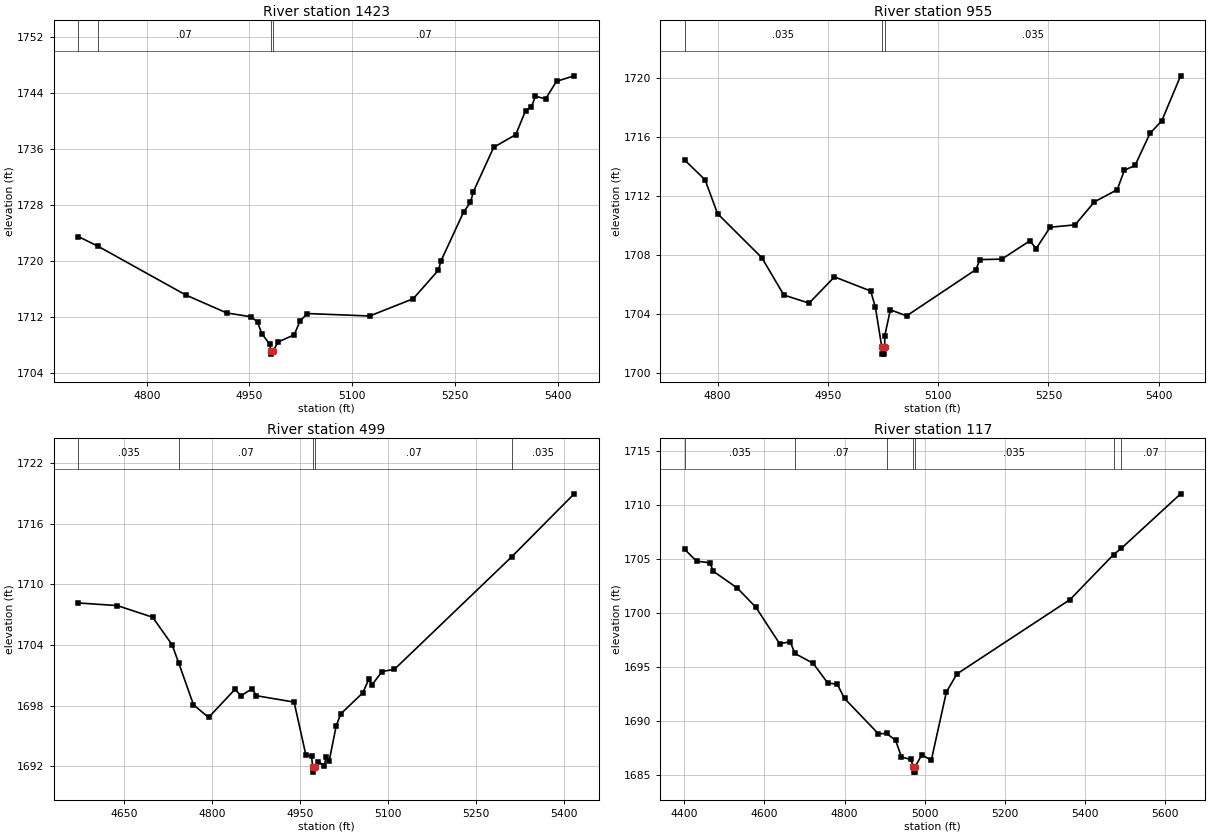
Type RM Length L Ch R = 1,1423,468,468,468
BEGIN DESCRIPTION:
Wolf Creek 3.0
END DESCRIPTION:
XS GIS Cut Line= 3
      1914625.00     13889024.99      1914625.00     13888725.00
      1914324.97     13888424.97
#Sta/Elev= 30
  4700.0 1723.53  4728.0 1722.19  4856.9 1715.20  4916.6 1712.64  4952.9 1712.08
  4961.9 1711.30  4967.9 1709.70  4979.6 1708.17  4980.9 1707.26  4981.2 1706.76
  4984.9 1707.26  4991.9 1708.49  5015.3 1709.51  5023.8 1711.47  5034.4 1712.55
  5125.6 1712.20  5189.2 1714.66  5226.1 1718.75  5229.5 1720.00  5262.7 1727.01
  5272.8 1728.41  5277.1 1729.94  5306.8 1736.27  5339.0 1738.07  5353.4 1741.51
  5361.9 1742.03  5367.7 1743.55  5382.5 1743.17  5398.6 1745.68  5424.3 1746.46
#Mann=4,-1,0
  4700.0     0.1       0  4728.0    0.07       0  4980.9    0.05       0
  4984.9    0.07       0
Bank Sta=4980.9,4984.9
Exp/Cntr=0.3,0.1

Type RM Length L Ch R = 1,955,456,456,456
BEGIN DESCRIPTION:
Wolf Creek 2.0
END DESCRIPTION:
XS GIS Cut Line= 3
      1915074.98     13888624.98      1914925.00     13888425.00
      1914625.03     13888125.03
#Sta/Elev= 30
  4755.5 1714.41  4783.1 1713.08  4800.0 1710.79  4860.2 1707.81  4890.2 1705.28
  4924.5 1704.73  4959.0 1706.51  5008.3 1705.55  5014.7 1704.44  5023.3 1701.78
  5023.5 1701.28  5027.0 1701.28  5027.3 1701.78  5027.4 1702.52  5035.0 1704.28
  5057.1 1703.87  5151.3 1707.00  5156.8 1707.68  5186.5 1707.71  5224.7 1708.95
  5233.2 1708.42  5252.3 1709.87  5286.2 1710.03  5312.5 1711.59  5343.5 1712.41
  5353.2 1713.73  5367.7 1714.05  5388.0 1716.22  5404.1 1717.08  5429.7 1720.12
#Mann=3,-1,0
  4755.5   0.035       0  5023.3   0.035       0  5027.3   0.035       0
Bank Sta=5023.3,5027.3
Exp/Cntr=0.3,0.1

Type RM Length L Ch R = 1,499,382,382,382
BEGIN DESCRIPTION:
Wolf Creek 1.0
END DESCRIPTION:
XS GIS Cut Line= 3
      1915333.05     13888365.85      1915075.00     13888025.00
      1914658.69     13887994.99
#Sta/Elev= 30
  4572.4 1708.17  4638.8 1707.91  4699.0 1706.76  4732.2 1704.03  4743.5 1702.22
  4768.6 1698.10  4794.3 1696.84  4839.3 1699.62  4849.6 1698.99  4868.4 1699.68
  4875.9 1698.99  4940.1 1698.36  4960.0 1693.16  4969.9 1692.98  4971.7 1691.93
  4972.0 1691.43  4975.7 1691.93  4981.2 1692.46  4991.3 1692.07  4994.7 1692.89
  4999.9 1692.55  5011.8 1696.00  5019.5 1697.19  5056.9 1699.26  5067.7 1700.65
  5072.9 1700.08  5090.0 1701.38  5111.1 1701.61  5310.9 1712.74  5417.3 1718.97
#Mann=5,-1,0
  4572.4   0.035       0  4743.5    0.07       0  4971.7    0.05       0
  4975.7    0.07       0  5310.9   0.035       0
Bank Sta=4971.7,4975.7
Exp/Cntr=0.3,0.1

Type RM Length L Ch R = 1,117,0,0,0
BEGIN DESCRIPTION:
Wolf Creek 0.0
END DESCRIPTION:
XS GIS Cut Line= 4
      1915443.51     13888381.25      1915415.48     13887913.03
      1915247.28     13887743.16      1914732.11     13887614.93
#Sta/Elev= 30
  4400.9 1705.92  4430.3 1704.83  4463.4 1704.69  4472.4 1703.89  4531.9 1702.35
  4578.4 1700.57  4637.9 1697.19  4664.7 1697.37  4675.5 1696.30  4721.8 1695.37
  4757.9 1693.56  4782.0 1693.44  4800.0 1692.12  4884.7 1688.85  4905.0 1688.88
  4927.6 1688.25  4942.4 1686.70  4965.7 1686.47  4972.2 1685.80  4972.5 1685.30
  4976.0 1685.30  4976.2 1685.80  4993.4 1686.90  5016.9 1686.40  5054.5 1692.71
  5080.8 1694.39  5363.7 1701.28  5472.2 1705.44  5492.0 1706.03  5639.9 1711.07
#Mann=7,-1,0
  4400.9   0.035       0  4675.5    0.07       0  4905.0   0.035       0
  4972.2    0.05       0  4976.2   0.035       0  5472.2   0.035       0
  5492.0    0.07       0
Bank Sta=4972.2,4976.2
Exp/Cntr=0.3,0.1

Chan Stop Cuts=-1