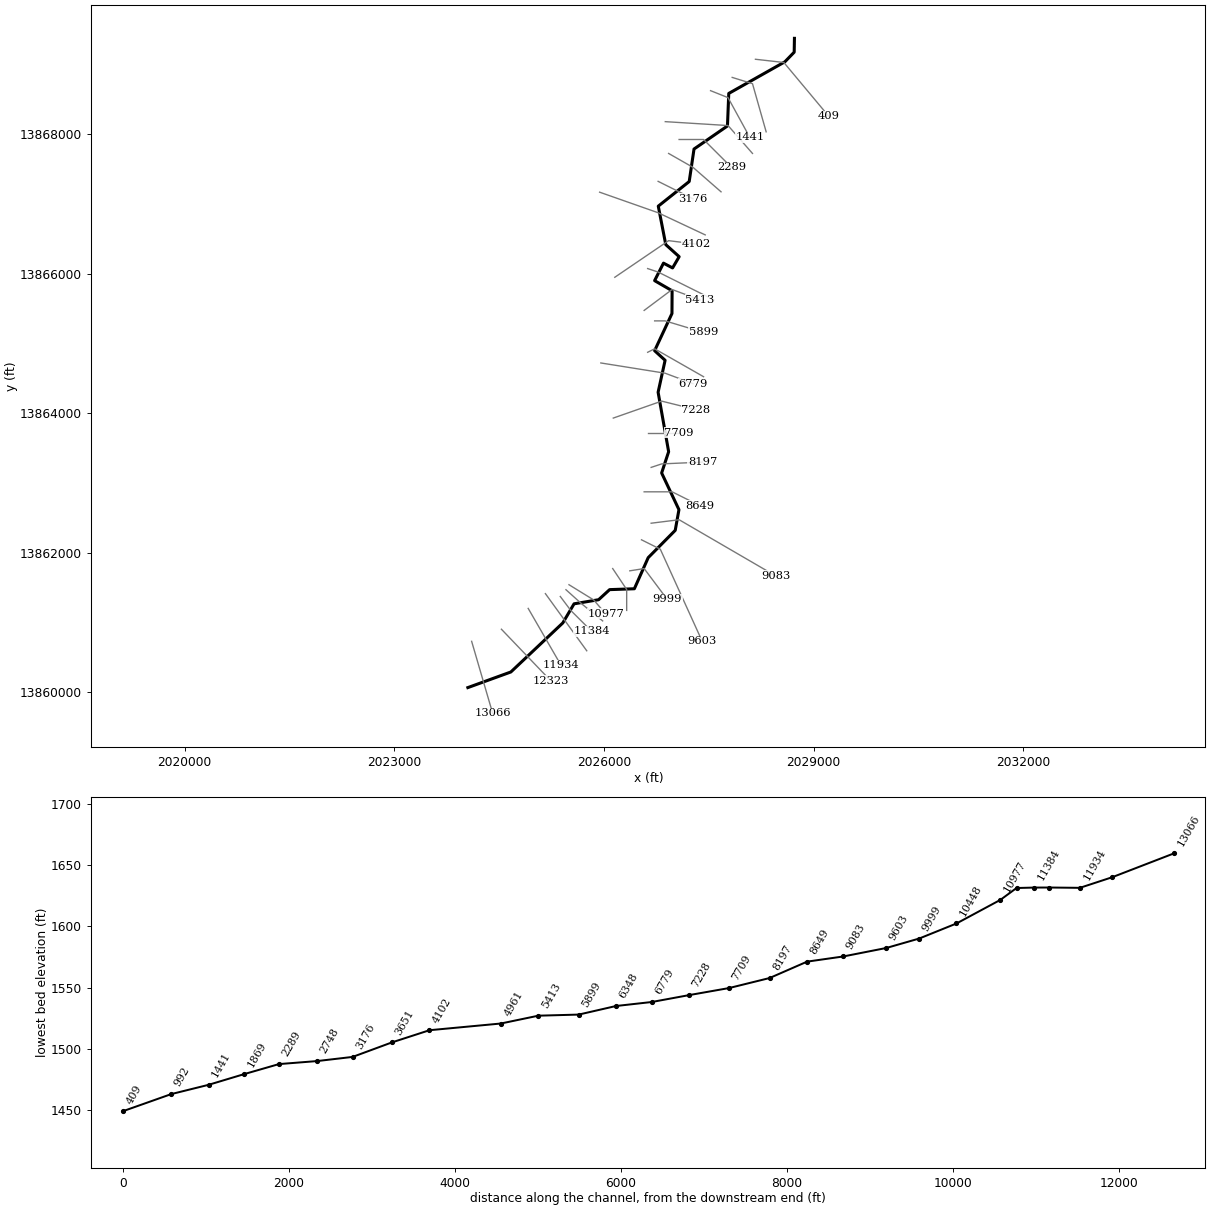
--- ALLEN CREEK.prj (project) ---

Proj Title=ALLEN CREEK Base Level Engineering
Current Plan=p01
Default Exp/Contr=0.3,0.1
English Units
Geom File=g01
Flow File=f01
Plan File=p01
Y Axis Title=Elevation
X Axis Title(PF)=Main Channel Distance
X Axis Title(XS)=Station
BEGIN DESCRIPTION:
ALLEN CREEK
END DESCRIPTION:
DSS Export Rating Curves= 0
DSS Export Rating Curve Sorted= 0
DSS Export Volume Flow Curves= 0
DXF OffsetX= 0
DXF OffsetY= 0
DXF ScaleX= 1
DXF ScaleY= 10

--- ALLEN CREEK.p01 (plan) ---

Plan Title=Multiple Run
Short Identifier=Multiple
Geom File=g01
Flow File=f01
Subcritical Flow
K Sum by GR= 0
Std Step Tol= 0.01
Critical Tol= 0.01
Num of Std Step Trials= 20
Max Error Tol= 0.3
Flow Tol Ratio= 0.001
Split Flow NTrial= 30
Split Flow Tol= 0.02
Split Flow Ratio= 0.02
Log Output Level= 0
Friction Slope Method= 1
Unsteady Friction Slope Method= 2
Unsteady Bridges Friction Slope Method= 1
Parabolic Critical Depth
Global Vel Dist=  1 , 1 , 1
Global Log Level= 0
CheckData=True
Encroach Param= -1, 0, 0, 0
BEGIN DESCRIPTION:
Multiple Run
END DESCRIPTION:

--- ALLEN CREEK.f01 (steady flow) ---

Flow Title=Multiple
Number of Profiles=7
Profile Names=10-year,25-year,50-year,1pct_min,100-year,1pct_plu,500-year
River Rch & RM= ALLEN CREEK,Reach-1,13066
    1003    1704    2375    1608    3208    6400    5782
River Rch & RM= ALLEN CREEK,Reach-1,11563
    1756    3084    4393    3033    6051   12073   11356
River Rch & RM= ALLEN CREEK,Reach-1,9083
    2428    4313    6190    4297    8573   17106   16280
River Rch & RM= ALLEN CREEK,Reach-1,2748
    2495    4431    6358    4412    8803   17564   16702
Boundary for River Rch & Prof#=ALLEN CREEK,Reach-1,1
Up Type=0
Dn Type=3
Dn Slope=0.005
Boundary for River Rch & Prof#=ALLEN CREEK,Reach-1,2
Up Type=0
Dn Type=3
Dn Slope=0.005
Boundary for River Rch & Prof#=ALLEN CREEK,Reach-1,3
Up Type=0
Dn Type=3
Dn Slope=0.005
Boundary for River Rch & Prof#=ALLEN CREEK,Reach-1,4
Up Type=0
Dn Type=3
Dn Slope=0.005
Boundary for River Rch & Prof#=ALLEN CREEK,Reach-1,5
Up Type=0
Dn Type=3
Dn Slope=0.005
Boundary for River Rch & Prof#=ALLEN CREEK,Reach-1,6
Up Type=0
Dn Type=3
Dn Slope=0.005
Boundary for River Rch & Prof#=ALLEN CREEK,Reach-1,7
Up Type=0
Dn Type=3
Dn Slope=0.005

--- ALLEN CREEK.g01 (geometry) ---

Geom Title=Existing Conditions
Program Version=4.10

River Reach=ALLEN CREEK     ,Reach-1
Reach XY= 30
      2024052.79     13860068.78      2024668.03     13860292.63
       2025411.1     13860995.52       2025572.3     13861269.64
      2025923.53     13861328.54      2026080.85     13861472.94
      2026434.83     13861485.47      2026632.85     13861931.19
      2027019.48     13862322.57      2027072.75     13862619.06
      2026825.06     13863145.03      2026925.29     13863449.88
      2026774.69     13864302.17      2026874.67     13864759.97
      2026724.48     13864897.67      2026972.82     13865430.45
      2026974.96     13865756.91       2026724.5     13865902.07
      2026851.61     13866152.63      2026981.69     13866083.96
      2027075.79     13866245.33      2026884.15     13866418.27
      2026777.07     13866969.53      2027219.53     13867322.55
      2027288.37     13867788.32      2027766.88     13868118.95
      2027785.34     13868585.12      2028588.22     13869038.62
      2028721.47     13869176.46        2028725.       13869375.

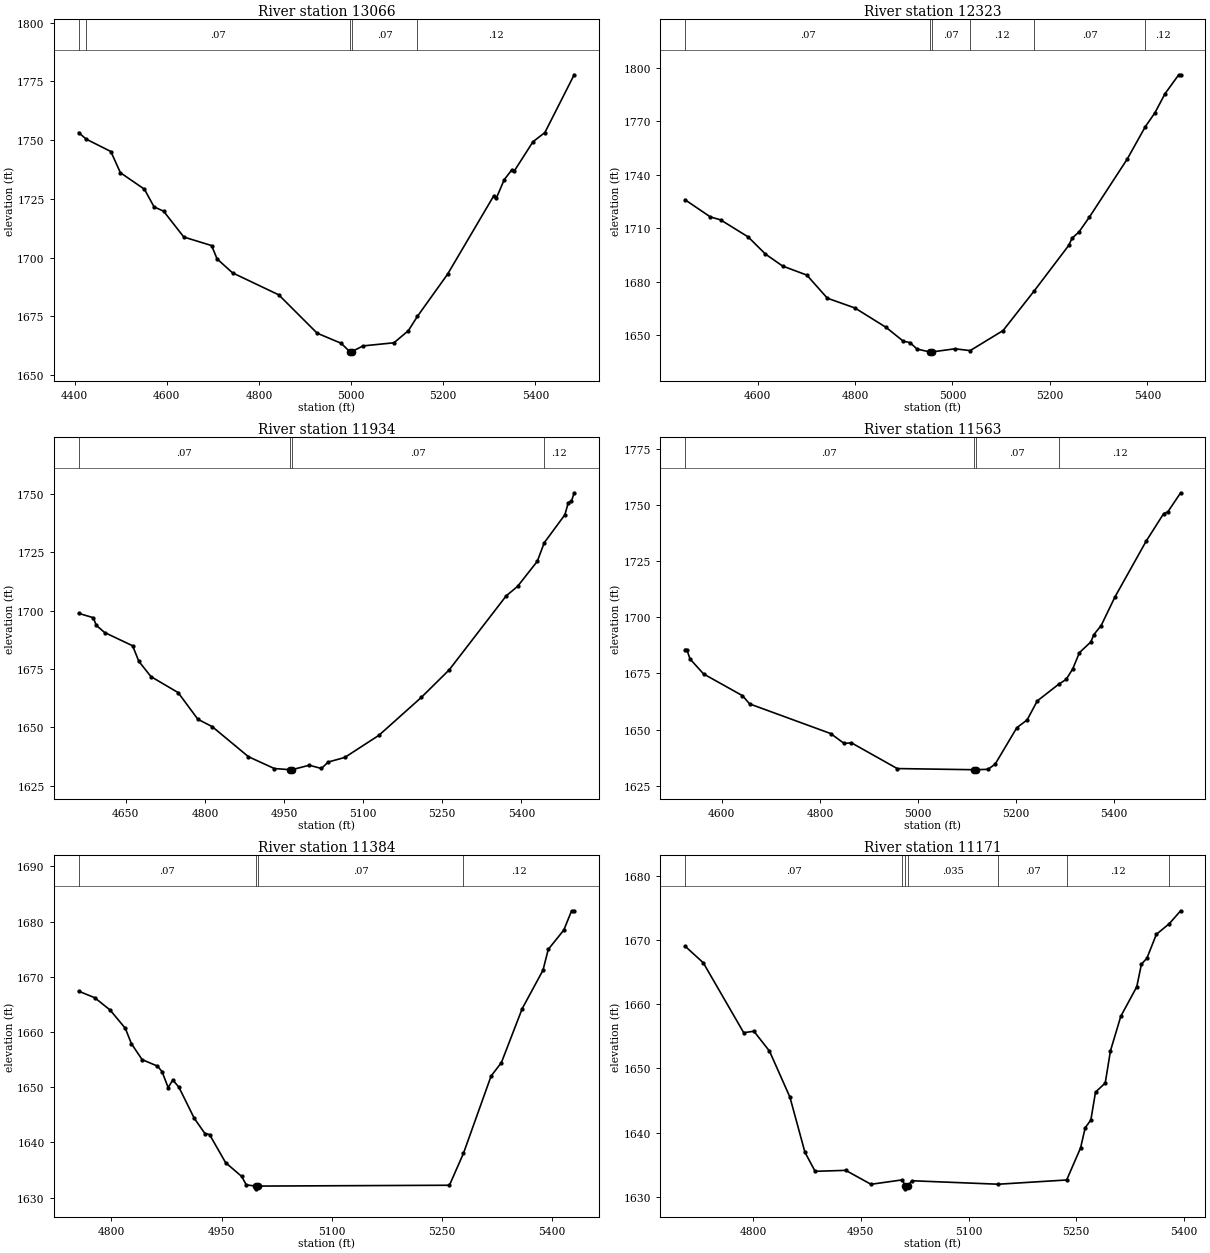
Type RM Length L Ch R = 1 ,13066   ,743,743,743
BEGIN DESCRIPTION:
ALLEN CREEK 28.0
END DESCRIPTION:
XS GIS Cut Line= 2
      2024106.94     13860732.12      2024407.92     13859699.28
#Sta/Elev= 30
  4408.5 1753.25  4425.1 1750.44  4478.4 1745.19  4499.2 1736.15  4551.3 1729.14
  4572.2 1721.63    4593 1719.76  4636.9 1708.77  4697.2 1705.13  4709.1 1699.45
  4742.6 1693.52    4843 1684.15  4926.3 1667.83  4978.4 1663.53  4997.2 1659.96
  4997.5 1659.46  5001.2 1659.96  5026.2 1662.42    5093 1663.74  5124.2 1668.86
  5144.1 1675.03  5209.3 1692.89  5309.8 1726.35    5315 1725.18  5332.5 1733.21
  5348.5 1737.25  5353.7 1736.72    5395 1749.37  5420.7 1753.26  5484.3 1777.86
#Mann= 5 ,-1 , 0
  4408.5     .12       0  4425.1     .07       0  4997.2     .05       0
  5001.2     .07       0  5144.1     .12       0
Bank Sta=4997.2,5001.2
XS Rating Curve= 0 ,0
Exp/Cntr=0.3,0.1

Type RM Length L Ch R = 1 ,12323   ,389,389,389
BEGIN DESCRIPTION:
ALLEN CREEK 27.0
END DESCRIPTION:
XS GIS Cut Line= 2
      2024532.64     13860905.64      2025235.45     13860170.42
#Sta/Elev= 30
  4451.3 1726.01    4503 1716.41  4524.1 1714.74  4580.7 1705.16  4616.2 1695.52
  4651.4 1688.79  4701.1 1683.71  4743.3 1670.73  4799.9 1665.23  4863.7 1654.36
    4899 1646.61  4913.1 1645.76  4927.3 1642.15  4953.6 1640.53  4953.8 1640.03
  4957.6 1640.53  5005.3  1642.3  5036.4 1641.28    5104 1652.57  5168.1 1674.91
  5238.6 1700.34  5245.5 1704.41  5259.7 1707.92  5281.1 1716.28  5358.8 1748.89
  5395.9 1767.09  5415.4 1774.77  5436.4 1785.64  5464.5 1796.24  5468.4 1796.24
#Mann= 6 ,-1 , 0
  4451.3     .07       0  4953.6     .05       0  4957.6     .07       0
  5036.4     .12       0  5168.1     .07       0  5395.9     .12       0
Bank Sta=4953.6,4957.6
XS Rating Curve= 0 ,0
Exp/Cntr=0.3,0.1

Type RM Length L Ch R = 1 ,11934   ,371,371,371
BEGIN DESCRIPTION:
ALLEN CREEK 26.0
END DESCRIPTION:
XS GIS Cut Line= 2
      2024916.06      13861203.9      2025385.14     13860389.76
#Sta/Elev= 30
  4560.5 1698.88  4588.2 1697.02    4594 1693.74  4609.8 1690.66  4662.9 1684.98
  4674.6 1678.33  4697.7 1671.75  4749.2 1664.91  4786.5 1653.51  4813.8 1650.32
  4882.4 1637.45  4931.6 1632.36  4961.2 1631.88  4961.4 1631.38  4965.2 1631.88
  4997.8 1633.78  5020.9 1632.39  5033.6 1635.14  5065.2 1637.13  5129.9 1646.61
  5210.3 1662.86  5263.2 1674.67  5371.3 1706.39  5392.8 1710.44  5430.2 1721.19
  5443.3 1729.11  5482.5 1741.14    5489 1746.36  5494.8 1746.83  5500.1 1750.55
#Mann= 4 ,-1 , 0
  4560.5     .07       0  4961.2     .05       0  4965.2     .07       0
  5443.3     .12       0
Bank Sta=4961.2,4965.2
XS Rating Curve= 0 ,0
Exp/Cntr=0.3,0.1

Type RM Length L Ch R = 1 ,11563   ,179,179,179
BEGIN DESCRIPTION:
ALLEN CREEK 25.0
END DESCRIPTION:
XS GIS Cut Line= 2
      2025162.16     13861415.59      2025753.58     13860596.61
#Sta/Elev= 30
  4525.1 1685.68  4528.5 1685.68  4535.2 1681.46  4562.8 1674.79    4642 1665.13
  4656.7 1661.45  4821.9 1648.24  4849.3 1643.84    4864 1644.14  4957.6 1632.65
  5113.5 1632.14  5113.7 1631.64  5117.5 1632.14  5142.6 1632.32  5157.2 1634.63
  5201.4 1650.87  5222.2 1654.28  5243.1 1662.79  5287.2  1670.3  5301.9 1672.35
  5315.3 1677.03    5329  1684.3  5352.2 1689.04  5358.4 1692.33  5373.1 1696.29
  5401.6 1709.18  5465.2 1734.01  5500.7 1746.21  5509.3 1747.03  5535.3 1755.49
#Mann= 4 ,-1 , 0
  4525.1     .07       0  5113.5     .05       0  5117.5     .07       0
  5287.2     .12       0
Bank Sta=5113.5,5117.5
XS Rating Curve= 0 ,0
Exp/Cntr=0.3,0.1

Type RM Length L Ch R = 1 ,11384   ,213,213,213
BEGIN DESCRIPTION:
ALLEN CREEK 24.0
END DESCRIPTION:
XS GIS Cut Line= 3
      2025375.02     13861374.98        2025525.       13861175.
      2025824.98     13860875.02
#Sta/Elev= 30
  4755.6  1667.4  4777.4 1666.22  4798.3    1664  4819.1 1660.68  4827.4 1657.89
    4842    1655  4862.9 1653.83  4869.1 1652.83  4877.4 1649.93  4883.7 1651.32
    4892 1650.01  4912.9 1644.38  4927.4 1641.62  4933.7 1641.44  4955.6 1636.34
  4977.4 1633.85  4983.7 1632.32  4996.3  1632.1  4996.5  1631.6  5000.3  1632.1
  5260.1 1632.25  5279.2 1638.04  5316.7 1652.01  5330.8 1654.47  5359.1 1664.24
  5387.4  1671.2  5394.5 1674.96  5415.7 1678.47  5426.3 1681.96  5429.8 1681.96
#Mann= 4 ,-1 , 0
  4755.6     .07       0  4996.3     .05       0  5000.3     .07       0
  5279.2     .12       0
Bank Sta=4996.3,5000.3
XS Rating Curve= 0 ,0
Exp/Cntr=0.3,0.1

Type RM Length L Ch R = 1 ,11171   ,194,194,194
BEGIN DESCRIPTION:
ALLEN CREEK 23.5
END DESCRIPTION:
XS GIS Cut Line= 3
      2025456.24     13861471.83      2025675.13     13861274.67
      2025981.32     13861024.65
#Sta/Elev= 30
  4705.4 1669.04  4730.7 1666.46    4787 1655.56  4801.2 1655.79  4822.9 1652.69
  4851.3 1645.53  4872.2 1636.94  4886.4 1633.96    4929 1634.11  4964.2 1631.94
    5008 1632.63  5011.3 1631.73  5011.5 1631.23  5015.3 1631.73  5021.2 1632.49
  5141.4 1631.95  5236.6 1632.61    5256 1637.61  5262.4 1640.74  5270.3 1641.96
  5276.8 1646.31  5290.3 1647.71  5297.6 1652.74    5312 1658.12  5334.2 1662.71
  5340.7 1666.23  5348.4 1667.18  5361.5 1670.89  5379.4 1672.54  5395.3 1674.56
#Mann= 7 ,-1 , 0
  4705.4     .07       0    5008    .035       0  5011.3     .05       0
  5015.3    .035       0  5141.4     .07       0  5236.6     .12       0
  5379.4     .07       0
Bank Sta=5011.3,5015.3
XS Rating Curve= 0 ,0
Exp/Cntr=0.3,0.1

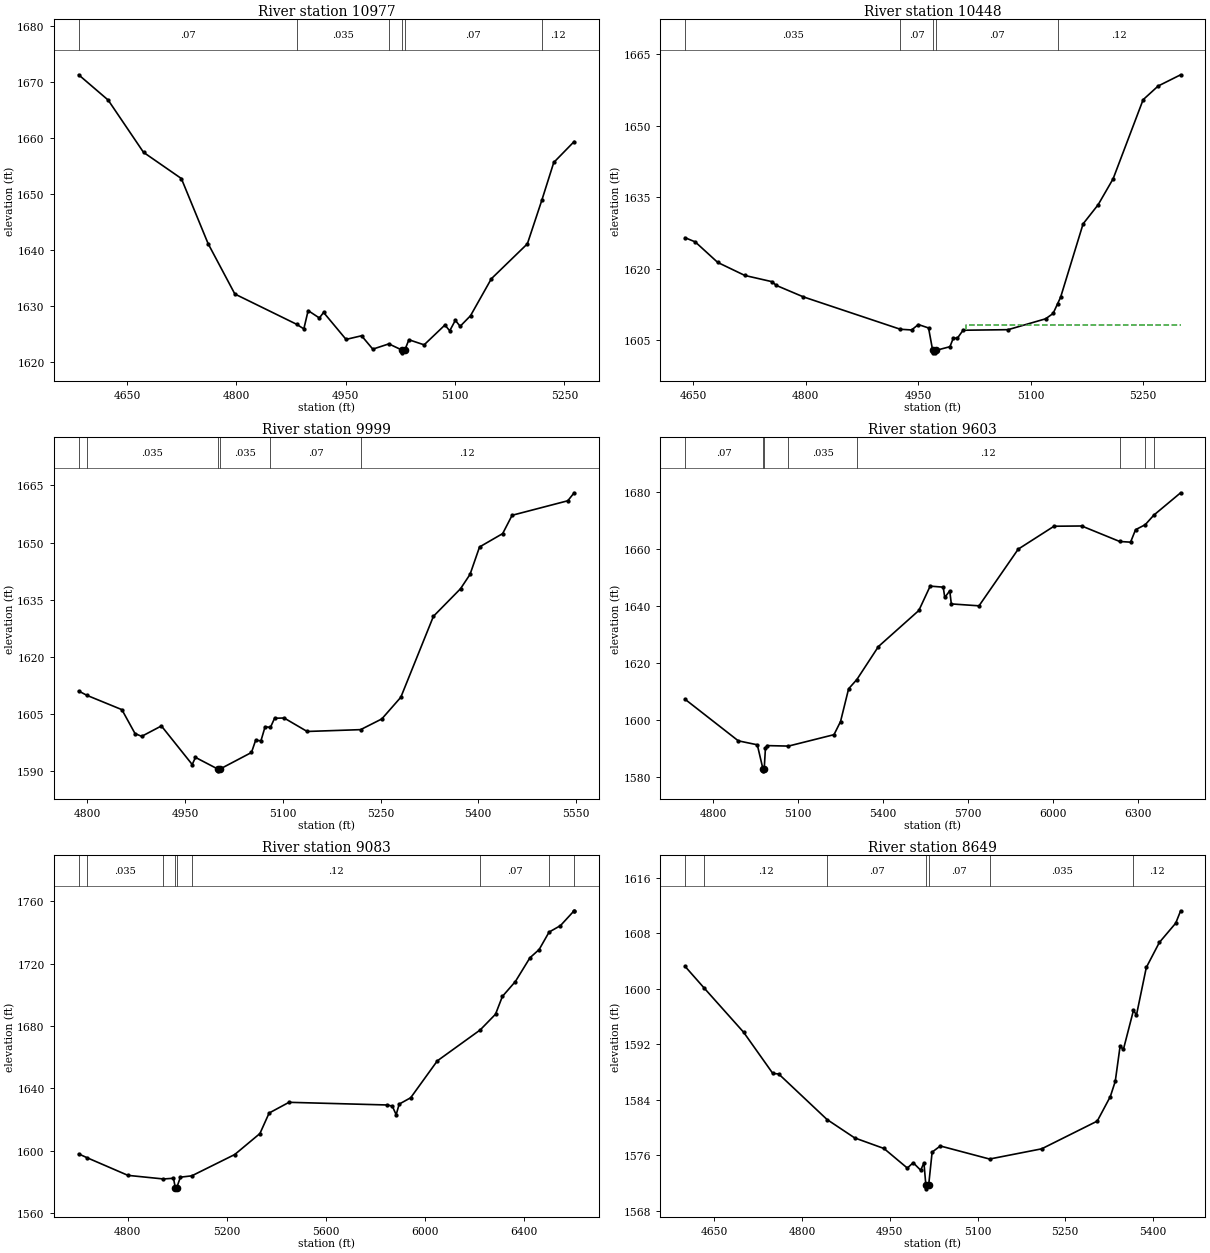
Type RM Length L Ch R = 1 ,10977   ,529,529,529
BEGIN DESCRIPTION:
ALLEN CREEK 23.0
END DESCRIPTION:
XS GIS Cut Line= 3
      2025499.27     13861543.53      2025853.45     13861324.96
      2026025.02     13861124.97
#Sta/Elev= 30
  4583.8 1671.27  4624.3 1666.75  4672.8 1657.41  4724.7 1652.73  4761.4 1641.09
  4798.1 1632.09  4882.7 1626.69  4892.7 1625.86  4898.6 1629.13    4914 1627.81
  4919.8  1628.8  4950.6 1623.98  4971.9 1624.63  4987.3 1622.24  5009.3 1623.18
  5027.2 1622.08  5027.4 1621.58  5031.2 1622.08  5036.8 1623.92  5057.7 1623.01
  5086.2 1626.55  5092.8 1625.52  5100.5 1627.39  5107.1 1626.32  5121.3 1628.21
  5149.9 1634.82  5199.3 1641.06  5219.1 1648.84  5235.5  1655.6  5263.5 1659.34
#Mann= 6 ,-1 , 0
  4583.8     .07       0  4882.7    .035       0  5009.3     .07       0
  5027.2    .035       0  5031.2     .07       0  5219.1     .12       0
Bank Sta=5027.2,5031.2
XS Rating Curve= 0 ,0
Exp/Cntr=0.3,0.1

Type RM Length L Ch R = 1 ,10448   ,449,449,449
BEGIN DESCRIPTION:
ALLEN CREEK 22.0
END DESCRIPTION:
XS GIS Cut Line= 3
      2026125.02     13861774.97        2026325.       13861475.
        2026325.     13861175.02
#Sta/Elev= 30
  4639.4 1626.47  4652.9 1625.59  4682.9 1621.28    4719 1618.55    4755 1617.25
  4761.1 1616.45  4797.1 1614.05  4926.2 1607.26  4941.3 1607.11  4950.3 1608.25
  4963.9 1607.53  4969.4 1602.81  4969.6 1602.31  4973.1 1602.31  4973.4 1602.81
  4992.4  1603.6  4996.9  1605.4  5002.4  1605.4  5009.9 1607.05  5069.9 1607.17
  5119.9 1609.45  5129.9 1610.57  5135.8 1612.58  5139.9 1613.97  5169.9 1629.38
  5189.9 1633.38  5209.9 1638.83  5249.9 1655.43  5269.9  1658.3  5299.9 1660.66
#Mann= 5 ,-1 , 0
  4639.4    .035       0  4926.2     .07       0  4969.4     .05       0
  4973.4     .07       0  5135.8     .12       0
#XS Ineff= 2 , 0
       0                  5013.3       0 1608.22
Permanent Ineff=
       F       F
Bank Sta=4969.4,4973.4
XS Rating Curve= 0 ,0
Exp/Cntr=0.3,0.1

Type RM Length L Ch R = 1 ,9999    ,396,396,396
BEGIN DESCRIPTION:
ALLEN CREEK 21.0
END DESCRIPTION:
XS GIS Cut Line= 3
      2026369.43     13861742.57        2026575.       13861775.
      2026905.88     13861332.18
#Sta/Elev= 30
  4786.4    1611  4799.1 1609.86  4852.8  1606.1    4873 1599.82  4883.2 1599.09
  4913.5 1601.82  4960.8 1591.69  4965.8 1593.56  4999.8 1590.53  5000.1 1590.03
  5003.8 1590.53  5051.8 1594.85  5058.1 1598.01  5066.4 1597.95  5072.7 1601.61
  5080.9 1601.44  5087.3 1603.84  5101.9 1603.91  5137.3 1600.37  5219.4 1600.85
  5251.9 1603.66  5281.1 1609.35  5331.2 1630.62  5372.8 1637.86  5387.4 1641.63
    5402 1648.83  5437.5 1652.34    5452 1657.15  5537.5 1660.96  5547.3 1663.06
#Mann= 6 ,-1 , 0
  4786.4     .07       0  4799.1    .035       0  4999.8    .035       0
  5003.8    .035       0  5080.9     .07       0  5219.4     .12       0
Bank Sta=4999.8,5003.8
XS Rating Curve= 0 ,0
Exp/Cntr=0.3,0.1

Type RM Length L Ch R = 1 ,9603    ,520,520,520
BEGIN DESCRIPTION:
ALLEN CREEK 20.0
END DESCRIPTION:
XS GIS Cut Line= 3
      2026536.95     13862187.22      2026806.05     13862052.67
      2027405.01     13860733.22
#Sta/Elev= 30
    4701 1607.39  4888.9 1592.84    4956 1591.45  4976.3 1582.83  4976.6 1582.33
  4980.3 1582.83  4984.7 1590.27  4990.3 1591.17    5066    1591  5226.8    1595
  5249.9  1599.6  5278.4 1611.07  5307.6 1614.32  5383.7 1625.87  5526.4  1638.5
  5566.4 1647.03  5612.5 1646.67    5618 1643.05  5635.6  1645.4  5641.1  1640.8
  5738.9 1640.13  5877.4 1659.99  6003.7 1668.01  6101.5  1668.1  6235.6 1662.67
  6274.1 1662.43  6291.7  1666.8  6325.8 1668.54  6356.4 1671.92  6450.9 1679.73
#Mann= 8 ,-1 , 0
    4701     .07       0  4976.3     .05       0  4980.3     .07       0
    5066    .035       0  5307.6     .12       0  6235.6     .07       0
  6325.8     .12       0  6356.4     .07       0
Bank Sta=4976.3,4980.3
XS Rating Curve= 0 ,0
Exp/Cntr=0.3,0.1

Type RM Length L Ch R = 1 ,9083    ,434,434,434
BEGIN DESCRIPTION:
ALLEN CREEK 19.0
END DESCRIPTION:
XS GIS Cut Line= 3
      2026675.01       13862425.        2027075.       13862475.
      2028455.37     13861670.71
#Sta/Elev= 30
  4601.8 1597.85  4635.5 1595.41  4800.8 1584.05  4944.3 1581.73  4984.7 1582.19
  4992.5 1575.89  4992.8 1575.39  4997.2 1575.89  5012.8 1582.89  5058.6 1583.74
    5232 1597.43  5333.7 1610.91  5370.9 1624.09  5451.2 1630.98  5846.5 1629.27
  5868.1 1628.55  5883.8 1623.04  5896.1 1629.84  5942.4 1633.91    6050 1657.62
  6222.8 1677.44  6284.9 1687.57  6312.7 1699.01  6365.2 1708.59  6423.9 1723.84
  6461.1 1729.14  6501.2 1740.34  6547.2 1744.51  6602.2 1754.03  6602.5 1754.03
#Mann= 9 ,-1 , 0
  4601.8     .07       0  4635.5    .035       0  4944.3     .07       0
  4992.5     .05       0  4997.2     .07       0  5058.6     .12       0
  6222.8     .07       0  6501.2     .12       0  6602.2     .07       0
Bank Sta=4992.5,4997.2
XS Rating Curve= 0 ,0
Exp/Cntr=0.3,0.1

Type RM Length L Ch R = 1 ,8649    ,452,452,452
BEGIN DESCRIPTION:
ALLEN CREEK 18.0
END DESCRIPTION:
XS GIS Cut Line= 3
      2026574.96       13862875.        2026975.       13862875.
      2027375.04     13862674.98
#Sta/Elev= 30
  4599.9 1603.21  4632.9 1600.06  4699.9 1593.74  4749.9  1587.8  4759.9 1587.73
  4842.6 1581.17  4889.9 1578.52  4939.9    1577  4979.9 1574.18  4989.9 1574.95
  5002.7 1573.87  5008.3 1574.93  5011.6 1571.69  5011.9 1571.19  5016.3 1571.69
  5022.3 1576.48  5036.3 1577.36  5120.5 1575.48  5209.6 1576.95  5304.6 1580.94
    5327 1584.48  5335.4 1586.66  5343.7 1591.74  5349.3 1591.25  5366.5 1596.87
  5371.7 1596.22  5388.5 1603.06  5410.8 1606.66  5438.8 1609.44  5447.2 1611.22
#Mann= 7 ,-1 , 0
  4599.9     .07       0  4632.9     .12       0  4842.6     .07       0
  5011.6     .05       0  5016.3     .07       0  5120.5    .035       0
  5366.5     .12       0
Bank Sta=5011.6,5016.3
XS Rating Curve= 0 ,0
Exp/Cntr=0.3,0.1

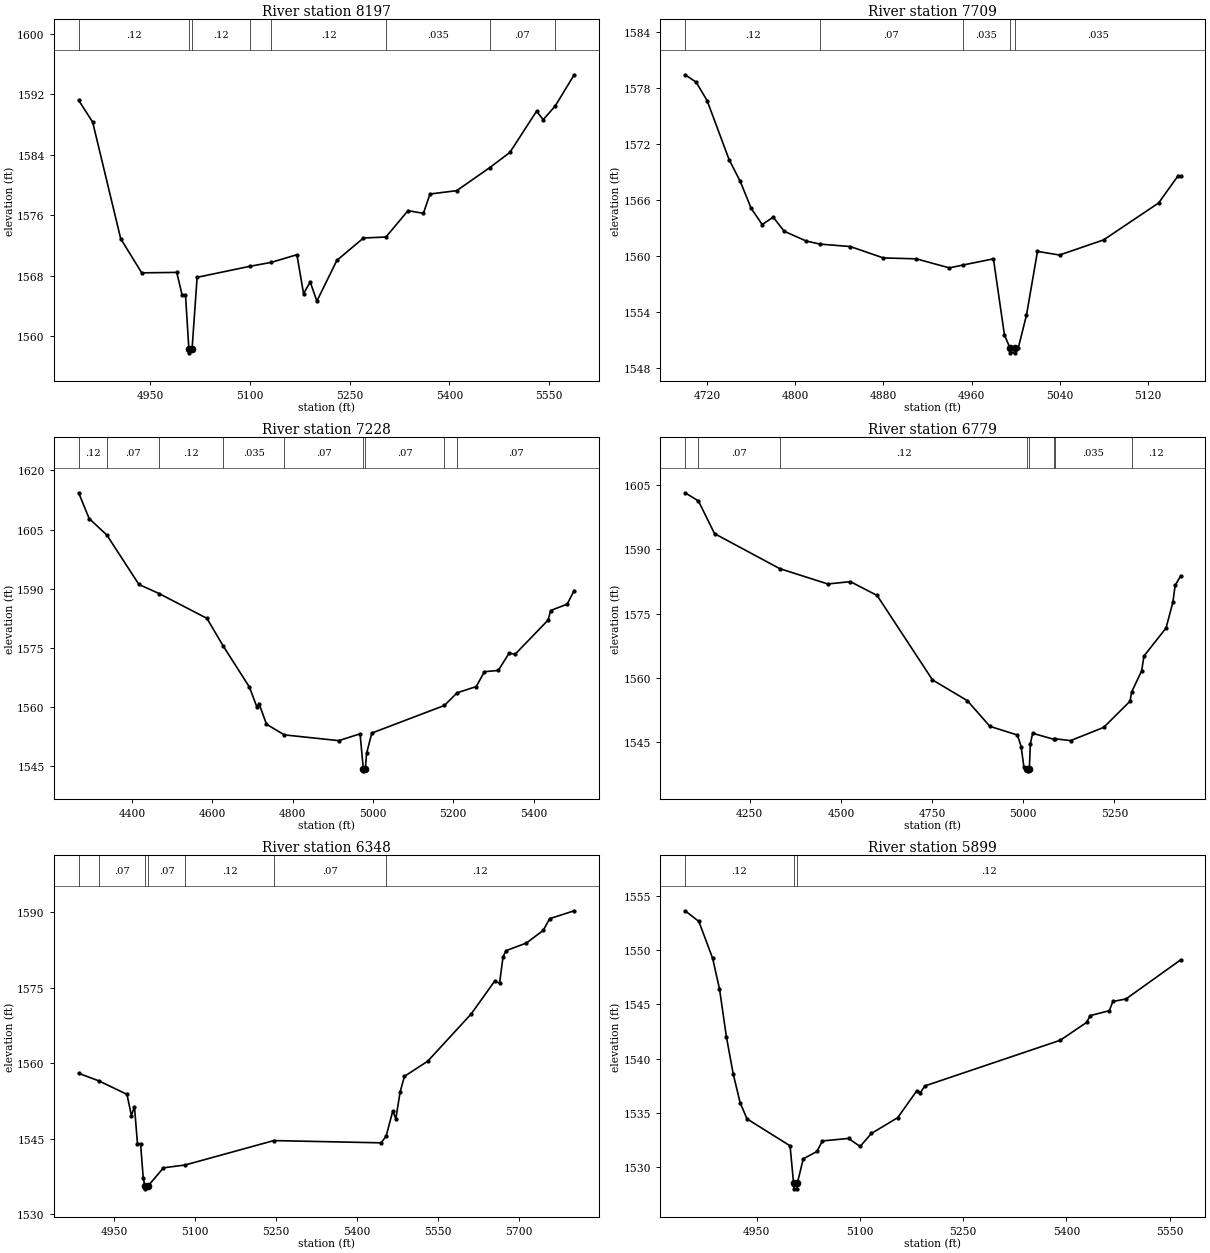
Type RM Length L Ch R = 1 ,8197    ,488,488,488
BEGIN DESCRIPTION:
ALLEN CREEK 17.0
END DESCRIPTION:
XS GIS Cut Line= 3
      2026674.96     13863224.99        2026825.       13863275.
      2027411.57     13863300.97
#Sta/Elev= 30
  4842.3 1591.22  4863.4 1588.33  4905.6  1572.9  4937.2 1568.39  4989.9 1568.45
  4997.8  1565.5    5003  1565.5  5008.1 1558.31  5008.4 1557.81  5012.9 1558.31
  5020.5  1567.8  5099.5 1569.25  5132.1 1569.78  5170.6 1570.79  5180.6 1565.64
  5190.6 1567.19  5200.6 1564.65  5230.7 1570.04  5270.7    1573  5304.5 1573.13
  5337.7 1576.62  5360.8 1576.26  5370.8 1578.82  5410.9 1579.26  5460.5  1582.3
  5490.9 1584.32    5531 1589.77    5541 1588.65    5559 1590.45  5587.6 1594.59
#Mann= 8 ,-1 , 0
  4842.3     .12       0  5008.1     .05       0  5012.9     .12       0
  5099.5     .07       0  5132.1     .12       0  5304.5    .035       0
  5460.5     .07       0    5559     .12       0
Bank Sta=5008.1,5012.9
XS Rating Curve= 0 ,0
Exp/Cntr=0.3,0.1

Type RM Length L Ch R = 1 ,7709    ,481,481,481
BEGIN DESCRIPTION:
ALLEN CREEK 16.0
END DESCRIPTION:
XS GIS Cut Line= 3
      2026624.98       13863725.        2026925.       13863725.
      2027074.98       13863725.
#Sta/Elev= 30
  4699.9 1579.46  4709.9 1578.67  4719.9 1576.69  4739.9 1570.35  4749.9 1568.05
  4759.9 1565.14  4769.9  1563.4  4779.9 1564.19  4789.9 1562.68  4809.9 1561.63
  4822.5  1561.3  4849.9 1561.04  4879.9 1559.82  4909.9 1559.72  4939.9 1558.75
  4951.9 1559.05  4979.9 1559.72  4989.9 1551.56    4995 1550.14  4995.3 1549.64
  4999.5 1549.64  4999.9 1550.14  5002.4 1550.14  5009.9 1553.68  5019.9 1560.52
  5039.9 1560.13  5079.9 1561.75  5129.9 1565.71  5147.4  1568.6  5149.9  1568.6
#Mann= 5 ,-1 , 0
  4699.9     .12       0  4822.5     .07       0  4951.9    .035       0
    4995    .035       0  4999.9    .035       0
Bank Sta=4995,4999.9
XS Rating Curve= 0 ,0
Exp/Cntr=0.3,0.1

Type RM Length L Ch R = 1 ,7228    ,449,449,449
BEGIN DESCRIPTION:
ALLEN CREEK 15.0
END DESCRIPTION:
XS GIS Cut Line= 3
      2026133.33     13863932.02        2026825.       13864175.
      2027311.89     13864054.03
#Sta/Elev= 30
  4266.5 1614.34  4292.7 1607.81  4336.8 1603.63  4416.7 1591.12  4467.7 1588.77
  4586.2 1582.52  4626.1 1575.63  4692.2 1565.09  4710.6 1560.09  4715.9 1560.95
  4734.6  1555.7  4779.1    1553  4914.8 1551.54  4967.8 1553.27  4975.9 1544.39
  4976.3 1543.89  4980.9 1544.39  4984.1 1548.33    4997 1553.46  5177.9 1560.45
  5209.6 1563.66  5257.2 1565.24  5277.8 1569.01  5312.3 1569.33  5339.6 1573.79
  5353.6 1573.37  5436.3 1582.08  5442.7 1584.51  5483.9 1586.12  5501.3 1589.57
#Mann= 9 ,-1 , 0
  4266.5     .12       0  4336.8     .07       0  4467.7     .12       0
  4626.1    .035       0  4779.1     .07       0  4975.9     .05       0
  4980.9     .07       0  5177.9    .035       0  5209.6     .07       0
Bank Sta=4975.9,4980.9
XS Rating Curve= 0 ,0
Exp/Cntr=0.3,0.1

Type RM Length L Ch R = 1 ,6779    ,431,431,431
BEGIN DESCRIPTION:
ALLEN CREEK 14.0
END DESCRIPTION:
XS GIS Cut Line= 3
      2025955.32     13864721.95        2026875.       13864575.
      2027274.96     13864425.02
#Sta/Elev= 30
  4072.9 1603.22  4109.4 1601.32  4153.6 1593.68  4332.1 1585.51    4464 1581.92
  4526.1 1582.46  4599.2 1579.24  4751.1 1559.51  4846.5 1554.67  4908.6 1548.66
    4984 1546.63  4994.1 1543.94  5001.7 1539.18  5011.4 1538.77  5011.8 1538.27
  5016.7 1538.77  5019.4 1544.61  5025.6 1547.04  5084.2 1545.63    5086 1545.77
  5129.7 1545.33  5220.5 1548.42  5292.6 1554.53  5297.2  1556.7  5324.6 1561.66
  5330.9 1565.09  5391.4 1571.63  5410.1 1577.64  5416.3 1581.57  5431.4 1583.81
#Mann= 8 ,-1 , 0
  4072.9     .12       0  4109.4     .07       0  4332.1     .12       0
  5011.4     .05       0  5016.7     .12       0  5084.2     .07       0
    5086    .035       0  5297.2     .12       0
Bank Sta=5011.4,5016.7
XS Rating Curve= 0 ,0
Exp/Cntr=0.3,0.1

Type RM Length L Ch R = 1 ,6348    ,449,449,449
BEGIN DESCRIPTION:
ALLEN CREEK 13.0
END DESCRIPTION:
XS GIS Cut Line= 3
      2026624.99       13864875.        2026725.       13864925.
      2027424.97     13864525.02
#Sta/Elev= 30
  4884.4 1557.95  4922.2 1556.44  4973.9 1553.77  4982.2 1549.56  4987.8 1551.34
  4993.4 1543.99  4999.1 1543.99  5004.1 1537.14  5007.2  1535.5  5007.6    1535
  5012.5  1535.5  5041.6 1539.18  5081.8 1539.74    5246 1544.59  5444.7 1544.14
  5454.1 1545.48  5466.3 1550.44    5472 1548.93  5479.9  1554.2  5487.9 1557.35
  5531.1 1560.36  5611.7 1569.76  5654.9 1576.24  5664.2 1575.88  5670.7 1581.15
  5676.5 1582.34  5713.9 1583.84  5744.9 1586.34  5757.1 1588.68  5802.4 1590.25
#Mann= 7 ,-1 , 0
  4884.4     .12       0  4922.2     .07       0  5007.2     .05       0
  5012.5     .07       0  5081.8     .12       0    5246     .07       0
  5454.1     .12       0
Bank Sta=5007.2,5012.5
XS Rating Curve= 0 ,0
Exp/Cntr=0.3,0.1

Type RM Length L Ch R = 1 ,5899    ,486,486,486
BEGIN DESCRIPTION:
ALLEN CREEK 12.0
END DESCRIPTION:
XS GIS Cut Line= 3
      2026725.03       13865325.        2026875.       13865325.
      2027421.14     13865160.68
#Sta/Elev= 30
  4845.7 1553.61  4865.7 1552.63  4885.7 1549.24  4895.7 1546.42  4905.7 1542.02
  4915.7 1538.57  4925.7 1535.94  4935.7 1534.45  4998.3 1531.97  5003.4 1528.51
  5003.8 1528.01  5008.4 1528.01  5008.8 1528.51  5017.4 1530.77  5037.4 1531.45
  5045.2 1532.42  5083.4 1532.65  5100.1 1531.91  5116.5 1533.11  5154.7 1534.56
  5182.5 1537.04  5187.7 1536.86  5194.1 1537.48    5391 1541.69  5429.3 1543.33
  5434.5 1543.96  5462.3 1544.41  5467.5 1545.26  5486.5 1545.49    5566 1549.09
#Mann= 3 ,-1 , 0
  4845.7     .12       0  5003.4     .05       0  5008.8     .12       0
Bank Sta=5003.4,5008.8
XS Rating Curve= 0 ,0
Exp/Cntr=0.3,0.1

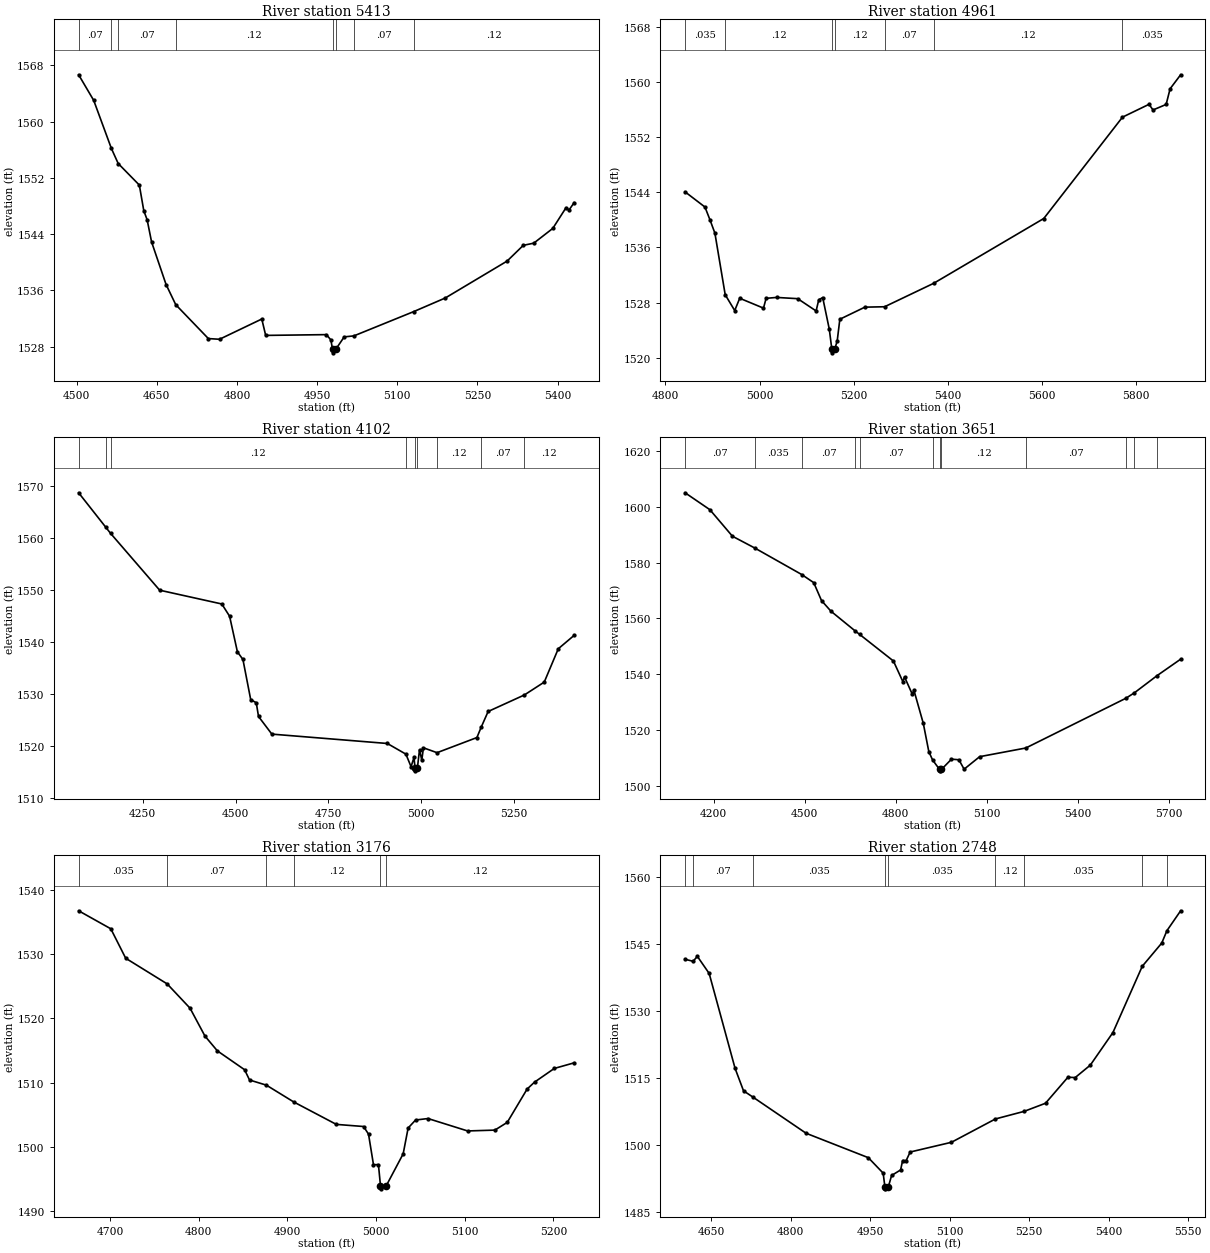
Type RM Length L Ch R = 1 ,5413    ,452,452,452
BEGIN DESCRIPTION:
ALLEN CREEK 11.0
END DESCRIPTION:
XS GIS Cut Line= 3
      2026574.97     13865474.98        2026975.       13865775.
      2027374.97     13865625.01
#Sta/Elev= 30
  4503.8 1566.66    4532 1563.02  4565.1 1556.18  4577.8 1554.04  4617.4 1550.97
  4625.7 1547.33    4632 1546.03  4640.3 1542.88  4667.4 1536.83  4685.5 1533.96
  4746.5 1529.14  4767.4 1529.04  4846.5 1531.92  4853.8 1529.59  4967.4  1529.7
  4975.7 1528.95    4979 1527.61  4979.5 1527.11  4984.9 1527.61  5000.7 1529.38
  5018.8 1529.52  5130.6 1532.97  5189.8 1534.91  5305.5 1540.16  5335.8  1542.4
  5355.4 1542.71    5391 1544.81  5415.9 1547.77  5421.2 1547.41    5431 1548.48
#Mann= 8 ,-1 , 0
  4503.8     .07       0  4565.1    .035       0  4577.8     .07       0
  4685.5     .12       0    4979     .05       0  4984.9     .12       0
  5018.8     .07       0  5130.6     .12       0
Bank Sta=4979,4984.9
XS Rating Curve= 0 ,0
Exp/Cntr=0.3,0.1

Type RM Length L Ch R = 1 ,4961    ,859,859,859
BEGIN DESCRIPTION:
ALLEN CREEK 10.0
END DESCRIPTION:
XS GIS Cut Line= 3
      2026624.96     13866075.01        2026775.       13866025.
      2027575.02     13865624.99
#Sta/Elev= 30
  4841.9 1544.05  4884.1 1541.85  4894.6 1540.02  4905.2 1538.07  4927.1 1529.14
  4947.3 1526.85  4957.9 1528.63  5008.4  1527.2    5014 1528.62  5036.4 1528.75
  5081.1 1528.57  5120.2 1526.79  5125.8 1528.41  5134.2 1528.73  5148.2 1524.15
  5153.6 1521.22  5154.1 1520.72  5159.6 1521.22    5165 1522.44  5170.6 1525.59
  5223.7 1527.34  5265.7  1527.4    5370  1530.8  5603.8 1540.19    5771 1554.88
  5827.4 1556.74  5835.8 1555.92  5863.7 1556.72  5872.1 1558.99  5894.5 1561.02
#Mann= 7 ,-1 , 0
  4841.9    .035       0  4927.1     .12       0  5153.6     .05       0
  5159.6     .12       0  5265.7     .07       0    5370     .12       0
    5771    .035       0
Bank Sta=5153.6,5159.6
XS Rating Curve= 0 ,0
Exp/Cntr=0.3,0.1

Type RM Length L Ch R = 1 ,4102    ,451,451,451
BEGIN DESCRIPTION:
ALLEN CREEK 9.0
END DESCRIPTION:
XS GIS Cut Line= 3
      2026154.99     13865950.23        2026925.       13866475.
      2027324.97       13866425.
#Sta/Elev= 30
  4077.3 1568.72  4149.8 1562.15  4163.2 1560.93  4295.6 1549.99    4463 1547.34
    4484 1544.98    4505 1538.14  4519.9 1536.67  4540.9 1528.93  4555.8 1528.36
  4561.9 1525.71  4597.8 1522.32  4908.9 1520.52  4958.9 1518.47  4972.8 1516.06
  4980.7 1517.83  4983.6 1515.76  4984.1 1515.26  4989.8 1515.76  4995.6 1519.33
  5001.7  1517.3  5006.1 1519.69  5042.8 1518.75  5150.2 1521.66  5161.6 1523.63
  5180.4 1526.67  5278.1 1529.85  5331.6 1532.32  5369.4 1538.73  5412.2 1541.31
#Mann= 9 ,-1 , 0
  4077.3     .12       0  4149.8     .07       0  4163.2     .12       0
  4958.9     .07       0  4983.6     .05       0  4989.8     .07       0
  5042.8     .12       0  5161.6     .07       0  5278.1     .12       0
Bank Sta=4983.6,4989.8
XS Rating Curve= 0 ,0
Exp/Cntr=0.3,0.1

Type RM Length L Ch R = 1 ,3651    ,475,475,475
BEGIN DESCRIPTION:
ALLEN CREEK 8.0
END DESCRIPTION:
XS GIS Cut Line= 3
        2025938.     13867169.86        2026775.       13866875.
      2027448.44     13866557.86
#Sta/Elev= 30
    4106 1604.98  4187.6 1598.92  4261.9 1589.41  4334.9 1585.22  4489.9  1575.7
  4529.6 1572.78  4555.2 1566.36  4586.2 1562.56  4666.6 1555.43  4680.3 1554.28
    4792 1544.71  4823.2 1537.29  4828.5 1539.02  4854.1 1532.82  4859.4 1534.28
  4890.4 1522.36  4908.6 1512.22  4921.1 1509.24  4943.9 1505.86  4944.4 1505.36
  4950.1 1505.86  4983.2 1509.54  5007.6 1509.33  5024.8 1505.95  5075.9 1510.43
  5227.9 1513.54  5557.3 1531.35  5585.6 1533.32  5660.7 1539.51  5737.8 1545.36
#Mann= 12 ,-1 , 0
    4106     .07       0  4334.9    .035       0  4489.9     .07       0
  4666.6     .12       0  4680.3     .07       0  4921.1     .12       0
  4943.9     .05       0  4950.1     .12       0  5227.9     .07       0
  5557.3     .12       0  5585.6     .07       0  5660.7     .12       0
Bank Sta=4943.9,4950.1
XS Rating Curve= 0 ,0
Exp/Cntr=0.3,0.1

Type RM Length L Ch R = 1 ,3176    ,428,428,428
BEGIN DESCRIPTION:
ALLEN CREEK 7.0
END DESCRIPTION:
XS GIS Cut Line= 3
      2026775.03     13867324.98        2027075.       13867175.
      2027275.02     13867074.99
#Sta/Elev= 30
  4664.4 1536.71  4700.7 1533.91  4717.5 1529.33  4764.3 1525.34  4790.1 1521.56
  4806.9 1517.23  4820.9 1514.93  4851.6    1512  4857.2  1510.4  4876.2  1509.6
  4906.9    1507  4955.1  1503.5  4985.8 1503.17  4991.4 1501.99    4997 1497.24
  5002.6 1497.24  5004.9 1493.98  5005.4 1493.48  5011.5 1493.98  5030.5 1498.92
  5036.1 1502.94  5044.5 1504.18  5058.5 1504.41  5103.2 1502.48  5133.9 1502.61
  5147.9 1503.81  5170.3 1508.99  5178.7 1510.07    5201  1512.2  5223.4 1513.07
#Mann= 6 ,-1 , 0
  4664.4    .035       0  4764.3     .07       0  4876.2    .035       0
  4906.9     .12       0  5004.9     .05       0  5011.5     .12       0
Bank Sta=5004.9,5011.5
XS Rating Curve= 0 ,0
Exp/Cntr=0.3,0.1

Type RM Length L Ch R = 1 ,2748    ,459,459,459
BEGIN DESCRIPTION:
ALLEN CREEK 6.0
END DESCRIPTION:
XS GIS Cut Line= 3
      2026924.97     13867725.02        2027275.       13867525.
      2027675.03     13867174.97
#Sta/Elev= 30
    4601 1541.58  4616.2 1541.14  4624.1 1542.25  4646.4 1538.41  4695.3 1517.11
  4711.2 1512.08  4729.1 1510.66  4829.2 1502.56  4946.6 1497.08  4974.6 1493.61
  4977.8 1490.59  4978.3 1490.09  4984.5 1490.59  4990.5 1493.09  5007.5 1494.33
  5011.3 1496.43  5017.9 1496.41  5025.5 1498.35  5103.3 1500.53  5186.4 1505.77
  5240.5 1507.47  5280.8 1509.29  5323.1 1515.13  5336.8 1515.05  5365.3 1517.84
    5408 1525.16  5463.3 1540.02  5500.1 1545.23  5509.8    1548  5535.7 1552.47
#Mann= 9 ,-1 , 0
    4601     .12       0  4616.2     .07       0  4729.1    .035       0
  4977.8    .035       0  4984.5    .035       0  5186.4     .12       0
  5240.5    .035       0  5463.3     .07       0  5509.8     .12       0
Bank Sta=4977.8,4984.5
XS Rating Curve= 0 ,0
Exp/Cntr=0.3,0.1

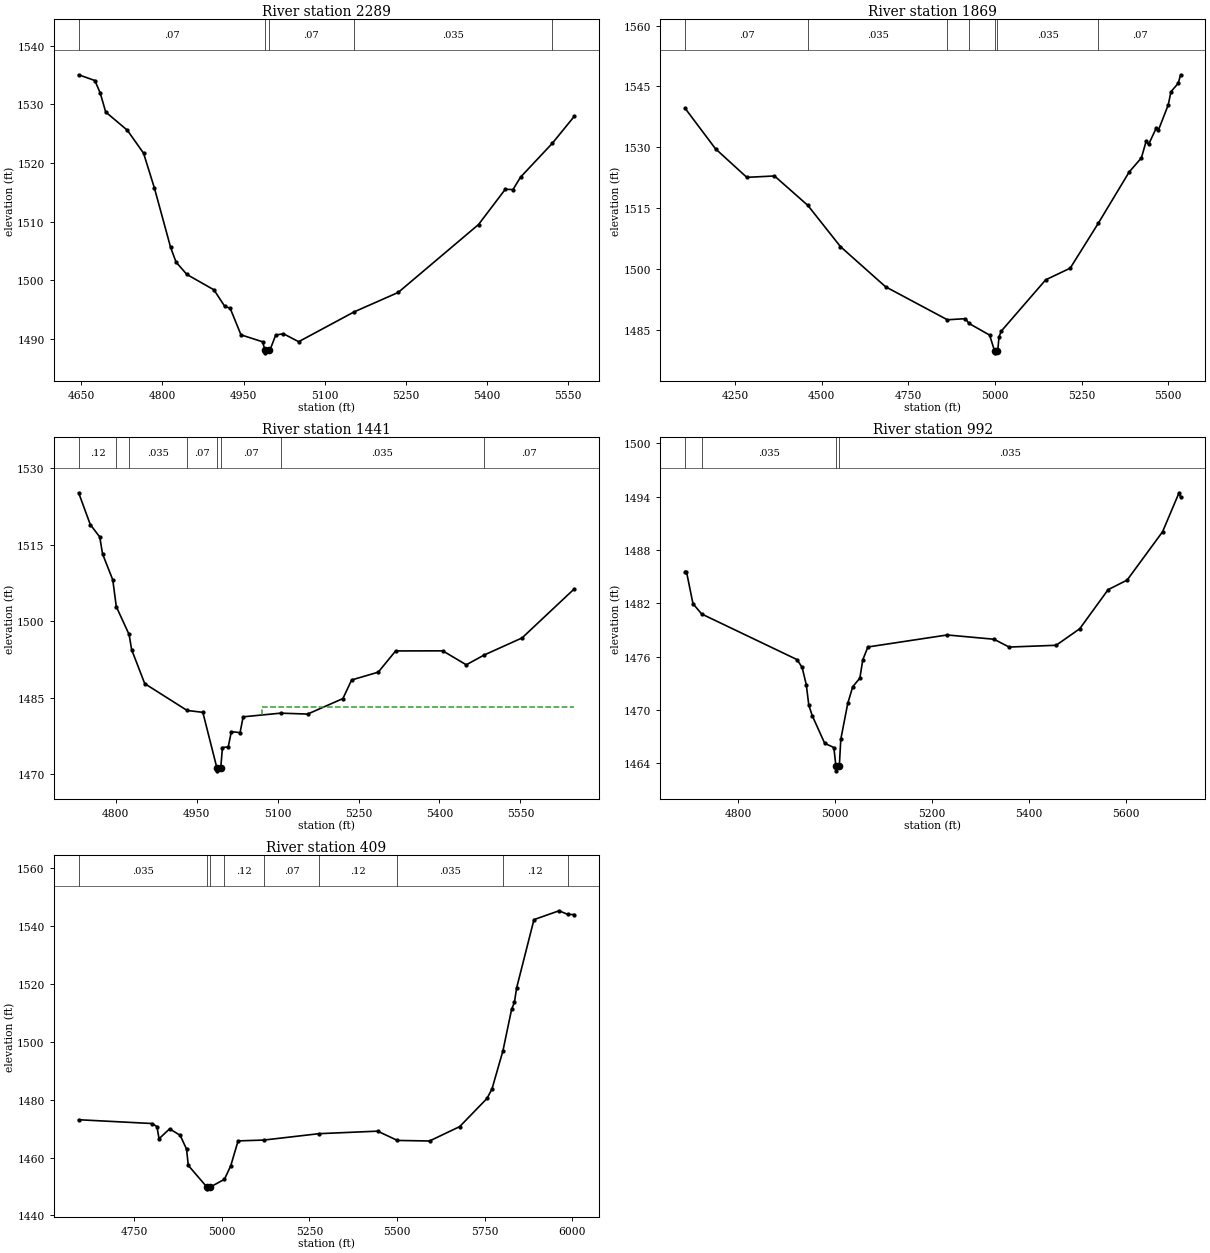
Type RM Length L Ch R = 1 ,2289    ,420,420,420
BEGIN DESCRIPTION:
ALLEN CREEK 5.0
END DESCRIPTION:
XS GIS Cut Line= 3
      2027074.96       13867925.        2027425.       13867925.
      2027824.98     13867525.02
#Sta/Elev= 30
  4645.2 1535.06  4675.2 1534.08  4685.2 1531.92  4695.2 1528.71  4735.2  1525.6
  4765.2 1521.68  4785.2 1515.75  4815.2 1505.61  4825.2 1503.11  4845.2    1501
  4895.2 1498.38  4915.2 1495.56  4925.2 1495.24  4945.2  1490.7  4985.2 1489.51
  4989.3 1488.13  4989.8 1487.63  4996.1 1488.13  4998.8 1488.13  5009.4 1490.66
  5023.5 1490.89  5051.8 1489.53  5154.4 1494.62  5235.7 1497.93  5384.2 1509.52
  5433.6 1515.53  5447.8 1515.48  5461.9 1517.61  5520.3 1523.35  5560.9 1527.95
#Mann= 5 ,-1 , 0
  4645.2     .07       0  4989.3     .05       0  4996.1     .07       0
  5154.4    .035       0  5520.3     .12       0
Bank Sta=4989.3,4996.1
XS Rating Curve= 0 ,0
Exp/Cntr=0.3,0.1

Type RM Length L Ch R = 1 ,1869    ,428,428,428
BEGIN DESCRIPTION:
ALLEN CREEK 4.0
END DESCRIPTION:
XS GIS Cut Line= 3
      2026877.35     13868180.75        2027775.       13868125.
      2028125.01     13867724.99
#Sta/Elev= 30
  4105.2 1539.63    4193 1529.66  4283.4 1522.63  4363.3 1522.97  4459.6 1515.73
  4553.7 1505.59    4684  1495.7  4862.5 1487.57  4914.4 1487.84  4925.1 1486.66
  4984.5  1483.8  4998.7 1479.93  4999.2 1479.43  5005.5 1479.93  5007.9 1479.93
  5011.7 1483.38  5018.3 1484.79  5146.5 1497.41  5217.2 1500.27  5298.6 1511.37
  5387.5 1523.95  5422.7 1527.41  5436.9 1531.62  5443.5 1530.72  5465.4 1534.72
    5472 1534.26  5500.5 1540.52  5508.1 1543.71    5529 1545.77  5536.1 1547.88
#Mann= 7 ,-1 , 0
  4105.2     .07       0  4459.6    .035       0  4862.5     .12       0
  4925.1    .035       0  4998.7    .035       0  5005.5    .035       0
  5298.6     .07       0
Bank Sta=4998.7,5005.5
XS Rating Curve= 0 ,0
Exp/Cntr=0.3,0.1

Type RM Length L Ch R = 1 ,1441    ,449,449,449
BEGIN DESCRIPTION:
ALLEN CREEK 3.0
END DESCRIPTION:
XS GIS Cut Line= 3
      2027524.98     13868625.01        2027775.       13868525.
      2028086.42     13867955.46
#Sta/Elev= 30
  4731.2 1525.23  4752.8    1519  4770.3 1516.57  4775.6 1513.22  4794.5 1508.15
    4801  1502.9  4824.7 1497.45  4829.5 1494.45  4853.7 1487.81  4932.2 1482.55
  4961.4 1482.18  4987.6 1471.21  4988.1 1470.71  4994.5 1471.21  4997.8 1475.28
  5008.5 1475.41  5014.2  1478.4  5030.4  1478.2  5036.1  1481.3  5105.6 1482.02
  5155.6 1481.84    5221 1484.88  5237.2 1488.53  5286.5 1490.06  5318.7 1494.22
    5406 1494.24  5449.6  1491.5    5483 1493.43    5553 1496.77  5649.6 1506.37
#Mann= 8 ,-1 , 0
  4731.2     .12       0    4801     .07       0  4824.7    .035       0
  4932.2     .07       0  4987.6     .05       0  4994.5     .07       0
  5105.6    .035       0    5483     .07       0
#XS Ineff= 2 , 0
       0                 5070.81       0 1483.19
Permanent Ineff=
       F       F
Bank Sta=4987.6,4994.5
XS Rating Curve= 0 ,0
Exp/Cntr=0.3,0.1

Type RM Length L Ch R = 1 ,992     ,583,583,583
BEGIN DESCRIPTION:
ALLEN CREEK 2.0
END DESCRIPTION:
XS GIS Cut Line= 3
      2027834.71     13868814.82        2028125.       13868725.
       2028320.4     13868035.01
#Sta/Elev= 30
  4691.2 1485.57    4694 1485.57  4707.4 1481.96  4725.3  1480.8  4921.8 1475.67
  4932.3  1474.8  4940.9 1472.84  4946.1 1470.54  4953.2 1469.36  4978.8 1466.26
  4997.7 1465.78    5002 1463.66  5002.5 1463.16  5008.9 1463.66    5012 1466.71
  5026.3 1470.74  5036.6 1472.62  5051.2 1473.58  5057.4 1475.66  5067.8 1477.09
  5231.3 1478.44  5327.7 1477.96  5358.8 1477.08  5455.7 1477.28  5504.3 1479.14
  5562.7 1483.53  5601.9 1484.61  5674.9 1490.04  5708.9 1494.43  5712.2 1493.93
#Mann= 4 ,-1 , 0
  4691.2     .07       0  4725.3    .035       0    5002    .035       0
  5008.9    .035       0
Bank Sta=5002,5008.9
XS Rating Curve= 0 ,0
Exp/Cntr=0.3,0.1

Type RM Length L Ch R = 1 ,409     ,0,0,0
BEGIN DESCRIPTION:
ALLEN CREEK 1.0
END DESCRIPTION:
XS GIS Cut Line= 3
      2028166.88     13869075.12      2028573.37     13869028.94
      2029217.33     13868256.45
#Sta/Elev= 30
  4590.9 1473.08  4800.4 1471.77  4814.4 1470.73  4820.5 1466.51  4850.7 1469.93
  4880.9 1467.68    4899  1462.9    4904 1457.28  4957.9 1449.68  4958.4 1449.18
  4964.8 1449.68  5007.2 1452.47  5025.3 1457.19  5046.1 1465.76  5119.8 1466.05
  5277.3 1468.26  5444.5 1469.13  5501.1 1465.92  5592.8 1465.73  5678.8  1470.7
  5756.9 1480.45  5771.2 1483.78  5802.3 1496.91  5827.1 1511.29    5835 1513.63
  5841.5 1518.72  5890.9 1542.29  5962.5 1545.35  5987.8 1544.08  6005.7 1544.05
#Mann= 9 ,-1 , 0
  4590.9    .035       0  4957.9    .035       0  4964.8    .035       0
  5007.2     .12       0  5119.8     .07       0  5277.3     .12       0
  5501.1    .035       0  5802.3     .12       0  5987.8     .07       0
Bank Sta=4957.9,4964.8
XS Rating Curve= 0 ,0
Exp/Cntr=0.3,0.1

Chan Stop Cuts=-1
Use User Specified Reach Order=0
Composite Channel Slope=5