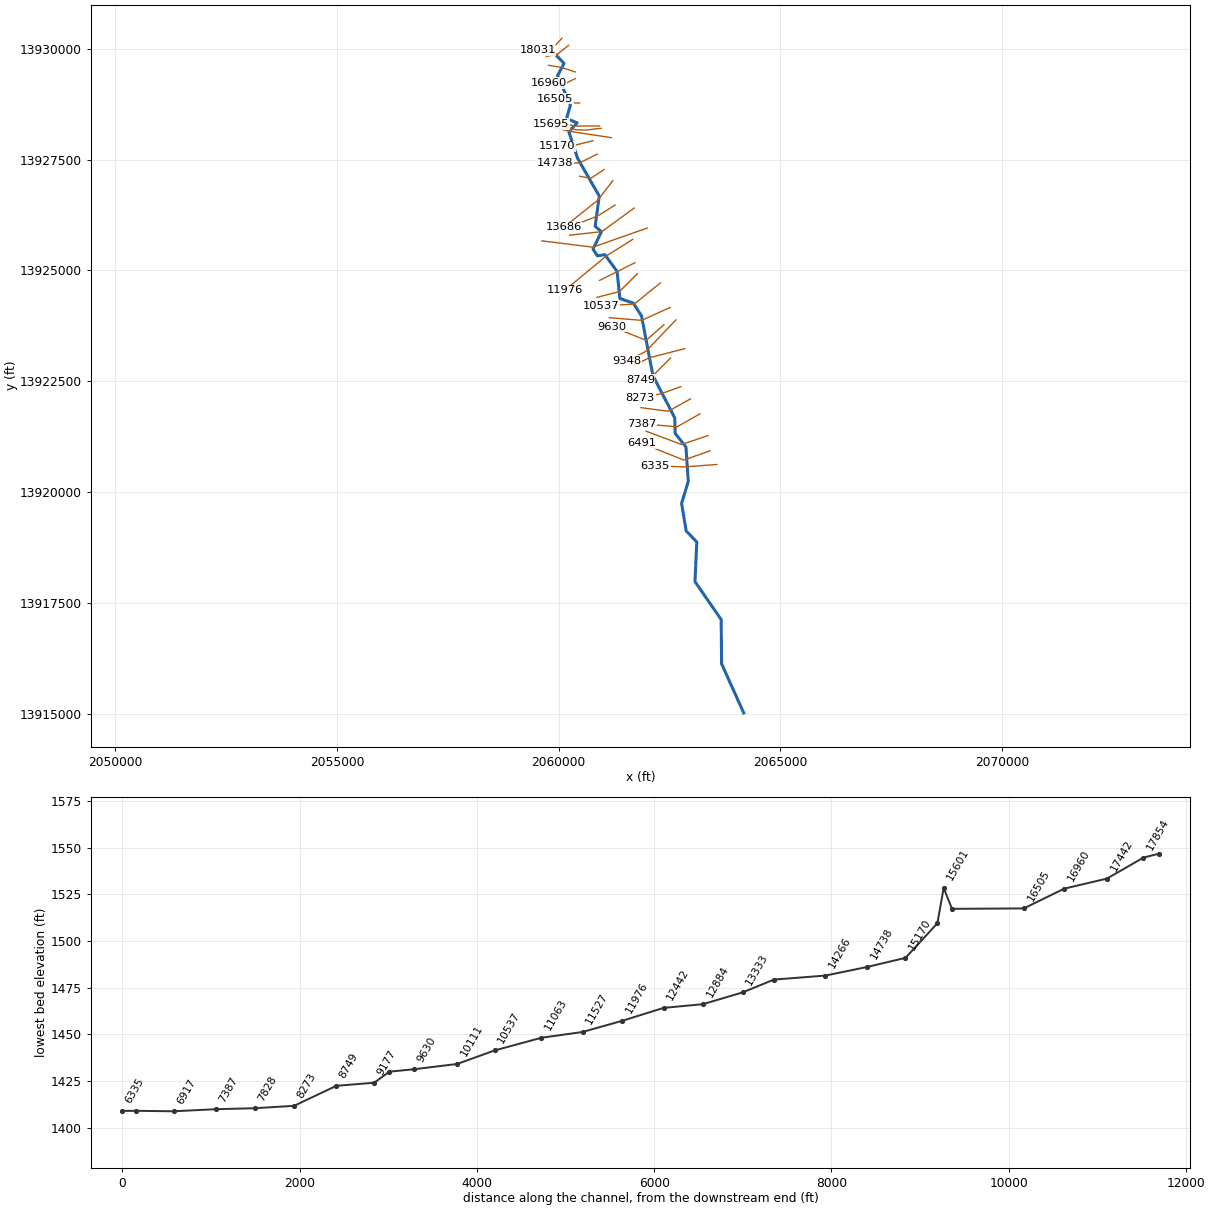
--- ASKEY CREEK.prj (project) ---

Proj Title=ASKEY CREEK Base Level Engineering
Current Plan=p01
Default Exp/Contr=0.3,0.1
English Units
Geom File=g01
Flow File=f01
Plan File=p01
Y Axis Title=Elevation
X Axis Title(PF)=Main Channel Distance
X Axis Title(XS)=Station
BEGIN DESCRIPTION:
ASKEY CREEK
END DESCRIPTION:
DSS Export Rating Curves= 0
DSS Export Rating Curve Sorted= 0
DSS Export Volume Flow Curves= 0
DXF OffsetX= 0
DXF OffsetY= 0
DXF ScaleX= 1
DXF ScaleY= 10

--- ASKEY CREEK.p01 (plan) ---

Plan Title=Multiple Run
Short Identifier=Multiple
Geom File=g01
Flow File=f01
Subcritical Flow
K Sum by GR= 0
Std Step Tol= 0.01
Critical Tol= 0.01
Num of Std Step Trials= 20
Max Error Tol= 0.3
Flow Tol Ratio= 0.001
Split Flow NTrial= 30
Split Flow Tol= 0.02
Split Flow Ratio= 0.02
Log Output Level= 0
Friction Slope Method= 1
Unsteady Friction Slope Method= 2
Unsteady Bridges Friction Slope Method= 1
Parabolic Critical Depth
Global Vel Dist=  1 , 1 , 1
Global Log Level= 0
CheckData=True
Encroach Param= -1, 0, 0, 0
BEGIN DESCRIPTION:
Multiple Run
END DESCRIPTION:

--- ASKEY CREEK.f01 (steady flow) ---

Flow Title=Multiple
Number of Profiles=7
Profile Names=10-year,25-year,50-year,1pct_min,100-year,1pct_plu,500-year
River Rch & RM= ASKEY CREEK,Reach-1,18031
     533     882    1209     807    1610    3213    2825
River Rch & RM= ASKEY CREEK,Reach-1,17854
     693    1160    1601    1076    2146    4283    3817
River Rch & RM= ASKEY CREEK,Reach-1,15695
    1286    2234    3159    2168    4326    8631    8040
River Rch & RM= ASKEY CREEK,Reach-1,13333
    1773    3123    4457    3082    6150   12271   11616
River Rch & RM= ASKEY CREEK,Reach-1,9348
    2057    3641    5212    3613    7208   14383   13679
River Rch & RM= ASKEY CREEK,Reach-1,5553
    2439    4350    6260    4359    8697   17352   16656
River Rch & RM= ASKEY CREEK,Reach-1,3309
    2529    4509    6487    4514    9007   17970   17228
Boundary for River Rch & Prof#=ASKEY CREEK,Reach-1,1
Up Type=0
Dn Type=3
Dn Slope=0.005
Boundary for River Rch & Prof#=ASKEY CREEK,Reach-1,2
Up Type=0
Dn Type=3
Dn Slope=0.005
Boundary for River Rch & Prof#=ASKEY CREEK,Reach-1,3
Up Type=0
Dn Type=3
Dn Slope=0.005
Boundary for River Rch & Prof#=ASKEY CREEK,Reach-1,4
Up Type=0
Dn Type=3
Dn Slope=0.005
Boundary for River Rch & Prof#=ASKEY CREEK,Reach-1,5
Up Type=0
Dn Type=3
Dn Slope=0.005
Boundary for River Rch & Prof#=ASKEY CREEK,Reach-1,6
Up Type=0
Dn Type=3
Dn Slope=0.005
Boundary for River Rch & Prof#=ASKEY CREEK,Reach-1,7
Up Type=0
Dn Type=3
Dn Slope=0.005

--- ASKEY CREEK.g01 (geometry) ---

Geom Title=Existing Conditions
Program Version=4.10

River Reach=ASKEY CREEK     ,Reach-1
Reach XY= 30
        2059825.       13929975.      2060123.08     13929669.03
      2059975.24     13929390.22      2060267.41     13928728.39
      2060178.52     13928425.99      2060417.42     13928328.35
      2060232.29     13928125.09      2060427.26     13927530.94
      2060916.96     13926678.32      2060824.75     13925994.95
      2060968.02     13925875.21      2060776.79     13925481.11
      2060876.28     13925328.37      2061045.08     13925355.73
      2061319.48     13924977.43      2061382.69     13924368.52
      2061685.12     13924264.65      2061871.25     13923973.45
      2062127.18     13922630.45      2062621.18     13921673.42
      2062628.67     13921326.58      2062872.91     13921019.74
      2062924.94     13920245.03      2062774.84     13919747.66
      2062878.54     13919126.46      2063117.01     13918878.34
        2063076.     13917985.51      2063666.97     13917128.35
      2063677.24     13916130.93        2064175.       13915025.

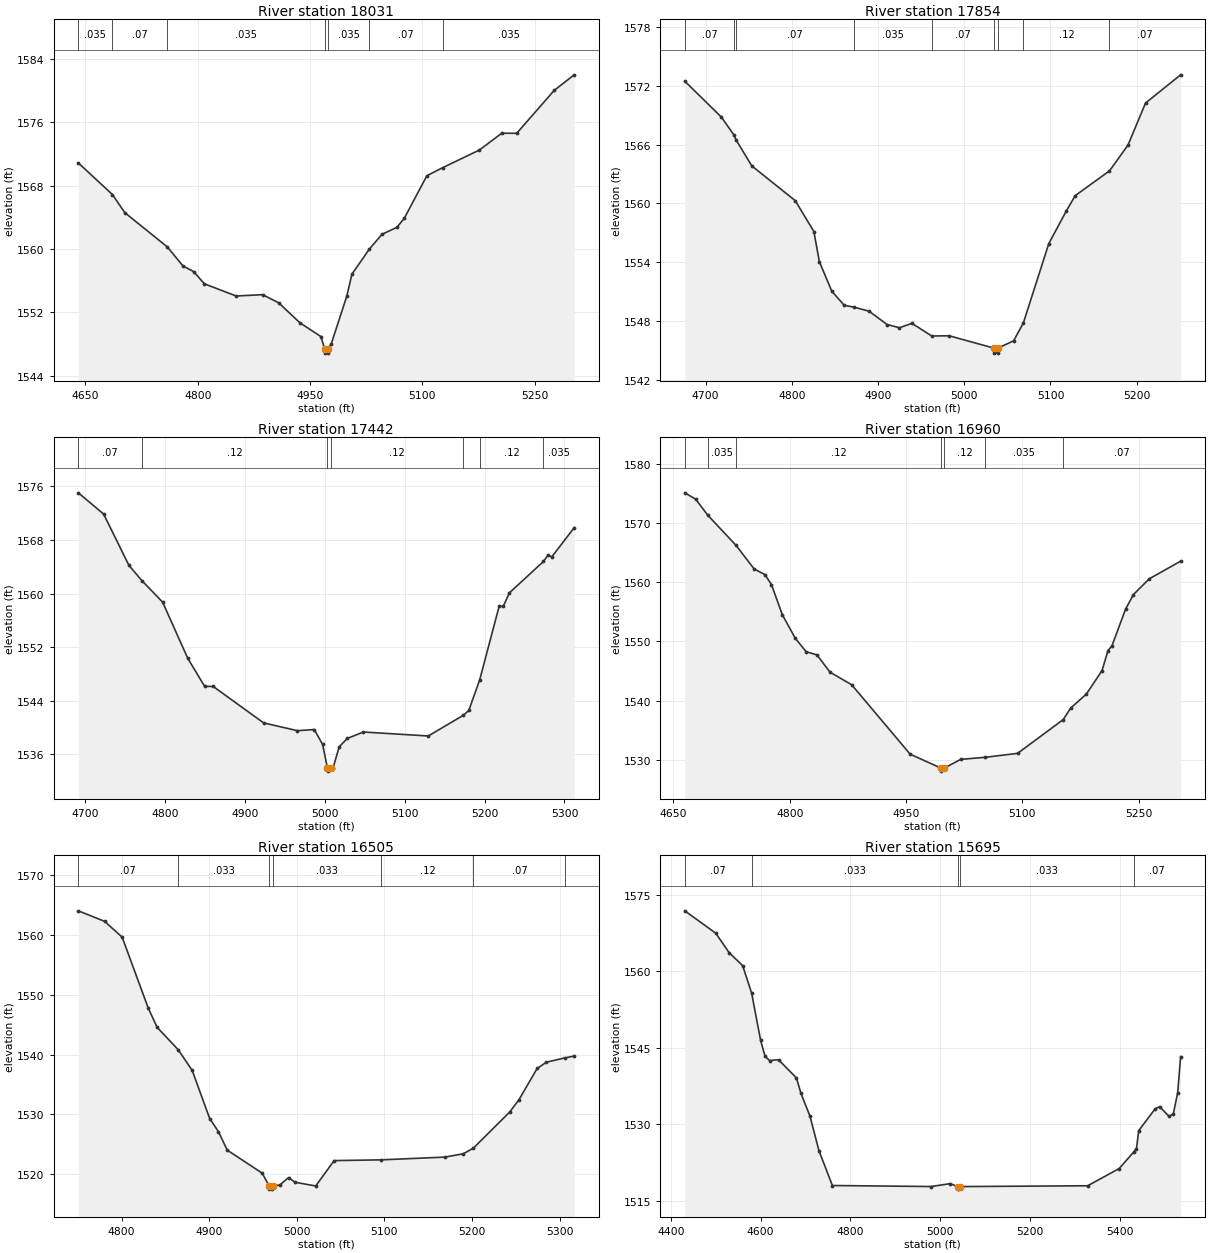
Type RM Length L Ch R = 1 ,18031   ,177,177,177
BEGIN DESCRIPTION:
ASKEY CREEK 38.0
END DESCRIPTION:
XS GIS Cut Line= 3
      2060073.83     13930233.88      2059830.94     13929968.84
      2059528.36     13929960.53
#Sta/Elev= 30
  4640.5 1570.88    4686 1566.89  4702.7 1564.59  4759.3 1560.28  4780.4 1557.86
  4794.6 1557.16  4808.8 1555.62  4851.3 1554.08  4886.5 1554.25    4908 1553.23
  4936.4  1550.7  4964.5 1548.96  4969.5 1547.37  4969.8 1546.87  4973.3 1546.87
  4973.5 1547.37  4978.3 1548.04  4999.2 1554.11  5005.9 1556.84    5029 1559.98
    5046 1561.87    5066 1562.75    5076 1563.92    5106 1569.26  5127.5  1570.3
    5176  1572.5    5206 1574.63    5226 1574.62    5276 1580.03  5302.7    1582
#Mann= 7 ,-1 , 0
  4640.5    .035       0    4686     .07       0  4759.3    .035       0
  4969.5    .035       0  4973.5    .035       0    5029     .07       0
  5127.5    .035       0
Bank Sta=4969.5,4973.5
XS Rating Curve= 0 ,0
Exp/Cntr=0.3,0.1

Type RM Length L Ch R = 1 ,17854   ,412,412,412
BEGIN DESCRIPTION:
ASKEY CREEK 37.0
END DESCRIPTION:
XS GIS Cut Line= 3
      2060225.03     13930075.03        2059975.       13929875.
      2059725.05     13929825.01
#Sta/Elev= 30
  4675.9 1572.48  4718.4 1568.81  4732.9 1566.99  4735.3  1566.5  4753.6 1563.84
    4804 1560.29  4825.6 1557.14    4832 1554.06  4846.4 1551.05  4860.8 1549.61
  4871.7 1549.43  4889.6 1549.01  4910.5 1547.65  4924.9 1547.32  4939.3 1547.77
  4962.3 1546.48  4982.5  1546.5  5034.9 1545.23  5035.1 1544.73  5038.6 1544.73
  5038.9 1545.23  5057.3 1545.99  5068.6 1547.81  5098.1 1555.91  5118.5 1559.25
  5128.7  1560.8  5168.5 1563.33  5189.9 1565.95  5210.3 1570.25    5251 1573.13
#Mann= 9 ,-1 , 0
  4675.9     .07       0  4732.9     .12       0  4735.3     .07       0
  4871.7    .035       0  4962.3     .07       0  5034.9     .05       0
  5038.9     .07       0  5068.6     .12       0  5168.5     .07       0
Bank Sta=5034.9,5038.9
XS Rating Curve= 0 ,0
Exp/Cntr=0.3,0.1

Type RM Length L Ch R = 1 ,17442   ,482,482,482
BEGIN DESCRIPTION:
ASKEY CREEK 36.0
END DESCRIPTION:
XS GIS Cut Line= 3
      2060375.01       13929475.        2060075.       13929575.
      2059774.98       13929625.
#Sta/Elev= 30
  4691.7 1575.04  4723.3 1571.88    4755 1564.21  4771.2 1561.93  4797.1 1558.73
  4828.7 1550.31  4849.8 1546.13  4860.4 1546.13  4923.6 1540.68  4965.8 1539.52
  4986.9 1539.69  4997.4 1537.46  5003.3 1533.98  5003.6 1533.48  5007.3 1533.98
  5010.5 1533.98  5018.1 1537.11  5028.2 1538.36  5048.5 1539.32  5129.6 1538.73
  5173.3 1541.81  5180.3 1542.55  5193.9 1547.11  5218.3 1558.13  5223.4 1558.08
    5231  1560.1  5273.7 1564.79  5279.1  1565.7  5284.2 1565.49  5312.1 1569.83
#Mann= 7 ,-1 , 0
  4691.7     .07       0  4771.2     .12       0  5003.3     .05       0
  5007.3     .12       0  5173.3     .07       0  5193.9     .12       0
  5273.7    .035       0
Bank Sta=5003.3,5007.3
XS Rating Curve= 0 ,0
Exp/Cntr=0.3,0.1

Type RM Length L Ch R = 1 ,16960   ,455,455,455
BEGIN DESCRIPTION:
ASKEY CREEK 35.0
END DESCRIPTION:
XS GIS Cut Line= 3
      2060374.99       13929325.        2060075.       13929175.
      2059775.04     13929224.99
#Sta/Elev= 30
  4664.7 1575.11  4678.7 1574.04  4694.4 1571.32  4730.9 1566.22  4754.1 1562.25
  4768.1 1561.29  4776.5  1559.6  4790.5 1554.51  4807.2 1550.54  4821.2 1548.27
  4835.2 1547.72    4852 1544.81  4879.9 1542.69  4955.4 1530.95  4995.3 1528.59
  4995.6 1528.09  4999.3 1528.59  5020.4 1530.07  5052.3 1530.43  5093.9 1531.09
  5152.8  1536.8  5162.3 1538.73  5182.6  1541.1  5202.9 1545.09  5210.5 1548.47
  5215.5 1549.22  5233.3 1555.49  5243.4 1557.93  5263.7 1560.58  5304.2 1563.56
#Mann= 7 ,-1 , 0
  4664.7     .07       0  4694.4    .035       0  4730.9     .12       0
  4995.3     .05       0  4999.3     .12       0  5052.3    .035       0
  5152.8     .07       0
Bank Sta=4995.3,4999.3
XS Rating Curve= 0 ,0
Exp/Cntr=0.3,0.1

Type RM Length L Ch R = 1 ,16505   ,810,810,810
BEGIN DESCRIPTION:
ASKEY CREEK 34.0
END DESCRIPTION:
XS GIS Cut Line= 3
      2060474.98       13928775.        2060225.       13928775.
      2059925.01       13928875.
#Sta/Elev= 30
  4750.5 1564.07  4780.5 1562.31  4800.5 1559.67  4830.5 1547.74  4840.5 1544.58
  4864.5 1540.84  4880.5 1537.38  4900.5 1529.32  4910.5 1527.13  4920.5 1524.04
  4960.5 1520.18  4968.5 1518.01  4968.7 1517.51  4972.2 1517.51  4972.5 1518.01
  4980.5  1518.2  4990.5 1519.44    4998 1518.66  5021.6 1518.04  5042.6 1522.28
  5096.6 1522.41  5169.1 1522.87  5190.2 1523.43  5201.6 1524.37  5242.9 1530.38
  5253.5 1532.43  5274.5 1537.71  5285.1 1538.75  5306.6 1539.48  5316.7 1539.77
#Mann= 7 ,-1 , 0
  4750.5     .07       0  4864.5    .033       0  4968.5    .033       0
  4972.5    .033       0  5096.6     .12       0  5201.6     .07       0
  5306.6    .035       0
Bank Sta=4968.5,4972.5
XS Rating Curve= 0 ,0
Exp/Cntr=0.3,0.1

Type RM Length L Ch R = 1 ,15695   ,94,94,94
BEGIN DESCRIPTION:
ASKEY CREEK 33.5
END DESCRIPTION:
XS GIS Cut Line= 4
      2060923.86     13928257.59      2060355.16       13928255.
      2060093.42     13928323.23      2059828.51     13928302.65
#Sta/Elev= 30
  4431.3 1571.87  4500.2 1567.49  4530.2 1563.65  4560.2 1561.12  4580.2 1555.74
  4600.2 1546.48  4610.2 1543.34  4620.2  1542.5  4640.2 1542.66  4680.2 1539.08
  4690.2 1536.04  4710.2 1531.61  4730.2 1524.84  4760.2 1517.99  4980.2 1517.79
  5022.9 1518.36  5039.5 1517.78  5039.7 1517.28  5043.6 1517.78  5329.1 1517.94
  5399.3 1521.32  5432.1  1524.6  5437.8 1525.24  5442.9 1528.76  5479.5 1533.05
  5489.6 1533.45  5509.6 1531.62  5519.7 1531.94  5529.7 1536.22  5536.2 1543.27
#Mann= 5 ,-1 , 0
  4431.3     .07       0  4580.2    .033       0  5039.5    .033       0
  5043.6    .033       0  5432.1     .07       0
Bank Sta=5039.5,5043.6
XS Rating Curve= 0 ,0
Exp/Cntr=0.3,0.1

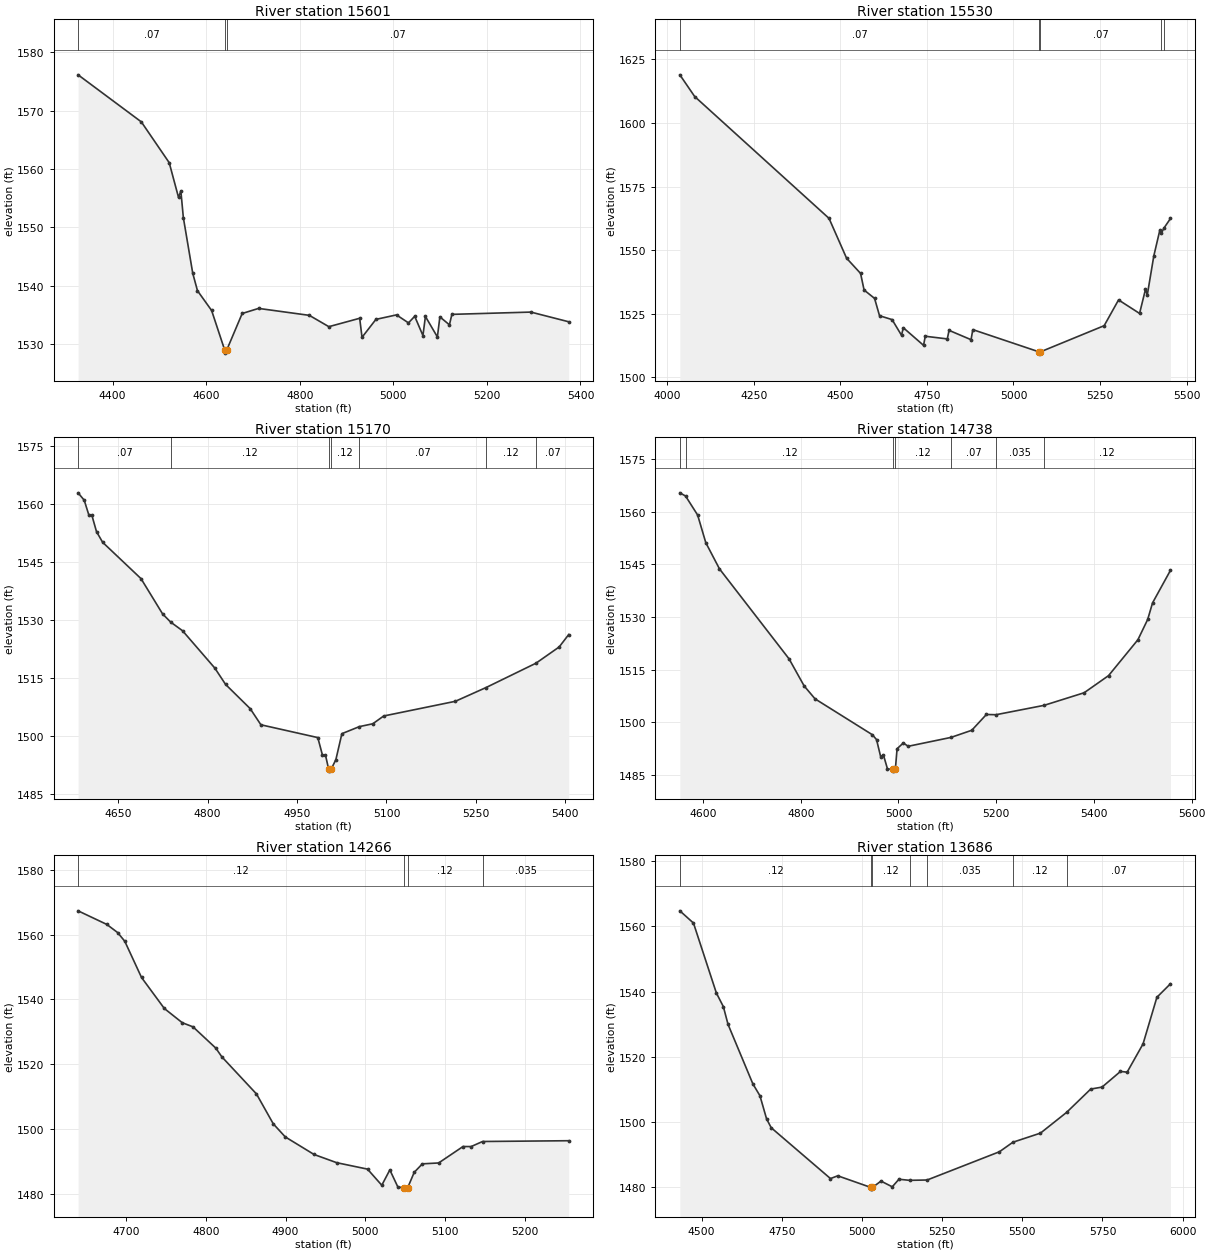
Type RM Length L Ch R = 1 ,15601   ,71,71,71
BEGIN DESCRIPTION:
ASKEY CREEK 33.0
END DESCRIPTION:
XS GIS Cut Line= 6
      2060958.53     13928204.82      2060609.96     13928165.15
      2060436.55     13928170.88       2060288.1     13928188.34
      2060132.79     13928243.21      2059925.02       13928275.
#Sta/Elev= 30
  4326.2 1576.13  4461.4 1568.07    4521 1561.08  4540.9 1555.13  4545.9 1556.23
  4551.2 1551.68  4571.3 1542.14  4581.4 1539.15  4611.6 1535.77  4639.7 1528.96
    4640 1528.46  4643.8 1528.96    4677 1535.25    4712 1536.12  4820.5 1534.93
  4862.2 1532.99  4928.1 1534.43  4933.1 1531.17  4962.8 1534.24  5006.8 1535.01
  5032.4 1533.64  5045.7 1534.77  5063.3 1531.47  5068.6 1534.74  5094.2 1531.23
  5099.5 1534.67  5119.9 1533.31  5125.2  1535.1    5294 1535.49  5374.9 1533.83
#Mann= 3 ,-1 , 0
  4326.2     .07       0  4639.7     .05       0  4643.8     .07       0
Bank Sta=4639.7,4643.8
XS Rating Curve= 0 ,0
Exp/Cntr=0.3,0.1

Type RM Length L Ch R = 1 ,15530   ,360,360,360
BEGIN DESCRIPTION:
ASKEY CREEK 32.0
END DESCRIPTION:
XS GIS Cut Line= 3
      2061190.94     13927993.35      2060238.52     13928138.38
      2059798.29     13928246.88
#Sta/Elev= 30
  4036.6 1618.91  4079.4 1610.39  4467.4  1562.5    4518 1546.86  4558.5 1540.86
  4568.6 1534.34  4598.9 1531.05  4613.2 1524.24  4649.5 1522.71  4676.7 1516.55
  4681.8 1519.53  4740.3  1512.6  4745.3 1516.17  4808.9 1515.13    4814 1518.49
  4877.5 1514.82  4882.6 1518.78  5073.7 1510.04  5073.9 1509.54  5077.8 1510.04
  5261.9 1520.33  5303.4 1530.45  5364.1 1525.14  5381.2 1534.62  5386.4 1532.41
  5405.3 1547.79  5422.7 1557.91  5426.9 1556.65  5434.8 1558.74  5453.4 1562.46
#Mann= 5 ,-1 , 0
  4036.6     .07       0  5073.7     .05       0  5077.8     .07       0
  5426.9    .035       0  5434.8     .07       0
Bank Sta=5073.7,5077.8
XS Rating Curve= 0 ,0
Exp/Cntr=0.3,0.1

Type RM Length L Ch R = 1 ,15170   ,432,432,432
BEGIN DESCRIPTION:
ASKEY CREEK 31.0
END DESCRIPTION:
XS GIS Cut Line= 3
      2060774.99       13927925.        2060375.       13927825.
      2059965.33     13927798.91
#Sta/Elev= 30
  4582.8 1562.94  4593.1 1561.03  4600.8 1557.24    4606  1557.1  4613.7 1552.91
    4624 1550.15  4688.4 1540.75  4724.5 1531.65  4738.1 1529.52    4758 1527.29
  4812.1 1517.64  4830.2 1513.41  4871.4 1507.16  4889.4 1502.98  4984.8 1499.67
  4992.5 1495.21  4997.6 1495.21    5003  1491.5  5003.3    1491  5007.2  1491.5
  5015.1 1493.96  5025.2 1500.68  5054.4  1502.5    5077 1503.24  5095.3 1505.25
  5215.5 1509.05    5267 1512.61  5350.7  1518.9  5389.6  1523.1  5405.6 1526.31
#Mann= 7 ,-1 , 0
  4582.8     .07       0  4738.1     .12       0    5003     .05       0
  5007.2     .12       0  5054.4     .07       0    5267     .12       0
  5350.7     .07       0
Bank Sta=5003,5007.2
XS Rating Curve= 0 ,0
Exp/Cntr=0.3,0.1

Type RM Length L Ch R = 1 ,14738   ,472,472,472
BEGIN DESCRIPTION:
ASKEY CREEK 30.0
END DESCRIPTION:
XS GIS Cut Line= 3
      2060875.03     13927625.02        2060475.       13927425.
      2059918.31     13927416.98
#Sta/Elev= 30
  4552.7 1565.32  4564.4 1564.41  4589.1    1559  4605.8 1551.13  4633.8 1543.68
  4776.3 1518.05  4807.1 1510.36  4829.4 1506.69  4946.8 1496.47  4955.2  1495.1
  4963.6 1490.25  4969.2 1490.78  4977.6 1486.74  4989.5 1486.63  4989.7 1486.13
  4993.7 1486.63  4997.2  1492.5  5009.9 1494.13    5020  1493.2  5107.4 1495.72
    5150 1497.75    5180 1502.25  5199.6 1502.18  5298.1 1504.85    5380 1508.43
    5430 1513.31    5490 1523.51    5510 1529.28    5520 1534.01  5556.7 1543.28
#Mann= 7 ,-1 , 0
  4552.7     .07       0  4564.4     .12       0  4989.5     .05       0
  4993.7     .12       0  5107.4     .07       0  5199.6    .035       0
  5298.1     .12       0
Bank Sta=4989.5,4993.7
XS Rating Curve= 0 ,0
Exp/Cntr=0.3,0.1

Type RM Length L Ch R = 1 ,14266   ,580,580,580
BEGIN DESCRIPTION:
ASKEY CREEK 29.0
END DESCRIPTION:
XS GIS Cut Line= 3
        2061025.       13927275.        2060725.       13927075.
      2060475.01       13927125.
#Sta/Elev= 30
  4639.7 1567.35  4675.8 1563.15  4689.3 1560.65  4698.3 1557.96  4719.3 1546.79
  4747.9 1537.23  4770.4 1532.84  4783.9 1531.56  4812.5    1525    4820 1522.33
  4863.5 1510.87  4884.6 1501.64  4899.6 1497.62  4935.7  1492.2  4964.2 1489.66
  5002.8 1487.68  5020.7 1482.71  5030.8 1487.44    5041  1482.1  5049.1 1482.01
  5049.4 1481.51  5053.1 1481.51  5053.3 1482.01  5061.4  1486.7  5071.6 1489.31
    5092 1489.58  5122.6 1494.65  5132.8 1494.64  5147.1  1496.2  5255.2 1496.44
#Mann= 4 ,-1 , 0
  4639.7     .12       0  5049.1     .05       0  5053.3     .12       0
  5147.1    .035       0
Bank Sta=5049.1,5053.3
XS Rating Curve= 0 ,0
Exp/Cntr=0.3,0.1

Type RM Length L Ch R = 1 ,13686   ,353,353,353
BEGIN DESCRIPTION:
ASKEY CREEK 28.0
END DESCRIPTION:
XS GIS Cut Line= 3
        2061225.       13927025.      2060885.43      13926587.1
      2060125.01       13925975.
#Sta/Elev= 30
  4431.9 1564.77  4474.4 1561.01  4545.8 1539.56  4567.7 1535.34  4582.2 1529.92
  4659.7 1511.65  4681.7 1508.02  4702.6 1500.86    4717 1498.19  4901.7  1482.6
  4924.4 1483.45  5028.2 1479.86  5028.5 1479.36  5032.5 1479.86  5059.2 1481.83
  5094.4 1480.07  5115.2 1482.39  5148.6 1482.06  5203.2 1482.16  5428.7 1490.83
  5470.6 1493.75  5556.7 1496.55    5638  1502.9  5713.4 1510.07  5748.7 1510.67
  5806.2 1515.48    5827 1515.26  5876.6 1523.93  5919.8 1538.24  5962.2 1542.39
#Mann= 7 ,-1 , 0
  4431.9     .12       0  5028.2     .05       0  5032.5     .12       0
  5148.6     .07       0  5203.2    .035       0  5470.6     .12       0
    5638     .07       0
Bank Sta=5028.2,5032.5
XS Rating Curve= 0 ,0
Exp/Cntr=0.3,0.1

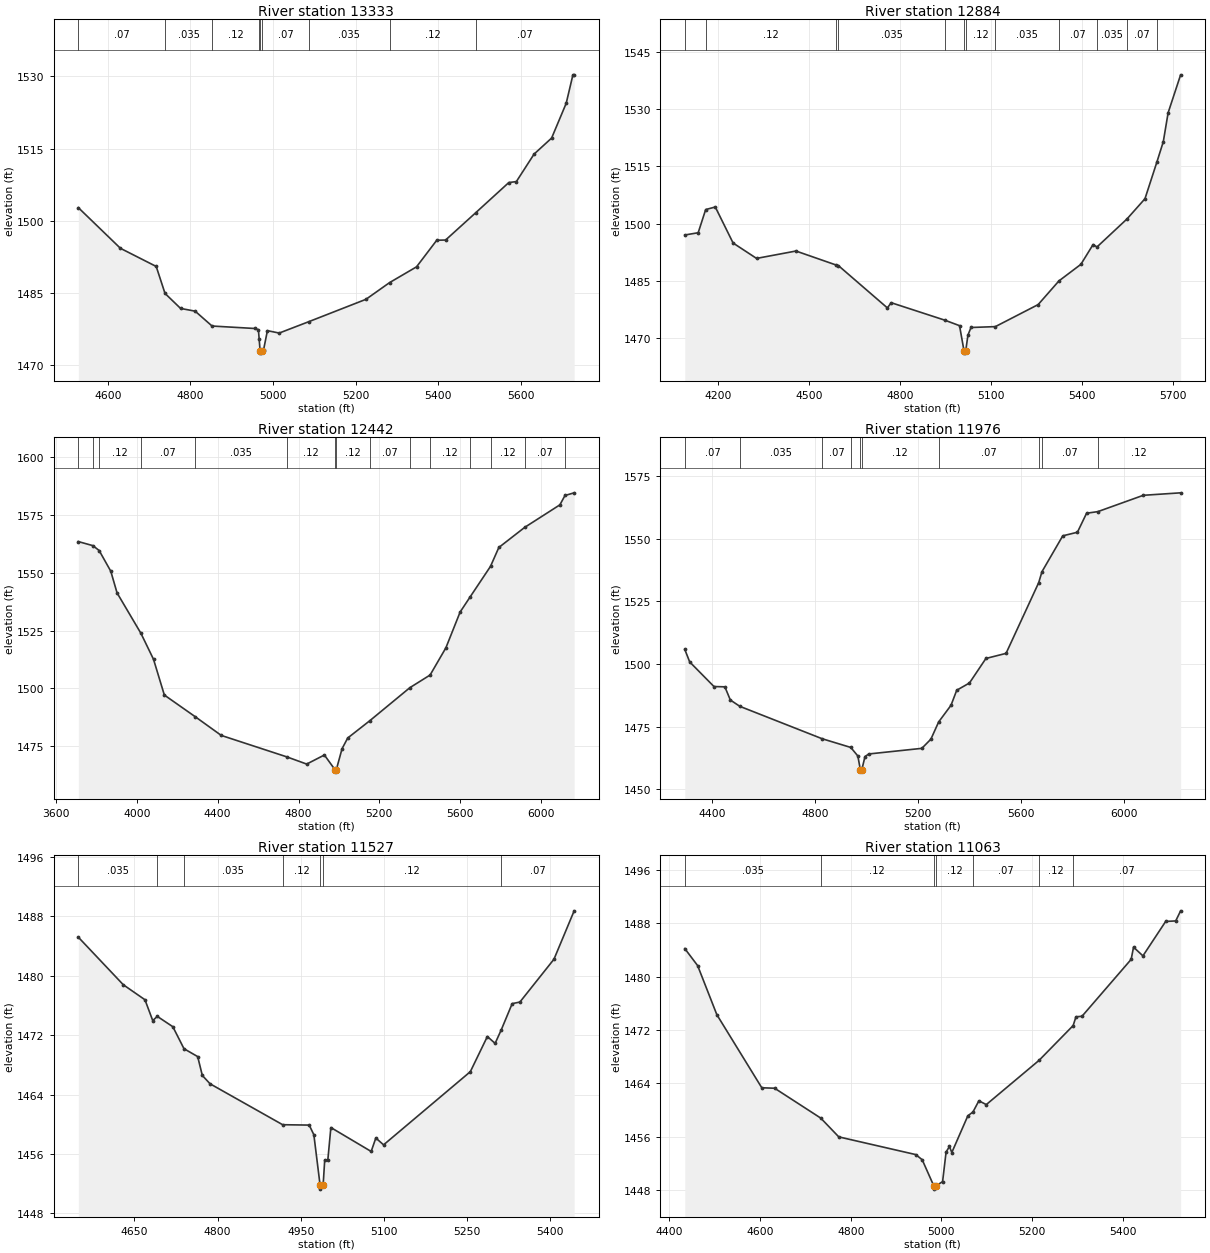
Type RM Length L Ch R = 1 ,13333   ,449,449,449
BEGIN DESCRIPTION:
ASKEY CREEK 27.0
END DESCRIPTION:
XS GIS Cut Line= 3
      2061275.01       13926475.        2060875.       13926225.
      2060194.43     13925962.09
#Sta/Elev= 30
  4528.4 1502.72  4630.4 1494.27  4717.1  1490.5  4738.4  1484.9  4776.1 1481.78
  4811.4 1481.21  4852.4 1478.12  4955.9 1477.61  4964.7 1477.36  4966.5 1475.44
  4968.8 1472.99  4969.2 1472.49  4973.6 1472.99  4977.1 1473.13  4986.5 1477.16
  5015.1 1476.66  5087.2 1479.04  5225.2 1483.67  5282.6 1487.15  5347.8 1490.42
  5396.8 1495.95  5418.2 1495.99  5491.4 1501.68  5571.3 1507.93  5589.7 1508.14
  5632.6 1513.85  5675.1 1517.18  5710.4  1524.4  5726.7 1530.32  5729.7 1530.32
#Mann= 9 ,-1 , 0
  4528.4     .07       0  4738.4    .035       0  4852.4     .12       0
  4966.5     .07       0  4968.8     .05       0  4973.6     .07       0
  5087.2    .035       0  5282.6     .12       0  5491.4     .07       0
Bank Sta=4968.8,4973.6
XS Rating Curve= 0 ,0
Exp/Cntr=0.3,0.1

Type RM Length L Ch R = 1 ,12884   ,442,442,442
BEGIN DESCRIPTION:
ASKEY CREEK 26.0
END DESCRIPTION:
XS GIS Cut Line= 3
      2061704.88     13926406.55        2060975.       13925875.
      2060248.24     13925795.62
#Sta/Elev= 30
  4089.9 1497.05    4134 1497.64  4158.7  1503.7  4190.4 1504.37  4249.1 1494.95
  4326.4 1490.93  4456.2 1492.86  4588.4 1489.21  4596.4 1489.03  4757.5 1477.99
  4770.1 1479.35  4946.2  1474.8  4995.3 1473.35  5010.3 1466.67  5010.7 1466.17
  5015.5 1466.67    5023 1470.88  5033.1 1472.87  5113.4  1473.1  5254.4 1478.86
  5322.9 1485.05  5395.2 1489.38  5435.4 1494.55  5448.3 1493.92  5547.2 1501.25
  5606.4 1506.53    5646  1516.2  5666.8 1521.44  5682.7    1529  5723.9 1538.92
#Mann= 12 ,-1 , 0
  4089.9     .07       0  4158.7     .12       0  4588.4     .07       0
  4596.4    .035       0  4946.2     .12       0  5010.3     .05       0
  5015.5     .12       0  5113.4    .035       0  5322.9     .07       0
  5448.3    .035       0  5547.2     .07       0    5646     .12       0
Bank Sta=5010.3,5015.5
XS Rating Curve= 0 ,0
Exp/Cntr=0.3,0.1

Type RM Length L Ch R = 1 ,12442   ,466,466,466
BEGIN DESCRIPTION:
ASKEY CREEK 25.0
END DESCRIPTION:
XS GIS Cut Line= 3
      2061996.53     13925955.15        2060775.       13925525.
      2059624.98     13925666.96
#Sta/Elev= 30
  3710.4 1563.56  3782.4  1561.8  3813.4 1559.69    3871 1550.73    3902 1541.35
  4020.2 1523.84  4082.5  1512.6  4136.1 1497.13    4288 1487.81  4417.7 1479.66
  4743.9 1470.32  4840.5 1467.25  4928.1 1471.18  4981.6  1464.7    4982  1464.2
  4986.8  1464.7  5015.5 1473.89  5043.5 1478.53    5152 1485.96  5351.4 1500.34
  5451.2 1505.79  5529.4 1517.57  5599.9 1533.07  5650.6 1539.77  5750.3 1552.85
  5791.4    1561  5919.8 1569.73  6093.6 1579.46  6118.8 1583.51  6164.2 1584.66
#Mann= 15 ,-1 , 0
  3710.4     .12       0  3782.4    .035       0  3813.4     .12       0
  4020.2     .07       0    4288    .035       0  4743.9     .12       0
  4981.6     .05       0  4986.8     .12       0    5152     .07       0
  5351.4    .035       0  5451.2     .12       0  5650.6     .07       0
  5750.3     .12       0  5919.8     .07       0  6118.8     .12       0
Bank Sta=4981.6,4986.8
XS Rating Curve= 0 ,0
Exp/Cntr=0.3,0.1

Type RM Length L Ch R = 1 ,11976   ,449,449,449
BEGIN DESCRIPTION:
ASKEY CREEK 24.0
END DESCRIPTION:
XS GIS Cut Line= 3
      2061673.64     13925701.69        2061075.       13925325.
      2060136.09     13924549.45
#Sta/Elev= 30
  4293.3 1505.85  4312.3 1500.87  4406.5 1491.05  4448.9 1490.93  4470.1 1485.67
  4507.1 1483.14  4826.7 1470.21  4937.8 1466.74  4965.2 1463.33    4975 1457.79
  4975.4 1457.29  4980.4 1457.79    4993 1463.11  5007.8 1464.14  5213.6 1466.38
  5248.8 1470.05    5279 1476.93  5326.9 1483.57  5349.1 1489.57  5398.6 1492.47
  5462.4 1502.25  5540.6 1504.28  5667.4 1532.51    5680 1536.87  5760.8 1551.19
  5817.7 1552.62  5853.3 1560.21  5897.1 1560.85  6073.4 1567.36  6218.4 1568.35
#Mann= 10 ,-1 , 0
  4293.3     .07       0  4507.1    .035       0  4826.7     .07       0
  4937.8     .12       0    4975     .05       0  4980.4     .12       0
    5279     .07       0  5667.4     .12       0    5680     .07       0
  5897.1     .12       0
Bank Sta=4975,4980.4
XS Rating Curve= 0 ,0
Exp/Cntr=0.3,0.1

Type RM Length L Ch R = 1 ,11527   ,464,464,464
BEGIN DESCRIPTION:
ASKEY CREEK 23.0
END DESCRIPTION:
XS GIS Cut Line= 3
      2061725.04     13925175.02        2061325.       13924975.
      2060924.98     13924774.99
#Sta/Elev= 30
  4548.8 1485.19  4629.9 1478.79    4669 1476.77    4683 1473.97  4691.3 1474.53
  4719.3 1473.14  4739.4 1470.18  4764.1 1469.12  4772.5 1466.58  4786.4 1465.46
  4917.4 1459.95  4965.3  1459.9  4973.7  1458.6    4985 1451.78  4985.4 1451.28
  4990.4 1451.78  4993.3  1455.2  4998.9  1455.2  5004.4 1459.57  5077.1 1456.35
  5085.5 1458.16  5099.5 1457.24    5256 1467.09  5286.7 1471.82  5300.7  1470.9
  5311.8 1472.72  5331.5 1476.25  5345.4 1476.46  5406.9 1482.23  5443.3 1488.74
#Mann= 7 ,-1 , 0
  4548.8    .035       0  4691.3     .07       0  4739.4    .035       0
  4917.4     .12       0    4985     .05       0  4990.4     .12       0
  5311.8     .07       0
Bank Sta=4985,4990.4
XS Rating Curve= 0 ,0
Exp/Cntr=0.3,0.1

Type RM Length L Ch R = 1 ,11063   ,526,526,526
BEGIN DESCRIPTION:
ASKEY CREEK 22.0
END DESCRIPTION:
XS GIS Cut Line= 3
      2061774.99     13924924.99        2061375.       13924525.
      2060864.56     13924392.64
#Sta/Elev= 30
  4434.3 1484.18  4462.6 1481.63    4505 1474.28    4604 1463.35  4632.3 1463.28
    4734 1458.81  4773.7    1456  4943.4 1453.35  4957.6 1452.58  4983.1 1448.68
  4983.5 1448.18  4988.6 1448.68  5002.6 1449.31  5010.3 1453.74  5017.7 1454.56
  5022.9 1453.66  5058.3 1459.16  5069.5 1459.72  5082.6  1461.4  5098.9 1460.83
  5215.2 1467.45  5290.4 1472.66  5296.6 1473.97  5309.9 1474.05  5418.3 1482.57
  5423.5 1484.39  5444.2 1483.09  5494.3 1488.24  5516.5 1488.32  5527.3 1489.83
#Mann= 7 ,-1 , 0
  4434.3    .035       0    4734     .12       0  4983.1     .05       0
  4988.6     .12       0  5069.5     .07       0  5215.2     .12       0
  5290.4     .07       0
Bank Sta=4983.1,4988.6
XS Rating Curve= 0 ,0
Exp/Cntr=0.3,0.1

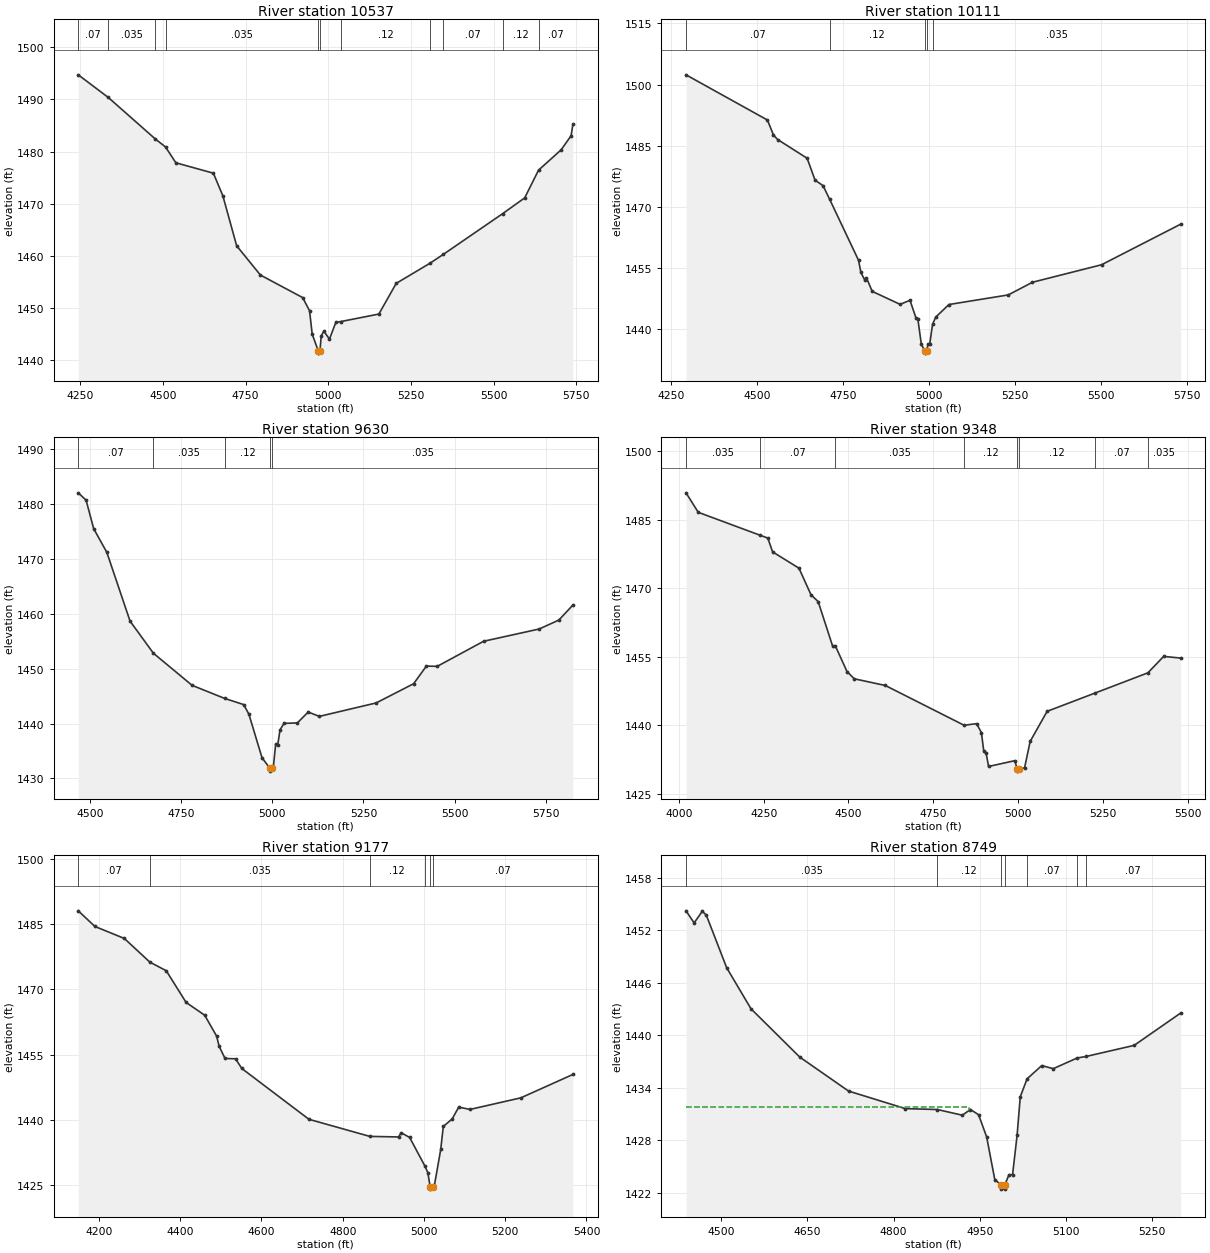
Type RM Length L Ch R = 1 ,10537   ,426,426,426
BEGIN DESCRIPTION:
ASKEY CREEK 21.0
END DESCRIPTION:
XS GIS Cut Line= 3
      2062295.19     13924719.07      2061708.34     13924243.35
      2060969.38     13924194.78
#Sta/Elev= 30
  4243.7 1494.68  4334.6 1490.34  4476.7  1482.4  4507.7 1480.86  4538.8 1477.84
  4652.3 1475.85    4681 1471.51  4722.7 1461.95  4794.5 1456.35  4922.4 1452.03
  4943.2  1449.5  4951.2 1445.01  4969.2  1441.9  4969.6  1441.4  4974.8  1441.9
  4978.4 1444.68  4986.4 1445.61  5003.3 1444.08  5022.5 1447.27  5038.2 1447.45
  5152.8 1448.88  5205.3 1454.76  5307.7 1458.62  5347.6  1460.3  5527.3 1468.11
  5593.8 1471.12  5635.7 1476.43    5704 1480.32  5734.1 1483.02  5739.7 1485.23
#Mann= 11 ,-1 , 0
  4243.7     .07       0  4334.6    .035       0  4476.7     .07       0
  4507.7    .035       0  4969.2    .035       0  4974.8    .035       0
  5038.2     .12       0  5307.7    .035       0  5347.6     .07       0
  5527.3     .12       0  5635.7     .07       0
Bank Sta=4969.2,4974.8
XS Rating Curve= 0 ,0
Exp/Cntr=0.3,0.1

Type RM Length L Ch R = 1 ,10111   ,481,481,481
BEGIN DESCRIPTION:
ASKEY CREEK 20.0
END DESCRIPTION:
XS GIS Cut Line= 3
      2062517.35     13924166.95        2061875.       13923875.
      2061145.79     13923934.32
#Sta/Elev= 30
  4294.5  1502.4    4531 1491.31  4548.6 1487.62  4560.7 1486.53  4646.4 1481.93
  4669.4 1476.55  4692.5 1475.22  4711.6  1471.9  4795.8 1456.88  4802.4 1453.94
  4813.3 1452.13  4818.8  1452.6  4835.3 1449.28  4916.6 1446.08  4945.2 1447.09
  4962.7 1442.73  4968.2 1442.41  4978.1 1436.33  4988.4 1434.62  4988.9 1434.12
  4994.2 1434.62  4997.3 1436.36  5002.6 1436.36  5010.8 1441.21  5020.1 1442.97
  5058.5 1446.05  5230.8  1448.4  5301.1 1451.51  5501.7  1455.8  5731.7 1465.76
#Mann= 5 ,-1 , 0
  4294.5     .07       0  4711.6     .12       0  4988.4     .05       0
  4994.2     .12       0  5010.8    .035       0
Bank Sta=4988.4,4994.2
XS Rating Curve= 0 ,0
Exp/Cntr=0.3,0.1

Type RM Length L Ch R = 1 ,9630    ,282,282,282
BEGIN DESCRIPTION:
ASKEY CREEK 19.0
END DESCRIPTION:
XS GIS Cut Line= 3
      2062375.01     13923775.01        2061975.       13923425.
      2061209.19     13923729.12
#Sta/Elev= 30
  4468.6 1482.06    4490 1480.72  4510.8 1475.53  4546.9  1471.2  4610.5 1458.67
  4674.5 1452.82  4780.4 1446.97  4870.2 1444.57  4921.8 1443.46  4936.1 1441.72
  4972.1 1433.77  4993.9 1431.83  4994.3 1431.33  4999.7 1431.83  5002.8 1431.83
  5009.6  1436.3    5015 1436.07  5021.6 1438.88  5032.4 1440.03    5069 1440.12
  5098.6  1442.1  5129.2 1441.31  5284.9 1443.76  5387.5 1447.26  5422.6 1450.48
  5452.3 1450.43  5579.2    1455  5731.8 1457.24  5785.6 1458.87  5824.1 1461.61
#Mann= 5 ,-1 , 0
  4468.6     .07       0  4674.5    .035       0  4870.2     .12       0
  4993.9    .035       0  4999.7    .035       0
Bank Sta=4993.9,4999.7
XS Rating Curve= 0 ,0
Exp/Cntr=0.3,0.1

Type RM Length L Ch R = 1 ,9348    ,171,171,171
BEGIN DESCRIPTION:
ASKEY CREEK 18.5
END DESCRIPTION:
XS GIS Cut Line= 3
       2062646.7     13923884.15       2061969.4     13923177.39
      2061543.32      13922958.1
#Sta/Elev= 30
  4021.1 1490.88  4057.1 1486.62  4240.5 1481.57  4262.2 1480.98  4276.3 1477.97
    4354  1474.4  4389.5 1468.58  4410.6 1467.09  4453.1 1457.39  4461.2 1457.42
  4495.5  1451.8  4516.9 1450.21  4608.7 1448.74  4840.8 1440.04  4877.6 1440.39
  4891.8 1438.44  4898.7 1434.43  4905.9 1433.88  4912.9 1431.03  4990.5  1432.3
  4996.8 1430.51  4997.3 1430.01  5003.2 1430.51    5019 1430.73  5035.5 1436.51
  5085.5 1443.09  5225.8 1447.06  5382.6 1451.51    5429  1455.1  5479.2 1454.74
#Mann= 8 ,-1 , 0
  4021.1    .035       0  4240.5     .07       0  4461.2    .035       0
  4840.8     .12       0  4996.8     .05       0  5003.2     .12       0
  5225.8     .07       0  5382.6    .035       0
Bank Sta=4996.8,5003.2
XS Rating Curve= 0 ,0
Exp/Cntr=0.3,0.1

Type RM Length L Ch R = 1 ,9177    ,428,428,428
BEGIN DESCRIPTION:
ASKEY CREEK 18.0
END DESCRIPTION:
XS GIS Cut Line= 3
       2062844.7     13923237.02        2062025.       13923025.
      2061698.99     13922848.09
#Sta/Elev= 30
  4149.1 1488.09  4190.1 1484.49  4262.4 1481.74  4325.3 1476.29  4365.7 1474.31
  4414.5 1467.02  4460.3 1464.08  4489.7 1459.26  4495.7 1456.97  4510.3 1454.13
  4536.3 1454.06  4551.6 1451.83  4716.9 1440.14  4866.6 1436.21  4937.4 1436.08
  4944.1 1437.04  4964.8 1435.96  5002.3 1429.39  5009.6 1427.87  5015.3 1424.58
  5015.8 1424.08  5021.8 1424.58  5025.7 1424.93  5041.3 1433.22  5047.6  1438.5
  5069.4 1440.21  5085.6 1442.95  5113.2 1442.41  5238.6 1445.08  5366.7 1450.46
#Mann= 6 ,-1 , 0
  4149.1     .07       0  4325.3    .035       0  4866.6     .12       0
  5002.3     .07       0  5015.3     .05       0  5021.8     .07       0
Bank Sta=5015.3,5021.8
XS Rating Curve= 0 ,0
Exp/Cntr=0.3,0.1

Type RM Length L Ch R = 1 ,8749    ,476,476,476
BEGIN DESCRIPTION:
ASKEY CREEK 17.0
END DESCRIPTION:
XS GIS Cut Line= 3
      2062524.98     13923024.98        2062125.       13922625.
       2061843.8     13922535.03
#Sta/Elev= 30
  4438.6 1454.22  4452.7 1452.84  4466.9 1454.17  4473.9 1453.73  4509.3 1447.72
  4551.7 1443.02  4636.6  1437.5  4721.4 1433.62  4820.4 1431.61    4876 1431.51
  4919.4 1430.86  4933.6 1431.51  4947.7 1430.92  4961.8 1428.38    4976 1423.49
  4986.8 1422.91  4987.3 1422.41    4993 1422.41  4993.5 1422.91  5000.7 1424.06
  5006.9 1424.06  5014.8 1428.56  5020.3 1432.96  5032.2 1435.02  5057.7 1436.53
  5077.8 1436.18  5119.4  1437.4  5134.6 1437.57  5218.5 1438.84  5299.5 1442.54
#Mann= 7 ,-1 , 0
  4438.6    .035       0    4876     .12       0  4986.8     .05       0
  4993.5     .12       0  5032.2     .07       0  5119.4    .035       0
  5134.6     .07       0
#XS Ineff= 2 , 0
       0  4931.1 1431.81               0
Permanent Ineff=
       F       F
Bank Sta=4986.8,4993.5
XS Rating Curve= 0 ,0
Exp/Cntr=0.3,0.1

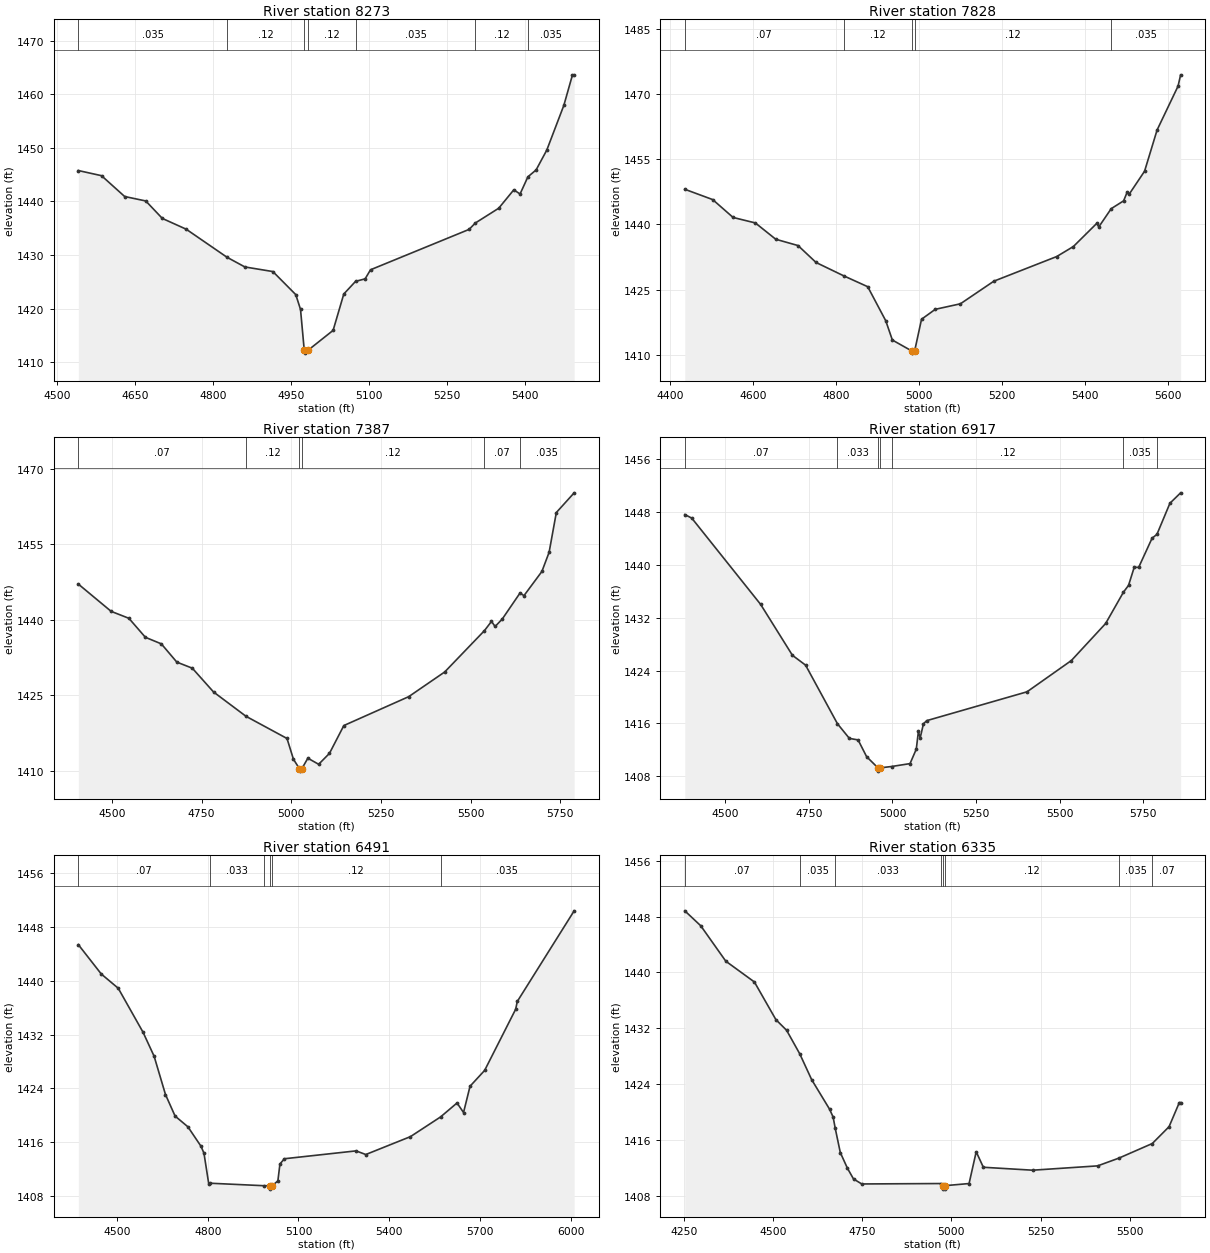
Type RM Length L Ch R = 1 ,8273    ,445,445,445
BEGIN DESCRIPTION:
ASKEY CREEK 16.0
END DESCRIPTION:
XS GIS Cut Line= 3
      2062756.96     13922378.77        2062325.       13922225.
      2061843.75     13922114.87
#Sta/Elev= 30
  4541.4 1445.78  4585.9 1444.82  4630.4 1440.93  4670.9  1440.1  4702.7 1436.84
  4748.5 1434.83  4826.9 1429.59  4861.2 1427.78    4915 1426.92    4959 1422.61
  4968.1 1419.85  4975.3 1412.19  4975.8 1411.69  4982.1 1412.19  5030.7 1415.94
  5051.2 1422.73  5073.8 1425.09  5092.2 1425.56  5102.5 1427.25  5291.8 1434.79
  5303.9 1435.99  5348.7 1438.74  5377.7 1442.18  5389.7  1441.4  5404.8 1444.61
  5420.5 1445.89    5441 1449.59  5473.8 1457.95  5490.4 1463.65  5493.6 1463.65
#Mann= 7 ,-1 , 0
  4541.4    .035       0  4826.9     .12       0  4975.3     .05       0
  4982.1     .12       0  5073.8    .035       0  5303.9     .12       0
  5404.8    .035       0
Bank Sta=4975.3,4982.1
XS Rating Curve= 0 ,0
Exp/Cntr=0.3,0.1

Type RM Length L Ch R = 1 ,7828    ,441,441,441
BEGIN DESCRIPTION:
ASKEY CREEK 15.0
END DESCRIPTION:
XS GIS Cut Line= 3
      2062975.67     13922104.44        2062475.       13921825.
      2061858.82     13921906.39
#Sta/Elev= 30
  4435.3 1448.09  4502.5 1445.72  4551.7 1441.61  4605.3 1440.35  4654.5  1436.6
  4708.2 1435.15  4751.6 1431.26  4818.3 1428.19  4876.1 1425.69  4919.6 1417.86
  4935.5 1413.43  4982.3 1410.92  4982.8 1410.42  4989.2 1410.92  5005.8 1418.21
  5038.9 1420.49  5099.5 1421.76  5180.1 1426.96  5331.5 1432.62  5371.8 1434.93
    5428 1440.24    5433 1439.44  5462.9 1443.63  5492.8 1445.43  5501.5 1447.45
  5506.5    1447  5543.3 1452.24  5573.5 1461.72    5624  1471.8  5630.2  1474.4
#Mann= 5 ,-1 , 0
  4435.3     .07       0  4818.3     .12       0  4982.3     .05       0
  4989.2     .12       0  5462.9    .035       0
Bank Sta=4982.3,4989.2
XS Rating Curve= 0 ,0
Exp/Cntr=0.3,0.1

Type RM Length L Ch R = 1 ,7387    ,470,470,470
BEGIN DESCRIPTION:
ASKEY CREEK 14.0
END DESCRIPTION:
XS GIS Cut Line= 3
      2063187.52     13921766.27        2062675.       13921475.
      2061885.46      13921542.3
#Sta/Elev= 30
  4406.4 1447.07  4497.8 1441.65  4547.3 1440.27  4593.3 1436.49  4637.7 1435.19
  4680.9 1431.56  4724.1 1430.35  4783.3 1425.62  4873.7 1420.79    4988 1416.38
  5005.9 1412.26  5022.5 1410.39    5023 1409.89  5029.5 1410.39  5046.1 1412.46
  5076.2 1411.25  5106.3 1413.42  5146.4 1418.95  5327.1 1424.69  5427.5  1429.6
  5538.3 1437.82  5557.9 1439.65    5568 1438.64    5588 1440.13  5637.5  1445.3
  5648.4 1444.77  5698.4 1449.58  5718.5 1453.39  5738.6 1461.29  5788.3 1465.21
#Mann= 6 ,-1 , 0
  4406.4     .07       0  4873.7     .12       0  5022.5     .05       0
  5029.5     .12       0  5538.3     .07       0  5637.5    .035       0
Bank Sta=5022.5,5029.5
XS Rating Curve= 0 ,0
Exp/Cntr=0.3,0.1

Type RM Length L Ch R = 1 ,6917    ,426,426,426
BEGIN DESCRIPTION:
ASKEY CREEK 13.0
END DESCRIPTION:
XS GIS Cut Line= 3
      2063369.79     13921276.68        2062775.       13921075.
      2061975.05     13921374.98
#Sta/Elev= 30
  4379.1 1447.66  4399.9 1447.12  4605.9 1434.04  4700.9 1426.33  4740.2 1424.84
  4835.5 1415.96  4871.1 1413.74  4897.2 1413.51  4922.7 1410.97  4956.5 1409.28
    4957 1408.78  4963.6 1409.28  4997.3 1409.48  5052.5 1409.92  5071.2 1412.11
  5077.5 1414.79  5082.8  1413.8  5092.6 1415.95  5102.4 1416.43  5402.3  1420.8
  5534.9 1425.54  5637.3 1431.15  5690.7 1435.91  5705.8 1436.93  5722.7 1439.66
  5736.1 1439.66  5776.1 1444.07  5790.7 1444.66  5829.5 1449.37  5861.5 1450.95
#Mann= 7 ,-1 , 0
  4379.1     .07       0  4835.5    .033       0  4956.5     .05       0
  4963.6    .033       0  4997.3     .12       0  5690.7    .035       0
  5790.7     .07       0
Bank Sta=4956.5,4963.6
XS Rating Curve= 0 ,0
Exp/Cntr=0.3,0.1

Type RM Length L Ch R = 1 ,6491    ,156,156,156
BEGIN DESCRIPTION:
ASKEY CREEK 12.0
END DESCRIPTION:
XS GIS Cut Line= 3
      2063416.71     13920932.94        2062825.       13920725.
       2061885.4     13921099.61
#Sta/Elev= 30
  4372.4  1445.4  4448.4 1441.02  4504.3 1438.91  4586.2 1432.37  4622.9 1428.79
  4660.4  1423.1  4692.2 1419.89  4734.6 1418.29  4777.8  1415.4  4787.6 1414.37
  4803.5 1409.78  4807.1  1409.9  4984.8 1409.53  5005.4 1409.52  5005.9 1409.02
  5012.6 1409.52  5031.9 1410.24  5038.7 1412.76  5053.4 1413.54  5290.2 1414.71
  5322.5 1414.17    5470 1416.83  5569.5 1419.76    5624 1421.84  5645.5 1420.42
    5667 1424.33  5715.3 1426.69  5817.8 1435.79  5823.1 1436.94  6011.1 1450.43
#Mann= 6 ,-1 , 0
  4372.4     .07       0  4807.1    .033       0  4984.8     .12       0
  5005.4     .05       0  5012.6     .12       0  5569.5    .035       0
Bank Sta=5005.4,5012.6
XS Rating Curve= 0 ,0
Exp/Cntr=0.3,0.1

Type RM Length L Ch R = 1 ,6335    ,75,75,75
BEGIN DESCRIPTION:
ASKEY CREEK 11.3
END DESCRIPTION:
XS GIS Cut Line= 3
      2063569.57     13920625.19      2062824.52      13920569.8
      2062182.65     13920598.19
#Sta/Elev= 30
  4252.9 1448.83  4297.6 1446.69  4367.8 1441.62    4448 1438.64  4508.2 1433.25
  4538.3 1431.72  4575.1 1428.35  4608.4 1424.66  4658.6 1420.43  4668.6  1419.3
  4674.5 1417.69  4688.7 1414.22  4708.7 1411.97  4725.7 1410.44  4748.8 1409.72
  4970.4 1409.78  4975.9 1409.48  4976.4 1408.98  4982.6 1408.98  4983.1 1409.48
  5049.6 1409.78  5069.6 1414.33  5089.6 1412.11  5227.8 1411.69  5409.9 1412.31
  5469.5 1413.42  5563.1 1415.51  5610.1 1417.92  5638.8 1421.37  5642.5 1421.37
#Mann= 8 ,-1 , 0
  4252.9     .07       0  4575.1    .035       0  4674.5    .033       0
  4970.4     .12       0  4975.9     .05       0  4983.1     .12       0
  5469.5    .035       0  5563.1     .07       0
Bank Sta=4975.9,4983.1
XS Rating Curve= 0 ,0
Exp/Cntr=0.3,0.1