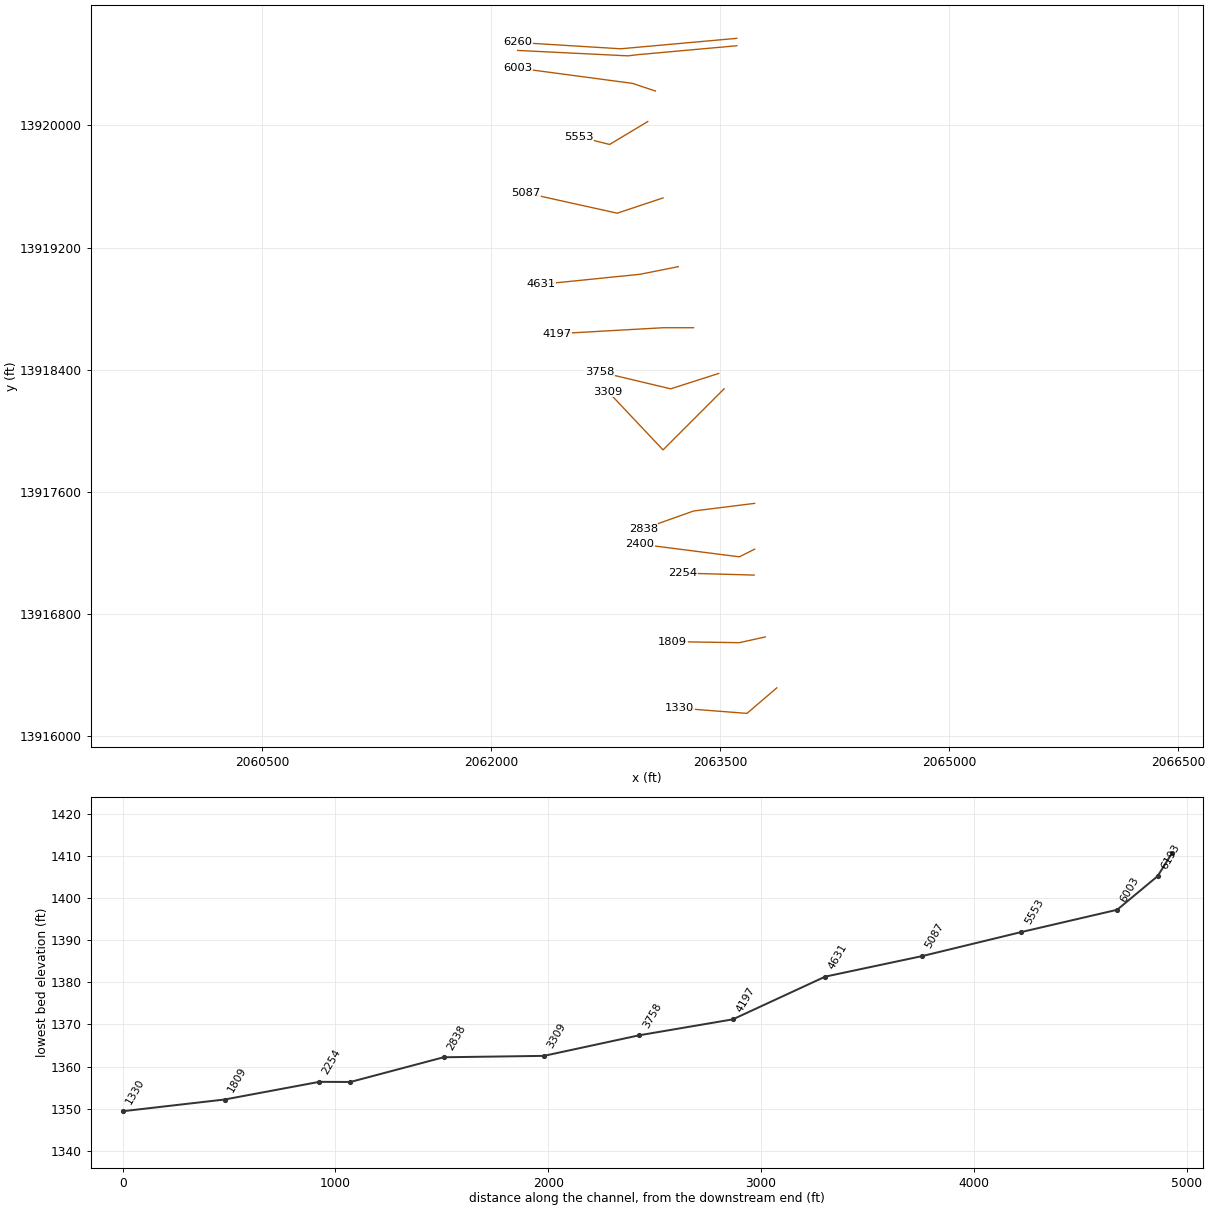
HEC-RAS study ASKEY CREEK.prj: ASKEY CREEK Base Level Engineering

--- ASKEY CREEK.g01 (geometry) --- (continued)

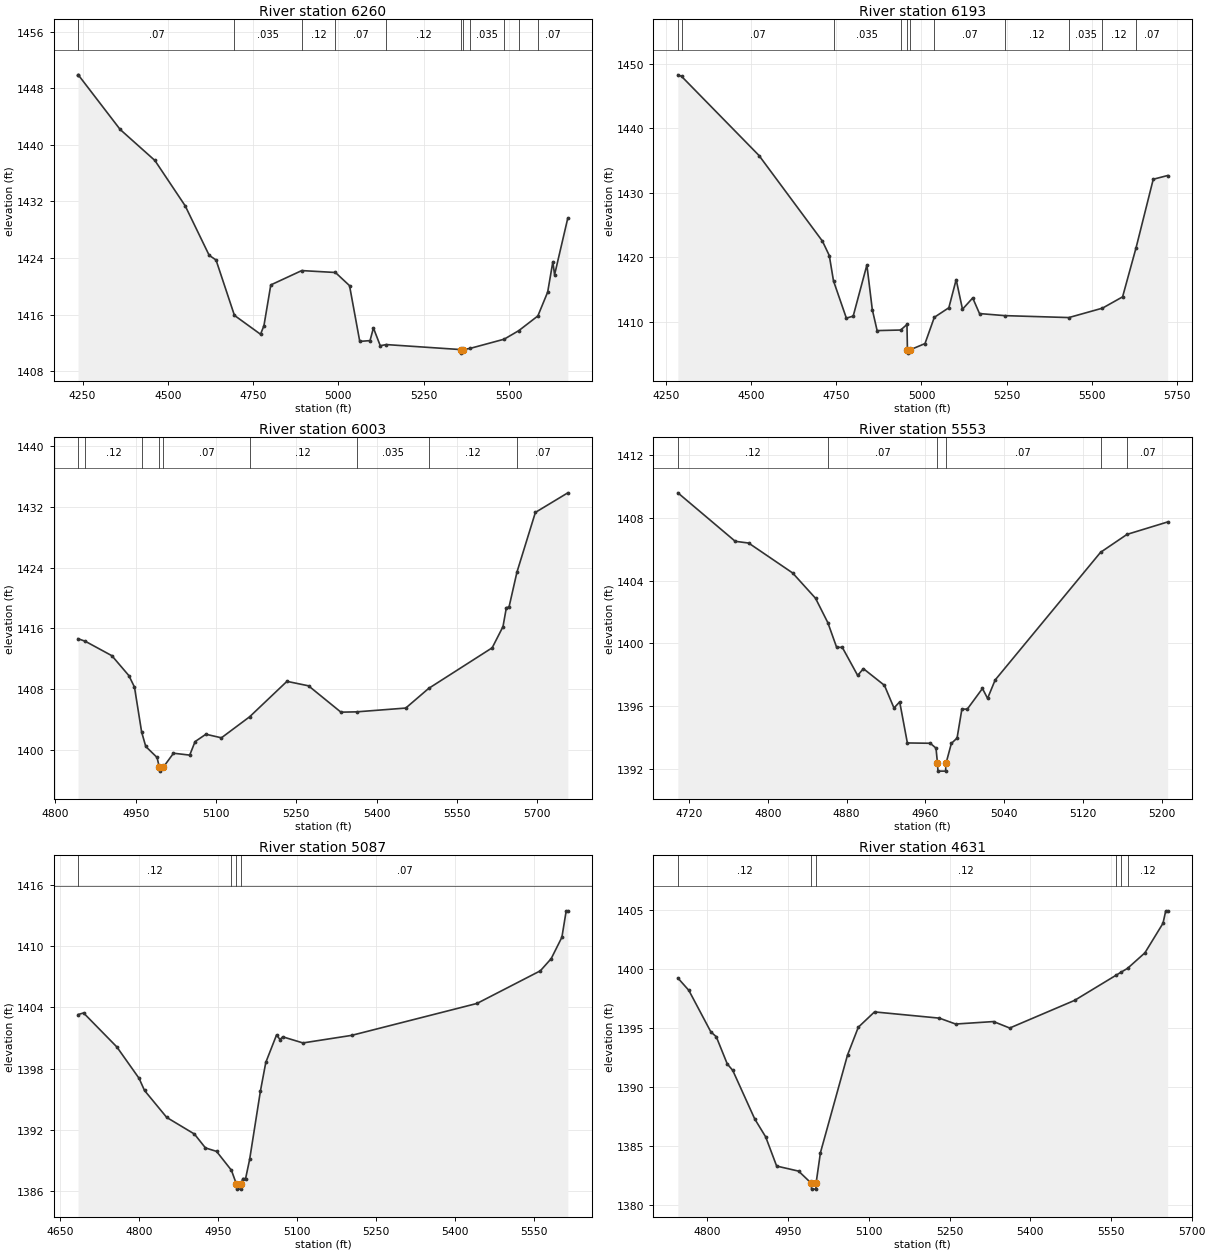
Type RM Length L Ch R = 1 ,6260    ,67,67,67
BEGIN DESCRIPTION:
ASKEY CREEK 11.2
END DESCRIPTION:
XS GIS Cut Line= 3
      2063608.04     13920569.89      2062847.91     13920501.49
      2062175.97     13920542.67
#Sta/Elev= 30
  4236.8 1449.92  4237.4 1449.92  4360.3 1442.19  4462.2  1437.8  4551.1 1431.38
  4621.4 1424.38  4641.5 1423.72  4695.5 1415.88    4772 1413.21    4782 1414.42
  4802.1 1420.19  4892.9 1422.22  4991.6 1421.95    5033 1420.09    5063  1412.2
  5093.1 1412.31  5103.1  1414.1  5123.1 1411.59  5140.8 1411.75    5360 1411.04
  5360.5 1410.54  5367.2 1411.04  5387.4 1411.22  5486.4 1412.51  5529.3 1413.72
  5585.3  1415.8  5614.1 1419.18  5629.3 1423.48  5634.3 1421.62  5673.2 1429.67
#Mann= 12 ,-1 , 0
  4236.8    .035       0  4237.4     .07       0  4695.5    .035       0
  4892.9     .12       0  4991.6     .07       0  5140.8     .12       0
    5360     .05       0  5367.2     .12       0  5387.4    .035       0
  5486.4     .12       0  5529.3    .035       0  5585.3     .07       0
Bank Sta=5360,5367.2
XS Rating Curve= 0 ,0
Exp/Cntr=0.3,0.1

Type RM Length L Ch R = 1 ,6193    ,190,190,190
BEGIN DESCRIPTION:
ASKEY CREEK 11.1
END DESCRIPTION:
XS GIS Cut Line= 4
      2063608.22     13920521.34      2062960.02     13920462.96
      2062895.41     13920455.17      2062172.68     13920490.65
#Sta/Elev= 30
  4284.1 1448.26  4294.8 1448.03  4522.6 1435.76    4709 1422.49  4729.1 1420.26
  4741.5 1416.33  4779.3 1410.56  4799.4 1410.88  4839.6 1418.79  4855.5 1411.89
  4869.7 1408.63  4938.9 1408.72  4957.4 1409.58  4958.8 1405.64  4959.3 1405.14
    4966 1405.64  5010.4 1406.62  5037.8 1410.69  5080.5 1412.17    5102 1416.53
  5120.6 1411.94  5150.6 1413.69  5170.6 1411.27  5244.6 1410.95  5433.2 1410.65
    5532 1412.11  5591.1 1413.86  5630.9  1421.5  5681.2 1432.08  5723.6 1432.66
#Mann= 11 ,-1 , 0
  4284.1    .035       0  4294.8     .07       0  4741.5    .035       0
  4938.9     .12       0  4958.8     .05       0    4966     .12       0
  5037.8     .07       0  5244.6     .12       0  5433.2    .035       0
    5532     .12       0  5630.9     .07       0
Bank Sta=4958.8,4966
XS Rating Curve= 0 ,0
Exp/Cntr=0.3,0.1

Type RM Length L Ch R = 1 ,6003    ,450,450,450
BEGIN DESCRIPTION:
ASKEY CREEK 11.0
END DESCRIPTION:
XS GIS Cut Line= 3
        2063075.       13920225.        2062925.       13920275.
      2062174.95     13920375.01
#Sta/Elev= 30
  4842.3 1414.62  4856.1 1414.27  4905.5 1412.38  4937.2 1409.76  4947.7 1408.25
  4961.1 1402.32  4968.8 1400.42  4989.9 1398.97  4994.2 1397.67  4994.7 1397.17
  5001.4 1397.67  5020.6 1399.53  5050.9 1399.28  5060.9 1401.06  5081.1 1402.03
  5110.1 1401.56  5162.8 1404.33  5232.5    1409  5272.8 1408.41  5333.3 1404.94
  5362.5 1404.98  5454.4 1405.48  5497.2 1408.07  5615.8 1413.42    5636 1416.21
  5642.3 1418.71  5647.3  1418.8  5662.1  1423.4  5696.5 1431.26  5757.1 1433.84
#Mann= 9 ,-1 , 0
  4842.3     .07       0  4856.1     .12       0  4961.1     .07       0
  4994.2     .05       0  5001.4     .07       0  5162.8     .12       0
  5362.5    .035       0  5497.2     .12       0  5662.1     .07       0
Bank Sta=4994.2,5001.4
XS Rating Curve= 0 ,0
Exp/Cntr=0.3,0.1

Type RM Length L Ch R = 1 ,5553    ,466,466,466
BEGIN DESCRIPTION:
ASKEY CREEK 10.0
END DESCRIPTION:
XS GIS Cut Line= 3
      2063024.96     13920024.98        2062775.       13919875.
      2062574.96     13919925.01
#Sta/Elev= 30
  4708.5 1409.57  4766.8 1406.49  4780.4 1406.38  4825.1 1404.48  4848.4 1402.87
  4860.9 1401.32  4869.8 1399.76  4875.6 1399.75  4891.2 1397.97    4897  1398.4
  4918.4 1397.34  4928.1  1395.9  4933.9 1396.29  4941.7 1393.68    4965 1393.66
  4970.8 1393.35  4972.3 1392.39  4972.8 1391.89  4980.5 1391.89    4981 1392.39
  4986.4 1393.65  4992.2 1393.99  4997.1 1395.83  5002.6 1395.83    5018 1397.14
  5023.2 1396.51  5030.9 1397.68    5138 1405.79  5164.9 1406.93  5206.2 1407.72
#Mann= 6 ,-1 , 0
  4708.5     .12       0  4860.9     .07       0  4972.3     .05       0
    4981     .07       0    5138    .035       0  5164.9     .07       0
Bank Sta=4972.3,4981
XS Rating Curve= 0 ,0
Exp/Cntr=0.3,0.1

Type RM Length L Ch R = 1 ,5087    ,456,456,456
BEGIN DESCRIPTION:
ASKEY CREEK 9.0
END DESCRIPTION:
XS GIS Cut Line= 3
        2063125.       13919525.        2062825.       13919425.
      2062223.96     13919557.93
#Sta/Elev= 30
  4683.4  1403.3  4693.9 1403.46  4757.2 1400.13  4799.4 1397.06  4809.9 1395.86
  4852.1 1393.22  4904.8 1391.59  4925.8 1390.23  4946.9 1389.89  4975.2 1388.04
  4984.7 1386.69  4985.2 1386.19    4993 1386.19  4993.5 1386.69    4997 1387.23
  5002.2 1387.23  5009.9 1389.11  5030.4 1395.81  5040.6 1398.61  5061.1 1401.31
  5067.6 1400.85  5072.8 1401.12  5111.3 1400.52  5203.7 1401.26  5442.3 1404.39
  5562.9 1407.59  5583.5 1408.78  5603.9 1410.88  5612.1 1413.47  5615.2 1413.47
#Mann= 4 ,-1 , 0
  4683.4     .12       0  4975.2     .07       0  4984.7     .05       0
  4993.5     .07       0
Bank Sta=4984.7,4993.5
XS Rating Curve= 0 ,0
Exp/Cntr=0.3,0.1

Type RM Length L Ch R = 1 ,4631    ,434,434,434
BEGIN DESCRIPTION:
ASKEY CREEK 8.0
END DESCRIPTION:
XS GIS Cut Line= 3
      2063225.02       13919075.        2062975.       13919025.
      2062322.91     13918958.97
#Sta/Elev= 30
    4745 1399.25  4765.4  1398.2  4806.2 1394.68  4816.4 1394.26  4836.8 1391.95
    4847  1391.4  4887.8 1387.28  4908.2 1385.75  4928.6 1383.27  4969.4 1382.84
    4993 1381.81  4993.5 1381.31  5001.4 1381.31  5001.9 1381.81    5010 1384.41
  5060.3  1392.7  5080.4 1395.07  5110.5 1396.37  5231.1 1395.84  5261.3 1395.34
  5331.7 1395.55  5361.8    1395  5482.4 1397.35  5558.9 1399.47  5568.2 1399.73
  5580.8 1400.07  5613.1 1401.39  5646.7  1403.9  5651.8 1404.96  5655.4 1404.96
#Mann= 6 ,-1 , 0
    4745     .12       0    4993     .05       0  5001.9     .12       0
  5558.9     .12       0  5568.2     .07       0  5580.8     .12       0
Bank Sta=4993,5001.9
XS Rating Curve= 0 ,0
Exp/Cntr=0.3,0.1

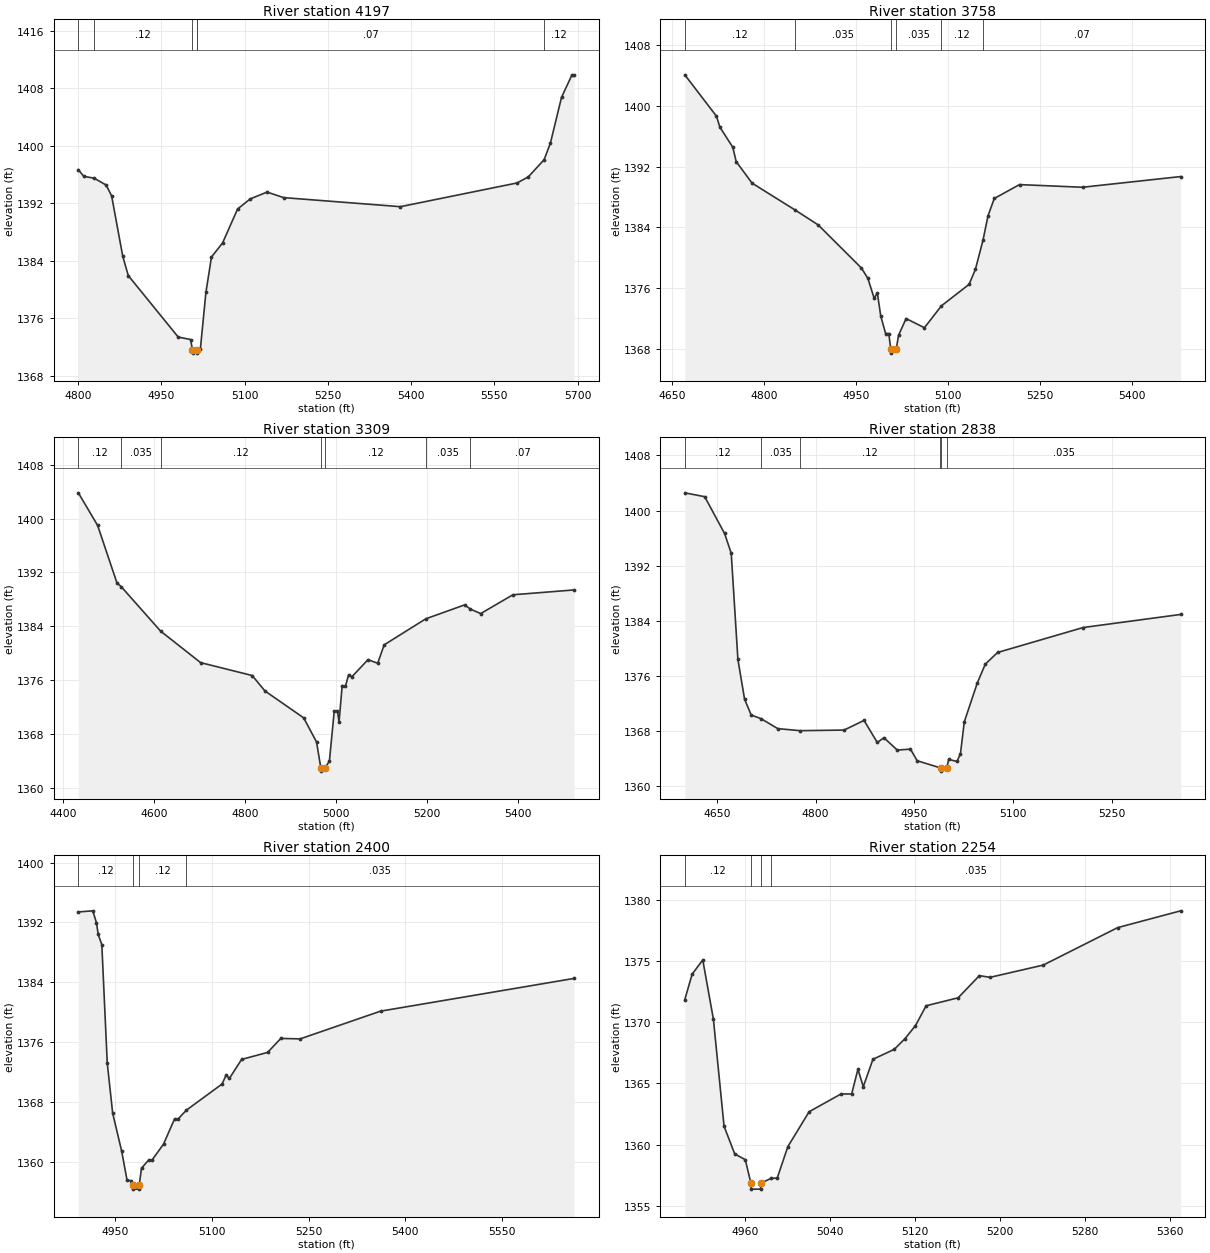
Type RM Length L Ch R = 1 ,4197    ,439,439,439
BEGIN DESCRIPTION:
ASKEY CREEK 7.0
END DESCRIPTION:
XS GIS Cut Line= 3
      2063324.97       13918675.        2063125.       13918675.
      2062432.26     13918636.05
#Sta/Elev= 30
  4800.1 1396.68  4810.1 1395.76  4828.3 1395.52  4850.1 1394.57  4860.1 1393.06
  4880.1 1384.68  4890.1 1381.97  4980.1 1373.42  5002.6 1373.07  5005.6 1371.68
  5006.1 1371.18    5014 1371.18  5014.5 1371.68  5014.9 1371.69  5020.1 1371.75
  5030.1 1379.64  5040.1 1384.54  5060.2 1386.52  5087.2 1391.23  5110.2 1392.64
  5140.3 1393.58  5170.3 1392.81  5380.7 1391.55    5591 1394.85    5611 1395.68
  5639.7 1398.08  5651.1 1400.39  5671.1 1406.75    5690 1409.89  5693.9 1409.89
#Mann= 6 ,-1 , 0
  4800.1    .035       0  4828.3     .12       0  5005.6     .05       0
  5014.5     .12       0  5014.9     .07       0  5639.7     .12       0
Bank Sta=5005.6,5014.5
XS Rating Curve= 0 ,0
Exp/Cntr=0.3,0.1

Type RM Length L Ch R = 1 ,3758    ,449,449,449
BEGIN DESCRIPTION:
ASKEY CREEK 6.0
END DESCRIPTION:
XS GIS Cut Line= 3
      2063489.59     13918375.64        2063175.       13918275.
      2062709.21     13918385.85
#Sta/Elev= 30
  4670.2 1404.12  4721.9 1398.66  4727.5 1397.21  4748.5 1394.57  4754.1 1392.67
    4780 1389.83    4850  1386.3  4887.9 1384.32  4958.5 1378.63    4969 1377.26
  4979.2 1374.65  4984.4 1375.33    4990 1372.29  4997.9 1369.99  5003.1 1369.99
  5006.3 1367.91  5006.8 1367.41  5015.2 1367.91    5019 1369.76  5031.3 1371.97
  5061.2 1370.76    5089 1373.65  5134.1 1376.48  5144.4 1378.45  5156.9 1382.34
    5165 1385.52  5175.2 1387.81  5216.4 1389.64  5319.2 1389.29  5479.3  1390.7
#Mann= 6 ,-1 , 0
  4670.2     .12       0    4850    .035       0  5006.3    .035       0
  5015.2    .035       0    5089     .12       0  5156.9     .07       0
Bank Sta=5006.3,5015.2
XS Rating Curve= 0 ,0
Exp/Cntr=0.3,0.1

Type RM Length L Ch R = 1 ,3309    ,471,471,471
BEGIN DESCRIPTION:
ASKEY CREEK 5.0
END DESCRIPTION:
XS GIS Cut Line= 3
      2063525.01     13918275.01        2063125.       13917875.
      2062765.65     13918255.83
#Sta/Elev= 30
  4434.3 1403.82  4476.7 1398.98  4519.2 1390.44  4528.3 1389.91    4615  1383.3
    4703 1378.62  4816.2 1376.71  4844.4 1374.41  4929.3 1370.43  4957.6 1366.85
    4967 1363.02  4967.5 1362.52  4976.5 1363.02  4985.9 1364.01  4996.5 1371.43
  5003.4 1371.43  5007.1 1369.85    5014 1375.21  5021.2 1375.13  5028.1 1376.82
  5035.4 1376.53  5070.6 1379.06    5092 1378.53  5106.2 1381.26  5197.5 1385.12
    5283 1387.19  5295.8 1386.56  5318.2  1385.9    5389 1388.69  5523.6 1389.41
#Mann= 7 ,-1 , 0
  4434.3     .12       0  4528.3    .035       0    4615     .12       0
    4967     .05       0  4976.5     .12       0  5197.5    .035       0
  5295.8     .07       0
Bank Sta=4967,4976.5
XS Rating Curve= 0 ,0
Exp/Cntr=0.3,0.1

Type RM Length L Ch R = 1 ,2838    ,438,438,438
BEGIN DESCRIPTION:
ASKEY CREEK 4.0
END DESCRIPTION:
XS GIS Cut Line= 3
      2063724.98       13917525.        2063325.       13917475.
      2062995.55     13917358.01
#Sta/Elev= 30
  4601.4 1402.58  4631.6 1402.02  4661.8 1396.68  4671.9  1393.8    4682 1378.42
  4692.1 1372.65  4702.2 1370.33    4717 1369.81  4742.5 1368.36  4776.4 1368.06
  4843.2 1368.15  4873.5 1369.55  4893.6 1366.35  4903.7 1367.04  4923.9 1365.25
    4944 1365.38  4954.1  1363.7  4988.2  1362.7  4989.7 1362.69  4990.2 1362.19
  4999.2 1362.69    5002  1363.9  5014.6 1363.59  5019.9 1364.73  5025.7 1369.34
  5045.5    1375  5057.6 1377.72  5076.3 1379.41  5206.1 1383.03  5354.1 1384.93
#Mann= 6 ,-1 , 0
  4601.4     .12       0    4717    .035       0  4776.4     .12       0
  4988.2    .035       0  4989.7    .035       0  4999.2    .035       0
Bank Sta=4989.7,4999.2
XS Rating Curve= 0 ,0
Exp/Cntr=0.3,0.1

Type RM Length L Ch R = 1 ,2400    ,146,146,146
BEGIN DESCRIPTION:
ASKEY CREEK 3.0
END DESCRIPTION:
XS GIS Cut Line= 3
      2063725.04     13917225.02        2063625.       13917175.
      2062973.84     13917258.18
#Sta/Elev= 30
  4893.2 1393.41  4915.6 1393.56  4921.2 1391.99    4924 1390.41  4929.6 1389.03
    4938 1373.21  4946.4 1366.49  4960.3 1361.43  4968.7 1357.52  4974.3 1357.47
  4977.9 1356.83  4978.4 1356.33    4987 1356.33  4987.5 1356.83  4991.1 1359.13
  5002.3 1360.24  5007.6 1360.24  5025.2 1362.35  5042.4 1365.74  5047.5 1365.69
  5060.6 1366.89  5115.9 1370.39  5122.2 1371.58  5127.2 1371.13  5146.2 1373.68
  5186.5 1374.62    5207 1376.49  5236.9 1376.43  5361.6 1380.14  5661.5 1384.52
#Mann= 4 ,-1 , 0
  4893.2     .12       0  4977.9     .05       0  4987.5     .12       0
  5060.6    .035       0
Bank Sta=4977.9,4987.5
XS Rating Curve= 0 ,0
Exp/Cntr=0.3,0.1

Type RM Length L Ch R = 1 ,2254    ,445,445,445
BEGIN DESCRIPTION:
ASKEY CREEK 2.0
END DESCRIPTION:
XS GIS Cut Line= 2
      2063721.85     13917055.41      2063255.83     13917068.49
#Sta/Elev= 30
  4903.6 1371.83  4910.5 1373.91  4920.5 1375.07  4930.5 1370.23  4940.5  1361.5
  4950.5 1359.24  4960.5 1358.76  4965.7 1356.86  4966.2 1356.36  4974.8 1356.36
  4975.3 1356.86  4984.8 1357.24  4990.5 1357.26  5000.5 1359.83  5020.5 1362.68
  5050.5 1364.13  5060.5 1364.13  5066.4 1366.15  5071.4 1364.72  5080.5 1366.96
  5100.5 1367.77  5110.5 1368.63  5120.5 1369.71  5130.5 1371.33  5160.6 1371.98
  5180.6 1373.79  5190.6 1373.65  5240.6 1374.65  5310.6 1377.71  5369.8 1379.08
#Mann= 4 ,-1 , 0
  4903.6     .12       0  4965.7    .035       0  4975.3     .12       0
  4984.8    .035       0
Bank Sta=4965.7,4975.3
XS Rating Curve= 0 ,0
Exp/Cntr=0.3,0.1

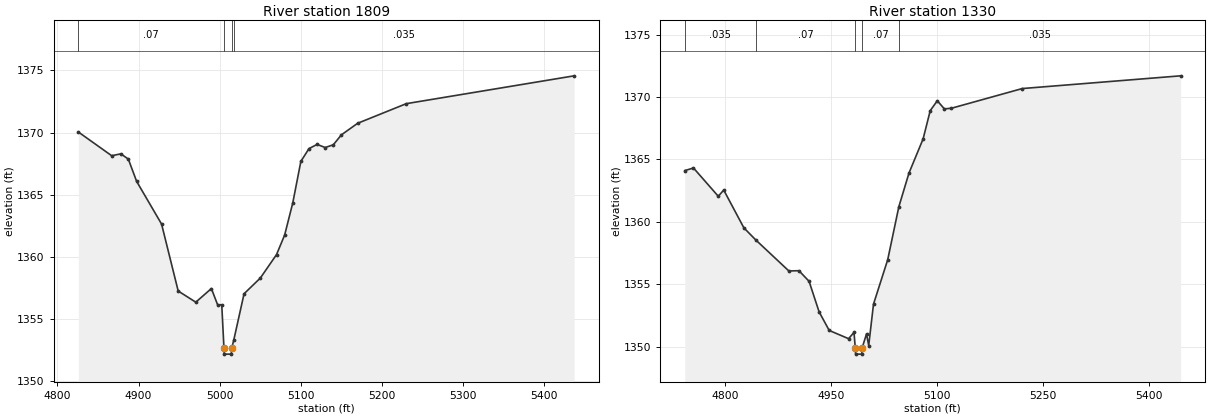
Type RM Length L Ch R = 1 ,1809    ,479,479,479
BEGIN DESCRIPTION:
ASKEY CREEK 1.0
END DESCRIPTION:
XS GIS Cut Line= 3
      2063795.18     13916650.44      2063624.99      13916612.8
      2063188.14     13916619.53
#Sta/Elev= 30
  4825.7 1370.05  4866.8 1368.14  4878.1 1368.29  4887.3 1367.87  4897.6 1366.07
  4928.3 1362.64  4948.8 1357.25  4970.5 1356.35  4989.7 1357.45  4997.4 1356.14
  5002.5 1356.14  5005.2 1352.67  5005.7 1352.17  5014.3 1352.17  5014.8 1352.67
  5017.2 1353.27    5030 1357.03    5050 1358.29    5070 1360.18    5080 1361.75
    5090 1364.33    5100 1367.68    5110 1368.71    5120 1369.05    5130  1368.8
    5140 1369.02    5150 1369.82    5170 1370.75    5230 1372.33  5436.9 1374.57
#Mann= 4 ,-1 , 0
  4825.7     .07       0  5005.2     .05       0  5014.8     .07       0
  5017.2    .035       0
Bank Sta=5005.2,5014.8
XS Rating Curve= 0 ,0
Exp/Cntr=0.3,0.1

Type RM Length L Ch R = 1 ,1330    ,0,0,0
BEGIN DESCRIPTION:
ASKEY CREEK 0.0
END DESCRIPTION:
XS GIS Cut Line= 3
      2063870.41     13916317.05      2063674.79     13916149.91
      2063231.61     13916184.13
#Sta/Elev= 30
  4742.7 1364.11    4755 1364.32  4790.1 1362.05  4797.8 1362.55  4826.3 1359.52
  4843.1 1358.55    4890 1356.06  4904.3 1356.08  4918.6 1355.23  4932.8 1352.78
  4947.1 1351.29  4974.5 1350.63  4982.2 1351.13    4984 1349.89  4984.5 1349.39
  4993.2 1349.39  4993.7 1349.89  4999.9 1351.01    5003 1350.08  5009.8  1353.4
  5029.9 1356.96  5045.7 1361.22    5060 1363.91    5080 1366.65  5090.1 1368.92
  5100.1 1369.71  5110.1 1369.06  5120.1 1369.11  5220.4 1370.69  5444.5 1371.71
#Mann= 5 ,-1 , 0
  4742.7    .035       0  4843.1     .07       0    4984     .05       0
  4993.7     .07       0  5045.7    .035       0
Bank Sta=4984,4993.7
XS Rating Curve= 0 ,0
Exp/Cntr=0.3,0.1

Chan Stop Cuts=-1
Use User Specified Reach Order=0
Composite Channel Slope=5