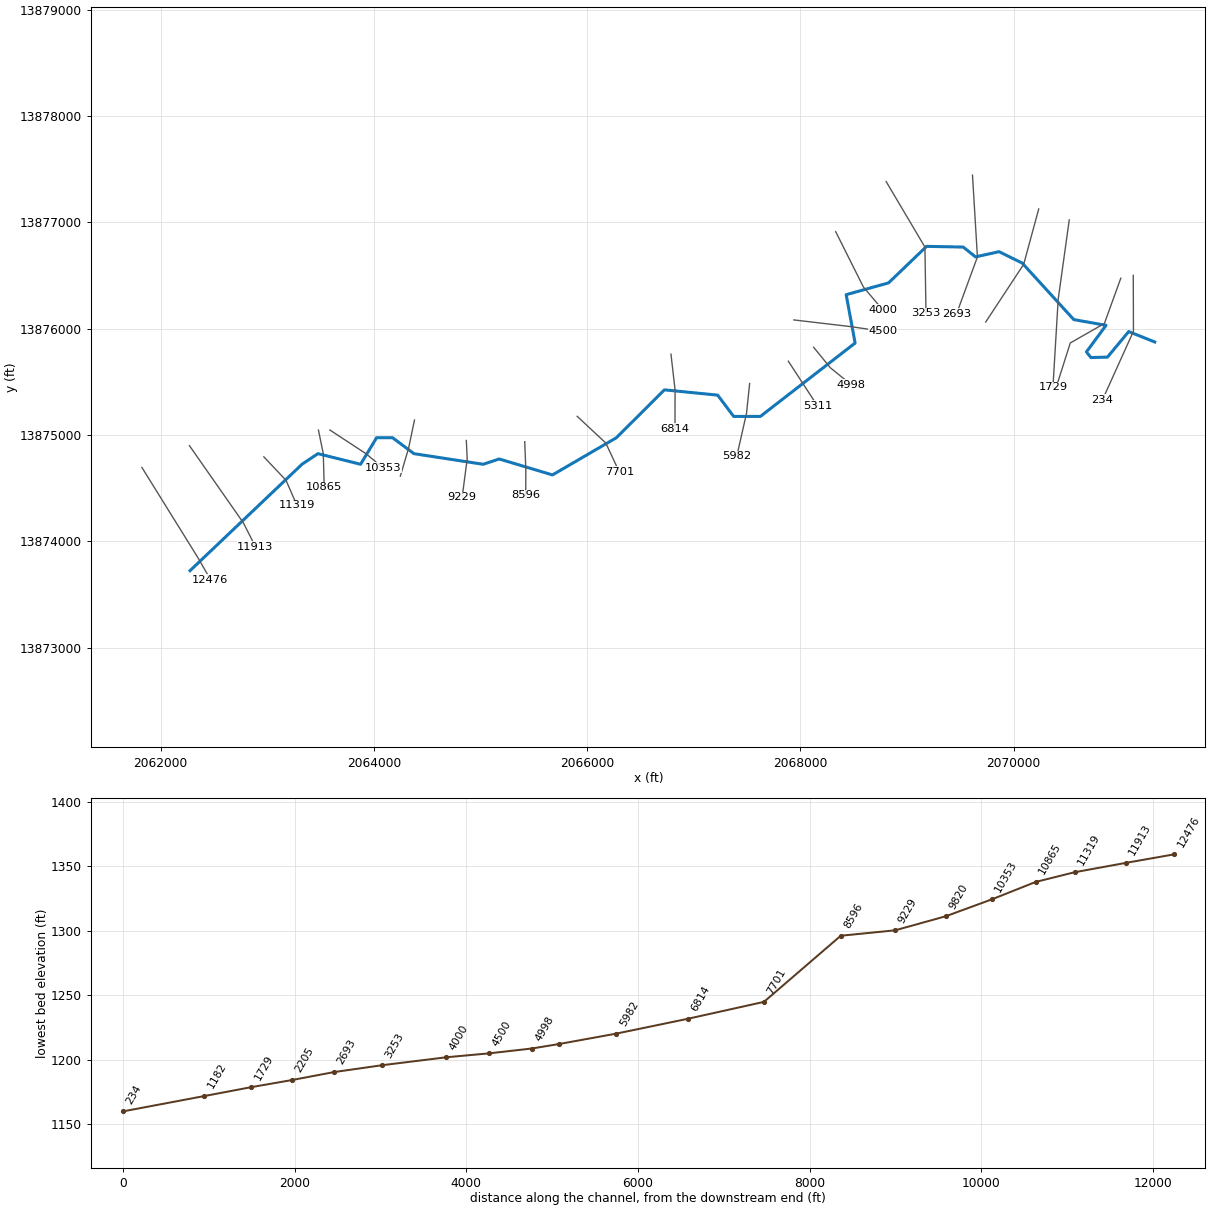
--- BEAR CREEK.prj (project) ---

Proj Title=BEAR CREEK Base Level Engineering
Current Plan=p01
Default Exp/Contr=0.3,0.1
English Units
Geom File=g01
Flow File=f01
Plan File=p01
BEGIN DESCRIPTION:
BEAR CREEK
END DESCRIPTION:

--- BEAR CREEK.p01 (plan) ---

Plan Title=Multiple Run
Short Identifier=Multiple
Geom File=g01
Flow File=f01
Subcritical Flow
K Sum by GR= 0
Std Step Tol= 0.01
Critical Tol= 0.01
Num of Std Step Trials= 20
Max Error Tol= 0.3
Flow Tol Ratio= 0.001
Split Flow NTrial= 30
Split Flow Tol= 0.02
Split Flow Ratio= 0.02
Log Output Level= 0
Friction Slope Method= 1
Unsteady Friction Slope Method= 2
Unsteady Bridges Friction Slope Method= 1
Parabolic Critical Depth
Global Vel Dist=  1 , 1 , 1
Global Log Level= 0
CheckData=True
Encroach Param= -1, 0, 0, 0
BEGIN DESCRIPTION:
Multiple Run
END DESCRIPTION:

--- BEAR CREEK.f01 (steady flow) ---

Flow Title=Multiple
Number of Profiles=7
Profile Names=10-year,25-year,50-year,1pct_min,100-year,1pct_plu,500-year
River Rch & RM= BEAR CREEK,Reach-1,12476
     310     477     622     396     789    1575    1249
River Rch & RM= BEAR CREEK,Reach-1,10865
     723    1185    1612    1066    2126    4242    3648
River Rch & RM= BEAR CREEK,Reach-1,7701
    1369    2331    3253    2198    4385    8750    7882
River Rch & RM= BEAR CREEK,Reach-1,4000
    1606    2753    3857    2615    5217   10409    9439
Boundary for River Rch & Prof#=BEAR CREEK,Reach-1,1
Up Type=0
Dn Type=3
Dn Slope=0.005
Boundary for River Rch & Prof#=BEAR CREEK,Reach-1,2
Up Type=0
Dn Type=3
Dn Slope=0.005
Boundary for River Rch & Prof#=BEAR CREEK,Reach-1,3
Up Type=0
Dn Type=3
Dn Slope=0.005
Boundary for River Rch & Prof#=BEAR CREEK,Reach-1,4
Up Type=0
Dn Type=3
Dn Slope=0.005
Boundary for River Rch & Prof#=BEAR CREEK,Reach-1,5
Up Type=0
Dn Type=3
Dn Slope=0.005
Boundary for River Rch & Prof#=BEAR CREEK,Reach-1,6
Up Type=0
Dn Type=3
Dn Slope=0.005
Boundary for River Rch & Prof#=BEAR CREEK,Reach-1,7
Up Type=0
Dn Type=3
Dn Slope=0.005

--- BEAR CREEK.g01 (geometry) ---

Geom Title=Existing Conditions

River Reach=BEAR CREEK,Reach-1
Reach XY= 30
      2062275.00     13873725.00      2063325.00     13874725.00
      2063475.00     13874825.00      2063875.00     13874725.00
      2064025.00     13874975.00      2064175.00     13874975.00
      2064375.00     13874825.00      2065025.00     13874725.00
      2065175.00     13874775.00      2065675.00     13874625.00
      2066275.00     13874975.00      2066725.00     13875425.00
      2067225.00     13875375.00      2067375.00     13875175.00
      2067625.00     13875175.00      2068513.90     13875864.94
      2068430.17     13876319.59      2068827.45     13876430.47
      2069184.63     13876773.91      2069528.41     13876767.19
      2069643.28     13876674.94      2069864.46     13876723.91
      2070081.32     13876616.93      2070565.20     13876085.48
      2070867.68     13876031.38      2070683.88     13875781.49
      2070725.98     13875728.53      2070881.47     13875732.69
      2071080.48     13875972.92      2071325.00     13875875.00

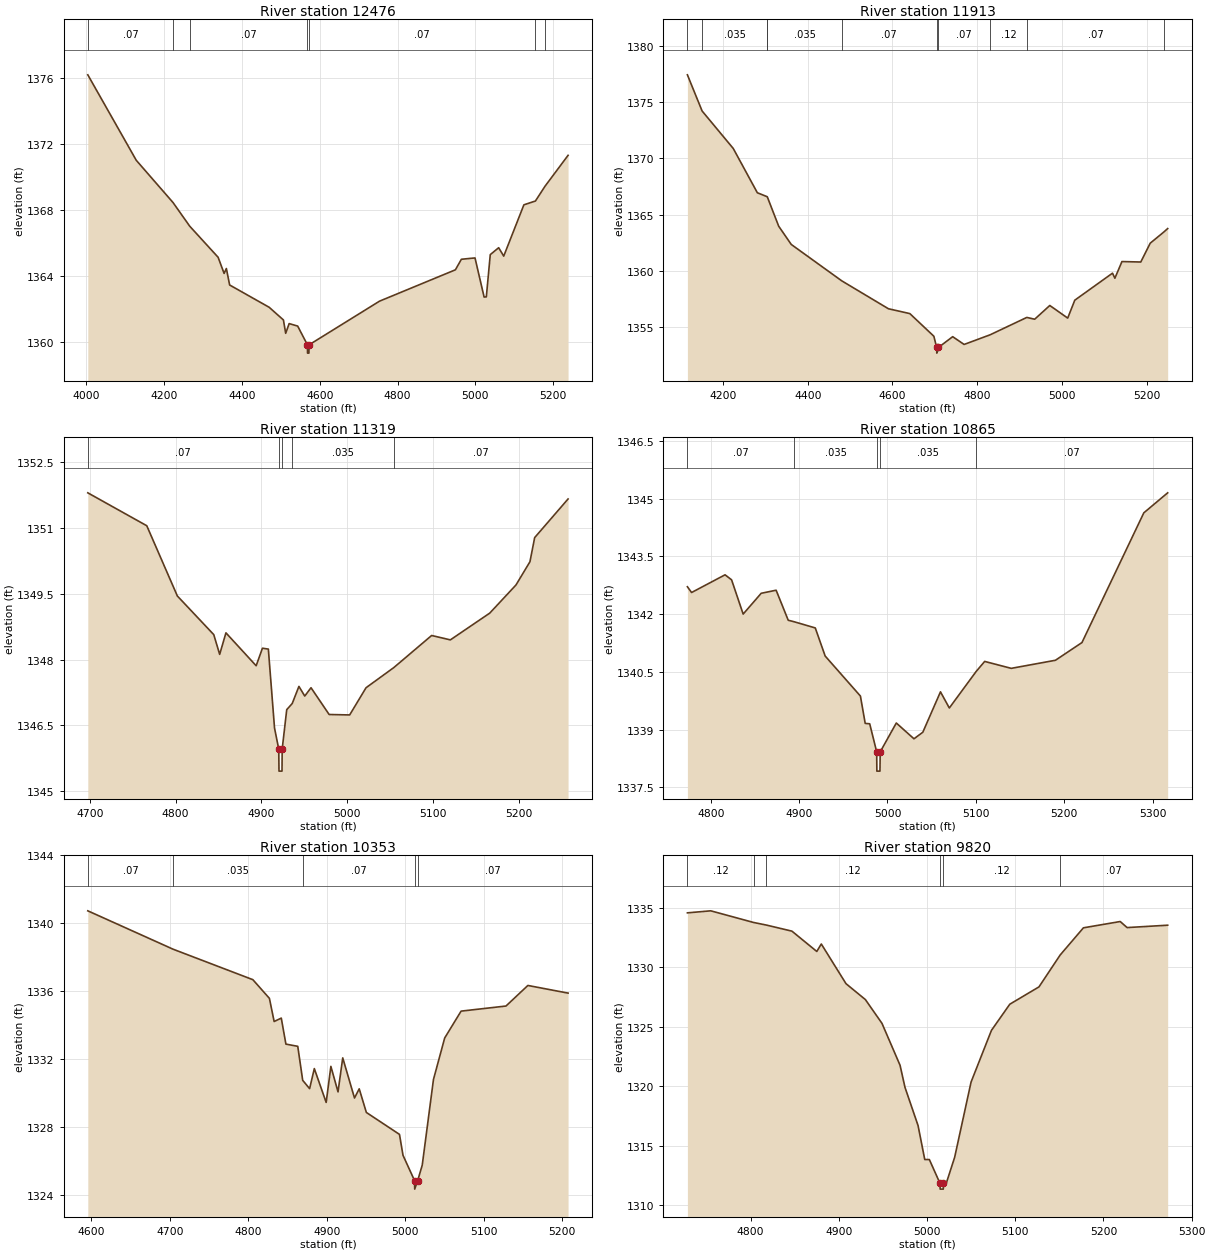
Type RM Length L Ch R = 1,12476,563,563,563
BEGIN DESCRIPTION:
BEAR CREEK_DS 21.0
END DESCRIPTION:
XS GIS Cut Line= 3
      2061823.78     13874694.74      2062348.25     13873848.25
      2062466.39     13873641.53
#Sta/Elev= 30
  4004.2 1376.19  4128.7 1371.01  4223.1 1368.45  4266.2 1367.01  4339.0 1365.13
  4354.4 1364.15  4360.2 1364.45  4368.6 1363.45  4470.1 1362.10  4506.8 1361.33
  4512.6 1360.52  4521.5 1361.11  4543.4 1360.96  4568.5 1359.82  4568.8 1359.32
  4572.3 1359.32  4572.5 1359.82  4753.7 1362.47  4948.6 1364.37  4964.0 1365.01
  4999.0 1365.09  5022.4 1362.72  5028.1 1362.73  5038.2 1365.29  5059.8 1365.71
  5072.8 1365.20  5124.6 1368.31  5154.2 1368.54  5178.7 1369.43  5238.1 1371.31
#Mann=7,-1,0
  4004.2    0.07       0  4223.1   0.035       0  4266.2    0.07       0
  4568.5    0.05       0  4572.5    0.07       0  5154.2   0.035       0
  5178.7    0.07       0
Bank Sta=4568.5,4572.5
Exp/Cntr=0.3,0.1

Type RM Length L Ch R = 1,11913,594,594,594
BEGIN DESCRIPTION:
BEAR CREEK_DS 20.0
END DESCRIPTION:
XS GIS Cut Line= 3
      2062269.22     13874900.50      2062775.00     13874175.00
      2062888.00     13873952.00
#Sta/Elev= 30
  4115.6 1377.41  4150.3 1374.20  4223.9 1370.87  4280.8 1366.94  4303.9 1366.59
  4304.3 1366.58  4331.2 1363.97  4360.9 1362.35  4480.1 1359.12  4590.4 1356.64
  4641.0 1356.21  4697.7 1354.20  4704.4 1353.20  4704.7 1352.70  4708.4 1353.20
  4742.2 1354.16  4769.2 1353.47  4830.8 1354.33  4917.3 1355.87  4935.9 1355.71
  4971.6 1356.93  5013.9 1355.81  5030.6 1357.40  5119.7 1359.80  5125.3 1359.35
  5142.0 1360.83  5186.5 1360.79  5208.8 1362.46  5241.1 1363.46  5250.0 1363.76
#Mann=10,-1,0
  4115.6    0.07       0  4150.3   0.035       0  4303.9    0.07       0
  4304.3   0.035       0  4480.1    0.07       0  4704.4    0.05       0
  4708.4    0.07       0  4830.8    0.12       0  4917.3    0.07       0
  5241.1   0.035       0
Bank Sta=4704.4,4708.4
Exp/Cntr=0.3,0.1

Type RM Length L Ch R = 1,11319,454,454,454
BEGIN DESCRIPTION:
BEAR CREEK_DS 19.0
END DESCRIPTION:
XS GIS Cut Line= 3
      2062967.49     13874794.83      2063175.00     13874575.00
      2063277.76     13874339.33
#Sta/Elev= 30
  4697.7 1351.80  4766.4 1351.05  4802.0 1349.45  4844.4 1348.57  4851.3 1348.12
  4858.6 1348.61  4893.8 1347.86  4901.1 1348.26  4908.0 1348.24  4915.2 1346.44
  4920.1 1345.96  4920.4 1345.46  4923.9 1345.46  4924.1 1345.96  4929.4 1346.86
  4935.8 1347.00  4943.6 1347.39  4950.4 1347.17  4957.7 1347.36  4978.8 1346.75
  5002.7 1346.74  5021.8 1347.36  5054.2 1347.82  5098.2 1348.55  5120.0 1348.45
  5165.9 1349.06  5196.4 1349.70  5212.7 1350.23  5218.2 1350.78  5257.1 1351.66
#Mann=5,-1,0
  4697.7    0.07       0  4920.1   0.035       0  4924.1    0.07       0
  4935.8   0.035       0  5054.2    0.07       0
Bank Sta=4920.1,4924.1
Exp/Cntr=0.3,0.1

Type RM Length L Ch R = 1,10865,512,512,512
BEGIN DESCRIPTION:
BEAR CREEK_DS 18.0
END DESCRIPTION:
XS GIS Cut Line= 3
      2063479.49     13875046.78      2063525.00     13874825.00
      2063533.86     13874508.02
#Sta/Elev= 30
  4773.6 1342.71  4778.3 1342.56  4816.2 1343.02  4823.6 1342.89  4836.7 1342.00
  4857.1 1342.54  4874.0 1342.62  4887.7 1341.84  4894.5 1341.80  4918.3 1341.64
  4929.5 1340.91  4969.4 1339.87  4974.8 1339.16  4979.9 1339.15  4987.8 1338.42
  4988.0 1337.92  4991.5 1337.92  4991.8 1338.42  5010.0 1339.17  5030.0 1338.76
  5040.0 1338.93  5060.0 1339.98  5070.0 1339.56  5100.4 1340.51  5110.0 1340.77
  5140.1 1340.59  5190.1 1340.80  5220.1 1341.26  5290.1 1344.63  5317.1 1345.15
#Mann=5,-1,0
  4773.6    0.07       0  4894.5   0.035       0  4987.8   0.035       0
  4991.8   0.035       0  5100.4    0.07       0
Bank Sta=4987.8,4991.8
Exp/Cntr=0.3,0.1

Type RM Length L Ch R = 1,10353,533,533,533
BEGIN DESCRIPTION:
BEAR CREEK_DS 17.0
END DESCRIPTION:
XS GIS Cut Line= 3
      2063586.93     13875047.29      2063925.00     13874825.00
      2064084.34     13874692.39
#Sta/Elev= 30
  4595.4 1340.73  4704.2 1338.47  4805.7 1336.68  4826.8 1335.58  4832.8 1334.22
  4841.9 1334.42  4847.8 1332.89  4862.9 1332.76  4869.2 1330.76  4878.0 1330.27
  4884.0 1331.45  4899.1 1329.46  4905.1 1331.58  4914.2 1330.08  4920.2 1332.08
  4935.2 1329.72  4941.2 1330.26  4950.3 1328.87  4992.5 1327.58  4997.0 1326.35
  5011.7 1324.86  5011.9 1324.36  5015.7 1324.86  5021.5 1325.77  5035.8 1330.81
  5050.1 1333.25  5071.0 1334.83  5128.2 1335.13  5156.1 1336.34  5207.3 1335.89
#Mann=5,-1,0
  4595.4    0.07       0  4704.2   0.035       0  4869.2    0.07       0
  5011.7    0.05       0  5015.7    0.07       0
Bank Sta=5011.7,5015.7
Exp/Cntr=0.3,0.1

Type RM Length L Ch R = 1,9820,591,591,591
BEGIN DESCRIPTION:
BEAR CREEK_DS 16.0
END DESCRIPTION:
XS GIS Cut Line= 3
      2064380.55     13875140.96      2064325.00     13874875.00
      2064247.69     13874613.38
#Sta/Elev= 30
  4728.3 1334.59  4754.8 1334.76  4803.3 1333.78  4817.9 1333.56  4846.8 1333.05
  4875.0 1331.34  4880.1 1331.97  4908.1 1328.63  4930.1 1327.29  4948.9 1325.29
  4969.4 1321.76  4975.0 1319.90  4989.8 1316.69  4997.4 1313.83  5002.6 1313.83
  5014.6 1311.84  5014.9 1311.34  5018.4 1311.34  5018.6 1311.84  5021.9 1311.86
  5031.3 1314.02  5049.9 1320.35  5073.0 1324.70  5093.8 1326.90  5126.9 1328.36
  5150.9 1331.04  5177.3 1333.33  5219.0 1333.86  5226.8 1333.35  5272.8 1333.55
#Mann=6,-1,0
  4728.3    0.12       0  4803.3    0.07       0  4817.9    0.12       0
  5014.6    0.05       0  5018.6    0.12       0  5150.9    0.07       0
Bank Sta=5014.6,5018.6
Exp/Cntr=0.3,0.1

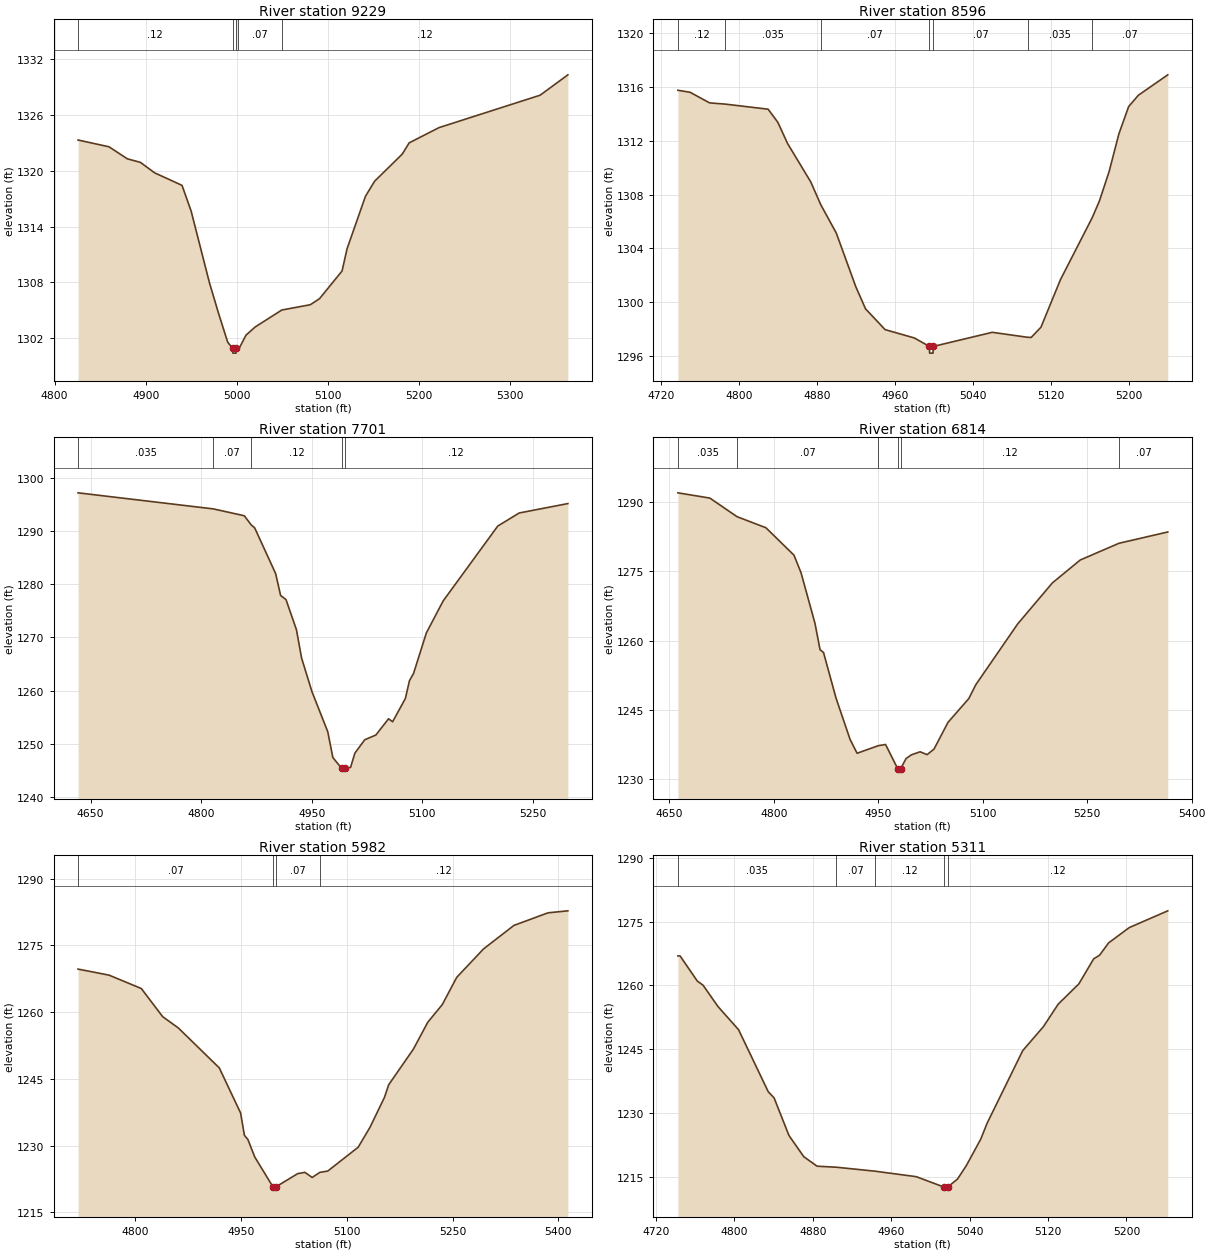
Type RM Length L Ch R = 1,9229,633,633,633
BEGIN DESCRIPTION:
BEAR CREEK_DS 15.0
END DESCRIPTION:
XS GIS Cut Line= 3
      2064866.81     13874949.01      2064875.00     13874775.00
      2064827.59     13874414.81
#Sta/Elev= 30
  4825.8 1323.29  4859.8 1322.56  4879.9 1321.27  4894.2 1320.89  4909.9 1319.76
  4939.9 1318.42  4949.9 1315.66  4970.0 1307.96  4980.0 1304.67  4990.0 1301.58
  4995.5 1300.90  4995.7 1300.40  4999.2 1300.40  4999.5 1300.90  5001.0 1300.90
  5002.5 1300.90  5010.1 1302.33  5020.2 1303.21  5049.4 1305.03  5080.7 1305.60
  5090.8 1306.25  5115.5 1309.22  5121.0 1311.61  5141.2 1317.25  5151.3 1318.87
  5181.6 1321.78  5189.1 1322.98  5221.9 1324.62  5332.8 1328.10  5363.3 1330.29
#Mann=5,-1,0
  4825.8    0.12       0  4995.5    0.05       0  4999.5    0.12       0
  5001.0    0.07       0  5049.4    0.12       0
Bank Sta=4995.5,4999.5
Exp/Cntr=0.3,0.1

Type RM Length L Ch R = 1,8596,895,895,895
BEGIN DESCRIPTION:
BEAR CREEK_DS 14.0
END DESCRIPTION:
XS GIS Cut Line= 3
      2065414.69     13874937.50      2065425.00     13874675.00
      2065423.87     13874434.80
#Sta/Elev= 30
  4737.3 1315.77  4749.8 1315.62  4769.8 1314.83  4785.7 1314.74  4829.9 1314.36
  4839.9 1313.38  4849.9 1311.80  4873.7 1308.94  4884.0 1307.24  4899.9 1305.13
  4919.9 1301.14  4929.9 1299.49  4950.0 1297.94  4980.0 1297.32  4995.5 1296.69
  4995.7 1296.19  4999.2 1296.19  4999.5 1296.69  5060.0 1297.74  5096.3 1297.37
  5100.0 1297.36  5110.0 1298.12  5130.0 1301.66  5162.7 1306.29  5170.0 1307.52
  5180.0 1309.72  5190.0 1312.52  5200.0 1314.55  5210.0 1315.40  5240.2 1316.92
#Mann=7,-1,0
  4737.3    0.12       0  4785.7   0.035       0  4884.0    0.07       0
  4995.5    0.05       0  4999.5    0.07       0  5096.3   0.035       0
  5162.7    0.07       0
Bank Sta=4995.5,4999.5
Exp/Cntr=0.3,0.1

Type RM Length L Ch R = 1,7701,887,887,887
BEGIN DESCRIPTION:
BEAR CREEK_DS 13.0
END DESCRIPTION:
XS GIS Cut Line= 3
      2065907.09     13875175.97      2066175.00     13874925.00
      2066300.84     13874655.10
#Sta/Elev= 30
  4632.9 1297.16  4816.5 1294.14  4858.6 1292.85  4867.9 1291.14  4872.7 1290.57
  4901.1 1281.99  4907.9 1277.86  4915.2 1277.09  4929.4 1271.41  4936.3 1266.13
  4950.4 1259.80  4971.9 1252.24  4978.8 1247.40  4990.9 1245.35  4991.2 1244.85
  4994.9 1245.35  5002.8 1245.55  5008.7 1248.23  5022.1 1250.75  5037.1 1251.63
  5054.4 1254.69  5059.9 1254.13  5077.2 1258.50  5082.8 1261.86  5088.3 1263.20
  5105.7 1270.83  5128.5 1276.84  5202.6 1290.91  5231.7 1293.37  5297.8 1295.14
#Mann=5,-1,0
  4632.9   0.035       0  4816.5    0.07       0  4867.9    0.12       0
  4990.9    0.05       0  4994.9    0.12       0
Bank Sta=4990.9,4994.9
Exp/Cntr=0.3,0.1

Type RM Length L Ch R = 1,6814,832,832,832
BEGIN DESCRIPTION:
BEAR CREEK_DS 12.0
END DESCRIPTION:
XS GIS Cut Line= 3
      2066786.50     13875760.60      2066825.00     13875425.00
      2066824.30     13875059.30
#Sta/Elev= 30
  4662.2 1292.01  4708.1 1290.87  4747.0 1286.85  4788.6 1284.44  4828.9 1278.50
  4839.0 1274.70  4859.1 1263.70  4866.3 1258.03  4871.3 1257.42  4889.3 1247.52
  4909.4 1238.61  4919.5 1235.59  4949.9 1237.23  4960.4 1237.49  4977.9 1232.22
  4978.1 1231.72  4981.9 1232.22  4989.9 1234.46  4997.5 1235.25  5010.0 1235.91
  5020.0 1235.29  5030.0 1236.50  5050.0 1242.27  5080.0 1247.45  5090.0 1250.44
  5150.0 1263.58  5200.0 1272.50  5240.0 1277.46  5295.6 1281.08  5365.7 1283.53
#Mann=6,-1,0
  4662.2   0.035       0  4747.0    0.07       0  4949.9    0.12       0
  4977.9    0.05       0  4981.9    0.12       0  5295.6    0.07       0
Bank Sta=4977.9,4981.9
Exp/Cntr=0.3,0.1

Type RM Length L Ch R = 1,5982,671,671,671
BEGIN DESCRIPTION:
BEAR CREEK_DS 11.0
END DESCRIPTION:
XS GIS Cut Line= 3
      2067524.51     13875484.33      2067495.35     13875204.65
      2067404.05     13874801.25
#Sta/Elev= 30
  4718.8 1269.67  4762.8 1268.31  4808.6 1265.30  4838.8 1258.99  4861.3 1256.41
  4919.2 1247.46  4949.4 1237.33  4954.8 1232.32  4959.8 1231.36  4969.5 1227.45
  4995.3 1220.73  4995.6 1220.23  4999.3 1220.73  5030.4 1223.71  5040.6 1224.00
  5050.9 1222.85  5061.9 1224.00  5073.0 1224.29  5116.2 1229.65  5132.9 1234.12
  5153.4 1240.83  5159.4 1243.67  5194.4 1251.67  5214.9 1257.73  5235.5 1261.70
  5256.0 1267.83  5293.9 1274.19  5337.1 1279.49  5385.4 1282.31  5413.6 1282.76
#Mann=4,-1,0
  4718.8    0.07       0  4995.3    0.05       0  4999.3    0.07       0
  5061.9    0.12       0
Bank Sta=4995.3,4999.3
Exp/Cntr=0.3,0.1

Type RM Length L Ch R = 1,5311,313,313,313
BEGIN DESCRIPTION:
BEAR CREEK_DS 10.0
END DESCRIPTION:
XS GIS Cut Line= 2
      2067887.63     13875694.04      2068160.21     13875275.11
#Sta/Elev= 30
  4742.4 1266.94  4744.6 1266.94  4762.1 1261.05  4768.1 1260.04  4783.2 1255.06
  4804.3 1249.58  4834.6 1234.99  4840.5 1233.57  4855.7 1224.72  4870.8 1219.74
  4884.4 1217.50  4904.1 1217.26  4943.5 1216.33  4985.5 1215.04  5013.7 1212.61
  5013.9 1212.11  5017.7 1212.61  5027.7 1214.49  5036.8 1217.69  5051.4 1223.88
  5057.9 1227.62  5094.2 1244.67  5115.3 1250.31  5130.4 1255.60  5151.5 1260.37
  5166.6 1266.26  5172.6 1267.10  5181.8 1270.00  5202.9 1273.60  5242.2 1277.54
#Mann=5,-1,0
  4742.4   0.035       0  4904.1    0.07       0  4943.5    0.12       0
  5013.7    0.05       0  5017.7    0.12       0
Bank Sta=5013.7,5017.7
Exp/Cntr=0.3,0.1

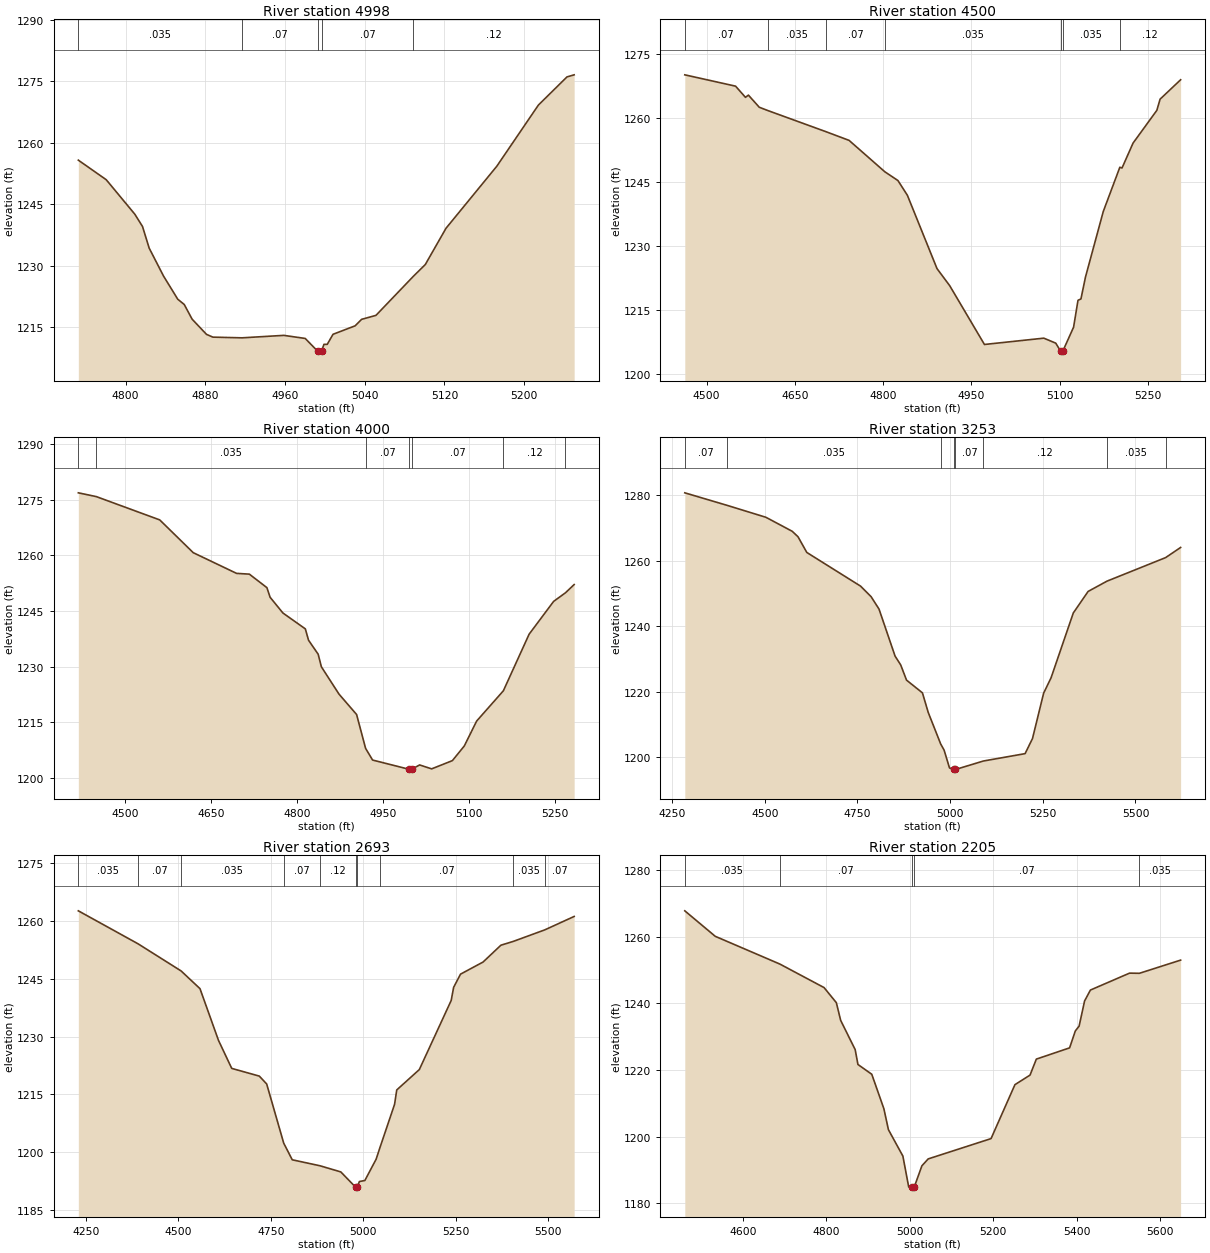
Type RM Length L Ch R = 1,4998,498,498,498
BEGIN DESCRIPTION:
BEAR CREEK_DS 9.0
END DESCRIPTION:
XS GIS Cut Line= 3
      2068125.00     13875825.00      2068281.09     13875633.05
      2068475.03     13875474.98
#Sta/Elev= 30
  4752.6 1255.73  4780.6 1250.96  4809.3 1242.55  4817.0 1239.56  4823.7 1234.28
  4838.1 1227.47  4852.4 1221.81  4858.9 1220.53  4866.8 1216.95  4881.2 1213.25
  4887.6 1212.57  4916.9 1212.40  4958.8 1213.00  4980.3 1212.25  4992.7 1209.17
  4992.9 1208.67  4996.7 1209.17  4999.1 1210.81  5002.4 1210.81  5008.2 1213.26
  5030.4 1215.33  5036.9 1216.91  5051.3 1217.88  5088.9 1227.42  5100.8 1230.27
  5121.6 1239.12  5172.6 1254.26  5214.3 1269.16  5243.0 1276.03  5250.2 1276.54
#Mann=5,-1,0
  4752.6   0.035       0  4916.9    0.07       0  4992.7    0.05       0
  4996.7    0.07       0  5088.9    0.12       0
Bank Sta=4992.7,4996.7
Exp/Cntr=0.3,0.1

Type RM Length L Ch R = 1,4500,500,500,500
BEGIN DESCRIPTION:
BEAR CREEK_DS 8.0
END DESCRIPTION:
XS GIS Cut Line= 3
      2067939.32     13876082.27      2068472.53     13876019.43
      2068774.99     13875975.00
#Sta/Elev= 30
  4463.1 1270.19  4549.4 1267.53  4566.2 1264.91  4571.2 1265.43  4589.6 1262.59
  4603.8 1261.83  4703.4 1256.83  4742.3 1254.81  4803.0 1247.45  4825.3 1245.39
  4841.4 1241.92  4891.7 1224.73  4913.3 1220.72  4972.3 1206.93  5073.2 1208.41
  5093.5 1207.24  5101.6 1205.40  5101.8 1204.90  5105.6 1205.40  5123.8 1210.98
  5131.3 1217.30  5136.3 1217.60  5144.0 1222.74  5174.3 1238.15  5202.4 1248.50
  5206.1 1248.33  5224.9 1254.18  5265.3 1261.86  5270.8 1264.48  5305.7 1269.03
#Mann=7,-1,0
  4463.1    0.07       0  4603.8   0.035       0  4703.4    0.07       0
  4803.0   0.035       0  5101.6   0.035       0  5105.6   0.035       0
  5202.4    0.12       0
Bank Sta=5101.6,5105.6
Exp/Cntr=0.3,0.1

Type RM Length L Ch R = 1,4000,747,747,747
BEGIN DESCRIPTION:
BEAR CREEK_DS 7.0
END DESCRIPTION:
XS GIS Cut Line= 3
      2068331.70     13876912.13      2068591.48     13876392.11
      2068775.02     13876174.98
#Sta/Elev= 30
  4418.7 1276.90  4450.1 1275.88  4560.8 1269.60  4619.3 1260.76  4694.9 1255.18
  4717.3 1254.97  4747.9 1251.33  4753.5 1248.73  4775.9 1244.49  4815.0 1240.21
  4820.6 1237.15  4837.4 1233.38  4843.0 1229.99  4873.8 1222.61  4904.5 1217.12
  4920.2 1207.99  4932.4 1204.84  4996.1 1202.35  4996.4 1201.85  5000.5 1202.35
  5014.5 1203.52  5035.5 1202.46  5071.7 1204.68  5092.5 1208.63  5114.1 1215.36
  5160.7 1223.51  5205.7 1238.78  5248.5 1247.63  5269.1 1249.94  5284.3 1252.16
#Mann=7,-1,0
  4418.7    0.07       0  4450.1   0.035       0  4920.2    0.07       0
  4996.1    0.05       0  5000.5    0.07       0  5160.7    0.12       0
  5269.1    0.07       0
Bank Sta=4996.1,5000.5
Exp/Cntr=0.3,0.1

Type RM Length L Ch R = 1,3253,560,560,560
BEGIN DESCRIPTION:
BEAR CREEK_DS 6.0
END DESCRIPTION:
XS GIS Cut Line= 3
      2068804.93     13877383.41      2069168.83     13876767.24
      2069178.83     13876145.52
#Sta/Elev= 30
  4284.4 1280.81  4399.4 1276.95  4503.2 1273.33  4574.2 1269.04  4589.8 1267.37
  4613.5 1262.57  4758.7 1252.26  4786.9 1249.05  4808.3 1245.25  4851.6 1230.87
  4866.8 1228.17  4882.5 1223.52  4925.4 1219.63  4941.0 1213.65  4974.5 1204.03
  4983.9 1202.10  4998.4 1196.66  5010.0 1196.19  5010.3 1195.69  5014.5 1196.19
  5089.7 1198.78  5202.3 1201.04  5222.3 1205.67  5252.3 1219.54  5272.3 1224.22
  5332.3 1244.06  5372.3 1250.65  5423.1 1253.79  5581.4 1261.00  5621.8 1264.10
#Mann=8,-1,0
  4284.4    0.07       0  4399.4   0.035       0  4974.5    0.07       0
  5010.0    0.05       0  5014.5    0.07       0  5089.7    0.12       0
  5423.1   0.035       0  5581.4    0.07       0
Bank Sta=5010,5014.5
Exp/Cntr=0.3,0.1

Type RM Length L Ch R = 1,2693,488,488,488
BEGIN DESCRIPTION:
BEAR CREEK_DS 5.0
END DESCRIPTION:
XS GIS Cut Line= 3
      2069615.13     13877443.33      2069661.28     13876674.21
      2069465.25     13876139.09
#Sta/Elev= 30
  4229.5 1262.65  4391.2 1254.07  4507.4 1247.03  4558.4 1242.43  4608.5 1228.98
  4644.2 1221.72  4718.7 1219.72  4738.7 1217.67  4784.7 1202.31  4807.8 1197.98
  4883.1 1196.42  4939.1 1194.83  4979.1 1190.86  4979.4 1190.36  4983.8 1190.86
  4989.2 1192.33  5004.1 1192.60  5034.6 1198.14  5044.6 1201.07  5084.4 1212.38
  5090.3 1216.12  5151.3 1221.41  5237.5 1239.37  5244.1 1242.78  5262.7 1246.20
  5323.7 1249.35  5371.9 1253.72  5405.1 1254.70  5490.7 1257.71  5569.9 1261.19
#Mann=10,-1,0
  4229.5   0.035       0  4391.2    0.07       0  4507.4   0.035       0
  4784.7    0.07       0  4883.1    0.12       0  4979.1    0.05       0
  4983.8    0.12       0  5044.6    0.07       0  5405.1   0.035       0
  5490.7    0.07       0
Bank Sta=4979.1,4983.8
Exp/Cntr=0.3,0.1

Type RM Length L Ch R = 1,2205,476,476,476
BEGIN DESCRIPTION:
BEAR CREEK_DS 4.0
END DESCRIPTION:
XS GIS Cut Line= 3
      2070236.32     13877125.44      2070095.43     13876605.28
      2069739.17     13876062.69
#Sta/Elev= 30
  4461.1 1267.81  4534.1 1260.15  4689.0 1251.81  4794.8 1244.75  4824.2 1240.22
  4834.6 1234.89  4869.3 1226.13  4876.0 1221.64  4909.1 1218.71  4938.1 1208.36
  4949.0 1202.06  4983.6 1194.14  4997.6 1184.85  5005.7 1184.70  5006.1 1184.20
  5010.5 1184.70  5029.2 1191.21  5044.3 1193.28  5194.9 1199.38  5252.1 1215.58
  5288.3 1218.46  5303.4 1223.26  5383.1 1226.64  5396.8 1231.72  5405.9 1233.18
  5419.0 1240.73  5433.0 1244.01  5526.7 1249.09  5550.3 1249.04  5649.1 1253.00
#Mann=5,-1,0
  4461.1   0.035       0  4689.0    0.07       0  5005.7    0.05       0
  5010.5    0.07       0  5550.3   0.035       0
Bank Sta=5005.7,5010.5
Exp/Cntr=0.3,0.1

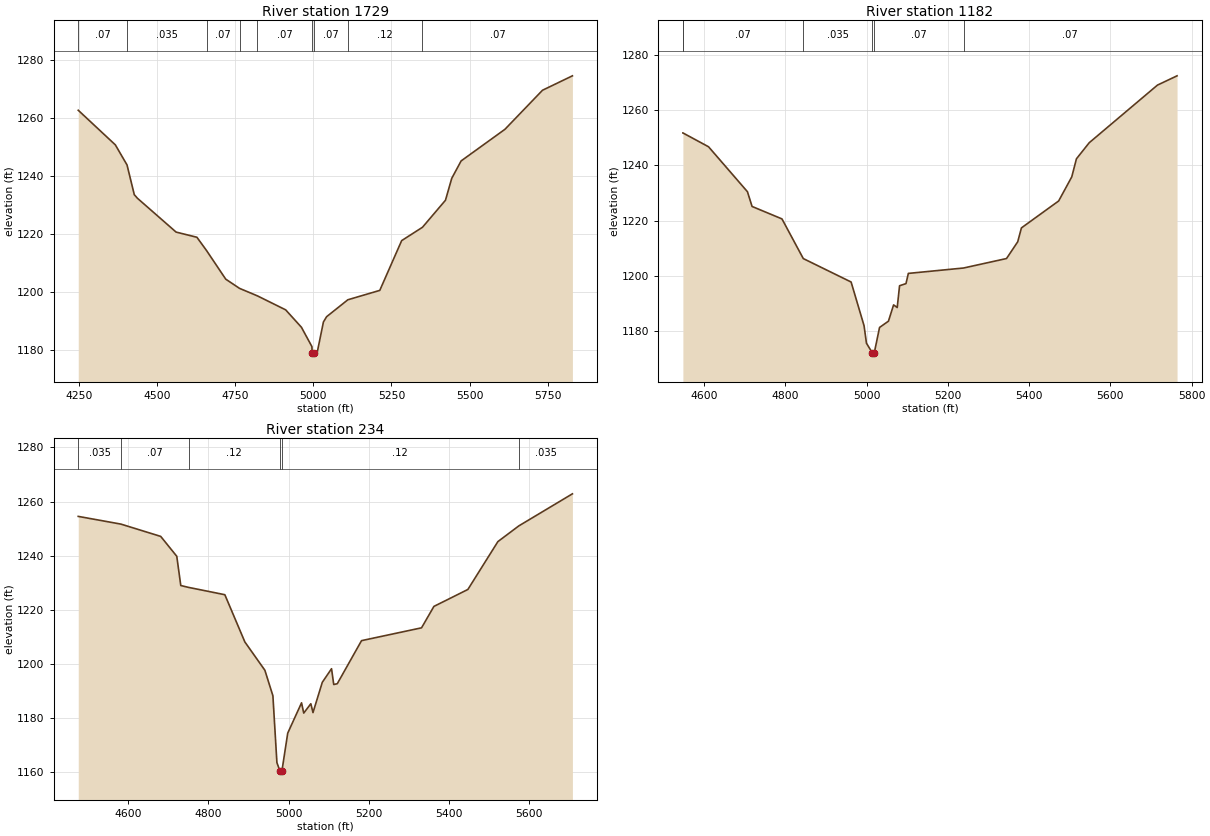
Type RM Length L Ch R = 1,1729,547,547,547
BEGIN DESCRIPTION:
BEAR CREEK_DS 3.0
END DESCRIPTION:
XS GIS Cut Line= 3
      2070522.82     13877022.71      2070419.14     13876277.29
      2070369.50     13875449.38
#Sta/Elev= 30
  4247.4 1262.65  4366.2 1250.73  4403.6 1243.81  4426.8 1233.58  4436.9 1232.34
  4560.7 1220.69  4627.3 1218.91  4658.6 1214.26  4719.6 1204.48  4763.7 1201.31
  4820.9 1198.73  4911.4 1193.91  4961.9 1187.91  4995.5 1181.24  4996.1 1179.16
  4996.5 1178.66  5001.2 1179.16  5012.3 1179.21  5032.3 1189.73  5042.4 1191.54
  5110.5 1197.38  5212.7 1200.61  5282.8 1217.76  5349.4 1222.35  5423.0 1231.66
  5443.1 1239.21  5473.1 1245.20  5613.4 1256.09  5733.6 1269.54  5829.4 1274.51
#Mann=9,-1,0
  4247.4    0.07       0  4403.6   0.035       0  4658.6    0.07       0
  4763.7   0.035       0  4820.9    0.07       0  4996.1    0.05       0
  5001.2    0.07       0  5110.5    0.12       0  5349.4    0.07       0
Bank Sta=4996.1,5001.2
Exp/Cntr=0.3,0.1

Type RM Length L Ch R = 1,1182,948,948,948
BEGIN DESCRIPTION:
BEAR CREEK_DS 2.0
END DESCRIPTION:
XS GIS Cut Line= 4
      2071006.34     13876474.41      2070852.51     13876048.97
      2070532.30     13875865.53      2070412.94     13875488.92
#Sta/Elev= 30
  4547.6 1251.74  4547.7 1251.74  4610.8 1246.73  4706.5 1230.48  4717.9 1225.15
  4791.5 1220.65  4844.0 1206.30  4961.7 1197.83  4993.6 1182.01  4999.5 1175.70
  5013.7 1172.25  5014.0 1171.75  5018.8 1172.25  5031.7 1181.39  5053.6 1183.67
  5066.3 1189.56  5075.2 1188.61  5081.0 1196.48  5096.8 1197.25  5102.6 1200.94
  5238.5 1202.89  5344.3 1206.32  5371.9 1212.39  5381.0 1217.40  5472.6 1227.13
  5504.9 1235.85  5516.4 1242.38  5547.9 1248.20  5715.8 1269.03  5764.1 1272.39
#Mann=6,-1,0
  4547.6   0.035       0  4547.7    0.07       0  4844.0   0.035       0
  5013.7   0.035       0  5018.8    0.07       0  5238.5    0.07       0
Bank Sta=5013.7,5018.8
Exp/Cntr=0.3,0.1

Type RM Length L Ch R = 1,234,0,0,0
BEGIN DESCRIPTION:
BEAR CREEK_DS 1.0
END DESCRIPTION:
XS GIS Cut Line= 3
      2071123.24     13876500.95      2071124.99     13875975.85
      2070833.85     13875329.71
#Sta/Elev= 30
  4474.9 1254.50  4581.5 1251.64  4680.8 1247.09  4720.9 1239.73  4730.9 1228.91
  4750.6 1228.21  4840.9 1225.51  4890.9 1208.02  4940.9 1197.54  4960.9 1188.10
  4970.9 1163.37  4978.3 1160.34  4978.7 1159.84  4983.5 1160.34  4997.9 1174.27
  5032.4 1185.49  5037.9 1181.70  5055.6 1185.15  5061.0 1181.88  5084.2 1193.08
  5107.3 1198.12  5112.8 1192.27  5121.6 1192.56  5182.2 1208.51  5332.0 1213.25
  5362.9 1221.18  5447.7 1227.45  5522.6 1245.16  5574.8 1250.97  5708.7 1262.85
#Mann=6,-1,0
  4474.9   0.035       0  4581.5    0.07       0  4750.6    0.12       0
  4978.3    0.05       0  4983.5    0.12       0  5574.8   0.035       0
Bank Sta=4978.3,4983.5
Exp/Cntr=0.3,0.1

Chan Stop Cuts=-1