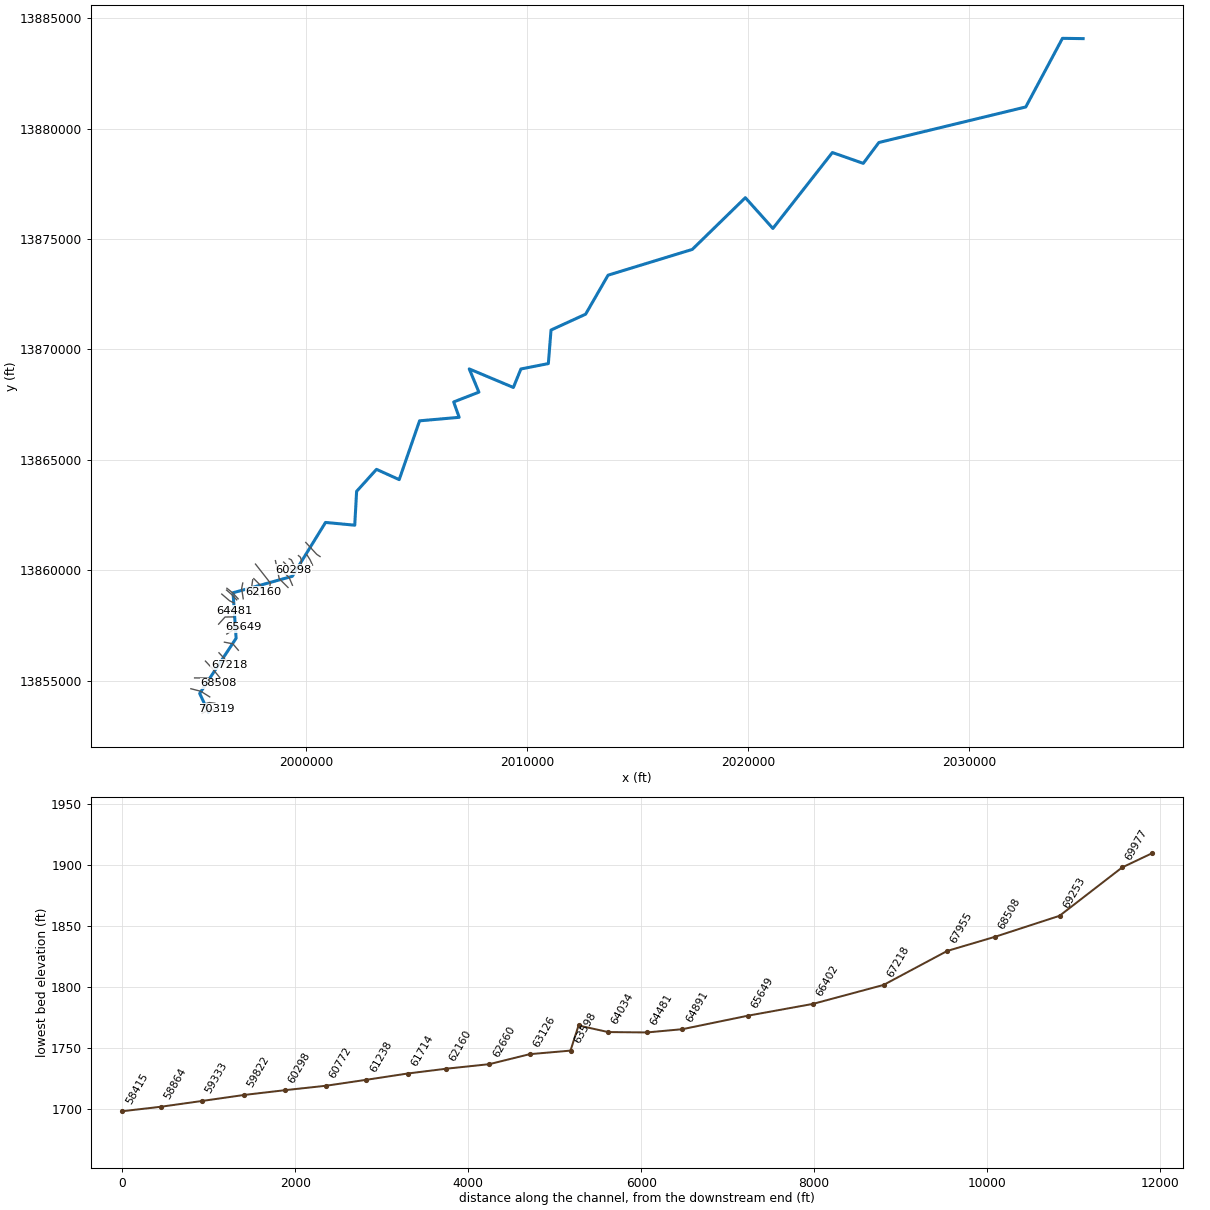
--- BIG JOSHUA CREEK.prj (project) ---

Proj Title=BIG JOSHUA CREEK Base Level Engineering
Current Plan=p01
Default Exp/Contr=0.3,0.1
English Units
Geom File=g01
Flow File=f01
Plan File=p01
Y Axis Title=Elevation
X Axis Title(PF)=Main Channel Distance
X Axis Title(XS)=Station
BEGIN DESCRIPTION:
BIG JOSHUA CREEK
END DESCRIPTION:
DSS Export Rating Curves= 0
DSS Export Rating Curve Sorted= 0
DSS Export Volume Flow Curves= 0
DXF OffsetX= 0
DXF OffsetY= 0
DXF ScaleX= 1
DXF ScaleY= 10

--- BIG JOSHUA CREEK.p01 (plan) ---

Plan Title=Multiple Run
Short Identifier=Multiple
Geom File=g01
Flow File=f01
Subcritical Flow
K Sum by GR= 0
Std Step Tol= 0.01
Critical Tol= 0.01
Num of Std Step Trials= 20
Max Error Tol= 0.3
Flow Tol Ratio= 0.001
Split Flow NTrial= 30
Split Flow Tol= 0.02
Split Flow Ratio= 0.02
Log Output Level= 0
Friction Slope Method= 1
Unsteady Friction Slope Method= 2
Unsteady Bridges Friction Slope Method= 1
Parabolic Critical Depth
Global Vel Dist=  1 , 1 , 1
Global Log Level= 0
CheckData=True
Encroach Param= -1, 0, 0, 0
BEGIN DESCRIPTION:
Multiple Run
END DESCRIPTION:

--- BIG JOSHUA CREEK.f01 (steady flow) ---

Flow Title=Multiple
Program Version=4.10
Number of Profiles= 7
Profile Names=10-year,25-year,50-year,1pct_min,100-year,1pct_plu,500-year
River Rch & RM=BIG JOSHUA CREEK,Reach-1         ,70319
     301     468     616     394     787    1570    1267
River Rch & RM=BIG JOSHUA CREEK,Reach-1         ,69977
     663    1094    1495     993    1981    3953    3435
River Rch & RM=BIG JOSHUA CREEK,Reach-1         ,67218
    1011    1715    2387    1611    3215    6415    5768
River Rch & RM=BIG JOSHUA CREEK,Reach-1         ,65649
    1834    3222    4589    3164    6312   12595   11826
River Rch & RM=BIG JOSHUA CREEK,Reach-1         ,64481
    2060    3621    5159    3554    7091   14148   13267
River Rch & RM=BIG JOSHUA CREEK,Reach-1         ,59333
    3352    6002    8653    6021   12014   23971   22944
River Rch & RM=BIG JOSHUA CREEK,Reach-1         ,54329
    3452    6186    8924    6212   12394   24729   23684
River Rch & RM=BIG JOSHUA CREEK,Reach-1         ,52994
    3720    6670    9624    6697   13363   26662   25527
River Rch & RM=BIG JOSHUA CREEK,Reach-1         ,48796
    3942    7085   10239    7136   14238   28408   27278
River Rch & RM=BIG JOSHUA CREEK,Reach-1         ,47375
    4022    7225   10439    7272   14509   28950   27773
River Rch & RM=BIG JOSHUA CREEK,Reach-1         ,43722
    4122    7411   10713    7466   14898   29724   28544
River Rch & RM=BIG JOSHUA CREEK,Reach-1         ,43265
    4183    7513   10854    7558   15080   30089   28844
River Rch & RM=BIG JOSHUA CREEK,Reach-1         ,38321
    4827    8723   12652    8843   17643   35203   33997
River Rch & RM=BIG JOSHUA CREEK,Reach-1         ,37853
    5125    9274   13464    9417   18789   37488   36252
River Rch & RM=BIG JOSHUA CREEK,Reach-1         ,34138
    5407    9801   14243    9971   19894   39693   38454
River Rch & RM=BIG JOSHUA CREEK,Reach-1         ,31335
    5699   10343   15045   10540   21030   41960   40707
River Rch & RM=BIG JOSHUA CREEK,Reach-1         ,27034
    5986   10878   15838   11104   22156   44206   42954
River Rch & RM=BIG JOSHUA CREEK,Reach-1         ,25397
    6054   10992   15993   11204   22355   44604   43273
River Rch & RM=BIG JOSHUA CREEK,Reach-1         ,19917
    6297   11439   16650   11667   23278   46445   45076
River Rch & RM=BIG JOSHUA CREEK,Reach-1         ,17700
    6503   11833   17242   12095   24132   48149   46830
River Rch & RM=BIG JOSHUA CREEK,Reach-1         ,15567
    7014   12788   18658   13103   26143   52162   50845
River Rch & RM=BIG JOSHUA CREEK,Reach-1         ,11053
    7233   13191   19251   13519   26975   53822   52469
River Rch & RM=BIG JOSHUA CREEK,Reach-1         ,7242
    7458   13608   19866   13955   27844   55556   54185
River Rch & RM=BIG JOSHUA CREEK,Reach-1         ,4982
    7531   13731   20036   14066   28066   55999   54555
Boundary for River Rch & Prof#=BIG JOSHUA CREEK,Reach-1         , 1
Up Type= 0
Dn Type= 3
Dn Slope=0.008
Boundary for River Rch & Prof#=BIG JOSHUA CREEK,Reach-1         , 2
Up Type= 0
Dn Type= 3
Dn Slope=0.008
Boundary for River Rch & Prof#=BIG JOSHUA CREEK,Reach-1         , 3
Up Type= 0
Dn Type= 3
Dn Slope=0.008
Boundary for River Rch & Prof#=BIG JOSHUA CREEK,Reach-1         , 4
Up Type= 0
Dn Type= 3
Dn Slope=0.008
Boundary for River Rch & Prof#=BIG JOSHUA CREEK,Reach-1         , 5
Up Type= 0
Dn Type= 3
Dn Slope=0.008
Boundary for River Rch & Prof#=BIG JOSHUA CREEK,Reach-1         , 6
Up Type= 0
Dn Type= 3
Dn Slope=0.008
Boundary for River Rch & Prof#=BIG JOSHUA CREEK,Reach-1         , 7
Up Type= 0
Dn Type= 3
Dn Slope=0.008
DSS Import GetInterval= 0
DSS Import GetPeak= 0
DSS Import FillOption= 0

--- BIG JOSHUA CREEK.g01 (geometry) ---

Geom Title=Existing Conditions
Program Version=4.10

River Reach=BIG JOSHUA CREEK,Reach-1
Reach XY= 30
        1995575.       13853575.        1995175.       13854425.
        1996825.       13856925.      1996685.65       13858985.
      1999369.83     13859730.41      2000872.69     13862169.18
      2002195.55     13862044.44      2002280.45     13863577.47
      2003180.44     13864572.83      2004208.37     13864108.29
      2005130.02     13866769.77      2006923.54     13866928.53
        2006675.       13867625.      2007817.24     13868068.83
      2007380.59     13869119.39      2009377.58     13868280.71
      2009718.65     13869117.57      2010961.37     13869361.79
      2011083.14     13870881.06      2012648.84     13871597.85
      2013664.95     13873363.88      2017477.67     13874530.42
      2019880.73      13876873.1      2021127.55     13875480.72
      2023821.58     13878917.21      2025219.02     13878427.17
      2025926.46     13879371.46      2032577.45     13880980.47
      2034238.69       13884088.        2035175.       13884075.

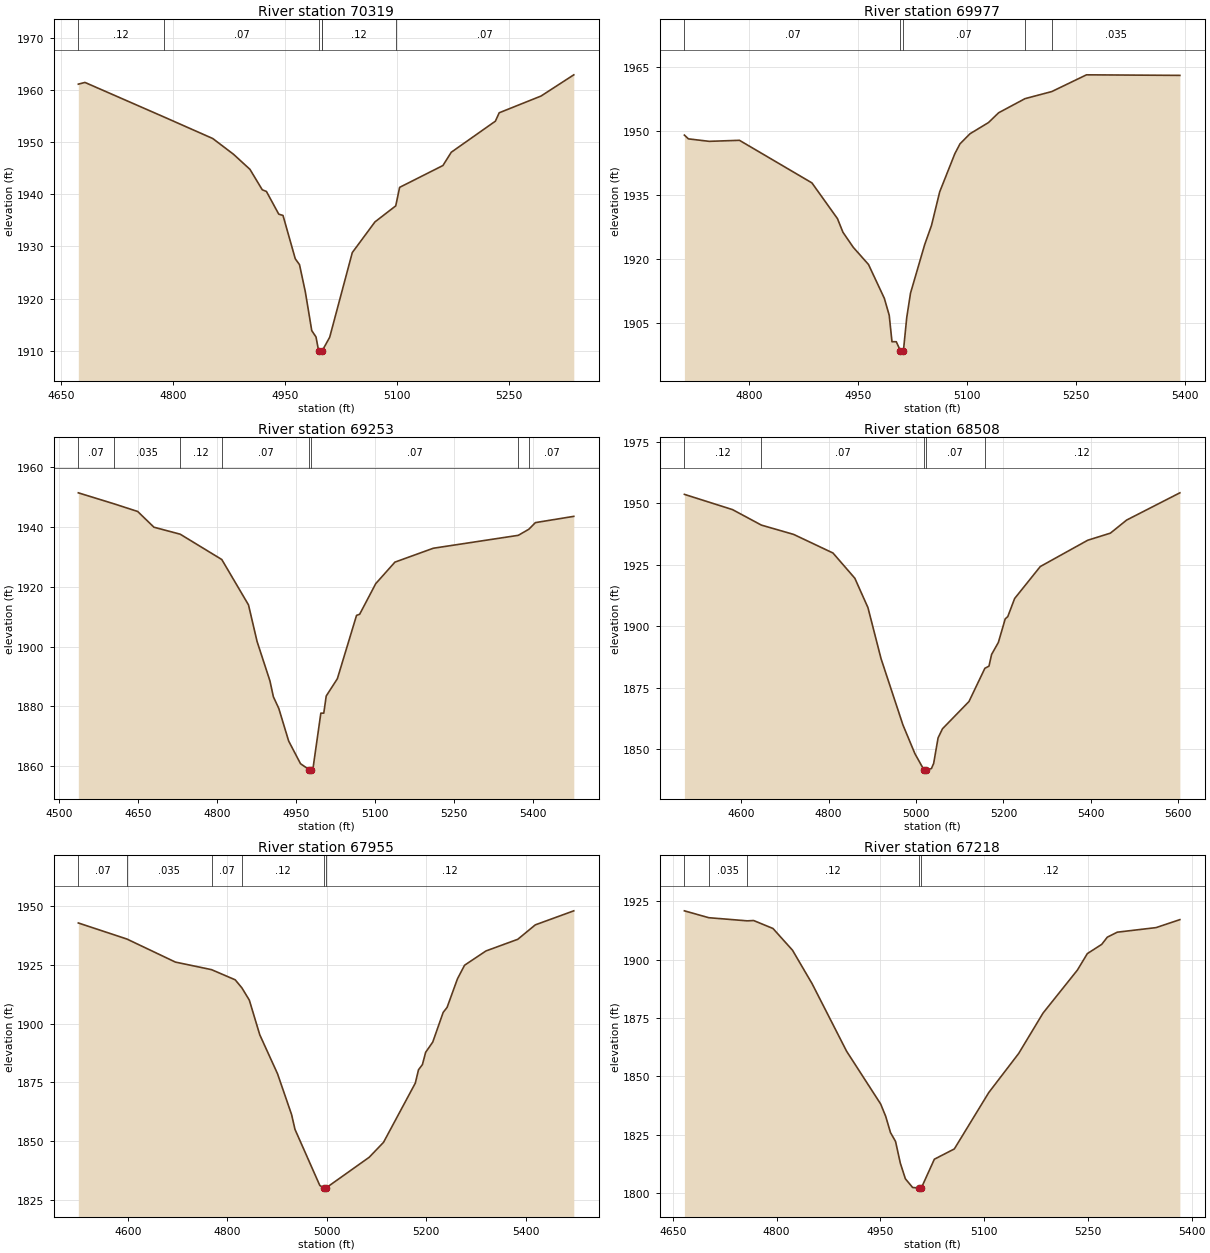
Type RM Length L Ch R = 1 ,70319   ,342,342,342
BEGIN DESCRIPTION:
BIG JOSHUA CREEK 131.0
END DESCRIPTION:
XS GIS Cut Line= 3
      1995285.26     13853524.28        1995575.       13853675.
       1995908.4     13853724.83
#Sta/Elev= 30
  4673.4 1961.14  4682.3 1961.47  4788.7 1954.81  4853.5 1950.71  4881.2  1947.7
  4903.3  1944.8  4919.8 1940.88  4925.4 1940.55  4941.9  1936.2  4947.6 1935.95
    4964 1927.65  4969.7 1926.51  4977.5 1921.29  4986.1 1913.86  4991.8 1912.64
  4995.2 1910.04  4995.4 1909.54  4999.2 1910.04  5000.3 1910.04  5010.1 1912.58
  5040.4 1928.83  5070.8 1934.72  5098.6 1937.79  5103.8 1941.34  5161.8 1945.53
    5173 1948.08  5232.1 1954.04  5237.2 1955.65  5293.2 1958.86  5337.1 1962.93
#Mann= 6 ,-1 , 0
  4673.4     .12       0  4788.7     .07       0  4995.2     .05       0
  4999.2     .07       0  5000.3     .12       0  5098.6     .07       0
Bank Sta=4995.2,4999.2
XS Rating Curve= 0 ,0
Exp/Cntr=0.3,0.1

Type RM Length L Ch R = 1 ,69977   ,724,724,724
BEGIN DESCRIPTION:
BIG JOSHUA CREEK 130.0
END DESCRIPTION:
XS GIS Cut Line= 4
      1995284.21     13853758.33        1995475.       13853975.
      1995615.83     13854014.69      1995860.17     13853984.66
#Sta/Elev= 30
  4711.3  1949.1  4716.8 1948.22  4745.3 1947.64    4787 1947.88  4886.6 1937.91
  4921.7 1929.55  4929.3 1926.34  4943.5 1922.81  4964.4  1918.8  4986.2 1910.86
  4992.9  1906.9  4996.7  1900.7  5002.6  1900.7  5008.4 1898.53  5008.6 1898.03
  5012.4 1898.53    5017 1906.39  5022.2  1912.1  5041.6 1923.42    5051 1927.93
  5062.3 1935.81  5083.1 1944.74  5090.2 1947.05  5103.9 1949.41  5129.4 1952.04
  5143.3 1954.33  5179.6 1957.64  5216.4  1959.3  5264.1 1963.22  5392.5 1963.09
#Mann= 5 ,-1 , 0
  4711.3     .07       0  5008.4     .05       0  5012.4     .07       0
  5179.6     .12       0  5216.4    .035       0
Bank Sta=5008.4,5012.4
XS Rating Curve= 0 ,0
Exp/Cntr=0.3,0.1

Type RM Length L Ch R = 1 ,69253   ,745,745,745
BEGIN DESCRIPTION:
BIG JOSHUA CREEK 129.0
END DESCRIPTION:
XS GIS Cut Line= 3
      1994775.59     13854640.03        1995225.       13854525.
       1995629.8     13854269.86
#Sta/Elev= 30
  4536.1 1951.37    4604  1947.7    4649 1945.14    4680 1939.88  4729.9 1937.55
    4809 1929.09  4859.8 1913.93  4876.1 1901.71  4900.6 1888.53  4907.1 1883.25
  4917.4 1879.35  4936.2 1868.45  4958.7 1860.89    4975  1858.9  4975.3  1858.4
    4979  1858.9  4982.2 1858.96  4997.4 1877.77    5003 1877.77  5007.6 1883.49
  5028.8 1889.27  5065.3 1910.43  5071.2  1910.8  5101.8 1921.03  5138.3 1928.22
  5211.3 1932.86  5372.9 1937.17    5393  1939.2  5405.5 1941.42  5478.5 1943.51
#Mann= 8 ,-1 , 0
  4536.1     .07       0    4604    .035       0  4729.9     .12       0
    4809     .07       0    4975     .05       0    4979     .07       0
  5372.9    .035       0    5393     .07       0
Bank Sta=4975,4979
XS Rating Curve= 0 ,0
Exp/Cntr=0.3,0.1

Type RM Length L Ch R = 1 ,68508   ,553,553,553
BEGIN DESCRIPTION:
BIG JOSHUA CREEK 128.0
END DESCRIPTION:
XS GIS Cut Line= 4
      1994944.92     13855129.67        1995475.       13855125.
      1995636.75      13855101.7      1996017.32     13854879.92
#Sta/Elev= 30
  4469.9 1953.55    4580 1947.36  4646.1 1941.07    4720 1937.29    4810 1929.74
    4860  1919.5    4890 1907.58    4920 1886.85    4970 1860.01  4997.5  1848.3
  5018.2 1841.72  5018.5 1841.22  5022.2 1841.72  5035.2 1842.24  5040.4 1844.35
  5050.5 1854.71  5060.6 1858.41  5121.2 1869.46  5157.6 1882.95    5167 1883.84
    5173 1888.58  5188.5 1893.46  5204.2 1903.02    5210 1903.93  5225.7 1911.27
  5284.4 1924.25  5392.9 1934.92  5444.9 1937.81  5482.1 1943.12  5603.9 1954.17
#Mann= 5 ,-1 , 0
  4469.9     .12       0  4646.1     .07       0  5018.2     .05       0
  5022.2     .07       0  5157.6     .12       0
Bank Sta=5018.2,5022.2
XS Rating Curve= 0 ,0
Exp/Cntr=0.3,0.1

Type RM Length L Ch R = 1 ,67955   ,737,737,737
BEGIN DESCRIPTION:
BIG JOSHUA CREEK 127.0
END DESCRIPTION:
XS GIS Cut Line= 3
      1995435.46     13855891.22        1995775.       13855525.
      1996089.05     13855140.18
#Sta/Elev= 30
  4500.6 1942.76  4598.3 1935.93  4695.8 1926.13  4768.4 1922.92    4816  1918.6
  4829.4 1915.19  4844.4 1909.97  4865.4 1895.23  4901.1 1878.67  4929.4 1861.29
  4936.2 1855.03  4986.1 1831.18  4994.6 1830.13  4994.8 1829.63  4998.6 1830.13
  5085.4 1843.17  5114.2 1849.52  5178.1 1874.69  5184.5 1880.35  5192.4 1882.58
  5198.9 1887.79  5213.2 1892.16  5234.1 1904.74    5242 1906.89  5262.8    1919
  5277.1 1924.79  5320.2 1930.87  5384.1 1935.82  5419.3 1941.95  5496.7 1947.92
#Mann= 6 ,-1 , 0
  4500.6     .07       0  4598.3    .035       0  4768.4     .07       0
  4829.4     .12       0  4994.6     .05       0  4998.6     .12       0
Bank Sta=4994.6,4998.6
XS Rating Curve= 0 ,0
Exp/Cntr=0.3,0.1

Type RM Length L Ch R = 1 ,67218   ,816,816,816
BEGIN DESCRIPTION:
BIG JOSHUA CREEK 126.0
END DESCRIPTION:
XS GIS Cut Line= 3
      1996047.32     13856268.56        1996275.       13856025.
       1996512.7     13855724.69
#Sta/Elev= 30
  4666.6 1920.85  4701.8 1917.91  4757.5 1916.56  4766.7  1916.7  4794.7 1913.29
  4822.9    1904  4851.3 1889.64  4901.1 1860.78  4950.4 1838.17  4957.7 1832.87
  4964.6 1825.95  4971.9 1822.16  4978.8 1812.88  4986.1 1806.18  4996.6 1802.45
  5005.2 1802.25  5005.5 1801.75  5009.2 1802.25    5028 1814.55  5056.9 1818.95
  5106.6 1843.04  5149.9 1859.79  5185.1 1877.07  5234.8 1895.48  5249.2 1902.54
    5270  1906.5  5278.1 1909.58  5292.5 1911.71  5348.6 1913.67    5383 1917.08
#Mann= 5 ,-1 , 0
  4666.6     .07       0  4701.8    .035       0  4757.5     .12       0
  5005.2     .05       0  5009.2     .12       0
Bank Sta=5005.2,5009.2
XS Rating Curve= 0 ,0
Exp/Cntr=0.3,0.1

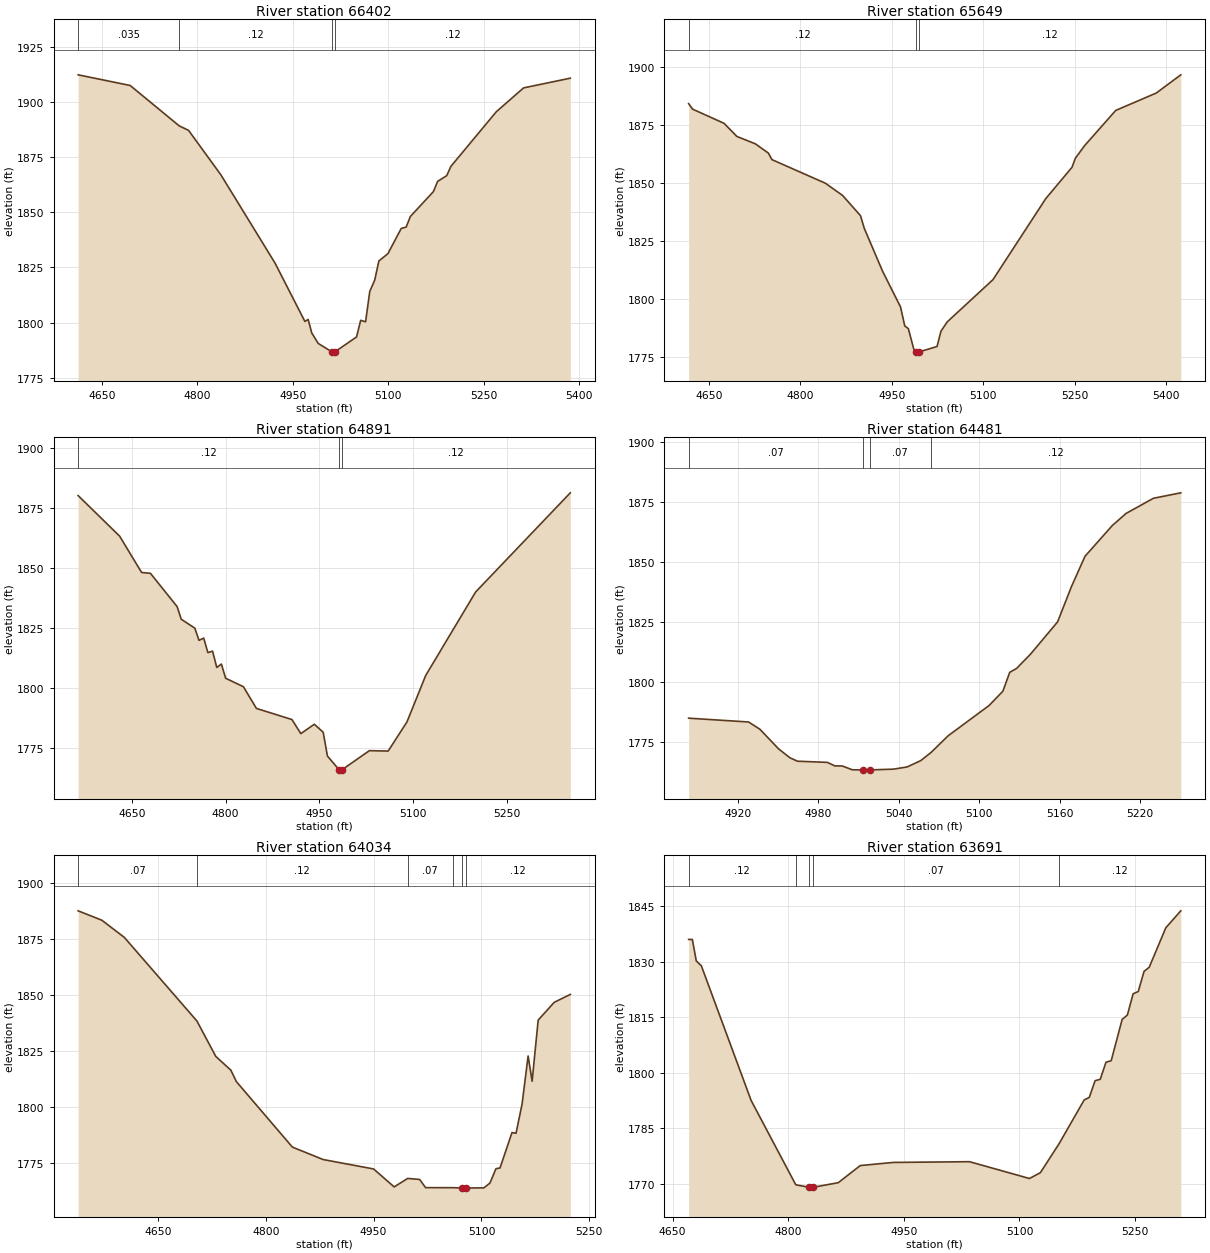
Type RM Length L Ch R = 1 ,66402   ,753,753,753
BEGIN DESCRIPTION:
BIG JOSHUA CREEK 125.0
END DESCRIPTION:
XS GIS Cut Line= 3
      1996294.77     13856748.14        1996675.       13856675.
      1996925.69     13856381.88
#Sta/Elev= 30
  4612.8 1912.22  4694.5  1907.4  4771.5 1889.11  4786.2 1887.08  4837.1 1866.89
  4922.1 1826.94  4968.9 1800.57    4974 1801.47  4979.6  1795.4  4989.8 1790.62
  5011.7 1786.73    5012 1786.23  5015.7 1786.73    5050 1793.56  5056.5 1801.08
  5064.2 1800.42  5070.8 1814.18  5078.5 1819.25  5085.1 1827.95  5099.3 1831.27
  5120.2 1842.68  5127.9 1843.28  5134.5 1848.08  5170.7 1859.35  5177.3 1863.97
  5191.6 1866.57  5198.1 1870.75  5269.5 1895.51  5312.3  1906.3  5385.7  1910.7
#Mann= 4 ,-1 , 0
  4612.8    .035       0  4771.5     .12       0  5011.7     .05       0
  5015.7     .12       0
Bank Sta=5011.7,5015.7
XS Rating Curve= 0 ,0
Exp/Cntr=0.3,0.1

Type RM Length L Ch R = 1 ,65649   ,758,758,758
BEGIN DESCRIPTION:
BIG JOSHUA CREEK 124.0
END DESCRIPTION:
XS GIS Cut Line= 3
      1996402.23      13857117.9        1996725.       13857325.
      1997139.24     13857417.76
#Sta/Elev= 30
  4616.5 1884.18  4623.1  1881.8  4674.6  1875.7  4695.7 1870.04  4726.1 1866.84
  4747.3 1862.88  4753.2 1860.04  4841.1 1849.84  4869.3 1844.56  4898.6 1835.88
  4904.9 1830.35  4934.9 1811.88  4964.4 1796.46  4971.3 1788.29  4977.2 1787.09
  4986.5  1777.9  4990.4 1777.05  4990.7 1776.55  4994.4 1777.05  5024.3 1779.41
  5030.7 1785.98    5041 1790.02  5116.1 1808.24  5202.9 1843.25  5245.9 1856.73
  5251.4 1860.63  5266.4 1866.02  5317.7 1881.27  5384.3 1888.77  5424.5 1896.62
#Mann= 3 ,-1 , 0
  4616.5     .12       0  4990.4     .05       0  4994.4     .12       0
Bank Sta=4990.4,4994.4
XS Rating Curve= 0 ,0
Exp/Cntr=0.3,0.1

Type RM Length L Ch R = 1 ,64891   ,410,410,410
BEGIN DESCRIPTION:
BIG JOSHUA CREEK 123.0
END DESCRIPTION:
XS GIS Cut Line= 3
      1996032.22     13857564.37      1996324.96     13857887.48
      1996676.42     13857892.41
#Sta/Elev= 30
    4564 1880.33  4630.4 1863.42  4665.5 1848.29  4679.7 1847.92  4722.3 1834.09
    4729 1828.79  4750.7 1825.07  4757.4 1819.99  4764.9 1820.94  4771.6 1814.88
  4779.1  1815.5  4785.8 1808.69  4793.2 1810.12    4800  1804.2  4828.4 1800.68
  4849.3 1791.62  4906.1 1786.99  4920.3 1781.12  4941.9 1785.03  4956.1  1781.7
  4962.9 1771.77  4981.8 1765.99  4982.1 1765.49  4985.8 1765.99    5030 1774.02
    5060 1773.84  5090.1 1785.98  5120.1 1805.35  5200.1 1840.18  5351.5 1881.48
#Mann= 3 ,-1 , 0
    4564     .12       0  4981.8     .05       0  4985.8     .12       0
Bank Sta=4981.8,4985.8
XS Rating Curve= 0 ,0
Exp/Cntr=0.3,0.1

Type RM Length L Ch R = 1 ,64481   ,447,447,447
BEGIN DESCRIPTION:
BIG JOSHUA CREEK 122.0
END DESCRIPTION:
XS GIS Cut Line= 3
      1996374.99       13858275.        1996475.       13858225.
      1996725.03     13858174.99
#Sta/Elev= 30
  4883.5 1784.87  4928.2 1783.28  4936.6 1780.26  4950.6 1772.06    4959 1768.38
  4964.6 1766.96  4986.9 1766.47  4992.5 1764.99  4997.9 1764.99  5005.5 1763.39
  5013.1 1763.33  5013.5 1762.83  5018.3 1763.33  5036.1 1763.65  5046.3 1764.56
  5056.5 1767.21  5064.2 1770.62  5076.9 1777.54  5107.5 1790.18  5117.7 1796.11
  5122.8 1803.95  5127.9 1805.57  5138.1 1811.39  5158.5 1824.97  5168.7  1839.5
  5178.9 1852.25  5199.3 1865.08  5209.5 1870.08  5229.9 1876.39  5250.3 1878.66
#Mann= 4 ,-1 , 0
  4883.5     .07       0  5013.1     .05       0  5018.3     .07       0
  5064.2     .12       0
Bank Sta=5013.1,5018.3
XS Rating Curve= 0 ,0
Exp/Cntr=0.3,0.1

Type RM Length L Ch R = 1 ,64034   ,343,343,343
BEGIN DESCRIPTION:
BIG JOSHUA CREEK 121.0
END DESCRIPTION:
XS GIS Cut Line= 3
      1996174.99       13858925.        1996525.       13858625.
      1996725.01       13858525.
#Sta/Elev= 30
    4539  1887.5  4571.9 1883.31  4603.2 1875.64  4704.1 1838.32  4730.5 1822.43
  4751.4 1816.31  4759.1 1811.18    4837 1781.92  4879.8 1776.36    4950 1772.15
  4978.6 1764.13  4997.4 1767.92    5014 1767.47  5022.3  1763.8    5060 1763.79
  5072.8 1763.64  5073.3 1763.14  5078.1 1763.64  5103.4 1763.71  5111.8 1765.85
  5120.2 1772.28  5125.8 1772.59  5142.5 1788.42  5148.1  1788.1  5156.5 1801.12
  5164.9 1822.63  5170.5 1811.37  5178.9 1838.66  5201.2 1846.61  5223.6 1850.14
#Mann= 6 ,-1 , 0
    4539     .07       0  4704.1     .12       0  4997.4     .07       0
    5060     .12       0  5072.8     .05       0  5078.1     .12       0
Bank Sta=5072.8,5078.1
XS Rating Curve= 0 ,0
Exp/Cntr=0.3,0.1

Type RM Length L Ch R = 1 ,63691   ,93,93,93
BEGIN DESCRIPTION:
BIG JOSHUA CREEK 120.5
END DESCRIPTION:
XS GIS Cut Line= 4
      1996392.71     13859106.65       1996640.9      13858890.9
      1996710.45     13858817.75      1996851.03     13858663.49
#Sta/Elev= 30
  4670.8 1835.98  4675.6 1835.98  4680.7 1830.19  4687.3 1828.85  4751.9 1792.47
  4809.8 1769.71  4827.1 1769.04  4827.5 1768.54  4832.4 1769.04  4864.9 1770.28
  4893.4  1774.9  4936.1 1775.75  5035.2 1775.95  5112.9 1771.41  5127.1 1772.98
  5151.4 1780.81  5183.9 1792.61  5190.6 1793.33  5198.1 1797.83  5204.8 1798.21
  5212.2 1802.81    5219 1803.23  5233.2 1814.37    5240 1815.57  5247.4 1821.29
  5254.1 1821.92  5261.6 1827.35  5268.3 1828.46  5289.9 1839.15  5309.3 1843.71
#Mann= 5 ,-1 , 0
  4670.8     .12       0  4809.8     .07       0  4827.1     .05       0
  4832.4     .07       0  5151.4     .12       0
Bank Sta=4827.1,4832.4
XS Rating Curve= 0 ,0
Exp/Cntr=0.3,0.1

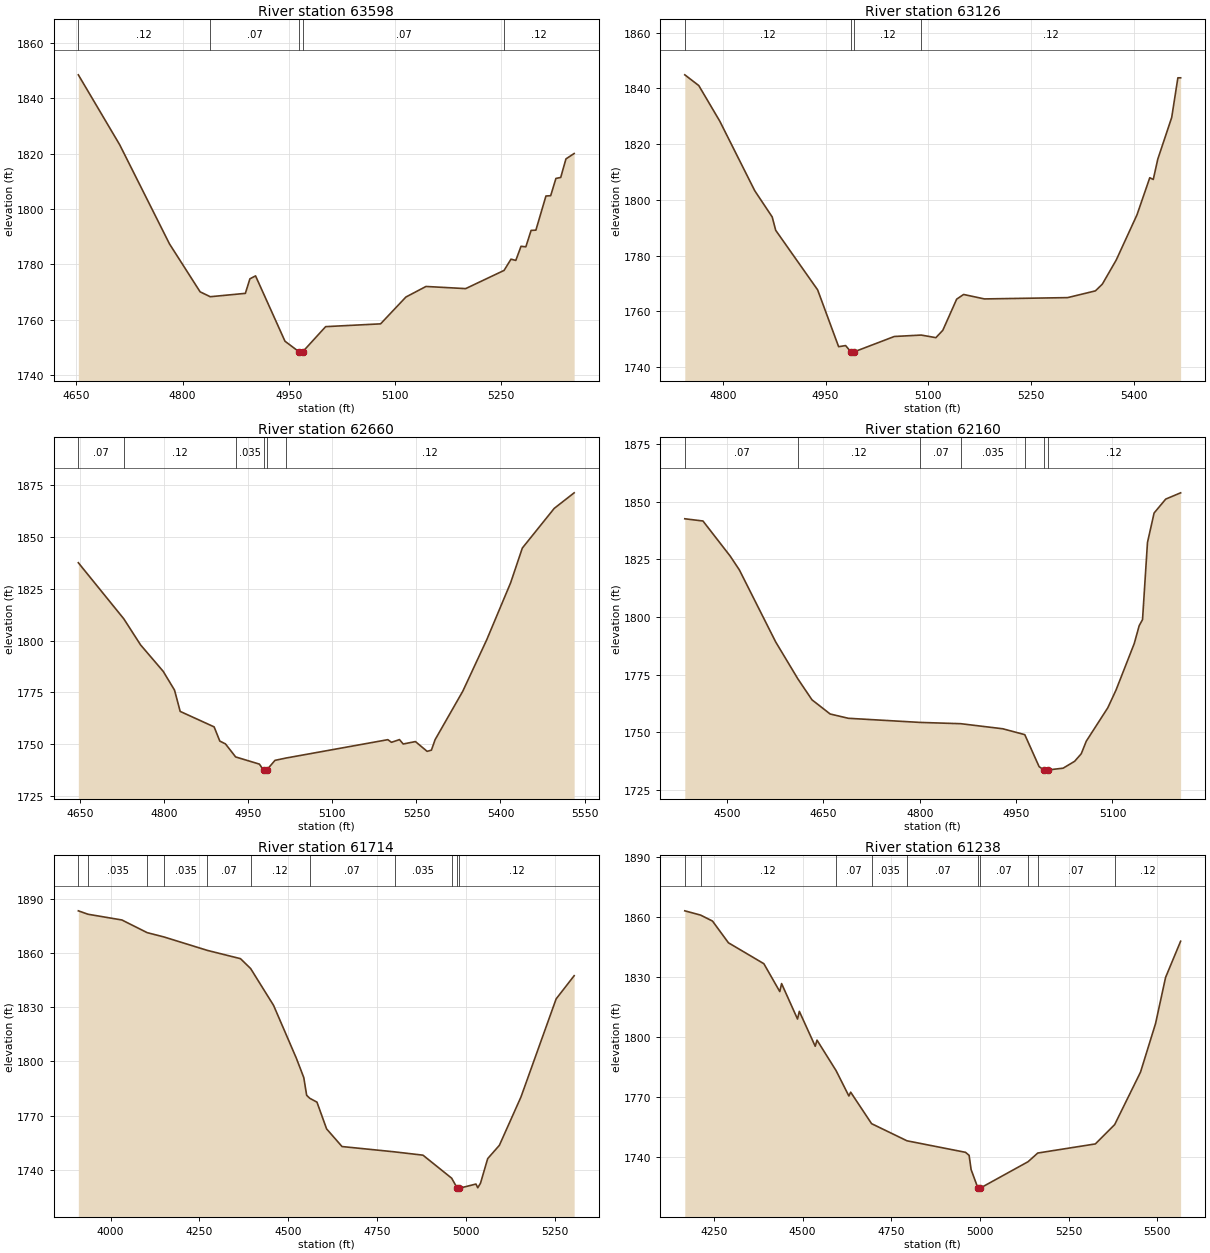
Type RM Length L Ch R = 1 ,63598   ,472,472,472
BEGIN DESCRIPTION:
BIG JOSHUA CREEK 120.0
END DESCRIPTION:
XS GIS Cut Line= 3
      1996407.48     13859189.08        1996675.       13858975.
      1996916.81     13858710.37
#Sta/Elev= 30
  4652.6  1848.5  4711.1 1823.23  4781.5 1787.41  4824.8 1770.09  4839.2 1768.32
  4888.8 1769.54  4895.2 1774.79  4903.2 1775.85  4944.8 1752.25  4964.6 1748.44
    4965 1747.94  4969.9 1748.44  5002.3 1757.51    5080 1758.52  5115.8 1768.21
  5144.2 1772.03  5200.3 1771.25  5254.6 1777.83  5264.4 1781.89  5271.2 1781.44
  5278.6 1786.55  5285.4 1786.35  5292.8 1792.28  5299.6 1792.38  5313.8 1804.72
  5320.5 1804.82  5327.9 1811.06  5334.7 1811.42  5342.1 1818.12  5353.7 1820.07
#Mann= 5 ,-1 , 0
  4652.6     .12       0  4839.2     .07       0  4964.6     .05       0
  4969.9     .07       0  5254.6     .12       0
Bank Sta=4964.6,4969.9
XS Rating Curve= 0 ,0
Exp/Cntr=0.3,0.1

Type RM Length L Ch R = 1 ,63126   ,466,466,466
BEGIN DESCRIPTION:
BIG JOSHUA CREEK 119.0
END DESCRIPTION:
XS GIS Cut Line= 3
        1997125.     13859425.01        1997075.       13859175.
      1997146.33     13858712.13
#Sta/Elev= 30
  4744.7  1844.9  4765.1 1841.05  4795.7 1828.29  4846.7 1803.33  4872.2  1793.9
  4877.3 1789.11  4938.5 1767.73  4969.1 1747.34  4979.3 1747.74  4986.8 1745.53
  4987.2 1745.03  4992.2 1745.53  5050.3    1751  5089.6 1751.51    5111 1750.58
  5121.1 1753.23  5141.3  1764.4  5151.4 1766.08  5181.8 1764.48  5303.2 1764.95
  5343.7 1767.37  5353.8 1769.79    5374 1778.41  5404.4 1794.69    5423 1807.98
  5428.1 1807.35  5434.7 1814.65    5455 1829.61    5464 1843.83    5468 1843.83
#Mann= 4 ,-1 , 0
  4744.7     .12       0  4986.8    .035       0  4992.2     .12       0
  5089.6     .12       0
Bank Sta=4986.8,4992.2
XS Rating Curve= 0 ,0
Exp/Cntr=0.3,0.1

Type RM Length L Ch R = 1 ,62660   ,500,500,500
BEGIN DESCRIPTION:
BIG JOSHUA CREEK 118.0
END DESCRIPTION:
XS GIS Cut Line= 3
      1997574.99     13859574.96        1997525.       13859225.
      1997874.99     13858825.01
#Sta/Elev= 30
  4646.5 1837.63  4727.7 1810.49  4757.6  1797.9    4798  1785.1  4818.2 1776.03
  4828.3 1765.73  4888.9 1758.25    4899 1751.39  4909.1 1750.02  4927.3 1743.71
  4969.7 1740.24  4977.1 1737.35  4977.5 1736.85  4982.6 1737.35  4997.5 1742.05
  5016.4 1743.14  5198.9 1752.06  5205.5 1750.78  5219.7  1752.1  5226.4 1749.97
  5248.2 1751.14  5269.1 1746.41  5276.7 1746.99  5283.3 1752.07  5332.7 1775.49
  5375.4 1800.34  5418.1 1827.93    5439 1844.73  5495.9 1863.91  5531.5 1871.44
#Mann= 6 ,-1 , 0
  4646.5     .07       0  4727.7     .12       0  4927.3    .035       0
  4977.1    .035       0  4982.6    .035       0  5016.4     .12       0
Bank Sta=4977.1,4982.6
XS Rating Curve= 0 ,0
Exp/Cntr=0.3,0.1

Type RM Length L Ch R = 1 ,62160   ,446,446,446
BEGIN DESCRIPTION:
BIG JOSHUA CREEK 117.0
END DESCRIPTION:
XS GIS Cut Line= 3
      1997624.99     13859625.01        1998025.       13859225.
      1998075.01     13859024.96
#Sta/Elev= 30
  4434.2 1842.61  4462.5 1841.64  4504.9  1826.4  4519.1 1820.45  4575.6 1789.21
  4610.4 1773.06  4632.2 1764.05  4660.5 1757.89  4688.8 1756.03  4800.4 1754.24
  4863.9 1753.68  4929.2 1751.48  4963.5 1748.93  4985.8 1735.04  4993.5  1733.6
    4994  1733.1  4999.2  1733.6  5023.1 1734.37  5041.1 1737.36  5051.4 1740.64
  5059.2 1746.08  5092.7 1760.58  5105.6 1768.32  5133.9 1788.47  5141.6 1796.22
  5146.8 1798.86  5154.5 1832.31  5164.8 1845.11  5182.9 1851.15  5206.1 1853.87
#Mann= 7 ,-1 , 0
  4434.2     .07       0  4610.4     .12       0  4800.4     .07       0
  4863.9    .035       0  4963.5     .12       0  4993.5     .05       0
  4999.2     .12       0
Bank Sta=4993.5,4999.2
XS Rating Curve= 0 ,0
Exp/Cntr=0.3,0.1

Type RM Length L Ch R = 1 ,61714   ,476,476,476
BEGIN DESCRIPTION:
BIG JOSHUA CREEK 116.0
END DESCRIPTION:
XS GIS Cut Line= 3
      1997701.87     13860283.37        1998375.       13859425.
      1998324.99     13859124.97
#Sta/Elev= 30
  3909.2 1883.59  3936.5 1881.69  4031.8 1878.51  4102.8 1871.49    4150  1869.1
    4272 1861.65  4365.4 1857.05    4394 1851.56  4458.5 1831.13  4522.7 1801.76
  4543.5 1791.08  4551.6 1781.23  4560.3 1779.58  4580.6 1777.44  4607.7 1762.58
  4651.1  1752.8    4799 1749.85  4878.9 1748.01  4959.6 1735.23  4975.4 1729.67
  4975.9 1729.17  4981.2 1729.67  5027.9 1731.99    5033 1729.94  5040.6 1732.39
  5060.9 1746.09  5093.8 1753.48  5154.6 1780.32  5253.5 1834.72  5304.2 1847.59
#Mann= 11 ,-1 , 0
  3909.2     .07       0  3936.5    .035       0  4102.8     .07       0
    4150    .035       0    4272     .07       0    4394     .12       0
  4560.3     .07       0    4799    .035       0  4959.6     .12       0
  4975.4     .05       0  4981.2     .12       0
Bank Sta=4975.4,4981.2
XS Rating Curve= 0 ,0
Exp/Cntr=0.3,0.1

Type RM Length L Ch R = 1 ,61238   ,466,466,466
BEGIN DESCRIPTION:
BIG JOSHUA CREEK 115.0
END DESCRIPTION:
XS GIS Cut Line= 3
      1998604.66      13860439.6        1998775.       13859625.
        1999175.       13859225.
#Sta/Elev= 30
  4167.8 1863.22  4212.2 1861.09  4245.9  1858.1  4290.8 1847.24  4390.7 1836.78
  4435.6 1822.83  4440.7 1826.83  4485.6  1809.1  4490.7 1812.95  4535.5  1795.5
  4540.6 1798.55  4594.5 1783.26  4630.4 1770.62  4635.5 1772.52  4694.4 1756.78
  4794.2 1748.21  4959.2 1742.45  4969.4 1740.93    4975 1733.82  4994.3 1724.54
  4994.8 1724.04  5000.6 1724.54  5135.6 1737.75  5162.9 1742.09  5325.3 1746.64
  5379.8 1756.32  5452.6 1782.54    5495 1806.83  5523.3 1829.92  5565.7 1848.01
#Mann= 10 ,-1 , 0
  4167.8     .07       0  4212.2     .12       0  4594.5     .07       0
  4694.4    .035       0  4794.2     .07       0  4994.3     .05       0
  5000.6     .07       0  5135.6    .035       0  5162.9     .07       0
  5379.8     .12       0
Bank Sta=4994.3,5000.6
XS Rating Curve= 0 ,0
Exp/Cntr=0.3,0.1

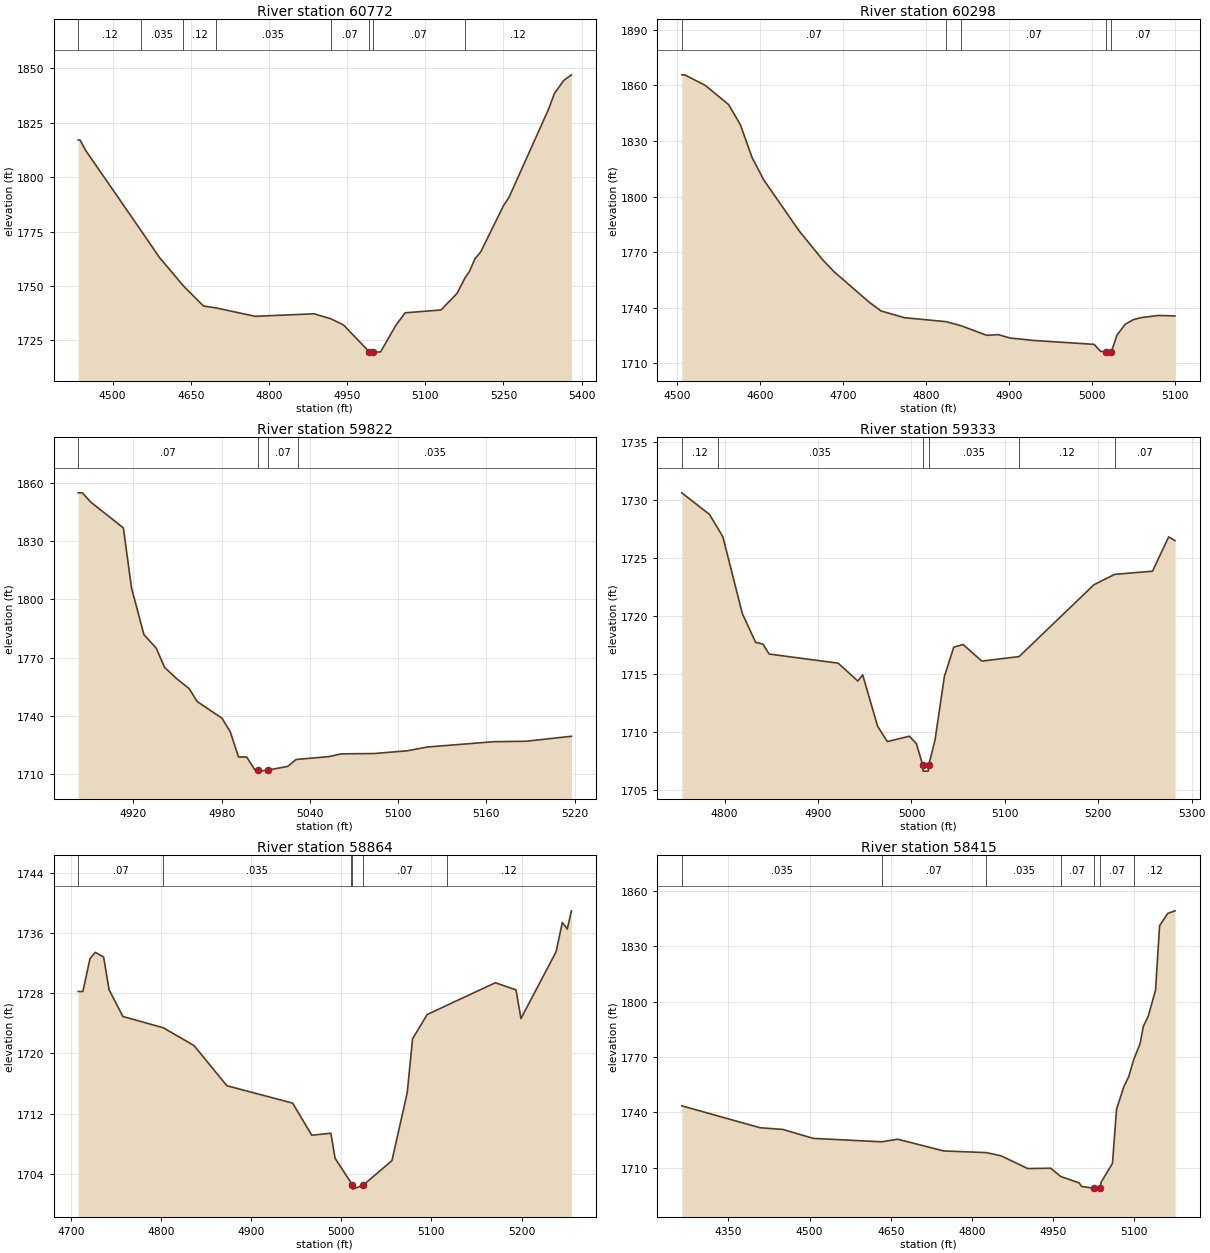
Type RM Length L Ch R = 1 ,60772   ,474,474,474
BEGIN DESCRIPTION:
BIG JOSHUA CREEK 114.0
END DESCRIPTION:
XS GIS Cut Line= 3
      1998824.97     13860075.03        1999225.       13859675.
      1999374.99     13859325.02
#Sta/Elev= 30
  4433.9    1817  4437.5    1817  4448.1 1812.27  4553.8 1775.68  4589.5  1763.2
  4635.9 1749.99  4674.4 1740.78  4697.7 1739.97  4773.4 1736.07  4886.5 1737.23
  4918.8 1734.94  4943.1 1732.09  4992.9 1719.67  4993.4 1719.17  4999.2 1719.67
  5014.1 1719.71  5043.2  1731.8  5061.3 1737.68  5130.2 1738.98    5161 1746.64
  5176.4 1753.81  5184.6 1756.65  5195.5 1762.59  5206.3 1765.61  5249.9  1786.8
  5260.7 1790.72  5336.9 1831.36  5347.8 1838.39  5365.9 1844.41  5380.4 1846.93
#Mann= 8 ,-1 , 0
  4433.9     .12       0  4553.8    .035       0  4635.9     .12       0
  4697.7    .035       0  4918.8     .07       0  4992.9     .05       0
  4999.2     .07       0  5176.4     .12       0
Bank Sta=4992.9,4999.2
XS Rating Curve= 0 ,0
Exp/Cntr=0.3,0.1

Type RM Length L Ch R = 1 ,60298   ,476,476,476
BEGIN DESCRIPTION:
BIG JOSHUA CREEK 113.0
END DESCRIPTION:
XS GIS Cut Line= 3
      1998975.02     13860374.98        1999325.       13860025.
      1999425.05       13860025.
#Sta/Elev= 30
  4505.6 1865.68  4509.1 1865.68  4533.9    1860  4562.1 1849.62  4576.3 1838.75
  4590.4 1821.02  4604.6  1808.9    4647 1781.58  4675.3 1766.02  4689.4 1759.41
  4731.9 1742.92    4746 1738.27  4774.3 1734.64  4824.3 1732.51  4842.7 1730.28
  4873.3 1725.15  4887.4 1725.51  4901.6 1723.69  4929.8 1722.38  5003.1 1720.26
  5010.6 1716.56  5017.4 1716.03  5017.9 1715.53  5023.7 1716.03  5030.6 1725.24
  5040.6 1731.13  5050.6 1733.64  5060.6 1734.75  5080.6 1735.85  5100.6  1735.6
#Mann= 5 ,-1 , 0
  4505.6     .07       0  4824.3    .035       0  4842.7     .07       0
  5017.4     .05       0  5023.7     .07       0
Bank Sta=5017.4,5023.7
XS Rating Curve= 0 ,0
Exp/Cntr=0.3,0.1

Type RM Length L Ch R = 1 ,59822   ,489,489,489
BEGIN DESCRIPTION:
BIG JOSHUA CREEK 112.0
END DESCRIPTION:
XS GIS Cut Line= 3
      1999225.03     13860524.98        1999325.       13860475.
      1999425.01     13860274.98
#Sta/Elev= 30
  4882.4  1854.9  4885.2  1854.9  4890.8 1850.22  4913.1 1836.86  4918.7  1805.8
  4927.1 1781.88  4935.5 1774.88  4941.1 1765.07  4949.4 1759.15  4957.8 1754.13
  4963.4 1747.38  4980.2 1738.82  4985.8 1731.87  4991.4 1718.86    4997 1718.86
  5002.6 1712.14  5004.9 1712.09  5005.4 1711.59  5011.3 1712.09  5024.9 1714.04
  5030.5 1717.53    5032 1717.67  5052.9 1719.07  5061.3 1720.48  5083.6 1720.65
    5106 1722.04  5119.9 1724.01  5164.7 1726.73    5187 1726.98  5217.8 1729.54
#Mann= 4 ,-1 , 0
  4882.4     .07       0  5004.9     .05       0  5011.3     .07       0
    5032    .035       0
Bank Sta=5004.9,5011.3
XS Rating Curve= 0 ,0
Exp/Cntr=0.3,0.1

Type RM Length L Ch R = 1 ,59333   ,469,469,469
BEGIN DESCRIPTION:
BIG JOSHUA CREEK 111.0
END DESCRIPTION:
XS GIS Cut Line= 4
      1999645.66     13860667.69      1999736.13     13860591.87
        1999775.       13860475.      1999780.51     13860188.16
#Sta/Elev= 30
  4754.1 1730.65  4783.7 1728.79  4792.5 1727.62  4798.1 1726.85  4818.9 1720.24
  4833.2 1717.75    4841 1717.61  4847.5 1716.75  4921.5 1715.96  4942.6 1714.42
  4947.8 1714.95  4963.7 1710.53  4974.2  1709.2  4997.8 1709.66  5005.3 1709.02
  5012.1 1707.15  5012.6 1706.65    5018 1706.65  5018.5 1707.15  5025.3 1709.36
  5035.3 1714.82  5045.3 1717.34  5055.3 1717.57  5075.3 1716.14  5115.3 1716.53
  5195.3 1722.72  5217.6 1723.62  5258.1 1723.89  5275.4 1726.85  5282.2 1726.53
#Mann= 6 ,-1 , 0
  4754.1     .12       0  4792.5    .035       0  5012.1    .035       0
  5018.5    .035       0  5115.3     .12       0  5217.6     .07       0
Bank Sta=5012.1,5018.5
XS Rating Curve= 0 ,0
Exp/Cntr=0.3,0.1

Type RM Length L Ch R = 1 ,58864   ,449,449,449
BEGIN DESCRIPTION:
BIG JOSHUA CREEK 110.0
END DESCRIPTION:
XS GIS Cut Line= 3
      2000021.63     13860718.85        2000175.       13860475.
      2000283.66     13860239.54
#Sta/Elev= 30
    4708 1728.21  4713.2 1728.21  4721.1 1732.58    4727 1733.41  4736.2 1732.78
  4742.3 1728.44  4757.6 1724.89  4802.3  1723.4  4836.5 1721.04    4873  1715.7
    4946 1713.39  4967.2 1709.13  4988.4 1709.39  4993.1 1706.07  5010.3 1702.91
  5012.3 1702.47  5012.8 1701.97    5024 1702.47  5056.2 1705.75  5073.2 1714.79
  5079.1 1721.92  5095.2 1725.14  5117.1 1726.37  5170.9 1729.37  5193.9 1728.43
  5199.4 1724.62  5238.4 1733.48  5245.3 1737.38  5250.8  1736.5  5255.4 1738.92
#Mann= 6 ,-1 , 0
    4708     .07       0  4802.3    .035       0  5010.3     .07       0
  5012.3    .035       0    5024     .07       0  5117.1     .12       0
Bank Sta=5012.3,5024
XS Rating Curve= 0 ,0
Exp/Cntr=0.3,0.1

Type RM Length L Ch R = 1 ,58415   ,471,471,471
BEGIN DESCRIPTION:
BIG JOSHUA CREEK 109.0
END DESCRIPTION:
XS GIS Cut Line= 3
      1999978.82      13861262.7        2000475.       13860725.
      2000624.97     13860625.02
#Sta/Elev= 30
  4263.7 1743.46  4408.2 1731.59  4450.7 1730.64  4506.8  1725.8  4633.4 1723.94
  4662.8 1725.35  4747.8 1718.99    4827 1718.07  4853.9 1716.36  4903.2 1709.43
  4945.7 1709.61  4964.2 1705.14  4998.4 1701.63  5002.9 1699.71  5025.5 1698.77
    5026 1698.27  5037.3 1698.77  5038.9 1701.99    5060 1712.27  5067.5 1741.59
    5081 1753.83    5090 1759.26  5099.4 1768.65    5111 1777.16    5117 1786.52
  5126.1 1792.03  5139.6 1806.24  5147.1 1841.17  5162.1 1847.84  5175.6 1849.24
#Mann= 7 ,-1 , 0
  4263.7    .035       0  4633.4     .07       0    4827    .035       0
  4964.2     .07       0  5025.5     .05       0  5037.3     .07       0
  5099.4     .12       0
Bank Sta=5025.5,5037.3
XS Rating Curve= 0 ,0
Exp/Cntr=0.3,0.1