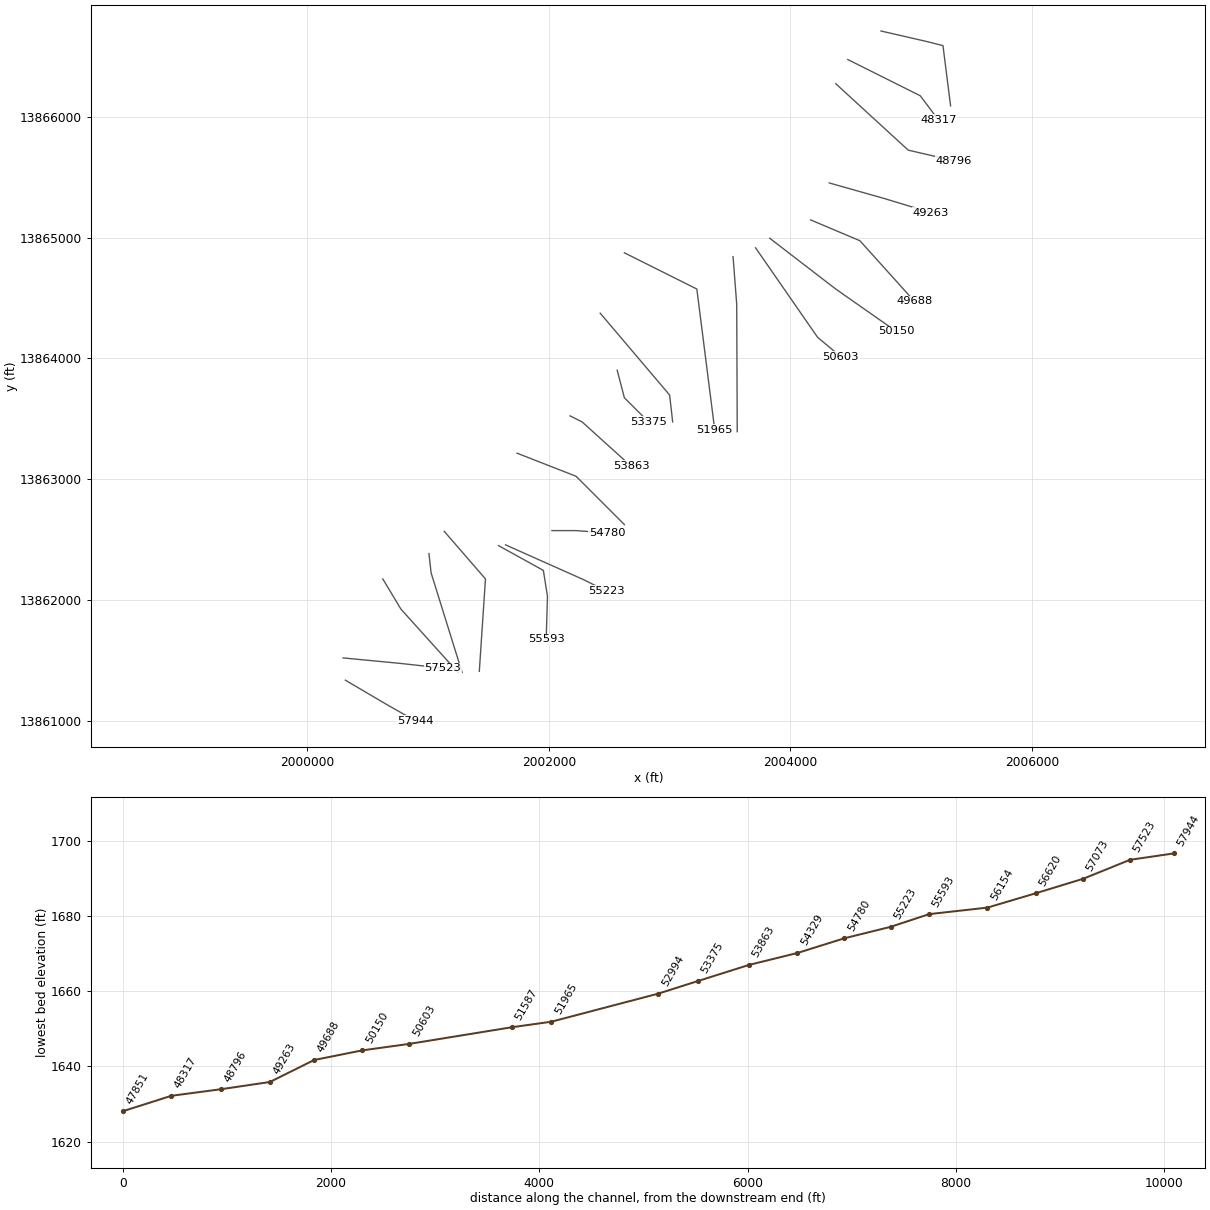
HEC-RAS study BIG JOSHUA CREEK.prj: BIG JOSHUA CREEK Base Level Engineering

--- BIG JOSHUA CREEK.g01 (geometry) --- (continued)

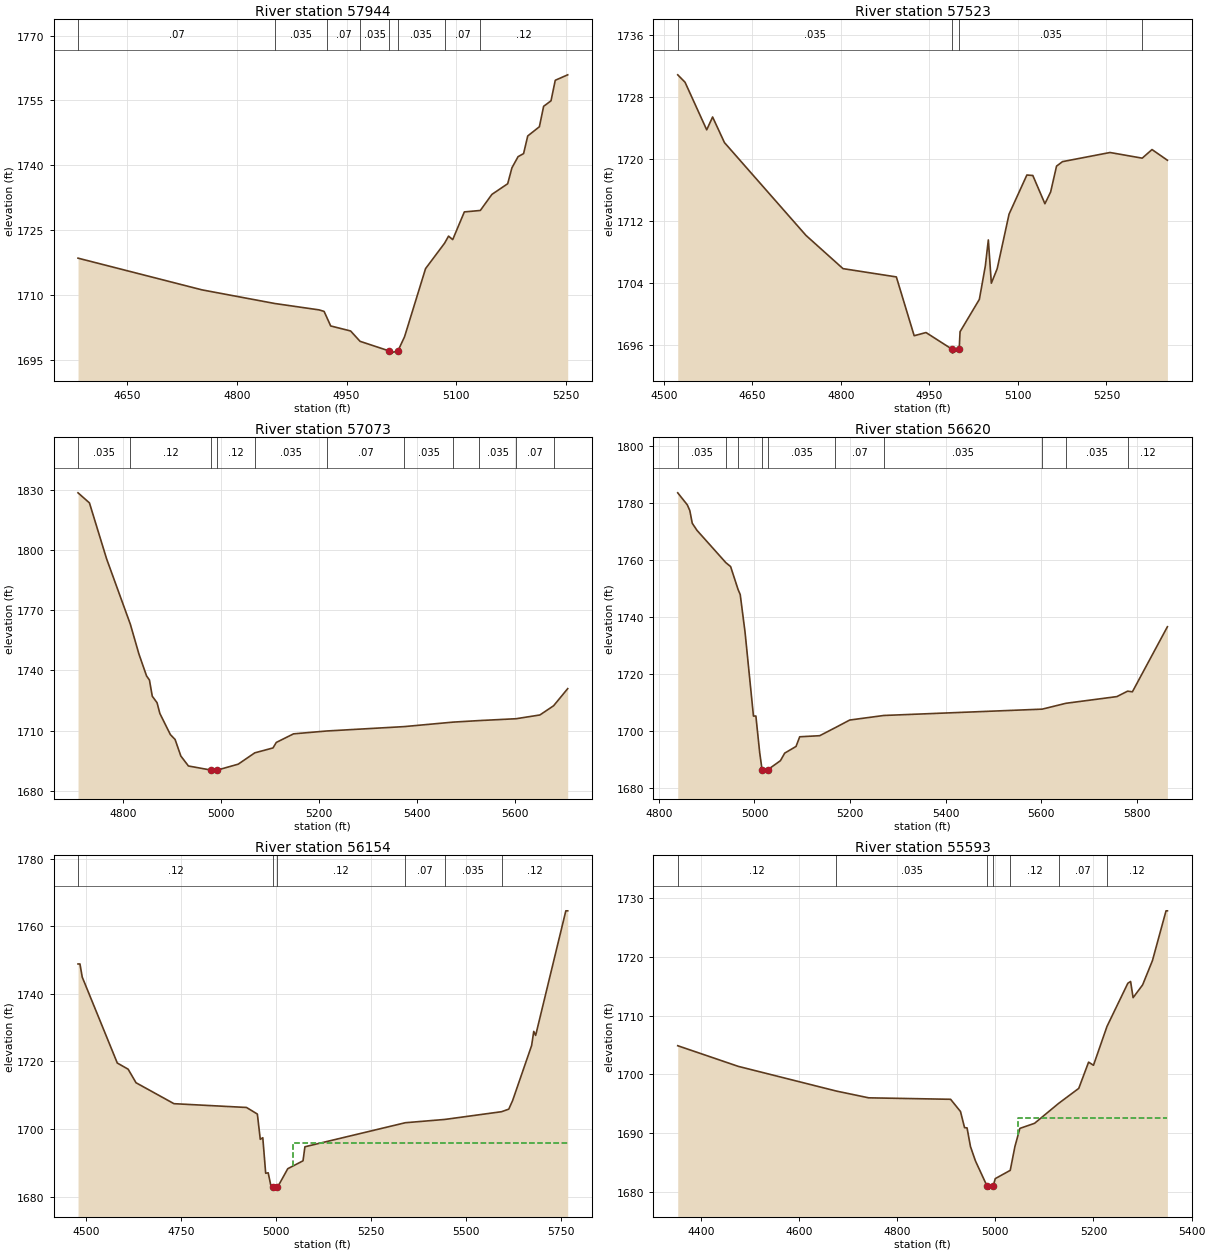
Type RM Length L Ch R = 1 ,57944   ,421,421,421
BEGIN DESCRIPTION:
BIG JOSHUA CREEK 108.0
END DESCRIPTION:
XS GIS Cut Line= 3
      2000315.16     13861336.52        2000675.       13861125.
      2000894.01     13861001.16
#Sta/Elev= 30
  4583.1 1718.55  4752.5 1711.22  4851.9 1708.07  4912.6 1706.59  4919.3 1706.24
  4923.1 1704.82  4928.3 1702.88  4955.5 1701.72  4968.4 1699.33  5008.3  1697.1
  5008.8  1696.6  5020.1  1697.1  5029.2 1700.38  5057.9 1716.13  5083.9 1722.01
  5089.3 1723.64    5095 1722.84  5110.9 1729.24  5132.7 1729.57  5148.5 1733.28
  5170.1 1735.75  5175.9 1739.43  5184.3 1742.01  5191.8 1742.71  5197.5 1746.79
  5213.4 1748.92  5219.2 1753.64  5229.3 1754.92  5235.1 1759.66  5252.1 1760.92
#Mann= 8 ,-1 , 0
  4583.1     .07       0  4851.9    .035       0  4923.1     .07       0
  4968.4    .035       0  5008.3    .035       0  5020.1    .035       0
  5083.9     .07       0  5132.7     .12       0
Bank Sta=5008.3,5020.1
XS Rating Curve= 0 ,0
Exp/Cntr=0.3,0.1

Type RM Length L Ch R = 1 ,57523   ,450,450,450
BEGIN DESCRIPTION:
BIG JOSHUA CREEK 107.0
END DESCRIPTION:
XS GIS Cut Line= 3
      2000296.16     13861521.04        2000775.       13861475.
      2001121.74     13861436.67
#Sta/Elev= 30
  4523.5 1730.87  4535.9 1729.91  4572.6 1723.76  4582.6 1725.42  4602.7 1722.11
  4740.8 1710.12  4803.6 1705.82    4894 1704.75  4924.2 1697.15  4944.3 1697.56
  4988.5  1695.4    4989  1694.9  5000.5  1695.4    5002 1697.67  5034.7 1701.85
  5044.8 1706.16  5049.9 1709.53    5055 1703.94  5064.9 1705.81    5085 1712.86
  5115.2 1717.92  5125.3 1717.86  5145.8 1714.21  5155.5 1715.73  5165.5 1719.07
  5175.6 1719.65  5256.1 1720.83  5310.7  1720.1  5327.3 1721.21  5353.4 1719.83
#Mann= 4 ,-1 , 0
  4523.5    .035       0  4988.5     .05       0  5000.5    .035       0
  5310.7     .12       0
Bank Sta=4988.5,5000.5
XS Rating Curve= 0 ,0
Exp/Cntr=0.3,0.1

Type RM Length L Ch R = 1 ,57073   ,453,453,453
BEGIN DESCRIPTION:
BIG JOSHUA CREEK 106.0
END DESCRIPTION:
XS GIS Cut Line= 3
      2000625.01     13862174.99        2000775.       13861925.
      2001249.04      13861398.9
#Sta/Elev= 30
  4708.5 1828.38  4731.8 1823.37  4766.8 1795.56  4815.3 1762.98  4832.9  1748.1
  4848.4 1737.26  4854.3  1735.2  4860.1 1727.14  4869.8 1723.93  4875.6 1718.55
    4897 1708.06  4906.7  1705.6  4918.4 1697.38  4933.9 1692.42  4980.4 1690.36
  4980.9 1689.86  4992.5 1690.36  5035.5 1693.32  5069.3 1698.95  5106.5  1701.4
  5113.3 1704.14  5148.4 1708.41  5216.3 1709.84  5374.4 1712.02  5473.9 1714.25
  5526.9 1715.01  5602.7 1715.94  5651.4 1717.81  5679.4 1722.39  5708.2 1730.92
#Mann= 11 ,-1 , 0
  4708.5    .035       0  4815.3     .12       0  4980.4     .05       0
  4992.5     .12       0  5069.3    .035       0  5216.3     .07       0
  5374.4    .035       0  5473.9     .07       0  5526.9    .035       0
  5602.7     .07       0  5679.4     .12       0
Bank Sta=4980.4,4992.5
XS Rating Curve= 0 ,0
Exp/Cntr=0.3,0.1

Type RM Length L Ch R = 1 ,56620   ,466,466,466
BEGIN DESCRIPTION:
BIG JOSHUA CREEK 105.0
END DESCRIPTION:
XS GIS Cut Line= 3
      2001007.18     13862385.03        2001025.       13862225.
       2001281.8     13861400.06
#Sta/Elev= 30
  4839.4  1783.6  4859.5 1779.37  4864.7 1777.36  4869.8 1772.93  4879.7 1770.45
  4940.1 1759.12  4950.1 1757.74  4965.8 1749.67  4970.2 1747.93  4980.3 1734.76
  4997.9 1705.34    5003 1705.34  5010.9 1692.61  5015.9 1686.53  5016.4 1686.03
    5028 1686.53  5054.4  1689.7  5063.3 1692.34    5087 1694.68  5094.7 1698.07
  5136.6 1698.45  5168.7 1701.23  5199.4 1703.94  5270.7 1705.54  5602.3 1707.76
  5651.9 1709.81  5758.6 1712.16    5781 1714.06  5791.1 1713.84  5864.4 1736.65
#Mann= 10 ,-1 , 0
  4839.4    .035       0  4940.1     .07       0  4965.8    .035       0
  5015.9    .035       0    5028    .035       0  5168.7     .07       0
  5270.7    .035       0  5602.3     .07       0  5651.9    .035       0
    5781     .12       0
Bank Sta=5015.9,5028
XS Rating Curve= 0 ,0
Exp/Cntr=0.3,0.1

Type RM Length L Ch R = 1 ,56154   ,561,561,561
BEGIN DESCRIPTION:
BIG JOSHUA CREEK 104.0
END DESCRIPTION:
XS GIS Cut Line= 3
      2001133.33     13862569.14        2001475.       13862175.
       2001424.1     13861410.31
#Sta/Elev= 30
  4478.5 1748.87  4483.6 1748.87  4489.6 1744.98  4581.8 1719.54  4610.3 1717.72
  4631.1  1713.7  4730.9  1707.5  4921.7 1706.38  4950.2 1704.43  4957.9 1696.94
  4964.5 1697.42  4972.1  1686.9  4978.7 1687.03  4986.4 1682.87  4990.8  1682.7
  4991.3  1682.2  5002.9  1682.7  5030.2 1688.25  5070.3 1690.58  5075.3 1694.74
  5339.3 1701.86  5443.6 1702.84  5592.7 1705.13  5611.5 1705.89  5621.5  1708.4
  5671.6 1724.73  5677.2  1728.9  5682.2 1727.73  5761.6 1764.61  5766.5 1764.61
#Mann= 6 ,-1 , 0
  4478.5     .12       0  4990.8    .035       0  5002.9     .12       0
  5339.3     .07       0  5443.6    .035       0  5592.7     .12       0
#XS Ineff= 2 , 0
       0                  5045.1       0 1695.98
Permanent Ineff=
       F       F
Bank Sta=4990.8,5002.9
XS Rating Curve= 0 ,0
Exp/Cntr=0.3,0.1

Type RM Length L Ch R = 1 ,55593   ,370,370,370
BEGIN DESCRIPTION:
BIG JOSHUA CREEK 103.0
END DESCRIPTION:
XS GIS Cut Line= 4
      2001583.54     13862450.54      2001954.49     13862245.35
      2001988.34     13862030.97       2001977.8     13861674.48
#Sta/Elev= 30
    4353  1704.9  4476.4 1701.38  4676.3 1697.17  4742.1 1696.02  4908.9 1695.77
  4929.1 1693.68  4937.3 1690.94  4942.4  1690.9  4949.4 1687.71  4959.5 1685.27
  4983.3 1680.96  4983.8 1680.46  4995.5 1680.96  4999.9 1682.25  5030.4 1683.66
  5039.9 1687.71    5050 1690.81    5080 1691.68  5128.9 1695.07    5170 1697.63
    5190  1702.1    5200 1701.57  5227.5 1708.19    5270 1715.55  5275.6 1715.85
  5280.7 1713.09  5300.1 1715.27  5320.1 1719.41  5347.8 1727.89  5350.6 1727.89
#Mann= 7 ,-1 , 0
    4353     .12       0  4676.3    .035       0  4983.3    .035       0
  4995.5    .035       0  5030.4     .12       0  5128.9     .07       0
  5227.5     .12       0
#XS Ineff= 2 , 0
       0                  5046.6       0  1692.5
Permanent Ineff=
       F       F
Bank Sta=4983.3,4995.5
XS Rating Curve= 0 ,0
Exp/Cntr=0.3,0.1

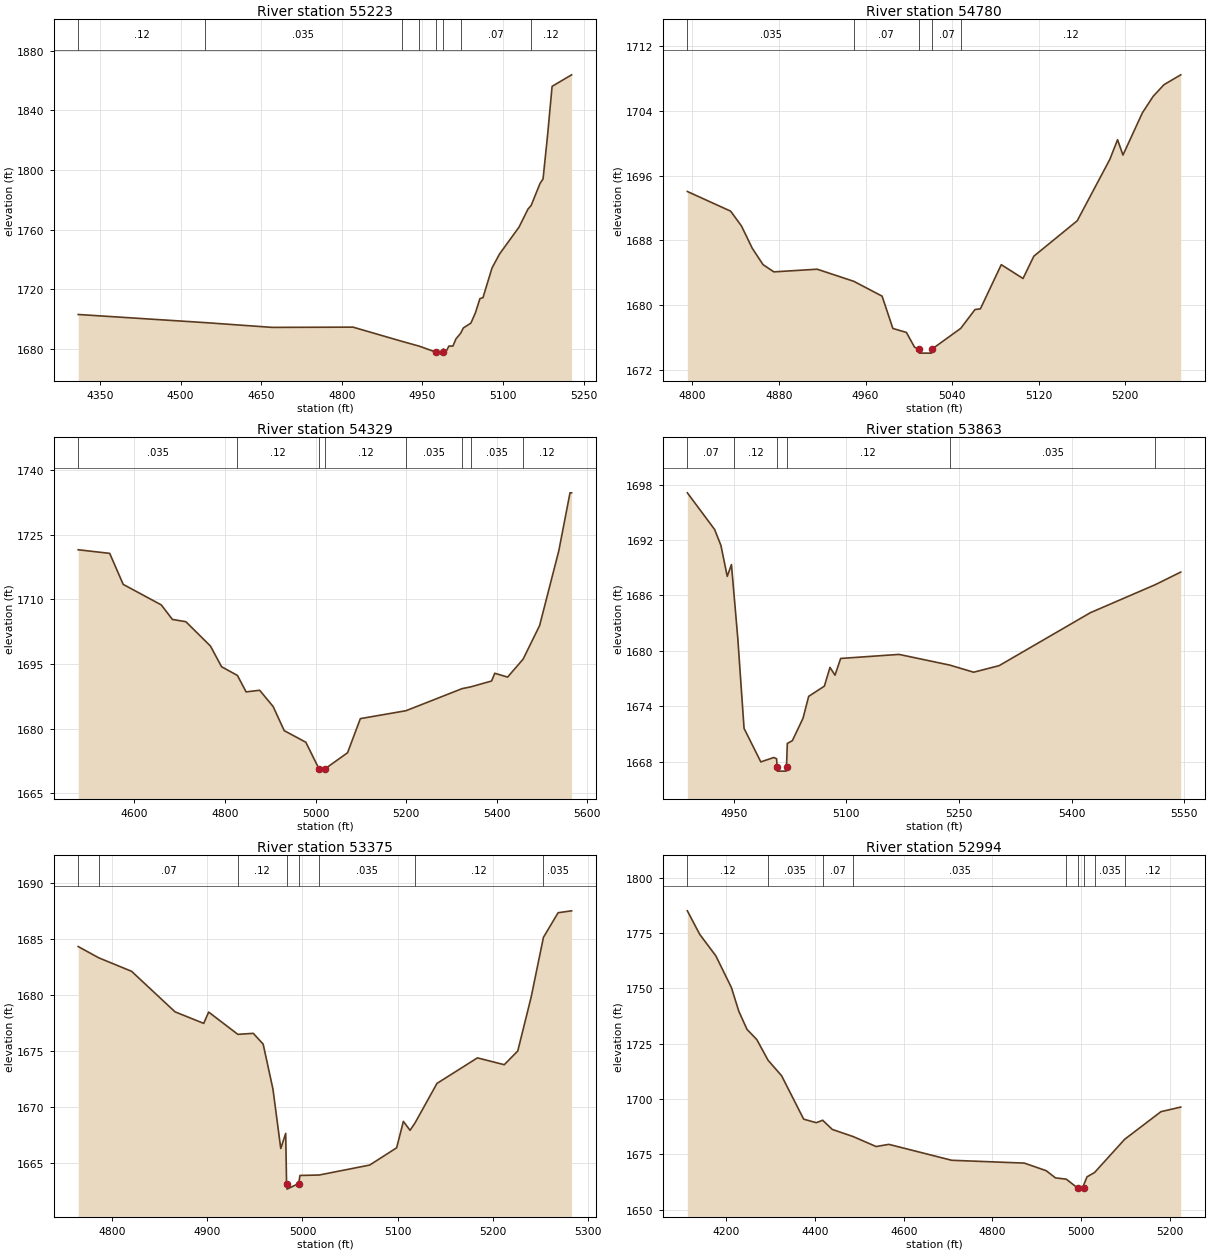
Type RM Length L Ch R = 1 ,55223   ,443,443,443
BEGIN DESCRIPTION:
BIG JOSHUA CREEK 102.0
END DESCRIPTION:
XS GIS Cut Line= 4
      2001640.74     13862457.25      2002271.22     13862175.94
        2002275.       13862175.        2002475.       13862075.
#Sta/Elev= 30
  4309.6 1703.01  4545.2 1697.57  4670.6 1694.35  4820.8 1694.52  4911.4 1685.04
  4944.4 1681.72  4976.1 1677.58  4976.6 1677.08  4988.3 1677.58  4988.9 1679.94
  4994.3 1678.42  4999.3 1681.82  5006.7 1681.82  5012.3 1686.61  5020.9 1690.33
  5026.2    1694  5040.2 1697.25  5048.6 1704.16    5057  1713.7  5062.6 1714.27
  5079.4 1734.19  5093.3 1743.51  5129.7 1761.65  5146.4 1773.77  5152.2 1776.11
  5168.8 1790.97  5174.4 1793.99  5182.8 1823.24  5191.2 1856.09  5227.5 1863.83
#Mann= 8 ,-1 , 0
  4309.6     .12       0  4545.2    .035       0  4911.4     .07       0
  4944.4     .12       0  4976.1     .05       0  4988.3     .12       0
  5020.9     .07       0  5152.2     .12       0
Bank Sta=4976.1,4988.3
XS Rating Curve= 0 ,0
Exp/Cntr=0.3,0.1

Type RM Length L Ch R = 1 ,54780   ,451,451,451
BEGIN DESCRIPTION:
BIG JOSHUA CREEK 101.0
END DESCRIPTION:
XS GIS Cut Line= 3
      2002025.03       13862575.        2002225.       13862575.
      2002480.41     13862555.77
#Sta/Elev= 30
  4795.3 1694.04  4835.3 1691.61  4845.3 1689.78  4855.3 1687.02  4865.3 1684.99
  4875.3  1684.1  4915.3 1684.43  4949.2 1682.93  4975.3  1681.1  4985.3  1677.1
  4997.8 1676.61  5005.3 1674.79  5009.2 1674.55  5009.7 1674.05    5021 1674.05
  5021.5 1674.55    5048 1677.11  5061.2 1679.44  5066.2 1679.53  5085.5 1684.99
  5105.6 1683.28  5115.6 1686.04  5155.7 1690.42  5185.8    1698    5193 1700.44
    5198 1698.55  5215.9 1703.76  5225.9 1705.81  5235.9 1707.25  5251.4 1708.47
#Mann= 5 ,-1 , 0
  4795.3    .035       0  4949.2     .07       0  5009.2     .05       0
  5021.5     .07       0    5048     .12       0
Bank Sta=5009.2,5021.5
XS Rating Curve= 0 ,0
Exp/Cntr=0.3,0.1

Type RM Length L Ch R = 1 ,54329   ,466,466,466
BEGIN DESCRIPTION:
BIG JOSHUA CREEK 100.0
END DESCRIPTION:
XS GIS Cut Line= 3
      2001736.57     13863215.88        2002225.       13863025.
      2002625.01     13862624.99
#Sta/Elev= 30
  4475.7 1721.55  4545.3 1720.71  4575.1 1713.51  4659.3 1708.74  4683.8 1705.37
  4713.6 1704.84  4767.9 1699.19  4792.4 1694.39  4827.5 1692.36  4846.7 1688.54
  4876.6 1688.92  4906.4 1685.14  4930.9 1679.54  4978.6 1676.85  5007.9 1670.64
  5008.4 1670.14  5020.6 1670.64  5070.8 1674.41  5099.1 1682.33  5199.9 1684.17
  5323.7 1689.29  5343.8 1689.73    5389 1691.07  5396.1 1692.86  5424.4 1691.98
  5458.6 1696.13  5495.1 1703.94  5537.5 1721.29  5562.3 1734.77  5565.8 1734.77
#Mann= 8 ,-1 , 0
  4475.7    .035       0  4827.5     .12       0  5007.9     .05       0
  5020.6     .12       0  5199.9    .035       0  5323.7     .07       0
  5343.8    .035       0  5458.6     .12       0
Bank Sta=5007.9,5020.6
XS Rating Curve= 0 ,0
Exp/Cntr=0.3,0.1

Type RM Length L Ch R = 1 ,53863   ,488,488,488
BEGIN DESCRIPTION:
BIG JOSHUA CREEK 99.0
END DESCRIPTION:
XS GIS Cut Line= 3
        2002175.       13863525.        2002275.       13863475.
      2002679.44     13863109.55
#Sta/Elev= 30
  4888.3 1697.12  4924.6 1693.15    4933 1691.42  4941.4 1688.07    4947 1689.34
  4950.9 1685.66  4955.4 1681.41  4963.8 1671.59  4986.1 1667.96  5003.5 1668.44
  5007.2 1668.29  5007.6 1667.46  5008.1 1666.96  5019.8 1666.96  5020.3 1667.46
  5021.4 1669.96  5028.1 1670.26  5042.3 1672.69  5049.8 1675.06  5070.7 1676.17
  5078.2  1678.2  5084.9 1677.36  5092.4 1679.17  5170.1 1679.61  5237.7 1678.45
  5269.5 1677.68  5303.4 1678.39  5424.9 1684.13  5511.1 1687.16  5545.2 1688.53
#Mann= 6 ,-1 , 0
  4888.3     .07       0  4950.9     .12       0  5007.6     .05       0
  5020.3     .12       0  5237.7    .035       0  5511.1     .07       0
Bank Sta=5007.6,5020.3
XS Rating Curve= 0 ,0
Exp/Cntr=0.3,0.1

Type RM Length L Ch R = 1 ,53375   ,381,381,381
BEGIN DESCRIPTION:
BIG JOSHUA CREEK 98.0
END DESCRIPTION:
XS GIS Cut Line= 3
      2002565.51     13863903.08        2002625.       13863675.
      2002825.03     13863474.97
#Sta/Elev= 30
  4764.3 1684.36    4786 1683.35  4820.4 1682.15  4866.1 1678.53  4896.2  1677.5
  4901.4 1678.51  4932.1 1676.52  4948.3 1676.61  4958.7 1675.65    4969 1671.63
  4977.2 1666.33  4982.4 1667.68  4983.3  1663.2  4983.8  1662.7    4996  1663.2
  4997.4 1663.92  5017.6 1663.96  5070.7 1664.85    5099 1666.39  5106.1 1668.75
  5113.1 1667.95  5118.4 1668.62  5141.4 1672.14  5183.9 1674.42  5212.1 1673.81
  5226.3 1675.03  5240.4 1679.85  5253.3 1685.18  5268.7 1687.38  5282.9 1687.55
#Mann= 8 ,-1 , 0
  4764.3     .12       0    4786     .07       0  4932.1     .12       0
  4983.3     .05       0    4996     .12       0  5017.6    .035       0
  5118.4     .12       0  5253.3    .035       0
Bank Sta=4983.3,4996
XS Rating Curve= 0 ,0
Exp/Cntr=0.3,0.1

Type RM Length L Ch R = 1 ,52994   ,1029,1029,1029
BEGIN DESCRIPTION:
BIG JOSHUA CREEK 97.0
END DESCRIPTION:
XS GIS Cut Line= 3
      2002425.02     13864374.98      2002999.62     13863697.64
        2003025.     13863475.01
#Sta/Elev= 30
  4112.2 1784.96  4140.2 1774.32  4176.5 1764.62  4211.6 1750.29  4228.1 1739.69
  4246.7 1731.44  4268.7 1726.87  4294.3 1717.49  4324.7 1710.52  4374.4 1690.94
  4402.7 1689.33  4417.3 1690.43    4439 1686.29  4486.3 1683.05  4537.8 1678.57
  4566.4 1679.56  4708.1 1672.37  4871.8  1671.1  4921.2 1667.67    4942 1664.43
  4966.4 1663.85  4992.1 1659.85  4992.6 1659.35  5005.6 1659.85  5005.9 1661.33
  5013.2  1664.9  5030.1 1666.82    5098 1681.83  5179.8  1694.3  5224.5 1696.39
#Mann= 9 ,-1 , 0
  4112.2     .12       0  4294.3    .035       0  4417.3     .07       0
  4486.3    .035       0  4966.4     .07       0  4992.1     .05       0
  5005.6     .07       0  5030.1    .035       0    5098     .12       0
Bank Sta=4992.1,5005.6
XS Rating Curve= 0 ,0
Exp/Cntr=0.3,0.1

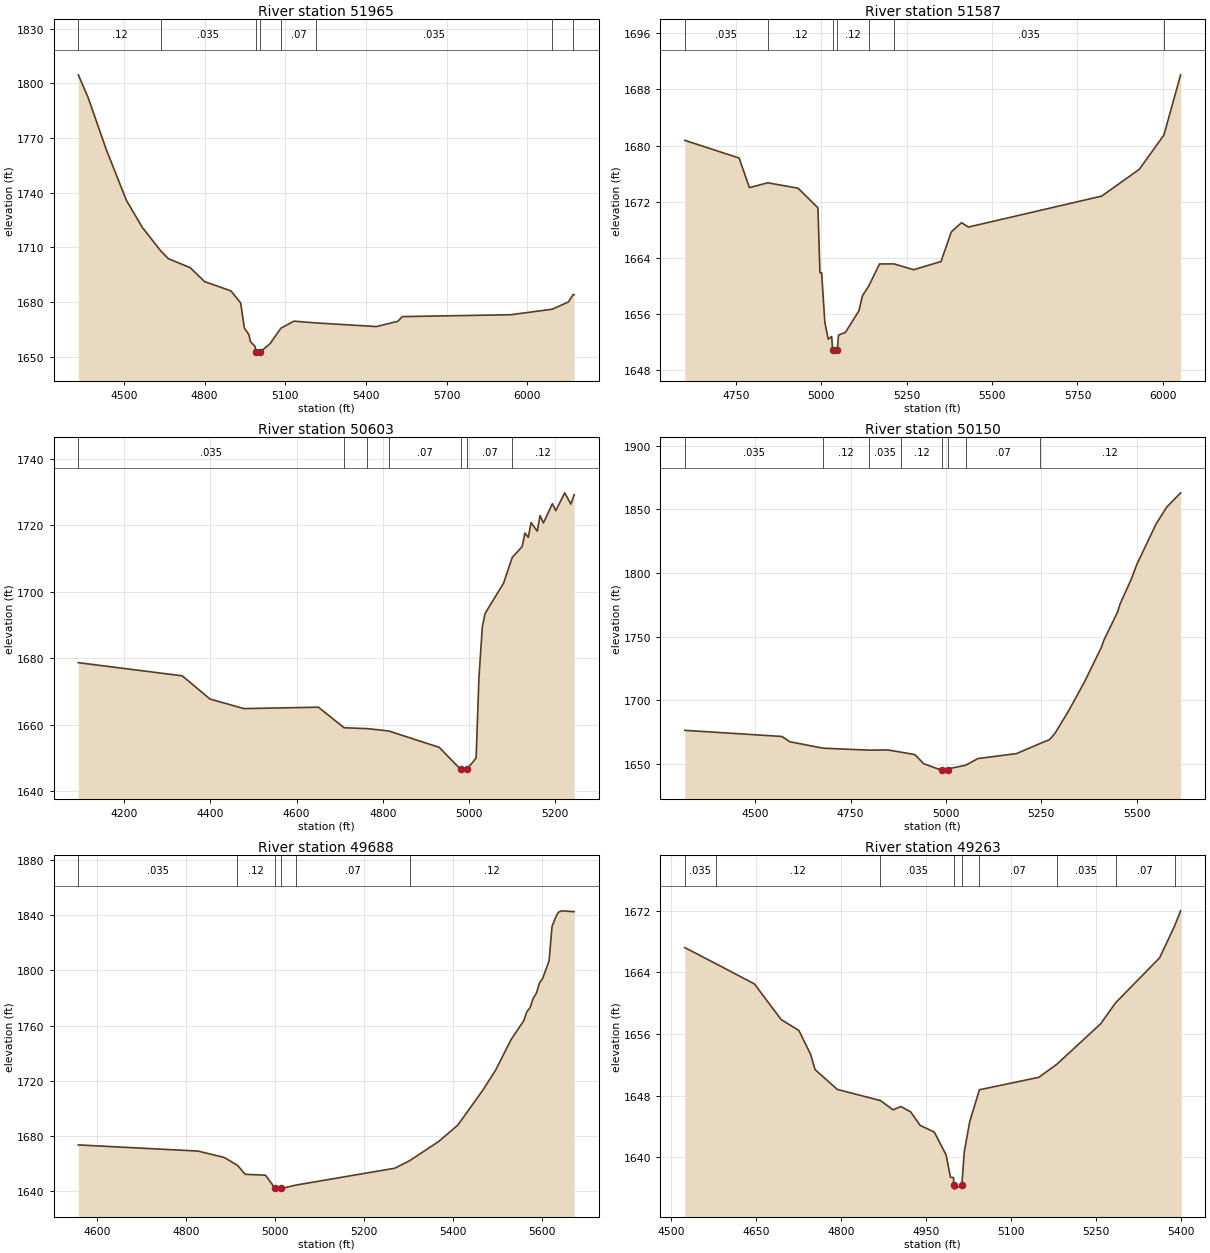
Type RM Length L Ch R = 1 ,51965   ,378,378,378
BEGIN DESCRIPTION:
BIG JOSHUA CREEK 96.0
END DESCRIPTION:
XS GIS Cut Line= 3
      2002625.04     13864874.98        2003225.       13864575.
      2003372.89     13863411.14
#Sta/Elev= 30
  4330.2 1804.61  4366.5  1792.2  4433.6 1763.81    4509 1735.72  4567.7 1720.97
  4636.8 1707.95  4665.6 1703.66  4746.6 1698.75  4799.7 1691.12  4897.6 1686.05
  4933.9 1679.42  4947.9 1665.55  4964.6 1662.01  4970.2  1658.2    4987 1655.65
  4991.3 1652.37  4991.8 1651.87    5005 1652.37  5043.5  1657.1  5083.4 1665.54
    5132 1669.41  5214.5 1668.44  5438.4 1666.45  5518.4 1669.32  5535.2 1671.92
  5938.5 1672.94  6092.9 1675.98  6153.2 1679.97    6170 1683.96  6174.2 1683.96
#Mann= 8 ,-1 , 0
  4330.2     .12       0  4636.8    .035       0  4991.3    .035       0
    5005    .035       0  5083.4     .07       0  5214.5    .035       0
  6092.9     .07       0    6170     .12       0
Bank Sta=4991.3,5005
XS Rating Curve= 0 ,0
Exp/Cntr=0.3,0.1

Type RM Length L Ch R = 1 ,51587   ,984,984,984
BEGIN DESCRIPTION:
BIG JOSHUA CREEK 95.0
END DESCRIPTION:
XS GIS Cut Line= 3
       2003524.8     13864843.49      2003555.18      13864448.5
      2003559.52     13863393.86
#Sta/Elev= 30
    4601 1680.74    4760 1678.22    4790    1674  4843.9 1674.69  4932.5 1673.92
  4990.6 1671.12  4996.4 1661.86  5001.4 1661.86  5010.7 1654.83  5020.7  1652.4
  5030.7 1652.77  5033.8 1650.91  5034.3 1650.41  5047.5 1650.91  5050.7 1652.98
  5070.7 1653.35  5110.7 1656.46  5120.7 1658.58  5139.1 1659.96  5170.7 1663.12
    5213 1663.13  5270.7  1662.3  5350.7 1663.47  5380.7 1667.68  5410.7 1669.01
  5430.7 1668.38  5820.7 1672.79  5930.7  1676.6    6003 1681.51  6051.8 1690.08
#Mann= 7 ,-1 , 0
    4601    .035       0  4843.9     .12       0  5033.8     .05       0
  5047.5     .12       0  5139.1     .07       0    5213    .035       0
    6003     .12       0
Bank Sta=5033.8,5047.5
XS Rating Curve= 0 ,0
Exp/Cntr=0.3,0.1

Type RM Length L Ch R = 1 ,50603   ,453,453,453
BEGIN DESCRIPTION:
BIG JOSHUA CREEK 94.0
END DESCRIPTION:
XS GIS Cut Line= 3
      2003711.26     13864916.34        2004225.       13864175.
      2004416.45     13864015.71
#Sta/Elev= 30
  4093.2 1678.62  4334.4 1674.66    4399 1667.67  4477.6  1664.8  4650.6 1665.22
  4710.1 1659.04  4764.4 1658.77  4813.6 1658.07    4931 1653.14  4980.8 1646.49
  4981.3 1645.99  4994.6 1646.49  5016.6 1649.91  5023.1 1673.87    5031  1689.4
  5037.5 1693.44  5080.4 1702.55  5100.4 1710.27  5123.4 1713.53  5129.9 1717.62
  5137.7 1716.33  5144.2 1720.75  5158.5  1718.2    5165 1722.86  5172.9 1720.64
  5193.7 1726.45  5201.5 1724.34  5222.3 1729.71  5236.6 1726.33  5244.2 1729.18
#Mann= 7 ,-1 , 0
  4093.2    .035       0  4710.1     .07       0  4764.4     .12       0
  4813.6     .07       0  4980.8     .05       0  4994.6     .07       0
  5100.4     .12       0
Bank Sta=4980.8,4994.6
XS Rating Curve= 0 ,0
Exp/Cntr=0.3,0.1

Type RM Length L Ch R = 1 ,50150   ,462,462,462
BEGIN DESCRIPTION:
BIG JOSHUA CREEK 93.0
END DESCRIPTION:
XS GIS Cut Line= 3
      2003828.62     13864995.37        2004375.       13864575.
        2004875.       13864225.
#Sta/Elev= 30
  4315.4 1676.33  4569.8  1671.5  4590.7 1667.36  4677.9 1662.28  4799.4 1660.75
    4848 1660.89    4883 1659.12  4918.7 1657.24  4941.4 1650.13  4990.6 1644.76
  4991.1 1644.26  5004.5 1644.76  5004.8 1646.02  5051.6 1648.89  5083.7 1654.13
  5184.8 1658.03  5245.9 1665.86  5271.1 1668.96  5285.5 1673.86  5321.7 1691.72
  5363.6 1714.69  5407.6 1741.71  5414.1  1747.3  5449.9 1769.35  5456.4 1775.72
  5485.6    1795  5500.4 1806.83    5551 1838.68  5578.5 1851.72  5615.1 1863.01
#Mann= 8 ,-1 , 0
  4315.4    .035       0  4677.9     .12       0  4799.4    .035       0
    4883     .12       0  4990.6     .05       0  5004.5     .12       0
  5051.6     .07       0  5245.9     .12       0
Bank Sta=4990.6,5004.5
XS Rating Curve= 0 ,0
Exp/Cntr=0.3,0.1

Type RM Length L Ch R = 1 ,49688   ,425,425,425
BEGIN DESCRIPTION:
BIG JOSHUA CREEK 92.0
END DESCRIPTION:
XS GIS Cut Line= 3
      2004167.14      13865147.3        2004575.       13864975.
      2005024.97     13864475.03
#Sta/Elev= 30
  4557.5  1673.7  4826.6 1669.24  4885.4 1664.64  4915.5 1658.94  4932.9 1652.43
  4978.5 1651.78  5000.4  1642.2  5000.9  1641.7  5014.3  1642.2  5047.8 1644.67
  5269.3 1656.82  5302.7 1662.25  5368.4 1676.23    5411 1687.95  5467.8 1713.45
  5496.2  1727.8  5531.3 1750.07  5559.7 1763.62  5566.4 1770.02  5573.9 1773.05
  5580.6 1779.74  5588.1 1783.54  5594.8 1790.81  5602.3 1794.29  5616.5 1806.97
  5623.2 1831.95  5630.7 1837.95  5637.4 1842.03  5644.9 1843.07  5672.9 1842.44
#Mann= 6 ,-1 , 0
  4557.5    .035       0  4915.5     .12       0  5000.4     .05       0
  5014.3     .12       0  5047.8     .07       0  5302.7     .12       0
Bank Sta=5000.4,5014.3
XS Rating Curve= 0 ,0
Exp/Cntr=0.3,0.1

Type RM Length L Ch R = 1 ,49263   ,467,467,467
BEGIN DESCRIPTION:
BIG JOSHUA CREEK 91.0
END DESCRIPTION:
XS GIS Cut Line= 3
      2004321.31     13865453.29        2004775.       13865325.
      2005161.17     13865207.93
#Sta/Elev= 30
  4524.3  1667.2  4578.9 1665.12  4647.1 1662.49  4694.4 1657.86  4725.6 1656.45
  4746.4 1653.34  4754.2 1651.37  4793.4  1648.8  4869.6 1647.35  4891.9 1646.15
  4905.7 1646.58    4923 1645.88  4939.6 1644.13  4964.6 1643.26  4985.4 1640.31
  4993.2 1637.38  4998.4 1637.38  4999.2 1636.36  4999.7 1635.86  5013.2 1636.36
  5017.5 1640.69  5027.1 1644.61  5044.2 1648.75  5149.1 1650.37  5180.7 1652.05
  5258.3 1657.32  5284.7 1660.05  5362.2 1665.87  5388.6    1670  5399.3 1671.97
#Mann= 9 ,-1 , 0
  4524.3    .035       0  4578.9     .12       0  4869.6    .035       0
  4999.2    .035       0  5013.2    .035       0  5044.2     .07       0
  5180.7    .035       0  5284.7     .07       0  5388.6     .12       0
Bank Sta=4999.2,5013.2
XS Rating Curve= 0 ,0
Exp/Cntr=0.3,0.1

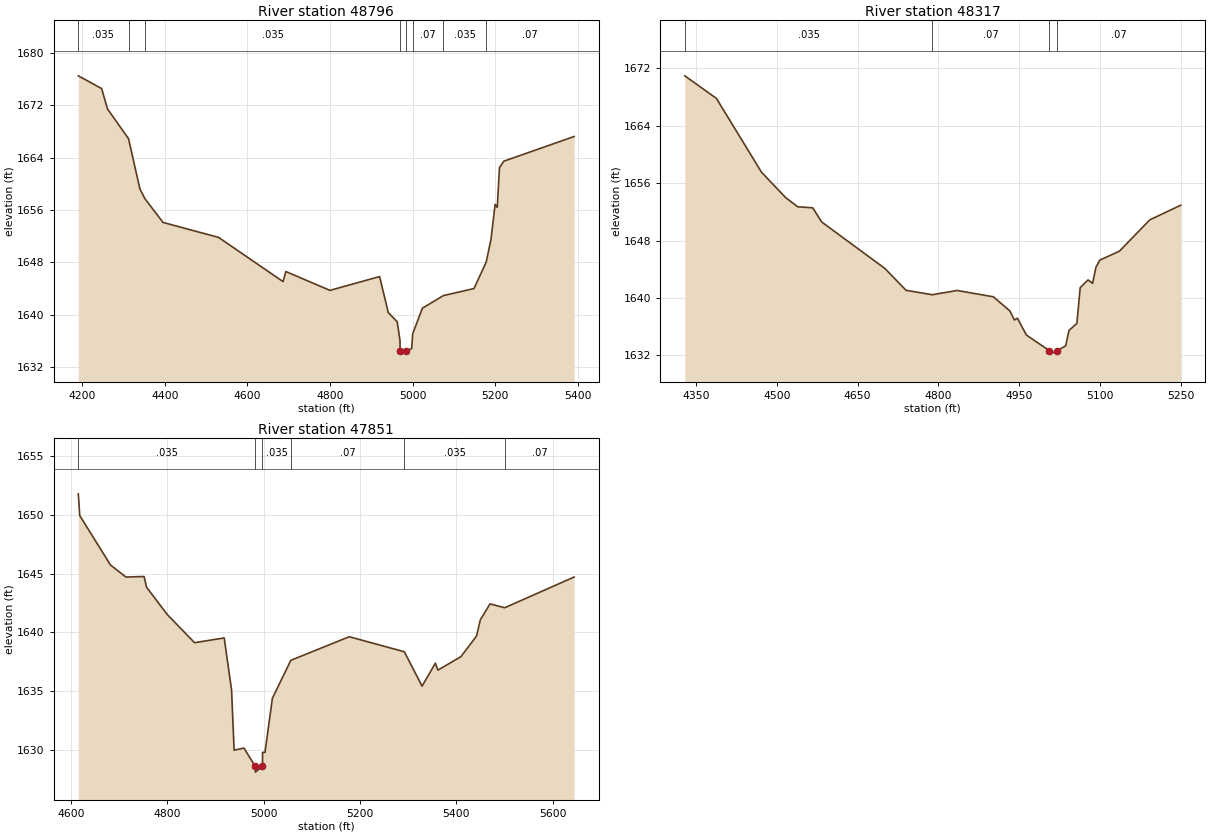
Type RM Length L Ch R = 1 ,48796   ,479,479,479
BEGIN DESCRIPTION:
BIG JOSHUA CREEK 90.0
END DESCRIPTION:
XS GIS Cut Line= 3
      2004375.03     13866274.97        2004975.       13865725.
      2005351.06     13865637.97
#Sta/Elev= 30
    4191 1676.51  4247.4 1674.56  4261.6 1671.45  4312.5 1666.89  4339.9 1659.25
    4352 1657.73    4396 1654.09  4530.4  1651.8  4686.4 1645.04  4693.2 1646.58
  4799.9  1643.7  4920.1 1645.81  4941.1  1640.3  4962.7  1638.9  4969.4 1636.06
  4969.7 1634.45  4970.2 1633.95    4984 1634.45  4997.8  1634.8  5000.1 1637.04
  5023.7 1640.98  5074.4  1642.9  5148.6 1643.98    5178 1648.02  5189.7 1651.51
  5199.6 1656.85  5204.8 1656.39  5210.2 1662.45  5220.5 1663.45  5390.9 1667.23
#Mann= 8 ,-1 , 0
    4191    .035       0  4312.5     .07       0    4352    .035       0
  4969.7    .035       0    4984    .035       0  5000.1     .07       0
  5074.4    .035       0    5178     .07       0
Bank Sta=4969.7,4984
XS Rating Curve= 0 ,0
Exp/Cntr=0.3,0.1

Type RM Length L Ch R = 1 ,48317   ,466,466,466
BEGIN DESCRIPTION:
BIG JOSHUA CREEK 89.0
END DESCRIPTION:
XS GIS Cut Line= 3
      2004475.02     13866474.99        2005075.       13866175.
        2005225.       13865975.
#Sta/Elev= 30
  4329.2 1670.93  4387.9 1667.79  4471.7 1657.51  4516.5 1653.98  4538.8  1652.7
  4566.8 1652.56  4583.5 1650.58  4700.9 1644.11  4740.1 1641.07  4788.8 1640.46
  4835.1 1641.05  4902.2 1640.17  4932.9 1638.21  4941.3 1636.94  4946.9 1637.19
  4963.7 1634.84    5006 1632.69  5006.5 1632.19  5021.1 1632.69  5036.5 1633.34
  5042.7 1635.49  5057.3 1636.46  5063.5 1641.45  5078.1 1642.52  5086.5 1642.04
  5092.7 1644.28    5100 1645.28  5136.5 1646.53  5192.7 1650.88    5250 1652.91
#Mann= 4 ,-1 , 0
  4329.2    .035       0  4788.8     .07       0    5006     .05       0
  5021.1     .07       0
Bank Sta=5006,5021.1
XS Rating Curve= 0 ,0
Exp/Cntr=0.3,0.1

Type RM Length L Ch R = 1 ,47851   ,476,476,476
BEGIN DESCRIPTION:
BIG JOSHUA CREEK 88.0
END DESCRIPTION:
XS GIS Cut Line= 4
      2004749.75     13866711.24        2005125.       13866625.
      2005262.82     13866590.15      2005325.79      13866091.7
#Sta/Elev= 30
  4614.9 1651.81  4617.8 1649.96  4681.8 1645.74  4713.7 1644.72  4751.5 1644.76
  4756.6 1643.85  4799.4 1641.53  4856.3 1639.12  4917.8 1639.53  4933.1 1635.09
  4938.4 1629.96  4958.9 1630.14  4982.1 1628.59  4982.6 1628.09  4997.3 1628.59
  4997.4 1629.77  5002.5 1629.77  5017.9 1634.39  5056.2 1637.62  5177.5 1639.63
  5291.8 1638.35  5328.7 1635.42  5356.4 1637.38  5361.5 1636.78  5409.3 1637.93
  5441.7 1639.68  5449.7 1641.07  5469.8 1642.43  5500.3  1642.1  5644.5 1644.72
#Mann= 6 ,-1 , 0
  4614.9    .035       0  4982.1    .035       0  4997.3    .035       0
  5056.2     .07       0  5291.8    .035       0  5500.3     .07       0
Bank Sta=4982.1,4997.3
XS Rating Curve= 0 ,0
Exp/Cntr=0.3,0.1