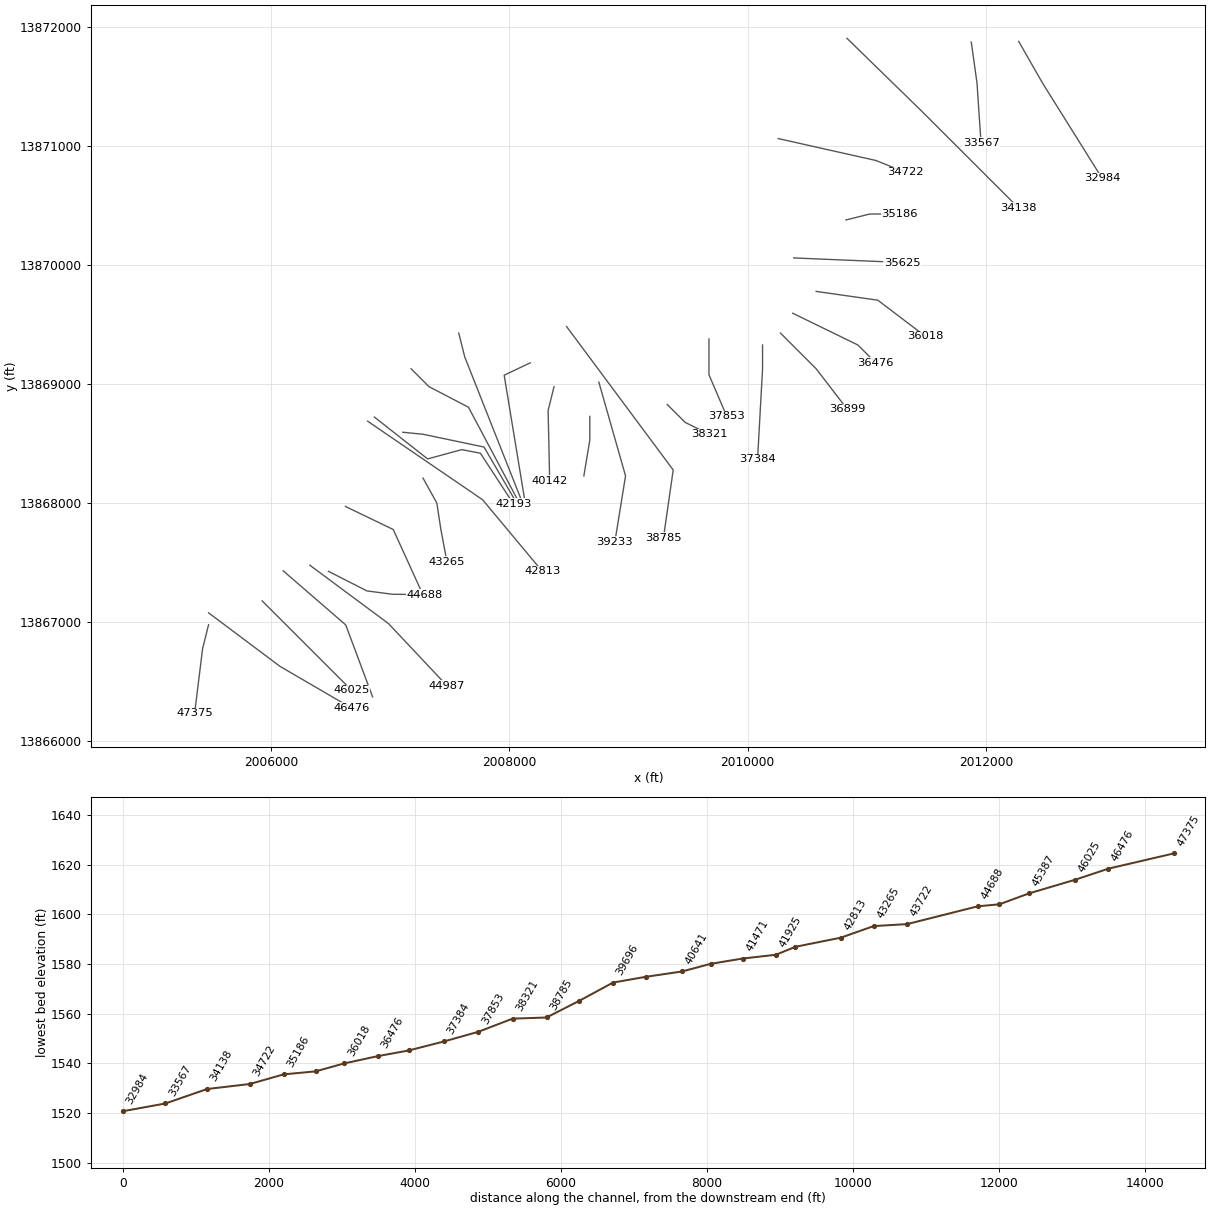
HEC-RAS study BIG JOSHUA CREEK.prj: BIG JOSHUA CREEK Base Level Engineering

--- BIG JOSHUA CREEK.g01 (geometry) --- (continued)

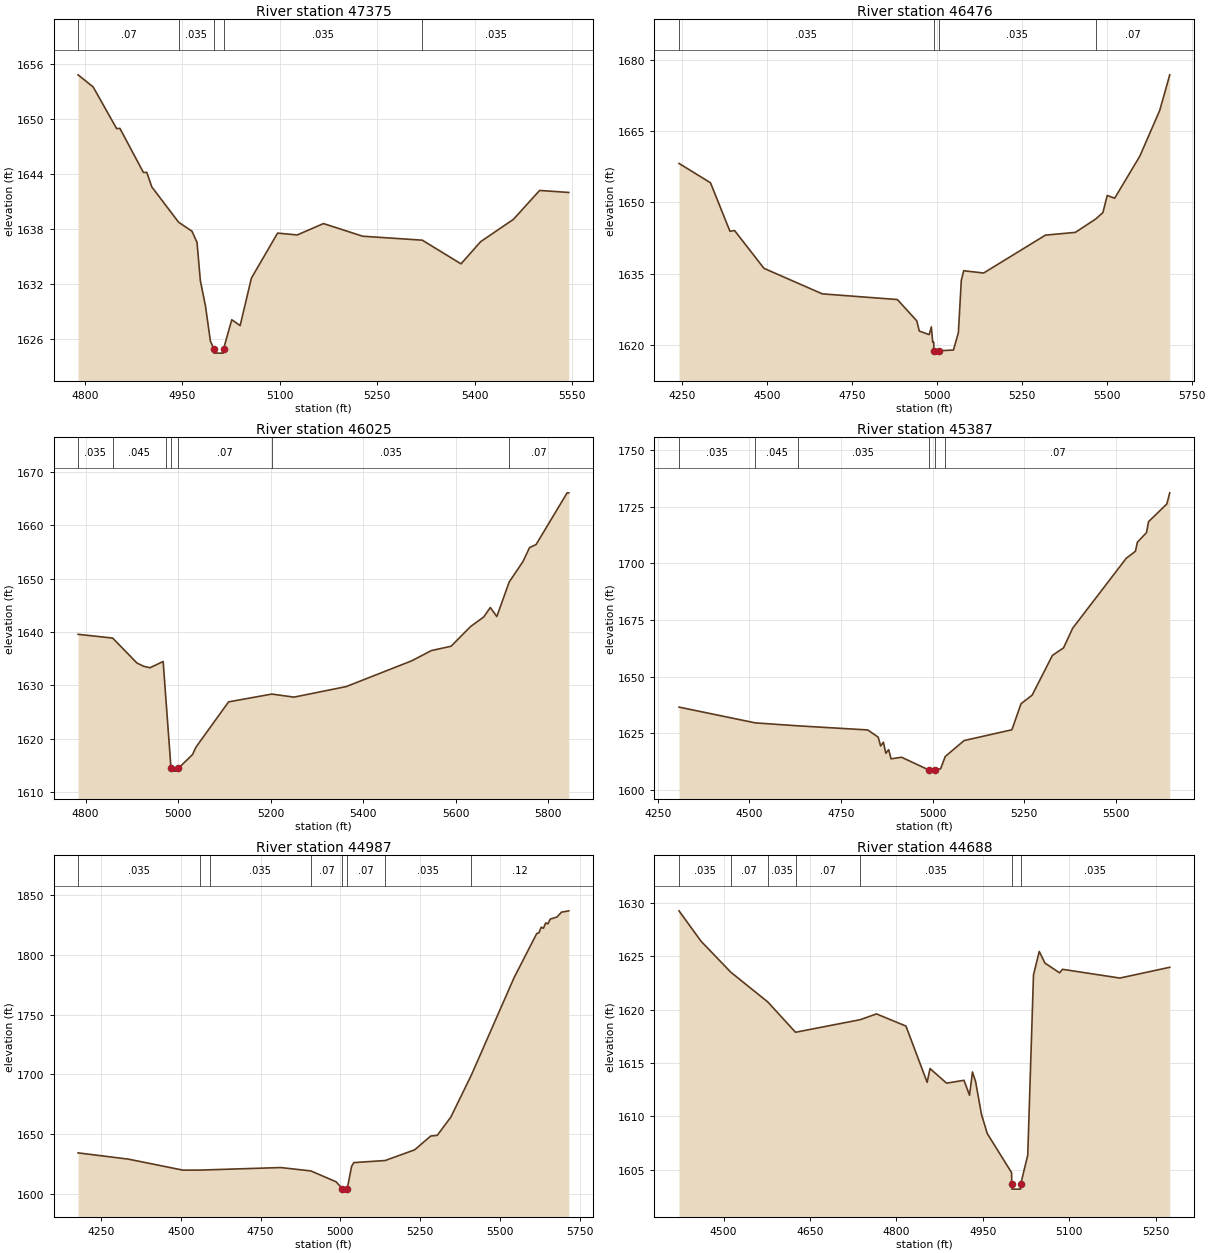
Type RM Length L Ch R = 1 ,47375   ,899,899,899
BEGIN DESCRIPTION:
BIG JOSHUA CREEK 87.0
END DESCRIPTION:
XS GIS Cut Line= 3
      2005475.01     13866975.02        2005425.       13866775.
      2005357.85      13866230.4
#Sta/Elev= 30
  4789.7 1654.82  4812.9  1653.5    4849 1648.96  4854.1 1648.98  4890.2 1644.18
  4895.4 1644.19  4903.1 1642.61  4944.3 1638.76    4965 1637.77  4972.7 1636.55
  4977.8 1632.38  4985.6 1629.66  4993.3 1625.79  4998.3 1624.99  4998.8 1624.49
  5013.2 1624.49  5013.7 1624.99  5026.1 1628.13    5039 1627.49  5056.3 1632.66
  5096.6 1637.57  5126.9 1637.37  5167.2 1638.61  5227.6 1637.23  5319.2  1636.8
  5378.8 1634.22    5409 1636.64  5459.4 1639.07  5499.7 1642.22  5544.6    1642
#Mann= 5 ,-1 , 0
  4789.7     .07       0  4944.3    .035       0  4998.3    .035       0
  5013.7    .035       0  5319.2    .035       0
Bank Sta=4998.3,5013.7
XS Rating Curve= 0 ,0
Exp/Cntr=0.3,0.1

Type RM Length L Ch R = 1 ,46476   ,451,451,451
BEGIN DESCRIPTION:
BIG JOSHUA CREEK 86.0
END DESCRIPTION:
XS GIS Cut Line= 3
        2005475.       13867075.        2006075.       13866625.
      2006674.98     13866275.01
#Sta/Elev= 30
  4240.9  1658.2  4333.6 1654.13  4390.9 1643.94  4404.4  1644.1  4490.9 1636.16
  4662.8 1630.79  4883.6  1629.6  4940.9 1625.12  4948.2 1622.98  4977.4 1622.23
  4983.6 1623.86  4987.8 1620.61  4990.9 1620.61    4991 1618.84  4991.5 1618.34
  5006.5 1618.84  5048.8 1618.99  5063.3 1622.66  5071.9 1633.64    5079 1635.65
  5137.7 1635.17  5319.6 1643.13  5407.7 1643.71  5467.6 1646.52  5488.7 1647.87
  5501.5 1651.46  5523.4 1650.89  5597.5 1659.73  5656.2 1669.37  5685.5 1676.81
#Mann= 4 ,-1 , 0
  4240.9    .035       0    4991    .035       0  5006.5    .035       0
  5467.6     .07       0
Bank Sta=4991,5006.5
XS Rating Curve= 0 ,0
Exp/Cntr=0.3,0.1

Type RM Length L Ch R = 1 ,46025   ,638,638,638
BEGIN DESCRIPTION:
BIG JOSHUA CREEK 85.0
END DESCRIPTION:
XS GIS Cut Line= 3
      2005924.99     13867175.01        2006075.       13867025.
      2006675.02     13866424.98
#Sta/Elev= 30
  4783.6 1639.55  4858.3 1638.85  4910.9 1634.17    4925 1633.57  4939.2 1633.29
  4967.5 1634.46  4972.8 1628.15  4984.5 1614.41    4985 1613.91  4999.5 1613.91
    5000 1614.41  5031.1 1617.03  5038.2 1618.38  5108.9 1626.89  5202.3 1628.35
  5250.3 1627.78  5363.4 1629.76  5504.9 1634.59  5547.3 1636.51  5589.7 1637.31
  5632.1 1641.02  5660.4  1642.8  5674.6 1644.58  5688.7 1642.89  5715.4 1649.35
  5745.3  1653.2  5759.4  1655.8  5773.6 1656.38  5840.7 1666.07  5844.3 1666.07
#Mann= 7 ,-1 , 0
  4783.6    .035       0  4858.3    .045       0  4972.8     .07       0
  4984.5     .05       0    5000     .07       0  5202.3    .035       0
  5715.4     .07       0
Bank Sta=4984.5,5000
XS Rating Curve= 0 ,0
Exp/Cntr=0.3,0.1

Type RM Length L Ch R = 1 ,45387   ,400,400,400
BEGIN DESCRIPTION:
BIG JOSHUA CREEK 84.0
END DESCRIPTION:
XS GIS Cut Line= 3
      2006101.54     13867427.49      2006625.96      13866973.9
      2006851.72     13866369.56
#Sta/Elev= 30
  4308.3 1636.59  4516.6 1629.63  4631.6 1628.35  4823.1 1626.52  4851.6 1623.34
  4858.2 1619.45  4865.8 1621.12  4872.4 1616.23  4880.1 1617.83  4886.7 1613.79
  4915.2 1614.49  4989.9 1608.86  4990.4 1608.36  5005.6 1608.86  5021.8 1609.38
  5034.5 1614.81  5085.9 1621.84  5216.3  1626.6  5241.2 1638.09  5271.5 1641.86
  5326.8 1659.39  5357.1 1662.71  5382.1  1671.4  5528.2 1702.23  5553.2  1705.3
  5558.5  1709.3  5583.5 1713.55  5588.8 1718.33  5638.8 1726.17  5646.8 1731.08
#Mann= 6 ,-1 , 0
  4308.3    .035       0  4516.6    .045       0  4631.6    .035       0
  4989.9    .035       0  5005.6    .035       0  5034.5     .07       0
Bank Sta=4989.9,5005.6
XS Rating Curve= 0 ,0
Exp/Cntr=0.3,0.1

Type RM Length L Ch R = 1 ,44987   ,299,299,299
BEGIN DESCRIPTION:
BIG JOSHUA CREEK 83.0
END DESCRIPTION:
XS GIS Cut Line= 3
      2006324.98     13867475.02      2006985.09     13866984.85
      2007475.54     13866463.06
#Sta/Elev= 30
  4177.8 1634.36  4335.4 1629.12  4506.4 1619.92  4560.2 1619.96  4590.7 1620.21
  4813.1 1622.08  4907.5 1619.25  4986.3 1610.21  5005.9 1604.52  5006.4 1604.02
  5021.6 1604.52  5035.2 1623.03  5042.1 1626.21  5140.5 1627.97  5233.1 1636.94
  5282.9 1648.41  5303.9 1649.08  5346.4 1664.37  5410.8 1699.59  5544.6 1781.04
  5615.5 1817.92  5622.3 1818.53  5629.6 1823.25  5636.5 1822.35  5643.8 1826.87
  5650.6 1826.05  5657.9 1830.02    5679 1831.76  5693.1 1835.84  5716.1 1836.95
#Mann= 8 ,-1 , 0
  4177.8    .035       0  4560.2     .07       0  4590.7    .035       0
  4907.5     .07       0  5005.9     .05       0  5021.6     .07       0
  5140.5    .035       0  5410.8     .12       0
Bank Sta=5005.9,5021.6
XS Rating Curve= 0 ,0
Exp/Cntr=0.3,0.1

Type RM Length L Ch R = 1 ,44688   ,966,966,966
BEGIN DESCRIPTION:
BIG JOSHUA CREEK 82.0
END DESCRIPTION:
XS GIS Cut Line= 4
      2006480.85     13867423.99      2006804.07     13867259.07
      2007016.87     13867231.07      2007291.55     13867227.55
#Sta/Elev= 30
  4422.5 1629.27  4460.8 1626.42  4512.4 1623.52  4576.7 1620.73  4624.8 1617.89
  4737.3 1619.07  4765.4 1619.61  4816.6 1618.47  4853.4  1613.2  4858.4 1614.49
  4887.2 1613.12  4917.4 1613.39    4927 1611.99  4932.1 1614.17  4937.6 1613.26
  4947.7 1610.21  4957.8  1608.4    5000 1604.74  5000.3 1603.69  5000.8 1603.19
  5015.5 1603.19    5016 1603.69  5028.1 1606.37  5038.1 1623.27  5048.1 1625.46
  5058.1 1624.37  5083.4 1623.46  5088.4 1623.79  5188.1 1622.97  5274.7 1623.98
#Mann= 7 ,-1 , 0
  4422.5    .035       0  4512.4     .07       0  4576.7    .035       0
  4624.8     .07       0  4737.3    .035       0  5000.3    .035       0
    5016    .035       0
Bank Sta=5000.3,5016
XS Rating Curve= 0 ,0
Exp/Cntr=0.3,0.1

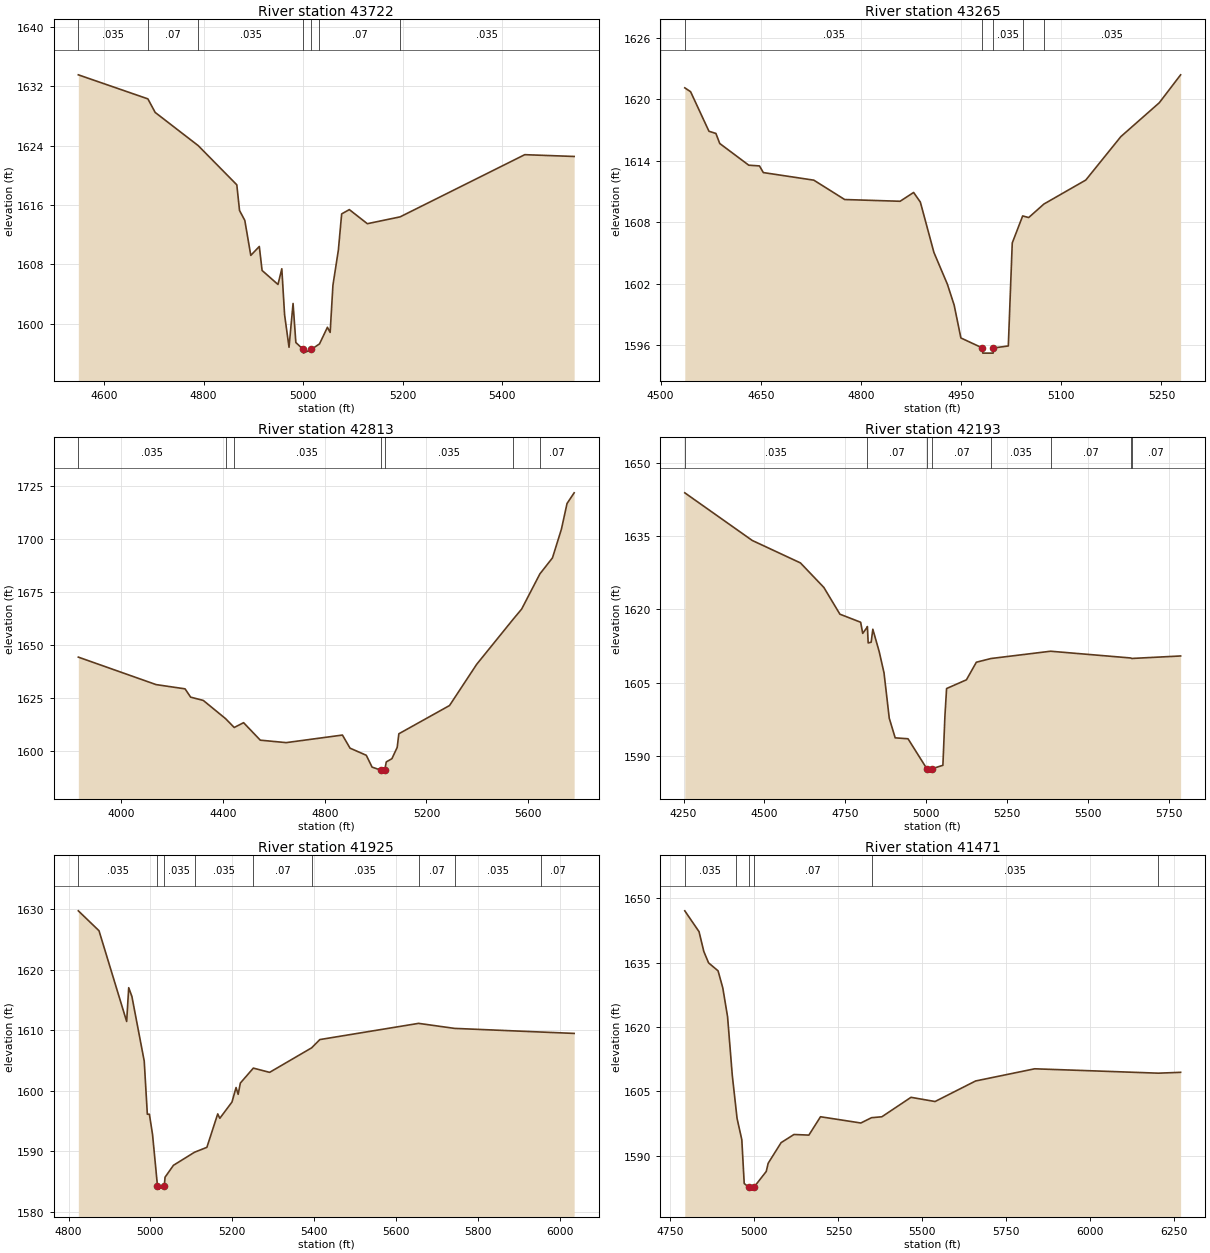
Type RM Length L Ch R = 1 ,43722   ,457,457,457
BEGIN DESCRIPTION:
BIG JOSHUA CREEK 81.0
END DESCRIPTION:
XS GIS Cut Line= 3
      2006623.78     13867968.46        2007025.       13867775.
       2007253.1     13867274.01
#Sta/Elev= 30
  4548.4 1633.54  4688.1  1630.3  4702.8 1628.47  4789.2    1624  4866.7 1618.72
  4872.2 1615.26  4882.8 1613.92  4894.8 1609.21  4911.9 1610.41  4917.5 1607.18
  4949.4 1605.29  4957.1 1607.41  4962.7  1601.2  4971.6 1596.83  4979.7 1602.73
  4985.3 1597.47    5000 1596.54  5000.5 1596.04  5016.2 1596.54  5032.8 1597.28
  5048.7 1599.52  5054.2 1598.83  5059.8  1605.2  5070.7 1609.92  5077.3  1614.8
  5092.7 1615.38  5128.9 1613.48  5194.7  1614.4  5445.1 1622.78  5544.3 1622.54
#Mann= 7 ,-1 , 0
  4548.4    .035       0  4688.1     .07       0  4789.2    .035       0
    5000    .035       0  5016.2    .035       0  5032.8     .07       0
  5194.7    .035       0
Bank Sta=5000,5016.2
XS Rating Curve= 0 ,0
Exp/Cntr=0.3,0.1

Type RM Length L Ch R = 1 ,43265   ,452,452,452
BEGIN DESCRIPTION:
BIG JOSHUA CREEK 80.0
END DESCRIPTION:
XS GIS Cut Line= 4
      2007275.18     13868206.57      2007390.95     13867997.08
        2007425.       13867775.      2007476.44     13867501.42
#Sta/Elev= 30
  4536.3 1621.13    4545 1620.75  4572.5 1616.89  4582.9 1616.68  4588.6  1615.7
  4632.1 1613.58  4648.1 1613.51  4653.9 1612.86  4729.5 1612.12  4775.7 1610.23
  4858.7 1610.06  4878.9 1610.92    4889 1609.98  4909.3 1605.07  4929.5 1601.96
  4939.6 1599.93  4949.7 1596.72    4982 1595.74  4982.5 1595.24    4998 1595.24
  4998.5 1595.74  5020.7 1595.94  5026.6 1605.99  5042.2 1608.63  5051.2 1608.47
    5074 1609.79  5136.7 1612.13  5189.2 1616.37  5246.7 1619.67  5278.7  1622.4
#Mann= 5 ,-1 , 0
  4536.3    .035       0    4982    .035       0  4998.5    .035       0
  5042.2     .07       0    5074    .035       0
Bank Sta=4982,4998.5
XS Rating Curve= 0 ,0
Exp/Cntr=0.3,0.1

Type RM Length L Ch R = 1 ,42813   ,620,620,620
BEGIN DESCRIPTION:
BIG JOSHUA CREEK 79.0
END DESCRIPTION:
XS GIS Cut Line= 3
      2006810.41      13868684.6        2007775.       13868025.
      2008275.02     13867424.98
#Sta/Elev= 30
  3831.2 1644.41    4137 1631.43  4250.8 1629.43  4272.9  1625.5  4322.5 1623.96
  4409.9 1615.38  4444.2 1611.18    4481 1613.45  4546.7 1605.19  4648.3 1604.03
  4869.7  1607.6  4899.5 1601.42  4963.4 1598.06  4986.2 1592.47  5019.4 1591.07
  5019.9 1590.57    5036 1591.07    5042 1594.91  5064.2 1596.45    5085 1601.78
  5091.5 1608.21  5290.7 1621.54  5397.4 1640.99  5541.3 1662.35  5574.4 1667.11
    5646  1683.7  5695.5 1691.27  5730.7 1704.83  5752.8 1716.96  5780.8    1722
#Mann= 7 ,-1 , 0
  3831.2    .035       0  4409.9     .07       0  4444.2    .035       0
  5019.4    .035       0    5036    .035       0  5541.3    .035       0
    5646     .07       0
Bank Sta=5019.4,5036
XS Rating Curve= 0 ,0
Exp/Cntr=0.3,0.1

Type RM Length L Ch R = 1 ,42193   ,268,268,268
BEGIN DESCRIPTION:
BIG JOSHUA CREEK 78.0
END DESCRIPTION:
XS GIS Cut Line= 5
      2006866.82     13868719.33      2007313.86     13868367.77
      2007600.32      13868445.9      2007756.57     13868415.52
      2008034.33     13867990.19
#Sta/Elev= 30
  4253.7 1643.84  4462.1  1634.1  4611.2  1629.5  4683.5 1624.49  4733.2 1619.01
  4797.4 1617.36  4803.7 1615.08  4815.5 1616.16  4818.2 1616.48  4820.6 1613.13
  4829.8 1613.27    4835 1615.93  4854.7 1611.35  4869.6    1607  4885.8 1597.72
  4904.1 1593.71  4943.8 1593.52  5001.9  1587.4  5002.4  1586.9  5018.5  1587.4
  5051.6 1588.09  5057.9 1598.22    5063  1603.8  5124.3 1605.58    5155 1609.18
  5200.2 1609.94  5384.5 1611.43  5632.2 1610.05  5635.2 1609.95  5786.5 1610.46
#Mann= 8 ,-1 , 0
  4253.7    .035       0  4815.5     .07       0  5001.9     .05       0
  5018.5     .07       0  5200.2    .035       0  5384.5     .07       0
  5632.2    .035       0  5635.2     .07       0
Bank Sta=5001.9,5018.5
XS Rating Curve= 0 ,0
Exp/Cntr=0.3,0.1

Type RM Length L Ch R = 1 ,41925   ,454,454,454
BEGIN DESCRIPTION:
BIG JOSHUA CREEK 77.0
END DESCRIPTION:
XS GIS Cut Line= 4
      2007104.76     13868591.85        2007275.       13868575.
      2007786.95      13868467.6      2008047.35     13868020.58
#Sta/Elev= 30
    4824 1629.72  4874.5 1626.43  4942.1 1611.42  4947.1 1617.01  4954.9 1615.56
    4985 1604.88  4992.6 1596.09  4997.6 1596.09  5005.3 1592.76  5017.4  1584.2
  5017.9  1583.7    5034  1584.2  5035.9 1585.67  5056.4 1587.64  5107.9  1589.8
  5138.1 1590.61  5164.6 1596.14  5169.7 1595.41  5199.4  1598.1  5209.4  1600.5
  5214.5 1599.38  5219.9 1601.24  5251.6 1603.71  5291.4 1603.01    5394 1607.06
  5414.1 1608.43  5655.4 1611.11  5743.2 1610.28  5953.5 1609.68  6035.5 1609.45
#Mann= 9 ,-1 , 0
    4824    .035       0  5017.4    .035       0    5034    .035       0
  5107.9    .035       0  5251.6     .07       0    5394    .035       0
  5655.4     .07       0  5743.2    .035       0  5953.5     .07       0
Bank Sta=5017.4,5034
XS Rating Curve= 0 ,0
Exp/Cntr=0.3,0.1

Type RM Length L Ch R = 1 ,41471   ,440,440,440
BEGIN DESCRIPTION:
BIG JOSHUA CREEK 76.0
END DESCRIPTION:
XS GIS Cut Line= 4
        2007175.       13869125.        2007325.       13868975.
      2007656.74      13868801.8       2008073.4     13868016.23
#Sta/Elev= 30
  4792.9 1647.09  4835.3 1642.23  4849.5 1637.62  4863.6 1634.96  4891.9  1633.1
    4906 1629.11  4920.2 1622.39  4934.3 1608.67  4944.4 1601.55  4948.5 1598.66
  4962.6 1593.71  4969.7 1583.51  4982.5 1582.69    4983 1582.19  4999.2 1582.69
  5035.3 1586.31    5041 1588.22  5079.5 1593.03  5117.8 1594.93  5162.2 1594.79
  5196.8 1599.07  5316.8 1597.61  5348.7 1598.85  5379.3 1599.06  5466.1  1603.6
  5537.7 1602.62  5658.3 1607.41  5834.2 1610.25  6202.6 1609.23  6268.5 1609.43
#Mann= 6 ,-1 , 0
  4792.9    .035       0  4944.4     .07       0  4982.5     .05       0
  4999.2     .07       0  5348.7    .035       0  6202.6     .07       0
Bank Sta=4982.5,4999.2
XS Rating Curve= 0 ,0
Exp/Cntr=0.3,0.1

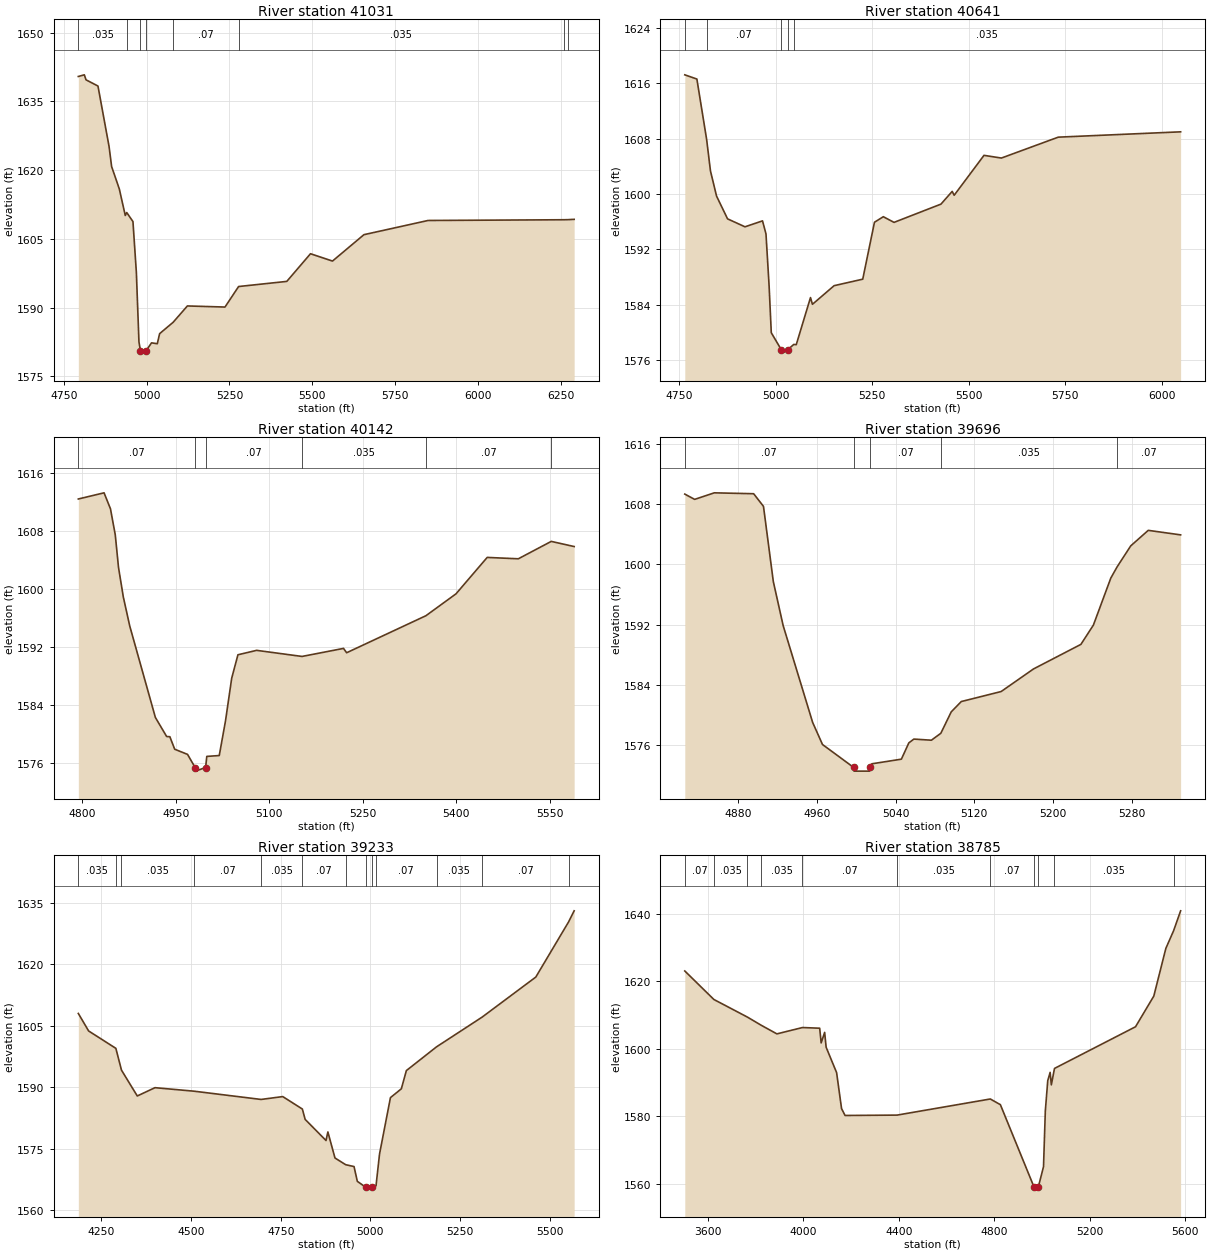
Type RM Length L Ch R = 1 ,41031   ,390,390,390
BEGIN DESCRIPTION:
BIG JOSHUA CREEK 75.0
END DESCRIPTION:
XS GIS Cut Line= 3
        2007575.     13869425.02        2007625.       13869225.
      2008099.46     13868024.86
#Sta/Elev= 30
    4794 1640.45  4812.1 1640.81  4817.2 1639.72  4853.3 1638.36  4886.8 1625.15
  4894.5 1620.78  4917.7  1615.9  4935.7  1610.1  4940.1 1610.74  4958.9 1608.77
  4969.2 1597.66    4977 1582.51  4981.5 1580.55    4982 1580.05  4998.2 1580.55
    5015 1582.29  5032.4 1582.11  5039.4  1584.3  5080.3 1586.79  5123.2 1590.35
  5236.7 1590.11  5277.8 1594.59  5423.3 1595.71  5494.8 1601.75  5561.2 1600.15
  5656.1 1605.91  5849.7 1609.01  6260.3 1609.17  6272.6 1609.19  6290.7 1609.26
#Mann= 8 ,-1 , 0
    4794    .035       0  4940.1     .12       0  4981.5     .05       0
  4998.2     .12       0  5080.3     .07       0  5277.8    .035       0
  6260.3     .07       0  6272.6    .035       0
Bank Sta=4981.5,4998.2
XS Rating Curve= 0 ,0
Exp/Cntr=0.3,0.1

Type RM Length L Ch R = 1 ,40641   ,499,499,499
BEGIN DESCRIPTION:
BIG JOSHUA CREEK 74.0
END DESCRIPTION:
XS GIS Cut Line= 3
      2008175.02     13869175.01      2007956.22      13869070.9
      2008125.49     13868042.24
#Sta/Elev= 30
  4764.5 1617.21  4795.8  1616.6  4821.1 1607.87    4831 1603.32  4846.8 1599.68
  4875.3 1596.39  4920.5 1595.24  4965.9  1596.1  4974.9  1594.2    4983 1586.66
  4988.6 1579.93  5014.5 1577.48    5015 1576.98  5031.3 1577.48    5047 1578.24
  5053.3  1578.2  5090.2 1585.01  5095.3 1584.04  5151.4 1586.73  5225.6 1587.67
    5256  1595.9  5278.9  1596.7  5306.7 1595.88  5428.3 1598.52  5457.4 1600.36
  5462.5  1599.8  5539.8 1605.57  5584.9 1605.18  5732.3  1608.2  6049.3 1608.97
#Mann= 5 ,-1 , 0
  4764.5    .035       0  4821.1     .07       0  5014.5     .05       0
  5031.3     .07       0    5047    .035       0
Bank Sta=5014.5,5031.3
XS Rating Curve= 0 ,0
Exp/Cntr=0.3,0.1

Type RM Length L Ch R = 1 ,40142   ,446,446,446
BEGIN DESCRIPTION:
BIG JOSHUA CREEK 73.0
END DESCRIPTION:
XS GIS Cut Line= 3
      2008375.01     13868975.04        2008325.       13868775.
      2008338.17     13868185.45
#Sta/Elev= 30
  4793.5 1612.36  4834.8 1613.21  4845.1    1611  4852.8 1607.41    4858 1602.92
  4865.7 1598.85    4876 1594.85  4917.2 1582.22  4935.3 1579.59  4940.4 1579.57
  4948.2 1577.84  4968.8 1577.13    4981 1575.32  4981.5 1574.82  4997.8 1575.32
  4999.7 1576.85  5019.7 1576.97  5029.7 1581.73  5039.7 1587.64  5049.7 1590.87
  5079.7 1591.48  5152.6 1590.64  5219.2 1591.75  5224.2 1591.15  5351.5 1596.26
  5399.8 1599.28  5449.8  1604.3  5499.8 1604.11  5552.6 1606.51  5589.4  1605.8
#Mann= 6 ,-1 , 0
  4793.5     .07       0    4981     .05       0  4997.8     .07       0
  5152.6    .035       0  5351.5     .07       0  5552.6    .035       0
Bank Sta=4981,4997.8
XS Rating Curve= 0 ,0
Exp/Cntr=0.3,0.1

Type RM Length L Ch R = 1 ,39696   ,463,463,463
BEGIN DESCRIPTION:
BIG JOSHUA CREEK 72.0
END DESCRIPTION:
XS GIS Cut Line= 3
        2008675.     13868724.97        2008675.       13868525.
        2008625.     13868225.01
#Sta/Elev= 30
  4825.6 1609.35  4835.6 1608.65  4855.6 1609.52  4895.6  1609.4  4905.6 1607.72
  4915.6 1597.72  4925.6 1591.87  4955.6 1578.99  4965.6 1576.06  4997.2 1573.02
  4997.7 1572.52  5013.5 1572.52    5014 1573.02  5015.6 1573.49  5045.8 1574.11
  5053.4 1576.28  5058.5 1576.78  5076.3 1576.63  5085.9 1577.55  5096.5  1580.4
  5106.7 1581.77  5147.2  1583.1  5180.2 1586.11  5228.3 1589.37    5241 1591.93
  5258.7 1598.18  5265.1 1599.67    5279 1602.47  5296.8 1604.53  5329.7 1603.93
#Mann= 5 ,-1 , 0
  4825.6     .07       0  4997.2     .05       0    5014     .07       0
  5085.9    .035       0  5265.1     .07       0
Bank Sta=4997.2,5014
XS Rating Curve= 0 ,0
Exp/Cntr=0.3,0.1

Type RM Length L Ch R = 1 ,39233   ,448,448,448
BEGIN DESCRIPTION:
BIG JOSHUA CREEK 71.0
END DESCRIPTION:
XS GIS Cut Line= 3
      2008750.86     13869013.07        2008975.       13868225.
      2008885.11     13867669.45
#Sta/Elev= 30
  4185.9 1608.02  4214.6 1603.75  4290.5 1599.51  4306.2 1594.19  4350.2 1587.89
  4399.6 1589.91  4508.9 1589.05  4695.4 1587.04  4755.7 1587.74  4810.4  1584.7
  4818.1 1582.18  4876.3 1577.02  4881.5 1579.11  4901.3 1572.76  4931.1 1571.12
  4954.4 1570.67  4963.6 1567.06  4986.4 1565.66  4986.9 1565.16  5003.3 1565.66
  5015.7 1565.98  5025.5 1573.73  5055.9 1587.48  5086.3 1589.64  5100.3 1594.08
  5184.3 1599.87  5311.5 1607.13  5461.1  1616.9  5552.3 1630.33    5568 1633.06
#Mann= 13 ,-1 , 0
  4185.9    .035       0  4290.5     .07       0  4306.2    .035       0
  4508.9     .07       0  4695.4    .035       0  4810.4     .07       0
  4931.1    .063       0  4986.4     .05       0  5003.3    .063       0
  5015.7     .07       0  5184.3    .035       0  5311.5     .07       0
  5552.3     .12       0
Bank Sta=4986.4,5003.3
XS Rating Curve= 0 ,0
Exp/Cntr=0.3,0.1

Type RM Length L Ch R = 1 ,38785   ,464,464,464
BEGIN DESCRIPTION:
BIG JOSHUA CREEK 70.0
END DESCRIPTION:
XS GIS Cut Line= 3
      2008479.99     13869479.86        2009375.       13868275.
      2009293.03     13867703.76
#Sta/Elev= 30
  3503.4 1623.06  3625.2 1614.62  3765.4 1609.42  3824.1 1606.97  3889.3 1604.43
  3996.6 1606.31  4068.7 1606.11  4074.9 1601.76  4089.5 1604.87  4095.8 1600.47
  4139.6 1592.97  4160.4 1582.31  4175.1 1580.27  4393.1 1580.38  4783.8 1585.15
    4826 1583.47  4967.7 1558.96  4968.2 1558.46  4984.6 1558.96  5006.8 1565.12
  5014.4 1581.64  5024.5 1590.57  5034.5 1593.03  5039.6 1589.34  5052.8  1594.2
  5392.4 1606.54    5469 1615.62  5519.5 1629.75    5552 1634.98  5581.4 1640.87
#Mann= 11 ,-1 , 0
  3503.4     .07       0  3625.2    .035       0  3765.4     .07       0
  3824.1    .035       0  3996.6     .07       0  4393.1    .035       0
  4783.8     .07       0  4967.7     .05       0  4984.6     .07       0
  5052.8    .035       0    5552     .12       0
Bank Sta=4967.7,4984.6
XS Rating Curve= 0 ,0
Exp/Cntr=0.3,0.1

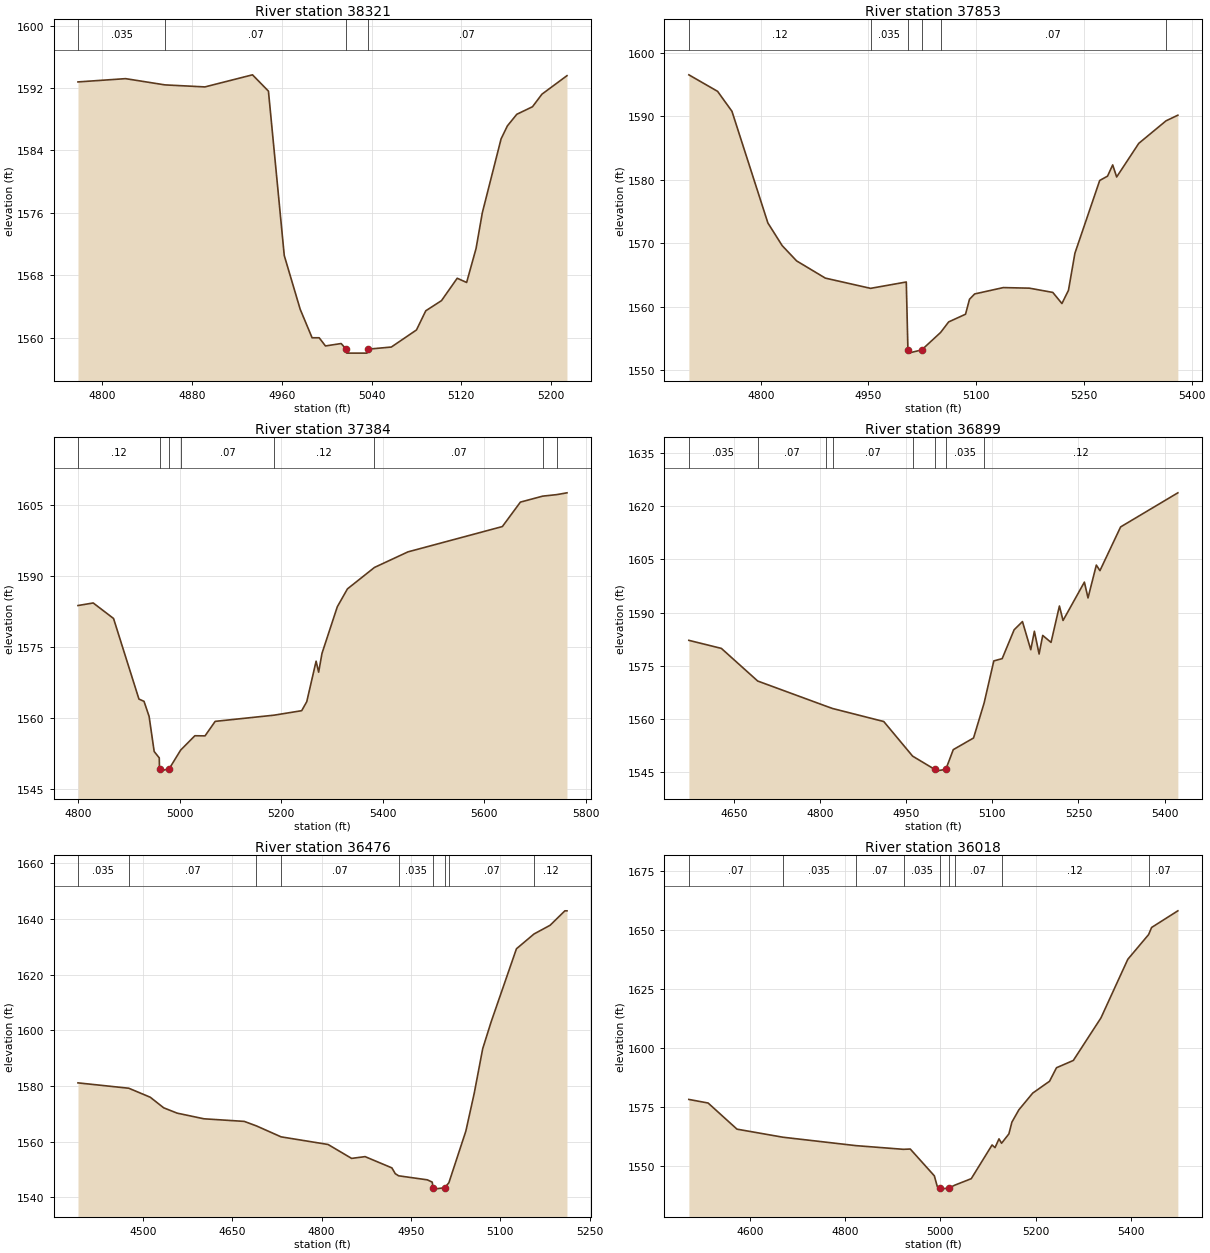
Type RM Length L Ch R = 1 ,38321   ,468,468,468
BEGIN DESCRIPTION:
BIG JOSHUA CREEK 69.0
END DESCRIPTION:
XS GIS Cut Line= 3
      2009325.01     13868824.99        2009475.       13868675.
      2009674.98     13868575.01
#Sta/Elev= 30
  4778.4 1592.77  4820.8 1593.19  4855.9 1592.39  4891.5 1592.13  4933.9 1593.68
  4948.1 1591.59  4962.2 1570.51  4976.4 1563.62    4987 1559.97  4993.3 1559.97
  4998.9 1558.92  5012.9 1559.23  5017.4  1558.5  5017.9    1558  5035.9    1558
  5036.4  1558.5  5057.6 1558.78    5080 1560.97  5088.3 1563.43  5102.3 1564.73
  5116.3  1567.6  5124.7 1567.06  5133.1 1571.42  5138.7 1576.01  5155.4 1585.47
    5161 1587.13  5169.4 1588.62  5183.4 1589.59  5191.8  1591.2  5214.1 1593.57
#Mann= 4 ,-1 , 0
  4778.4    .035       0  4855.9     .07       0  5017.4     .05       0
  5036.4     .07       0
Bank Sta=5017.4,5036.4
XS Rating Curve= 0 ,0
Exp/Cntr=0.3,0.1

Type RM Length L Ch R = 1 ,37853   ,469,469,469
BEGIN DESCRIPTION:
BIG JOSHUA CREEK 68.0
END DESCRIPTION:
XS GIS Cut Line= 3
        2009675.       13869375.        2009675.       13869075.
        2009825.     13868724.99
#Sta/Elev= 30
    4700  1596.5    4740  1593.9    4760 1590.76    4810  1573.2    4830 1569.62
    4850 1567.23    4890 1564.52    4953 1562.91  5002.7 1563.91    5005 1553.22
  5005.5 1552.72  5024.1 1553.22  5050.4 1555.96  5061.7 1557.63  5085.2 1558.84
  5090.7 1561.19  5097.9 1562.03  5137.8 1563.03  5174.1 1562.94  5206.7 1562.27
  5219.4 1560.52  5228.5  1562.6  5237.5 1568.44    5272 1579.88  5282.9 1580.56
  5290.1 1582.33  5295.6 1580.43  5326.4 1585.72  5364.3 1589.26  5380.8 1590.15
#Mann= 6 ,-1 , 0
    4700     .12       0    4953    .035       0    5005    .035       0
  5024.1    .035       0  5050.4     .07       0  5364.3     .12       0
Bank Sta=5005,5024.1
XS Rating Curve= 0 ,0
Exp/Cntr=0.3,0.1

Type RM Length L Ch R = 1 ,37384   ,485,485,485
BEGIN DESCRIPTION:
BIG JOSHUA CREEK 67.0
END DESCRIPTION:
XS GIS Cut Line= 3
        2010125.     13869325.02        2010125.       13869125.
      2010082.96     13868363.48
#Sta/Elev= 30
    4800 1583.75    4830 1584.29    4870 1581.02    4920 1564.03    4930 1563.55
    4940 1560.39    4950 1552.98    4960 1551.63  4960.5 1549.34    4961 1548.84
  4979.6 1549.34  5002.1 1553.27  5030.1  1556.3  5050.1 1556.27  5070.1 1559.33
  5186.3 1560.64  5240.4 1561.58  5250.4 1563.48  5268.8 1572.02  5273.8 1569.71
  5280.4 1573.67  5310.5 1583.48  5330.5 1587.26  5383.7 1591.78  5449.6 1595.06
  5635.5  1600.4    5671 1605.55  5714.8 1606.81  5742.5 1607.13  5762.7 1607.51
#Mann= 8 ,-1 , 0
    4800     .12       0  4960.5     .05       0  4979.6     .12       0
  5002.1     .07       0  5186.3     .12       0  5383.7     .07       0
  5714.8     .12       0  5742.5     .07       0
Bank Sta=4960.5,4979.6
XS Rating Curve= 0 ,0
Exp/Cntr=0.3,0.1

Type RM Length L Ch R = 1 ,36899   ,423,423,423
BEGIN DESCRIPTION:
BIG JOSHUA CREEK 66.0
END DESCRIPTION:
XS GIS Cut Line= 3
      2010274.97     13869425.03        2010575.       13869125.
      2010835.38     13868785.95
#Sta/Elev= 30
  4571.3 1582.14  4627.9 1579.87  4691.2 1570.65  4810.3 1563.55  4821.9 1562.88
  4910.8 1559.21  4961.1 1549.43  4999.5  1545.7    5000  1545.2  5018.9  1545.7
  5031.9 1551.27  5067.2 1554.56  5085.7 1564.49  5102.5 1576.33  5117.1 1576.98
  5137.9 1585.12  5152.4 1587.44  5166.9 1579.49  5173.2 1584.71  5181.4 1578.28
  5187.7 1583.53  5202.2 1581.56  5216.8 1591.84  5223.1 1587.75  5260.3 1598.59
  5266.6 1594.12  5281.1  1603.4  5287.4 1601.83  5323.4 1614.18  5423.1 1623.81
#Mann= 8 ,-1 , 0
  4571.3    .035       0  4691.2     .07       0  4810.3     .12       0
  4821.9     .07       0  4961.1    .035       0  4999.5    .035       0
  5018.9    .035       0  5085.7     .12       0
Bank Sta=4999.5,5018.9
XS Rating Curve= 0 ,0
Exp/Cntr=0.3,0.1

Type RM Length L Ch R = 1 ,36476   ,458,458,458
BEGIN DESCRIPTION:
BIG JOSHUA CREEK 65.0
END DESCRIPTION:
XS GIS Cut Line= 3
       2010378.1     13869591.73        2010925.       13869325.
      2011074.99     13869175.01
#Sta/Elev= 30
  4391.3  1581.1  4476.6 1579.17  4512.6 1575.94  4535.1 1572.14  4557.6 1570.23
  4602.7 1568.19  4670.3 1567.26  4690.7 1565.64  4732.2  1561.7    4811 1558.96
  4850.5 1553.96  4873.1  1554.6  4918.1 1550.55  4923.7 1548.49  4929.3 1547.71
  4977.5 1546.26  4985.7 1545.45  4987.3 1543.42  4987.8 1542.92  5006.7 1543.42
  5013.7  1545.2  5042.2 1563.77  5056.3  1577.4  5070.5 1593.39  5084.6    1603
  5127.1 1629.28  5156.6  1634.6  5183.6 1637.73  5208.4 1642.92  5211.9 1642.92
#Mann= 9 ,-1 , 0
  4391.3    .035       0  4476.6     .07       0  4690.7    .035       0
  4732.2     .07       0  4929.3    .035       0  4987.3    .035       0
  5006.7    .035       0  5013.7     .07       0  5156.6     .12       0
Bank Sta=4987.3,5006.7
XS Rating Curve= 0 ,0
Exp/Cntr=0.3,0.1

Type RM Length L Ch R = 1 ,36018   ,393,393,393
BEGIN DESCRIPTION:
BIG JOSHUA CREEK 64.0
END DESCRIPTION:
XS GIS Cut Line= 3
      2010575.01       13869775.      2011092.36     13869701.04
      2011493.52     13869396.44
#Sta/Elev= 30
    4472 1578.02  4512.4  1576.5    4573 1565.42  4669.5    1562  4822.5 1558.44
  4922.5 1556.87  4936.7    1557  4987.2 1545.64  4993.4 1541.12  4998.8  1540.5
  4999.3    1540  5018.2  1540.5    5030 1541.67  5064.7 1544.43  5108.4 1558.72
  5114.6 1557.59  5122.9 1561.31  5128.3 1559.44  5143.7 1563.42    5150  1568.4
  5164.6 1573.61  5193.7 1580.71    5229 1585.73  5243.6 1591.46  5278.9 1594.54
  5336.9 1612.58  5393.3 1637.43  5436.9 1647.89  5443.2 1650.91  5498.3 1657.97
#Mann= 9 ,-1 , 0
    4472     .07       0  4669.5    .035       0  4822.5     .07       0
  4922.5    .035       0  4998.8    .035       0  5018.2    .035       0
    5030     .07       0  5128.3     .12       0  5436.9     .07       0
Bank Sta=4998.8,5018.2
XS Rating Curve= 0 ,0
Exp/Cntr=0.3,0.1

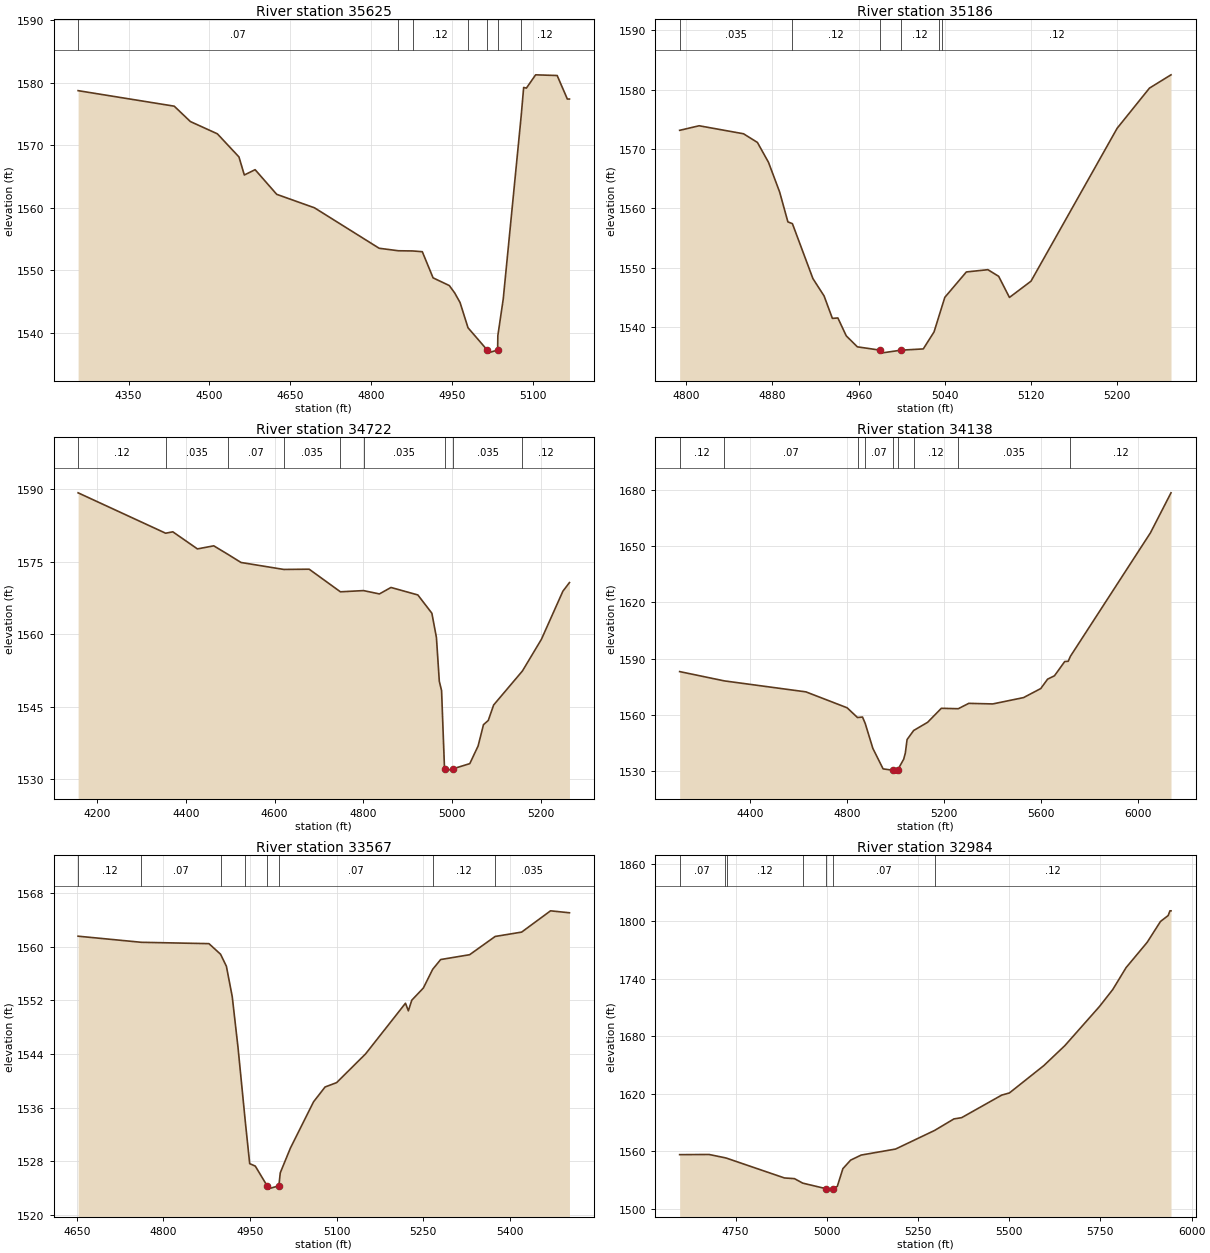
Type RM Length L Ch R = 1 ,35625   ,439,439,439
BEGIN DESCRIPTION:
BIG JOSHUA CREEK 63.0
END DESCRIPTION:
XS GIS Cut Line= 3
      2010386.75     13870056.14        2011125.       13870025.
      2011297.74     13870015.49
#Sta/Elev= 30
  4256.3 1578.74  4434.7 1576.26  4464.7  1573.8  4514.8 1571.84  4554.8 1568.15
  4564.8 1565.26  4584.8 1566.11  4624.9 1562.17  4694.9 1560.02    4815 1553.55
  4850.8 1553.15  4877.2 1553.12  4895.1    1553  4915.1 1548.82  4945.2 1547.59
  4955.2 1546.41  4965.2 1544.87  4979.9 1540.85  5015.5 1537.29    5016 1536.79
  5034.9 1537.29  5035.3 1539.59  5045.3 1545.44  5078.7 1574.79  5083.2 1579.25
  5088.3 1579.15  5105.4 1581.27  5145.4 1581.16  5164.3  1577.4  5168.2  1577.4
#Mann= 7 ,-1 , 0
  4256.3     .07       0  4850.8    .035       0  4877.2     .12       0
  4979.9    .035       0  5015.5    .035       0  5034.9    .035       0
  5078.7     .12       0
Bank Sta=5015.5,5034.9
XS Rating Curve= 0 ,0
Exp/Cntr=0.3,0.1

Type RM Length L Ch R = 1 ,35186   ,464,464,464
BEGIN DESCRIPTION:
BIG JOSHUA CREEK 62.0
END DESCRIPTION:
XS GIS Cut Line= 3
      2010824.95     13870374.99        2011025.       13870425.
        2011275.       13870425.
#Sta/Elev= 30
  4793.8 1573.14  4811.9 1573.91  4853.1 1572.56    4866  1571.1  4876.3 1567.74
  4886.6 1562.76  4894.3  1557.7  4898.5  1557.4  4917.5 1548.15  4927.9 1545.21
  4935.6 1541.43  4940.7  1541.5  4948.5 1538.48  4958.8 1536.63  4979.9 1536.07
  4980.4 1535.57  4999.4 1536.07    5020 1536.28    5030 1539.15  5034.9 1542.01
  5037.3 1543.41    5040 1544.98    5060 1549.26    5080 1549.64    5090 1548.52
    5100 1544.96    5120  1547.7    5200 1573.49    5230 1580.26    5250  1582.5
#Mann= 6 ,-1 , 0
  4793.8    .035       0  4898.5     .12       0  4979.9     .05       0
  4999.4     .12       0  5034.9    .035       0  5037.3     .12       0
Bank Sta=4979.9,4999.4
XS Rating Curve= 0 ,0
Exp/Cntr=0.3,0.1

Type RM Length L Ch R = 1 ,34722   ,584,584,584
BEGIN DESCRIPTION:
BIG JOSHUA CREEK 61.0
END DESCRIPTION:
XS GIS Cut Line= 3
      2010256.55     13871058.75        2011075.       13870875.
      2011325.01     13870774.99
#Sta/Elev= 30
  4156.9  1589.3  4354.3 1580.94  4370.5 1581.23    4426 1577.69  4462.8 1578.33
  4495.4 1576.53  4524.3 1574.88  4620.8 1573.44    4678 1573.49  4748.5 1568.81
  4800.6 1569.06  4836.4 1568.37  4862.5 1569.71  4923.1 1568.16  4954.7 1564.38
    4965 1559.35  4971.5 1550.27  4976.6 1548.36  4983.2 1532.19  4983.7 1531.69
  5003.1 1532.19  5040.2 1533.24    5059  1536.9  5071.1 1541.31  5081.9 1542.18
    5094 1545.38  5158.9 1552.42  5201.7 1558.97  5250.2 1568.94    5265 1570.72
#Mann= 9 ,-1 , 0
  4156.9     .12       0  4354.3    .035       0  4495.4     .07       0
  4620.8    .035       0  4748.5     .07       0  4800.6    .035       0
  4983.2    .035       0  5003.1    .035       0  5158.9     .12       0
Bank Sta=4983.2,5003.1
XS Rating Curve= 0 ,0
Exp/Cntr=0.3,0.1

Type RM Length L Ch R = 1 ,34138   ,571,571,571
BEGIN DESCRIPTION:
BIG JOSHUA CREEK 60.0
END DESCRIPTION:
XS GIS Cut Line= 3
      2010833.86     13871900.73        2011475.       13871275.
      2012275.03     13870474.97
#Sta/Elev= 30
  4108.8 1582.99  4293.2 1578.01  4629.8 1572.13  4799.6 1563.62  4842.6 1558.39
  4863.3 1558.65  4874.7 1555.12  4905.8 1541.91  4948.2 1530.88  4987.4 1530.18
  4987.9 1529.68  5007.8 1530.18    5033 1536.03    5040 1539.37  5047.1 1546.58
  5074.3 1551.44    5132 1555.84  5188.5 1563.33  5258.4 1563.11  5301.7 1565.98
  5400.7 1565.67  5527.9 1569.07  5598.7 1573.91  5626.9 1578.94  5655.2 1580.74
  5697.6 1588.38  5711.8 1588.51  5721.3 1591.24  6051.2 1657.31  6136.1 1678.74
#Mann= 9 ,-1 , 0
  4108.8     .12       0  4293.2     .07       0  4842.6    .035       0
  4874.7     .07       0  4987.4     .05       0  5007.8     .07       0
  5074.3     .12       0  5258.4    .035       0  5721.3     .12       0
Bank Sta=4987.4,5007.8
XS Rating Curve= 0 ,0
Exp/Cntr=0.3,0.1

Type RM Length L Ch R = 1 ,33567   ,583,583,583
BEGIN DESCRIPTION:
BIG JOSHUA CREEK 59.0
END DESCRIPTION:
XS GIS Cut Line= 3
      2011876.85     13871869.67        2011925.       13871525.
      2011958.79     13871022.25
#Sta/Elev= 30
    4652 1561.55  4761.7 1560.64  4878.9 1560.44    4899 1558.86  4909.1 1557.07
  4919.2 1552.56  4929.3 1544.93  4941.9 1533.91  4949.5 1527.66  4959.2 1527.29
  4979.7 1524.36  4980.2 1523.86  5000.1 1524.36  5002.5 1526.29  5020.1 1529.98
  5060.2 1536.87  5080.2 1539.08  5100.2 1539.73  5150.4 1544.01  5219.6 1551.56
  5224.6 1550.43  5230.5 1552.01  5250.6 1553.83  5266.7 1556.61  5280.6 1558.07
  5330.8 1558.79  5375.1 1561.51    5421 1562.16  5471.1 1565.33  5503.9 1565.04
#Mann= 8 ,-1 , 0
    4652     .12       0  4761.7     .07       0    4899    .035       0
  4941.9     .07       0  4979.7     .05       0  5000.1     .07       0
  5266.7     .12       0  5375.1    .035       0
Bank Sta=4979.7,5000.1
XS Rating Curve= 0 ,0
Exp/Cntr=0.3,0.1

Type RM Length L Ch R = 1 ,32984   ,560,560,560
BEGIN DESCRIPTION:
BIG JOSHUA CREEK 58.0
END DESCRIPTION:
XS GIS Cut Line= 3
        2012275.     13871874.99        2012475.       13871525.
        2012975.       13870725.
#Sta/Elev= 30
  4596.9 1556.69  4677.5 1556.86  4720.1 1553.53  4725.6    1553  4884.1 1532.38
  4911.5 1531.68  4934.1    1527  4997.5 1521.24    4998 1520.74  5017.9 1521.24
  5028.9 1523.61  5044.2 1542.07  5065.5 1550.98  5094.3 1556.25  5188.7 1562.54
  5295.5 1581.91  5348.5 1593.94  5369.7 1595.26  5479.4 1618.76  5500.6 1621.03
  5594.9 1649.54  5652.7 1670.43  5747.1 1711.03  5783.6 1728.74  5820.2 1751.64
    5878 1778.02  5914.5 1799.77  5935.7 1806.04  5940.5  1810.9  5943.4  1810.9
#Mann= 7 ,-1 , 0
  4596.9     .07       0  4720.1    .035       0  4725.6     .12       0
  4934.1     .07       0  4997.5     .05       0  5017.9     .07       0
  5295.5     .12       0
Bank Sta=4997.5,5017.9
XS Rating Curve= 0 ,0
Exp/Cntr=0.3,0.1