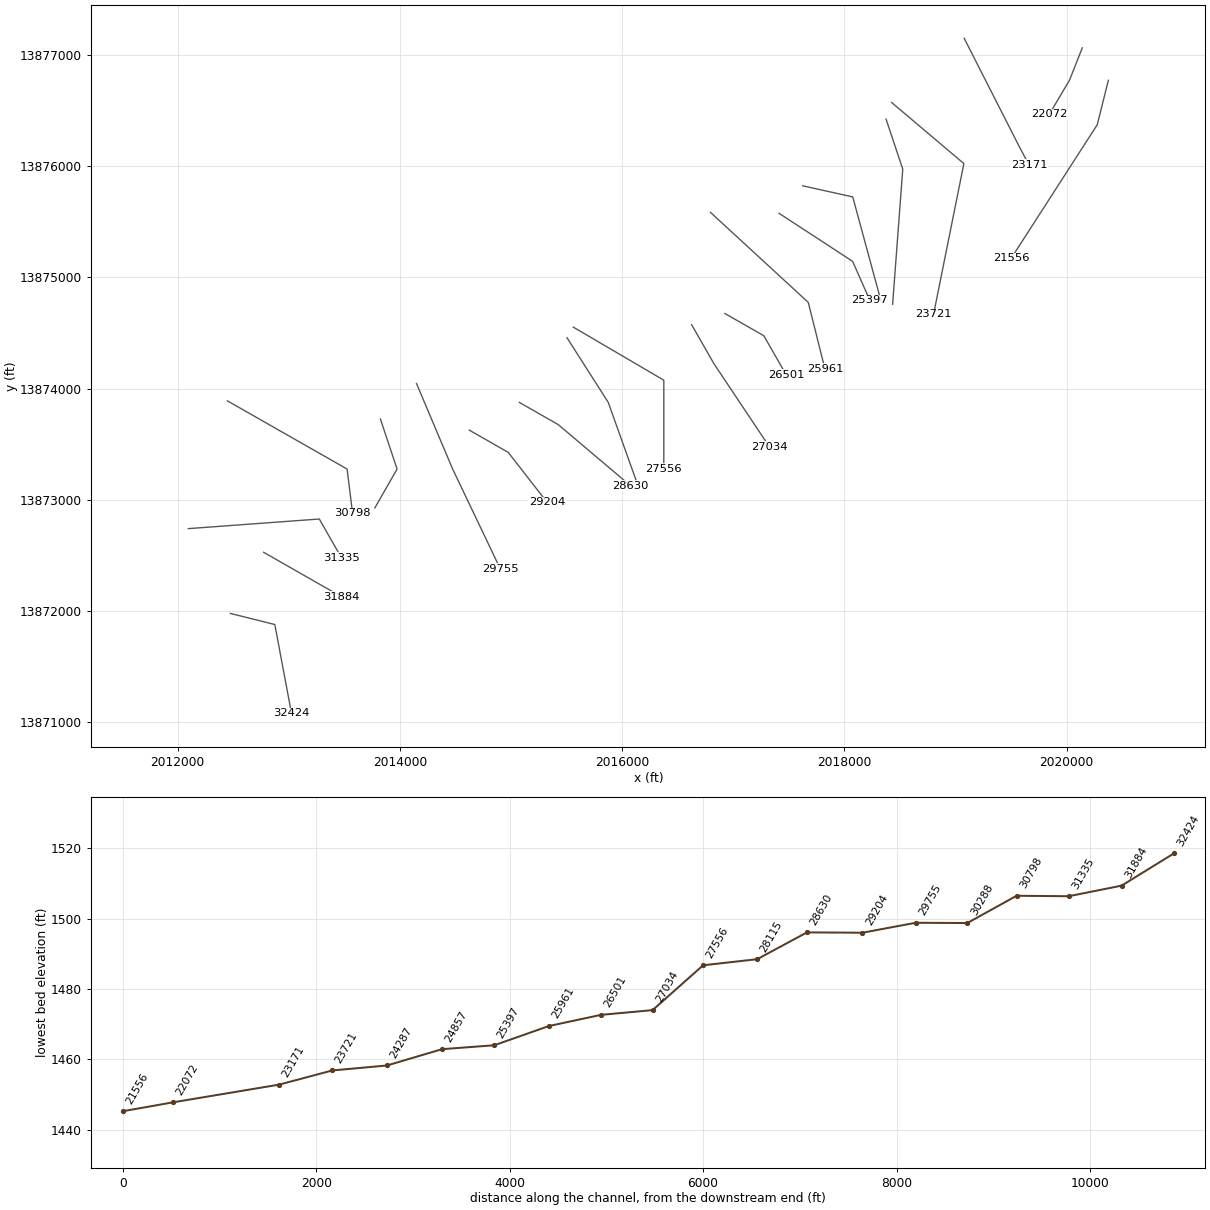
HEC-RAS study BIG JOSHUA CREEK.prj: BIG JOSHUA CREEK Base Level Engineering

--- BIG JOSHUA CREEK.g01 (geometry) --- (continued)

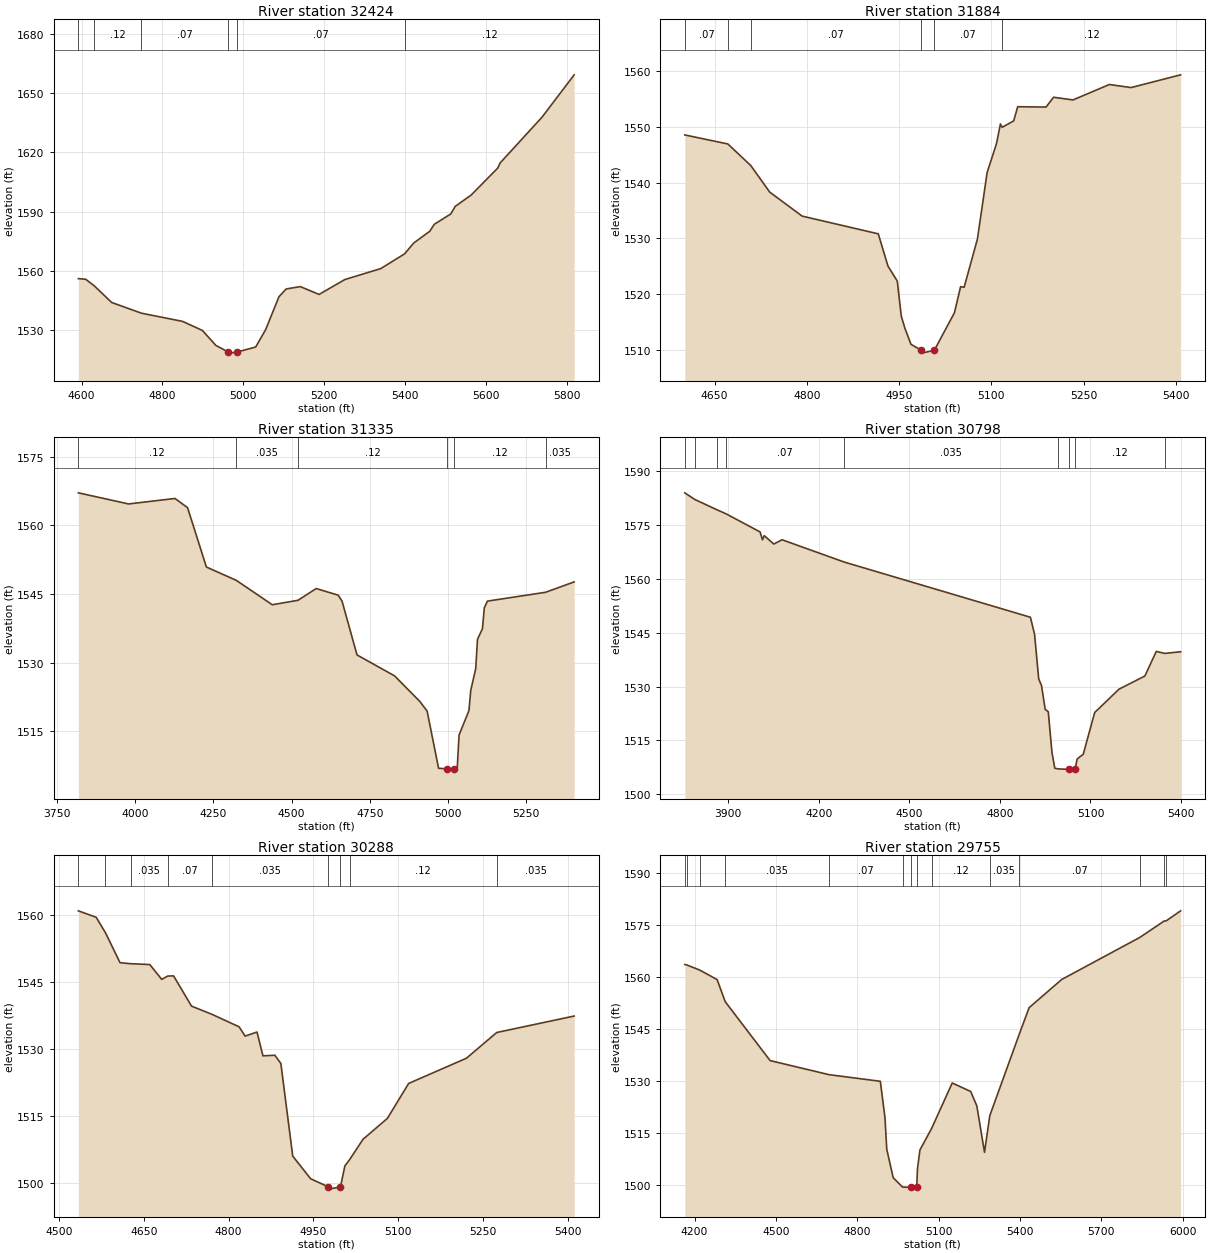
Type RM Length L Ch R = 1 ,32424   ,540,540,540
BEGIN DESCRIPTION:
BIG JOSHUA CREEK 57.0
END DESCRIPTION:
XS GIS Cut Line= 3
      2012474.96     13871975.01        2012875.       13871875.
        2013025.       13871075.
#Sta/Elev= 30
    4592 1556.14  4610.1 1555.84  4631.4 1552.52  4674.5  1544.1  4748.2 1538.68
  4849.7 1534.56  4898.7 1529.98  4932.2 1522.41  4963.2 1519.01  4963.7 1518.51
  4983.7 1519.01  5030.6 1521.59  5055.2 1530.33  5088.3 1547.04  5106.1 1550.93
  5140.9 1552.12  5187.5 1548.17  5251.1 1555.68  5340.1 1561.23    5399 1568.68
  5421.5 1574.14  5461.3 1580.09  5472.4  1583.6  5513.1 1588.83  5524.1 1592.64
  5563.9 1598.44  5629.2 1611.99  5635.2 1614.59  5739.4 1637.86  5818.3 1659.12
#Mann= 6 ,-1 , 0
    4592     .07       0  4631.4     .12       0  4748.2     .07       0
  4963.2     .05       0  4983.7     .07       0    5399     .12       0
Bank Sta=4963.2,4983.7
XS Rating Curve= 0 ,0
Exp/Cntr=0.3,0.1

Type RM Length L Ch R = 1 ,31884   ,549,549,549
BEGIN DESCRIPTION:
BIG JOSHUA CREEK 56.0
END DESCRIPTION:
XS GIS Cut Line= 3
      2012775.01       13872525.        2013125.       13872325.
      2013474.98     13872125.01
#Sta/Elev= 30
  4601.5 1548.55  4671.5 1546.93  4708.8 1543.05  4739.7 1538.27  4792.3 1533.97
  4916.1 1530.78  4931.9 1524.98    4947  1522.3  4953.5    1516  4959.3 1513.85
  4969.3 1510.93  4986.2 1509.85  4986.7 1509.35  5007.2 1509.85  5039.9  1516.6
    5050  1521.3  5055.7 1521.18  5077.3 1529.85  5093.1 1541.81  5108.3 1546.99
  5114.7 1550.52  5117.5 1549.92  5136.3 1551.08  5142.8 1553.62  5188.9 1553.56
  5201.1 1555.32  5232.8 1554.84  5291.8 1557.61  5327.1 1557.06  5407.7 1559.35
#Mann= 6 ,-1 , 0
  4601.5     .07       0  4671.5     .12       0  4708.8     .07       0
  4986.2     .05       0  5007.2     .07       0  5117.5     .12       0
Bank Sta=4986.2,5007.2
XS Rating Curve= 0 ,0
Exp/Cntr=0.3,0.1

Type RM Length L Ch R = 1 ,31335   ,537,537,537
BEGIN DESCRIPTION:
BIG JOSHUA CREEK 55.0
END DESCRIPTION:
XS GIS Cut Line= 3
      2012096.88     13872738.44        2013275.       13872825.
        2013475.       13872475.
#Sta/Elev= 30
  3818.7 1567.13  3979.4  1564.7  4127.6  1565.9  4167.8 1563.88  4227.9 1550.92
  4323.4 1548.01  4438.5 1542.68  4520.5 1543.65  4578.9 1546.22    4649 1544.77
  4661.5 1543.45  4709.2 1531.72  4829.5 1527.13  4909.8 1521.56  4933.3 1519.45
  4969.9 1506.95  4997.3 1506.83  4997.8 1506.33  5018.6 1506.83  5029.5 1507.02
  5035.3 1514.21  5066.9 1519.55  5072.7 1523.98  5088.5 1528.71  5094.3 1535.14
  5110.1 1537.44  5115.9    1542    5126 1543.47  5311.6  1545.4  5403.1 1547.67
#Mann= 6 ,-1 , 0
  3818.7     .12       0  4323.4    .035       0  4520.5     .12       0
  4997.3     .05       0  5018.6     .12       0  5311.6    .035       0
Bank Sta=4997.3,5018.6
XS Rating Curve= 0 ,0
Exp/Cntr=0.3,0.1

Type RM Length L Ch R = 1 ,30798   ,510,510,510
BEGIN DESCRIPTION:
BIG JOSHUA CREEK 54.0
END DESCRIPTION:
XS GIS Cut Line= 3
       2012448.4     13873888.61        2013525.       13873275.
        2013575.       13872875.
#Sta/Elev= 30
  3756.3 1583.97  3789.4 1582.12  3863.4 1579.23  3893.3 1578.11  4005.6 1573.08
  4013.7 1570.89  4019.4 1572.05  4051.2 1569.71  4078.5  1570.9  4284.4 1564.69
  4901.1 1549.32  4914.9 1544.54  4928.5 1532.19  4937.9 1530.26  4950.1 1523.67
  4960.2 1523.01  4972.5 1511.64  4981.8 1507.29  4993.5 1507.08  5027.7 1506.97
  5028.2 1506.47    5049 1506.97  5055.9 1509.85  5076.1 1511.18  5113.9 1522.78
  5194.5 1529.29  5280.2 1532.96    5318 1539.81  5346.6 1539.25  5398.6 1539.72
#Mann= 9 ,-1 , 0
  3756.3    .035       0  3789.4     .12       0  3863.4    .035       0
  3893.3     .07       0  4284.4    .035       0  4993.5     .12       0
  5027.7     .05       0    5049     .12       0  5346.6    .035       0
Bank Sta=5027.7,5049
XS Rating Curve= 0 ,0
Exp/Cntr=0.3,0.1

Type RM Length L Ch R = 1 ,30288   ,533,533,533
BEGIN DESCRIPTION:
BIG JOSHUA CREEK 53.0
END DESCRIPTION:
XS GIS Cut Line= 3
      2013825.01     13873724.97        2013975.       13873275.
      2013775.01     13872925.02
#Sta/Elev= 30
  4534.1 1560.97  4565.7 1559.52  4582.1 1556.07  4607.9 1549.37  4626.8 1549.14
  4660.6 1548.95  4681.6 1545.64  4692.4 1546.38  4702.7 1546.41  4734.4 1539.65
  4770.7 1537.81  4818.7 1535.01  4829.2 1532.95  4850.3 1533.85  4860.8 1528.53
  4881.9 1528.66  4892.5 1526.82  4913.5  1506.1  4945.2 1501.03  4976.7 1499.21
  4977.2 1498.71    4998 1499.21  5005.8 1503.92  5014.1  1505.3  5037.9 1509.86
  5081.1 1514.55  5118.6 1522.35  5220.8 1527.99  5274.5 1533.75  5411.5 1537.43
#Mann= 9 ,-1 , 0
  4534.1    .035       0  4582.1     .07       0  4626.8    .035       0
  4692.4     .07       0  4770.7    .035       0  4976.7    .035       0
    4998     .07       0  5014.1     .12       0  5274.5    .035       0
Bank Sta=4976.7,4998
XS Rating Curve= 0 ,0
Exp/Cntr=0.3,0.1

Type RM Length L Ch R = 1 ,29755   ,551,551,551
BEGIN DESCRIPTION:
BIG JOSHUA CREEK 52.0
END DESCRIPTION:
XS GIS Cut Line= 3
      2014149.81     13874044.83        2014475.       13873275.
      2014902.21     13872379.37
#Sta/Elev= 30
  4164.2 1563.59  4171.3 1563.47  4219.4 1561.99  4283.4 1559.24  4313.2 1552.87
  4478.8 1535.87  4696.4 1531.81  4885.1  1529.9  4902.2 1519.43  4908.8 1510.31
  4932.5 1502.08    4967 1499.38  4997.7 1499.29  4998.2 1498.79  5019.2 1499.29
  5022.1 1504.75  5031.2  1510.1  5073.8 1516.24  5150.2 1529.41  5218.3 1526.96
  5240.9 1522.79  5269.2 1509.41  5288.6 1519.97    5396  1543.2  5433.6 1551.14
  5553.9 1559.28  5841.6  1571.4  5932.5 1576.18  5938.7 1576.17  5992.2 1579.08
#Mann= 14 ,-1 , 0
  4164.2     .07       0  4171.3    .035       0  4219.4     .07       0
  4313.2    .035       0  4696.4     .07       0    4967    .035       0
  4997.7    .035       0  5019.2    .035       0  5073.8     .12       0
  5288.6    .035       0    5396     .07       0  5841.6     .12       0
  5932.5     .07       0  5938.7     .12       0
Bank Sta=4997.7,5019.2
XS Rating Curve= 0 ,0
Exp/Cntr=0.3,0.1

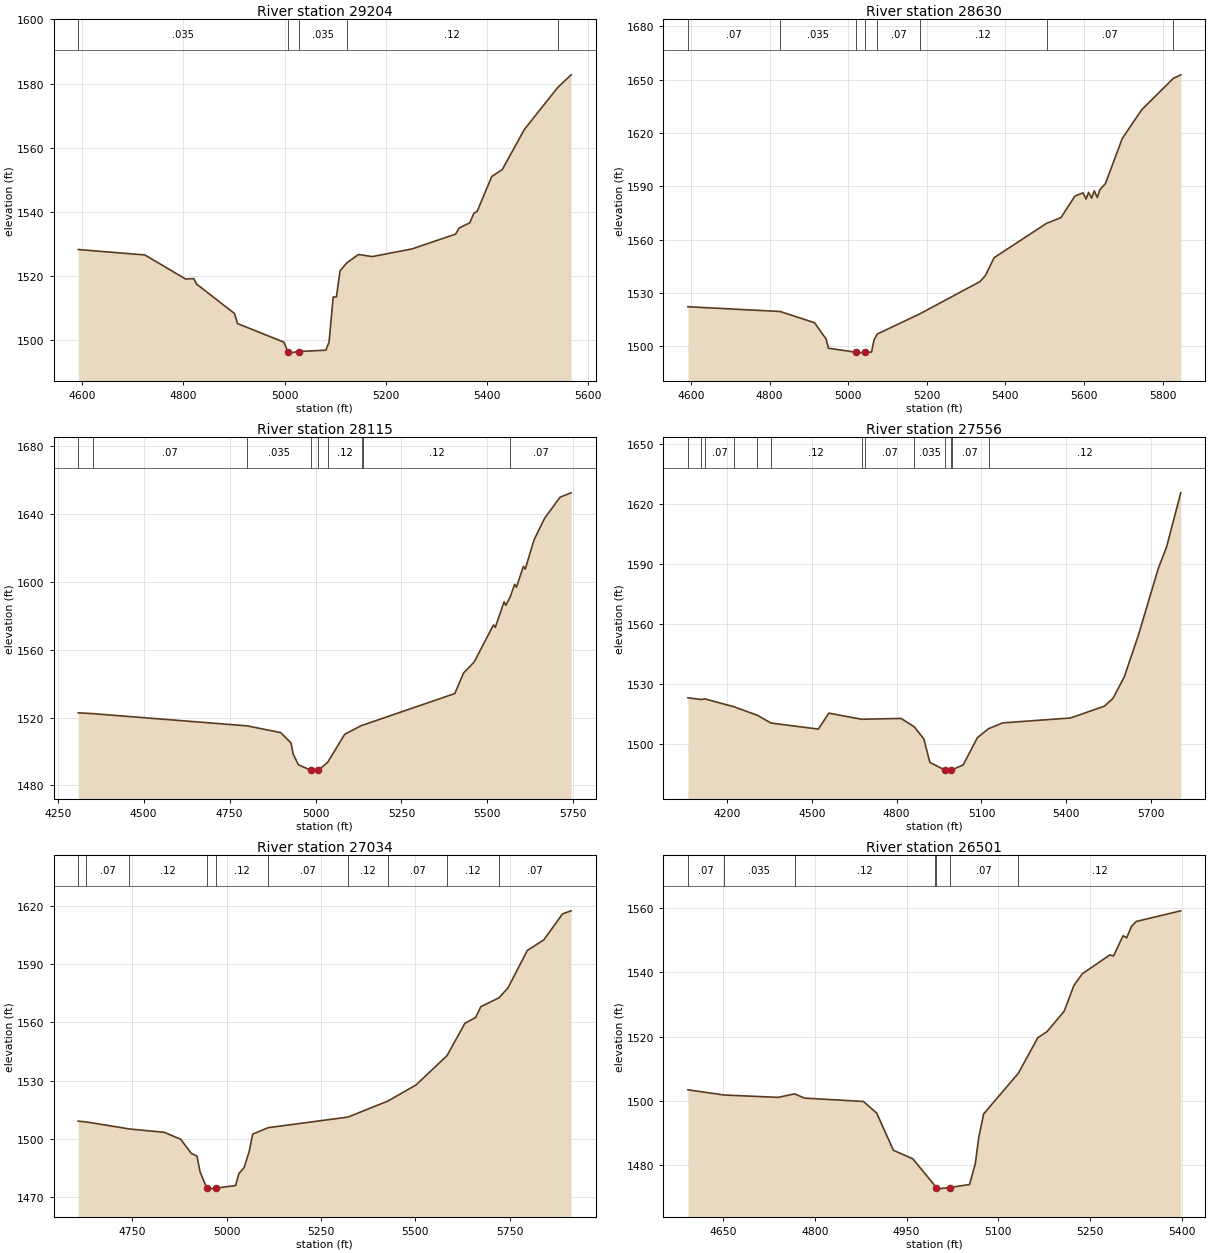
Type RM Length L Ch R = 1 ,29204   ,574,574,574
BEGIN DESCRIPTION:
BIG JOSHUA CREEK 51.0
END DESCRIPTION:
XS GIS Cut Line= 3
      2014625.01     13873624.99        2014975.       13873425.
      2015325.01     13872974.99
#Sta/Elev= 30
  4592.5 1528.26  4724.2 1526.57  4804.8 1519.05  4820.7 1519.21  4826.4 1517.48
  4901.3  1508.3  4907.1 1505.18  4998.8 1499.37  5006.3 1496.46  5006.8 1495.96
  5028.3 1496.46  5081.6 1496.88  5087.9 1499.44    5096 1513.46  5102.4 1513.48
  5109.6 1521.61  5122.6 1524.05  5145.8 1526.71    5173 1526.06  5251.7 1528.45
  5337.7 1533.07  5344.9 1534.99  5365.7 1536.58  5373.9 1539.59  5380.2 1540.14
  5409.1 1551.02    5430 1553.21  5473.4 1565.68  5539.2 1578.76  5565.7 1582.73
#Mann= 5 ,-1 , 0
  4592.5    .035       0  5006.3    .035       0  5028.3    .035       0
  5122.6     .12       0  5539.2     .07       0
Bank Sta=5006.3,5028.3
XS Rating Curve= 0 ,0
Exp/Cntr=0.3,0.1

Type RM Length L Ch R = 1 ,28630   ,515,515,515
BEGIN DESCRIPTION:
BIG JOSHUA CREEK 50.0
END DESCRIPTION:
XS GIS Cut Line= 3
      2015075.03     13873874.98        2015425.       13873675.
      2016074.96     13873125.03
#Sta/Elev= 30
  4591.9 1522.17  4826.9 1519.49  4914.4 1513.15  4943.9 1503.89  4949.6 1498.82
  5019.7 1496.55  5020.2 1496.05  5041.7 1496.55  5059.3 1496.65  5065.8 1503.64
  5073.9 1506.79    5182 1518.14  5335.6 1536.36  5349.3 1539.78  5371.3  1549.8
  5504.8 1569.13  5541.6 1572.36  5576.7 1584.41  5597.6 1586.33  5605.3 1582.84
  5611.8 1586.59  5619.6  1583.3  5626.1 1587.46  5633.9 1583.66  5640.4 1588.07
  5654.7 1591.53  5697.6 1616.95    5747  1633.1  5827.6 1650.77  5846.4 1652.75
#Mann= 8 ,-1 , 0
  4591.9     .07       0  4826.9    .035       0  5019.7    .035       0
  5041.7    .035       0  5073.9     .07       0    5182     .12       0
  5504.8     .07       0  5827.6     .12       0
Bank Sta=5019.7,5041.7
XS Rating Curve= 0 ,0
Exp/Cntr=0.3,0.1

Type RM Length L Ch R = 1 ,28115   ,559,559,559
BEGIN DESCRIPTION:
BIG JOSHUA CREEK 49.0
END DESCRIPTION:
XS GIS Cut Line= 3
      2015503.96     13874457.19        2015875.       13873875.
      2016125.01     13873174.98
#Sta/Elev= 30
  4309.6 1522.84  4352.8 1522.33  4800.9 1515.14  4898.4 1511.18  4928.8 1505.02
  4934.8 1498.59    4950 1492.24    4986 1488.93  4986.5 1488.43  5008.1 1488.93
  5035.3 1493.63  5084.9 1510.17  5134.8 1515.46  5138.6 1515.65  5405.1  1534.2
  5430.6 1546.29  5461.4 1552.79  5517.6 1574.69  5522.9 1573.26  5548.4  1588.3
  5553.7 1586.28  5566.6 1591.41  5579.2 1598.63  5584.5 1596.96  5604.7 1609.27
    5610 1607.65  5635.5 1624.79  5666.3 1637.58  5711.4 1650.08  5743.3 1652.62
#Mann= 9 ,-1 , 0
  4309.6    .035       0  4352.8     .07       0  4800.9    .035       0
    4986    .035       0  5008.1    .035       0  5035.3     .12       0
  5134.8     .07       0  5138.6     .12       0  5566.6     .07       0
Bank Sta=4986,5008.1
XS Rating Curve= 0 ,0
Exp/Cntr=0.3,0.1

Type RM Length L Ch R = 1 ,27556   ,522,522,522
BEGIN DESCRIPTION:
BIG JOSHUA CREEK 48.0
END DESCRIPTION:
XS GIS Cut Line= 3
      2015560.39     13874552.67        2016375.       13874075.
        2016375.     13873275.03
#Sta/Elev= 30
  4061.1  1523.3  4107.3 1522.44  4122.1 1522.71  4223.7 1518.84  4306.8 1514.58
  4355.4 1510.69  4522.7 1507.67  4559.9 1515.63  4676.1 1512.57  4686.4 1512.62
  4815.9 1512.99  4862.5 1508.77    4896 1502.81  4917.5 1491.05  4971.2  1487.2
  4971.7  1486.7  4993.3  1487.2  4995.8 1487.36  5035.4 1489.82  5085.4 1503.34
  5125.1 1507.88  5175.4 1510.77  5415.4 1513.22  5535.4 1519.12  5565.4 1522.99
  5605.4 1533.71  5655.4  1554.5  5725.4 1587.64  5755.4 1598.66  5805.4 1625.55
#Mann= 13 ,-1 , 0
  4061.1    .035       0  4107.3     .12       0  4122.1     .07       0
  4223.7     .12       0  4306.8     .07       0  4355.4     .12       0
  4676.1    .035       0  4686.4     .07       0  4862.5    .035       0
  4971.2     .05       0  4993.3    .035       0  4995.8     .07       0
  5125.1     .12       0
Bank Sta=4971.2,4993.3
XS Rating Curve= 0 ,0
Exp/Cntr=0.3,0.1

Type RM Length L Ch R = 1 ,27034   ,533,533,533
BEGIN DESCRIPTION:
BIG JOSHUA CREEK 47.0
END DESCRIPTION:
XS GIS Cut Line= 3
      2016625.02     13874574.97        2016825.       13874225.
      2017325.02     13873474.97
#Sta/Elev= 30
  4607.4 1509.04  4628.2 1508.65  4743.1    1505  4835.6 1503.26  4878.7 1499.67
  4906.8  1492.4  4921.9 1490.98  4929.9 1482.92  4947.9 1474.45  4948.4 1473.95
  4970.9 1474.45    5024  1475.8    5033 1482.08  5046.5 1485.08  5060.1 1493.42
  5069.1 1502.31  5110.1 1505.66  5321.6 1511.14  5427.3 1519.42  5501.7 1527.74
  5583.6 1542.86  5630.9 1559.51  5659.5 1562.58    5673 1568.11  5721.3 1572.72
  5745.1 1577.86  5796.2 1597.16  5839.8  1602.6  5889.3    1616  5911.9 1617.58
#Mann= 10 ,-1 , 0
  4607.4    .035       0  4628.2     .07       0  4743.1     .12       0
  4947.9     .05       0  4970.9     .12       0  5110.1     .07       0
  5321.6     .12       0  5427.3     .07       0  5583.6     .12       0
  5721.3     .07       0
Bank Sta=4947.9,4970.9
XS Rating Curve= 0 ,0
Exp/Cntr=0.3,0.1

Type RM Length L Ch R = 1 ,26501   ,540,540,540
BEGIN DESCRIPTION:
BIG JOSHUA CREEK 46.0
END DESCRIPTION:
XS GIS Cut Line= 3
      2016924.99     13874675.01        2017275.       13874475.
      2017474.98     13874125.03
#Sta/Elev= 30
  4592.3 1503.48  4651.4 1501.86  4739.9 1501.13  4766.9 1502.21  4783.1  1500.9
  4879.5 1499.85  4901.1 1496.24  4928.5 1484.67  4960.2 1482.04  4996.2 1473.71
  4997.6 1473.11  4998.1 1472.61  5020.7 1473.11    5053 1474.05  5062.4 1480.51
  5068.1 1488.69    5076 1495.96  5132.8 1508.62  5164.6 1519.65  5179.7 1521.55
  5207.8 1527.92  5223.6 1535.85  5237.3 1539.52  5282.6  1545.4  5288.4 1545.06
  5304.2 1551.36    5310  1550.7  5317.9 1554.27  5325.8  1555.8  5398.5  1559.1
#Mann= 7 ,-1 , 0
  4592.3     .07       0  4651.4    .035       0  4766.9     .12       0
  4996.2     .07       0  4997.6     .05       0  5020.7     .07       0
  5132.8     .12       0
Bank Sta=4997.6,5020.7
XS Rating Curve= 0 ,0
Exp/Cntr=0.3,0.1

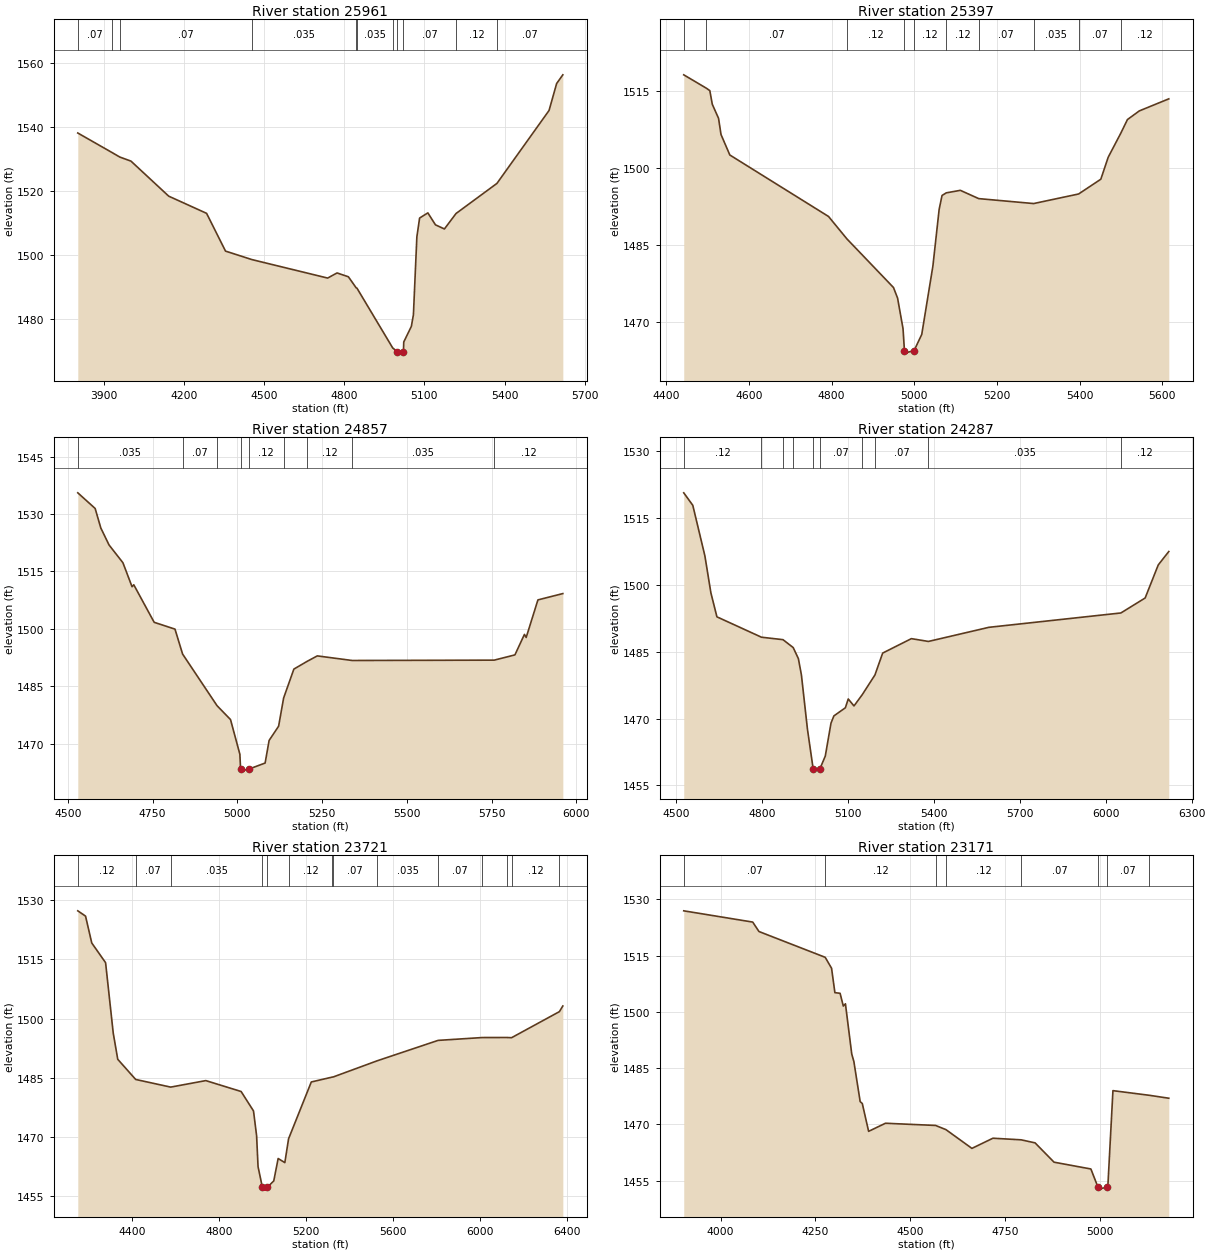
Type RM Length L Ch R = 1 ,25961   ,564,564,564
BEGIN DESCRIPTION:
BIG JOSHUA CREEK 45.0
END DESCRIPTION:
XS GIS Cut Line= 3
      2016794.74     13875585.89        2017675.       13874775.
        2017825.     13874174.99
#Sta/Elev= 30
  3802.9 1538.25  3932.7 1532.06  3959.9 1530.74  4001.9 1529.46  4143.2  1518.5
  4284.9 1513.13  4355.8 1501.32  4454.9 1498.66    4738 1492.89  4773.2 1494.49
  4815.7 1493.29  4844.5 1489.87  4847.9 1489.71  4981.6 1471.03  4998.5 1469.92
    4999 1469.42  5021.6 1469.92  5022.9 1472.91  5051.3 1477.78    5059 1481.42
  5071.9 1505.77  5082.2 1511.66  5113.1 1513.27  5141.5 1509.54    5175 1508.24
  5218.5 1513.08  5371.6 1522.49  5566.6 1545.29    5595 1553.72  5618.2 1556.44
#Mann= 11 ,-1 , 0
  3802.9     .07       0  3932.7    .035       0  3959.9     .07       0
  4454.9    .035       0  4844.5     .12       0  4847.9    .035       0
  4981.6     .07       0  4998.5     .05       0  5021.6     .07       0
  5218.5     .12       0  5371.6     .07       0
Bank Sta=4998.5,5021.6
XS Rating Curve= 0 ,0
Exp/Cntr=0.3,0.1

Type RM Length L Ch R = 1 ,25397   ,540,540,540
BEGIN DESCRIPTION:
BIG JOSHUA CREEK 44.0
END DESCRIPTION:
XS GIS Cut Line= 4
      2017411.59     13875577.41        2017875.       13875275.
       2018074.1      13875144.3      2018228.72     13874794.58
#Sta/Elev= 30
    4442 1518.05  4496.7 1515.45  4505.1 1514.98  4511.1 1512.32  4526.2  1509.6
  4532.2 1506.45  4553.5 1502.47  4792.4 1490.52  4836.8 1486.17  4949.6 1476.71
  4959.5 1474.66  4972.7 1468.71  4976.1 1464.46  4976.6 1463.96  4999.5 1464.46
    5018 1467.59    5045 1480.89  5060.1 1491.89  5067.1  1494.6  5077.3 1495.11
  5111.4  1495.6  5155.9 1493.99  5288.9 1493.03  5397.6 1494.89  5451.4 1497.76
  5469.3 1502.04  5499.4 1506.65  5515.9 1509.36  5544.6 1511.04  5615.9 1513.38
#Mann= 10 ,-1 , 0
    4442    .035       0  4496.7     .07       0  4836.8     .12       0
  4976.1     .05       0  4999.5     .12       0  5077.3     .12       0
  5155.9     .07       0  5288.9    .035       0  5397.6     .07       0
  5499.4     .12       0
Bank Sta=4976.1,4999.5
XS Rating Curve= 0 ,0
Exp/Cntr=0.3,0.1

Type RM Length L Ch R = 1 ,24857   ,570,570,570
BEGIN DESCRIPTION:
BIG JOSHUA CREEK 43.0
END DESCRIPTION:
XS GIS Cut Line= 3
        2017625.       13875825.        2018075.       13875725.
      2018329.08     13874788.54
#Sta/Elev= 30
    4529 1535.52  4580.2 1531.44  4596.9 1526.35  4621.2 1521.91  4662.2 1517.26
  4689.1    1511  4694.2 1511.51  4754.4 1501.71  4815.8 1499.93  4838.3 1493.42
    4940 1479.93  4979.7 1476.31  5007.3 1467.25  5009.4 1463.35  5009.9 1462.85
  5032.8 1463.35  5081.8 1464.96  5093.6 1470.87  5121.6 1474.58  5136.4 1481.94
  5166.6 1489.49  5206.1 1491.53  5235.8 1492.94  5338.6 1491.74  5757.8 1491.83
  5818.9  1493.2    5847 1498.55  5852.2 1497.76  5886.8 1507.56  5960.3 1509.21
#Mann= 9 ,-1 , 0
    4529    .035       0  4838.3     .07       0    4940     .12       0
  5009.4     .05       0  5032.8     .12       0  5136.4     .07       0
  5206.1     .12       0  5338.6    .035       0  5757.8     .12       0
Bank Sta=5009.4,5032.8
XS Rating Curve= 0 ,0
Exp/Cntr=0.3,0.1

Type RM Length L Ch R = 1 ,24287   ,566,566,566
BEGIN DESCRIPTION:
BIG JOSHUA CREEK 42.0
END DESCRIPTION:
XS GIS Cut Line= 3
      2018375.01     13876424.98        2018525.       13875975.
      2018433.78     13874758.33
#Sta/Elev= 30
  4525.7 1520.66  4557.3 1517.86  4599.5 1506.53  4620.5 1498.22  4641.6 1492.83
  4797.2 1488.26  4872.3 1487.71    4908 1485.94  4926.2 1483.45  4936.8 1479.77
  4957.9 1467.58  4977.8 1458.71  4978.3 1458.21  5001.2 1458.71  5020.1 1461.58
  5040.1 1468.98  5050.2  1470.6  5090.3 1472.43  5100.3  1474.4  5120.4 1472.84
  5149.1 1475.35  5193.6 1479.79  5220.6  1484.7  5320.9 1487.94  5380.4 1487.31
  5591.7 1490.48  6052.8  1493.7  6137.5 1497.06  6183.3 1504.48  6220.1 1507.49
#Mann= 10 ,-1 , 0
  4525.7     .12       0  4797.2     .07       0  4872.3     .12       0
    4908     .07       0  4977.8     .05       0  5001.2     .07       0
  5149.1    .035       0  5193.6     .07       0  5380.4    .035       0
  6052.8     .12       0
Bank Sta=4977.8,5001.2
XS Rating Curve= 0 ,0
Exp/Cntr=0.3,0.1

Type RM Length L Ch R = 1 ,23721   ,550,550,550
BEGIN DESCRIPTION:
BIG JOSHUA CREEK 41.0
END DESCRIPTION:
XS GIS Cut Line= 3
      2018424.98     13876575.01        2019075.       13876025.
      2018802.58      13874669.9
#Sta/Elev= 30
  4148.5 1527.31  4184.2 1525.97  4212.8 1519.17  4276.5 1514.17  4311.7 1496.34
  4332.5 1489.69  4415.1 1484.58  4576.3 1482.64    4738 1484.29  4900.6 1481.53
  4957.7  1476.6    4972  1470.3  4978.6 1462.49  4998.4 1457.29  4998.9 1456.79
  5021.9 1457.29    5051 1458.87  5071.2 1464.55    5102 1463.51  5119.2 1469.55
  5223.8 1483.94  5321.2 1485.19  5324.2  1485.2  5527.4 1489.31  5807.8 1494.48
  6011.4  1495.2  6125.3 1495.21  6146.2 1495.16  6366.3 1501.76  6382.2  1503.2
#Mann= 14 ,-1 , 0
  4148.5     .12       0  4415.1     .07       0  4576.3    .035       0
  4998.4    .035       0  5021.9    .035       0  5119.2     .12       0
  5321.2    .035       0  5324.2     .07       0  5527.4    .035       0
  5807.8     .07       0  6011.4     .12       0  6125.3     .07       0
  6146.2     .12       0  6366.3     .07       0
Bank Sta=4998.4,5021.9
XS Rating Curve= 0 ,0
Exp/Cntr=0.3,0.1

Type RM Length L Ch R = 1 ,23171   ,1099,1099,1099
BEGIN DESCRIPTION:
BIG JOSHUA CREEK 40.0
END DESCRIPTION:
XS GIS Cut Line= 3
      2019077.81     13877152.77        2019575.       13876175.
      2019660.78     13876013.14
#Sta/Elev= 30
  3902.6 1526.94  4084.6 1523.94  4101.2 1521.42  4275.9 1514.55  4292.7 1511.63
  4301.5 1505.13  4315.2 1504.96  4323.7 1501.56  4329.3 1502.16    4346 1488.76
  4351.6 1486.77  4368.2 1476.09  4373.8 1475.58  4390.5 1468.16    4435 1470.32
  4567.3 1469.73  4594.4 1468.63  4663.1 1463.62  4718.6 1466.33  4793.1  1465.9
  4829.8 1465.09  4879.9 1459.94  4977.1 1458.13  4995.9 1453.26  4996.4 1452.76
  5019.4 1453.26  5022.2 1454.13  5035.3 1479.01  5131.3 1477.77  5182.7 1476.99
#Mann= 8 ,-1 , 0
  3902.6     .07       0  4275.9     .12       0  4567.3    .035       0
  4594.4     .12       0  4793.1     .07       0  4995.9     .05       0
  5019.4     .07       0  5131.3    .035       0
Bank Sta=4995.9,5019.4
XS Rating Curve= 0 ,0
Exp/Cntr=0.3,0.1

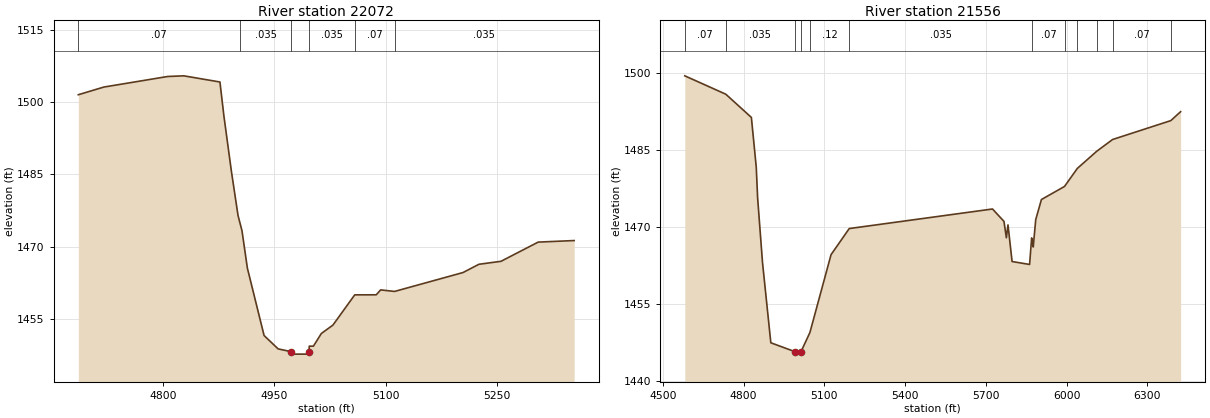
Type RM Length L Ch R = 1 ,22072   ,516,516,516
BEGIN DESCRIPTION:
BIG JOSHUA CREEK 39.0
END DESCRIPTION:
XS GIS Cut Line= 3
      2020140.39     13877066.97        2020025.       13876775.
      2019844.12     13876470.17
#Sta/Elev= 30
  4685.9 1501.51  4720.3  1503.1  4806.3 1505.29  4828.1 1505.43  4876.8 1504.15
  4882.2 1497.03  4892.3 1485.58  4901.2 1476.46  4903.6 1475.04  4906.5 1473.32
  4913.8 1465.55  4936.3 1451.58  4955.2 1448.81    4973 1448.22  4973.5 1447.72
  4996.4 1447.72  4996.9 1448.22  4997.2 1449.37  5002.8 1449.37  5013.5    1452
  5029.1 1453.74  5058.5 1460.01  5087.5 1460.02  5093.4 1461.04  5112.2 1460.72
  5204.5 1464.64  5225.9 1466.35  5255.7 1466.97  5305.8 1470.95  5354.3 1471.27
#Mann= 6 ,-1 , 0
  4685.9     .07       0  4903.6    .035       0    4973    .035       0
  4996.9    .035       0  5058.5     .07       0  5112.2    .035       0
Bank Sta=4973,4996.9
XS Rating Curve= 0 ,0
Exp/Cntr=0.3,0.1

Type RM Length L Ch R = 1 ,21556   ,527,527,527
BEGIN DESCRIPTION:
BIG JOSHUA CREEK 38.0
END DESCRIPTION:
XS GIS Cut Line= 3
      2020374.99     13876774.96        2020275.       13876375.
      2019501.38     13875173.36
#Sta/Elev= 30
  4581.9 1499.39  4734.2 1495.81  4829.2 1491.29  4847.3 1481.59  4852.4  1475.6
  4870.5 1463.04  4901.4 1447.41  4989.8  1445.7  4990.3  1445.2  5013.7  1445.7
  5046.5  1449.4    5125 1464.56  5192.6 1469.65  5724.7 1473.46  5767.2 1471.05
  5776.2 1467.86  5782.2 1470.36  5797.4 1463.23  5862.4 1462.66    5870 1467.83
  5872.7 1467.02  5875.9 1466.06  5885.2 1471.39  5906.3  1475.3  5992.1 1477.85
  6039.7 1481.36  6111.5 1484.69  6170.6 1486.99  6386.9 1490.67  6423.3 1492.41
#Mann= 12 ,-1 , 0
  4581.9     .07       0  4734.2    .035       0  4989.8    .035       0
  5013.7    .035       0  5046.5     .12       0  5192.6    .035       0
  5872.7     .07       0  5992.1     .12       0  6039.7     .07       0
  6111.5     .12       0  6170.6     .07       0  6386.9     .12       0
Bank Sta=4989.8,5013.7
XS Rating Curve= 0 ,0
Exp/Cntr=0.3,0.1