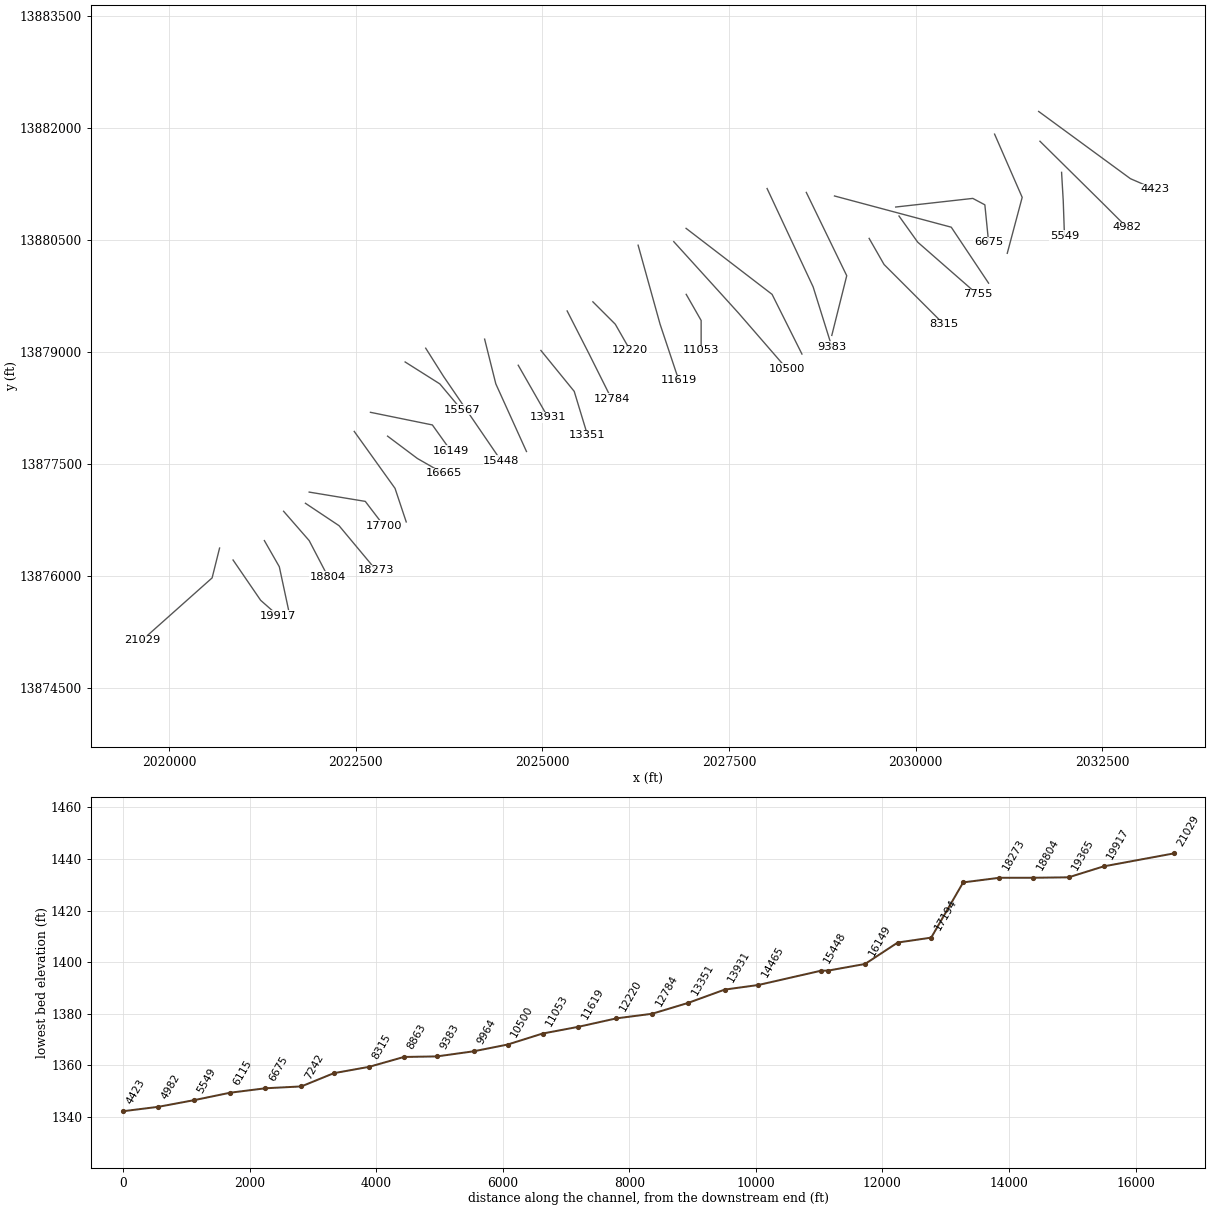
HEC-RAS study BIG JOSHUA CREEK.prj: BIG JOSHUA CREEK Base Level Engineering

--- BIG JOSHUA CREEK.g01 (geometry) --- (continued)

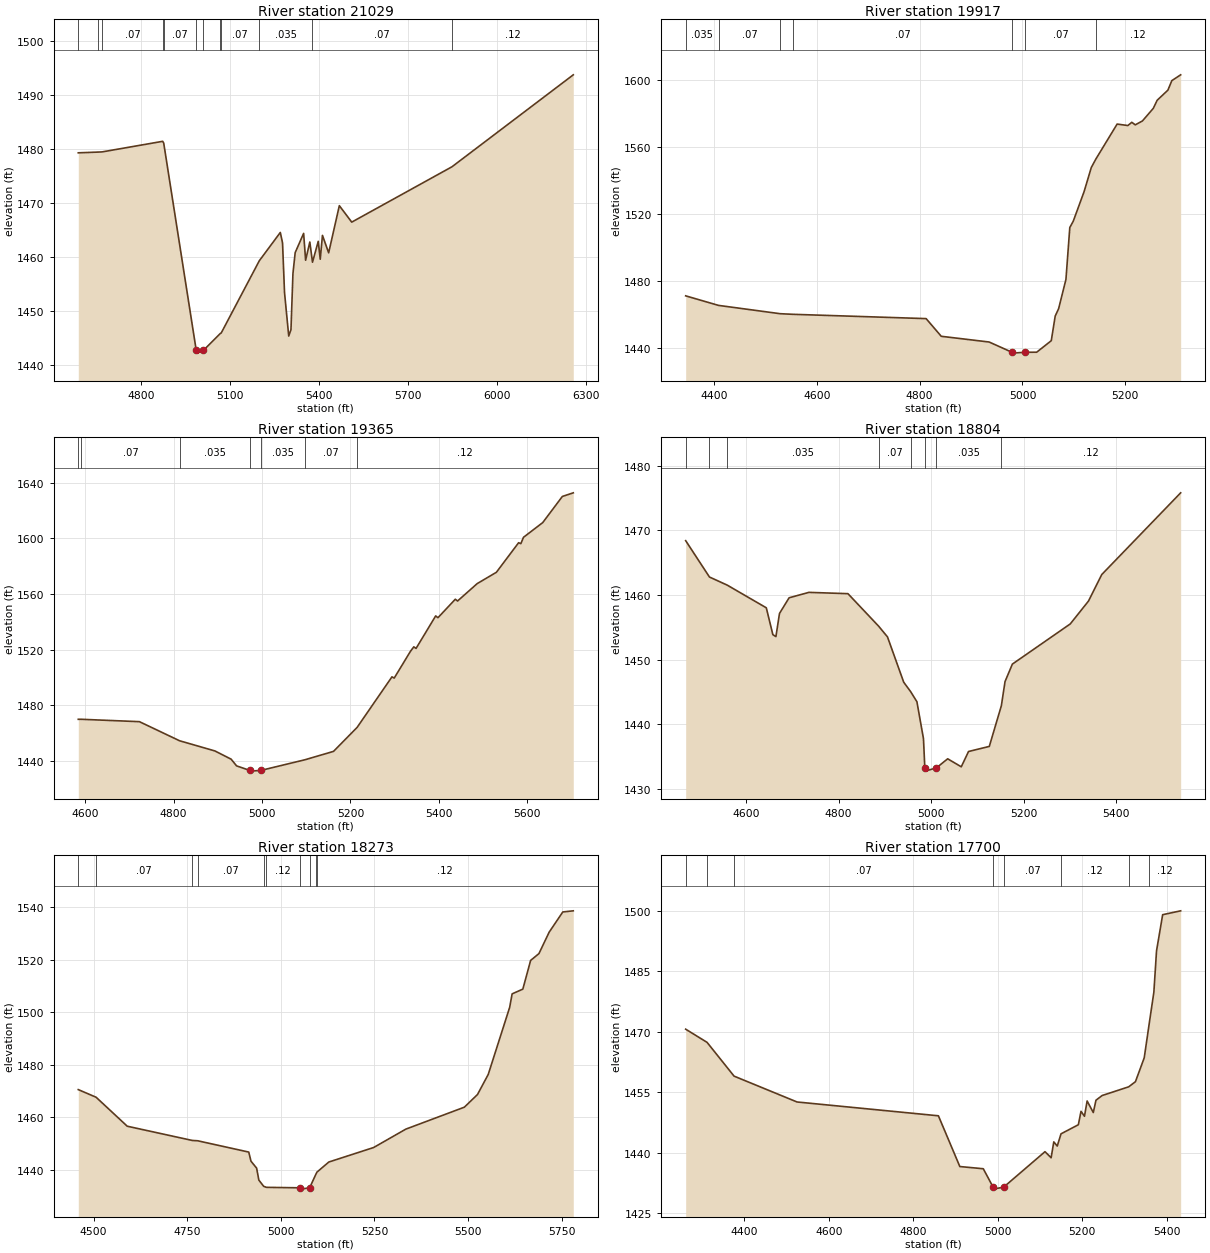
Type RM Length L Ch R = 1 ,21029   ,1112,1112,1112
BEGIN DESCRIPTION:
BIG JOSHUA CREEK 37.0
END DESCRIPTION:
XS GIS Cut Line= 3
      2020674.99     13876374.95        2020575.       13875975.
      2019636.67     13875139.29
#Sta/Elev= 30
    4588 1479.24  4655.7 1479.38  4668.2 1479.41  4872.5 1481.37    4876 1481.05
  4985.7 1442.66  4986.2 1442.16  5009.6 1442.66  5067.3 1445.82  5069.8 1445.88
  5198.3 1459.26  5269.1  1464.5  5276.6 1462.57  5283.3 1453.38  5297.5 1445.32
    5305 1446.49  5311.7 1456.91  5319.2 1460.76  5347.7 1464.33  5354.4 1459.36
  5368.6 1462.73  5377.6 1458.99    5397 1462.86  5403.7 1459.54  5411.2 1463.96
  5432.1 1460.73  5468.1 1469.46  5509.9 1466.41  5847.9 1476.66  6256.8 1493.68
#Mann= 12 ,-1 , 0
    4588     .07       0  4655.7    .035       0  4668.2     .07       0
  4872.5    .035       0    4876     .07       0  4985.7     .05       0
  5009.6     .07       0  5067.3    .035       0  5069.8     .07       0
  5198.3    .035       0  5377.6     .07       0  5847.9     .12       0
Bank Sta=4985.7,5009.6
XS Rating Curve= 0 ,0
Exp/Cntr=0.3,0.1

Type RM Length L Ch R = 1 ,19917   ,552,552,552
BEGIN DESCRIPTION:
BIG JOSHUA CREEK 36.0
END DESCRIPTION:
XS GIS Cut Line= 3
      2020855.54     13876214.98        2021225.       13875675.
       2021455.8     13875471.16
#Sta/Elev= 30
  4345.3 1471.28  4409.2 1465.58  4528.9 1460.63  4553.4 1460.27  4812.7  1457.7
  4842.1 1447.16  4935.3 1443.74  4979.7 1437.62  4980.2 1437.12  5004.5 1437.62
  5027.6 1437.66    5056 1444.54  5063.6 1459.21  5070.3 1463.65  5084.5 1481.09
    5092 1512.04  5098.7 1515.78  5119.7 1533.37  5133.8 1547.82  5142.9 1552.98
    5184 1573.71  5204.9 1572.84  5212.5 1574.77  5219.2 1573.25  5233.1 1575.55
  5254.3 1583.08  5261.8  1587.9  5282.7 1593.95  5290.3 1599.61  5307.5 1603.08
#Mann= 7 ,-1 , 0
  4345.3    .035       0  4409.2     .07       0  4528.9    .035       0
  4553.4     .07       0  4979.7     .05       0  5004.5     .07       0
  5142.9     .12       0
Bank Sta=4979.7,5004.5
XS Rating Curve= 0 ,0
Exp/Cntr=0.3,0.1

Type RM Length L Ch R = 1 ,19365   ,561,561,561
BEGIN DESCRIPTION:
BIG JOSHUA CREEK 35.0
END DESCRIPTION:
XS GIS Cut Line= 3
        2021275.     13876475.01        2021475.       13876125.
        2021625.     13875425.01
#Sta/Elev= 30
  4584.7 1470.08  4591.1  1470.1  4722.9 1468.38  4813.7 1454.68  4893.5 1447.38
  4930.2 1441.47  4942.5 1436.67  4972.5 1433.39    4973 1432.89  4997.3 1433.39
  5096.8 1441.02  5161.7 1447.06    5215 1464.26  5293.8 1500.55  5298.9 1499.66
  5335.5 1518.81  5343.2 1522.08  5348.3 1520.95  5392.6 1544.27  5397.8 1542.99
    5437 1556.25  5442.1 1554.96  5486.4 1567.44  5529.9 1575.59  5580.1  1596.8
  5585.2 1596.14  5591.2  1600.7  5634.7 1611.26    5679    1630  5703.7 1632.61
#Mann= 7 ,-1 , 0
  4584.7    .035       0  4591.1     .07       0  4813.7    .035       0
  4972.5    .035       0  4997.3    .035       0  5096.8     .07       0
    5215     .12       0
Bank Sta=4972.5,4997.3
XS Rating Curve= 0 ,0
Exp/Cntr=0.3,0.1

Type RM Length L Ch R = 1 ,18804   ,531,531,531
BEGIN DESCRIPTION:
BIG JOSHUA CREEK 34.0
END DESCRIPTION:
XS GIS Cut Line= 3
      2021532.55     13876867.99        2021875.       13876475.
      2022128.62     13875988.27
#Sta/Elev= 30
  4469.3 1468.42  4520.7 1462.79  4559.2 1461.53  4643.6 1458.02  4657.8 1453.86
  4664.4 1453.56  4672.1 1457.14  4692.9 1459.57  4735.7 1460.41  4820.1 1460.21
  4886.5 1455.17  4905.6 1453.51  4940.7 1446.49  4955.6 1445.04  4969.2 1443.47
  4983.4 1437.75  4986.3 1433.22  4986.8 1432.72  5011.3 1433.22  5035.7 1434.63
  5065.1 1433.39  5080.8 1435.76  5125.7 1436.55  5151.8 1442.86  5159.7 1446.59
  5175.6  1449.3  5300.7 1455.52  5340.1 1459.06  5368.8 1463.17  5539.4 1475.83
#Mann= 8 ,-1 , 0
  4469.3    .035       0  4520.7     .07       0  4559.2    .035       0
  4886.5     .07       0  4955.6    .035       0  4986.3    .035       0
  5011.3    .035       0  5151.8     .12       0
Bank Sta=4986.3,5011.3
XS Rating Curve= 0 ,0
Exp/Cntr=0.3,0.1

Type RM Length L Ch R = 1 ,18273   ,573,573,573
BEGIN DESCRIPTION:
BIG JOSHUA CREEK 33.0
END DESCRIPTION:
XS GIS Cut Line= 3
      2021825.02     13876974.99        2022275.       13876675.
      2022774.98     13876075.03
#Sta/Elev= 30
  4459.3 1470.61  4506.9  1467.7    4590 1456.67  4763.6 1451.25  4778.2 1451.12
  4914.5 1446.82  4920.5 1443.34  4935.5 1440.71  4941.5 1436.14  4954.4 1433.78
  4961.7 1433.39    5052 1433.21  5052.5 1432.71  5077.1 1433.21  5094.2 1438.51
  5096.6 1439.18  5128.3 1443.03  5248.1 1448.56    5334 1455.56  5490.2 1463.91
  5525.3 1468.73    5554 1476.38  5611.3 1501.96  5617.8 1507.07  5646.4 1508.87
  5667.2  1519.8  5689.4  1522.4  5716.7 1530.56  5753.1 1538.26  5781.1 1538.69
#Mann= 10 ,-1 , 0
  4459.3    .035       0  4506.9     .07       0  4763.6    .035       0
  4778.2     .07       0  4954.4    .035       0  4961.7     .12       0
    5052     .05       0  5077.1     .12       0  5094.2     .07       0
  5096.6     .12       0
Bank Sta=5052,5077.1
XS Rating Curve= 0 ,0
Exp/Cntr=0.3,0.1

Type RM Length L Ch R = 1 ,17700   ,506,506,506
BEGIN DESCRIPTION:
BIG JOSHUA CREEK 32.0
END DESCRIPTION:
XS GIS Cut Line= 3
      2021875.01       13877125.      2022626.36     13877000.59
      2022874.97     13876675.04
#Sta/Elev= 30
  4261.6 1470.65  4312.2 1467.38  4376.1 1458.99  4525.1 1452.57  4859.6 1449.14
  4910.3 1436.54  4965.8 1435.99    4989 1431.43  4989.5 1430.93  5014.1 1431.43
  5111.8 1440.23  5126.3 1438.72  5132.6 1442.66  5140.8 1441.63  5149.7 1444.66
  5190.7 1446.92    5197 1450.25  5205.2 1449.03  5211.5 1452.82  5226.1 1449.95
  5232.4    1453  5246.9 1454.17  5309.9 1456.34  5325.8 1457.61  5346.6 1463.54
  5358.6 1472.18  5369.4 1479.84  5375.7  1490.1  5390.2 1499.08  5432.8 1500.04
#Mann= 8 ,-1 , 0
  4261.6     .07       0  4312.2    .035       0  4376.1     .07       0
    4989     .05       0  5014.1     .07       0  5149.7     .12       0
  5309.9     .07       0  5358.6     .12       0
Bank Sta=4989,5014.1
XS Rating Curve= 0 ,0
Exp/Cntr=0.3,0.1

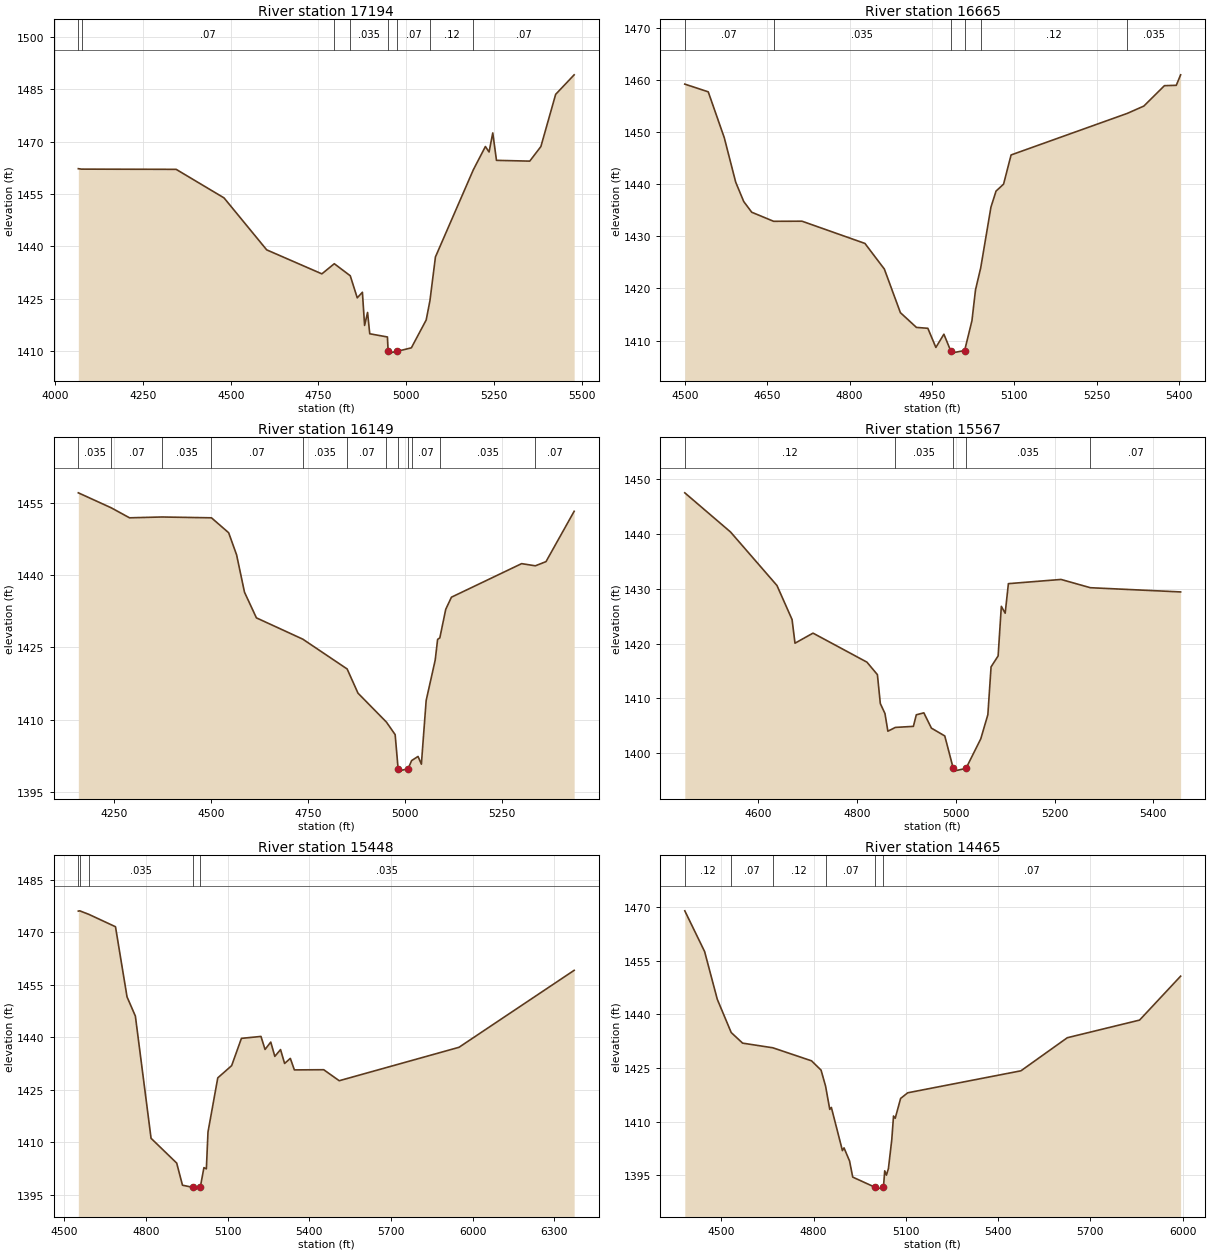
Type RM Length L Ch R = 1 ,17194   ,529,529,529
BEGIN DESCRIPTION:
BIG JOSHUA CREEK 31.0
END DESCRIPTION:
XS GIS Cut Line= 3
      2022478.81     13877938.06        2023025.       13877175.
      2023174.99     13876725.03
#Sta/Elev= 30
  4065.9 1462.24  4075.1 1462.11  4344.6 1462.05    4481 1453.89  4602.6 1439.03
  4759.8 1432.17  4795.2 1435.07  4840.7 1431.62  4860.6 1425.32  4875.3 1426.91
  4881.5 1417.43    4890 1421.13  4896.2 1415.04  4946.6 1414.13  4948.6 1410.01
  4949.1 1409.51  4973.9 1410.01  5014.8 1411.03    5057 1418.98  5067.7  1424.5
  5083.4 1437.01  5191.3 1461.92  5225.7 1468.57  5236.2 1467.01  5246.7 1472.46
  5257.3 1464.62  5352.1  1464.4  5383.8 1468.57  5425.9 1483.49  5478.6 1489.07
#Mann= 8 ,-1 , 0
  4065.9    .035       0  4075.1     .07       0  4795.2    .094       0
  4840.7    .035       0  4948.6     .05       0  4973.9     .07       0
  5067.7     .12       0  5191.3     .07       0
Bank Sta=4948.6,4973.9
XS Rating Curve= 0 ,0
Exp/Cntr=0.3,0.1

Type RM Length L Ch R = 1 ,16665   ,516,516,516
BEGIN DESCRIPTION:
BIG JOSHUA CREEK 30.0
END DESCRIPTION:
XS GIS Cut Line= 3
      2022925.02     13877874.99        2023325.       13877575.
      2023675.01     13877374.99
#Sta/Elev= 30
    4500 1459.18  4542.7  1457.7  4571.9 1448.91  4592.7 1440.39  4607.3 1436.68
  4621.9 1434.62  4661.8 1432.88  4713.5  1432.9  4828.1 1428.64  4863.5 1423.72
  4892.7 1415.37  4921.9 1412.54  4942.7 1412.37  4957.3  1408.7  4971.9 1411.24
  4984.1 1408.11  4984.6 1407.61  5009.7 1408.11    5023 1413.82  5029.5 1419.74
    5039 1423.97  5057.6 1435.59  5066.9 1438.67  5080.6    1440  5094.3  1445.6
    5306 1453.57  5336.1 1454.97  5373.6 1458.88  5395.2 1458.95  5403.1 1460.96
#Mann= 6 ,-1 , 0
    4500     .07       0  4661.8    .035       0  4984.1    .035       0
  5009.7    .035       0    5039     .12       0    5306    .035       0
Bank Sta=4984.1,5009.7
XS Rating Curve= 0 ,0
Exp/Cntr=0.3,0.1

Type RM Length L Ch R = 1 ,16149   ,582,582,582
BEGIN DESCRIPTION:
BIG JOSHUA CREEK 29.0
END DESCRIPTION:
XS GIS Cut Line= 3
      2022695.84     13878194.16        2023525.       13878025.
      2023775.02     13877674.97
#Sta/Elev= 30
  4158.4 1457.11    4243    1454  4290.2 1451.92  4373.3 1452.09  4501.1 1451.92
  4545.4 1448.82  4565.8 1444.23  4586.2 1436.46  4616.8 1431.14  4736.3 1426.71
  4850.4 1420.52  4878.3  1415.5  4951.6 1409.48    4974 1406.88  4981.6  1399.8
  4982.1  1399.3  5007.3  1399.8  5016.4 1401.49  5032.9 1402.35  5041.5 1400.75
  5053.8 1413.96  5077.1 1422.37  5083.3 1426.66    5089 1426.98  5104.2 1432.91
  5118.9 1435.43  5299.6  1442.4  5334.9 1441.95  5362.3 1442.82  5434.8 1453.27
#Mann= 12 ,-1 , 0
  4158.4    .035       0    4243     .07       0  4373.3    .035       0
  4501.1     .07       0  4736.3    .035       0  4850.4     .07       0
  4951.6     .12       0  4981.6     .05       0  5007.3     .12       0
  5016.4     .07       0    5089    .035       0  5334.9     .07       0
Bank Sta=4981.6,5007.3
XS Rating Curve= 0 ,0
Exp/Cntr=0.3,0.1

Type RM Length L Ch R = 1 ,15567   ,119,119,119
BEGIN DESCRIPTION:
BIG JOSHUA CREEK 28.0
END DESCRIPTION:
XS GIS Cut Line= 3
      2023160.38     13878868.77        2023625.       13878575.
      2023917.47     13878226.46
#Sta/Elev= 30
  4450.7 1447.54  4543.4 1440.39  4637.5 1430.62  4668.1  1424.4    4674 1420.09
  4710.5 1421.93  4819.8 1416.63    4841 1414.35  4846.9 1409.07  4856.3 1407.26
  4862.2 1404.03  4877.4 1404.72  4913.9 1404.91  4919.8 1407.02  4935.1 1407.38
  4950.4 1404.59  4977.5 1403.16  4994.7 1397.24  4995.2 1396.74  5020.5 1397.24
  5050.5 1402.65  5064.8 1407.05  5071.3 1415.77  5085.6 1417.77  5092.1 1426.82
  5099.9 1425.57  5106.4 1430.96  5213.1 1431.73  5272.5 1430.22  5455.4 1429.45
#Mann= 5 ,-1 , 0
  4450.7     .12       0  4877.4    .035       0  4994.7    .035       0
  5020.5    .035       0  5272.5     .07       0
Bank Sta=4994.7,5020.5
XS Rating Curve= 0 ,0
Exp/Cntr=0.3,0.1

Type RM Length L Ch R = 1 ,15448   ,983,983,983
BEGIN DESCRIPTION:
BIG JOSHUA CREEK 27.0
END DESCRIPTION:
XS GIS Cut Line= 3
       2023435.9     13879053.39        2023675.       13878675.
      2024448.34     13877541.11
#Sta/Elev= 30
  4552.4 1476.01  4557.6 1476.09  4591.4 1475.07  4688.8 1471.55  4731.2 1451.53
  4761.8 1446.05  4819.4 1411.17  4913.5 1404.09  4934.7 1397.78    4973 1397.16
  4973.5 1396.66  4999.9 1397.16  5013.5  1402.8  5022.4 1402.44  5028.4 1412.98
  5064.3 1428.42  5115.2  1431.9  5151.1 1439.69  5222.9 1440.24  5237.8 1436.52
  5258.8 1438.63  5273.7 1434.55  5294.7 1436.49  5309.6 1432.52  5330.6 1433.98
  5345.5 1430.69  5453.2 1430.74  5510.1  1427.6  5949.8 1437.14  6372.5 1459.11
#Mann= 5 ,-1 , 0
  4552.4    .035       0  4557.6    .063       0  4591.4    .035       0
    4973    .035       0  4999.9    .035       0
Bank Sta=4973,4999.9
XS Rating Curve= 0 ,0
Exp/Cntr=0.3,0.1

Type RM Length L Ch R = 1 ,14465   ,534,534,534
BEGIN DESCRIPTION:
BIG JOSHUA CREEK 26.0
END DESCRIPTION:
XS GIS Cut Line= 3
      2024224.99     13879175.02        2024375.       13878575.
      2024785.46     13877669.14
#Sta/Elev= 30
  4380.8  1468.9  4445.2 1457.54  4486.5 1444.19  4531.8  1434.9  4568.9 1431.94
  4667.3 1430.64  4793.1    1427  4824.1  1424.4  4838.8 1419.93  4852.4 1413.43
  4857.6 1413.98  4893.6 1401.92  4898.8 1402.68  4916.8 1399.02  4927.1 1394.52
  5000.1 1391.66  5000.6 1391.16    5027 1391.66  5031.2 1396.28  5036.7 1395.07
  5043.2 1396.89  5054.2 1405.02  5059.8 1411.58  5065.3 1410.95  5082.9 1416.49
    5106 1418.07  5474.3 1424.21  5625.1 1433.45  5860.3 1438.38  5993.8 1450.65
#Mann= 6 ,-1 , 0
  4380.8     .12       0  4531.8     .07       0  4667.3     .12       0
  4838.8     .07       0  5000.1     .05       0    5027     .07       0
Bank Sta=5000.1,5027
XS Rating Curve= 0 ,0
Exp/Cntr=0.3,0.1

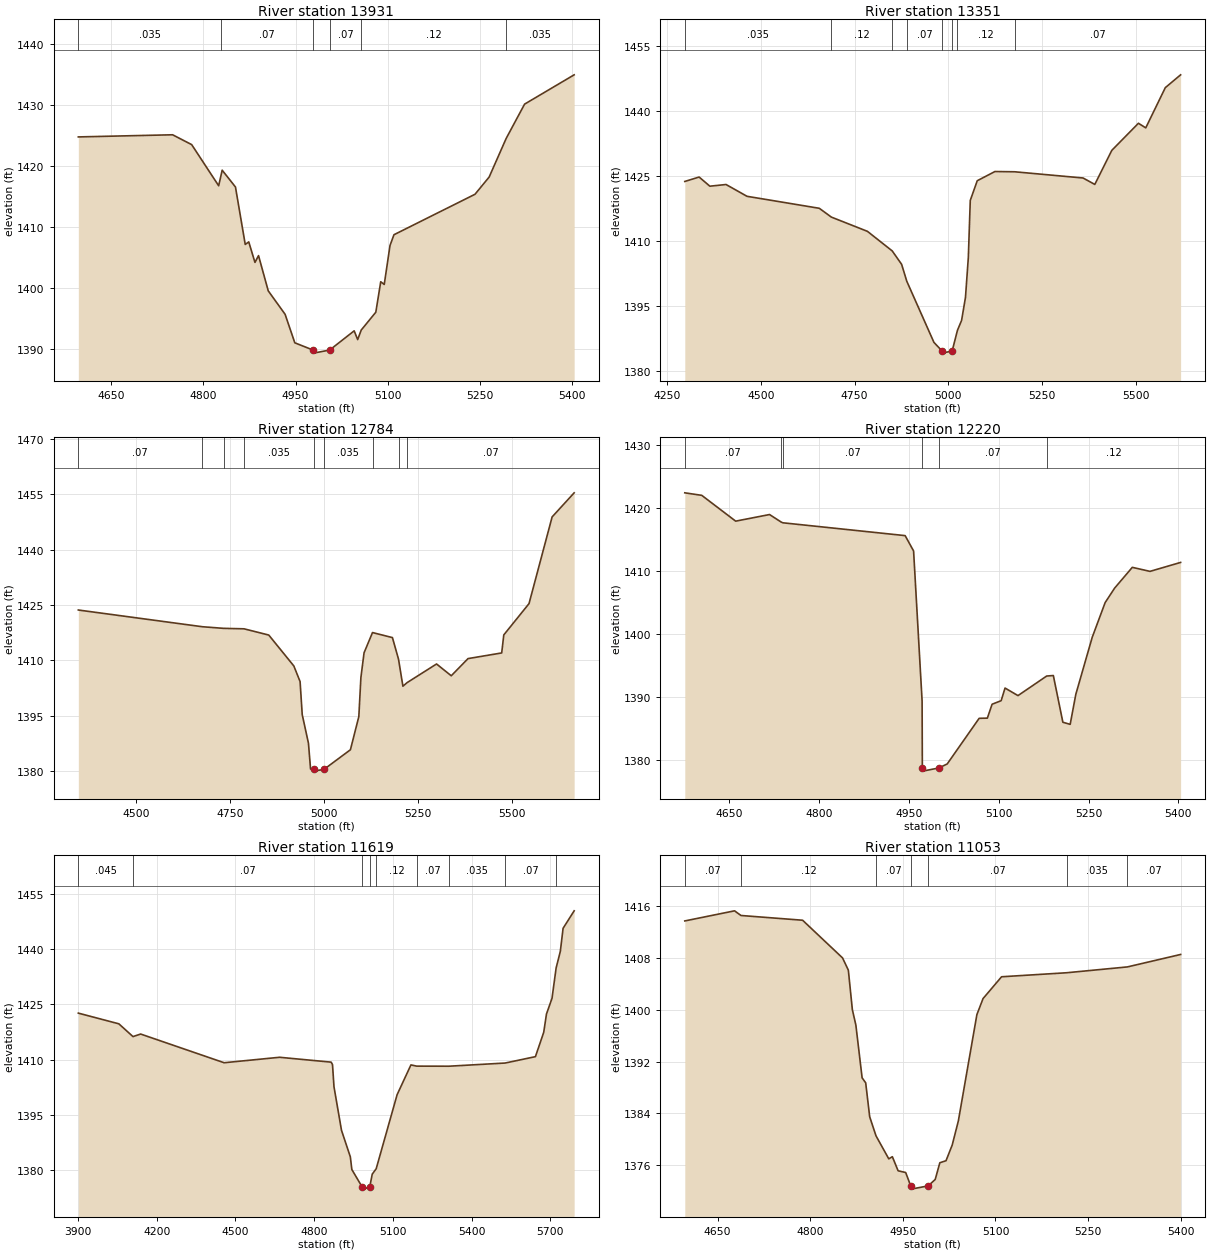
Type RM Length L Ch R = 1 ,13931   ,580,580,580
BEGIN DESCRIPTION:
BIG JOSHUA CREEK 25.0
END DESCRIPTION:
XS GIS Cut Line= 3
        2024675.       13878825.        2024875.       13878475.
      2025074.99     13878125.02
#Sta/Elev= 30
  4596.8 1424.78  4750.1 1425.13  4781.1 1423.52    4825 1416.78  4828.7 1418.44
  4830.7 1419.33  4852.3 1416.58  4868.2 1407.17  4873.9 1407.59    4884 1404.23
  4889.8 1405.34  4905.6 1399.57    4933 1395.73  4948.8 1391.06  4978.5 1389.87
    4979 1389.37  5005.4 1389.87  5045.3 1393.02    5051 1391.59  5056.8 1393.15
  5080.5 1396.07  5088.5 1401.06  5094.2 1400.62  5103.6    1407    5110 1408.76
  5241.8 1415.39  5264.8 1418.21  5292.5 1424.54  5322.4 1430.15    5403 1434.95
#Mann= 6 ,-1 , 0
  4596.8    .035       0  4828.7     .07       0  4978.5     .05       0
  5005.4     .07       0  5056.8     .12       0  5292.5    .035       0
Bank Sta=4978.5,5005.4
XS Rating Curve= 0 ,0
Exp/Cntr=0.3,0.1

Type RM Length L Ch R = 1 ,13351   ,567,567,567
BEGIN DESCRIPTION:
BIG JOSHUA CREEK 24.0
END DESCRIPTION:
XS GIS Cut Line= 3
      2024978.78     13879023.17        2025425.       13878475.
       2025603.8     13877885.97
#Sta/Elev= 30
  4297.1 1423.74  4335.3 1424.76    4364 1422.65  4407.1 1423.04  4463.1 1420.32
  4655.8 1417.56    4688 1415.53  4784.2 1412.25  4850.3 1407.74  4875.4 1404.65
  4889.1 1400.77  4961.6 1386.66  4983.2 1384.69  4983.7 1384.19  5010.2 1384.69
  5024.3 1389.45  5035.3 1391.72  5045.7 1397.04  5053.3 1406.24  5058.5 1419.38
  5077.1 1423.91  5124.3 1426.03  5177.1 1425.97  5359.3 1424.54  5390.6 1423.06
    5436 1430.91    5507 1437.15  5526.5 1436.09  5578.7 1445.36  5619.5 1448.31
#Mann= 8 ,-1 , 0
  4297.1    .035       0    4688     .12       0  4850.3    .035       0
  4889.1     .07       0  4983.2     .05       0  5010.2     .07       0
  5024.3     .12       0  5177.1     .07       0
Bank Sta=4983.2,5010.2
XS Rating Curve= 0 ,0
Exp/Cntr=0.3,0.1

Type RM Length L Ch R = 1 ,12784   ,564,564,564
BEGIN DESCRIPTION:
BIG JOSHUA CREEK 23.0
END DESCRIPTION:
XS GIS Cut Line= 3
      2025330.37     13879552.63        2025625.       13878975.
      2025924.98     13878375.04
#Sta/Elev= 30
  4345.8 1423.68  4675.6 1419.15  4732.1 1418.71  4786.7 1418.58  4852.5 1416.89
  4919.2 1408.51  4935.8 1404.28  4941.5 1395.32  4958.1 1387.55  4963.7 1380.55
  4972.2  1380.5  4972.7    1380  4999.7  1380.5  5069.7 1385.79  5092.1 1394.79
  5097.6 1405.37    5106 1412.08  5128.5 1417.57  5181.5  1416.2  5197.7 1410.35
  5209.4 1403.02  5220.6    1404  5298.9 1409.05    5338 1405.85  5382.7 1410.51
  5472.2 1412.04  5477.8 1416.93  5544.9 1425.41  5606.4 1448.92    5665 1455.45
#Mann= 9 ,-1 , 0
  4345.8     .07       0  4675.6    .035       0  4732.1     .07       0
  4786.7    .035       0  4972.2    .035       0  4999.7    .035       0
  5128.5     .07       0  5197.7     .12       0  5220.6     .07       0
Bank Sta=4972.2,4999.7
XS Rating Curve= 0 ,0
Exp/Cntr=0.3,0.1

Type RM Length L Ch R = 1 ,12220   ,601,601,601
BEGIN DESCRIPTION:
BIG JOSHUA CREEK 22.0
END DESCRIPTION:
XS GIS Cut Line= 3
        2025675.       13879675.        2025975.       13879375.
      2026175.01     13879024.99
#Sta/Elev= 30
  4576.3 1422.44  4604.6 1422.04  4661.2 1417.94  4717.7 1418.99  4736.9 1417.81
  4739.8 1417.68    4944 1415.64  4958.1  1413.2  4972.3 1389.37  4972.7 1378.72
  4973.2 1378.22  5000.2 1378.72  5014.2 1379.36  5067.5 1386.61  5081.2 1386.64
  5089.1 1388.85  5104.2 1389.41  5110.7 1391.42  5132.3 1390.22  5180.2 1393.33
  5191.3 1393.41  5207.2 1385.99  5219.4 1385.65  5228.8 1390.42  5256.1 1399.46
  5277.7 1404.99  5293.5 1407.29  5323.1  1410.6  5352.6 1409.96  5403.7 1411.38
#Mann= 6 ,-1 , 0
  4576.3     .07       0  4736.9    .035       0  4739.8     .07       0
  4972.7     .05       0  5000.2     .07       0  5180.2     .12       0
Bank Sta=4972.7,5000.2
XS Rating Curve= 0 ,0
Exp/Cntr=0.3,0.1

Type RM Length L Ch R = 1 ,11619   ,566,566,566
BEGIN DESCRIPTION:
BIG JOSHUA CREEK 21.0
END DESCRIPTION:
XS GIS Cut Line= 3
      2026280.86     13880433.79        2026575.       13879375.
      2026825.01     13878624.96
#Sta/Elev= 30
  3901.1 1422.65  4055.5 1419.75  4109.4 1416.29  4138.6 1416.98  4456.7  1409.2
  4667.9 1410.68  4864.6 1409.36  4869.7  1408.7  4875.4 1402.67    4904 1390.88
  4937.7 1383.68  4943.4 1380.26  4983.4 1375.44  4983.9 1374.94  5011.4 1375.44
  5021.1    1379  5036.2 1380.46  5115.9 1400.54  5168.6 1408.61  5190.4 1408.28
  5313.5 1408.26  5527.7 1409.12    5643 1410.85  5674.6 1417.45  5685.1 1422.41
  5706.2 1426.66  5721.9 1434.89  5737.9 1439.39  5748.4 1445.64  5790.6 1450.38
#Mann= 9 ,-1 , 0
  3901.1    .045       0  4109.4     .07       0  4983.4     .05       0
  5011.4     .07       0  5036.2     .12       0  5190.4     .07       0
  5313.5    .035       0  5527.7     .07       0  5721.9     .12       0
Bank Sta=4983.4,5011.4
XS Rating Curve= 0 ,0
Exp/Cntr=0.3,0.1

Type RM Length L Ch R = 1 ,11053   ,553,553,553
BEGIN DESCRIPTION:
BIG JOSHUA CREEK 20.0
END DESCRIPTION:
XS GIS Cut Line= 3
        2026925.       13879775.        2027125.       13879425.
        2027125.     13879025.02
#Sta/Elev= 30
  4596.8 1413.69  4677.4 1415.25  4687.8 1414.53  4787.6  1413.8  4852.3 1407.99
  4861.7  1406.1  4868.2 1400.01  4873.9 1397.62    4884  1389.5  4889.8 1388.72
  4896.3 1383.48  4906.5 1380.55  4927.2    1377    4933 1377.33  4942.3 1375.16
  4954.6 1374.89  4962.7 1372.83  4963.2 1372.33    4991 1372.83  5002.4 1373.82
  5009.9  1376.4  5019.9 1376.71  5029.9 1379.12  5039.9 1382.85  5069.9 1399.24
  5079.9 1401.72  5109.9 1405.08  5215.3  1405.7  5313.7  1406.6  5399.9 1408.52
#Mann= 7 ,-1 , 0
  4596.8     .07       0  4687.8     .12       0  4906.5     .07       0
  4962.7     .05       0    4991     .07       0  5215.3    .035       0
  5313.7     .07       0
Bank Sta=4962.7,4991
XS Rating Curve= 0 ,0
Exp/Cntr=0.3,0.1

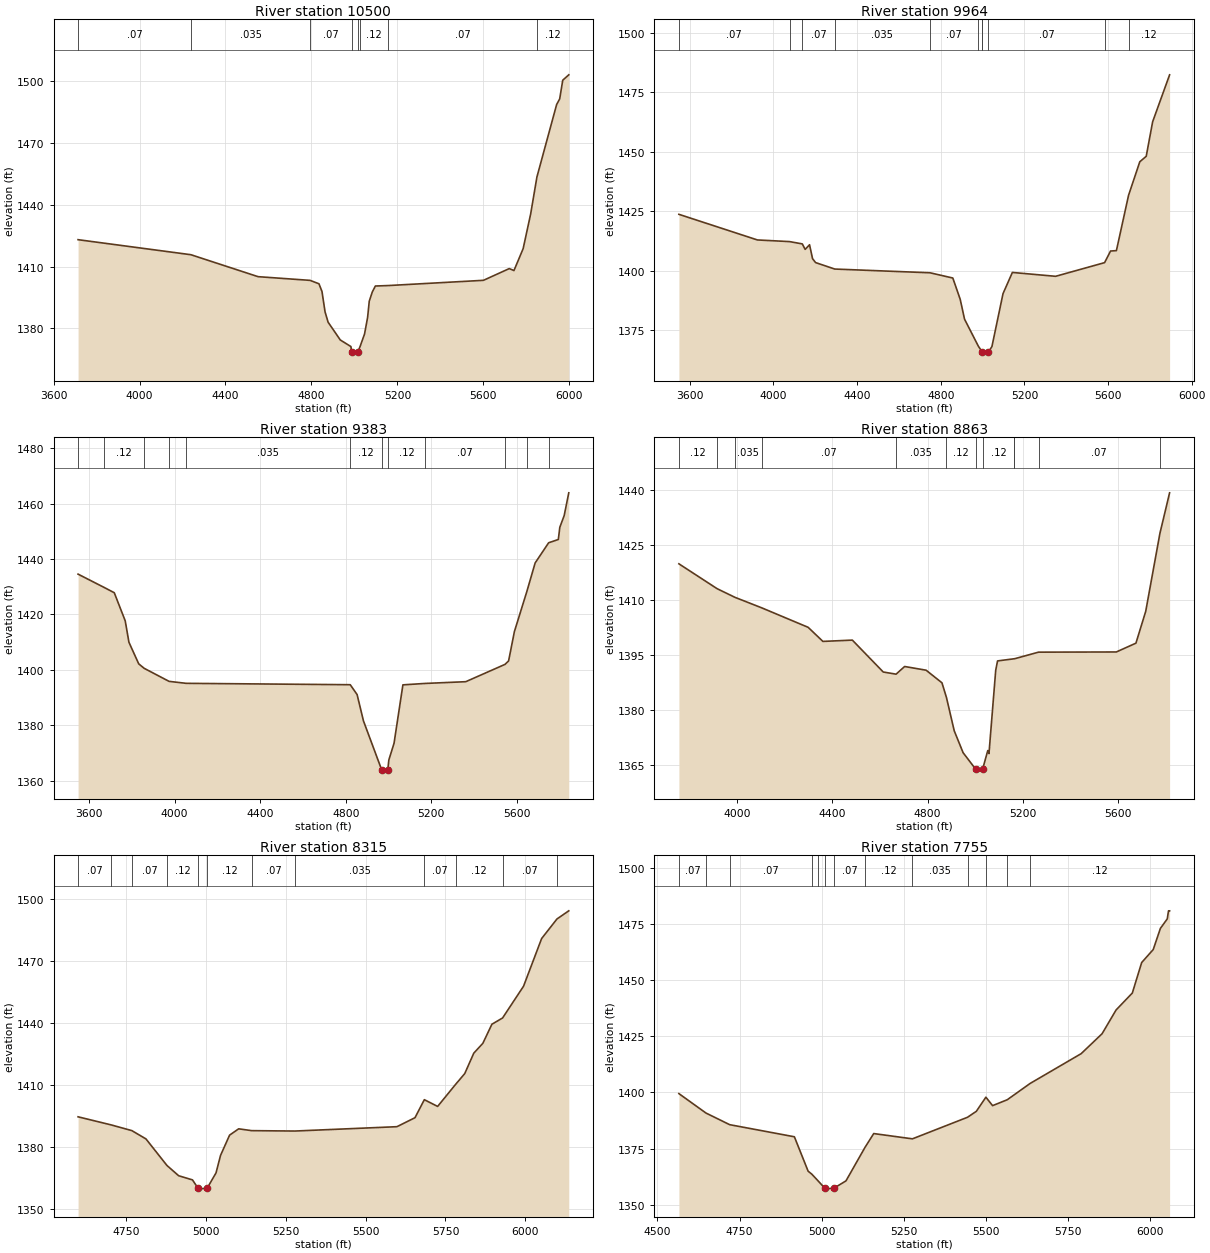
Type RM Length L Ch R = 1 ,10500   ,536,536,536
BEGIN DESCRIPTION:
BIG JOSHUA CREEK 19.0
END DESCRIPTION:
XS GIS Cut Line= 3
      2026758.28     13880481.52        2027625.       13879525.
      2028275.03     13878774.97
#Sta/Elev= 30
  3714.1 1423.03  4239.1 1415.75  4551.7 1405.11  4793.7 1403.32  4834.9 1401.67
  4849.1 1397.92  4863.3 1388.09  4877.5 1383.06  4934.3 1374.43  4983.6 1371.25
  4987.2 1368.56  4987.7 1368.06  5015.9 1368.56  5026.6 1371.35  5047.1 1377.34
  5061.4  1385.4    5069 1393.22  5083.3 1397.72  5097.5 1400.58  5155.3 1400.79
  5600.4 1403.34  5720.5 1409.02  5742.4 1408.08  5785.1  1418.7  5820.2 1435.57
  5849.1 1453.38  5940.9 1488.52  5955.1 1491.24  5969.4 1500.32  5997.4 1502.92
#Mann= 8 ,-1 , 0
  3714.1     .07       0  4239.1    .035       0  4793.7     .07       0
  4987.2     .05       0  5015.9     .07       0  5026.6     .12       0
  5155.3     .07       0  5849.1     .12       0
Bank Sta=4987.2,5015.9
XS Rating Curve= 0 ,0
Exp/Cntr=0.3,0.1

Type RM Length L Ch R = 1 ,9964    ,581,581,581
BEGIN DESCRIPTION:
BIG JOSHUA CREEK 18.0
END DESCRIPTION:
XS GIS Cut Line= 3
      2026923.24     13880659.44        2028075.       13879775.
        2028475.     13878974.99
#Sta/Elev= 30
  3547.9 1423.74  3923.3 1412.98  4077.3 1412.28    4138 1411.32  4151.7 1409.01
  4172.6 1410.97  4187.1 1405.11  4201.6 1403.47  4293.2 1400.76  4748.7 1399.19
  4857.8 1396.99  4893.1 1388.06  4913.9 1379.71  4980.4 1368.28  4995.8 1366.32
  4999.7 1365.95  5000.2 1365.45  5028.4 1365.95  5044.8  1368.2  5097.9 1390.43
  5142.6 1399.33  5349.4 1397.71  5583.6 1403.45  5612.2 1408.33  5640.1 1408.49
  5698.2 1431.72  5751.9  1445.8  5782.7 1448.11  5813.4 1462.61  5894.5 1482.32
#Mann= 11 ,-1 , 0
  3547.9     .07       0  4077.3    .035       0    4138     .07       0
  4293.2    .035       0  4748.7     .07       0  4980.4     .12       0
  4995.8     .07       0  4999.7     .05       0  5028.4     .07       0
  5583.6    .035       0  5698.2     .12       0
Bank Sta=4999.7,5028.4
XS Rating Curve= 0 ,0
Exp/Cntr=0.3,0.1

Type RM Length L Ch R = 1 ,9383    ,520,520,520
BEGIN DESCRIPTION:
BIG JOSHUA CREEK 17.0
END DESCRIPTION:
XS GIS Cut Line= 3
      2028008.31     13881193.29        2028625.       13879875.
      2028875.01     13879074.96
#Sta/Elev= 30
  3548.7 1434.53  3671.8 1429.68  3717.9 1427.82  3769.1 1417.68  3786.4 1409.97
  3832.1 1402.18  3857.5 1400.56  3974.1 1395.85  4053.6 1395.14  4820.9 1394.64
  4852.9 1391.09  4882.7 1381.57  4967.6 1363.97  4968.1 1363.47  4996.4 1363.97
  5001.3 1367.51  5025.6 1373.52    5067 1394.59  5170.7  1395.1  5360.8 1395.73
    5544 1401.97    5561 1403.21  5588.2 1413.82    5646 1428.18  5685.1 1438.56
  5748.1 1445.84  5793.5 1447.03  5800.4 1451.42  5820.8 1455.64  5842.3 1463.86
#Mann= 12 ,-1 , 0
  3548.7     .07       0  3671.8     .12       0  3857.5    .035       0
  3974.1     .07       0  4053.6    .035       0  4820.9     .12       0
  4967.6     .05       0  4996.4     .12       0  5170.7     .07       0
    5544    .035       0    5646     .12       0  5748.1     .07       0
Bank Sta=4967.6,4996.4
XS Rating Curve= 0 ,0
Exp/Cntr=0.3,0.1

Type RM Length L Ch R = 1 ,8863    ,548,548,548
BEGIN DESCRIPTION:
BIG JOSHUA CREEK 16.0
END DESCRIPTION:
XS GIS Cut Line= 3
       2028533.5     13881141.17        2029075.       13880025.
        2028875.     13879225.01
#Sta/Elev= 30
  3753.7 1419.77  3914.5 1412.99  3989.4 1410.64    4103 1407.75  4297.6 1402.46
  4359.7 1398.62  4483.7 1398.97  4613.6 1390.28  4667.7 1389.69  4703.8 1391.78
  4794.1 1390.77  4860.9 1387.33  4879.8 1383.32  4912.5 1374.25  4949.8 1368.29
  5003.1 1363.76  5003.6 1363.26  5031.9 1363.76  5053.6 1368.86  5058.7 1368.05
  5087.1 1390.77  5094.8  1393.3  5165.1 1393.89  5165.6 1393.88  5267.3 1395.69
  5594.7 1395.74  5677.2 1398.14  5718.4 1406.82  5778.3 1428.12  5818.9 1439.12
#Mann= 12 ,-1 , 0
  3753.7     .12       0  3914.5     .07       0  3989.4    .035       0
    4103     .07       0  4667.7    .035       0  4879.8     .12       0
  5003.1     .05       0  5031.9     .12       0  5165.1     .07       0
  5165.6     .12       0  5267.3     .07       0  5778.3     .12       0
Bank Sta=5003.1,5031.9
XS Rating Curve= 0 ,0
Exp/Cntr=0.3,0.1

Type RM Length L Ch R = 1 ,8315    ,560,560,560
BEGIN DESCRIPTION:
BIG JOSHUA CREEK 15.0
END DESCRIPTION:
XS GIS Cut Line= 3
        2029375.       13880525.        2029575.       13880175.
      2030375.02     13879374.98
#Sta/Elev= 30
  4601.1 1394.46  4704.4 1390.55  4769.4 1387.77  4813.4 1383.75  4879.1 1370.89
  4915.7 1365.92  4958.9 1363.91    4976 1359.94  4976.5 1359.44    5005 1359.94
  5032.5 1367.31  5046.6 1375.76  5074.9 1385.58  5103.2 1388.64  5144.2 1387.76
  5279.1 1387.57  5598.2 1389.68  5654.7 1394.03  5683.9 1402.76  5725.5 1399.49
  5781.8 1410.19  5810.3  1415.4  5838.6  1425.3  5866.9 1430.05  5895.2 1439.29
  5928.6 1442.33  5994.2 1457.72  6050.7 1480.79  6098.6 1490.26  6135.6 1494.22
#Mann= 12 ,-1 , 0
  4601.1     .07       0  4704.4     .12       0  4769.4     .07       0
  4879.1     .12       0    4976     .05       0    5005     .12       0
  5144.2     .07       0  5279.1    .035       0  5683.9     .07       0
  5781.8     .12       0  5928.6     .07       0  6098.6     .12       0
Bank Sta=4976,5005
XS Rating Curve= 0 ,0
Exp/Cntr=0.3,0.1

Type RM Length L Ch R = 1 ,7755    ,513,513,513
BEGIN DESCRIPTION:
BIG JOSHUA CREEK 14.0
END DESCRIPTION:
XS GIS Cut Line= 3
      2029775.02     13880824.97        2030025.       13880475.
      2030825.01     13879774.99
#Sta/Elev= 30
  4565.4 1399.48  4647.8 1390.83    4720 1385.65  4916.8 1380.27  4958.6 1364.96
  4970.2 1363.58  4988.9 1360.64  5008.9 1357.47  5009.4 1356.97  5038.1 1357.47
  5073.8 1360.65  5131.7 1375.56  5158.2  1381.7    5276 1379.35  5443.6 1388.95
  5470.5 1391.61  5499.5 1397.88  5519.9 1394.13  5564.5 1396.75  5634.1    1404
  5789.4 1417.26    5853 1426.12  5895.7 1436.71  5945.1 1444.25  5973.5 1457.81
  6008.7  1463.6  6030.5 1473.01  6051.4 1477.24  6055.2 1480.83  6058.5 1480.83
#Mann= 13 ,-1 , 0
  4565.4     .07       0  4647.8     .12       0    4720     .07       0
  4970.2     .12       0  4988.9     .07       0  5008.9     .05       0
  5038.1     .07       0  5131.7     .12       0    5276    .035       0
  5443.6     .07       0  5499.5    .035       0  5564.5     .07       0
  5634.1     .12       0
Bank Sta=5008.9,5038.1
XS Rating Curve= 0 ,0
Exp/Cntr=0.3,0.1

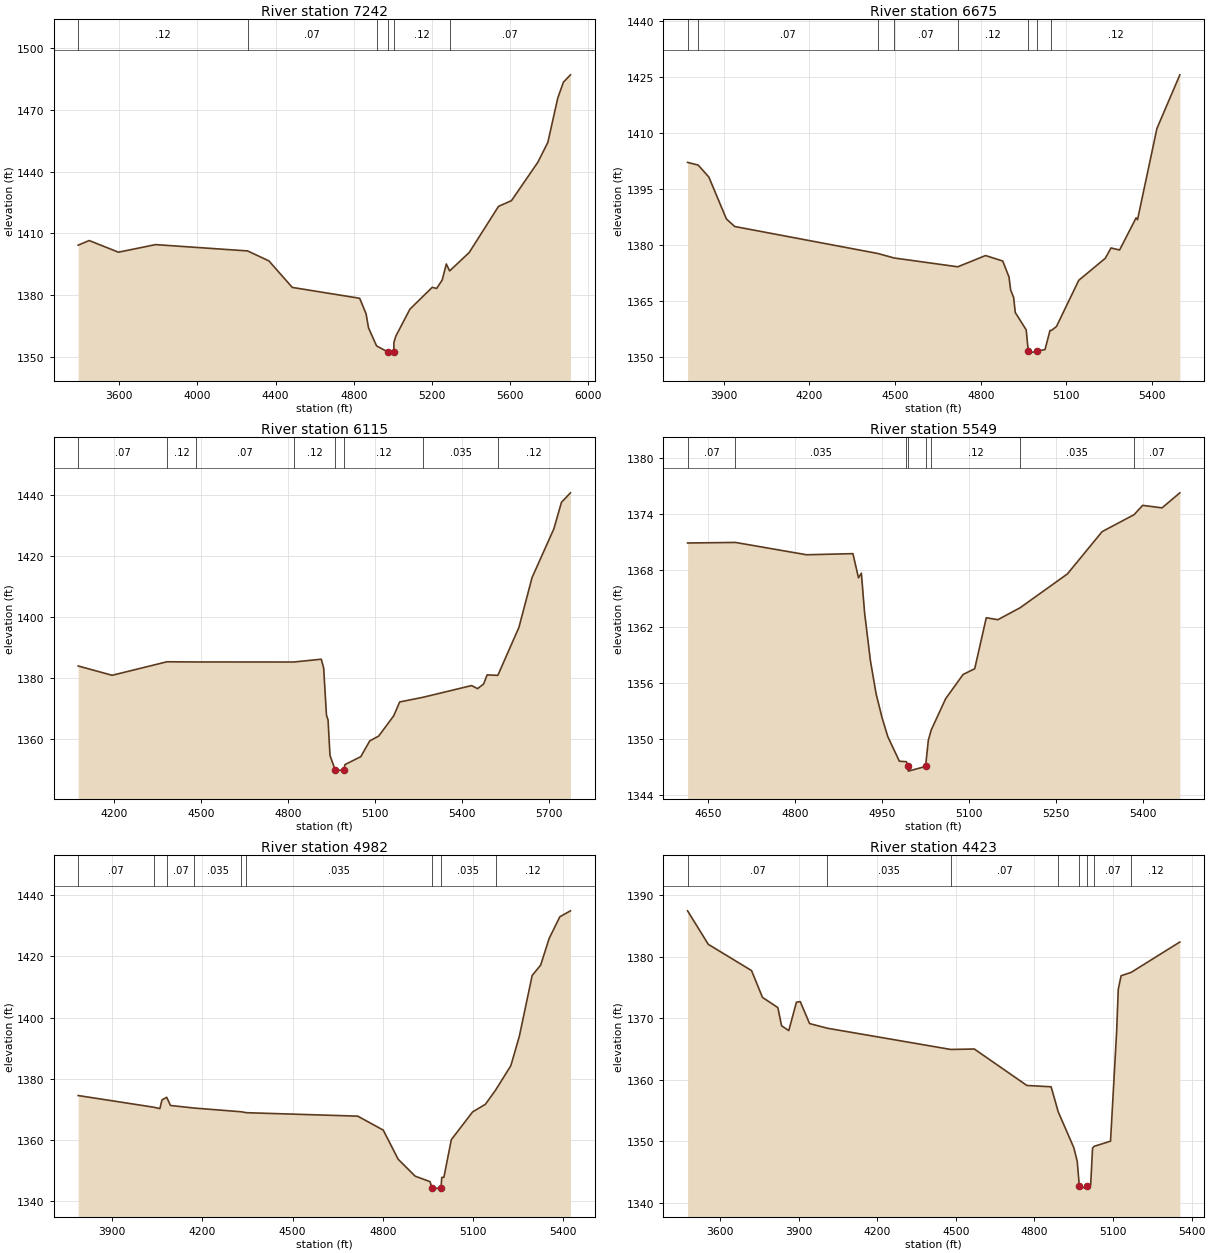
Type RM Length L Ch R = 1 ,7242    ,567,567,567
BEGIN DESCRIPTION:
BIG JOSHUA CREEK 13.0
END DESCRIPTION:
XS GIS Cut Line= 3
      2028911.09     13881093.47        2030475.       13880675.
      2030974.99     13879925.01
#Sta/Elev= 30
  3389.2 1404.26  3445.7 1406.51  3595.6 1400.85  3785.5 1404.53  4256.7 1401.46
  4365.5 1396.65  4485.6 1383.74  4830.5 1378.47  4863.2 1370.97  4875.7 1364.14
    4917 1355.35    4976 1352.34  4976.5 1351.84  5005.4 1352.34  5005.5 1356.93
  5015.6 1360.09  5087.7 1373.19  5201.9 1383.79  5224.5 1383.24    5253 1387.35
    5274 1395.13  5291.1 1391.76  5391.2 1400.69  5541.4 1423.11  5607.5 1425.87
  5742.8 1444.54  5793.8 1454.17  5844.9 1475.79  5873.5 1483.41  5909.5 1486.97
#Mann= 6 ,-1 , 0
  3389.2     .12       0  4256.7     .07       0    4917     .12       0
    4976     .05       0  5005.4     .12       0  5291.1     .07       0
Bank Sta=4976,5005.4
XS Rating Curve= 0 ,0
Exp/Cntr=0.3,0.1

Type RM Length L Ch R = 1 ,6675    ,560,560,560
BEGIN DESCRIPTION:
BIG JOSHUA CREEK 12.0
END DESCRIPTION:
XS GIS Cut Line= 4
      2029730.74     13880945.32      2030763.44     13881060.99
        2030925.       13880975.        2030975.     13880474.97
#Sta/Elev= 30
    3773 1402.22  3810.3  1401.5  3847.7 1398.28    3909 1387.07  3938.3 1385.04
  4439.3 1377.82  4496.7 1376.61  4719.7 1374.25  4816.9 1377.26  4877.2  1375.8
  4899.1 1371.52  4904.8 1368.07  4915.4 1366.03  4921.1 1362.01  4959.4 1357.35
  4966.7 1351.62  4967.2 1351.12  4996.1 1351.62  5025.3 1352.08  5042.9 1357.22
  5047.6 1357.19  5065.5 1358.26  5143.4 1370.62  5236.4 1376.53  5256.5  1379.3
  5286.6 1378.75  5344.4 1387.36  5349.4 1386.86  5417.3 1411.29  5497.7 1425.68
#Mann= 8 ,-1 , 0
    3773     .12       0  3810.3     .07       0  4439.3     .12       0
  4496.7     .07       0  4719.7     .12       0  4966.7     .05       0
  4996.1     .12       0  5047.6     .12       0
Bank Sta=4966.7,4996.1
XS Rating Curve= 0 ,0
Exp/Cntr=0.3,0.1

Type RM Length L Ch R = 1 ,6115    ,566,566,566
BEGIN DESCRIPTION:
BIG JOSHUA CREEK 11.0
END DESCRIPTION:
XS GIS Cut Line= 3
      2031055.19     13881922.44        2031425.       13881075.
      2031225.01     13880325.03
#Sta/Elev= 30
    4075 1383.88  4192.4 1380.82  4381.7 1385.25  4483.4 1385.19  4820.3 1385.17
    4915  1386.1  4923.2 1383.22  4932.9 1367.75  4938.4 1366.18  4945.1 1354.54
  4962.6 1349.89  4963.1 1349.39  4992.9 1349.89  4996.9 1351.54  5051.4 1354.13
  5082.4  1359.3  5113.5  1360.9  5165.2 1367.54  5185.9 1372.08  5266.6 1373.61
  5434.3 1377.45    5455 1376.45  5475.7 1377.95    5488 1380.95    5525  1380.8
  5597.9 1396.56  5643.2 1412.88  5718.3  1428.8  5744.8 1437.56  5775.8 1440.66
#Mann= 8 ,-1 , 0
    4075     .07       0  4381.7     .12       0  4483.4     .07       0
  4820.3     .12       0  4962.6     .05       0  4992.9     .12       0
  5266.6    .035       0    5525     .12       0
Bank Sta=4962.6,4992.9
XS Rating Curve= 0 ,0
Exp/Cntr=0.3,0.1

Type RM Length L Ch R = 1 ,5549    ,567,567,567
BEGIN DESCRIPTION:
BIG JOSHUA CREEK 10.0
END DESCRIPTION:
XS GIS Cut Line= 3
      2031952.58     13881410.15        2031975.       13881025.
      2031991.13     13880560.88
#Sta/Elev= 30
  4614.2 1370.94  4696.9    1371  4819.7 1369.68  4899.8  1369.8  4909.4 1367.21
  4914.4 1367.71  4919.9 1363.49  4929.9 1358.38  4939.9 1354.77  4949.9 1352.29
  4959.9 1350.23    4980 1347.58    4992 1347.53  4994.9 1347.02  4995.4 1346.52
  5025.2 1347.02    5030 1349.82  5034.9 1350.91    5060 1354.28  5090.1 1356.87
  5110.1 1357.48  5130.1 1362.94  5150.1 1362.73  5188.6 1364.01  5270.2 1367.63
  5330.2 1372.16  5385.3 1373.97  5400.2 1374.97  5433.6  1374.7  5464.4 1376.31
#Mann= 8 ,-1 , 0
  4614.2     .07       0  4696.9    .035       0    4992     .07       0
  4994.9     .05       0  5025.2     .07       0  5034.9     .12       0
  5188.6    .035       0  5385.3     .07       0
Bank Sta=4994.9,5025.2
XS Rating Curve= 0 ,0
Exp/Cntr=0.3,0.1

Type RM Length L Ch R = 1 ,4982    ,559,559,559
BEGIN DESCRIPTION:
BIG JOSHUA CREEK 9.0
END DESCRIPTION:
XS GIS Cut Line= 3
      2031662.85     13881826.95        2032525.       13880975.
      2032824.97     13880675.03
#Sta/Elev= 30
  3787.3 1374.53  4038.1 1370.72  4058.9 1370.26    4066  1373.1  4081.6 1373.95
  4094.3 1371.28  4172.7 1370.44  4329.3 1369.22  4346.6 1368.92  4716.6 1367.79
  4801.4 1363.23  4850.9 1353.72  4907.4 1348.17    4957 1346.37    4963 1344.43
  4963.5 1343.93  4993.4 1344.43  4995.9 1347.77  5002.9 1347.77  5027.7 1360.11
  5098.4 1369.17  5140.8 1371.66  5174.6 1376.27  5225.6 1384.31  5253.9 1393.98
  5296.4 1413.78  5324.6 1417.18  5352.9  1425.9  5388.3 1432.97  5423.6 1434.92
#Mann= 9 ,-1 , 0
  3787.3     .07       0  4038.1     .12       0  4081.6     .07       0
  4172.7    .035       0  4329.3     .07       0  4346.6    .035       0
    4963     .05       0  4993.4    .035       0  5174.6     .12       0
Bank Sta=4963,4993.4
XS Rating Curve= 0 ,0
Exp/Cntr=0.3,0.1

Type RM Length L Ch R = 1 ,4423    ,544,544,544
BEGIN DESCRIPTION:
BIG JOSHUA CREEK 8.0
END DESCRIPTION:
XS GIS Cut Line= 3
      2031645.45     13882226.28        2032875.       13881325.
      2033200.89     13881183.97
#Sta/Elev= 30
  3475.5 1387.49  3554.7 1382.04  3719.8 1377.77  3761.5 1373.41  3820.2 1371.75
  3834.5 1368.79  3861.9 1368.01  3891.2 1372.63  3905.8 1372.72  3941.4 1369.15
  4009.7 1368.39  4480.4 1364.94  4570.5 1365.01  4771.1 1359.08  4863.6 1358.87
  4890.9 1354.77  4950.4 1348.95  4963.4 1346.72  4971.2 1342.72  4971.7 1342.22
  5001.7 1342.72  5014.5 1342.86  5021.8  1348.9  5027.7 1349.18  5090.4 1350.02
  5113.9 1367.99  5119.9 1374.72  5130.8 1376.93  5169.3 1377.48  5355.1 1382.42
#Mann= 8 ,-1 , 0
  3475.5     .07       0  4009.7    .035       0  4480.4     .07       0
  4890.9    .035       0  4971.2    .035       0  5001.7    .035       0
  5027.7     .07       0  5169.3     .12       0
Bank Sta=4971.2,5001.7
XS Rating Curve= 0 ,0
Exp/Cntr=0.3,0.1