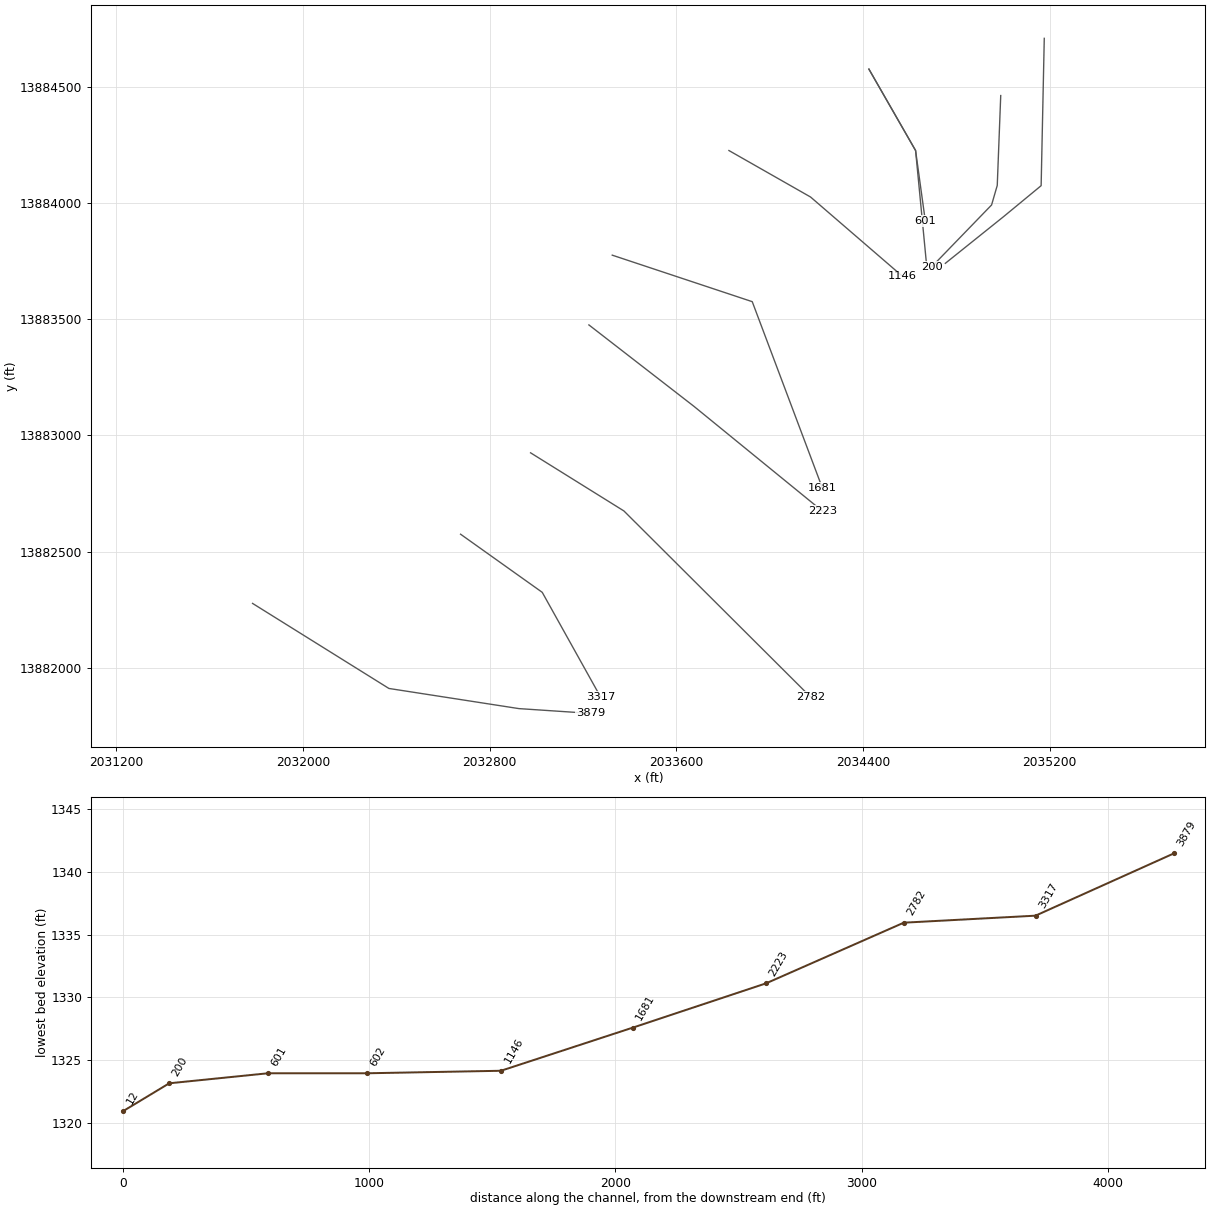
HEC-RAS study BIG JOSHUA CREEK.prj: BIG JOSHUA CREEK Base Level Engineering

--- BIG JOSHUA CREEK.g01 (geometry) --- (continued)

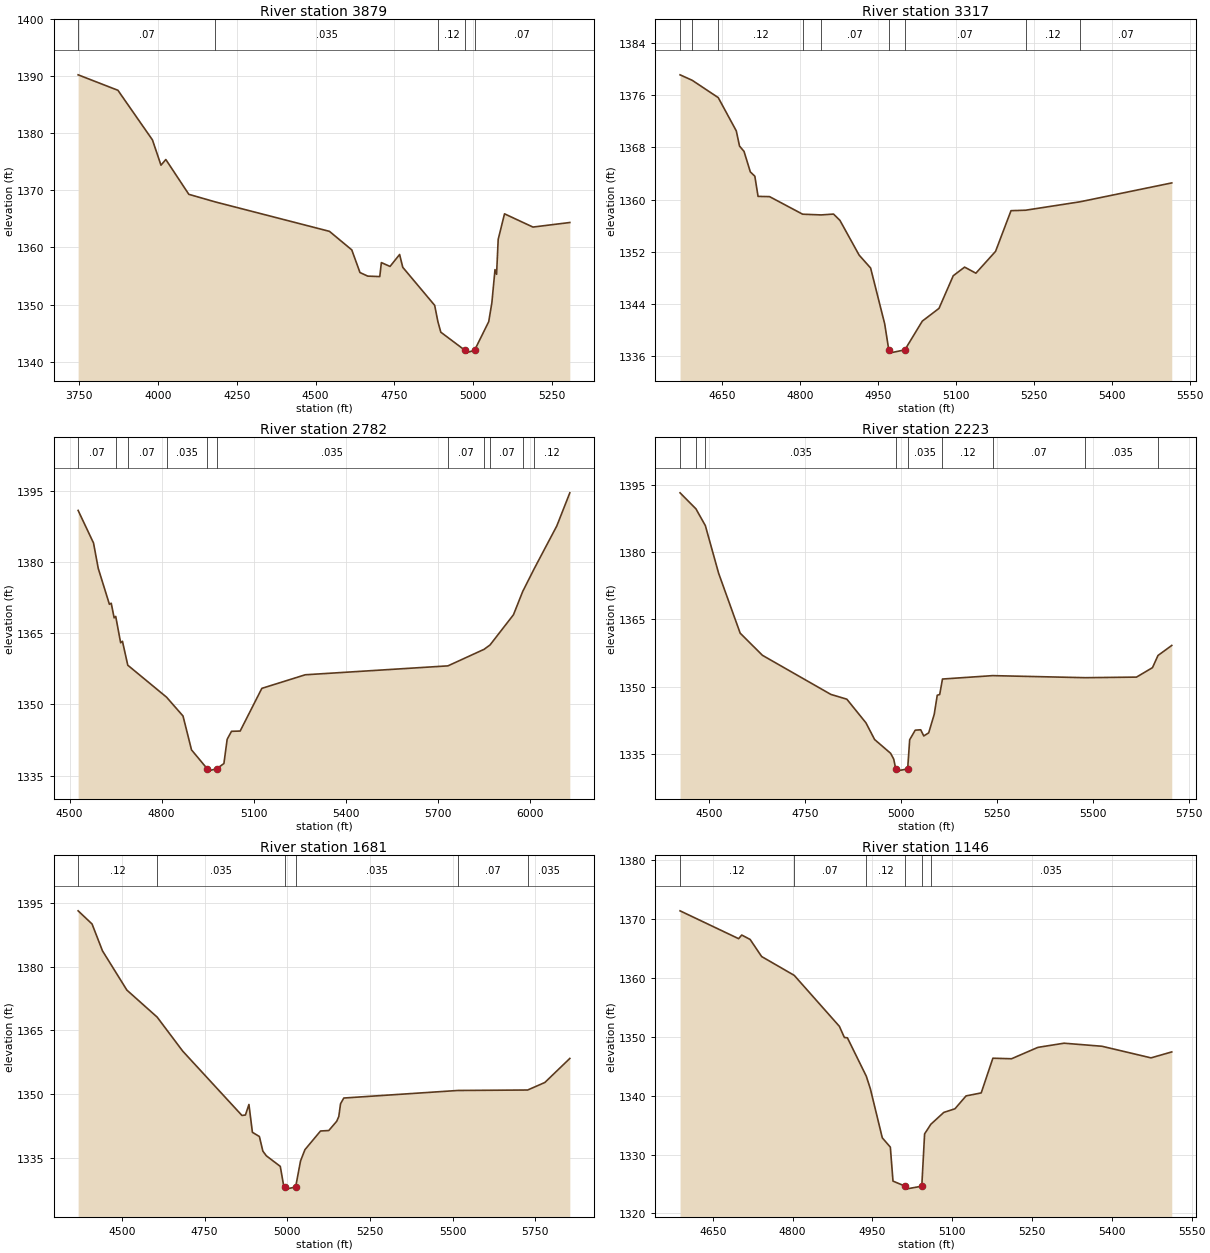
Type RM Length L Ch R = 1 ,3879    ,562,562,562
BEGIN DESCRIPTION:
BIG JOSHUA CREEK 7.0
END DESCRIPTION:
XS GIS Cut Line= 4
      2031783.57     13882277.39      2032367.85     13881911.66
        2032925.       13881825.      2033231.86     13881804.48
#Sta/Elev= 30
  3746.5 1390.27  3872.8 1387.56  3982.4 1378.86  4009.5 1374.43  4024.9 1375.42
  4097.9 1369.32  4182.5 1367.98  4544.2 1362.83  4615.1 1359.58  4641.1 1355.61
  4665.7 1354.98    4704  1354.9    4709 1357.35  4736.5 1356.68  4766.9 1358.77
    4777 1356.52  4878.2 1349.86  4888.4 1347.01  4897.7 1345.15  4974.3 1341.98
  4974.8 1341.48  5004.8 1341.98  5049.8    1347  5059.8 1350.33  5069.7 1356.12
  5074.7  1355.3  5079.8 1361.41  5099.9  1365.9  5190.1 1363.58  5307.2 1364.38
#Mann= 5 ,-1 , 0
  3746.5     .07       0  4182.5    .035       0  4888.4     .12       0
  4974.3     .05       0  5004.8     .07       0
Bank Sta=4974.3,5004.8
XS Rating Curve= 0 ,0
Exp/Cntr=0.3,0.1

Type RM Length L Ch R = 1 ,3317    ,535,535,535
BEGIN DESCRIPTION:
BIG JOSHUA CREEK 6.0
END DESCRIPTION:
XS GIS Cut Line= 3
      2032675.03     13882574.98        2033025.       13882325.
      2033275.02     13881874.97
#Sta/Elev= 30
  4569.9 1379.12  4593.3 1378.28  4643.3 1375.63    4678 1370.53  4684.2 1368.21
  4692.8  1367.4    4705 1364.25  4713.6  1363.6  4719.8 1360.51  4741.9 1360.47
  4805.5 1357.78    4841 1357.67  4864.8  1357.8  4877.1 1356.84    4914 1351.52
  4936.1 1349.54  4963.1 1341.01    4971 1337.01  4971.5 1336.51  5001.9 1337.01
  5035.4 1341.41  5067.5 1343.36  5094.9 1348.36  5116.7 1349.68  5138.4 1348.75
  5176.2 1352.09  5205.9 1358.32  5233.9 1358.39  5338.5 1359.68  5514.8 1362.57
#Mann= 9 ,-1 , 0
  4569.9    .035       0  4593.3     .07       0  4643.3     .12       0
  4805.5    .035       0    4841     .07       0    4971     .05       0
  5001.9     .07       0  5233.9     .12       0  5338.5     .07       0
Bank Sta=4971,5001.9
XS Rating Curve= 0 ,0
Exp/Cntr=0.3,0.1

Type RM Length L Ch R = 1 ,2782    ,559,559,559
BEGIN DESCRIPTION:
BIG JOSHUA CREEK 5.0
END DESCRIPTION:
XS GIS Cut Line= 3
      2032974.96     13882925.02        2033375.       13882675.
      2034174.99     13881875.01
#Sta/Elev= 30
  4527.8 1390.91    4578 1384.04  4593.3 1378.72  4629.8 1371.12  4635.7 1371.35
  4645.2 1368.27  4650.4 1368.56  4666.4 1363.01  4672.3 1363.33  4689.7 1358.28
  4816.1 1351.54  4869.8 1347.57  4897.5 1340.43  4948.7 1336.45  4949.2 1335.95
  4979.6 1336.45  5003.1 1337.55  5013.7 1342.66  5027.8 1344.34  5056.1  1344.4
  5126.8  1353.4  5268.2 1356.26  5733.5 1358.14  5851.4 1361.63  5870.6 1362.54
  5947.1 1368.91  5977.4 1373.84  6014.5 1378.59  6088.5 1387.65  6130.9 1394.62
#Mann= 11 ,-1 , 0
  4527.8     .07       0  4650.4     .12       0  4689.7     .07       0
  4816.1    .035       0  4948.7    .035       0  4979.6    .035       0
  5733.5     .07       0  5851.4    .035       0  5870.6     .07       0
  5977.4    .035       0  6014.5     .12       0
Bank Sta=4948.7,4979.6
XS Rating Curve= 0 ,0
Exp/Cntr=0.3,0.1

Type RM Length L Ch R = 1 ,2223    ,542,542,542
BEGIN DESCRIPTION:
BIG JOSHUA CREEK 4.0
END DESCRIPTION:
XS GIS Cut Line= 3
      2033224.98     13883475.01        2033675.       13883125.
      2034224.97     13882675.03
#Sta/Elev= 30
  4425.1 1393.24  4466.5 1389.66    4491 1385.92  4525.6 1375.27  4581.7 1361.91
  4639.6 1356.97  4817.8 1348.24  4859.5 1347.17  4909.2  1341.9  4931.9 1338.16
  4973.5 1335.09  4981.6  1333.8  4986.9 1331.61  4987.4 1331.11  5017.9 1331.61
  5023.2 1338.12  5037.6 1340.25  5051.9 1340.34  5059.8 1338.97  5072.7 1339.65
  5087.1 1343.79    5095 1348.05  5101.4 1348.22  5108.6 1351.67  5239.3 1352.43
  5480.5 1351.97    5614  1352.1  5655.6 1354.21    5670 1356.93  5705.8 1359.17
#Mann= 9 ,-1 , 0
  4425.1    .035       0  4466.5     .07       0    4491    .035       0
  4986.9    .035       0  5017.9    .035       0  5108.6     .12       0
  5239.3     .07       0  5480.5    .035       0    5670     .07       0
Bank Sta=4986.9,5017.9
XS Rating Curve= 0 ,0
Exp/Cntr=0.3,0.1

Type RM Length L Ch R = 1 ,1681    ,535,535,535
BEGIN DESCRIPTION:
BIG JOSHUA CREEK 3.0
END DESCRIPTION:
XS GIS Cut Line= 3
      2033325.04     13883774.99        2033925.       13883575.
      2034224.99     13882775.02
#Sta/Elev= 30
  4367.6 1393.16  4409.7 1390.06  4441.3 1383.72  4515.1 1374.47  4606.6 1368.11
  4683.8  1360.1    4863 1344.93  4873.5 1345.04  4884.1 1347.52  4894.6 1340.96
  4915.7 1339.97  4926.2 1336.53  4936.8 1335.42  4978.9 1332.93  4989.5  1328.2
  4994.3 1328.07  4994.8 1327.57  5025.3 1328.07  5040.1  1334.2  5053.4 1336.87
  5100.6 1341.27  5125.5 1341.38  5149.5 1343.56  5155.8 1344.68  5161.1 1347.69
  5170.9 1349.04  5515.7 1350.82  5726.9 1350.93  5778.8  1352.7  5854.4 1358.37
#Mann= 6 ,-1 , 0
  4367.6     .12       0  4606.6    .035       0  4994.3    .035       0
  5025.3    .035       0  5515.7     .07       0  5726.9    .035       0
Bank Sta=4994.3,5025.3
XS Rating Curve= 0 ,0
Exp/Cntr=0.3,0.1

Type RM Length L Ch R = 1 ,1146    ,544,544,544
BEGIN DESCRIPTION:
BIG JOSHUA CREEK 2.0
END DESCRIPTION:
XS GIS Cut Line= 3
      2033825.02     13884224.99        2034175.       13884025.
      2034568.96     13883684.05
#Sta/Elev= 30
  4588.5 1371.39  4698.6 1366.66  4704.4 1367.28  4720.2 1366.53  4741.8 1363.63
  4803.1 1360.43  4887.9 1351.78  4897.3 1349.89    4903 1349.83  4938.5 1343.31
  4946.2 1341.15  4968.6 1332.84  4983.7 1331.26  4988.7 1325.49  5011.7 1324.63
  5012.2 1324.13  5042.8 1324.63  5048.1 1333.51  5059.8 1335.14  5084.2 1337.16
  5105.1 1337.77    5126 1339.96  5154.5 1340.47  5176.4 1346.36  5211.5 1346.27
  5260.9  1348.2  5310.2 1348.91  5381.5 1348.39  5473.6 1346.42  5512.6 1347.43
#Mann= 6 ,-1 , 0
  4588.5     .12       0  4803.1     .07       0  4938.5     .12       0
  5011.7     .05       0  5042.8     .12       0  5059.8    .035       0
Bank Sta=5011.7,5042.8
XS Rating Curve= 0 ,0
Exp/Cntr=0.3,0.1

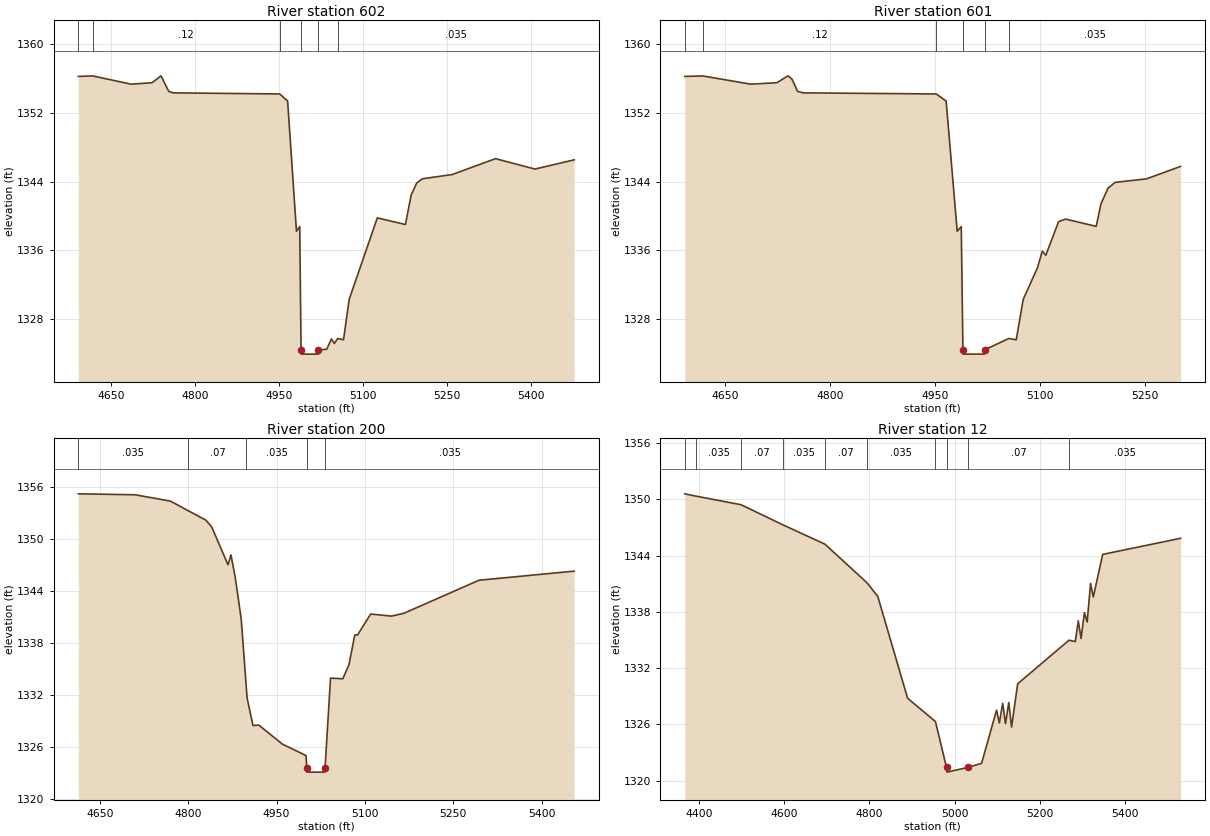
Type RM Length L Ch R = 1 ,602     ,402,402,402
BEGIN DESCRIPTION:
BIG JOSHUA CREEK 1.0
END DESCRIPTION:
XS GIS Cut Line= 3
        2034425.     13884575.01        2034625.       13884225.
      2034670.98     13883745.22
#Sta/Elev= 30
  4592.1 1356.22  4617.7 1356.28  4686.4 1355.32  4723.8 1355.49  4739.7 1356.29
  4753.4 1354.49  4761.3 1354.31  4951.6 1354.18  4965.7 1353.36  4981.5 1338.22
  4987.3 1338.76  4989.7 1324.43  4990.2 1323.93  5020.3 1323.93  5020.8 1324.43
  5035.4 1324.49    5044  1325.7  5049.1 1325.17  5055.2 1325.75  5065.5  1325.6
  5075.6  1330.3  5125.8 1339.77    5176    1339  5186.1 1342.39  5196.1 1343.82
  5206.2 1344.32  5259.4 1344.81  5336.8 1346.66  5407.1 1345.45  5477.2 1346.52
#Mann= 6 ,-1 , 0
  4592.1     .07       0  4617.7     .12       0  4951.6     .07       0
  4989.7     .05       0  5020.8     .07       0  5055.2    .035       0
Bank Sta=4989.7,5020.8
XS Rating Curve= 0 ,0
Exp/Cntr=0.3,0.1

Type RM Length L Ch R = 1 ,601     ,401,401,401
BEGIN DESCRIPTION:
BIG JOSHUA CREEK 1.0
END DESCRIPTION:
XS GIS Cut Line= 3
      2034425.01     13884574.98        2034625.       13884225.
      2034666.71     13883922.15
#Sta/Elev= 30
    4592 1356.22  4617.5 1356.28  4686.3 1355.32  4723.7 1355.49  4739.5 1356.29
  4745.3  1355.9  4753.2 1354.49  4761.1 1354.31  4951.5 1354.18  4965.6 1353.36
  4981.4 1338.22  4987.2 1338.76  4989.6 1324.43  4990.1 1323.93  5020.2 1323.93
  5020.7 1324.43  5055.2 1325.75  5065.8  1325.6  5075.8  1330.3    5096 1333.94
  5103.1  1335.9  5108.1 1335.43  5126.3 1339.33  5136.4 1339.63  5180.1 1338.79
  5186.9 1341.39    5197 1343.22  5207.1  1343.9  5252.1 1344.31  5300.8 1345.76
#Mann= 6 ,-1 , 0
    4592     .07       0  4617.5     .12       0  4951.5     .07       0
  4989.6     .05       0  5020.7     .07       0  5055.2    .035       0
Bank Sta=4989.6,5020.7
XS Rating Curve= 0 ,0
Exp/Cntr=0.3,0.1

Type RM Length L Ch R = 1 ,200     ,188,188,188
BEGIN DESCRIPTION:
BIG JOSHUA CREEK 0.1
END DESCRIPTION:
XS GIS Cut Line= 4
       2034989.9     13884461.38        2034975.       13884075.
      2034950.71      13883990.9      2034695.34     13883726.22
#Sta/Elev= 30
  4613.3 1355.24  4709.8 1355.13  4769.8  1354.4  4800.2 1353.28  4829.8 1352.21
  4839.8 1351.42  4867.5 1347.05  4872.5  1348.2  4879.9 1345.55  4889.9  1340.8
  4898.7 1332.77  4899.9 1331.68  4909.9 1328.51  4919.9 1328.55  4959.9 1326.36
    5000 1325.04  5001.2 1323.63  5001.7 1323.13  5031.8 1323.13  5032.3 1323.63
  5041.6 1333.98  5062.4  1333.9  5072.8  1335.5  5082.8 1338.96  5087.5 1338.96
  5109.7 1341.37  5145.2 1341.13  5166.3 1341.46  5293.7 1345.27  5455.3 1346.32
#Mann= 5 ,-1 , 0
  4613.3    .035       0  4800.2     .07       0  4898.7    .035       0
  5001.2    .035       0  5032.3    .035       0
Bank Sta=5001.2,5032.3
XS Rating Curve= 0 ,0
Exp/Cntr=0.3,0.1

Type RM Length L Ch R = 1 ,12      ,0,0,0
BEGIN DESCRIPTION:
BIG JOSHUA CREEK 0.0
END DESCRIPTION:
XS GIS Cut Line= 4
      2035176.49     13884707.46      2035163.07     13884073.87
       2035002.1     13883940.69      2034752.56     13883739.97
#Sta/Elev= 30
  4367.4 1350.58  4394.1 1350.33  4499.2 1349.42  4597.6 1347.27  4696.1 1345.21
  4794.6  1341.1    4820 1339.64    4890 1328.78  4955.3 1326.29  4981.2  1321.4
  4982.2  1320.9  5031.2  1321.4  5063.5 1321.84  5098.6 1327.51  5105.1 1326.14
    5113 1328.23  5119.5 1326.07  5127.3 1328.31  5133.8 1325.71  5148.1 1330.32
  5268.5 1334.97  5283.3 1334.82  5290.3 1337.03  5296.8 1335.16  5304.7  1337.9
  5311.1 1336.91  5319.1 1341.03  5325.5 1339.58  5347.5 1344.12  5530.3 1345.84
#Mann= 10 ,-1 , 0
  4367.4     .07       0  4394.1    .035       0  4499.2     .07       0
  4597.6    .035       0  4696.1     .07       0  4794.6    .035       0
  4955.3     .07       0  4981.2     .05       0  5031.2     .07       0
  5268.5    .035       0
Bank Sta=4981.2,5031.2
XS Rating Curve= 0 ,0
Exp/Cntr=0.3,0.1

Chan Stop Cuts=-1
Use User Specified Reach Order=0
Composite Channel Slope=5