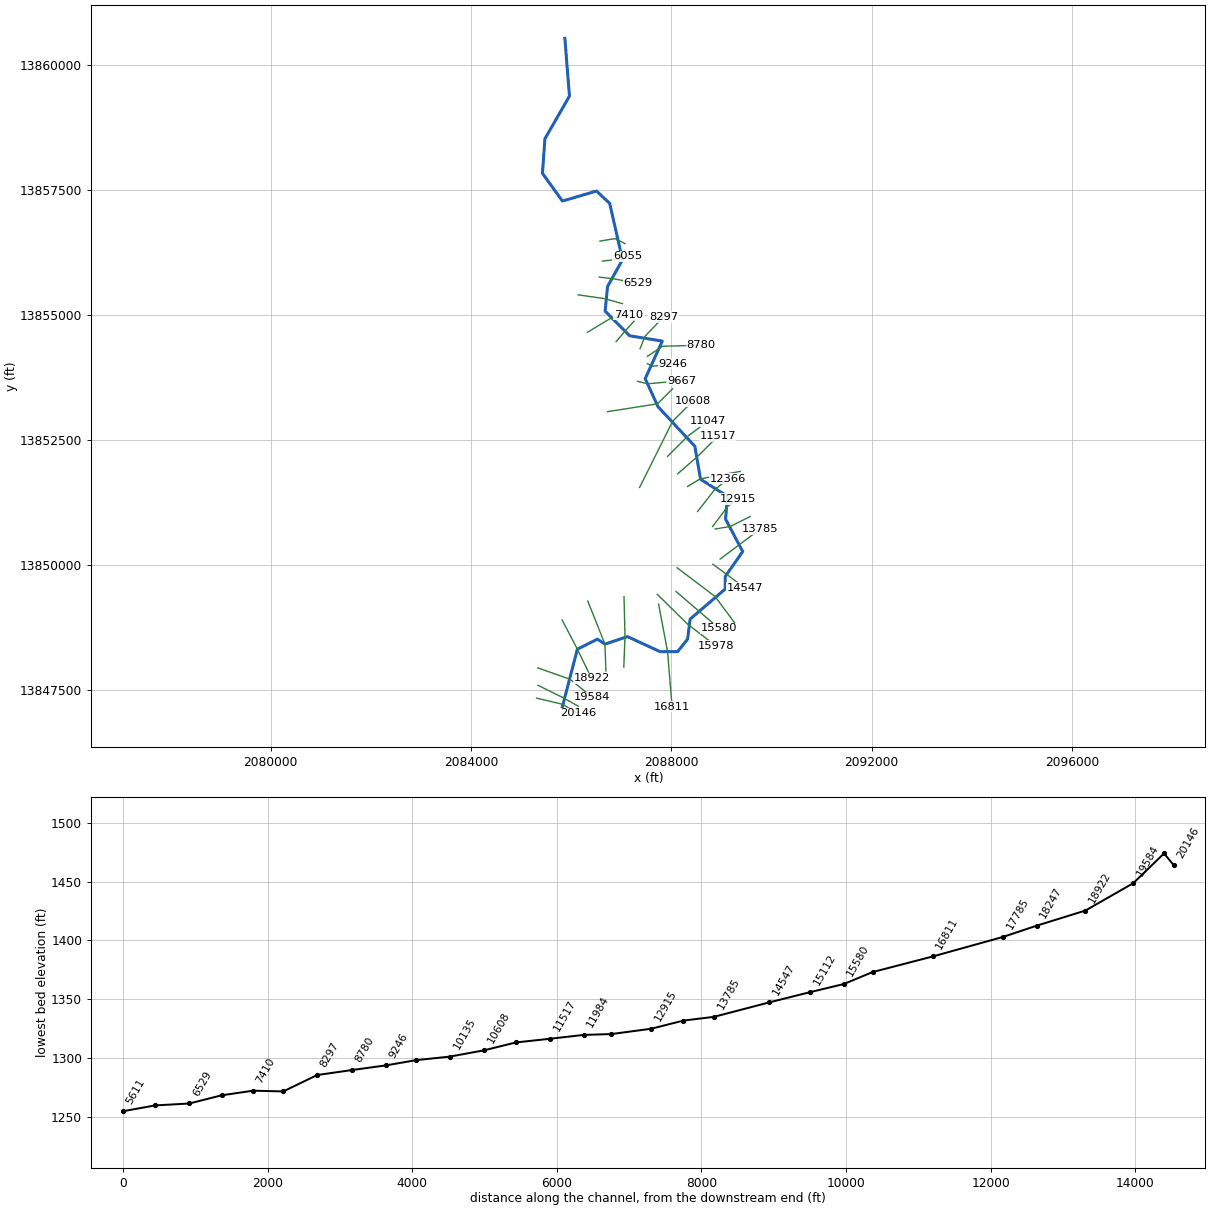
--- BLACK CREEK.prj (project) ---

Proj Title=BLACK CREEK Base Level Engineering
Current Plan=p01
Default Exp/Contr=0.3,0.1
English Units
Geom File=g01
Flow File=f01
Plan File=p01
Y Axis Title=Elevation
X Axis Title(PF)=Main Channel Distance
X Axis Title(XS)=Station
BEGIN DESCRIPTION:
BLACK CREEK
END DESCRIPTION:
DSS Export Rating Curves= 0
DSS Export Rating Curve Sorted= 0
DSS Export Volume Flow Curves= 0
DXF OffsetX= 0
DXF OffsetY= 0
DXF ScaleX= 1
DXF ScaleY= 10

--- BLACK CREEK.p01 (plan) ---

Plan Title=Multiple Run
Short Identifier=Multiple
Geom File=g01
Flow File=f01
Subcritical Flow
K Sum by GR= 0
Std Step Tol= 0.01
Critical Tol= 0.01
Num of Std Step Trials= 20
Max Error Tol= 0.3
Flow Tol Ratio= 0.001
Split Flow NTrial= 30
Split Flow Tol= 0.02
Split Flow Ratio= 0.02
Log Output Level= 0
Friction Slope Method= 1
Unsteady Friction Slope Method= 2
Unsteady Bridges Friction Slope Method= 1
Parabolic Critical Depth
Global Vel Dist=  1 , 1 , 1
Global Log Level= 0
CheckData=True
Encroach Param= -1, 0, 0, 0
BEGIN DESCRIPTION:
Multiple Run
END DESCRIPTION:

--- BLACK CREEK.f01 (steady flow) ---

Flow Title=Multiple
Number of Profiles=7
Profile Names=10-year,25-year,50-year,1pct_min,100-year,1pct_plu,500-year
River Rch & RM= BLACK CREEK,Reach-1,20146
     324     505     664     427     851    1698    1374
River Rch & RM= BLACK CREEK,Reach-1,18247
     964    1620    2239    1503    2999    5984    5313
River Rch & RM= BLACK CREEK,Reach-1,15580
    1803    3141    4451    3054    6093   12158   11295
River Rch & RM= BLACK CREEK,Reach-1,13785
    1945    3387    4797    3287    6559   13087   12131
River Rch & RM= BLACK CREEK,Reach-1,10135
    2581    4553    6501    4487    8953   17864   16803
River Rch & RM= BLACK CREEK,Reach-1,6529
    2743    4847    6931    4789    9554   19064   17969
River Rch & RM= BLACK CREEK,Reach-1,3736
    3575    6394    9215    6412   12793   25526   24406
Boundary for River Rch & Prof#=BLACK CREEK,Reach-1,1
Up Type=0
Dn Type=3
Dn Slope=0.005
Boundary for River Rch & Prof#=BLACK CREEK,Reach-1,2
Up Type=0
Dn Type=3
Dn Slope=0.005
Boundary for River Rch & Prof#=BLACK CREEK,Reach-1,3
Up Type=0
Dn Type=3
Dn Slope=0.005
Boundary for River Rch & Prof#=BLACK CREEK,Reach-1,4
Up Type=0
Dn Type=3
Dn Slope=0.005
Boundary for River Rch & Prof#=BLACK CREEK,Reach-1,5
Up Type=0
Dn Type=3
Dn Slope=0.005
Boundary for River Rch & Prof#=BLACK CREEK,Reach-1,6
Up Type=0
Dn Type=3
Dn Slope=0.005
Boundary for River Rch & Prof#=BLACK CREEK,Reach-1,7
Up Type=0
Dn Type=3
Dn Slope=0.005

--- BLACK CREEK.g01 (geometry) ---

Geom Title=Existing Conditions
Program Version=4.10

River Reach=BLACK CREEK     ,Reach-1
Reach XY= 30
        2085825.       13847175.        2086125.       13848325.
        2086525.       13848525.        2086675.       13848425.
        2087125.       13848575.        2087775.       13848275.
        2088125.       13848275.        2088325.       13848525.
        2088375.       13848925.        2089075.       13849525.
        2089075.       13849775.        2089425.       13850275.
      2089082.81     13850921.59      2089119.54     13851377.45
      2088582.74     13851718.54      2088469.46     13852377.42
      2087735.76     13853165.32      2087478.34     13853726.72
      2087819.66     13854477.73      2087168.27     13854584.15
      2086678.75     13855076.55      2086727.33     13855569.03
       2087025.5     13856102.25      2086769.64      13857227.7
      2086506.73     13857475.35        2085825.       13857275.
      2085427.35     13857830.52      2085477.35     13858519.48
       2085966.9     13859371.71        2085875.       13860525.

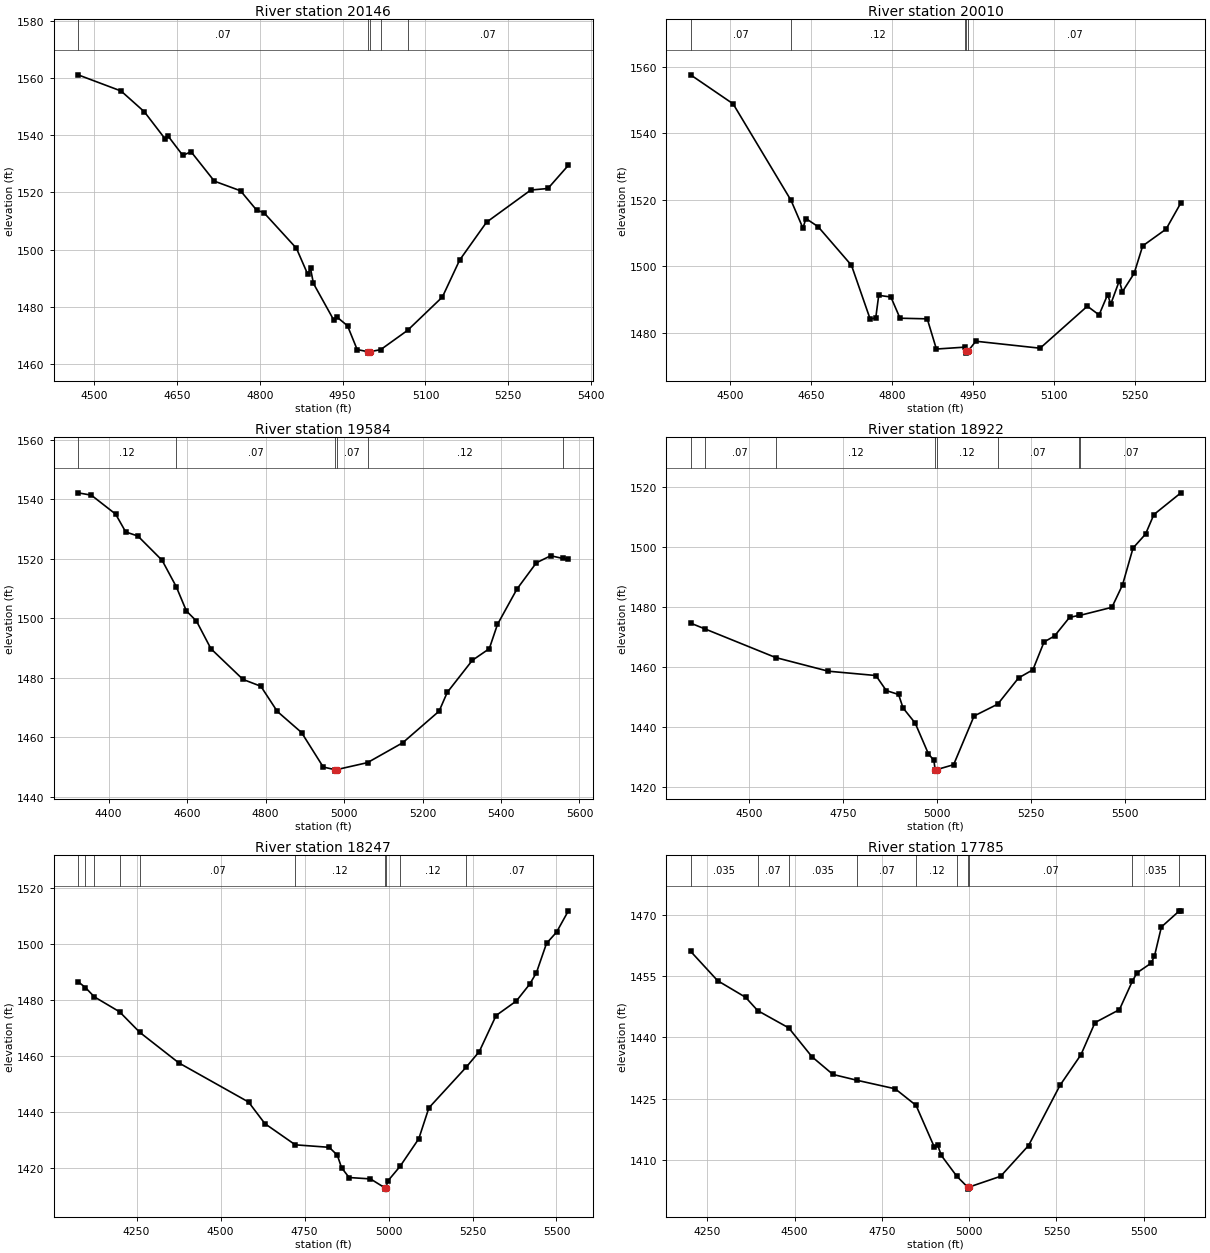
Type RM Length L Ch R = 1 ,20146   ,136,136,136
BEGIN DESCRIPTION:
BLACK CREEK 38.0
END DESCRIPTION:
XS GIS Cut Line= 3
      2085310.48     13847347.06        2085825.       13847225.
      2086133.48     13847042.14
#Sta/Elev= 30
  4471.2 1561.21    4549 1555.55  4591.2 1548.26  4628.3 1538.89  4633.5 1539.93
  4660.8 1532.98  4675.7 1534.28  4717.9 1523.97  4765.2  1520.6  4794.4 1513.82
  4807.5 1512.94  4866.4 1500.46  4886.8 1491.39  4891.9  1493.4  4897.2 1488.15
  4934.1 1475.28  4939.2 1476.47  4958.9 1473.31  4976.3    1465  4995.4 1464.24
  4995.7 1463.74  4999.4 1464.24  5018.9 1464.96  5067.6 1471.72  5130.6  1483.4
  5161.8 1496.32  5210.5 1509.59  5290.6 1520.86  5321.6  1521.4  5358.6 1529.53
#Mann= 5 ,-1 , 0
  4471.2     .07       0  4995.4     .05       0  4999.4     .07       0
  5018.9     .12       0  5067.6     .07       0
Bank Sta=4995.4,4999.4
XS Rating Curve= 0 ,0
Exp/Cntr=0.3,0.1

Type RM Length L Ch R = 1 ,20010   ,426,426,426
BEGIN DESCRIPTION:
BLACK CREEK 37.0
END DESCRIPTION:
XS GIS Cut Line= 3
      2085337.11     13847603.73       2085850.4      13847350.4
      2086141.63     13847185.25
#Sta/Elev= 30
  4427.6 1557.62  4506.3 1548.89  4613.5 1519.85  4635.5 1511.51    4641  1514.4
  4663.5 1511.96  4725.3 1500.33  4759.8 1484.19  4770.2 1484.51  4775.7  1491.3
  4798.2  1490.8  4815.1 1484.42  4865.5 1484.23  4882.4 1475.15    4935 1475.72
  4936.5 1474.42  4936.7 1473.92  4940.5 1474.42  4955.3  1477.5  5074.3  1475.4
  5161.7 1488.04  5183.4 1485.41  5199.3 1491.55    5205 1488.65  5220.9  1495.7
  5226.6 1492.38  5248.3 1497.92  5264.1 1506.17  5307.4 1511.22  5334.8 1519.12
#Mann= 5 ,-1 , 0
  4427.6     .07       0  4613.5     .12       0    4935     .07       0
  4936.5     .05       0  4940.5     .07       0
Bank Sta=4936.5,4940.5
XS Rating Curve= 0 ,0
Exp/Cntr=0.3,0.1

Type RM Length L Ch R = 1 ,19584   ,662,662,662
BEGIN DESCRIPTION:
BLACK CREEK 36.0
END DESCRIPTION:
XS GIS Cut Line= 3
      2085335.57     13847950.42        2085975.       13847725.
      2086419.88     13847365.78
#Sta/Elev= 30
    4322 1542.23  4355.9 1541.44  4417.8 1535.06  4443.5 1529.06  4474.4  1527.7
  4536.3 1519.51  4572.2 1510.67  4598.2 1502.47  4623.8 1499.08  4660.7 1489.76
  4742.3 1479.45  4787.9 1477.14  4829.8 1468.68  4891.7 1461.56    4947 1449.95
  4976.8 1449.08    4977 1448.58  4980.8 1449.08  5059.8 1451.44  5149.5 1458.12
  5242.3 1468.76  5263.1 1475.09    5327 1485.87  5370.2 1489.78    5391 1497.93
  5440.6 1509.82  5490.2 1518.69  5526.9 1521.06  5557.3 1520.15  5571.8 1519.81
#Mann= 6 ,-1 , 0
    4322     .12       0  4572.2     .07       0  4976.8     .05       0
  4980.8     .07       0  5059.8     .12       0  5557.3    .035       0
Bank Sta=4976.8,4980.8
XS Rating Curve= 0 ,0
Exp/Cntr=0.3,0.1

Type RM Length L Ch R = 1 ,18922   ,675,675,675
BEGIN DESCRIPTION:
BLACK CREEK 35.0
END DESCRIPTION:
XS GIS Cut Line= 3
      2085820.25     13848905.91        2086125.       13848325.
       2086407.8     13847740.19
#Sta/Elev= 30
    4344 1474.58    4382 1472.67  4570.7 1463.12  4710.7 1458.58  4837.4 1457.14
  4865.1 1452.13  4897.9 1450.83  4909.7 1446.35    4942 1441.32  4977.4 1431.05
  4991.8 1428.93  4995.2 1425.82  4995.4 1425.32  4999.2 1425.82  5044.4 1427.46
  5098.9 1443.67  5161.8 1447.61  5217.4 1456.35  5255.5 1459.05  5285.2 1468.31
  5313.3 1470.32    5353 1476.48  5377.2 1477.14    5382  1477.2  5465.9 1479.84
  5494.1 1487.28  5522.2 1499.58  5555.4  1504.2  5577.6 1510.71  5649.6 1517.95
#Mann= 8 ,-1 , 0
    4344    .035       0    4382     .07       0  4570.7     .12       0
  4995.2     .05       0  4999.2     .12       0  5161.8     .07       0
  5377.2     .12       0    5382     .07       0
Bank Sta=4995.2,4999.2
XS Rating Curve= 0 ,0
Exp/Cntr=0.3,0.1

Type RM Length L Ch R = 1 ,18247   ,462,462,462
BEGIN DESCRIPTION:
BLACK CREEK 39.0
END DESCRIPTION:
XS GIS Cut Line= 3
      2086333.04     13849283.72        2086675.       13848425.
      2086694.55     13847889.96
#Sta/Elev= 30
  4075.7 1486.53  4097.7 1484.41  4124.2  1481.1  4199.3 1475.76  4259.3 1468.44
  4375.7 1457.52  4583.3 1443.54  4631.9 1435.83  4722.4 1428.26  4823.4 1427.37
  4847.6 1424.56  4860.1 1420.08  4882.7 1416.58  4946.2 1416.09  4988.6 1412.94
  4988.8 1412.44  4992.6 1412.94  4997.3 1415.26  5034.1 1420.53  5090.1 1430.44
  5120.1 1441.46  5230.8 1455.93  5270.2 1461.57  5320.2 1474.44  5380.3  1479.6
  5420.3 1485.63  5440.3 1489.74  5470.3  1500.2  5500.3 1504.22  5535.4 1511.82
#Mann= 10 ,-1 , 0
  4075.7     .07       0  4097.7    .035       0  4124.2     .07       0
  4199.3    .035       0  4259.3     .07       0  4722.4     .12       0
  4988.6     .05       0  4992.6     .12       0  5034.1     .12       0
  5230.8     .07       0
Bank Sta=4988.6,4992.6
XS Rating Curve= 0 ,0
Exp/Cntr=0.3,0.1

Type RM Length L Ch R = 1 ,17785   ,974,974,974
BEGIN DESCRIPTION:
BLACK CREEK 34.0
END DESCRIPTION:
XS GIS Cut Line= 3
      2087055.88     13849372.47        2087075.       13848575.
      2087051.68     13847969.15
#Sta/Elev= 30
  4202.3 1461.07  4279.8 1453.88  4359.8 1449.83  4394.5 1446.57  4483.3 1442.35
  4549.9 1435.29  4609.9 1430.97    4680 1429.52  4788.2 1427.46    4848  1423.4
    4900 1413.27    4910 1413.67    4920 1411.21  4964.4 1406.11  4995.5 1403.44
  4995.7 1402.94  4999.5 1403.44  5090.1 1406.08  5170.1  1413.6  5260.2 1428.32
  5320.2  1435.8  5360.3 1443.64  5430.3 1446.81  5466.9 1453.69  5480.4  1455.8
  5520.4 1458.13  5530.4 1459.82  5550.4 1467.01  5601.6 1470.93  5606.3 1470.96
#Mann= 10 ,-1 , 0
  4202.3    .035       0  4394.5     .07       0  4483.3    .035       0
    4680     .07       0    4848     .12       0  4964.4     .07       0
  4995.5     .05       0  4999.5     .07       0  5466.9    .035       0
  5601.6     .07       0
Bank Sta=4995.5,4999.5
XS Rating Curve= 0 ,0
Exp/Cntr=0.3,0.1

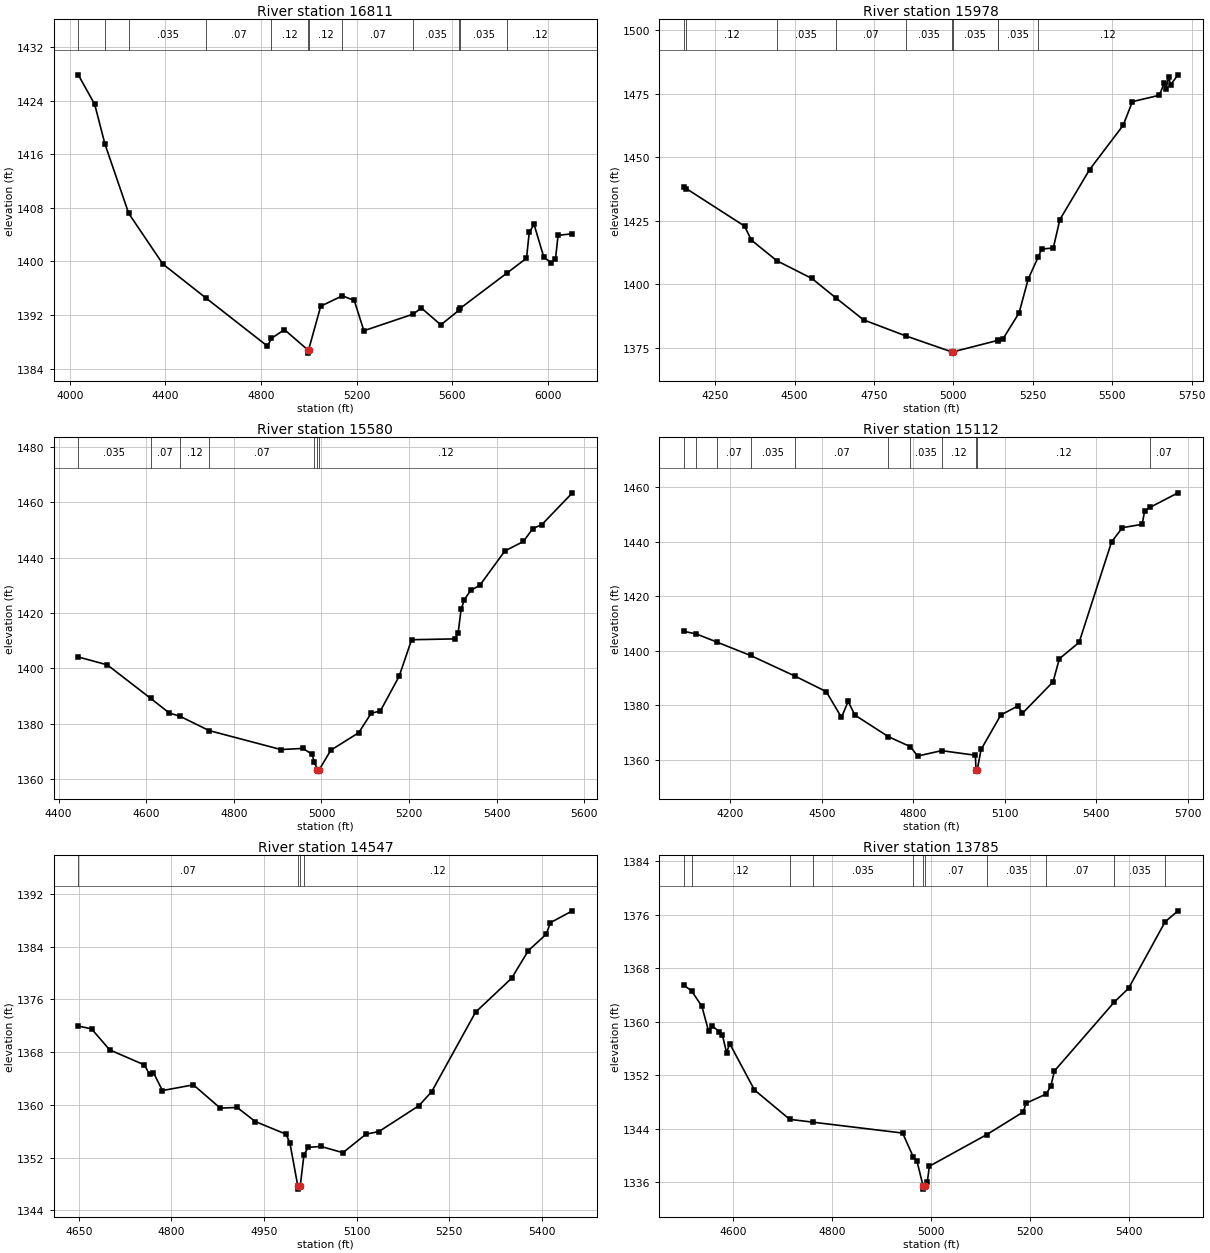
Type RM Length L Ch R = 1 ,16811   ,833,833,833
BEGIN DESCRIPTION:
BLACK CREEK 33.0
END DESCRIPTION:
XS GIS Cut Line= 3
      2087746.45     13849223.03        2087925.       13848275.
      2088015.48     13847175.22
#Sta/Elev= 30
  4035.3 1427.85    4104 1423.46    4147 1417.52  4246.5 1407.16  4389.5  1399.6
  4571.8 1394.47    4827 1387.35  4843.8  1388.5  4898.2 1389.81  4995.5  1386.8
  4995.7  1386.3  4999.5  1386.8  5050.2 1393.31  5140.9 1394.86  5190.6 1394.16
  5230.8 1389.64  5436.3 1392.12  5471.6 1393.03  5552.9 1390.52    5630 1392.74
  5633.3 1392.97  5830.2 1398.27  5911.4 1400.47  5923.1 1404.38  5943.2 1405.51
  5983.3 1400.69  6013.4 1399.79  6032.6 1400.31  6043.5 1403.88  6103.5 1404.13
#Mann= 12 ,-1 , 0
  4035.3     .12       0    4147     .07       0  4246.5    .035       0
  4571.8     .07       0  4843.8     .12       0  4995.5     .05       0
  4999.5     .12       0  5140.9     .07       0  5436.3    .035       0
    5630     .07       0  5633.3    .035       0  5830.2     .12       0
Bank Sta=4995.5,4999.5
XS Rating Curve= 0 ,0
Exp/Cntr=0.3,0.1

Type RM Length L Ch R = 1 ,15978   ,398,398,398
BEGIN DESCRIPTION:
BLACK CREEK 40.0
END DESCRIPTION:
XS GIS Cut Line= 3
      2087719.28     13849419.75        2088325.       13848825.
      2088885.17      13848393.5
#Sta/Elev= 30
  4151.1  1438.2  4159.2 1437.65  4342.3 1422.93  4363.6 1417.44    4444 1409.32
  4554.5 1402.34  4629.2 1394.77  4717.2 1386.06  4849.6 1379.79  4994.5  1373.5
  4994.7    1373  4998.5  1373.5  5138.8 1377.98  5139.6 1377.91  5156.7 1378.75
  5206.6 1388.79  5235.6 1402.18    5267 1410.79  5277.7 1413.93  5314.4 1414.32
  5335.2 1425.52  5428.6 1445.12  5534.5 1462.57  5563.5 1471.87  5648.7 1474.38
  5663.2 1479.05  5669.5 1476.93  5677.7 1481.47    5684 1478.51  5707.1 1482.41
#Mann= 10 ,-1 , 0
  4151.1     .07       0  4159.2     .12       0    4444    .035       0
  4629.2     .07       0  4849.6    .035       0  4994.5    .035       0
  4998.5    .035       0  5138.8     .12       0  5139.6    .035       0
    5267     .12       0
Bank Sta=4994.5,4998.5
XS Rating Curve= 0 ,0
Exp/Cntr=0.3,0.1

Type RM Length L Ch R = 1 ,15580   ,468,468,468
BEGIN DESCRIPTION:
BLACK CREEK 32.0
END DESCRIPTION:
XS GIS Cut Line= 2
      2088093.81      13849476.7      2088949.88     13848742.02
#Sta/Elev= 30
  4444.8  1404.1  4511.1 1401.25  4609.9 1389.16  4652.7 1383.84  4676.9 1382.68
  4743.3  1377.5  4907.6 1370.63  4957.8 1371.04  4978.6  1368.9  4983.3 1366.25
  4990.9 1363.33  4991.1 1362.83  4994.9 1363.33  5021.4  1370.4  5085.1 1376.72
  5113.6 1383.76  5134.5 1384.58  5177.3 1397.09  5205.8 1410.34  5304.6 1410.64
  5312.2 1412.94  5318.8 1421.31  5326.5 1424.88  5340.8 1428.19  5361.6 1430.02
  5418.7 1442.43  5461.1 1445.86  5482.3 1450.49  5503.2 1451.97  5572.9 1463.45
#Mann= 7 ,-1 , 0
  4444.8    .035       0  4609.9     .07       0  4676.9     .12       0
  4743.3     .07       0  4983.3     .12       0  4990.9     .05       0
  4994.9     .12       0
Bank Sta=4990.9,4994.9
XS Rating Curve= 0 ,0
Exp/Cntr=0.3,0.1

Type RM Length L Ch R = 1 ,15112   ,565,565,565
BEGIN DESCRIPTION:
BLACK CREEK 41.0
END DESCRIPTION:
XS GIS Cut Line= 3
      2088115.58     13849950.26        2088875.       13849375.
      2089272.26     13848838.59
#Sta/Elev= 30
  4047.3 1407.12  4088.7 1406.13  4157.2 1403.11  4266.1 1398.26  4410.3 1390.79
  4514.2 1385.03  4564.2 1375.59    4586 1381.45  4607.8 1376.47  4717.8 1368.54
  4790.1 1364.86  4813.8 1361.43  4892.5 1363.41  5003.1 1361.72  5005.3 1356.41
  5005.6 1355.91  5009.3 1356.41  5021.9 1363.84  5086.6 1376.47    5143 1379.81
  5157.6 1377.11  5257.8  1388.6  5278.6 1397.08  5343.3 1403.06  5449.7 1439.86
  5485.3 1445.08  5549.9  1446.3  5558.3  1451.2    5577 1452.58  5667.5 1457.84
#Mann= 11 ,-1 , 0
  4047.3     .07       0  4088.7     .12       0  4157.2     .07       0
  4266.1    .035       0  4410.3     .07       0  4717.8     .12       0
  4790.1    .035       0  4892.5     .12       0  5005.3     .05       0
  5009.3     .12       0    5577     .07       0
Bank Sta=5005.3,5009.3
XS Rating Curve= 0 ,0
Exp/Cntr=0.3,0.1

Type RM Length L Ch R = 1 ,14547   ,762,762,762
BEGIN DESCRIPTION:
BLACK CREEK 31.0
END DESCRIPTION:
XS GIS Cut Line= 2
      2088829.83     13850020.82       2089474.2     13849545.19
#Sta/Elev= 30
  4648.9 1371.96  4670.5 1371.52  4699.8 1368.34  4756.1 1366.05  4764.6  1364.6
  4770.8 1364.87  4785.4 1362.16  4835.5 1363.03    4879  1359.5  4906.5 1359.59
  4935.8 1357.46  4985.9 1355.53  4992.1 1354.13  5004.7  1347.7    5005  1347.2
  5008.7  1347.7  5014.7 1352.38  5021.4 1353.54  5042.2 1353.68  5077.9 1352.73
  5115.2 1355.54  5136.2 1355.94    5201 1359.86  5221.8    1362  5292.8 1374.05
  5351.3 1379.21  5378.4  1383.4  5407.7 1385.92  5413.9 1387.63  5449.8 1389.44
#Mann= 4 ,-1 , 0
  4648.9     .07       0  5004.7     .05       0  5008.7     .07       0
  5014.7     .12       0
Bank Sta=5004.7,5008.7
XS Rating Curve= 0 ,0
Exp/Cntr=0.3,0.1

Type RM Length L Ch R = 1 ,13785   ,423,423,423
BEGIN DESCRIPTION:
BLACK CREEK 30.0
END DESCRIPTION:
XS GIS Cut Line= 3
      2088974.96     13850124.97        2089375.       13850425.
      2089774.96     13850724.97
#Sta/Elev= 30
    4500 1365.49  4516.4 1364.55  4536.5  1362.3    4550 1358.62  4557.3 1359.35
  4571.9 1358.52  4578.2 1357.96  4586.5 1355.35  4592.8 1356.73  4642.8  1349.8
  4714.3 1345.39  4762.1 1344.96  4942.8 1343.34  4964.7  1339.7  4971.9 1339.09
  4984.1 1335.45  4984.4 1334.95    4989 1335.45  4992.8 1336.08  4996.9 1338.38
    5113 1343.11  5186.5 1346.48  5192.8 1347.82  5233.3 1349.18  5242.8 1350.39
    5250 1352.64  5371.4 1362.97    5400    1365  5474.1 1374.97    5500  1376.6
#Mann= 11 ,-1 , 0
    4500     .07       0  4516.4     .12       0  4714.3     .07       0
  4762.1    .035       0  4964.7     .07       0  4984.1     .05       0
    4989     .07       0    5113    .035       0  5233.3     .07       0
  5371.4    .035       0  5474.1     .07       0
Bank Sta=4984.1,4989
XS Rating Curve= 0 ,0
Exp/Cntr=0.3,0.1

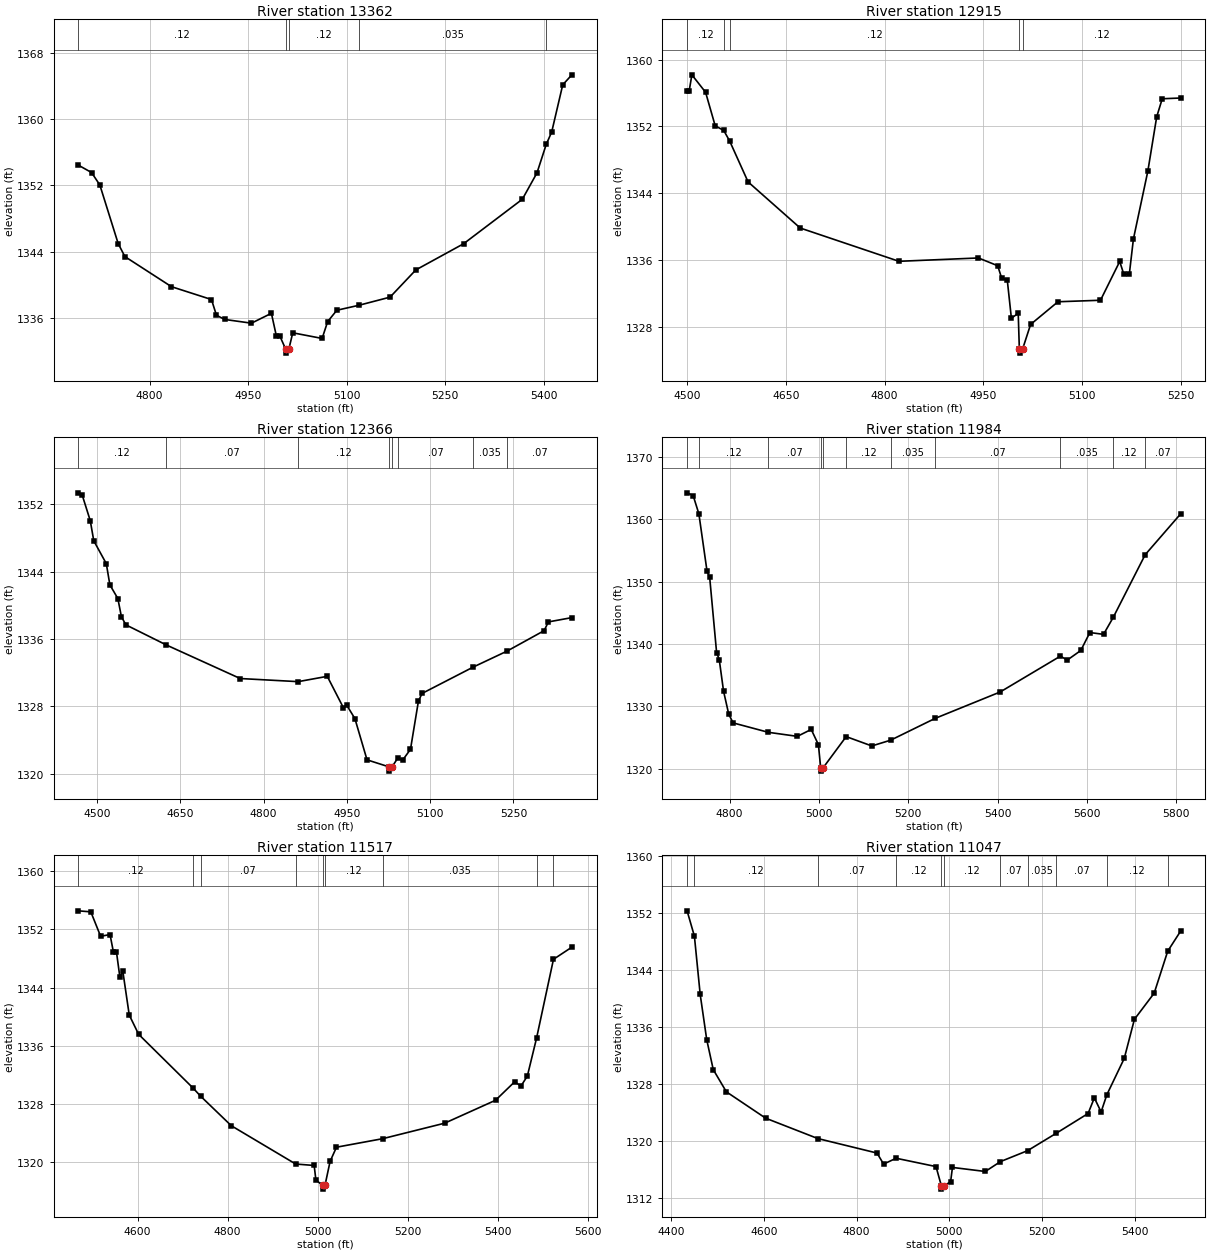
Type RM Length L Ch R = 1 ,13362   ,447,447,447
BEGIN DESCRIPTION:
BLACK CREEK 29.0
END DESCRIPTION:
XS GIS Cut Line= 3
      2088875.01       13850725.        2089175.       13850775.
      2089574.96     13850974.98
#Sta/Elev= 30
  4691.3 1354.43  4711.6 1353.53  4724.2 1352.03  4752.1 1344.97  4762.3  1343.4
  4833.2 1339.77  4894.1 1338.22  4901.7 1336.32  4914.3 1335.82  4954.9 1335.37
  4985.3 1336.56  4992.9 1333.81  4998.2 1333.81  5006.9 1332.26  5007.3 1331.76
  5011.9 1332.26  5017.8 1334.21  5062.5 1333.53  5070.9 1335.56  5084.9 1336.93
  5118.6 1337.53  5165.9 1338.51  5205.1 1341.79  5277.7 1344.94  5367.2 1350.31
  5389.5 1353.49  5403.6 1356.93  5411.9 1358.42  5428.7 1364.11  5442.6 1365.31
#Mann= 5 ,-1 , 0
  4691.3     .12       0  5006.9     .05       0  5011.9     .12       0
  5118.6    .035       0  5403.6     .12       0
Bank Sta=5006.9,5011.9
XS Rating Curve= 0 ,0
Exp/Cntr=0.3,0.1

Type RM Length L Ch R = 1 ,12915   ,549,549,549
BEGIN DESCRIPTION:
BLACK CREEK 28.0
END DESCRIPTION:
XS GIS Cut Line= 3
      2088825.01     13850775.01        2089125.       13851175.
      2089325.01     13851325.01
#Sta/Elev= 30
    4500 1356.22  4503.1 1356.22  4507.3 1358.18  4528.1 1356.09  4542.7 1352.07
  4555.7 1351.51  4564.7 1350.24  4592.7 1345.34  4671.9 1339.81  4821.9 1335.82
  4942.7 1336.22  4971.9 1335.29  4978.1 1333.76  4986.4 1333.62  4992.7    1329
  5003.1 1329.58  5004.8 1325.31  5005.1 1324.81  5009.8 1325.31  5021.9 1328.25
  5063.5 1330.97  5128.1 1331.15  5157.3  1335.8  5163.5 1334.27  5171.9 1334.29
  5178.1 1338.49    5200 1346.62  5213.5 1353.15  5221.9 1355.31    5250  1355.4
#Mann= 5 ,-1 , 0
    4500     .12       0  4555.7     .07       0  4564.7     .12       0
  5004.8     .05       0  5009.8     .12       0
Bank Sta=5004.8,5009.8
XS Rating Curve= 0 ,0
Exp/Cntr=0.3,0.1

Type RM Length L Ch R = 1 ,12366   ,382,382,382
BEGIN DESCRIPTION:
BLACK CREEK 27.0
END DESCRIPTION:
XS GIS Cut Line= 3
        2088525.       13851075.        2088856.     13851498.94
      2089124.98     13851724.98
#Sta/Elev= 30
  4466.1 1353.34  4473.3 1353.07  4487.8 1350.03  4494.1 1347.65  4516.7 1344.93
  4523.1 1342.42  4537.5 1340.79  4543.9 1338.63    4552 1337.67  4624.9 1335.28
  4757.9  1331.3  4862.3 1330.93  4914.7 1331.56  4943.7 1327.84    4950 1328.11
  4964.5 1326.54  4986.3 1321.65  5026.2 1320.81  5026.6 1320.31  5031.3 1320.81
  5041.8 1321.87  5050.3  1321.6  5064.6  1322.9  5078.9 1328.62  5085.4 1329.53
  5177.6 1332.66  5238.4 1334.55  5305.3 1336.98    5313 1338.02  5355.3 1338.53
#Mann= 8 ,-1 , 0
  4466.1     .12       0  4624.9     .07       0  4862.3     .12       0
  5026.2     .05       0  5031.3     .12       0  5041.8     .07       0
  5177.6    .035       0  5238.4     .07       0
Bank Sta=5026.2,5031.3
XS Rating Curve= 0 ,0
Exp/Cntr=0.3,0.1

Type RM Length L Ch R = 1 ,11984   ,467,467,467
BEGIN DESCRIPTION:
BLACK CREEK 26.0
END DESCRIPTION:
XS GIS Cut Line= 3
      2088324.97     13851574.98        2088575.       13851725.
      2089374.97       13851875.
#Sta/Elev= 30
  4704.6 1364.25  4718.2 1363.81    4731 1360.88  4749.3 1351.66  4755.2 1350.69
  4770.7 1338.62  4776.6  1337.5  4786.3 1332.41  4797.9 1328.72  4807.7 1327.33
  4886.5 1325.82  4951.5 1325.17  4982.6 1326.28  4998.7 1323.84  5003.8 1320.09
  5004.2 1319.59  5008.9 1320.09  5060.9 1325.13  5118.3 1323.63  5160.6 1324.56
  5260.3 1328.06  5405.7 1332.29  5540.8 1338.05  5555.8  1337.4  5586.3 1338.95
  5606.6 1341.83  5637.2 1341.54    5659 1344.27  5730.5 1354.32  5810.1 1360.89
#Mann= 11 ,-1 , 0
  4704.6     .07       0    4731     .12       0  4886.5     .07       0
  5003.8     .05       0  5008.9     .07       0  5060.9     .12       0
  5160.6    .035       0  5260.3     .07       0  5540.8    .035       0
    5659     .12       0  5730.5     .07       0
Bank Sta=5003.8,5008.9
XS Rating Curve= 0 ,0
Exp/Cntr=0.3,0.1

Type RM Length L Ch R = 1 ,11517   ,470,470,470
BEGIN DESCRIPTION:
BLACK CREEK 25.0
END DESCRIPTION:
XS GIS Cut Line= 3
      2088124.99     13851824.99        2088525.       13852175.
      2088924.99     13852574.99
#Sta/Elev= 30
  4467.9 1354.55  4495.9 1354.41  4517.7 1351.05  4538.6 1351.29  4546.2 1348.86
  4552.9 1348.89  4560.5 1345.43  4567.1 1346.22  4581.3 1340.23  4602.2 1337.58
  4722.8 1330.22  4739.8 1329.09  4808.2 1325.02  4951.2 1319.76  4992.3 1319.56
  4996.1 1317.59  5010.9 1316.81  5011.3 1316.31  5016.3 1316.81  5027.7 1320.12
  5041.9 1322.07  5144.5 1323.24  5282.3 1325.37  5395.4 1328.52  5437.8 1331.05
    5452 1330.48  5466.1 1331.84  5486.5 1337.03  5524.2 1347.89  5565.1 1349.56
#Mann= 9 ,-1 , 0
  4467.9     .12       0  4722.8    .035       0  4739.8     .07       0
  4951.2     .12       0  5010.9     .05       0  5016.3     .12       0
  5144.5    .035       0  5486.5     .07       0  5524.2    .035       0
Bank Sta=5010.9,5016.3
XS Rating Curve= 0 ,0
Exp/Cntr=0.3,0.1

Type RM Length L Ch R = 1 ,11047   ,439,439,439
BEGIN DESCRIPTION:
BLACK CREEK 24.0
END DESCRIPTION:
XS GIS Cut Line= 3
      2087925.02     13852175.02        2088325.       13852575.
      2088725.03     13852875.03
#Sta/Elev= 30
  4434.1 1352.32  4449.9 1348.76  4462.4 1340.57  4476.5 1334.21  4490.6    1330
  4518.9 1326.88  4603.8 1323.17  4716.3 1320.31  4844.2 1318.27  4858.3 1316.72
  4885.4 1317.54  4971.5 1316.37  4982.9  1313.7  4983.3  1313.2  4988.3  1313.7
  5002.9  1314.2    5007 1316.25  5077.9 1315.68  5110.6 1317.07  5169.3 1318.61
    5231 1321.05  5299.8 1323.83  5313.3 1326.03  5327.9 1324.05  5340.3 1326.47
  5377.9 1331.58  5399.8 1337.07  5442.5 1340.75  5471.7 1346.65  5499.8 1349.49
#Mann= 11 ,-1 , 0
  4434.1     .07       0  4449.9     .12       0  4716.3     .07       0
  4885.4     .12       0  4982.9     .05       0  4988.3     .12       0
  5110.6     .07       0  5169.3    .035       0    5231     .07       0
  5340.3     .12       0  5471.7     .07       0
Bank Sta=4982.9,4988.3
XS Rating Curve= 0 ,0
Exp/Cntr=0.3,0.1

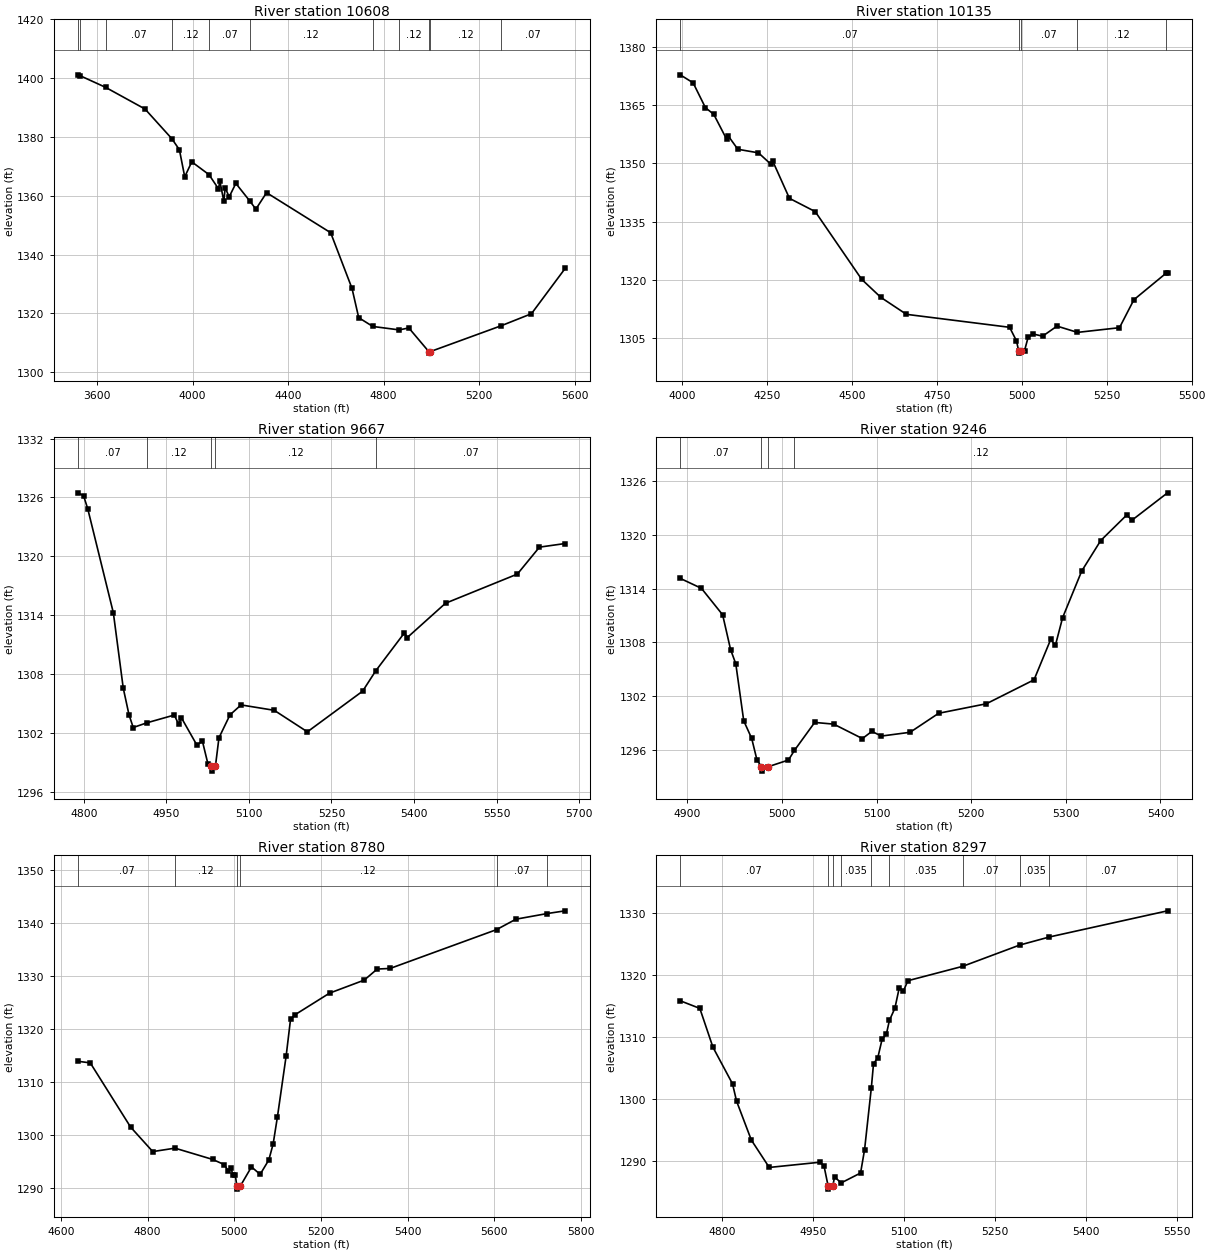
Type RM Length L Ch R = 1 ,10608   ,473,473,473
BEGIN DESCRIPTION:
BLACK CREEK 23.0
END DESCRIPTION:
XS GIS Cut Line= 3
      2087366.42     13851554.51        2088025.       13852875.
        2088425.       13853275.
#Sta/Elev= 30
  3519.3 1401.17  3528.8 1400.86  3635.1 1396.92  3800.5 1389.54  3912.8 1379.45
  3944.5 1375.68  3966.8 1366.48  3996.3 1371.58  4068.5 1367.22  4108.2  1362.4
  4113.8  1365.1  4130.6 1358.17  4136.2 1362.78    4153 1359.66  4180.9 1364.25
  4239.7 1358.22  4264.8 1355.49  4309.6 1361.09  4578.1 1347.47  4667.6 1328.52
  4695.6 1318.58  4754.6 1315.59  4865.2 1314.42  4905.5 1315.09  4989.4 1307.02
  4989.8 1306.52  4994.9 1307.02  5292.4 1315.83  5419.2 1319.92  5560.6 1335.35
#Mann= 11 ,-1 , 0
  3519.3     .07       0  3528.8     .12       0  3635.1     .07       0
  3912.8     .12       0  4068.5     .07       0  4239.7     .12       0
  4754.6    .035       0  4865.2     .12       0  4989.4     .05       0
  4994.9     .12       0  5292.4     .07       0
Bank Sta=4989.4,4994.9
XS Rating Curve= 0 ,0
Exp/Cntr=0.3,0.1

Type RM Length L Ch R = 1 ,10135   ,468,468,468
BEGIN DESCRIPTION:
BLACK CREEK 22.0
END DESCRIPTION:
XS GIS Cut Line= 3
      2086727.55     13853068.39        2087725.       13853225.
      2088024.98     13853524.98
#Sta/Elev= 30
  3995.1 1372.82    4033 1370.76  4069.2 1364.36  4093.7 1362.65  4131.8  1356.2
  4136.9 1357.02  4164.6 1353.65  4225.3 1352.73  4262.1 1349.78  4267.1 1350.63
  4316.4 1341.02  4392.3  1337.6    4529 1320.16  4585.2 1315.53  4660.6 1311.15
  4964.3 1307.81  4984.5 1304.31  4991.1 1301.66  4991.6 1301.16  4998.2 1301.66
  5008.3 1301.83  5018.9 1305.28  5033.1  1306.1  5061.3 1305.52  5103.8 1308.12
  5163.9  1306.5  5287.6 1307.71    5330 1314.91  5425.7 1321.81    5429 1321.81
#Mann= 5 ,-1 , 0
  3995.1     .07       0  4991.1     .05       0  4998.2     .07       0
  5163.9     .12       0  5425.7     .07       0
Bank Sta=4991.1,4998.2
XS Rating Curve= 0 ,0
Exp/Cntr=0.3,0.1

Type RM Length L Ch R = 1 ,9667    ,421,421,421
BEGIN DESCRIPTION:
BLACK CREEK 21.0
END DESCRIPTION:
XS GIS Cut Line= 3
      2087325.02       13853675.        2087525.       13853625.
      2088201.59     13853686.29
#Sta/Elev= 30
  4789.3 1326.47  4799.6 1326.17  4807.3 1324.82  4853.7 1314.26  4871.7 1306.59
  4882.1 1303.89  4889.8 1302.58  4915.3 1303.07  4964.5 1303.85  4972.2 1302.92
  4977.4 1303.57  5005.5 1300.79  5015.5  1301.2  5025.6 1298.87    5032 1298.64
  5032.5 1298.14  5039.2 1298.64  5045.6 1301.53  5065.7 1303.87  5085.8 1304.88
  5146.1 1304.33  5206.3 1302.14  5306.7 1306.28  5330.4 1308.34  5382.7 1312.22
  5387.7 1311.73  5457.3 1315.23  5587.9  1318.2    5628 1320.94  5674.8 1321.31
#Mann= 5 ,-1 , 0
  4789.3     .07       0  4915.3     .12       0    5032     .05       0
  5039.2     .12       0  5330.4     .07       0
Bank Sta=5032,5039.2
XS Rating Curve= 0 ,0
Exp/Cntr=0.3,0.1

Type RM Length L Ch R = 1 ,9246    ,466,466,466
BEGIN DESCRIPTION:
BLACK CREEK 20.0
END DESCRIPTION:
XS GIS Cut Line= 3
      2087524.96     13854025.02        2087625.       13853975.
      2088025.04       13854025.
#Sta/Elev= 30
  4892.5 1315.14  4914.9 1314.03  4937.3 1311.08  4945.7  1307.2  4951.2 1305.62
  4959.6 1299.26    4968  1297.3  4973.6 1294.89  4978.3 1294.15  4978.8 1293.65
  4985.7 1294.15  5006.9 1294.89  5013.1 1295.95  5034.6 1299.08  5054.7 1298.89
    5085 1297.28    5095 1298.08  5105.1 1297.56  5135.4 1297.98  5165.6  1300.1
    5216 1301.16  5266.4 1303.83    5284 1308.33    5289 1307.68  5296.6 1310.76
  5316.8 1315.96  5336.9 1319.36  5364.6 1322.23  5369.7 1321.61  5407.5 1324.68
#Mann= 4 ,-1 , 0
  4892.5     .07       0  4978.3     .05       0  4985.7     .07       0
  5013.1     .12       0
Bank Sta=4978.3,4985.7
XS Rating Curve= 0 ,0
Exp/Cntr=0.3,0.1

Type RM Length L Ch R = 1 ,8780    ,483,483,483
BEGIN DESCRIPTION:
BLACK CREEK 19.0
END DESCRIPTION:
XS GIS Cut Line= 3
      2087525.03     13854175.02        2087825.       13854375.
      2088588.63     13854394.77
#Sta/Elev= 30
    4639 1313.88  4667.5 1313.58  4760.6 1301.45  4811.7 1296.82    4863 1297.47
  4949.9 1295.34    4977 1294.35    4986  1293.1    4992 1293.77  4996.5 1292.48
    5002 1292.48  5005.8 1290.23  5006.3 1289.73  5013.2 1290.23  5039.5 1293.93
  5059.5 1292.52  5079.5 1295.24  5089.5 1298.26  5099.5 1303.44  5119.6 1314.95
  5129.6 1321.79  5139.6 1322.65  5219.6 1326.75  5299.6 1329.21  5329.6  1331.3
  5359.6 1331.42    5605 1338.75  5649.7 1340.72  5722.1 1341.79  5763.4  1342.3
#Mann= 6 ,-1 , 0
    4639     .07       0    4863     .12       0  5005.8     .05       0
  5013.2     .12       0    5605     .07       0  5722.1     .12       0
Bank Sta=5005.8,5013.2
XS Rating Curve= 0 ,0
Exp/Cntr=0.3,0.1

Type RM Length L Ch R = 1 ,8297    ,468,468,468
BEGIN DESCRIPTION:
BLACK CREEK 18.0
END DESCRIPTION:
XS GIS Cut Line= 3
      2087374.99     13854324.98        2087475.       13854575.
      2087845.24     13854960.39
#Sta/Elev= 30
  4730.8 1315.87  4763.1 1314.64  4784.7 1308.38    4817 1302.47  4823.7 1299.67
    4848  1293.4  4877.6 1288.97    4961 1289.81  4967.8 1289.26  4974.7 1285.97
  4975.2 1285.47  4982.4 1285.97  4985.3 1287.43  4996.3 1286.48  5028.2 1288.07
  5034.8 1291.83  5045.9 1301.76  5049.6 1305.74  5056.5 1306.63  5063.8 1309.69
  5070.7 1310.46  5075.8 1312.71  5084.8 1314.67  5092.1    1318    5099 1317.46
  5106.2 1319.11  5196.6 1321.43  5290.5 1324.86  5339.7 1326.17  5534.5 1330.39
#Mann= 9 ,-1 , 0
  4730.8     .07       0  4974.7    .035       0  4982.4     .07       0
  4996.3    .035       0  5045.9     .07       0  5075.8    .035       0
  5196.6     .07       0  5290.5    .035       0  5339.7     .07       0
Bank Sta=4974.7,4982.4
XS Rating Curve= 0 ,0
Exp/Cntr=0.3,0.1

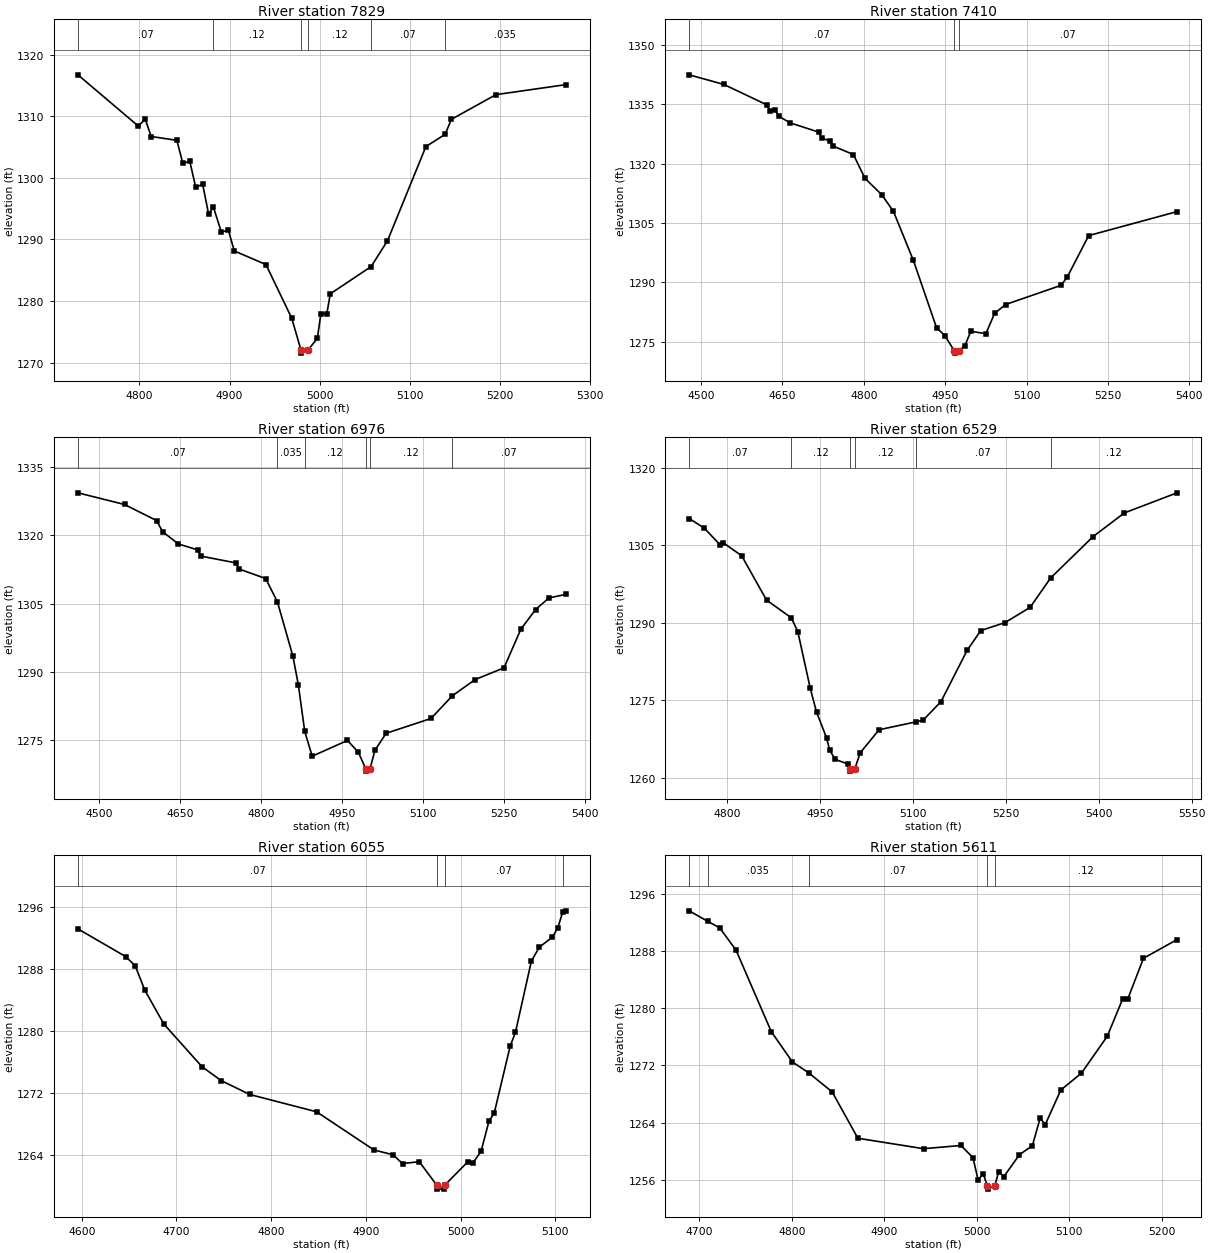
Type RM Length L Ch R = 1 ,7829    ,419,419,419
BEGIN DESCRIPTION:
BLACK CREEK 17.0
END DESCRIPTION:
XS GIS Cut Line= 3
      2086897.64     13854467.66        2087075.       13854675.
      2087255.27     13854873.91
#Sta/Elev= 30
  4731.8 1316.75  4798.8 1308.42  4806.5 1309.55  4813.1 1306.73  4841.6 1306.11
  4848.2 1302.35  4855.9 1302.72  4862.5 1298.48  4870.2 1298.96  4876.8 1294.13
  4882.1 1295.26    4891 1291.19  4898.7 1291.53  4905.3 1288.14  4940.4 1285.93
    4969 1277.23  4979.3 1272.04  4979.8 1271.54  4987.1 1272.04  4997.5 1273.95
  5001.4 1277.97    5008 1277.97  5011.8 1281.17  5057.2 1285.61  5075.3  1289.8
  5117.9 1305.09  5139.2 1307.08  5146.2 1309.52  5195.6 1313.53  5273.1 1315.15
#Mann= 6 ,-1 , 0
  4731.8     .07       0  4882.1     .12       0  4979.3     .05       0
  4987.1     .12       0  5057.2     .07       0  5139.2    .035       0
Bank Sta=4979.3,4987.1
XS Rating Curve= 0 ,0
Exp/Cntr=0.3,0.1

Type RM Length L Ch R = 1 ,7410    ,434,434,434
BEGIN DESCRIPTION:
BLACK CREEK 16.0
END DESCRIPTION:
XS GIS Cut Line= 3
      2086328.24      13854655.2        2086775.       13854925.
      2087144.17     13855002.41
#Sta/Elev= 30
  4478.1 1342.39    4542 1339.96  4621.6 1334.79  4627.4 1333.21  4637.1 1333.51
  4642.9 1331.95  4664.3 1330.26  4716.7 1327.94  4722.5 1326.42    4738 1325.68
  4743.8 1324.39  4780.7 1322.28  4802.1 1316.27  4833.1 1312.11  4854.5 1307.94
  4891.3 1295.55    4934 1278.56  4949.5 1276.56    4967 1272.66  4967.5 1272.16
  4974.8 1272.66  4986.4 1274.08  4997.1 1277.66    5025 1277.08  5040.9 1282.19
  5061.3 1284.43  5163.5 1289.27  5174.7 1291.31  5214.4 1301.82  5377.2 1307.87
#Mann= 3 ,-1 , 0
  4478.1     .07       0    4967     .05       0  4974.8     .07       0
Bank Sta=4967,4974.8
XS Rating Curve= 0 ,0
Exp/Cntr=0.3,0.1

Type RM Length L Ch R = 1 ,6976    ,447,447,447
BEGIN DESCRIPTION:
BLACK CREEK 15.0
END DESCRIPTION:
XS GIS Cut Line= 3
       2086140.7     13855401.72        2086675.       13855325.
      2087025.02       13855225.
#Sta/Elev= 30
  4460.3 1329.28  4546.6 1326.72  4606.1 1323.19  4617.2 1320.74  4646.5 1318.06
  4682.7 1316.74  4687.7 1315.41  4753.2  1313.9  4758.2 1312.59  4808.1 1310.48
    4830 1305.33  4858.6 1293.43  4868.7 1287.13  4880.5 1276.94  4894.3 1271.51
  4959.7 1274.96  4979.9 1272.35  4993.6 1268.73  4994.1 1268.23  5001.5 1268.73
  5010.5 1272.79  5031.3 1276.53  5114.5 1279.78  5153.8 1284.74  5196.4 1288.33
  5249.7 1290.89  5280.9 1299.37  5308.2 1303.68  5332.9 1306.22  5364.1    1307
#Mann= 6 ,-1 , 0
  4460.3     .07       0    4830    .035       0  4880.5     .12       0
  4993.6     .05       0  5001.5     .12       0  5153.8     .07       0
Bank Sta=4993.6,5001.5
XS Rating Curve= 0 ,0
Exp/Cntr=0.3,0.1

Type RM Length L Ch R = 1 ,6529    ,474,474,474
BEGIN DESCRIPTION:
BLACK CREEK 14.0
END DESCRIPTION:
XS GIS Cut Line= 3
       2086560.9     13855755.88        2086825.       13855725.
      2087338.66     13855634.35
#Sta/Elev= 30
  4738.9 1310.17  4763.2 1308.31  4788.9 1305.05    4794 1305.46  4823.6 1302.96
  4863.8 1294.37  4903.7 1290.95  4914.2 1288.29  4934.3  1277.3  4944.4 1272.73
  4960.6 1267.72  4965.7 1265.32  4974.6 1263.54  4994.7 1262.67  4998.2 1261.77
  4998.7 1261.27  5006.4 1261.77    5015 1264.82  5045.4 1269.28  5104.8  1270.8
  5116.5 1271.13  5145.3 1274.72  5187.6 1284.65  5209.6 1288.48  5248.5 1290.01
  5289.1 1292.95  5322.4 1298.66  5390.7 1306.65  5441.4 1311.25  5526.4 1315.14
#Mann= 6 ,-1 , 0
  4738.9     .07       0  4903.7     .12       0  4998.2     .05       0
  5006.4     .12       0  5104.8     .07       0  5322.4     .12       0
Bank Sta=4998.2,5006.4
XS Rating Curve= 0 ,0
Exp/Cntr=0.3,0.1

Type RM Length L Ch R = 1 ,6055    ,444,444,444
BEGIN DESCRIPTION:
BLACK CREEK 13.0
END DESCRIPTION:
XS GIS Cut Line= 3
      2086625.01       13856075.        2087025.       13856125.
      2087124.99       13856175.
#Sta/Elev= 30
    4596 1293.18  4646.4 1289.61  4656.5 1288.42  4666.5  1285.3  4686.7 1280.91
    4727 1275.41  4747.2 1273.62  4777.4 1271.83  4847.9  1269.6  4908.4 1264.68
  4928.6 1264.06  4938.6 1262.92  4956.3 1263.17  4974.8 1260.13  4975.3 1259.63
  4982.6 1259.63  4983.1 1260.13  5007.5 1263.15  5013.1 1263.05  5021.5  1264.5
  5029.9 1268.41  5035.4 1269.43  5052.2 1278.05  5057.8 1279.85  5074.6 1289.02
    5083 1290.83  5096.9 1292.12  5102.5 1293.33  5107.7 1295.35  5110.9 1295.51
#Mann= 4 ,-1 , 0
    4596     .07       0  4974.8     .05       0  4983.1     .07       0
  5107.7     .12       0
Bank Sta=4974.8,4983.1
XS Rating Curve= 0 ,0
Exp/Cntr=0.3,0.1

Type RM Length L Ch R = 1 ,5611    ,470,470,470
BEGIN DESCRIPTION:
BLACK CREEK 12.0
END DESCRIPTION:
XS GIS Cut Line= 3
      2086574.95     13856474.99        2086875.       13856525.
      2087075.01       13856425.
#Sta/Elev= 30
  4688.9 1293.58  4708.7 1292.13  4721.9  1291.2  4739.6 1288.08  4777.7  1276.7
  4800.5 1272.47  4818.1 1270.95  4843.6 1268.27  4871.4  1261.8  4942.4 1260.34
  4982.9 1260.79  4995.9 1259.09  5001.5 1255.97  5007.1 1256.86  5011.2 1255.19
  5011.7 1254.69  5019.6 1255.19  5023.8 1257.15  5029.4 1256.45  5046.2  1259.5
  5060.2 1260.76  5068.6 1264.61  5074.1  1263.7  5090.9 1268.53  5113.3  1270.9
  5141.2 1276.05    5158 1281.29  5163.6 1281.32  5180.4 1286.95  5216.7 1289.56
#Mann= 5 ,-1 , 0
  4688.9     .07       0  4708.7    .035       0  4818.1     .07       0
  5011.2     .05       0  5019.6     .12       0
Bank Sta=5011.2,5019.6
XS Rating Curve= 0 ,0
Exp/Cntr=0.3,0.1