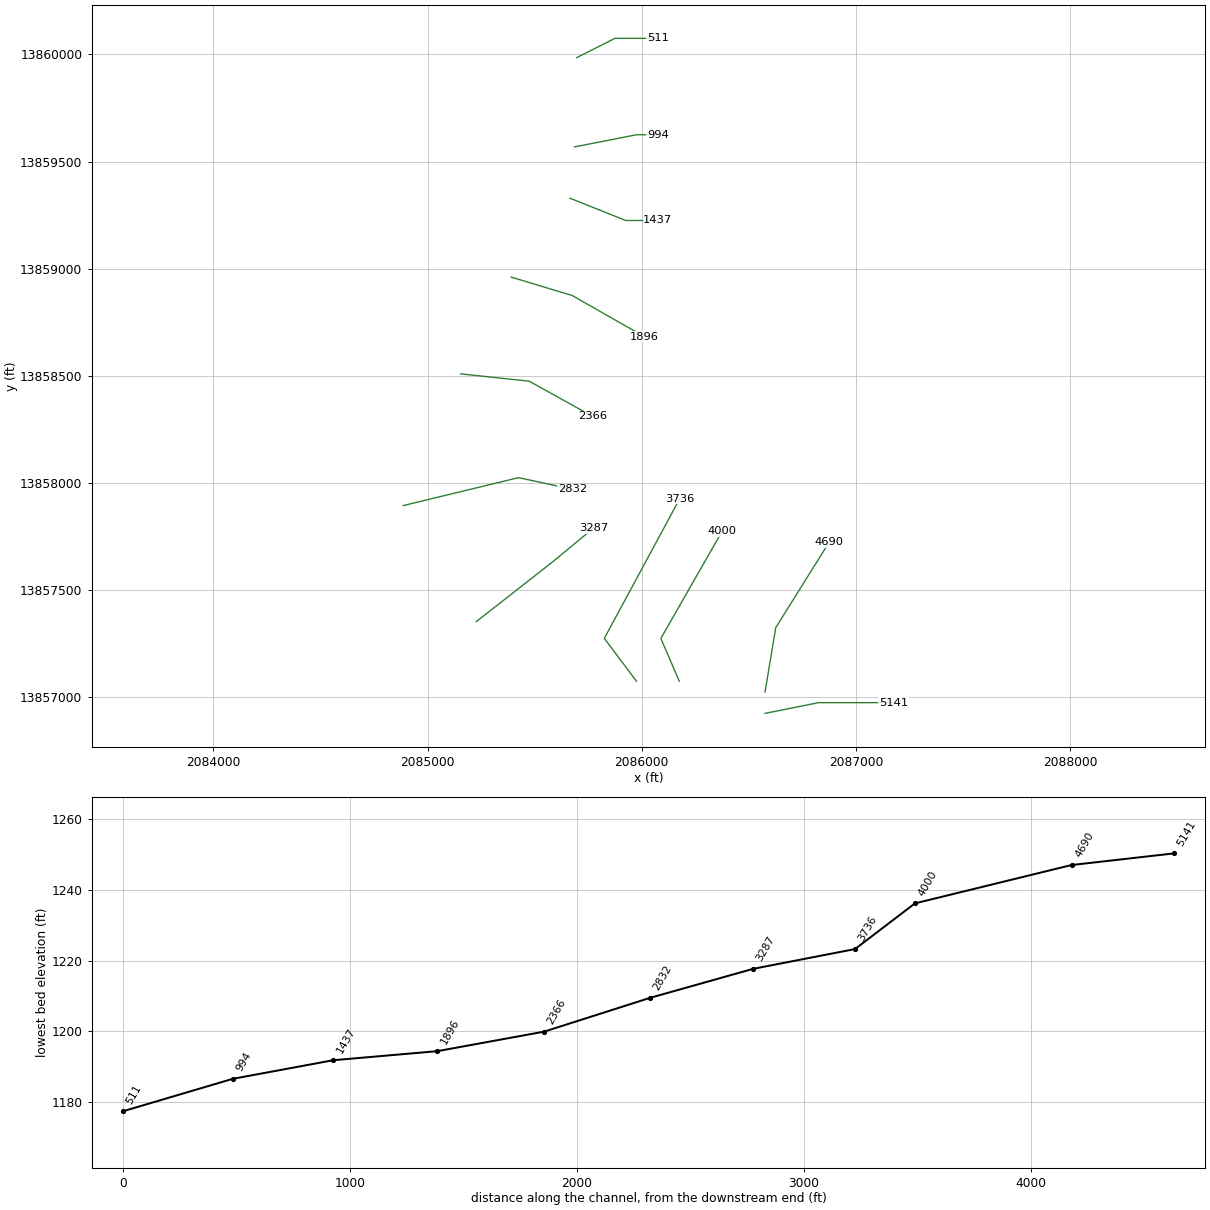
HEC-RAS study BLACK CREEK.prj: BLACK CREEK Base Level Engineering

--- BLACK CREEK.g01 (geometry) --- (continued)

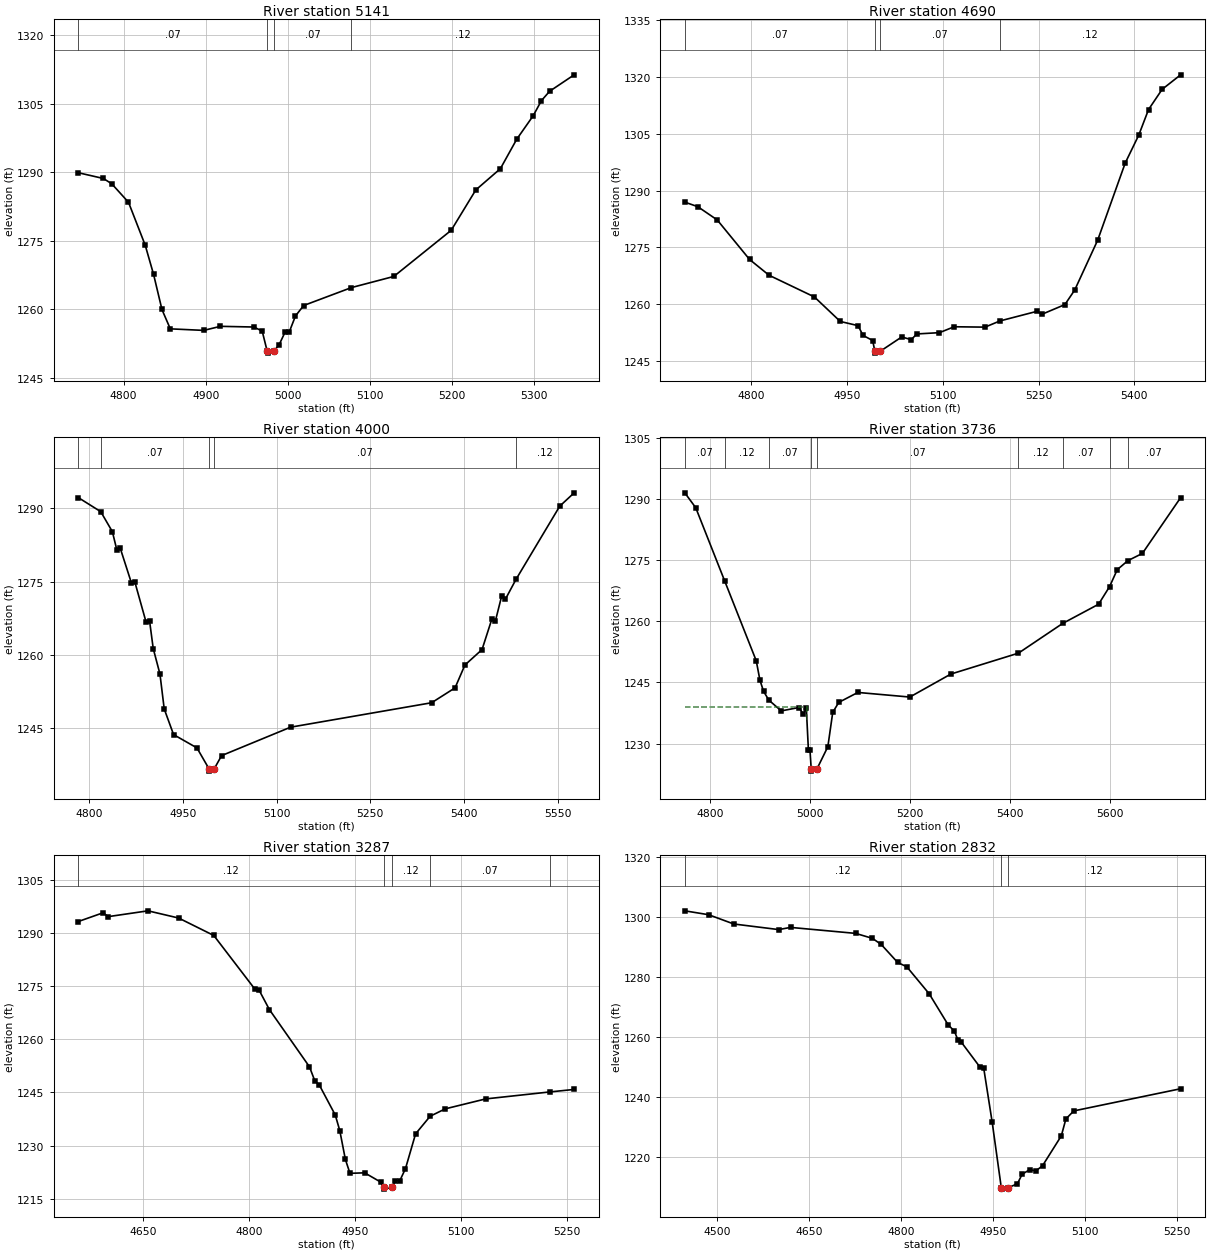
Type RM Length L Ch R = 1 ,5141    ,451,451,451
BEGIN DESCRIPTION:
BLACK CREEK 11.0
END DESCRIPTION:
XS GIS Cut Line= 3
      2086575.02       13856925.        2086825.       13856975.
      2087174.97       13856975.
#Sta/Elev= 30
  4744.7 1289.87  4775.3 1288.61  4785.5 1287.44  4805.9  1283.4  4826.3 1273.99
  4836.5  1267.6  4846.7 1259.91  4856.9 1255.67  4897.7 1255.33    4918 1256.22
  4958.8 1256.07    4969 1255.18    4975 1250.85  4975.5 1250.35  4983.4 1250.85
  4989.4 1252.09  4997.1 1255.02  5002.1 1255.02  5009.6 1258.49  5019.6 1260.78
  5077.9 1264.71  5129.6 1267.15  5199.6 1277.26  5229.6  1286.1  5259.6 1290.76
  5279.6 1297.23  5299.6 1302.35  5309.6 1305.65  5319.6 1307.71  5349.6 1311.32
#Mann= 4 ,-1 , 0
  4744.7     .07       0    4975     .05       0  4983.4     .07       0
  5077.9     .12       0
Bank Sta=4975,4983.4
XS Rating Curve= 0 ,0
Exp/Cntr=0.3,0.1

Type RM Length L Ch R = 1 ,4690    ,690,690,690
BEGIN DESCRIPTION:
BLACK CREEK 10.0
END DESCRIPTION:
XS GIS Cut Line= 3
        2086575.     13857024.98        2086625.       13857325.
      2086875.02     13857725.04
#Sta/Elev= 30
  4696.4 1286.97  4716.7 1285.77  4747.1 1282.27  4797.8 1271.81  4828.2 1267.65
  4899.2 1261.91  4939.7 1255.43  4967.6 1254.32  4975.2 1251.76  4990.4 1250.39
  4993.8 1247.56  4994.3 1247.06  5002.3 1247.56  5035.9 1251.34  5050.7 1250.62
  5059.5 1252.13  5094.9 1252.47  5117.9 1254.03  5166.2 1253.93  5189.4 1255.56
  5248.2 1258.14  5254.7 1257.29  5291.2 1259.89  5306.6 1263.75  5342.5 1276.92
  5385.6 1297.31  5406.8 1304.69  5422.1 1311.45  5443.4 1316.79  5472.3 1320.62
#Mann= 4 ,-1 , 0
  4696.4     .07       0  4993.8     .05       0  5002.3     .07       0
  5189.4     .12       0
Bank Sta=4993.8,5002.3
XS Rating Curve= 0 ,0
Exp/Cntr=0.3,0.1

Type RM Length L Ch R = 1 ,4000    ,264,264,264
BEGIN DESCRIPTION:
BLACK CREEK 9.0
END DESCRIPTION:
XS GIS Cut Line= 3
      2086175.01     13857074.97      2086088.82     13857274.55
        2086375.     13857775.01
#Sta/Elev= 30
  4782.6 1292.23  4818.5 1289.35  4837.1 1285.25  4844.1 1281.59  4849.6 1281.91
  4867.6 1274.75  4873.1 1274.94  4891.1 1266.71  4896.6 1267.04  4902.5 1261.32
  4913.3 1256.08  4920.1 1248.95  4935.1 1243.68  4972.5 1240.96  4991.7  1236.7
  4992.2  1236.2  5000.3  1236.7    5012 1239.38  5122.4  1245.2  5348.3 1250.21
  5385.8 1253.26  5401.6 1257.94    5429  1261.1  5444.8 1267.38  5450.5 1267.02
  5460.6 1272.15  5466.4 1271.42  5483.3 1275.46  5553.5 1290.49  5576.5 1293.21
#Mann= 5 ,-1 , 0
  4782.6     .12       0  4818.5     .07       0  4991.7     .05       0
  5000.3     .07       0  5483.3     .12       0
Bank Sta=4991.7,5000.3
XS Rating Curve= 0 ,0
Exp/Cntr=0.3,0.1

Type RM Length L Ch R = 1 ,3736    ,449,449,449
BEGIN DESCRIPTION:
BLACK CREEK 8.0
END DESCRIPTION:
XS GIS Cut Line= 3
        2085975.       13857075.        2085825.       13857275.
      2086176.73     13857926.41
#Sta/Elev= 30
    4750 1291.46  4771.9  1287.8  4829.9 1269.79  4892.7 1250.31    4900 1245.59
  4907.3 1242.83  4917.9 1240.66  4942.7 1238.03  4978.1 1238.86  4986.5 1237.22
  4992.7 1238.72  4996.9 1228.42    5000 1228.42  5002.5 1223.77    5003 1223.27
  5013.8 1223.77  5035.7 1229.25  5045.5 1237.68  5057.6 1240.12  5095.7 1242.55
  5199.4 1241.42  5281.3 1247.05  5416.4 1252.18  5504.7 1259.46  5576.4 1264.16
  5598.4 1268.48  5613.7 1272.63  5634.9 1274.84  5663.9 1276.61  5740.3 1290.28
#Mann= 9 ,-1 , 0
    4750     .07       0  4829.9     .12       0  4917.9     .07       0
  5002.5     .05       0  5013.8     .07       0  5416.4     .12       0
  5504.7     .07       0  5598.4     .12       0  5634.9     .07       0
#XS Ineff= 2 , 0
       0 4993.85 1238.92               0
Permanent Ineff=
       F       F
Bank Sta=5002.5,5013.8
XS Rating Curve= 0 ,0
Exp/Cntr=0.3,0.1

Type RM Length L Ch R = 1 ,3287    ,455,455,455
BEGIN DESCRIPTION:
BLACK CREEK 7.0
END DESCRIPTION:
XS GIS Cut Line= 3
      2085227.54     13857353.12        2085575.       13857625.
       2085775.8     13857790.33
#Sta/Elev= 30
  4558.8 1293.35  4593.7 1295.81  4601.2 1294.73  4657.3 1296.37  4700.7 1294.33
  4750.4  1289.4  4808.3 1274.28  4814.6 1273.89  4829.1 1268.42  4885.7 1252.27
  4893.3 1248.28  4899.6 1247.13  4922.2 1238.63  4928.6 1234.22  4936.5 1226.08
    4943 1222.14  4963.8 1222.28  4986.4 1219.67  4991.2 1218.17  4991.7 1217.67
  5002.5 1218.17  5007.2 1220.04  5013.6 1220.09  5021.5 1223.46  5035.8  1233.3
  5056.4 1238.28  5077.7 1240.37  5134.9 1243.18  5225.4 1245.15  5260.1 1245.86
#Mann= 5 ,-1 , 0
  4558.8     .12       0  4991.2     .05       0  5002.5     .12       0
  5056.4     .07       0  5225.4     .12       0
Bank Sta=4991.2,5002.5
XS Rating Curve= 0 ,0
Exp/Cntr=0.3,0.1

Type RM Length L Ch R = 1 ,2832    ,466,466,466
BEGIN DESCRIPTION:
BLACK CREEK 6.0
END DESCRIPTION:
XS GIS Cut Line= 3
      2084887.26     13857894.77        2085425.       13858025.
      2085675.49     13857971.15
#Sta/Elev= 30
  4446.8 1301.98  4485.6 1300.69  4526.8  1297.6  4600.2 1295.74  4619.4 1296.47
  4725.7 1294.48  4753.2 1292.82  4767.5 1290.79  4794.3 1284.82  4809.3 1283.36
  4845.8 1274.39  4876.6 1264.12  4886.9 1261.97    4893  1258.9  4898.1 1258.35
  4928.1 1250.18  4934.8  1249.7  4948.6 1231.75  4963.5 1209.94    4964 1209.44
  4974.9 1209.94  4989.8 1211.21  4997.5 1214.38  5010.3 1215.96  5019.7 1215.46
  5030.8 1217.21  5061.5 1227.15    5069 1232.79  5081.9 1235.45  5256.3 1242.82
#Mann= 3 ,-1 , 0
  4446.8     .12       0  4963.5     .05       0  4974.9     .12       0
Bank Sta=4963.5,4974.9
XS Rating Curve= 0 ,0
Exp/Cntr=0.3,0.1

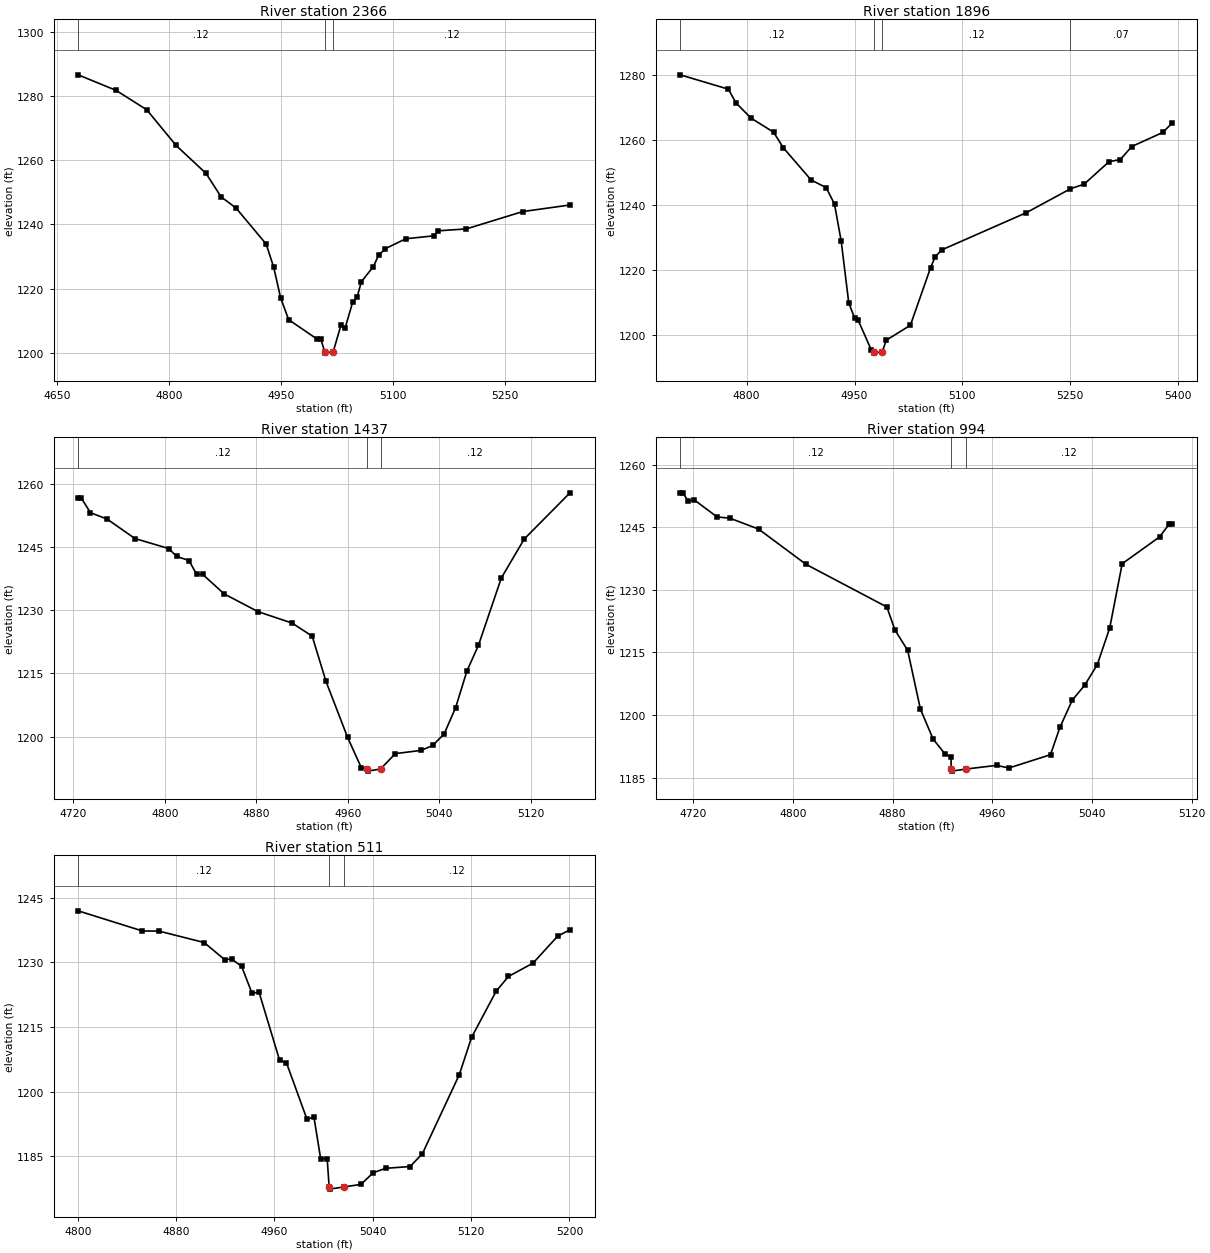
Type RM Length L Ch R = 1 ,2366    ,470,470,470
BEGIN DESCRIPTION:
BLACK CREEK 5.0
END DESCRIPTION:
XS GIS Cut Line= 3
      2085154.56     13858509.36        2085475.       13858475.
      2085769.21     13858311.43
#Sta/Elev= 30
  4678.1 1286.55  4728.8 1281.72    4770 1275.68  4809.3 1264.57  4849.5 1255.84
  4869.6 1248.57  4889.7 1245.05    4930 1233.85    4940 1226.71  4949.3 1217.18
  4960.1 1210.31  4997.9 1204.31  5003.2 1204.31  5008.3 1200.39  5008.8 1199.89
  5019.9 1200.39  5030.1 1208.51  5035.8 1207.72  5046.1 1215.92  5051.8 1217.32
  5057.6 1222.15  5073.6 1226.82  5080.5  1230.3  5089.6  1232.4    5117  1235.5
  5154.8 1236.42  5160.6 1237.98  5198.2 1238.57  5273.7 1243.97    5337 1246.02
#Mann= 3 ,-1 , 0
  4678.1     .12       0  5008.3     .05       0  5019.9     .12       0
Bank Sta=5008.3,5019.9
XS Rating Curve= 0 ,0
Exp/Cntr=0.3,0.1

Type RM Length L Ch R = 1 ,1896    ,459,459,459
BEGIN DESCRIPTION:
BLACK CREEK 4.0
END DESCRIPTION:
XS GIS Cut Line= 3
       2085390.7     13858960.75        2085675.       13858875.
      2086011.09     13858683.63
#Sta/Elev= 30
  4707.7 1279.99  4774.6 1275.58  4785.3 1271.34  4806.2 1266.66  4837.5 1262.35
    4851 1257.56  4889.8 1247.61  4910.6  1245.3  4922.2 1240.21  4931.5 1228.83
    4942 1209.85    4950 1205.25  4955.2 1204.44  4973.3 1195.36  4977.1 1194.87
  4977.6 1194.37  4988.7 1194.87  4994.2 1198.35  5027.7 1202.95  5055.8 1220.68
  5062.2 1224.05  5071.7 1226.17  5188.8 1237.57  5250.2 1244.93  5269.3 1246.37
  5303.8 1253.27  5319.5 1253.93  5335.4 1257.93  5378.6 1262.27  5391.4 1265.11
#Mann= 4 ,-1 , 0
  4707.7     .12       0  4977.1     .05       0  4988.7     .12       0
  5250.2     .07       0
Bank Sta=4977.1,4988.7
XS Rating Curve= 0 ,0
Exp/Cntr=0.3,0.1

Type RM Length L Ch R = 1 ,1437    ,443,443,443
BEGIN DESCRIPTION:
BLACK CREEK 3.0
END DESCRIPTION:
XS GIS Cut Line= 3
      2085665.01      13859328.8        2085925.       13859225.
      2086074.96       13859225.
#Sta/Elev= 30
  4724.2  1256.6  4726.9  1256.6    4735 1253.11  4749.5 1251.61  4773.8 1246.99
  4803.4 1244.61  4810.3 1242.75  4821.1 1241.76  4827.7 1238.53    4833 1238.49
  4851.9 1233.84  4881.5 1229.63  4911.2 1226.93  4928.8 1223.82  4940.8 1213.13
  4959.7 1199.82  4971.8 1192.57  4976.8  1192.3  4977.3  1191.8  4988.5  1192.3
  5001.5 1195.96  5024.1 1196.72  5034.1 1197.89  5044.1 1200.62  5054.1 1206.82
  5064.1  1215.6  5074.1 1221.64  5094.1 1237.62  5114.1 1246.86  5154.1 1257.83
#Mann= 3 ,-1 , 0
  4724.2     .12       0  4976.8     .05       0  4988.5     .12       0
Bank Sta=4976.8,4988.5
XS Rating Curve= 0 ,0
Exp/Cntr=0.3,0.1

Type RM Length L Ch R = 1 ,994     ,483,483,483
BEGIN DESCRIPTION:
BLACK CREEK 2.0
END DESCRIPTION:
XS GIS Cut Line= 3
      2085685.91     13859568.39        2085975.       13859625.
      2086075.02       13859625.
#Sta/Elev= 30
  4709.6 1253.28  4711.7 1253.28  4715.9 1251.34    4721 1251.55  4739.2  1247.5
  4749.4  1247.2  4772.5 1244.58  4810.6 1236.12  4875.4  1225.9  4881.9 1220.37
  4892.1  1215.5  4902.3 1201.42  4912.5 1194.23  4921.8 1190.75  4926.9  1189.9
    4927 1187.03  4927.5 1186.53  4938.8 1187.03  4963.4 1187.91  4973.3 1187.28
  5006.7 1190.47  5014.2    1197  5024.2 1203.57  5034.2 1207.17  5044.2 1212.05
  5054.2 1220.86  5064.2 1236.27  5094.2 1242.71  5101.7 1245.69  5104.2 1245.69
#Mann= 3 ,-1 , 0
  4709.6     .12       0    4927     .05       0  4938.8     .12       0
Bank Sta=4927,4938.8
XS Rating Curve= 0 ,0
Exp/Cntr=0.3,0.1

Type RM Length L Ch R = 1 ,511     ,0,0,0
BEGIN DESCRIPTION:
BLACK CREEK 1.0
END DESCRIPTION:
XS GIS Cut Line= 3
      2085696.23     13859985.03        2085875.       13860075.
      2086074.97       13860075.
#Sta/Elev= 30
  4800.3 1241.99  4852.6 1237.31  4866.1 1237.28  4902.8 1234.63  4919.5 1230.65
  4925.1 1230.81  4933.3  1229.1  4941.8 1222.81  4947.4 1223.15  4964.2 1207.28
  4969.8 1206.67  4986.5 1193.56  4992.1 1194.13  4997.6 1184.42  5002.9 1184.42
  5004.5 1177.86    5005 1177.36  5016.3 1177.86  5030.4 1178.46  5040.4 1181.18
  5050.4 1182.19  5070.4 1182.61  5080.4 1185.61  5110.4 1203.95  5120.4 1212.63
  5140.4 1223.34  5150.4 1226.75  5170.4 1229.86  5190.4 1236.11  5200.4 1237.59
#Mann= 3 ,-1 , 0
  4800.3     .12       0  5004.5     .05       0  5016.3     .12       0
Bank Sta=5004.5,5016.3
XS Rating Curve= 0 ,0
Exp/Cntr=0.3,0.1

Chan Stop Cuts=-1
Use User Specified Reach Order=0
Composite Channel Slope=5