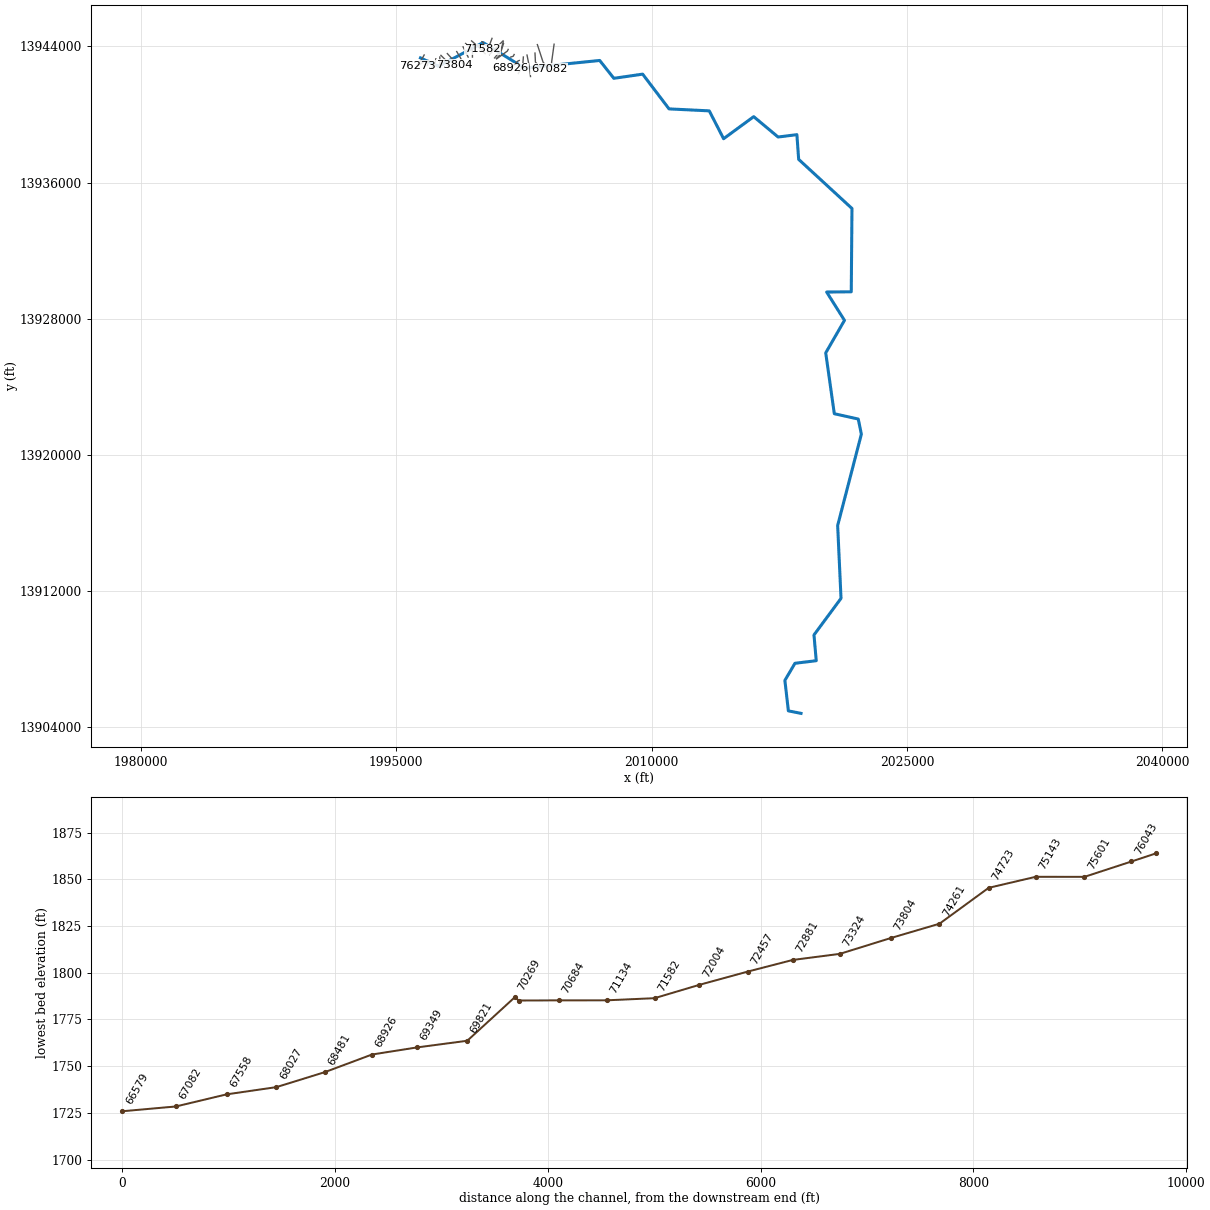
--- BLOCK CREEK.prj (project) ---

Proj Title=BLOCK CREEK Base Level Engineering
Current Plan=p01
Default Exp/Contr=0.3,0.1
English Units
Geom File=g01
Flow File=f01
Plan File=p01
Y Axis Title=Elevation
X Axis Title(PF)=Main Channel Distance
X Axis Title(XS)=Station
BEGIN DESCRIPTION:
BLOCK CREEK
END DESCRIPTION:
DSS Export Rating Curves= 0
DSS Export Rating Curve Sorted= 0
DSS Export Volume Flow Curves= 0
DXF OffsetX= 0
DXF OffsetY= 0
DXF ScaleX= 1
DXF ScaleY= 10

--- BLOCK CREEK.p01 (plan) ---

Plan Title=Multiple Run
Short Identifier=Multiple
Geom File=g01
Flow File=f01
Subcritical Flow
K Sum by GR= 0
Std Step Tol= 0.01
Critical Tol= 0.01
Num of Std Step Trials= 20
Max Error Tol= 0.3
Flow Tol Ratio= 0.001
Split Flow NTrial= 30
Split Flow Tol= 0.02
Split Flow Ratio= 0.02
Log Output Level= 0
Friction Slope Method= 1
Unsteady Friction Slope Method= 2
Unsteady Bridges Friction Slope Method= 1
Parabolic Critical Depth
Global Vel Dist=  1 , 1 , 1
Global Log Level= 0
CheckData=True
Encroach Param= -1, 0, 0, 0
BEGIN DESCRIPTION:
Multiple Run
END DESCRIPTION:

--- BLOCK CREEK.f01 (steady flow) ---

Flow Title=Multiple
Program Version=4.10
Number of Profiles= 7
Profile Names=10-year,25-year,50-year,1pct_min,100-year,1pct_plu,500-year
River Rch & RM=BLOCK CREEK,Reach-1         ,76273
    1052    1816    2557    1747    3487    6957    6431
River Rch & RM=BLOCK CREEK,Reach-1         ,73324
    1086    1873    2635    1798    3588    7160    6603
River Rch & RM=BLOCK CREEK,Reach-1         ,71134
    1748    3092    4424    3066    6117   12206   11611
River Rch & RM=BLOCK CREEK,Reach-1         ,68926
    2169    3873    5577    3886    7753   15470   14881
River Rch & RM=BLOCK CREEK,Reach-1         ,66101
    2538    4558    6585    4601    9180   18317   17721
River Rch & RM=BLOCK CREEK,Reach-1         ,61537
    3006    5433    7884    5529   11032   22013   21458
River Rch & RM=BLOCK CREEK,Reach-1         ,59702
    4410    8101   11887    8420   16801   33522   33341
River Rch & RM=BLOCK CREEK,Reach-1         ,57505
    4394    8032   11743    8286   16533   32987   32553
River Rch & RM=BLOCK CREEK,Reach-1         ,49243
    5129    9422   13820    9779   19513   38933   38636
River Rch & RM=BLOCK CREEK,Reach-1         ,45841
    5729   10540   15478   10960   21868   43633   43357
River Rch & RM=BLOCK CREEK,Reach-1         ,38593
    7290   13525   19976   14219   28371   56608   56837
River Rch & RM=BLOCK CREEK,Reach-1         ,37462
    7313   13551   19996   14220   28372   56609   56724
River Rch & RM=BLOCK CREEK,Reach-1         ,34107
    8115   15077   22288   15875   31674   63198   63519
River Rch & RM=BLOCK CREEK,Reach-1         ,31968
    8877   16499   24397   17376   34670   69176   69517
River Rch & RM=BLOCK CREEK,Reach-1         ,25380
    9509   17655   26096   18579   37069   73963   74229
River Rch & RM=BLOCK CREEK,Reach-1         ,24814
    9742   18093   26748   19045   38000   75819   76108
River Rch & RM=BLOCK CREEK,Reach-1         ,23130
    9760   18118   26776   19058   38025   75870   76100
River Rch & RM=BLOCK CREEK,Reach-1         ,21480
    9774   18120   26756   19025   37960   75741   75826
River Rch & RM=BLOCK CREEK,Reach-1         ,16500
   10059   18658   27559   19601   39109   78032   78156
River Rch & RM=BLOCK CREEK,Reach-1         ,15383
   10790   20034   29614   21074   42049   83898   84118
River Rch & RM=BLOCK CREEK,Reach-1         ,12121
   10985   20376   30098   21403   42704   85205   85293
River Rch & RM=BLOCK CREEK,Reach-1         ,7216
   12951   24125   35722   25425   50729  101218  101340
River Rch & RM=BLOCK CREEK,Reach-1         ,4481
   13325   24816   36740   26144   52164  104080  104153
Boundary for River Rch & Prof#=BLOCK CREEK,Reach-1         , 1
Up Type= 0
Dn Type= 3
Dn Slope=0.006
Boundary for River Rch & Prof#=BLOCK CREEK,Reach-1         , 2
Up Type= 0
Dn Type= 3
Dn Slope=0.006
Boundary for River Rch & Prof#=BLOCK CREEK,Reach-1         , 3
Up Type= 0
Dn Type= 3
Dn Slope=0.006
Boundary for River Rch & Prof#=BLOCK CREEK,Reach-1         , 4
Up Type= 0
Dn Type= 3
Dn Slope=0.006
Boundary for River Rch & Prof#=BLOCK CREEK,Reach-1         , 5
Up Type= 0
Dn Type= 3
Dn Slope=0.006
Boundary for River Rch & Prof#=BLOCK CREEK,Reach-1         , 6
Up Type= 0
Dn Type= 3
Dn Slope=0.006
Boundary for River Rch & Prof#=BLOCK CREEK,Reach-1         , 7
Up Type= 0
Dn Type= 3
Dn Slope=0.006
DSS Import GetInterval= 0
DSS Import GetPeak= 0
DSS Import FillOption= 0

--- BLOCK CREEK.g01 (geometry) ---

Geom Title=Existing Conditions
Program Version=4.10

River Reach=BLOCK CREEK     ,Reach-1
Reach XY= 30
        1996425.       13943325.      1997478.66     13942832.67
      2000104.84     13944225.48      2002535.44     13942726.04
      2006950.08      13943175.2      2007780.85     13942127.06
      2009473.44     13942371.26      2011022.45     13940330.73
      2013384.82     13940214.54      2014226.58     13938578.83
        2015995.     13939875.01      2017426.56     13938678.76
       2018531.2      13938817.2      2018635.48      13937365.2
      2021765.87     13934481.74      2021724.16     13929586.95
       2020278.6     13929573.52      2021325.65     13927909.91
      2020224.71     13925999.88      2020728.19      13922426.4
       2022134.7     13922114.23      2022317.22      13921225.1
      2020925.39     13915859.84      2021122.76     13911580.93
      2019534.29     13909431.69      2019667.25     13907918.81
      2018418.94     13907766.87       2017825.7      13906764.3
      2018030.52     13904972.57        2018775.       13904825.

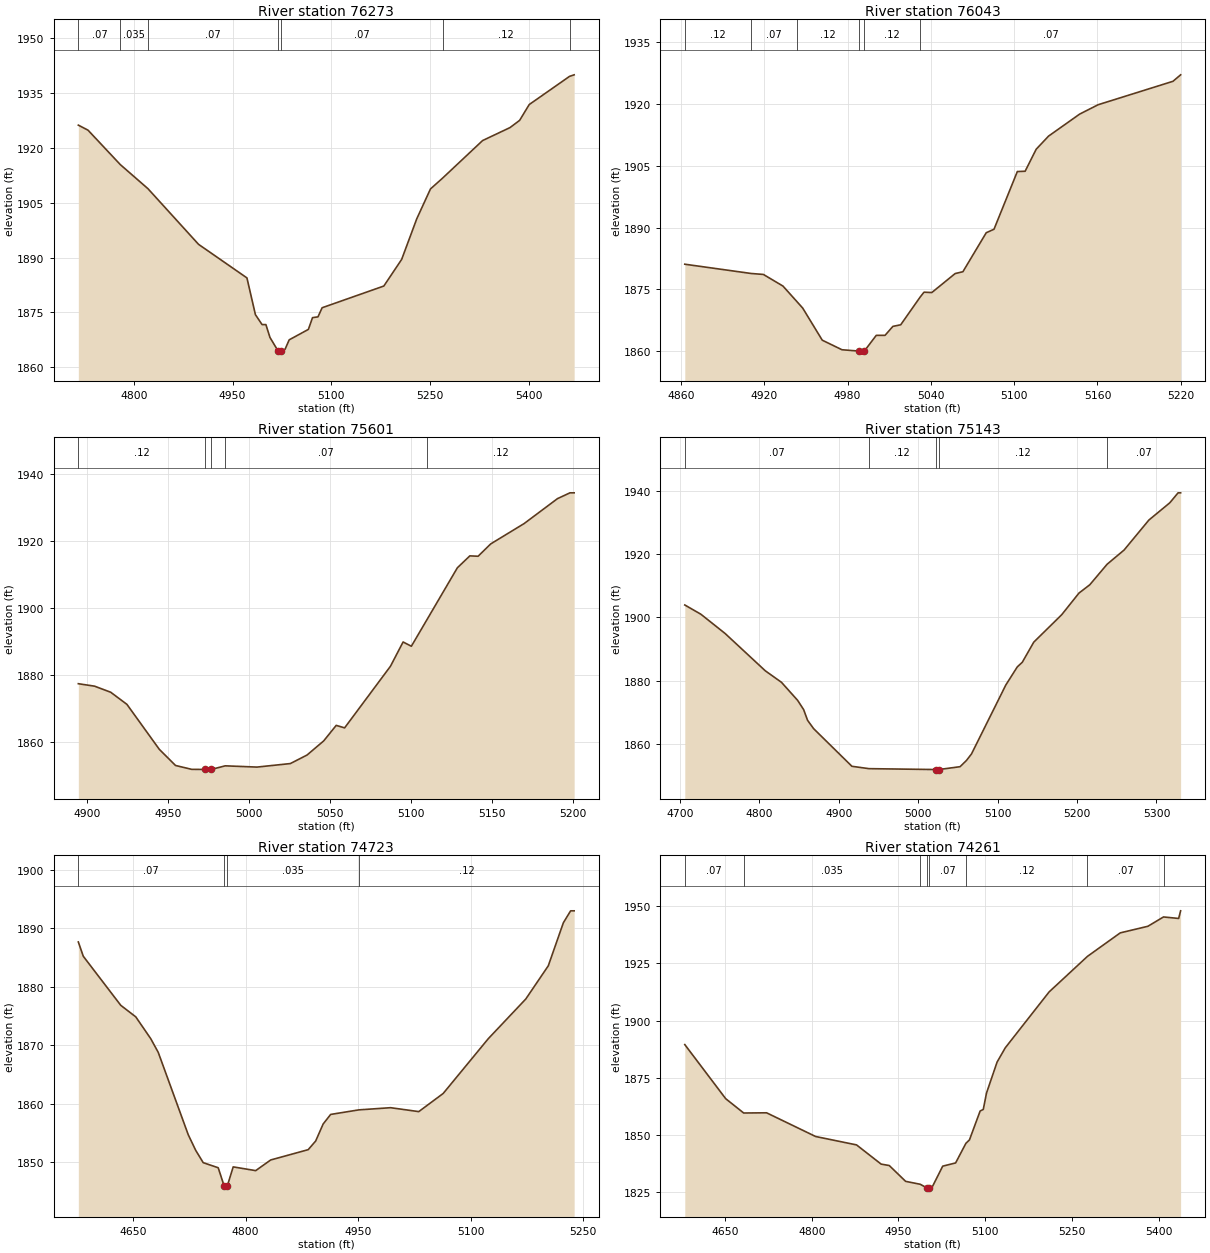
Type RM Length L Ch R = 1 ,76273   ,230,230,230
BEGIN DESCRIPTION:
BLOCK CREEK 145.0
END DESCRIPTION:
XS GIS Cut Line= 3
      1996640.94      13943497.8        1996500.       13943250.
      1996219.95     13942874.26
#Sta/Elev= 30
  4715.5 1926.22  4730.2 1924.85  4779.3 1915.43  4821.3 1908.85  4898.2 1893.63
  4971.8 1884.44  4984.7 1874.39  4994.8 1871.68  5000.6 1871.68  5006.8 1868.16
  5019.4 1864.37  5019.7 1863.87  5023.4 1864.37  5029.8 1864.94    5036  1867.5
  5065.2 1870.36  5071.5 1873.57  5079.8 1873.79  5086.1 1876.28  5179.9 1882.22
    5207  1889.5    5230 1900.63  5250.8 1908.77  5269.4 1911.76    5330    1922
  5371.7 1925.55  5386.3 1927.52  5400.9 1931.85  5462.2 1939.56  5469.2 1939.98
#Mann= 7 ,-1 , 0
  4715.5     .07       0  4779.3    .035       0  4821.3     .07       0
  5019.4     .05       0  5023.4     .07       0  5269.4     .12       0
  5462.2     .07       0
Bank Sta=5019.4,5023.4
XS Rating Curve= 0 ,0
Exp/Cntr=0.3,0.1

Type RM Length L Ch R = 1 ,76043   ,442,442,442
BEGIN DESCRIPTION:
BLOCK CREEK 144.0
END DESCRIPTION:
XS GIS Cut Line= 3
      1996625.02     13943125.02        1996525.       13943025.
      1996331.79     13942929.22
#Sta/Elev= 30
  4862.8  1881.1  4910.6 1878.85  4919.4 1878.62  4933.5  1875.8  4943.5 1872.05
  4947.7 1870.47  4961.8 1862.68    4976 1860.36  4988.1 1860.04  4988.4 1859.54
  4992.1 1860.04  5000.7 1863.85    5007 1863.85  5012.7 1866.03  5018.3 1866.41
  5032.3 1873.13  5035.1 1874.32  5040.7 1874.23  5057.5 1878.83  5063.1 1879.28
  5079.9 1888.73  5085.5 1889.58  5102.3 1903.57  5107.9 1903.64  5115.9 1908.99
  5124.8 1912.16  5147.2  1917.5  5160.5 1919.77  5214.4 1925.45  5219.9 1927.02
#Mann= 6 ,-1 , 0
  4862.8     .12       0  4910.6     .07       0  4943.5     .12       0
  4988.1     .05       0  4992.1     .12       0  5032.3     .07       0
Bank Sta=4988.1,4992.1
XS Rating Curve= 0 ,0
Exp/Cntr=0.3,0.1

Type RM Length L Ch R = 1 ,75601   ,458,458,458
BEGIN DESCRIPTION:
BLOCK CREEK 143.0
END DESCRIPTION:
XS GIS Cut Line= 3
        1996875.     13943174.96        1996875.       13943075.
        1996825.     13942875.02
#Sta/Elev= 30
  4894.7 1877.44  4904.7 1876.71  4914.7 1874.89  4924.7 1871.27  4944.7 1857.83
  4954.7 1853.01  4964.7 1851.85  4972.7 1851.82  4972.9 1851.32  4976.4 1851.32
  4976.7 1851.82  4985.4  1852.9    5005 1852.53  5025.6 1853.58  5035.9 1856.13
  5046.2 1860.36  5053.9 1864.99  5059.1 1864.25  5087.4 1882.66  5095.2 1889.91
  5100.3 1888.64  5110.1 1896.72  5128.7 1912.08  5136.4 1915.64  5141.5 1915.53
  5149.3 1919.22  5169.9 1925.29  5190.5 1932.74  5198.2 1934.48  5200.8 1934.48
#Mann= 5 ,-1 , 0
  4894.7     .12       0  4972.7     .05       0  4976.7     .12       0
  4985.4     .07       0  5110.1     .12       0
Bank Sta=4972.7,4976.7
XS Rating Curve= 0 ,0
Exp/Cntr=0.3,0.1

Type RM Length L Ch R = 1 ,75143   ,443,443,443
BEGIN DESCRIPTION:
BLOCK CREEK 142.0
END DESCRIPTION:
XS GIS Cut Line= 3
        1997325.     13943275.02        1997275.       13942975.
      1997075.01     13942725.01
#Sta/Elev= 30
  4706.1 1903.88  4726.4 1900.95  4756.8 1894.88  4807.5 1883.06  4827.8 1879.44
  4848.1 1873.75  4855.7 1870.82  4860.7 1867.42  4868.3 1864.78  4916.5 1852.88
    4938 1852.13  5021.9 1851.85  5022.1 1851.35  5025.9 1851.85  5052.7 1852.75
  5060.7 1854.71  5067.1 1856.79  5110.3 1878.58  5124.7 1884.29  5131.1 1885.79
  5145.5 1892.13  5180.7 1900.81  5202.4 1907.64    5216 1910.26  5237.8 1916.75
  5259.2 1921.25  5290.4 1930.72  5316.8 1936.19  5327.2 1939.34  5330.4 1939.34
#Mann= 5 ,-1 , 0
  4706.1     .07       0    4938     .12       0  5021.9     .05       0
  5025.9     .12       0  5237.8     .07       0
Bank Sta=5021.9,5025.9
XS Rating Curve= 0 ,0
Exp/Cntr=0.3,0.1

Type RM Length L Ch R = 1 ,74723   ,462,462,462
BEGIN DESCRIPTION:
BLOCK CREEK 141.0
END DESCRIPTION:
XS GIS Cut Line= 3
      1997559.63     13943381.61      1997558.15     13942958.42
      1997571.39     13942720.59
#Sta/Elev= 30
  4576.8 1887.65  4583.4 1885.21  4633.4 1876.83  4653.4 1874.86  4673.4 1871.13
  4683.4 1868.79  4723.4 1854.73  4733.4 1852.05  4743.4 1849.95  4763.4 1849.08
  4771.4 1845.93  4771.7 1845.43  4775.4 1845.93  4783.4 1849.23  4813.4 1848.59
  4833.4 1850.41  4883.4 1852.17  4893.4 1853.65  4903.4 1856.56  4913.4 1858.19
  4951.1 1858.97  4993.4 1859.34  5030.9 1858.67  5063.5 1861.77  5123.6 1871.12
  5173.7 1877.91  5203.7 1883.58  5223.8 1890.93  5233.5 1892.97  5238.2 1892.97
#Mann= 4 ,-1 , 0
  4576.8     .07       0  4771.4     .05       0  4775.4    .035       0
  4951.1     .12       0
Bank Sta=4771.4,4775.4
XS Rating Curve= 0 ,0
Exp/Cntr=0.3,0.1

Type RM Length L Ch R = 1 ,74261   ,457,457,457
BEGIN DESCRIPTION:
BLOCK CREEK 140.0
END DESCRIPTION:
XS GIS Cut Line= 3
      1997625.03     13943474.97        1997925.       13943175.
      1998090.48     13942774.89
#Sta/Elev= 30
  4580.6 1889.46  4651.3  1865.8  4682.4 1859.53    4722 1859.62  4806.8 1849.25
  4877.5 1845.58    4920 1837.18  4934.1 1836.55  4962.4 1829.63  4987.7 1828.35
  4999.3 1826.73  4999.5 1826.23  5003.3 1826.73  5007.5 1826.73  5026.5 1836.28
  5048.8 1837.69  5066.6 1846.27  5072.7 1847.76  5091.2  1860.4  5096.6 1861.09
  5102.2 1868.26  5120.5 1881.81  5134.7 1888.07  5210.4 1912.49  5276.7 1928.05
  5333.4 1938.33  5381.2 1941.22  5408.2  1945.3  5434.4 1944.64  5437.8 1947.98
#Mann= 8 ,-1 , 0
  4580.6     .07       0  4682.4    .035       0  4987.7     .07       0
  4999.3     .05       0  5003.3     .07       0  5066.6     .12       0
  5276.7     .07       0  5408.2     .12       0
Bank Sta=4999.3,5003.3
XS Rating Curve= 0 ,0
Exp/Cntr=0.3,0.1

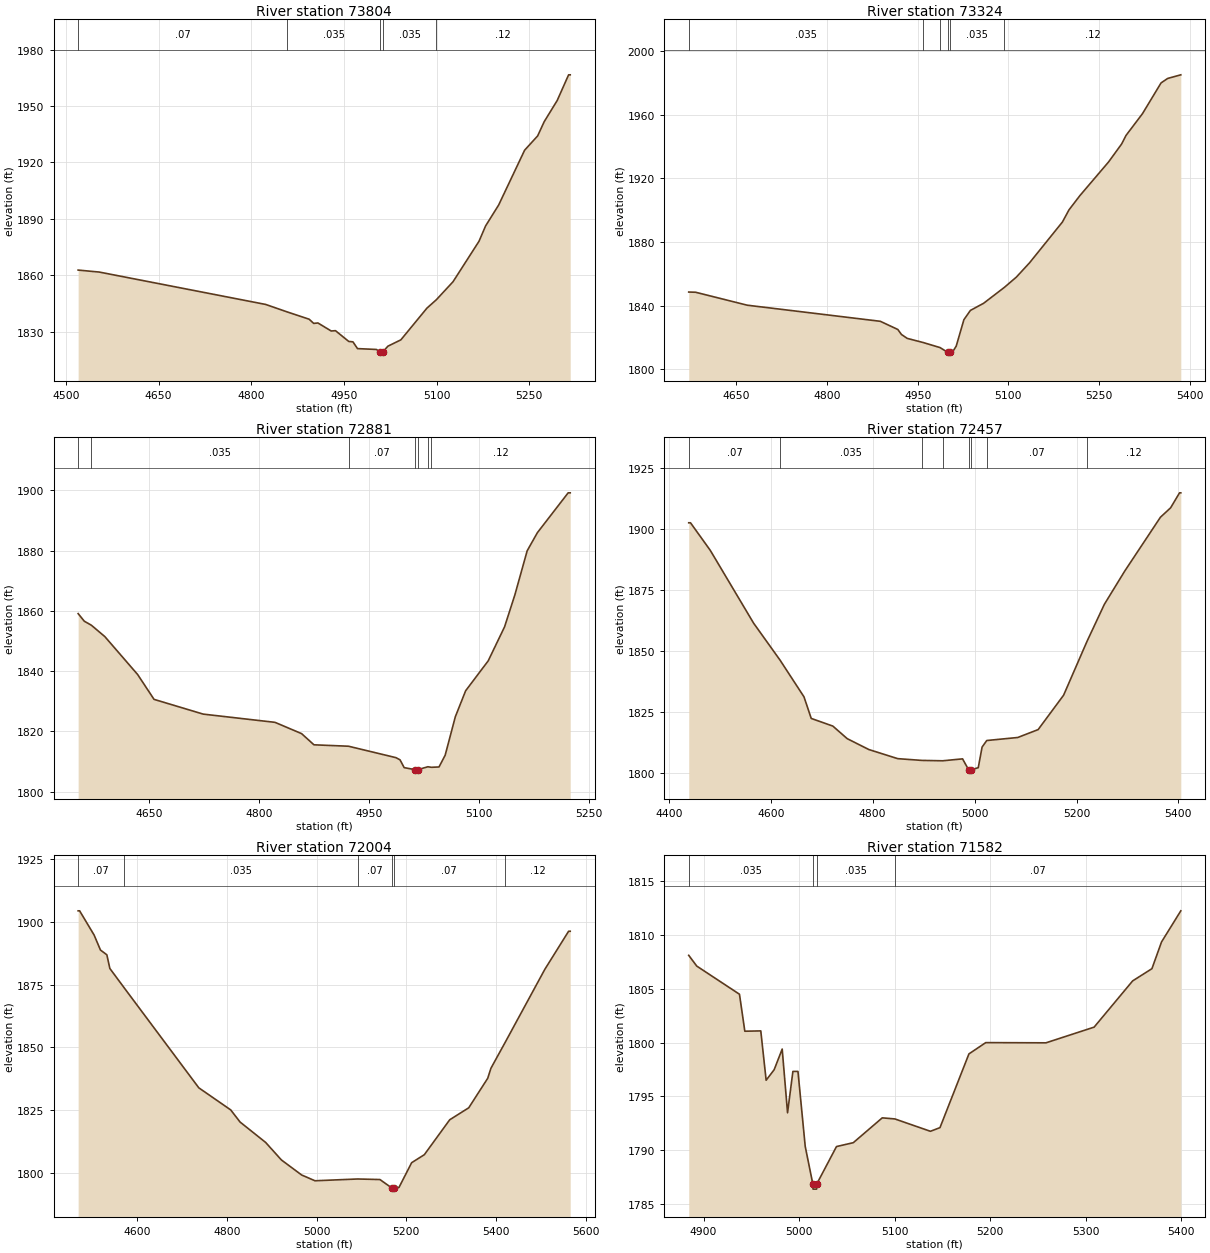
Type RM Length L Ch R = 1 ,73804   ,480,480,480
BEGIN DESCRIPTION:
BLOCK CREEK 139.0
END DESCRIPTION:
XS GIS Cut Line= 3
       1998000.7     13943579.26        1998325.       13943225.
        1998425.     13942925.01
#Sta/Elev= 30
  4519.7 1862.75  4553.8  1861.7  4823.3 1844.47  4857.7 1840.54  4893.6 1836.62
    4901 1834.39  4907.8 1834.62  4929.4 1830.34  4936.2 1830.53  4957.7  1824.8
  4964.5 1824.58  4971.9 1820.98  5002.6 1820.53  5008.5 1819.08  5008.8 1818.58
  5012.5 1819.08  5021.1 1822.27  5042.1 1825.65  5084.3 1842.52  5099.4 1846.94
  5126.5 1856.55  5168.6  1878.1  5179.2 1886.22  5200.3 1897.32  5242.4 1926.52
  5263.5 1934.12    5274 1941.63  5295.1 1952.94  5313.6  1966.6  5316.2  1966.6
#Mann= 5 ,-1 , 0
  4519.7     .07       0  4857.7    .035       0  5008.5    .035       0
  5012.5    .035       0  5099.4     .12       0
Bank Sta=5008.5,5012.5
XS Rating Curve= 0 ,0
Exp/Cntr=0.3,0.1

Type RM Length L Ch R = 1 ,73324   ,443,443,443
BEGIN DESCRIPTION:
BLOCK CREEK 138.0
END DESCRIPTION:
XS GIS Cut Line= 3
      1998552.78     13943697.32        1998775.       13943325.
      1998925.01     13942974.98
#Sta/Elev= 30
    4571  1848.5  4582.3 1848.37  4667.9 1840.22  4888.1  1830.1    4917 1824.97
  4923.1 1821.81  4932.6 1819.36    4959 1816.76  4986.9 1813.58  4999.6 1810.59
  4999.9 1810.09  5003.7 1810.59  5007.3 1810.59  5013.7 1814.51  5026.4  1831.1
  5037.2 1836.95    5059 1841.42  5093.6 1851.49  5113.4 1857.95  5135.1  1866.9
  5189.5 1892.55  5200.4 1900.21  5218.6 1909.23  5265.7 1930.22  5287.5 1941.62
  5294.7 1946.96  5321.9 1960.62  5352.7 1979.98  5363.6  1982.8  5385.4 1985.08
#Mann= 6 ,-1 , 0
    4571    .035       0    4959     .07       0  4986.9    .035       0
  4999.6    .035       0  5003.7    .035       0  5093.6     .12       0
Bank Sta=4999.6,5003.7
XS Rating Curve= 0 ,0
Exp/Cntr=0.3,0.1

Type RM Length L Ch R = 1 ,72881   ,424,424,424
BEGIN DESCRIPTION:
BLOCK CREEK 137.0
END DESCRIPTION:
XS GIS Cut Line= 3
      1998924.98     13943975.04        1999125.       13943575.
      1999225.02     13943374.97
#Sta/Elev= 30
    4553 1859.08  4561.4 1856.56    4571 1855.23  4589.4 1851.45  4634.1 1838.88
  4656.5 1830.63  4723.5 1825.74  4821.4 1823.01  4857.7 1819.26  4874.5 1815.56
  4921.6 1815.09  4986.3  1811.3  4991.9 1810.56  4997.5 1807.99  5012.2 1807.33
  5012.4 1806.83  5016.3 1807.33  5029.8 1808.28  5034.6  1808.1    5045 1808.21
  5053.4 1812.11  5067.3  1824.9  5081.3 1833.48  5112.1 1843.42  5134.4  1854.7
  5148.4 1865.27  5165.2 1879.91  5179.1 1885.91  5221.1 1899.14  5223.9 1899.14
#Mann= 7 ,-1 , 0
    4553     .07       0    4571    .035       0  4921.6     .07       0
  5012.2     .05       0  5016.3     .07       0  5029.8    .035       0
  5034.6     .12       0
Bank Sta=5012.2,5016.3
XS Rating Curve= 0 ,0
Exp/Cntr=0.3,0.1

Type RM Length L Ch R = 1 ,72457   ,453,453,453
BEGIN DESCRIPTION:
BLOCK CREEK 136.0
END DESCRIPTION:
XS GIS Cut Line= 3
      1999075.02     13944174.98        1999475.       13943775.
        1999475.     13943374.95
#Sta/Elev= 30
    4439 1902.48  4442.5 1902.48  4481.4 1891.13  4566.2 1861.34  4618.6 1846.01
  4665.2 1831.07  4679.4 1822.21  4721.8 1819.07  4750.1  1813.9  4792.5 1809.45
  4849.1 1805.71  4896.2 1804.99  4937.3 1804.83  4976.4 1805.62  4988.4 1801.09
  4988.7 1800.59  4992.6 1801.09  5007.2 1802.01  5014.7 1810.45  5023.9 1813.15
  5084.7 1814.39  5124.7 1817.63  5174.7 1831.75  5220.6 1853.82  5254.7 1869.04
  5294.7 1882.68  5364.7 1904.75  5384.7 1908.62  5402.2 1914.77  5404.7 1914.77
#Mann= 8 ,-1 , 0
    4439     .07       0  4618.6    .035       0  4896.2     .07       0
  4937.3    .035       0  4988.4    .035       0  4992.6    .035       0
  5023.9     .07       0  5220.6     .12       0
Bank Sta=4988.4,4992.6
XS Rating Curve= 0 ,0
Exp/Cntr=0.3,0.1

Type RM Length L Ch R = 1 ,72004   ,422,422,422
BEGIN DESCRIPTION:
BLOCK CREEK 135.0
END DESCRIPTION:
XS GIS Cut Line= 3
      1999425.03     13944324.97        1999825.       13943975.
      2000225.03     13943574.97
#Sta/Elev= 30
  4468.5 1904.43  4471.8 1904.43  4504.1 1894.78  4518.3  1888.8  4532.5 1886.91
  4539.2 1881.46  4571.6 1873.64  4737.5  1833.9  4808.7 1825.09  4829.6 1820.25
  4886.5 1812.14  4921.7 1805.15  4966.7 1799.17  4996.6 1796.85  5091.4 1797.56
  5141.4 1797.34  5167.6 1794.02  5167.8 1793.52  5171.8 1794.02  5183.8 1794.17
  5212.1 1804.05  5240.4 1807.24    5297 1821.16  5339.4 1825.93  5381.8 1837.71
  5388.9 1841.69  5420.3 1851.89  5509.1 1881.12  5562.1 1896.29  5565.7 1896.29
#Mann= 6 ,-1 , 0
  4468.5     .07       0  4571.6    .035       0  5091.4     .07       0
  5167.6    .035       0  5171.8     .07       0  5420.3     .12       0
Bank Sta=5167.6,5171.8
XS Rating Curve= 0 ,0
Exp/Cntr=0.3,0.1

Type RM Length L Ch R = 1 ,71582   ,448,448,448
BEGIN DESCRIPTION:
BLOCK CREEK 134.0
END DESCRIPTION:
XS GIS Cut Line= 3
      2000025.02     13944274.99        2000125.       13944225.
        2000075.       13943825.
#Sta/Elev= 30
  4884.5 1808.12  4892.9 1807.12  4937.6  1804.5  4943.2 1801.06  4959.9 1801.09
  4965.5  1796.5  4973.9 1797.48  4982.3  1799.4  4987.9 1793.47  4993.5 1797.32
  4998.8 1797.32  5006.4 1790.34  5014.3 1786.87  5014.6 1786.37  5018.3 1786.37
  5018.6 1786.87  5039.1 1790.33  5056.7 1790.69    5087    1793  5100.2  1792.9
  5137.4 1791.75  5147.4 1792.09  5177.7 1798.95  5195.3    1800  5258.3 1799.98
  5308.7 1801.44    5349 1805.74  5369.2 1806.88  5379.2 1809.36  5399.4 1812.26
#Mann= 4 ,-1 , 0
  4884.5    .035       0  5014.3    .035       0  5018.6    .035       0
  5100.2     .07       0
Bank Sta=5014.3,5018.6
XS Rating Curve= 0 ,0
Exp/Cntr=0.3,0.1

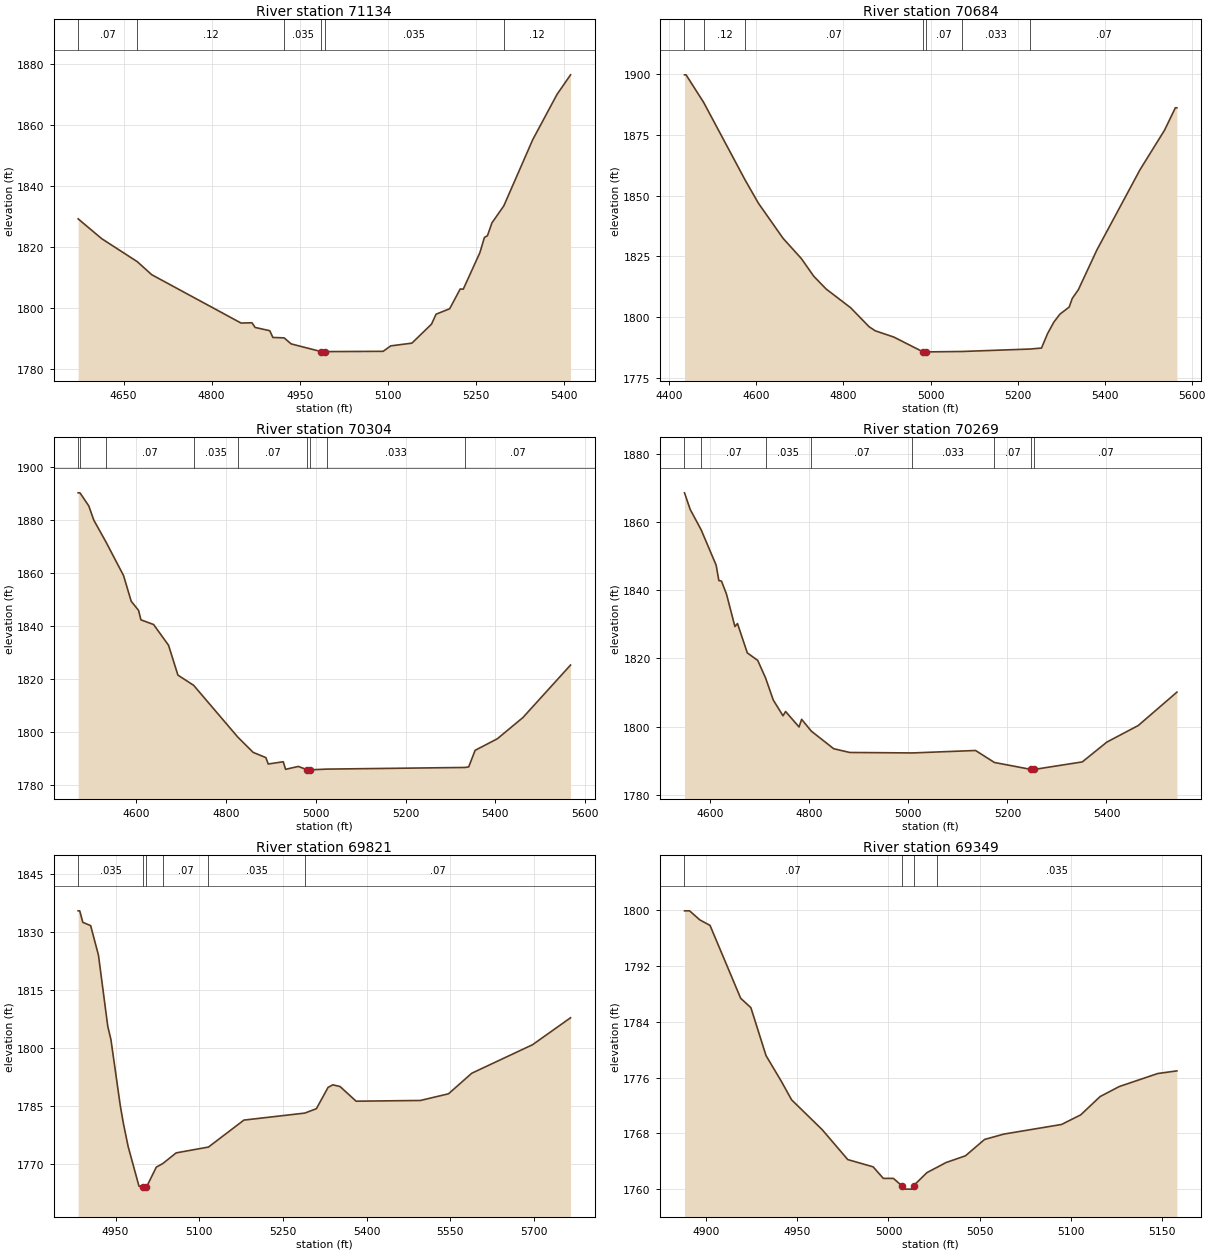
Type RM Length L Ch R = 1 ,71134   ,450,450,450
BEGIN DESCRIPTION:
BLOCK CREEK 133.0
END DESCRIPTION:
XS GIS Cut Line= 3
      2000625.01     13944475.04        2000475.       13944075.
      2000375.01     13943675.05
#Sta/Elev= 30
  4572.4 1829.19  4612.5 1822.71  4673.1 1815.19  4697.9  1810.9  4850.1 1795.08
  4868.8 1795.17  4874.1 1793.64  4899.1 1792.57  4904.4 1790.36  4923.6 1790.22
  4935.6 1788.25  4986.7 1785.73  4987.2 1785.23  4992.9 1785.73  5092.4 1785.82
  5105.3  1787.6  5141.4  1788.5  5174.9 1794.73  5182.6 1797.97  5205.8 1799.76
  5223.8 1806.23    5229 1806.17  5257.3 1818.11  5265.1 1823.11  5270.2 1823.66
  5277.9 1827.88  5298.1 1833.44  5347.5 1855.14  5388.8 1869.93  5411.9 1876.35
#Mann= 6 ,-1 , 0
  4572.4     .07       0  4673.1     .12       0  4923.6    .035       0
  4986.7     .05       0  4992.9    .035       0  5298.1     .12       0
Bank Sta=4986.7,4992.9
XS Rating Curve= 0 ,0
Exp/Cntr=0.3,0.1

Type RM Length L Ch R = 1 ,70684   ,380,380,380
BEGIN DESCRIPTION:
BLOCK CREEK 132.0
END DESCRIPTION:
XS GIS Cut Line= 3
      2001275.03     13944325.03        2000875.       13943925.
      2000475.01     13943525.01
#Sta/Elev= 30
  4434.7 1899.67  4438.3 1899.67  4478.8 1888.31  4574.3 1856.32  4604.4 1846.91
    4661 1832.47  4703.4 1824.06  4731.7 1816.83    4760  1811.6  4816.6 1803.85
    4859 1796.04  4873.1 1794.38  4915.6 1791.82  4983.1  1785.7  4983.6  1785.2
  4989.5  1785.7  5073.1 1785.88  5229.6 1786.89    5255 1787.29  5269.1 1793.27
  5283.3 1797.93  5297.4 1801.24  5318.6 1804.13  5325.7 1807.68  5339.8 1811.32
  5382.3 1827.63  5481.3 1860.61  5537.8 1876.91  5562.6 1886.11  5566.1 1886.11
#Mann= 7 ,-1 , 0
  4434.7     .07       0  4478.8     .12       0  4574.3     .07       0
  4983.1     .05       0  4989.5     .07       0  5073.1    .033       0
  5229.6     .07       0
Bank Sta=4983.1,4989.5
XS Rating Curve= 0 ,0
Exp/Cntr=0.3,0.1

Type RM Length L Ch R = 1 ,70304   ,35,35,35
BEGIN DESCRIPTION:
BLOCK CREEK 131.0
END DESCRIPTION:
XS GIS Cut Line= 3
      2001287.85     13944268.51      2001139.38     13943758.04
      2000774.98     13943324.97
#Sta/Elev= 30
  4470.1 1890.25  4474.1 1890.25  4493.8 1885.31    4505 1879.93  4531.9 1871.75
  4571.3 1858.99  4588.3 1849.31  4604.8 1845.83    4610 1842.28  4638.3  1840.5
  4671.6 1832.66  4692.5 1821.39  4727.6 1817.53  4825.9 1797.99  4860.3 1792.19
  4888.6 1790.23  4893.8 1787.81  4927.3 1788.66  4932.5  1785.8  4960.9 1786.89
  4980.9 1785.62  4981.4 1785.12  4987.3 1785.62  5023.9 1785.88    5333 1786.51
  5340.7 1786.73    5355 1792.98  5404.4 1797.33  5461.6 1805.37  5567.7 1825.19
#Mann= 9 ,-1 , 0
  4470.1     .07       0  4474.1     .12       0  4531.9     .07       0
  4727.6    .035       0  4825.9     .07       0  4980.9     .05       0
  4987.3     .07       0  5023.9    .033       0    5333     .07       0
Bank Sta=4980.9,4987.3
XS Rating Curve= 0 ,0
Exp/Cntr=0.3,0.1

Type RM Length L Ch R = 1 ,70269   ,448,448,448
BEGIN DESCRIPTION:
BLOCK CREEK 130.5
END DESCRIPTION:
XS GIS Cut Line= 4
      2001300.95     13944165.97      2001165.09     13943734.91
        2001083.     13943495.23      2000881.12     13943288.87
#Sta/Elev= 30
  4548.1 1868.64  4559.6 1863.77  4581.7 1857.79    4612 1847.41  4617.5 1842.88
  4622.8 1842.73    4633 1838.85  4649.9 1829.38  4655.1 1830.26  4674.9 1821.64
  4695.9 1819.44  4711.7 1814.31  4727.4 1807.78    4747 1803.17  4752.2 1804.43
  4779.3 1799.89  4784.6 1802.13  4804.1 1798.67  4849.3  1793.5  4881.7  1792.4
  5008.1 1792.26  5135.7 1792.98  5173.8 1789.46  5247.7 1787.42  5248.2 1786.92
  5254.1 1787.42  5351.2 1789.63  5400.7 1795.44  5464.2 1800.32  5542.1  1810.1
#Mann= 8 ,-1 , 0
  4548.1     .12       0  4581.7     .07       0  4711.7    .035       0
  4804.1     .07       0  5008.1    .033       0  5173.8     .07       0
  5247.7     .05       0  5254.1     .07       0
Bank Sta=5247.7,5254.1
XS Rating Curve= 0 ,0
Exp/Cntr=0.3,0.1

Type RM Length L Ch R = 1 ,69821   ,472,472,472
BEGIN DESCRIPTION:
BLOCK CREEK 130.0
END DESCRIPTION:
XS GIS Cut Line= 3
      2001575.02     13943825.03        2001525.       13943725.
      2000900.04     13943273.72
#Sta/Elev= 30
  4882.9 1835.42  4885.7 1835.42  4891.3 1832.44  4905.3  1831.6  4919.3 1823.97
    4936 1805.59  4941.6 1802.22  4958.4 1785.15    4964 1780.54  4972.4 1774.64
  4991.9 1764.35  4998.8 1764.07  4999.3 1763.57  5005.3 1764.07    5023 1769.25
  5034.6 1770.17  5058.6 1772.93  5116.5 1774.43    5180 1781.39  5289.1  1783.2
    5310 1784.34  5330.9 1789.83  5339.4  1790.5  5352.4 1790.06  5381.2 1786.27
  5496.5 1786.46  5546.8 1788.18  5588.5 1793.49  5697.6 1800.86  5765.6 1807.81
#Mann= 6 ,-1 , 0
  4882.9    .035       0  4998.8    .035       0  5005.3    .035       0
  5034.6     .07       0  5116.5    .035       0  5289.1     .07       0
Bank Sta=4998.8,5005.3
XS Rating Curve= 0 ,0
Exp/Cntr=0.3,0.1

Type RM Length L Ch R = 1 ,69349   ,423,423,423
BEGIN DESCRIPTION:
BLOCK CREEK 129.0
END DESCRIPTION:
XS GIS Cut Line= 3
      2001925.01     13943525.02        2001875.       13943425.
      2001725.04     13943375.01
#Sta/Elev= 30
  4888.2 1799.95    4891 1799.95  4896.6 1798.65  4902.2 1797.86    4919  1787.4
  4924.6 1786.05  4932.9 1779.17  4941.3 1775.48  4946.9 1772.83  4963.7 1768.54
  4977.7 1764.25  4991.6 1763.21  4997.2 1761.55  5002.7 1761.55  5007.3 1760.51
  5007.8 1760.01  5013.3 1760.01  5013.8 1760.51  5021.1 1762.38  5026.7 1763.15
  5031.6 1763.83  5042.2 1764.79  5052.7 1767.14  5063.3 1767.91  5094.9 1769.29
  5105.4 1770.67    5116 1773.29  5126.5 1774.73  5147.6  1776.6  5158.1 1776.98
#Mann= 4 ,-1 , 0
  4888.2     .07       0  5007.3     .05       0  5013.8     .07       0
  5026.7    .035       0
Bank Sta=5007.3,5013.8
XS Rating Curve= 0 ,0
Exp/Cntr=0.3,0.1

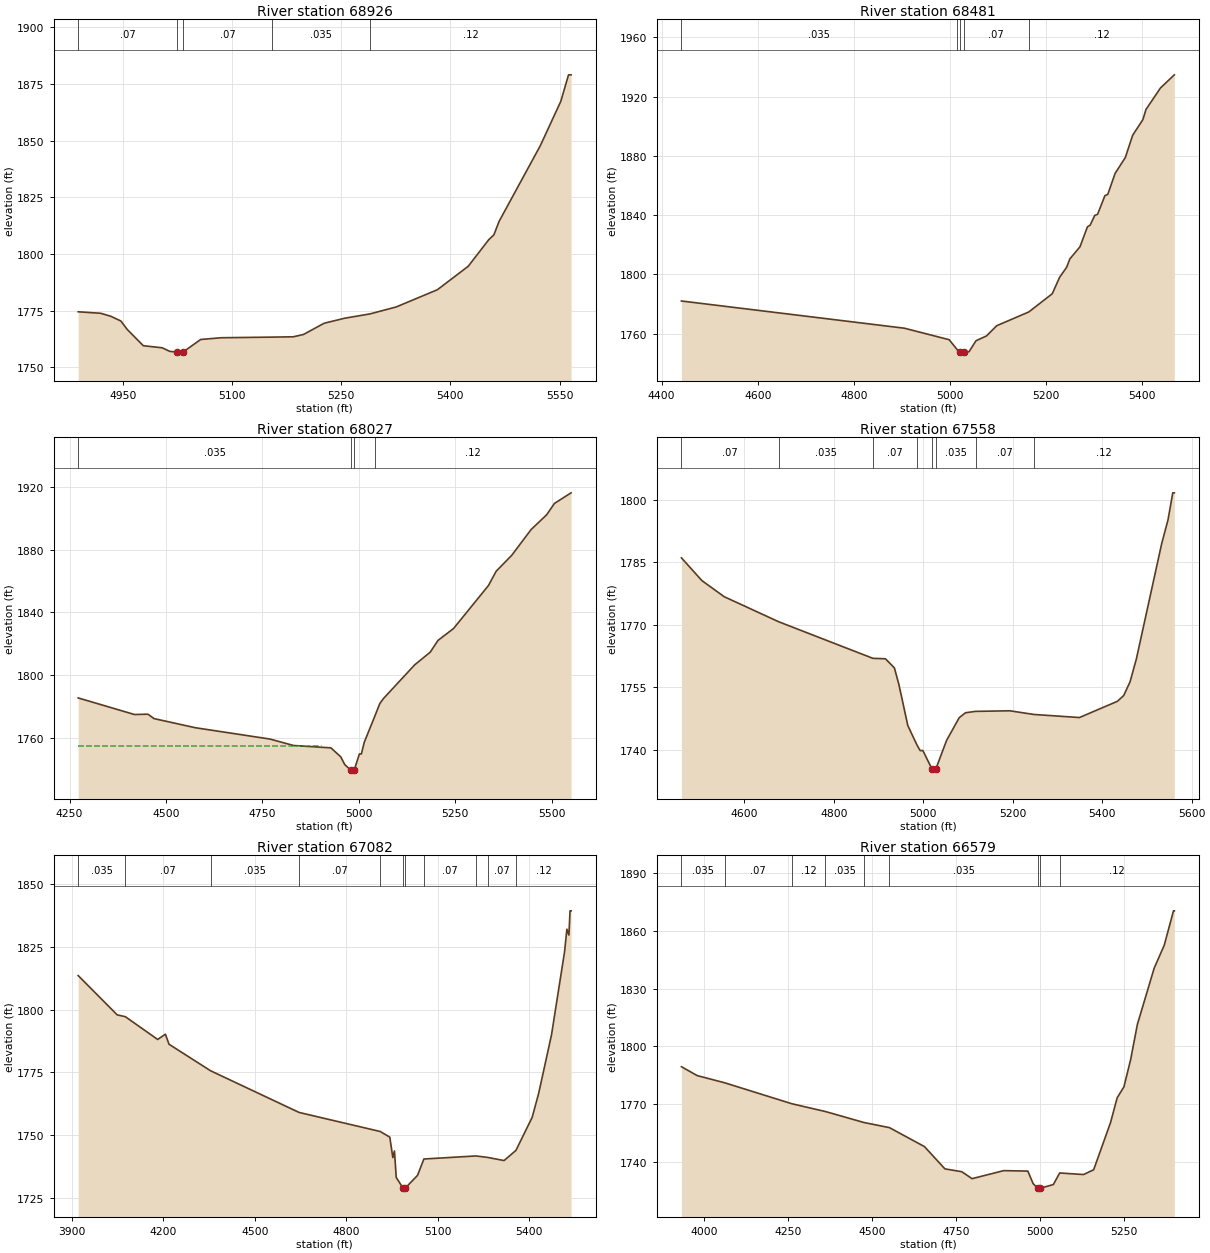
Type RM Length L Ch R = 1 ,68926   ,445,445,445
BEGIN DESCRIPTION:
BLOCK CREEK 128.0
END DESCRIPTION:
XS GIS Cut Line= 3
      2002225.01     13943175.01        2002125.       13943125.
        2001725.       13942725.
#Sta/Elev= 30
  4888.4 1774.46  4919.2 1773.81  4933.1 1772.51  4947.1  1770.4  4955.5 1766.79
  4977.9 1759.49  5003.8 1758.58  5014.4 1756.98  5024.5 1756.72    5025 1756.22
  5032.1 1756.22  5032.6 1756.72  5056.8 1762.24  5085.1 1763.01  5154.2 1763.28
  5184.1 1763.43  5198.2 1764.46  5226.5 1769.41  5254.8 1771.63  5289.3 1773.51
  5325.5 1776.59  5382.1 1784.19  5424.5 1794.54  5452.8  1806.3  5459.8 1808.41
  5466.9 1814.34  5523.5  1847.7  5551.8 1867.36  5562.4 1879.03  5565.9 1879.03
#Mann= 5 ,-1 , 0
  4888.4     .07       0  5024.5     .05       0  5032.6     .07       0
  5154.2    .035       0  5289.3     .12       0
Bank Sta=5024.5,5032.6
XS Rating Curve= 0 ,0
Exp/Cntr=0.3,0.1

Type RM Length L Ch R = 1 ,68481   ,454,454,454
BEGIN DESCRIPTION:
BLOCK CREEK 127.0
END DESCRIPTION:
XS GIS Cut Line= 3
      2002465.98     13943377.85        2002425.       13942825.
      2002174.98     13942424.97
#Sta/Elev= 30
  4441.2 1781.96  4905.3 1763.59  4998.5 1755.83  5015.3  1749.1  5020.4 1747.26
  5020.9 1746.76  5028.6 1747.26  5039.8 1747.68  5054.5 1755.14  5076.3 1758.37
  5097.6 1765.28  5164.2 1774.54  5213.1 1786.83  5228.5 1797.97  5243.2 1804.78
  5249.7 1810.34  5270.9 1818.57  5286.3 1831.99  5292.1 1833.21  5301.6 1839.74
  5307.5 1840.48  5322.8 1853.13  5328.7 1853.93    5344 1868.11  5365.3 1878.85
  5380.6 1893.91  5401.8 1904.42  5408.3 1911.31  5438.4 1925.79  5467.3 1934.68
#Mann= 5 ,-1 , 0
  4441.2    .035       0  5015.3     .07       0  5020.4    .035       0
  5028.6     .07       0  5164.2     .12       0
Bank Sta=5020.4,5028.6
XS Rating Curve= 0 ,0
Exp/Cntr=0.3,0.1

Type RM Length L Ch R = 1 ,68027   ,469,469,469
BEGIN DESCRIPTION:
BLOCK CREEK 126.0
END DESCRIPTION:
XS GIS Cut Line= 3
      2002681.25     13943492.49        2002825.       13942775.
      2002886.11     13942232.07
#Sta/Elev= 30
  4272.3 1785.43  4418.1 1774.87  4453.3 1775.05  4469.1 1772.25  4576.1 1766.43
  4769.5 1759.22  4830.8  1755.1  4927.6  1753.6  4953.1 1747.89  4963.3 1743.01
  4979.5 1739.26    4980 1738.76  4987.8 1739.26  5001.5 1749.71  5006.6 1749.71
  5014.1 1757.17  5041.5 1773.81  5054.4 1781.85  5064.4 1785.18  5144.9 1806.54
  5185.2 1814.62  5205.3  1822.1  5245.6 1829.69  5336.1 1857.09  5356.3 1866.28
  5396.5 1876.37  5446.8 1892.81  5487.1 1902.24  5507.2 1909.44  5550.4 1916.21
#Mann= 4 ,-1 , 0
  4272.3    .035       0  4979.5    .035       0  4987.8    .035       0
  5041.5     .12       0
#XS Ineff= 2 , 0
       0  4902.1  1754.9               0
Permanent Ineff=
       F       F
Bank Sta=4979.5,4987.8
XS Rating Curve= 0 ,0
Exp/Cntr=0.3,0.1

Type RM Length L Ch R = 1 ,67558   ,476,476,476
BEGIN DESCRIPTION:
BLOCK CREEK 125.0
END DESCRIPTION:
XS GIS Cut Line= 3
      2003150.01     13943610.46        2003175.       13943075.
      2003574.98     13942675.02
#Sta/Elev= 30
  4459.6 1786.03  4505.1 1780.59  4555.2 1776.71  4677.2 1770.69  4887.5 1761.93
  4915.6 1761.82  4935.6 1759.64  4945.6 1755.68  4965.6 1745.81  4985.8  1741.2
  4993.1 1739.81  4999.2 1739.81  5019.7 1735.38  5020.2 1734.88  5028.2 1735.38
  5052.2 1742.24  5080.5  1747.7  5094.6 1748.88    5117 1749.21  5193.6 1749.35
  5247.2 1748.47  5349.2 1747.73    5434 1751.62  5448.2 1753.02  5462.3 1756.29
  5476.5 1761.82    5533 1789.43  5547.2 1795.15  5557.8 1801.62  5561.3 1801.62
#Mann= 8 ,-1 , 0
  4459.6     .07       0  4677.2    .035       0  4887.5     .07       0
  4985.8    .035       0  5019.7    .035       0  5028.2    .035       0
    5117     .07       0  5247.2     .12       0
Bank Sta=5019.7,5028.2
XS Rating Curve= 0 ,0
Exp/Cntr=0.3,0.1

Type RM Length L Ch R = 1 ,67082   ,503,503,503
BEGIN DESCRIPTION:
BLOCK CREEK 124.0
END DESCRIPTION:
XS GIS Cut Line= 3
      2003288.91       13944107.        2003625.       13943075.
      2003975.03     13942674.97
#Sta/Elev= 30
  3920.4 1813.61  4048.3 1797.94  4075.1 1797.21  4181.2 1788.12  4206.5 1790.22
  4218.4 1786.21    4355 1775.61  4645.1    1759  4911.1  1751.4  4942.6 1749.14
  4952.6 1740.97  4957.9 1743.64  4963.7 1733.06  4985.5  1728.9    4986  1728.4
    4994  1728.9  5033.7  1733.9  5054.4 1740.42  5225.2 1741.64    5264 1741.05
  5317.5  1739.8  5356.4 1743.86  5409.6 1757.03    5431 1766.63  5473.2 1790.05
  5515.9 1823.11  5523.5 1832.12  5530.1 1829.79  5533.9 1839.45  5537.3 1839.45
#Mann= 11 ,-1 , 0
  3920.4    .035       0  4075.1     .07       0    4355    .035       0
  4645.1     .07       0  4911.1    .035       0  4985.5    .035       0
    4994    .035       0  5054.4     .07       0  5225.2     .12       0
    5264     .07       0  5356.4     .12       0
Bank Sta=4985.5,4994
XS Rating Curve= 0 ,0
Exp/Cntr=0.3,0.1

Type RM Length L Ch R = 1 ,66579   ,478,478,478
BEGIN DESCRIPTION:
BLOCK CREEK 123.0
END DESCRIPTION:
XS GIS Cut Line= 3
      2004271.54     13944131.38        2004125.       13943075.
        2004125.     13942674.99
#Sta/Elev= 30
  3933.5 1789.44  3980.3 1784.82  4062.4 1781.07  4261.9  1770.2  4361.6 1766.16
  4476.6 1760.45  4552.3 1757.79  4656.7 1747.93  4717.3 1736.38  4767.8 1734.88
  4798.1 1731.28  4892.4 1735.46  4964.1 1735.22  4979.8 1728.74  4993.2 1726.35
  4993.7 1725.85  5001.7 1726.35    5040 1728.22  5058.8 1734.24    5130 1733.43
    5160 1735.92    5210 1760.33    5230 1773.31    5250 1778.96    5270 1793.11
    5290 1811.39    5340  1840.6    5370 1852.55  5397.5 1870.39    5400 1870.39
#Mann= 9 ,-1 , 0
  3933.5    .035       0  4062.4     .07       0  4261.9     .12       0
  4361.6    .035       0  4476.6     .07       0  4552.3    .035       0
  4993.2    .035       0  5001.7    .035       0  5058.8     .12       0
Bank Sta=4993.2,5001.7
XS Rating Curve= 0 ,0
Exp/Cntr=0.3,0.1