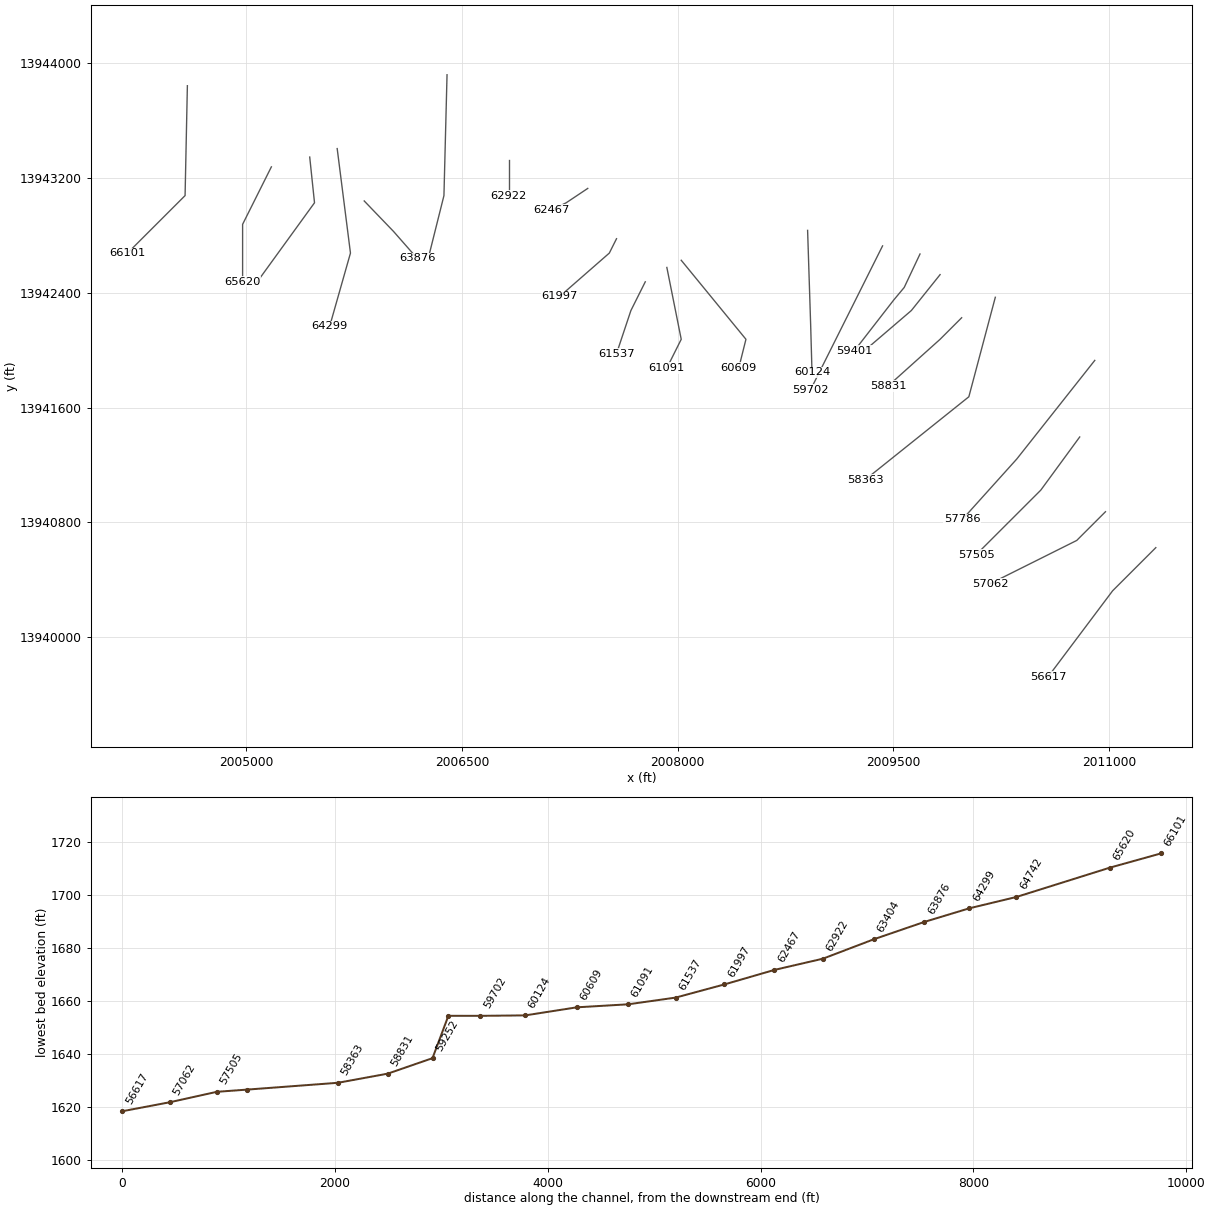
HEC-RAS study BLOCK CREEK.prj: BLOCK CREEK Base Level Engineering

--- BLOCK CREEK.g01 (geometry) --- (continued)

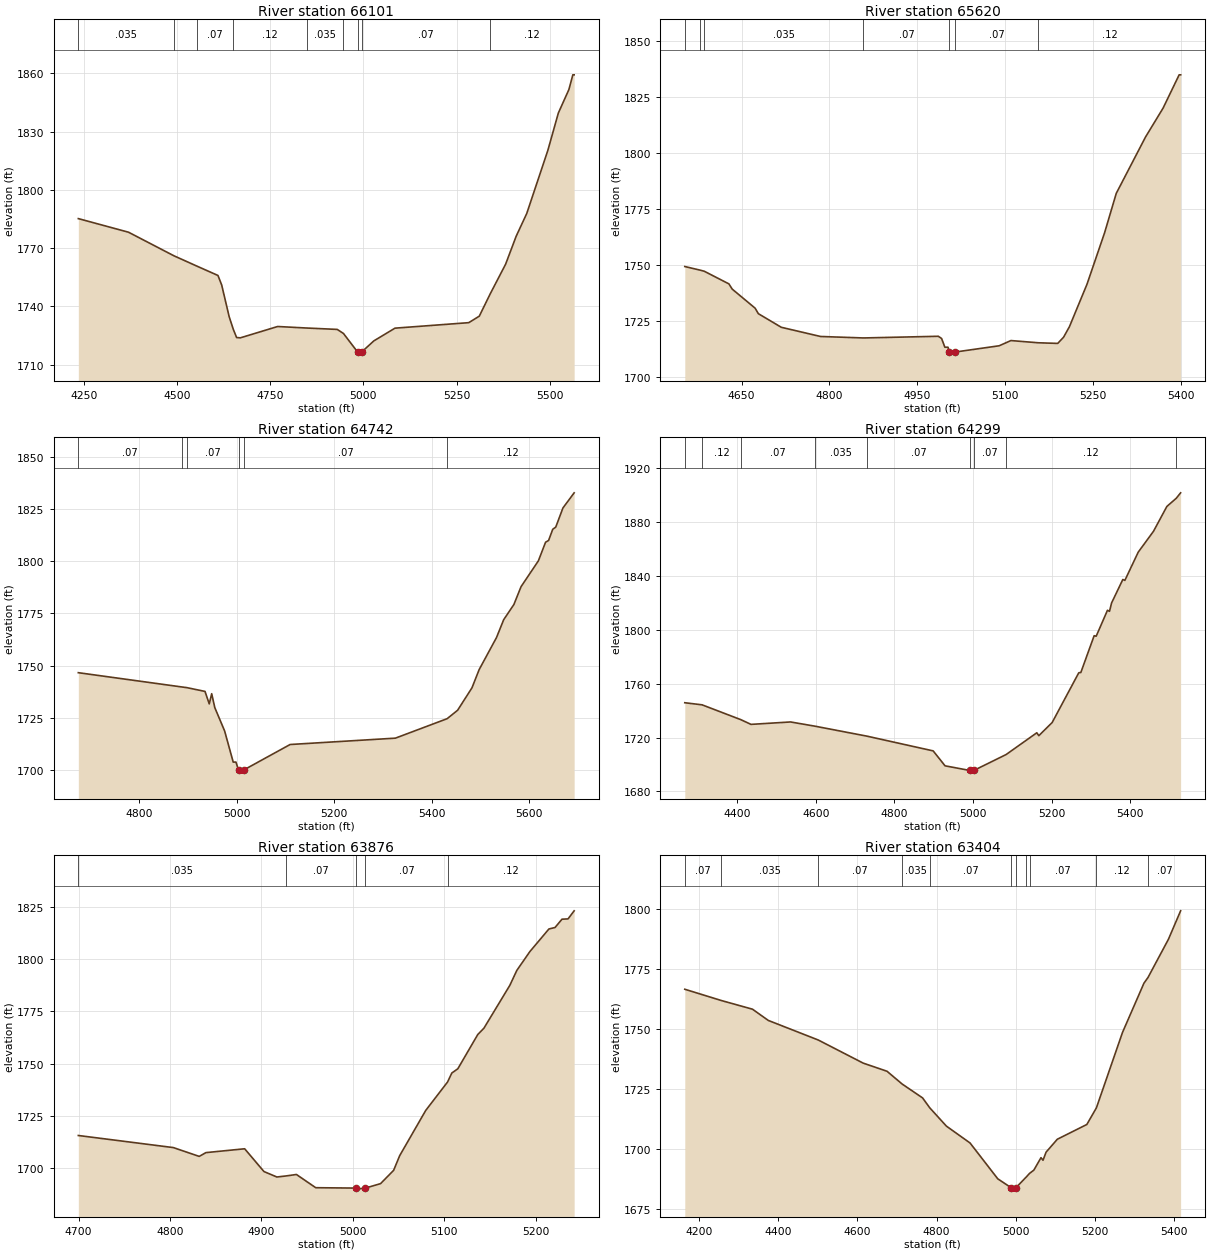
Type RM Length L Ch R = 1 ,66101   ,481,481,481
BEGIN DESCRIPTION:
BLOCK CREEK 122.0
END DESCRIPTION:
XS GIS Cut Line= 3
      2004590.98     13943839.64        2004575.       13943075.
        2004175.       13942675.
#Sta/Elev= 30
  4235.2 1785.14  4369.9 1778.13  4491.5 1766.01  4552.6 1760.74  4609.9 1755.86
  4619.9 1750.95  4639.9 1734.67  4651.1 1728.09  4659.9  1723.9  4669.9 1723.73
    4770 1729.57  4847.9 1728.79    4930 1728.07  4946.7 1725.97  4984.9 1716.36
  4985.4 1715.86  4995.1 1716.36  5028.3 1722.18  5084.9 1728.72  5282.9 1731.55
  5311.1 1734.89  5340.7 1746.48  5381.8 1761.67  5410.1 1776.06  5438.4 1787.74
    5495 1820.21  5523.3 1839.52  5551.6 1851.62  5562.2 1859.19  5565.7 1859.19
#Mann= 9 ,-1 , 0
  4235.2    .035       0  4491.5     .12       0  4552.6     .07       0
  4651.1     .12       0  4847.9    .035       0  4946.7     .07       0
  4984.9     .05       0  4995.1     .07       0  5340.7     .12       0
Bank Sta=4984.9,4995.1
XS Rating Curve= 0 ,0
Exp/Cntr=0.3,0.1

Type RM Length L Ch R = 1 ,65620   ,878,878,878
BEGIN DESCRIPTION:
BLOCK CREEK 121.0
END DESCRIPTION:
XS GIS Cut Line= 3
      2005174.98     13943274.96        2004975.       13942875.
        2004975.     13942474.97
#Sta/Elev= 30
  4552.8 1749.22  4578.1 1747.66    4586 1747.12  4628.2 1741.45  4633.8 1739.12
  4672.9  1730.6  4678.5 1728.12  4717.7 1722.03  4784.7 1717.92    4858 1717.26
    4986 1718.01  4991.6 1717.02  4997.2 1713.11  5002.5 1713.11  5004.9 1710.97
  5005.4 1710.47  5015.1 1710.97    5090 1713.76    5110 1716.09  5156.9  1715.1
    5190 1714.82    5200 1717.59    5210  1722.3    5240 1741.28    5270 1764.26
    5290 1781.94    5340 1807.16    5370 1820.09  5397.5    1835    5400    1835
#Mann= 7 ,-1 , 0
  4552.8     .12       0  4578.1     .07       0    4586    .035       0
    4858     .07       0  5004.9     .05       0  5015.1     .07       0
  5156.9     .12       0
Bank Sta=5004.9,5015.1
XS Rating Curve= 0 ,0
Exp/Cntr=0.3,0.1

Type RM Length L Ch R = 1 ,64742   ,443,443,443
BEGIN DESCRIPTION:
BLOCK CREEK 120.0
END DESCRIPTION:
XS GIS Cut Line= 3
      2005441.67     13943343.19        2005475.       13943025.
      2005066.65     13942461.17
#Sta/Elev= 30
  4675.6 1746.58  4887.6 1739.74    4898 1739.42  4935.2  1737.6  4943.9 1731.62
  4948.9 1736.51  4955.3 1729.82  4975.4 1718.65    4993 1703.72  4998.6 1703.72
  5003.9 1699.89  5004.4 1699.39  5014.2 1699.89  5109.6 1712.15  5325.4  1715.2
  5431.4 1724.53  5452.9 1728.58  5482.3 1739.33    5497 1748.06  5532.6 1763.45
  5547.3    1772  5568.2 1779.26  5582.9 1787.83  5618.4 1800.21  5633.1 1809.12
  5639.3 1809.98  5647.8 1815.33    5654 1816.38  5668.7 1825.55  5691.7 1832.81
#Mann= 6 ,-1 , 0
  4675.6     .07       0  4887.6     .12       0    4898     .07       0
  5003.9     .05       0  5014.2     .07       0  5431.4     .12       0
Bank Sta=5003.9,5014.2
XS Rating Curve= 0 ,0
Exp/Cntr=0.3,0.1

Type RM Length L Ch R = 1 ,64299   ,423,423,423
BEGIN DESCRIPTION:
BLOCK CREEK 119.0
END DESCRIPTION:
XS GIS Cut Line= 3
      2005632.64     13943402.18        2005725.       13942675.
      2005580.55     13942166.02
#Sta/Elev= 30
  4266.4 1745.81  4310.4 1744.26  4409.1 1733.26  4434.9 1729.76  4535.7 1731.56
    4599 1728.36  4730.3 1721.02  4898.6 1710.11  4928.9 1699.03  4991.8  1695.6
  4992.3  1695.1  5002.1  1695.6  5084.3  1707.4  5162.4 1723.53  5167.6 1721.39
  5201.5 1731.14  5269.3 1768.05  5274.5 1768.24  5308.4 1795.51  5313.6 1795.15
  5342.3 1814.36  5347.5 1813.61  5352.8 1819.83  5381.4  1837.2  5386.6 1836.53
  5420.5 1857.42  5459.6 1873.01  5493.5 1891.37  5517.4 1897.42  5528.5 1901.46
#Mann= 9 ,-1 , 0
  4266.4     .07       0  4310.4     .12       0  4409.1     .07       0
    4599    .035       0  4730.3     .07       0  4991.8     .05       0
  5002.1     .07       0  5084.3     .12       0  5517.4     .07       0
Bank Sta=4991.8,5002.1
XS Rating Curve= 0 ,0
Exp/Cntr=0.3,0.1

Type RM Length L Ch R = 1 ,63876   ,472,472,472
BEGIN DESCRIPTION:
BLOCK CREEK 118.0
END DESCRIPTION:
XS GIS Cut Line= 3
      2005820.64      13943037.7        2006025.       13942825.
      2006188.11     13942639.21
#Sta/Elev= 30
  4699.8 1715.59  4803.7 1709.81    4832  1705.6  4839.3  1707.4  4881.7 1709.24
  4902.8 1698.35  4916.9 1695.75  4926.4 1696.22  4938.3 1696.95  4959.4 1690.63
  5003.3 1690.45  5003.8 1689.95  5013.7 1690.45  5030.3 1692.58  5044.6 1698.94
  5051.2 1705.94  5079.7 1727.58  5103.6 1741.18  5108.2 1745.45  5114.8 1747.49
  5136.6 1763.86  5143.3 1766.87  5171.7  1787.4  5179.3 1794.51  5193.6 1803.53
  5214.4 1814.32  5221.1 1815.03  5228.7    1819  5235.3 1819.14    5242    1823
#Mann= 5 ,-1 , 0
  4699.8    .035       0  4926.4     .07       0  5003.3     .05       0
  5013.7     .07       0  5103.6     .12       0
Bank Sta=5003.3,5013.7
XS Rating Curve= 0 ,0
Exp/Cntr=0.3,0.1

Type RM Length L Ch R = 1 ,63404   ,482,482,482
BEGIN DESCRIPTION:
BLOCK CREEK 117.0
END DESCRIPTION:
XS GIS Cut Line= 3
      2006396.53     13943916.04        2006375.       13943075.
      2006275.01     13942675.02
#Sta/Elev= 30
  4163.4 1766.65  4255.9 1761.95  4334.5 1758.35  4374.5 1753.67  4500.9 1745.51
  4614.6 1735.88  4674.6 1732.51  4713.1 1727.17  4764.6 1721.41  4782.5 1717.33
  4824.7 1709.68  4884.7 1702.63  4954.7 1687.72  4989.3 1683.93  4989.8 1683.43
  5000.1 1683.93  5026.3 1688.41  5035.2    1690  5045.9 1691.34    5064 1696.53
  5069.1 1695.46  5076.9 1698.83  5105.2 1704.19  5179.9 1710.35  5204.1 1717.28
  5270.1 1748.69  5324.3 1769.18  5334.6 1771.57  5386.1 1787.43    5417  1799.3
#Mann= 11 ,-1 , 0
  4163.4     .07       0  4255.9    .035       0  4500.9     .07       0
  4713.1    .035       0  4782.5     .07       0  4989.3     .05       0
  5000.1     .07       0  5026.3    .035       0  5035.2     .07       0
  5204.1     .12       0  5334.6     .07       0
Bank Sta=4989.3,5000.1
XS Rating Curve= 0 ,0
Exp/Cntr=0.3,0.1

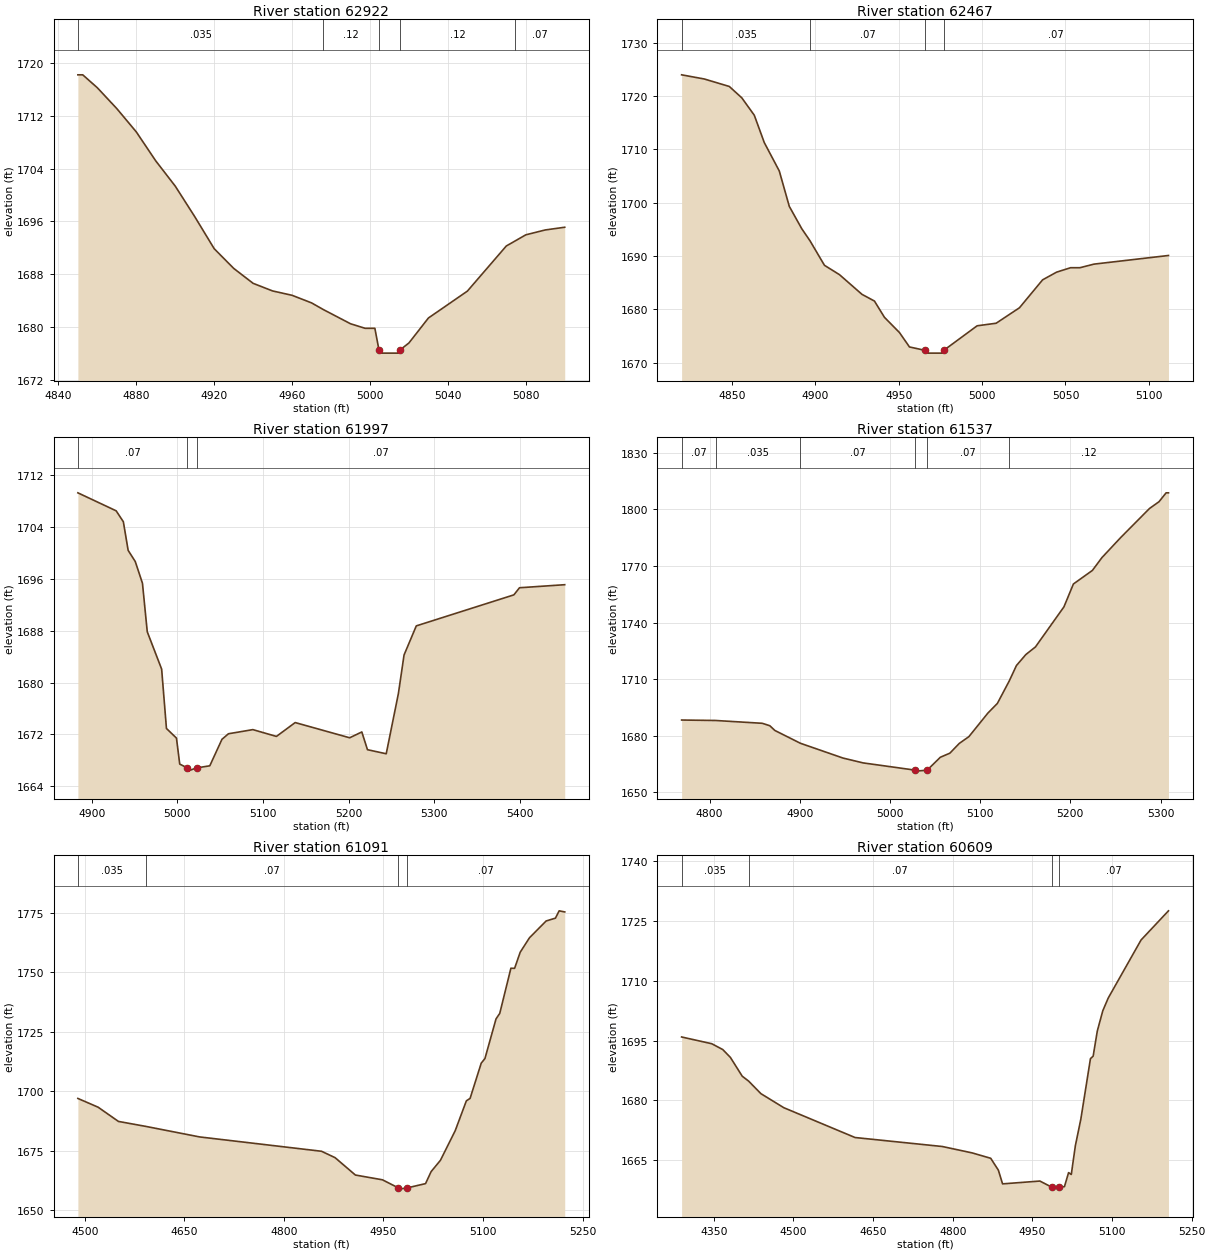
Type RM Length L Ch R = 1 ,62922   ,455,455,455
BEGIN DESCRIPTION:
BLOCK CREEK 116.0
END DESCRIPTION:
XS GIS Cut Line= 3
        2006825.     13943325.03        2006825.       13943175.
        2006825.     13943075.03
#Sta/Elev= 30
    4850  1718.2  4852.5  1718.2    4860 1716.24    4870 1713.08    4880 1709.55
    4890 1705.16    4900 1701.34    4910 1696.72    4920 1691.86    4930 1688.88
    4940 1686.61    4950 1685.46    4960  1684.8    4970 1683.65  4976.1 1682.63
    4990 1680.49  4997.5  1679.8  5002.5  1679.8  5004.6 1676.54  5005.1 1676.04
    5015 1676.04  5015.5 1676.54    5020 1677.58    5030 1681.36    5050 1685.43
    5070 1692.27  5074.4 1693.01    5080 1693.96    5090  1694.7    5100 1695.11
#Mann= 5 ,-1 , 0
    4850    .035       0  4976.1     .12       0  5004.6     .05       0
  5015.5     .12       0  5074.4     .07       0
Bank Sta=5004.6,5015.5
XS Rating Curve= 0 ,0
Exp/Cntr=0.3,0.1

Type RM Length L Ch R = 1 ,62467   ,470,470,470
BEGIN DESCRIPTION:
BLOCK CREEK 115.0
END DESCRIPTION:
XS GIS Cut Line= 3
      2007375.03     13943125.02        2007225.       13943025.
      2007125.01     13942975.01
#Sta/Elev= 30
  4819.7 1723.96  4833.3 1723.18  4848.3 1721.78  4855.8 1719.65  4863.3 1716.39
  4869.3 1711.26  4878.3 1705.94  4884.3 1699.31  4891.8 1695.11  4896.7 1692.87
  4905.4 1688.26  4914.4 1686.51  4927.9 1682.82  4935.4 1681.56  4941.4 1678.51
  4950.4 1675.66  4956.4 1672.96    4966  1672.3  4966.5  1671.8  4976.4  1671.8
  4976.9  1672.3    4997 1676.92  5008.4  1677.4  5022.4  1680.3  5036.3 1685.54
  5044.7 1686.98  5053.1 1687.81  5058.7 1687.81  5067.1 1688.48  5111.8  1690.1
#Mann= 4 ,-1 , 0
  4819.7    .035       0  4896.7     .07       0    4966     .05       0
  4976.9     .07       0
Bank Sta=4966,4976.9
XS Rating Curve= 0 ,0
Exp/Cntr=0.3,0.1

Type RM Length L Ch R = 1 ,61997   ,460,460,460
BEGIN DESCRIPTION:
BLOCK CREEK 114.0
END DESCRIPTION:
XS GIS Cut Line= 3
      2007574.98     13942774.97        2007525.       13942675.
      2007181.26      13942374.4
#Sta/Elev= 30
  4883.8  1709.3  4928.5 1706.52  4936.9 1704.83  4942.5 1700.41  4950.8 1698.69
  4959.2 1695.33  4964.8 1687.84  4981.6 1682.07  4987.2 1672.91  4998.9 1671.42
  5002.7 1667.41  5011.5 1666.82    5012 1666.32  5022.4 1666.82  5037.8 1667.14
    5052 1671.23  5059.6 1672.09  5088.1 1672.73  5115.6 1671.68  5137.5 1673.82
  5201.1 1671.47  5215.3 1672.37  5221.9 1669.63  5243.8    1669    5258  1678.3
  5264.6 1684.25  5278.9 1688.75  5392.8 1693.54  5399.4 1694.64  5452.2 1695.11
#Mann= 3 ,-1 , 0
  4883.8     .07       0  5011.5     .05       0  5022.4     .07       0
Bank Sta=5011.5,5022.4
XS Rating Curve= 0 ,0
Exp/Cntr=0.3,0.1

Type RM Length L Ch R = 1 ,61537   ,446,446,446
BEGIN DESCRIPTION:
BLOCK CREEK 113.0
END DESCRIPTION:
XS GIS Cut Line= 3
        2007775.       13942475.        2007675.       13942275.
      2007575.01     13941975.03
#Sta/Elev= 30
    4769 1688.39  4806.6 1688.15  4858.4 1686.66  4866.8 1685.37  4872.4 1682.86
  4900.7 1676.08  4947.9 1668.25  4970.2 1665.68  5028.3 1661.82  5028.8 1661.32
  5041.2 1661.82  5055.9 1668.68  5066.4 1670.82  5076.9 1676.01  5087.5 1679.58
  5108.6 1692.08  5119.1 1697.19  5132.4 1709.21  5140.2 1717.24  5150.7 1723.09
  5161.3 1727.11  5192.9 1748.34  5203.4 1760.46  5224.5 1767.67    5235 1774.42
  5256.1  1785.2  5287.8 1800.47  5298.3 1804.04  5306.2 1808.76  5308.8 1808.76
#Mann= 6 ,-1 , 0
    4769     .07       0  4806.6    .035       0  4900.7     .07       0
  5028.3     .05       0  5041.2     .07       0  5132.4     .12       0
Bank Sta=5028.3,5041.2
XS Rating Curve= 0 ,0
Exp/Cntr=0.3,0.1

Type RM Length L Ch R = 1 ,61091   ,482,482,482
BEGIN DESCRIPTION:
BLOCK CREEK 112.0
END DESCRIPTION:
XS GIS Cut Line= 3
      2007925.01     13942574.95        2008025.       13942075.
      2007924.98     13941874.96
#Sta/Elev= 30
  4489.7 1696.95  4520.2 1693.26  4550.8 1687.28  4591.6 1685.21  4673.2 1680.75
  4856.8 1674.72  4877.2 1672.03  4907.8 1664.72  4948.6 1662.71  4972.7 1659.29
  4973.2 1658.79  4985.6 1659.29  5013.5 1661.11  5021.9 1666.16  5035.9  1670.9
  5058.2 1683.38    5075 1695.94  5080.6 1696.97  5097.4 1711.79    5103 1713.75
  5119.7 1730.42  5125.3 1732.74  5142.1 1751.73  5147.7  1751.7  5156.1 1758.46
  5170.1 1764.56  5195.2 1771.62  5209.2 1772.81  5214.8 1775.89  5223.2 1775.42
#Mann= 4 ,-1 , 0
  4489.7    .035       0  4591.6     .07       0  4972.7     .05       0
  4985.6     .07       0
Bank Sta=4972.7,4985.6
XS Rating Curve= 0 ,0
Exp/Cntr=0.3,0.1

Type RM Length L Ch R = 1 ,60609   ,485,485,485
BEGIN DESCRIPTION:
BLOCK CREEK 111.0
END DESCRIPTION:
XS GIS Cut Line= 3
      2008025.01     13942624.99        2008475.       13942075.
      2008424.99     13941874.97
#Sta/Elev= 30
  4289.4 1695.89  4346.1  1694.2  4366.9 1692.73  4381.3 1690.75  4403.5 1686.04
  4415.6  1684.8  4438.7 1681.65  4481.8 1678.12    4616 1670.62  4780.4 1668.36
  4836.4 1666.76  4871.5  1665.4  4885.9 1662.41  4893.8 1658.97  4964.1 1659.68
  4986.3 1658.15  4986.8 1657.65  4999.3 1658.15  5010.3 1658.27  5018.1  1661.8
  5023.2 1661.33  5030.9 1668.58  5041.2 1675.25  5059.3 1690.44  5064.4 1691.08
  5072.2  1697.4  5082.5 1702.47  5092.8 1705.69  5154.6 1720.27  5206.2  1727.6
#Mann= 4 ,-1 , 0
  4289.4    .035       0  4415.6     .07       0  4986.3     .05       0
  4999.3     .07       0
Bank Sta=4986.3,4999.3
XS Rating Curve= 0 ,0
Exp/Cntr=0.3,0.1

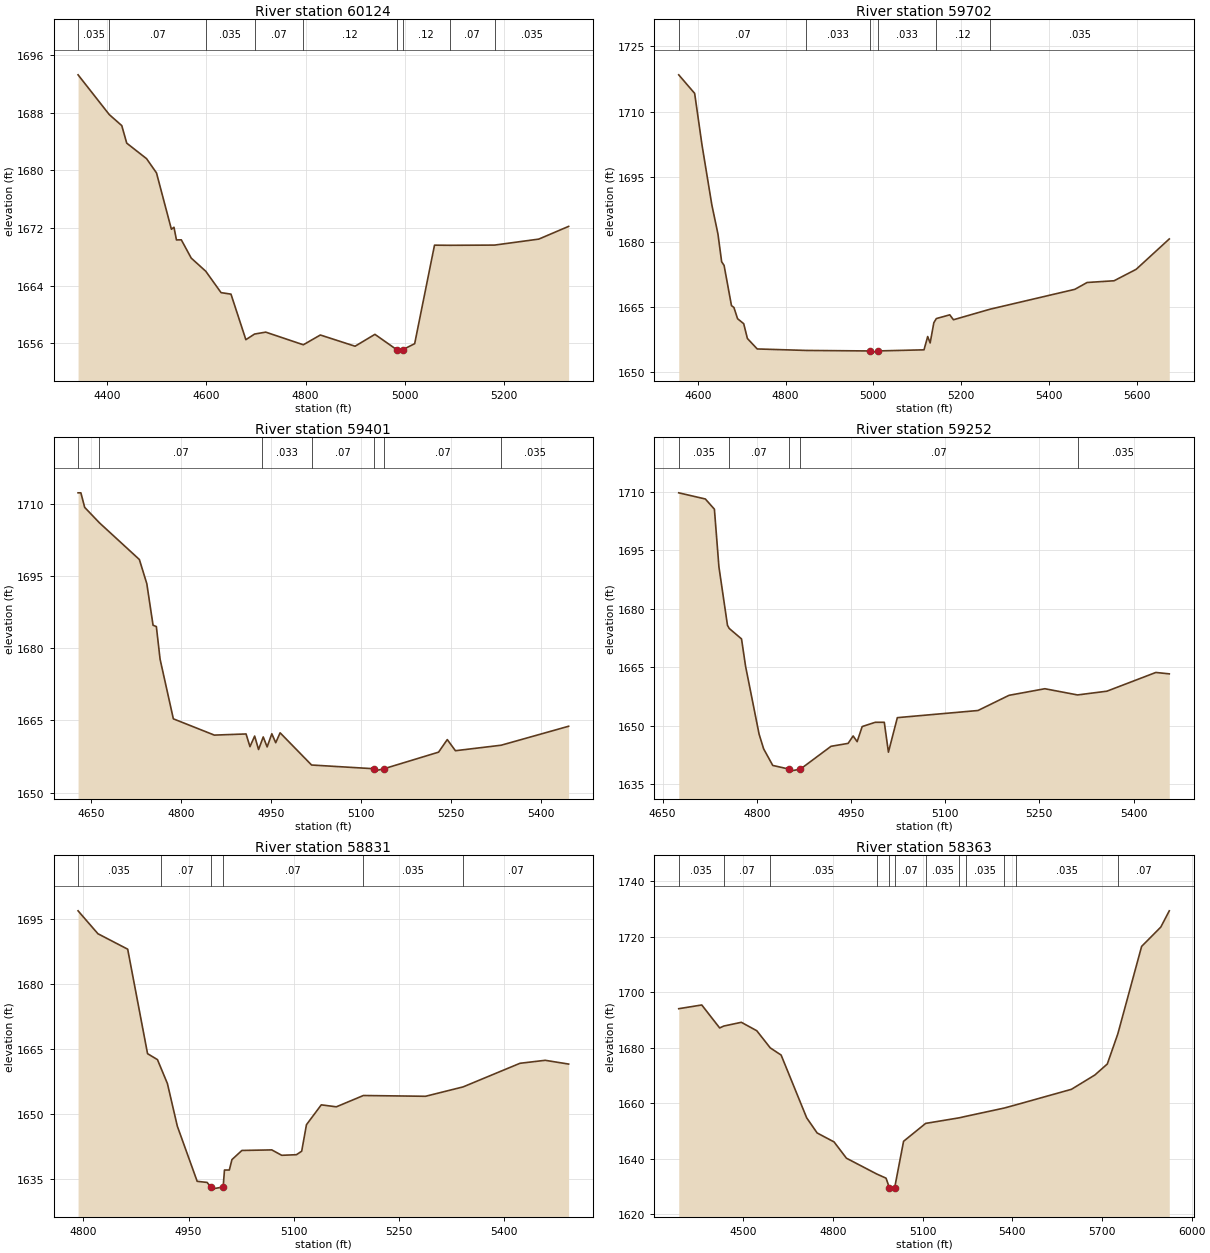
Type RM Length L Ch R = 1 ,60124   ,422,422,422
BEGIN DESCRIPTION:
BLOCK CREEK 110.0
END DESCRIPTION:
XS GIS Cut Line= 3
      2008903.76     13942833.01        2008925.       13942175.
      2008934.35     13941844.79
#Sta/Elev= 30
  4341.6 1693.29  4404.4 1687.77  4429.7 1686.23  4439.7 1683.79  4479.7 1681.63
  4499.7 1679.65  4529.7 1671.82  4534.9  1672.1  4539.9 1670.34  4549.7 1670.35
  4569.7 1667.81    4599 1665.98  4629.8 1663.01  4649.8  1662.8  4679.8 1656.47
  4697.3 1657.25  4719.8 1657.52  4795.6 1655.76  4829.9 1657.12  4899.9 1655.56
  4939.9 1657.21  4983.5  1655.1    4984  1654.6  4996.5  1655.1    5020 1655.91
    5060 1669.61  5090.4 1669.59  5181.1 1669.62  5270.1 1670.45  5330.3 1672.22
#Mann= 9 ,-1 , 0
  4341.6    .035       0  4404.4     .07       0    4599    .035       0
  4697.3     .07       0  4795.6     .12       0  4983.5     .05       0
  4996.5     .12       0  5090.4     .07       0  5181.1    .035       0
Bank Sta=4983.5,4996.5
XS Rating Curve= 0 ,0
Exp/Cntr=0.3,0.1

Type RM Length L Ch R = 1 ,59702   ,301,301,301
BEGIN DESCRIPTION:
BLOCK CREEK 109.0
END DESCRIPTION:
XS GIS Cut Line= 3
      2009424.99     13942724.98        2009225.       13942325.
      2008925.01     13941725.01
#Sta/Elev= 30
  4556.6 1718.46  4592.9 1714.19  4609.7 1702.28    4632 1688.57    4646 1681.83
  4654.4 1675.46    4660  1674.6  4676.8 1665.37  4682.4 1664.93  4690.7 1662.35
  4704.7  1661.2  4713.1  1657.8  4735.5 1655.39  4846.6 1655.05  4992.2 1654.93
  4992.7 1654.43  5009.7 1654.93  5115.6 1655.19    5124 1658.25  5129.6 1656.77
    5138 1661.43  5143.7 1662.38  5174.3 1663.24  5182.7 1662.11  5266.3 1664.54
  5459.4 1669.11  5487.3 1670.68  5548.8 1671.08  5599.1 1673.71  5674.6  1680.7
#Mann= 6 ,-1 , 0
  4556.6     .07       0  4846.6    .033       0  4992.2    .033       0
  5009.7    .033       0  5143.7     .12       0  5266.3    .035       0
Bank Sta=4992.2,5009.7
XS Rating Curve= 0 ,0
Exp/Cntr=0.3,0.1

Type RM Length L Ch R = 1 ,59401   ,149,149,149
BEGIN DESCRIPTION:
BLOCK CREEK 108.5
END DESCRIPTION:
XS GIS Cut Line= 4
      2009685.36     13942668.55      2009575.44     13942435.64
      2009502.17     13942347.83      2009229.49     13941996.04
#Sta/Elev= 30
  4628.3 1712.24    4633 1712.24  4639.3 1709.22  4663.9 1706.01  4730.4 1698.39
  4742.8 1693.37  4753.2 1684.74  4758.7 1684.46  4764.9 1677.68    4787  1665.3
  4855.3 1661.92  4908.1 1662.16  4914.6 1659.52  4922.4 1661.72  4928.9 1658.93
  4934.2  1660.7  4936.7 1661.54  4943.2 1659.47    4951  1662.2  4957.5 1660.34
  4964.8  1662.4  5017.2 1655.71  5120.4 1654.94  5120.9 1654.44  5137.9 1654.94
  5228.7 1658.38  5243.2 1660.99  5256.8 1658.68  5332.9 1659.82  5445.3 1663.76
#Mann= 7 ,-1 , 0
  4628.3    .035       0  4663.9     .07       0  4934.2    .033       0
  5017.2     .07       0  5120.4    .033       0  5137.9     .07       0
  5332.9    .035       0
Bank Sta=5120.4,5137.9
XS Rating Curve= 0 ,0
Exp/Cntr=0.3,0.1

Type RM Length L Ch R = 1 ,59252   ,421,421,421
BEGIN DESCRIPTION:
BLOCK CREEK 108.0
END DESCRIPTION:
XS GIS Cut Line= 3
      2009824.99     13942524.99        2009625.       13942275.
      2009275.01     13941975.01
#Sta/Elev= 30
  4675.8 1709.72  4718.2 1708.14  4732.6 1705.53  4739.8 1690.75  4753.4  1675.8
  4756.1 1674.99  4775.8 1672.29  4782.2 1665.31  4803.8 1647.87    4811 1644.13
  4825.5 1639.88  4851.9 1638.92  4852.4 1638.42  4869.4 1638.92  4918.3 1644.78
  4945.5 1645.53  4953.5 1647.43  4959.9 1645.97  4967.9 1649.84  4988.7 1650.93
  5003.1 1650.93  5009.7 1643.28  5023.9 1652.12  5152.3 1653.95  5201.7 1657.84
  5258.8 1659.53  5310.8 1657.94  5357.6  1658.9  5435.5  1663.7  5456.9 1663.34
#Mann= 5 ,-1 , 0
  4675.8    .035       0  4756.1     .07       0  4851.9     .05       0
  4869.4     .07       0  5310.8    .035       0
Bank Sta=4851.9,4869.4
XS Rating Curve= 0 ,0
Exp/Cntr=0.3,0.1

Type RM Length L Ch R = 1 ,58831   ,468,468,468
BEGIN DESCRIPTION:
BLOCK CREEK 107.0
END DESCRIPTION:
XS GIS Cut Line= 3
      2009974.98     13942224.98        2009825.       13942075.
      2009462.85      13941749.7
#Sta/Elev= 30
  4792.6 1696.83  4820.9 1691.54  4863.3 1687.97  4891.6 1663.84  4905.7 1662.47
  4910.4 1660.64  4919.9 1656.94    4934 1647.11  4962.3 1634.36  4976.4 1634.11
  4981.8 1633.06  4982.3 1632.56  4999.3 1633.06  5001.2 1636.97  5008.1 1636.97
  5011.8 1639.37    5026 1641.49  5068.6 1641.62  5082.8 1640.37  5103.7 1640.51
  5111.2 1641.32    5118 1647.44  5139.1 1652.02  5160.6 1651.57  5199.1 1654.18
  5287.6    1654  5341.2 1656.17  5422.2 1661.62  5458.1 1662.31  5491.5 1661.44
#Mann= 6 ,-1 , 0
  4792.6    .035       0  4910.4     .07       0  4981.8     .05       0
  4999.3     .07       0  5199.1    .035       0  5341.2     .07       0
Bank Sta=4981.8,4999.3
XS Rating Curve= 0 ,0
Exp/Cntr=0.3,0.1

Type RM Length L Ch R = 1 ,58363   ,858,858,858
BEGIN DESCRIPTION:
BLOCK CREEK 106.0
END DESCRIPTION:
XS GIS Cut Line= 3
      2010209.03     13942367.45        2010025.       13941675.
      2009302.75     13941096.59
#Sta/Elev= 30
  4283.3 1694.06  4360.4  1695.4  4420.3 1687.13  4434.1 1687.81  4492.8 1689.16
  4544.5 1686.13  4589.6 1679.96    4626 1677.37  4711.5 1654.78  4746.5 1649.33
  4803.2  1646.1  4844.6 1640.24  4945.3 1634.59  4977.1 1633.06  4988.4 1629.61
  4988.9 1629.11    5006 1629.61  5035.8 1646.33  5109.7 1652.77  5222.2 1654.78
  5243.2 1655.29  5372.8  1658.3  5411.3 1659.43  5597.6 1665.04    5676 1670.19
  5717.7 1674.16    5753 1685.05  5832.5 1716.48  5896.6 1723.43  5925.1 1729.29
#Mann= 12 ,-1 , 0
  4283.3    .035       0  4434.1     .07       0  4589.6    .035       0
  4945.3     .07       0  4988.4     .05       0    5006     .07       0
  5109.7    .035       0  5222.2     .07       0  5243.2    .035       0
  5372.8     .07       0  5411.3    .035       0    5753     .07       0
Bank Sta=4988.4,5006
XS Rating Curve= 0 ,0
Exp/Cntr=0.3,0.1

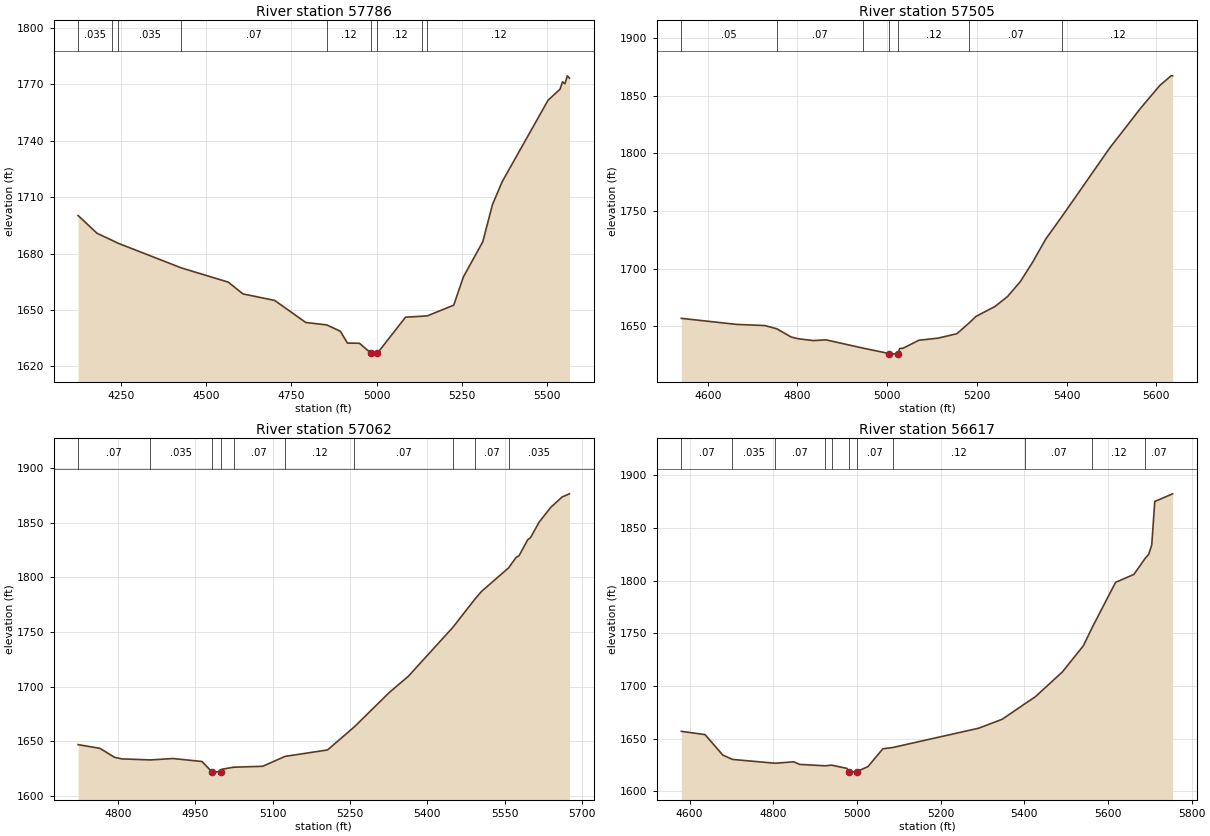
Type RM Length L Ch R = 1 ,57786   ,281,281,281
BEGIN DESCRIPTION:
BLOCK CREEK 105.0
END DESCRIPTION:
XS GIS Cut Line= 3
      2010900.65     13941928.14      2010357.96     13941241.51
      2009979.94     13940821.19
#Sta/Elev= 30
  4124.8  1700.2  4180.2 1690.78  4225.4 1686.92  4242.2 1685.45  4427.9 1672.32
  4564.9  1664.8  4608.2 1658.53  4701.2 1655.06  4792.5 1643.33  4853.9 1642.05
  4893.6  1638.7  4914.4 1632.39  4949.6 1632.29  4983.6 1627.02  4984.1 1626.52
  5002.3 1627.02  5084.7 1646.15  5132.5 1646.66  5148.8 1646.87    5226 1652.54
  5254.4 1667.56  5311.2 1686.24  5339.6 1705.98    5368 1718.14  5502.5 1761.44
  5537.7 1767.35  5545.1 1771.28  5551.9 1770.19  5559.3 1774.45  5565.3 1773.23
#Mann= 9 ,-1 , 0
  4124.8    .035       0  4225.4     .07       0  4242.2    .035       0
  4427.9     .07       0  4853.9     .12       0  4983.6     .05       0
  5002.3     .12       0  5132.5     .07       0  5148.8     .12       0
Bank Sta=4983.6,5002.3
XS Rating Curve= 0 ,0
Exp/Cntr=0.3,0.1

Type RM Length L Ch R = 1 ,57505   ,443,443,443
BEGIN DESCRIPTION:
BLOCK CREEK 104.0
END DESCRIPTION:
XS GIS Cut Line= 3
      2010795.82      13941395.2        2010525.       13941025.
      2010074.98     13940574.98
#Sta/Elev= 30
  4541.1 1656.76  4664.3 1651.51  4727.2  1650.5  4753.9 1647.71  4785.5 1640.65
  4800.2  1639.1  4835.7 1637.45  4863.5  1638.1  4946.9 1630.84  5004.6 1626.19
  5005.1 1625.69  5023.3 1626.19  5028.1 1630.64  5035.1 1630.75  5070.5 1637.75
  5112.9 1639.54  5155.3 1643.41  5182.8 1652.83  5197.8 1658.42  5240.2 1667.06
  5268.5 1675.82  5296.8 1688.74    5325  1706.1  5353.3 1725.61  5390.1 1745.55
  5494.8  1804.1  5565.5  1839.6  5607.9  1859.1  5632.6 1867.36  5636.2 1867.36
#Mann= 7 ,-1 , 0
  4541.1     .05       0  4753.9     .07       0  4946.9     .12       0
  5004.6     .05       0  5023.3     .12       0  5182.8     .07       0
  5390.1     .12       0
Bank Sta=5004.6,5023.3
XS Rating Curve= 0 ,0
Exp/Cntr=0.3,0.1

Type RM Length L Ch R = 1 ,57062   ,445,445,445
BEGIN DESCRIPTION:
BLOCK CREEK 103.0
END DESCRIPTION:
XS GIS Cut Line= 3
      2010974.98     13940874.98        2010775.       13940675.
      2010175.03     13940375.02
#Sta/Elev= 30
  4722.2  1646.9  4764.6 1643.49  4792.9 1635.31    4807 1633.86  4862.2  1632.9
    4906  1634.2  4962.6 1631.47  4981.5 1622.24    4982 1621.74  5000.3 1622.24
  5001.5 1624.37  5023.9 1626.24  5080.5 1627.09  5123.7 1636.12  5206.3 1642.03
  5258.5 1663.24  5326.4 1694.72  5362.8 1709.28  5449.3 1754.08    5493 1780.41
  5505.3 1787.14  5557.8 1808.71  5572.4 1818.22    5578 1819.71  5594.8 1834.35
  5600.4  1836.4  5617.1 1850.57  5639.5 1863.98  5661.9 1873.58  5675.8 1876.37
#Mann= 10 ,-1 , 0
  4722.2     .07       0  4862.2    .035       0  4981.5    .035       0
  5000.3    .035       0  5023.9     .07       0  5123.7     .12       0
  5258.5     .07       0  5449.3     .12       0    5493     .07       0
  5557.8    .035       0
Bank Sta=4981.5,5000.3
XS Rating Curve= 0 ,0
Exp/Cntr=0.3,0.1

Type RM Length L Ch R = 1 ,56617   ,479,479,479
BEGIN DESCRIPTION:
BLOCK CREEK 102.0
END DESCRIPTION:
XS GIS Cut Line= 3
      2011325.03     13940625.03        2011025.       13940325.
      2010575.01     13939725.01
#Sta/Elev= 30
  4580.3 1657.04  4636.9 1653.93  4679.3 1634.61  4702.1 1630.42  4804.3 1626.78
    4849 1628.13  4863.2 1625.68  4924.5 1624.35  4939.5 1624.99  4976.3 1621.88
  4981.1 1618.85  4981.6 1618.35  4999.9 1618.85  5026.5 1623.63  5061.9 1640.46
  5086.4 1641.76  5291.1    1660  5347.3 1668.48  5401.8 1683.24  5426.5 1689.83
  5491.1 1713.36  5541.1  1738.1  5562.6 1755.69  5618.2 1798.24  5661.9 1805.77
  5689.7 1821.44  5697.3  1824.8  5704.6 1833.69  5711.9 1874.94  5754.6 1882.17
#Mann= 11 ,-1 , 0
  4580.3     .07       0  4702.1    .035       0  4804.3     .07       0
  4924.5     .12       0  4939.5     .07       0  4981.1     .05       0
  4999.9     .07       0  5086.4     .12       0  5401.8     .07       0
  5562.6     .12       0  5689.7     .07       0
Bank Sta=4981.1,4999.9
XS Rating Curve= 0 ,0
Exp/Cntr=0.3,0.1