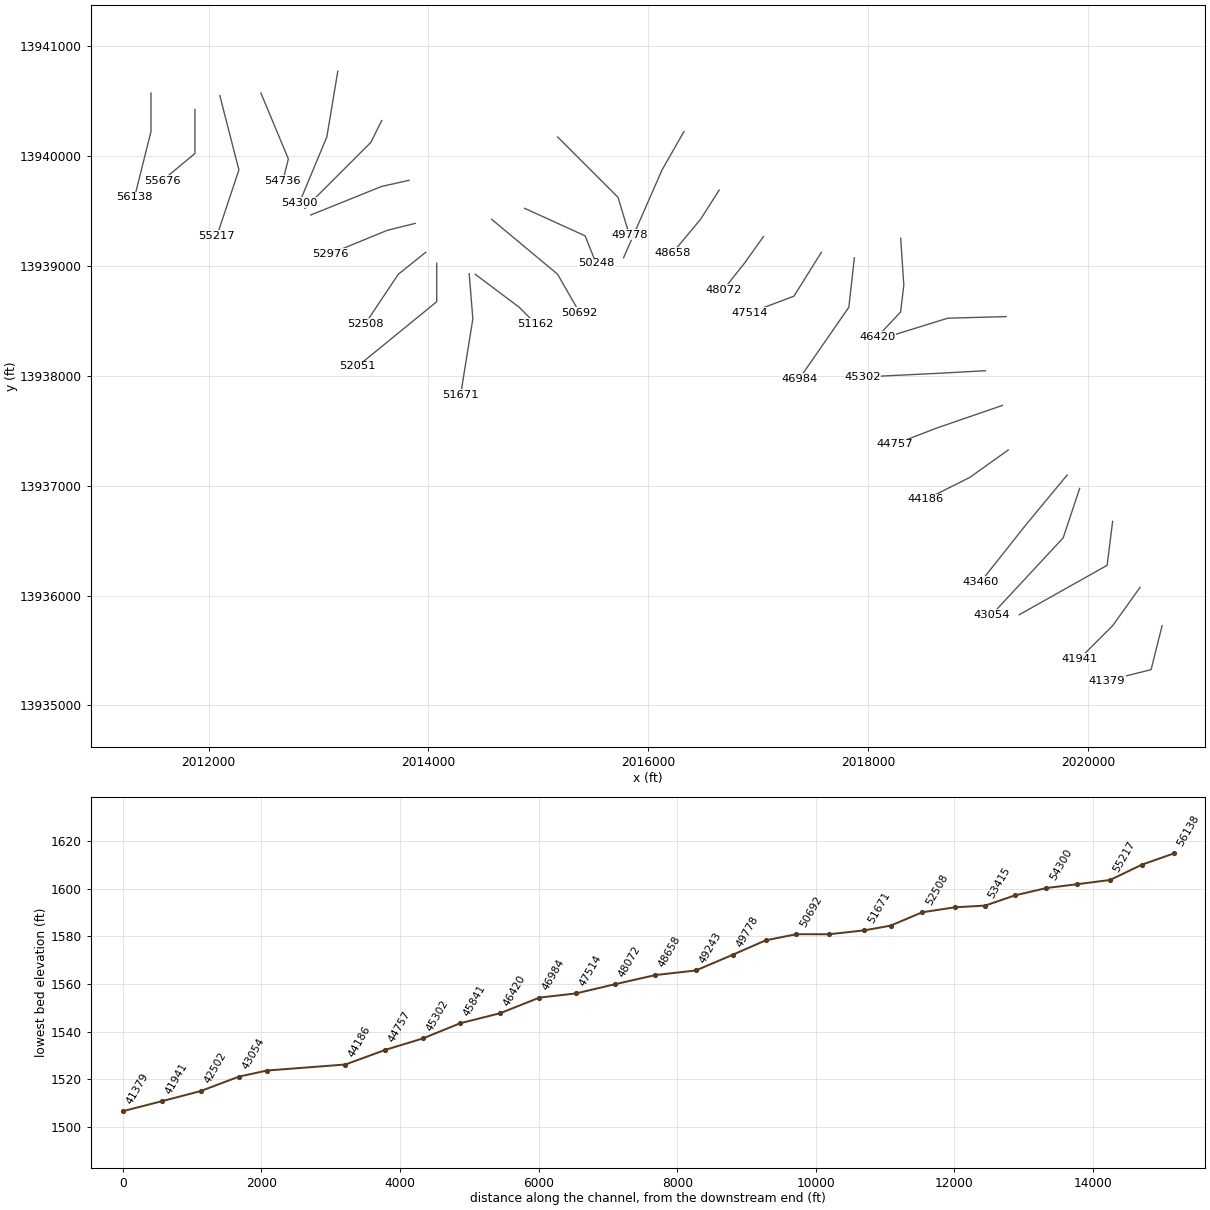
HEC-RAS study BLOCK CREEK.prj: BLOCK CREEK Base Level Engineering

--- BLOCK CREEK.g01 (geometry) --- (continued)

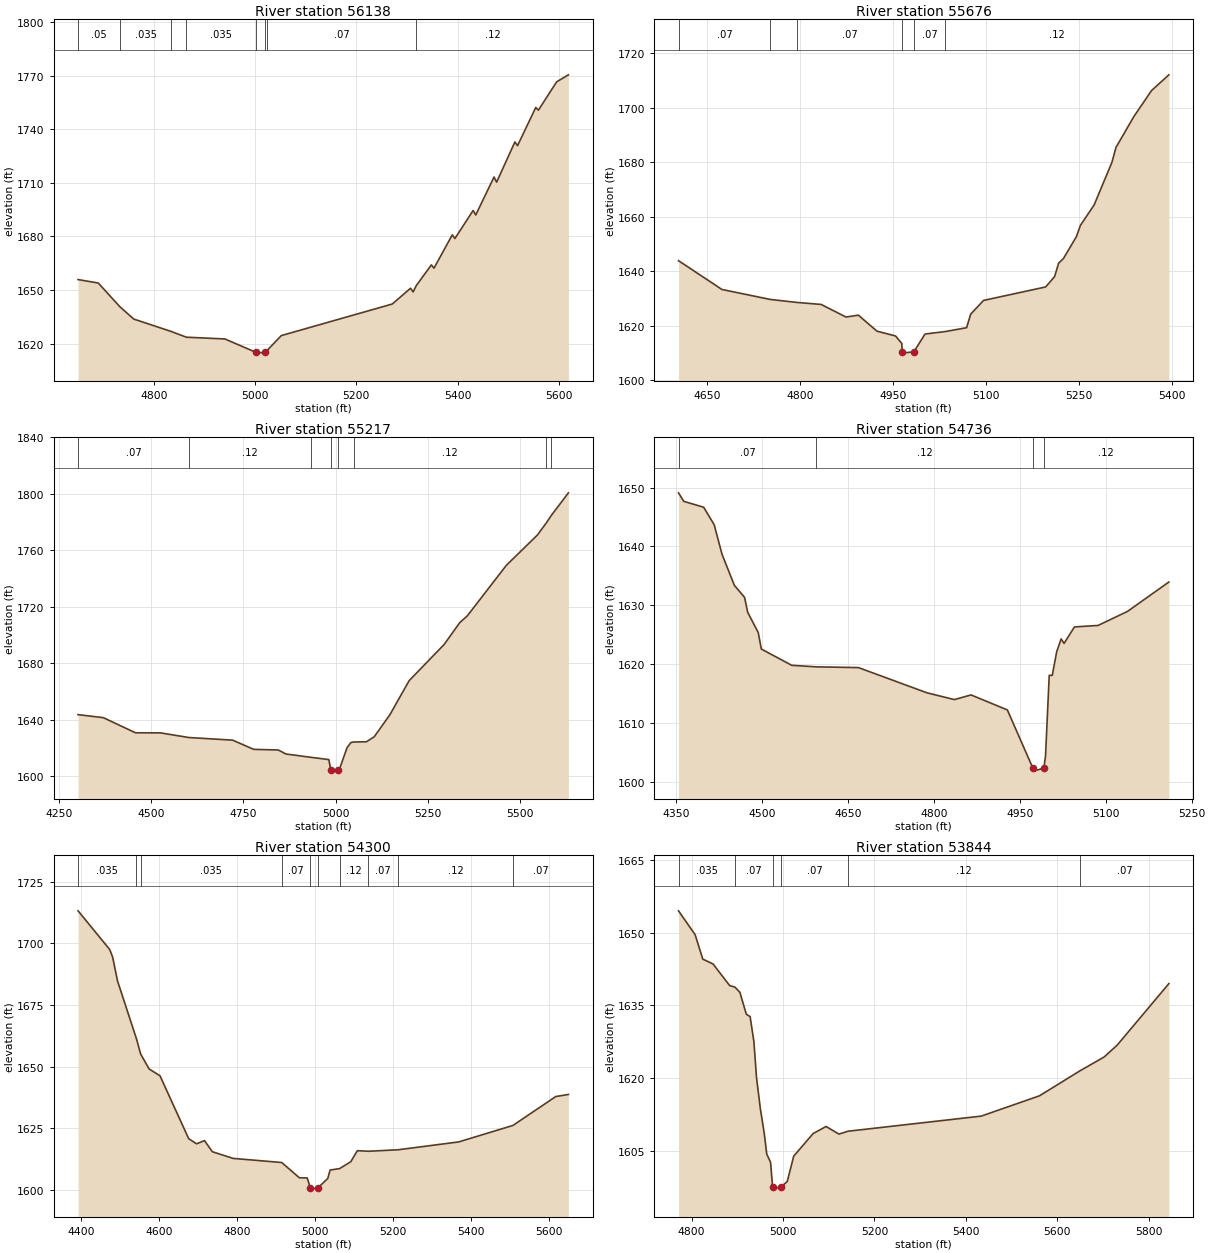
Type RM Length L Ch R = 1 ,56138   ,462,462,462
BEGIN DESCRIPTION:
BLOCK CREEK 101.0
END DESCRIPTION:
XS GIS Cut Line= 3
        2011475.       13940575.        2011475.       13940225.
      2011324.99     13939624.96
#Sta/Elev= 30
  4650.4 1655.88  4690.4 1653.93  4733.1 1640.64  4760.4 1633.78  4834.3 1626.84
  4864.4 1623.63  4940.4 1622.65  5001.3 1615.22  5001.8 1614.72  5020.2 1615.22
  5024.3 1616.38  5051.9 1624.54    5271  1642.2  5307.1 1651.02  5312.2 1648.96
  5318.6 1652.58  5348.3 1664.11  5353.4 1662.26  5389.5  1680.9  5394.7 1678.86
  5430.7 1694.53  5435.9 1692.02    5472 1713.25  5477.1 1710.36  5513.2 1732.88
  5518.4 1730.77  5554.4 1752.17  5559.6 1750.64  5595.7 1766.51  5618.9 1770.43
#Mann= 8 ,-1 , 0
  4650.4     .05       0  4733.1    .035       0  4834.3     .07       0
  4864.4    .035       0  5001.3    .035       0  5020.2    .035       0
  5024.3     .07       0  5318.6     .12       0
Bank Sta=5001.3,5020.2
XS Rating Curve= 0 ,0
Exp/Cntr=0.3,0.1

Type RM Length L Ch R = 1 ,55676   ,459,459,459
BEGIN DESCRIPTION:
BLOCK CREEK 100.0
END DESCRIPTION:
XS GIS Cut Line= 3
        2011875.     13940425.04        2011875.       13940025.
      2011574.96     13939774.97
#Sta/Elev= 30
  4604.5 1643.88  4674.5 1633.32  4752.3 1629.67  4795.3 1628.57  4834.5 1627.83
  4874.5 1623.22  4894.5  1623.9  4924.5 1618.03  4954.5 1616.26  4964.5 1613.53
  4965.1 1610.48  4965.6 1609.98    4984 1610.48    5002 1616.99  5033.8 1617.86
    5069  1619.3  5075.5 1624.26  5096.3  1629.3  5196.5 1634.25  5210.9 1638.06
  5217.4 1642.98  5225.2 1644.69    5246 1652.69  5252.5 1656.83  5274.6 1664.31
  5303.3 1679.95  5309.8 1685.39  5338.4 1696.62  5367.1 1706.24  5395.1 1712.02
#Mann= 6 ,-1 , 0
  4604.5     .07       0  4752.3     .12       0  4795.3     .07       0
  4965.1     .05       0    4984     .07       0  5033.8     .12       0
Bank Sta=4965.1,4984
XS Rating Curve= 0 ,0
Exp/Cntr=0.3,0.1

Type RM Length L Ch R = 1 ,55217   ,481,481,481
BEGIN DESCRIPTION:
BLOCK CREEK 99.0
END DESCRIPTION:
XS GIS Cut Line= 3
       2012101.4     13940551.48        2012275.       13939875.
      2012074.99     13939274.96
#Sta/Elev= 30
  4301.1 1643.57  4369.7 1641.43  4456.9 1630.72  4524.6 1630.66  4602.1 1627.36
  4720.7 1625.51  4777.9 1618.98  4844.6 1618.55  4865.3 1615.71  4934.6  1613.3
  4981.7 1611.74  4987.4 1604.07  4987.9 1603.57  5006.4 1604.07    5010 1604.55
  5031.1 1620.13  5041.7 1623.82  5048.7 1624.19  5083.8 1624.37  5104.9 1627.89
  5147.1 1643.36  5199.8 1667.66  5294.6 1693.23  5336.8 1708.63  5357.9 1713.63
  5463.3 1749.26  5547.6 1770.71  5572.5 1779.53  5584.7 1784.32    5632 1800.66
#Mann= 8 ,-1 , 0
  4301.1     .07       0  4602.1     .12       0  4934.6     .07       0
  4987.4     .05       0  5006.4     .07       0  5048.7     .12       0
  5572.5     .07       0  5584.7     .12       0
Bank Sta=4987.4,5006.4
XS Rating Curve= 0 ,0
Exp/Cntr=0.3,0.1

Type RM Length L Ch R = 1 ,54736   ,436,436,436
BEGIN DESCRIPTION:
BLOCK CREEK 98.0
END DESCRIPTION:
XS GIS Cut Line= 3
      2012474.99     13940575.02        2012725.       13939975.
      2012674.99     13939774.98
#Sta/Elev= 30
  4353.9 1649.12  4363.1 1647.67  4397.8 1646.67  4416.2 1643.69  4429.8 1638.69
  4451.4 1633.39  4469.3 1631.33  4474.7  1628.8  4493.1 1625.35  4498.5 1622.55
  4551.6 1619.78  4594.4 1619.52  4668.1 1619.39  4787.8  1615.1  4835.5 1613.95
  4864.7 1614.74  4928.1 1612.19  4972.7 1602.28  4973.2 1601.78  4991.8 1602.28
  4994.7 1604.29  5001.2 1618.07  5006.5 1618.07  5014.2 1622.08    5022 1624.27
  5027.1  1623.5  5045.2 1626.31  5086.4 1626.56  5137.9 1628.95  5210.1 1633.95
#Mann= 4 ,-1 , 0
  4353.9     .07       0  4594.4     .12       0  4972.7     .05       0
  4991.8     .12       0
Bank Sta=4972.7,4991.8
XS Rating Curve= 0 ,0
Exp/Cntr=0.3,0.1

Type RM Length L Ch R = 1 ,54300   ,456,456,456
BEGIN DESCRIPTION:
BLOCK CREEK 97.0
END DESCRIPTION:
XS GIS Cut Line= 3
      2013174.99     13940774.96        2013075.       13940175.
      2012825.01     13939575.03
#Sta/Elev= 30
  4392.2 1713.23  4473.3 1697.55  4480.9 1694.48  4493.5 1684.73    4542  1661.3
  4552.7  1655.1  4574.6    1649  4602.5 1646.22    4676 1620.71  4696.3  1618.6
  4716.6 1619.91  4736.8 1615.39  4790.1 1612.68  4914.8 1611.01  4959.9 1604.82
  4980.2 1604.74  4988.3  1600.7  4988.8  1600.2  5007.4  1600.7  5032.9 1604.52
  5038.9 1607.95  5063.3 1608.54    5092 1611.33  5108.8 1615.81  5137.1 1615.58
  5213.2 1616.18  5368.8 1619.37    5508 1626.06  5617.9  1637.8  5650.4 1638.65
#Mann= 10 ,-1 , 0
  4392.2    .035       0    4542     .12       0  4552.7    .035       0
  4914.8     .07       0  4988.3     .05       0  5007.4     .07       0
  5063.3     .12       0  5137.1     .07       0  5213.2     .12       0
    5508     .07       0
Bank Sta=4988.3,5007.4
XS Rating Curve= 0 ,0
Exp/Cntr=0.3,0.1

Type RM Length L Ch R = 1 ,53844   ,429,429,429
BEGIN DESCRIPTION:
BLOCK CREEK 96.0
END DESCRIPTION:
XS GIS Cut Line= 3
      2013575.02     13940325.03        2013475.       13940125.
      2012874.98     13939524.98
#Sta/Elev= 30
  4771.6 1654.51    4808 1649.58  4824.7 1644.55  4847.1 1643.55  4883.4  1639.1
    4895 1638.77  4905.8 1637.71  4919.8  1633.2  4928.2 1632.68  4936.5 1627.48
  4942.1 1620.18  4950.5 1613.73  4958.9 1608.73  4964.5 1604.36  4972.9 1602.62
  4977.3 1597.61  4977.8 1597.11  4996.4 1597.61  5009.4 1598.68  5023.5 1603.92
    5066 1608.57  5094.2 1610.03  5122.5 1608.46  5142.2 1609.05  5433.6 1612.17
  5560.9 1616.36  5650.3 1621.56  5702.3 1624.37  5730.6 1626.79  5843.8  1639.5
#Mann= 6 ,-1 , 0
  4771.6    .035       0    4895     .07       0  4977.3     .05       0
  4996.4     .07       0  5142.2     .12       0  5650.3     .07       0
Bank Sta=4977.3,4996.4
XS Rating Curve= 0 ,0
Exp/Cntr=0.3,0.1

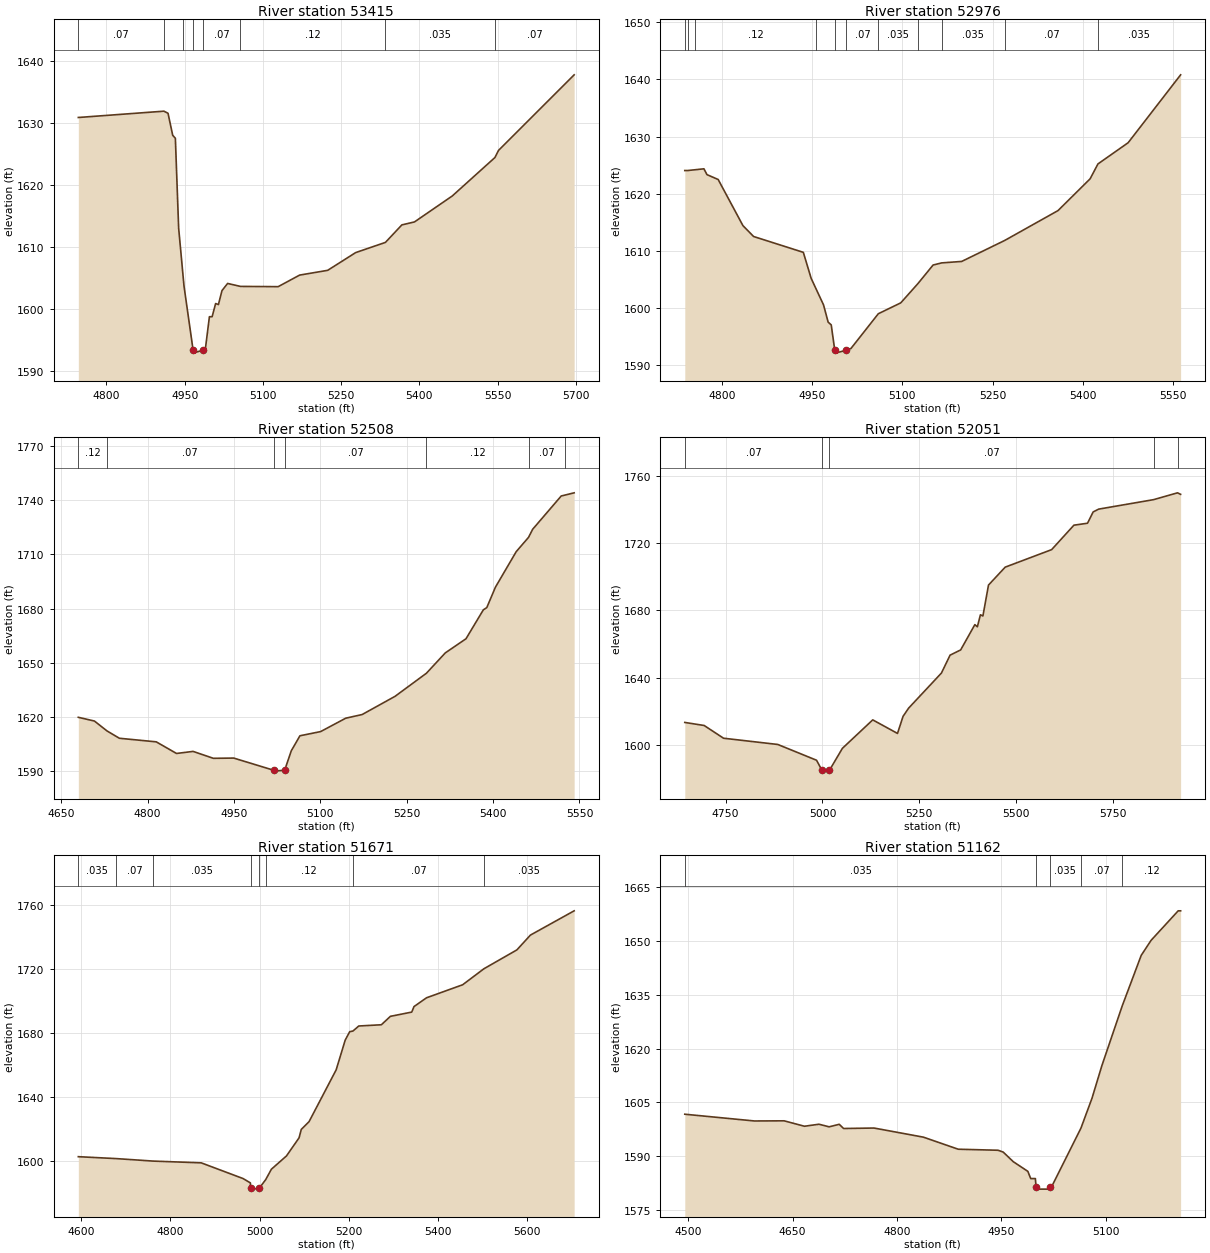
Type RM Length L Ch R = 1 ,53415   ,439,439,439
BEGIN DESCRIPTION:
BLOCK CREEK 95.0
END DESCRIPTION:
XS GIS Cut Line= 3
      2013822.85      13939780.2        2013575.       13939725.
      2012928.51     13939464.56
#Sta/Elev= 30
    4746 1630.94  4910.1 1631.96    4918 1631.63    4927 1628.06  4932.1 1627.58
  4938.4 1613.04  4945.8 1606.29  4948.7 1603.65  4966.1 1593.33  4966.6 1592.83
  4985.2 1593.33  4989.7 1593.55  4997.4 1598.72  5002.6 1598.72  5009.3 1600.85
  5014.7 1600.69  5021.5 1602.94  5032.3  1604.1  5056.9 1603.62  5129.3 1603.58
  5170.4 1605.45  5224.2 1606.22  5277.9 1609.09    5335 1610.74  5366.5 1613.57
  5390.7 1614.05  5463.2 1618.25  5544.9 1624.46  5551.8 1625.61  5696.9 1637.84
#Mann= 8 ,-1 , 0
    4746     .07       0  4910.1     .12       0  4945.8     .07       0
  4966.1     .05       0  4985.2     .07       0  5056.9     .12       0
    5335    .035       0  5544.9     .07       0
Bank Sta=4966.1,4985.2
XS Rating Curve= 0 ,0
Exp/Cntr=0.3,0.1

Type RM Length L Ch R = 1 ,52976   ,468,468,468
BEGIN DESCRIPTION:
BLOCK CREEK 94.0
END DESCRIPTION:
XS GIS Cut Line= 3
      2013878.88     13939388.16        2013625.       13939325.
      2013104.19     13939111.48
#Sta/Elev= 30
  4738.3 1624.05    4743 1624.05  4755.1 1624.18  4770.1 1624.35  4775.2 1623.33
  4793.8 1622.48    4835 1614.41  4852.7 1612.51  4935.4 1609.74  4948.4  1605.2
  4956.8  1603.3    4969 1600.55  4976.7 1597.53  4981.8 1597.05  4987.7 1592.61
  4988.2 1592.11  5006.9 1592.61  5014.6 1592.92  5060.1    1599  5097.4  1600.9
  5125.8 1604.25  5151.2 1607.52  5165.3 1607.89  5198.8 1608.15  5270.5 1611.83
  5358.9 1617.04  5412.3  1622.6  5425.3  1625.2  5475.5 1628.91  5562.8 1640.79
#Mann= 11 ,-1 , 0
  4738.3     .12       0    4743     .07       0  4755.1     .12       0
  4956.8     .07       0  4987.7     .05       0  5006.9     .07       0
  5060.1    .035       0  5125.8     .07       0  5165.3    .035       0
  5270.5     .07       0  5425.3    .035       0
Bank Sta=4987.7,5006.9
XS Rating Curve= 0 ,0
Exp/Cntr=0.3,0.1

Type RM Length L Ch R = 1 ,52508   ,457,457,457
BEGIN DESCRIPTION:
BLOCK CREEK 93.0
END DESCRIPTION:
XS GIS Cut Line= 3
      2013975.01     13939125.01        2013725.       13938925.
        2013425.     13938475.01
#Sta/Elev= 30
  4679.8 1619.83  4707.8 1617.76  4729.6 1612.28  4751.1 1608.23  4815.1 1606.24
  4850.3 1599.81  4879.1 1600.95  4914.3 1597.12  4949.6 1597.26  5018.9 1590.53
  5019.4 1590.03  5038.1 1590.53  5049.6 1601.29  5064.6  1609.6  5100.6 1611.93
  5144.2 1619.34  5172.7 1621.37  5229.8 1631.45  5284.3 1644.24    5317 1655.49
    5353 1663.33  5383.1 1679.34  5389.1 1680.58  5404.1 1691.89  5440.2 1711.56
  5461.6 1719.48  5468.7 1723.93  5518.3 1742.37    5525 1742.89  5540.8 1744.13
#Mann= 7 ,-1 , 0
  4679.8     .12       0  4729.6     .07       0  5018.9     .05       0
  5038.1     .07       0  5284.3     .12       0  5461.6     .07       0
    5525     .12       0
Bank Sta=5018.9,5038.1
XS Rating Curve= 0 ,0
Exp/Cntr=0.3,0.1

Type RM Length L Ch R = 1 ,52051   ,380,380,380
BEGIN DESCRIPTION:
BLOCK CREEK 92.0
END DESCRIPTION:
XS GIS Cut Line= 3
        2014075.     13939024.99        2014075.       13938675.
      2013354.76     13938087.43
#Sta/Elev= 30
  4644.7 1613.37  4694.7 1611.55  4744.7 1603.98  4884.7 1600.27  4984.7 1590.89
  4998.7 1584.92  4999.2 1584.42    5018 1584.92  5051.4 1597.97  5129.7 1614.89
  5193.6 1606.84  5207.9 1616.97  5222.3 1621.87    5307 1642.75  5329.3 1653.38
  5356.6 1656.48  5393.2 1671.51  5399.7 1670.23  5407.6 1677.36    5414 1676.65
  5428.4 1695.03  5471.5 1705.69  5591.4 1716.11  5648.8 1730.64    5684 1731.81
  5698.4 1738.51  5712.7 1740.19  5854.4 1745.82  5916.2 1749.88  5924.2 1748.98
#Mann= 5 ,-1 , 0
  4644.7     .07       0  4998.7     .05       0    5018     .07       0
  5854.4    .035       0  5916.2     .07       0
Bank Sta=4998.7,5018
XS Rating Curve= 0 ,0
Exp/Cntr=0.3,0.1

Type RM Length L Ch R = 1 ,51671   ,509,509,509
BEGIN DESCRIPTION:
BLOCK CREEK 91.0
END DESCRIPTION:
XS GIS Cut Line= 3
      2014370.46     13938929.59      2014403.56     13938518.84
      2014292.61     13937828.27
#Sta/Elev= 30
  4593.8 1602.69  4678.7 1601.49  4761.5 1599.94  4869.3 1598.84  4963.1 1589.04
  4979.6 1586.31    4980 1582.94  4980.5 1582.44  4999.3 1582.94    5014 1588.45
  5026.6 1594.87  5060.4 1603.16  5088.6 1614.45  5093.6 1619.71    5111 1624.53
  5171.8  1656.9  5192.1 1675.47  5202.2 1680.72  5209.3 1681.09  5222.5 1684.25
  5273.1 1685.02  5293.4 1690.28  5341.2 1692.93  5346.3 1696.37  5374.4 1701.86
  5455.4 1709.99  5502.9 1719.95  5576.9 1731.74  5607.3 1740.99  5705.3 1756.13
#Mann= 8 ,-1 , 0
  4593.8    .035       0  4678.7     .07       0  4761.5    .035       0
    4980    .035       0  4999.3    .035       0    5014     .12       0
  5209.3     .07       0  5502.9    .035       0
Bank Sta=4980,4999.3
XS Rating Curve= 0 ,0
Exp/Cntr=0.3,0.1

Type RM Length L Ch R = 1 ,51162   ,470,470,470
BEGIN DESCRIPTION:
BLOCK CREEK 90.0
END DESCRIPTION:
XS GIS Cut Line= 3
      2014425.02     13938924.98        2014825.       13938625.
        2014975.       13938475.
#Sta/Elev= 30
  4495.2 1601.69  4595.2 1599.81  4637.9 1599.85    4667 1598.34  4687.9  1598.9
  4702.5 1598.18    4717 1598.88  4723.3 1597.71    4767 1597.84  4837.9  1595.3
  4887.9 1591.94  4945.2 1591.65  4952.5 1591.14    4967 1588.46  4987.9 1585.77
    4992 1583.76  4998.7 1583.76  4999.7 1581.32  5000.2 1580.82  5018.5 1580.82
    5019 1581.32  5023.5 1582.06  5064.1 1597.79    5080 1606.13  5094.2 1615.22
  5123.3  1631.8  5150.7 1645.95  5164.9 1650.14  5203.8 1658.36  5207.3 1658.36
#Mann= 5 ,-1 , 0
  4495.2    .035       0  4999.7    .035       0    5019    .035       0
  5064.1     .07       0  5123.3     .12       0
Bank Sta=4999.7,5019
XS Rating Curve= 0 ,0
Exp/Cntr=0.3,0.1

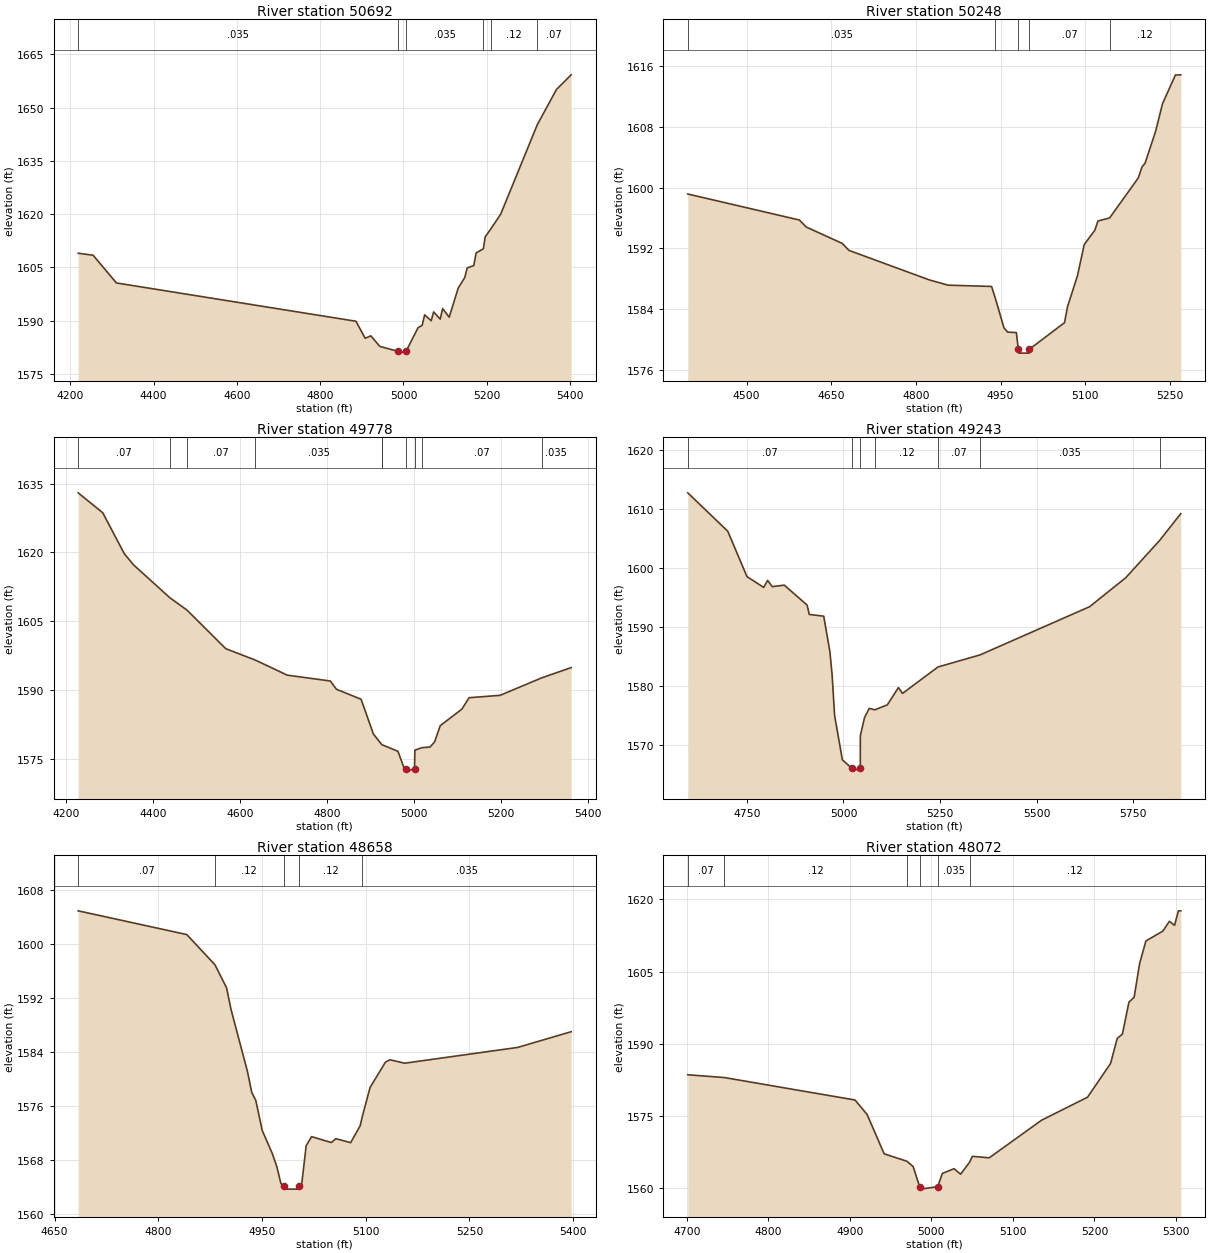
Type RM Length L Ch R = 1 ,50692   ,444,444,444
BEGIN DESCRIPTION:
BLOCK CREEK 89.0
END DESCRIPTION:
XS GIS Cut Line= 3
      2014574.97     13939425.02        2015175.       13938925.
      2015375.01     13938574.98
#Sta/Elev= 30
  4218.7 1608.97  4254.5 1608.42  4310.5  1600.6  4885.9 1589.81    4908 1585.02
  4921.7  1585.7  4943.1 1582.74  4986.8 1581.33  4987.3 1580.83  5006.2 1581.33
    5035 1587.97  5045.1 1588.69  5050.9 1591.61  5066.7 1589.95  5072.5 1592.44
  5088.3 1590.42  5094.1 1593.37  5109.9 1590.96  5131.5 1599.13  5147.3 1602.13
  5153.1 1604.83  5168.9  1605.5  5174.7 1609.07    5192 1610.22  5196.3 1613.57
    5210 1615.84  5233.7    1620  5321.3 1645.12  5367.6 1655.11  5402.9 1659.23
#Mann= 6 ,-1 , 0
  4218.7    .035       0  4986.8    .035       0  5006.2    .035       0
    5192     .07       0    5210     .12       0  5321.3     .07       0
Bank Sta=4986.8,5006.2
XS Rating Curve= 0 ,0
Exp/Cntr=0.3,0.1

Type RM Length L Ch R = 1 ,50248   ,470,470,470
BEGIN DESCRIPTION:
BLOCK CREEK 88.0
END DESCRIPTION:
XS GIS Cut Line= 3
      2014874.96     13939525.02        2015425.       13939275.
      2015525.02     13939024.96
#Sta/Elev= 30
  4395.8 1599.16  4593.6 1595.74  4605.7 1594.82  4669.4 1592.67  4681.4 1591.75
  4824.2 1587.86  4857.2 1587.18  4934.1 1587.01    4941 1585.39  4956.1 1581.56
  4962.7 1581.01    4978 1580.95  4981.5 1578.75    4982 1578.25  5000.4 1578.25
  5000.9 1578.75  5063.3 1582.25  5068.7 1584.36  5086.2  1588.4  5098.3 1592.53
  5117.1  1594.4  5122.5 1595.61  5143.2 1596.01  5193.9 1601.26  5200.6 1602.71
    5206  1603.2  5224.8 1607.41  5236.9 1611.01  5259.8  1614.8  5269.3 1614.82
#Mann= 5 ,-1 , 0
  4395.8    .035       0    4941     .07       0  4981.5     .05       0
  5000.9     .07       0  5143.2     .12       0
Bank Sta=4981.5,5000.9
XS Rating Curve= 0 ,0
Exp/Cntr=0.3,0.1

Type RM Length L Ch R = 1 ,49778   ,535,535,535
BEGIN DESCRIPTION:
BLOCK CREEK 87.0
END DESCRIPTION:
XS GIS Cut Line= 3
      2015175.03     13940174.97        2015725.       13939625.
      2015827.09     13939284.13
#Sta/Elev= 30
    4227 1632.99  4283.5 1628.64    4333 1619.71  4354.2 1617.28  4437.8 1610.09
  4477.2  1607.4  4566.4 1598.98  4634.4 1596.49  4707.8  1593.2  4806.8 1591.93
  4820.9 1590.12  4877.5 1587.95  4905.8 1580.36  4925.4 1578.01  4926.4 1577.99
  4962.3 1576.58  4976.5 1572.91  4980.9 1572.76  4981.4 1572.26  5000.4 1572.76
  5001.2 1576.83  5017.2 1577.37  5036.1 1577.52  5046.5 1578.62  5059.6 1582.19
  5109.2 1585.78  5125.8 1588.28  5197.2  1588.8  5292.8 1592.61  5360.6 1594.85
#Mann= 10 ,-1 , 0
    4227     .07       0  4437.8    .035       0  4477.2     .07       0
  4634.4    .035       0  4925.4     .07       0  4926.4    .035       0
  4980.9    .035       0  5000.4    .035       0  5017.2     .07       0
  5292.8    .035       0
Bank Sta=4980.9,5000.4
XS Rating Curve= 0 ,0
Exp/Cntr=0.3,0.1

Type RM Length L Ch R = 1 ,49243   ,585,585,585
BEGIN DESCRIPTION:
BLOCK CREEK 86.0
END DESCRIPTION:
XS GIS Cut Line= 3
      2016324.99     13940224.99        2016125.       13939875.
        2015775.     13939075.01
#Sta/Elev= 30
  4596.9 1612.69  4700.5 1606.19  4750.2 1598.52  4793.4  1596.7  4803.5 1597.88
  4815.7 1596.83  4846.7 1597.08  4905.7 1593.72  4911.5 1592.13  4948.9 1591.83
  4964.7 1585.88  4970.5 1581.97    4977 1575.07  4997.1 1567.54  5021.3 1566.13
  5021.8 1565.63  5043.5 1566.13  5043.7 1571.62  5054.6 1574.71  5066.7 1576.24
  5081.2    1576  5113.4 1576.83  5142.3 1579.76  5152.8 1578.77  5244.6 1583.24
  5353.4 1585.28  5637.4 1593.44  5730.9 1598.34  5818.4 1604.63  5873.2 1609.17
#Mann= 7 ,-1 , 0
  4596.9     .07       0  5021.3     .05       0  5043.5     .07       0
  5081.2     .12       0  5244.6     .07       0  5353.4    .035       0
  5818.4     .07       0
Bank Sta=5021.3,5043.5
XS Rating Curve= 0 ,0
Exp/Cntr=0.3,0.1

Type RM Length L Ch R = 1 ,48658   ,586,586,586
BEGIN DESCRIPTION:
BLOCK CREEK 85.0
END DESCRIPTION:
XS GIS Cut Line= 3
      2016645.26     13939691.34        2016475.       13939425.
      2016221.22     13939119.72
#Sta/Elev= 30
  4684.1 1604.96  4841.2 1601.44  4881.9 1596.97  4898.7 1593.55  4905.3 1590.29
    4929 1581.12  4935.1 1578.05    4941 1576.86  4950.3  1572.4  4964.6 1569.05
  4971.4 1567.05  4977.4 1564.51  4981.5  1564.2    4982  1563.7  5003.2  1563.7
  5003.7  1564.2  5007.4 1564.44  5013.9 1570.14  5021.7 1571.48  5050.3 1570.61
  5056.8 1571.18  5078.2 1570.59    5092  1573.1  5095.1 1574.47  5106.3 1578.77
  5128.5 1582.52    5135 1582.88  5156.3 1582.37  5319.9 1584.71  5397.2 1587.04
#Mann= 5 ,-1 , 0
  4684.1     .07       0  4881.9     .12       0  4981.5     .05       0
  5003.7     .12       0  5095.1    .035       0
Bank Sta=4981.5,5003.7
XS Rating Curve= 0 ,0
Exp/Cntr=0.3,0.1

Type RM Length L Ch R = 1 ,48072   ,558,558,558
BEGIN DESCRIPTION:
BLOCK CREEK 84.0
END DESCRIPTION:
XS GIS Cut Line= 3
      2017048.22     13939268.42        2016875.       13939025.
      2016684.12     13938785.53
#Sta/Elev= 30
    4701 1583.57  4745.9 1582.99  4906.3 1578.33  4921.1 1575.32    4942 1567.16
  4969.9 1565.62  4977.6 1564.52  4985.5 1560.33    4986 1559.83  5007.8 1560.33
  5013.4 1563.09  5027.8 1564.07  5035.8 1562.93    5047 1565.45  5050.2 1566.64
    5071 1566.33  5135.1 1574.13  5191.6 1578.91  5219.9 1585.93    5228  1591.1
  5234.4 1592.02  5242.4 1598.64  5248.8 1599.67  5255.5 1606.65  5263.2 1611.34
    5284 1613.39    5292 1615.42  5298.4  1614.6  5303.1  1617.6    5306  1617.6
#Mann= 6 ,-1 , 0
    4701     .07       0  4745.9     .12       0  4969.9    .035       0
  4985.5    .035       0  5007.8    .035       0    5047     .12       0
Bank Sta=4985.5,5007.8
XS Rating Curve= 0 ,0
Exp/Cntr=0.3,0.1

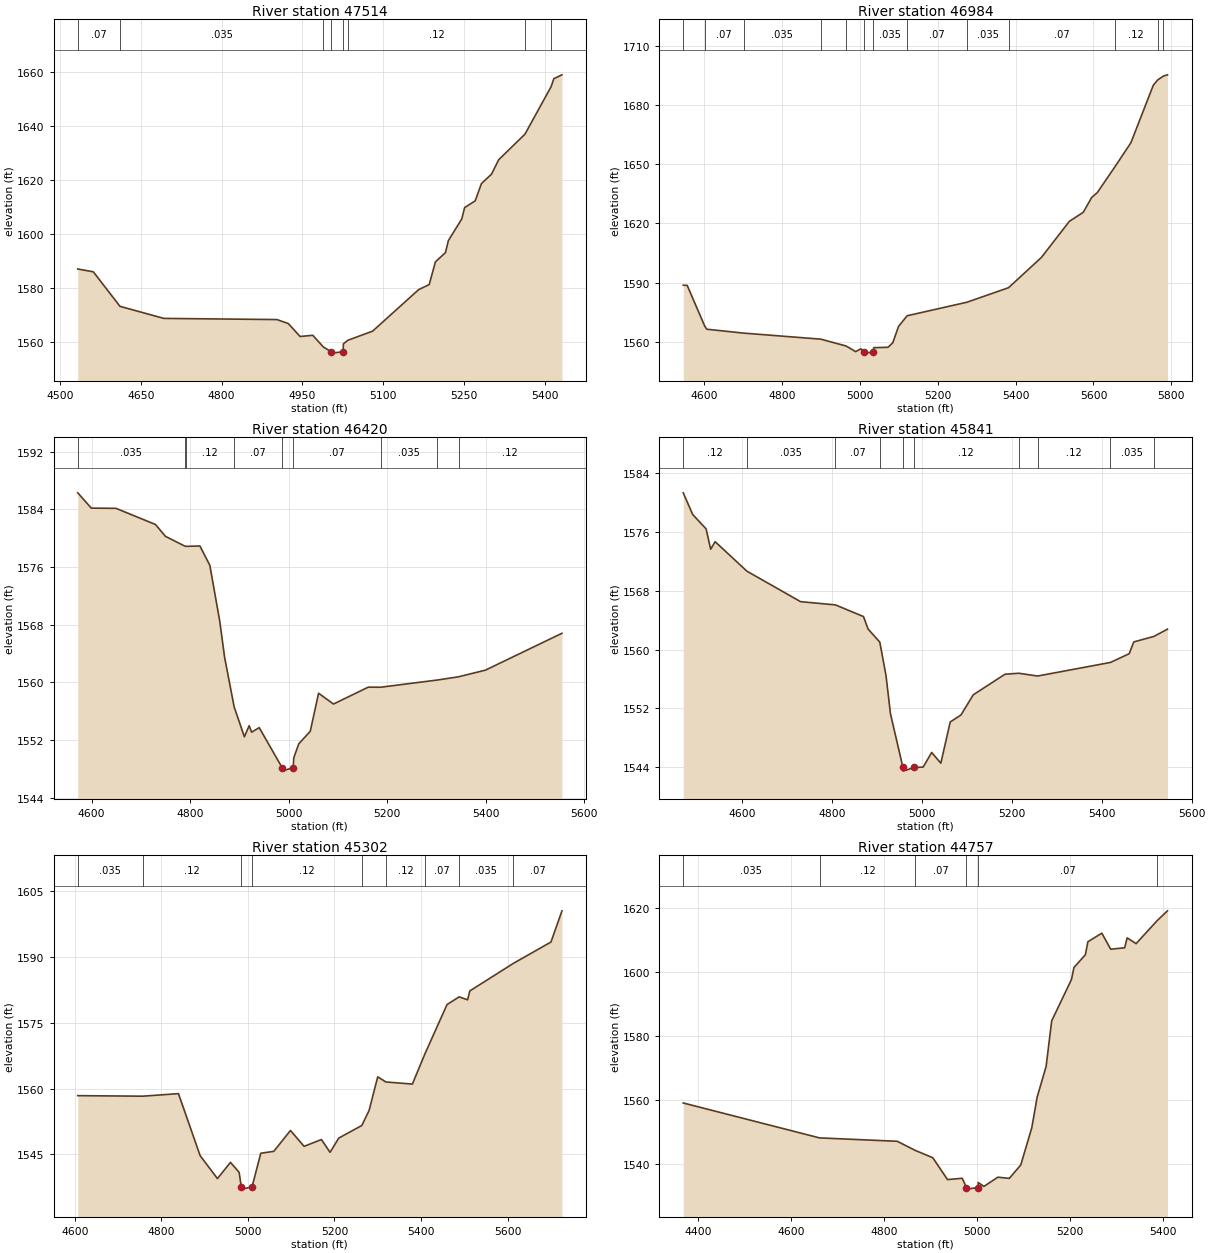
Type RM Length L Ch R = 1 ,47514   ,530,530,530
BEGIN DESCRIPTION:
BLOCK CREEK 83.0
END DESCRIPTION:
XS GIS Cut Line= 3
      2017575.01     13939125.01        2017325.       13938725.
      2016925.01     13938575.01
#Sta/Elev= 30
  4532.9 1587.16  4561.8 1586.12  4611.3 1573.33  4692.7 1568.86  4902.6 1568.43
  4923.8 1566.95  4945.7 1562.16  4969.2  1562.6  4988.8 1558.29  5003.3  1556.5
  5003.8    1556  5025.6  1556.5    5026 1559.43  5034.4 1560.77  5080.3 1564.14
  5165.7 1579.51  5185.3 1581.39  5196.9 1589.81  5215.5 1593.23  5220.9 1597.67
  5245.8  1605.7  5251.1  1609.9  5270.7 1612.39  5282.3 1618.79    5301 1622.28
  5314.3 1627.61  5363.1  1637.1  5411.6 1654.67  5416.7 1657.64  5431.8 1659.07
#Mann= 8 ,-1 , 0
  4532.9     .07       0  4611.3    .035       0  4988.8     .07       0
  5003.3     .05       0  5025.6     .07       0  5034.4     .12       0
  5363.1     .07       0  5411.6    .035       0
Bank Sta=5003.3,5025.6
XS Rating Curve= 0 ,0
Exp/Cntr=0.3,0.1

Type RM Length L Ch R = 1 ,46984   ,564,564,564
BEGIN DESCRIPTION:
BLOCK CREEK 82.0
END DESCRIPTION:
XS GIS Cut Line= 3
        2017875.     13939075.04        2017825.       13938625.
      2017374.99     13937974.98
#Sta/Elev= 30
  4546.7 1588.62  4556.8 1588.54  4602.1 1567.82  4607.1 1566.35  4701.4 1564.38
    4900 1561.31  4964.8 1557.85  4989.5 1554.99  5002.6 1556.44  5010.6 1554.74
  5011.1 1554.24    5033 1554.74    5036 1557.01  5072.5  1557.2  5084.7 1559.48
  5099.5 1567.76  5121.5 1573.16  5275.1 1580.01    5382 1587.37  5466.4  1602.7
    5538 1620.95  5573.9 1625.56  5595.5 1633.08  5609.7 1635.47  5654.1  1648.3
  5696.2 1660.78  5753.6 1689.85  5764.8 1692.55  5779.8 1694.57  5790.1 1695.17
#Mann= 13 ,-1 , 0
  4546.7     .12       0  4602.1     .07       0  4701.4    .035       0
    4900     .12       0  4964.8    .035       0  5010.6    .035       0
    5033    .035       0  5121.5     .07       0  5275.1    .035       0
    5382     .07       0  5654.1     .12       0  5764.8     .07       0
  5779.8     .12       0
Bank Sta=5010.6,5033
XS Rating Curve= 0 ,0
Exp/Cntr=0.3,0.1

Type RM Length L Ch R = 1 ,46420   ,579,579,579
BEGIN DESCRIPTION:
BLOCK CREEK 81.0
END DESCRIPTION:
XS GIS Cut Line= 4
      2018296.73     13939252.47        2018325.       13938825.
      2018295.49     13938580.57      2018084.09     13938356.32
#Sta/Elev= 30
    4572 1586.29  4599.5 1584.17  4649.6 1584.14  4729.8  1581.9  4749.9 1580.26
  4789.1 1578.91  4791.2 1578.87    4820 1578.92  4840.1 1576.24  4860.1 1568.55
  4870.1 1563.48  4889.5  1556.6  4910.2 1552.47  4919.9 1554.01  4924.9 1553.11
  4940.3 1553.74  4986.7 1548.21  4987.2 1547.71  5009.2 1548.21  5010.5 1549.56
  5020.6  1551.5  5043.9 1553.23  5060.8 1558.51  5091.1 1557.01  5161.6 1559.35
  5186.6 1559.34  5301.9 1560.34  5345.1 1560.79  5399.5 1561.71  5554.8 1566.82
#Mann= 9 ,-1 , 0
    4572    .035       0  4789.1     .07       0  4791.2     .12       0
  4889.5     .07       0  4986.7     .05       0  5009.2     .07       0
  5186.6    .035       0  5301.9     .07       0  5345.1     .12       0
Bank Sta=4986.7,5009.2
XS Rating Curve= 0 ,0
Exp/Cntr=0.3,0.1

Type RM Length L Ch R = 1 ,45841   ,539,539,539
BEGIN DESCRIPTION:
BLOCK CREEK 80.0
END DESCRIPTION:
XS GIS Cut Line= 3
      2019255.88     13938539.47        2018725.       13938525.
      2018203.33     13938363.41
#Sta/Elev= 30
    4469 1581.34  4489.9  1578.4  4519.9 1576.43  4529.9 1573.66  4539.9 1574.69
  4610.6 1570.68    4730 1566.53  4807.6 1566.09    4870  1564.5    4880 1562.82
  4906.2 1561.03    4920 1556.49    4930 1551.26  4957.7 1543.97  4958.2 1543.47
  4982.4 1543.97  5002.7 1544.02  5021.6 1546.01    5042 1544.55  5062.9 1550.16
  5086.8 1551.11  5114.2 1553.86  5184.6 1556.65  5215.1 1556.79  5257.2 1556.41
  5419.4 1558.26  5461.1 1559.45  5471.2 1561.05    5516  1561.8  5546.2 1562.79
#Mann= 10 ,-1 , 0
    4469     .12       0  4610.6    .035       0  4807.6     .07       0
  4906.2     .12       0  4957.7     .05       0  4982.4     .12       0
  5215.1    .035       0  5257.2     .12       0  5419.4    .035       0
    5516     .12       0
Bank Sta=4957.7,4982.4
XS Rating Curve= 0 ,0
Exp/Cntr=0.3,0.1

Type RM Length L Ch R = 1 ,45302   ,545,545,545
BEGIN DESCRIPTION:
BLOCK CREEK 79.0
END DESCRIPTION:
XS GIS Cut Line= 3
      2019067.44      13938046.6        2018675.       13938025.
       2017949.6     13937989.44
#Sta/Elev= 30
  4606.6  1558.4  4756.9 1558.28  4839.4 1558.86  4889.5 1544.73  4929.5  1539.5
  4959.6  1543.2  4979.6 1540.94  4984.7  1537.6  4985.2  1537.1  5009.5  1537.6
  5029.7 1545.28  5059.7 1545.71  5098.3 1550.46  5129.8 1546.85  5169.8  1548.4
  5189.9 1545.49  5209.9 1548.73  5263.2  1551.6    5280 1555.01    5300 1562.69
  5318.8 1561.52  5380.1 1561.04  5409.1 1567.92  5460.2 1579.16  5488.2 1580.91
  5507.8 1580.24  5512.8 1582.26  5613.8 1588.56  5700.5 1593.41  5725.9 1600.52
#Mann= 9 ,-1 , 0
  4606.6    .035       0  4756.9     .12       0  4984.7     .05       0
  5009.5     .12       0  5263.2     .07       0  5318.8     .12       0
  5409.1     .07       0  5488.2    .035       0  5613.8     .07       0
Bank Sta=4984.7,5009.5
XS Rating Curve= 0 ,0
Exp/Cntr=0.3,0.1

Type RM Length L Ch R = 1 ,44757   ,571,571,571
BEGIN DESCRIPTION:
BLOCK CREEK 78.0
END DESCRIPTION:
XS GIS Cut Line= 3
      2019222.71     13937730.86        2018625.       13937525.
      2018242.55     13937377.41
#Sta/Elev= 30
  4367.4 1559.19  4660.7 1548.28  4827.9 1547.22    4867 1544.35  4904.4 1542.08
  4936.1 1535.25  4967.8 1535.66  4976.8 1532.77  4977.3 1532.27  5001.7 1532.77
  5002.2 1534.34  5014.5 1533.12  5044.5    1536  5069.1 1535.63  5093.7 1539.81
  5117.5 1551.45    5129    1561  5148.3 1570.61  5160.3 1584.85  5202.9 1597.79
  5208.2 1601.53  5232.8 1605.51  5238.2 1609.58  5268.2 1612.25  5287.4 1607.24
  5317.4  1607.7  5322.7  1610.8    5342 1608.99  5387.5 1616.21  5409.5 1619.24
#Mann= 6 ,-1 , 0
  4367.4    .035       0  4660.7     .12       0    4867     .07       0
  4976.8     .05       0  5001.7     .07       0  5387.5     .12       0
Bank Sta=4976.8,5001.7
XS Rating Curve= 0 ,0
Exp/Cntr=0.3,0.1

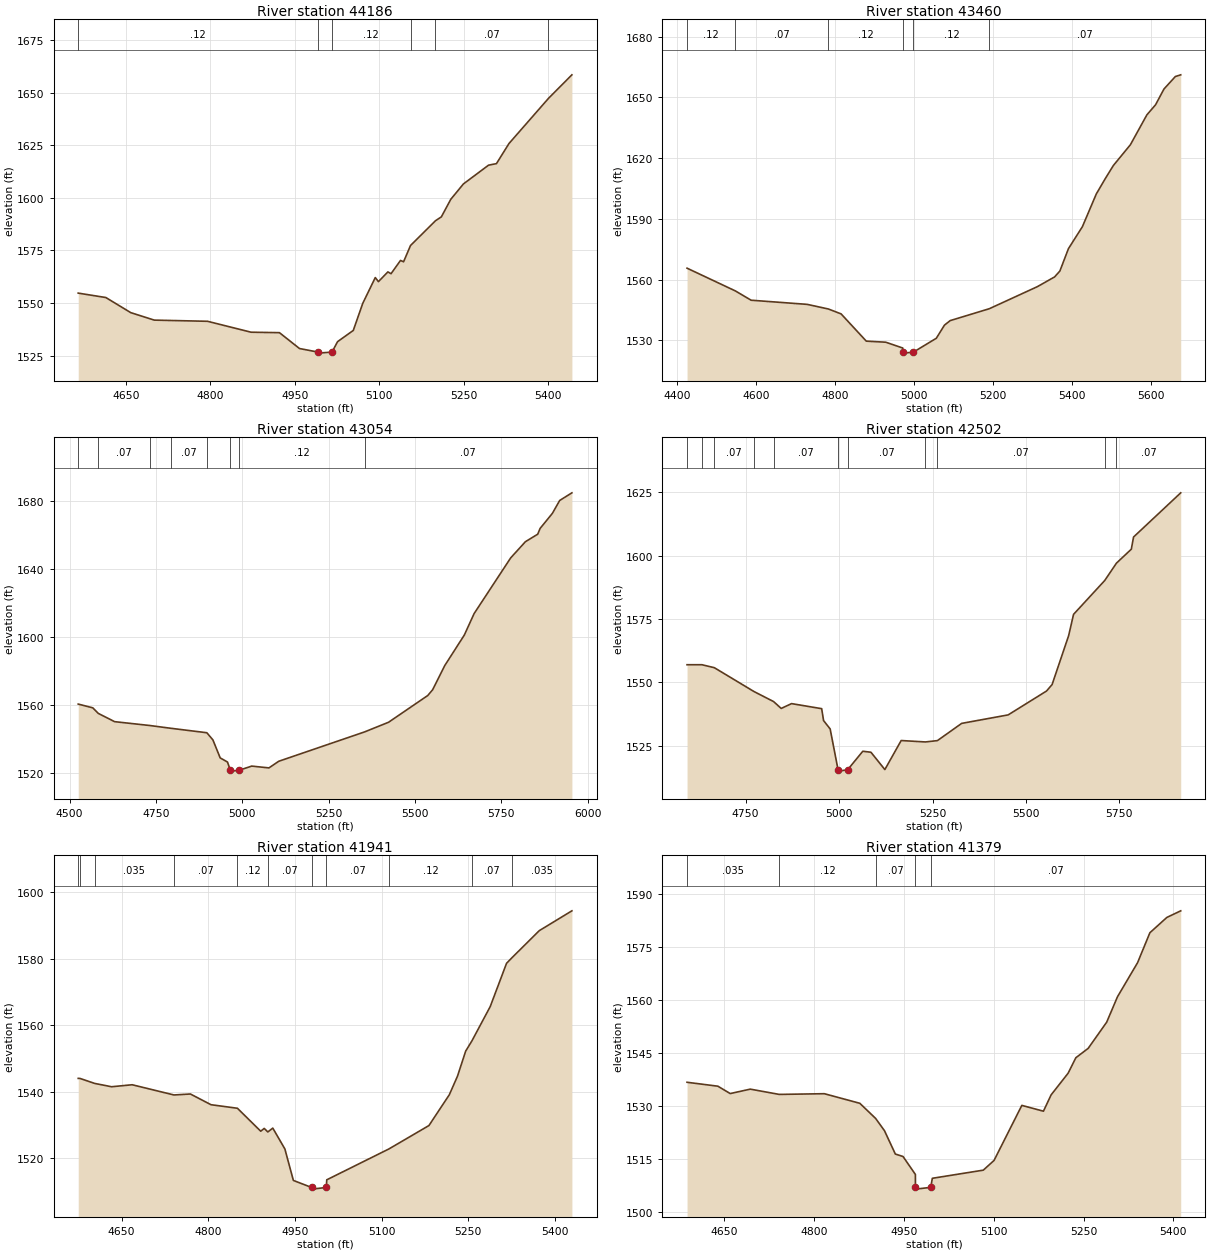
Type RM Length L Ch R = 1 ,44186   ,1132,1132,1132
BEGIN DESCRIPTION:
BLOCK CREEK 77.0
END DESCRIPTION:
XS GIS Cut Line= 3
      2019274.99     13937324.99        2018925.       13937075.
      2018525.02     13936875.01
#Sta/Elev= 30
  4565.3 1554.72  4614.4 1552.62  4658.7 1545.43  4700.5 1541.88  4795.1 1541.32
  4872.5 1536.13  4922.9 1535.91  4958.5 1528.37  4991.3 1526.68  4991.8 1526.18
  5016.3 1526.68  5026.2 1531.64  5054.1 1536.97  5070.9 1549.83  5093.2 1562.12
  5098.8 1560.18  5115.6 1564.81  5121.2 1563.95    5138 1570.26  5143.5 1569.63
  5155.8 1577.36  5200.2 1589.15  5210.6 1590.98  5227.4 1599.35  5249.8 1606.64
  5294.5 1615.58  5308.5  1616.3  5330.8 1625.87    5401 1647.35  5442.6 1658.54
#Mann= 6 ,-1 , 0
  4565.3     .12       0  4991.3     .05       0  5016.3     .12       0
  5155.8    .035       0  5200.2     .07       0    5401     .12       0
Bank Sta=4991.3,5016.3
XS Rating Curve= 0 ,0
Exp/Cntr=0.3,0.1

Type RM Length L Ch R = 1 ,43460   ,406,406,406
BEGIN DESCRIPTION:
BLOCK CREEK 76.0
END DESCRIPTION:
XS GIS Cut Line= 3
      2019811.65     13937097.29      2019444.84     13936654.62
      2019025.03     13936125.03
#Sta/Elev= 30
  4425.1  1565.6  4547.5 1554.37  4587.4 1549.78  4729.4 1547.73  4783.2 1545.44
  4815.4 1543.02  4879.2 1529.57  4928.6 1529.04  4971.6 1526.17  4973.4 1524.15
  4973.9 1523.65  4998.6 1524.15  5056.5 1530.98  5077.3 1537.48  5091.8 1539.71
    5191 1545.59  5312.9  1556.5  5356.2 1561.28  5369.6 1564.18  5391.4 1575.26
  5426.7 1586.09  5461.9 1602.25  5484.4 1609.75  5505.2 1616.32  5548.2 1626.53
  5590.1 1641.33    5612 1646.28  5633.4 1654.09  5662.2 1660.24  5675.8 1661.08
#Mann= 6 ,-1 , 0
  4425.1     .12       0  4547.5     .07       0  4783.2     .12       0
  4973.4     .05       0  4998.6     .12       0    5191     .07       0
Bank Sta=4973.4,4998.6
XS Rating Curve= 0 ,0
Exp/Cntr=0.3,0.1

Type RM Length L Ch R = 1 ,43054   ,552,552,552
BEGIN DESCRIPTION:
BLOCK CREEK 75.0
END DESCRIPTION:
XS GIS Cut Line= 3
        2019925.       13936975.        2019775.       13936525.
      2019124.99     13935824.99
#Sta/Elev= 30
  4525.1 1560.52  4567.3 1558.31  4583.2 1555.04  4630.5 1550.18  4732.1 1547.92
  4792.7  1546.3  4897.5 1543.67  4915.1 1539.46  4936.2 1528.87  4957.3 1526.44
  4965.7 1521.58  4966.2 1521.08    4991 1521.58  5027.5 1524.04  5077.4 1522.98
  5105.7 1526.87  5354.5 1544.16  5423.8 1549.83  5537.2 1565.55  5551.3 1568.91
  5586.5 1583.17  5643.2 1601.14  5671.5 1613.75  5777.5 1646.54  5820.1 1656.05
  5855.7 1660.46  5862.6 1663.84  5898.3 1672.75  5919.3  1680.3  5954.7  1684.8
#Mann= 8 ,-1 , 0
  4525.1     .12       0  4583.2     .07       0  4732.1     .12       0
  4792.7     .07       0  4897.5     .12       0  4965.7     .05       0
    4991     .12       0  5354.5     .07       0
Bank Sta=4965.7,4991
XS Rating Curve= 0 ,0
Exp/Cntr=0.3,0.1

Type RM Length L Ch R = 1 ,42502   ,561,561,561
BEGIN DESCRIPTION:
BLOCK CREEK 74.0
END DESCRIPTION:
XS GIS Cut Line= 3
      2020224.99     13936674.95        2020175.       13936275.
      2019375.04     13935825.02
#Sta/Elev= 30
  4593.2 1556.96  4633.1 1556.96  4666.2 1555.79  4772.2  1546.4  4824.7 1542.44
  4845.1 1539.73  4872.8 1541.63  4953.4 1539.64  4958.5 1534.94  4976.1 1531.65
  4997.3 1515.52  4997.8 1515.02  5022.6 1515.52  5063.5 1522.86  5085.2 1522.46
  5122.5 1515.64  5166.1 1527.08  5230.9 1526.52  5263.1 1527.05    5328 1533.84
  5452.3 1537.18    5555 1546.59  5569.9 1549.14  5614.2 1568.42  5627.3 1576.81
  5710.7 1590.15  5742.1    1597  5781.9 1602.51  5787.9  1607.3  5914.1 1624.72
#Mann= 11 ,-1 , 0
  4593.2     .07       0  4633.1     .12       0  4666.2     .07       0
  4772.2     .12       0  4824.7     .07       0  4997.3     .05       0
  5022.6     .07       0  5230.9     .12       0  5263.1     .07       0
  5710.7    .035       0  5742.1     .07       0
Bank Sta=4997.3,5022.6
XS Rating Curve= 0 ,0
Exp/Cntr=0.3,0.1

Type RM Length L Ch R = 1 ,41941   ,562,562,562
BEGIN DESCRIPTION:
BLOCK CREEK 73.0
END DESCRIPTION:
XS GIS Cut Line= 3
      2020474.98     13936074.97        2020225.       13935725.
      2019925.03     13935425.03
#Sta/Elev= 30
  4574.9 1544.08    4578 1544.06  4603.2 1542.57  4632.6 1541.56  4668.3 1542.16
  4740.5 1539.09    4769 1539.38  4804.7 1536.16  4850.4 1535.09  4890.7 1528.19
  4896.8 1529.03    4903 1527.97  4911.6 1529.12  4932.5 1522.86  4947.2 1513.39
  4978.7 1511.27  4979.2 1510.77  5004.2 1511.27    5005 1513.57  5112.6 1522.86
  5181.8 1529.89  5217.1 1539.16  5231.3 1544.78  5245.4 1552.29  5256.1 1555.33
  5287.8 1565.65  5316.1 1578.68  5325.7  1580.4  5372.7  1588.5  5429.2 1594.47
#Mann= 11 ,-1 , 0
  4574.9    .035       0    4578     .07       0  4603.2    .035       0
  4740.5     .07       0  4850.4     .12       0    4903     .07       0
  4978.7     .05       0  5004.2     .07       0  5112.6     .12       0
  5256.1     .07       0  5325.7    .035       0
Bank Sta=4978.7,5004.2
XS Rating Curve= 0 ,0
Exp/Cntr=0.3,0.1

Type RM Length L Ch R = 1 ,41379   ,565,565,565
BEGIN DESCRIPTION:
BLOCK CREEK 72.0
END DESCRIPTION:
XS GIS Cut Line= 3
        2020675.     13935724.99        2020575.       13935325.
      2020175.01       13935225.
#Sta/Elev= 30
  4587.7 1536.77  4639.2 1535.66  4659.8 1533.58  4693.3 1534.83  4741.7 1533.34
    4817 1533.54  4876.3 1530.83  4902.7 1526.55  4917.5 1523.08  4935.6  1516.5
  4948.5 1515.79  4969.1 1510.73  4969.2 1507.08  4969.7 1506.58  4994.7 1507.08
  4997.4 1509.64  5082.5 1511.94  5100.5 1514.69  5146.9 1530.24    5183  1528.6
  5195.8 1533.21  5224.2 1539.33  5237.1  1543.7  5257.7 1546.35  5288.6 1553.74
  5306.7 1560.94  5340.2 1570.55  5360.8 1579.02  5389.1 1583.34  5412.3 1585.21
#Mann= 5 ,-1 , 0
  4587.7    .035       0  4741.7     .12       0  4902.7     .07       0
  4969.2     .05       0  4994.7     .07       0
Bank Sta=4969.2,4994.7
XS Rating Curve= 0 ,0
Exp/Cntr=0.3,0.1