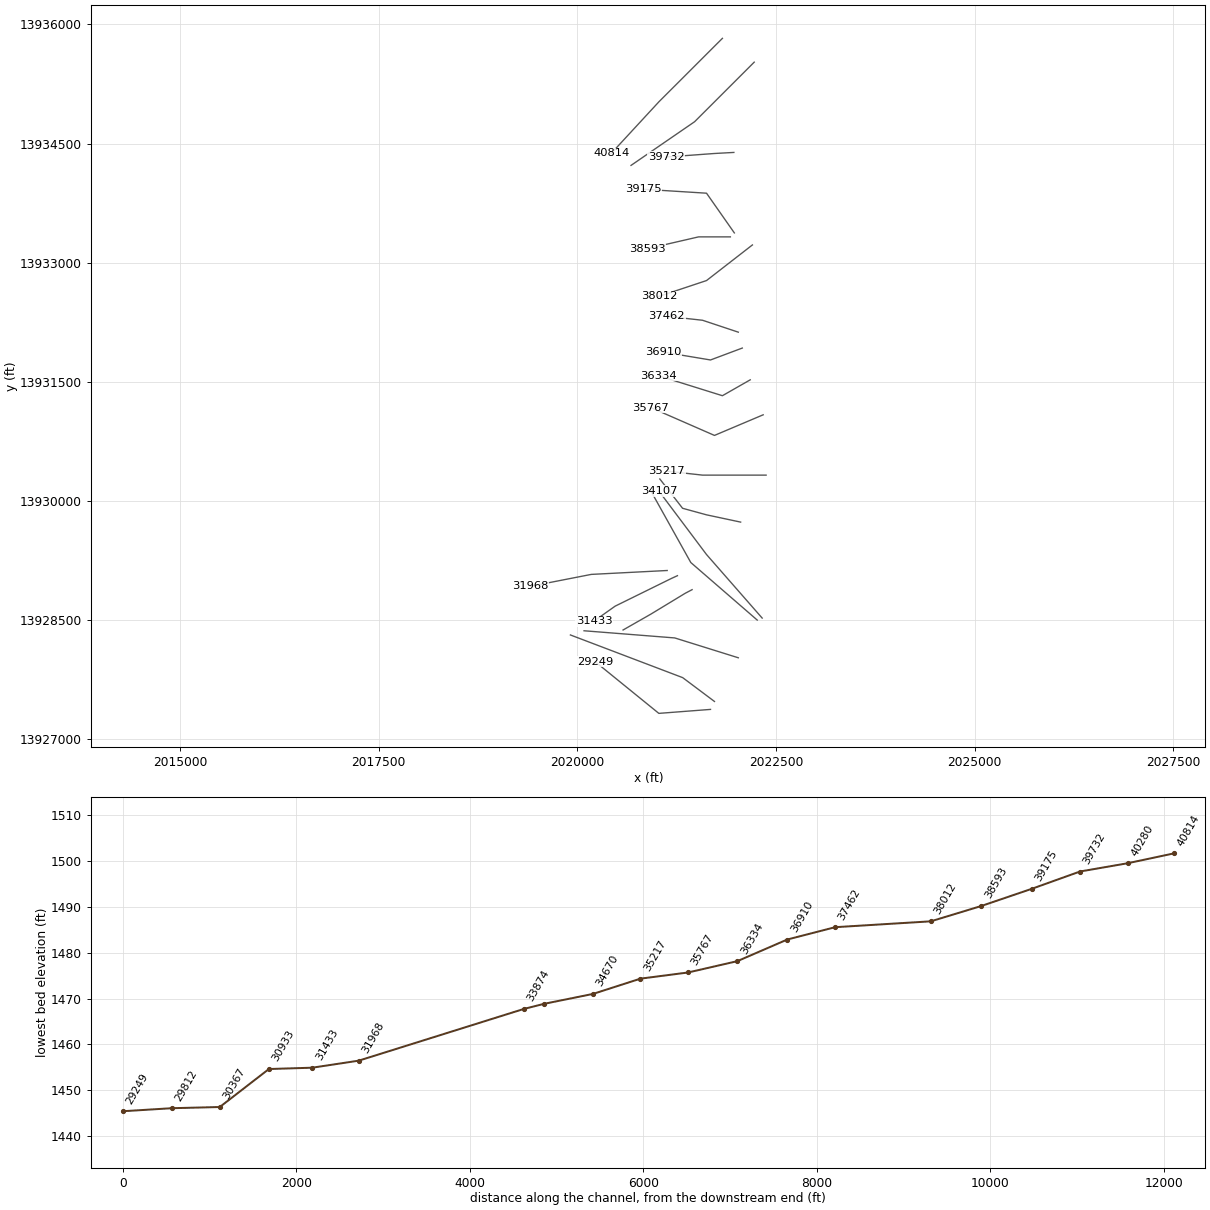
HEC-RAS study BLOCK CREEK.prj: BLOCK CREEK Base Level Engineering

--- BLOCK CREEK.g01 (geometry) --- (continued)

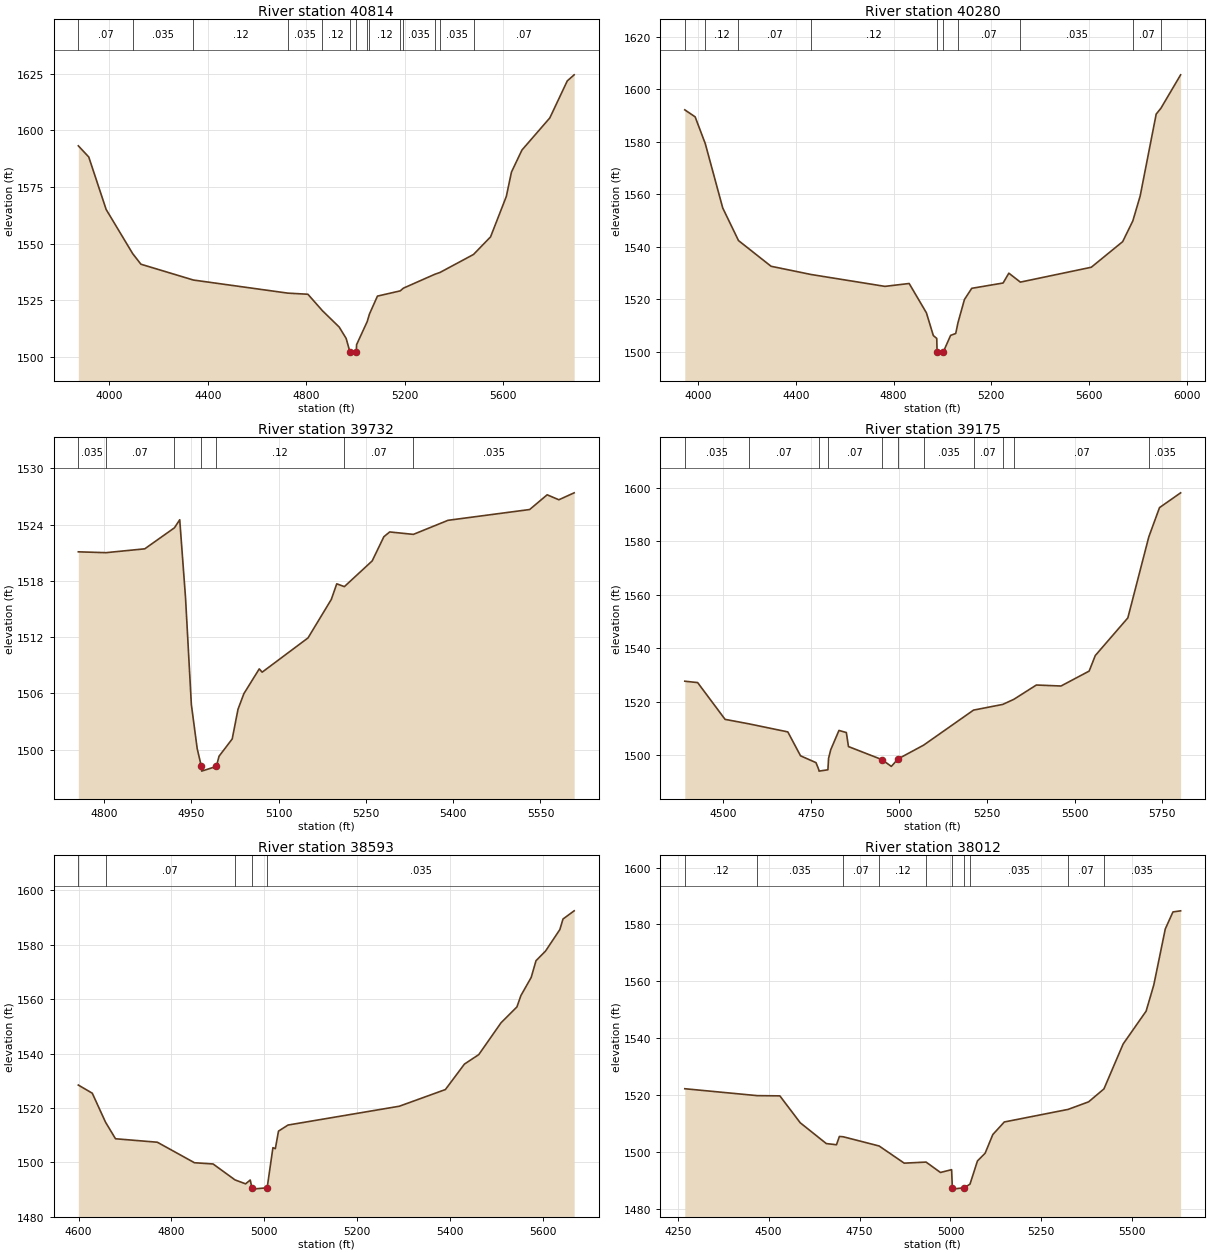
Type RM Length L Ch R = 1 ,40814   ,534,534,534
BEGIN DESCRIPTION:
BLOCK CREEK 71.0
END DESCRIPTION:
XS GIS Cut Line= 3
      2021824.98     13935824.98        2021025.       13935025.
      2020425.02     13934375.03
#Sta/Elev= 30
  3873.7 1593.11  3916.1 1588.19  3986.8 1565.04  4094.5 1545.59  4128.2 1540.89
  4341.5 1533.91    4725 1528.14  4807.1 1527.64  4866.3 1520.36  4934.3 1513.18
  4962.6 1508.15  4978.1 1502.17  4978.6 1501.67  5003.7 1502.17    5005  1505.4
  5048.3 1515.61  5057.2 1518.89  5089.8 1526.82  5182.8 1529.14    5195 1530.31
  5323.4 1536.47  5343.7 1537.23  5480.4 1545.19  5549.7 1552.95  5613.8 1570.79
  5634.7 1581.53  5677.3 1591.25  5790.7 1605.43  5861.6 1621.75  5889.6 1624.43
#Mann= 14 ,-1 , 0
  3873.7     .07       0  4094.5    .035       0  4341.5     .12       0
    4725    .035       0  4866.3     .12       0  4978.1     .05       0
  5003.7     .12       0  5048.3     .07       0  5057.2     .12       0
  5182.8     .07       0    5195    .035       0  5323.4     .07       0
  5343.7    .035       0  5480.4     .07       0
Bank Sta=4978.1,5003.7
XS Rating Curve= 0 ,0
Exp/Cntr=0.3,0.1

Type RM Length L Ch R = 1 ,40280   ,548,548,548
BEGIN DESCRIPTION:
BLOCK CREEK 70.0
END DESCRIPTION:
XS GIS Cut Line= 3
      2022224.97     13935524.97        2021475.       13934775.
      2020675.03     13934225.02
#Sta/Elev= 30
  3944.5 1592.13  3986.9 1589.46  4028.4 1579.27    4100 1554.76  4164.5 1542.37
    4298 1532.58    4462 1529.45  4764.7 1524.93  4863.7 1526.03  4934.4 1514.86
  4962.7 1506.21  4976.8 1505.11  4978.1 1500.02  4978.6 1499.52  5003.8 1500.02
  5033.5 1506.27  5054.5    1507  5063.8 1511.14  5090.3 1519.94  5120.1 1524.19
  5248.6 1526.21  5272.1 1529.96  5319.3 1526.55  5609.9 1532.21  5738.5 1541.96
  5780.1 1549.86  5810.2 1559.35  5875.8 1590.51  5895.2 1592.75  5975.9 1605.46
#Mann= 10 ,-1 , 0
  3944.5     .07       0  4028.4     .12       0  4164.5     .07       0
    4462     .12       0  4978.1     .05       0  5003.8     .12       0
  5063.8     .07       0  5319.3    .035       0  5780.1     .07       0
  5895.2    .035       0
Bank Sta=4978.1,5003.8
XS Rating Curve= 0 ,0
Exp/Cntr=0.3,0.1

Type RM Length L Ch R = 1 ,39732   ,557,557,557
BEGIN DESCRIPTION:
BLOCK CREEK 69.0
END DESCRIPTION:
XS GIS Cut Line= 3
      2021969.04     13934388.33        2021725.       13934375.
      2021118.75     13934330.32
#Sta/Elev= 30
  4755.6  1521.1  4803.1 1521.01  4869.8 1521.42  4920.8 1523.66  4929.9 1524.52
  4939.9 1516.18  4949.9 1504.82  4959.9 1500.13  4967.1 1498.22  4967.6 1497.72
  4992.8 1498.22  4997.5 1499.31  5020.1 1501.15  5030.1 1504.32  5040.1 1505.97
  5066.6 1508.62  5071.6 1508.27  5150.4 1511.92  5190.5 1516.03  5199.8 1517.69
  5212.9 1517.39  5260.7 1520.13  5280.8 1522.71  5290.8 1523.22  5331.5 1522.96
  5391.1 1524.46  5531.4 1525.61  5561.5 1527.18  5581.6 1526.65  5607.9 1527.39
#Mann= 7 ,-1 , 0
  4755.6    .035       0  4803.1     .07       0  4920.8     .12       0
  4967.1     .05       0  4992.8     .12       0  5212.9     .07       0
  5331.5    .035       0
Bank Sta=4967.1,4992.8
XS Rating Curve= 0 ,0
Exp/Cntr=0.3,0.1

Type RM Length L Ch R = 1 ,39175   ,582,582,582
BEGIN DESCRIPTION:
BLOCK CREEK 68.0
END DESCRIPTION:
XS GIS Cut Line= 3
      2021975.01     13933374.98        2021625.       13933875.
      2020825.01       13933925.
#Sta/Elev= 30
  4390.2 1527.64  4426.8 1527.12  4504.9 1513.34  4571.7 1511.69  4683.6 1508.64
  4719.8 1499.68  4763.8 1497.12  4771.9 1494.44  4772.4 1493.94  4797.7 1494.44
  4799.6 1498.74  4805.7 1501.94  4829.2 1509.19  4850.2  1508.4  4856.3 1503.14
  4951.3 1498.27  4978.3 1495.71  4997.5 1498.52  5070.4 1503.69  5212.4 1516.81
  5295.5 1518.94  5327.2 1520.85  5391.3 1526.21  5461.5 1525.84  5541.6 1531.43
  5559.1 1537.26  5651.8 1551.37  5711.5 1581.74    5742  1592.7  5802.1 1598.24
#Mann= 11 ,-1 , 0
  4390.2    .035       0  4571.7     .07       0  4771.9     .05       0
  4797.7     .07       0  4951.3    .035       0  4997.5     .12       0
  5070.4    .035       0  5212.4     .07       0  5295.5    .035       0
  5327.2     .07       0  5711.5    .035       0
Bank Sta=4951.3,4997.5
XS Rating Curve= 0 ,0
Exp/Cntr=0.3,0.1

Type RM Length L Ch R = 1 ,38593   ,581,581,581
BEGIN DESCRIPTION:
BLOCK CREEK 67.0
END DESCRIPTION:
XS GIS Cut Line= 3
      2021925.01       13933325.        2021525.       13933325.
      2020874.99       13933175.
#Sta/Elev= 30
  4599.6 1528.42  4629.6 1525.43  4658.1  1514.8  4679.6 1508.69  4769.6 1507.42
  4849.6 1499.88  4889.6 1499.43  4936.8 1493.58  4959.6 1492.13  4969.6 1493.54
  4973.2 1490.69  4973.8 1490.19    5006 1490.69  5018.4 1505.42  5023.6 1505.04
  5030.4  1511.5  5050.9 1513.73  5290.4 1520.64  5389.6 1526.77  5430.6 1536.13
  5461.4  1539.6  5509.3 1551.29  5543.5 1557.12  5552.1  1561.3  5574.3 1567.98
  5584.6  1574.1  5605.1 1577.64  5635.9 1585.53  5642.7 1589.41  5666.7 1592.42
#Mann= 5 ,-1 , 0
  4599.6    .035       0  4658.1     .07       0  4936.8    .035       0
  4973.2    .035       0    5006    .035       0
Bank Sta=4973.2,5006
XS Rating Curve= 0 ,0
Exp/Cntr=0.3,0.1

Type RM Length L Ch R = 1 ,38012   ,1103,1103,1103
BEGIN DESCRIPTION:
BLOCK CREEK 66.0
END DESCRIPTION:
XS GIS Cut Line= 3
      2022202.38     13933223.52        2021625.       13932775.
      2021024.97     13932574.99
#Sta/Elev= 30
  4269.4 1522.18  4468.6 1519.75  4530.8 1519.67  4586.9  1510.2  4658.6 1502.88
  4686.5 1502.47  4694.6 1505.39  4705.3 1505.27  4803.9 1502.03  4872.9 1495.99
    4933 1496.37  4972.5 1492.71  5003.2  1493.7  5005.2 1487.35  5005.7 1486.85
    5038 1487.35  5053.7  1488.6  5074.3 1496.78  5095.4  1499.5  5116.5 1506.06
  5148.1 1510.48  5323.6 1514.91    5380 1517.57  5422.1 1522.12  5474.9 1537.92
  5538.1 1549.49  5559.2 1558.69  5590.8 1578.41  5611.9  1584.4    5633 1584.79
#Mann= 10 ,-1 , 0
  4269.4     .12       0  4468.6    .035       0  4705.3     .07       0
  4803.9     .12       0    4933     .07       0  5005.2     .05       0
    5038     .07       0  5053.7    .035       0  5323.6     .07       0
  5422.1    .035       0
Bank Sta=5005.2,5038
XS Rating Curve= 0 ,0
Exp/Cntr=0.3,0.1

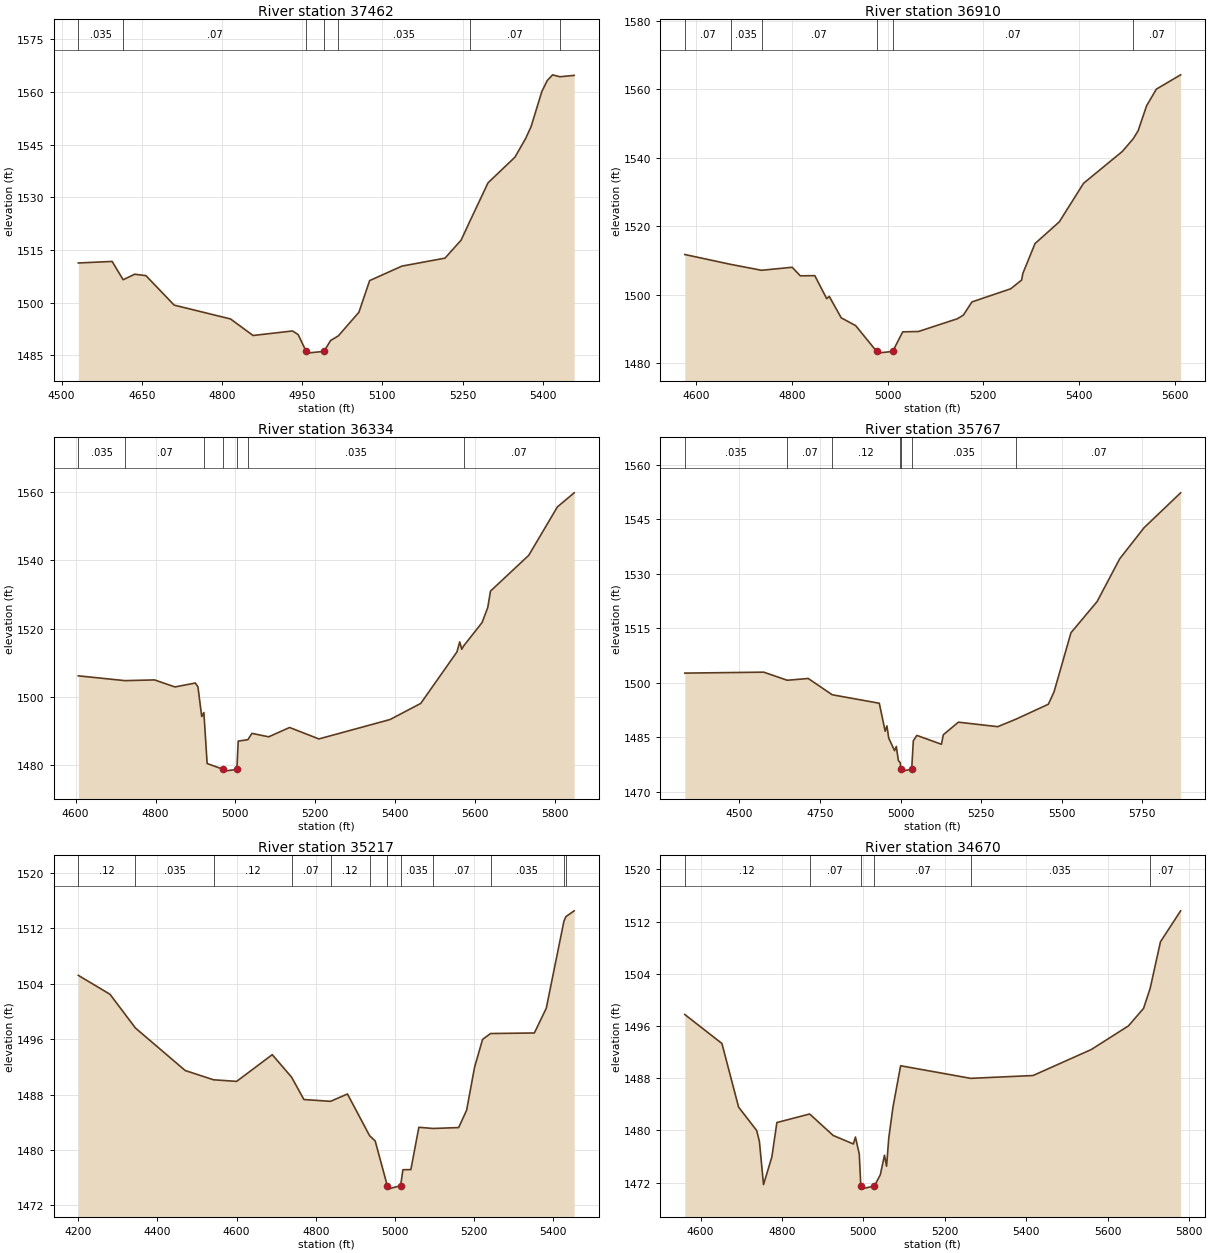
Type RM Length L Ch R = 1 ,37462   ,552,552,552
BEGIN DESCRIPTION:
BLOCK CREEK 65.0
END DESCRIPTION:
XS GIS Cut Line= 3
      2022024.96     13932125.01        2021575.       13932275.
      2021124.97       13932325.
#Sta/Elev= 30
  4531.4 1511.27  4594.6 1511.71  4615.2 1506.49  4636.8 1508.07  4657.8 1507.66
  4710.6 1499.26    4816 1495.31  4858.1  1490.6  4931.9 1491.89  4942.5 1490.85
  4957.4 1486.07    4958 1485.57  4990.8 1486.07  5003.1 1489.17  5017.6  1490.5
    5056 1497.21  5076.1 1506.25  5136.5 1510.38    5217 1512.65  5247.2  1517.8
  5263.3  1523.1  5297.5 1534.13  5347.8 1541.44  5367.9 1546.79    5378 1550.17
  5398.1 1560.16  5408.2 1563.29  5418.2 1564.91  5431.8 1564.36  5458.5 1564.75
#Mann= 7 ,-1 , 0
  4531.4    .035       0  4615.2     .07       0  4957.4     .05       0
  4990.8     .07       0  5017.6    .035       0  5263.3     .07       0
  5431.8    .035       0
Bank Sta=4957.4,4990.8
XS Rating Curve= 0 ,0
Exp/Cntr=0.3,0.1

Type RM Length L Ch R = 1 ,36910   ,576,576,576
BEGIN DESCRIPTION:
BLOCK CREEK 64.0
END DESCRIPTION:
XS GIS Cut Line= 3
      2022075.04     13931925.01        2021675.       13931775.
      2021075.01       13931875.
#Sta/Elev= 30
  4576.6 1511.72  4673.4 1508.81    4737 1507.11  4800.9 1507.99  4817.8 1505.49
  4848.1 1505.54    4873  1498.8  4878.3 1499.48  4903.3  1493.2  4933.5 1490.92
  4977.3 1483.38  4977.9 1482.88  5010.8 1483.38  5031.7  1489.1  5064.7 1489.21
  5145.8 1492.93  5158.4    1494  5176.2 1497.85  5257.3  1501.7  5280.1 1504.26
  5282.6 1506.19    5308 1514.92  5358.7 1521.27  5409.4 1532.55  5490.5 1541.88
  5513.2 1545.59  5523.4 1547.93  5541.1 1555.24  5561.4 1560.08  5612.1 1564.27
#Mann= 6 ,-1 , 0
  4576.6     .07       0  4673.4    .035       0    4737     .07       0
  4977.3    .035       0  5010.8     .07       0  5513.2     .07       0
Bank Sta=4977.3,5010.8
XS Rating Curve= 0 ,0
Exp/Cntr=0.3,0.1

Type RM Length L Ch R = 1 ,36334   ,567,567,567
BEGIN DESCRIPTION:
BLOCK CREEK 63.0
END DESCRIPTION:
XS GIS Cut Line= 3
      2022175.03     13931525.02        2021825.       13931325.
        2021025.       13931575.
#Sta/Elev= 30
  4606.8 1506.13  4723.5 1504.72  4797.6 1504.93  4848.7 1502.87  4899.8 1504.02
  4906.3 1502.87  4915.7 1494.19  4921.1 1495.36  4929.3 1480.39  4970.2 1478.66
  4970.8 1478.16  5003.7 1478.66  5007.1 1486.98  5031.2 1487.38  5041.4 1489.24
  5083.3 1488.23  5135.7 1490.97    5209 1487.61  5387.1  1493.3  5464.1 1498.04
  5554.7 1513.16  5561.6 1516.08  5566.8 1513.94  5571.5 1514.91  5617.6 1521.78
  5631.8 1526.18  5638.6 1530.99  5734.4  1541.5  5806.2 1555.72  5848.1 1559.84
#Mann= 7 ,-1 , 0
  4606.8    .035       0  4723.5     .07       0  4921.1     .12       0
  4970.2     .05       0  5003.7     .12       0  5031.2    .035       0
  5571.5     .07       0
Bank Sta=4970.2,5003.7
XS Rating Curve= 0 ,0
Exp/Cntr=0.3,0.1

Type RM Length L Ch R = 1 ,35767   ,550,550,550
BEGIN DESCRIPTION:
BLOCK CREEK 62.0
END DESCRIPTION:
XS GIS Cut Line= 3
      2022337.78     13931084.61        2021725.       13930825.
      2020925.02     13931174.99
#Sta/Elev= 30
  4330.4 1502.68  4575.4 1502.94  4648.4 1500.71  4713.5  1501.2  4787.8 1496.72
    4934 1494.38  4952.2 1486.68  4957.7 1488.15  4963.3 1484.78  4981.4 1481.31
  4986.8 1482.48  4993.2 1478.61  4999.2 1477.98  5000.9 1476.19  5001.6 1475.69
  5034.5 1476.19  5039.6 1484.04  5050.5 1485.53  5126.9 1483.09  5132.7 1485.71
  5179.5 1489.17  5301.5 1487.93    5359 1490.03  5458.6 1494.11  5476.2 1497.49
  5528.8 1513.79  5609.9 1522.38  5680.1 1534.16  5755.7 1542.72  5869.1 1552.32
#Mann= 7 ,-1 , 0
  4330.4    .035       0  4648.4     .07       0  4787.8     .12       0
  4999.2    .035       0  5000.9    .035       0  5034.5    .035       0
    5359     .07       0
Bank Sta=5000.9,5034.5
XS Rating Curve= 0 ,0
Exp/Cntr=0.3,0.1

Type RM Length L Ch R = 1 ,35217   ,547,547,547
BEGIN DESCRIPTION:
BLOCK CREEK 61.0
END DESCRIPTION:
XS GIS Cut Line= 3
        2022375.       13930325.        2021575.       13930325.
      2021124.97       13930375.
#Sta/Elev= 30
    4200 1505.21    4280 1502.48  4344.4  1497.6    4470 1491.47  4541.6 1490.13
    4600  1489.9    4690 1493.76  4738.8 1490.51    4770 1487.28  4837.3 1487.02
    4880 1488.08  4935.9 1482.06    4950 1481.31  4980.7 1474.84  4981.3 1474.34
  5014.3 1474.84  5020.1 1477.14  5040.2 1477.16  5060.4 1483.27  5096.4  1483.1
    5161 1483.23  5181.1 1485.74  5201.2 1491.95  5221.4 1495.96  5241.5 1496.81
  5352.2 1496.89  5382.3 1500.45  5427.1 1513.07  5432.1  1513.7  5452.8 1514.53
#Mann= 12 ,-1 , 0
    4200     .12       0  4344.4    .035       0  4541.6     .12       0
  4738.8     .07       0  4837.3     .12       0  4935.9    .035       0
  4980.7    .035       0  5014.3    .035       0  5096.4     .07       0
  5241.5    .035       0  5427.1     .07       0  5432.1    .035       0
Bank Sta=4980.7,5014.3
XS Rating Curve= 0 ,0
Exp/Cntr=0.3,0.1

Type RM Length L Ch R = 1 ,34670   ,563,563,563
BEGIN DESCRIPTION:
BLOCK CREEK 60.0
END DESCRIPTION:
XS GIS Cut Line= 4
      2022054.16     13929733.44        2021625.       13929825.
      2021323.58     13929907.55      2021037.47     13930276.22
#Sta/Elev= 30
  4561.2 1497.76  4652.4 1493.32  4693.4 1483.57  4737.8 1479.99  4744.4 1478.35
  4754.6 1471.71  4775.1 1475.95  4787.4 1481.21  4867.9 1482.52  4925.7 1479.23
  4975.3 1477.93  4980.4 1478.99  4989.8 1476.38  4993.6 1471.51  4994.2 1471.01
  5027.2 1471.51  5041.5 1473.22  5051.7  1476.2  5056.9 1474.52  5062.2 1478.81
  5072.6 1483.58  5091.4 1489.91  5263.4 1487.98  5416.6 1488.41  5559.6 1492.39
  5651.1 1496.02  5688.1 1498.69  5704.3 1501.75  5729.7  1508.9  5779.2 1513.64
#Mann= 6 ,-1 , 0
  4561.2     .12       0  4867.9     .07       0  4993.6     .05       0
  5027.2     .07       0  5263.4    .035       0  5704.3     .07       0
Bank Sta=4993.6,5027.2
XS Rating Curve= 0 ,0
Exp/Cntr=0.3,0.1

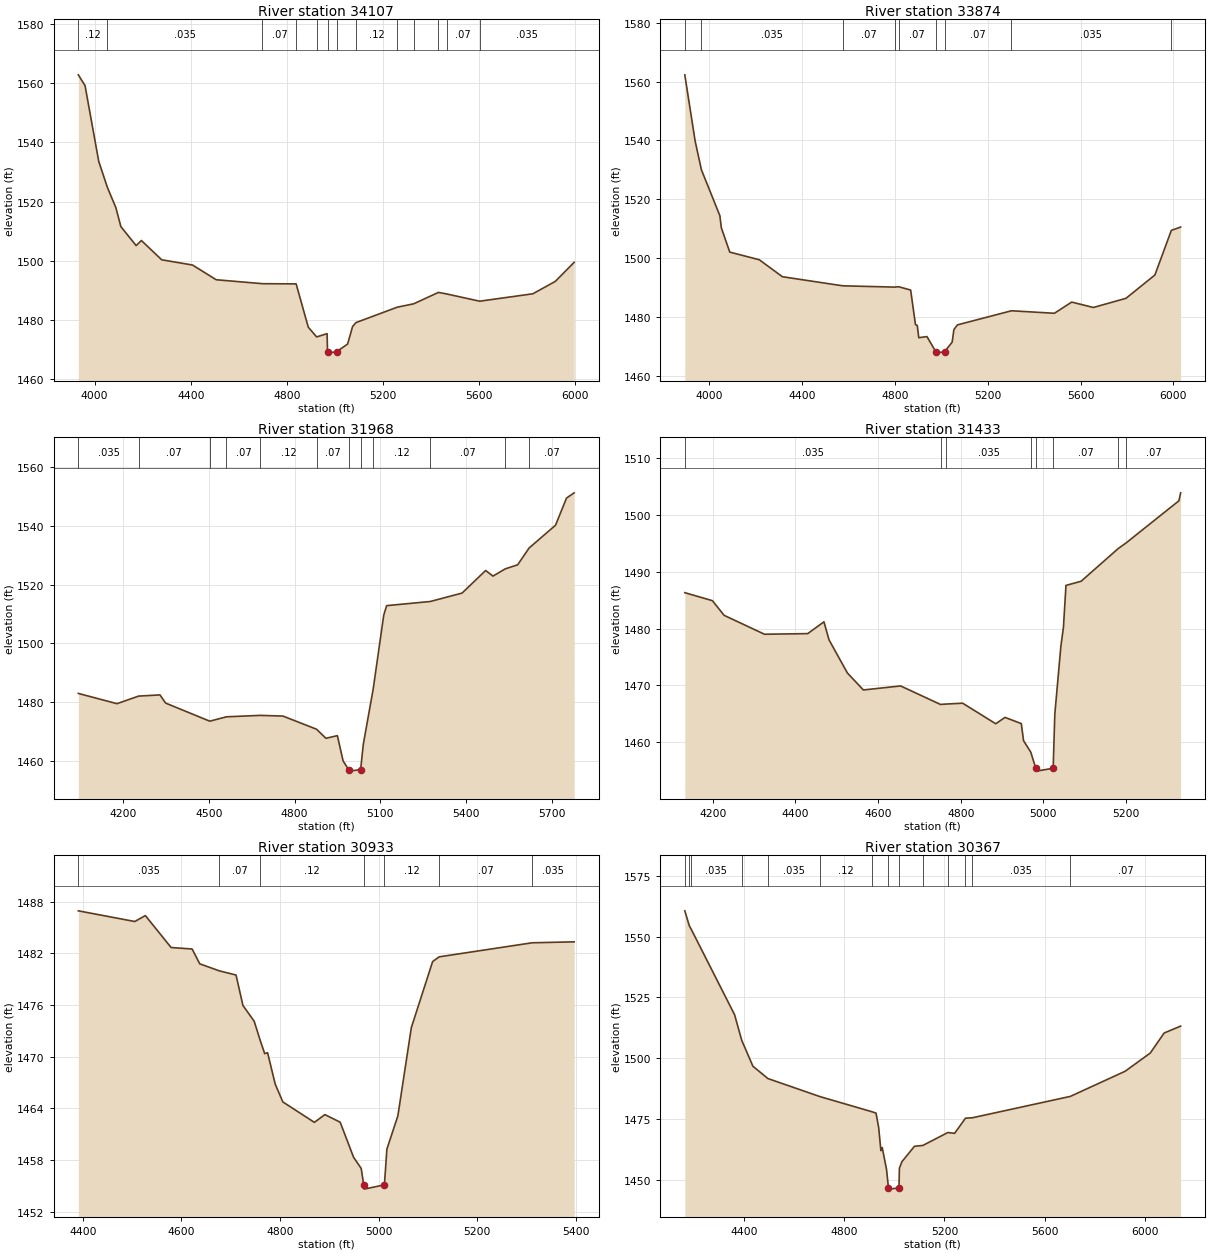
Type RM Length L Ch R = 1 ,34107   ,233,233,233
BEGIN DESCRIPTION:
BLOCK CREEK 59.0
END DESCRIPTION:
XS GIS Cut Line= 3
      2022324.98     13928525.03        2021625.       13929325.
      2021024.99     13930125.02
#Sta/Elev= 30
    3932 1562.75    3960 1559.09  4016.9 1533.55  4052.9 1524.77  4088.1 1517.96
    4109 1511.54  4172.6 1505.13  4194.4 1506.85  4278.9 1500.34    4407 1498.58
  4505.7 1493.61  4698.2 1492.28  4838.3 1492.21  4888.7 1477.61  4923.5 1474.32
    4967 1475.42  4968.9 1469.35  4969.9 1468.85  5006.9 1469.35  5052.3  1471.9
  5073.1 1477.82  5087.3 1479.16    5259 1484.35  5327.5 1485.49  5430.4 1489.34
    5465 1488.81  5601.8 1486.37  5823.1 1488.87  5916.9 1493.07    5995 1499.49
#Mann= 13 ,-1 , 0
    3932     .12       0  4052.9    .035       0  4698.2     .07       0
  4838.3     .12       0  4923.5     .07       0  4968.9     .05       0
  5006.9     .07       0  5087.3     .12       0    5259     .07       0
  5327.5     .12       0  5430.4    .035       0    5465     .07       0
  5601.8    .035       0
Bank Sta=4968.9,5006.9
XS Rating Curve= 0 ,0
Exp/Cntr=0.3,0.1

Type RM Length L Ch R = 1 ,33874   ,1906,1906,1906
BEGIN DESCRIPTION:
BLOCK CREEK 58.0
END DESCRIPTION:
XS GIS Cut Line= 3
      2022262.82     13928499.98      2021427.19     13929224.41
      2020924.99     13930125.02
#Sta/Elev= 30
  3894.4 1562.29    3939 1539.78    3966 1530.03  4045.4 1514.47    4052  1510.3
  4088.2 1502.06  4215.4 1499.47    4315  1493.7  4575.1 1490.61  4799.3 1490.17
    4816  1490.3  4867.9 1489.17  4888.7 1477.41  4896.4 1477.15    4903 1472.98
  4938.1 1473.36  4976.1 1468.24  4977.1 1467.74  5014.1 1468.24  5046.8 1471.47
  5054.3 1475.76  5069.7 1477.34  5302.3 1482.13  5487.5 1481.28    5562 1485.08
  5655.5 1483.25    5796 1486.36  5920.6 1494.28  5991.5 1509.44  6031.5 1510.57
#Mann= 9 ,-1 , 0
  3894.4     .12       0    3966    .035       0  4575.1     .07       0
  4799.3     .12       0    4816     .07       0  4976.1     .05       0
  5014.1     .07       0  5302.3    .035       0  5991.5     .07       0
Bank Sta=4976.1,5014.1
XS Rating Curve= 0 ,0
Exp/Cntr=0.3,0.1

Type RM Length L Ch R = 1 ,31968   ,535,535,535
BEGIN DESCRIPTION:
BLOCK CREEK 57.0
END DESCRIPTION:
XS GIS Cut Line= 3
      2021130.23     13929124.06        2020175.       13929075.
      2019411.09     13928925.42
#Sta/Elev= 30
  4043.1 1482.92  4178.5 1479.43  4253.9 1482.01  4328.7 1482.42  4348.7 1479.62
  4503.1 1473.46  4561.3 1474.95  4679.5 1475.44  4759.3  1475.2  4876.6 1470.72
  4909.5 1467.63  4949.5 1468.53  4969.5 1459.94  4988.8 1456.94  4989.8 1456.44
  5030.8 1456.94  5040.3 1465.64  5074.6 1484.29  5111.7 1509.58  5121.9 1512.84
  5274.3 1514.25  5385.8 1517.12  5468.3 1524.82  5493.9 1522.91  5536.8 1525.37
  5580.4 1526.76  5620.3 1532.48  5712.9 1540.26  5751.3 1549.51    5778 1551.29
#Mann= 12 ,-1 , 0
  4043.1    .035       0  4253.9     .07       0  4503.1    .035       0
  4561.3     .07       0  4679.5     .12       0  4876.6     .07       0
  4988.8     .05       0  5030.8     .07       0  5074.6     .12       0
  5274.3     .07       0  5536.8    .035       0  5620.3     .07       0
Bank Sta=4988.8,5030.8
XS Rating Curve= 0 ,0
Exp/Cntr=0.3,0.1

Type RM Length L Ch R = 1 ,31433   ,500,500,500
BEGIN DESCRIPTION:
BLOCK CREEK 56.0
END DESCRIPTION:
XS GIS Cut Line= 4
      2021258.86     13929058.78      2021182.68     13929023.73
        2020475.       13928675.      2020208.63     13928486.18
#Sta/Elev= 30
  4132.6 1486.33  4199.4 1484.92  4227.7 1482.34  4325.4 1479.01  4429.9 1479.12
  4469.2  1481.2  4481.4 1478.03    4526 1472.18  4564.6  1469.2  4654.5 1469.91
  4751.1 1466.65  4764.9 1466.72  4804.7 1466.87  4884.7 1463.25  4907.1 1464.37
  4946.5 1463.28    4952 1460.27  4969.4 1458.26  4981.6 1455.41  4982.6 1454.91
  5023.6 1455.41  5027.6 1464.94  5042.2 1476.85  5048.5 1480.27  5054.6 1487.61
  5091.2 1488.34    5181  1494.1    5200 1495.09  5327.8 1502.51  5331.9 1503.91
#Mann= 8 ,-1 , 0
  4132.6    .035       0  4751.1     .07       0  4764.9    .035       0
  4969.4     .07       0  4981.6     .05       0  5023.6     .07       0
    5181    .035       0    5200     .07       0
Bank Sta=4981.6,5023.6
XS Rating Curve= 0 ,0
Exp/Cntr=0.3,0.1

Type RM Length L Ch R = 1 ,30933   ,566,566,566
BEGIN DESCRIPTION:
BLOCK CREEK 55.0
END DESCRIPTION:
XS GIS Cut Line= 4
      2021443.42     13928882.75      2021356.93     13928837.27
        2020925.       13928575.      2020575.04     13928375.02
#Sta/Elev= 30
  4390.7 1486.92  4505.3 1485.68  4526.7 1486.37    4579 1482.66  4621.6 1482.49
  4637.1 1480.77  4676.9 1479.95  4710.7 1479.47  4724.7 1475.94  4747.5 1474.11
  4759.6 1471.91  4768.9 1470.34  4774.7 1470.46  4790.2 1466.81  4805.7 1464.74
  4869.7 1462.37    4891 1463.27    4922 1462.39  4949.2 1458.32  4964.7 1457.02
  4969.8 1455.12  4970.8 1454.62  5011.8 1455.12  5016.8 1459.26  5039.1 1463.13
  5066.4 1473.36  5109.6 1481.03  5122.9 1481.58  5311.5 1483.21  5396.8 1483.32
#Mann= 7 ,-1 , 0
  4390.7    .035       0  4676.9     .07       0  4759.6     .12       0
  4969.8     .05       0  5011.8     .12       0  5122.9     .07       0
  5311.5    .035       0
Bank Sta=4969.8,5011.8
XS Rating Curve= 0 ,0
Exp/Cntr=0.3,0.1

Type RM Length L Ch R = 1 ,30367   ,555,555,555
BEGIN DESCRIPTION:
BLOCK CREEK 54.0
END DESCRIPTION:
XS GIS Cut Line= 3
      2022025.02       13928025.        2021225.       13928275.
      2020083.92     13928365.15
#Sta/Elev= 30
  4161.5 1560.55  4179.5 1554.44    4186 1553.22  4360.6 1517.91  4389.3 1507.38
  4433.9 1496.77  4493.9 1491.71  4702.2  1484.3  4910.9 1478.06  4926.3 1477.52
  4936.8 1471.63  4945.7 1462.12    4951 1463.41  4968.2 1454.44    4976 1446.83
    4977 1446.33    5018 1446.83  5019.7 1454.92  5029.8 1457.59  5079.9 1463.91
  5113.5 1464.26  5213.5 1469.56  5240.4 1469.22  5283.9 1475.44  5311.8 1475.62
  5703.3 1484.39  5922.5 1494.71  6022.8 1502.17  6078.5 1510.41  6144.3 1513.23
#Mann= 14 ,-1 , 0
  4161.5    .035       0  4179.5     .07       0    4186    .035       0
  4389.3     .07       0  4493.9    .035       0  4702.2     .12       0
  4910.9     .07       0    4976     .05       0    5018     .07       0
  5113.5     .07       0  5213.5    .035       0  5283.9     .07       0
  5311.8    .035       0  5703.3     .07       0
Bank Sta=4976,5018
XS Rating Curve= 0 ,0
Exp/Cntr=0.3,0.1

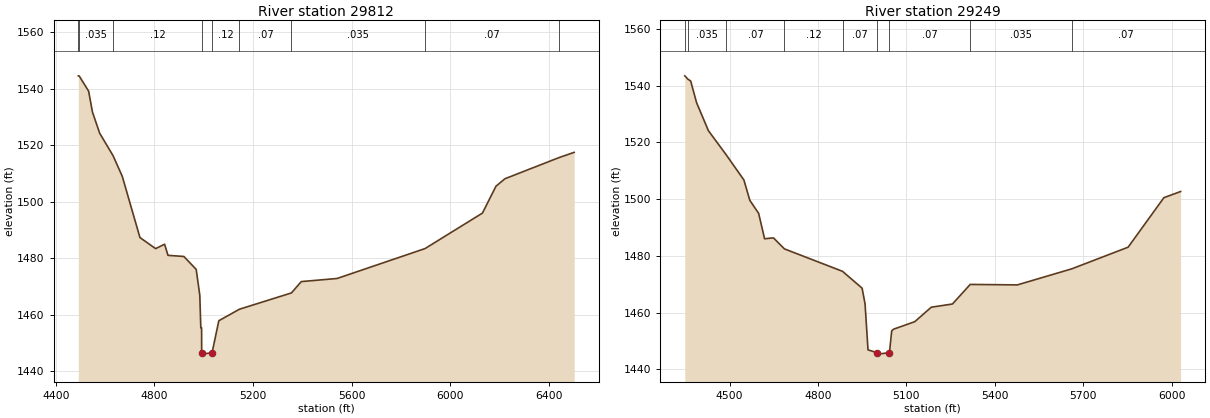
Type RM Length L Ch R = 1 ,29812   ,563,563,563
BEGIN DESCRIPTION:
BLOCK CREEK 53.0
END DESCRIPTION:
XS GIS Cut Line= 3
      2021725.01     13927474.99        2021325.       13927775.
      2019912.47     13928312.35
#Sta/Elev= 30
  4491.1 1544.59  4494.6 1544.54  4532.8 1539.18  4548.4 1531.77  4577.6 1524.29
    4632 1516.32  4669.2 1509.05  4741.1 1487.33  4804.7 1483.42  4841.1 1484.98
  4854.7 1481.04  4919.2 1480.64  4969.2 1476.07  4983.8 1466.95    4988  1455.4
  4991.1  1455.4  4991.5 1446.57  4992.5 1446.07  5033.6 1446.57    5061 1457.89
  5144.7 1461.97  5355.4 1467.73  5395.6 1471.75  5540.8 1472.85  5897.4 1483.43
  6130.4    1496  6185.2  1505.5  6221.5 1508.15  6439.7  1515.6  6502.4  1517.5
#Mann= 9 ,-1 , 0
  4491.1     .07       0  4494.6    .035       0    4632     .12       0
  4991.5     .05       0  5033.6     .12       0  5144.7     .07       0
  5355.4    .035       0  5897.4     .07       0  6439.7     .12       0
Bank Sta=4991.5,5033.6
XS Rating Curve= 0 ,0
Exp/Cntr=0.3,0.1

Type RM Length L Ch R = 1 ,29249   ,540,540,540
BEGIN DESCRIPTION:
BLOCK CREEK 52.0
END DESCRIPTION:
XS GIS Cut Line= 3
      2021674.98       13927375.        2021025.       13927325.
      2020224.98     13927975.01
#Sta/Elev= 30
  4348.1 1543.42  4358.1 1542.29  4368.1 1541.58  4388.2 1533.94  4428.3 1524.09
  4488.9 1515.57  4548.7 1506.74  4568.7  1499.6  4598.8 1494.96  4618.9 1486.04
    4649 1486.35  4686.1 1482.48  4883.4 1474.57  4949.9 1468.63  4959.9 1463.06
  4969.9 1446.91  5000.5 1445.91  5001.5 1445.41  5042.6 1445.91  5050.3 1453.61
  5056.7 1454.19  5128.6 1456.84  5184.6 1461.93  5256.5 1463.07  5316.8 1469.96
  5476.7 1469.79  5661.5 1475.45  5852.6 1483.07    5974  1500.5  6030.8 1502.68
#Mann= 9 ,-1 , 0
  4348.1     .07       0  4358.1    .035       0  4488.9     .07       0
  4686.1     .12       0  4883.4     .07       0  5000.5     .05       0
  5042.6     .07       0  5316.8    .035       0  5661.5     .07       0
Bank Sta=5000.5,5042.6
XS Rating Curve= 0 ,0
Exp/Cntr=0.3,0.1