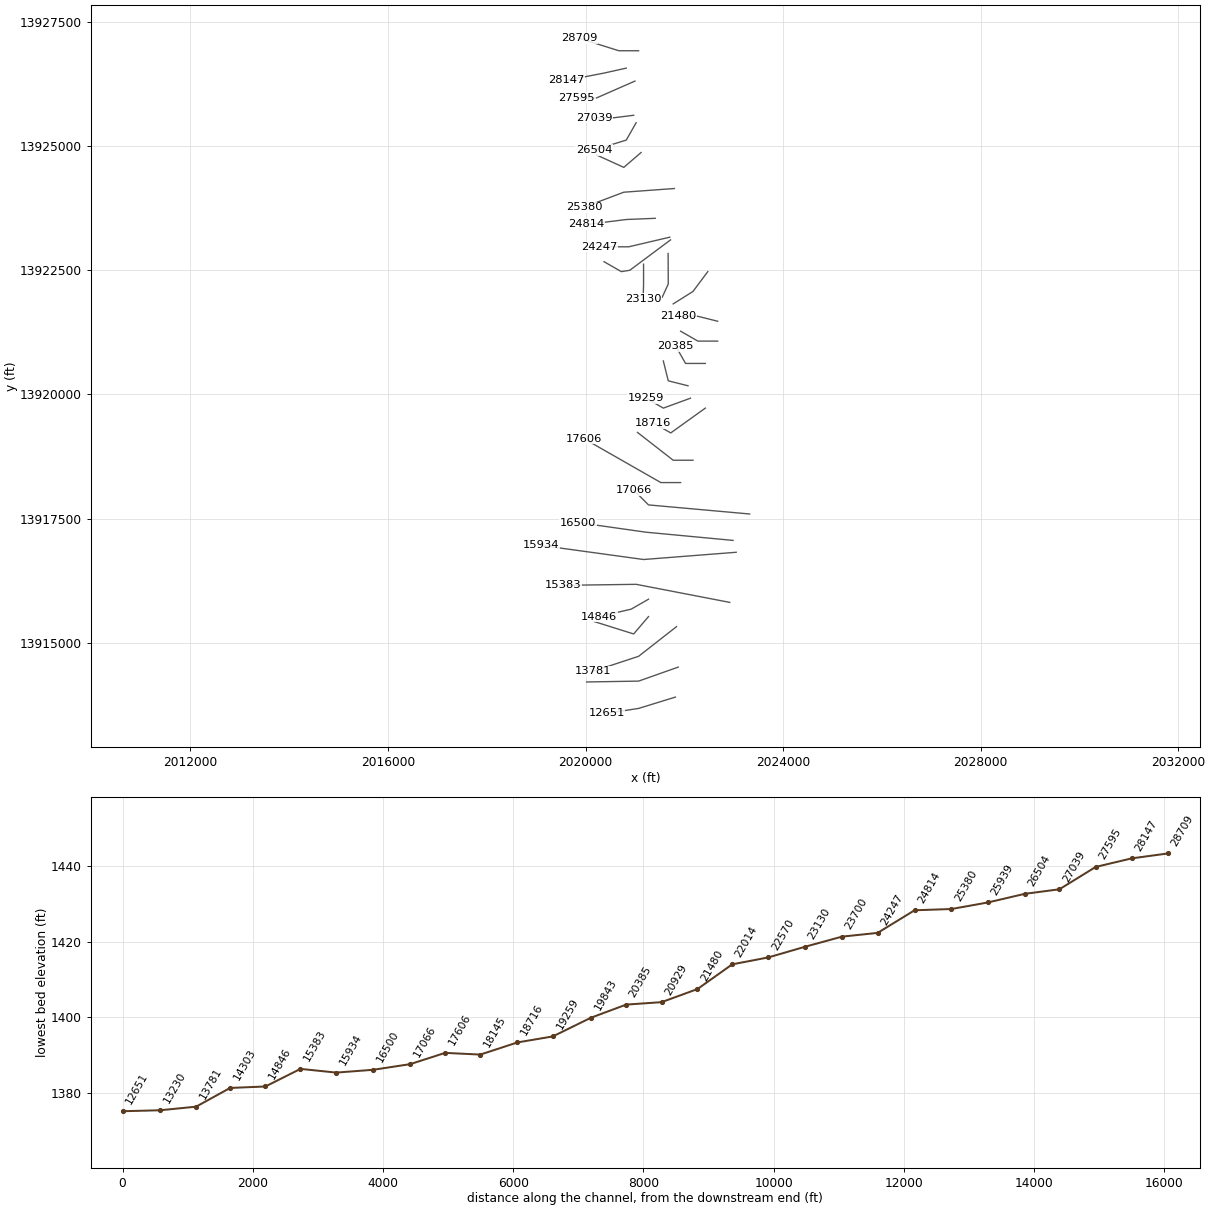
HEC-RAS study BLOCK CREEK.prj: BLOCK CREEK Base Level Engineering

--- BLOCK CREEK.g01 (geometry) --- (continued)

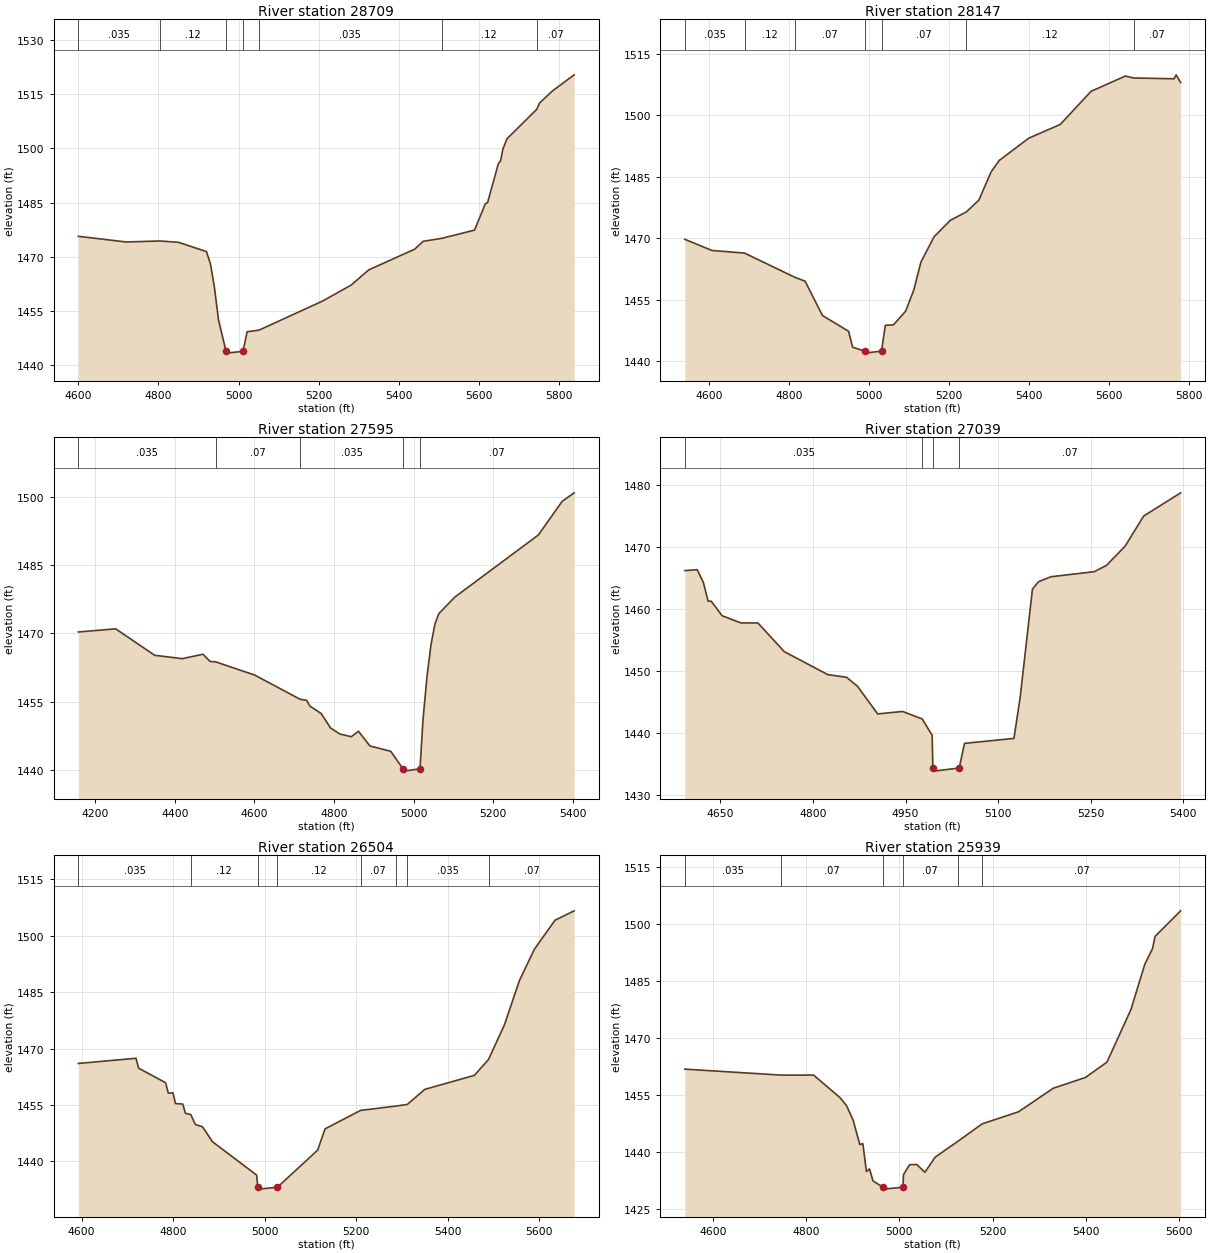
Type RM Length L Ch R = 1 ,28709   ,562,562,562
BEGIN DESCRIPTION:
BLOCK CREEK 51.0
END DESCRIPTION:
XS GIS Cut Line= 3
      2021074.97       13926925.        2020675.       13926925.
      2019875.02     13927174.99
#Sta/Elev= 30
    4600 1475.66    4720 1474.09  4803.2 1474.37    4850    1474    4920 1471.43
    4930    1468    4940 1461.39    4950 1452.58  4968.8 1443.85  4969.8 1443.35
  5011.2 1443.85  5021.5 1449.26  5051.2 1449.71  5209.5 1457.73  5281.3 1462.17
  5324.8 1466.35    5440 1472.11    5461 1474.27  5507.7  1475.1  5589.3 1477.37
  5616.5 1484.71  5621.8 1484.94    5649 1495.82  5654.3 1496.48    5660 1499.74
  5670.5 1502.65  5744.8 1510.78  5751.7 1512.52  5784.2  1515.9  5838.1 1520.32
#Mann= 7 ,-1 , 0
    4600    .035       0  4803.2     .12       0  4968.8     .05       0
  5011.2     .12       0  5051.2    .035       0  5507.7     .12       0
  5744.8     .07       0
Bank Sta=4968.8,5011.2
XS Rating Curve= 0 ,0
Exp/Cntr=0.3,0.1

Type RM Length L Ch R = 1 ,28147   ,552,552,552
BEGIN DESCRIPTION:
BLOCK CREEK 50.0
END DESCRIPTION:
XS GIS Cut Line= 3
      2020825.04     13926575.01        2020375.       13926475.
      2019609.34      13926327.8
#Sta/Elev= 30
    4539 1469.78  4606.9 1467.06  4688.4 1466.42  4815.7 1460.46    4840 1459.57
  4883.5  1451.2  4948.8 1447.36    4959 1443.48  4988.9 1442.53  4989.9 1442.03
  5031.4 1442.53  5040.7 1448.81  5061.1 1448.92  5091.7 1452.27    5112 1457.43
  5129.9 1464.24  5162.9 1470.42  5203.7 1474.43  5243.4 1476.44    5275 1479.36
  5305.5 1486.22  5325.9 1489.01  5399.8 1494.44  5478.6 1497.79  5555.6 1505.86
  5641.6 1509.59    5662 1509.11  5763.4 1508.92  5768.5 1509.88  5779.7 1507.99
#Mann= 7 ,-1 , 0
    4539    .035       0  4688.4     .12       0  4815.7     .07       0
  4988.9     .05       0  5031.4     .07       0  5243.4     .12       0
    5662     .07       0
Bank Sta=4988.9,5031.4
XS Rating Curve= 0 ,0
Exp/Cntr=0.3,0.1

Type RM Length L Ch R = 1 ,27595   ,556,556,556
BEGIN DESCRIPTION:
BLOCK CREEK 49.0
END DESCRIPTION:
XS GIS Cut Line= 3
      2021000.92     13926313.76        2020225.       13925975.
      2019825.04       13925975.
#Sta/Elev= 30
  4157.2 1470.29    4251 1470.99  4349.2 1465.18  4418.3 1464.44  4470.6 1465.41
  4488.5 1463.83  4502.3 1463.74  4600.1 1460.86  4714.6 1455.54  4731.1  1455.3
    4739 1454.07  4767.8  1452.4  4791.2 1449.24  4814.6 1447.91  4843.5 1447.31
  4861.5 1448.51  4890.3 1445.29  4942.6 1444.11  4973.6 1440.26  4974.6 1439.76
  5016.2 1440.26  5023.8 1451.08  5033.8 1460.49  5043.8 1467.46  5053.8 1472.08
  5063.8 1474.35  5103.8 1477.95  5313.8 1491.58  5373.8 1498.97  5403.8 1500.83
#Mann= 5 ,-1 , 0
  4157.2    .035       0  4502.3     .07       0  4714.6    .035       0
  4973.6     .05       0  5016.2     .07       0
Bank Sta=4973.6,5016.2
XS Rating Curve= 0 ,0
Exp/Cntr=0.3,0.1

Type RM Length L Ch R = 1 ,27039   ,535,535,535
BEGIN DESCRIPTION:
BLOCK CREEK 48.0
END DESCRIPTION:
XS GIS Cut Line= 3
      2020974.96     13925624.99        2020575.       13925575.
      2020174.97       13925575.
#Sta/Elev= 30
  4592.4 1466.21  4612.5 1466.36  4622.6 1464.26  4630.2 1461.27  4635.2 1461.27
  4652.8 1458.93  4683.1 1457.77  4710.8 1457.76  4753.6 1453.13  4824.1 1449.42
  4854.4 1448.99    4872 1447.56  4904.8 1443.08  4945.1 1443.48    4977 1442.27
    4993 1439.64  4994.2 1434.35  4995.2 1433.85  5036.8 1434.35  5045.5 1438.33
  5125.5 1439.13  5135.5 1445.66  5155.5 1463.22  5165.5 1464.43  5185.5 1465.22
  5255.5 1466.03  5275.5 1467.06  5305.5 1470.14  5335.5    1475  5395.5 1478.76
#Mann= 4 ,-1 , 0
  4592.4    .035       0    4977     .07       0  4994.2     .05       0
  5036.8     .07       0
Bank Sta=4994.2,5036.8
XS Rating Curve= 0 ,0
Exp/Cntr=0.3,0.1

Type RM Length L Ch R = 1 ,26504   ,565,565,565
BEGIN DESCRIPTION:
BLOCK CREEK 47.0
END DESCRIPTION:
XS GIS Cut Line= 3
      2021024.99     13925474.99        2020825.       13925125.
      2020174.97     13924924.99
#Sta/Elev= 30
  4592.8 1466.06  4718.8 1467.44  4724.5  1464.8  4783.5 1460.93  4789.3 1458.18
  4799.4 1458.25  4805.1 1455.39    4821 1455.25  4826.7 1452.81  4838.4 1452.48
  4848.3 1449.85  4864.2 1449.19  4885.8 1445.24  4982.2 1436.38    4985 1433.13
    4986 1432.63  5027.7 1433.13  5115.6    1443  5131.9 1448.67  5209.4 1453.57
  5286.8 1454.73  5311.6 1455.17  5349.7 1459.17  5458.2  1462.9  5488.9 1467.12
  5523.6 1476.32  5556.3 1488.07    5589 1496.41  5634.1 1504.16    5676 1506.66
#Mann= 8 ,-1 , 0
  4592.8    .035       0  4838.4     .12       0    4985     .05       0
  5027.7     .12       0  5209.4     .07       0  5286.8     .12       0
  5311.6    .035       0  5488.9     .07       0
Bank Sta=4985,5027.7
XS Rating Curve= 0 ,0
Exp/Cntr=0.3,0.1

Type RM Length L Ch R = 1 ,25939   ,559,559,559
BEGIN DESCRIPTION:
BLOCK CREEK 46.0
END DESCRIPTION:
XS GIS Cut Line= 3
      2021125.03     13924875.03        2020775.       13924575.
      2020224.97     13924825.01
#Sta/Elev= 30
  4538.9 1461.87  4746.4  1460.3  4815.5 1460.31  4872.1 1454.42  4886.3 1452.31
  4900.6 1448.44  4914.9 1442.06  4921.4 1442.31  4929.1 1434.98  4935.7 1435.65
  4943.4 1432.49  4964.8 1430.85  4965.8 1430.35  5007.5 1430.85  5008.7 1434.15
  5021.9 1436.77  5037.3 1436.81  5054.8 1434.79  5076.8 1438.75  5125.1 1442.87
  5177.8  1447.5  5255.9 1450.67  5330.6 1456.86  5399.8 1459.69  5445.9 1463.72
  5497.5 1477.58  5527.2 1489.45  5543.7 1493.51  5549.1 1496.73  5604.1 1503.46
#Mann= 6 ,-1 , 0
  4538.9    .035       0  4746.4     .07       0  4964.8     .05       0
  5007.5     .07       0  5125.1     .12       0  5177.8     .07       0
Bank Sta=4964.8,5007.5
XS Rating Curve= 0 ,0
Exp/Cntr=0.3,0.1

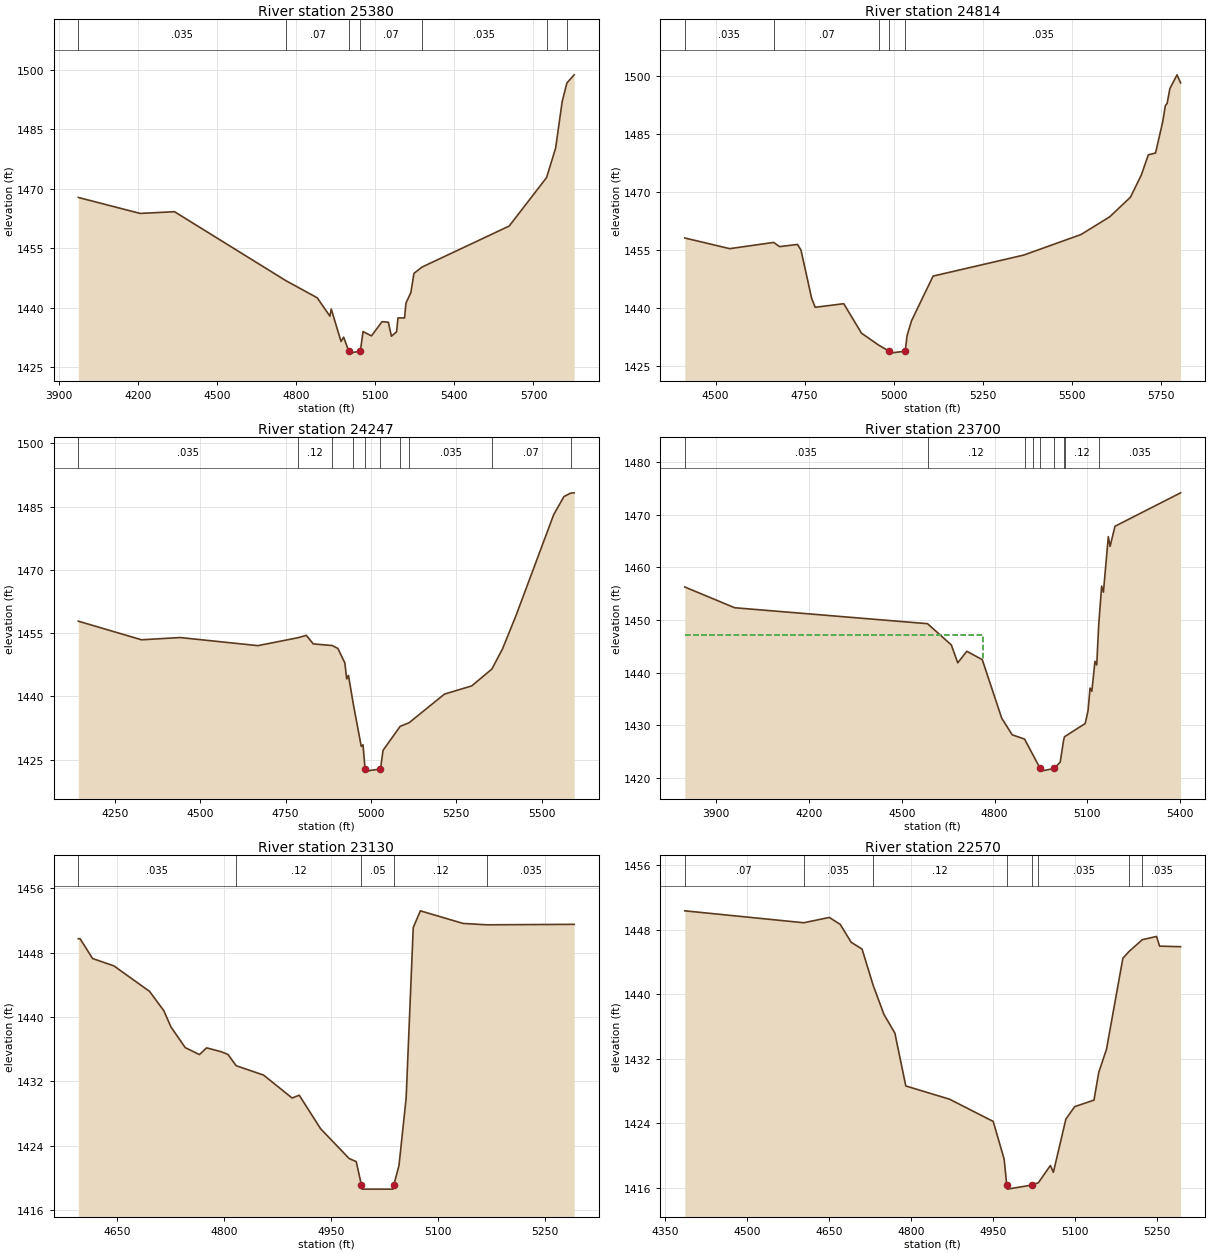
Type RM Length L Ch R = 1 ,25380   ,566,566,566
BEGIN DESCRIPTION:
BLOCK CREEK 45.0
END DESCRIPTION:
XS GIS Cut Line= 3
      2021799.01     13924149.28        2020775.       13924075.
        2019975.       13923775.
#Sta/Elev= 30
  3973.3 1467.83  4207.9 1463.81  4338.3 1464.24  4761.1 1446.86  4879.7 1442.55
  4927.8 1437.93  4932.9 1439.72  4969.9 1431.56  4979.9 1432.64  4999.4 1429.12
  5000.4 1428.62  5043.3 1429.12  5053.4 1434.05  5085.4 1432.97  5125.5 1436.54
  5149.5 1436.41  5161.1 1432.88  5180.7 1433.99    5186 1437.49  5210.9 1437.48
  5216.3 1441.21    5235  1443.9  5246.5  1448.7  5277.3  1450.3  5607.9 1460.63
  5749.7 1472.83  5784.1 1480.27    5809    1492  5826.8 1496.67  5854.4 1498.72
#Mann= 7 ,-1 , 0
  3973.3    .035       0  4761.1     .07       0  4999.4     .05       0
  5043.3     .07       0  5277.3    .035       0  5749.7     .07       0
  5826.8    .035       0
Bank Sta=4999.4,5043.3
XS Rating Curve= 0 ,0
Exp/Cntr=0.3,0.1

Type RM Length L Ch R = 1 ,24814   ,567,567,567
BEGIN DESCRIPTION:
BLOCK CREEK 44.0
END DESCRIPTION:
XS GIS Cut Line= 3
      2021411.01     13923548.99        2020825.       13923525.
      2020025.02       13923425.
#Sta/Elev= 30
  4413.5 1458.07  4539.6 1455.31  4663.2 1456.92  4679.7 1455.83  4729.8  1456.4
  4739.8 1454.97  4769.8 1442.46  4779.8 1440.14  4859.9 1441.07  4909.9 1433.43
  4958.8 1430.31  4987.5 1428.78  4988.5 1428.28  5032.6 1428.78  5037.8 1432.79
  5050.4 1436.66  5110.9 1448.21  5365.3 1453.64  5526.6 1458.97  5607.2 1463.56
  5665.1  1468.6  5695.4 1474.27  5715.5 1479.58  5735.7 1480.05  5755.8 1488.09
  5763.4 1492.34  5768.4  1492.9    5776  1496.7  5796.1 1500.28  5806.2 1498.19
#Mann= 5 ,-1 , 0
  4413.5    .035       0  4663.2     .07       0  4958.8    .035       0
  4987.5    .035       0  5032.6    .035       0
Bank Sta=4987.5,5032.6
XS Rating Curve= 0 ,0
Exp/Cntr=0.3,0.1

Type RM Length L Ch R = 1 ,24247   ,547,547,547
BEGIN DESCRIPTION:
BLOCK CREEK 43.0
END DESCRIPTION:
XS GIS Cut Line= 3
      2021705.39     13923168.91        2020875.       13922975.
      2020275.03       13922975.
#Sta/Elev= 30
  4142.7 1457.84  4327.9 1453.43  4440.8 1453.96  4668.8 1452.04  4785.8 1453.91
  4810.6 1454.48  4831.1 1452.45  4886.3 1452.07    4903 1451.39  4923.5 1447.96
  4929.1 1444.15  4934.2 1444.99  4948.6 1438.07  4971.6 1428.17  4976.7 1428.54
  4982.9 1422.79  4983.9 1422.29    5028 1422.79  5035.4 1427.21  5085.6  1432.9
  5111.7 1433.76  5215.4 1440.55  5295.4  1442.5  5354.3 1446.49  5385.4 1451.25
  5425.4 1459.25  5535.4 1483.09  5565.4 1487.38  5584.8 1488.19  5595.4 1488.27
#Mann= 10 ,-1 , 0
  4142.7    .035       0  4785.8     .12       0  4886.3    .035       0
  4948.6     .12       0  4982.9    .035       0    5028     .12       0
  5085.6     .12       0  5111.7    .035       0  5354.3     .07       0
  5584.8    .035       0
Bank Sta=4982.9,5028
XS Rating Curve= 0 ,0
Exp/Cntr=0.3,0.1

Type RM Length L Ch R = 1 ,23700   ,570,570,570
BEGIN DESCRIPTION:
BLOCK CREEK 42.0
END DESCRIPTION:
XS GIS Cut Line= 4
       2021721.7     13923114.46      2020896.17     13922502.09
        2020725.       13922475.      2020374.97     13922675.01
#Sta/Elev= 30
  3797.9 1456.28  3959.2 1452.34  4583.3 1449.31  4660.3 1445.28  4681.1 1441.87
  4710.3 1444.07  4760.4 1442.48  4823.4 1431.35  4857.3  1428.2  4897.2 1427.39
    4923 1424.54  4947.9  1421.8  4948.9  1421.3    4993  1421.8  5012.7 1423.03
  5023.5 1427.17  5026.6 1427.84  5093.4 1430.34  5102.7 1432.81  5109.2 1437.08
    5115 1436.47    5125 1442.16  5130.8 1441.47  5136.9 1448.82  5146.6 1456.44
  5152.4  1455.3  5168.2 1465.84    5174    1464  5189.8 1467.82  5402.2 1474.17
#Mann= 9 ,-1 , 0
  3797.9    .035       0  4583.3     .12       0  4897.2    .035       0
    4923     .12       0  4947.9     .05       0    4993     .12       0
  5023.5    .035       0  5026.6     .12       0  5136.9    .035       0
#XS Ineff= 2 , 0
       0 4761.91 1447.08               0
Permanent Ineff=
       F       F
Bank Sta=4947.9,4993
XS Rating Curve= 0 ,0
Exp/Cntr=0.3,0.1

Type RM Length L Ch R = 1 ,23130   ,560,560,560
BEGIN DESCRIPTION:
BLOCK CREEK 41.0
END DESCRIPTION:
XS GIS Cut Line= 3
        2021175.     13922624.96        2021175.       13922225.
      2021166.78     13921929.27
#Sta/Elev= 30
  4595.5 1449.75    4598 1449.75  4615.5 1447.29  4645.5 1446.37  4695.5  1443.2
  4715.5  1440.8  4725.5 1438.78  4745.5 1436.21  4765.5 1435.34  4775.5 1436.18
  4795.5 1435.71  4805.5 1435.36    4817 1433.96  4855.5 1432.79  4895.5 1429.94
  4905.5 1430.29  4935.5 1426.12  4975.5 1422.42  4985.5 1422.03  4992.8 1419.11
  4993.8 1418.61  5037.2 1418.61  5038.2 1419.11  5045.5 1421.56  5055.5 1429.91
  5065.5 1451.14  5075.5 1453.22  5135.5 1451.65    5169 1451.48  5291.3 1451.54
#Mann= 5 ,-1 , 0
  4595.5    .035       0    4817     .12       0  4992.8     .05       0
  5038.2     .12       0    5169    .035       0
Bank Sta=4992.8,5038.2
XS Rating Curve= 0 ,0
Exp/Cntr=0.3,0.1

Type RM Length L Ch R = 1 ,22570   ,556,556,556
BEGIN DESCRIPTION:
BLOCK CREEK 40.0
END DESCRIPTION:
XS GIS Cut Line= 3
      2021672.33      13922839.5        2021675.       13922225.
      2021551.99     13921959.08
#Sta/Elev= 30
  4385.4 1450.33  4603.1 1448.85  4649.9 1449.51  4669.9 1448.65  4689.9 1446.43
  4709.9 1445.58  4730.1  1441.1  4749.9 1437.48  4769.9 1435.16  4789.9  1428.6
  4869.9 1426.96  4949.9  1424.2  4969.9 1419.52  4974.7  1416.3  4975.7  1415.8
  5020.2  1416.3  5032.6  1416.6  5054.5 1418.73    5060 1417.89  5082.9 1424.49
  5099.1 1426.04  5134.3 1426.84  5143.1  1430.3  5157.2 1433.15  5187.2 1444.44
  5198.5 1445.29  5222.8 1446.75  5248.9 1447.15  5254.4 1445.95  5292.9 1445.88
#Mann= 8 ,-1 , 0
  4385.4     .07       0  4603.1    .035       0  4730.1     .12       0
  4974.7     .05       0  5020.2     .12       0  5032.6    .035       0
  5198.5     .07       0  5222.8    .035       0
Bank Sta=4974.7,5020.2
XS Rating Curve= 0 ,0
Exp/Cntr=0.3,0.1

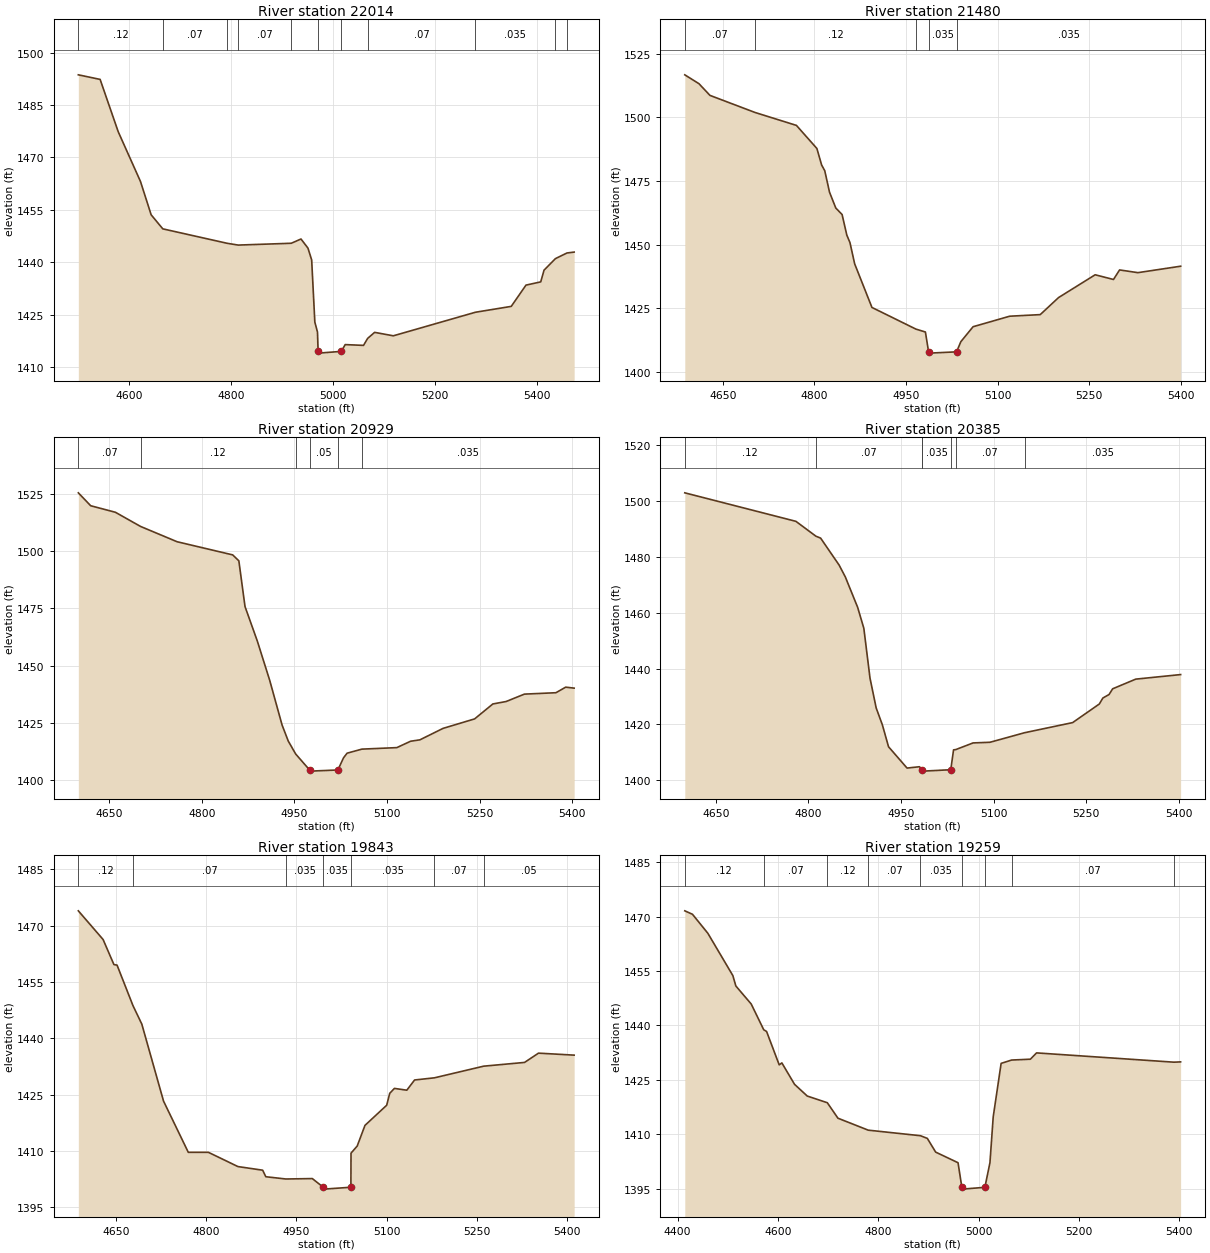
Type RM Length L Ch R = 1 ,22014   ,534,534,534
BEGIN DESCRIPTION:
BLOCK CREEK 39.0
END DESCRIPTION:
XS GIS Cut Line= 3
      2022474.98     13922474.97        2022175.       13922075.
      2021774.97     13921824.98
#Sta/Elev= 30
  4500.5 1493.68  4543.2 1492.37  4578.6 1477.41  4622.3 1463.13  4643.2 1453.59
    4666 1449.56  4791.9 1445.43  4813.7 1444.91  4917.8 1445.43  4936.9 1446.65
  4950.5 1444.05  4957.8 1440.65    4964 1422.84  4969.2 1419.98  4970.4 1414.46
  4971.4 1413.96  5015.9 1414.46  5023.5  1416.4  5059.4 1416.18  5067.5 1418.18
  5081.2 1419.91  5117.8 1418.92  5278.7 1425.67  5348.9 1427.35  5377.8 1433.44
  5406.7 1434.37  5413.2 1437.73  5435.5 1441.03  5458.2 1442.65  5472.2  1442.9
#Mann= 11 ,-1 , 0
  4500.5     .12       0    4666     .07       0  4791.9    .035       0
  4813.7     .07       0  4917.8     .12       0  4970.4     .05       0
  5015.9     .12       0  5067.5     .07       0  5278.7    .035       0
  5435.5     .07       0  5458.2    .035       0
Bank Sta=4970.4,5015.9
XS Rating Curve= 0 ,0
Exp/Cntr=0.3,0.1

Type RM Length L Ch R = 1 ,21480   ,551,551,551
BEGIN DESCRIPTION:
BLOCK CREEK 38.0
END DESCRIPTION:
XS GIS Cut Line= 3
      2022674.97     13921475.01        2022275.       13921575.
      2021874.98       13921575.
#Sta/Elev= 30
  4587.7  1516.7  4610.9 1513.22  4628.9 1508.63  4702.7 1501.92  4770.6 1496.84
  4804.1 1487.77  4811.9 1481.27    4817 1479.04  4824.8 1470.61  4835.1 1464.39
  4845.4 1461.84  4853.1 1453.78  4858.3  1450.8    4866 1442.47  4894.3 1425.35
  4966.3 1416.85  4981.9  1415.7  4987.1 1407.91  4988.1 1407.41  5032.9 1407.91
    5040 1411.92    5060 1417.78    5120 1421.91    5170 1422.53    5200 1429.22
    5260 1438.18    5290 1436.33    5300 1440.08    5330 1439.01    5400 1441.54
#Mann= 5 ,-1 , 0
  4587.7     .07       0  4702.7     .12       0  4966.3    .035       0
  4987.1    .035       0  5032.9    .035       0
Bank Sta=4987.1,5032.9
XS Rating Curve= 0 ,0
Exp/Cntr=0.3,0.1

Type RM Length L Ch R = 1 ,20929   ,544,544,544
BEGIN DESCRIPTION:
BLOCK CREEK 37.0
END DESCRIPTION:
XS GIS Cut Line= 3
      2022675.01       13921075.        2022275.       13921075.
      2021925.02     13921274.99
#Sta/Elev= 30
    4600 1525.52    4620 1519.88    4660 1517.03  4700.9 1510.82    4760 1504.15
    4850 1498.41    4860 1495.82    4870 1475.82    4890  1460.7    4910 1443.58
    4930  1424.1    4940  1417.1    4952 1411.44  4974.6 1404.44  4975.6 1403.94
  5020.4 1404.44  5029.5 1409.73  5035.3 1411.78  5059.3 1413.55  5115.9 1414.21
  5138.2    1417  5153.3 1417.61  5190.8 1422.62  5241.9 1426.76  5271.4 1433.28
    5293 1434.36  5322.5 1437.58  5373.6 1438.19  5389.4 1440.62  5403.1  1440.2
#Mann= 6 ,-1 , 0
    4600     .07       0  4700.9     .12       0    4952     .07       0
  4974.6     .05       0  5020.4     .07       0  5059.3    .035       0
Bank Sta=4974.6,5020.4
XS Rating Curve= 0 ,0
Exp/Cntr=0.3,0.1

Type RM Length L Ch R = 1 ,20385   ,542,542,542
BEGIN DESCRIPTION:
BLOCK CREEK 36.0
END DESCRIPTION:
XS GIS Cut Line= 3
      2022425.03       13920625.        2022025.       13920625.
      2021825.02     13920974.96
#Sta/Elev= 30
  4599.9 1502.85  4779.9 1492.65  4812.3 1487.33  4819.9 1486.65  4849.9 1476.99
  4859.9 1472.77  4879.9 1461.87  4889.9 1454.39  4899.9 1436.54  4909.9 1425.88
  4919.9 1419.86  4929.9 1412.01  4959.9 1404.38  4979.9 1404.86  4983.5 1404.09
  4984.9 1403.79  4985.9 1403.29  5030.7 1403.79  5035.2 1410.89    5039 1411.01
  5066.9 1413.38  5094.2 1413.61  5150.3 1417.03  5228.1 1420.65  5271.3  1427.3
  5277.1 1429.45  5287.1  1430.7  5292.9 1432.74  5330.3  1436.2    5403 1437.83
#Mann= 7 ,-1 , 0
  4599.9     .12       0  4812.3     .07       0  4983.5    .035       0
  4984.9    .035       0  5030.7    .035       0    5039     .07       0
  5150.3    .035       0
Bank Sta=4984.9,5030.7
XS Rating Curve= 0 ,0
Exp/Cntr=0.3,0.1

Type RM Length L Ch R = 1 ,19843   ,584,584,584
BEGIN DESCRIPTION:
BLOCK CREEK 35.0
END DESCRIPTION:
XS GIS Cut Line= 3
      2022074.96     13920175.01        2021675.       13920275.
      2021574.99     13920675.02
#Sta/Elev= 30
  4587.2 1473.94  4628.4  1466.3  4646.4 1459.62  4651.6 1459.48  4678.1 1448.68
  4692.8 1443.76  4728.9 1423.26  4770.1 1409.61  4803.6 1409.61  4852.6 1405.82
  4893.8 1404.85    4899 1403.11  4932.4 1402.51  4976.3 1402.62  4994.6 1400.31
  4995.6 1399.81  5040.5 1400.31  5040.7 1409.39    5051 1411.29  5063.9 1416.79
    5100 1422.15  5105.1 1425.33  5112.9 1426.64  5133.5 1426.16  5146.4 1428.88
  5179.5 1429.46  5261.3 1432.56  5329.3 1433.56  5352.5 1436.03  5411.8  1435.5
#Mann= 7 ,-1 , 0
  4587.2     .12       0  4678.1     .07       0  4932.4    .035       0
  4994.6    .035       0  5040.5    .035       0  5179.5     .07       0
  5261.3     .05       0
Bank Sta=4994.6,5040.5
XS Rating Curve= 0 ,0
Exp/Cntr=0.3,0.1

Type RM Length L Ch R = 1 ,19259   ,543,543,543
BEGIN DESCRIPTION:
BLOCK CREEK 34.0
END DESCRIPTION:
XS GIS Cut Line= 3
      2022125.02     13919925.01        2021575.       13919725.
      2021224.97     13919925.02
#Sta/Elev= 30
  4414.3 1471.61  4429.6 1470.66  4460.2 1465.43  4510.1 1453.75  4516.1 1450.88
  4546.7 1445.91  4571.7  1438.8  4577.3 1438.35  4602.5 1429.13  4607.8 1429.67
  4633.1 1423.76  4658.4 1420.53  4698.4 1418.69  4719.6 1414.42    4780 1411.12
  4884.1 1409.59  4897.8 1408.85  4914.4 1405.07    4959 1402.14  4966.6 1395.36
  4967.6 1394.86  5012.5 1395.36  5022.6 1402.15  5029.1 1414.78  5044.9 1429.54
  5065.9 1430.46  5103.2 1430.69  5115.5 1432.43  5389.4 1429.87  5402.7 1429.95
#Mann= 9 ,-1 , 0
  4414.3     .12       0  4571.7     .07       0  4698.4     .12       0
    4780     .07       0  4884.1    .035       0  4966.6    .035       0
  5012.5    .035       0  5065.9     .07       0  5389.4     .05       0
Bank Sta=4966.6,5012.5
XS Rating Curve= 0 ,0
Exp/Cntr=0.3,0.1

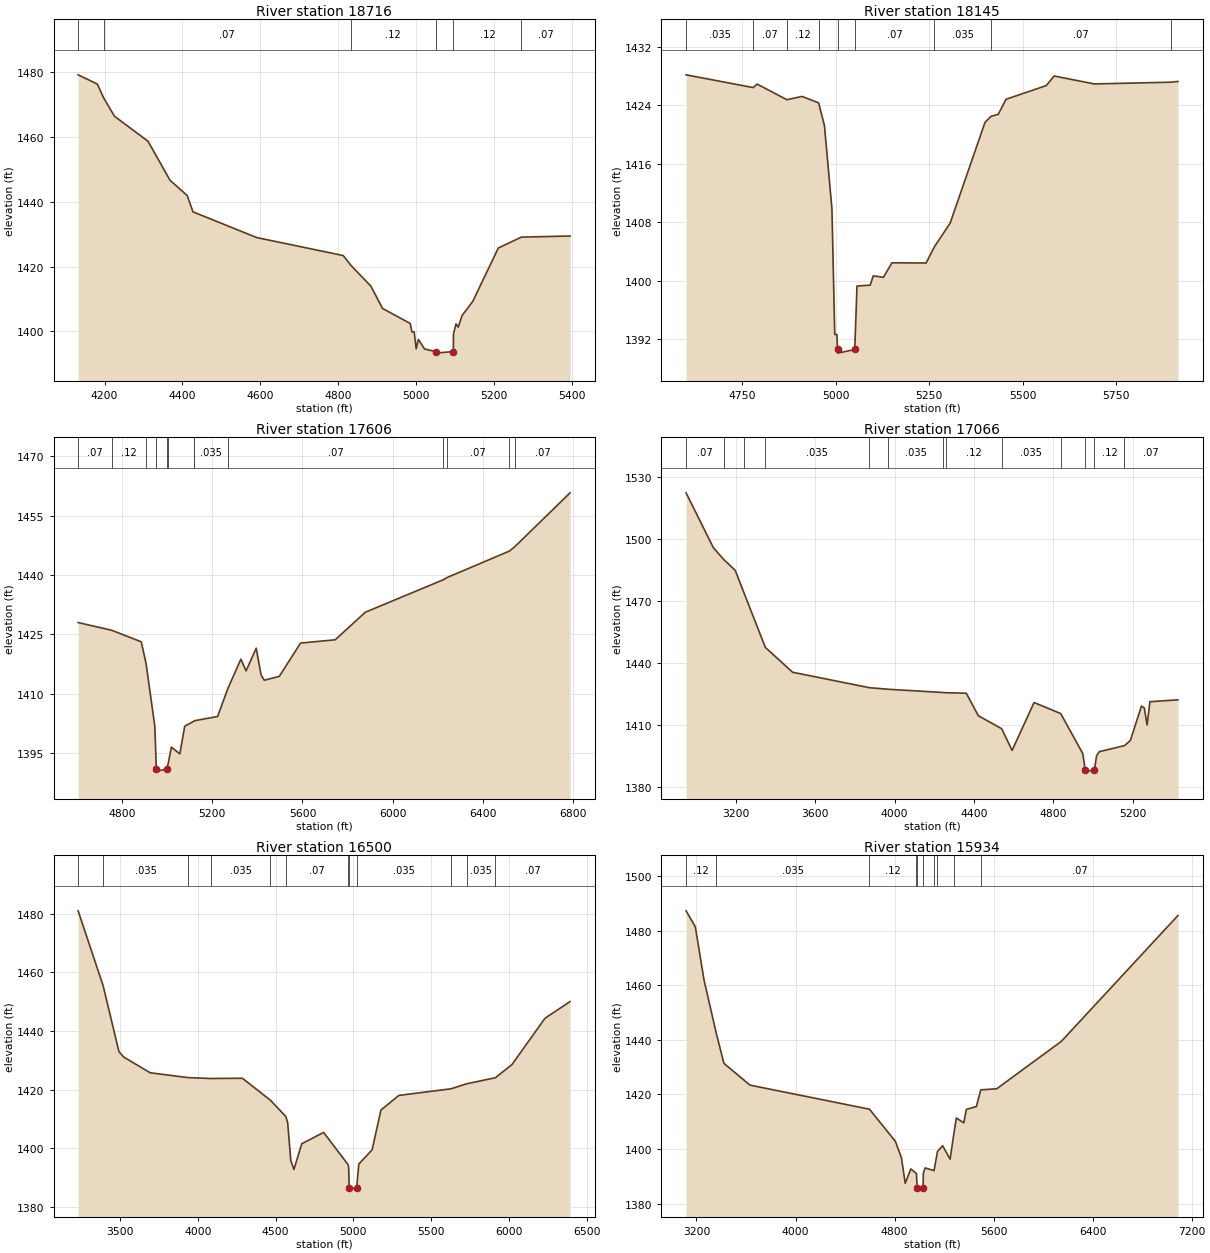
Type RM Length L Ch R = 1 ,18716   ,571,571,571
BEGIN DESCRIPTION:
BLOCK CREEK 33.0
END DESCRIPTION:
XS GIS Cut Line= 3
      2022425.02     13919725.02        2021725.       13919225.
      2021374.98     13919425.01
#Sta/Elev= 30
  4132.1  1479.2  4181.3 1476.36  4197.8 1472.04  4225.5  1466.4  4311.5  1458.7
  4368.1 1446.65  4412.3 1441.92  4427.1 1436.89  4590.5 1428.96  4812.9  1423.4
  4832.6 1420.38  4884.2 1413.92  4913.7 1407.08    4985 1402.43  4989.3 1399.82
  4995.2 1399.82  5000.3 1394.61    5006  1397.5  5021.9 1394.53    5050 1393.77
    5051 1393.27  5095.9 1393.77    5096 1399.08  5102.5  1402.3  5108.3  1401.3
  5118.3  1404.9  5145.7 1409.26  5211.2 1425.72  5270.4 1429.09  5395.5 1429.43
#Mann= 6 ,-1 , 0
  4132.1     .12       0  4197.8     .07       0  4832.6     .12       0
    5050     .05       0  5095.9     .12       0  5270.4     .07       0
Bank Sta=5050,5095.9
XS Rating Curve= 0 ,0
Exp/Cntr=0.3,0.1

Type RM Length L Ch R = 1 ,18145   ,539,539,539
BEGIN DESCRIPTION:
BLOCK CREEK 32.0
END DESCRIPTION:
XS GIS Cut Line= 3
      2022174.99       13918675.        2021775.       13918675.
      2021051.79     13919235.55
#Sta/Elev= 30
  4600.4 1428.19  4779.9 1426.44  4790.4 1426.92  4870.1 1424.78  4910.4 1425.23
  4954.8 1424.35  4970.4 1421.23  4990.4 1409.83  4997.9 1392.61  5003.6 1392.61
  5005.4 1390.55  5006.4 1390.05  5051.4 1390.55  5057.4 1399.24  5092.7 1399.37
  5100.9 1400.64    5128 1400.44  5150.7 1402.43  5242.1  1402.4  5264.2 1404.61
  5306.4 1407.87  5399.6 1421.68  5416.2 1422.52  5434.9 1422.77  5455.9 1424.84
  5563.5 1426.72  5584.3 1428.03    5692 1426.94  5896.4 1427.18  5915.4 1427.28
#Mann= 9 ,-1 , 0
  4600.4    .035       0  4779.9     .07       0  4870.1     .12       0
  4954.8     .07       0  5005.4     .05       0  5051.4     .07       0
  5264.2    .035       0  5416.2     .07       0  5896.4     .05       0
Bank Sta=5005.4,5051.4
XS Rating Curve= 0 ,0
Exp/Cntr=0.3,0.1

Type RM Length L Ch R = 1 ,17606   ,540,540,540
BEGIN DESCRIPTION:
BLOCK CREEK 31.0
END DESCRIPTION:
XS GIS Cut Line= 3
      2021924.96       13918225.        2021525.       13918225.
      2019975.71     13919105.74
#Sta/Elev= 30
  4604.8 1428.02  4754.5 1426.05  4884.8 1423.15  4906.1 1417.67  4944.8 1401.91
  4951.8    1391  4952.8  1390.5  4997.8    1391  5004.7 1392.53  5018.4 1396.56
  5055.9 1394.85  5077.6 1401.85  5116.8 1403.04  5120.1 1403.22  5223.3 1404.29
  5269.2 1411.38  5326.8 1418.78  5349.8 1415.81  5394.7 1421.54  5416.3  1414.8
  5430.4 1413.45  5497.1 1414.43  5591.4 1422.83    5745 1423.66    5879 1430.63
  6224.6 1438.82  6240.8 1439.37  6517.8 1446.06  6541.5 1447.15  6786.9 1460.77
#Mann= 13 ,-1 , 0
  4604.8     .07       0  4754.5     .12       0  4906.1     .07       0
  4951.8     .05       0  4997.8     .07       0  5004.7     .12       0
  5116.8     .07       0  5120.1    .035       0  5269.2     .07       0
  6224.6     .12       0  6240.8     .07       0  6517.8     .12       0
  6541.5     .07       0
Bank Sta=4951.8,4997.8
XS Rating Curve= 0 ,0
Exp/Cntr=0.3,0.1

Type RM Length L Ch R = 1 ,17066   ,566,566,566
BEGIN DESCRIPTION:
BLOCK CREEK 30.0
END DESCRIPTION:
XS GIS Cut Line= 3
        2023322.     13917591.89        2021275.       13917775.
      2020975.03     13918074.97
#Sta/Elev= 30
  2949.1 1522.31  3086.6 1495.78  3138.8 1490.02  3197.1 1484.75  3243.7 1473.21
  3348.8 1447.44  3486.1 1435.41  3873.1 1427.93  3968.6 1427.16  4242.1  1425.6
  4259.3 1425.48  4361.7 1425.24    4422 1414.38  4539.8 1408.06  4592.6 1397.56
  4703.1 1420.73  4837.5  1415.4  4948.6 1396.02    4961 1388.01    4962 1387.51
  5007.3 1388.01  5018.4 1395.04  5032.6 1396.95  5158.7 1399.86  5188.1 1402.26
  5244.7 1419.03  5258.8 1418.12    5273 1409.85  5287.1 1421.13  5428.5 1422.05
#Mann= 13 ,-1 , 0
  2949.1     .07       0  3138.8     .12       0  3243.7     .07       0
  3348.8    .035       0  3873.1     .07       0  3968.6    .035       0
  4242.1     .07       0  4259.3     .12       0  4539.8    .035       0
  4837.5     .12       0    4961    .035       0  5007.3     .12       0
  5158.7     .07       0
Bank Sta=4961,5007.3
XS Rating Curve= 0 ,0
Exp/Cntr=0.3,0.1

Type RM Length L Ch R = 1 ,16500   ,566,566,566
BEGIN DESCRIPTION:
BLOCK CREEK 29.0
END DESCRIPTION:
XS GIS Cut Line= 3
      2022986.37      13917059.8        2021225.       13917225.
      2019845.13     13917420.16
#Sta/Elev= 30
  3230.9 1480.96  3391.1  1455.5  3493.4 1432.93  3523.5 1431.09  3694.3 1425.71
  3937.8 1424.06  4083.8 1423.76  4286.9 1423.84  4467.6 1416.33  4566.9 1410.75
  4578.2 1408.63  4598.2 1395.76  4618.3 1392.72  4668.6 1401.51  4809.2 1405.37
  4964.1 1394.54  4969.9 1393.78  4973.6 1386.52  4974.6 1386.02  5021.3 1386.52
  5035.5 1394.58  5121.2 1399.45  5177.6 1412.98  5292.9 1417.99  5629.8 1420.26
  5727.8 1421.95  5913.1 1424.01  6020.1 1428.51  6232.1 1444.29  6393.6    1450
#Mann= 12 ,-1 , 0
  3230.9     .12       0  3391.1    .035       0  3937.8     .07       0
  4083.8    .035       0  4467.6     .12       0  4566.9     .07       0
  4964.1    .035       0  4973.6    .035       0  5021.3    .035       0
  5629.8     .07       0  5727.8    .035       0  5913.1     .07       0
Bank Sta=4973.6,5021.3
XS Rating Curve= 0 ,0
Exp/Cntr=0.3,0.1

Type RM Length L Ch R = 1 ,15934   ,551,551,551
BEGIN DESCRIPTION:
BLOCK CREEK 28.0
END DESCRIPTION:
XS GIS Cut Line= 3
       2023049.9     13916820.82        2021175.       13916675.
      2019101.28     13916958.71
#Sta/Elev= 30
  3115.6 1487.31  3190.7 1481.47  3260.9 1461.94  3358.6 1442.65  3421.4 1431.39
  3632.1 1423.41  4597.3 1414.58  4806.7  1402.8  4855.7 1396.73  4885.8 1387.45
  4931.3 1392.68  4976.6 1390.99  4982.4 1385.78  4983.4 1385.28  5030.2 1385.78
  5032.3 1391.16  5046.6 1393.06  5118.8 1392.05  5146.6 1399.06  5187.9  1401.2
  5248.5 1396.26  5279.7 1405.82    5299 1411.36  5359.5 1409.58  5379.7 1414.51
  5460.5 1415.54  5496.3 1421.68  5625.1 1422.07  6146.8 1439.44  7089.2 1485.61
#Mann= 10 ,-1 , 0
  3115.6     .12       0  3358.6    .035       0  4597.3     .12       0
  4976.6     .07       0  4982.4     .05       0  5030.2     .07       0
  5118.8     .12       0  5146.6     .07       0  5279.7    .035       0
  5496.3     .07       0
Bank Sta=4982.4,5030.2
XS Rating Curve= 0 ,0
Exp/Cntr=0.3,0.1

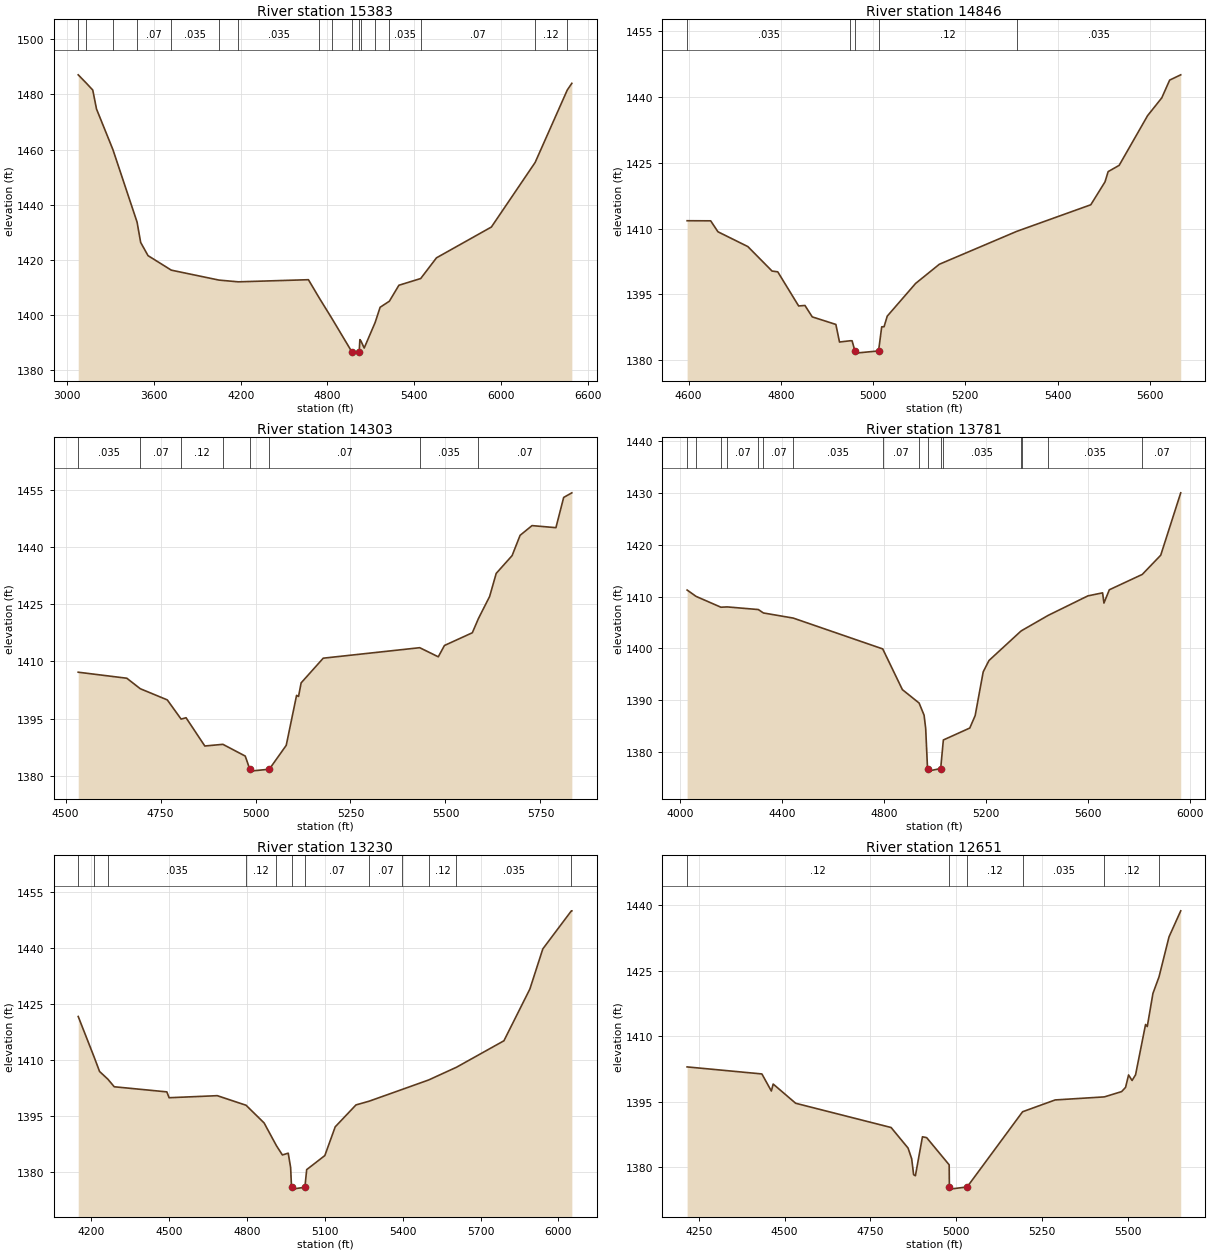
Type RM Length L Ch R = 1 ,15383   ,537,537,537
BEGIN DESCRIPTION:
BLOCK CREEK 27.0
END DESCRIPTION:
XS GIS Cut Line= 3
      2022919.31     13915811.12        2021025.       13916175.
      2019538.38      13916154.5
#Sta/Elev= 30
  3075.3 1487.05  3130.6 1484.08  3175.9 1481.53  3201.9 1474.67  3315.3 1459.98
  3482.6  1433.7  3507.4 1426.35  3558.3 1421.57  3719.3 1416.31  4049.5 1412.71
  4183.1 1412.08  4668.2 1412.85  4744.3 1406.14  4830.1 1398.87  4968.5 1386.76
  4969.5 1386.26  5019.7 1386.76  5024.2 1391.15  5031.4  1390.7  5054.2 1388.11
  5129.9 1397.36  5164.3 1402.86  5228.5 1405.07  5294.3 1410.84  5445.2 1413.28
  5554.3 1420.77  5934.3 1431.93  6237.1 1455.32  6459.6 1481.57    6491 1483.98
#Mann= 17 ,-1 , 0
  3075.3     .07       0  3130.6    .035       0  3315.3     .12       0
  3482.6     .07       0  3719.3    .035       0  4049.5     .07       0
  4183.1    .035       0  4744.3     .07       0  4830.1     .12       0
  4968.5     .05       0  5019.7     .12       0  5031.4    .035       0
  5129.9     .07       0  5228.5    .035       0  5445.2     .07       0
  6237.1     .12       0  6459.6     .07       0
Bank Sta=4968.5,5019.7
XS Rating Curve= 0 ,0
Exp/Cntr=0.3,0.1

Type RM Length L Ch R = 1 ,14846   ,543,543,543
BEGIN DESCRIPTION:
BLOCK CREEK 26.0
END DESCRIPTION:
XS GIS Cut Line= 3
      2021274.97     13915874.98        2020925.       13915675.
      2020274.96     13915524.99
#Sta/Elev= 30
  4596.9 1411.77    4648 1411.75  4663.8 1409.25  4728.6 1405.88  4781.1  1400.3
  4793.4 1400.13  4838.7 1392.35  4852.4 1392.46  4868.2 1389.86  4919.4 1388.14
  4927.3 1384.13  4950.7 1384.42  4954.6 1384.41  4960.7  1382.1  4961.7  1381.6
    5012  1382.1  5018.8  1387.6  5023.9 1387.61  5030.8 1390.03  5092.3 1397.48
  5143.7 1401.85  5311.6 1409.35  5472.1 1415.41  5502.9 1420.62  5509.7 1422.96
  5533.6 1424.39  5595.2 1435.71    5626 1439.77  5643.1 1443.82  5667.1 1445.02
#Mann= 5 ,-1 , 0
  4596.9    .035       0  4950.7     .12       0  4960.7     .05       0
    5012     .12       0  5311.6    .035       0
Bank Sta=4960.7,5012
XS Rating Curve= 0 ,0
Exp/Cntr=0.3,0.1

Type RM Length L Ch R = 1 ,14303   ,522,522,522
BEGIN DESCRIPTION:
BLOCK CREEK 25.0
END DESCRIPTION:
XS GIS Cut Line= 3
      2021275.03     13915525.04        2020975.       13915175.
      2020174.98     13915425.01
#Sta/Elev= 30
  4533.4 1407.16  4661.3 1405.58  4696.7 1402.83  4767.8  1399.9  4804.2 1394.86
  4817.2 1395.22  4866.6  1387.8  4914.2 1388.24    4973 1385.16    4985 1381.71
    4986 1381.21  5036.3 1381.71  5080.9 1387.98  5108.1 1401.09  5113.3 1400.81
  5120.1 1404.36  5178.3 1410.84  5432.2 1413.59  5481.1  1411.2  5497.3 1414.17
  5570.7 1417.51  5586.8 1421.25  5616.2 1427.03  5633.5 1433.08  5675.4 1437.75
  5696.4 1443.07  5727.8 1445.62  5790.7 1445.08  5811.1 1453.01  5832.6 1454.22
#Mann= 8 ,-1 , 0
  4533.4    .035       0  4696.7     .07       0  4804.2     .12       0
  4914.2     .07       0    4985     .05       0  5036.3     .07       0
  5432.2    .035       0  5586.8     .07       0
Bank Sta=4985,5036.3
XS Rating Curve= 0 ,0
Exp/Cntr=0.3,0.1

Type RM Length L Ch R = 1 ,13781   ,551,551,551
BEGIN DESCRIPTION:
BLOCK CREEK 24.0
END DESCRIPTION:
XS GIS Cut Line= 3
      2021841.68     13915322.46        2021075.       13914725.
      2020158.84     13914424.41
#Sta/Elev= 30
  4028.5 1411.25  4063.8 1410.02  4161.1 1407.93  4185.8 1407.99  4307.8 1407.48
  4327.8 1406.82  4444.9 1405.83  4795.8 1399.87  4872.9    1392  4938.5 1389.41
    4958 1387.06  4964.3  1384.5  4971.5 1376.75  4972.5 1376.25  5023.1 1376.75
  5033.6 1382.27  5137.3 1384.58  5158.4 1386.99  5189.9 1395.44  5212.6 1397.63
  5336.7 1403.26  5341.6 1403.43  5444.3 1406.34  5600.4 1410.12  5658.2 1410.71
  5663.5 1408.73  5684.6  1411.3  5813.9 1414.27  5886.2 1417.98  5964.7 1430.04
#Mann= 16 ,-1 , 0
  4028.5    .035       0  4063.8     .07       0  4161.1    .035       0
  4185.8     .07       0  4307.8    .035       0  4327.8     .07       0
  4444.9    .035       0  4795.8     .07       0  4938.5    .035       0
  4971.5     .05       0  5023.1    .035       0  5033.6    .035       0
  5336.7     .07       0  5341.6     .12       0  5444.3    .035       0
  5813.9     .07       0
Bank Sta=4971.5,5023.1
XS Rating Curve= 0 ,0
Exp/Cntr=0.3,0.1

Type RM Length L Ch R = 1 ,13230   ,579,579,579
BEGIN DESCRIPTION:
BLOCK CREEK 23.0
END DESCRIPTION:
XS GIS Cut Line= 3
       2021877.1     13914507.56        2021075.       13914225.
      2020023.26     13914207.74
#Sta/Elev= 30
  4149.5 1421.63  4209.7 1410.95  4231.8 1406.87  4263.3 1404.84  4288.4 1402.77
    4491  1401.4  4499.8 1399.83  4685.5 1400.38  4796.3 1397.81  4865.9 1393.06
  4913.4 1386.95  4936.3 1384.47  4958.8 1384.95  4968.1 1381.08  4971.5  1375.8
  4972.5  1375.3  5023.1  1375.8  5029.9 1380.53  5099.9 1384.31  5139.9 1392.02
  5219.9  1397.9  5270.2 1398.89  5398.9 1402.08  5500.1  1404.6  5607.2 1408.01
    5790 1415.11    5890 1428.99    5940 1439.78  6050.1 1449.99  6051.8 1449.99
#Mann= 12 ,-1 , 0
  4149.5    .035       0  4209.7     .12       0  4263.3    .035       0
  4796.3     .12       0  4913.4     .07       0  4971.5     .05       0
  5023.1     .07       0  5270.2     .07       0  5398.9    .035       0
  5500.1     .12       0  5607.2    .035       0  6050.1     .07       0
Bank Sta=4971.5,5023.1
XS Rating Curve= 0 ,0
Exp/Cntr=0.3,0.1

Type RM Length L Ch R = 1 ,12651   ,530,530,530
BEGIN DESCRIPTION:
BLOCK CREEK 22.0
END DESCRIPTION:
XS GIS Cut Line= 3
        2021820.     13913903.19        2021075.       13913675.
      2020425.01       13913575.
#Sta/Elev= 30
  4216.4 1403.01  4434.1  1401.4  4461.6 1397.49  4466.9 1399.09  4532.4 1394.69
  4810.2 1389.14  4859.6 1384.43  4870.1 1381.97  4875.7 1378.35  4880.9  1378.1
  4901.4 1387.02  4913.7 1386.82  4979.2  1380.6  4979.8 1375.54  4980.8 1375.04
  5031.5 1375.54  5192.9 1392.75  5287.7 1395.45  5430.9 1396.15  5481.2 1397.36
  5492.6 1398.33  5501.4 1401.17  5511.6  1399.9  5521.7  1401.2  5550.8 1412.72
  5555.8 1412.25  5572.3 1419.83    5590 1423.62  5619.1 1432.77  5653.2 1438.73
#Mann= 6 ,-1 , 0
  4216.4     .12       0  4979.8     .05       0  5031.5     .12       0
  5192.9    .035       0  5430.9     .12       0    5590    .035       0
Bank Sta=4979.8,5031.5
XS Rating Curve= 0 ,0
Exp/Cntr=0.3,0.1