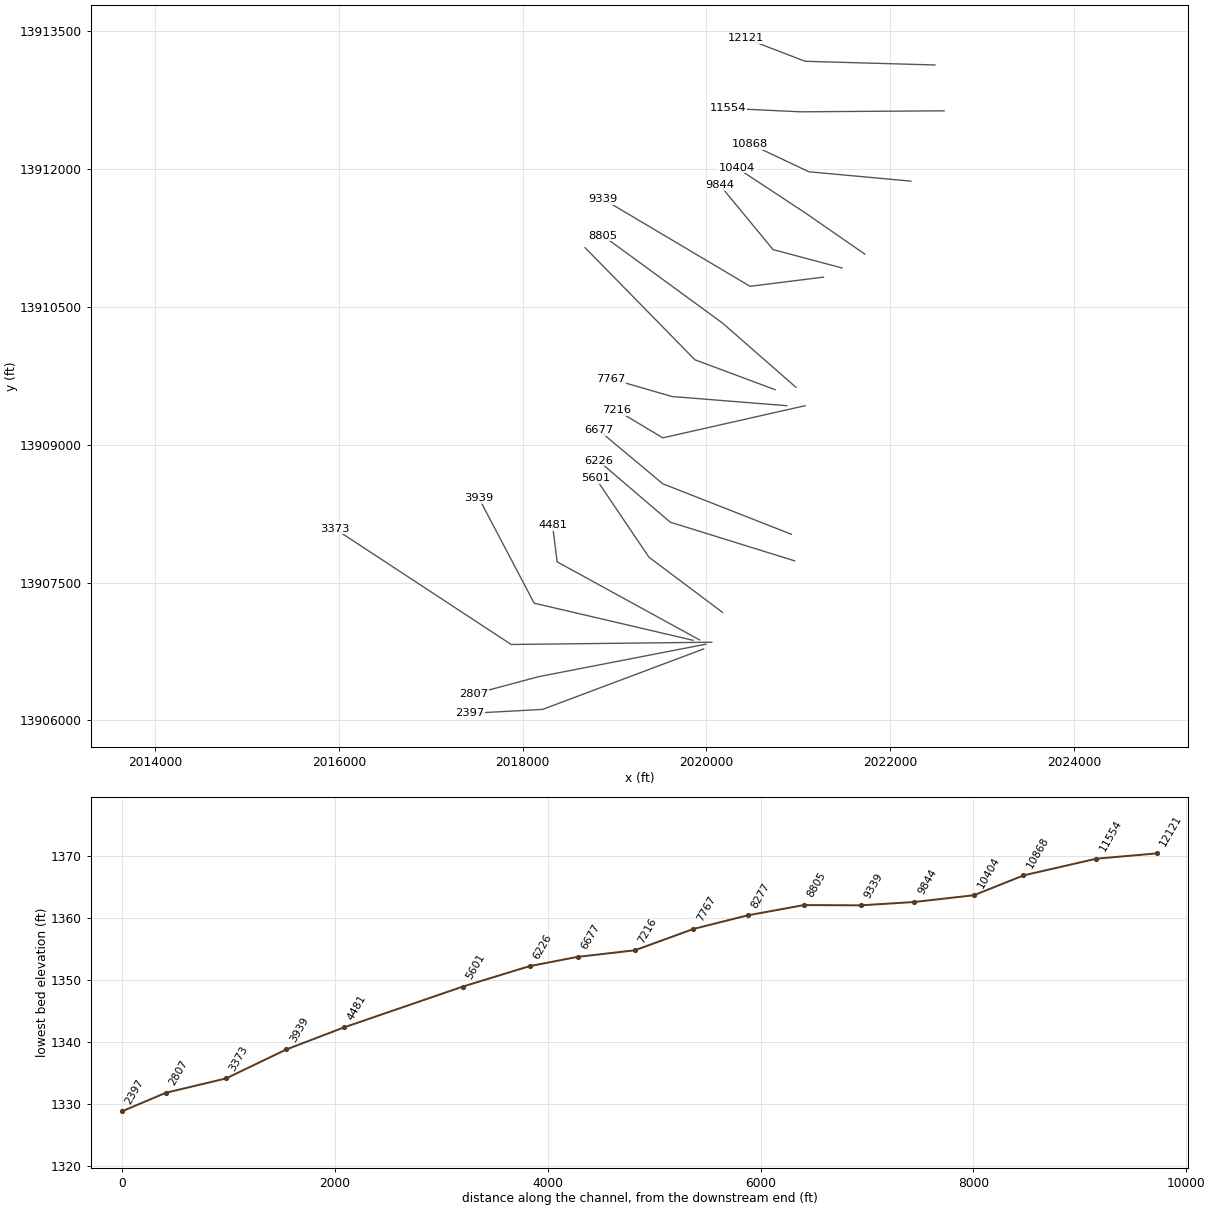
HEC-RAS study BLOCK CREEK.prj: BLOCK CREEK Base Level Engineering

--- BLOCK CREEK.g01 (geometry) --- (continued)

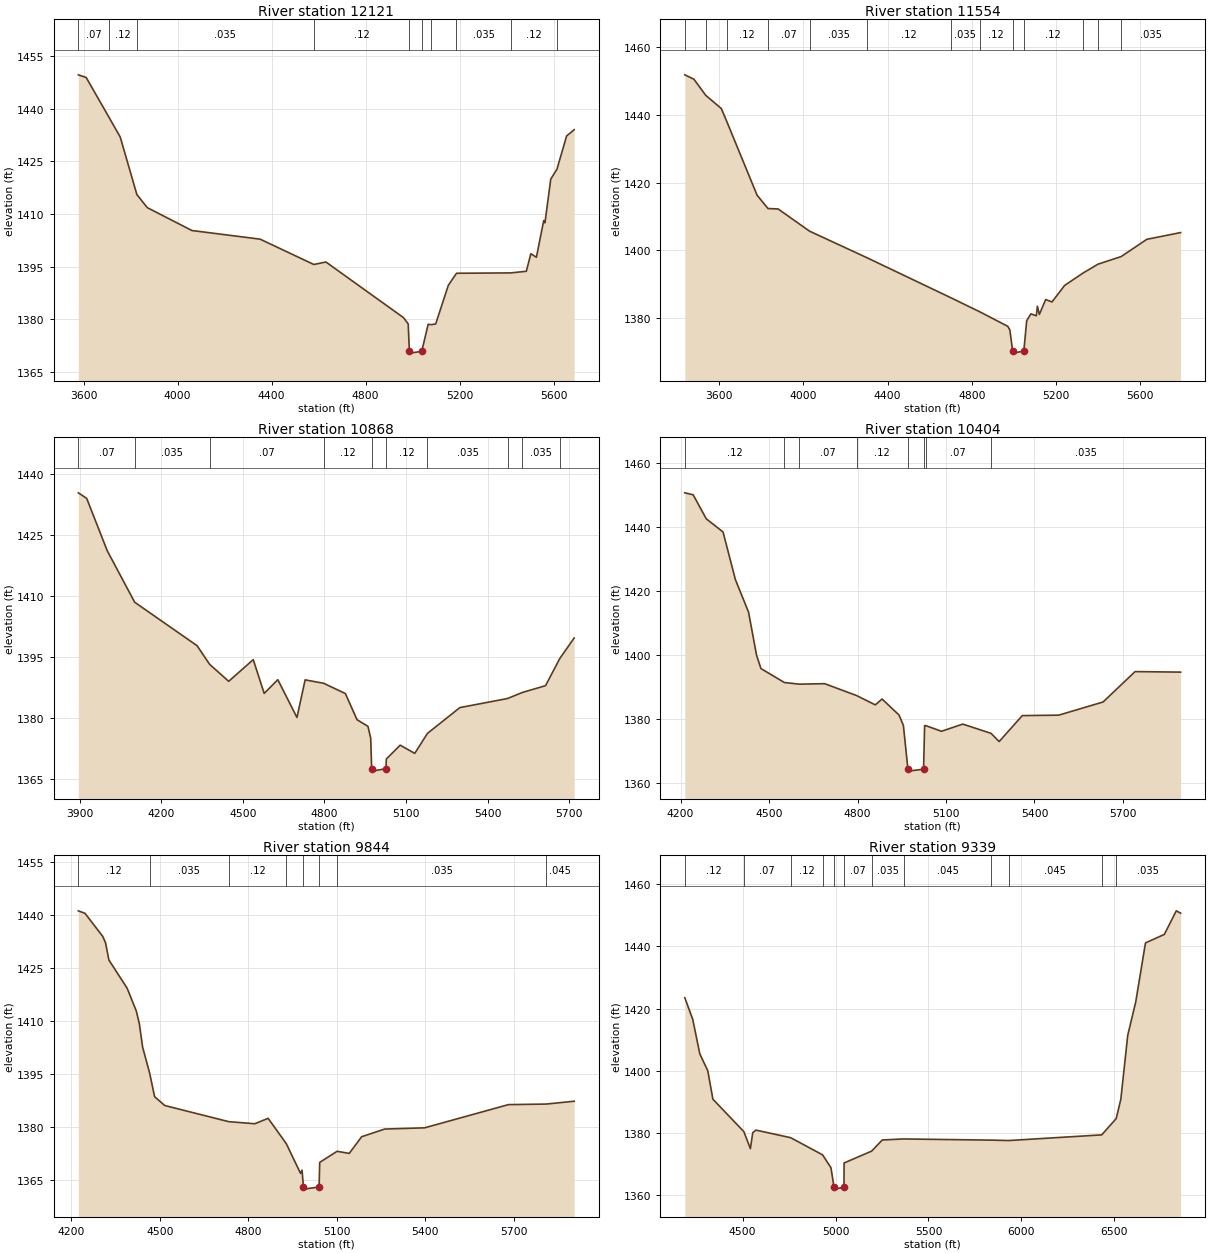
Type RM Length L Ch R = 1 ,12121   ,567,567,567
BEGIN DESCRIPTION:
BLOCK CREEK 21.0
END DESCRIPTION:
XS GIS Cut Line= 3
      2022488.41     13913134.95        2021075.       13913175.
        2020425.       13913425.
#Sta/Elev= 30
  3577.4 1449.68  3610.8 1448.92    3708 1437.57  3755.7 1431.96  3826.6 1415.56
  3870.9 1411.83    4061 1405.31  4351.1 1402.85  4579.8 1395.63  4631.2 1396.34
  4961.4 1380.49  4981.4  1378.7  4986.5 1370.87  4987.5 1370.37  5039.1 1370.87
  5066.4 1378.59  5080.1 1378.48  5098.5 1378.69  5152.1 1389.68    5187 1393.13
  5417.8 1393.23  5484.2  1393.7  5503.5  1398.7  5527.1 1397.68  5558.2 1408.13
  5563.5  1407.5  5588.2 1419.97  5614.6 1422.78  5655.7 1432.26  5687.8 1434.04
#Mann= 10 ,-1 , 0
  3577.4     .07       0    3708     .12       0  3826.6    .035       0
  4579.8     .12       0  4986.5     .05       0  5039.1     .12       0
  5080.1     .07       0    5187    .035       0  5417.8     .12       0
  5614.6    .035       0
Bank Sta=4986.5,5039.1
XS Rating Curve= 0 ,0
Exp/Cntr=0.3,0.1

Type RM Length L Ch R = 1 ,11554   ,686,686,686
BEGIN DESCRIPTION:
BLOCK CREEK 20.0
END DESCRIPTION:
XS GIS Cut Line= 3
      2022588.15     13912635.82        2021025.       13912625.
      2020234.96     13912662.15
#Sta/Elev= 30
  3436.8 1451.86    3480 1450.57  3536.3 1445.79    3610  1441.9  3634.8 1438.26
    3780 1416.25  3831.9  1412.3    3880 1412.17    4029 1405.61  4303.7 1397.69
  4699.3 1385.93  4837.5 1381.74    4970 1377.46    4980  1376.4  4993.6 1370.12
  4994.7 1369.52  5046.4 1370.12  5060.1 1379.11  5080.1 1381.13  5105.8 1380.58
  5110.8 1383.39  5120.1 1380.97  5150.2 1385.36  5180.2 1384.67  5240.3 1389.55
  5326.2 1393.16  5398.6 1395.84  5508.7 1398.09  5630.7  1403.2  5790.9 1405.19
#Mann= 13 ,-1 , 0
  3436.8    .035       0  3536.3     .07       0  3634.8     .12       0
  3831.9     .07       0    4029    .035       0  4303.7     .12       0
  4699.3    .035       0  4837.5     .12       0  4993.6     .05       0
  5046.4     .12       0  5326.2    .035       0  5398.6     .12       0
  5508.7    .035       0
Bank Sta=4993.6,5046.4
XS Rating Curve= 0 ,0
Exp/Cntr=0.3,0.1

Type RM Length L Ch R = 1 ,10868   ,464,464,464
BEGIN DESCRIPTION:
BLOCK CREEK 19.0
END DESCRIPTION:
XS GIS Cut Line= 3
      2022225.56     13911870.28      2021116.85     13911971.76
      2020475.02     13912274.99
#Sta/Elev= 30
  3895.2 1435.28  3925.9 1433.92  4001.5 1421.03  4102.4 1408.37  4331.8 1397.68
    4378 1393.09  4448.1 1388.91  4538.4 1394.25  4578.6 1385.94  4628.8 1389.31
  4699.1 1380.02  4729.2 1389.27  4797.3 1388.43  4877.2  1385.9    4920 1379.47
  4960.2 1377.84  4970.2 1374.94  4973.9 1367.42    4975 1366.82  5026.8 1367.42
  5027.5 1369.78  5078.6  1373.2  5132.3 1371.19  5178.9  1376.1  5298.2 1382.45
  5473.3 1384.68  5527.9 1386.17  5613.2 1387.84  5665.3 1394.49  5718.4 1399.58
#Mann= 10 ,-1 , 0
  3895.2     .07       0  4102.4    .035       0    4378     .07       0
  4797.3     .12       0  4973.9     .05       0  5026.8     .12       0
  5178.9    .035       0  5473.3     .07       0  5527.9    .035       0
  5665.3     .07       0
Bank Sta=4973.9,5026.8
XS Rating Curve= 0 ,0
Exp/Cntr=0.3,0.1

Type RM Length L Ch R = 1 ,10404   ,560,560,560
BEGIN DESCRIPTION:
BLOCK CREEK 18.0
END DESCRIPTION:
XS GIS Cut Line= 3
      2021724.98     13911075.01        2021075.       13911525.
      2020331.24     13912015.17
#Sta/Elev= 30
  4214.2 1450.75  4242.6 1450.13  4287.1 1442.61  4343.9  1438.5  4385.8 1423.57
  4430.4 1413.42  4457.4 1399.98  4472.3 1395.75    4552 1391.37  4602.8 1390.86
  4688.5 1391.01  4797.1 1387.28  4860.1 1384.38  4883.1 1386.21  4940.6 1381.21
  4955.4 1377.97  4970.8 1364.24  4971.9 1363.64  5023.9 1364.24  5027.4 1377.88
  5030.5  1377.9  5084.6 1376.11  5156.8 1378.36  5252.6 1375.47  5280.2  1372.9
  5358.6 1381.02  5482.1 1381.16  5632.6 1385.28    5741 1394.79  5895.5 1394.63
#Mann= 8 ,-1 , 0
  4214.2     .12       0    4552    .035       0  4602.8     .07       0
  4797.1     .12       0  4970.8     .05       0  5023.9     .12       0
  5030.5     .07       0  5252.6    .035       0
Bank Sta=4970.8,5023.9
XS Rating Curve= 0 ,0
Exp/Cntr=0.3,0.1

Type RM Length L Ch R = 1 ,9844    ,505,505,505
BEGIN DESCRIPTION:
BLOCK CREEK 17.0
END DESCRIPTION:
XS GIS Cut Line= 3
      2021474.98     13910925.01        2020725.       13911125.
      2020149.48     13911823.57
#Sta/Elev= 30
  4223.6 1441.13  4246.2 1440.43  4306.4 1433.91  4316.1 1432.05  4327.1 1427.27
  4389.2 1419.27  4420.2 1412.84  4430.6 1409.22  4441.6 1402.63  4465.4 1395.32
  4482.3 1388.64  4516.6 1386.16  4733.7  1381.6  4821.9 1381.01  4867.2 1382.54
  4928.6 1375.42  4977.1 1366.99  4982.3 1367.91  4986.9 1363.15  4987.9 1362.55
    5040 1363.15  5042.1  1370.1    5101 1373.23  5142.3 1372.64  5184.2 1377.34
  5262.3 1379.51  5397.9 1379.86    5682 1386.41  5810.5 1386.57  5904.9 1387.37
#Mann= 8 ,-1 , 0
  4223.6     .12       0  4465.4    .035       0  4733.7     .12       0
  4928.6     .07       0  4986.9     .05       0    5040     .07       0
    5101    .035       0  5810.5    .045       0
Bank Sta=4986.9,5040
XS Rating Curve= 0 ,0
Exp/Cntr=0.3,0.1

Type RM Length L Ch R = 1 ,9339    ,534,534,534
BEGIN DESCRIPTION:
BLOCK CREEK 16.0
END DESCRIPTION:
XS GIS Cut Line= 3
      2021275.05     13910825.01        2020475.       13910725.
      2018874.96     13911675.02
#Sta/Elev= 30
  4189.3  1423.5  4232.2 1416.54    4270 1405.47  4312.8 1400.07  4340.5  1390.9
  4507.1 1380.48  4542.1 1375.01  4554.7 1380.14  4572.3 1380.97  4758.6 1378.54
  4930.3 1373.03  4975.4 1368.91  4992.2 1362.61  4993.2 1362.01  5045.5 1362.61
  5046.2 1370.41  5194.6 1374.23  5251.4  1377.8  5366.1 1378.13  5838.1 1377.75
  5932.7 1377.62  6431.9 1379.44    6510 1384.69  6534.8 1390.89  6571.9 1411.42
  6614.7 1422.07  6667.4 1441.12  6768.7 1443.83  6833.1 1451.42  6856.4 1450.67
#Mann= 12 ,-1 , 0
  4189.3     .12       0  4507.1     .07       0  4758.6     .12       0
  4930.3     .07       0  4992.2     .05       0  5045.5     .07       0
  5194.6    .035       0  5366.1    .045       0  5838.1    .035       0
  5932.7    .045       0  6431.9     .07       0    6510    .035       0
Bank Sta=4992.2,5045.5
XS Rating Curve= 0 ,0
Exp/Cntr=0.3,0.1

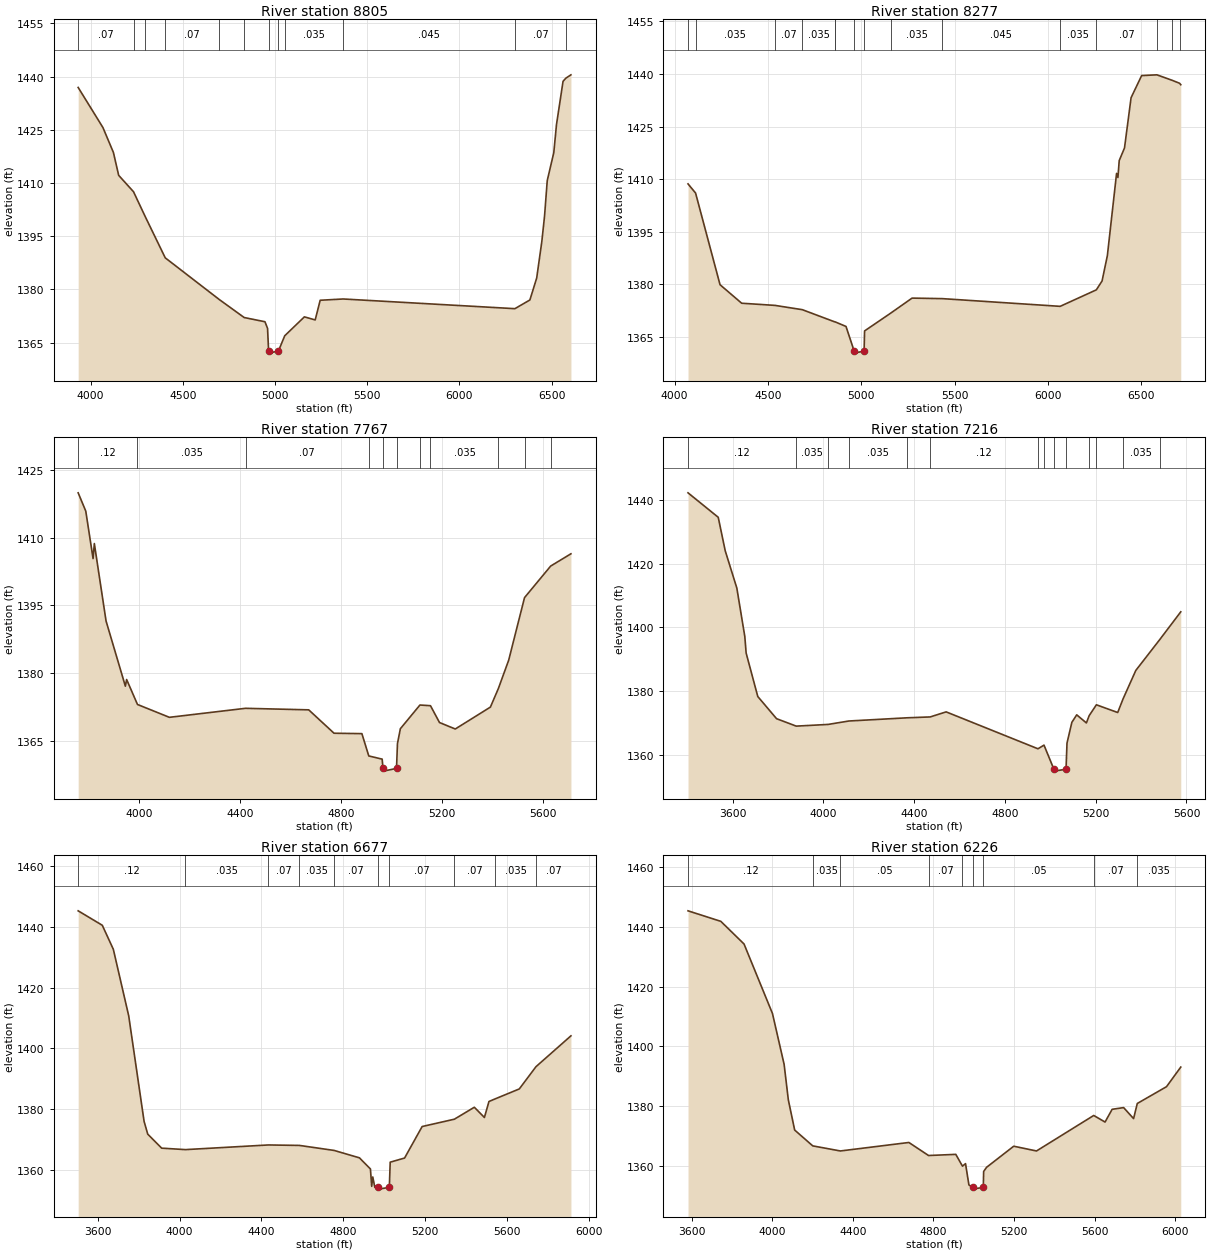
Type RM Length L Ch R = 1 ,8805    ,528,528,528
BEGIN DESCRIPTION:
BLOCK CREEK 15.0
END DESCRIPTION:
XS GIS Cut Line= 3
        2020975.       13909625.        2020175.       13910325.
      2018875.03     13911274.98
#Sta/Elev= 30
  3932.3 1436.93  4066.6 1425.63  4123.5  1418.6    4152 1412.16  4232.6 1407.53
  4294.2 1400.73  4404.6 1388.91  4698.2 1377.14  4832.9 1372.08  4945.5  1370.9
  4959.7 1369.01  4965.3 1362.65  4966.4 1362.05  5018.7 1362.65  5052.8 1366.94
  5159.4 1372.27  5218.1 1371.41  5245.1 1376.95  5369.9 1377.31  6301.4 1374.58
  6382.7 1377.03  6419.7 1383.23  6447.5 1393.52  6462.2 1400.64  6476.9 1410.69
  6512.4 1418.55    6527 1426.44  6562.6 1438.65  6577.9 1439.55  6605.4 1440.49
#Mann= 12 ,-1 , 0
  3932.3     .07       0  4232.6     .12       0  4294.2    .035       0
  4404.6     .07       0  4698.2    .035       0  4832.9     .12       0
  4965.3     .05       0  5018.7     .12       0  5052.8    .035       0
  5369.9    .045       0  6301.4     .07       0  6577.9    .035       0
Bank Sta=4965.3,5018.7
XS Rating Curve= 0 ,0
Exp/Cntr=0.3,0.1

Type RM Length L Ch R = 1 ,8277    ,510,510,510
BEGIN DESCRIPTION:
BLOCK CREEK 14.0
END DESCRIPTION:
XS GIS Cut Line= 3
      2020748.42     13909599.13        2019875.       13909925.
      2018679.01     13911145.58
#Sta/Elev= 30
  4071.7 1408.66  4112.2 1406.05  4243.3 1379.91  4359.2 1374.63    4538 1374.01
  4684.2 1372.79  4857.4 1369.33  4859.4 1369.33  4918.5 1368.01  4962.1    1361
  4963.2  1360.4  5015.5    1361    5018 1366.73    5158  1371.8  5272.6 1376.09
  5434.6 1375.94  6066.3 1373.74  6260.2 1378.44    6291 1380.99  6319.3  1388.2
  6368.7 1411.66  6375.9 1410.49  6382.9 1415.31  6411.2 1418.91  6446.4 1433.23
    6503 1439.54    6585 1439.76  6668.3 1438.16  6706.8 1437.34  6712.8 1436.94
#Mann= 15 ,-1 , 0
  4071.7     .07       0  4112.2    .035       0    4538     .07       0
  4684.2    .035       0  4857.4     .12       0  4859.4     .07       0
  4962.1     .05       0  5015.5     .07       0    5158    .035       0
  5434.6    .045       0  6066.3    .035       0  6260.2     .07       0
    6585    .035       0  6668.3     .07       0  6706.8    .035       0
Bank Sta=4962.1,5015.5
XS Rating Curve= 0 ,0
Exp/Cntr=0.3,0.1

Type RM Length L Ch R = 1 ,7767    ,551,551,551
BEGIN DESCRIPTION:
BLOCK CREEK 13.0
END DESCRIPTION:
XS GIS Cut Line= 3
      2020875.05       13909425.        2019625.       13909525.
      2018955.12     13909719.18
#Sta/Elev= 30
  3759.9 1419.97    3790 1415.91  3818.9 1405.38  3823.9 1408.71  3870.3 1391.53
  3946.8 1377.06  3951.8 1378.54  3994.8    1373  4121.1 1370.15  4422.6 1372.15
  4672.9 1371.81  4773.2 1366.62  4883.5 1366.53  4910.8 1361.58  4963.8 1360.87
  4967.2 1358.81  4968.3 1358.21  5020.6 1358.81  5024.4 1364.34  5035.9 1367.62
  5113.4 1372.88  5155.2 1372.73  5190.9 1368.99  5253.4 1367.56  5392.5 1372.42
  5424.1 1376.55  5464.9 1382.83  5527.6 1396.71  5631.2 1403.72  5711.4 1406.44
#Mann= 11 ,-1 , 0
  3759.9     .12       0  3994.8    .035       0  4422.6     .07       0
  4910.8     .12       0  4967.2     .05       0  5020.6     .12       0
  5113.4     .07       0  5155.2    .035       0  5424.1     .12       0
  5527.6     .07       0  5631.2    .035       0
Bank Sta=4967.2,5020.6
XS Rating Curve= 0 ,0
Exp/Cntr=0.3,0.1

Type RM Length L Ch R = 1 ,7216    ,539,539,539
BEGIN DESCRIPTION:
BLOCK CREEK 12.0
END DESCRIPTION:
XS GIS Cut Line= 3
      2021074.95     13909424.99        2019525.       13909075.
      2019024.98     13909375.01
#Sta/Elev= 30
  3402.9 1442.33  3536.1 1434.63  3566.9  1424.1  3618.1 1412.36  3653.3  1397.1
  3659.1 1391.92  3710.4 1378.25  3793.2 1371.27  3879.9 1368.93  4020.1 1369.46
  4112.1 1370.54    4370 1371.55  4470.3 1371.82  4540.8 1373.41  4945.5  1361.8
  4972.1 1362.95  5015.7 1355.37  5016.8 1354.77  5069.2 1355.37  5073.5 1363.59
  5094.9 1370.12  5116.3 1372.48    5159 1369.93  5171.1 1372.21    5203 1375.64
    5297 1373.21  5320.2 1377.43  5376.7 1386.44  5482.7 1396.19    5575 1404.89
#Mann= 14 ,-1 , 0
  3402.9     .12       0  3879.9    .035       0  4020.1     .12       0
  4112.1    .035       0    4370     .07       0  4470.3     .12       0
  4945.5     .07       0  4972.1     .12       0  5015.7     .05       0
  5069.2     .12       0  5171.1     .07       0    5203     .12       0
  5320.2    .035       0  5482.7     .07       0
Bank Sta=5015.7,5069.2
XS Rating Curve= 0 ,0
Exp/Cntr=0.3,0.1

Type RM Length L Ch R = 1 ,6677    ,451,451,451
BEGIN DESCRIPTION:
BLOCK CREEK 11.0
END DESCRIPTION:
XS GIS Cut Line= 3
        2020925.       13908025.        2019525.       13908575.
      2018830.34     13909155.28
#Sta/Elev= 30
  3504.5 1445.21  3622.4 1440.46  3676.4 1432.56  3751.6 1410.68  3826.8 1375.98
  3844.6 1371.79  3912.8 1367.18  4029.1  1366.7  4434.3 1368.23  4586.4 1368.08
    4756 1366.43  4879.7    1364  4933.5 1360.33  4939.6 1354.63  4944.9 1357.71
  4954.9 1354.33  4972.4 1354.31  4973.5 1353.71  5025.9 1354.31  5030.1 1362.57
  5100.4 1363.93  5186.3 1374.29  5343.9  1376.7  5441.4 1380.63  5490.8 1377.27
    5513 1382.52  5543.7 1383.39  5661.3 1386.65  5742.8 1393.96  5913.8 1404.11
#Mann= 10 ,-1 , 0
  3504.5     .12       0  4029.1    .035       0  4434.3     .07       0
  4586.4    .035       0    4756     .07       0  4972.4     .05       0
  5025.9     .07       0  5343.9     .07       0  5543.7    .035       0
  5742.8     .07       0
Bank Sta=4972.4,5025.9
XS Rating Curve= 0 ,0
Exp/Cntr=0.3,0.1

Type RM Length L Ch R = 1 ,6226    ,625,625,625
BEGIN DESCRIPTION:
BLOCK CREEK 10.0
END DESCRIPTION:
XS GIS Cut Line= 3
      2020960.59     13907735.65      2019606.43     13908156.66
      2018825.04     13908824.97
#Sta/Elev= 30
  3581.7 1445.35  3744.6 1441.83  3859.8 1434.25  4000.9    1411  4058.8 1393.98
  4079.7 1382.09  4111.2 1371.99    4201 1366.69  4338.2 1364.99  4678.1 1367.83
  4775.8 1363.47  4911.1 1363.85  4944.3  1359.9  4959.4 1360.75  4976.2 1353.63
  4994.1 1352.82  4995.2 1352.22  5047.6 1352.82  5049.4 1358.13  5063.7 1359.51
  5198.7 1366.58  5311.8 1364.99  5595.9 1376.87  5652.1 1374.67  5687.2 1378.93
  5744.3  1379.5  5793.7 1375.82  5812.1 1380.88  5957.2  1386.5    6028 1393.06
#Mann= 9 ,-1 , 0
  3581.7     .12       0    4201    .035       0  4338.2     .05       0
  4775.8     .07       0  4944.3     .05       0  4994.1     .05       0
  5047.6     .05       0  5595.9     .07       0  5812.1    .035       0
Bank Sta=4994.1,5047.6
XS Rating Curve= 0 ,0
Exp/Cntr=0.3,0.1

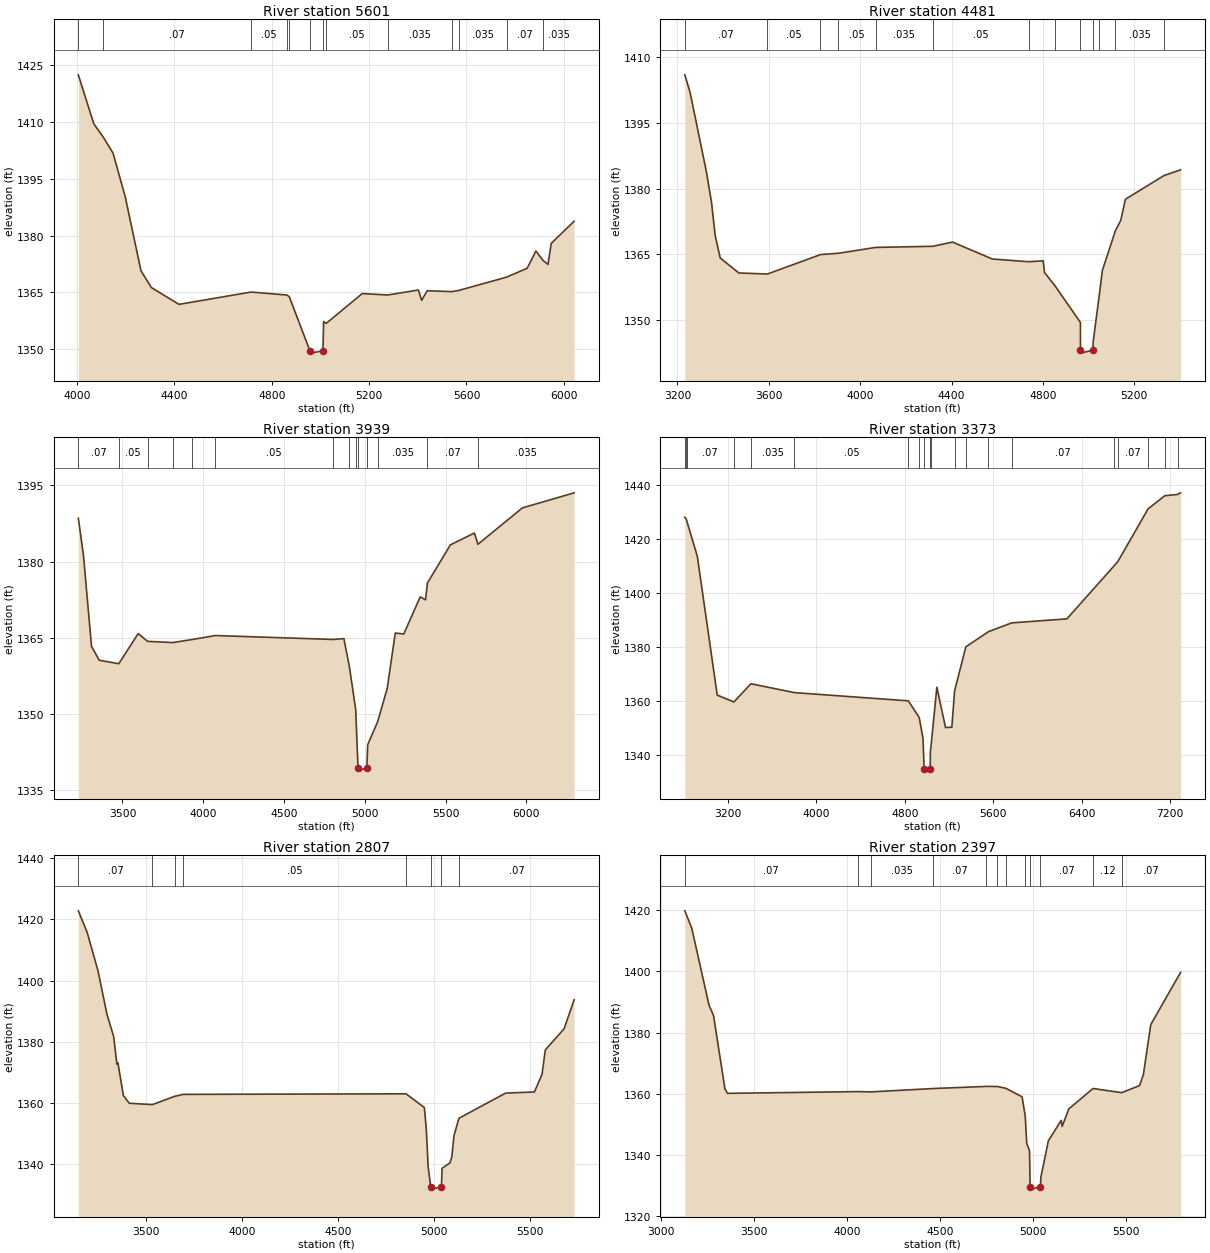
Type RM Length L Ch R = 1 ,5601    ,1120,1120,1120
BEGIN DESCRIPTION:
BLOCK CREEK 9.0
END DESCRIPTION:
XS GIS Cut Line= 3
        2020175.       13907175.        2019375.       13907775.
      2018794.78     13908634.12
#Sta/Elev= 30
  4005.7 1422.48  4069.2 1409.55  4108.8 1405.94  4148.4 1401.77  4198.4 1390.25
    4263 1370.72  4305.7 1366.27  4419.2 1361.83  4715.3 1365.08  4862.8 1364.29
  4872.7 1363.78    4957 1349.54  4958.1 1348.94  5010.6 1349.54  5013.2 1357.27
  5023.7 1356.79    5172 1364.68  5276.7  1364.3  5402.8 1365.62    5416  1362.9
  5438.8 1365.43  5539.4 1365.19  5567.5 1365.49  5764.5 1369.01  5849.4 1371.36
  5885.3 1375.92  5915.6 1373.36  5934.9 1372.39  5948.3 1377.95  6042.4 1383.79
#Mann= 13 ,-1 , 0
  4005.7     .12       0  4108.8     .07       0  4715.3     .05       0
  4862.8     .07       0  4872.7     .05       0    4957     .05       0
  5010.6     .05       0  5023.7     .05       0  5276.7    .035       0
  5539.4     .07       0  5567.5    .035       0  5764.5     .07       0
  5915.6    .035       0
Bank Sta=4957,5010.6
XS Rating Curve= 0 ,0
Exp/Cntr=0.3,0.1

Type RM Length L Ch R = 1 ,4481    ,542,542,542
BEGIN DESCRIPTION:
BLOCK CREEK 8.0
END DESCRIPTION:
XS GIS Cut Line= 3
      2019924.97     13906875.02        2018375.       13907725.
      2018325.01     13908124.95
#Sta/Elev= 30
    3232 1406.01  3254.8 1402.08  3327.2 1383.69    3349 1376.83  3365.1 1369.26
  3386.9 1364.13  3468.5 1360.69  3593.6 1360.44  3825.9 1364.89  3904.2 1365.19
  4067.7 1366.53  4318.1 1366.79    4404 1367.75  4578.4 1363.88  4737.4 1363.26
  4801.2 1363.46  4806.9 1360.79  4851.8 1357.82  4964.2 1349.36  4964.3 1343.05
  4965.5 1342.35    5019 1343.05  5019.9 1344.94  5046.9 1355.69  5060.2 1361.28
  5117.1 1370.32  5140.8 1372.74    5161 1377.55  5330.1 1382.97  5402.8 1384.28
#Mann= 13 ,-1 , 0
    3232     .07       0  3593.6     .05       0  3825.9    .035       0
  3904.2     .05       0  4067.7    .035       0  4318.1     .05       0
  4737.4     .07       0  4851.8     .12       0  4964.3    .035       0
    5019     .12       0  5046.9     .07       0  5117.1    .035       0
  5330.1     .07       0
Bank Sta=4964.3,5019
XS Rating Curve= 0 ,0
Exp/Cntr=0.3,0.1

Type RM Length L Ch R = 1 ,3939    ,566,566,566
BEGIN DESCRIPTION:
BLOCK CREEK 7.0
END DESCRIPTION:
XS GIS Cut Line= 3
      2019855.77     13906870.53        2018125.       13907275.
      2017523.47     13908418.31
#Sta/Elev= 30
  3226.8 1388.51  3258.4 1381.27  3308.5 1363.31  3356.1  1360.6  3477.4 1359.91
  3597.3 1365.84  3655.4 1364.31  3811.6 1364.07  3931.9 1364.67  4075.7 1365.45
  4803.1 1364.68  4870.7 1364.84    4905 1359.28  4943.9 1350.88  4958.1  1339.5
  4959.3  1338.8  5012.9  1339.5  5018.1 1343.98  5079.3 1348.48    5139 1355.06
  5188.7 1365.94  5241.5 1365.75  5343.2 1373.05  5375.7 1372.46  5388.1 1375.79
    5530 1383.27  5678.6  1385.6    5700 1383.38  5975.9 1390.54  6296.1  1393.5
#Mann= 14 ,-1 , 0
  3226.8     .07       0  3477.4     .05       0  3655.4    .035       0
  3811.6     .05       0  3931.9    .035       0  4075.7     .05       0
  4803.1     .07       0    4905     .12       0  4943.9     .07       0
  4958.1     .05       0  5012.9     .07       0  5079.3    .035       0
  5388.1     .07       0    5700    .035       0
Bank Sta=4958.1,5012.9
XS Rating Curve= 0 ,0
Exp/Cntr=0.3,0.1

Type RM Length L Ch R = 1 ,3373    ,566,566,566
BEGIN DESCRIPTION:
BLOCK CREEK 6.0
END DESCRIPTION:
XS GIS Cut Line= 3
      2020058.06     13906849.79        2017875.       13906825.
      2015953.72     13908086.12
#Sta/Elev= 30
  2812.1 1428.03  2819.2 1427.81  2827.6 1427.04  2925.2 1413.64  3105.2 1362.27
  3255.9 1359.71  3409.5 1366.46    3803 1363.18  4832.5 1360.14    4931 1353.97
  4965.3 1346.15  4975.1 1334.84  4976.3 1334.14  5030.6 1334.84  5031.2 1341.31
  5037.2 1343.28  5090.3 1365.18  5168.6 1350.27  5225.8  1350.4  5250.6 1363.85
  5352.6 1380.12  5556.1 1385.72  5767.2 1388.98  6265.5 1390.47    6695  1410.2
  6725.8 1411.65  6999.8 1431.17  7150.5 1436.02  7265.4 1436.49  7293.5 1437.09
#Mann= 20 ,-1 , 0
  2812.1     .07       0  2819.2     .12       0  2827.6     .07       0
  3255.9     .05       0  3409.5    .035       0    3803     .05       0
  4832.5     .07       0    4931     .12       0  4975.1     .05       0
  5030.6     .12       0  5037.2     .07       0  5250.6     .12       0
  5352.6     .07       0  5556.1    .035       0  5767.2     .07       0
    6695    .035       0  6725.8     .07       0  6999.8     .12       0
  7150.5     .07       0  7265.4     .12       0
Bank Sta=4975.1,5030.6
XS Rating Curve= 0 ,0
Exp/Cntr=0.3,0.1

Type RM Length L Ch R = 1 ,2807    ,410,410,410
BEGIN DESCRIPTION:
BLOCK CREEK 5.0
END DESCRIPTION:
XS GIS Cut Line= 3
       2019995.7      13906828.7        2018175.       13906475.
      2017469.71     13906286.44
#Sta/Elev= 30
  3145.6  1422.8  3191.7 1415.75  3248.5  1403.1  3295.1 1388.92  3329.7 1381.73
  3346.7 1372.65  3351.8 1373.15  3380.6 1362.42  3411.2  1359.9  3531.2 1359.45
  3647.8 1362.16  3691.9  1362.8  4853.8 1362.99  4949.4 1358.51  4959.6 1351.54
  4969.4 1338.96  4982.9 1332.53  4984.2 1331.83  5038.4 1332.53  5041.7 1338.65
  5083.1 1340.41  5092.7 1342.42  5103.9 1349.31  5129.9    1355  5373.2 1363.22
  5523.1 1363.59  5563.1 1369.39    5580 1377.33  5678.1 1384.26  5730.4 1393.74
#Mann= 8 ,-1 , 0
  3145.6     .07       0  3531.2     .05       0  3647.8    .035       0
  3691.9     .05       0  4853.8     .07       0  4982.9     .05       0
  5038.4     .07       0  5129.9     .07       0
Bank Sta=4982.9,5038.4
XS Rating Curve= 0 ,0
Exp/Cntr=0.3,0.1

Type RM Length L Ch R = 1 ,2397    ,655,655,655
BEGIN DESCRIPTION:
BLOCK CREEK 4.0
END DESCRIPTION:
XS GIS Cut Line= 3
       2019969.9     13906776.55      2018217.36     13906118.55
      2017424.95       13906075.
#Sta/Elev= 30
    3128 1419.78  3165.3 1414.13  3258.3 1388.96  3282.8  1385.5  3343.7 1361.63
  3357.6 1360.15  4058.2 1360.72  4129.6 1360.63  4464.5 1361.73  4749.9 1362.42
  4808.3 1362.39    4854  1361.8  4941.4 1359.02    4958 1352.81  4966.3 1343.81
  4981.2 1341.42  4984.6 1329.56  4985.9 1328.86  5040.1 1329.56  5042.4  1332.8
  5082.5 1344.64  5151.7 1351.33  5156.7 1349.34  5192.6 1355.08  5322.7 1361.73
  5477.2 1360.38  5573.2  1362.7  5593.3 1366.26  5633.3 1382.63  5793.6  1399.7
#Mann= 12 ,-1 , 0
    3128     .07       0  4058.2     .05       0  4129.6    .035       0
  4464.5     .07       0  4749.9    .035       0  4808.3     .07       0
    4854     .12       0    4958     .07       0  4984.6     .05       0
  5040.1     .07       0  5322.7     .12       0  5477.2     .07       0
Bank Sta=4984.6,5040.1
XS Rating Curve= 0 ,0
Exp/Cntr=0.3,0.1