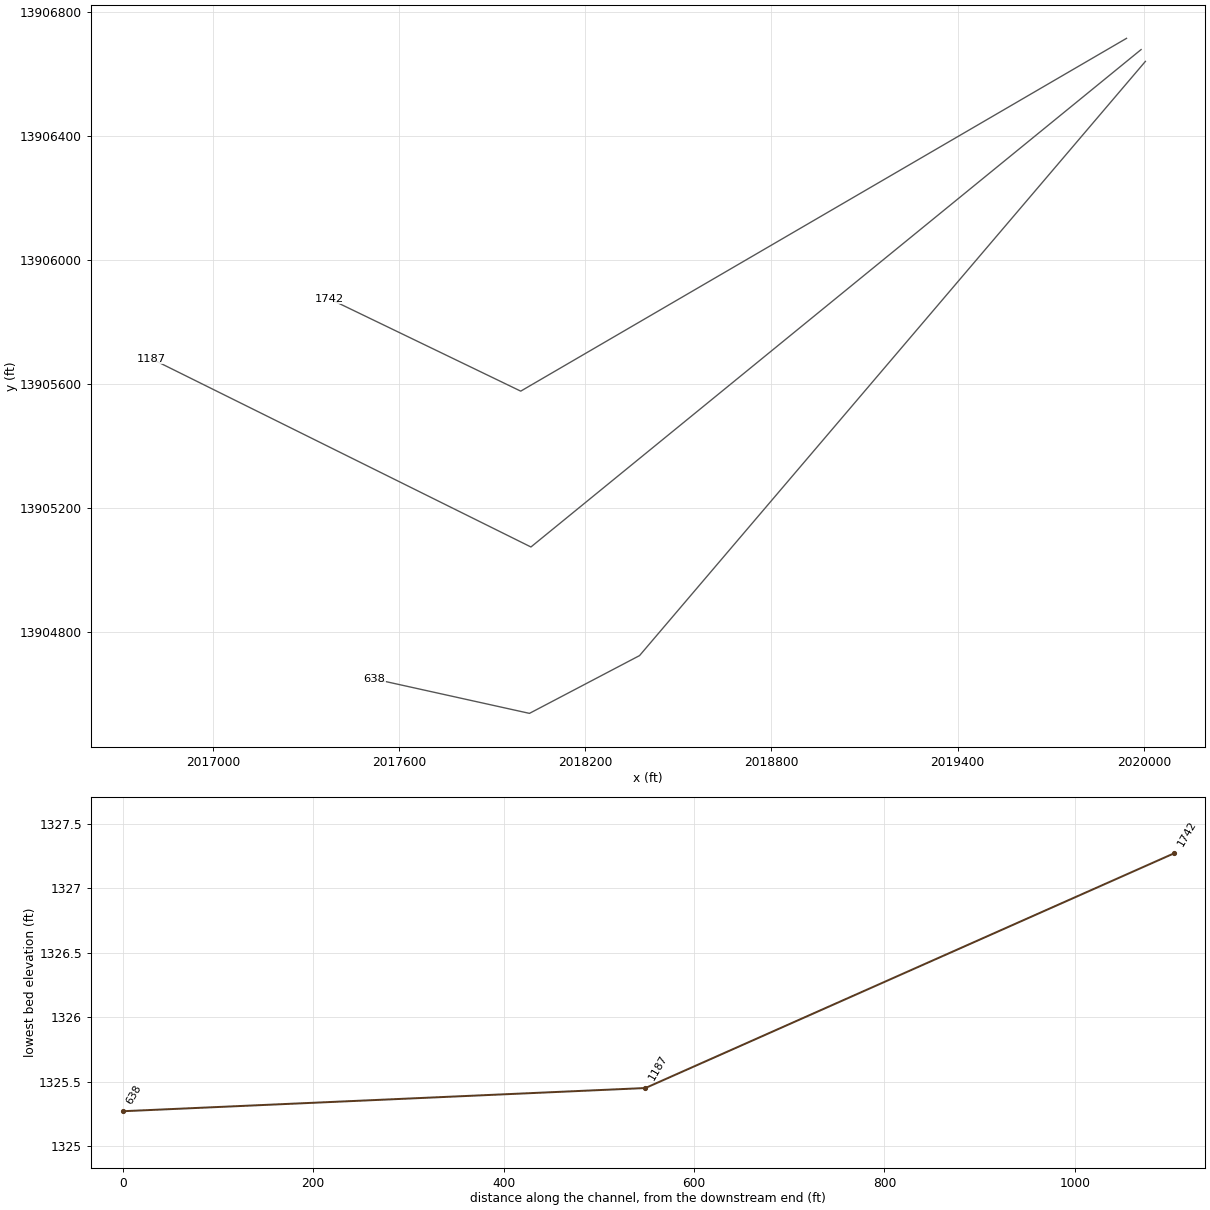
HEC-RAS study BLOCK CREEK.prj: BLOCK CREEK Base Level Engineering

--- BLOCK CREEK.g01 (geometry) --- (continued)

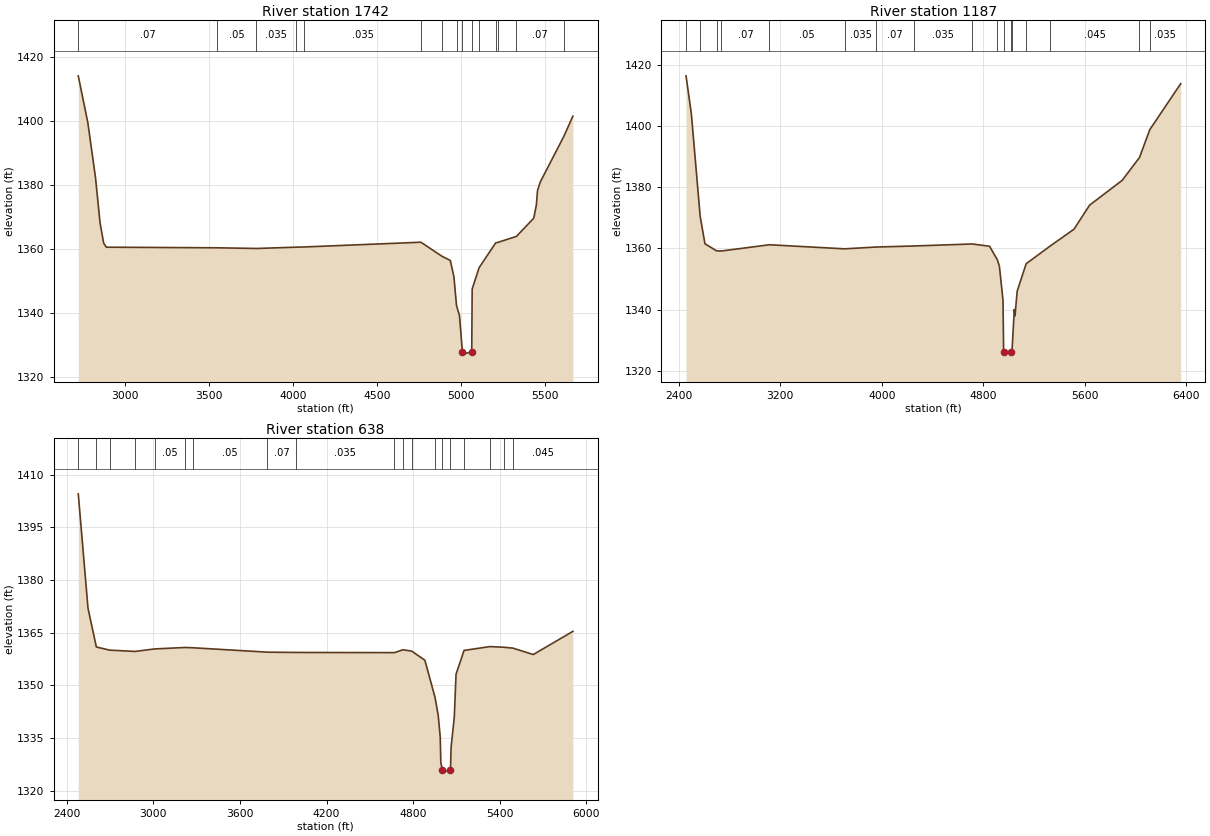
Type RM Length L Ch R = 1 ,1742    ,555,555,555
BEGIN DESCRIPTION:
BLOCK CREEK 3.0
END DESCRIPTION:
XS GIS Cut Line= 3
      2019944.22     13906714.03      2017992.13     13905577.17
      2017375.04     13905874.98
#Sta/Elev= 30
  2720.7 1414.01  2777.7 1399.38  2823.1 1382.37  2850.4  1368.2  2871.9 1361.86
  2887.6  1360.6  3549.4 1360.41  3781.5  1360.2  4014.3  1360.6  4066.9 1360.67
  4759.9 1362.15  4886.9 1357.73  4935.1 1356.47  4956.6 1351.41  4972.2 1342.38
  4989.7  1339.3  5007.2 1327.97  5008.4 1327.27  5062.7 1327.97  5065.3 1347.56
  5106.4 1354.19  5205.1 1361.94  5217.5 1362.09  5328.6 1363.96  5431.8 1369.64
  5447.4 1373.76    5454 1378.18    5470 1380.85    5610 1395.04  5664.9 1401.45
#Mann= 15 ,-1 , 0
  2720.7     .07       0  3549.4     .05       0  3781.5    .035       0
  4014.3     .07       0  4066.9    .035       0  4759.9     .07       0
  4886.9     .12       0  4972.2     .07       0  5007.2     .05       0
  5062.7     .07       0  5106.4    .035       0  5205.1     .07       0
  5217.5    .035       0  5328.6     .07       0    5610    .035       0
Bank Sta=5007.2,5062.7
XS Rating Curve= 0 ,0
Exp/Cntr=0.3,0.1

Type RM Length L Ch R = 1 ,1187    ,549,549,549
BEGIN DESCRIPTION:
BLOCK CREEK 2.0
END DESCRIPTION:
XS GIS Cut Line= 3
      2019991.18     13906677.82        2018025.       13905075.
      2016801.32     13905681.83
#Sta/Elev= 30
  2456.2  1416.4  2498.3 1403.93  2567.6 1370.54  2605.3 1361.52  2696.7 1359.21
  2733.9 1359.15  3114.1 1361.19  3706.7 1359.86  3957.6 1360.45  4253.2 1360.79
  4714.7 1361.45    4851  1360.7  4912.5 1356.28  4928.4  1354.2    4957 1343.08
  4961.9 1326.15  4963.1 1325.45  5017.4 1326.15    5028 1326.56  5046.2 1340.03
  5051.7 1337.94  5068.6 1345.99  5139.7 1354.99  5327.3 1360.72  5516.9 1366.27
  5640.3 1374.14    5897 1382.23  6033.8 1389.71  6115.3 1398.82  6358.8 1413.83
#Mann= 17 ,-1 , 0
  2456.2     .12       0  2567.6     .07       0  2696.7     .05       0
  2733.9     .07       0  3114.1     .05       0  3706.7    .035       0
  3957.6     .07       0  4253.2    .035       0  4714.7     .07       0
  4912.5     .12       0  4961.9     .05       0  5017.4     .12       0
    5028    .035       0  5139.7     .07       0  5327.3    .045       0
  6033.8     .07       0  6115.3    .035       0
Bank Sta=4961.9,5017.4
XS Rating Curve= 0 ,0
Exp/Cntr=0.3,0.1

Type RM Length L Ch R = 1 ,638     ,0,0,0
BEGIN DESCRIPTION:
BLOCK CREEK 1.0
END DESCRIPTION:
XS GIS Cut Line= 4
      2020005.04     13906639.72        2018375.       13904725.
      2018020.25     13904538.81      2017521.26     13904649.22
#Sta/Elev= 30
  2479.7  1404.5  2547.1 1371.94    2605  1360.9  2696.9    1360  2872.9 1359.63
  3008.3 1360.34  3219.8 1360.76  3271.1 1360.68  3790.2 1359.42    3986 1359.34
  4670.1 1359.29  4728.3  1360.1  4789.4 1359.72  4880.6 1357.13  4951.2 1346.51
  4972.9 1341.46  4987.2 1335.15    4991 1327.93  5002.5 1325.97  5003.7 1325.27
    5058 1325.97  5062.1 1332.28  5084.6 1341.05  5096.4 1353.13  5152.1 1359.92
  5330.9 1361.01  5426.3 1360.83    5491 1360.57  5631.3 1358.74    5906 1365.35
#Mann= 19 ,-1 , 0
  2479.7     .12       0    2605     .07       0  2696.9     .05       0
  2872.9     .07       0  3008.3     .05       0  3219.8     .07       0
  3271.1     .05       0  3790.2     .07       0    3986    .035       0
  4670.1     .07       0  4728.3    .035       0  4789.4     .07       0
  4951.2     .12       0  5002.5     .05       0    5058     .12       0
  5152.1    .035       0  5330.9    .045       0  5426.3    .035       0
    5491    .045       0
Bank Sta=5002.5,5058
XS Rating Curve= 0 ,0
Exp/Cntr=0.3,0.1

Chan Stop Cuts=-1
Use User Specified Reach Order=0
Composite Channel Slope=5