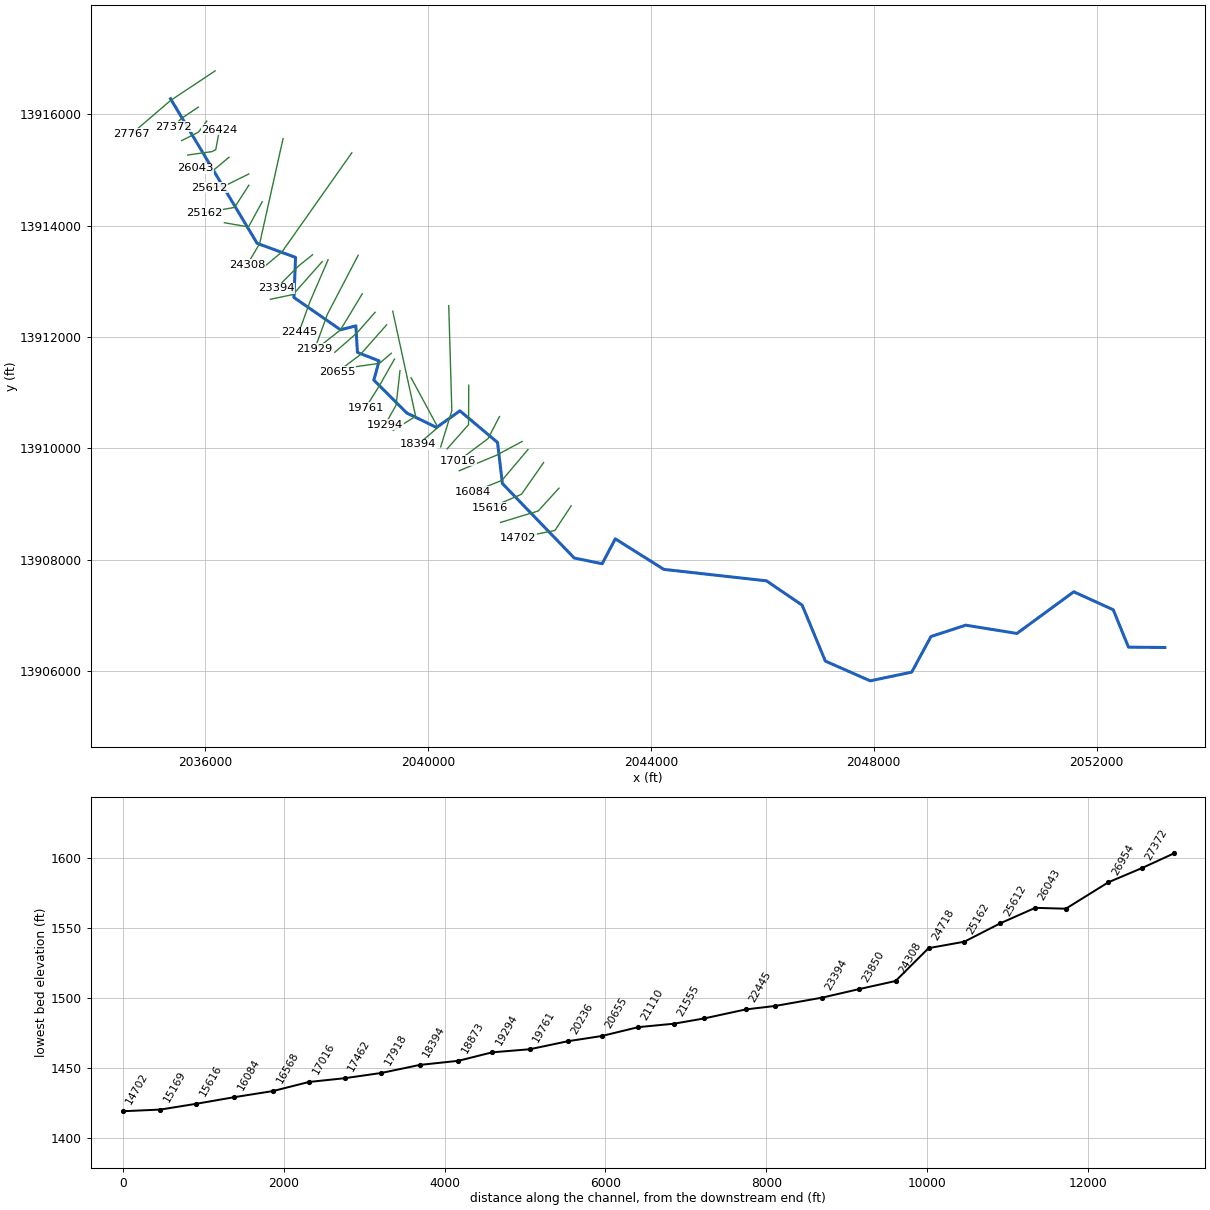
--- DARMSTADT CREEK.prj (project) ---

Proj Title=DARMSTADT CREEK Base Level Engineering
Current Plan=p01
Default Exp/Contr=0.3,0.1
English Units
Geom File=g01
Flow File=f01
Plan File=p01
Y Axis Title=Elevation
X Axis Title(PF)=Main Channel Distance
X Axis Title(XS)=Station
BEGIN DESCRIPTION:
DARMSTADT CREEK
END DESCRIPTION:
DSS Export Rating Curves= 0
DSS Export Rating Curve Sorted= 0
DSS Export Volume Flow Curves= 0
DXF OffsetX= 0
DXF OffsetY= 0
DXF ScaleX= 1
DXF ScaleY= 10

--- DARMSTADT CREEK.p01 (plan) ---

Plan Title=Multiple Run
Short Identifier=Multiple
Geom File=g01
Flow File=f01
Subcritical Flow
K Sum by GR= 0
Std Step Tol= 0.01
Critical Tol= 0.01
Num of Std Step Trials= 20
Max Error Tol= 0.3
Flow Tol Ratio= 0.001
Split Flow NTrial= 30
Split Flow Tol= 0.02
Split Flow Ratio= 0.02
Log Output Level= 0
Friction Slope Method= 1
Unsteady Friction Slope Method= 2
Unsteady Bridges Friction Slope Method= 1
Parabolic Critical Depth
Global Vel Dist=  1 , 1 , 1
Global Log Level= 0
CheckData=True
Encroach Param= -1, 0, 0, 0
BEGIN DESCRIPTION:
Multiple Run
END DESCRIPTION:

--- DARMSTADT CREEK.f01 (steady flow) ---

Flow Title=Multiple
Number of Profiles=7
Profile Names=10-year,25-year,50-year,1pct_min,100-year,1pct_plu,500-year
River Rch & RM= DARMSTADT CREEK,Reach-1,27767
     444     722     979     647    1291    2576    2218
River Rch & RM= DARMSTADT CREEK,Reach-1,27372
     972    1664    2332    1588    3169    6322    5795
River Rch & RM= DARMSTADT CREEK,Reach-1,24308
    1622    2847    4055    2800    5587   11147   10516
River Rch & RM= DARMSTADT CREEK,Reach-1,19761
    2541    4520    6489    4503    8984   17925   17056
River Rch & RM= DARMSTADT CREEK,Reach-1,11020
    3039    5426    7810    5431   10836   21621   20653
River Rch & RM= DARMSTADT CREEK,Reach-1,7803
    3326    5948    8571    5963   11897   23738   22698
River Rch & RM= DARMSTADT CREEK,Reach-1,2351
    3933    7081   10251    7160   14286   28505   27482
Boundary for River Rch & Prof#=DARMSTADT CREEK,Reach-1,1
Up Type=0
Dn Type=3
Dn Slope=0.005
Boundary for River Rch & Prof#=DARMSTADT CREEK,Reach-1,2
Up Type=0
Dn Type=3
Dn Slope=0.005
Boundary for River Rch & Prof#=DARMSTADT CREEK,Reach-1,3
Up Type=0
Dn Type=3
Dn Slope=0.005
Boundary for River Rch & Prof#=DARMSTADT CREEK,Reach-1,4
Up Type=0
Dn Type=3
Dn Slope=0.005
Boundary for River Rch & Prof#=DARMSTADT CREEK,Reach-1,5
Up Type=0
Dn Type=3
Dn Slope=0.005
Boundary for River Rch & Prof#=DARMSTADT CREEK,Reach-1,6
Up Type=0
Dn Type=3
Dn Slope=0.005
Boundary for River Rch & Prof#=DARMSTADT CREEK,Reach-1,7
Up Type=0
Dn Type=3
Dn Slope=0.005

--- DARMSTADT CREEK.g01 (geometry) ---

Geom Title=Existing Conditions
Program Version=4.10

River Reach=DARMSTADT CREEK ,Reach-1
Reach XY= 30
        2035375.       13916275.      2036930.23     13913680.02
      2037619.48     13913427.44      2037591.27     13912707.86
      2038426.63     13912128.12      2038702.28     13912199.15
      2038730.34     13911722.26      2039119.91     13911569.56
        2039025.       13911225.      2039618.83     13910632.86
      2040150.21     13910374.64      2040569.76     13910672.92
      2041245.59     13910105.42      2041332.69     13909368.52
      2042622.71     13908030.84      2043123.78     13907928.43
      2043359.58     13908375.13       2044230.7     13907826.91
      2046073.45     13907621.25      2046714.22     13907184.68
      2047130.25     13906180.44      2047935.51     13905826.22
      2048681.06     13905982.48      2049026.25     13906621.49
      2049649.92      13906825.2      2050569.29     13906676.94
      2051590.17     13907424.63      2052298.71     13907101.82
       2052572.3     13906430.36        2053225.       13906425.

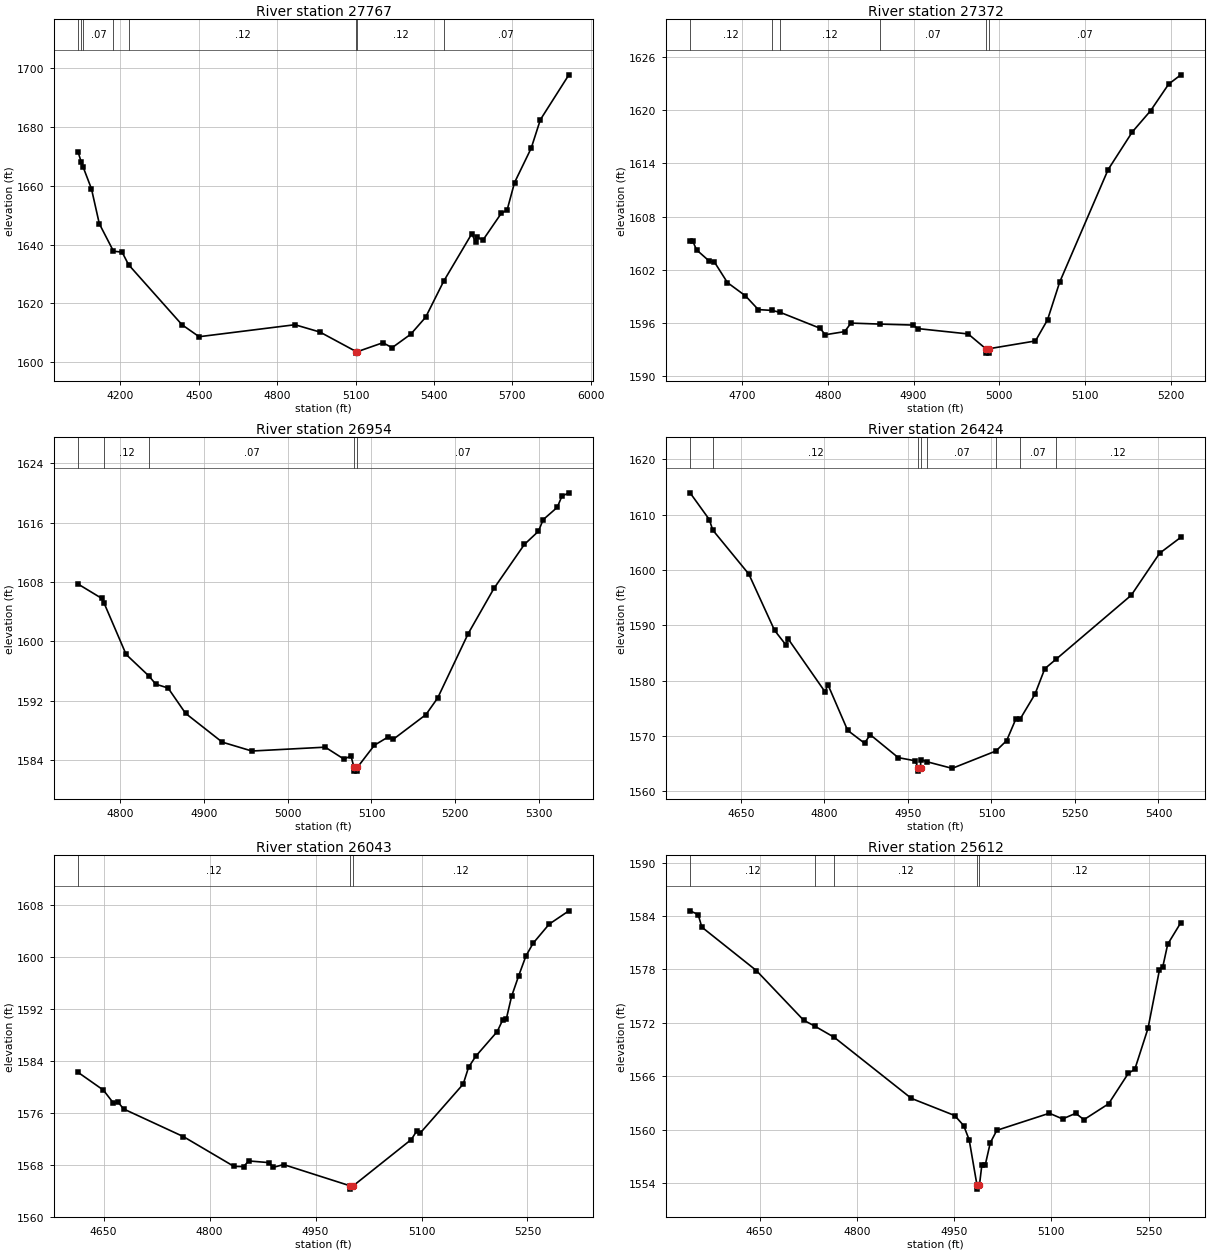
Type RM Length L Ch R = 1 ,27767   ,395,395,395
BEGIN DESCRIPTION:
DARMSTADT CREEK 57.0
END DESCRIPTION:
XS GIS Cut Line= 3
      2036176.24     13916775.97      2035374.61     13916243.79
      2034678.63     13915647.63
#Sta/Elev= 30
  4037.8 1671.52  4049.4 1668.21  4057.4 1666.32    4089 1658.97  4119.1 1647.07
  4173.3 1637.72  4206.3 1637.41    4231 1633.13  4435.4  1612.7    4501 1608.61
  4867.9 1612.69  4963.5  1610.2  5102.8 1603.52  5103.1 1603.02  5106.8 1603.52
  5204.6 1606.56  5239.7 1604.87  5311.1 1609.46  5368.2 1615.25  5437.2  1627.5
  5544.9 1643.69  5559.1 1640.77  5565.7 1642.56  5587.7 1641.54  5657.9 1650.66
  5679.9 1651.73  5708.4  1661.1  5772.1  1672.8  5807.2 1682.49  5916.4 1697.78
#Mann= 8 ,-1 , 0
  4037.8     .07       0  4049.4     .12       0  4057.4     .07       0
  4173.3    .035       0    4231     .12       0  5102.8     .05       0
  5106.8     .12       0  5437.2     .07       0
Bank Sta=5102.8,5106.8
XS Rating Curve= 0 ,0
Exp/Cntr=0.3,0.1

Type RM Length L Ch R = 1 ,27372   ,418,418,418
BEGIN DESCRIPTION:
DARMSTADT CREEK 56.0
END DESCRIPTION:
XS GIS Cut Line= 3
      2035874.99       13916125.        2035575.       13915925.
      2035424.99     13915774.99
#Sta/Elev= 30
  4639.2 1605.27  4642.2 1605.27  4646.7 1604.25  4661.7 1602.97  4667.7 1602.86
  4682.8 1600.56  4703.8 1599.07  4718.8 1597.52  4734.5 1597.43  4744.4 1597.21
  4790.9 1595.42  4796.9 1594.69  4819.5 1595.04    4827    1596  4860.5 1595.89
  4899.1 1595.78  4905.1 1595.38  4963.7 1594.78  4984.2 1593.12  4984.5 1592.62
    4988 1592.62  4988.2 1593.12  5042.2 1593.99  5056.3 1596.37  5070.5 1600.62
    5127 1613.28  5155.3 1617.53  5176.5  1619.9  5197.7 1622.91  5211.9 1623.95
#Mann= 6 ,-1 , 0
  4639.2     .12       0  4734.5     .07       0  4744.4     .12       0
  4860.5     .07       0  4984.2     .05       0  4988.2     .07       0
Bank Sta=4984.2,4988.2
XS Rating Curve= 0 ,0
Exp/Cntr=0.3,0.1

Type RM Length L Ch R = 1 ,26954   ,530,530,530
BEGIN DESCRIPTION:
DARMSTADT CREEK 55.0
END DESCRIPTION:
XS GIS Cut Line= 3
      2036025.02     13915875.02        2035875.       13915675.
      2035575.04     13915525.02
#Sta/Elev= 30
  4750.1 1607.72  4778.3 1605.79  4781.2 1605.13  4807.4 1598.23  4834.7 1595.31
  4842.8 1594.22  4857.4 1593.71  4878.3 1590.29    4922 1586.41  4957.4 1585.21
  5044.9 1585.73  5067.2 1584.12  5075.6 1584.54  5079.2    1583  5079.4  1582.5
  5082.9  1582.5  5083.2    1583  5103.5 1585.99  5120.3 1587.13  5125.9 1586.78
    5165 1590.12    5179 1592.36  5215.4 1601.04  5246.1 1607.13  5282.4 1613.06
  5299.2 1614.84  5304.8  1616.4  5321.6 1618.06  5327.2 1619.57  5335.5 1620.02
#Mann= 5 ,-1 , 0
  4750.1     .07       0  4781.2     .12       0  4834.7     .07       0
  5079.2     .05       0  5083.2     .07       0
Bank Sta=5079.2,5083.2
XS Rating Curve= 0 ,0
Exp/Cntr=0.3,0.1

Type RM Length L Ch R = 1 ,26424   ,381,381,381
BEGIN DESCRIPTION:
DARMSTADT CREEK 54.0
END DESCRIPTION:
XS GIS Cut Line= 4
      2035684.69     13915265.32      2036121.84     13915327.18
      2036187.05     13915362.96      2036254.93     13915722.53
#Sta/Elev= 30
  4558.5 1613.93    4593 1609.11  4599.2 1607.21  4664.1 1599.24  4710.3 1589.08
  4730.1 1586.52  4735.1 1587.48  4801.1 1577.95  4806.1 1579.28  4841.6 1571.01
  4871.9 1568.69  4882.2 1570.22  4932.5 1566.08  4962.8 1565.51  4968.6 1564.14
  4968.9 1563.64  4972.6 1564.14  4972.9 1565.73  4984.3 1565.33  5029.4 1564.14
    5108 1567.28  5127.3 1569.16  5143.4 1572.97  5151.5 1573.05  5178.2 1577.55
  5195.8 1582.15  5215.7 1583.83  5351.2 1595.43  5402.1 1603.01  5440.3  1605.9
#Mann= 8 ,-1 , 0
  4558.5     .07       0  4599.2     .12       0  4968.6     .05       0
  4972.6     .12       0  4984.3     .07       0    5108     .12       0
  5151.5     .07       0  5215.7     .12       0
Bank Sta=4968.6,4972.6
XS Rating Curve= 0 ,0
Exp/Cntr=0.3,0.1

Type RM Length L Ch R = 1 ,26043   ,431,431,431
BEGIN DESCRIPTION:
DARMSTADT CREEK 53.0
END DESCRIPTION:
XS GIS Cut Line= 3
      2036425.01     13915225.01        2036125.       13914975.
      2035824.96     13915025.01
#Sta/Elev= 30
  4613.9 1582.22  4649.7 1579.49    4664 1577.48  4670.5 1577.64  4678.3 1576.59
    4763 1572.33  4834.5 1567.75  4848.2 1567.72  4855.4 1568.59    4884 1568.33
  4890.5 1567.61  4904.8 1568.03  4999.2 1564.75  4999.4 1564.25  5003.2 1564.75
  5085.5 1571.88  5093.1 1573.16  5098.2 1572.88    5159 1580.41  5166.6    1583
  5176.8  1584.7  5207.2  1588.5  5214.8 1590.26  5219.9 1590.38  5227.5 1593.92
  5237.6  1597.1  5247.7  1600.1  5257.9 1602.08  5280.7 1605.03  5308.6 1607.08
#Mann= 3 ,-1 , 0
  4613.9     .12       0  4999.2     .05       0  5003.2     .12       0
Bank Sta=4999.2,5003.2
XS Rating Curve= 0 ,0
Exp/Cntr=0.3,0.1

Type RM Length L Ch R = 1 ,25612   ,450,450,450
BEGIN DESCRIPTION:
DARMSTADT CREEK 52.0
END DESCRIPTION:
XS GIS Cut Line= 3
      2036780.98     13914925.63        2036375.       13914725.
      2036074.99       13914675.
#Sta/Elev= 30
  4542.7 1584.59  4555.2 1584.17  4560.8 1582.76  4644.9 1577.88  4717.8  1572.3
  4735.3 1571.62  4764.9 1570.38    4884 1563.51  4950.9 1561.58  4964.7 1560.45
  4973.2 1558.85  4985.1 1553.81  4985.4 1553.31  4989.1 1553.81  4992.8 1556.07
  4998.1 1556.07  5005.7 1558.51  5015.8 1559.92  5096.9 1561.84  5117.2  1561.2
  5137.5 1561.83  5150.2 1561.12  5188.2  1562.9  5218.6 1566.32  5228.7 1566.79
    5249 1571.38  5266.7 1577.96  5271.8  1578.3  5279.4 1580.84  5299.7 1583.27
#Mann= 5 ,-1 , 0
  4542.7     .12       0  4735.3     .07       0  4764.9     .12       0
  4985.1     .05       0  4989.1     .12       0
Bank Sta=4985.1,4989.1
XS Rating Curve= 0 ,0
Exp/Cntr=0.3,0.1

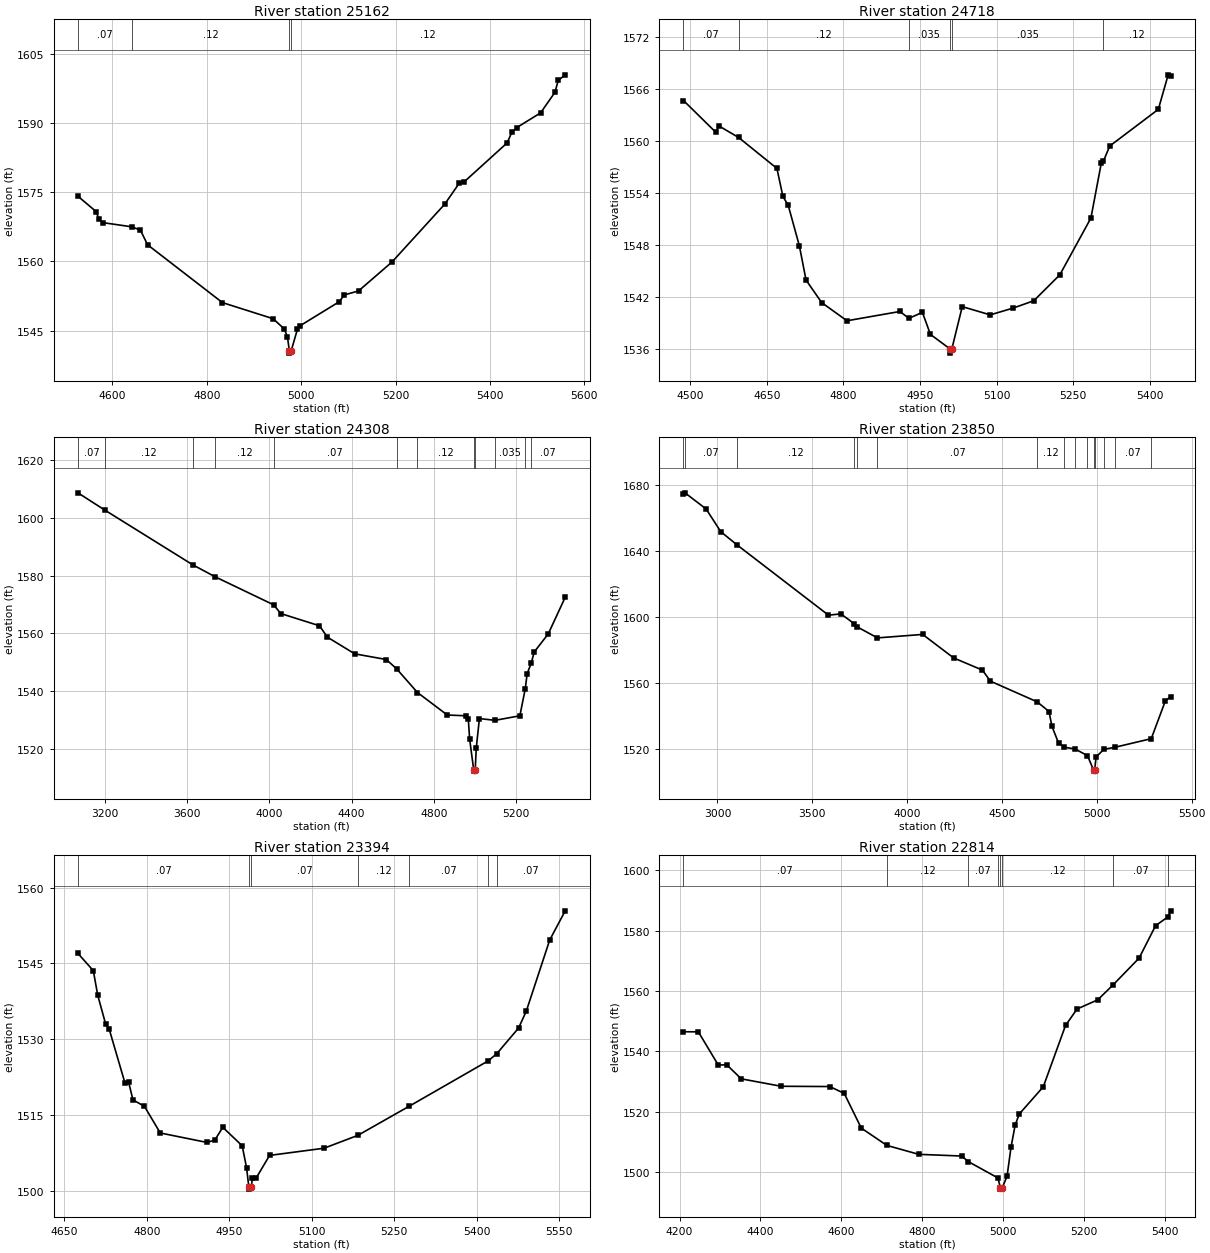
Type RM Length L Ch R = 1 ,25162   ,444,444,444
BEGIN DESCRIPTION:
DARMSTADT CREEK 51.0
END DESCRIPTION:
XS GIS Cut Line= 3
      2036780.97     13914722.52        2036525.       13914325.
      2035973.62      13914227.7
#Sta/Elev= 30
  4526.9 1574.14  4565.6  1570.8  4571.6 1569.13  4580.8  1568.4  4640.9 1567.51
  4659.4 1566.79  4674.5 1563.62  4833.2 1551.08  4940.6 1547.59    4964 1545.39
    4971 1543.66  4974.9 1540.63  4975.2 1540.13  4978.9 1540.63  4992.1 1545.31
  4996.7    1546  5080.9 1551.28  5091.1 1552.73  5121.6 1553.61  5192.6 1559.89
  5304.3 1572.42  5334.8 1576.93    5345 1577.21  5436.4 1585.69  5446.5 1587.99
  5456.7    1589  5507.4  1592.2  5537.9 1596.67  5544.7 1599.23  5559.6 1600.45
#Mann= 4 ,-1 , 0
  4526.9     .07       0  4640.9     .12       0  4974.9     .05       0
  4978.9     .12       0
Bank Sta=4974.9,4978.9
XS Rating Curve= 0 ,0
Exp/Cntr=0.3,0.1

Type RM Length L Ch R = 1 ,24718   ,410,410,410
BEGIN DESCRIPTION:
DARMSTADT CREEK 50.0
END DESCRIPTION:
XS GIS Cut Line= 3
      2037020.55     13914425.63        2036775.       13913975.
      2036340.94     13914050.16
#Sta/Elev= 30
    4487 1564.68  4550.6    1561  4556.3 1561.75  4594.9 1560.42  4669.9 1556.85
  4681.6 1553.63  4692.1 1552.58  4713.9 1547.91  4726.9 1543.98  4757.6 1541.38
    4807 1539.29  4910.5 1540.36  4928.3 1539.57  4954.6 1540.26  4970.3 1537.72
  5008.3 1536.06  5008.6 1535.56  5012.3 1536.06  5032.6 1540.92  5087.3 1539.97
  5132.1 1540.75  5172.7  1541.6  5223.5 1544.58  5284.4 1551.13  5304.6 1557.43
  5308.6 1557.65  5321.2 1559.43  5416.3 1563.66  5435.6 1567.64  5440.7 1567.49
#Mann= 6 ,-1 , 0
    4487     .07       0  4594.9     .12       0  4928.3    .035       0
  5008.3    .035       0  5012.3    .035       0  5308.6     .12       0
Bank Sta=5008.3,5012.3
XS Rating Curve= 0 ,0
Exp/Cntr=0.3,0.1

Type RM Length L Ch R = 1 ,24308   ,458,458,458
BEGIN DESCRIPTION:
DARMSTADT CREEK 49.0
END DESCRIPTION:
XS GIS Cut Line= 3
      2037395.54     13915561.01        2036975.       13913675.
      2036749.83     13913295.62
#Sta/Elev= 30
    3067  1608.7  3198.7 1602.68    3627  1583.7    3736 1579.55    4021 1569.82
  4054.5 1566.83  4243.7 1562.57  4282.1 1558.63  4415.3 1552.84    4569 1550.87
  4619.4 1547.64  4720.9 1539.42  4866.1 1531.62  4958.3 1531.34  4968.6  1530.1
    4975 1523.24  4994.7 1512.65    4995 1512.15  4998.8 1512.65  5002.2 1512.65
  5007.1 1520.11  5022.6 1530.39  5098.5 1529.77  5219.6 1531.35  5245.6 1540.62
  5255.2 1545.98  5274.3 1549.49    5290 1553.53  5357.9 1559.77  5440.5 1572.47
#Mann= 12 ,-1 , 0
    3067     .07       0  3198.7     .12       0    3627     .07       0
    3736     .12       0    4021     .07       0  4619.4    .035       0
  4720.9     .12       0  4994.7     .05       0  4998.8     .12       0
  5098.5    .035       0  5245.6     .12       0  5274.3     .07       0
Bank Sta=4994.7,4998.8
XS Rating Curve= 0 ,0
Exp/Cntr=0.3,0.1

Type RM Length L Ch R = 1 ,23850   ,456,456,456
BEGIN DESCRIPTION:
DARMSTADT CREEK 48.0
END DESCRIPTION:
XS GIS Cut Line= 3
       2038629.9     13915305.81        2037375.       13913525.
      2037074.97     13913274.97
#Sta/Elev= 30
  2820.8 1674.86  2828.7 1675.38  2940.1 1665.58  3017.6 1651.76  3105.4 1643.55
  3585.4 1601.06  3650.7 1601.85  3720.5 1595.93  3737.6  1593.9  3843.5 1587.26
  4081.8 1589.37  4245.6 1575.06  4397.1 1567.69  4438.9 1560.98  4685.7 1548.41
  4748.1 1542.54  4762.9 1533.68  4798.6 1523.29  4827.6 1520.86  4884.7  1519.8
  4950.7 1515.75  4983.4 1506.83  4983.8 1506.33  4988.2 1506.83  4996.3 1514.93
  5036.9 1519.54  5095.8 1520.83    5287 1526.04  5361.9 1549.17  5389.9 1551.53
#Mann= 15 ,-1 , 0
  2820.8     .12       0  2828.7     .07       0  3105.4     .12       0
  3720.5     .07       0  3737.6    .035       0  3843.5     .07       0
  4685.7     .12       0  4827.6     .07       0  4884.7    .035       0
  4950.7     .07       0  4983.4     .05       0  4988.2     .07       0
  5036.9     .12       0  5095.8     .07       0    5287     .12       0
Bank Sta=4983.4,4988.2
XS Rating Curve= 0 ,0
Exp/Cntr=0.3,0.1

Type RM Length L Ch R = 1 ,23394   ,580,580,580
BEGIN DESCRIPTION:
DARMSTADT CREEK 47.0
END DESCRIPTION:
XS GIS Cut Line= 3
        2037925.       13913475.        2037675.       13913275.
      2037275.03     13912875.03
#Sta/Elev= 30
  4674.8 1546.99  4702.8 1543.57  4710.8 1538.72  4725.2    1533  4731.6 1532.02
  4760.4 1521.29  4766.9 1521.52  4774.9 1517.97  4795.7  1516.7  4824.5 1511.42
  4909.3 1509.55  4923.7 1510.01  4938.1 1512.55  4973.4 1508.89  4981.4 1504.52
  4985.4  1500.8  4985.7  1500.3  4990.2  1500.8  4991.8 1502.44  4998.5 1502.44
  5023.2 1506.98  5122.2  1508.4  5183.7 1510.95  5277.5 1516.75    5421 1525.73
  5436.3 1527.14  5475.8  1532.2  5489.9 1535.57  5532.4 1549.64  5560.6 1555.42
#Mann= 7 ,-1 , 0
  4674.8     .07       0  4985.4     .05       0  4990.2     .07       0
  5183.7     .12       0  5277.5     .07       0    5421     .12       0
  5436.3     .07       0
Bank Sta=4985.4,4990.2
XS Rating Curve= 0 ,0
Exp/Cntr=0.3,0.1

Type RM Length L Ch R = 1 ,22814   ,369,369,369
BEGIN DESCRIPTION:
DARMSTADT CREEK 46.0
END DESCRIPTION:
XS GIS Cut Line= 3
      2038098.65     13913352.69      2037574.48     13912761.11
      2037168.19     13912676.01
#Sta/Elev= 30
  4209.6 1546.52  4246.4 1546.49  4295.7 1535.49  4316.6 1535.58  4352.6 1530.92
  4451.3 1528.46  4571.7 1528.37  4607.3 1526.09  4649.5 1514.61  4712.7 1508.88
  4791.7 1505.92  4897.9 1505.36  4914.3 1503.51  4987.6 1498.09  4993.4  1494.9
  4993.7  1494.4  4998.3  1494.9  5010.1 1498.67  5019.9 1508.29  5030.1  1515.6
  5040.3 1519.27  5099.7 1528.29  5154.8 1548.62  5183.4 1554.06  5234.5 1557.09
    5273 1562.12  5336.6 1570.88  5377.5 1581.63  5408.4 1584.61  5415.1 1586.56
#Mann= 8 ,-1 , 0
  4209.6     .07       0  4712.7     .12       0  4914.3     .07       0
  4987.6     .12       0  4993.4     .05       0  4998.3     .12       0
    5273     .07       0  5408.4     .12       0
Bank Sta=4993.4,4998.3
XS Rating Curve= 0 ,0
Exp/Cntr=0.3,0.1

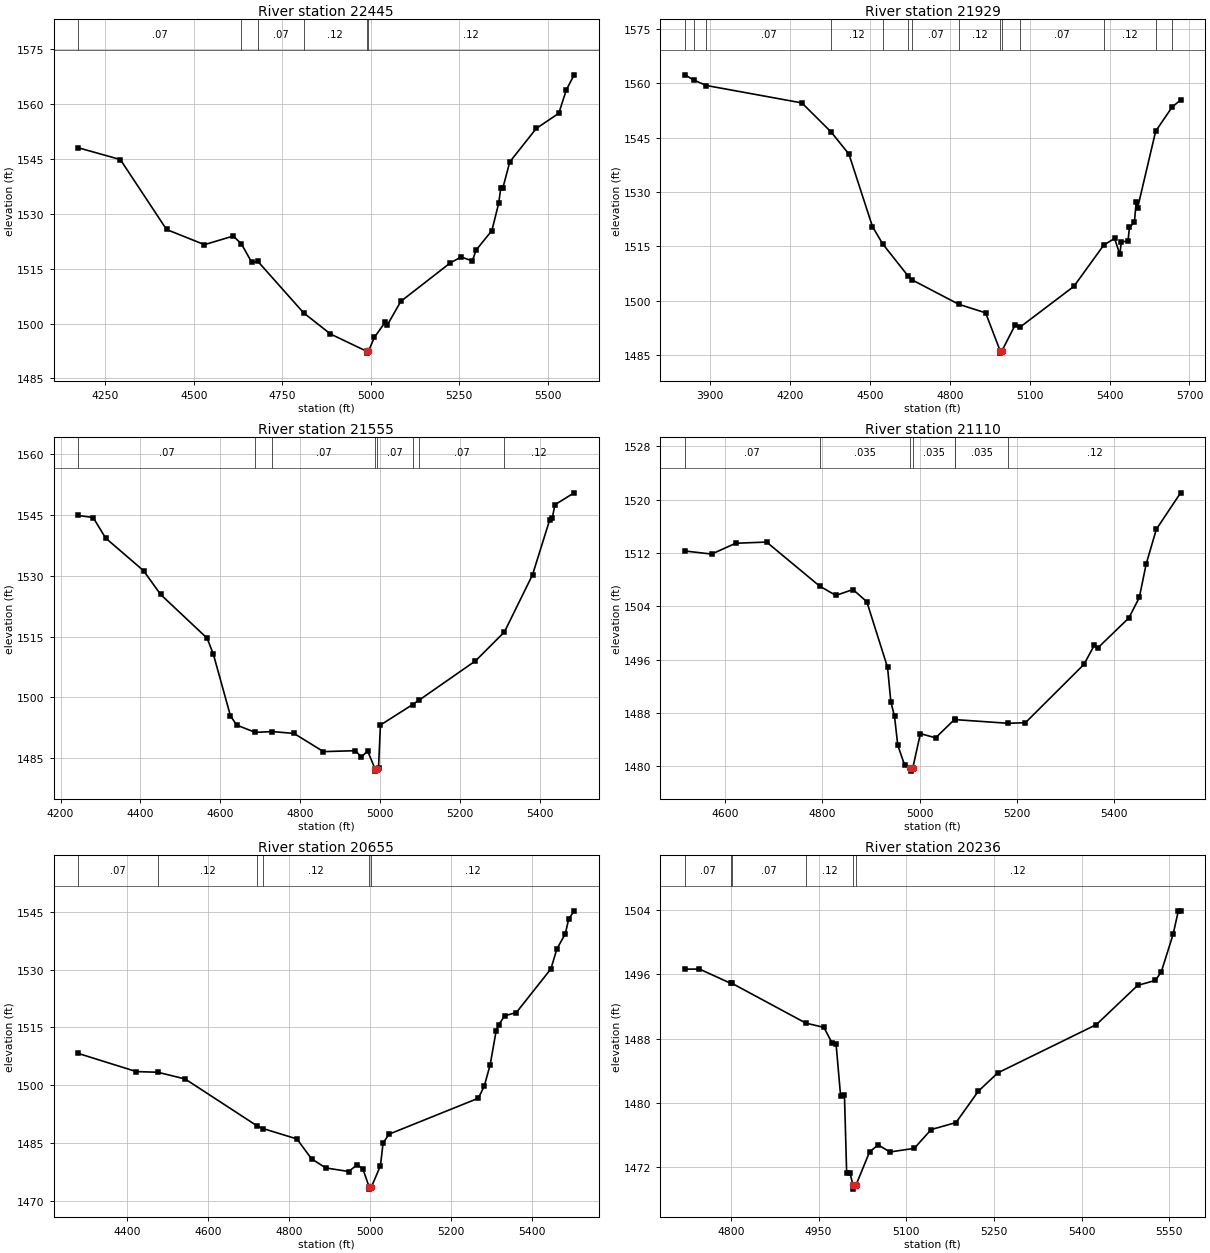
Type RM Length L Ch R = 1 ,22445   ,516,516,516
BEGIN DESCRIPTION:
DARMSTADT CREEK 45.0
END DESCRIPTION:
XS GIS Cut Line= 3
      2038202.85     13913383.99        2037875.       13912625.
      2037680.04     13912084.14
#Sta/Elev= 30
  4173.2    1548  4291.9 1544.79  4422.6 1525.68  4529.8 1521.54  4611.2 1523.89
  4634.2 1521.75  4663.6 1516.68  4680.8 1516.96  4809.9 1502.93    4886 1497.13
  4988.5 1492.41  4988.8 1491.91  4993.4 1492.41    5010  1496.2  5040.7 1500.36
    5046 1499.47    5085 1506.06  5224.8 1516.56  5255.5 1518.17    5287 1517.08
  5297.6 1520.04  5342.3 1525.38  5361.4 1532.79  5367.6 1537.07    5373  1536.9
    5393 1544.16  5467.7 1553.27  5531.5 1557.42  5552.7  1563.8  5574.9 1567.93
#Mann= 6 ,-1 , 0
  4173.2     .07       0  4634.2     .12       0  4680.8     .07       0
  4809.9     .12       0  4988.5     .05       0  4993.4     .12       0
Bank Sta=4988.5,4993.4
XS Rating Curve= 0 ,0
Exp/Cntr=0.3,0.1

Type RM Length L Ch R = 1 ,21929   ,374,374,374
BEGIN DESCRIPTION:
DARMSTADT CREEK 44.0
END DESCRIPTION:
XS GIS Cut Line= 3
      2038744.48     13913467.25      2038191.83      13912408.4
      2037963.16     13911782.04
#Sta/Elev= 30
  3805.6 1562.39  3840.8 1560.89  3886.8 1559.44    4245 1554.63  4354.6 1546.62
  4421.7 1540.48    4510 1520.48  4548.2  1515.7  4644.9  1506.7  4658.1 1505.76
  4834.1 1498.99  4934.8 1496.63  4990.1    1486  4990.5  1485.5  4995.1    1486
  5046.2 1493.37  5065.3 1492.75  5266.1 1503.94  5378.5 1515.37  5418.9 1517.18
  5438.8 1512.76  5444.1 1516.25  5469.3 1516.45  5474.6 1520.22  5493.3 1521.64
  5499.9 1527.24  5505.2 1525.57  5573.1 1546.81  5634.8 1553.47  5666.8 1555.44
#Mann= 14 ,-1 , 0
  3805.6     .12       0  3840.8    .035       0  3886.8     .07       0
  4354.6     .12       0  4548.2     .07       0  4644.9     .12       0
  4658.1     .07       0  4834.1     .12       0  4990.1     .05       0
  4995.1     .12       0  5065.3     .07       0  5378.5     .12       0
  5573.1     .07       0  5634.8     .12       0
Bank Sta=4990.1,4995.1
XS Rating Curve= 0 ,0
Exp/Cntr=0.3,0.1

Type RM Length L Ch R = 1 ,21555   ,445,445,445
BEGIN DESCRIPTION:
DARMSTADT CREEK 43.0
END DESCRIPTION:
XS GIS Cut Line= 3
      2038817.45     13912774.63        2038425.       13912125.
      2038046.62     13911826.69
#Sta/Elev= 30
  4244.6 1544.93  4281.7 1544.42  4312.7 1539.36  4407.7 1531.29  4450.5 1525.41
  4566.9  1514.6  4582.5 1510.65  4625.2 1495.45  4640.7 1493.14  4687.4 1491.34
  4730.2 1491.53  4784.3 1491.07    4858 1486.58  4937.6 1486.81  4953.1 1485.25
  4968.5 1486.76  4987.4 1482.26  4987.8 1481.76  4992.5 1482.26  4995.8 1482.55
  5000.6 1493.14  5080.9 1498.19  5097.1 1499.28  5238.5    1509  5310.9 1516.15
  5381.2 1530.26  5423.8 1543.72  5430.9 1544.41  5437.2 1547.58  5485.4 1550.52
#Mann= 8 ,-1 , 0
  4244.6     .07       0  4687.4     .12       0  4730.2     .07       0
  4987.4     .05       0  4992.5     .07       0  5080.9     .12       0
  5097.1     .07       0  5310.9     .12       0
Bank Sta=4987.4,4992.5
XS Rating Curve= 0 ,0
Exp/Cntr=0.3,0.1

Type RM Length L Ch R = 1 ,21110   ,455,455,455
BEGIN DESCRIPTION:
DARMSTADT CREEK 42.0
END DESCRIPTION:
XS GIS Cut Line= 3
       2039046.6     13912441.27        2038725.       13912075.
      2038325.02     13911725.02
#Sta/Elev= 30
  4517.4 1512.29  4572.6 1511.83  4621.9 1513.45  4685.5 1513.63  4794.3 1507.04
  4827.8 1505.63    4863 1506.51  4891.4 1504.69  4934.1 1494.83  4940.8 1489.68
  4948.4 1487.49    4955 1483.19  4969.2 1480.17  4980.9 1479.79  4981.3 1479.29
    4986 1479.79  5001.5 1484.91  5032.8 1484.28  5072.3 1487.08  5073.5 1487.01
    5182 1486.46  5217.4 1486.55  5337.5 1495.28  5359.3  1498.2    5366 1497.75
    5430 1502.26  5451.4 1505.32  5465.6 1510.37  5486.5 1515.56  5536.3 1521.01
#Mann= 7 ,-1 , 0
  4517.4     .07       0  4794.3    .035       0  4980.9    .035       0
    4986    .035       0  5072.3     .12       0  5073.5    .035       0
    5182     .12       0
Bank Sta=4980.9,4986
XS Rating Curve= 0 ,0
Exp/Cntr=0.3,0.1

Type RM Length L Ch R = 1 ,20655   ,419,419,419
BEGIN DESCRIPTION:
DARMSTADT CREEK 41.0
END DESCRIPTION:
XS GIS Cut Line= 3
      2039254.93      13912217.3        2038775.       13911675.
      2038374.98     13911374.98
#Sta/Elev= 30
  4279.8  1508.2  4423.1 1503.49  4476.1 1503.32  4543.5 1501.57  4721.2 1489.39
  4735.5 1488.71  4819.5    1486  4855.5 1480.85  4890.6 1478.48  4947.5 1477.54
  4968.4 1479.35  4982.6 1478.11  4998.1 1473.47  4998.4 1472.97  5003.2 1473.47
  5025.8 1479.06  5032.1  1484.9  5046.7 1487.23  5267.5 1496.58  5282.1 1499.74
  5296.7  1505.3  5311.3 1514.02  5317.5 1515.54  5332.1 1517.97  5361.3 1518.83
  5446.7 1530.18  5461.3 1535.34  5482.1 1539.26  5490.4 1543.05    5504 1545.24
#Mann= 6 ,-1 , 0
  4279.8     .07       0  4476.1     .12       0  4721.2     .07       0
  4735.5     .12       0  4998.1     .05       0  5003.2     .12       0
Bank Sta=4998.1,5003.2
XS Rating Curve= 0 ,0
Exp/Cntr=0.3,0.1

Type RM Length L Ch R = 1 ,20236   ,475,475,475
BEGIN DESCRIPTION:
DARMSTADT CREEK 40.0
END DESCRIPTION:
XS GIS Cut Line= 3
      2039338.27     13911706.88        2039125.       13911525.
      2038562.25     13911446.46
#Sta/Elev= 30
    4721 1496.64    4746 1496.66  4799.6 1494.88    4802 1494.87  4928.2 1489.93
    4959  1489.4  4973.3 1487.43  4979.9  1487.3  4987.6  1480.9  4994.2 1481.01
    4998 1471.28  5003.8 1471.28  5008.7 1469.78  5009.1 1469.28    5014 1469.78
  5037.1  1473.9  5051.8 1474.79    5072  1473.9  5113.6 1474.35  5142.6 1476.69
  5185.1 1477.56  5223.4 1481.47  5256.6 1483.74  5425.4 1489.75    5496 1494.63
  5526.3 1495.24  5536.4 1496.31  5556.6 1500.97  5565.6  1503.9  5569.5  1503.9
#Mann= 6 ,-1 , 0
    4721     .07       0  4799.6    .035       0    4802     .07       0
  4928.2     .12       0  5008.7     .05       0    5014     .12       0
Bank Sta=5008.7,5014
XS Rating Curve= 0 ,0
Exp/Cntr=0.3,0.1

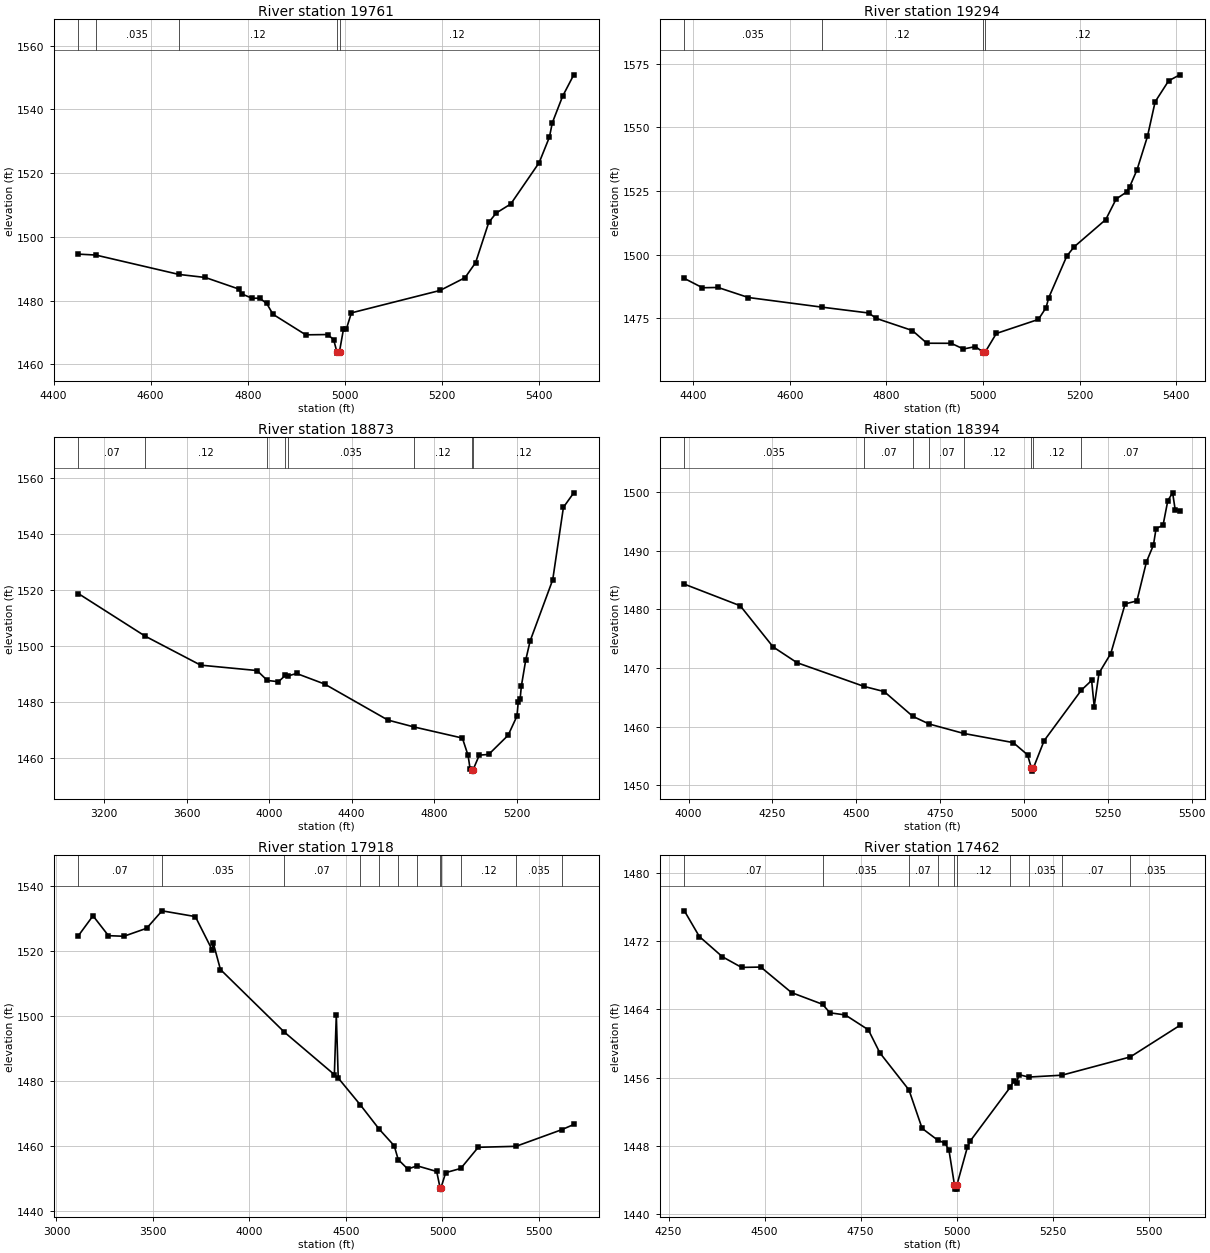
Type RM Length L Ch R = 1 ,19761   ,467,467,467
BEGIN DESCRIPTION:
DARMSTADT CREEK 39.0
END DESCRIPTION:
XS GIS Cut Line= 3
      2039395.56     13911602.73        2039125.       13911125.
      2038875.02     13910725.02
#Sta/Elev= 30
    4451 1494.61    4487 1494.32  4658.2 1488.24  4712.7 1487.28  4781.4 1483.67
  4787.2 1482.16  4808.8 1480.78  4824.7 1480.78  4839.1 1479.13  4852.1 1475.73
  4919.6 1469.29  4964.7 1469.38    4977  1467.8  4983.5 1464.05    4984 1463.55
  4989.1 1464.05  4997.2 1471.02    5003 1471.02  5013.6 1476.18  5196.4 1483.22
  5247.7 1487.22  5269.5 1491.94  5296.6 1504.57  5311.9  1507.5    5342 1510.35
  5400.4  1523.3  5421.6 1531.33  5427.5  1535.8  5448.7 1544.12  5471.7 1550.86
#Mann= 5 ,-1 , 0
    4451     .12       0    4487    .035       0  4658.2     .12       0
  4983.5     .05       0  4989.1     .12       0
Bank Sta=4983.5,4989.1
XS Rating Curve= 0 ,0
Exp/Cntr=0.3,0.1

Type RM Length L Ch R = 1 ,19294   ,421,421,421
BEGIN DESCRIPTION:
DARMSTADT CREEK 38.0
END DESCRIPTION:
XS GIS Cut Line= 3
       2039494.5     13911394.36        2039425.       13910775.
      2039224.98     13910424.97
#Sta/Elev= 30
  4381.3 1490.71  4418.8 1487.05  4451.1 1487.15  4513.9 1483.21  4665.6 1479.44
    4763 1477.13  4779.3 1474.98  4853.6 1470.24  4883.8 1465.25  4934.1 1465.22
  4959.5 1462.98  4984.4 1463.93  4999.2 1461.86  4999.7 1461.36  5004.8 1461.86
  5027.6 1469.08  5114.7  1474.6  5130.5 1479.18  5136.3 1483.18  5173.7 1499.52
  5188.8 1503.11  5254.3 1513.82  5275.9 1521.92  5297.5 1524.65    5304 1526.76
  5319.1 1533.39  5340.7 1546.47  5356.6 1560.09  5384.6 1568.35  5407.7 1570.69
#Mann= 4 ,-1 , 0
  4381.3    .035       0  4665.6     .12       0  4999.2     .05       0
  5004.8     .12       0
Bank Sta=4999.2,5004.8
XS Rating Curve= 0 ,0
Exp/Cntr=0.3,0.1

Type RM Length L Ch R = 1 ,18873   ,479,479,479
BEGIN DESCRIPTION:
DARMSTADT CREEK 37.0
END DESCRIPTION:
XS GIS Cut Line= 3
      2039364.31     13912462.04        2039775.       13910575.
      2039375.01     13910325.01
#Sta/Elev= 30
  3074.6 1518.84  3398.6 1503.61    3668 1493.22  3941.5 1491.29  3991.4 1487.74
  4045.4  1487.3  4078.4 1489.54  4091.3 1489.36  4133.3 1490.24    4269 1486.47
    4576 1473.58  4701.8 1471.13  4937.3 1467.14  4964.9 1460.95  4975.1 1455.95
  4983.5 1455.81    4984 1455.31  4989.2 1455.81  5019.4 1461.03  5064.8 1461.28
  5159.1 1468.13  5202.2 1475.01  5208.1 1479.95  5217.5  1481.2  5223.4 1485.73
  5244.6 1495.05  5265.8 1501.84  5375.5 1523.76  5427.4 1549.69  5477.5 1554.87
#Mann= 8 ,-1 , 0
  3074.6     .07       0  3398.6     .12       0  3991.4    .035       0
  4078.4     .12       0  4091.3    .035       0  4701.8     .12       0
  4983.5     .05       0  4989.2     .12       0
Bank Sta=4983.5,4989.2
XS Rating Curve= 0 ,0
Exp/Cntr=0.3,0.1

Type RM Length L Ch R = 1 ,18394   ,476,476,476
BEGIN DESCRIPTION:
DARMSTADT CREEK 36.0
END DESCRIPTION:
XS GIS Cut Line= 3
      2039692.41      13911269.4        2040175.       13910375.
      2039824.98     13910074.98
#Sta/Elev= 30
  3987.4 1484.31    4154 1480.62  4252.1 1473.59  4323.4  1470.9  4523.8 1466.84
  4583.3 1465.97  4668.4 1461.75    4717 1460.44  4820.6 1458.82    4968 1457.26
  5010.8 1455.17  5022.2 1452.89  5022.7 1452.39  5027.9 1452.89  5060.2 1457.59
  5171.4 1466.23  5201.8 1467.87  5209.5 1463.42  5223.8 1469.13  5258.9 1472.46
  5301.7 1480.94  5336.8 1481.45  5365.3 1488.12  5386.2    1491  5393.9 1493.79
  5414.7 1494.36    5429 1498.57  5443.3  1499.9    5451    1497  5464.7 1496.82
#Mann= 8 ,-1 , 0
  3987.4    .035       0  4523.8     .07       0  4668.4    .035       0
    4717     .07       0  4820.6     .12       0  5022.2     .05       0
  5027.9     .12       0  5171.4     .07       0
Bank Sta=5022.2,5027.9
XS Rating Curve= 0 ,0
Exp/Cntr=0.3,0.1

Type RM Length L Ch R = 1 ,17918   ,456,456,456
BEGIN DESCRIPTION:
DARMSTADT CREEK 35.0
END DESCRIPTION:
XS GIS Cut Line= 3
       2040369.5     13912561.09        2040425.       13910675.
      2040224.99     13910024.98
#Sta/Elev= 30
  3113.2 1524.67  3189.3 1530.83  3269.4 1524.71  3349.4 1524.53  3467.3 1526.99
  3546.9 1532.36  3719.5 1530.59  3807.3 1520.26  3812.3 1522.48  3849.6 1514.29
  4180.7 1495.02  4439.9 1481.93  4449.9 1500.33  4459.9 1480.88    4574 1472.65
  4672.3 1465.13    4750 1460.03  4770.6 1455.79    4820 1452.87  4868.9 1453.85
  4970.1 1452.11  4987.2 1447.18  4987.7 1446.68  4992.9 1447.18  5016.5 1451.75
  5094.8 1453.05  5185.2 1459.56    5381 1459.86  5617.1 1464.96  5680.2 1466.58
#Mann= 12 ,-1 , 0
  3113.2     .07       0  3546.9    .035       0  4180.7     .07       0
    4574     .12       0  4672.3     .07       0  4770.6     .12       0
  4868.9     .07       0  4987.2     .05       0  4992.9     .07       0
  5094.8     .12       0    5381    .035       0  5617.1     .12       0
Bank Sta=4987.2,4992.9
XS Rating Curve= 0 ,0
Exp/Cntr=0.3,0.1

Type RM Length L Ch R = 1 ,17462   ,446,446,446
BEGIN DESCRIPTION:
DARMSTADT CREEK 34.0
END DESCRIPTION:
XS GIS Cut Line= 3
      2040728.88     13911133.96        2040725.       13910425.
      2040339.94     13909990.03
#Sta/Elev= 30
    4291 1475.55    4330 1472.54    4390 1470.17    4440 1468.92    4490 1468.96
    4570 1465.97  4650.7  1464.6    4670  1463.6    4710 1463.35    4770 1461.61
    4800 1458.91  4875.8 1454.56    4910 1450.06  4950.4 1448.69    4970 1448.31
    4980 1447.48  4994.2 1443.44  4994.7 1442.94  5000.2 1442.94  5000.7 1443.44
    5028 1447.88  5035.5 1448.59    5139 1454.85  5148.4 1455.59    5156 1455.43
  5162.6 1456.35  5187.3 1456.07    5274 1456.29    5452 1458.43  5580.9 1462.12
#Mann= 10 ,-1 , 0
    4291     .07       0  4650.7    .035       0  4875.8     .07       0
  4950.4     .12       0  4994.2     .05       0  5000.7     .12       0
    5139     .07       0  5187.3    .035       0    5274     .07       0
    5452    .035       0
Bank Sta=4994.2,5000.7
XS Rating Curve= 0 ,0
Exp/Cntr=0.3,0.1

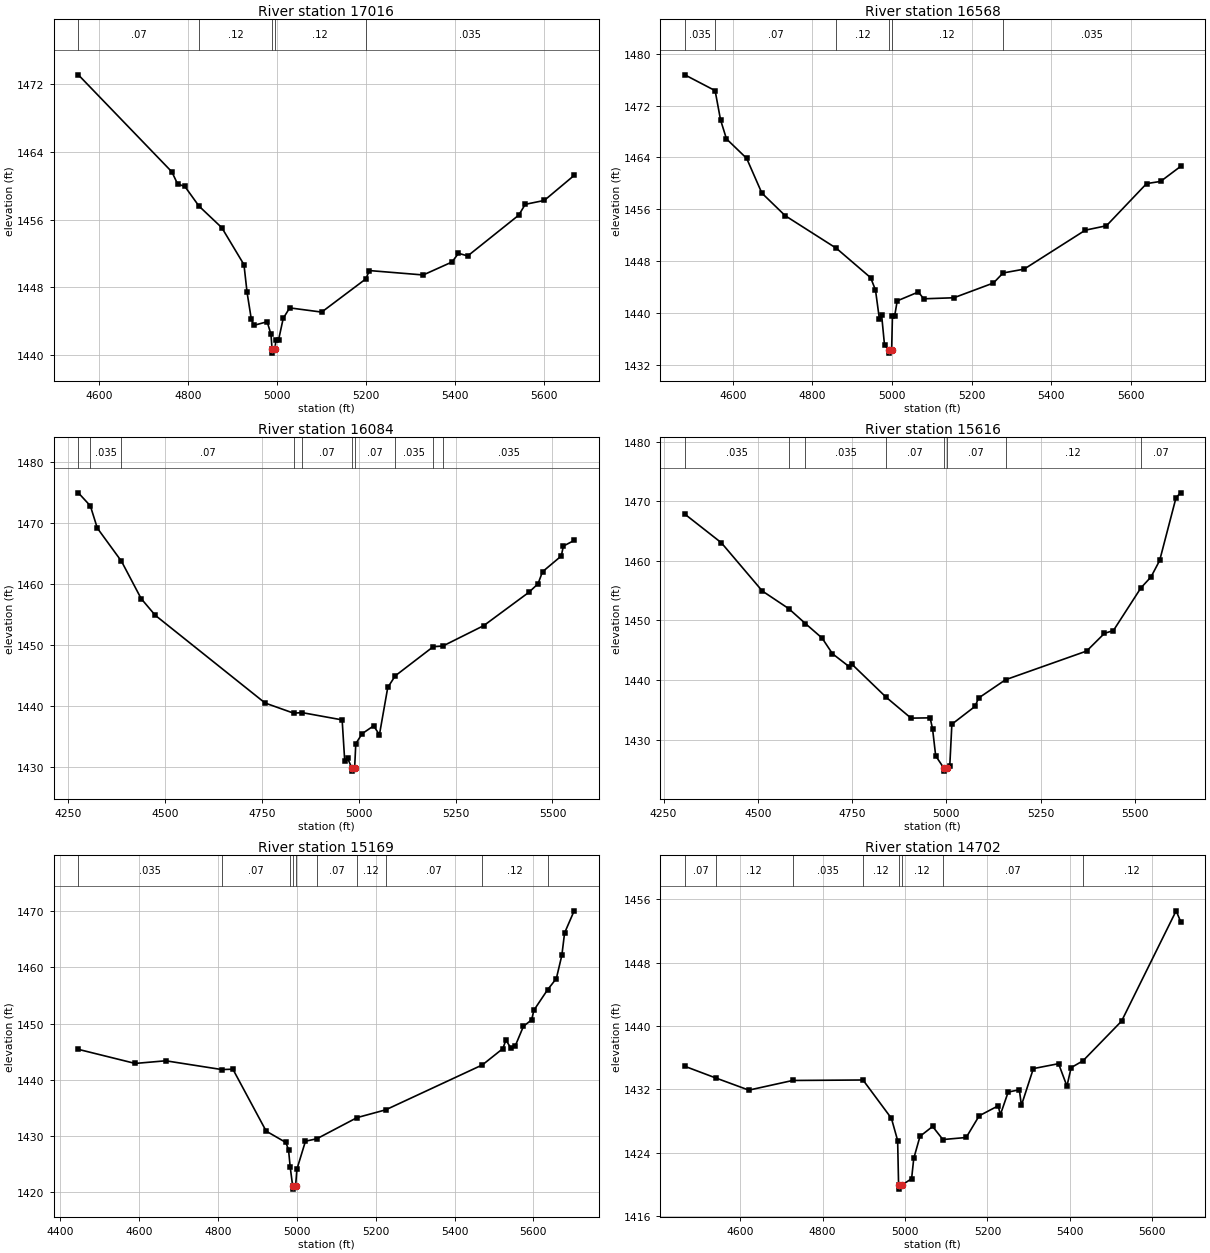
Type RM Length L Ch R = 1 ,17016   ,448,448,448
BEGIN DESCRIPTION:
DARMSTADT CREEK 33.0
END DESCRIPTION:
XS GIS Cut Line= 3
      2041280.94     13910571.42        2041075.       13910175.
      2040541.35     13909774.56
#Sta/Elev= 30
  4553.3 1473.14  4763.4 1461.67  4776.3 1460.24  4792.7 1459.94  4824.2 1457.63
  4875.6 1455.07  4925.4  1450.7  4932.4 1447.41  4941.9 1444.25  4947.5 1443.52
  4977.5 1443.95  4986.1 1442.46  4988.5 1440.74    4989 1440.24    4995 1440.74
  4997.2 1441.79  5003.1 1441.79  5013.6 1444.35  5028.1 1445.59    5100 1445.09
  5199.1 1449.01  5207.3    1450  5328.1 1449.48  5392.7 1451.01  5407.3 1452.04
  5428.1 1451.73  5542.7 1456.55  5557.3 1457.83  5600.1 1458.29  5667.2 1461.25
#Mann= 5 ,-1 , 0
  4553.3     .07       0  4824.2     .12       0  4988.5     .05       0
    4995     .12       0  5199.1    .035       0
Bank Sta=4988.5,4995
XS Rating Curve= 0 ,0
Exp/Cntr=0.3,0.1

Type RM Length L Ch R = 1 ,16568   ,484,484,484
BEGIN DESCRIPTION:
DARMSTADT CREEK 32.0
END DESCRIPTION:
XS GIS Cut Line= 3
      2041687.22     13910123.54        2041225.       13909875.
      2040558.52     13909598.13
#Sta/Elev= 30
    4479 1476.74  4555.2  1474.3  4568.8  1469.8  4583.7 1466.85  4634.5 1463.84
  4672.7 1458.48  4731.3 1454.99  4860.1 1449.95  4946.2 1445.41  4958.4  1443.5
  4968.1 1439.08  4973.8 1439.64  4981.1 1434.99  4992.4 1434.26  4992.9 1433.76
    4999 1434.26    5001 1439.46  5006.5 1439.46    5013 1441.83  5066.2  1443.2
  5079.6 1442.15  5155.4 1442.31  5254.9 1444.59  5279.2 1446.14  5331.9 1446.73
  5485.9 1452.75    5539 1453.43  5639.9 1459.94  5675.2 1460.28  5725.5  1462.6
#Mann= 6 ,-1 , 0
    4479    .035       0  4555.2     .07       0  4860.1     .12       0
  4992.4     .05       0    4999     .12       0  5279.2    .035       0
Bank Sta=4992.4,4999
XS Rating Curve= 0 ,0
Exp/Cntr=0.3,0.1

Type RM Length L Ch R = 1 ,16084   ,468,468,468
BEGIN DESCRIPTION:
DARMSTADT CREEK 31.0
END DESCRIPTION:
XS GIS Cut Line= 3
       2041791.4     13909977.74        2041325.       13909425.
       2040808.5     13909217.89
#Sta/Elev= 30
  4276.3  1474.9  4307.3 1472.77  4325.3 1469.13  4387.7  1463.7  4438.5 1457.59
  4474.8 1454.87  4758.3 1440.52    4832 1438.86  4853.8 1438.95  4957.2 1437.76
  4963.8 1431.08  4971.5 1431.45  4982.3 1429.88  4982.8 1429.38  4989.4 1429.88
  4992.4 1433.87  5008.9 1435.51  5038.5 1436.79  5053.4 1435.33  5074.9 1443.06
  5094.3 1444.97  5192.3 1449.73  5217.1 1449.84  5322.7 1453.18  5439.4 1458.64
  5462.8 1460.03  5474.3 1461.99  5522.8 1464.57  5528.1 1466.19    5556 1467.11
#Mann= 10 ,-1 , 0
  4276.3     .07       0  4307.3    .035       0  4387.7     .07       0
    4832     .12       0  4853.8     .07       0  4982.3     .05       0
  4989.4     .07       0  5094.3    .035       0  5192.3     .12       0
  5217.1    .035       0
Bank Sta=4982.3,4989.4
XS Rating Curve= 0 ,0
Exp/Cntr=0.3,0.1

Type RM Length L Ch R = 1 ,15616   ,447,447,447
BEGIN DESCRIPTION:
DARMSTADT CREEK 30.0
END DESCRIPTION:
XS GIS Cut Line= 3
      2042072.65     13909743.36        2041675.       13909175.
      2041103.86     13908930.82
#Sta/Elev= 30
  4306.4 1467.83  4403.2 1463.03  4511.9 1454.93    4582 1451.97  4626.2 1449.47
  4670.5 1447.03  4697.9 1444.41  4742.4 1442.23  4748.5 1442.71  4840.6 1437.09
  4906.3  1433.6  4956.9 1433.65  4963.4 1431.81  4971.7 1427.27  4993.4 1425.21
  4993.9 1424.71  5000.6 1425.21  5009.1 1425.65  5014.6 1432.58  5076.2 1435.58
  5085.4 1436.97  5156.9 1440.04  5372.1 1444.86  5419.3 1447.83  5442.9 1448.29
    5516 1455.46  5542.7 1457.29  5565.6 1460.05  5609.1 1470.61  5621.2  1471.4
#Mann= 8 ,-1 , 0
  4306.4    .035       0    4582     .07       0  4626.2    .035       0
  4840.6     .07       0  4993.4     .05       0  5000.6     .07       0
  5156.9     .12       0    5516     .07       0
Bank Sta=4993.4,5000.6
XS Rating Curve= 0 ,0
Exp/Cntr=0.3,0.1

Type RM Length L Ch R = 1 ,15169   ,467,467,467
BEGIN DESCRIPTION:
DARMSTADT CREEK 29.0
END DESCRIPTION:
XS GIS Cut Line= 3
      2042348.65     13909284.97        2041975.       13908875.
       2041301.8     13908670.42
#Sta/Elev= 30
  4445.3 1445.41  4589.5 1442.91  4667.2 1443.38  4809.6 1441.82  4837.5 1441.89
    4922 1430.89  4971.9 1428.88  4978.7 1427.59    4983  1424.5  4989.3 1421.09
  4989.8 1420.59  4996.6 1421.09    5000 1424.13  5021.7  1429.1  5050.5 1429.53
  5152.6 1433.29  5225.3 1434.67  5470.7 1442.65  5522.6 1445.54  5530.4 1447.06
  5543.5 1445.58  5553.9 1445.99  5574.8 1449.49  5595.7 1450.66  5601.4 1452.36
  5636.1 1455.99  5658.4 1457.99  5672.4 1462.13  5679.3 1466.08  5703.6 1470.01
#Mann= 10 ,-1 , 0
  4445.3    .035       0  4809.6     .07       0    4983     .12       0
  4989.3     .05       0  4996.6     .12       0  5050.5     .07       0
  5152.6     .12       0  5225.3     .07       0  5470.7     .12       0
  5636.1     .07       0
Bank Sta=4989.3,4996.6
XS Rating Curve= 0 ,0
Exp/Cntr=0.3,0.1

Type RM Length L Ch R = 1 ,14702   ,464,464,464
BEGIN DESCRIPTION:
DARMSTADT CREEK 28.0
END DESCRIPTION:
XS GIS Cut Line= 3
      2042567.41     13908967.27        2042275.       13908525.
      2041614.28     13908394.37
#Sta/Elev= 30
  4465.4 1434.92  4540.9 1433.44  4620.9 1431.91  4727.3 1433.13    4898 1433.19
    4967 1428.35  4982.1 1425.55  4984.4 1419.91  4984.9 1419.41  4991.7 1419.91
    5016 1420.72  5021.2 1423.28  5036.4 1426.08    5067 1427.32    5092 1425.67
  5148.5 1425.93  5180.1 1428.67  5226.3 1429.93  5231.4 1428.79  5250.4 1431.66
  5277.5 1431.96  5282.6 1429.99  5311.6 1434.63  5372.8 1435.25  5393.1 1432.42
  5403.3 1434.75  5432.2 1435.62  5525.7 1440.62  5658.2 1454.55  5669.1  1453.2
#Mann= 8 ,-1 , 0
  4465.4     .07       0  4540.9     .12       0  4727.3    .035       0
    4898     .12       0  4984.4     .05       0  4991.7     .12       0
    5092     .07       0  5432.2     .12       0
Bank Sta=4984.4,4991.7
XS Rating Curve= 0 ,0
Exp/Cntr=0.3,0.1