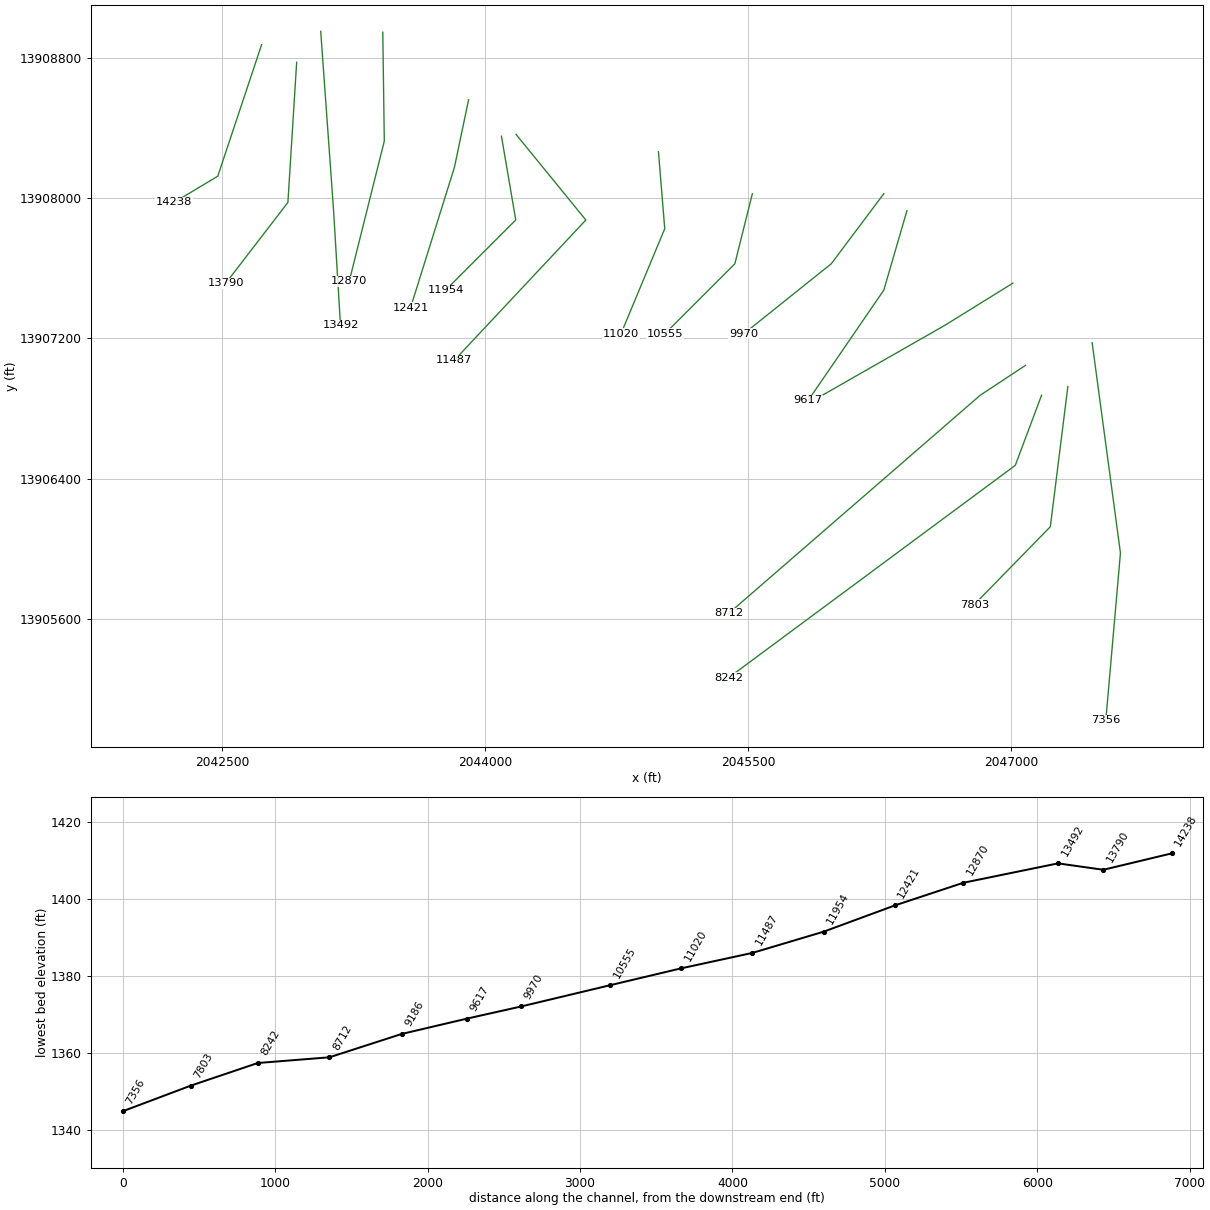
HEC-RAS study DARMSTADT CREEK.prj: DARMSTADT CREEK Base Level Engineering

--- DARMSTADT CREEK.g01 (geometry) --- (continued)

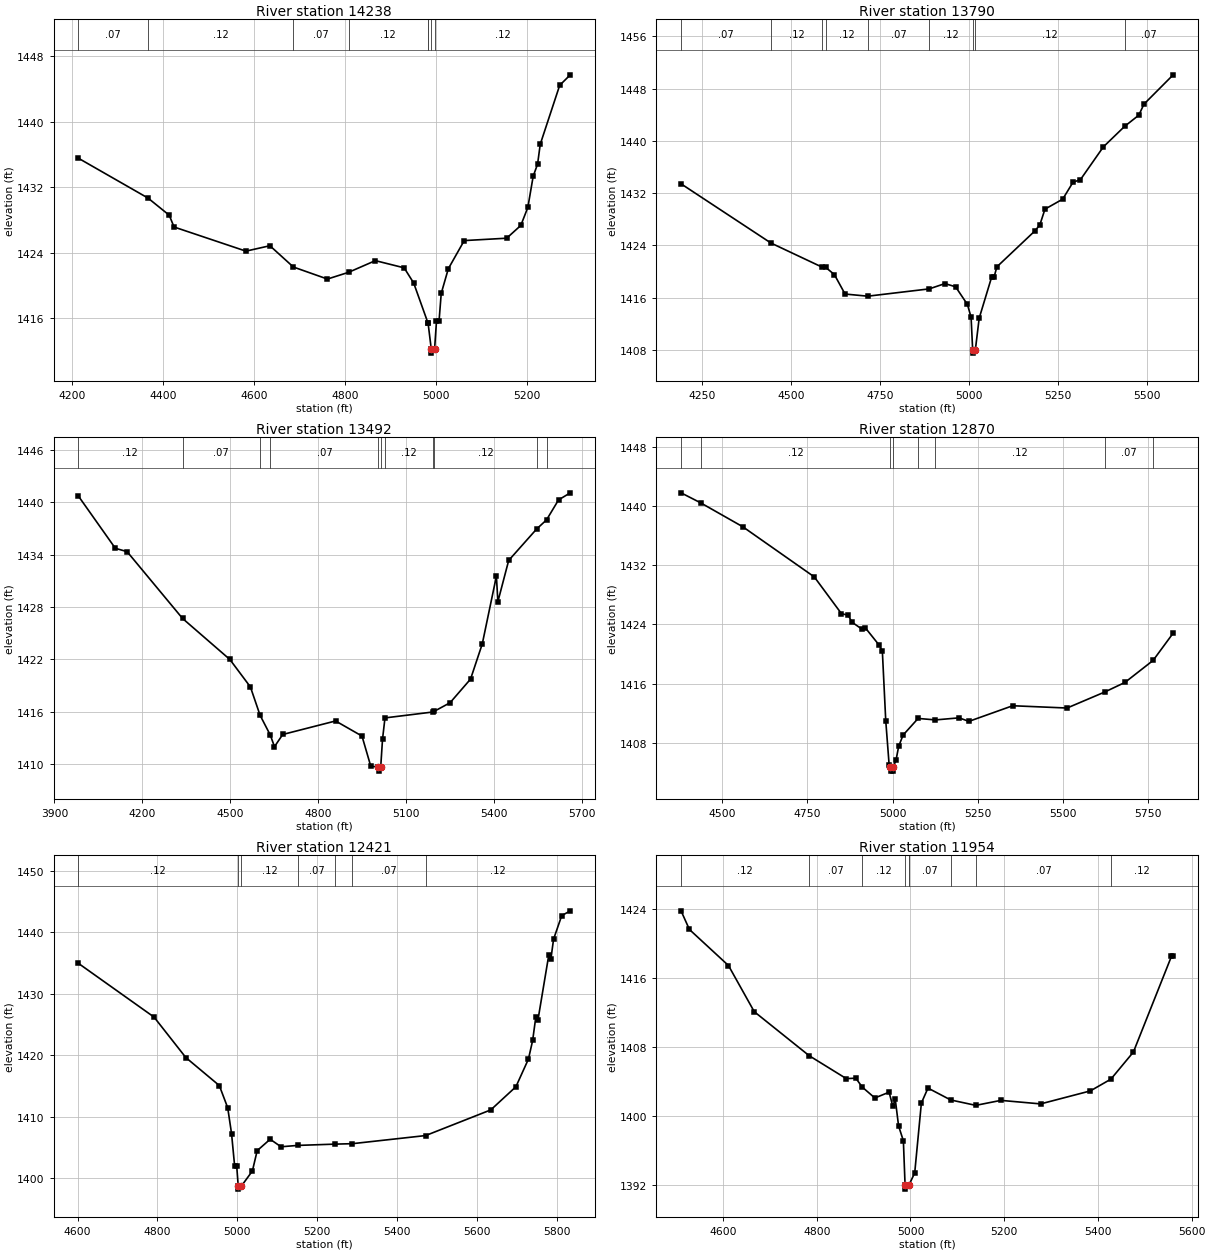
Type RM Length L Ch R = 1 ,14238   ,448,448,448
BEGIN DESCRIPTION:
DARMSTADT CREEK 27.0
END DESCRIPTION:
XS GIS Cut Line= 3
        2042725.     13908874.99        2042475.       13908125.
        2042225.       13907975.
#Sta/Elev= 30
  4213.6 1435.58  4367.3 1430.69  4413.9  1428.6  4424.4 1427.16  4582.5 1424.21
  4635.2 1424.87  4686.8 1422.27  4761.7  1420.8  4808.1 1421.62  4867.1 1423.05
  4930.4 1422.17  4951.4 1420.31  4982.6 1415.46  4983.1 1415.38    4990 1412.25
  4990.5 1411.75  4997.3 1412.25  5001.5 1415.65  5007.1 1415.65  5011.9 1419.04
  5027.5 1422.06  5062.5  1425.5  5155.8 1425.79  5186.9 1427.35  5202.4 1429.56
  5214.1 1433.36  5223.8 1434.85  5229.6 1437.26  5272.4 1444.47  5295.7 1445.75
#Mann= 8 ,-1 , 0
  4213.6     .07       0  4367.3     .12       0  4686.8     .07       0
  4808.1     .12       0  4982.6     .07       0  4983.1     .12       0
    4990     .05       0  4997.3     .12       0
Bank Sta=4990,4997.3
XS Rating Curve= 0 ,0
Exp/Cntr=0.3,0.1

Type RM Length L Ch R = 1 ,13790   ,298,298,298
BEGIN DESCRIPTION:
DARMSTADT CREEK 26.0
END DESCRIPTION:
XS GIS Cut Line= 3
        2042925.     13908775.02        2042875.       13907975.
      2042520.52     13907514.13
#Sta/Elev= 30
  4190.2 1433.44  4442.9 1424.37    4587 1420.67  4596.8 1420.64  4621.1 1419.54
  4651.1 1416.56  4714.9 1416.23  4887.8 1417.35  4931.7 1418.16  4961.7 1417.67
  4994.9 1414.97  5005.3 1413.01  5009.7 1408.01  5010.2 1407.51  5017.3 1408.01
    5028 1412.85  5063.4 1419.22  5069.7 1419.15  5077.9 1420.73  5183.9 1426.19
  5198.4 1427.13  5212.9 1429.56  5262.7 1431.09  5291.7 1433.68  5312.6 1434.08
  5376.9 1439.09  5436.8 1442.24  5476.6 1443.95  5491.1 1445.64  5573.2 1450.13
#Mann= 9 ,-1 , 0
  4190.2     .07       0  4442.9     .12       0    4587     .07       0
  4596.8     .12       0  4714.9     .07       0  4887.8     .12       0
  5009.7     .05       0  5017.3     .12       0  5436.8     .07       0
Bank Sta=5009.7,5017.3
XS Rating Curve= 0 ,0
Exp/Cntr=0.3,0.1

Type RM Length L Ch R = 1 ,13492   ,622,622,622
BEGIN DESCRIPTION:
DARMSTADT CREEK 25.0
END DESCRIPTION:
XS GIS Cut Line= 3
      2043062.21      13908951.7      2043135.13     13907936.04
        2043175.     13907275.01
#Sta/Elev= 30
    3981 1440.74    4108 1434.71  4148.1 1434.33  4337.5 1426.67    4499 1421.97
  4569.2 1418.82  4602.1 1415.58  4637.3 1413.29  4651.4 1411.97  4679.5 1413.37
    4860 1414.92  4950.2 1413.19  4980.3 1409.72  5006.5 1409.67    5007 1409.17
  5014.2 1409.67  5020.4 1412.85  5028.7 1415.27  5192.9 1415.95  5197.1 1416.03
    5251 1417.01  5320.9 1419.72    5361 1423.76  5409.2 1431.52  5414.2 1428.59
  5451.1 1433.32  5546.2 1436.91  5580.4 1437.97  5621.4 1440.26  5661.5 1441.07
#Mann= 11 ,-1 , 0
    3981     .12       0  4337.5     .07       0  4602.1     .12       0
  4637.3     .07       0  5006.5     .05       0  5014.2     .07       0
  5028.7     .12       0  5192.9     .07       0  5197.1     .12       0
  5546.2     .07       0  5580.4     .12       0
Bank Sta=5006.5,5014.2
XS Rating Curve= 0 ,0
Exp/Cntr=0.3,0.1

Type RM Length L Ch R = 1 ,12870   ,449,449,449
BEGIN DESCRIPTION:
DARMSTADT CREEK 24.0
END DESCRIPTION:
XS GIS Cut Line= 3
      2043416.38     13908946.44        2043425.       13908325.
        2043225.     13907525.02
#Sta/Elev= 30
  4378.6 1441.84    4436 1440.49  4560.1 1437.24  4770.1 1430.45  4850.1 1425.46
  4870.1 1425.26  4880.1 1424.34  4910.1 1423.37  4920.1 1423.55  4960.1 1421.24
  4970.1 1420.42  4980.1 1410.97  4990.1 1404.96  4993.6 1404.63  4994.1 1404.13
  5001.1 1404.13  5001.6 1404.63  5010.4 1405.64  5018.1 1407.49    5031 1409.01
  5075.2 1411.27  5126.2 1411.07  5195.9 1411.35  5224.3 1410.87  5353.1 1412.99
  5512.9 1412.68  5624.1 1414.86    5683 1416.15  5765.7 1419.13  5824.7 1422.83
#Mann= 8 ,-1 , 0
  4378.6     .07       0    4436     .12       0  4993.6     .05       0
  5001.6     .12       0  5075.2     .07       0  5126.2     .12       0
  5624.1     .07       0  5765.7     .12       0
Bank Sta=4993.6,5001.6
XS Rating Curve= 0 ,0
Exp/Cntr=0.3,0.1

Type RM Length L Ch R = 1 ,12421   ,467,467,467
BEGIN DESCRIPTION:
DARMSTADT CREEK 23.0
END DESCRIPTION:
XS GIS Cut Line= 3
      2043905.97     13908561.05        2043825.       13908175.
        2043575.     13907375.01
#Sta/Elev= 30
  4601.6 1434.97  4791.7 1426.21  4871.3 1419.64  4955.2 1415.09  4976.2 1411.48
  4985.8 1407.29  4993.5 1402.04  4998.7 1402.04  5002.5 1398.77    5003 1398.27
  5010.5 1398.77    5038 1401.22    5050 1404.52  5082.5 1406.37  5109.7 1405.15
  5151.5 1405.37  5245.4 1405.58  5288.2 1405.65  5471.9 1406.97  5635.1 1411.14
    5698  1414.9  5729.4  1419.4  5739.9 1422.41  5747.8 1426.21    5753 1425.66
  5780.3 1436.28  5785.5  1435.6  5792.3 1438.86  5812.7 1442.69  5834.2 1443.47
#Mann= 7 ,-1 , 0
  4601.6     .12       0  5002.5     .05       0  5010.5     .12       0
  5151.5     .07       0  5245.4     .12       0  5288.2     .07       0
  5471.9     .12       0
Bank Sta=5002.5,5010.5
XS Rating Curve= 0 ,0
Exp/Cntr=0.3,0.1

Type RM Length L Ch R = 1 ,11954   ,467,467,467
BEGIN DESCRIPTION:
DARMSTADT CREEK 22.0
END DESCRIPTION:
XS GIS Cut Line= 3
      2044093.47     13908352.69        2044175.       13907875.
      2043774.99     13907474.99
#Sta/Elev= 30
  4510.3 1423.83  4528.2 1421.66  4611.5 1417.47  4666.6  1412.1  4783.9 1406.98
    4863 1404.32  4883.3 1404.37  4897.1 1403.33  4923.9 1402.07  4954.3 1402.74
  4962.3  1401.1  4967.4 1401.95  4974.6 1398.81  4984.8 1397.09  4988.4 1391.97
  4988.9 1391.47  4996.4 1391.97    4997 1391.97    5009 1393.36  5023.2 1401.48
  5037.3 1403.22  5085.7 1401.84  5139.3 1401.21  5192.9 1401.79  5277.7 1401.38
  5383.8 1402.89  5427.7 1404.26  5475.7 1407.41    5557 1418.55  5560.6 1418.55
#Mann= 9 ,-1 , 0
  4510.3     .12       0  4783.9     .07       0  4897.1     .12       0
  4988.4     .05       0  4996.4     .12       0    4997     .07       0
  5085.7     .12       0  5139.3     .07       0  5427.7     .12       0
Bank Sta=4988.4,4996.4
XS Rating Curve= 0 ,0
Exp/Cntr=0.3,0.1

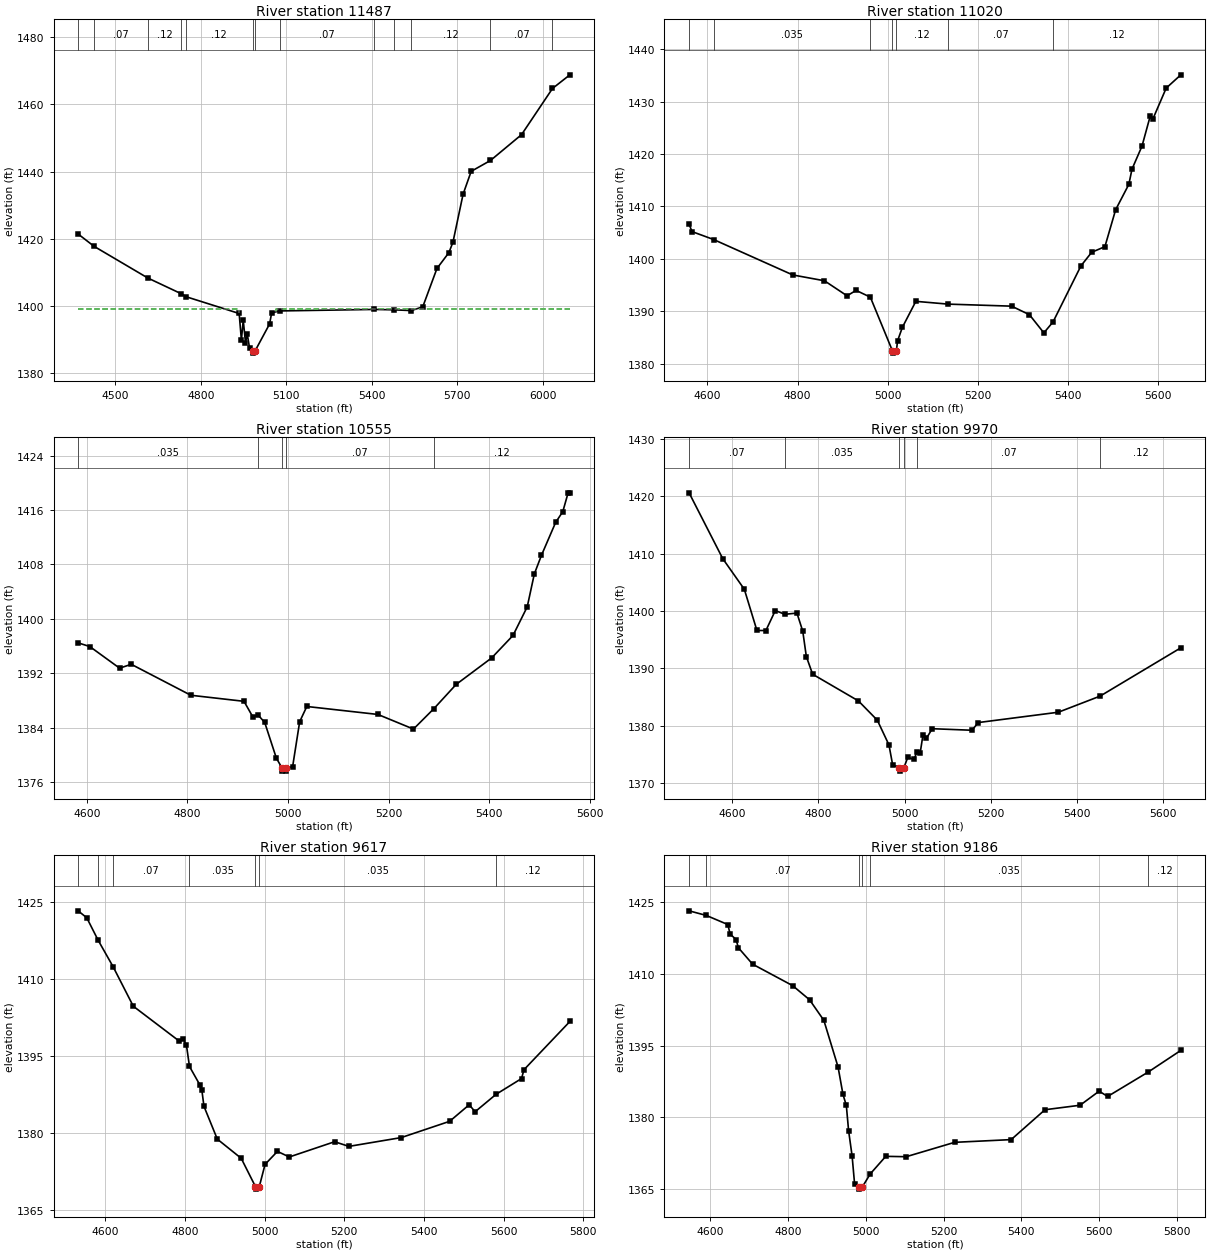
Type RM Length L Ch R = 1 ,11487   ,467,467,467
BEGIN DESCRIPTION:
DARMSTADT CREEK 21.0
END DESCRIPTION:
XS GIS Cut Line= 3
      2044176.81     13908363.11        2044575.       13907875.
      2043825.01     13907075.01
#Sta/Elev= 30
  4369.4 1421.44  4425.4 1417.77  4613.9 1408.35  4731.4 1403.66    4747 1402.81
  4934.8 1397.78  4942.6  1389.9  4949.1 1395.77    4957 1389.14  4963.4 1391.54
  4971.3 1387.46  4981.7 1386.48  4982.2 1385.98  4989.7 1386.48  5041.6 1394.66
  5048.9 1397.98  5076.9 1398.54  5408.7 1398.99  5478.1 1398.87  5539.3 1398.65
  5579.4 1399.76  5629.2 1411.18  5671.2  1415.9  5685.4 1419.02    5721  1433.3
  5749.4  1440.1  5817.1 1443.33  5926.2 1451.02  6034.9 1464.77  6095.9 1468.83
#Mann= 13 ,-1 , 0
  4369.4     .12       0  4425.4     .07       0  4613.9     .12       0
  4731.4     .07       0    4747     .12       0  4981.7     .05       0
  4989.7     .12       0  5076.9     .07       0  5408.7     .12       0
  5478.1     .07       0  5539.3     .12       0  5817.1     .07       0
  6034.9     .12       0
#XS Ineff= 2 , 0
       0  4932.6 1399.19 5064.47       0 1399.19
Permanent Ineff=
       F       F
Bank Sta=4981.7,4989.7
XS Rating Curve= 0 ,0
Exp/Cntr=0.3,0.1

Type RM Length L Ch R = 1 ,11020   ,465,465,465
BEGIN DESCRIPTION:
DARMSTADT CREEK 20.0
END DESCRIPTION:
XS GIS Cut Line= 3
      2044989.29      13908264.2        2045025.       13907825.
      2044775.02     13907225.04
#Sta/Elev= 30
  4559.4 1406.61  4565.9  1405.2  4613.7 1403.69  4789.4 1396.92  4859.6 1395.81
  4909.7 1392.94  4929.8 1393.97  4961.4 1392.68  5010.1 1382.49  5010.6 1381.99
  5019.3 1382.49  5021.7 1384.32  5032.5 1386.93  5062.3 1391.88  5133.7 1391.35
  5274.7 1390.96  5314.2 1389.33  5346.2 1385.86  5366.6 1387.95  5428.5 1398.66
  5452.3 1401.25  5481.6 1402.32  5505.4 1409.37  5534.7 1414.22  5541.7 1417.13
  5563.9 1421.53  5582.3 1427.32  5587.8 1426.66  5617.5  1432.6    5650 1435.14
#Mann= 7 ,-1 , 0
  4559.4     .12       0  4613.7    .035       0  4961.4     .12       0
  5010.1     .05       0  5019.3     .12       0  5133.7     .07       0
  5366.6     .12       0
Bank Sta=5010.1,5019.3
XS Rating Curve= 0 ,0
Exp/Cntr=0.3,0.1

Type RM Length L Ch R = 1 ,10555   ,585,585,585
BEGIN DESCRIPTION:
DARMSTADT CREEK 19.0
END DESCRIPTION:
XS GIS Cut Line= 3
      2045525.01     13908025.04        2045425.       13907625.
      2045025.03     13907225.03
#Sta/Elev= 30
  4582.6 1396.48  4605.8 1395.94  4665.1 1392.76  4688.3 1393.33  4806.8 1388.78
  4912.5 1387.89  4930.5 1385.54  4939.9 1385.93  4953.7 1384.78  4976.9 1379.53
  4987.8 1378.13  4988.3 1377.63  4996.5 1377.63    4997 1378.13  5009.1 1378.24
  5023.2 1384.89  5037.4 1387.13  5178.8 1385.96  5249.5 1383.81  5290.4 1386.83
  5334.4 1390.37  5405.1 1394.27  5447.5 1397.57  5475.8 1401.78  5489.9 1406.61
  5504.1 1409.35  5532.4  1414.2  5546.5 1415.76  5557.1 1418.53  5560.6 1418.53
#Mann= 5 ,-1 , 0
  4582.6    .035       0  4939.9     .07       0  4987.8     .05       0
    4997     .07       0  5290.4     .12       0
Bank Sta=4987.8,4997
XS Rating Curve= 0 ,0
Exp/Cntr=0.3,0.1

Type RM Length L Ch R = 1 ,9970    ,353,353,353
BEGIN DESCRIPTION:
DARMSTADT CREEK 18.0
END DESCRIPTION:
XS GIS Cut Line= 3
      2046275.01     13908025.02        2045975.     13907625.15
      2045475.01       13907225.
#Sta/Elev= 30
  4500.1 1420.59  4578.2 1409.12  4628.2 1403.79  4657.4 1396.61  4678.2  1396.6
  4700.1 1400.09  4721.9 1399.43  4750.2 1399.64  4763.7 1396.49    4772 1392.07
  4786.6 1388.99  4892.8 1384.34  4936.6 1380.98  4963.6 1376.67    4972 1373.26
    4988 1372.61  4988.5 1372.11  4997.7 1372.61  5007.3 1374.51  5021.7 1374.15
  5028.2  1375.4  5036.1 1375.34  5042.5 1378.44  5050.5 1377.83    5064  1379.5
  5156.2 1379.23  5170.6 1380.57  5356.3 1382.37  5453.3 1385.18  5640.4 1393.59
#Mann= 6 ,-1 , 0
  4500.1     .07       0  4721.9    .035       0    4988    .035       0
  4997.7    .035       0  5028.2     .07       0  5453.3     .12       0
Bank Sta=4988,4997.7
XS Rating Curve= 0 ,0
Exp/Cntr=0.3,0.1

Type RM Length L Ch R = 1 ,9617    ,431,431,431
BEGIN DESCRIPTION:
DARMSTADT CREEK 17.0
END DESCRIPTION:
XS GIS Cut Line= 3
      2046406.92     13907927.98        2046275.       13907475.
      2045843.99     13906846.12
#Sta/Elev= 30
  4532.1 1423.36  4553.8    1422  4582.4  1417.6  4619.9 1412.44  4670.6 1404.72
  4785.2 1397.95  4795.6 1398.37    4804 1397.08  4811.6 1392.95  4837.3  1389.4
  4842.7 1388.29  4847.9 1385.17  4881.4 1378.76  4941.4 1375.01  4977.1 1369.49
  4977.6 1368.99  4986.8 1369.49  5001.3 1373.83  5032.3 1376.36  5062.1 1375.27
  5175.8 1378.25  5211.7 1377.34  5343.1 1379.06  5464.6 1382.24  5513.6 1385.47
  5528.5 1384.11    5581 1387.51    5645 1390.59    5651 1392.31  5766.3 1401.74
#Mann= 7 ,-1 , 0
  4532.1     .07       0  4582.4    .035       0  4619.9     .07       0
  4811.6    .035       0  4977.1    .035       0  4986.8    .035       0
    5581     .12       0
Bank Sta=4977.1,4986.8
XS Rating Curve= 0 ,0
Exp/Cntr=0.3,0.1

Type RM Length L Ch R = 1 ,9186    ,474,474,474
BEGIN DESCRIPTION:
DARMSTADT CREEK 16.0
END DESCRIPTION:
XS GIS Cut Line= 3
      2047011.27     13907514.57        2046625.       13907275.
      2045921.63     13906873.56
#Sta/Elev= 30
  4545.5 1423.21    4590 1422.24  4645.1 1420.34    4651 1418.36  4666.3 1417.21
  4672.2 1415.49  4708.8 1412.05  4811.8 1407.56  4855.3  1404.6    4892  1400.3
  4928.6 1390.53  4941.2  1384.8  4949.8  1382.5  4955.7 1377.18  4964.7 1371.91
  4971.1 1366.03  4981.6 1365.49  4982.1 1364.99  4991.3 1365.49  5011.3 1368.17
  5051.2 1371.85  5103.7 1371.77  5228.3 1374.78  5373.7 1375.35  5460.6  1381.6
  5550.9 1382.54  5599.8 1385.48  5621.8 1384.38  5725.9 1389.48  5809.9 1394.01
#Mann= 6 ,-1 , 0
  4545.5    .035       0    4590     .07       0  4981.6     .05       0
  4991.3     .07       0  5011.3    .035       0  5725.9     .12       0
Bank Sta=4981.6,4991.3
XS Rating Curve= 0 ,0
Exp/Cntr=0.3,0.1

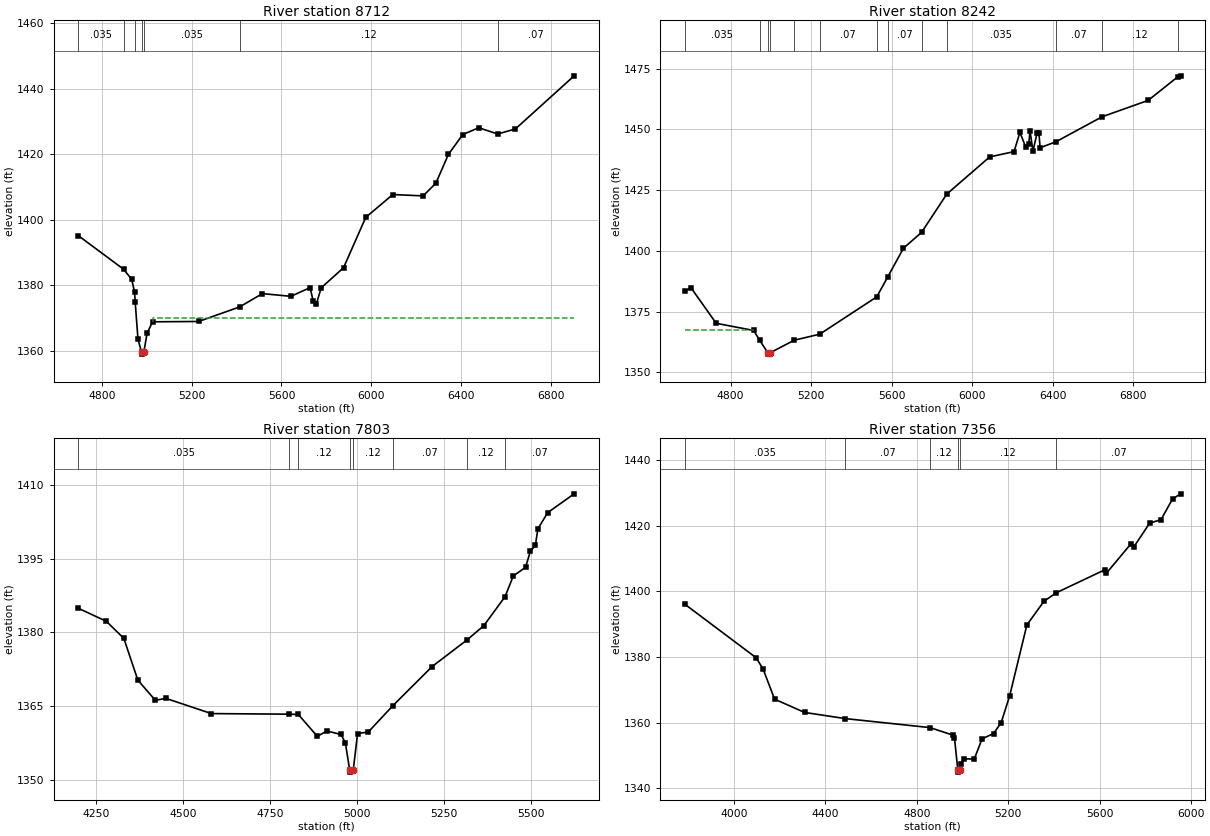
Type RM Length L Ch R = 1 ,8712    ,470,470,470
BEGIN DESCRIPTION:
DARMSTADT CREEK 15.0
END DESCRIPTION:
XS GIS Cut Line= 3
      2047083.03      13907045.4        2046825.       13906875.
      2045390.05     13905630.43
#Sta/Elev= 30
    4695 1395.13  4896.2 1384.89  4932.3 1381.84  4945.5 1377.95  4948.3 1374.83
  4960.6  1363.6  4976.7 1359.45  4977.2 1358.95  4986.5 1359.45  5001.2 1365.29
  5025.6 1368.82  5230.7 1368.92  5413.5 1373.36  5514.7 1377.43  5641.9  1376.6
  5727.4 1379.26  5741.7 1375.03  5755.9  1374.4  5776.8 1379.19  5876.5 1385.35
  5975.3 1400.71  6095.9 1407.69  6230.7 1407.27  6287.7 1411.16  6343.7 1419.96
  6407.4    1426  6478.6 1428.09    6563 1426.17    6642 1427.72  6903.7 1443.94
#Mann= 7 ,-1 , 0
    4695    .035       0  4896.2     .12       0  4948.3    .035       0
  4976.7    .035       0  4986.5    .035       0  5413.5     .12       0
    6563     .07       0
#XS Ineff= 2 , 0
       0                  5029.3       0    1370
Permanent Ineff=
       F       F
Bank Sta=4976.7,4986.5
XS Rating Curve= 0 ,0
Exp/Cntr=0.3,0.1

Type RM Length L Ch R = 1 ,8242    ,439,439,439
BEGIN DESCRIPTION:
DARMSTADT CREEK 14.0
END DESCRIPTION:
XS GIS Cut Line= 3
      2047175.01     13906875.04        2047025.       13906475.
      2045390.34     13905264.17
#Sta/Elev= 30
  4572.9 1383.58    4605 1384.66  4728.7 1370.16  4914.7 1367.22  4944.9 1363.14
  4985.5 1357.97    4986 1357.47  4995.3 1357.97  5116.4 1363.21  5242.7 1365.68
  5525.7 1381.05  5579.8 1389.18  5658.6  1401.1  5748.3 1407.61  5873.7 1423.39
  6086.4 1438.68  6207.4 1440.87  6236.7  1448.8  6265.9 1442.57  6280.5 1444.21
  6286.8 1449.31  6301.4 1441.13  6322.2 1448.66  6330.6 1448.66  6336.9 1442.47
  6414.1 1444.87  6644.9 1455.23  6873.2 1461.96  7019.9 1471.65  7034.4 1472.08
#Mann= 13 ,-1 , 0
  4572.9    .035       0  4944.9     .07       0  4985.5     .05       0
  4995.3     .07       0  5116.4    .035       0  5242.7     .07       0
  5525.7    .035       0  5579.8     .07       0  5748.3     .12       0
  5873.7    .035       0  6414.1     .07       0  6644.9     .12       0
  7019.9     .07       0
#XS Ineff= 2 , 0
       0 4914.39 1367.59               0
Permanent Ineff=
       F       F
Bank Sta=4985.5,4995.3
XS Rating Curve= 0 ,0
Exp/Cntr=0.3,0.1

Type RM Length L Ch R = 1 ,7803    ,447,447,447
BEGIN DESCRIPTION:
DARMSTADT CREEK 13.0
END DESCRIPTION:
XS GIS Cut Line= 3
        2047325.     13906925.02        2047225.       13906125.
      2046791.37     13905680.82
#Sta/Elev= 30
  4198.1  1384.9  4278.7 1382.26  4329.1 1378.78  4369.4  1370.3  4419.8 1366.21
  4450.1  1366.6  4581.1 1363.51  4805.5 1363.39  4831.3 1363.33  4885.9 1358.89
  4913.6 1359.98    4954 1359.27  4966.6 1357.58  4978.9 1352.12  4979.4 1351.62
  4989.4 1352.12  5001.8 1359.46  5032.6 1359.77  5102.7 1365.07  5216.4 1373.07
  5316.9 1378.48  5365.1 1381.37  5426.2 1387.26  5449.9 1391.46  5485.2 1393.23
  5499.3 1396.53  5513.5 1397.66  5520.6 1401.02  5548.9 1404.33  5625.1 1408.15
#Mann= 8 ,-1 , 0
  4198.1    .035       0  4805.5     .07       0  4831.3     .12       0
  4978.9     .05       0  4989.4     .12       0  5102.7     .07       0
  5316.9     .12       0  5426.2     .07       0
Bank Sta=4978.9,4989.4
XS Rating Curve= 0 ,0
Exp/Cntr=0.3,0.1

Type RM Length L Ch R = 1 ,7356    ,453,453,453
BEGIN DESCRIPTION:
DARMSTADT CREEK 12.0
END DESCRIPTION:
XS GIS Cut Line= 3
      2047463.58     13907174.21        2047625.       13905975.
      2047541.41     13905019.68
#Sta/Elev= 30
  3785.4 1396.13  4097.4 1379.82  4127.7 1376.39  4178.1 1367.21  4309.3 1363.16
  4487.8 1361.28    4858 1358.54    4959 1356.23  4965.2 1355.35    4980 1345.48
  4980.5 1344.98  4990.6 1345.48  4992.9 1347.47  5005.5 1349.03  5051.7 1348.98
  5085.8 1355.12    5136 1356.73  5169.3 1360.05  5206.2 1368.13  5281.9 1389.82
  5356.8 1397.03  5410.3  1399.6  5624.6 1406.67  5629.6 1405.55  5737.2 1414.52
  5748.3 1413.42  5818.6 1420.79  5868.8 1421.89  5918.9 1428.16  5954.4 1429.74
#Mann= 6 ,-1 , 0
  3785.4    .035       0  4487.8     .07       0    4858     .12       0
    4980     .05       0  4990.6     .12       0  5410.3     .07       0
Bank Sta=4980,4990.6
XS Rating Curve= 0 ,0
Exp/Cntr=0.3,0.1