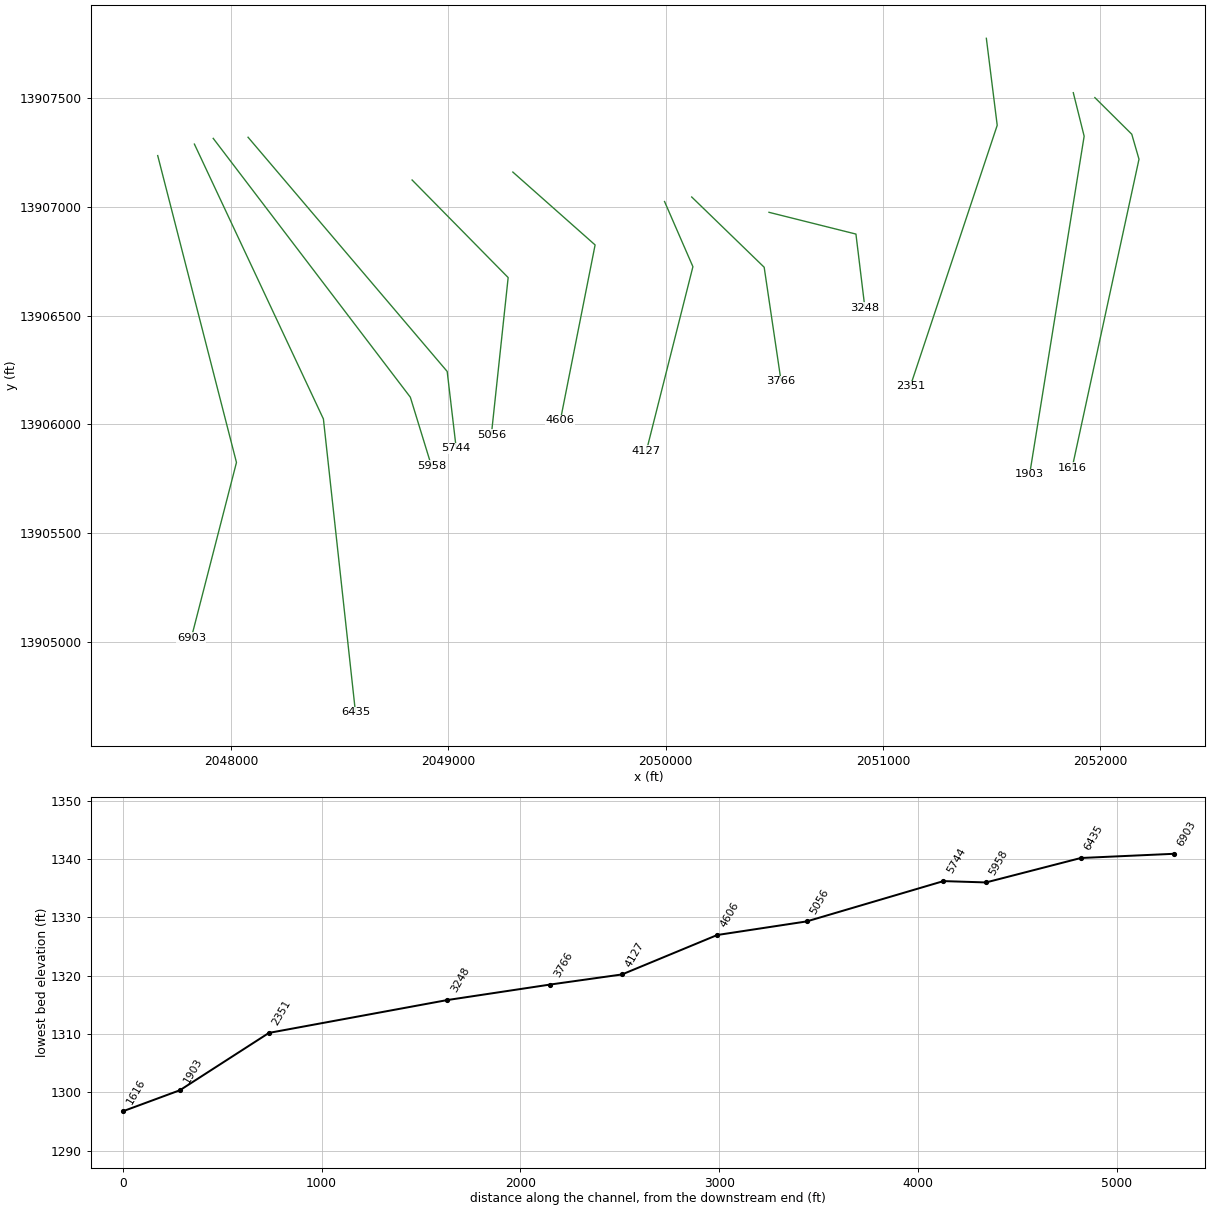
HEC-RAS study DARMSTADT CREEK.prj: DARMSTADT CREEK Base Level Engineering

--- DARMSTADT CREEK.g01 (geometry) --- (continued)

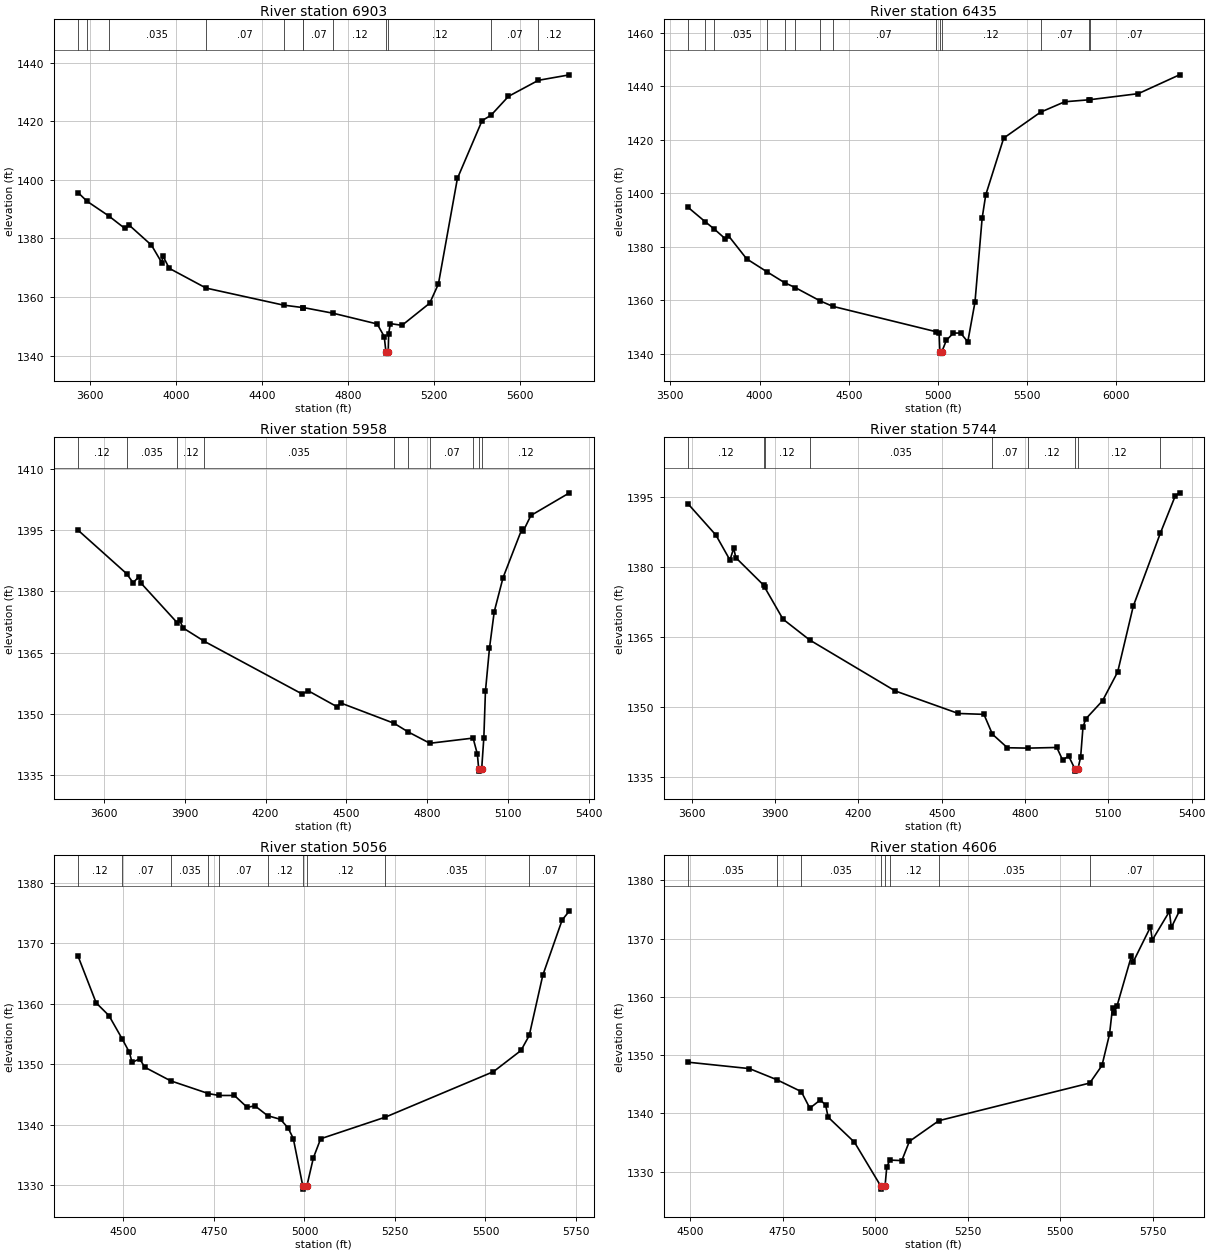
Type RM Length L Ch R = 1 ,6903    ,468,468,468
BEGIN DESCRIPTION:
DARMSTADT CREEK 11.0
END DESCRIPTION:
XS GIS Cut Line= 3
       2047662.7     13907235.76        2048025.       13905825.
      2047817.49     13905019.65
#Sta/Elev= 30
  3543.3 1395.63  3585.2 1392.68  3685.9  1387.7  3760.9 1383.43  3781.6 1384.52
  3884.8 1377.73  3932.9 1371.76    3938 1374.11  3967.4 1369.84  4139.3 1363.09
  4499.8 1357.28  4589.9 1356.44  4592.8 1356.44  4731.6  1354.5  4936.1 1350.85
  4968.9 1346.55  4976.6 1341.41  4977.1 1340.91  4987.4 1341.41  4989.5 1347.58
  4997.3 1350.98  5051.5 1350.38  5180.4 1357.93  5221.1 1364.48  5309.6 1400.49
  5424.5  1420.2  5465.9 1422.01  5547.2 1428.46  5686.6 1433.94  5831.5 1435.81
#Mann= 12 ,-1 , 0
  3543.3     .07       0  3585.2     .12       0  3685.9    .035       0
  4139.3     .07       0  4499.8    .035       0  4589.9     .12       0
  4592.8     .07       0  4731.6     .12       0  4976.6     .05       0
  4987.4     .12       0  5465.9     .07       0  5686.6     .12       0
Bank Sta=4976.6,4987.4
XS Rating Curve= 0 ,0
Exp/Cntr=0.3,0.1

Type RM Length L Ch R = 1 ,6435    ,477,477,477
BEGIN DESCRIPTION:
DARMSTADT CREEK 10.0
END DESCRIPTION:
XS GIS Cut Line= 3
      2047831.48     13907288.58        2048425.       13906025.
      2048572.63     13904675.58
#Sta/Elev= 30
  3599.9 1394.72  3696.2 1389.32  3746.8 1386.59  3808.2 1382.96  3824.8  1384.2
  3927.7 1375.47    4042 1370.61  4140.4 1366.54  4200.3 1364.71  4338.9 1359.76
  4409.7 1357.71  4988.4 1348.22    5006 1347.83  5010.6 1340.69  5011.1 1340.19
  5021.5 1340.69  5046.6 1344.97  5086.5  1347.7  5126.7  1347.7  5166.9 1344.42
  5207.2 1359.25  5247.4 1390.72  5267.5 1399.39  5368.1 1420.65  5574.4 1430.34
  5710.2 1434.25  5848.9    1435  5854.5 1435.05  6122.6 1437.29  6353.4 1444.33
#Mann= 14 ,-1 , 0
  3599.9     .12       0  3696.2     .07       0  3746.8    .035       0
    4042     .12       0  4140.4    .035       0  4200.3     .07       0
  4338.9    .035       0  4409.7     .07       0  4988.4     .12       0
  5010.6     .05       0  5021.5     .12       0  5574.4     .07       0
  5848.9    .035       0  5854.5     .07       0
Bank Sta=5010.6,5021.5
XS Rating Curve= 0 ,0
Exp/Cntr=0.3,0.1

Type RM Length L Ch R = 1 ,5958    ,214,214,214
BEGIN DESCRIPTION:
DARMSTADT CREEK 9.0
END DESCRIPTION:
XS GIS Cut Line= 3
      2047918.09     13907314.92        2048825.       13906125.
      2048921.59     13905811.04
#Sta/Elev= 30
  3503.9 1394.98  3683.6 1384.37  3708.1 1382.13  3730.1 1383.63  3737.2 1382.05
  3871.2 1372.38  3880.6 1373.03  3893.6 1371.06  3972.6 1367.78  4335.9 1354.88
  4358.7 1355.66  4464.8 1351.78  4479.3 1352.68  4677.3 1347.71    4729 1345.62
  4810.1 1342.82  4970.6 1344.09  4986.5 1340.14  4991.4  1336.5  4991.9    1336
  5002.4  1336.5  5010.5 1344.22  5016.4 1355.55  5031.4 1366.11  5049.1 1375.04
  5081.8 1383.37  5152.4 1395.38  5157.6 1394.87  5185.1 1398.59  5328.5 1404.14
#Mann= 10 ,-1 , 0
  3503.9     .12       0  3683.6    .035       0  3871.2     .12       0
  3972.6    .035       0  4677.3     .07       0    4729     .12       0
  4810.1     .07       0  4970.6     .12       0  4991.4     .05       0
  5002.4     .12       0
Bank Sta=4991.4,5002.4
XS Rating Curve= 0 ,0
Exp/Cntr=0.3,0.1

Type RM Length L Ch R = 1 ,5744    ,688,688,688
BEGIN DESCRIPTION:
DARMSTADT CREEK 8.0
END DESCRIPTION:
XS GIS Cut Line= 3
      2048078.39     13907320.04       2048994.5     13906243.33
      2049036.12     13905889.57
#Sta/Elev= 30
  3586.5  1393.6  3686.6 1386.91  3737.1 1381.56  3750.7 1384.12    3758 1382.08
  3858.6 1376.15  3861.7 1375.75  3928.2 1368.86  4024.3 1364.39  4332.3 1353.45
  4559.7 1348.61  4651.9 1348.42  4682.5 1344.16  4736.4 1341.25    4811 1341.17
  4914.4 1341.31  4935.2 1338.63  4957.2 1339.45  4979.4 1336.73  4979.9 1336.23
  4990.4 1336.73  5000.2 1339.21  5008.6 1345.65  5018.7 1347.44  5079.1 1351.34
  5133.6 1357.52  5189.8 1371.65    5287 1387.27  5340.9 1395.31  5356.4 1395.99
#Mann= 9 ,-1 , 0
  3586.5     .12       0  3858.6     .07       0  3861.7     .12       0
  4024.3    .035       0  4682.5     .07       0    4811     .12       0
  4979.4     .05       0  4990.4     .12       0    5287     .07       0
Bank Sta=4979.4,4990.4
XS Rating Curve= 0 ,0
Exp/Cntr=0.3,0.1

Type RM Length L Ch R = 1 ,5056    ,450,450,450
BEGIN DESCRIPTION:
DARMSTADT CREEK 7.0
END DESCRIPTION:
XS GIS Cut Line= 3
      2048833.05     13907123.54        2049275.       13906675.
      2049197.63     13905951.71
#Sta/Elev= 30
  4374.9 1367.82  4424.8 1360.12  4460.1 1358.02  4496.2 1354.21  4516.6 1351.94
  4523.8 1350.28  4544.9 1350.86  4559.1 1349.48  4630.2 1347.24    4735 1345.12
  4764.2 1344.81  4806.6 1344.81  4841.9 1342.84  4863.2  1343.1  4898.2 1341.47
  4933.9 1340.86  4955.1 1339.41  4969.2 1337.69  4995.5 1329.82    4996 1329.32
  5006.6 1329.82  5024.7  1334.5  5044.8 1337.65  5223.6 1341.23  5522.1 1348.75
    5598 1352.25  5620.8 1354.73  5658.3  1364.7  5711.7 1373.83    5732 1375.35
#Mann= 10 ,-1 , 0
  4374.9     .12       0  4496.2     .07       0  4630.2    .035       0
    4735     .12       0  4764.2     .07       0  4898.2     .12       0
  4995.5     .05       0  5006.6     .12       0  5223.6    .035       0
  5620.8     .07       0
Bank Sta=4995.5,5006.6
XS Rating Curve= 0 ,0
Exp/Cntr=0.3,0.1

Type RM Length L Ch R = 1 ,4606    ,479,479,479
BEGIN DESCRIPTION:
DARMSTADT CREEK 6.0
END DESCRIPTION:
XS GIS Cut Line= 3
      2049296.57     13907160.02        2049675.       13906825.
       2049515.4     13906019.68
#Sta/Elev= 30
  4495.2 1348.79  4660.6 1347.69  4734.7 1345.78  4800.6 1343.74  4823.7 1340.89
  4852.2 1342.32  4866.4  1341.4  4873.1 1339.35  4944.2 1335.04  5015.4 1327.49
  5015.9 1326.99  5026.7 1327.49  5031.3 1330.74  5039.6 1331.98    5072 1331.89
  5092.4 1335.19  5172.1 1338.75  5579.3 1345.21  5612.3 1348.23  5632.7 1353.61
  5640.7 1358.12  5645.8 1357.28  5653.1  1358.5  5691.9 1367.06    5697 1366.07
  5743.1    1372  5748.2 1369.78  5794.3 1374.68  5799.4 1371.93  5821.6 1374.79
#Mann= 8 ,-1 , 0
  4495.2    .035       0  4734.7     .12       0  4800.6    .035       0
  5015.4    .035       0  5026.7    .035       0  5039.6     .12       0
  5172.1    .035       0  5579.3     .07       0
Bank Sta=5015.4,5026.7
XS Rating Curve= 0 ,0
Exp/Cntr=0.3,0.1

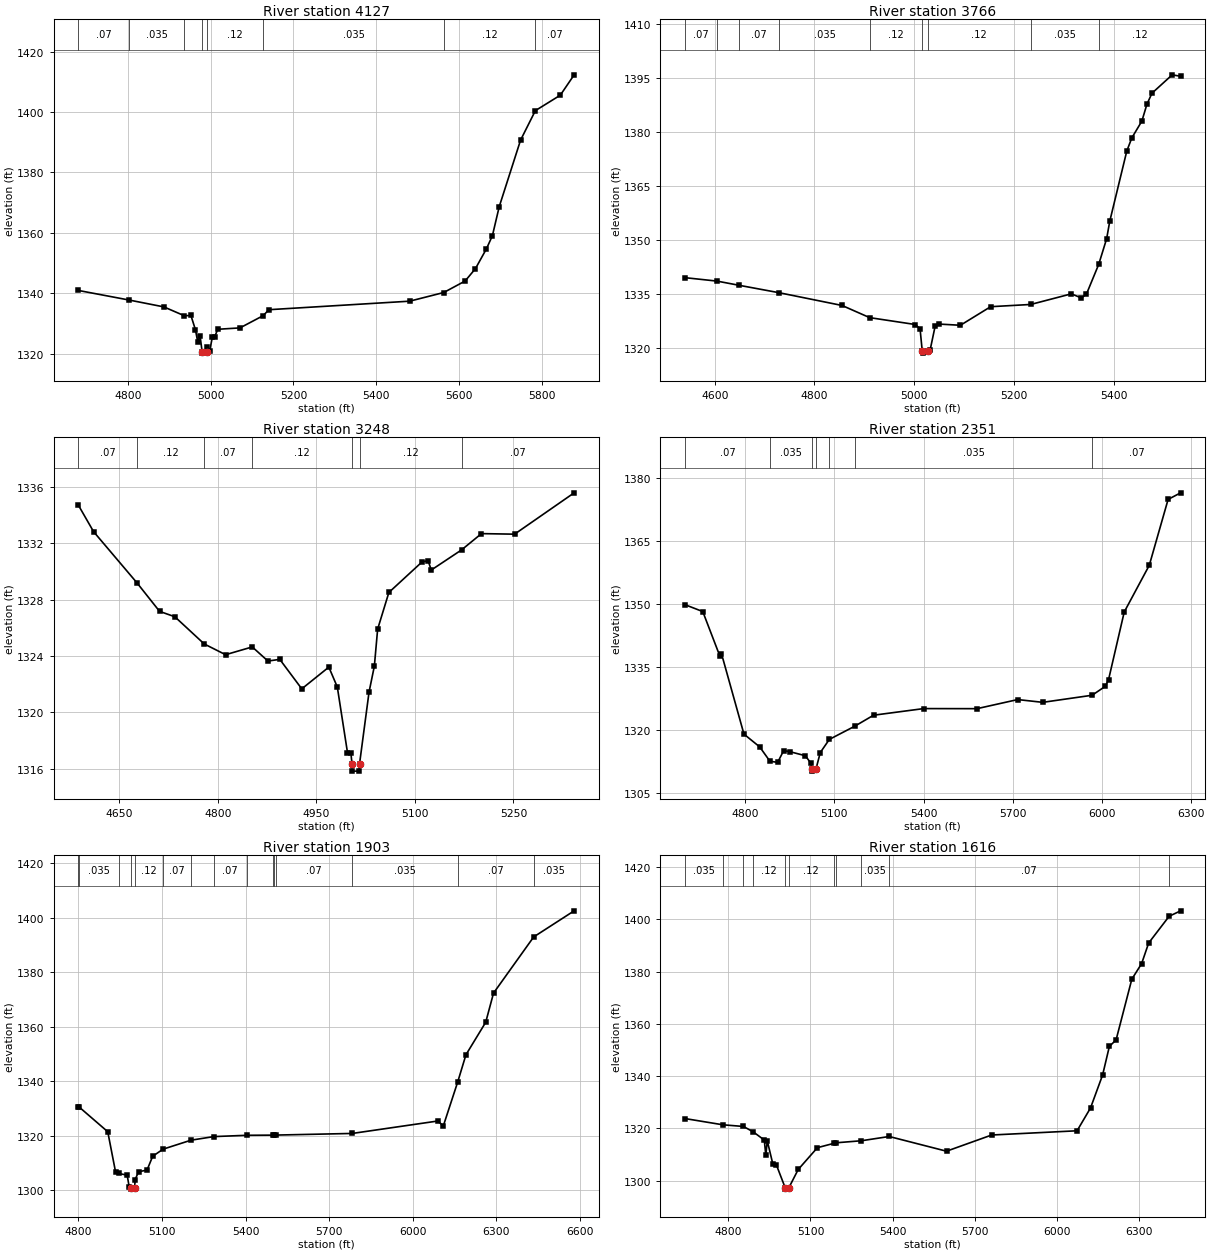
Type RM Length L Ch R = 1 ,4127    ,361,361,361
BEGIN DESCRIPTION:
DARMSTADT CREEK 5.0
END DESCRIPTION:
XS GIS Cut Line= 3
      2049994.51     13907024.57        2050125.       13906725.
      2049911.32     13905879.33
#Sta/Elev= 30
  4679.8 1340.97  4803.3 1337.78  4886.6 1335.53  4936.5 1332.58    4952 1332.71
  4962.9    1328  4968.7 1323.85  4974.1 1326.05  4979.1 1320.73  4979.6 1320.23
  4990.4 1320.73  4992.1 1322.16  4997.6 1321.03  5003.8  1325.5  5009.1  1325.5
  5016.9 1328.12  5070.7 1328.58  5126.9 1332.64  5140.6  1334.6  5481.1 1337.42
  5563.5 1340.29  5615.1 1344.09  5640.1 1348.19  5666.7 1354.75  5681.1  1359.1
  5697.6 1368.69  5749.2 1390.71    5785 1400.47  5845.3 1405.58  5878.8 1412.32
#Mann= 8 ,-1 , 0
  4679.8     .07       0  4803.3    .035       0  4936.5     .12       0
  4979.1     .05       0  4990.4     .12       0  5126.9    .035       0
  5563.5     .12       0    5785     .07       0
Bank Sta=4979.1,4990.4
XS Rating Curve= 0 ,0
Exp/Cntr=0.3,0.1

Type RM Length L Ch R = 1 ,3766    ,518,518,518
BEGIN DESCRIPTION:
DARMSTADT CREEK 4.0
END DESCRIPTION:
XS GIS Cut Line= 3
      2050119.49     13907045.43      2050452.84      13906722.5
      2050530.69     13906198.27
#Sta/Elev= 30
    4540 1339.47  4604.6 1338.51  4648.7 1337.35  4729.6 1335.27  4855.3 1331.74
  4910.7 1328.36  5002.1 1326.45  5011.7 1325.24  5016.1    1319  5016.6  1318.5
  5027.5    1319  5031.9 1319.39    5042 1326.05    5050 1326.57  5092.6 1326.24
  5153.2  1331.4  5233.5 1332.02    5315 1334.97  5335.2 1333.83  5345.3  1334.9
  5369.9 1343.17  5385.8 1350.31    5392 1355.13  5426.2 1374.66  5436.3 1378.31
  5456.4 1382.97  5466.6 1387.68  5476.7 1390.72  5517.2 1395.82  5534.1 1395.42
#Mann= 9 ,-1 , 0
    4540     .07       0  4604.6    .035       0  4648.7     .07       0
  4729.6    .035       0  4910.7     .12       0  5016.1     .05       0
  5027.5     .12       0  5233.5    .035       0  5369.9     .12       0
Bank Sta=5016.1,5027.5
XS Rating Curve= 0 ,0
Exp/Cntr=0.3,0.1

Type RM Length L Ch R = 1 ,3248    ,897,897,897
BEGIN DESCRIPTION:
DARMSTADT CREEK 3.0
END DESCRIPTION:
XS GIS Cut Line= 3
      2050474.96     13906975.01        2050875.       13906875.
      2050916.38     13906534.96
#Sta/Elev= 30
  4587.6 1334.69  4610.8 1332.81  4676.9 1329.18  4711.3 1327.16  4734.5 1326.78
  4779.3 1324.85  4811.8 1324.09  4852.4 1324.64  4876.3 1323.64  4894.3 1323.76
  4927.8 1321.67    4969 1323.21  4981.9  1321.8  4997.4 1317.15  5002.5 1317.15
  5004.3 1316.34  5004.8 1315.84  5015.2 1315.84  5015.7 1316.34  5030.2 1321.44
  5038.3 1323.28  5043.3  1325.9  5060.4  1328.5  5110.8 1330.66    5120 1330.76
    5125 1330.09  5171.2 1331.52  5201.4 1332.67  5251.8 1332.63  5342.5 1335.56
#Mann= 7 ,-1 , 0
  4587.6     .07       0  4676.9     .12       0  4779.3     .07       0
  4852.4     .12       0  5004.3     .05       0  5015.7     .12       0
  5171.2     .07       0
Bank Sta=5004.3,5015.7
XS Rating Curve= 0 ,0
Exp/Cntr=0.3,0.1

Type RM Length L Ch R = 1 ,2351    ,448,448,448
BEGIN DESCRIPTION:
DARMSTADT CREEK 2.0
END DESCRIPTION:
XS GIS Cut Line= 3
        2051475.       13907775.        2051525.       13907375.
      2051125.01     13906175.02
#Sta/Elev= 30
  4596.9 1349.91  4657.4 1348.25  4715.3 1337.55  4720.3 1338.22  4795.9 1319.03
  4848.8 1315.99  4883.3 1312.57  4909.3  1312.3  4929.5  1315.1  4949.6 1314.86
  5002.6 1313.88  5021.1 1312.08    5025 1310.71  5025.5 1310.21  5038.2 1310.71
  5052.7 1314.64  5083.1 1317.77  5168.9 1320.93  5231.9 1323.54  5400.6 1325.12
  5579.8  1325.1  5716.8 1327.27  5801.1 1326.61  5967.2  1328.3  6011.9 1330.45
  6022.5 1332.04  6075.2 1348.15  6159.5 1359.29  6222.8 1374.99  6264.9 1376.56
#Mann= 7 ,-1 , 0
  4596.9     .07       0  4883.3    .035       0    5025    .035       0
  5038.2    .035       0  5083.1     .12       0  5168.9    .035       0
  5967.2     .07       0
Bank Sta=5025,5038.2
XS Rating Curve= 0 ,0
Exp/Cntr=0.3,0.1

Type RM Length L Ch R = 1 ,1903    ,287,287,287
BEGIN DESCRIPTION:
DARMSTADT CREEK 1.0
END DESCRIPTION:
XS GIS Cut Line= 3
      2051875.01     13907524.97        2051925.       13907325.
      2051674.34     13905771.52
#Sta/Elev= 30
  4799.8 1330.68    4801 1330.68  4905.4 1321.46  4933.8 1306.49    4944 1306.12
    4975 1305.54  4982.7 1301.04    4989 1300.88  4989.5 1300.38  5002.2 1300.88
  5003.3 1303.81  5016.1 1306.76  5046.4 1307.38  5066.7 1312.45    5104 1315.06
  5204.1 1318.35  5286.1 1319.67  5404.4 1320.15  5498.3 1320.21  5503.8 1320.22
  5509.7 1320.23  5783.1 1320.83  6089.8 1325.39    6110 1323.63  6161.6 1339.76
  6191.1 1349.72    6262 1361.65  6290.1 1372.37  6434.2 1392.99  6579.5 1402.58
#Mann= 15 ,-1 , 0
  4799.8     .07       0    4801    .035       0    4944     .12       0
    4989     .05       0  5002.2     .12       0    5104     .07       0
  5204.1    .035       0  5286.1     .07       0  5404.4    .035       0
  5498.3     .07       0  5503.8    .035       0  5509.7     .07       0
  5783.1    .035       0  6161.6     .07       0  6434.2    .035       0
Bank Sta=4989,5002.2
XS Rating Curve= 0 ,0
Exp/Cntr=0.3,0.1

Type RM Length L Ch R = 1 ,1616    ,0,0,0
BEGIN DESCRIPTION:
DARMSTADT CREEK 0.0
END DESCRIPTION:
XS GIS Cut Line= 4
      2051974.29     13907502.28      2052144.09       13907334.
       2052177.3     13907219.17      2051869.82     13905800.92
#Sta/Elev= 30
  4641.4  1323.8  4780.4  1321.4  4855.4 1320.76  4890.9 1318.71  4931.5 1315.57
  4937.2 1309.66  4942.4 1315.28  4962.7  1306.4    4976 1305.96  5007.9 1297.27
  5008.4 1296.77  5021.1 1297.27  5055.4  1304.3  5125.4 1312.64  5184.8 1314.28
  5193.4 1314.51  5286.1 1315.29  5387.4 1316.92  5596.7 1311.29  5761.5 1317.49
  6073.2 1319.11  6122.3 1327.84  6166.4 1340.46  6191.2 1351.44  6215.6 1353.89
  6273.1 1377.16  6308.8  1383.1  6334.5 1390.99  6409.3 1401.24  6451.2 1403.32
#Mann= 11 ,-1 , 0
  4641.4    .035       0  4780.4     .12       0  4855.4     .07       0
  4890.9     .12       0  5007.9     .05       0  5021.1     .12       0
  5184.8    .035       0  5193.4     .07       0  5286.1    .035       0
  5387.4     .07       0  6409.3    .035       0
Bank Sta=5007.9,5021.1
XS Rating Curve= 0 ,0
Exp/Cntr=0.3,0.1

Chan Stop Cuts=-1
Use User Specified Reach Order=0
Composite Channel Slope=5