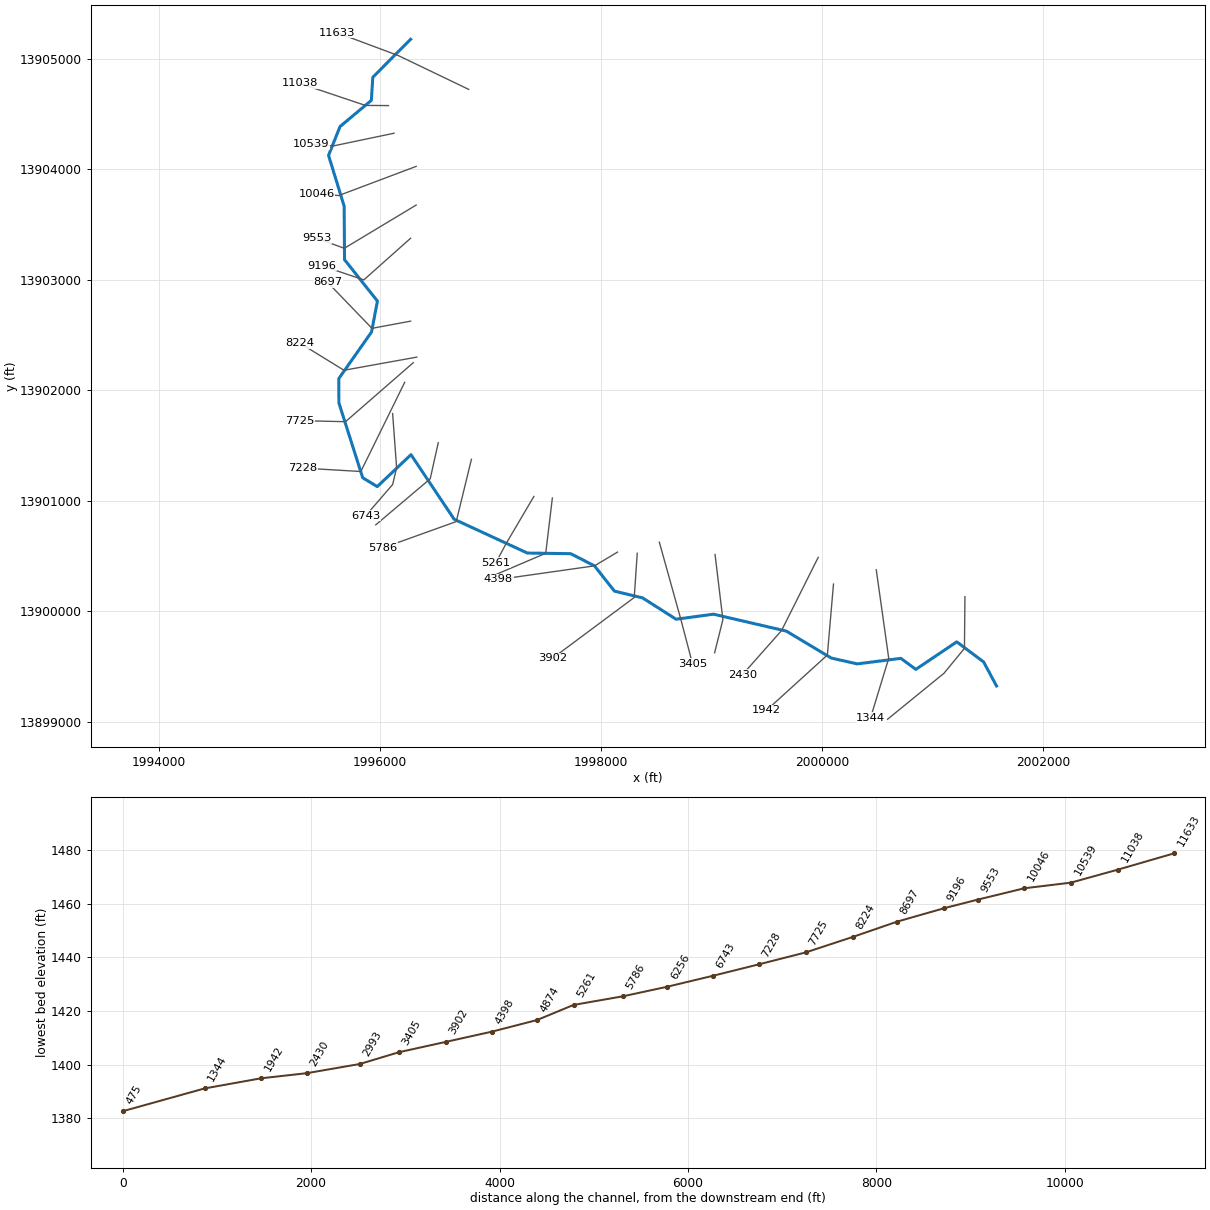
--- DRY CREEK 2.prj (project) ---

Proj Title=DRY CREEK 2 Base Level Engineering
Current Plan=p01
Default Exp/Contr=0.3,0.1
English Units
Geom File=g01
Flow File=f01
Plan File=p01
Y Axis Title=Elevation
X Axis Title(PF)=Main Channel Distance
X Axis Title(XS)=Station
BEGIN DESCRIPTION:
DRY CREEK 2
END DESCRIPTION:
DSS Export Rating Curves= 0
DSS Export Rating Curve Sorted= 0
DSS Export Volume Flow Curves= 0
DXF OffsetX= 0
DXF OffsetY= 0
DXF ScaleX= 1
DXF ScaleY= 10

--- DRY CREEK 2.p01 (plan) ---

Plan Title=Multiple Run
Short Identifier=Multiple
Geom File=g01
Flow File=f01
Subcritical Flow
K Sum by GR= 0
Std Step Tol= 0.01
Critical Tol= 0.01
Num of Std Step Trials= 20
Max Error Tol= 0.3
Flow Tol Ratio= 0.001
Split Flow NTrial= 30
Split Flow Tol= 0.02
Split Flow Ratio= 0.02
Log Output Level= 0
Friction Slope Method= 1
Unsteady Friction Slope Method= 2
Unsteady Bridges Friction Slope Method= 1
Parabolic Critical Depth
Global Vel Dist=  1 , 1 , 1
Global Log Level= 0
CheckData=True
Encroach Param= -1, 0, 0, 0
BEGIN DESCRIPTION:
Multiple Run
END DESCRIPTION:

--- DRY CREEK 2.f01 (steady flow) ---

Flow Title=Multiple
Number of Profiles=7
Profile Names=10-year,25-year,50-year,1pct_min,100-year,1pct_plu,500-year
River Rch & RM= DRY CREEK 2,Reach-1,11633
    1059    1796    2496    1682    3355    6695    5999
River Rch & RM= DRY CREEK 2,Reach-1,10046
    1421    2438    3414    2313    4615    9208    8350
Boundary for River Rch & Prof#=DRY CREEK 2,Reach-1,1
Up Type=0
Dn Type=3
Dn Slope=0.005
Boundary for River Rch & Prof#=DRY CREEK 2,Reach-1,2
Up Type=0
Dn Type=3
Dn Slope=0.005
Boundary for River Rch & Prof#=DRY CREEK 2,Reach-1,3
Up Type=0
Dn Type=3
Dn Slope=0.005
Boundary for River Rch & Prof#=DRY CREEK 2,Reach-1,4
Up Type=0
Dn Type=3
Dn Slope=0.005
Boundary for River Rch & Prof#=DRY CREEK 2,Reach-1,5
Up Type=0
Dn Type=3
Dn Slope=0.005
Boundary for River Rch & Prof#=DRY CREEK 2,Reach-1,6
Up Type=0
Dn Type=3
Dn Slope=0.005
Boundary for River Rch & Prof#=DRY CREEK 2,Reach-1,7
Up Type=0
Dn Type=3
Dn Slope=0.005

--- DRY CREEK 2.g01 (geometry) ---

Geom Title=Existing Conditions
Program Version=4.10

River Reach=DRY CREEK 2     ,Reach-1
Reach XY= 30
        1996275.       13905175.      1995932.81     13904831.19
      1995919.64      13904622.3      1995635.76     13904384.68
      1995532.56       13904125.      1995673.78      13903664.5
      1995677.06     13903180.85      1995974.82     13902806.73
      1995921.18     13902526.58      1995625.06     13902104.97
      1995626.38     13901884.66      1995841.44     13901208.21
      1995973.29      13901128.3      1996278.27     13901417.18
      1996668.66     13900833.02      1997330.94     13900527.26
      1997723.45     13900521.25      1997938.22     13900411.38
      1998118.55     13900182.74       1998373.5     13900121.38
      1998676.47     13899928.55      1999015.15     13899974.07
      1999673.45     13899821.25      2000080.52     13899577.36
      2000314.83      13899524.5      2000709.84     13899574.61
      2000845.06     13899474.79      2001215.36     13899723.91
      2001458.51     13899542.05        2001575.       13899325.

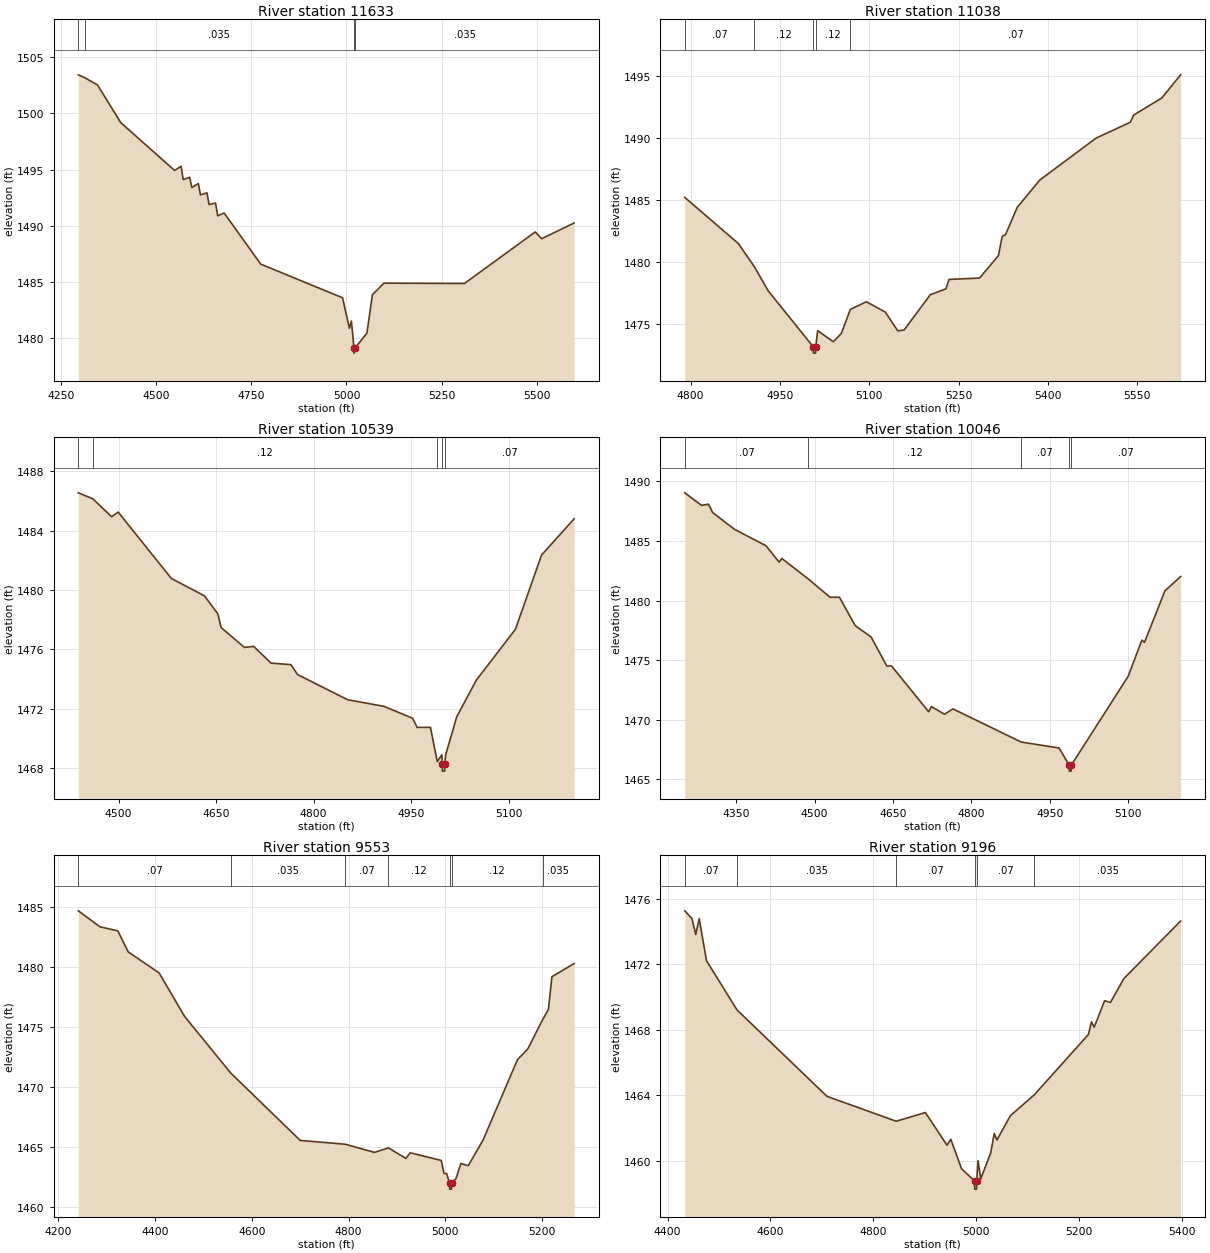
Type RM Length L Ch R = 1 ,11633   ,595,595,595
BEGIN DESCRIPTION:
DRY CREEK_2_DS 20.0
END DESCRIPTION:
XS GIS Cut Line= 3
       1996800.3     13904721.62      1996165.36     13905026.63
      1995605.05     13905236.16
#Sta/Elev= 30
  4295.6 1503.43  4311.9 1503.19  4345.9 1502.53  4407.1 1499.18  4548.5 1494.93
  4565.6  1495.3  4571.1 1494.12  4588.2 1494.32  4593.8 1493.41  4610.9 1493.77
  4616.4 1492.76  4633.5 1492.94  4639.1  1491.9  4656.2 1492.03  4661.7  1490.9
  4678.7 1491.14  4774.9  1486.6  4989.8 1483.61  5007.7 1480.91    5013 1481.54
  5019.7 1479.19    5020 1478.69  5023.7 1479.19  5053.8 1480.47  5068.2 1483.88
  5098.5 1484.91    5310 1484.88  5495.9 1489.46  5512.8 1488.86  5598.2 1490.26
#Mann= 4 ,-1 , 0
  4295.6     .12       0  4311.9    .035       0  5019.7    .035       0
  5023.7    .035       0
Bank Sta=5019.7,5023.7
XS Rating Curve= 0 ,0
Exp/Cntr=0.3,0.1

Type RM Length L Ch R = 1 ,11038   ,499,499,499
BEGIN DESCRIPTION:
DRY CREEK_2_DS 19.0
END DESCRIPTION:
XS GIS Cut Line= 3
      1996075.02       13904575.      1995865.38     13904576.63
      1995274.96     13904775.01
#Sta/Elev= 30
  4790.3 1485.19  4880.3 1481.47  4907.3 1479.59  4930.3 1477.66  5006.1 1473.14
  5006.3 1472.64  5009.8 1472.64  5010.1 1473.14  5013.4 1474.45  5039.6 1473.56
  5053.1 1474.22  5068.3 1476.17  5095.3 1476.78  5126.9 1475.95    5148 1474.43
  5158.6 1474.51  5202.5 1477.35  5228.7 1477.82    5234 1478.58  5285.2 1478.69
  5316.8 1480.49  5323.3 1482.06  5328.6 1482.17  5348.5 1484.39  5386.3 1486.59
  5480.9 1489.97  5538.4 1491.25    5544 1491.83  5591.1  1493.2  5622.8 1495.07
#Mann= 5 ,-1 , 0
  4790.3     .07       0  4907.3     .12       0  5006.1     .05       0
  5010.1     .12       0  5068.3     .07       0
Bank Sta=5006.1,5010.1
XS Rating Curve= 0 ,0
Exp/Cntr=0.3,0.1

Type RM Length L Ch R = 1 ,10539   ,493,493,493
BEGIN DESCRIPTION:
DRY CREEK_2_DS 18.0
END DESCRIPTION:
XS GIS Cut Line= 3
      1996124.98     13904324.99      1995575.09     13904209.91
      1995374.96       13904225.
#Sta/Elev= 30
  4438.2 1486.55  4460.5 1486.15  4489.3 1484.94  4499.5 1485.25  4581.2 1480.78
  4632.3  1479.6  4652.7 1478.39  4657.8 1477.47  4693.6 1476.13  4707.8  1476.2
  4734.5 1475.07  4765.1 1474.97  4775.3  1474.3  4852.5  1472.6  4908.1 1472.16
  4952.4 1471.35  4959.2 1470.74  4979.7 1470.74  4990.2 1468.44  4997.3 1468.89
  4997.8 1468.29    4998 1467.79  5001.5 1467.79  5001.8 1468.29  5003.1 1468.89
  5020.1 1471.45  5050.2 1473.92  5110.4 1477.35  5150.5 1482.35  5200.7  1484.8
#Mann= 5 ,-1 , 0
  4438.2     .07       0  4460.5     .12       0  4990.2     .07       0
  4997.8     .05       0  5001.8     .07       0
Bank Sta=4997.8,5001.8
XS Rating Curve= 0 ,0
Exp/Cntr=0.3,0.1

Type RM Length L Ch R = 1 ,10046   ,493,493,493
BEGIN DESCRIPTION:
DRY CREEK_2_DS 17.0
END DESCRIPTION:
XS GIS Cut Line= 3
      1996324.96     13904024.98      1995624.85      13903761.3
      1995425.04       13903775.
#Sta/Elev= 30
  4251.9 1489.04  4283.9 1487.99  4297.2 1488.09  4305.3 1487.38  4346.9 1485.98
  4407.3  1484.6  4432.2 1483.23  4437.6 1483.53    4488 1481.82  4529.7 1480.28
  4547.7 1480.28  4577.9  1477.9  4608.2 1476.95  4638.4 1474.51  4647.2 1474.53
  4718.3 1470.68  4723.7 1471.11  4748.6 1470.47  4764.8 1470.92  4895.3 1468.14
  4967.8 1467.64  4987.2  1466.2  4987.4  1465.7  4990.9  1465.7  4991.2  1466.2
  5100.1 1473.66  5126.2 1476.69  5131.2  1476.5  5170.3 1480.82  5200.3 1482.02
#Mann= 5 ,-1 , 0
  4251.9     .07       0    4488     .12       0  4895.3     .07       0
  4987.2     .05       0  4991.2     .07       0
Bank Sta=4987.2,4991.2
XS Rating Curve= 0 ,0
Exp/Cntr=0.3,0.1

Type RM Length L Ch R = 1 ,9553    ,357,357,357
BEGIN DESCRIPTION:
DRY CREEK_2_DS 16.0
END DESCRIPTION:
XS GIS Cut Line= 3
      1996325.04     13903675.03      1995674.95     13903284.07
      1995424.97     13903375.01
#Sta/Elev= 30
  4241.4 1484.68  4286.1 1483.35    4323 1483.01  4344.4 1481.26  4408.5  1479.5
    4461 1475.88  4556.2 1471.17  4699.9 1465.55  4793.1 1465.23  4853.4 1464.55
  4882.2 1464.93  4918.3 1464.05  4927.2 1464.52  4991.3 1463.88  4997.1 1462.79
  5002.6 1462.79  5008.5 1461.99  5008.8 1461.49  5012.4 1461.49  5012.6 1461.99
  5021.9 1462.38  5031.9 1463.62  5047.2 1463.45  5077.8 1465.58  5148.9 1472.28
  5170.2 1473.17  5200.6 1475.59  5212.8 1476.46  5220.1 1479.19    5266 1480.29
#Mann= 7 ,-1 , 0
  4241.4     .07       0  4556.2    .035       0  4793.1     .07       0
  4882.2     .12       0  5008.5     .05       0  5012.6     .12       0
  5200.6    .035       0
Bank Sta=5008.5,5012.6
XS Rating Curve= 0 ,0
Exp/Cntr=0.3,0.1

Type RM Length L Ch R = 1 ,9196    ,499,499,499
BEGIN DESCRIPTION:
DRY CREEK_2_DS 15.0
END DESCRIPTION:
XS GIS Cut Line= 3
      1996275.01     13903375.01      1995851.73     13902998.36
      1995475.04     13903124.99
#Sta/Elev= 30
  4433.4 1475.26  4447.2 1474.79  4454.7 1473.82  4461.4 1474.78  4475.6 1472.22
  4534.8 1469.22  4709.8 1463.95  4844.4 1462.43  4901.2 1462.96  4943.1 1460.97
  4950.6 1461.33  4971.5 1459.53  4996.7 1458.79    4997 1458.29  5000.6 1458.29
  5000.9 1458.79  5003.5 1460.03  5008.8 1458.92  5028.2  1460.5    5035 1461.68
  5040.3 1461.29  5066.5 1462.77  5113.2 1464.05  5218.1 1467.72  5224.1 1468.49
  5229.4 1468.17  5249.7 1469.78  5260.9 1469.67  5287.1 1471.13  5397.4 1474.64
#Mann= 6 ,-1 , 0
  4433.4     .07       0  4534.8    .035       0  4844.4     .07       0
  4996.7     .05       0  5000.9     .07       0  5113.2    .035       0
Bank Sta=4996.7,5000.9
XS Rating Curve= 0 ,0
Exp/Cntr=0.3,0.1

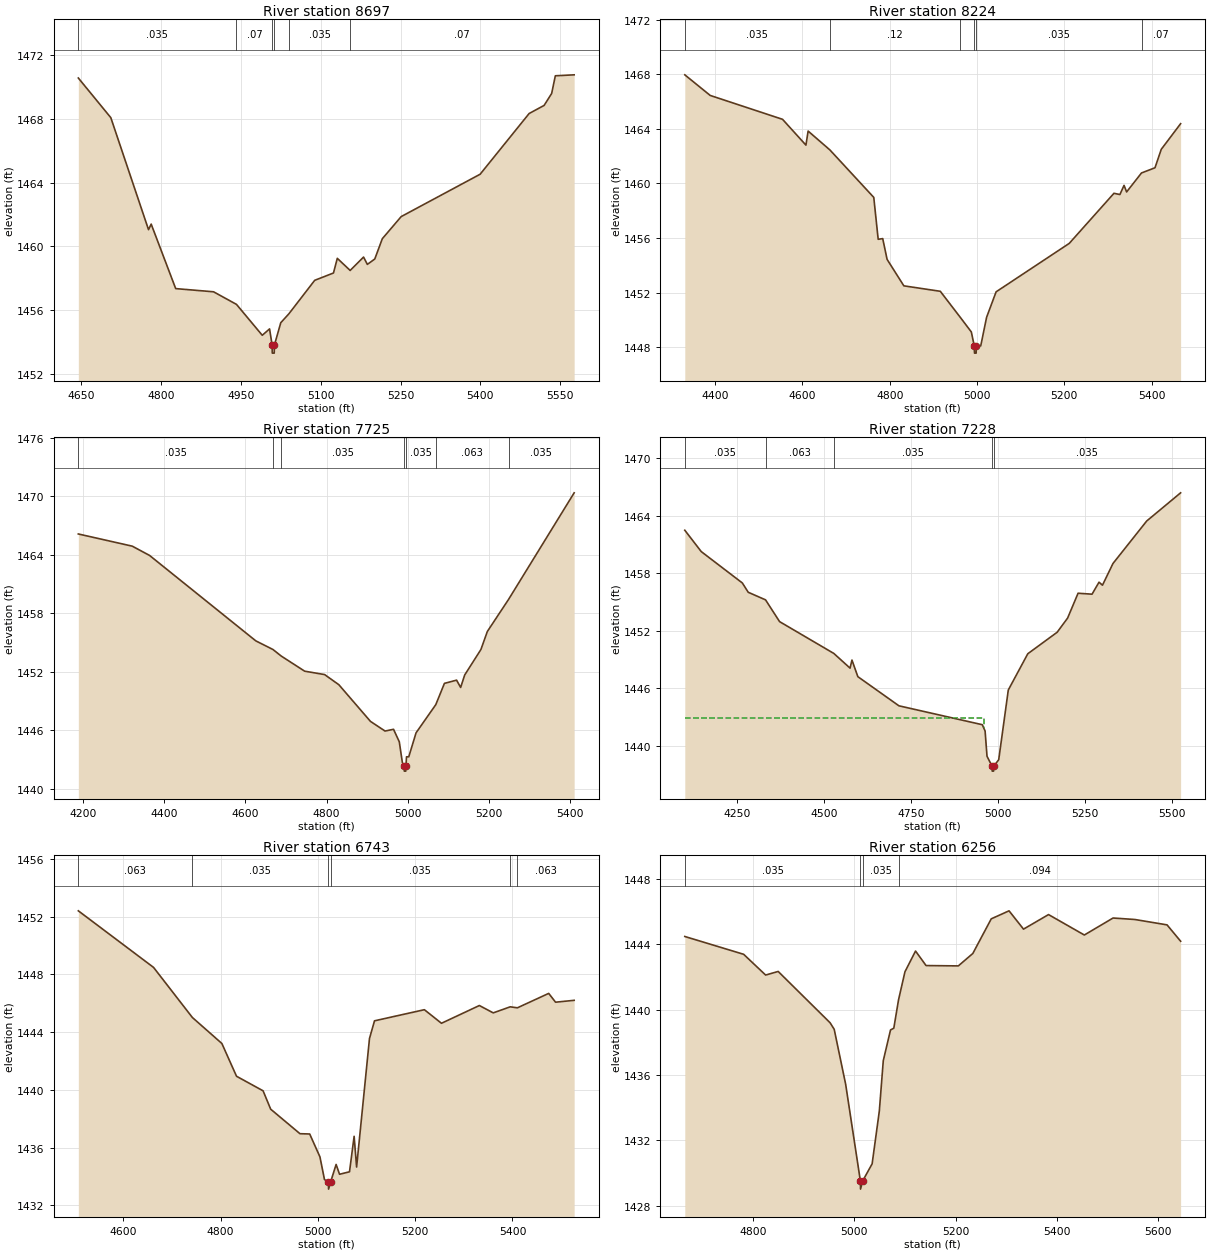
Type RM Length L Ch R = 1 ,8697    ,473,473,473
BEGIN DESCRIPTION:
DRY CREEK_2_DS 14.0
END DESCRIPTION:
XS GIS Cut Line= 3
      1996275.03     13902625.01      1995925.16     13902559.94
      1995525.01     13902974.99
#Sta/Elev= 30
  4644.1 1470.56  4705.2 1468.07  4776.1 1461.04  4781.1 1461.39  4827.2 1457.34
  4898.4 1457.14  4941.5 1456.35    4990 1454.41  5003.7 1454.81  5008.6 1453.79
  5008.8 1453.29  5012.5 1453.29  5012.8 1453.79  5024.8  1455.2  5040.1 1455.76
  5088.6 1457.86  5123.9 1458.32  5131.1 1459.24  5155.3 1458.48  5180.5 1459.32
  5187.6 1458.86  5201.6  1459.2  5215.7 1460.47  5251.2 1461.86  5399.7 1464.52
  5491.8 1468.33    5520 1468.84  5534.2 1469.59  5541.1  1470.7  5576.5 1470.76
#Mann= 6 ,-1 , 0
  4644.1    .035       0  4941.5     .07       0  5008.6     .05       0
  5012.8     .07       0  5040.1    .035       0  5155.3     .07       0
Bank Sta=5008.6,5012.8
XS Rating Curve= 0 ,0
Exp/Cntr=0.3,0.1

Type RM Length L Ch R = 1 ,8224    ,499,499,499
BEGIN DESCRIPTION:
DRY CREEK_2_DS 13.0
END DESCRIPTION:
XS GIS Cut Line= 3
        1996331.     13902299.65      1995672.15     13902180.73
      1995274.96     13902425.02
#Sta/Elev= 30
  4330.5 1467.95  4388.7 1466.44  4554.4 1464.69    4608  1462.8    4613 1463.83
  4662.8 1462.45  4763.4 1458.97  4773.5  1455.9  4783.9 1455.95  4793.9 1454.43
  4832.3 1452.49  4915.8 1452.09  4961.6 1450.18  4986.9 1449.11  4993.8 1448.06
  4994.1 1447.56  4997.9 1447.56  4998.2 1448.06  5008.4 1448.09  5021.8 1450.18
  5043.6 1452.05  5211.2  1455.6  5313.6 1459.27  5327.2 1459.18  5336.7 1459.85
  5342.6 1459.37  5376.7 1460.76  5407.6 1461.14  5421.9 1462.49  5466.3 1464.37
#Mann= 6 ,-1 , 0
  4330.5    .035       0  4662.8     .12       0  4961.6    .035       0
  4993.8    .035       0  4998.2    .035       0  5376.7     .07       0
Bank Sta=4993.8,4998.2
XS Rating Curve= 0 ,0
Exp/Cntr=0.3,0.1

Type RM Length L Ch R = 1 ,7725    ,497,497,497
BEGIN DESCRIPTION:
DRY CREEK_2_DS 12.0
END DESCRIPTION:
XS GIS Cut Line= 3
      1996298.63     13902248.94      1995685.89     13901715.37
        1995275.       13901725.
#Sta/Elev= 30
  4187.5 1466.12  4320.6 1464.87  4363.3 1463.92  4625.4 1455.16  4667.9 1454.27
  4688.2  1453.6    4746 1452.05  4795.3  1451.7  4830.4 1450.66  4908.4  1446.9
  4944.4 1445.91  4965.3 1446.09  4979.5 1444.81  4987.1 1442.68  4991.5  1442.3
  4991.8  1441.8  4995.6  1441.8    4996  1442.3  4997.3 1443.27  5002.9 1443.27
  5020.9 1445.73  5069.6 1448.62  5090.9  1450.8  5120.9 1451.13  5130.9 1450.38
  5140.9 1451.66  5180.9 1454.27  5196.8 1456.12    5249  1459.4    5411 1470.34
#Mann= 7 ,-1 , 0
  4187.5    .035       0  4667.9    .063       0  4688.2    .035       0
  4991.5    .035       0    4996    .035       0  5069.6    .063       0
    5249    .035       0
Bank Sta=4991.5,4996
XS Rating Curve= 0 ,0
Exp/Cntr=0.3,0.1

Type RM Length L Ch R = 1 ,7228    ,485,485,485
BEGIN DESCRIPTION:
DRY CREEK_2_DS 11.0
END DESCRIPTION:
XS GIS Cut Line= 3
      1996221.28     13902071.56      1995824.82     13901264.93
      1995301.12     13901295.61
#Sta/Elev= 30
  4101.2 1462.48  4148.5 1460.25  4266.4 1456.98  4283.3 1456.01    4333 1455.22
  4373.3 1452.95  4529.1 1449.63  4575.6  1448.1  4581.1 1448.94    4598 1447.21
    4716 1444.17  4955.3  1442.2  4963.3 1441.54  4968.8 1438.91  4983.5 1437.86
  4983.8 1437.36  4987.7 1437.36    4988 1437.86  5002.4 1438.55  5029.9 1445.82
  5085.9  1449.6  5170.1 1451.84  5200.2 1453.32  5230.2 1455.91  5270.3 1455.81
  5290.3 1457.06  5300.3 1456.75  5330.4 1459.01  5427.2 1463.44  5524.6 1466.38
#Mann= 5 ,-1 , 0
  4101.2    .035       0    4333    .063       0  4529.1    .035       0
  4983.5    .035       0    4988    .035       0
#XS Ineff= 2 , 0
       0    4960 1442.85               0
Permanent Ineff=
       F       F
Bank Sta=4983.5,4988
XS Rating Curve= 0 ,0
Exp/Cntr=0.3,0.1

Type RM Length L Ch R = 1 ,6743    ,487,487,487
BEGIN DESCRIPTION:
DRY CREEK_2_DS 10.0
END DESCRIPTION:
XS GIS Cut Line= 4
      1996112.23     13901789.23      1996148.28     13901298.36
      1996112.23     13901146.87      1995869.59      13900866.1
#Sta/Elev= 30
  4507.8  1452.4  4662.4 1448.48  4742.2 1445.01  4802.8 1443.21  4832.9 1440.94
  4887.5 1439.93  4903.1 1438.66  4963.3 1436.96  4983.3 1436.94  5004.3 1435.36
  5013.7 1433.78  5021.8 1433.62  5022.1 1433.12  5026.3 1433.62  5037.6 1434.83
  5044.6 1434.15  5065.1 1434.32  5074.6 1436.78  5079.7 1434.65  5106.2 1443.56
  5116.5 1444.78    5219 1445.55  5254.1 1444.61    5332 1445.84  5360.5 1445.33
  5395.4 1445.75  5410.1 1445.68  5474.5 1446.68  5488.6 1446.07  5526.8  1446.2
#Mann= 6 ,-1 , 0
  4507.8    .063       0  4742.2    .035       0  5021.8    .035       0
  5026.3    .035       0  5395.4    .094       0  5410.1    .063       0
Bank Sta=5021.8,5026.3
XS Rating Curve= 0 ,0
Exp/Cntr=0.3,0.1

Type RM Length L Ch R = 1 ,6256    ,470,470,470
BEGIN DESCRIPTION:
DRY CREEK_2_DS 9.0
END DESCRIPTION:
XS GIS Cut Line= 3
      1996524.99     13901524.96      1996452.07      13901198.5
      1995959.76     13900782.55
#Sta/Elev= 30
  4665.5 1444.48  4781.7 1443.39  4825.1 1442.12  4849.9 1442.34  4952.4  1439.2
  4960.5  1438.8  4983.1 1435.44  5012.2 1429.52  5012.5 1429.02  5016.7 1429.52
  5035.4 1430.57  5049.6  1433.8  5057.4 1436.88  5071.7 1438.76  5078.2 1438.87
  5087.5  1440.6  5100.2 1442.32  5121.1 1443.59  5141.9  1442.7  5205.6 1442.68
  5234.2 1443.44  5270.6 1445.56  5305.7 1446.05  5334.3 1444.93  5383.7 1445.82
  5454.4 1444.57  5511.1 1445.61    5554 1445.52  5617.7 1445.19  5644.5 1444.19
#Mann= 4 ,-1 , 0
  4665.5    .035       0  5012.2    .035       0  5016.7    .035       0
  5087.5    .094       0
Bank Sta=5012.2,5016.7
XS Rating Curve= 0 ,0
Exp/Cntr=0.3,0.1

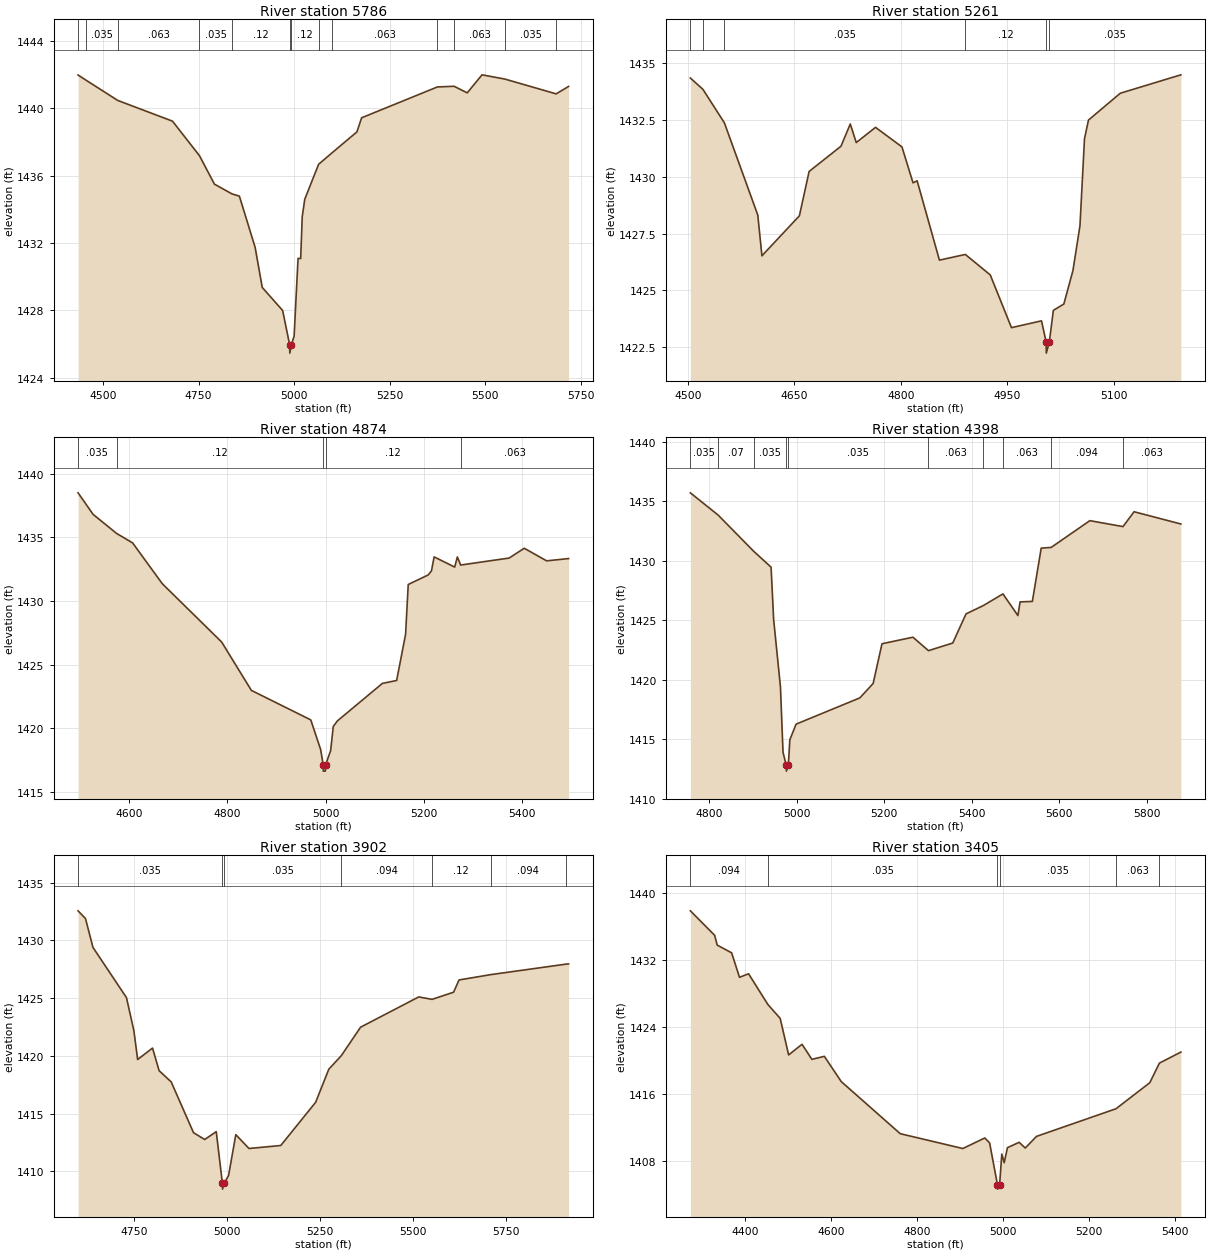
Type RM Length L Ch R = 1 ,5786    ,525,525,525
BEGIN DESCRIPTION:
DRY CREEK_2_DS 8.0
END DESCRIPTION:
XS GIS Cut Line= 3
      1996824.99     13901374.97      1996687.58     13900811.83
      1996025.47     13900573.97
#Sta/Elev= 30
  4434.6 1441.97  4454.2 1441.68  4538.4 1440.46  4681.6 1439.23  4752.2 1437.18
  4791.4 1435.49  4837.5 1434.91  4856.6 1434.78  4897.8 1431.74  4916.4 1429.36
  4969.8 1427.99  4988.1 1425.96  4988.5 1425.46  4992.7 1425.96  4999.8 1426.47
  5010.1 1431.08    5017 1431.08    5021 1433.55  5027.6 1434.59  5063.9 1436.67
  5099.5 1437.36    5164 1438.59  5176.4 1439.43  5374.6 1441.26  5418.3  1441.3
  5452.7 1440.91  5491.4 1441.98  5550.9 1441.73  5685.3 1440.85  5717.8 1441.29
#Mann= 13 ,-1 , 0
  4434.6    .063       0  4454.2    .035       0  4538.4    .063       0
  4752.2    .035       0  4837.5     .12       0  4988.1     .05       0
  4992.7     .12       0  5063.9    .094       0  5099.5    .063       0
  5374.6    .094       0  5418.3    .063       0  5550.9    .035       0
  5685.3    .063       0
Bank Sta=4988.1,4992.7
XS Rating Curve= 0 ,0
Exp/Cntr=0.3,0.1

Type RM Length L Ch R = 1 ,5261    ,387,387,387
BEGIN DESCRIPTION:
DRY CREEK_2_DS 7.0
END DESCRIPTION:
XS GIS Cut Line= 3
      1997389.76     13901039.19      1997138.13     13900611.18
      1997045.99     13900439.78
#Sta/Elev= 30
  4503.5 1434.34  4521.2 1433.84  4551.4 1432.37  4598.5 1428.31  4604.3 1426.52
  4657.1 1428.28  4670.8 1430.23  4715.7 1431.34  4728.8 1432.32  4737.2  1431.5
  4764.4 1432.17  4801.6 1431.31  4817.2 1429.73    4823 1429.82  4854.4 1426.33
  4890.9 1426.58    4926 1425.68  4955.9 1423.36  4998.2 1423.66  5004.7 1422.74
    5005 1422.24  5009.3 1422.74  5014.9 1424.12  5029.7  1424.4  5042.5 1425.87
  5052.4 1427.84  5058.8 1431.67  5064.4 1432.49  5109.2 1433.67  5194.6 1434.48
#Mann= 6 ,-1 , 0
  4503.5    .035       0  4521.2     .12       0  4551.4    .035       0
  4890.9     .12       0  5004.7     .05       0  5009.3    .035       0
Bank Sta=5004.7,5009.3
XS Rating Curve= 0 ,0
Exp/Cntr=0.3,0.1

Type RM Length L Ch R = 1 ,4874    ,476,476,476
BEGIN DESCRIPTION:
DRY CREEK_2_DS 6.0
END DESCRIPTION:
XS GIS Cut Line= 3
      1997557.15     13901025.28      1997497.06     13900524.98
      1997042.03     13900331.12
#Sta/Elev= 30
  4496.1 1438.51  4526.6 1436.82  4574.4 1435.32  4607.2 1434.57  4667.6 1431.36
  4788.5 1426.77  4848.9 1422.97  4969.8 1420.65  4989.9 1418.32  4995.1 1417.12
  4995.4 1416.62  4999.5 1416.62  4999.9 1417.12  5010.2 1418.22  5015.6 1420.13
    5024 1420.57  5115.6 1423.52  5144.6 1423.75  5162.8 1427.38  5168.2  1431.3
  5208.8 1432.05  5215.5 1432.37  5220.9 1433.47  5262.8 1432.67  5268.2 1433.47
  5274.9 1432.83  5373.6 1433.38  5404.4 1434.15  5449.9 1433.16  5494.6 1433.34
#Mann= 5 ,-1 , 0
  4496.1    .035       0  4574.4     .12       0  4995.1     .05       0
  4999.9     .12       0  5274.9    .063       0
Bank Sta=4995.1,4999.9
XS Rating Curve= 0 ,0
Exp/Cntr=0.3,0.1

Type RM Length L Ch R = 1 ,4398    ,496,496,496
BEGIN DESCRIPTION:
DRY CREEK_2_DS 5.0
END DESCRIPTION:
XS GIS Cut Line= 3
      1998146.33     13900535.66      1997938.22     13900411.38
      1997069.13     13900288.02
#Sta/Elev= 30
  4757.6 1435.71    4821 1433.84  4902.1  1430.8  4941.9 1429.46  4947.8 1425.04
  4963.3  1419.4  4969.2 1413.89  4976.5 1412.81  4976.9 1412.31  4981.3 1412.81
  4984.7 1414.94    4999 1416.26  5144.7 1418.47    5175 1419.68  5195.2 1423.02
  5265.9 1423.57  5301.3 1422.44  5356.8 1423.08  5387.1 1425.53  5426.6 1426.23
  5471.4 1427.21  5505.6 1425.39  5510.6 1426.54  5538.6 1426.58  5558.8 1431.06
  5581.6 1431.12  5669.9 1433.37  5745.6 1432.87  5770.9 1434.12  5877.8 1433.09
#Mann= 10 ,-1 , 0
  4757.6    .035       0    4821     .07       0  4902.1    .035       0
  4976.5    .035       0  4981.3    .035       0  5301.3    .063       0
  5426.6     .07       0  5471.4    .063       0  5581.6    .094       0
  5745.6    .063       0
Bank Sta=4976.5,4981.3
XS Rating Curve= 0 ,0
Exp/Cntr=0.3,0.1

Type RM Length L Ch R = 1 ,3902    ,497,497,497
BEGIN DESCRIPTION:
DRY CREEK_2_DS 4.0
END DESCRIPTION:
XS GIS Cut Line= 3
        1998325.     13900524.97      1998297.77      13900125.1
      1997560.35     13899576.33
#Sta/Elev= 30
  4599.2 1432.56  4619.2 1431.89  4639.3 1429.39  4729.5 1425.04  4749.5 1422.16
  4759.5 1419.68  4799.6 1420.67  4817.3 1418.71  4849.8 1417.74  4909.9 1413.34
    4940 1412.75  4971.1 1413.43  4987.6 1408.95    4988 1408.45  4992.5 1408.95
  5004.3 1409.64  5023.7 1413.17  5059.2 1411.97  5144.7 1412.23  5238.5 1415.97
    5274 1418.84  5307.8 1420.02  5359.5 1422.48  5515.9  1425.1  5551.8 1424.89
  5609.8 1425.51  5624.4 1426.57  5709.1 1427.03    5912 1427.94  5919.2 1427.96
#Mann= 7 ,-1 , 0
  4599.2    .035       0  4987.6    .035       0  4992.5    .035       0
  5307.8    .094       0  5551.8     .12       0  5709.1    .094       0
    5912    .063       0
Bank Sta=4987.6,4992.5
XS Rating Curve= 0 ,0
Exp/Cntr=0.3,0.1

Type RM Length L Ch R = 1 ,3405    ,412,412,412
BEGIN DESCRIPTION:
DRY CREEK_2_DS 3.0
END DESCRIPTION:
XS GIS Cut Line= 3
      1998524.99     13900625.02      1998720.26     13899924.52
      1998824.99     13899525.03
#Sta/Elev= 30
  4272.8 1437.84  4329.3 1434.91  4335.1 1433.75  4368.7 1432.82    4387  1429.9
  4408.1 1430.32    4453 1426.65  4481.6 1424.99  4501.2 1420.63  4532.4  1421.9
  4555.2  1420.1  4584.2 1420.46  4623.6 1417.44  4760.7 1411.22  4906.1 1409.45
  4957.3 1410.71  4968.4 1410.11  4986.7  1405.1    4987  1404.6  4991.6  1405.1
  4996.7 1408.79  5002.3 1407.75  5009.8 1409.55  5037.1 1410.19  5051.2 1409.51
  5077.4  1410.9  5262.2  1414.2  5340.7 1417.31  5363.1 1419.65    5413 1420.97
#Mann= 6 ,-1 , 0
  4272.8    .094       0    4453    .035       0  4986.7    .035       0
  4991.6    .035       0  5262.2    .063       0  5363.1    .094       0
Bank Sta=4986.7,4991.6
XS Rating Curve= 0 ,0
Exp/Cntr=0.3,0.1

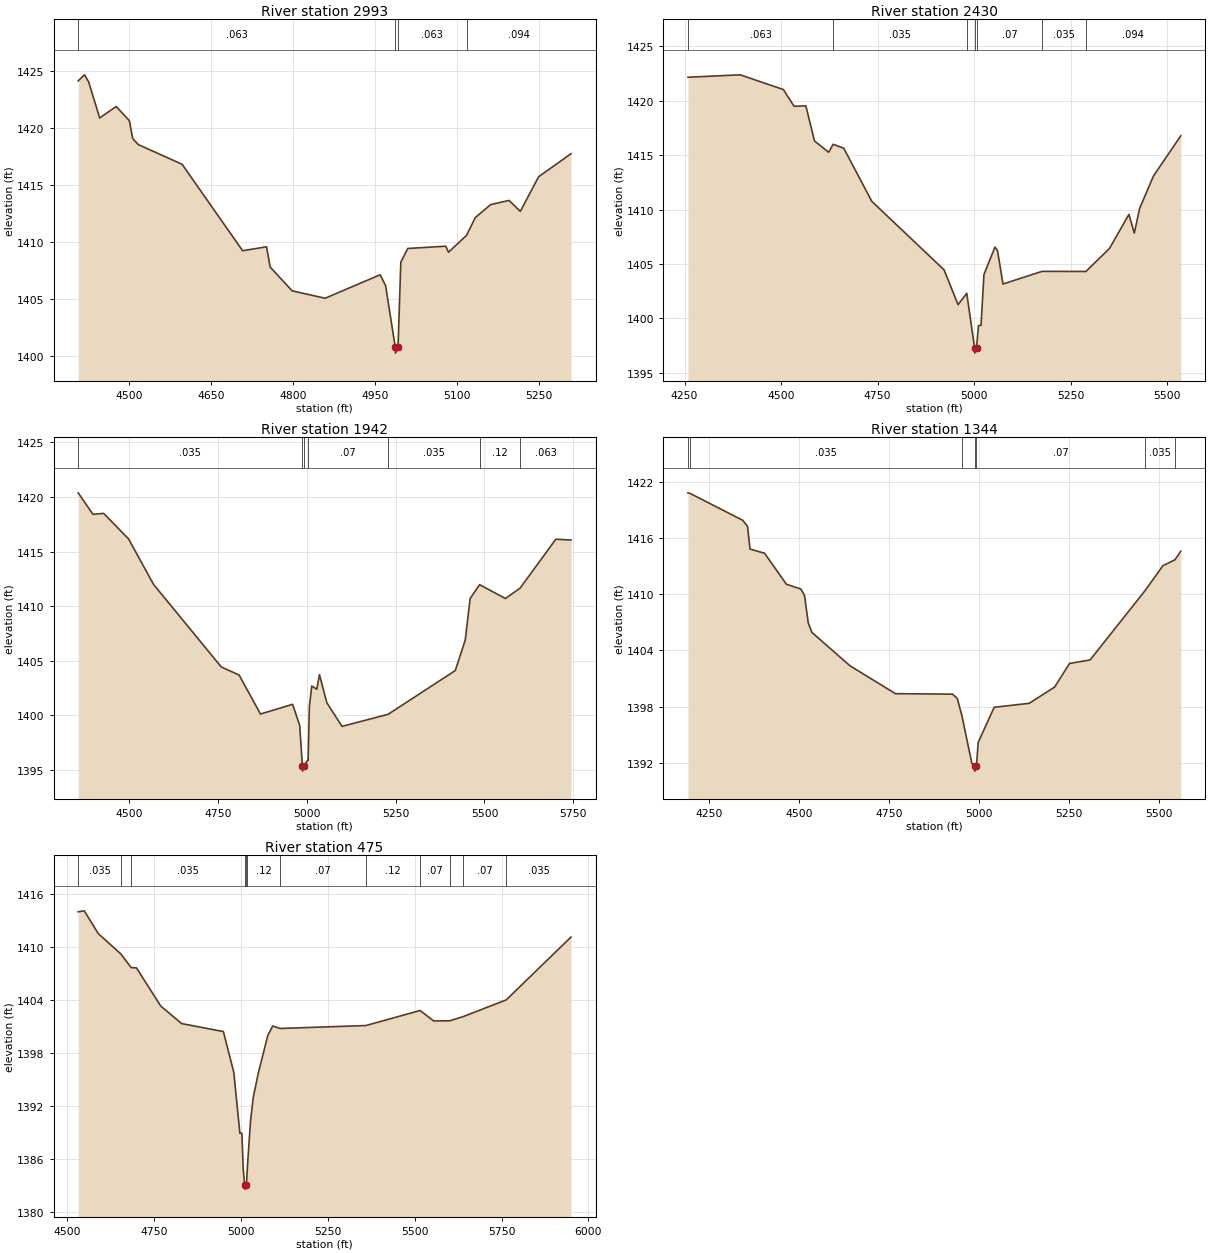
Type RM Length L Ch R = 1 ,2993    ,563,563,563
BEGIN DESCRIPTION:
DRY CREEK_2_DS 2.0
END DESCRIPTION:
XS GIS Cut Line= 3
      1999028.89     13900514.07      1999099.92     13899924.83
      1999024.99     13899624.95
#Sta/Elev= 30
  4406.5 1424.15  4418.2 1424.68  4425.7 1424.06  4445.9 1420.89  4476.1  1421.9
  4500.3 1420.65  4506.3 1419.09  4516.4 1418.56  4596.9 1416.82  4707.7 1409.23
  4751.5 1409.58  4758.1  1407.8  4798.4 1405.71  4858.8 1405.06  4959.5 1407.12
  4969.6 1406.16  4987.3 1400.74  4987.7 1400.24  4992.3 1400.74  4997.4 1408.22
  5010.1 1409.43  5079.7 1409.63  5084.8  1409.1  5117.9 1410.59  5133.8 1412.14
  5162.1 1413.29  5195.7 1413.65  5216.3 1412.69  5249.8 1415.73  5309.1 1417.75
#Mann= 4 ,-1 , 0
  4406.5    .063       0  4987.3     .05       0  4992.3    .063       0
  5117.9    .094       0
Bank Sta=4987.3,4992.3
XS Rating Curve= 0 ,0
Exp/Cntr=0.3,0.1

Type RM Length L Ch R = 1 ,2430    ,488,488,488
BEGIN DESCRIPTION:
DRY CREEK_2_DS 1.0
END DESCRIPTION:
XS GIS Cut Line= 3
      1999962.08     13900488.06      1999630.18     13899825.44
      1999274.97     13899424.97
#Sta/Elev= 30
  4258.9 1422.15  4394.2 1422.37    4506 1421.02  4533.9 1419.48  4564.3 1419.52
  4586.7 1416.29  4623.3 1415.26  4634.9 1415.99  4662.4 1415.63  4735.1 1410.75
  4922.2 1404.46  4958.5 1401.26    4981 1402.31  5001.2 1397.31  5001.6 1396.81
  5006.4 1397.31  5011.3 1399.33    5018 1399.37  5025.5 1404.02    5054 1406.55
  5060.6 1406.23  5074.9 1403.16  5176.2 1404.32  5289.6 1404.31  5350.8 1406.43
    5401 1409.55    5415 1407.83  5428.6 1410.09  5464.6 1413.08  5535.3 1416.77
#Mann= 7 ,-1 , 0
  4258.9    .063       0  4634.9    .035       0    4981     .07       0
  5001.2     .05       0  5006.4     .07       0  5176.2    .035       0
  5289.6    .094       0
Bank Sta=5001.2,5006.4
XS Rating Curve= 0 ,0
Exp/Cntr=0.3,0.1

Type RM Length L Ch R = 1 ,1942    ,598,598,598
BEGIN DESCRIPTION:
DRY CREEK_2_DS 0.2
END DESCRIPTION:
XS GIS Cut Line= 3
       2000100.3     13900246.54      2000044.89     13899604.72
      1999494.51     13899104.69
#Sta/Elev= 30
  4355.8 1420.38  4397.5 1418.41  4427.6  1418.5  4497.9 1416.15  4568.1 1411.99
  4758.8 1404.43    4809 1403.69  4869.2 1400.12  4959.6 1401.01  4979.6 1399.08
  4987.1 1395.39  4987.5 1394.89  4992.3 1395.39  5001.7 1395.88  5003.3 1395.88
  5006.8 1400.79  5013.6 1402.69  5027.8 1402.39  5035.2 1403.73  5056.1 1401.15
  5098.7 1398.99  5228.4 1400.09  5417.7  1404.1  5445.7 1406.88  5459.6  1410.7
  5486.2 1411.97  5558.9  1410.7  5600.3 1411.65  5700.8 1416.13  5743.6 1416.06
#Mann= 7 ,-1 , 0
  4355.8    .035       0  4987.1    .035       0  4992.3    .035       0
  5001.7     .07       0  5228.4    .035       0  5486.2     .12       0
  5600.3    .063       0
Bank Sta=4987.1,4992.3
XS Rating Curve= 0 ,0
Exp/Cntr=0.3,0.1

Type RM Length L Ch R = 1 ,1344    ,869,869,869
BEGIN DESCRIPTION:
DRY CREEK_2_DS 0.1
END DESCRIPTION:
XS GIS Cut Line= 3
       2000487.2     13900375.74        2000600.     13899575.05
      2000436.38     13899039.38
#Sta/Elev= 30
  4191.4  1420.8  4197.7 1420.73  4343.6 1417.87  4356.8 1417.24  4363.8  1414.8
  4404.2 1414.36  4464.8 1411.05  4505.2 1410.54  4515.3 1409.82  4525.4 1406.95
  4535.5 1405.92  4641.6 1402.35  4767.8 1399.38  4926.3 1399.33  4939.5 1398.87
  4952.1 1397.05  4979.9 1391.95  4987.3 1391.62  4987.7 1391.12  4992.6 1391.62
  4997.5 1394.19  5041.9 1397.93  5139.1 1398.35  5209.9 1400.09    5251  1402.6
  5308.3 1402.98  5461.9 1410.42  5510.3 1413.02    5544 1413.66  5560.1 1414.57
#Mann= 7 ,-1 , 0
  4191.4     .07       0  4197.7    .035       0  4952.1     .07       0
  4987.3     .05       0  4992.6     .07       0  5461.9    .035       0
    5544    .094       0
Bank Sta=4987.3,4992.6
XS Rating Curve= 0 ,0
Exp/Cntr=0.3,0.1

Type RM Length L Ch R = 1 ,475     ,0,0,0
BEGIN DESCRIPTION:
DRY CREEK_2_DS 0.0
END DESCRIPTION:
XS GIS Cut Line= 4
      2001289.32     13900132.51      2001285.05     13899665.13
       2001100.1     13899439.82      2000589.84     13899024.05
#Sta/Elev= 30
  4532.6 1413.96  4550.1 1414.07  4590.1 1411.51  4655.3  1409.2  4685.1 1407.65
  4700.1 1407.63  4770.1 1403.31  4830.1 1401.33  4950.1 1400.43  4980.1 1395.82
  4997.6 1388.94  5003.3 1388.94  5007.3 1384.84  5011.1 1383.13  5011.5 1382.63
  5016.5 1383.13  5019.1 1385.05  5028.1  1390.3    5036 1392.98  5050.3 1395.69
  5077.8 1399.98    5092 1401.06  5113.3 1400.78  5359.9 1401.11  5515.8 1402.81
    5555 1401.63  5601.5 1401.65  5639.7 1402.12  5763.5 1404.01  5949.7 1411.11
#Mann= 12 ,-1 , 0
  4532.6    .035       0  4655.3    .063       0  4685.1    .035       0
  5011.1    .035       0  5016.5    .035       0  5019.1     .12       0
  5113.3     .07       0  5359.9     .12       0  5515.8     .07       0
  5601.5    .035       0  5639.7     .07       0  5763.5    .035       0
Bank Sta=5011.1,5016.5
XS Rating Curve= 0 ,0
Exp/Cntr=0.3,0.1

Chan Stop Cuts=-1
Use User Specified Reach Order=0
Composite Channel Slope=5