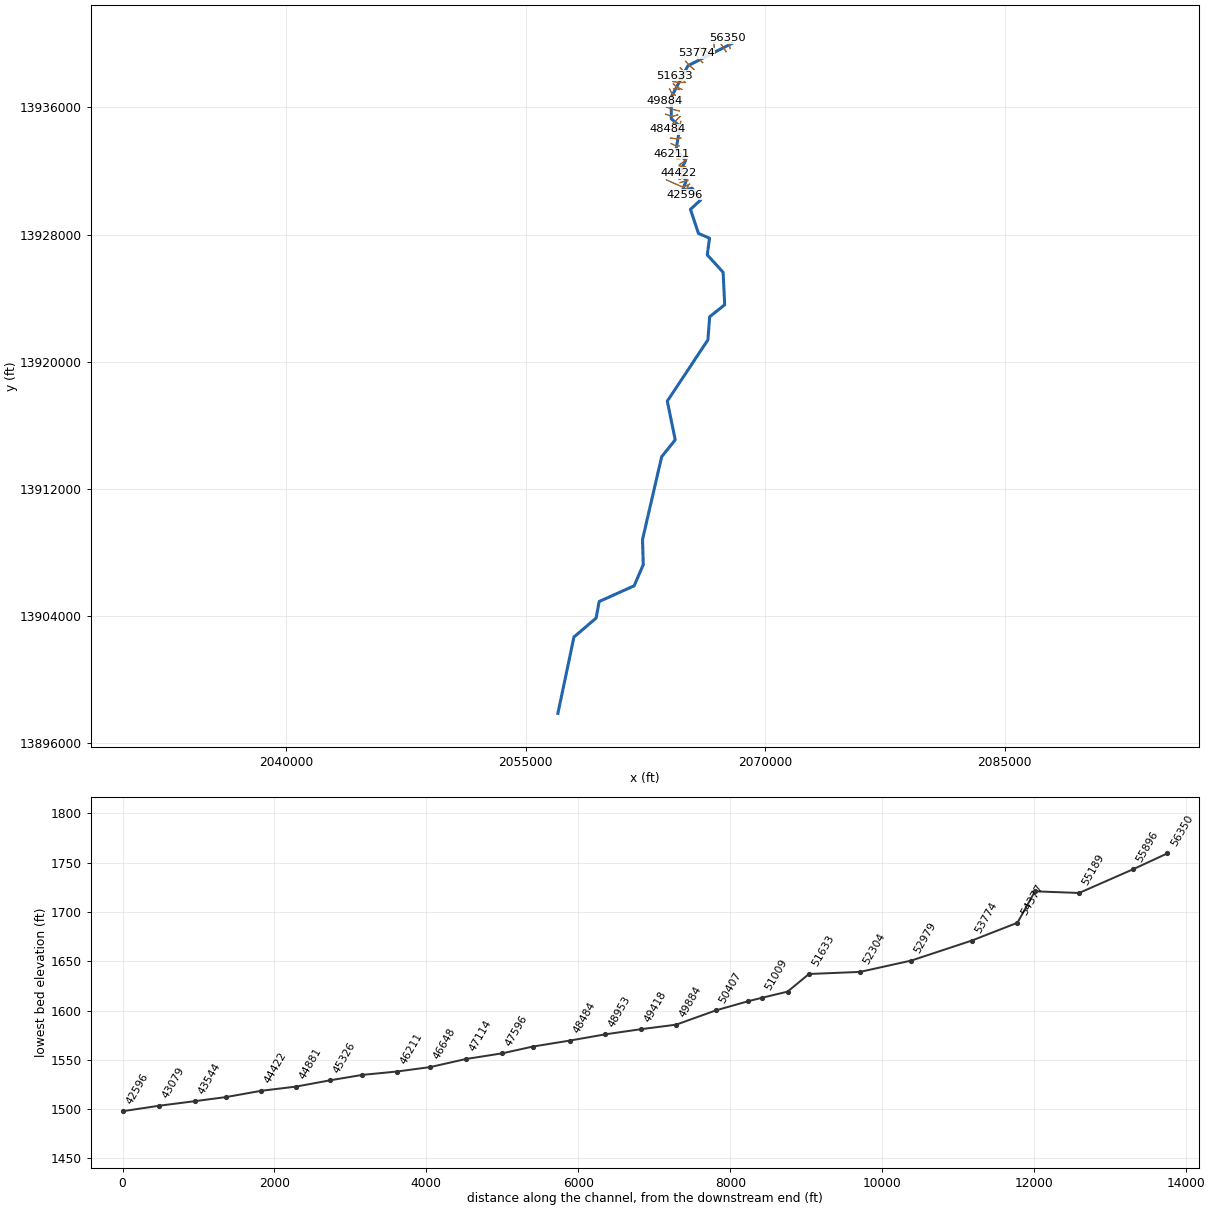
--- EAST SISTER CREEK.prj (project) ---

Proj Title=EAST SISTER CREEK Base Level Engineering
Current Plan=p01
Default Exp/Contr=0.3,0.1
English Units
Geom File=g01
Flow File=f01
Plan File=p01
Y Axis Title=Elevation
X Axis Title(PF)=Main Channel Distance
X Axis Title(XS)=Station
BEGIN DESCRIPTION:
EAST SISTER CREEK
END DESCRIPTION:
DSS Export Rating Curves= 0
DSS Export Rating Curve Sorted= 0
DSS Export Volume Flow Curves= 0
DXF OffsetX= 0
DXF OffsetY= 0
DXF ScaleX= 1
DXF ScaleY= 10

--- EAST SISTER CREEK.p01 (plan) ---

Plan Title=Multiple Run
Short Identifier=Multiple
Geom File=g01
Flow File=f01
Subcritical Flow
K Sum by GR= 0
Std Step Tol= 0.01
Critical Tol= 0.01
Num of Std Step Trials= 20
Max Error Tol= 0.3
Flow Tol Ratio= 0.001
Split Flow NTrial= 30
Split Flow Tol= 0.02
Split Flow Ratio= 0.02
Log Output Level= 0
Friction Slope Method= 1
Unsteady Friction Slope Method= 2
Unsteady Bridges Friction Slope Method= 1
Parabolic Critical Depth
Global Vel Dist=  1 , 1 , 1
Global Log Level= 0
CheckData=True
Encroach Param= -1, 0, 0, 0
BEGIN DESCRIPTION:
Multiple Run
END DESCRIPTION:

--- EAST SISTER CREEK.f01 (steady flow) ---

Flow Title=Multiple
Program Version=4.10
Number of Profiles= 7
Profile Names=10-year,25-year,50-year,1pct_min,100-year,1pct_plu,500-year
River Rch & RM=EAST SISTER CREE,Reach-1         ,56350
     239     375     495     320     639    1275    1048
River Rch & RM=EAST SISTER CREE,Reach-1         ,55896
     408     663     897     592    1182    2359    2028
River Rch & RM=EAST SISTER CREE,Reach-1         ,52979
    1420    2494    3553    2456    4899    9776    9241
River Rch & RM=EAST SISTER CREE,Reach-1         ,48484
    1769    3140    4505    3133    6251   12472   11940
River Rch & RM=EAST SISTER CREE,Reach-1         ,46648
    1964    3500    5035    3509    7001   13970   13435
River Rch & RM=EAST SISTER CREE,Reach-1         ,44881
    2400    4279    6155    4285    8549   17058   16364
River Rch & RM=EAST SISTER CREE,Reach-1         ,36778
    2423    4314    6202    4314    8607   17174   16449
River Rch & RM=EAST SISTER CREE,Reach-1         ,34923
    4261    7777   11365    8022   16006   31937   31511
River Rch & RM=EAST SISTER CREE,Reach-1         ,31718
    4399    8033   11745    8293   16546   33014   32595
River Rch & RM=EAST SISTER CREE,Reach-1         ,28868
    6847   12671   18692   13299   26535   52945   53067
River Rch & RM=EAST SISTER CREE,Reach-1         ,24991
    7040   13015   19187   13639   27213   54298   54325
River Rch & RM=EAST SISTER CREE,Reach-1         ,22790
    8336   15445   22810   16239   32401   64649   64843
River Rch & RM=EAST SISTER CREE,Reach-1         ,20046
    8369   15499   22881   16283   32489   64823   64963
River Rch & RM=EAST SISTER CREE,Reach-1         ,18945
    8555   15845   23393   16647   33215   66273   66414
River Rch & RM=EAST SISTER CREE,Reach-1         ,17815
   10216   18997   28109   20017   39938   79688   79830
River Rch & RM=EAST SISTER CREE,Reach-1         ,15637
   10334   19220   28443   20257   40418   80644   80804
River Rch & RM=EAST SISTER CREE,Reach-1         ,14498
   10375   19289   28537   20317   40538   80884   80993
River Rch & RM=EAST SISTER CREE,Reach-1         ,13404
   10223   18957   27995   19894   39693   79198   79002
River Rch & RM=EAST SISTER CREE,Reach-1         ,11145
   10328   19109   28176   19987   39879   79569   79093
Boundary for River Rch & Prof#=EAST SISTER CREE,Reach-1         , 1
Up Type= 0
Dn Type= 3
Dn Slope=0.005
Boundary for River Rch & Prof#=EAST SISTER CREE,Reach-1         , 2
Up Type= 0
Dn Type= 3
Dn Slope=0.005
Boundary for River Rch & Prof#=EAST SISTER CREE,Reach-1         , 3
Up Type= 0
Dn Type= 3
Dn Slope=0.005
Boundary for River Rch & Prof#=EAST SISTER CREE,Reach-1         , 4
Up Type= 0
Dn Type= 3
Dn Slope=0.005
Boundary for River Rch & Prof#=EAST SISTER CREE,Reach-1         , 5
Up Type= 0
Dn Type= 3
Dn Slope=0.005
Boundary for River Rch & Prof#=EAST SISTER CREE,Reach-1         , 6
Up Type= 0
Dn Type= 3
Dn Slope=0.005
Boundary for River Rch & Prof#=EAST SISTER CREE,Reach-1         , 7
Up Type= 0
Dn Type= 3
Dn Slope=0.005
DSS Import GetInterval= 0
DSS Import GetPeak= 0
DSS Import FillOption= 0

--- EAST SISTER CREEK.g01 (geometry) ---

Geom Title=Existing Conditions
Program Version=4.10

River Reach=EAST SISTER CREE,Reach-1
Reach XY= 30
        2067925.       13940025.        2065175.       13938625.
      2064124.61      13936652.2      2064127.14     13935280.97
      2064674.64     13934810.11      2064426.21     13933334.59
       2065024.6     13932661.09      2064625.07     13931859.61
      2065074.47     13931414.53       2064826.6     13930786.81
       2065427.3     13930919.91       2065967.4     13930178.34
       2065325.7      13929584.8       2065832.8     13928068.79
      2066521.99     13927773.57      2066380.83      13926722.7
        2067375.       13925625.      2067472.72     13923580.57
      2066530.45     13922827.45      2066421.86     13921376.03
      2063877.19     13917519.55      2064374.47     13915088.85
        2063525.       13914025.       2062326.2      13908814.5
      2062371.46     13907226.47      2061802.14     13905901.47
      2059611.65      13904911.7      2059417.26     13903868.55
      2058030.54     13902677.42        2057025.       13897875.

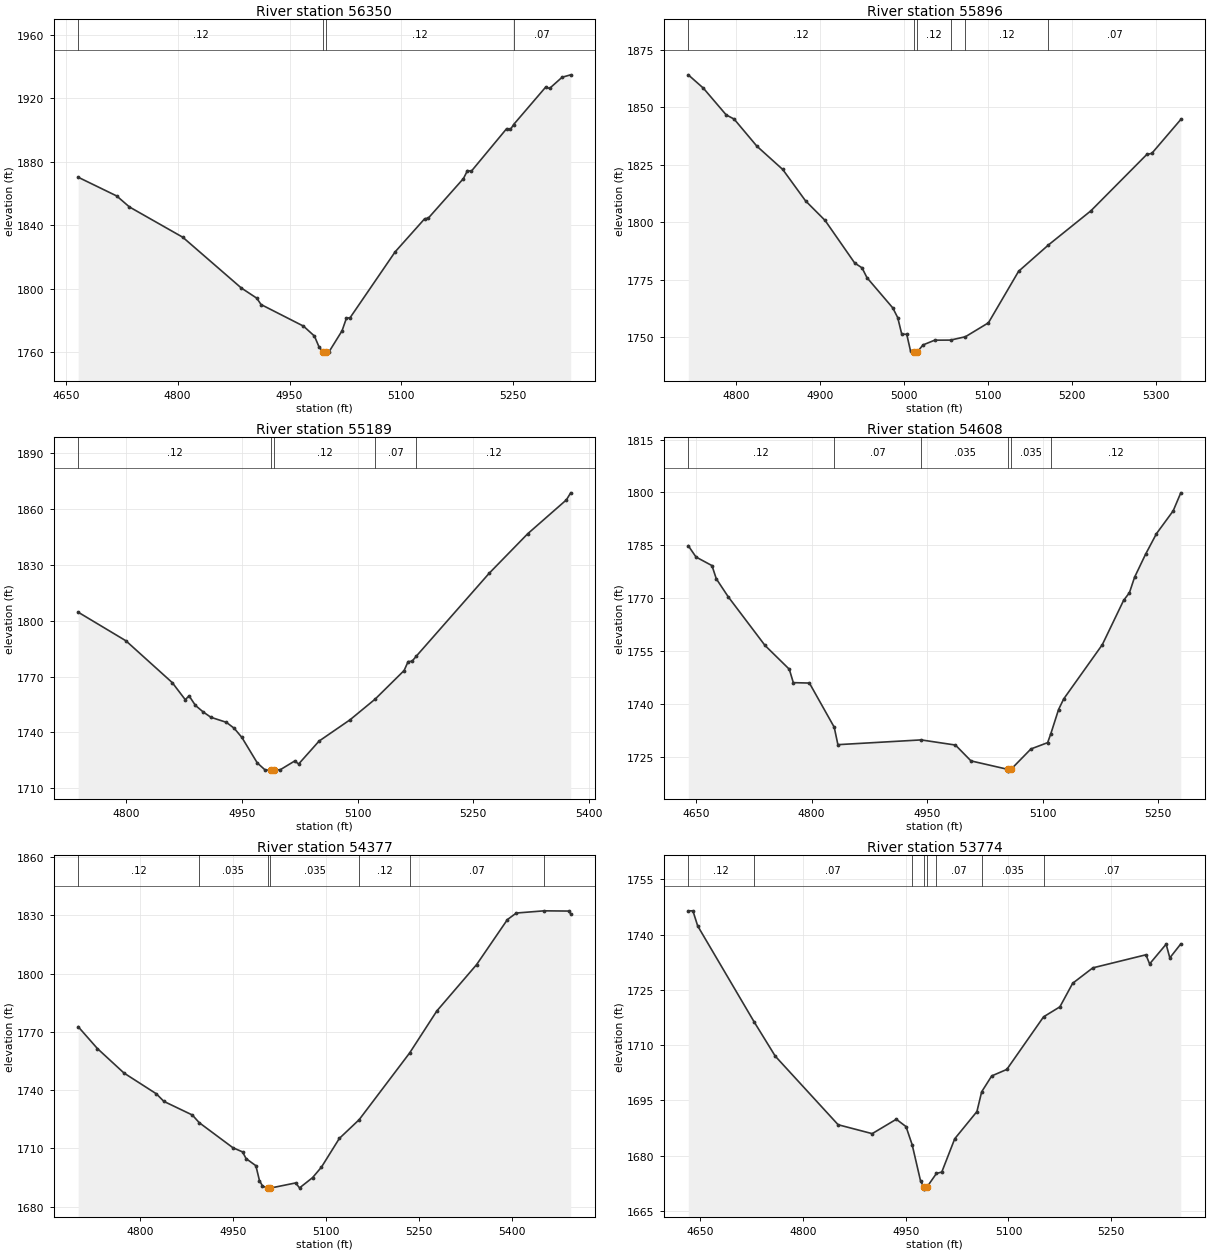
Type RM Length L Ch R = 1 ,56350   ,454,454,454
BEGIN DESCRIPTION:
EAST SISTER CREEK 108.0
END DESCRIPTION:
XS GIS Cut Line= 3
      2067819.91     13939705.39        2067725.       13940025.
      2067664.44     13940346.34
#Sta/Elev= 30
  4666.6 1870.24  4718.3 1858.43  4735.3 1851.52  4806.9 1832.41  4885.3 1800.45
  4906.1 1794.01  4911.8 1790.01  4968.7  1776.4  4983.4 1770.13  4989.6 1763.24
  4995.4 1759.88  4995.6 1759.38  4999.4 1759.88  5002.5 1759.88  5020.4 1773.44
  5026.2 1781.29  5031.3 1781.77  5091.6 1823.21  5131.1 1844.03  5136.2 1844.53
  5183.2 1869.42  5188.6 1874.45  5193.7 1873.99  5241.1 1900.85  5246.2 1900.33
  5250.5 1903.47  5293.5 1927.07  5298.6 1926.19  5315.5 1933.26    5327 1934.78
#Mann= 4 ,-1 , 0
  4666.6     .12       0  4995.4     .05       0  4999.4     .12       0
  5250.5     .07       0
Bank Sta=4995.4,4999.4
XS Rating Curve= 0 ,0
Exp/Cntr=0.3,0.1

Type RM Length L Ch R = 1 ,55896   ,707,707,707
BEGIN DESCRIPTION:
EAST SISTER CREEK 107.0
END DESCRIPTION:
XS GIS Cut Line= 3
      2067560.68     13939506.62        2067425.       13939725.
      2067239.72     13939997.23
#Sta/Elev= 30
  4742.9 1864.01  4760.9 1858.22  4788.1  1846.6  4797.5  1844.8  4824.6 1833.03
  4855.4 1822.91  4882.5 1809.31  4905.8 1800.79  4941.1 1782.28  4949.8  1780.2
  4955.7 1775.92  4986.4 1762.81  4992.3 1758.58  4997.1 1751.37    5003 1751.37
  5007.5 1744.16  5011.5 1743.67  5011.8 1743.17  5015.5 1743.67  5022.4 1746.73
  5036.3 1748.79  5055.2 1748.83  5072.9 1750.29  5100.3 1756.34  5136.2 1778.71
  5171.7 1790.13  5222.2 1804.94  5288.8 1829.42  5294.8 1829.91  5329.3 1844.62
#Mann= 6 ,-1 , 0
  4742.9     .12       0  5011.5     .05       0  5015.5     .12       0
  5055.2     .07       0  5072.9     .12       0  5171.7     .07       0
Bank Sta=5011.5,5015.5
XS Rating Curve= 0 ,0
Exp/Cntr=0.3,0.1

Type RM Length L Ch R = 1 ,55189   ,581,581,581
BEGIN DESCRIPTION:
EAST SISTER CREEK 106.0
END DESCRIPTION:
XS GIS Cut Line= 2
      2066839.78     13939413.23      2066795.36     13940050.59
#Sta/Elev= 30
  4737.6 1804.51  4799.5 1789.18  4859.7 1766.71  4876.5 1757.59  4881.5 1759.61
  4889.7 1754.51  4899.8 1750.99  4909.8 1748.13  4929.8 1745.44  4939.9 1742.27
  4949.9 1737.36  4969.9 1723.68    4980 1719.91    4988 1719.75  4988.2 1719.25
    4992 1719.75    5000 1720.06  5018.5 1724.69  5023.6 1723.08  5050.1 1735.37
  5090.2 1746.77  5122.8 1757.87  5160.4 1773.22  5165.6 1778.01  5170.7  1778.2
  5176.4    1781  5270.7 1825.37  5320.8 1846.61  5370.9 1864.76  5376.5 1868.54
#Mann= 5 ,-1 , 0
  4737.6     .12       0    4988     .05       0    4992     .12       0
  5122.8     .07       0  5176.4     .12       0
Bank Sta=4988,4992
XS Rating Curve= 0 ,0
Exp/Cntr=0.3,0.1

Type RM Length L Ch R = 1 ,54608   ,231,231,231
BEGIN DESCRIPTION:
EAST SISTER CREEK 105.0
END DESCRIPTION:
XS GIS Cut Line= 3
       2066694.2     13939388.32      2066352.61     13939502.61
      2066166.57     13939710.93
#Sta/Elev= 30
  4639.8 1784.89  4649.9 1781.67  4670.6 1779.24  4676.2  1775.5  4691.7 1770.39
  4739.4  1756.6    4771 1749.83  4776.2 1746.03  4797.1 1745.91  4829.3 1733.39
  4834.1 1728.43  4942.2 1729.78  4986.7 1728.32  5006.9 1723.82  5054.8 1721.42
  5055.1 1720.92  5058.8 1721.42  5084.7 1727.21  5106.4    1729  5110.6 1731.56
  5120.6  1738.4  5127.3 1741.42  5177.4  1756.8  5205.1 1769.39  5212.6 1771.54
  5219.3 1775.94  5233.5 1782.43  5247.7  1788.3  5269.4 1794.77  5279.3 1799.89
#Mann= 6 ,-1 , 0
  4639.8     .12       0  4829.3     .07       0  4942.2    .035       0
  5054.8    .035       0  5058.8    .035       0  5110.6     .12       0
Bank Sta=5054.8,5058.8
XS Rating Curve= 0 ,0
Exp/Cntr=0.3,0.1

Type RM Length L Ch R = 1 ,54377   ,603,603,603
BEGIN DESCRIPTION:
EAST SISTER CREEK 104.0
END DESCRIPTION:
XS GIS Cut Line= 3
      2066483.62     13939172.37        2066225.       13939325.
      2065919.74     13939713.91
#Sta/Elev= 30
  4699.7 1772.67  4730.8 1761.39  4773.7 1748.79  4825.8 1738.12    4838 1734.21
  4883.9  1727.2    4895 1723.26  4949.3 1710.37  4964.9 1708.21  4970.7 1704.73
  4986.4 1701.11  4992.2 1693.48  4997.1 1690.67  5005.2 1689.54  5005.5 1689.04
  5009.2 1689.54  5050.6 1692.23  5056.9 1689.67  5077.8 1694.93  5092.2 1700.35
  5121.1 1715.14  5153.1  1724.8  5234.5 1759.13  5278.4 1780.76  5342.6 1804.63
  5392.3 1827.81  5406.7 1831.18  5451.5 1832.31  5491.7 1832.19  5494.4 1830.71
#Mann= 7 ,-1 , 0
  4699.7     .12       0    4895    .035       0  5005.2    .035       0
  5009.2    .035       0  5153.1     .12       0  5234.5     .07       0
  5451.5     .12       0
Bank Sta=5005.2,5009.2
XS Rating Curve= 0 ,0
Exp/Cntr=0.3,0.1

Type RM Length L Ch R = 1 ,53774   ,795,795,795
BEGIN DESCRIPTION:
EAST SISTER CREEK 103.0
END DESCRIPTION:
XS GIS Cut Line= 3
      2066089.85     13938820.37        2065825.       13939075.
       2065692.2     13939400.56
#Sta/Elev= 30
  4632.6 1746.49  4639.4 1746.49  4646.4 1742.37  4728.5 1716.41  4759.6 1707.02
  4851.4 1688.39  4901.1 1685.97  4936.3 1689.88  4950.5 1687.88  4959.5 1682.93
  4971.8 1673.05  4976.8  1671.4    4977  1670.9  4980.8  1671.4  4994.9 1675.16
  5002.7 1675.54  5021.6 1684.58    5054 1691.97  5060.9 1697.33  5075.6 1701.65
  5097.6 1703.41  5151.3  1717.7  5175.1 1720.41  5193.8 1726.82  5223.2    1731
  5300.7 1734.55  5306.1 1732.07  5330.2 1737.43  5335.6 1733.71  5351.6  1737.5
#Mann= 8 ,-1 , 0
  4632.6     .12       0  4728.5     .07       0  4959.5    .035       0
  4976.8     .05       0  4980.8    .035       0  4994.9     .07       0
  5060.9    .035       0  5151.3     .07       0
Bank Sta=4976.8,4980.8
XS Rating Curve= 0 ,0
Exp/Cntr=0.3,0.1

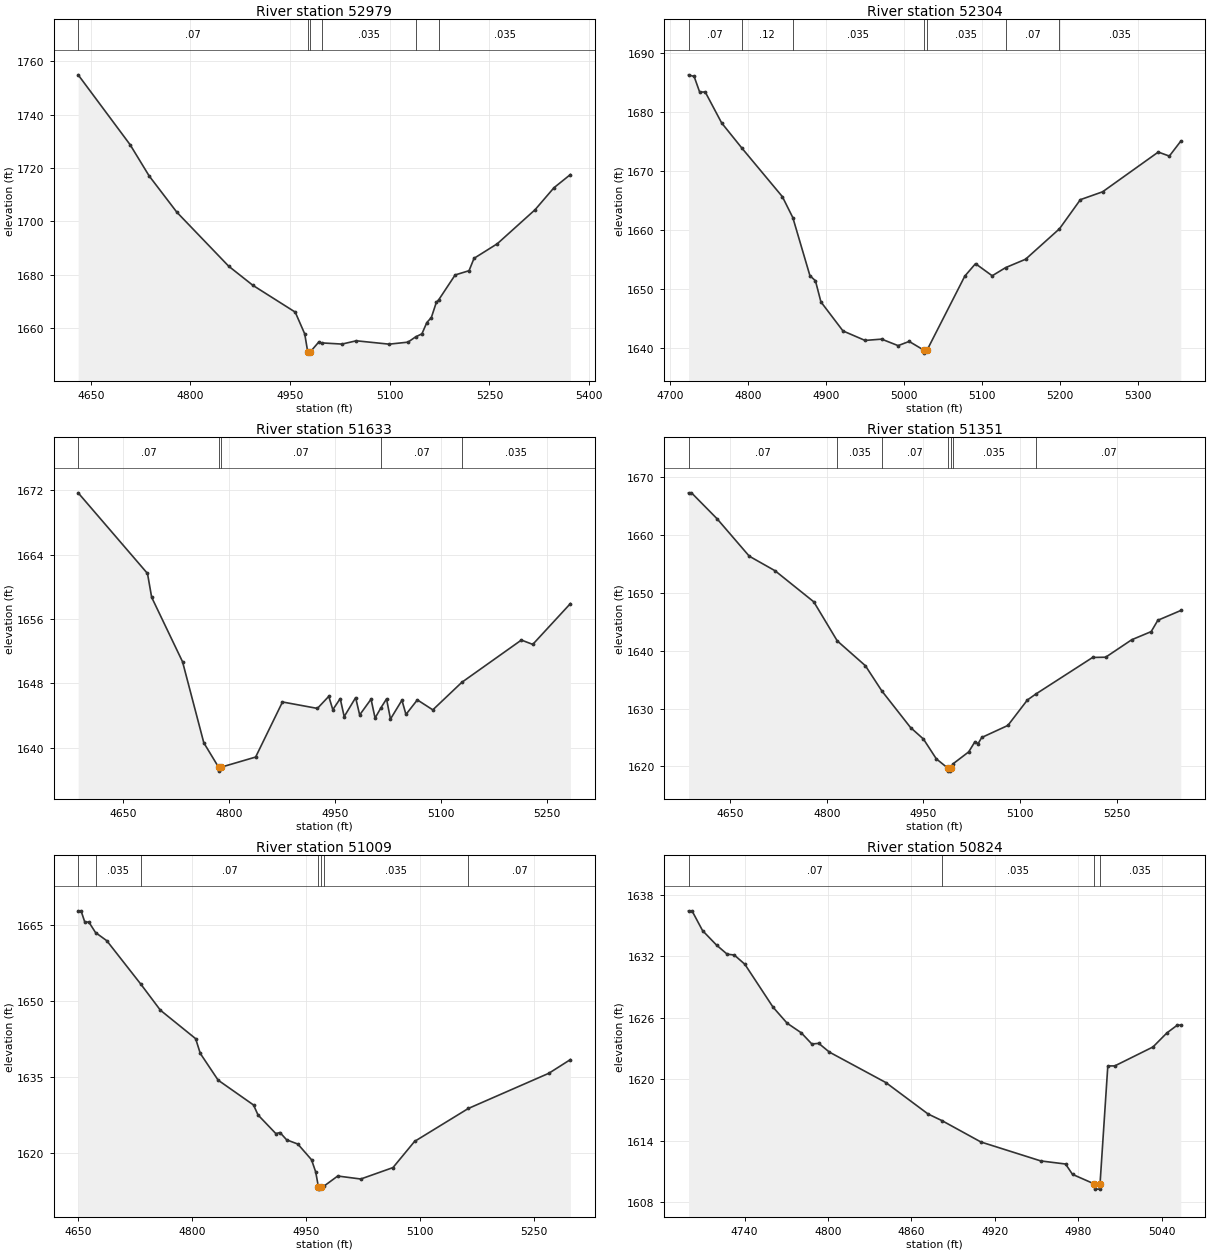
Type RM Length L Ch R = 1 ,52979   ,675,675,675
BEGIN DESCRIPTION:
EAST SISTER CREEK 102.0
END DESCRIPTION:
XS GIS Cut Line= 3
      2065557.77     13938387.93        2065275.       13938625.
       2065025.9     13938901.15
#Sta/Elev= 30
    4631 1754.91  4709.2 1728.74  4737.8 1717.07  4779.5 1703.47  4857.6 1683.23
    4894 1676.07  4957.7 1666.04    4972 1657.88  4976.5 1651.18  4976.8 1650.68
  4980.5 1651.18  4992.8 1654.74  4997.6 1654.51    5028 1654.07  5049.7  1655.3
    5099 1654.04  5127.4 1654.79  5138.8 1656.75  5148.4 1657.92  5155.8 1662.14
  5162.6 1664.02    5170 1669.65  5173.8  1670.7  5198.4 1679.96  5219.3 1681.55
  5226.8 1686.18  5261.9 1691.66  5318.7 1704.39  5347.1 1712.62  5371.9 1717.57
#Mann= 6 ,-1 , 0
    4631     .07       0  4976.5    .035       0  4980.5     .07       0
  4997.6    .035       0  5138.8     .07       0  5173.8    .035       0
Bank Sta=4976.5,4980.5
XS Rating Curve= 0 ,0
Exp/Cntr=0.3,0.1

Type RM Length L Ch R = 1 ,52304   ,671,671,671
BEGIN DESCRIPTION:
EAST SISTER CREEK 101.0
END DESCRIPTION:
XS GIS Cut Line= 3
      2065118.95     13938028.78        2064925.       13938225.
      2064693.79     13938495.04
#Sta/Elev= 30
  4724.1 1686.32  4731.3 1686.04  4738.4 1683.39  4745.5 1683.42  4766.6 1678.17
  4792.5 1673.92  4844.5 1665.68  4857.9 1662.13  4879.8 1652.31  4886.9 1651.44
  4893.9 1647.87  4922.2 1642.95  4950.5 1641.34  4971.8 1641.56  4992.9 1640.46
  5007.1 1641.17    5026 1639.69  5026.2 1639.19    5030 1639.69  5078.5 1652.24
  5092.2 1654.34  5113.6 1652.29  5130.8 1653.67  5156.4 1655.09  5199.9 1660.25
  5226.7 1665.18  5255.2 1666.51  5326.6 1673.24  5340.8 1672.56  5355.5 1675.09
#Mann= 7 ,-1 , 0
  4724.1     .07       0  4792.5     .12       0  4857.9    .035       0
    5026    .035       0    5030    .035       0  5130.8     .07       0
  5199.9    .035       0
Bank Sta=5026,5030
XS Rating Curve= 0 ,0
Exp/Cntr=0.3,0.1

Type RM Length L Ch R = 1 ,51633   ,282,282,282
BEGIN DESCRIPTION:
EAST SISTER CREEK 100.0
END DESCRIPTION:
XS GIS Cut Line= 2
      2064961.09     13937650.09      2064349.61     13937983.56
#Sta/Elev= 30
  4586.5 1671.69  4684.6 1661.66  4690.5  1658.7  4734.2 1650.68  4764.3  1640.6
  4785.1 1637.58  4785.3 1637.08  4789.1 1637.58  4837.6 1638.83  4875.6 1645.68
    4925 1644.88  4941.1 1646.38  4946.8 1644.72  4957.3  1646.1  4962.9 1643.86
  4979.1 1646.22  4984.8 1644.07  5000.9 1646.03  5006.6 1643.68  5015.1 1644.99
  5022.8 1646.06  5028.4 1643.56  5044.6  1645.9  5050.3 1644.13  5066.4 1645.94
  5088.3  1644.7  5129.3 1648.12  5213.6 1653.38  5229.7 1652.84    5283 1657.92
#Mann= 5 ,-1 , 0
  4586.5     .07       0  4785.1     .05       0  4789.1     .07       0
  5015.1     .07       0  5129.3    .035       0
Bank Sta=4785.1,4789.1
XS Rating Curve= 0 ,0
Exp/Cntr=0.3,0.1

Type RM Length L Ch R = 1 ,51351   ,342,342,342
BEGIN DESCRIPTION:
EAST SISTER CREEK 99.0
END DESCRIPTION:
XS GIS Cut Line= 3
      2064989.18     13937570.45        2064575.       13937575.
      2064229.74     13937625.98
#Sta/Elev= 30
  4585.8 1667.31  4590.4 1667.31    4630 1662.83    4680 1656.35    4720 1653.83
    4780 1648.46  4816.4  1641.7    4860 1637.41  4885.5 1633.05    4930 1626.72
    4950 1624.73    4970  1621.3    4988 1619.68  4988.2 1619.18  4991.7 1619.18
    4992 1619.68  4995.5 1620.41  5020.2 1622.51  5029.8 1624.26  5034.8 1623.95
  5040.4    1625  5080.9 1627.08  5111.2 1631.49  5124.6 1632.54  5212.3 1638.84
  5232.5 1638.88  5272.9  1641.9  5303.1 1643.31  5313.4 1645.27    5349 1646.96
#Mann= 7 ,-1 , 0
  4585.8     .07       0  4816.4    .035       0  4885.5     .07       0
    4988    .035       0    4992     .07       0  4995.5    .035       0
  5124.6     .07       0
Bank Sta=4988,4992
XS Rating Curve= 0 ,0
Exp/Cntr=0.3,0.1

Type RM Length L Ch R = 1 ,51009   ,185,185,185
BEGIN DESCRIPTION:
EAST SISTER CREEK 98.0
END DESCRIPTION:
XS GIS Cut Line= 3
      2064796.95      13937136.1        2064475.       13937275.
      2064259.17     13937479.27
#Sta/Elev= 30
  4649.7 1667.86  4653.5 1667.86  4658.4 1665.66  4663.8 1665.63  4672.6 1663.56
  4687.4 1661.95  4732.5  1653.3  4757.9 1648.22  4804.3 1642.59  4810.4 1639.68
  4833.9 1634.39  4880.5 1629.48  4886.4 1627.51  4909.9 1623.82  4915.3 1624.04
  4924.1 1622.59  4938.8 1621.76  4956.8 1618.66  4962.3 1616.24  4965.8 1613.35
    4966 1612.85  4969.8 1613.35  4973.4 1613.47  4991.3 1615.44  5021.6 1614.85
    5064 1617.11  5092.4 1622.28  5163.1 1628.79  5269.1 1635.75  5297.5 1638.46
#Mann= 7 ,-1 , 0
  4649.7     .07       0  4672.6    .035       0  4732.5     .07       0
  4965.8    .035       0  4969.8     .07       0  4973.4    .035       0
  5163.1     .07       0
Bank Sta=4965.8,4969.8
XS Rating Curve= 0 ,0
Exp/Cntr=0.3,0.1

Type RM Length L Ch R = 1 ,50824   ,417,417,417
BEGIN DESCRIPTION:
EAST SISTER CREEK 97.0
END DESCRIPTION:
XS GIS Cut Line= 3
      2064624.96     13937125.01        2064325.       13937175.
        2064275.       13937175.
#Sta/Elev= 30
  4699.7 1636.44  4702.2 1636.44  4709.8 1634.51  4719.9 1633.09  4727.5 1632.21
  4732.6 1632.13  4740.2 1631.23  4760.5 1627.04  4770.6 1625.48  4780.8 1624.54
  4788.4 1623.45  4793.4 1623.51    4801 1622.66  4841.6 1619.69    4872 1616.62
  4881.9 1615.98    4910 1613.89  4953.1 1612.04  4970.9 1611.74  4975.9 1610.73
  4991.7 1609.79  4991.9 1609.29  4995.4 1609.29  4995.7 1609.79  5001.3 1621.31
  5006.3 1621.31  5033.8 1623.16  5043.8 1624.53  5051.3 1625.29  5053.8 1625.29
#Mann= 4 ,-1 , 0
  4699.7     .07       0  4881.9    .035       0  4991.7    .035       0
  4995.7    .035       0
Bank Sta=4991.7,4995.7
XS Rating Curve= 0 ,0
Exp/Cntr=0.3,0.1

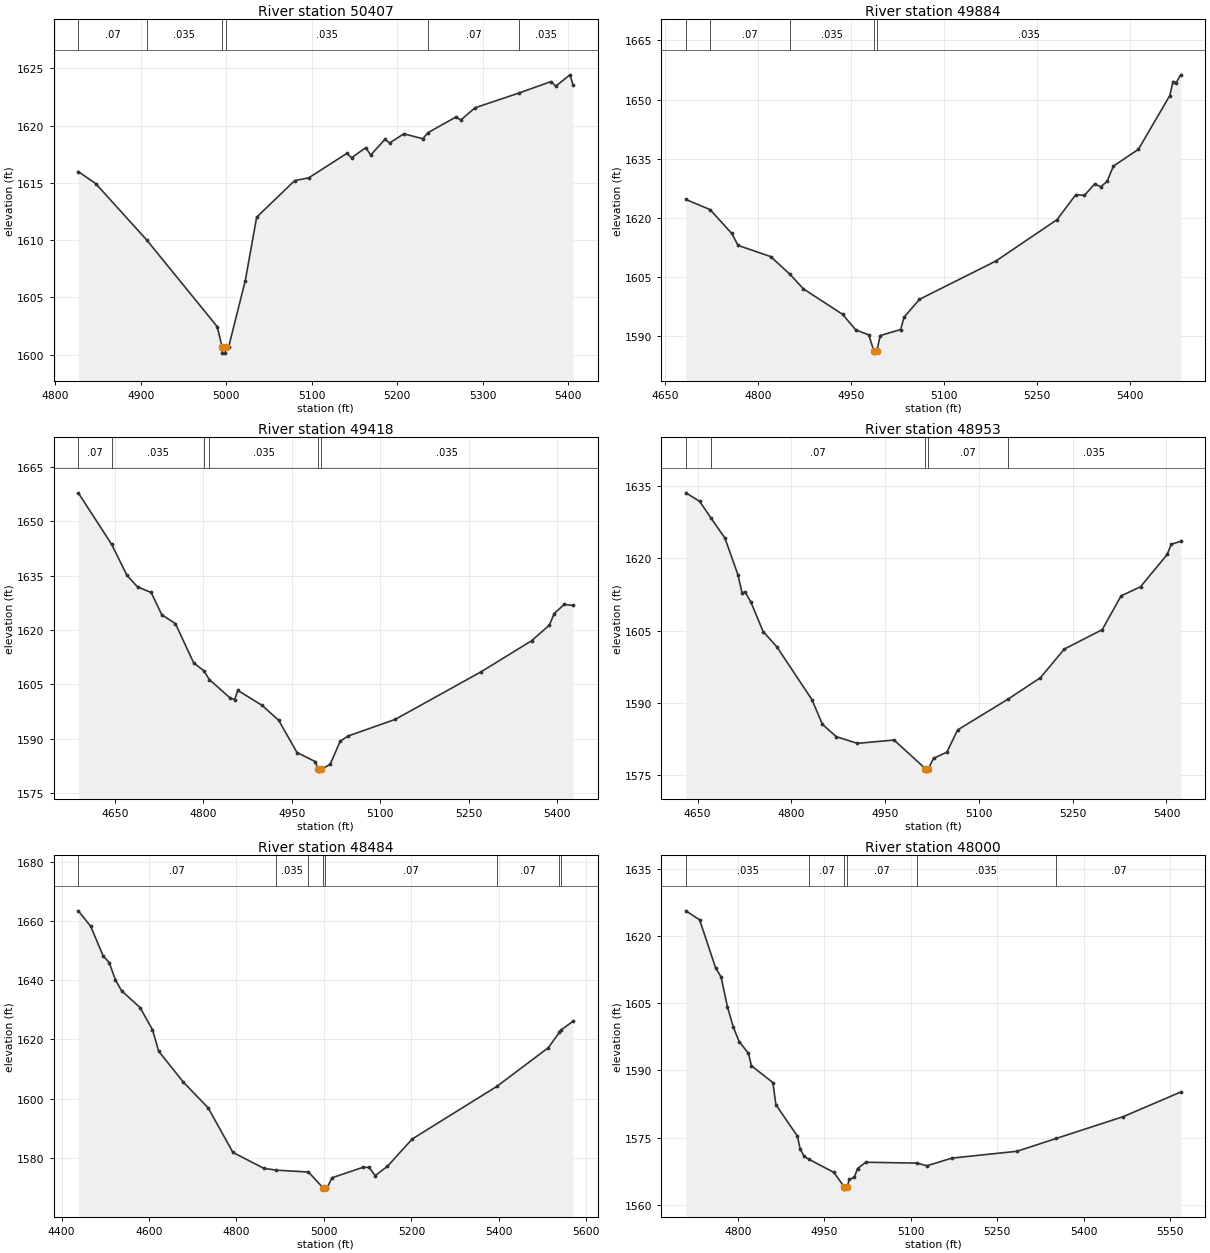
Type RM Length L Ch R = 1 ,50407   ,523,523,523
BEGIN DESCRIPTION:
EAST SISTER CREEK 96.0
END DESCRIPTION:
XS GIS Cut Line= 3
      2064374.97     13936775.01      2064204.61     13936805.16
      2064019.95     13937166.29
#Sta/Elev= 30
    4827 1615.99  4847.3 1614.95  4906.8 1610.04  4989.5 1602.45  4995.3 1600.64
  4995.5 1600.14    4999 1600.14  4999.3 1600.64  5002.7 1600.64  5022.3 1606.47
  5035.6 1612.01    5080  1615.2  5096.6 1615.45  5141.1 1617.58  5146.7  1617.2
  5163.3 1618.09  5168.9 1617.43  5185.5  1618.8  5191.1 1618.49  5207.7 1619.29
  5229.9 1618.86    5236 1619.39  5268.7 1620.76  5274.4  1620.5  5290.9 1621.56
  5342.7 1622.86  5379.8 1623.85  5385.4 1623.45    5402 1624.44  5405.6 1623.56
#Mann= 6 ,-1 , 0
    4827     .07       0  4906.8    .035       0  4995.3    .035       0
  4999.3    .035       0    5236     .07       0  5342.7    .035       0
Bank Sta=4995.3,4999.3
XS Rating Curve= 0 ,0
Exp/Cntr=0.3,0.1

Type RM Length L Ch R = 1 ,49884   ,466,466,466
BEGIN DESCRIPTION:
EAST SISTER CREEK 95.0
END DESCRIPTION:
XS GIS Cut Line= 3
      2064474.97     13936225.01        2064175.       13936325.
      2063697.42     13936391.61
#Sta/Elev= 30
  4683.8 1624.64  4722.8 1622.08  4757.6 1616.05  4768.1 1612.98  4820.8 1610.15
  4851.6 1605.67  4873.5 1601.96  4936.8  1595.5  4957.8 1591.57  4978.9  1590.3
  4987.2 1586.17  4987.6 1585.67  4991.7 1586.17  4997.4 1590.13  5030.3 1591.65
  5035.8 1594.76  5060.6 1599.32  5183.9 1609.02  5282.7 1619.53    5313 1625.88
  5326.9 1625.69  5343.3 1628.57  5353.4 1627.87  5363.5 1629.25  5373.6  1633.1
    5414 1637.37  5464.5 1650.96    5470 1654.56  5475.1 1654.31  5482.2 1656.26
#Mann= 5 ,-1 , 0
  4683.8    .035       0  4722.8     .07       0  4851.6    .035       0
  4987.2    .035       0  4991.7    .035       0
Bank Sta=4987.2,4991.7
XS Rating Curve= 0 ,0
Exp/Cntr=0.3,0.1

Type RM Length L Ch R = 1 ,49418   ,465,465,465
BEGIN DESCRIPTION:
EAST SISTER CREEK 94.0
END DESCRIPTION:
XS GIS Cut Line= 3
      2064624.98       13935775.        2064225.       13935875.
      2063824.99       13936025.
#Sta/Elev= 30
  4587.8  1657.9  4644.5 1643.65  4670.2 1635.16  4688.3 1631.93  4711.5 1630.38
  4729.5 1624.23  4752.7 1621.77  4783.6 1610.95  4800.8 1608.79  4810.2 1606.34
  4845.5 1601.25  4853.2 1600.81  4858.4 1603.36  4899.6 1599.23  4927.9 1595.09
  4958.9  1586.2  4989.8  1583.7  4995.2 1581.56  4995.6 1581.06  4999.8 1581.56
  5015.2 1582.92  5032.1 1589.29  5045.5 1590.75  5125.6 1595.35  5271.5 1608.51
    5357 1617.06  5387.2  1621.4  5395.3 1624.56  5412.2 1627.08  5427.3  1626.8
#Mann= 6 ,-1 , 0
  4587.8     .07       0  4644.5    .035       0  4800.8     .07       0
  4810.2    .035       0  4995.2    .035       0  4999.8    .035       0
Bank Sta=4995.2,4999.8
XS Rating Curve= 0 ,0
Exp/Cntr=0.3,0.1

Type RM Length L Ch R = 1 ,48953   ,469,469,469
BEGIN DESCRIPTION:
EAST SISTER CREEK 93.0
END DESCRIPTION:
XS GIS Cut Line= 3
      2064525.04     13935525.01        2064175.       13935425.
      2063774.95     13935575.02
#Sta/Elev= 30
  4631.4 1633.51  4653.5 1631.73  4671.2 1628.34  4693.8 1624.14  4714.6 1616.54
  4721.1 1612.84  4726.3 1612.94  4735.4 1610.85  4754.9 1604.79    4777  1601.6
  4832.9 1590.69  4849.8 1585.56  4871.9 1583.01  4905.7 1581.63  4964.3 1582.32
  5014.5 1576.38  5014.9 1575.88  5019.1 1576.38  5027.5 1578.54  5048.9 1579.81
  5065.8  1584.4  5146.7  1590.8  5198.4 1595.23  5236.6 1601.16  5297.2 1605.17
  5327.4 1612.17  5358.6 1614.07  5401.3 1620.78  5407.5 1622.84  5422.7 1623.48
#Mann= 5 ,-1 , 0
  4631.4    .035       0  4671.2     .07       0  5014.5     .05       0
  5019.1     .07       0  5146.7    .035       0
Bank Sta=5014.5,5019.1
XS Rating Curve= 0 ,0
Exp/Cntr=0.3,0.1

Type RM Length L Ch R = 1 ,48484   ,484,484,484
BEGIN DESCRIPTION:
EAST SISTER CREEK 92.0
END DESCRIPTION:
XS GIS Cut Line= 3
      2064675.03     13935425.03        2064275.       13935025.
      2063875.01     13934625.01
#Sta/Elev= 30
  4438.2  1663.4  4466.5 1658.21  4494.8 1648.27  4508.9 1645.95  4523.1 1640.12
  4537.2 1636.44  4579.7 1630.74  4607.9 1623.28  4622.1 1616.04  4678.7 1605.59
  4735.2 1596.94  4791.8 1581.92  4862.5 1576.54  4891.1 1575.93  4964.5  1575.3
  4997.6 1570.03  4998.1 1569.53  5003.1 1570.03  5007.5 1570.03  5018.1 1573.35
  5088.8 1576.86  5102.9 1576.88  5117.1 1574.08  5145.3 1577.24  5201.9 1586.45
  5395.1 1604.16    5513 1617.22  5538.6 1622.47  5541.7 1623.14  5569.6 1626.16
#Mann= 8 ,-1 , 0
  4438.2     .07       0  4891.1    .035       0  4964.5     .07       0
  4997.6    .035       0  5003.1     .07       0  5395.1     .07       0
  5538.6    .035       0  5541.7     .07       0
Bank Sta=4997.6,5003.1
XS Rating Curve= 0 ,0
Exp/Cntr=0.3,0.1

Type RM Length L Ch R = 1 ,48000   ,404,404,404
BEGIN DESCRIPTION:
EAST SISTER CREEK 91.0
END DESCRIPTION:
XS GIS Cut Line= 3
      2064725.01     13935125.04      2064658.59     13934842.65
      2064224.98     13934474.98
#Sta/Elev= 30
  4709.9 1625.61  4733.7  1623.6  4761.3 1612.93    4771 1610.84  4781.9 1604.23
  4792.1 1599.66  4802.4 1596.41  4818.5 1593.78  4823.6 1591.03  4860.9 1587.28
    4866 1582.35  4903.2 1575.36  4908.4 1572.39  4915.4 1570.79  4923.8 1570.14
  4966.8 1567.22  4984.6    1564    4985  1563.5  4990.1    1564  4993.1 1565.67
  5002.1 1566.11  5007.7 1568.09    5022  1569.5  5110.2 1569.31  5128.5 1568.72
  5171.4 1570.42  5284.5 1571.95  5352.6 1574.81  5469.1 1579.69  5568.5 1585.17
#Mann= 6 ,-1 , 0
  4709.9    .035       0  4923.8     .07       0  4984.6     .05       0
  4990.1     .07       0  5110.2    .035       0  5352.6     .07       0
Bank Sta=4984.6,4990.1
XS Rating Curve= 0 ,0
Exp/Cntr=0.3,0.1

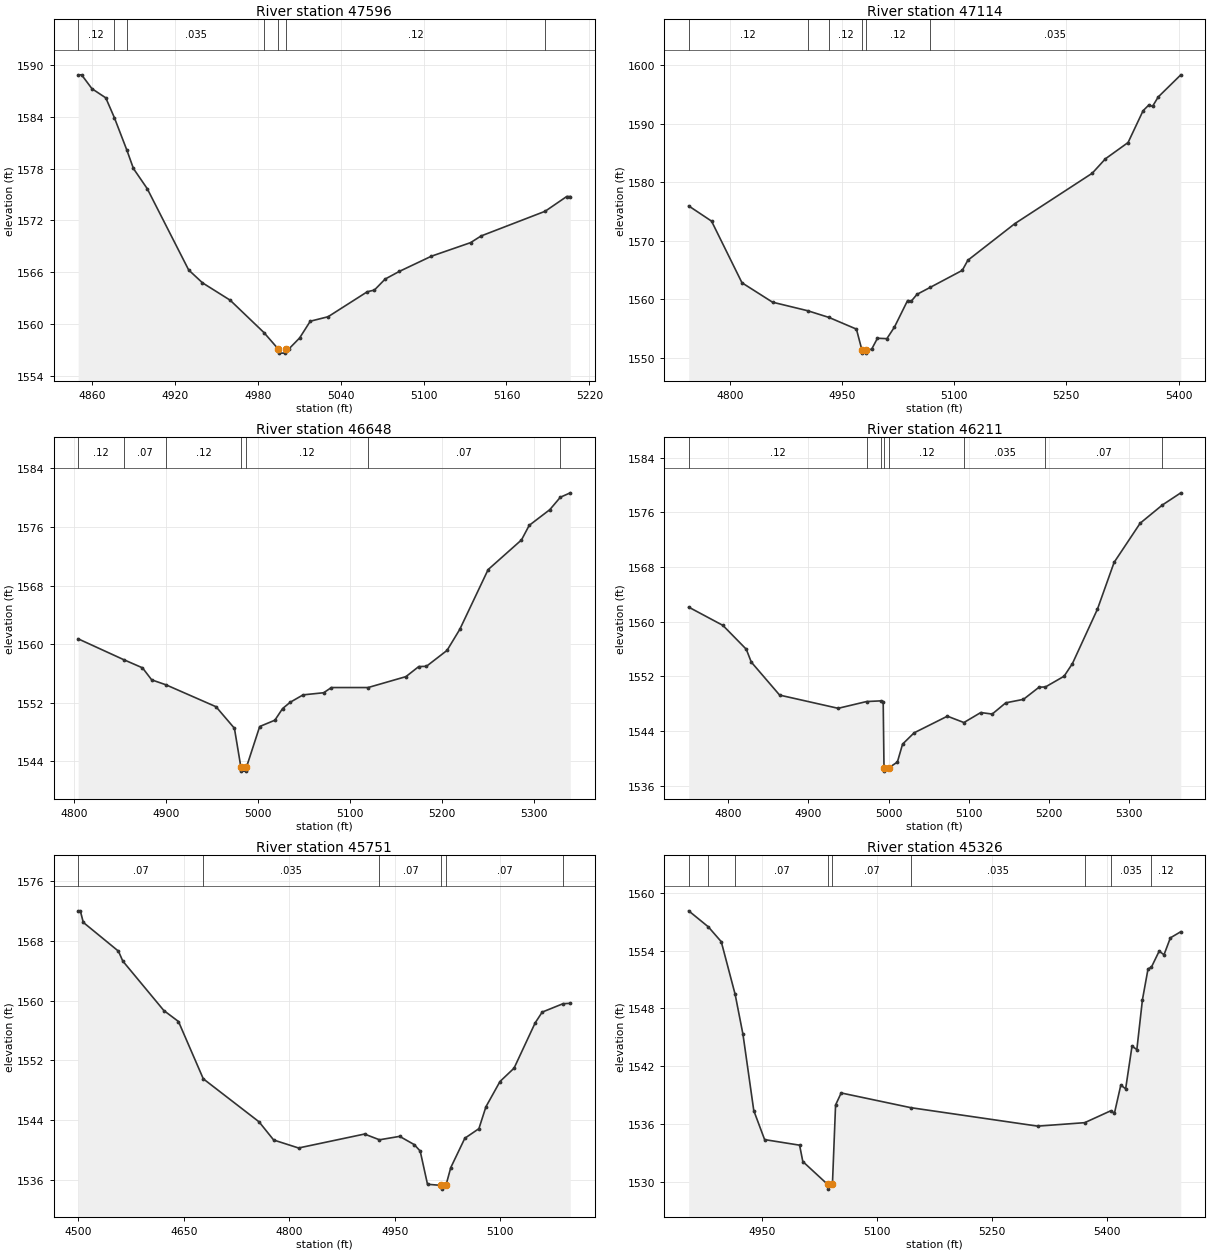
Type RM Length L Ch R = 1 ,47596   ,482,482,482
BEGIN DESCRIPTION:
EAST SISTER CREEK 90.0
END DESCRIPTION:
XS GIS Cut Line= 3
        2064725.       13934475.        2064575.       13934475.
      2064374.95     13934525.01
#Sta/Elev= 30
    4850 1588.89  4852.5 1588.89    4860 1587.28    4870 1586.22  4876.2 1583.93
  4885.3 1580.14    4890 1578.03    4900 1575.69    4930 1566.26    4940 1564.77
    4960 1562.76  4984.5    1559  4994.7 1557.12  4995.1 1556.62  4999.8 1556.62
  5000.3 1557.12  5002.6 1557.12  5010.3 1558.38    5018 1560.32  5030.9 1560.84
  5059.3 1563.74  5064.4 1563.93  5072.2 1565.21  5082.5  1566.1  5105.7 1567.86
    5134 1569.43  5141.7 1570.21    5188 1573.07  5203.6 1574.78  5206.2 1574.78
#Mann= 7 ,-1 , 0
    4850     .12       0  4876.2     .07       0  4885.3    .035       0
  4984.5     .12       0  4994.7     .05       0  5000.3     .12       0
    5188    .035       0
Bank Sta=4994.7,5000.3
XS Rating Curve= 0 ,0
Exp/Cntr=0.3,0.1

Type RM Length L Ch R = 1 ,47114   ,466,466,466
BEGIN DESCRIPTION:
EAST SISTER CREEK 89.0
END DESCRIPTION:
XS GIS Cut Line= 3
      2064724.96     13934074.99        2064475.       13934025.
      2064075.02       13934075.
#Sta/Elev= 30
    4745 1575.95  4775.6 1573.35  4816.3 1562.82  4857.1 1559.51  4904.1 1558.05
  4932.7  1556.9  4969.3 1554.91  4976.7 1551.31  4977.2 1550.81  4981.9 1550.81
  4982.3 1551.31  4989.7 1551.49  4997.4 1553.35    5010 1553.28  5020.1 1555.25
  5037.7 1559.79  5042.7 1559.69  5050.3 1560.85  5067.7 1562.02  5110.8 1564.94
  5118.3 1566.67  5181.3 1572.94  5284.6 1581.53  5302.2 1583.99  5332.5 1586.77
  5352.6 1592.21  5360.2 1593.17  5365.2 1592.95  5372.8 1594.55    5403 1598.33
#Mann= 6 ,-1 , 0
    4745     .12       0  4904.1    .035       0  4932.7     .12       0
  4976.7     .05       0  4982.3     .12       0  5067.7    .035       0
Bank Sta=4976.7,4982.3
XS Rating Curve= 0 ,0
Exp/Cntr=0.3,0.1

Type RM Length L Ch R = 1 ,46648   ,437,437,437
BEGIN DESCRIPTION:
EAST SISTER CREEK 88.0
END DESCRIPTION:
XS GIS Cut Line= 3
      2064625.03       13933575.        2064425.       13933575.
      2064125.03     13933724.98
#Sta/Elev= 30
  4804.5 1560.73    4854 1557.89  4874.5 1556.77  4884.5 1555.13  4900.1 1554.45
  4954.5 1551.46  4974.5 1548.52  4981.6 1543.17  4982.1 1542.67    4987 1542.67
  4987.5 1543.17    5002 1548.76  5018.5 1549.62  5026.9 1551.21  5035.3 1552.08
  5049.2 1553.08  5071.6 1553.37    5080 1554.08  5119.9 1554.08  5161.1 1555.57
    5175 1556.94  5183.4 1556.98  5205.8 1559.15  5219.7 1562.03  5250.5 1570.18
  5286.8 1574.23  5295.2 1576.22  5317.6 1578.36  5329.1 1580.06  5339.9 1580.66
#Mann= 7 ,-1 , 0
  4804.5     .12       0    4854     .07       0  4900.1     .12       0
  4981.6     .05       0  4987.5     .12       0  5119.9     .07       0
  5329.1    .035       0
Bank Sta=4981.6,4987.5
XS Rating Curve= 0 ,0
Exp/Cntr=0.3,0.1

Type RM Length L Ch R = 1 ,46211   ,460,460,460
BEGIN DESCRIPTION:
EAST SISTER CREEK 87.0
END DESCRIPTION:
XS GIS Cut Line= 3
        2064725.       13933325.        2064525.       13933175.
      2064175.01       13933075.
#Sta/Elev= 30
  4750.5 1562.14  4793.2 1559.47  4822.4 1555.98  4828.6 1554.11    4864 1549.28
    4937 1547.35  4972.5 1548.34  4990.8 1548.44  4993.2 1548.33  4994.2 1538.67
  4994.7 1538.17  5000.5 1538.67  5010.9  1539.5  5017.4 1542.12  5031.7 1543.76
  5073.3  1546.2  5093.9 1545.27  5114.9 1546.73  5129.2 1546.51  5146.1 1548.15
  5168.2 1548.66  5187.7 1550.44  5195.6 1550.47  5218.9 1552.04  5229.3 1553.89
  5260.5 1561.84  5281.3 1568.68  5313.8  1574.4  5341.6 1577.07  5364.5 1578.84
#Mann= 8 ,-1 , 0
  4750.5     .12       0  4972.5     .07       0  4990.8     .12       0
  4994.2     .05       0  5000.5     .12       0  5093.9    .035       0
  5195.6     .07       0  5341.6    .035       0
Bank Sta=4994.2,5000.5
XS Rating Curve= 0 ,0
Exp/Cntr=0.3,0.1

Type RM Length L Ch R = 1 ,45751   ,425,425,425
BEGIN DESCRIPTION:
EAST SISTER CREEK 86.0
END DESCRIPTION:
XS GIS Cut Line= 3
        2065075.       13933075.        2064675.       13932775.
      2064474.99       13932775.
#Sta/Elev= 30
  4499.6 1572.05  4502.7 1572.05  4506.9  1570.5  4556.9 1566.64  4563.1 1565.31
  4621.5 1558.67  4642.3  1557.2  4677.6 1549.51  4756.9 1543.74  4777.7  1541.3
  4813.1 1540.23  4906.9  1542.1  4928.2 1541.33  4956.9 1541.79  4977.7 1540.68
  4986.1 1539.82  4996.5 1535.36  5016.4 1535.21  5016.9 1534.71  5022.7 1535.21
  5029.6  1537.6  5049.6 1541.54  5069.6 1542.82  5079.6 1545.76  5099.6 1549.15
  5119.6 1550.94  5149.6 1557.01  5159.6 1558.46  5189.3 1559.59  5199.6 1559.64
#Mann= 6 ,-1 , 0
  4499.6     .07       0  4677.6    .035       0  4928.2     .07       0
  5016.4     .05       0  5022.7     .07       0  5189.3    .035       0
Bank Sta=5016.4,5022.7
XS Rating Curve= 0 ,0
Exp/Cntr=0.3,0.1

Type RM Length L Ch R = 1 ,45326   ,445,445,445
BEGIN DESCRIPTION:
EAST SISTER CREEK 85.0
END DESCRIPTION:
XS GIS Cut Line= 3
      2065125.03     13932775.03        2065025.       13932675.
      2064624.97     13932374.98
#Sta/Elev= 30
  4854.6 1558.15  4880.3 1556.48  4897.1 1554.94  4915.2 1549.46  4925.4  1545.3
  4939.5 1537.37  4953.6 1534.36  4999.2 1533.78  5003.4 1532.08  5035.6 1529.71
  5036.1 1529.21    5042 1529.71  5046.1 1537.96  5053.4 1539.21  5144.2 1537.68
  5309.6 1535.76  5370.8 1536.12  5404.6 1537.35  5409.6 1537.11  5417.9 1540.03
  5424.2 1539.64  5432.5 1544.08  5438.8 1543.72  5446.1 1548.91  5453.4 1552.12
  5457.7 1552.28  5467.9 1553.96  5474.2 1553.58  5482.5 1555.34  5496.1 1555.98
#Mann= 9 ,-1 , 0
  4854.6     .07       0  4880.3    .035       0  4915.2     .07       0
  5035.6     .05       0    5042     .07       0  5144.2    .035       0
  5370.8     .07       0  5404.6    .035       0  5457.7     .12       0
Bank Sta=5035.6,5042
XS Rating Curve= 0 ,0
Exp/Cntr=0.3,0.1

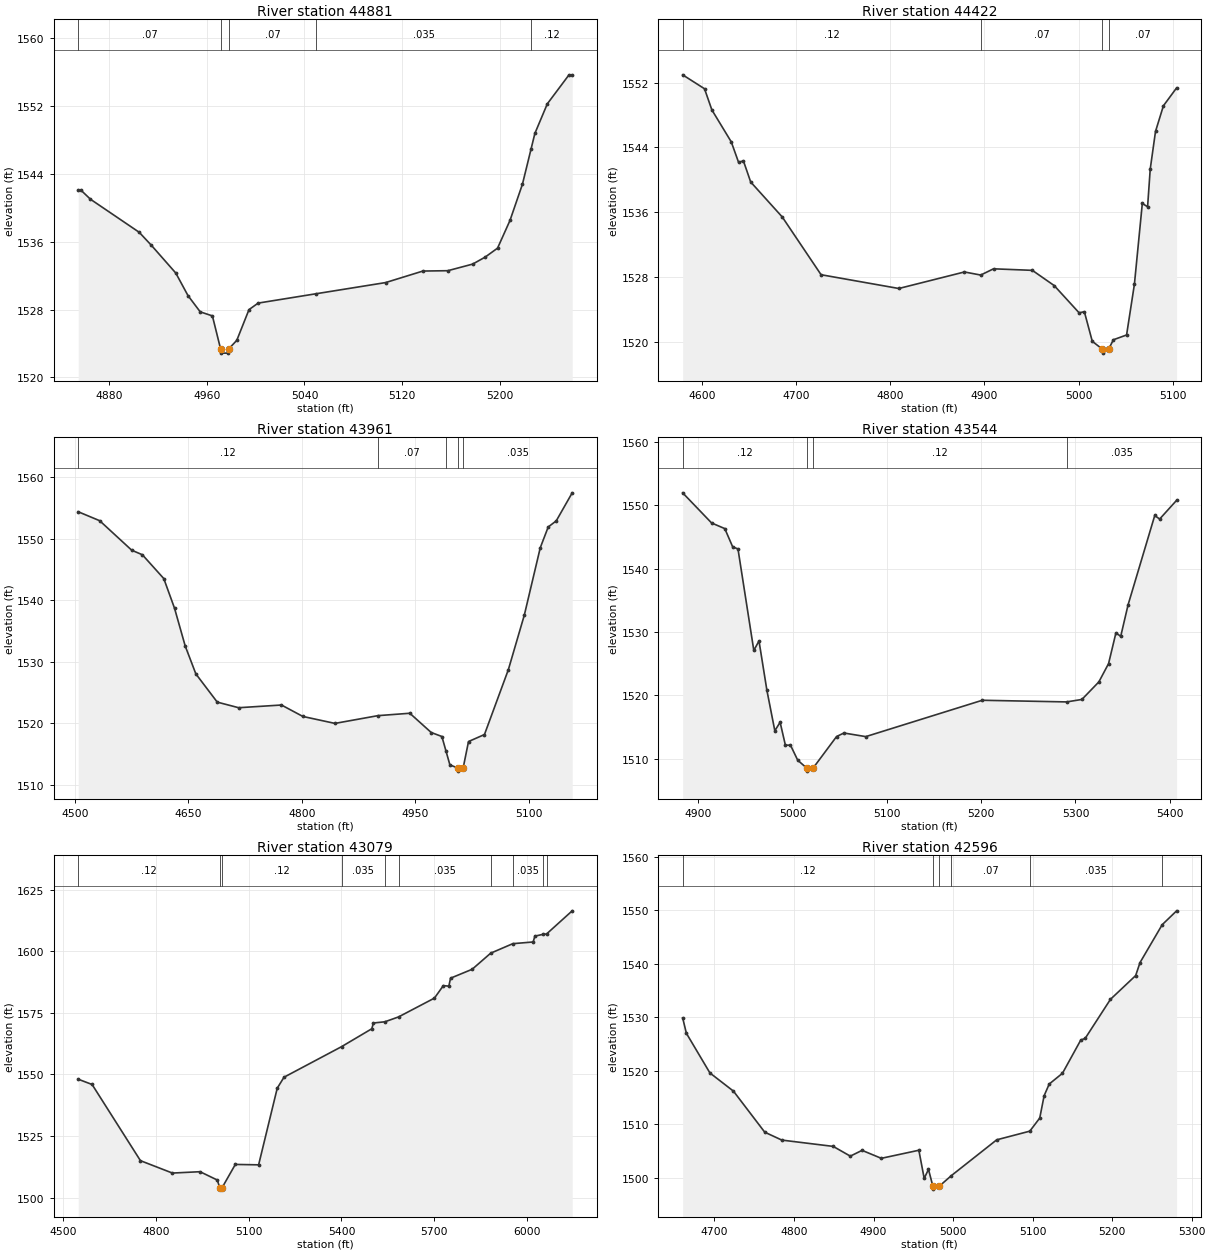
Type RM Length L Ch R = 1 ,44881   ,459,459,459
BEGIN DESCRIPTION:
EAST SISTER CREEK 84.0
END DESCRIPTION:
XS GIS Cut Line= 3
      2065025.04       13932275.        2064875.       13932275.
      2064624.99       13932325.
#Sta/Elev= 30
  4854.5 1542.04    4857 1542.04  4864.5 1541.01  4904.5 1537.11  4914.5 1535.57
  4934.5  1532.3  4944.5 1529.64  4954.5 1527.73  4964.5 1527.25  4971.2 1523.36
  4971.7 1522.86  4977.4 1522.86  4977.9 1523.36  4984.5 1524.37  4994.5 1527.99
    5002 1528.76  5049.4 1529.86  5106.5 1531.18  5137.1 1532.54  5157.5 1532.58
  5177.9 1533.36  5188.1 1534.18  5198.3 1535.24  5208.5 1538.51  5218.7 1542.78
  5225.7 1546.89  5228.9 1548.77  5239.1 1552.26  5256.9 1555.68  5259.5 1555.68
#Mann= 5 ,-1 , 0
  4854.5     .07       0  4971.2     .05       0  4977.9     .07       0
  5049.4    .035       0  5225.7     .12       0
Bank Sta=4971.2,4977.9
XS Rating Curve= 0 ,0
Exp/Cntr=0.3,0.1

Type RM Length L Ch R = 1 ,44422   ,461,461,461
BEGIN DESCRIPTION:
EAST SISTER CREEK 83.0
END DESCRIPTION:
XS GIS Cut Line= 3
      2065075.05     13932025.01        2064675.       13931925.
      2064574.97     13931874.98
#Sta/Elev= 30
  4579.8 1552.97    4603 1551.25  4610.8 1548.64  4631.4 1544.69  4639.1 1542.18
  4644.3 1542.34    4652 1539.74  4685.5 1535.42  4726.7 1528.29  4809.2 1526.59
  4878.8 1528.63  4896.1 1528.25  4909.7 1529.02  4950.9 1528.83  4974.1 1526.95
  5000.5 1523.59  5006.1 1523.72  5014.5 1520.07  5025.1 1519.11  5025.6 1518.61
  5031.9 1519.11  5036.9 1520.26  5050.9 1520.85  5059.2  1527.1  5067.6 1537.09
  5073.2 1536.68    5076 1541.33  5081.6 1545.98    5090 1549.15    5104 1551.36
#Mann= 4 ,-1 , 0
  4579.8     .12       0  4896.1     .07       0  5025.1     .05       0
  5031.9     .07       0
Bank Sta=5025.1,5031.9
XS Rating Curve= 0 ,0
Exp/Cntr=0.3,0.1

Type RM Length L Ch R = 1 ,43961   ,417,417,417
BEGIN DESCRIPTION:
EAST SISTER CREEK 82.0
END DESCRIPTION:
XS GIS Cut Line= 3
      2065124.98     13931874.98        2064775.       13931525.
      2064624.96     13931474.99
#Sta/Elev= 30
  4504.4 1554.42  4532.7 1552.97  4575.1 1548.17  4589.2 1547.43  4617.5 1543.56
  4631.7 1538.74  4645.8 1532.61  4659.9 1528.06  4688.2 1523.47  4716.5 1522.56
  4773.1    1523  4801.4 1521.14  4843.8 1520.01  4900.6 1521.27  4942.8 1521.66
  4971.1 1518.53  4985.2 1517.88  4990.6 1515.53  4995.8 1513.26  5006.5 1512.75
    5007 1512.25  5013.3 1512.75  5020.4 1517.06  5041.5  1518.2  5073.1 1528.75
  5094.2 1537.62  5115.3 1548.58  5125.8 1551.95  5136.4 1552.94  5157.5  1557.5
#Mann= 5 ,-1 , 0
  4504.4     .12       0  4900.6     .07       0  4990.6    .035       0
  5006.5    .035       0  5013.3    .035       0
Bank Sta=5006.5,5013.3
XS Rating Curve= 0 ,0
Exp/Cntr=0.3,0.1

Type RM Length L Ch R = 1 ,43544   ,465,465,465
BEGIN DESCRIPTION:
EAST SISTER CREEK 81.0
END DESCRIPTION:
XS GIS Cut Line= 3
      2065174.99     13931424.99        2065075.       13931375.
        2064675.       13931275.
#Sta/Elev= 30
  4883.2 1551.99  4913.9 1547.23  4927.9 1546.34  4936.3 1543.45  4941.9 1543.13
  4958.7  1527.1  4964.2  1528.6  4972.6 1520.79    4981 1514.41  4986.6 1515.76
  4992.2 1512.14  4997.6 1512.14  5005.3 1509.76  5014.7 1508.54  5015.2 1508.04
  5021.7 1508.54  5046.5  1513.5  5054.3 1514.06  5077.5 1513.49  5201.1 1519.23
  5290.6 1518.97  5306.8 1519.36  5324.8 1522.13  5335.1 1525.02  5342.9 1529.87
    5348 1529.33  5355.8  1534.3  5384.1 1548.41  5389.3 1547.85  5407.3 1550.81
#Mann= 4 ,-1 , 0
  4883.2     .12       0  5014.7     .05       0  5021.7     .12       0
  5290.6    .035       0
Bank Sta=5014.7,5021.7
XS Rating Curve= 0 ,0
Exp/Cntr=0.3,0.1

Type RM Length L Ch R = 1 ,43079   ,483,483,483
BEGIN DESCRIPTION:
EAST SISTER CREEK 80.0
END DESCRIPTION:
XS GIS Cut Line= 3
      2065275.04     13931175.02        2064875.       13930975.
      2063821.89     13931439.87
#Sta/Elev= 30
  4548.2 1548.05    4593 1545.92  4749.5    1515  4852.9 1509.97  4942.3 1510.52
  4998.2 1507.14  5006.3 1503.95  5006.8 1503.45  5013.3 1503.95  5056.5 1513.47
  5131.9 1513.31  5192.2 1544.43  5214.1 1548.87  5400.2 1561.26    5498 1568.52
  5503.4 1570.87  5540.4 1571.36  5584.6 1573.33  5700.8 1580.97  5729.6 1586.03
  5747.5 1585.83  5752.9 1589.05  5822.9 1592.67  5882.8  1599.2  5954.4 1603.06
  6020.3 1603.75  6025.8 1606.12  6052.2 1606.85  6063.6 1606.99  6146.6 1616.39
#Mann= 10 ,-1 , 0
  4548.2     .12       0  5006.3     .05       0  5013.3     .12       0
  5400.2    .035       0  5540.4     .07       0  5584.6    .035       0
  5882.8     .07       0  5954.4    .035       0  6052.2     .07       0
  6063.6    .035       0
Bank Sta=5006.3,5013.3
XS Rating Curve= 0 ,0
Exp/Cntr=0.3,0.1

Type RM Length L Ch R = 1 ,42596   ,411,411,411
BEGIN DESCRIPTION:
EAST SISTER CREEK 79.0
END DESCRIPTION:
XS GIS Cut Line= 3
      2065193.12     13931090.82      2065064.94     13930769.74
       2064950.3     13930519.36
#Sta/Elev= 30
    4660 1529.89  4664.7 1527.01  4694.3 1519.59  4723.9 1516.19  4763.2 1508.52
  4784.7 1507.04  4849.3 1505.86  4870.8 1504.04  4885.6 1505.12  4909.8 1503.63
    4957 1505.14  4963.7 1499.88  4969.1 1501.56  4974.7 1498.37  4975.2 1497.87
  4982.3 1498.37  4997.9  1500.4  5054.9 1507.09  5096.5 1508.71    5109 1511.16
  5114.5 1515.33  5120.9 1517.52  5137.6 1519.54  5160.6 1525.75  5166.1 1526.05
  5197.9 1533.36  5229.6  1537.8  5235.1 1540.24    5263 1547.32  5281.1 1549.91
#Mann= 6 ,-1 , 0
    4660     .12       0  4974.7     .05       0  4982.3     .12       0
  4997.9     .07       0  5096.5    .035       0    5263     .07       0
Bank Sta=4974.7,4982.3
XS Rating Curve= 0 ,0
Exp/Cntr=0.3,0.1