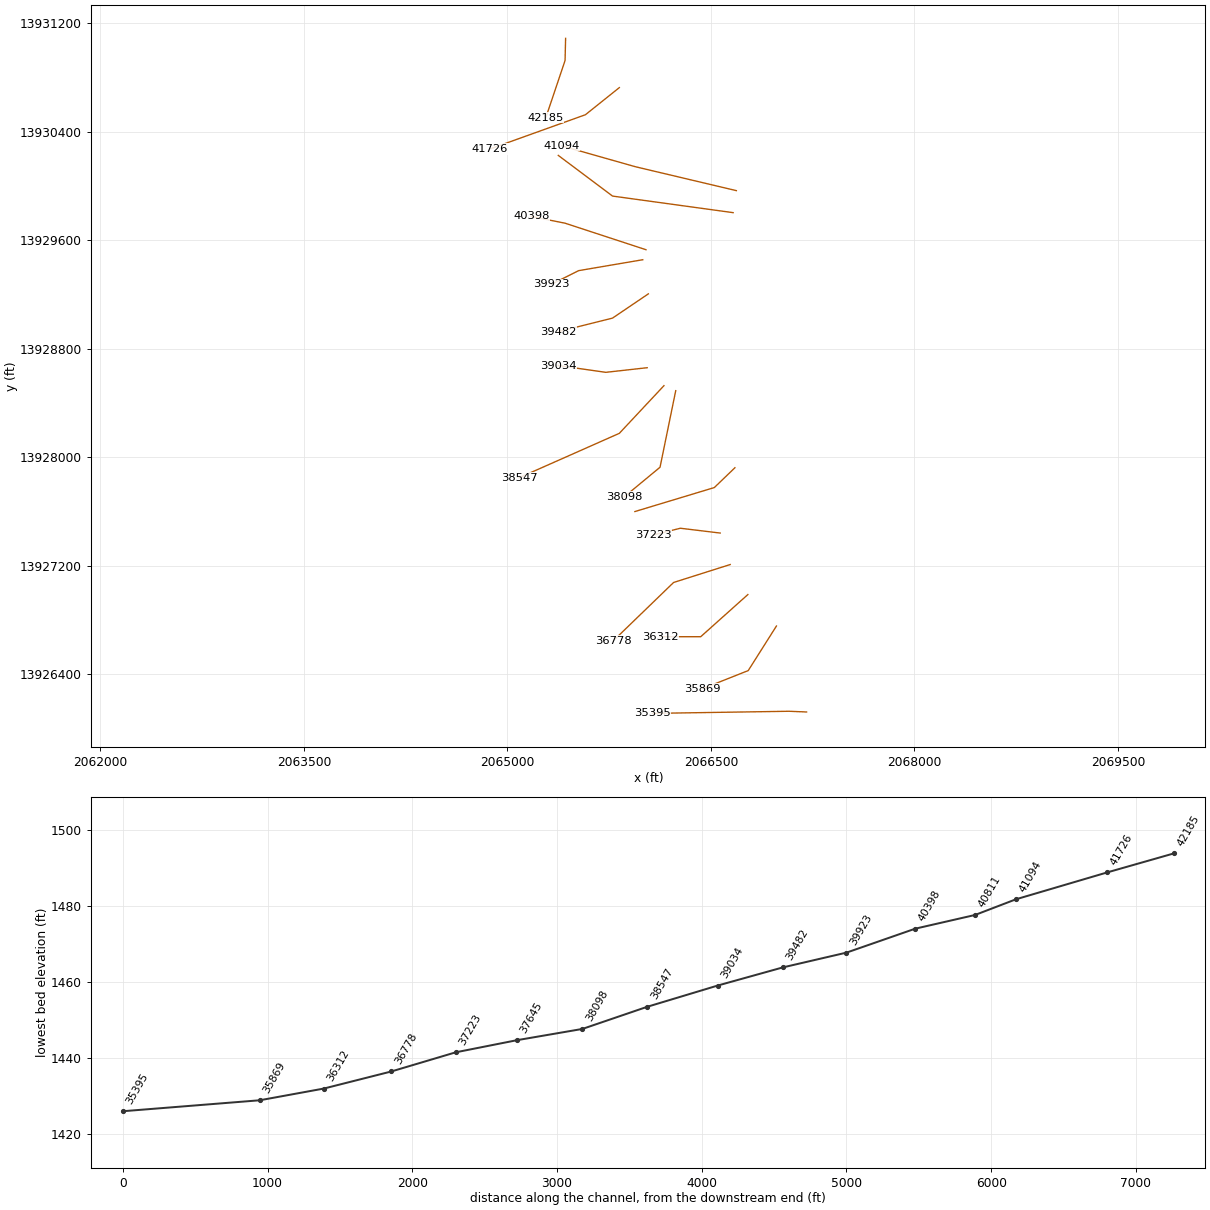
HEC-RAS study EAST SISTER CREEK.prj: EAST SISTER CREEK Base Level Engineering

--- EAST SISTER CREEK.g01 (geometry) --- (continued)

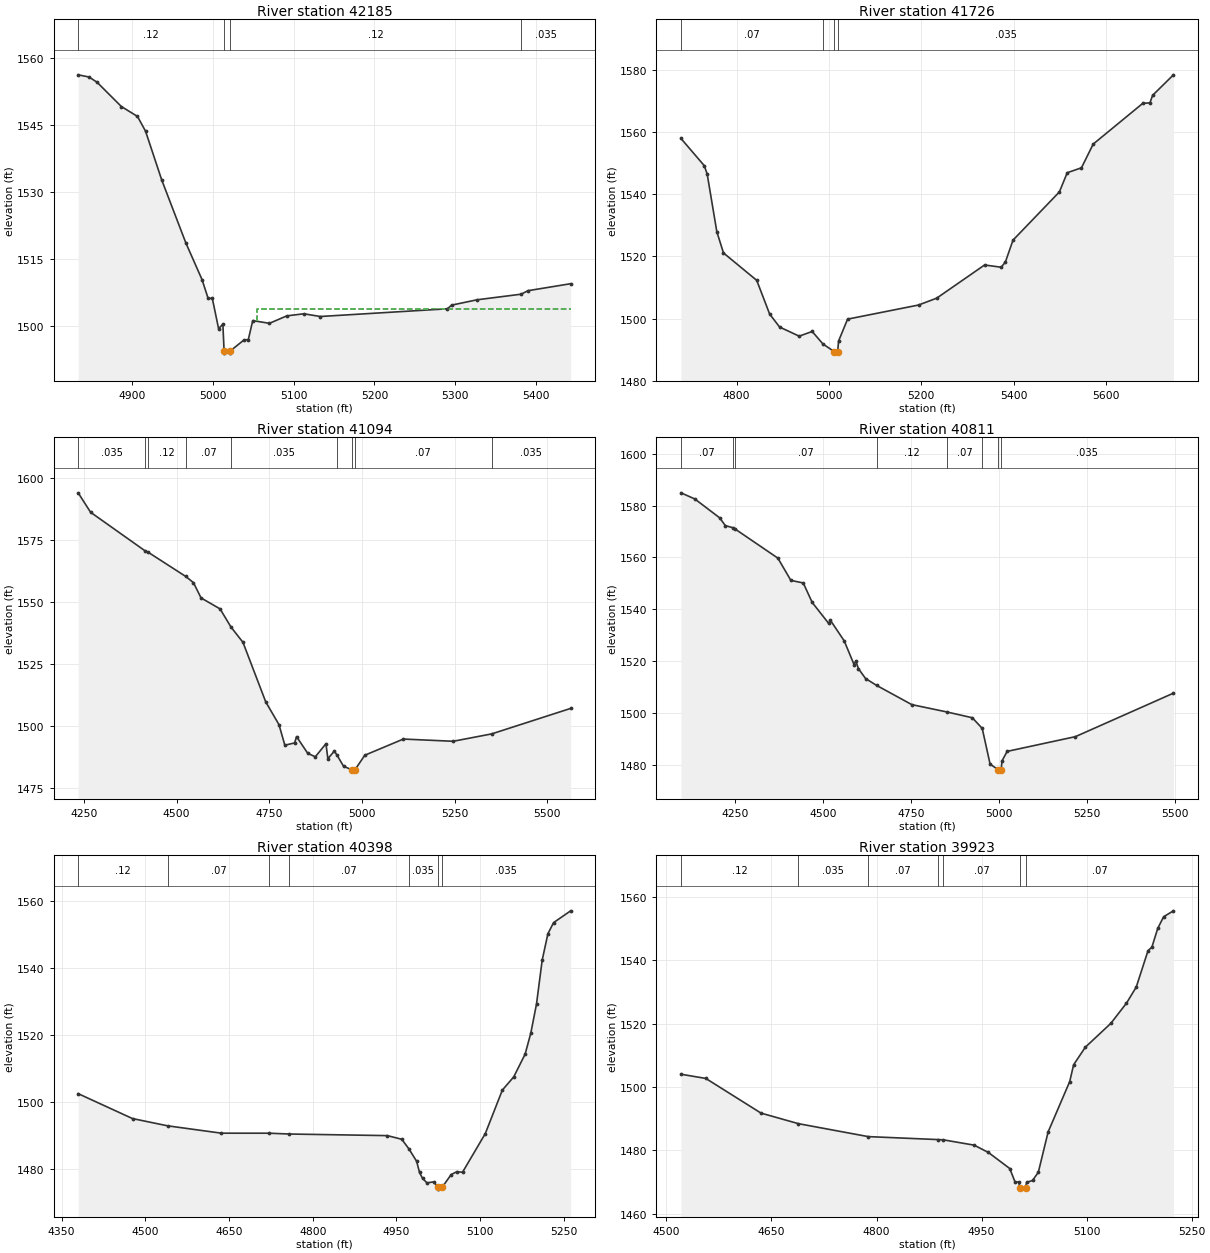
Type RM Length L Ch R = 1 ,42185   ,459,459,459
BEGIN DESCRIPTION:
EAST SISTER CREEK 78.0
END DESCRIPTION:
XS GIS Cut Line= 3
      2065428.96     13931088.49        2065425.       13930925.
      2065282.45      13930501.7
#Sta/Elev= 30
  4832.9 1556.32  4846.4 1555.83  4856.4 1554.64  4886.4 1549.21  4906.4 1546.98
  4916.4 1543.67  4936.4 1532.74  4966.4 1518.56  4986.4 1510.35  4993.9 1506.16
  4999.1 1506.16  5006.9 1499.35  5012.2 1500.36  5013.7 1494.36  5014.2 1493.86
  5020.9 1493.86  5021.4 1494.36  5038.4 1496.82  5043.7 1496.89  5049.2 1501.16
  5069.9 1500.55  5091.4 1502.22  5112.5 1502.69  5132.9 1502.08  5290.4 1503.81
  5295.6 1504.63  5327.1 1505.83  5381.9 1507.09  5390.1 1507.87  5443.1 1509.44
#Mann= 4 ,-1 , 0
  4832.9     .12       0  5013.7     .05       0  5021.4     .12       0
  5381.9    .035       0
#XS Ineff= 2 , 0
       0                 5054.87       0  1503.8
Permanent Ineff=
       F       F
Bank Sta=5013.7,5021.4
XS Rating Curve= 0 ,0
Exp/Cntr=0.3,0.1

Type RM Length L Ch R = 1 ,41726   ,632,632,632
BEGIN DESCRIPTION:
EAST SISTER CREEK 77.0
END DESCRIPTION:
XS GIS Cut Line= 3
      2065825.01     13930725.01        2065575.       13930525.
      2064872.52     13930272.64
#Sta/Elev= 30
  4679.7 1557.96  4730.1 1549.21  4736.5 1546.51  4757.4 1527.93  4771.8 1521.11
  4843.8 1512.29  4871.8 1501.44  4893.4 1497.26  4935.8 1494.33  4963.9 1495.84
  4987.2 1491.82  5011.4 1489.37  5011.9 1488.87  5019.1 1489.37  5021.1 1492.77
  5040.6 1499.81  5194.3 1504.35  5233.6 1506.56  5337.3 1517.24  5373.3 1516.51
  5382.4 1518.21  5398.8 1525.22  5499.3 1540.75  5516.3 1546.93  5547.1 1548.51
  5572.5 1556.14  5679.9 1569.25  5695.4 1569.41  5701.2 1571.83  5746.3 1578.43
#Mann= 4 ,-1 , 0
  4679.7     .07       0  4987.2    .035       0  5011.4    .035       0
  5019.1    .035       0
Bank Sta=5011.4,5019.1
XS Rating Curve= 0 ,0
Exp/Cntr=0.3,0.1

Type RM Length L Ch R = 1 ,41094   ,283,283,283
BEGIN DESCRIPTION:
EAST SISTER CREEK 76.0
END DESCRIPTION:
XS GIS Cut Line= 3
      2066687.58     13929965.18       2065942.5      13930141.7
      2065400.87     13930295.34
#Sta/Elev= 30
  4234.3 1593.95  4267.8 1586.12  4415.5 1570.49  4422.6 1570.05  4524.7 1560.23
  4545.3 1557.75  4565.8 1551.59  4617.2 1547.16  4646.7 1539.83  4678.9 1533.69
  4740.5 1509.63  4776.1 1500.51  4791.9 1492.22  4818.3 1493.14  4823.5 1495.67
  4853.6 1488.97  4874.1 1487.54  4902.8 1492.83    4908 1486.78  4925.5 1489.86
  4932.9 1488.14  4950.2 1483.77  4972.9 1482.27  4973.4 1481.77  4980.8 1482.27
  5007.8 1488.19  5111.7  1494.7    5246  1493.8    5350 1496.78    5563 1507.05
#Mann= 9 ,-1 , 0
  4234.3    .035       0  4415.5     .07       0  4422.6     .12       0
  4524.7     .07       0  4646.7    .035       0  4932.9     .07       0
  4972.9     .05       0  4980.8     .07       0    5350    .035       0
Bank Sta=4972.9,4980.8
XS Rating Curve= 0 ,0
Exp/Cntr=0.3,0.1

Type RM Length L Ch R = 1 ,40811   ,413,413,413
BEGIN DESCRIPTION:
EAST SISTER CREEK 75.0
END DESCRIPTION:
XS GIS Cut Line= 3
       2066663.9     13929802.72        2065775.       13929925.
      2065374.98     13930225.02
#Sta/Elev= 30
  4097.5 1584.93  4136.8 1582.57  4207.4 1575.28  4223.4 1572.29    4244 1571.51
  4250.6 1571.03  4372.5 1559.75  4409.3 1551.17  4444.5 1550.18  4469.9 1542.66
  4516.6 1534.59  4521.6 1535.78  4560.7 1527.85  4588.6 1518.71  4593.6  1520.1
  4601.1 1517.12  4621.3 1513.33  4652.5 1510.69  4752.5 1503.27  4852.4 1500.43
  4924.1 1498.21  4952.3  1494.1  4974.6 1480.34  4998.1 1478.13  4998.6 1477.63
    5006 1478.13  5008.3 1481.54  5022.9 1485.24  5216.6 1490.92  5494.8 1507.69
#Mann= 8 ,-1 , 0
  4097.5     .07       0    4244    .035       0  4250.6     .07       0
  4652.5     .12       0  4852.4     .07       0  4952.3    .035       0
  4998.1    .035       0    5006    .035       0
Bank Sta=4998.1,5006
XS Rating Curve= 0 ,0
Exp/Cntr=0.3,0.1

Type RM Length L Ch R = 1 ,40398   ,475,475,475
BEGIN DESCRIPTION:
EAST SISTER CREEK 74.0
END DESCRIPTION:
XS GIS Cut Line= 3
      2066021.54     13929529.28        2065425.       13929725.
      2065174.98       13929775.
#Sta/Elev= 30
  4379.6 1502.52    4477 1495.08  4539.8 1492.92  4636.2 1490.72  4722.5 1490.71
  4757.6 1490.47  4933.8 1489.99  4959.7  1488.9  4972.4 1486.05  4986.3 1482.34
  4991.5 1478.99  4996.9 1477.25  5004.8 1475.89  5017.6  1476.2  5023.8 1474.52
  5024.3 1474.02  5031.8 1474.52  5048.2 1478.36  5058.4 1479.23  5068.6 1479.06
  5109.4  1490.6    5140 1503.59  5160.4 1507.53  5180.8 1514.32    5191  1520.6
  5201.2 1529.28  5211.4 1542.39  5221.6 1550.24  5231.8 1553.57  5262.4 1557.09
#Mann= 7 ,-1 , 0
  4379.6     .12       0  4539.8     .07       0  4722.5    .035       0
  4757.6     .07       0  4972.4    .035       0  5023.8    .035       0
  5031.8    .035       0
Bank Sta=5023.8,5031.8
XS Rating Curve= 0 ,0
Exp/Cntr=0.3,0.1

Type RM Length L Ch R = 1 ,39923   ,441,441,441
BEGIN DESCRIPTION:
EAST SISTER CREEK 73.0
END DESCRIPTION:
XS GIS Cut Line= 3
      2065997.69      13929455.5        2065525.       13929375.
        2065325.       13929275.
#Sta/Elev= 30
  4520.8    1504  4556.3 1502.67  4635.1 1491.72  4688.6 1488.38  4788.1  1484.3
  4887.5 1483.36  4895.4 1483.28  4939.4  1481.6  4959.7 1479.29  4990.2 1474.22
  4997.8 1469.96  5003.1 1469.96  5004.7 1468.21  5005.2 1467.71  5012.7 1468.21
  5014.3 1469.84  5022.7 1470.44    5031 1473.03    5045 1485.78  5075.8 1501.67
  5081.4 1506.99  5098.1 1512.53  5134.5 1520.06  5156.8 1526.43  5170.8 1531.53
  5187.6 1543.01  5193.2 1544.17  5201.5 1550.07  5209.9 1553.74  5223.9 1555.61
#Mann= 7 ,-1 , 0
  4520.8     .12       0  4688.6    .035       0  4788.1     .07       0
  4887.5    .035       0  4895.4     .07       0  5004.7     .05       0
  5012.7     .07       0
Bank Sta=5004.7,5012.7
XS Rating Curve= 0 ,0
Exp/Cntr=0.3,0.1

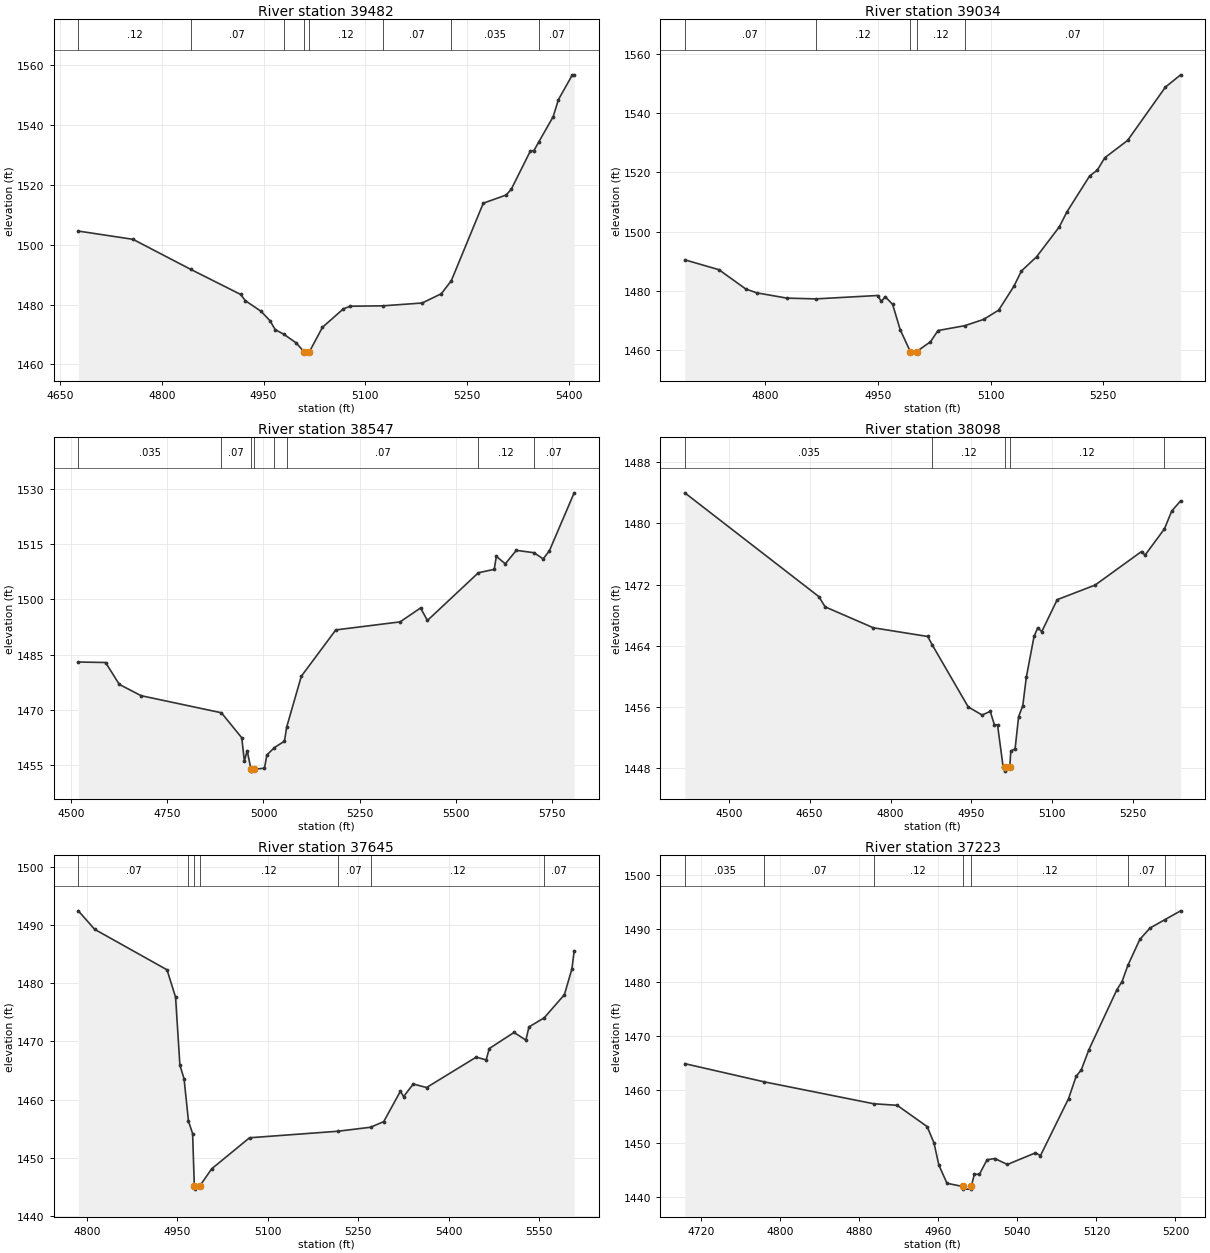
Type RM Length L Ch R = 1 ,39482   ,448,448,448
BEGIN DESCRIPTION:
EAST SISTER CREEK 72.0
END DESCRIPTION:
XS GIS Cut Line= 3
       2066038.9     13929203.77        2065775.       13929025.
      2065374.96     13928924.99
#Sta/Elev= 30
  4676.9 1504.62  4757.5 1501.86  4842.3 1491.85  4916.3 1483.42  4923.2 1481.33
  4946.2 1477.81  4959.4 1474.67  4967.2 1471.66  4979.8 1470.13  4998.2 1467.21
  5009.6  1464.3  5010.1  1463.8  5017.7  1464.3  5036.9 1472.45  5067.8 1478.63
  5078.1 1479.49  5125.9 1479.62  5183.8 1480.56  5212.1 1483.66  5226.8 1487.99
    5274 1513.94  5307.5 1516.66  5315.2 1518.57  5343.5 1531.43  5348.7 1531.54
  5355.8 1534.42    5377 1542.85  5384.8 1548.59  5405.4 1556.87    5408 1556.87
#Mann= 8 ,-1 , 0
  4676.9     .12       0  4842.3     .07       0  4979.8     .12       0
  5009.6     .05       0  5017.7     .12       0  5125.9     .07       0
  5226.8    .035       0  5355.8     .07       0
Bank Sta=5009.6,5017.7
XS Rating Curve= 0 ,0
Exp/Cntr=0.3,0.1

Type RM Length L Ch R = 1 ,39034   ,487,487,487
BEGIN DESCRIPTION:
EAST SISTER CREEK 71.0
END DESCRIPTION:
XS GIS Cut Line= 3
      2066030.19     13928659.06        2065725.       13928625.
      2065375.04     13928674.99
#Sta/Elev= 30
  4692.5 1490.49    4738 1487.15  4773.7 1480.66  4788.3 1479.36  4828.5 1477.58
    4867 1477.32  4949.3 1478.46  4954.4 1476.44  4959.4 1478.08  4969.4 1475.47
  4979.5 1466.92    4993 1459.54  4993.5 1459.04  5001.2 1459.54  5019.8 1462.87
  5029.9 1466.66  5065.5 1468.29  5090.5 1470.39  5110.7 1473.53  5130.9 1481.55
    5141 1486.73  5161.2 1491.51  5191.5 1501.61  5201.6 1506.64  5231.9 1518.76
    5242 1520.68  5252.1 1524.89  5282.4 1530.71  5332.9 1548.71  5353.1 1552.83
#Mann= 5 ,-1 , 0
  4692.5     .07       0    4867     .12       0    4993     .05       0
  5001.2     .12       0  5065.5     .07       0
Bank Sta=4993,5001.2
XS Rating Curve= 0 ,0
Exp/Cntr=0.3,0.1

Type RM Length L Ch R = 1 ,38547   ,449,449,449
BEGIN DESCRIPTION:
EAST SISTER CREEK 70.0
END DESCRIPTION:
XS GIS Cut Line= 3
      2066153.91     13928526.67        2065825.       13928175.
      2065086.18     13927847.41
#Sta/Elev= 30
  4518.4 1483.03  4589.3  1482.9    4625 1476.96  4681.7  1473.9  4890.5 1469.27
  4943.5 1462.49  4950.3 1456.16  4957.6 1458.99  4967.5 1453.94    4968 1453.44
  4976.2 1453.94  5002.6 1454.25  5008.8 1457.83  5028.6 1459.84  5054.6 1461.56
  5060.3 1465.38  5098.4 1479.17  5188.1 1491.74  5355.4 1493.92  5408.6  1497.7
  5426.4  1494.3  5558.9 1507.24  5600.2 1508.17  5605.7 1511.69    5629 1509.67
  5657.7 1513.32  5703.7 1512.68  5727.5    1511  5743.8 1513.23  5808.1 1528.92
#Mann= 8 ,-1 , 0
  4518.4    .035       0  4890.5     .07       0  4967.5     .05       0
  4976.2     .07       0  5028.6    .035       0  5060.3     .07       0
  5558.9     .12       0  5703.7     .07       0
Bank Sta=4967.5,4976.2
XS Rating Curve= 0 ,0
Exp/Cntr=0.3,0.1

Type RM Length L Ch R = 1 ,38098   ,453,453,453
BEGIN DESCRIPTION:
EAST SISTER CREEK 69.0
END DESCRIPTION:
XS GIS Cut Line= 3
      2066240.72      13928489.8        2066125.       13927925.
      2065860.98      13927706.4
#Sta/Elev= 30
  4418.6 1484.01  4667.3 1470.42  4678.7 1469.09  4768.2 1466.35  4869.1 1465.21
  4877.3 1464.12  4944.1 1455.99  4969.9 1454.93  4984.9 1455.41  4992.6 1453.66
  4998.4 1453.66  5008.8 1448.15  5012.3 1448.09  5012.8 1447.59    5021 1448.09
  5023.1 1450.22    5031  1450.5  5037.5 1454.72  5045.3 1456.17  5051.8 1459.87
  5066.1 1465.21    5073 1466.36  5080.4 1465.84  5109.1 1470.03  5179.4 1471.94
  5265.4 1476.33  5271.9 1475.86  5307.9 1479.29  5321.4 1481.63  5337.9 1482.96
#Mann= 5 ,-1 , 0
  4418.6    .035       0  4877.3     .12       0  5012.3     .05       0
    5021     .12       0  5307.9     .07       0
Bank Sta=5012.3,5021
XS Rating Curve= 0 ,0
Exp/Cntr=0.3,0.1

Type RM Length L Ch R = 1 ,37645   ,422,422,422
BEGIN DESCRIPTION:
EAST SISTER CREEK 68.0
END DESCRIPTION:
XS GIS Cut Line= 3
       2066676.9     13927921.19        2066525.       13927775.
       2065939.5     13927597.99
#Sta/Elev= 30
  4785.8 1492.42  4812.8 1489.25  4932.9 1482.29  4947.1 1477.59  4954.3 1465.91
  4961.2 1463.57  4968.5  1456.3  4975.4 1454.15  4978.2 1445.12  4978.7 1444.62
    4987 1445.12  5007.1 1448.12  5069.8 1453.44  5216.2 1454.56  5270.7 1455.25
  5292.4 1456.22  5320.1 1461.43  5325.3 1460.51  5341.4 1462.67  5363.5 1462.07
  5445.8 1467.29  5462.3 1466.82  5467.5 1468.77  5508.5 1471.53  5528.2 1470.22
  5533.4 1472.49  5558.5 1474.03  5592.1 1478.02  5604.6 1482.45  5608.3 1485.55
#Mann= 7 ,-1 , 0
  4785.8     .07       0  4968.5     .12       0  4978.2     .05       0
    4987     .12       0  5216.2     .07       0  5270.7     .12       0
  5558.5     .07       0
Bank Sta=4978.2,4987
XS Rating Curve= 0 ,0
Exp/Cntr=0.3,0.1

Type RM Length L Ch R = 1 ,37223   ,445,445,445
BEGIN DESCRIPTION:
EAST SISTER CREEK 67.0
END DESCRIPTION:
XS GIS Cut Line= 3
      2066568.37     13927439.45        2066275.       13927475.
      2066074.97     13927424.99
#Sta/Elev= 30
  4703.5 1464.83    4784 1461.43  4894.7 1457.35  4918.4 1457.06  4948.7  1453.1
  4955.6 1450.07  4960.6  1445.9  4968.8 1442.52  4984.5 1441.93    4985 1441.43
  4992.8 1441.43  4993.3 1441.93  4996.5  1444.2  5001.6  1444.2  5009.3  1446.9
  5017.1 1447.14  5029.9 1446.03  5058.3 1448.19  5063.4 1447.69  5091.8 1458.31
  5099.5 1462.48  5104.7 1463.68  5112.4 1467.44  5140.7 1478.62  5145.9 1480.13
  5151.8 1483.15  5163.9    1488  5174.2 1490.12  5189.4  1491.7  5205.2 1493.33
#Mann= 7 ,-1 , 0
  4703.5    .035       0    4784     .07       0  4894.7     .12       0
  4984.5     .05       0  4993.3     .12       0  5151.8     .07       0
  5189.4    .035       0
Bank Sta=4984.5,4993.3
XS Rating Curve= 0 ,0
Exp/Cntr=0.3,0.1

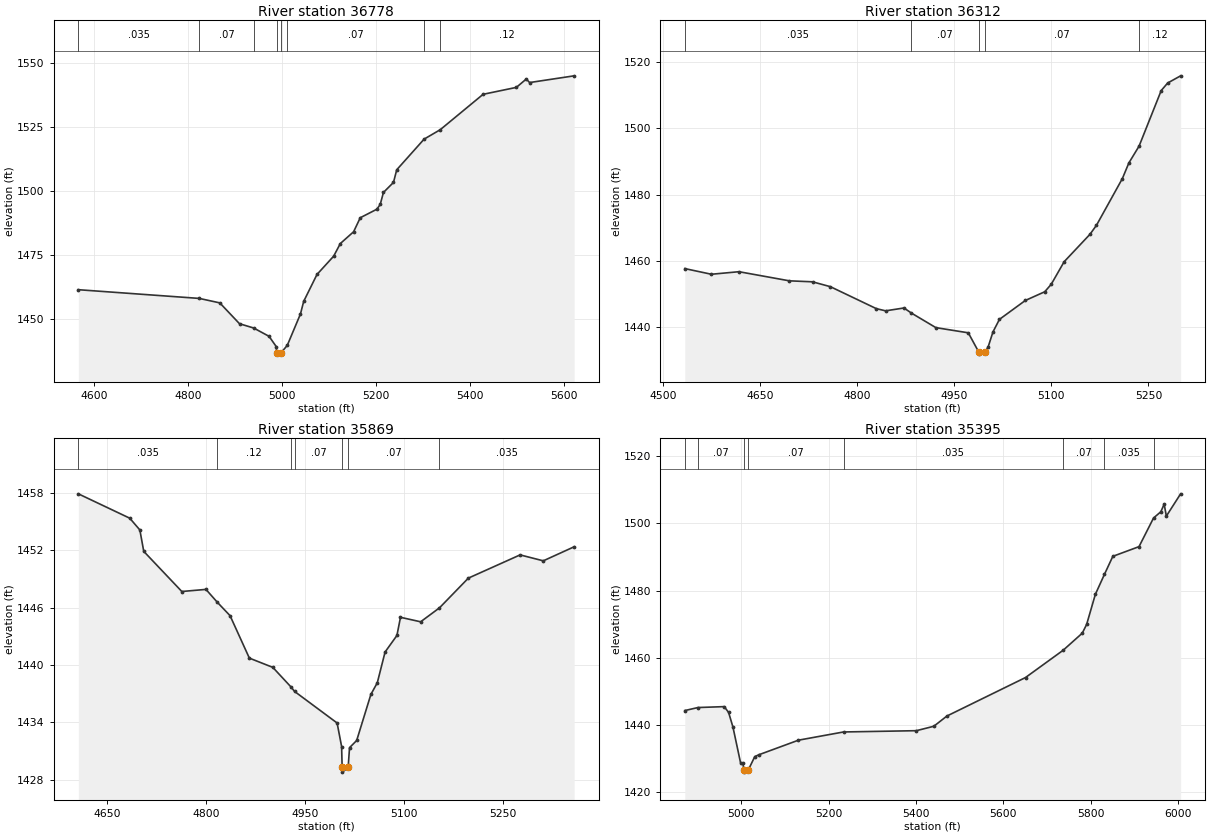
Type RM Length L Ch R = 1 ,36778   ,466,466,466
BEGIN DESCRIPTION:
EAST SISTER CREEK 66.0
END DESCRIPTION:
XS GIS Cut Line= 3
      2066642.16     13927207.22        2066225.       13927075.
      2065780.68     13926645.19
#Sta/Elev= 30
  4566.6 1461.51  4824.3 1458.11  4867.8 1456.37  4909.8 1448.24  4939.8 1446.58
  4972.7 1443.33  4988.1  1439.3  4989.2 1436.88  4989.7 1436.38  4998.2 1436.88
  5011.6 1439.83  5039.6 1452.05  5046.5 1456.97  5074.8 1467.46  5110.3 1474.59
  5124.5 1479.52  5152.8 1484.12  5166.9 1489.58  5202.2  1492.9  5209.4 1494.75
  5216.3 1499.45  5237.7 1503.37  5244.6 1508.29  5302.9 1520.25  5337.2 1523.92
  5428.5 1537.73  5499.3 1540.43  5520.4 1543.68  5527.6 1542.32  5622.4 1544.94
#Mann= 8 ,-1 , 0
  4566.6    .035       0  4824.3     .07       0  4939.8    .035       0
  4989.2    .035       0  4998.2    .035       0  5011.6     .07       0
  5302.9    .035       0  5337.2     .12       0
Bank Sta=4989.2,4998.2
XS Rating Curve= 0 ,0
Exp/Cntr=0.3,0.1

Type RM Length L Ch R = 1 ,36312   ,443,443,443
BEGIN DESCRIPTION:
EAST SISTER CREEK 65.0
END DESCRIPTION:
XS GIS Cut Line= 3
      2066772.37     13926985.85        2066425.       13926675.
      2066124.95       13926675.
#Sta/Elev= 30
  4533.5 1457.68  4574.6 1455.97  4617.2 1456.74    4695 1453.99  4730.9 1453.69
  4758.5 1452.22  4829.6 1445.59  4843.8 1444.94  4872.2  1445.8  4883.7 1444.26
  4921.5 1439.87  4971.6 1438.31  4988.1 1432.38  4988.6 1431.88  4997.1 1432.38
  5002.2 1434.01  5009.7 1438.57  5019.7 1442.36  5059.7 1448.06  5089.7 1450.69
  5099.7 1452.93  5119.7 1459.75  5159.7 1468.04  5169.7 1470.76  5209.7 1484.84
  5219.7 1489.54  5235.5 1494.62  5269.7 1511.38  5279.7 1513.66  5299.7 1515.82
#Mann= 5 ,-1 , 0
  4533.5    .035       0  4883.7     .07       0  4988.1     .05       0
  4997.1     .07       0  5235.5     .12       0
Bank Sta=4988.1,4997.1
XS Rating Curve= 0 ,0
Exp/Cntr=0.3,0.1

Type RM Length L Ch R = 1 ,35869   ,946,946,946
BEGIN DESCRIPTION:
EAST SISTER CREEK 64.0
END DESCRIPTION:
XS GIS Cut Line= 3
      2066982.92     13926753.69        2066775.       13926425.
      2066439.08     13926291.79
#Sta/Elev= 30
  4606.9 1457.91  4684.7 1455.36    4700 1454.13  4705.9 1451.89  4763.5 1447.69
    4800 1447.91  4817.4 1446.55  4836.5 1445.16  4865.7 1440.72  4901.2 1439.75
  4928.6 1437.71  4934.2 1437.23  4998.5 1433.93  5005.3 1431.47  5006.1 1429.29
  5006.6 1428.79  5015.2 1429.29  5017.3 1431.35  5028.1  1432.1  5049.6 1436.92
  5059.3 1438.14  5071.1 1441.36    5089 1443.09  5094.4 1444.99  5124.9 1444.52
  5153.4 1445.98  5197.1 1449.09  5275.4 1451.52  5310.5  1450.9  5357.2 1452.37
#Mann= 7 ,-1 , 0
  4606.9    .035       0  4817.4     .12       0  4928.6    .035       0
  4934.2     .07       0  5006.1     .05       0  5015.2     .07       0
  5153.4    .035       0
Bank Sta=5006.1,5015.2
XS Rating Curve= 0 ,0
Exp/Cntr=0.3,0.1

Type RM Length L Ch R = 1 ,35395   ,472,472,472
BEGIN DESCRIPTION:
EAST SISTER CREEK 63.0
END DESCRIPTION:
XS GIS Cut Line= 3
      2067205.22     13926119.72        2067075.       13926125.
      2066069.75     13926109.46
#Sta/Elev= 30
  4870.5 1444.25  4900.7 1445.15  4960.8 1445.42  4970.8  1443.7  4980.8 1439.33
  4998.3 1428.64  5003.3 1428.64  5006.3  1426.4  5006.8  1425.9  5015.4  1426.4
  5030.8 1430.53  5040.8 1431.11  5130.8 1435.42  5234.1 1437.87  5400.9 1438.25
  5440.9 1439.57  5470.9 1442.62  5650.9 1454.09  5737.2 1462.23  5780.9 1467.31
  5790.9 1469.91  5810.9 1478.89  5831.6 1484.81  5850.9 1490.21  5910.9  1493.1
  5944.2 1501.64  5960.9  1503.5  5968.5 1505.77  5973.5  1502.2  6006.2 1508.84
#Mann= 8 ,-1 , 0
  4870.5     .12       0  4900.7     .07       0  5006.3     .05       0
  5015.4     .07       0  5234.1    .035       0  5737.2     .07       0
  5831.6    .035       0  5944.2     .07       0
Bank Sta=5006.3,5015.4
XS Rating Curve= 0 ,0
Exp/Cntr=0.3,0.1