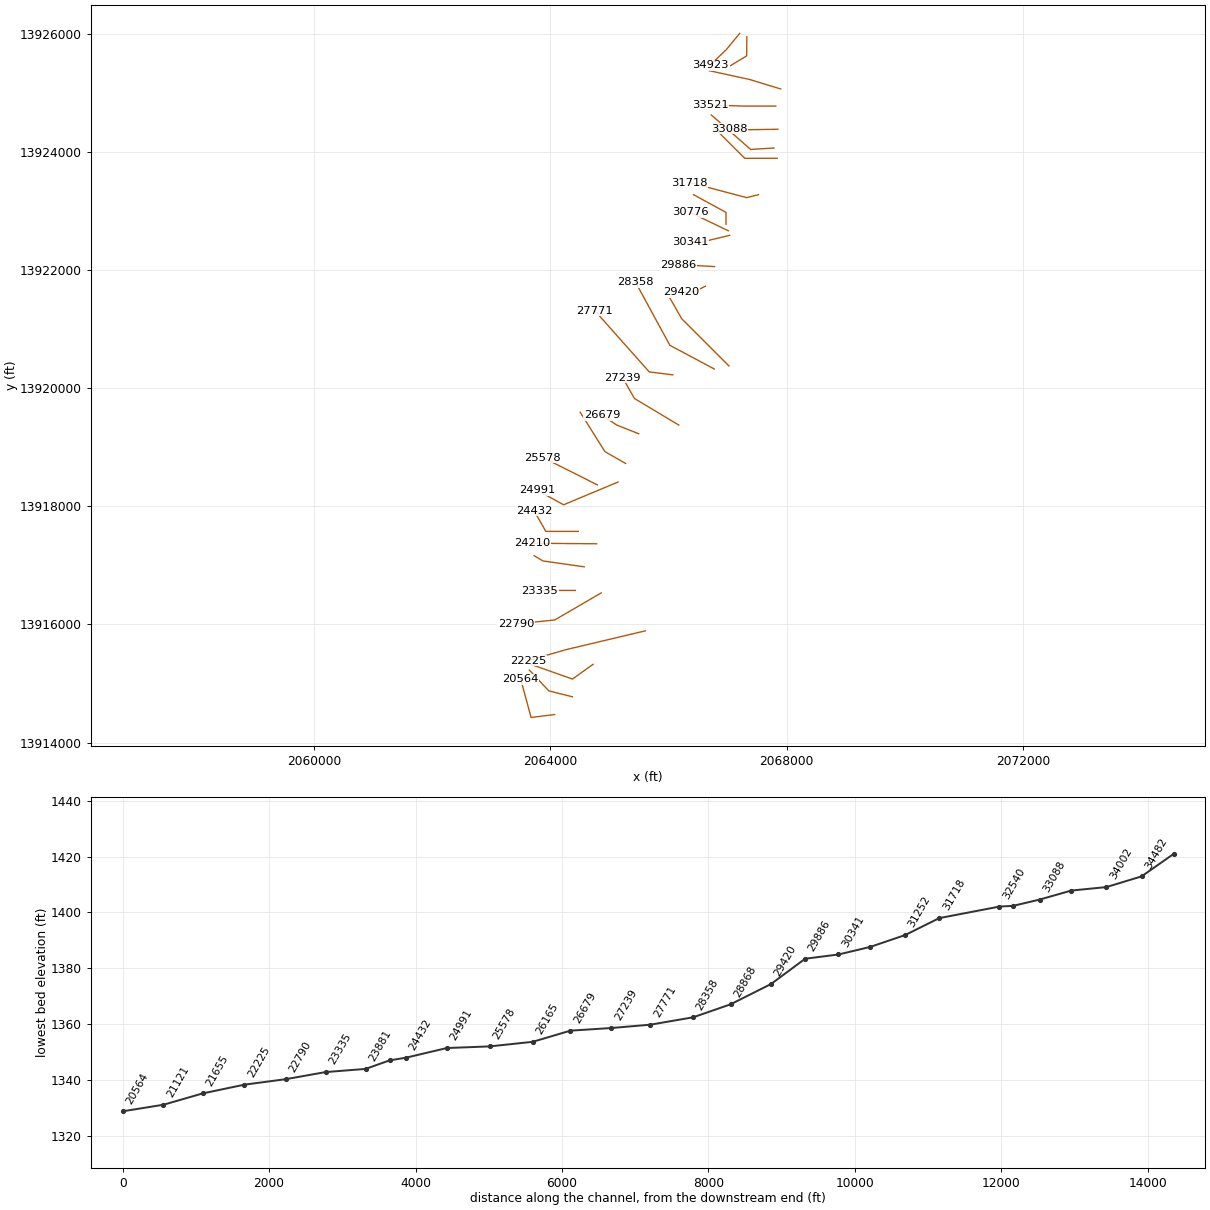
HEC-RAS study EAST SISTER CREEK.prj: EAST SISTER CREEK Base Level Engineering

--- EAST SISTER CREEK.g01 (geometry) --- (continued)

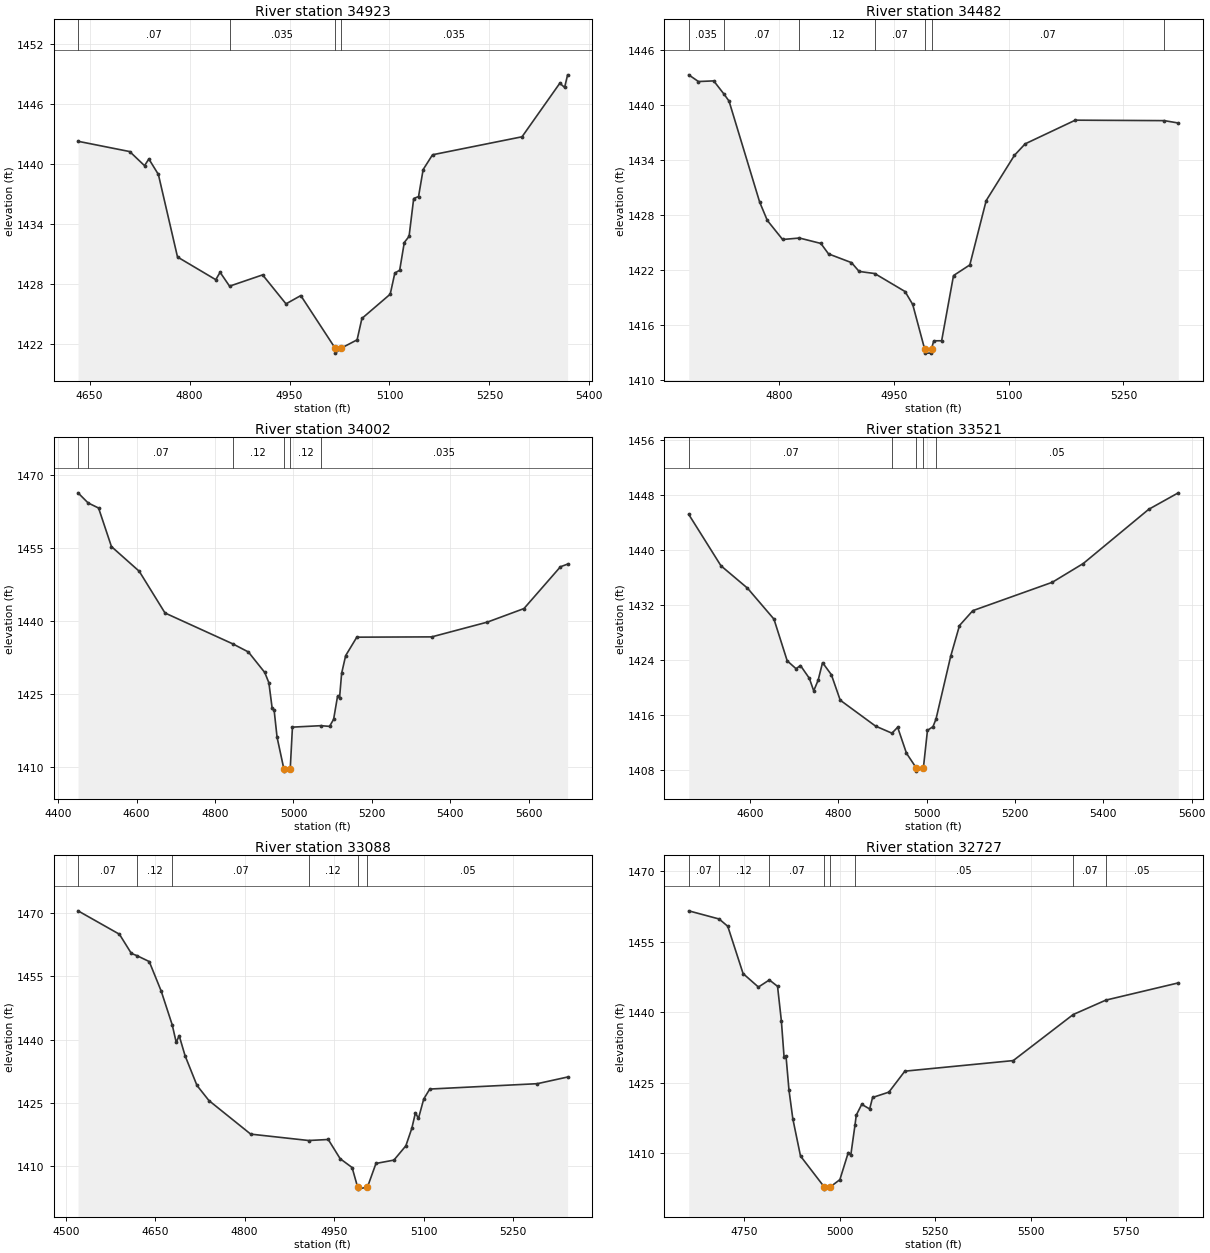
Type RM Length L Ch R = 1 ,34923   ,441,441,441
BEGIN DESCRIPTION:
EAST SISTER CREEK 62.0
END DESCRIPTION:
XS GIS Cut Line= 3
      2067205.68     13926004.41        2066975.       13925725.
      2066704.51     13925469.07
#Sta/Elev= 30
  4632.6 1442.25  4710.2 1441.22  4732.4 1439.81  4738.9 1440.48  4753.2 1438.93
  4781.9 1430.67  4839.3  1428.4  4845.8 1429.14    4860 1427.75  4909.6 1428.88
  4944.7 1425.98  4966.9 1426.81  5018.4 1421.55  5018.9 1421.05  5027.6 1421.55
  5051.4 1422.38  5058.6 1424.52  5101.1 1426.95    5108 1429.06  5115.3 1429.35
  5122.2 1432.12  5129.4 1432.74  5136.3 1436.52  5143.6 1436.72  5150.5 1439.42
  5164.6  1440.9  5298.9  1442.7  5355.6 1448.06  5362.8 1447.64  5367.3  1448.9
#Mann= 4 ,-1 , 0
  4632.6     .07       0    4860    .035       0  5018.4    .035       0
  5027.6    .035       0
Bank Sta=5018.4,5027.6
XS Rating Curve= 0 ,0
Exp/Cntr=0.3,0.1

Type RM Length L Ch R = 1 ,34482   ,480,480,480
BEGIN DESCRIPTION:
EAST SISTER CREEK 61.0
END DESCRIPTION:
XS GIS Cut Line= 3
      2067327.27     13925947.73        2067325.       13925625.
      2067053.77       13925461.
#Sta/Elev= 30
    4682 1443.26  4694.7 1442.53  4714.7  1442.6  4728.3 1441.14  4734.7  1440.4
  4774.7  1429.4  4784.7  1427.4  4804.7 1425.32  4826.7 1425.48  4854.7 1424.89
  4864.7 1423.75  4894.7  1422.8  4904.7 1421.84  4925.1 1421.61  4964.7 1419.65
  4974.7 1418.24  4990.1 1413.44  4990.6 1412.94  4998.8 1412.94  4999.3 1413.44
  5002.2 1414.28  5012.5 1414.29    5028 1421.39  5049.3 1422.55  5070.7 1429.56
  5107.6 1434.49  5121.6 1435.74  5187.1 1438.32  5303.4 1438.27  5321.7 1438.01
#Mann= 7 ,-1 , 0
    4682    .035       0  4728.3     .07       0  4826.7     .12       0
  4925.1     .07       0  4990.1     .05       0  4999.3     .07       0
  5303.4    .035       0
Bank Sta=4990.1,4999.3
XS Rating Curve= 0 ,0
Exp/Cntr=0.3,0.1

Type RM Length L Ch R = 1 ,34002   ,481,481,481
BEGIN DESCRIPTION:
EAST SISTER CREEK 60.0
END DESCRIPTION:
XS GIS Cut Line= 3
      2067900.46     13925064.84        2067375.       13925225.
      2066692.06     13925373.88
#Sta/Elev= 30
  4450.7 1466.42  4476.4 1464.34  4503.1 1463.29  4535.9 1455.35  4606.8 1450.26
  4672.5 1441.67  4845.6  1435.3  4885.1 1433.64  4926.8 1429.42  4937.3 1427.31
  4945.6 1422.11  4950.8  1421.6  4958.2 1416.08  4975.4  1409.6  4975.9  1409.1
  4991.8  1409.6  4997.4 1418.16  5069.7 1418.46  5092.1 1418.32  5102.4 1419.78
  5112.4 1424.52  5117.6 1424.26  5122.8 1429.24  5133.1 1432.89  5161.5 1436.69
  5352.6 1436.75  5494.7  1439.8  5587.7 1442.58  5680.7 1451.19    5699 1451.74
#Mann= 6 ,-1 , 0
  4450.7    .035       0  4476.4     .07       0  4845.6     .12       0
  4975.4     .05       0  4991.8     .12       0  5069.7    .035       0
Bank Sta=4975.4,4991.8
XS Rating Curve= 0 ,0
Exp/Cntr=0.3,0.1

Type RM Length L Ch R = 1 ,33521   ,433,433,433
BEGIN DESCRIPTION:
EAST SISTER CREEK 59.0
END DESCRIPTION:
XS GIS Cut Line= 3
      2067818.01     13924774.31        2067275.       13924775.
      2066709.96     13924791.91
#Sta/Elev= 30
  4461.5  1445.2  4534.5 1437.72  4594.5 1434.47  4654.5 1429.96  4684.5 1423.89
  4704.5 1422.75  4714.5 1423.21  4734.5 1421.36  4744.5 1419.53  4754.5 1421.07
  4764.5 1423.63  4784.5 1421.87  4804.5 1418.17  4884.5  1414.4  4921.6 1413.37
  4934.5 1414.23  4954.5 1410.45  4976.3 1408.35  4976.8 1407.85  4992.8 1408.35
    5002 1413.78  5014.5 1414.32  5021.3 1415.42  5054.5 1424.54  5074.5 1429.03
  5104.6 1431.19  5284.6 1435.32  5354.7 1438.05  5502.8 1445.93  5569.8 1448.33
#Mann= 5 ,-1 , 0
  4461.5     .07       0  4921.6     .12       0  4976.3     .05       0
  4992.8     .12       0  5021.3     .05       0
Bank Sta=4976.3,4992.8
XS Rating Curve= 0 ,0
Exp/Cntr=0.3,0.1

Type RM Length L Ch R = 1 ,33088   ,361,361,361
BEGIN DESCRIPTION:
EAST SISTER CREEK 58.0
END DESCRIPTION:
XS GIS Cut Line= 3
      2067854.42     13924382.62        2067375.       13924375.
      2067034.25     13924394.57
#Sta/Elev= 30
  4520.6 1470.49    4590 1464.95    4610 1460.41  4619.4 1459.88    4640 1458.48
    4660 1451.51  4678.6 1443.46  4685.2 1439.36  4690.2 1440.94    4700 1436.22
    4720 1429.16  4740.1 1425.57  4810.1 1417.63  4907.3 1416.12  4940.1 1416.36
  4960.1 1411.81  4980.1 1409.72  4989.3 1405.11  4989.8 1404.61  5005.9 1405.11
  5020.1 1410.69  5050.2 1411.48  5070.2 1414.86  5080.2    1419  5086.3  1422.7
  5091.3 1421.33  5100.2 1425.95  5110.3  1428.3  5290.6 1429.57  5341.4 1431.15
#Mann= 6 ,-1 , 0
  4520.6     .07       0  4619.4     .12       0  4678.6     .07       0
  4907.3     .12       0  4989.3     .05       0  5005.9     .05       0
Bank Sta=4989.3,5005.9
XS Rating Curve= 0 ,0
Exp/Cntr=0.3,0.1

Type RM Length L Ch R = 1 ,32727   ,187,187,187
BEGIN DESCRIPTION:
EAST SISTER CREEK 57.0
END DESCRIPTION:
XS GIS Cut Line= 3
      2067787.16     13924064.87      2067392.05     13924041.52
      2066725.28     13924624.96
#Sta/Elev= 30
  4604.2 1461.56  4683.9 1459.82  4706.5 1458.27  4746.6 1448.21  4786.7 1445.35
  4815.3 1446.86  4836.8  1445.5  4846.8 1438.17    4854 1430.37    4859 1430.63
  4866.8 1423.39  4876.8 1417.33  4896.9 1409.41  4958.7 1402.87  4959.2 1402.37
  4975.3 1402.87    5000 1404.39    5022 1410.15  5028.7 1409.67  5039.7 1416.07
  5042.9  1418.1  5057.2  1420.4    5078 1419.42  5085.6 1421.86  5128.3    1423
  5170.1 1427.46  5453.9 1429.71  5610.8  1439.5  5696.4 1442.57    5886 1446.23
#Mann= 8 ,-1 , 0
  4604.2     .07       0  4683.9     .12       0  4815.3     .07       0
  4958.7     .05       0  4975.3     .07       0  5039.7     .05       0
  5610.8     .07       0  5696.4     .05       0
Bank Sta=4958.7,4975.3
XS Rating Curve= 0 ,0
Exp/Cntr=0.3,0.1

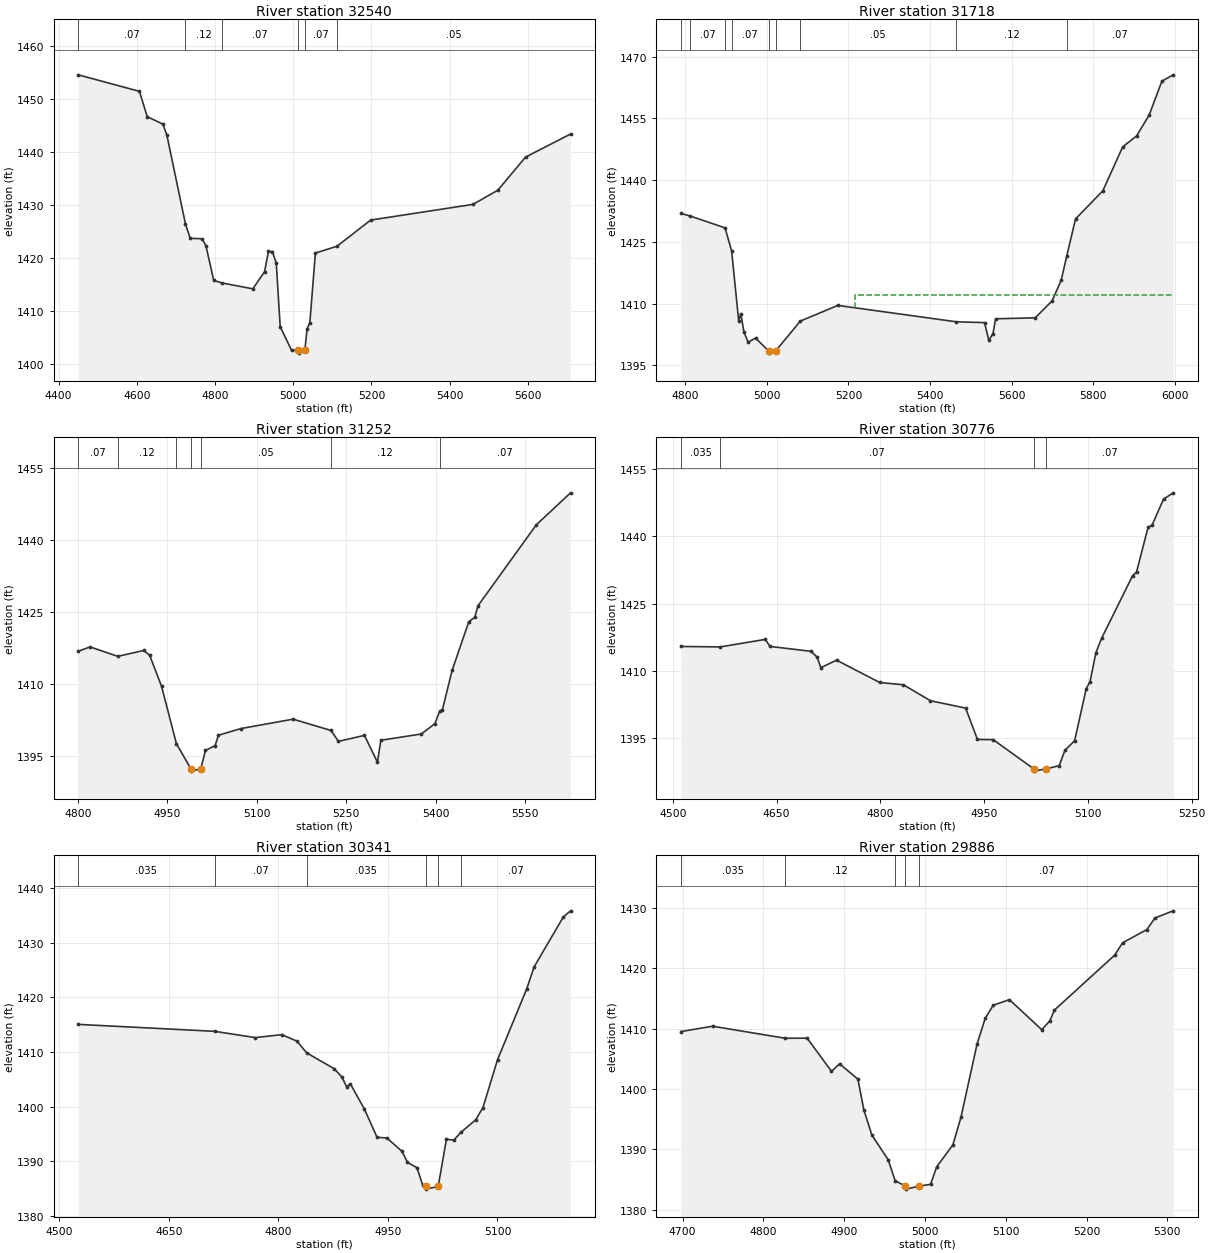
Type RM Length L Ch R = 1 ,32540   ,822,822,822
BEGIN DESCRIPTION:
EAST SISTER CREEK 56.5
END DESCRIPTION:
XS GIS Cut Line= 3
      2067841.68     13923891.31      2067291.58     13923891.52
      2066789.37     13924392.27
#Sta/Elev= 30
  4449.9 1454.53  4606.6 1451.42  4626.6 1446.65  4666.6 1445.24  4676.6 1443.23
  4724.4  1426.4  4736.6 1423.74  4766.6 1423.65  4776.6 1422.36  4796.6 1415.81
  4816.6 1415.34  4896.6 1414.22  4926.6 1417.44  4936.6 1421.26  4946.6 1421.23
  4956.6 1419.06  4966.6 1407.11  4995.8 1402.62    5013 1402.61  5013.5 1402.11
  5029.6 1402.61  5035.4  1406.7  5042.5 1407.86  5056.6 1420.96  5111.8 1422.24
    5198 1427.17  5459.7 1430.13  5523.3  1432.8    5594 1439.03  5709.2 1443.38
#Mann= 6 ,-1 , 0
  4449.9     .07       0  4724.4     .12       0  4816.6     .07       0
    5013     .05       0  5029.6     .07       0  5111.8     .05       0
Bank Sta=5013,5029.6
XS Rating Curve= 0 ,0
Exp/Cntr=0.3,0.1

Type RM Length L Ch R = 1 ,31718   ,466,466,466
BEGIN DESCRIPTION:
EAST SISTER CREEK 56.0
END DESCRIPTION:
XS GIS Cut Line= 3
      2067524.99       13923275.        2067325.       13923225.
      2066358.11     13923481.19
#Sta/Elev= 30
  4789.5 1431.91  4813.1 1431.25  4897.7 1428.39  4913.9 1422.81  4931.2 1405.79
  4936.4 1407.56  4944.1  1403.1  4954.4 1400.62  4972.5 1401.64  5004.8 1398.47
  5005.3 1397.97  5021.5 1398.47  5082.2 1405.75    5174 1409.56  5464.3 1405.58
  5533.6 1405.38  5543.9 1401.06  5554.3 1402.73  5560.6 1406.31  5657.7 1406.54
  5699.1 1410.66  5721.5 1415.71  5734.9 1421.54  5756.5 1430.57  5823.3 1437.38
    5872 1448.06    5906 1450.71    5937 1455.81  5968.1 1464.02  5995.9 1465.56
#Mann= 9 ,-1 , 0
  4789.5     .12       0  4813.1     .07       0  4897.7     .12       0
  4913.9     .07       0  5004.8     .05       0  5021.5     .07       0
  5082.2     .05       0  5464.3     .12       0  5734.9     .07       0
#XS Ineff= 2 , 0
       0                 5215.96       0    1412
Permanent Ineff=
       F       F
Bank Sta=5004.8,5021.5
XS Rating Curve= 0 ,0
Exp/Cntr=0.3,0.1

Type RM Length L Ch R = 1 ,31252   ,476,476,476
BEGIN DESCRIPTION:
EAST SISTER CREEK 55.0
END DESCRIPTION:
XS GIS Cut Line= 3
        2066975.     13922775.05        2066975.       13922975.
      2066425.04     13923274.98
#Sta/Elev= 30
  4800.1 1416.88  4820.1 1417.79  4866.6 1415.82  4910.1 1417.05  4920.1 1416.03
  4940.1 1409.56    4965 1397.62  4989.2  1392.4  4989.7  1391.9  5005.9  1392.4
  5013.8  1396.2    5030 1397.23  5035.6 1399.39  5073.6 1400.78  5160.9 1402.73
  5224.6 1400.37  5236.9  1398.1  5280.6 1399.35  5302.4 1393.75  5308.1 1398.33
    5376 1399.64  5398.7 1401.78  5406.7 1404.33  5411.5 1404.73  5427.7 1412.89
  5455.7 1423.03  5465.7 1423.97  5471.3 1426.39  5569.1 1443.24  5626.5  1449.9
#Mann= 7 ,-1 , 0
  4800.1     .07       0  4866.6     .12       0    4965     .05       0
  4989.2     .05       0  5005.9     .05       0  5224.6     .12       0
  5406.7     .07       0
Bank Sta=4989.2,5005.9
XS Rating Curve= 0 ,0
Exp/Cntr=0.3,0.1

Type RM Length L Ch R = 1 ,30776   ,435,435,435
BEGIN DESCRIPTION:
EAST SISTER CREEK 54.0
END DESCRIPTION:
XS GIS Cut Line= 3
       2067014.9     13922663.52        2066575.       13922875.
        2066375.       13922975.
#Sta/Elev= 30
  4511.6 1415.44  4568.4 1415.34  4633.5 1417.01  4640.5 1415.45  4700.1 1414.35
  4708.4 1413.08    4714 1410.71  4736.6 1412.39    4799 1407.41  4833.3  1406.9
  4872.4 1403.34  4923.2  1401.7  4940.3 1394.71    4963 1394.67  5021.8 1388.15
  5022.3 1387.65    5039 1388.15  5058.4 1388.85  5066.8 1392.32  5080.7  1394.4
  5097.5 1406.02  5103.1 1407.63  5111.5 1414.04  5119.9 1417.31  5164.6 1431.24
  5170.2 1432.03    5187 1442.05  5192.6 1442.45  5209.3 1448.29  5223.3 1449.69
#Mann= 4 ,-1 , 0
  4511.6    .035       0  4568.4     .07       0  5021.8     .05       0
    5039     .07       0
Bank Sta=5021.8,5039
XS Rating Curve= 0 ,0
Exp/Cntr=0.3,0.1

Type RM Length L Ch R = 1 ,30341   ,455,455,455
BEGIN DESCRIPTION:
EAST SISTER CREEK 53.0
END DESCRIPTION:
XS GIS Cut Line= 3
      2067036.02      13922587.3        2066575.       13922475.
        2066375.       13922475.
#Sta/Elev= 30
  4525.6 1415.08  4712.5 1413.81  4768.1 1412.66  4804.5  1413.2  4825.1 1412.02
  4838.8 1409.85  4876.6 1406.94  4886.9 1405.42  4893.3 1403.68  4898.4 1404.21
  4917.8 1399.55    4935 1394.42  4948.6 1394.28  4969.2 1391.85  4976.7 1389.83
  4989.8 1388.84  4997.5 1385.68  5001.5 1385.43    5002 1384.93  5018.8 1385.43
  5030.1 1394.07  5040.1 1393.89  5049.8 1395.31  5070.1 1397.61  5080.1 1399.85
  5100.1 1408.63  5140.1 1421.59  5150.1 1425.58  5190.1 1434.72  5200.1 1435.86
#Mann= 6 ,-1 , 0
  4525.6    .035       0  4712.5     .07       0  4838.8    .035       0
  5001.5    .035       0  5018.8    .035       0  5049.8     .07       0
Bank Sta=5001.5,5018.8
XS Rating Curve= 0 ,0
Exp/Cntr=0.3,0.1

Type RM Length L Ch R = 1 ,29886   ,466,466,466
BEGIN DESCRIPTION:
EAST SISTER CREEK 52.0
END DESCRIPTION:
XS GIS Cut Line= 3
      2066781.07     13922057.92        2066475.       13922075.
       2066172.4     13922084.68
#Sta/Elev= 30
  4697.9 1409.51  4737.1  1410.4  4826.9 1408.41  4854.2 1408.42  4884.3 1402.93
  4894.3 1404.17    4917 1401.63  4924.3 1396.55  4934.3 1392.36  4954.4 1388.29
  4963.1 1384.79  4975.8 1383.91  4976.3 1383.41  4993.1 1383.91  5006.9 1384.21
  5014.5 1387.11  5034.5 1390.73  5044.5 1395.31  5064.5 1407.48  5074.5 1411.69
  5084.5 1413.89  5104.5  1414.8  5144.5 1409.83  5154.5 1411.29  5160.2 1413.08
  5234.6 1422.16  5244.6 1424.23  5274.6 1426.42  5284.6 1428.34  5307.2 1429.52
#Mann= 5 ,-1 , 0
  4697.9    .035       0  4826.9     .12       0  4963.1     .07       0
  4975.8     .05       0  4993.1     .07       0
Bank Sta=4975.8,4993.1
XS Rating Curve= 0 ,0
Exp/Cntr=0.3,0.1

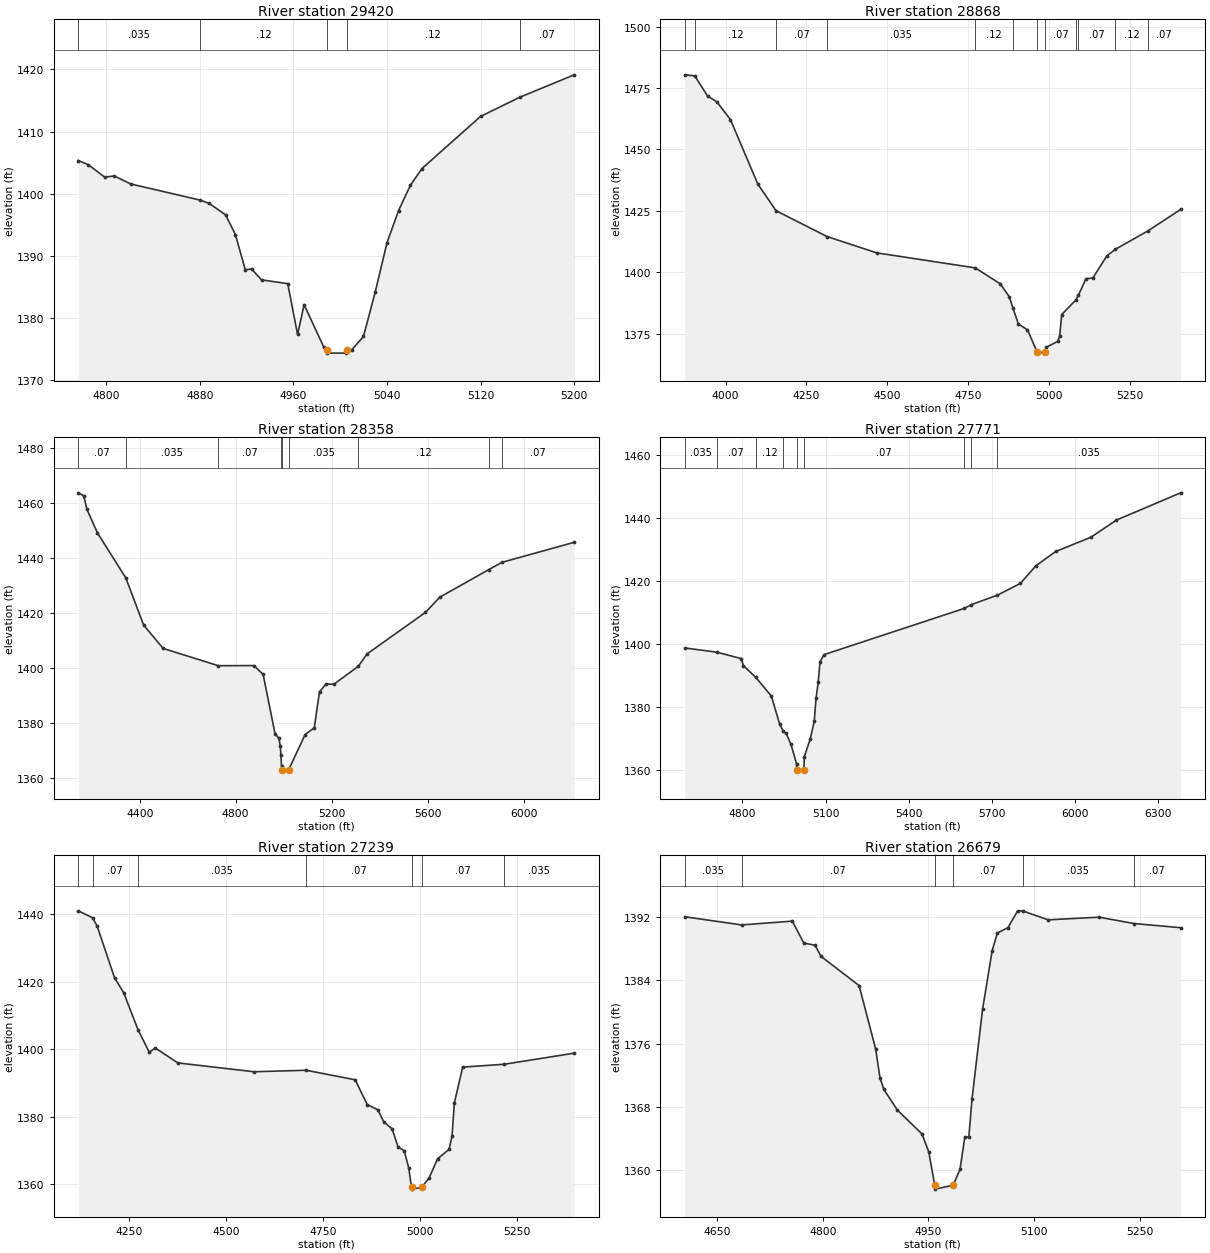
Type RM Length L Ch R = 1 ,29420   ,552,552,552
BEGIN DESCRIPTION:
EAST SISTER CREEK 51.0
END DESCRIPTION:
XS GIS Cut Line= 3
        2066625.       13921725.        2066425.       13921625.
      2066225.01       13921625.
#Sta/Elev= 30
  4776.3 1405.33  4784.7 1404.68  4798.7 1402.68  4807.1 1402.85    4821 1401.57
  4880.5 1398.96  4888.1 1398.44  4902.1 1396.59  4910.5 1393.42  4918.9 1387.76
  4924.4 1387.87  4932.8 1386.13  4955.2 1385.52  4963.6 1377.34  4969.2 1382.13
  4985.9 1375.35  4988.4 1374.84  4988.9 1374.34  5005.3 1374.34  5005.8 1374.84
  5009.9 1374.88  5019.9 1377.02  5029.9 1384.13  5039.9 1392.04  5049.9 1397.28
  5059.9 1401.33  5069.9 1404.05  5119.9 1412.43  5153.3 1415.51  5199.9 1419.13
#Mann= 5 ,-1 , 0
  4776.3    .035       0  4880.5     .12       0  4988.4     .05       0
  5005.8     .12       0  5153.3     .07       0
Bank Sta=4988.4,5005.8
XS Rating Curve= 0 ,0
Exp/Cntr=0.3,0.1

Type RM Length L Ch R = 1 ,28868   ,510,510,510
BEGIN DESCRIPTION:
EAST SISTER CREEK 50.0
END DESCRIPTION:
XS GIS Cut Line= 3
      2067024.98     13920375.02        2066225.       13921175.
      2066024.98     13921525.04
#Sta/Elev= 30
  3873.7 1480.37  3904.6 1479.95  3944.4 1471.68  3972.7 1469.41  4015.1 1462.11
  4099.9 1435.83  4156.2 1425.04  4313.5 1414.55  4467.6 1407.89  4772.8 1401.77
  4849.5 1395.31  4877.8 1390.11  4889.1 1385.43    4906 1378.94  4934.3 1376.57
  4963.8 1367.57  4964.3 1367.07  4989.7 1367.57  4990.9 1369.38  5028.1 1371.85
  5033.8 1374.01  5040.3 1382.79    5084 1388.74  5091.8 1390.65  5115.2 1397.29
  5136.8 1397.72    5180 1406.67  5206.1 1409.32  5306.6  1416.8  5408.2 1425.56
#Mann= 12 ,-1 , 0
  3873.7     .07       0  3904.6     .12       0  4156.2     .07       0
  4313.5    .035       0  4772.8     .12       0  4889.1     .07       0
  4963.8     .05       0  4989.7     .07       0    5084     .12       0
  5091.8     .07       0  5206.1     .12       0  5306.6     .07       0
Bank Sta=4963.8,4989.7
XS Rating Curve= 0 ,0
Exp/Cntr=0.3,0.1

Type RM Length L Ch R = 1 ,28358   ,587,587,587
BEGIN DESCRIPTION:
EAST SISTER CREEK 49.0
END DESCRIPTION:
XS GIS Cut Line= 3
      2066774.96     13920325.02        2066025.       13920725.
      2065443.46     13921793.77
#Sta/Elev= 30
  4144.2 1463.73  4166.8 1462.65  4179.9 1457.74  4223.8 1449.15  4341.9 1432.78
  4416.2 1415.61    4498 1407.07  4727.8  1400.8  4876.2 1400.84  4914.5 1397.62
  4964.1 1376.06  4980.3 1374.31    4986  1371.6  4988.4 1368.29  4991.3 1364.29
    4995 1362.92  4995.5 1362.42  5020.9 1362.92  5089.6 1375.74  5127.6 1378.21
  5149.5 1391.33    5177 1394.12  5209.3 1394.05  5311.4 1400.59  5347.1 1405.05
  5591.1  1420.2    5651 1425.75  5854.9 1435.78  5910.2 1438.43  6210.9 1445.72
#Mann= 9 ,-1 , 0
  4144.2     .07       0  4341.9    .035       0  4727.8     .07       0
  4988.4    .035       0    4995    .035       0  5020.9    .035       0
  5311.4     .12       0  5854.9    .035       0  5910.2     .07       0
Bank Sta=4995,5020.9
XS Rating Curve= 0 ,0
Exp/Cntr=0.3,0.1

Type RM Length L Ch R = 1 ,27771   ,532,532,532
BEGIN DESCRIPTION:
EAST SISTER CREEK 48.0
END DESCRIPTION:
XS GIS Cut Line= 3
      2066074.96       13920225.        2065675.       13920275.
      2064754.25     13921310.99
#Sta/Elev= 30
    4592 1398.85  4707.1 1397.52    4796 1395.46  4803.6 1393.21  4847.8 1389.56
  4904.4 1383.58  4934.6 1374.57  4947.5 1372.35  4957.3 1371.83  4974.9 1368.31
  4995.1 1362.16  4995.8 1360.26  4996.3 1359.76  5021.9 1360.26  5023.1 1364.28
  5044.8 1369.97    5059 1375.56  5065.7 1382.93  5073.3 1387.89    5080 1394.52
  5094.2 1396.73  5600.7 1411.41  5626.1 1412.61  5719.8  1415.6  5802.5 1419.32
  5859.3 1424.96  5930.4 1429.47  6057.5 1433.99  6149.5 1439.44  6381.1 1448.09
#Mann= 9 ,-1 , 0
    4592    .035       0  4707.1     .07       0  4847.8     .12       0
  4947.5     .07       0  4995.8     .05       0  5021.9     .07       0
  5600.7    .035       0  5626.1     .07       0  5719.8    .035       0
Bank Sta=4995.8,5021.9
XS Rating Curve= 0 ,0
Exp/Cntr=0.3,0.1

Type RM Length L Ch R = 1 ,27239   ,560,560,560
BEGIN DESCRIPTION:
EAST SISTER CREEK 47.0
END DESCRIPTION:
XS GIS Cut Line= 3
      2066175.04     13919374.98        2065425.       13919825.
        2065225.       13920175.
#Sta/Elev= 30
  4119.3 1441.04  4155.9 1438.99  4167.9 1436.48  4212.6 1421.21    4236 1416.82
    4273 1405.84  4302.1 1399.12  4317.6  1400.4  4375.9 1395.97  4572.2 1393.35
  4706.2  1393.8  4832.7 1390.97  4863.8 1383.62    4891 1382.08  4906.5 1378.49
  4927.9 1376.43  4943.5 1371.03    4959 1369.99  4970.7 1364.89    4978 1359.07
  4978.5 1358.57  5004.1 1359.07  5023.5 1361.94  5045.1 1367.56  5074.6 1370.33
  5082.5 1374.39  5088.3  1384.1  5109.9 1394.73  5216.5 1395.57  5397.1 1398.86
#Mann= 7 ,-1 , 0
  4119.3     .12       0  4155.9     .07       0    4273    .035       0
  4706.2     .07       0    4978     .05       0  5004.1     .07       0
  5216.5    .035       0
Bank Sta=4978,5004.1
XS Rating Curve= 0 ,0
Exp/Cntr=0.3,0.1

Type RM Length L Ch R = 1 ,26679   ,514,514,514
BEGIN DESCRIPTION:
EAST SISTER CREEK 46.0
END DESCRIPTION:
XS GIS Cut Line= 3
      2065496.77     13919227.75        2065125.       13919375.
      2064872.97     13919543.96
#Sta/Elev= 30
  4604.4    1392  4685.1 1390.97  4756.9 1391.45  4773.2 1388.68  4789.2 1388.41
  4797.6    1387  4851.6 1383.32  4875.2 1375.28  4881.3 1371.64  4886.7 1370.22
  4905.7 1367.62  4940.8 1364.59  4950.5  1362.3  4958.9 1358.12  4959.4 1357.62
  4985.1 1358.12  4994.8 1360.12  5001.6  1364.2  5007.3  1364.2  5011.8    1369
  5026.8 1380.34  5040.4 1387.73  5047.8 1389.96  5062.8 1390.62  5076.5 1392.75
  5084.3 1392.72  5119.8 1391.61  5191.9 1391.95  5241.2 1391.15  5307.7 1390.62
#Mann= 6 ,-1 , 0
  4604.4    .035       0  4685.1     .07       0  4958.9     .05       0
  4985.1     .07       0  5084.3    .035       0  5241.2     .07       0
Bank Sta=4958.9,4985.1
XS Rating Curve= 0 ,0
Exp/Cntr=0.3,0.1

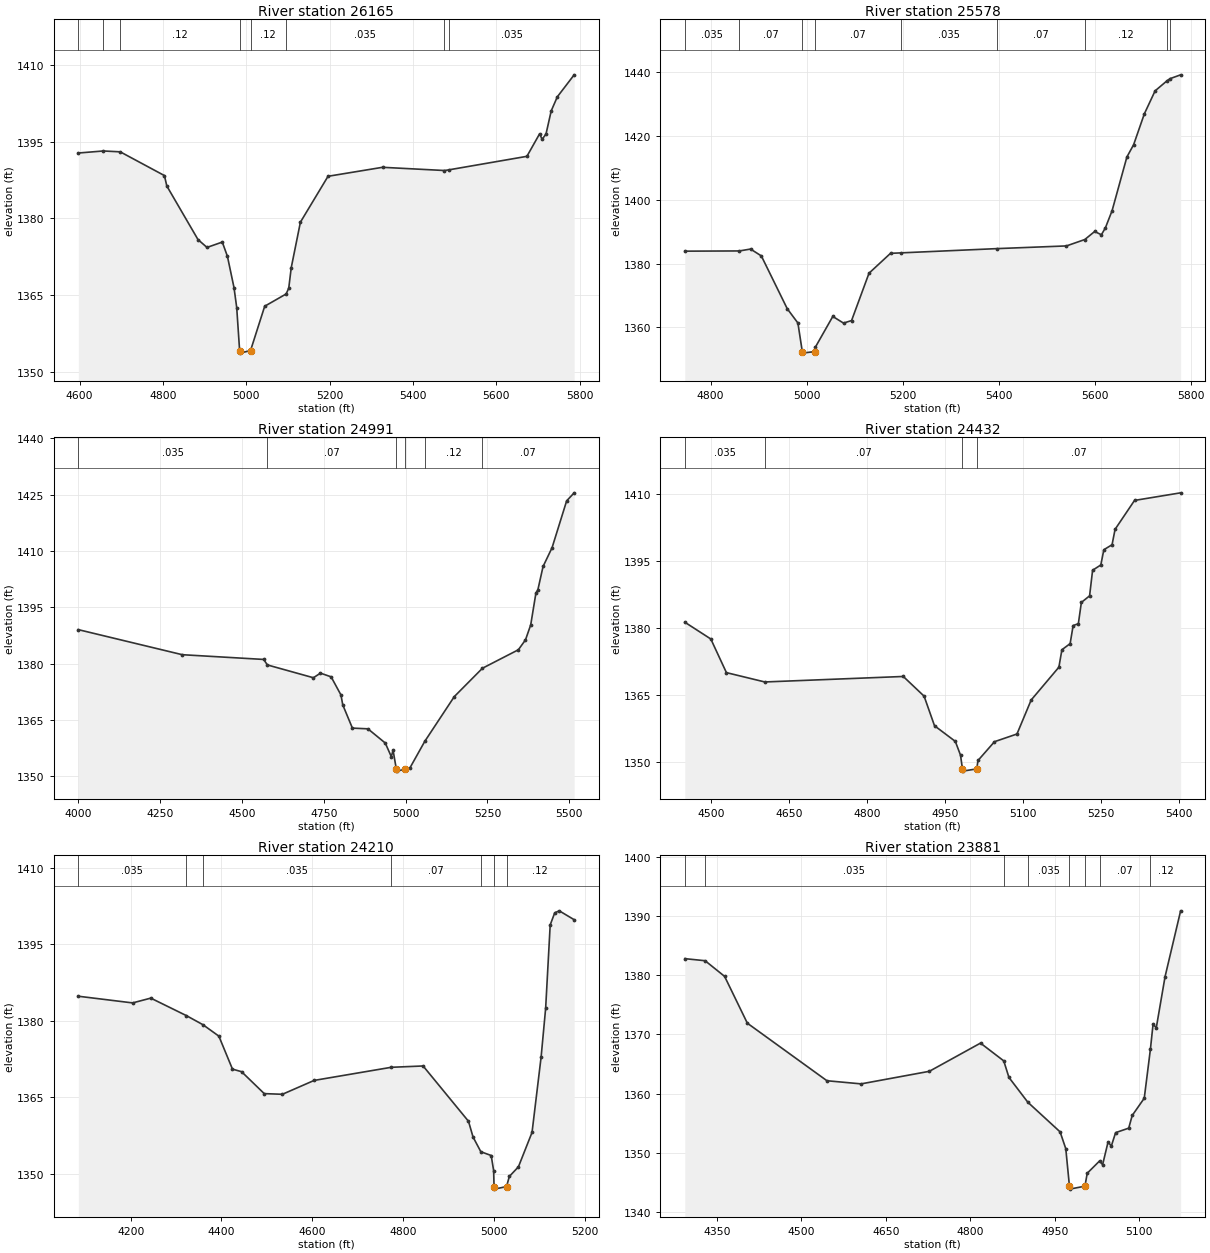
Type RM Length L Ch R = 1 ,26165   ,587,587,587
BEGIN DESCRIPTION:
EAST SISTER CREEK 45.0
END DESCRIPTION:
XS GIS Cut Line= 3
      2065275.01       13918725.        2064925.       13918925.
      2064506.96     13919591.65
#Sta/Elev= 30
  4597.1 1392.83  4657.3 1393.23  4697.7 1393.06  4803.7 1388.41  4809.5 1386.36
  4884.3 1375.87  4905.9 1374.33  4942.6 1375.38  4954.9 1372.59  4970.7 1366.47
  4977.2 1362.56  4984.2 1354.12  4984.7 1353.62  5010.4 1354.12  5044.4 1362.81
  5095.8 1365.21  5102.1 1366.35  5108.1 1370.37  5130.1 1379.28  5196.4 1388.27
  5327.2 1390.03  5475.9  1389.4  5486.2 1389.53  5673.7 1392.18  5704.3 1396.61
  5710.2  1395.5  5719.6 1396.57    5732 1401.08  5746.7 1403.84  5787.1 1408.15
#Mann= 8 ,-1 , 0
  4597.1     .07       0  4657.3    .035       0  4697.7     .12       0
  4984.2     .05       0  5010.4     .12       0  5095.8    .035       0
  5475.9     .07       0  5486.2    .035       0
Bank Sta=4984.2,5010.4
XS Rating Curve= 0 ,0
Exp/Cntr=0.3,0.1

Type RM Length L Ch R = 1 ,25578   ,587,587,587
BEGIN DESCRIPTION:
EAST SISTER CREEK 44.0
END DESCRIPTION:
XS GIS Cut Line= 3
      2064796.74     13918361.15        2064575.       13918475.
      2063874.99     13918825.01
#Sta/Elev= 30
  4746.4 1383.87  4860.1 1383.94  4883.3 1384.53  4905.7 1382.38  4959.6 1365.87
  4981.8  1361.4  4990.9 1352.48  4991.4 1351.98  5017.1 1352.48    5018 1353.81
  5054.4 1363.45  5076.7 1361.37  5093.5 1362.17  5129.8 1376.98  5174.5 1383.19
  5196.9 1383.34  5396.7 1384.67  5540.7 1385.51  5578.9 1387.51  5599.4 1390.02
  5613.4    1389  5621.8 1391.18  5635.7 1396.55  5666.5 1413.33  5680.5 1417.17
  5702.8 1426.82  5725.2 1434.01    5750 1437.16  5756.6 1437.84  5778.3 1439.02
#Mann= 9 ,-1 , 0
  4746.4    .035       0  4860.1     .07       0  4990.9     .05       0
  5017.1     .07       0  5196.9    .035       0  5396.7     .07       0
  5578.9     .12       0    5750     .07       0  5756.6     .12       0
Bank Sta=4990.9,5017.1
XS Rating Curve= 0 ,0
Exp/Cntr=0.3,0.1

Type RM Length L Ch R = 1 ,24991   ,559,559,559
BEGIN DESCRIPTION:
EAST SISTER CREEK 43.0
END DESCRIPTION:
XS GIS Cut Line= 3
      2065147.41     13918410.68        2064225.       13918025.
      2063774.98     13918275.01
#Sta/Elev= 30
  4000.2 1389.05  4317.8 1382.38  4566.4 1381.12  4577.6 1379.66  4718.2 1376.25
  4739.9 1377.47  4772.4 1376.49  4802.5 1371.65  4807.9 1369.04  4837.4 1362.84
  4884.8 1362.65  4937.8 1358.87  4956.2 1355.25  4961.6 1356.94  4971.7 1351.89
  4972.2 1351.39  4999.1 1351.89  5013.7 1352.34  5058.5 1359.32  5148.7 1371.23
  5234.7 1378.78  5344.3 1383.69  5366.1 1386.32  5382.1 1390.32  5398.1 1398.84
  5403.8 1399.59  5419.8 1405.86  5447.3 1410.86  5491.9 1423.34  5514.8 1425.47
#Mann= 6 ,-1 , 0
  4000.2    .035       0  4577.6     .07       0  4971.7     .05       0
  4999.1     .07       0  5058.5     .12       0  5234.7     .07       0
Bank Sta=4971.7,4999.1
XS Rating Curve= 0 ,0
Exp/Cntr=0.3,0.1

Type RM Length L Ch R = 1 ,24432   ,222,222,222
BEGIN DESCRIPTION:
EAST SISTER CREEK 42.0
END DESCRIPTION:
XS GIS Cut Line= 3
      2064474.95       13917575.        2063925.       13917575.
      2063724.98     13917925.03
#Sta/Elev= 30
    4450 1381.26    4500  1377.5    4530 1369.97  4603.8 1367.88    4870 1369.11
    4910  1364.7    4930 1358.08    4970 1354.58    4980 1351.49  4983.7 1348.42
  4984.2 1347.92  5011.2 1348.42  5013.6  1350.3  5045.3 1354.51  5088.5 1356.23
  5115.8 1363.84  5169.1 1371.19  5174.9 1375.09  5190.7 1376.46  5196.5 1380.51
  5206.5 1380.92  5212.3 1385.68  5228.1 1387.16  5233.9 1392.89  5249.7 1394.07
  5255.5 1397.48  5271.3  1398.6  5277.1 1402.05  5314.5 1408.52  5403.1 1410.22
#Mann= 4 ,-1 , 0
    4450    .035       0  4603.8     .07       0  4983.7     .05       0
  5011.2     .07       0
Bank Sta=4983.7,5011.2
XS Rating Curve= 0 ,0
Exp/Cntr=0.3,0.1

Type RM Length L Ch R = 1 ,24210   ,329,329,329
BEGIN DESCRIPTION:
EAST SISTER CREEK 41.5
END DESCRIPTION:
XS GIS Cut Line= 3
      2064784.58     13917365.31      2063869.21     13917372.65
      2063692.22     13917370.83
#Sta/Elev= 30
  4084.6 1384.78  4204.2 1383.47  4244.2 1384.41  4322.9 1380.97  4359.1  1379.2
  4394.2 1376.96  4424.2 1370.49  4444.2 1369.99  4494.2 1365.69  4534.2 1365.56
  4604.2 1368.28    4774 1370.85  4844.2 1371.11  4944.2 1360.27  4954.2 1357.19
  4971.4  1354.3  4994.2 1353.56  4999.6 1350.61  5000.5 1347.47    5001 1346.97
    5028 1347.47  5034.2 1349.46  5054.2 1351.34  5084.2 1358.09  5104.2 1372.86
  5114.2 1382.43  5124.2 1398.76  5134.2 1401.13  5144.2 1401.52    5177 1399.78
#Mann= 7 ,-1 , 0
  4084.6    .035       0  4322.9     .07       0  4359.1    .035       0
    4774     .07       0  4971.4     .12       0  5000.5     .05       0
    5028     .12       0
Bank Sta=5000.5,5028
XS Rating Curve= 0 ,0
Exp/Cntr=0.3,0.1

Type RM Length L Ch R = 1 ,23881   ,546,546,546
BEGIN DESCRIPTION:
EAST SISTER CREEK 41.0
END DESCRIPTION:
XS GIS Cut Line= 3
      2064575.01       13916975.        2063875.       13917075.
      2063725.73     13917163.79
#Sta/Elev= 30
  4292.8 1382.79  4328.9 1382.44  4363.5  1379.8  4403.9  1371.9  4545.3 1362.19
    4606 1361.66  4727.2 1363.78  4818.1 1368.54  4859.4 1365.54  4868.6 1362.75
  4902.2 1358.56  4959.5 1353.56  4969.6 1350.72  4976.1  1344.4  4976.6  1343.9
  5003.6  1344.4  5007.7 1346.58  5029.7 1348.66    5035 1348.02  5044.7 1351.85
  5050.5 1351.17  5058.1 1353.43  5081.4 1354.19  5087.6 1356.33    5109 1359.24
  5119.9 1367.49  5124.6 1371.69  5130.4 1371.15    5146 1379.77  5173.6 1390.86
#Mann= 8 ,-1 , 0
  4292.8     .07       0  4328.9    .035       0  4859.4     .07       0
  4902.2    .035       0  4976.1    .035       0  5003.6    .035       0
  5029.7     .07       0  5119.9     .12       0
Bank Sta=4976.1,5003.6
XS Rating Curve= 0 ,0
Exp/Cntr=0.3,0.1

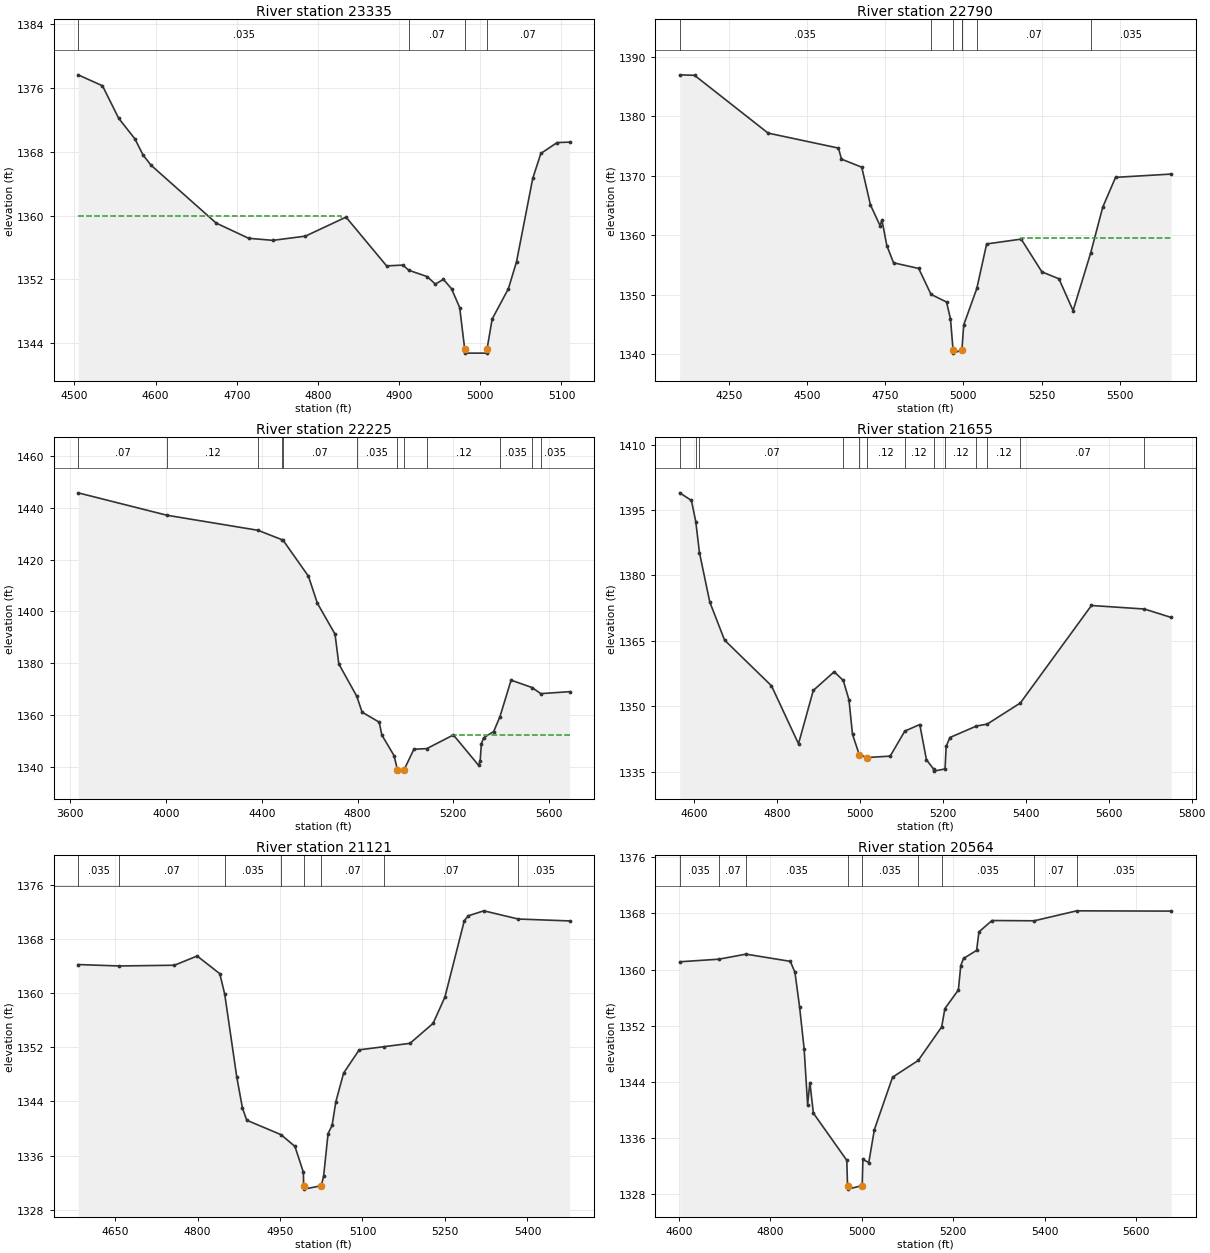
Type RM Length L Ch R = 1 ,23335   ,545,545,545
BEGIN DESCRIPTION:
EAST SISTER CREEK 40.0
END DESCRIPTION:
XS GIS Cut Line= 3
      2064424.97       13916575.        2063925.       13916575.
      2063819.68     13916573.85
#Sta/Elev= 30
  4504.6 1377.64  4534.6 1376.27  4554.6 1372.19  4574.6 1369.61  4584.6 1367.59
  4594.6  1366.3  4674.6 1359.07  4714.6 1357.16  4744.6  1356.9  4784.6 1357.43
  4834.6 1359.81  4884.6  1353.7  4904.6  1353.8    4912 1353.15  4934.6 1352.36
  4944.6 1351.42  4954.6 1352.01  4964.6 1350.83  4974.6 1348.48  4980.8 1343.27
  4981.3 1342.77  5007.8 1342.77  5008.3 1343.27  5014.6 1347.04  5034.6 1350.84
  5044.6 1354.21  5064.6 1364.66  5074.6 1367.79  5094.6 1369.15  5109.9 1369.21
#Mann= 4 ,-1 , 0
  4504.6    .035       0    4912     .07       0  4980.8     .05       0
  5008.3     .07       0
#XS Ineff= 2 , 0
       0  4828.9    1360               0
Permanent Ineff=
       F       F
Bank Sta=4980.8,5008.3
XS Rating Curve= 0 ,0
Exp/Cntr=0.3,0.1

Type RM Length L Ch R = 1 ,22790   ,565,565,565
BEGIN DESCRIPTION:
EAST SISTER CREEK 39.0
END DESCRIPTION:
XS GIS Cut Line= 3
      2064861.85     13916533.35        2064075.       13916075.
      2063418.29     13916008.36
#Sta/Elev= 30
  4093.6 1386.99    4141 1386.91  4375.9  1377.2  4600.9 1374.68  4610.7 1372.82
  4675.4 1371.47  4703.3 1365.12  4734.1 1361.63  4739.9 1362.61  4755.6  1358.3
  4777.1  1355.4  4857.4 1354.45  4896.9 1350.09  4946.4 1348.81  4959.1 1345.96
  4967.3 1340.72  4967.8 1340.22  4994.9 1340.72  4995.9 1340.93  5001.3 1344.95
  5043.3  1351.1  5074.6 1358.57  5185.1 1359.38  5251.2 1353.88  5305.8 1352.71
  5350.9 1347.36  5407.2 1357.06  5445.7 1364.75  5486.7 1369.76  5664.3 1370.31
#Mann= 7 ,-1 , 0
  4093.6    .035       0  4896.9     .07       0  4967.3    .035       0
  4994.9     .07       0  4995.9    .035       0  5043.3     .07       0
  5407.2    .035       0
#XS Ineff= 2 , 0
       0                 5185.94       0  1359.5
Permanent Ineff=
       F       F
Bank Sta=4967.3,4994.9
XS Rating Curve= 0 ,0
Exp/Cntr=0.3,0.1

Type RM Length L Ch R = 1 ,22225   ,570,570,570
BEGIN DESCRIPTION:
EAST SISTER CREEK 38.0
END DESCRIPTION:
XS GIS Cut Line= 3
      2065608.38       13915891.        2064275.       13915575.
      2063620.54     13915387.52
#Sta/Elev= 30
  3633.7 1445.81  4004.3 1437.15  4384.6 1431.33  4485.2 1427.67  4489.5 1427.45
  4595.1 1413.57  4632.2 1403.17    4706 1391.21  4721.8 1379.69  4796.9 1367.17
    4819 1361.04  4890.7 1357.16  4901.2 1352.25  4952.6 1344.22  4966.5 1338.75
    4967 1338.25  4994.1 1338.75  5035.2 1346.71  5089.4 1346.96  5200.1 1352.24
  5305.7 1340.45  5311.8 1342.27    5317 1348.88  5326.5 1351.16  5368.1 1353.53
  5394.3 1359.26  5440.9 1373.42  5528.7 1370.55  5564.7  1368.2  5684.8 1368.96
#Mann= 12 ,-1 , 0
  3633.7     .07       0  4004.3     .12       0  4384.6     .07       0
  4485.2    .035       0  4489.5     .07       0  4796.9    .035       0
  4966.5    .035       0  4994.1    .035       0  5089.4     .12       0
  5394.3    .035       0  5528.7     .07       0  5564.7    .035       0
#XS Ineff= 2 , 0
       0                 5194.73       0 1352.39
Permanent Ineff=
       F       F
Bank Sta=4966.5,4994.1
XS Rating Curve= 0 ,0
Exp/Cntr=0.3,0.1

Type RM Length L Ch R = 1 ,21655   ,534,534,534
BEGIN DESCRIPTION:
EAST SISTER CREEK 37.0
END DESCRIPTION:
XS GIS Cut Line= 3
      2064724.96     13915324.97        2064375.       13915075.
      2063663.92     13915326.77
#Sta/Elev= 30
  4566.1 1398.94  4594.3 1397.19  4604.8 1392.33  4613.7 1385.21  4638.6 1373.88
  4674.2 1365.16  4787.3 1354.68  4852.4 1341.38    4888 1353.61  4938.4  1357.9
  4960.3  1355.9    4974 1351.48  4982.6 1343.53  4998.8 1338.91  5017.4 1338.23
  5073.4 1338.55  5108.6 1344.29  5144.7  1345.8  5160.8 1337.71  5177.8 1335.61
  5178.3 1335.11  5205.6 1335.61  5208.3 1340.78  5217.3 1342.82  5281.4 1345.46
  5307.1 1345.89  5387.1 1350.74  5558.4  1373.1  5686.1 1372.29  5750.5 1370.36
#Mann= 13 ,-1 , 0
  4566.1     .07       0  4604.8     .12       0  4613.7     .07       0
  4960.3    .035       0  4998.8    .035       0  5017.4     .12       0
  5108.6     .12       0  5177.8    .035       0  5205.6     .12       0
  5281.4    .035       0  5307.1     .12       0  5387.1     .07       0
  5686.1    .035       0
Bank Sta=4998.8,5017.4
XS Rating Curve= 0 ,0
Exp/Cntr=0.3,0.1

Type RM Length L Ch R = 1 ,21121   ,557,557,557
BEGIN DESCRIPTION:
EAST SISTER CREEK 36.0
END DESCRIPTION:
XS GIS Cut Line= 3
        2064375.       13914775.        2063975.       13914875.
      2063646.57     13915226.95
#Sta/Elev= 30
  4582.8 1364.21  4657.8    1364    4758 1364.11  4799.3 1365.47  4840.5 1362.86
  4849.4 1359.85  4871.4 1347.58  4881.7 1343.02  4889.5 1341.23  4951.8  1339.1
  4977.1 1337.37  4992.5 1333.55    4993 1331.56  4993.5 1331.06  5025.1 1331.56
  5029.3 1332.98  5037.4 1339.27  5044.7 1340.46  5051.5 1343.95  5065.7  1348.2
    5094 1351.62  5138.5 1352.08  5186.4 1352.58  5228.4 1355.53  5249.9 1359.41
  5285.1 1370.67  5292.4 1371.41  5320.7 1372.14  5383.2 1370.93  5476.5 1370.65
#Mann= 8 ,-1 , 0
  4582.8    .035       0  4657.8     .07       0  4849.4    .035       0
  4951.8     .07       0    4993     .05       0  5025.1     .07       0
  5138.5     .07       0  5383.2    .035       0
Bank Sta=4993,5025.1
XS Rating Curve= 0 ,0
Exp/Cntr=0.3,0.1

Type RM Length L Ch R = 1 ,20564   ,518,518,518
BEGIN DESCRIPTION:
EAST SISTER CREEK 35.0
END DESCRIPTION:
XS GIS Cut Line= 3
      2064075.05     13914475.01        2063675.       13914425.
       2063499.5      13915073.2
#Sta/Elev= 30
  4601.8  1361.1  4687.4 1361.47  4746.8 1362.19  4843.7 1361.16  4853.8  1359.6
  4863.9  1354.7  4873.9  1348.7  4881.5 1340.76  4886.5  1343.9  4894.1 1339.54
  4967.2 1332.81  4968.8 1329.21  4969.3 1328.71  5000.9 1329.21  5002.4 1332.94
  5015.3  1332.5  5027.5 1337.19  5067.3 1344.66  5123.4 1347.04  5174.7 1351.82
  5181.7 1354.43  5211.2 1357.08  5216.4 1360.55  5222.5 1361.58  5251.1 1362.72
  5256.2 1365.36  5284.7 1366.98    5377 1366.94  5470.1 1368.36  5676.5 1368.32
#Mann= 9 ,-1 , 0
  4601.8    .035       0  4687.4     .07       0  4746.8    .035       0
  4968.8    .035       0  5000.9    .035       0  5123.4     .07       0
  5174.7    .035       0    5377     .07       0  5470.1    .035       0
Bank Sta=4968.8,5000.9
XS Rating Curve= 0 ,0
Exp/Cntr=0.3,0.1