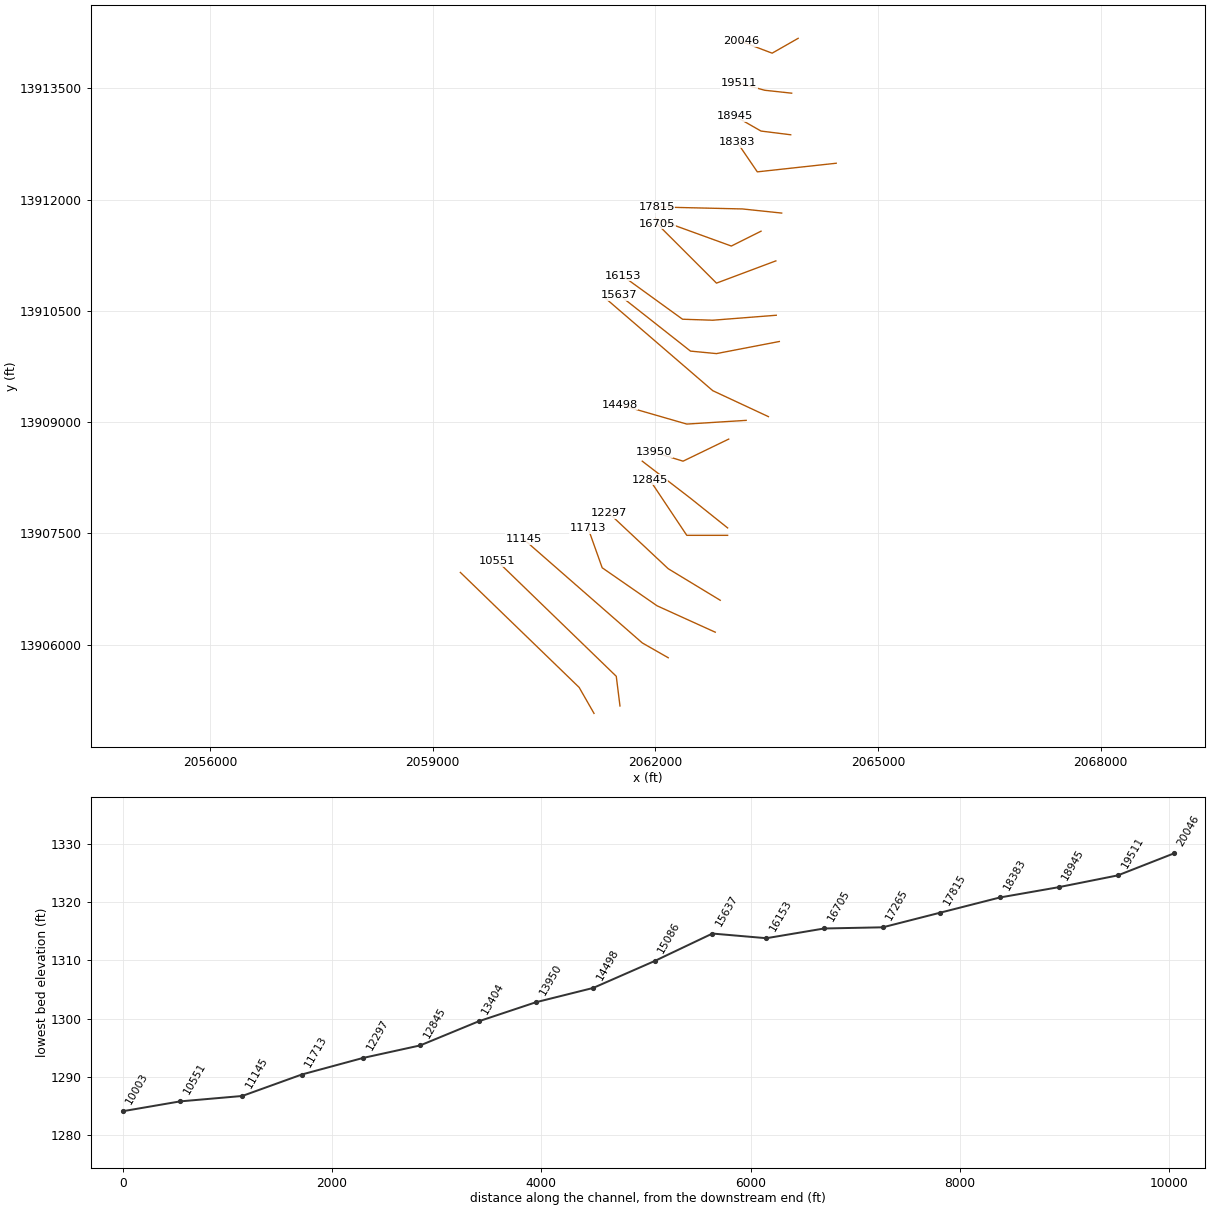
HEC-RAS study EAST SISTER CREEK.prj: EAST SISTER CREEK Base Level Engineering

--- EAST SISTER CREEK.g01 (geometry) --- (continued)

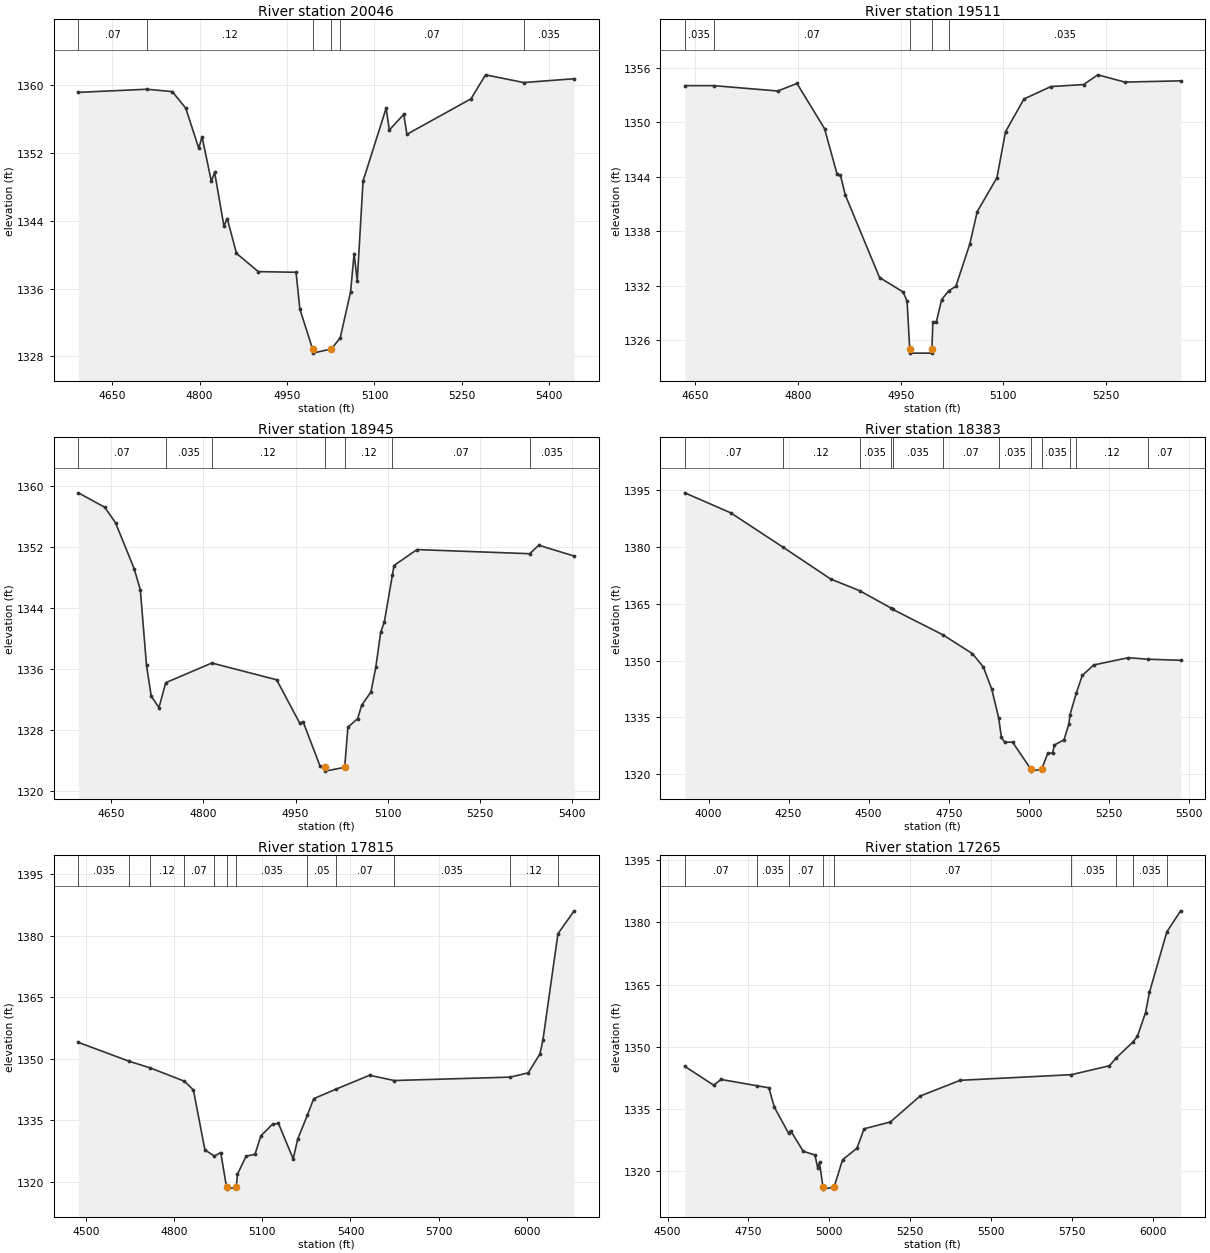
Type RM Length L Ch R = 1 ,20046   ,535,535,535
BEGIN DESCRIPTION:
EAST SISTER CREEK 34.0
END DESCRIPTION:
XS GIS Cut Line= 3
      2063924.98     13914174.99        2063575.       13913975.
      2063156.16     13914133.17
#Sta/Elev= 30
  4591.9 1359.15  4709.4 1359.52  4753.1 1359.24  4776.2 1357.29  4798.5 1352.56
  4804.2 1353.91  4820.1 1348.66  4825.8 1349.71  4841.7 1343.38  4847.4 1344.26
  4863.3 1340.15  4900.7    1338  4965.5 1337.92    4972 1333.59  4993.8 1328.88
  4994.4 1328.38  5026.3 1328.88  5041.3 1330.19  5059.1 1335.62  5065.1 1340.13
  5070.5 1336.94  5080.5  1348.7  5120.1 1357.29  5125.5  1354.7  5150.3 1356.56
  5155.7  1354.2  5265.7 1358.39  5290.6 1361.22  5356.3 1360.31  5442.7 1360.76
#Mann= 6 ,-1 , 0
  4591.9     .07       0  4709.4     .12       0  4993.8     .05       0
  5026.3     .07       0  5041.3     .07       0  5356.3    .035       0
Bank Sta=4993.8,5026.3
XS Rating Curve= 0 ,0
Exp/Cntr=0.3,0.1

Type RM Length L Ch R = 1 ,19511   ,566,566,566
BEGIN DESCRIPTION:
EAST SISTER CREEK 33.0
END DESCRIPTION:
XS GIS Cut Line= 3
      2063838.08     13913435.69        2063475.       13913475.
      2063128.29     13913570.76
#Sta/Elev= 30
  4634.4 1354.04  4676.8 1354.04  4770.3 1353.45  4798.4 1354.28  4838.7 1349.31
    4857 1344.31    4862 1344.19  4868.8 1342.06  4919.1 1332.93  4953.7 1331.33
  4959.4 1330.31  4963.2 1325.11  4963.7 1324.61  4995.2 1324.61  4995.7 1325.11
  4997.1 1328.06  5002.2 1328.06    5010 1330.51  5020.2 1331.46  5030.7 1331.96
  5051.1 1336.62  5061.9 1340.18  5090.7  1343.9  5103.3 1348.97  5130.2 1352.57
  5169.7 1353.94  5217.5 1354.16  5238.2 1355.23  5277.9 1354.43  5359.3 1354.57
#Mann= 5 ,-1 , 0
  4634.4    .035       0  4676.8     .07       0  4963.2     .05       0
  4995.7     .07       0  5020.2    .035       0
Bank Sta=4963.2,4995.7
XS Rating Curve= 0 ,0
Exp/Cntr=0.3,0.1

Type RM Length L Ch R = 1 ,18945   ,562,562,562
BEGIN DESCRIPTION:
EAST SISTER CREEK 32.0
END DESCRIPTION:
XS GIS Cut Line= 3
      2063825.05     13912874.99        2063425.       13912925.
      2063074.98     13913125.01
#Sta/Elev= 30
  4596.8 1359.11  4639.7 1357.22  4657.3 1355.18  4687.5 1349.17  4697.6 1346.39
  4707.7 1336.45  4715.3 1332.44  4727.9 1330.92    4739 1334.19  4813.9 1336.77
  4919.3 1334.57  4957.1 1328.84  4962.2 1329.09  4989.9 1323.24  4997.3 1323.08
  4997.9 1322.58  5029.9 1323.08  5035.2 1328.35  5051.1 1329.48  5057.5 1331.22
  5072.7 1332.99  5080.6 1336.25  5088.5 1340.82  5094.3 1342.11  5107.5 1348.31
  5110.1 1349.57  5147.5 1351.66  5330.8 1351.12  5345.5 1352.23  5403.1 1350.81
#Mann= 7 ,-1 , 0
  4596.8     .07       0    4739    .035       0  4813.9     .12       0
  4997.3     .05       0  5029.9     .12       0  5107.5     .07       0
  5330.8    .035       0
Bank Sta=4997.3,5029.9
XS Rating Curve= 0 ,0
Exp/Cntr=0.3,0.1

Type RM Length L Ch R = 1 ,18383   ,568,568,568
BEGIN DESCRIPTION:
EAST SISTER CREEK 31.0
END DESCRIPTION:
XS GIS Cut Line= 3
      2064437.78     13912491.25        2063375.       13912375.
      2063105.35     13912771.23
#Sta/Elev= 30
  3925.8 1394.25  4069.4 1388.96    4233 1379.88  4381.3 1371.51  4471.4 1368.43
  4570.2 1363.83  4575.6 1363.48  4731.3 1356.81  4823.9 1351.82    4858 1348.32
  4884.3 1342.46  4905.9 1334.89  4914.4 1329.82  4924.5 1328.44  4949.3 1328.47
  5006.6 1321.31  5007.3 1320.81  5040.1 1321.31  5059.3 1325.52  5074.2 1325.57
  5080.3  1327.7  5110.1 1329.09  5125.1 1333.23  5128.8 1335.72  5148.5 1341.42
    5167 1346.06    5203 1348.83  5310.7 1350.74  5372.4 1350.34  5474.2 1350.06
#Mann= 12 ,-1 , 0
  3925.8     .07       0    4233     .12       0  4471.4    .035       0
  4570.2     .07       0  4575.6    .035       0  4731.3     .07       0
  4905.9    .035       0  5006.6    .035       0  5040.1    .035       0
  5128.8     .07       0  5148.5     .12       0  5372.4     .07       0
Bank Sta=5006.6,5040.1
XS Rating Curve= 0 ,0
Exp/Cntr=0.3,0.1

Type RM Length L Ch R = 1 ,17815   ,550,550,550
BEGIN DESCRIPTION:
EAST SISTER CREEK 30.0
END DESCRIPTION:
XS GIS Cut Line= 3
       2063703.4     13911819.39        2063175.       13911875.
      2062018.73     13911901.77
#Sta/Elev= 30
  4473.5 1353.98  4644.6 1349.42  4718.8 1347.74  4834.1 1344.53  4865.3 1342.38
  4904.3 1327.79  4936.5 1326.26  4958.3 1327.13    4978 1318.71  4978.6 1318.21
  5011.6 1318.71  5014.8 1321.79  5044.8 1326.26  5074.8 1326.68  5094.8 1331.18
  5134.9 1334.06  5154.9 1334.21  5204.9 1325.59  5220.4 1330.43  5253.1 1336.21
  5274.9 1340.26  5351.7 1342.61  5464.9 1345.96  5549.1 1344.68  5943.7 1345.51
  6005.1 1346.55  6045.1 1351.19  6055.1 1354.55  6106.2 1380.46  6161.4 1386.04
#Mann= 12 ,-1 , 0
  4473.5    .035       0  4644.6     .07       0  4718.8     .12       0
  4834.1     .07       0  4936.5    .035       0    4978    .035       0
  5011.6    .035       0  5253.1     .05       0  5351.7     .07       0
  5549.1    .035       0  5943.7     .12       0  6106.2     .07       0
Bank Sta=4978,5011.6
XS Rating Curve= 0 ,0
Exp/Cntr=0.3,0.1

Type RM Length L Ch R = 1 ,17265   ,560,560,560
BEGIN DESCRIPTION:
EAST SISTER CREEK 29.0
END DESCRIPTION:
XS GIS Cut Line= 3
      2063425.03     13911575.01        2063025.       13911375.
      2062004.37     13911745.68
#Sta/Elev= 30
  4553.2 1345.29  4642.7 1340.75    4665 1342.14  4775.7 1340.63  4813.2 1340.13
  4829.9 1335.47  4874.2 1329.15  4880.3  1329.8  4919.4 1324.81  4955.7 1323.92
  4964.1 1320.83  4969.7 1322.13  4980.4 1316.19  4981.1 1315.69  5014.8 1316.19
    5041 1322.77  5085.6 1325.56  5107.6 1330.24  5188.7 1331.88  5280.6 1338.13
  5404.7 1341.93  5748.8 1343.29  5866.1 1345.44  5887.3 1347.35  5937.7 1351.08
  5952.6  1352.5  5977.9 1358.26  5989.9 1363.15  6043.8 1377.75  6086.3  1382.8
#Mann= 9 ,-1 , 0
  4553.2     .07       0  4775.7    .035       0  4874.2     .07       0
  4980.4     .05       0  5014.8     .07       0  5748.8    .035       0
  5887.3     .07       0  5937.7    .035       0  6043.8     .12       0
Bank Sta=4980.4,5014.8
XS Rating Curve= 0 ,0
Exp/Cntr=0.3,0.1

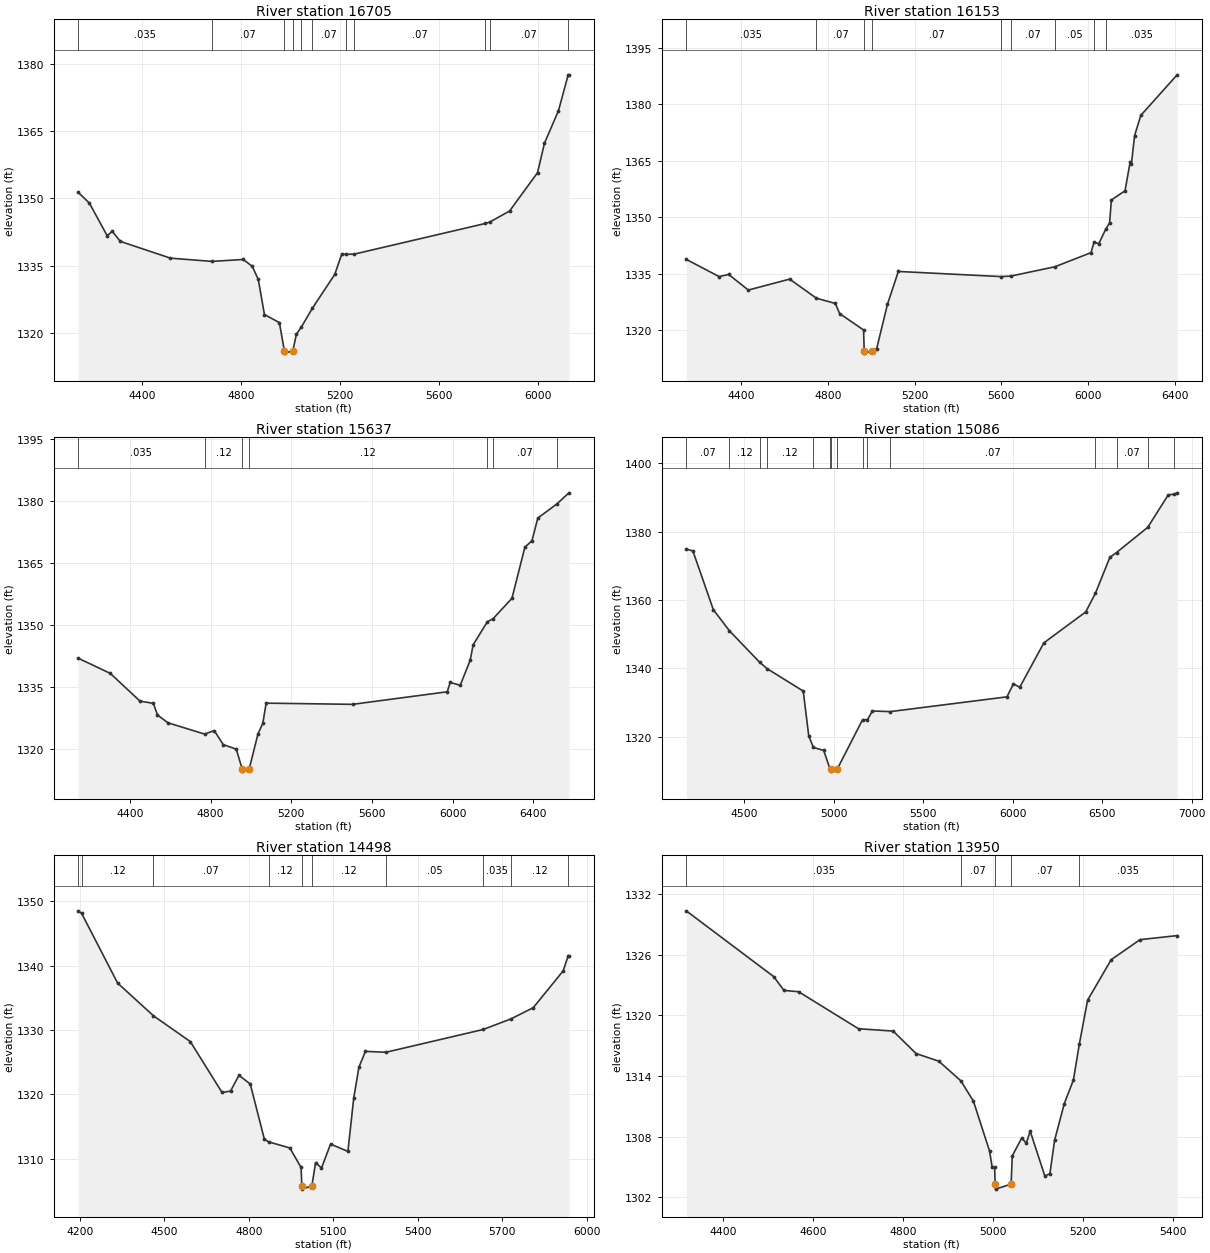
Type RM Length L Ch R = 1 ,16705   ,552,552,552
BEGIN DESCRIPTION:
EAST SISTER CREEK 28.0
END DESCRIPTION:
XS GIS Cut Line= 3
      2063624.97     13911174.99        2062825.       13910875.
      2062025.03     13911674.97
#Sta/Elev= 30
  4140.6 1351.35    4186 1348.96    4258 1341.69  4279.4 1342.64  4311.4  1340.4
  4514.4 1336.66  4681.7 1335.94    4809 1336.37  4845.4 1334.82  4869.5 1331.93
  4894.4  1324.1  4954.9 1322.29  4975.1 1315.99  4975.8 1315.49  5009.5 1315.99
  5023.3 1319.66  5043.6 1321.29  5088.5 1325.51  5178.8 1333.03  5207.1 1337.54
  5222.4 1337.51  5257.7 1337.56  5787.8 1344.39  5805.2 1344.69  5885.9 1347.16
  5999.1 1355.71  6027.3  1362.3  6083.9 1369.54  6123.1 1377.53  6126.3 1377.53
#Mann= 11 ,-1 , 0
  4140.6    .035       0  4681.7     .07       0  4975.1     .05       0
  5009.5     .07       0  5043.6    .035       0  5088.5     .07       0
  5222.4     .05       0  5257.7     .07       0  5787.8    .035       0
  5805.2     .07       0  6123.1     .12       0
Bank Sta=4975.1,5009.5
XS Rating Curve= 0 ,0
Exp/Cntr=0.3,0.1

Type RM Length L Ch R = 1 ,16153   ,516,516,516
BEGIN DESCRIPTION:
EAST SISTER CREEK 27.0
END DESCRIPTION:
XS GIS Cut Line= 4
      2063630.15     13910441.91        2062775.       13910375.
      2062367.61     13910388.36      2061559.43     13910973.76
#Sta/Elev= 30
  4146.9 1338.77  4298.6 1334.17  4342.6 1334.75  4432.9  1330.6  4623.5 1333.51
  4747.3 1328.42  4834.1 1327.05  4854.2 1324.33  4964.5 1319.98  4967.4 1314.32
  4968.1 1313.82  5001.9 1314.32  5024.7 1314.98  5074.7 1326.83  5124.7 1335.55
  5599.5 1334.18  5643.5 1334.32  5846.4 1336.79    6013 1340.55  6027.4 1343.41
  6048.6  1342.9  6081.9  1346.9  6098.9 1348.49    6107 1354.57    6170 1357.01
  6193.2 1364.57  6199.4 1364.12  6214.1 1371.71  6242.8 1377.07  6410.2 1387.86
#Mann= 9 ,-1 , 0
  4146.9    .035       0  4747.3     .07       0  4967.4     .05       0
  5001.9     .07       0  5599.5     .05       0  5643.5     .07       0
  5846.4     .05       0  6027.4     .07       0  6081.9    .035       0
Bank Sta=4967.4,5001.9
XS Rating Curve= 0 ,0
Exp/Cntr=0.3,0.1

Type RM Length L Ch R = 1 ,15637   ,551,551,551
BEGIN DESCRIPTION:
EAST SISTER CREEK 26.0
END DESCRIPTION:
XS GIS Cut Line= 4
      2063671.57     13910088.11        2062825.       13909925.
      2062474.71     13909958.64      2061516.59     13910713.98
#Sta/Elev= 30
  4142.9 1341.97  4302.4 1338.29    4450 1331.57  4516.2 1331.03  4536.6 1328.22
  4587.5 1326.34  4770.4 1323.59  4818.3 1324.43  4862.5 1321.05  4927.2 1319.94
  4956.8 1315.12  4957.5 1314.62  4991.3 1315.12  5035.2 1323.68  5058.8 1326.16
  5075.4 1331.08  5503.8 1330.79  5973.5 1333.83    5988  1336.1  6037.7  1335.4
  6087.4 1341.48  6101.8 1345.21  6172.4 1350.78  6200.6 1351.52  6294.2 1356.45
  6358.4 1368.83  6393.6 1370.41  6422.5 1375.89  6515.8 1379.26    6577    1382
#Mann= 7 ,-1 , 0
  4142.9    .035       0  4770.4     .12       0  4956.8     .05       0
  4991.3     .12       0  6172.4     .05       0  6200.6     .07       0
  6515.8     .12       0
Bank Sta=4956.8,4991.3
XS Rating Curve= 0 ,0
Exp/Cntr=0.3,0.1

Type RM Length L Ch R = 1 ,15086   ,588,588,588
BEGIN DESCRIPTION:
EAST SISTER CREEK 25.0
END DESCRIPTION:
XS GIS Cut Line= 3
      2063525.01       13909075.        2062775.       13909425.
      2061324.98     13910675.02
#Sta/Elev= 30
  4176.9 1374.87    4214 1374.32  4328.2 1357.13    4418 1350.97  4587.2 1341.74
  4628.4 1339.89  4830.4 1333.33  4861.1 1320.26  4887.1 1316.83  4944.6 1315.96
  4977.7 1310.92  4984.3 1310.41    4985 1309.91  5019.3 1310.41  5161.6 1324.94
  5189.2 1324.96  5216.9 1327.51  5316.3 1327.32  5968.4 1331.64  6004.5 1335.45
  6039.7 1334.44  6174.6 1347.43  6408.3 1356.48  6462.7 1361.95  6543.2 1372.43
  6580.7 1373.86  6754.9 1381.23  6869.1  1390.7  6903.2 1390.93    6919 1391.32
#Mann= 15 ,-1 , 0
  4176.9     .07       0    4418     .12       0  4587.2     .07       0
  4628.4     .12       0  4887.1     .07       0  4977.7    .035       0
  4984.3    .035       0  5019.3    .035       0  5161.6     .07       0
  5189.2    .035       0  5316.3     .07       0  6462.7     .12       0
  6580.7     .07       0  6754.9     .12       0  6903.2     .07       0
Bank Sta=4984.3,5019.3
XS Rating Curve= 0 ,0
Exp/Cntr=0.3,0.1

Type RM Length L Ch R = 1 ,14498   ,548,548,548
BEGIN DESCRIPTION:
EAST SISTER CREEK 24.0
END DESCRIPTION:
XS GIS Cut Line= 3
        2063225.       13909025.        2062425.       13908975.
      2061521.11     13909236.06
#Sta/Elev= 30
    4194 1348.51  4206.4 1348.13  4334.3 1337.29  4461.4 1332.21  4592.3  1328.2
    4705 1320.29  4735.1 1320.51  4765.1 1322.97  4805.2  1321.6  4855.3 1313.02
  4871.1 1312.61  4945.5 1311.68  4985.5 1308.64  4988.2 1305.78    4989 1305.28
  5023.7 1305.78  5037.2 1309.41    5058 1308.55  5090.1 1312.28  5151.7 1311.14
  5172.5 1319.44  5190.9 1324.23  5214.1 1326.68  5286.7 1326.54  5632.1 1330.08
  5730.3 1331.72  5809.5 1333.46  5915.6 1339.17  5933.1 1341.44  5936.4 1341.44
#Mann= 10 ,-1 , 0
    4194    .035       0  4206.4     .12       0  4461.4     .07       0
  4871.1     .12       0  4988.2     .05       0  5023.7     .12       0
  5286.7     .05       0  5632.1    .035       0  5730.3     .12       0
  5933.1    .035       0
Bank Sta=4988.2,5023.7
XS Rating Curve= 0 ,0
Exp/Cntr=0.3,0.1

Type RM Length L Ch R = 1 ,13950   ,546,546,546
BEGIN DESCRIPTION:
EAST SISTER CREEK 23.0
END DESCRIPTION:
XS GIS Cut Line= 3
      2062989.86     13908772.49        2062375.       13908475.
       2061984.7     13908595.42
#Sta/Elev= 30
  4317.4 1330.34    4512 1323.83  4534.6 1322.47  4567.2 1322.34  4700.5 1318.68
  4777.5 1318.45  4828.3 1316.23    4879 1315.47    4928 1313.53    4956 1311.51
  4991.9 1306.57  4997.7 1304.96  5003.1 1304.96  5004.3 1303.32  5005.1 1302.82
  5039.8 1303.32  5042.3 1306.11  5063.2 1307.86  5073.7 1307.37  5082.1 1308.56
  5114.7 1304.12    5126 1304.35  5136.5 1307.66  5157.9 1311.26  5178.4 1313.63
  5191.3 1317.13  5209.8  1321.5  5262.1  1325.5  5326.4 1327.49  5408.9 1327.89
#Mann= 5 ,-1 , 0
  4317.4    .035       0    4928     .07       0  5004.3     .05       0
  5039.8     .07       0  5191.3    .035       0
Bank Sta=5004.3,5039.8
XS Rating Curve= 0 ,0
Exp/Cntr=0.3,0.1

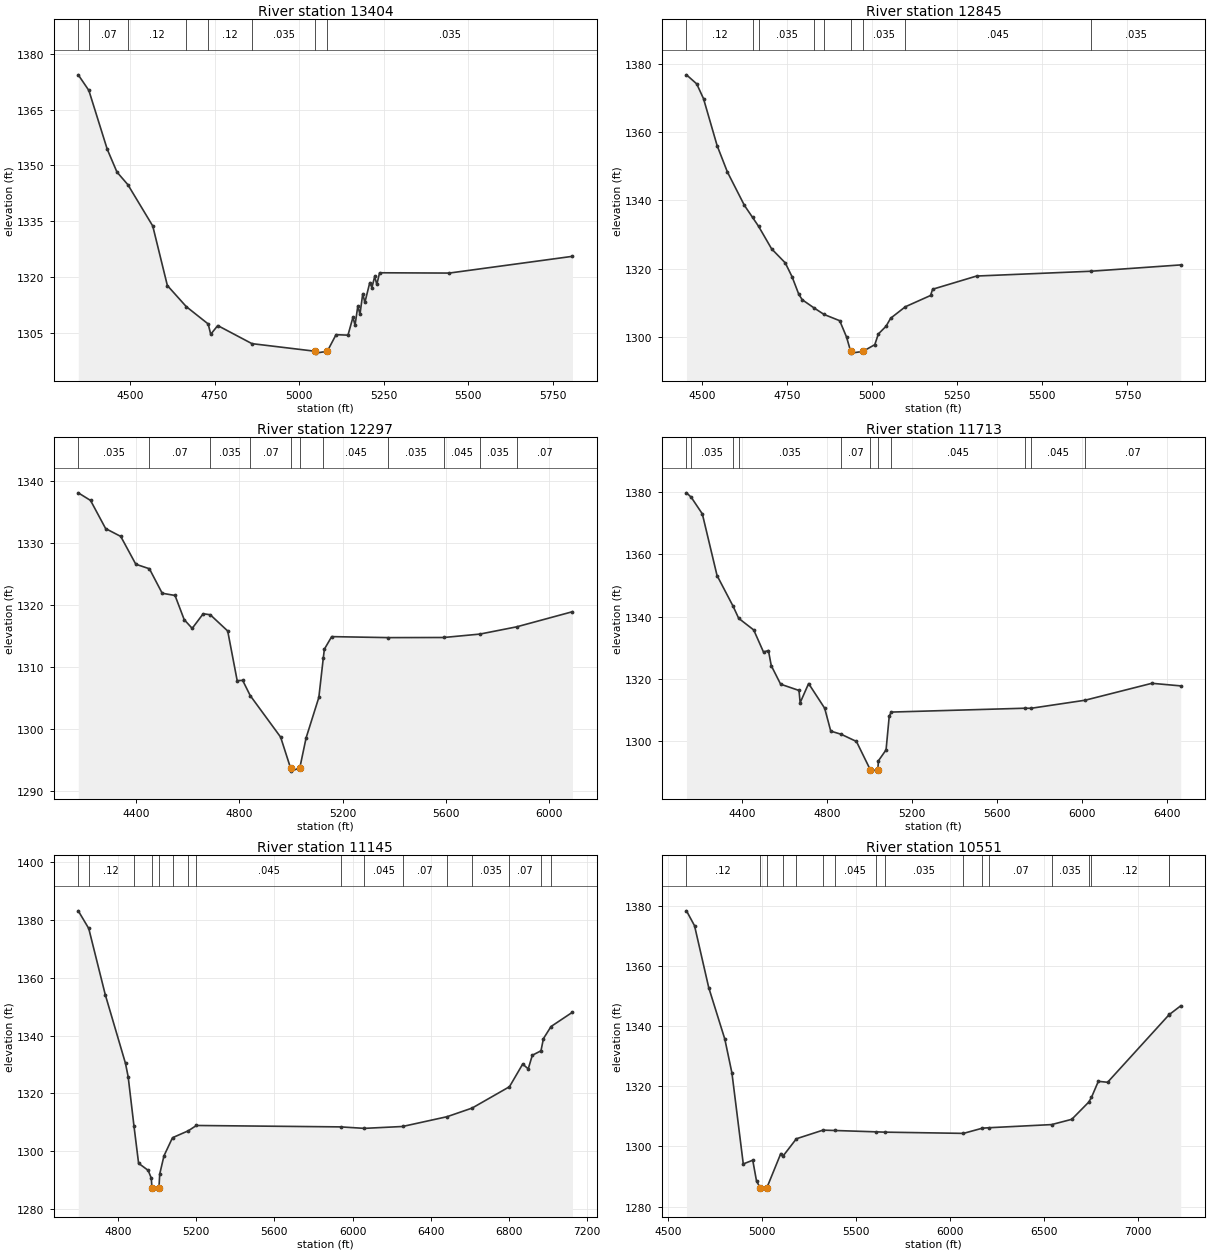
Type RM Length L Ch R = 1 ,13404   ,559,559,559
BEGIN DESCRIPTION:
EAST SISTER CREEK 22.0
END DESCRIPTION:
XS GIS Cut Line= 3
      2062974.98     13907575.02        2062475.       13907975.
      2061825.04     13908474.97
#Sta/Elev= 30
  4347.3 1374.36  4378.6 1370.17  4432.9 1354.37  4461.7 1348.22  4493.9 1344.83
  4567.4 1333.73  4610.6 1317.72  4666.5 1312.05  4731.2 1307.39  4738.7 1304.62
  4759.5 1306.96  4860.5  1302.1  5047.7 1300.05  5048.5 1299.55  5083.2 1300.05
    5109 1304.51  5144.3 1304.38  5158.9 1309.17  5165.2 1307.08  5173.4 1312.23
  5179.7 1309.97  5187.9 1315.53  5194.2 1313.19  5208.7  1318.5    5215 1317.16
  5223.2 1320.15  5229.5 1318.03  5237.7 1321.15  5443.4 1321.07  5807.6 1325.57
#Mann= 8 ,-1 , 0
  4347.3     .12       0  4378.6     .07       0  4493.9     .12       0
  4666.5    .035       0  4731.2     .12       0  4860.5    .035       0
  5047.7    .035       0  5083.2    .035       0
Bank Sta=5047.7,5083.2
XS Rating Curve= 0 ,0
Exp/Cntr=0.3,0.1

Type RM Length L Ch R = 1 ,12845   ,548,548,548
BEGIN DESCRIPTION:
EAST SISTER CREEK 21.0
END DESCRIPTION:
XS GIS Cut Line= 3
        2062975.       13907475.        2062425.       13907475.
      2061924.99     13908225.01
#Sta/Elev= 30
    4455 1376.71    4485 1374.07    4505 1369.75    4545 1356.02    4575 1348.36
    4625 1338.59  4649.2 1335.04  4666.7 1332.46    4705 1325.87    4745 1321.78
    4765 1317.74    4785 1312.55    4795    1311  4830.7 1308.54  4859.2  1306.7
    4905 1304.88    4925 1300.12  4937.2 1295.91    4938 1295.41  4972.9 1295.91
    5008 1297.88  5018.5 1301.01  5041.1 1303.27  5054.6 1305.61  5097.8 1308.96
  5171.8 1312.25  5177.8 1314.07    5307 1317.93  5642.4 1319.33  5906.4 1321.18
#Mann= 9 ,-1 , 0
    4455     .12       0  4649.2     .07       0  4666.7    .035       0
  4830.7     .07       0  4859.2    .035       0  4937.2    .035       0
  4972.9    .035       0  5097.8    .045       0  5642.4    .035       0
Bank Sta=4937.2,4972.9
XS Rating Curve= 0 ,0
Exp/Cntr=0.3,0.1

Type RM Length L Ch R = 1 ,12297   ,584,584,584
BEGIN DESCRIPTION:
EAST SISTER CREEK 20.0
END DESCRIPTION:
XS GIS Cut Line= 3
       2062875.8     13906599.61        2062175.       13907025.
      2061374.99     13907775.01
#Sta/Elev= 30
  4175.3 1338.15    4223 1336.92  4281.5 1332.38    4340 1331.12  4398.5 1326.63
  4451.2  1325.9  4500.8 1321.95  4550.6 1321.59  4586.1 1317.69  4617.1 1316.28
  4659.8 1318.64  4687.2 1318.48  4754.8 1315.86  4791.6 1307.85  4812.9 1307.89
  4842.1 1305.44    4960 1298.74  4998.5 1293.75  4999.3 1293.25  5034.3 1293.75
  5058.8 1298.61  5108.2 1305.14  5125.5  1311.5  5129.7 1312.93    5158 1314.95
  5378.2 1314.79  5592.7 1314.81  5732.7 1315.36  5875.3 1316.53  6091.7 1318.97
#Mann= 11 ,-1 , 0
  4175.3    .035       0  4451.2     .07       0  4687.2    .035       0
  4842.1     .07       0  4998.5     .05       0  5034.3     .07       0
  5125.5    .045       0  5378.2    .035       0  5592.7    .045       0
  5732.7    .035       0  5875.3     .07       0
Bank Sta=4998.5,5034.3
XS Rating Curve= 0 ,0
Exp/Cntr=0.3,0.1

Type RM Length L Ch R = 1 ,11713   ,568,568,568
BEGIN DESCRIPTION:
EAST SISTER CREEK 19.0
END DESCRIPTION:
XS GIS Cut Line= 4
      2062808.35     13906169.35        2062025.       13906525.
      2061285.02     13907038.09       2061095.6     13907570.64
#Sta/Elev= 30
  4139.8 1379.77    4162 1378.36  4214.4    1373  4283.6 1353.22  4359.3 1343.34
  4385.5 1339.47  4456.2 1335.74  4502.3 1328.64  4525.4 1329.14  4538.8 1324.28
  4582.8 1318.33  4669.3 1316.31  4674.8 1312.38  4714.6 1318.53  4790.2  1310.6
  4818.8 1303.26  4868.4 1302.23  4939.7 1299.93  5004.5 1290.91  5005.3 1290.41
  5040.3 1290.91  5043.3 1293.75  5079.1 1297.23    5094 1308.02  5103.1 1309.37
  5733.2 1310.61  5761.8 1310.59  6016.1 1313.18  6330.2 1318.61  6465.8 1317.78
#Mann= 11 ,-1 , 0
  4139.8     .07       0    4162    .035       0  4359.3     .07       0
  4385.5    .035       0  4868.4     .07       0  5004.5     .05       0
  5040.3     .07       0  5103.1    .045       0  5733.2    .035       0
  5761.8    .045       0  6016.1     .07       0
Bank Sta=5004.5,5040.3
XS Rating Curve= 0 ,0
Exp/Cntr=0.3,0.1

Type RM Length L Ch R = 1 ,11145   ,594,594,594
BEGIN DESCRIPTION:
EAST SISTER CREEK 18.0
END DESCRIPTION:
XS GIS Cut Line= 3
      2062174.98     13905825.01        2061825.       13906025.
      2060225.01     13907424.99
#Sta/Elev= 30
  4596.5 1383.23  4650.2 1377.11  4734.7 1354.17  4838.3 1330.31    4852 1325.67
  4881.4 1308.75  4905.3 1295.69  4954.2 1293.24  4970.1 1290.57  4973.7 1287.23
  4974.6 1286.73  5009.6 1287.23  5013.4 1291.96  5035.2 1298.28  5078.8 1304.56
  5159.7 1306.96  5201.1  1308.8  5938.9 1308.31  6060.6  1307.8    6256 1308.45
  6483.7 1311.84  6612.1 1314.84  6803.2 1322.24  6870.8 1330.09  6899.3 1328.42
  6920.1 1333.15  6964.4 1334.69  6977.1 1338.93    7016 1343.12  7125.6 1348.07
#Mann= 16 ,-1 , 0
  4596.5     .07       0  4650.2     .12       0  4881.4    .035       0
  4973.7    .035       0  5009.6    .035       0  5078.8    .045       0
  5159.7    .035       0  5201.1    .045       0  5938.9    .035       0
  6060.6    .045       0    6256     .07       0  6483.7    .045       0
  6612.1    .035       0  6803.2     .07       0  6964.4    .035       0
    7016     .07       0
Bank Sta=4973.7,5009.6
XS Rating Curve= 0 ,0
Exp/Cntr=0.3,0.1

Type RM Length L Ch R = 1 ,10551   ,548,548,548
BEGIN DESCRIPTION:
EAST SISTER CREEK 17.0
END DESCRIPTION:
XS GIS Cut Line= 3
        2061525.     13905174.99        2061475.       13905575.
        2059875.       13907125.
#Sta/Elev= 30
  4597.2 1378.25    4640 1373.31  4715.6 1352.75  4801.3 1335.62  4839.1 1324.39
  4899.5 1294.17  4949.9  1295.4  4970.1 1288.46  4989.5  1286.3  4990.3  1285.8
  5025.4  1286.3  5099.2 1297.62  5112.5 1296.89  5182.1 1302.53  5323.6 1305.39
  5386.5 1305.28  5606.5 1304.83  5651.7 1304.73  6071.5 1304.32  6172.5 1306.05
  6208.5  1306.2  6540.9 1307.24  6648.1 1308.99  6738.5 1314.71  6752.9 1316.26
  6789.5 1321.61  6838.9  1321.3  7163.5 1343.56  7168.3 1343.84    7228 1346.69
#Mann= 17 ,-1 , 0
  4597.2     .12       0  4989.5     .05       0  5025.4     .12       0
  5112.5    .035       0  5182.1    .045       0  5323.6    .035       0
  5386.5    .045       0  5606.5     .07       0  5651.7    .035       0
  6071.5     .07       0  6172.5    .035       0  6208.5     .07       0
  6540.9    .035       0  6738.5     .07       0  6752.9     .12       0
  7163.5     .07       0  7168.3     .12       0
Bank Sta=4989.5,5025.4
XS Rating Curve= 0 ,0
Exp/Cntr=0.3,0.1

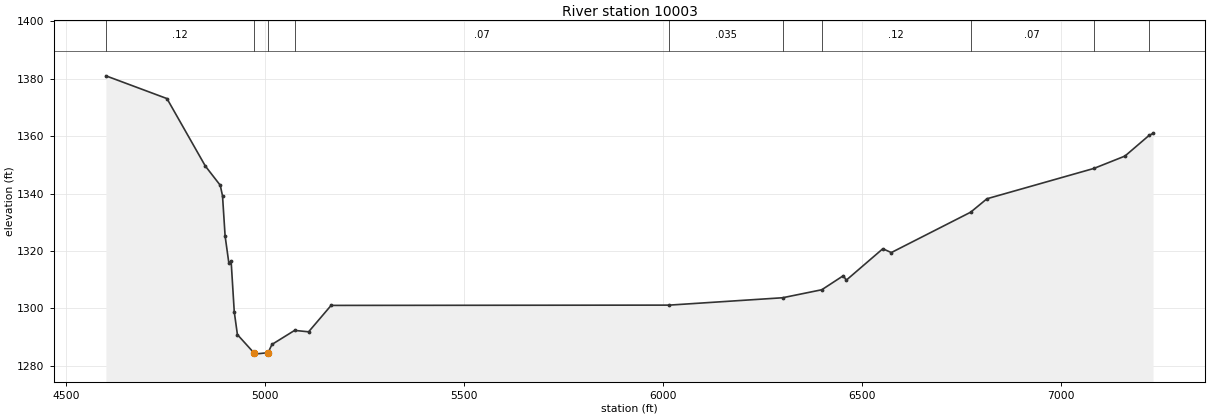
Type RM Length L Ch R = 1 ,10003   ,545,545,545
BEGIN DESCRIPTION:
EAST SISTER CREEK 16.0
END DESCRIPTION:
XS GIS Cut Line= 3
      2061175.02     13905074.96        2060975.       13905425.
      2059375.01     13906974.99
#Sta/Elev= 30
    4601 1380.98  4754.4 1373.06  4850.8 1349.58  4888.3 1342.88    4894 1339.19
  4900.5  1325.2  4909.9 1315.81  4915.6  1316.5  4923.5 1298.82  4931.4  1290.9
  4972.5 1284.61  4973.3 1284.11  5008.4 1284.61  5018.2 1287.48  5075.1 1292.37
  5110.3 1291.88  5166.8 1301.07  6016.6 1301.17  6300.9 1303.73  6399.6 1306.52
  6453.8 1311.42    6461 1309.84  6552.9 1320.79  6574.2 1319.46  6773.5 1333.51
  6814.5 1338.19  7083.2 1348.75  7161.2 1353.05  7221.6 1360.22  7231.8 1360.97
#Mann= 10 ,-1 , 0
    4601     .12       0  4972.5     .05       0  5008.4     .12       0
  5075.1     .07       0  6016.6    .035       0  6300.9     .07       0
  6399.6     .12       0  6773.5     .07       0  7083.2     .12       0
  7221.6     .07       0
Bank Sta=4972.5,5008.4
XS Rating Curve= 0 ,0
Exp/Cntr=0.3,0.1