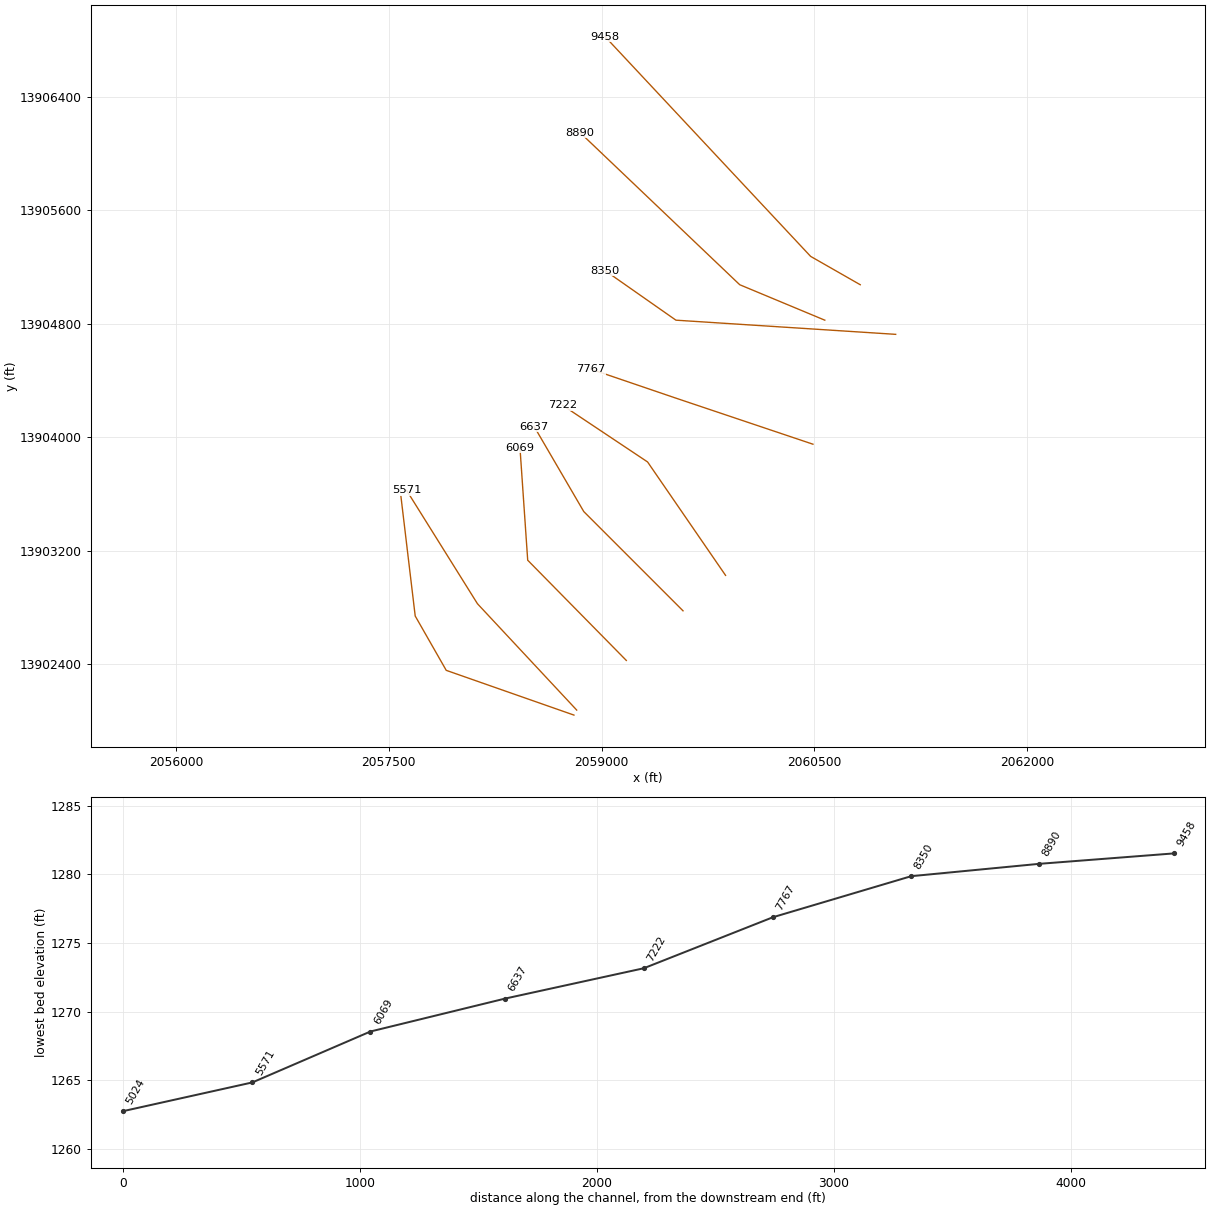
HEC-RAS study EAST SISTER CREEK.prj: EAST SISTER CREEK Base Level Engineering

--- EAST SISTER CREEK.g01 (geometry) --- (continued)

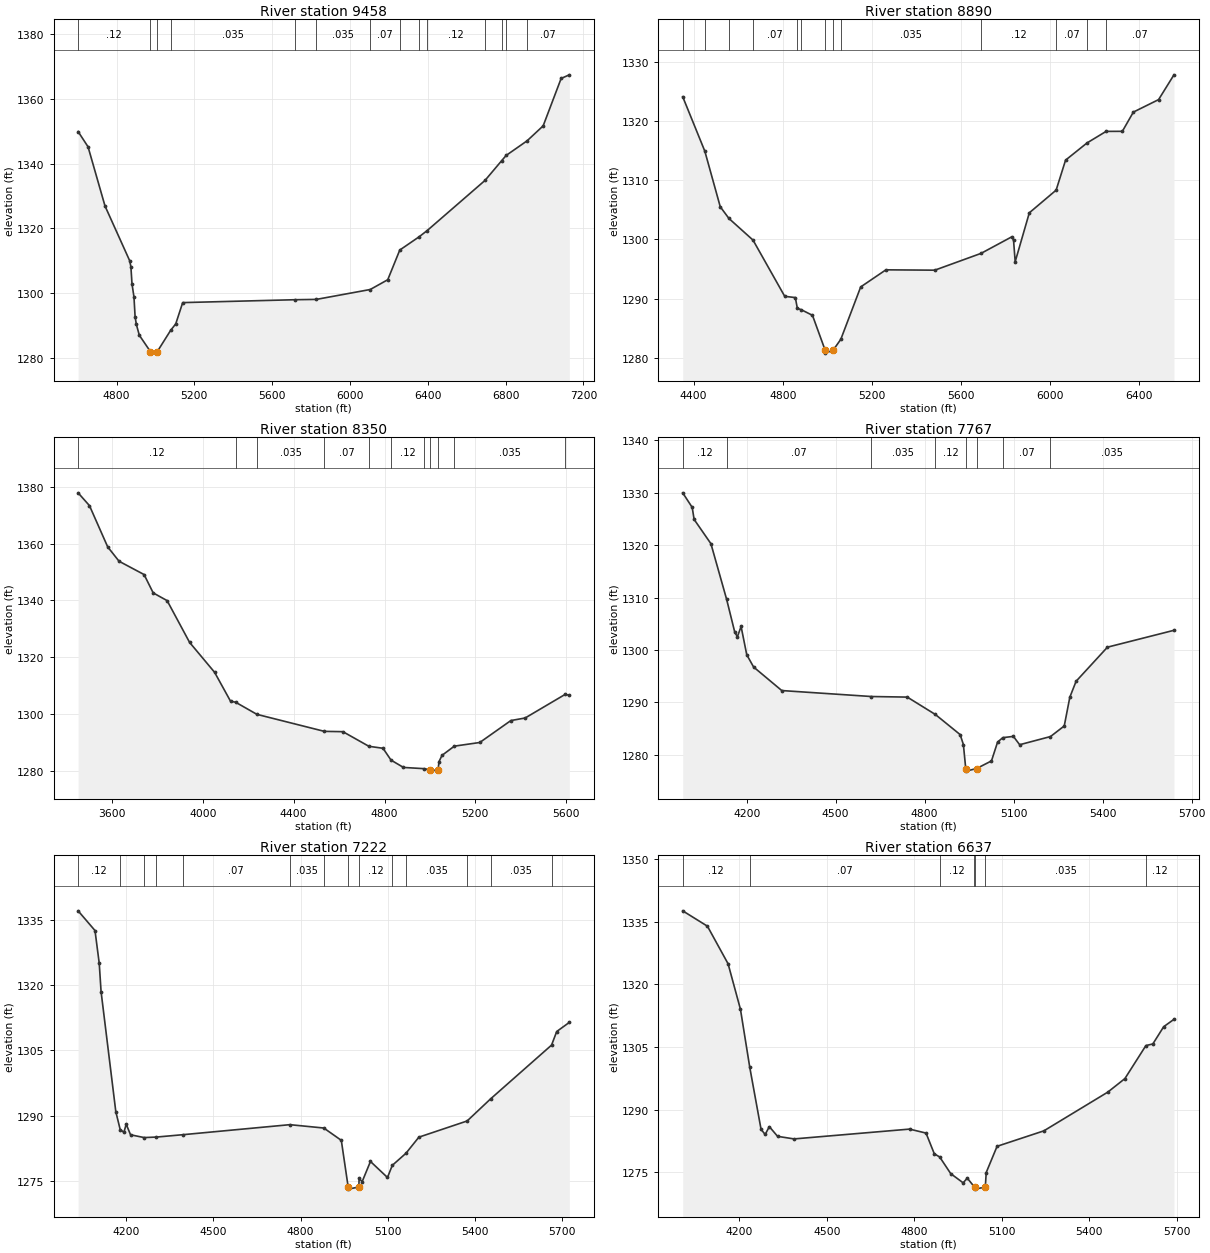
Type RM Length L Ch R = 1 ,9458    ,568,568,568
BEGIN DESCRIPTION:
EAST SISTER CREEK 15.0
END DESCRIPTION:
XS GIS Cut Line= 3
      2060825.01       13905075.        2060475.       13905275.
      2059025.01     13906824.98
#Sta/Elev= 30
  4602.4 1349.86  4653.5 1345.16  4740.6 1326.92  4867.3 1310.06  4873.8  1308.2
  4879.5 1302.87  4889.6 1298.86  4895.4 1292.76  4901.9 1290.39    4917 1287.06
  4973.9 1282.03  4974.7 1281.53  5009.8 1282.03  5078.1 1288.55  5104.4 1290.55
  5140.1 1297.11    5719    1298  5827.4  1298.1  6104.3 1301.15  6194.3 1304.16
  6256.2 1313.32  6355.3 1317.39  6396.4 1319.29  6694.6  1334.8  6779.8 1340.86
    6803 1342.49  6910.7    1347  6993.4 1351.62  7085.8 1366.24    7128 1367.35
#Mann= 14 ,-1 , 0
  4602.4     .12       0  4973.9     .05       0  5009.8     .12       0
  5078.1    .035       0    5719     .07       0  5827.4    .035       0
  6104.3     .07       0  6256.2    .035       0  6355.3     .07       0
  6396.4     .12       0  6694.6     .07       0  6779.8     .12       0
    6803    .035       0  6910.7     .07       0
Bank Sta=4973.9,5009.8
XS Rating Curve= 0 ,0
Exp/Cntr=0.3,0.1

Type RM Length L Ch R = 1 ,8890    ,540,540,540
BEGIN DESCRIPTION:
EAST SISTER CREEK 14.0
END DESCRIPTION:
XS GIS Cut Line= 3
      2060575.04     13904824.98        2059975.       13905075.
      2058849.63     13906147.17
#Sta/Elev= 30
  4350.8 1324.11  4450.1  1314.9  4519.3 1305.51  4558.3 1303.53  4666.4 1299.87
  4808.6 1290.37  4856.2 1290.16  4865.2 1288.34  4882.8 1288.11  4933.1 1287.16
  4989.9 1281.27  4990.8 1280.77  5025.9 1281.27  5060.3 1283.11  5149.5 1291.96
  5262.7 1294.85  5481.9 1294.79  5689.5 1297.63  5828.5 1300.45  5835.5 1299.81
  5842.7 1296.22  5906.2 1304.49  6026.5 1308.32  6068.8 1313.39  6165.2  1316.3
  6250.7 1318.25  6323.6 1318.26    6373 1321.51  6486.2 1323.62  6555.2 1327.81
#Mann= 13 ,-1 , 0
  4350.8     .12       0  4450.1     .07       0  4558.3     .12       0
  4666.4     .07       0  4865.2     .12       0  4882.8     .12       0
  4989.9     .05       0  5025.9     .12       0  5060.3    .035       0
  5689.5     .12       0  6026.5     .07       0  6165.2    .035       0
  6250.7     .07       0
Bank Sta=4989.9,5025.9
XS Rating Curve= 0 ,0
Exp/Cntr=0.3,0.1

Type RM Length L Ch R = 1 ,8350    ,583,583,583
BEGIN DESCRIPTION:
EAST SISTER CREEK 13.0
END DESCRIPTION:
XS GIS Cut Line= 3
        2061075.       13904725.        2059525.       13904825.
      2059025.04     13905174.97
#Sta/Elev= 30
  3450.6 1377.93  3500.7 1373.41  3580.9 1358.88    3631 1353.82  3741.2 1349.13
  3781.3 1342.67  3842.7 1339.94  3941.6 1325.23  4051.8 1314.68    4122 1304.49
    4144 1304.16  4238.2 1299.87  4535.2 1293.88  4616.8 1293.77  4731.2 1288.62
  4793.4 1287.92  4828.7 1283.75  4883.6 1281.17  4973.6 1280.74    4999 1280.37
  4999.9 1279.87  5035.7 1280.37  5040.4 1283.26  5053.1 1285.42  5107.5 1288.67
  5219.6 1289.96  5356.5 1297.69  5419.3 1298.59  5595.6 1306.91  5614.1  1306.6
#Mann= 11 ,-1 , 0
  3450.6     .12       0    4144     .07       0  4238.2    .035       0
  4535.2     .07       0  4731.2    .035       0  4828.7     .12       0
  4973.6     .12       0    4999     .05       0  5035.7     .12       0
  5107.5    .035       0  5595.6     .07       0
Bank Sta=4999,5035.7
XS Rating Curve= 0 ,0
Exp/Cntr=0.3,0.1

Type RM Length L Ch R = 1 ,7767    ,545,545,545
BEGIN DESCRIPTION:
EAST SISTER CREEK 12.0
END DESCRIPTION:
XS GIS Cut Line= 3
      2060491.51     13903950.17        2059525.       13904275.
      2058922.76     13904480.28
#Sta/Elev= 30
  3984.5    1330  4016.5 1327.22    4023 1324.92  4079.6 1320.29  4132.6 1309.66
  4160.2 1303.35  4168.9 1302.53  4181.3 1304.49  4200.4 1299.09  4223.5 1296.75
  4318.4 1292.26  4620.7 1291.12  4741.5 1291.01  4836.2 1287.69  4919.7 1283.85
  4930.6 1281.96  4938.5 1277.38  4939.4 1276.88  4975.3 1277.38  5025.3 1278.83
  5045.9 1282.43  5063.5 1283.27  5099.2 1283.51  5120.3 1281.92  5224.2 1283.48
  5270.6  1285.5  5289.4 1290.99  5310.5 1294.03  5416.2 1300.54  5640.4 1303.76
#Mann= 8 ,-1 , 0
  3984.5     .12       0  4132.6     .07       0  4620.7    .035       0
  4836.2     .12       0  4938.5     .05       0  4975.3     .12       0
  5063.5     .07       0  5224.2    .035       0
Bank Sta=4938.5,4975.3
XS Rating Curve= 0 ,0
Exp/Cntr=0.3,0.1

Type RM Length L Ch R = 1 ,7222    ,585,585,585
BEGIN DESCRIPTION:
EAST SISTER CREEK 11.0
END DESCRIPTION:
XS GIS Cut Line= 3
      2059874.99     13903025.01        2059325.       13903825.
      2058725.02     13904224.99
#Sta/Elev= 30
  4033.7 1337.06  4091.9 1332.53  4106.5 1324.99  4112.8 1318.52  4163.6 1290.93
  4178.6 1286.85  4191.4  1286.2  4199.4 1288.06  4214.3 1285.64  4261.1    1285
    4303 1285.11  4393.3 1285.65    4763 1287.96  4879.9 1287.19  4940.2 1284.36
  4963.8 1273.66  4964.7 1273.16  5000.6 1273.66  5001.5 1275.61    5012 1274.88
  5040.6 1279.51  5099.2 1275.83  5115.8 1278.62  5162.8 1281.39  5207.3 1285.09
  5373.6 1288.81  5454.3 1293.88  5664.3 1306.23  5682.1 1309.35  5725.6 1311.45
#Mann= 14 ,-1 , 0
  4033.7     .12       0  4178.6    .035       0  4261.1     .07       0
    4303    .035       0  4393.3     .07       0    4763    .035       0
  4879.9     .12       0  4963.8     .05       0  5000.6     .12       0
  5115.8     .07       0  5162.8    .035       0  5373.6     .12       0
  5454.3    .035       0  5664.3     .12       0
Bank Sta=4963.8,5000.6
XS Rating Curve= 0 ,0
Exp/Cntr=0.3,0.1

Type RM Length L Ch R = 1 ,6637    ,568,568,568
BEGIN DESCRIPTION:
EAST SISTER CREEK 10.0
END DESCRIPTION:
XS GIS Cut Line= 3
      2059574.99     13902775.01        2058875.       13903475.
      2058524.98     13904075.03
#Sta/Elev= 30
  4005.7 1337.58  4090.5  1333.9  4161.3  1324.9  4203.7 1314.02  4235.7 1300.09
  4274.4 1285.26  4288.5 1284.03  4302.7 1285.92    4331 1283.59  4387.5 1282.97
  4783.5 1285.32  4840.1 1284.37  4868.4 1279.42    4887 1278.64  4924.9 1274.65
  4967.4 1272.46  4981.5 1273.58  5005.2 1271.54  5006.6 1271.45  5007.5 1270.95
  5043.4 1271.45  5046.5 1274.93  5083.7  1281.2  5244.1  1284.9  5463.3 1294.17
    5522 1297.41  5594.1 1305.32  5617.9 1305.71  5655.1 1309.84  5690.3  1311.6
#Mann= 7 ,-1 , 0
  4005.7     .12       0  4235.7     .07       0    4887     .12       0
  5005.2    .035       0  5006.6     .05       0  5043.4    .035       0
  5594.1     .12       0
Bank Sta=5006.6,5043.4
XS Rating Curve= 0 ,0
Exp/Cntr=0.3,0.1

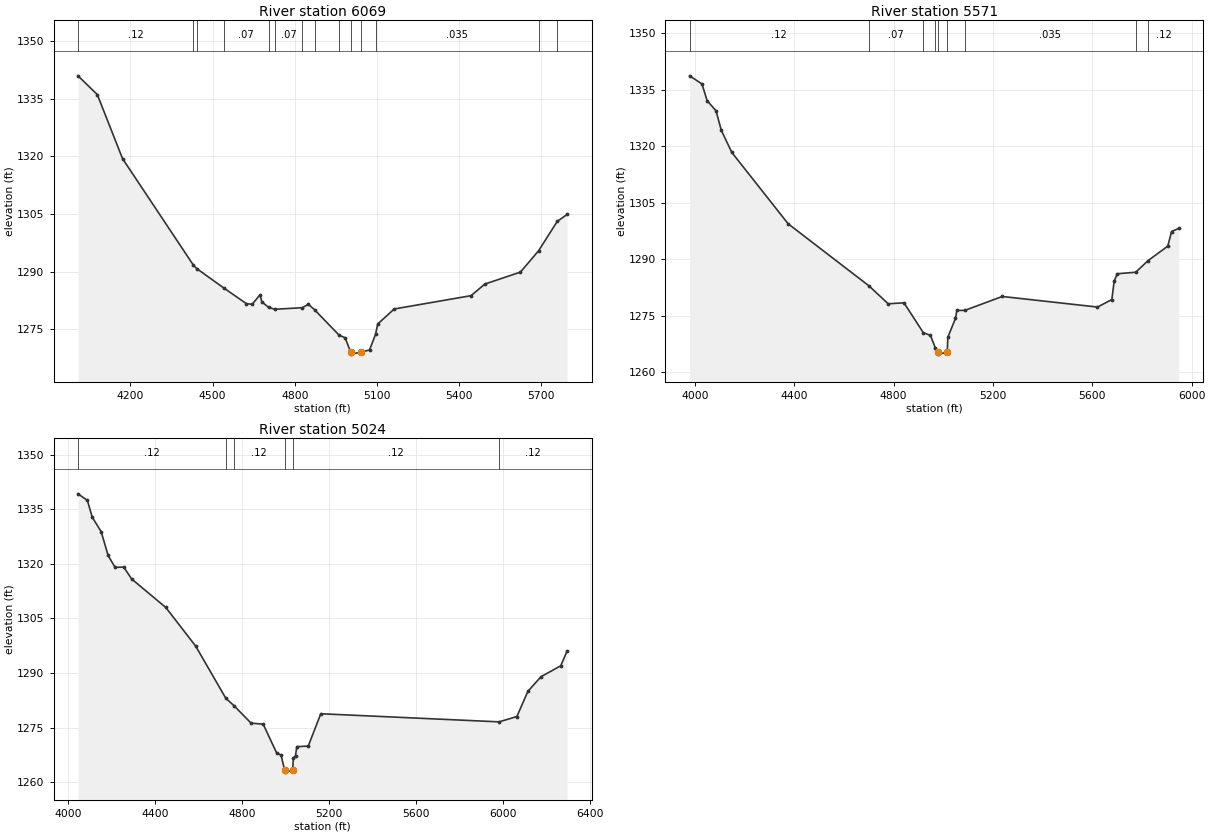
Type RM Length L Ch R = 1 ,6069    ,498,498,498
BEGIN DESCRIPTION:
EAST SISTER CREEK 9.0
END DESCRIPTION:
XS GIS Cut Line= 3
      2059174.97     13902425.03      2058479.48     13903131.88
        2058425.     13903924.98
#Sta/Elev= 30
  4008.3 1340.98  4078.9  1336.1  4170.9 1319.44  4429.6 1291.73  4442.4 1290.79
  4540.2  1285.8  4623.5 1281.68  4644.7 1281.53  4672.9 1283.97  4680.1 1282.15
  4704.5 1280.72  4727.6 1280.23  4827.8 1280.63  4849.8 1281.53  4872.8 1280.07
  4961.7 1273.51  4984.1  1272.8  5004.6 1269.05  5005.5 1268.55  5041.6 1269.05
  5073.2 1269.64  5095.1 1273.68  5103.3 1276.41  5163.4  1280.3  5444.1 1283.77
  5494.2 1286.78  5624.5  1289.9    5691 1295.48  5758.9  1303.1  5794.9  1304.9
#Mann= 14 ,-1 , 0
  4008.3     .12       0  4429.6     .07       0  4442.4     .12       0
  4540.2     .07       0  4704.5    .035       0  4727.6     .07       0
  4827.8     .12       0  4872.8     .07       0  4961.7     .12       0
  5004.6     .05       0  5041.6     .12       0  5095.1    .035       0
    5691     .07       0  5758.9    .035       0
Bank Sta=5004.6,5041.6
XS Rating Curve= 0 ,0
Exp/Cntr=0.3,0.1

Type RM Length L Ch R = 1 ,5571    ,547,547,547
BEGIN DESCRIPTION:
EAST SISTER CREEK 8.0
END DESCRIPTION:
XS GIS Cut Line= 3
      2058825.02     13902074.98        2058125.       13902825.
      2057625.02     13903624.97
#Sta/Elev= 30
  3978.8 1338.74  4028.4 1336.59  4049.4 1332.12  4085.1 1329.46  4106.1  1324.3
  4148.6  1318.4  4375.3 1299.46  4700.2    1283  4778.3 1278.21  4841.8 1278.47
  4919.6 1270.54  4948.3 1269.82  4968.4 1266.43  4979.1 1265.34  4980.1 1264.84
  5016.2 1265.34  5018.3  1269.3    5049 1274.31  5054.9 1276.45    5087 1276.46
  5237.6 1280.15  5620.9 1277.34  5678.7 1279.33  5688.1  1284.2  5700.5 1286.18
  5774.9 1286.59  5824.6 1289.67  5903.9 1293.51  5919.2 1297.39  5948.1 1298.24
#Mann= 9 ,-1 , 0
  3978.8     .12       0  4700.2     .07       0  4919.6     .12       0
  4968.4     .07       0  4979.1     .05       0  5016.2     .07       0
    5087    .035       0  5774.9     .07       0  5824.6     .12       0
Bank Sta=4979.1,5016.2
XS Rating Curve= 0 ,0
Exp/Cntr=0.3,0.1

Type RM Length L Ch R = 1 ,5024    ,0,0,0
BEGIN DESCRIPTION:
EAST SISTER CREEK 7.0
END DESCRIPTION:
XS GIS Cut Line= 4
      2058805.62     13902039.52      2057904.88     13902355.05
      2057685.95     13902738.41      2057585.06     13903584.04
#Sta/Elev= 30
  4045.6  1339.2  4088.6  1337.4  4111.3 1332.75  4152.2 1328.79    4184 1322.26
  4215.8 1319.01  4255.8 1319.07  4292.1 1315.81  4448.9 1307.99  4586.4 1297.36
  4724.9 1283.03  4762.7 1280.98  4840.9  1276.2  4896.6 1275.91  4958.6 1267.99
  4978.7 1267.45    4995 1263.24  4995.9 1262.74  5032.1 1263.24  5035.1 1266.54
  5045.2  1267.3    5051 1269.74  5103.6 1269.89  5161.2 1278.78  5980.8 1276.55
  6062.4 1278.02  6112.8 1284.93  6173.2 1288.96  6263.9 1291.96  6293.1 1296.03
#Mann= 6 ,-1 , 0
  4045.6     .12       0  4724.9     .07       0  4762.7     .12       0
    4995     .05       0  5032.1     .12       0  5980.8     .12       0
Bank Sta=4995,5032.1
XS Rating Curve= 0 ,0
Exp/Cntr=0.3,0.1

Chan Stop Cuts=-1
Use User Specified Reach Order=0
Composite Channel Slope=5