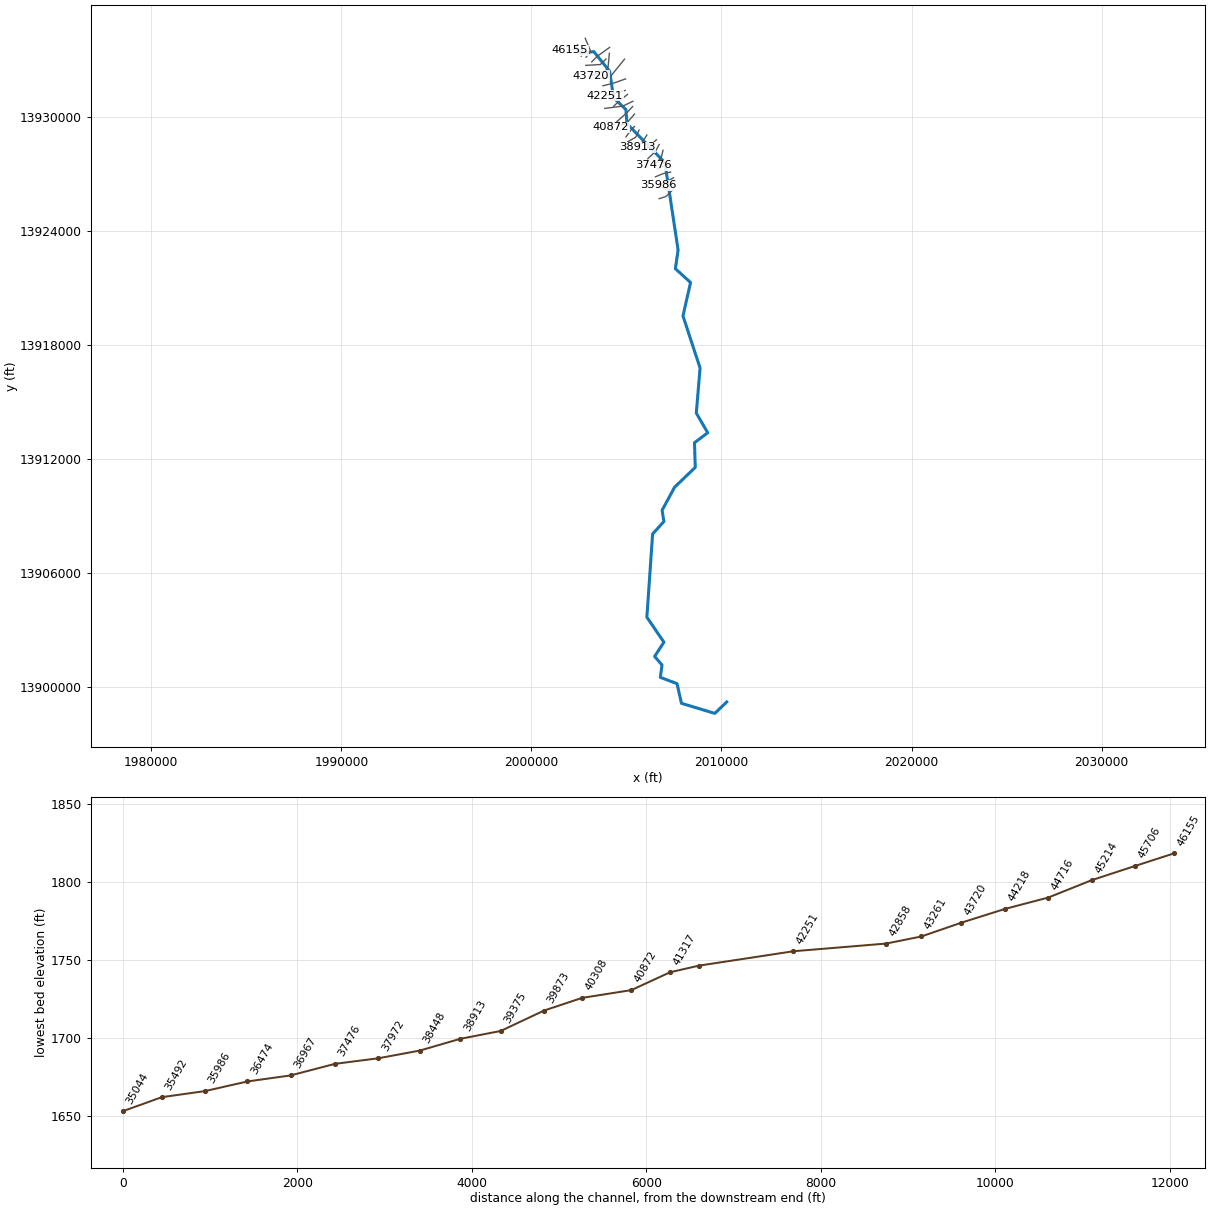
--- FLAT ROCK CREEK.prj (project) ---

Proj Title=FLAT ROCK CREEK Base Level Engineering
Current Plan=p01
Default Exp/Contr=0.3,0.1
English Units
Geom File=g01
Flow File=f01
Plan File=p01
Y Axis Title=Elevation
X Axis Title(PF)=Main Channel Distance
X Axis Title(XS)=Station
BEGIN DESCRIPTION:
FLAT ROCK CREEK
END DESCRIPTION:
DSS Export Rating Curves= 0
DSS Export Rating Curve Sorted= 0
DSS Export Volume Flow Curves= 0
DXF OffsetX= 0
DXF OffsetY= 0
DXF ScaleX= 1
DXF ScaleY= 10

--- FLAT ROCK CREEK.p01 (plan) ---

Plan Title=Multiple Run
Short Identifier=Multiple
Geom File=g01
Flow File=f01
Subcritical Flow
K Sum by GR= 0
Std Step Tol= 0.01
Critical Tol= 0.01
Num of Std Step Trials= 20
Max Error Tol= 0.3
Flow Tol Ratio= 0.001
Split Flow NTrial= 30
Split Flow Tol= 0.02
Split Flow Ratio= 0.02
Log Output Level= 0
Friction Slope Method= 1
Unsteady Friction Slope Method= 2
Unsteady Bridges Friction Slope Method= 1
Parabolic Critical Depth
Global Vel Dist=  1 , 1 , 1
Global Log Level= 0
CheckData=True
Encroach Param= -1, 0, 0, 0
BEGIN DESCRIPTION:
Multiple Run
END DESCRIPTION:

--- FLAT ROCK CREEK.f01 (steady flow) ---

Flow Title=Multiple
Program Version=4.10
Number of Profiles= 7
Profile Names=10-year,25-year,50-year,1pct_min,100-year,1pct_plu,500-year
River Rch & RM=FLAT ROCK CREEK,Reach-1         ,46155
     426     695     942     623    1242    2479    2137
River Rch & RM=FLAT ROCK CREEK,Reach-1         ,45706
    1078    1858    2612    1782    3556    7095    6536
River Rch & RM=FLAT ROCK CREEK,Reach-1         ,40308
    1176    2034    2866    1958    3907    7796    7205
River Rch & RM=FLAT ROCK CREEK,Reach-1         ,37476
    1639    2885    4112    2840    5666   11304   10676
River Rch & RM=FLAT ROCK CREEK,Reach-1         ,34544
    2128    3789    5445    3786    7553   15070   14434
River Rch & RM=FLAT ROCK CREEK,Reach-1         ,31139
    2567    4586    6605    4600    9177   18311   17592
River Rch & RM=FLAT ROCK CREEK,Reach-1         ,26670
    2744    4912    7082    4935    9847   19648   18904
River Rch & RM=FLAT ROCK CREEK,Reach-1         ,24702
    3089    5559    8044    5625   11223   22393   21691
River Rch & RM=FLAT ROCK CREEK,Reach-1         ,22262
    3434    6195    8977    6283   12536   25013   24277
River Rch & RM=FLAT ROCK CREEK,Reach-1         ,16411
    4330    7862   11440    8026   16014   31953   31109
River Rch & RM=FLAT ROCK CREEK,Reach-1         ,13958
    4679    8495   12357    8663   17285   34489   33528
River Rch & RM=FLAT ROCK CREEK,Reach-1         ,2499
    5143    9364   13650    9587   19128   38165   37233
Boundary for River Rch & Prof#=FLAT ROCK CREEK,Reach-1         , 1
Up Type= 0
Dn Type= 3
Dn Slope=0.005
Boundary for River Rch & Prof#=FLAT ROCK CREEK,Reach-1         , 2
Up Type= 0
Dn Type= 3
Dn Slope=0.005
Boundary for River Rch & Prof#=FLAT ROCK CREEK,Reach-1         , 3
Up Type= 0
Dn Type= 3
Dn Slope=0.005
Boundary for River Rch & Prof#=FLAT ROCK CREEK,Reach-1         , 4
Up Type= 0
Dn Type= 3
Dn Slope=0.005
Boundary for River Rch & Prof#=FLAT ROCK CREEK,Reach-1         , 5
Up Type= 0
Dn Type= 3
Dn Slope=0.005
Boundary for River Rch & Prof#=FLAT ROCK CREEK,Reach-1         , 6
Up Type= 0
Dn Type= 3
Dn Slope=0.005
Boundary for River Rch & Prof#=FLAT ROCK CREEK,Reach-1         , 7
Up Type= 0
Dn Type= 3
Dn Slope=0.005
DSS Import GetInterval= 0
DSS Import GetPeak= 0
DSS Import FillOption= 0

--- FLAT ROCK CREEK.g01 (geometry) ---

Geom Title=Existing Conditions
Program Version=4.10

River Reach=FLAT ROCK CREEK ,Reach-1
Reach XY= 30
        2002275.       13933725.      2002630.97     13933377.14
      2003281.52     13933467.32      2004114.52      13932434.8
      2004326.96     13931030.88      2004971.81     13930416.65
      2005030.41     13929672.58      2007022.76     13927619.07
      2007717.47     13923025.01      2007575.93     13922035.48
      2008374.92     13921309.61      2007974.76     13919549.92
      2008874.48     13916809.78       2008676.1     13914435.55
      2009275.32     13913399.89      2008580.82     13912877.31
      2008621.17     13911576.58      2007533.09     13910531.08
      2006877.14     13909319.03      2006971.26     13908726.52
      2006377.24     13908069.07      2006075.52     13903690.22
      2006972.94     13902369.14      2006482.56       13901625.
      2006872.94     13901169.15      2006783.02     13900521.69
      2007661.38     13900188.21      2007894.58     13899154.42
      2009650.12      13898624.7        2010275.       13899225.

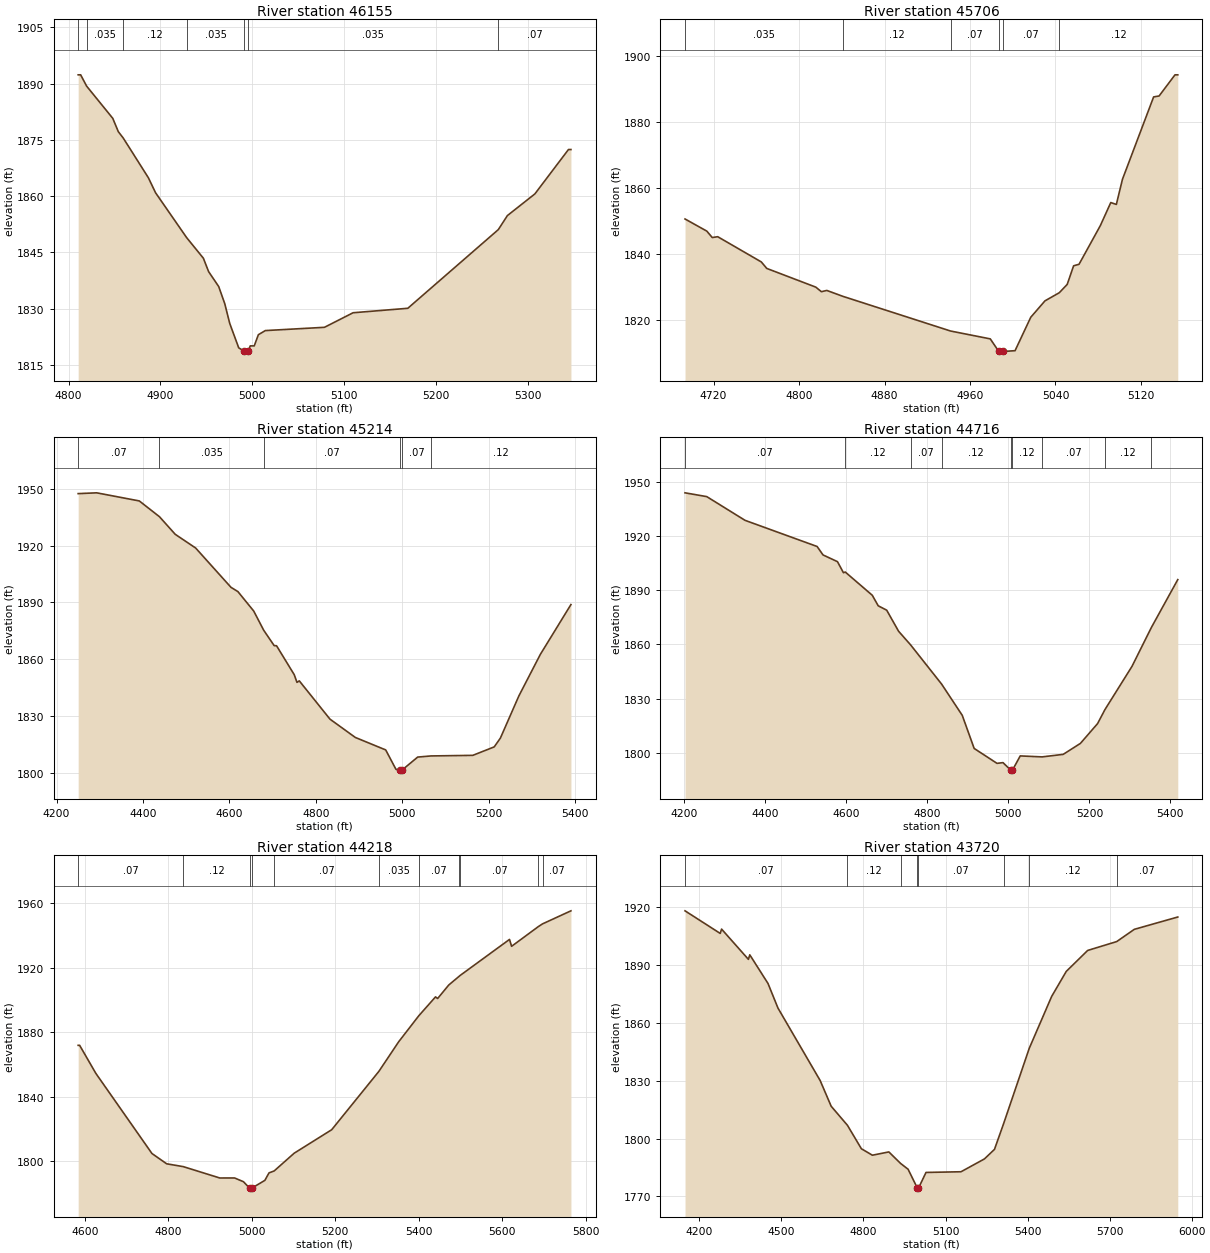
Type RM Length L Ch R = 1 ,46155   ,449,449,449
BEGIN DESCRIPTION:
FLAT ROCK CREEK_DS 85.0
END DESCRIPTION:
XS GIS Cut Line= 3
      2002425.01     13933825.01      2002348.39     13933651.69
      2002025.02     13933525.01
#Sta/Elev= 30
  4810.5 1892.32  4813.2 1892.32  4819.7 1889.31  4848.2 1880.72  4854.2 1877.18
  4859.6 1875.47    4887 1864.88  4894.8 1860.89  4928.7 1848.92  4946.9 1843.44
  4952.6 1839.87  4963.6 1835.89  4970.2 1831.32  4975.6 1826.07  4985.4 1819.56
  4991.5 1818.65  4991.7 1818.15  4995.5 1818.65    4998 1820.08  5002.3 1820.08
  5006.8 1823.06  5014.4 1824.16  5078.8 1825.03    5110 1828.91  5169.6  1830.1
  5268.2 1851.07  5278.1 1854.81    5308 1860.58  5344.6 1872.41  5347.3 1872.41
#Mann= 7 ,-1 , 0
  4810.5     .07       0  4819.7    .035       0  4859.6     .12       0
  4928.7    .035       0  4991.5    .035       0  4995.5    .035       0
  5268.2     .07       0
Bank Sta=4991.5,4995.5
XS Rating Curve= 0 ,0
Exp/Cntr=0.3,0.1

Type RM Length L Ch R = 1 ,45706   ,492,492,492
BEGIN DESCRIPTION:
FLAT ROCK CREEK_DS 84.0
END DESCRIPTION:
XS GIS Cut Line= 3
        2002725.     13933674.98      2002664.95     13933374.22
      2002624.99     13933224.98
#Sta/Elev= 30
  4693.3 1850.59  4713.7 1846.92  4718.8 1844.97  4723.9 1845.23  4764.7  1837.6
  4769.8 1835.64  4815.7 1829.98  4820.9  1828.6    4826 1828.98    4841  1827.2
  4941.9  1816.7    4979 1814.33    4987 1810.52  4987.3 1810.02    4991 1810.52
  5002.2 1810.76  5016.9 1820.87  5030.2 1825.83  5043.6 1828.29    5051  1830.8
    5057 1836.43  5062.1  1836.9    5082 1848.58  5091.8 1855.56    5097 1854.99
  5102.7 1862.58  5131.9 1887.51    5137 1887.79  5151.9 1894.19  5154.5 1894.19
#Mann= 6 ,-1 , 0
  4693.3    .035       0    4841     .12       0  4941.9     .07       0
    4987     .05       0    4991     .07       0  5043.6     .12       0
Bank Sta=4987,4991
XS Rating Curve= 0 ,0
Exp/Cntr=0.3,0.1

Type RM Length L Ch R = 1 ,45214   ,498,498,498
BEGIN DESCRIPTION:
FLAT ROCK CREEK_DS 83.0
END DESCRIPTION:
XS GIS Cut Line= 3
      2002831.43     13934165.19        2003125.     13933475.02
      2002875.03     13933175.03
#Sta/Elev= 30
    4250 1947.37  4292.8 1947.79  4391.5 1943.51  4438.1  1935.2  4474.6 1925.92
  4521.9 1918.68  4603.7 1897.94  4619.7  1895.7  4656.4 1885.41  4679.4 1875.32
  4703.7 1867.19  4709.1 1867.15  4750.1 1851.86  4756.4 1847.83  4761.8 1848.61
  4832.8 1828.43  4891.4 1818.78  4961.8 1812.19  4985.5 1801.96  4995.3 1801.51
  4995.6 1801.01  4999.3 1801.51  5035.8 1808.42  5066.7 1809.02  5163.4 1809.33
  5212.9 1813.79  5227.2 1818.42  5270.1 1840.72  5319.6 1862.54  5390.5 1888.86
#Mann= 6 ,-1 , 0
    4250     .07       0  4438.1    .035       0  4679.4     .07       0
  4995.3     .05       0  4999.3     .07       0  5066.7     .12       0
Bank Sta=4995.3,4999.3
XS Rating Curve= 0 ,0
Exp/Cntr=0.3,0.1

Type RM Length L Ch R = 1 ,44716   ,498,498,498
BEGIN DESCRIPTION:
FLAT ROCK CREEK_DS 82.0
END DESCRIPTION:
XS GIS Cut Line= 3
      2004116.15     13933689.49      2003468.96     13933222.47
      2003175.01     13932925.01
#Sta/Elev= 30
  4201.9 1943.75  4255.6 1941.65    4350 1928.54  4527.9 1914.08  4542.6  1909.4
  4578.2 1905.69  4592.9 1899.59  4597.4 1899.96  4664.1 1887.11  4678.8 1881.28
  4699.7 1878.86  4729.1  1867.2  4758.5 1859.73  4835.1 1838.04  4886.2 1820.72
  4915.6 1802.41    4972 1794.17  4986.8 1794.57  5006.1 1790.37  5006.4 1789.87
  5010.1 1790.37  5029.3 1798.28  5083.3 1797.74  5135.4 1799.14  5177.8 1805.19
  5220.3 1816.17  5238.4 1823.89  5305.1 1847.77  5353.1 1869.32  5418.2 1895.77
#Mann= 9 ,-1 , 0
  4201.9     .07       0  4597.4     .12       0  4758.5     .07       0
  4835.1     .12       0  5006.1     .05       0  5010.1     .12       0
  5083.3     .07       0  5238.4     .12       0  5353.1     .07       0
Bank Sta=5006.1,5010.1
XS Rating Curve= 0 ,0
Exp/Cntr=0.3,0.1

Type RM Length L Ch R = 1 ,44218   ,498,498,498
BEGIN DESCRIPTION:
FLAT ROCK CREEK_DS 81.0
END DESCRIPTION:
XS GIS Cut Line= 3
      2003924.99     13933074.99      2003626.43     13932785.45
      2002862.69     13932741.58
#Sta/Elev= 30
  4584.1 1871.77  4587.6 1871.77  4626.4 1854.38  4760.9 1804.64  4796.2 1798.25
  4835.8 1796.51  4923.5 1789.45    4959 1789.46  4980.1 1787.15  4995.5 1783.04
  4995.8 1782.54  4999.5 1783.04  5031.5 1787.98  5041.5 1792.63  5053.7  1793.8
  5101.6  1804.8  5191.7 1819.41  5304.7 1855.59    5352  1873.9  5400.3 1890.08
  5440.5 1901.83  5445.5  1900.8  5472.2 1909.19  5497.5 1914.68  5499.8 1915.18
  5617.8 1937.48  5622.8  1933.2  5687.1 1945.47    5697 1947.13    5765 1955.22
#Mann= 11 ,-1 , 0
  4584.1     .07       0  4835.8     .12       0  4995.5     .05       0
  4999.5     .12       0  5053.7     .07       0  5304.7    .035       0
  5400.3     .07       0  5497.5    .035       0  5499.8     .07       0
  5687.1    .035       0    5697     .07       0
Bank Sta=4995.5,4999.5
XS Rating Curve= 0 ,0
Exp/Cntr=0.3,0.1

Type RM Length L Ch R = 1 ,43720   ,459,459,459
BEGIN DESCRIPTION:
FLAT ROCK CREEK_DS 80.0
END DESCRIPTION:
XS GIS Cut Line= 3
      2004102.27     13933377.03      2004021.68     13932528.34
      2003133.49     13932192.96
#Sta/Elev= 30
  4147.5 1918.06  4276.2 1906.34  4281.2 1908.59  4379.3  1892.9  4384.3 1895.25
  4450.9  1880.4  4487.4 1867.63  4641.7 1830.05  4681.9 1816.74  4741.6 1806.82
  4792.4 1794.69  4832.6 1791.34  4892.9 1793.04  4935.8 1787.07  4963.2 1784.07
  4997.2 1774.25  4997.4 1773.75  5001.2 1774.25  5028.7  1782.4  5156.8 1782.76
  5242.3 1789.41  5279.1 1794.36  5312.2 1807.59  5406.2 1846.75  5488.2 1873.67
  5541.6 1886.65  5619.9 1897.52  5726.2 1902.12  5790.4 1908.46  5949.4 1914.85
#Mann= 8 ,-1 , 0
  4147.5     .07       0  4741.6     .12       0  4935.8     .07       0
  4997.2     .05       0  5001.2     .07       0  5312.2     .07       0
  5406.2     .12       0  5726.2     .07       0
Bank Sta=4997.2,5001.2
XS Rating Curve= 0 ,0
Exp/Cntr=0.3,0.1

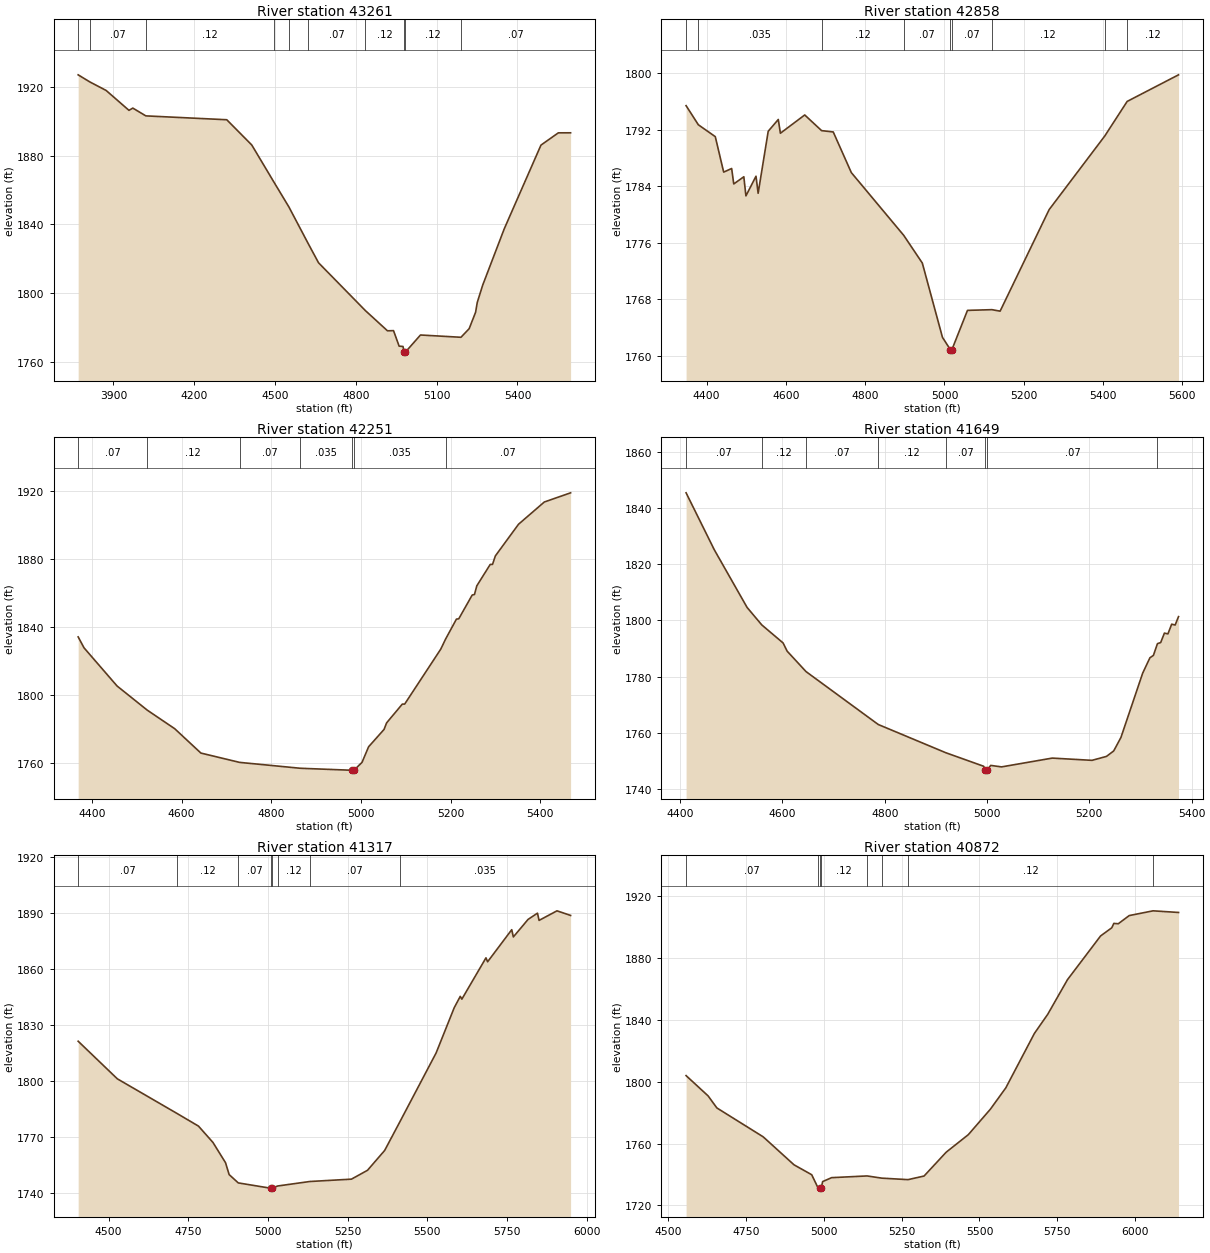
Type RM Length L Ch R = 1 ,43261   ,403,403,403
BEGIN DESCRIPTION:
FLAT ROCK CREEK_DS 79.0
END DESCRIPTION:
XS GIS Cut Line= 3
       2004897.4     13933067.96      2004124.86     13932109.94
      2003529.66     13932061.05
#Sta/Elev= 30
  3769.3    1927  3812.7 1922.86  3873.1  1917.9  3957.9 1906.31  3972.2 1907.62
  4020.5 1903.09  4320.9 1900.84  4413.7 1886.14  4495.2 1864.72  4551.6 1850.03
  4621.7 1829.15  4661.6 1817.52  4835.4 1789.68  4917.5  1777.9  4939.9    1778
  4960.7 1768.97  4975.1 1768.77  4979.5  1765.4  4979.7  1764.9  4983.5  1765.4
    5040 1775.46  5190.3 1774.13  5220.6 1779.12  5244.6 1788.71  5250.7  1794.4
  5270.8 1804.45    5351 1837.34  5487.2 1886.06  5551.7 1893.21  5597.2 1893.23
#Mann= 10 ,-1 , 0
  3769.3     .12       0  3812.7     .07       0  4020.5     .12       0
  4495.2     .07       0  4551.6     .12       0  4621.7     .07       0
  4835.4     .12       0  4979.5     .05       0  4983.5     .12       0
  5190.3     .07       0
Bank Sta=4979.5,4983.5
XS Rating Curve= 0 ,0
Exp/Cntr=0.3,0.1

Type RM Length L Ch R = 1 ,42858   ,1062,1062,1062
BEGIN DESCRIPTION:
FLAT ROCK CREEK_DS 78.0
END DESCRIPTION:
XS GIS Cut Line= 3
      2004954.23     13932030.29       2004334.9     13931807.55
       2003768.2     13931668.01
#Sta/Elev= 30
  4348.4 1795.44  4379.3 1792.73    4422 1791.05  4443.2 1786.02  4463.3 1786.53
  4468.6 1784.34    4494 1785.36  4499.3 1782.65  4524.7 1785.44  4530.1 1783.02
  4555.5 1791.81  4580.9 1793.48  4586.2 1791.53  4647.6 1794.12  4690.1  1791.9
  4719.5 1791.71  4765.1 1785.95  4897.3 1777.05  4944.1 1773.13  4994.9  1762.6
  5014.8 1760.86    5015 1760.36  5018.8 1760.86    5058 1766.42  5119.7 1766.52
  5140.3 1766.31  5263.9  1780.7  5404.1 1791.13  5460.7 1796.04  5590.2 1799.81
#Mann= 9 ,-1 , 0
  4348.4     .07       0  4379.3    .035       0  4690.1     .12       0
  4897.3     .07       0  5014.8     .05       0  5018.8     .07       0
  5119.7     .12       0  5404.1     .07       0  5460.7     .12       0
Bank Sta=5014.8,5018.8
XS Rating Curve= 0 ,0
Exp/Cntr=0.3,0.1

Type RM Length L Ch R = 1 ,42251   ,1081,1081,1081
BEGIN DESCRIPTION:
FLAT ROCK CREEK_DS 77.0
END DESCRIPTION:
XS GIS Cut Line= 3
      2004932.52     13931423.53       2004324.9     13931254.84
      2003872.78     13931135.13
#Sta/Elev= 30
  4369.4 1834.34  4382.5  1827.9  4456.2 1805.47  4523.3 1791.32  4584.8 1780.36
  4643.1 1766.06  4729.4 1760.58  4864.9 1757.12  4980.5 1755.94  4980.8 1755.44
  4984.5 1755.94  5002.5 1760.59  5017.2 1769.75  5051.6 1779.93  5057.4 1783.82
  5092.4 1794.84  5097.6 1794.83  5178.1 1827.13  5188.9 1833.06  5213.1 1844.79
  5218.3 1844.98  5248.2 1858.93  5253.3 1859.25  5258.5 1864.33  5288.4 1876.91
  5293.6 1876.97  5299.9 1881.93  5351.6 1900.55  5409.1 1913.62  5467.7 1919.01
#Mann= 7 ,-1 , 0
  4369.4     .07       0  4523.3     .12       0  4729.4     .07       0
  4864.9    .035       0  4980.5    .035       0  4984.5    .035       0
  5188.9     .07       0
Bank Sta=4980.5,4984.5
XS Rating Curve= 0 ,0
Exp/Cntr=0.3,0.1

Type RM Length L Ch R = 1 ,41649   ,332,332,332
BEGIN DESCRIPTION:
FLAT ROCK CREEK_DS 76.0
END DESCRIPTION:
XS GIS Cut Line= 3
        2005061.     13931216.09      2004601.75     13930848.41
      2004328.89     13930592.05
#Sta/Elev= 30
  4411.7 1845.56  4466.8 1825.25  4530.9 1804.67  4559.6 1798.43  4601.3 1791.98
  4609.3 1789.04  4646.2 1781.75  4787.4 1762.87  4919.5 1752.79  4993.4 1747.97
  4996.7 1746.73    4997 1746.23  5000.7 1746.73  5007.3 1748.27  5028.4 1747.74
  5127.5 1750.88  5205.2 1750.08  5233.5 1751.48  5247.7 1753.44  5261.8 1758.24
  5304.3 1781.19  5318.5 1786.69  5325.3 1787.54  5333.2 1791.73  5339.5 1792.11
  5346.8 1795.49  5353.7 1795.22    5361 1798.68  5367.8 1798.38  5374.4 1801.38
#Mann= 8 ,-1 , 0
  4411.7     .07       0  4559.6     .12       0  4646.2     .07       0
  4787.4     .12       0  4919.5     .07       0  4996.7     .05       0
  5000.7     .07       0  5333.2    .035       0
Bank Sta=4996.7,5000.7
XS Rating Curve= 0 ,0
Exp/Cntr=0.3,0.1

Type RM Length L Ch R = 1 ,41317   ,445,445,445
BEGIN DESCRIPTION:
FLAT ROCK CREEK_DS 75.0
END DESCRIPTION:
XS GIS Cut Line= 3
      2005341.84     13930852.69      2004805.07     13930595.03
      2003862.65     13930477.69
#Sta/Elev= 30
  4404.6 1821.33  4527.5 1801.16  4715.2 1782.54  4782.2 1775.79  4827.5 1767.04
    4867 1756.16  4878.3  1749.8  4906.9 1745.33  5008.1 1742.49  5008.4 1741.99
  5012.1 1742.49  5030.5 1743.67  5131.4 1746.08  5262.1 1747.34  5312.5  1752.1
  5366.2 1762.71  5414.6 1778.29  5527.7 1815.02  5584.6 1839.32  5603.5  1845.4
  5608.5  1843.9  5684.2 1866.06  5689.3 1863.94    5765 1881.16  5770.1 1877.27
  5816.3 1886.68  5845.8 1890.03  5850.8 1886.15    5907 1891.28  5949.7 1888.81
#Mann= 8 ,-1 , 0
  4404.6     .07       0  4715.2     .12       0  4906.9     .07       0
  5008.1     .05       0  5012.1     .07       0  5030.5     .12       0
  5131.4     .07       0  5414.6    .035       0
Bank Sta=5008.1,5012.1
XS Rating Curve= 0 ,0
Exp/Cntr=0.3,0.1

Type RM Length L Ch R = 1 ,40872   ,564,564,564
BEGIN DESCRIPTION:
FLAT ROCK CREEK_DS 74.0
END DESCRIPTION:
XS GIS Cut Line= 3
      2005324.99     13930574.98      2005025.18     13930250.07
      2004175.19     13929491.59
#Sta/Elev= 30
  4557.9 1803.87  4628.5 1790.79  4656.8 1782.98  4805.4 1764.33  4904.6 1746.22
  4961.3 1739.83  4980.2 1731.91  4987.7 1731.03  4987.9 1730.53  4991.7 1731.03
  4996.4  1735.4  5025.2 1737.94    5139 1739.05  5186.5 1737.62  5270.6 1736.66
  5322.1 1738.99  5393.1 1754.39  5464.2 1765.72  5535.2 1782.21  5584.6 1795.97
  5676.5 1831.16  5719.2 1843.49  5782.7 1865.88  5888.9  1894.1  5924.8 1899.38
  5931.5 1902.21  5945.7 1901.99  5980.8 1907.27  6057.5 1910.34  6139.2 1909.28
#Mann= 8 ,-1 , 0
  4557.9     .07       0  4980.2     .12       0  4987.7     .05       0
  4991.7     .12       0    5139     .12       0  5186.5     .07       0
  5270.6     .12       0  6057.5     .07       0
Bank Sta=4987.7,4991.7
XS Rating Curve= 0 ,0
Exp/Cntr=0.3,0.1

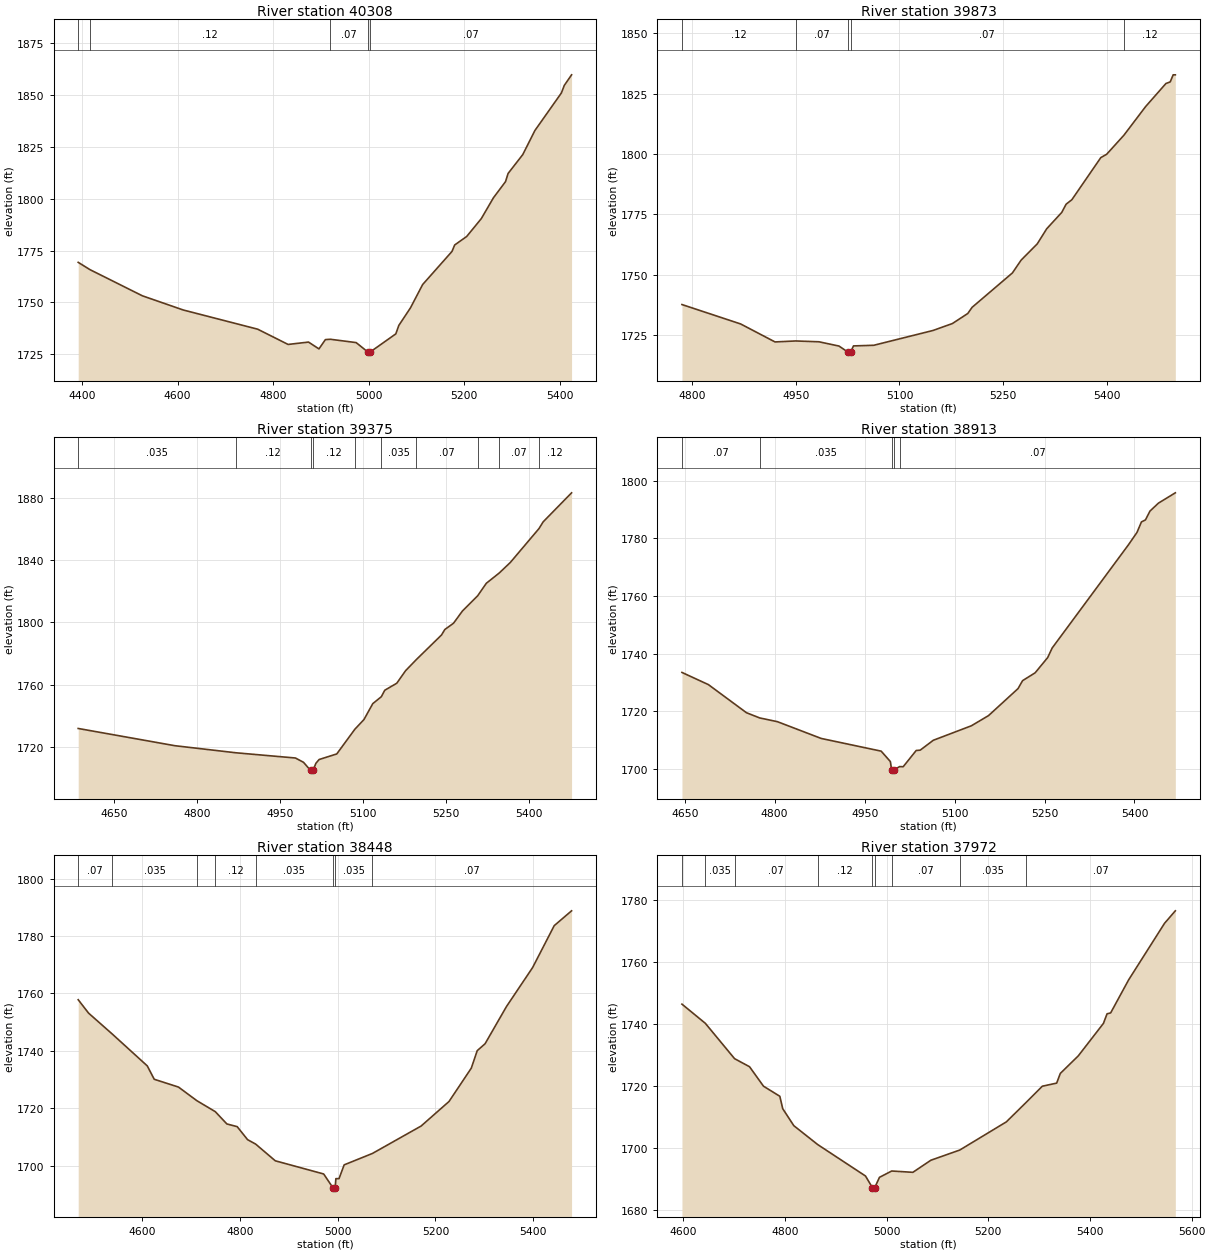
Type RM Length L Ch R = 1 ,40308   ,435,435,435
BEGIN DESCRIPTION:
FLAT ROCK CREEK_DS 73.0
END DESCRIPTION:
XS GIS Cut Line= 3
        2005425.       13930175.      2005029.35     13929720.75
      2004625.01       13929575.
#Sta/Elev= 30
  4392.1 1769.34  4416.7 1765.82  4526.4 1753.19  4611.9 1746.35  4767.6 1737.09
  4831.2 1729.73  4873.9 1730.87  4895.8 1727.58  4909.3 1732.07  4919.9 1732.22
  4973.6 1730.62  4998.4 1726.04  4998.7 1725.54  5002.7 1726.04  5056.6 1734.83
  5062.9 1738.91  5087.3  1747.4  5112.7 1758.62  5174.1  1774.6  5179.8 1777.73
  5204.8  1781.8  5235.5 1790.45  5260.8 1800.48  5286.1 1808.27  5291.5 1812.22
  5322.2 1821.32  5347.6 1832.95    5403 1851.06    5409 1854.68  5424.3 1859.81
#Mann= 5 ,-1 , 0
  4392.1     .07       0  4416.7     .12       0  4919.9     .07       0
  4998.4     .05       0  5002.7     .07       0
Bank Sta=4998.4,5002.7
XS Rating Curve= 0 ,0
Exp/Cntr=0.3,0.1

Type RM Length L Ch R = 1 ,39873   ,498,498,498
BEGIN DESCRIPTION:
FLAT ROCK CREEK_DS 72.0
END DESCRIPTION:
XS GIS Cut Line= 3
        2005425.       13929525.      2005269.48     13929377.43
      2004974.98     13928974.97
#Sta/Elev= 30
  4785.6 1737.58  4870.4 1729.54  4920.1 1722.09  4949.8 1722.49  4983.6 1722.15
  5012.6 1720.38  5025.1 1717.95  5025.4 1717.45  5029.5 1717.95  5033.5 1720.44
  5062.8  1720.7  5148.5 1726.84  5176.5 1729.71  5198.7 1733.87  5204.9 1736.41
  5263.2 1750.68  5275.9 1756.02  5299.1 1762.71  5312.8 1768.98  5334.6 1775.78
  5340.8 1779.15  5349.2 1781.04    5391 1798.47  5399.4 1799.84  5424.3 1807.72
  5455.8 1819.63  5485.1 1829.17  5491.3 1829.84  5495.6 1832.77  5498.7 1832.77
#Mann= 5 ,-1 , 0
  4785.6     .12       0  4949.8     .07       0  5025.1     .05       0
  5029.5     .07       0  5424.3     .12       0
Bank Sta=5025.1,5029.5
XS Rating Curve= 0 ,0
Exp/Cntr=0.3,0.1

Type RM Length L Ch R = 1 ,39375   ,462,462,462
BEGIN DESCRIPTION:
FLAT ROCK CREEK_DS 71.0
END DESCRIPTION:
XS GIS Cut Line= 3
      2005664.76     13929335.32      2005491.58      13928958.3
      2005074.96     13928724.98
#Sta/Elev= 30
  4585.1 1731.76  4760.1 1720.67  4870.5 1716.12    4978 1712.77  4992.6 1710.01
  5005.3 1704.83  5005.6 1704.33  5009.8 1704.83  5015.1 1709.39  5020.9  1711.8
  5052.8 1715.39  5085.5 1731.26  5101.9 1737.47  5117.9 1747.72  5133.4 1752.19
  5139.6 1756.34  5161.3 1760.85  5177.2 1768.89  5196.6 1776.02  5242.3  1791.9
  5248.2 1795.39    5264 1799.45    5280 1807.26  5307.6 1817.07  5323.3 1825.13
  5346.6 1831.72  5366.7 1838.51  5418.6 1860.32  5426.1 1864.63  5477.5  1883.3
#Mann= 10 ,-1 , 0
  4585.1    .035       0  4870.5     .12       0  5005.3     .05       0
  5009.8     .12       0  5085.5     .07       0  5133.4    .035       0
  5196.6     .07       0  5307.6     .12       0  5346.6     .07       0
  5418.6     .12       0
Bank Sta=5005.3,5009.8
XS Rating Curve= 0 ,0
Exp/Cntr=0.3,0.1

Type RM Length L Ch R = 1 ,38913   ,465,465,465
BEGIN DESCRIPTION:
FLAT ROCK CREEK_DS 70.0
END DESCRIPTION:
XS GIS Cut Line= 3
      2006075.01     13929075.02      2005885.21      13928775.5
      2005574.97     13928424.97
#Sta/Elev= 30
  4645.4 1733.51  4689.5 1729.29    4753 1719.55  4774.9 1717.76  4804.7 1716.44
  4877.6 1710.64  4977.6 1706.24  4992.9 1702.64    4995 1699.82  4995.4 1699.32
  4999.6 1699.82  5008.3 1700.89  5014.3 1700.85    5036 1706.47  5042.7 1706.59
  5064.5 1710.01    5128 1715.03  5156.5 1718.54  5205.8 1727.91  5213.4 1730.67
  5234.3 1733.38  5255.2 1738.65  5262.7 1741.97  5389.8  1777.7  5404.1    1782
  5411.6 1785.66  5418.3 1786.36  5425.8 1789.41    5440 1792.18  5468.1 1795.74
#Mann= 5 ,-1 , 0
  4645.4     .07       0  4774.9    .035       0    4995    .035       0
  4999.6    .035       0  5008.3     .07       0
Bank Sta=4995,4999.6
XS Rating Curve= 0 ,0
Exp/Cntr=0.3,0.1

Type RM Length L Ch R = 1 ,38448   ,476,476,476
BEGIN DESCRIPTION:
FLAT ROCK CREEK_DS 69.0
END DESCRIPTION:
XS GIS Cut Line= 3
      2006574.97     13928824.97      2006194.77     13928454.58
      2005775.04     13928225.02
#Sta/Elev= 30
  4469.2  1757.8  4490.4 1753.13  4539.1  1745.8  4610.5 1734.73  4624.7 1730.07
  4674.3 1727.35    4712 1722.59  4749.6 1718.78  4773.3 1714.49  4794.4 1713.55
  4815.7 1709.01  4832.1 1707.48  4872.3 1701.65  4971.3 1697.05  4990.2 1692.27
  4990.5 1691.77  4994.8 1692.27  4996.3 1695.42  5002.7 1695.42  5013.2 1700.23
  5071.1 1704.21  5170.6 1713.76  5227.7 1722.32  5273.3 1733.95  5285.4 1740.04
  5301.5 1742.46  5345.2 1755.41  5398.7 1769.01  5442.9 1783.62  5478.4 1788.79
#Mann= 8 ,-1 , 0
  4469.2     .07       0  4539.1    .035       0    4712     .07       0
  4749.6     .12       0  4832.1    .035       0  4990.2    .035       0
  4994.8    .035       0  5071.1     .07       0
Bank Sta=4990.2,4994.8
XS Rating Curve= 0 ,0
Exp/Cntr=0.3,0.1

Type RM Length L Ch R = 1 ,37972   ,496,496,496
BEGIN DESCRIPTION:
FLAT ROCK CREEK_DS 68.0
END DESCRIPTION:
XS GIS Cut Line= 3
        2006725.     13928574.99      2006530.54     13928222.58
      2006125.02     13927825.02
#Sta/Elev= 30
  4597.5 1746.35  4643.4 1740.19    4701  1728.8  4730.4 1726.21  4757.9 1719.94
    4790  1716.7  4795.7  1712.7  4817.5 1707.24  4864.5 1701.16  4958.5 1691.04
    4972 1687.32  4972.4 1686.82  4976.7 1687.32    4986 1690.62    5010 1692.65
  5051.7 1692.23  5087.1 1696.12  5143.9  1699.4  5235.5 1708.46  5273.3 1714.54
  5306.3 1719.94  5334.5 1720.94  5341.7 1724.06    5377  1729.7  5426.5 1740.16
  5433.6 1743.24  5440.7 1743.53    5476 1754.15  5546.7 1772.37  5567.9 1776.38
#Mann= 9 ,-1 , 0
  4597.5     .07       0  4643.4    .035       0    4701     .07       0
  4864.5     .12       0    4972     .05       0  4976.7     .12       0
    5010     .07       0  5143.9    .035       0  5273.3     .07       0
Bank Sta=4972,4976.7
XS Rating Curve= 0 ,0
Exp/Cntr=0.3,0.1

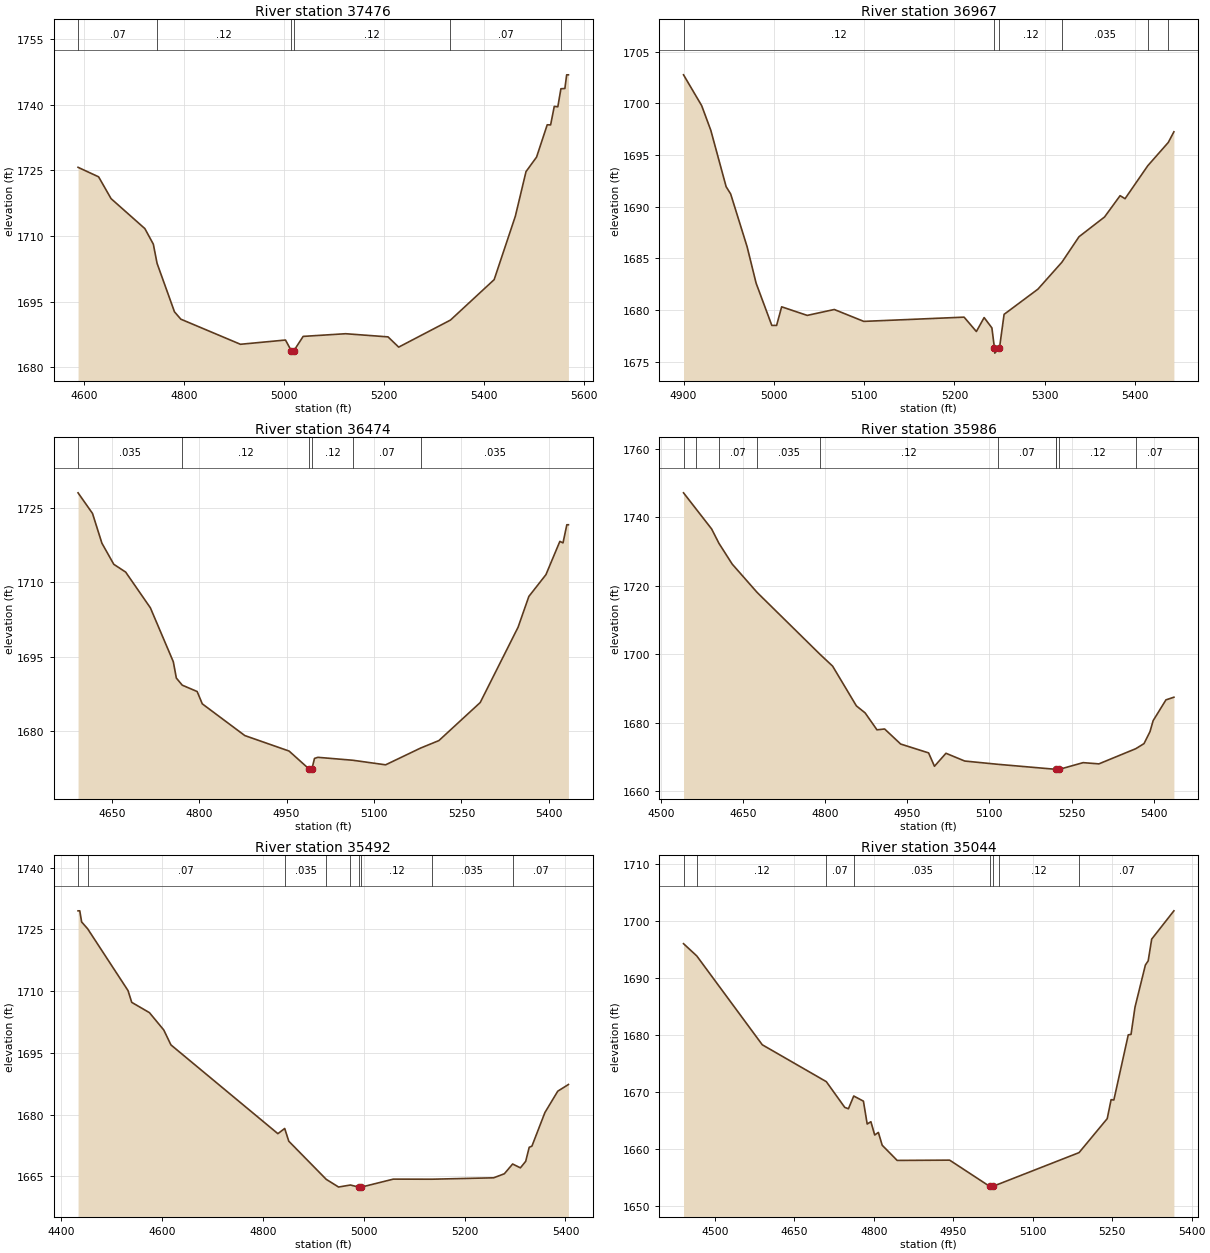
Type RM Length L Ch R = 1 ,37476   ,509,509,509
BEGIN DESCRIPTION:
FLAT ROCK CREEK_DS 67.0
END DESCRIPTION:
XS GIS Cut Line= 3
        2006925.     13928274.99      2006830.42     13927875.24
      2006424.99     13927474.99
#Sta/Elev= 30
    4588 1725.68  4629.1 1723.51    4654 1718.53  4721.6 1711.69  4738.5 1708.14
    4746 1703.76  4780.8 1692.69  4793.5 1691.01  4912.7 1685.28  5002.8 1686.25
  5014.6 1683.76    5015 1683.26  5019.3 1683.76  5038.1 1687.08    5123 1687.69
  5207.8 1686.97  5229.1 1684.63  5332.7 1690.81    5420 1700.04  5462.4 1714.53
  5483.7  1724.7  5504.8 1728.02  5526.1 1735.39  5532.9 1735.37  5540.2 1739.59
  5547.3  1739.5  5553.5 1743.62  5561.4 1743.67    5565  1746.8  5568.5  1746.8
#Mann= 6 ,-1 , 0
    4588     .07       0    4746     .12       0  5014.6     .05       0
  5019.3     .12       0  5332.7     .07       0  5553.5    .035       0
Bank Sta=5014.6,5019.3
XS Rating Curve= 0 ,0
Exp/Cntr=0.3,0.1

Type RM Length L Ch R = 1 ,36967   ,493,493,493
BEGIN DESCRIPTION:
FLAT ROCK CREEK_DS 66.0
END DESCRIPTION:
XS GIS Cut Line= 3
        2007125.       13927475.      2007025.46     13927464.81
      2006625.02     13927275.01
#Sta/Elev= 30
  4899.9 1702.75    4920 1699.77  4930.1 1697.39  4947.1 1691.93  4952.1 1691.23
  4970.3 1686.13  4980.3  1682.6  4997.7 1678.51    5003 1678.51  5008.6 1680.31
  5036.9 1679.48  5066.9 1680.05  5099.6  1678.9  5210.7 1679.31  5224.3 1677.92
  5232.9 1679.27  5241.5 1678.27  5244.3 1676.33  5244.7 1675.83  5249.9 1676.33
    5255 1679.58  5292.5 1682.02  5319.1 1684.63    5338 1687.09  5366.3    1689
  5383.5 1691.06    5389 1690.77  5414.2 1693.96  5436.9 1696.21  5443.1 1697.24
#Mann= 6 ,-1 , 0
  4899.9     .12       0  5244.3     .05       0  5249.9     .12       0
  5319.1    .035       0  5414.2     .07       0  5436.9    .035       0
Bank Sta=5244.3,5249.9
XS Rating Curve= 0 ,0
Exp/Cntr=0.3,0.1

Type RM Length L Ch R = 1 ,36474   ,488,488,488
BEGIN DESCRIPTION:
FLAT ROCK CREEK_DS 65.0
END DESCRIPTION:
XS GIS Cut Line= 3
      2007324.97     13927124.99      2006925.94     13927040.39
      2006525.01       13926875.
#Sta/Elev= 30
  4592.1 1728.03  4616.9 1723.88    4633  1717.9  4653.4 1713.64  4673.8 1712.07
  4716.2 1704.88  4755.6 1694.01  4760.8 1690.73  4770.9  1689.3  4796.5 1688.02
  4805.3 1685.54  4878.3 1679.15  4954.3 1676.03  4987.9 1672.49  4988.3 1671.99
  4993.6 1672.49  4997.9 1674.55  5003.7 1674.77  5063.6 1674.18    5120 1673.26
  5179.9 1676.63  5211.4 1678.14  5282.3  1685.8  5347.3 1700.97  5365.8 1707.17
  5395.1 1711.55    5419 1718.25  5424.4 1717.95    5431  1721.6  5433.7  1721.6
#Mann= 6 ,-1 , 0
  4592.1    .035       0  4770.9     .12       0  4987.9     .05       0
  4993.6     .12       0  5063.6     .07       0  5179.9    .035       0
Bank Sta=4987.9,4993.6
XS Rating Curve= 0 ,0
Exp/Cntr=0.3,0.1

Type RM Length L Ch R = 1 ,35986   ,494,494,494
BEGIN DESCRIPTION:
FLAT ROCK CREEK_DS 64.0
END DESCRIPTION:
XS GIS Cut Line= 3
      2007474.98     13926824.99      2007075.36      13926599.8
      2006674.96     13926424.98
#Sta/Elev= 30
  4541.3 1747.17  4564.6 1742.37  4592.6 1736.61  4605.9 1732.43  4630.2 1726.33
  4675.8 1718.03  4790.5 1699.96  4813.6 1696.49    4857 1684.87  4872.9 1682.83
  4894.6 1677.87  4908.6 1678.11  4937.9 1673.71  4988.9 1671.12  4999.6 1667.21
  5020.6 1671.01  5054.9 1668.74    5115 1667.79  5221.2 1666.32  5221.4 1666.29
  5221.9 1665.79  5227.1 1666.29  5271.1 1668.27  5299.9 1667.91  5367.3 1672.35
  5382.3 1673.83  5393.2 1677.31    5399 1680.55  5422.4 1686.63  5436.9  1687.4
#Mann= 10 ,-1 , 0
  4541.3     .07       0  4564.6    .035       0  4605.9     .07       0
  4675.8    .035       0  4790.5     .12       0    5115     .07       0
  5221.2     .12       0  5221.4     .05       0  5227.1     .12       0
  5367.3     .07       0
Bank Sta=5221.4,5227.1
XS Rating Curve= 0 ,0
Exp/Cntr=0.3,0.1

Type RM Length L Ch R = 1 ,35492   ,448,448,448
BEGIN DESCRIPTION:
FLAT ROCK CREEK_DS 63.0
END DESCRIPTION:
XS GIS Cut Line= 3
      2007475.02     13926625.02      2007058.43     13926241.71
      2006675.04     13926374.99
#Sta/Elev= 30
  4433.9 1729.49  4437.3 1729.49    4441 1726.79  4452.9 1725.13  4532.9 1710.13
  4540.3 1707.26  4575.4 1704.76  4603.8 1700.55    4618 1696.93    4830 1675.37
  4843.5 1676.63  4851.6 1673.54  4925.8 1664.28  4950.3 1662.41  4973.8  1662.9
  4989.9  1662.4  4990.4  1661.9  4995.7  1662.4  5058.8 1664.33  5135.6 1664.31
  5257.7 1664.65  5278.9 1665.63  5295.3    1668  5310.7 1667.07  5321.2 1668.65
  5328.2 1672.07  5333.5 1672.33  5359.3  1680.5  5384.8 1685.69  5405.9 1687.31
#Mann= 9 ,-1 , 0
  4433.9    .035       0  4452.9     .07       0  4843.5    .035       0
  4925.8     .07       0  4973.8     .12       0  4989.9     .05       0
  4995.7     .12       0  5135.6    .035       0  5295.3     .07       0
Bank Sta=4989.9,4995.7
XS Rating Curve= 0 ,0
Exp/Cntr=0.3,0.1

Type RM Length L Ch R = 1 ,35044   ,500,500,500
BEGIN DESCRIPTION:
FLAT ROCK CREEK_DS 62.0
END DESCRIPTION:
XS GIS Cut Line= 3
      2007475.03     13926225.03      2007074.55     13925835.19
        2006725.       13925725.
#Sta/Elev= 30
  4441.1 1695.99  4466.1 1693.84  4589.7 1678.24  4710.6 1671.76  4745.3 1667.25
  4752.3    1667  4762.3 1669.24  4780.6 1668.34  4787.7 1664.32  4794.7 1664.73
  4801.9 1662.39  4808.8 1662.85    4816  1660.6  4844.3 1657.93  4943.3 1657.98
  5018.6 1653.39  5019.1 1652.89  5024.4 1653.39  5035.8 1653.77  5187.5  1659.3
  5240.7 1665.27    5248  1668.6  5253.2 1668.54  5280.4 1679.98  5285.6 1680.06
  5293.1 1684.84  5312.7 1692.24    5318 1692.98  5324.6 1696.79  5366.5 1701.76
#Mann= 8 ,-1 , 0
  4441.1     .07       0  4466.1     .12       0  4710.6     .07       0
  4762.3    .035       0  5018.6    .035       0  5024.4    .035       0
  5035.8     .12       0  5187.5     .07       0
Bank Sta=5018.6,5024.4
XS Rating Curve= 0 ,0
Exp/Cntr=0.3,0.1