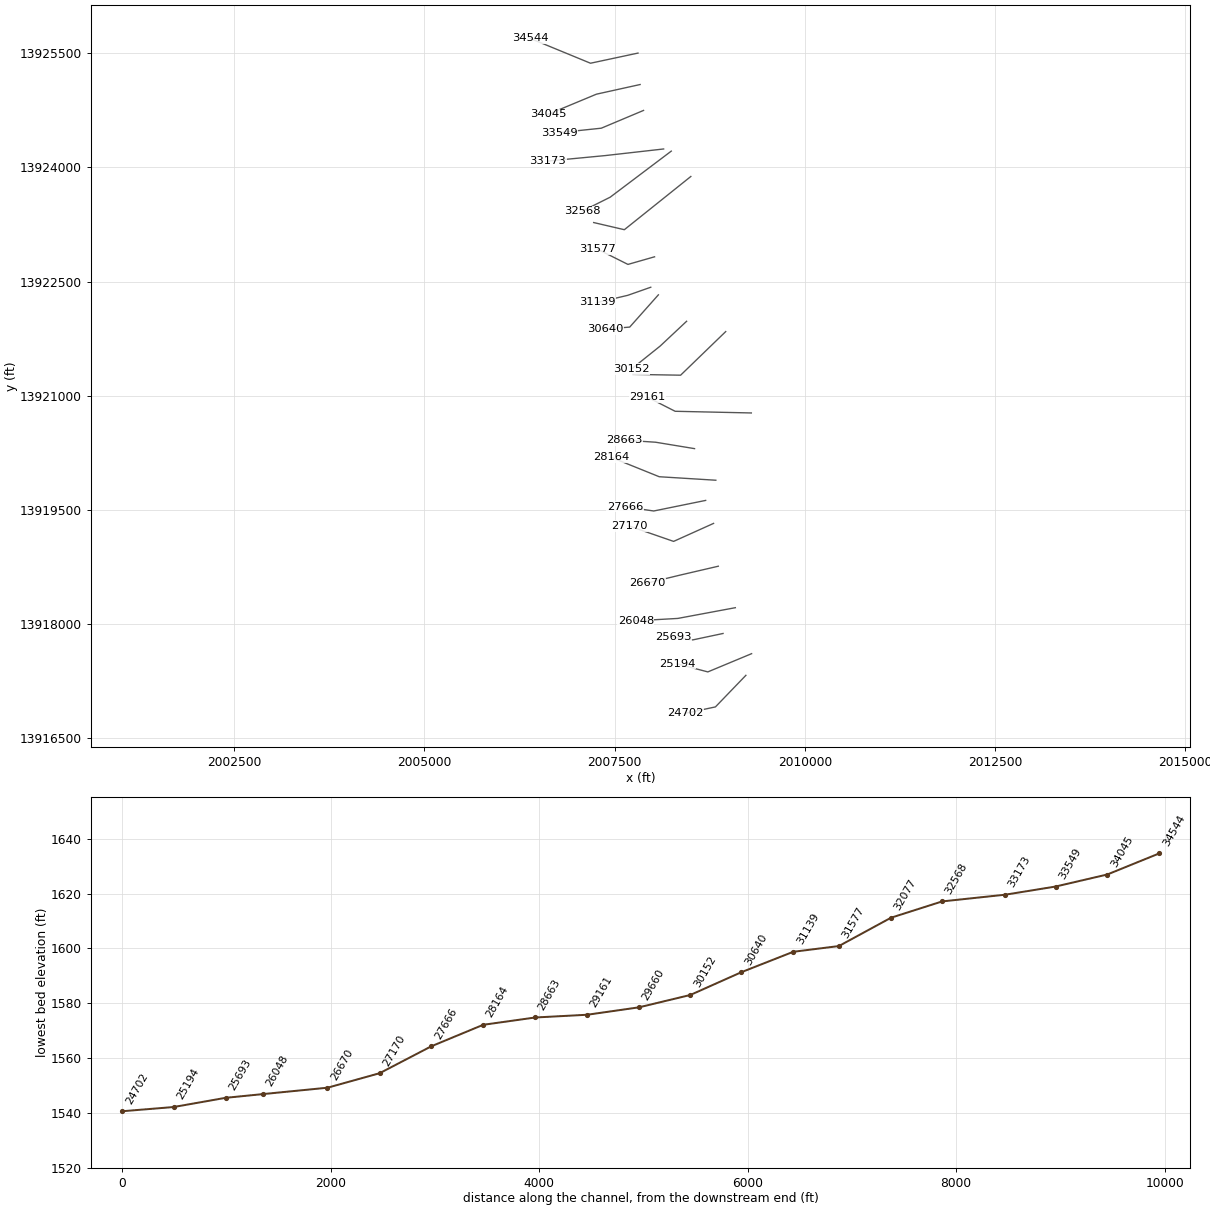
HEC-RAS study FLAT ROCK CREEK.prj: FLAT ROCK CREEK Base Level Engineering

--- FLAT ROCK CREEK.g01 (geometry) --- (continued)

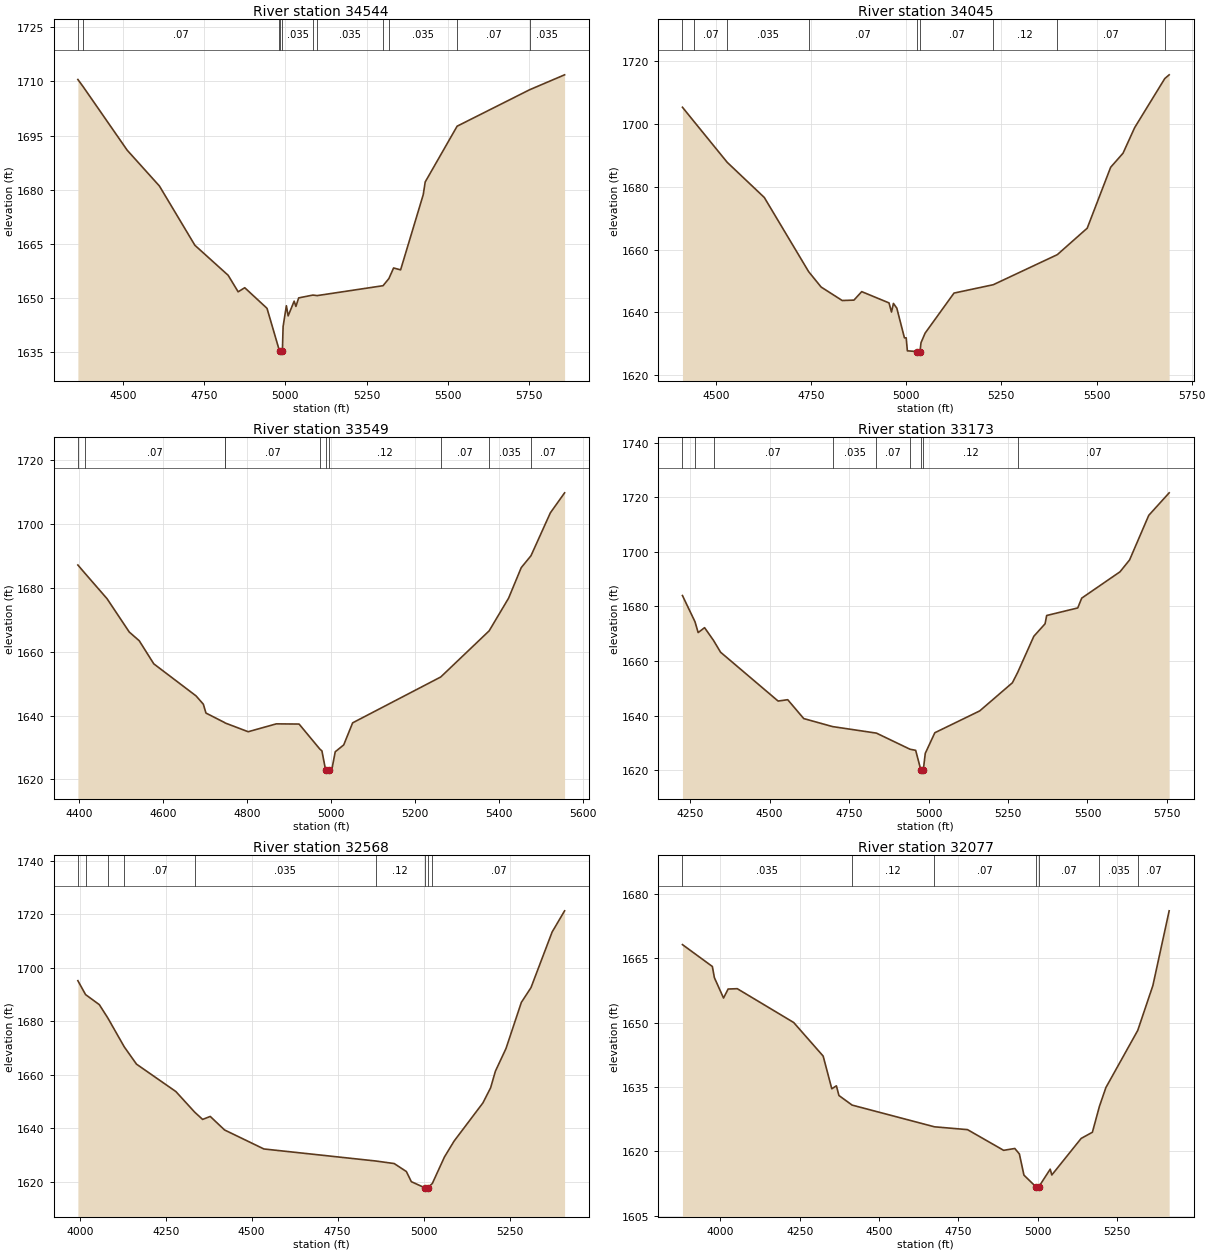
Type RM Length L Ch R = 1 ,34544   ,499,499,499
BEGIN DESCRIPTION:
FLAT ROCK CREEK_DS 61.0
END DESCRIPTION:
XS GIS Cut Line= 3
      2007807.09     13925501.99      2007183.07     13925368.68
      2006388.48     13925695.83
#Sta/Elev= 30
  4361.9 1710.51  4377.6 1708.59  4513.7 1690.92  4612.7 1681.02  4721.9 1664.59
  4824.2 1656.28    4855  1651.7  4875.3 1652.83  4943.8 1647.12  4981.9 1635.39
  4984.5 1635.21    4985 1634.71  4991.1 1635.21  4993.3 1642.09  5003.4 1647.84
  5008.8 1645.03  5027.3 1649.11  5032.7 1647.65  5041.2 1650.01  5084.7 1650.79
  5098.4 1650.65  5300.8 1653.39  5318.7 1655.36  5333.2  1658.3  5354.8 1657.78
  5424.4  1678.6  5430.5 1682.14  5528.7 1697.58  5751.8 1707.68  5859.3 1711.81
#Mann= 11 ,-1 , 0
  4361.9    .035       0  4377.6     .07       0  4981.9    .035       0
  4984.5    .035       0  4991.1    .035       0  5084.7     .07       0
  5098.4    .035       0  5300.8     .07       0  5318.7    .035       0
  5528.7     .07       0  5751.8    .035       0
Bank Sta=4984.5,4991.1
XS Rating Curve= 0 ,0
Exp/Cntr=0.3,0.1

Type RM Length L Ch R = 1 ,34045   ,496,496,496
BEGIN DESCRIPTION:
FLAT ROCK CREEK_DS 60.0
END DESCRIPTION:
XS GIS Cut Line= 3
      2007834.91      13925088.8      2007260.96     13924961.96
      2006623.11     13924696.45
#Sta/Elev= 30
  4412.2 1705.34    4443 1700.73  4529.8 1687.79  4627.2  1676.6  4743.8 1652.95
  4776.5 1648.06    4832 1643.76  4862.7 1643.89  4883.2 1646.59  4954.9    1643
  4961.4 1640.09  4966.5 1642.84  4975.4 1641.33  4995.4 1631.87    5000 1631.87
  5003.1 1627.73  5028.4  1627.5  5028.9    1627  5036.2  1627.5    5039 1630.34
  5049.8 1633.38  5125.6 1646.13  5228.9  1648.8  5397.1 1658.38  5475.6 1666.81
  5537.2 1686.22  5569.7  1690.7  5600.2 1698.84  5679.3 1714.47  5690.9 1715.67
#Mann= 9 ,-1 , 0
  4412.2    .035       0    4443     .07       0  4529.8    .035       0
  4743.8     .07       0  5028.4     .05       0  5036.2     .07       0
  5228.9     .12       0  5397.1     .07       0  5679.3    .035       0
Bank Sta=5028.4,5036.2
XS Rating Curve= 0 ,0
Exp/Cntr=0.3,0.1

Type RM Length L Ch R = 1 ,33549   ,483,483,483
BEGIN DESCRIPTION:
FLAT ROCK CREEK_DS 59.0
END DESCRIPTION:
XS GIS Cut Line= 3
      2007880.05     13924748.53      2007324.89     13924514.95
      2006772.44     13924456.86
#Sta/Elev= 30
  4397.7 1687.07  4414.4  1684.5  4467.1 1676.53    4520  1666.1  4543.7 1663.38
  4578.3 1656.16  4678.7 1646.15  4696.1 1643.55  4702.4 1640.77  4746.6 1637.81
  4747.8 1637.68  4802.8 1634.93  4869.7 1637.39  4923.9 1637.33  4973.6 1629.46
  4978.2 1628.95  4986.8 1623.11  4987.3 1622.61  4994.6 1623.11  5002.5 1623.58
  5009.9 1628.66  5030.1 1630.81  5051.3 1637.71  5260.9 1652.05    5376 1666.47
  5422.2 1676.68  5452.4 1686.25  5475.6 1689.98  5521.6 1703.37  5555.5 1709.64
#Mann= 10 ,-1 , 0
  4397.7    .035       0  4414.4     .07       0  4746.6    .035       0
  4747.8     .07       0  4973.6     .12       0  4986.8     .05       0
  4994.6     .12       0  5260.9     .07       0    5376    .035       0
  5475.6     .07       0
Bank Sta=4986.8,4994.6
XS Rating Curve= 0 ,0
Exp/Cntr=0.3,0.1

Type RM Length L Ch R = 1 ,33173   ,605,605,605
BEGIN DESCRIPTION:
FLAT ROCK CREEK_DS 58.0
END DESCRIPTION:
XS GIS Cut Line= 3
      2008144.13     13924241.92      2007374.64     13924154.85
      2006621.07     13924082.92
#Sta/Elev= 30
  4225.6 1683.98    4265  1674.4    4275 1670.41  4295.2 1672.21  4323.3 1667.55
  4345.5 1663.22  4526.6 1645.31  4556.8 1645.81  4607.2 1638.89    4698 1635.95
    4836 1633.56  4941.3 1627.67  4959.4 1627.25  4975.5 1620.13    4976 1619.63
  4983.5 1620.13  4989.6 1626.14  5019.7  1633.7  5160.9  1641.7  5263.7 1652.01
  5280.6 1655.87  5331.1 1669.04  5366.5 1673.62  5371.6 1676.67  5469.4 1679.44
  5481.8 1683.03  5602.4 1692.69  5632.5 1697.05  5692.8 1713.38    5757 1721.63
#Mann= 9 ,-1 , 0
  4225.6     .07       0    4265    .035       0  4323.3     .07       0
    4698    .035       0    4836     .07       0  4941.3     .12       0
  4975.5     .05       0  4983.5     .12       0  5280.6     .07       0
Bank Sta=4975.5,4983.5
XS Rating Curve= 0 ,0
Exp/Cntr=0.3,0.1

Type RM Length L Ch R = 1 ,32568   ,491,491,491
BEGIN DESCRIPTION:
FLAT ROCK CREEK_DS 57.0
END DESCRIPTION:
XS GIS Cut Line= 3
      2008244.66     13924213.83      2007441.94     13923608.45
      2007075.04     13923425.02
#Sta/Elev= 30
  3994.6 1695.09    4017 1689.89  4056.9 1686.15  4081.7 1681.16  4129.7 1670.32
  4165.1  1663.9  4279.6 1653.66    4334    1646  4357.4 1643.24  4379.6 1644.35
  4421.2  1639.3  4535.7 1632.19  4861.3 1627.69  4914.6 1626.74    4950 1623.76
  4964.5 1619.96  5003.7 1617.68  5004.2 1617.18  5011.8 1617.68  5025.5 1619.29
  5060.8 1629.21  5088.8 1635.13  5172.7 1649.42    5195 1655.05    5209 1661.28
  5239.7 1669.72  5284.5    1687  5312.4 1692.49  5373.9 1713.28  5410.2 1721.21
#Mann= 9 ,-1 , 0
  3994.6    .035       0    4017     .07       0  4081.7    .035       0
  4129.7     .07       0    4334    .035       0  4861.3     .12       0
  5003.7     .05       0  5011.8     .12       0  5025.5     .07       0
Bank Sta=5003.7,5011.8
XS Rating Curve= 0 ,0
Exp/Cntr=0.3,0.1

Type RM Length L Ch R = 1 ,32077   ,500,500,500
BEGIN DESCRIPTION:
FLAT ROCK CREEK_DS 56.0
END DESCRIPTION:
XS GIS Cut Line= 3
      2008501.54     13923880.44      2007627.72     13923181.12
      2007225.01       13923275.
#Sta/Elev= 30
  3880.8 1668.19    3975 1663.09  3981.4 1660.48  4010.2 1655.74  4024.6 1657.84
  4053.4 1657.92  4231.1 1650.04  4323.9 1642.22  4351.1  1634.6  4365.6 1635.29
  4373.6 1633.03    4415  1630.8  4674.3 1625.74  4778.5 1625.08  4892.2 1620.26
  4927.4 1620.69  4941.8 1619.42  4956.2 1614.48  4994.5 1611.72    4995 1611.22
  5002.6 1611.72  5038.9 1615.87    5044 1614.52  5136.3 1623.03  5171.7 1624.47
  5194.1 1630.56  5214.3 1634.89  5314.5 1648.19  5362.2 1658.65  5413.5 1676.06
#Mann= 7 ,-1 , 0
  3880.8    .035       0    4415     .12       0  4674.3     .07       0
  4994.5     .05       0  5002.6     .07       0  5194.1    .035       0
  5314.5     .07       0
Bank Sta=4994.5,5002.6
XS Rating Curve= 0 ,0
Exp/Cntr=0.3,0.1

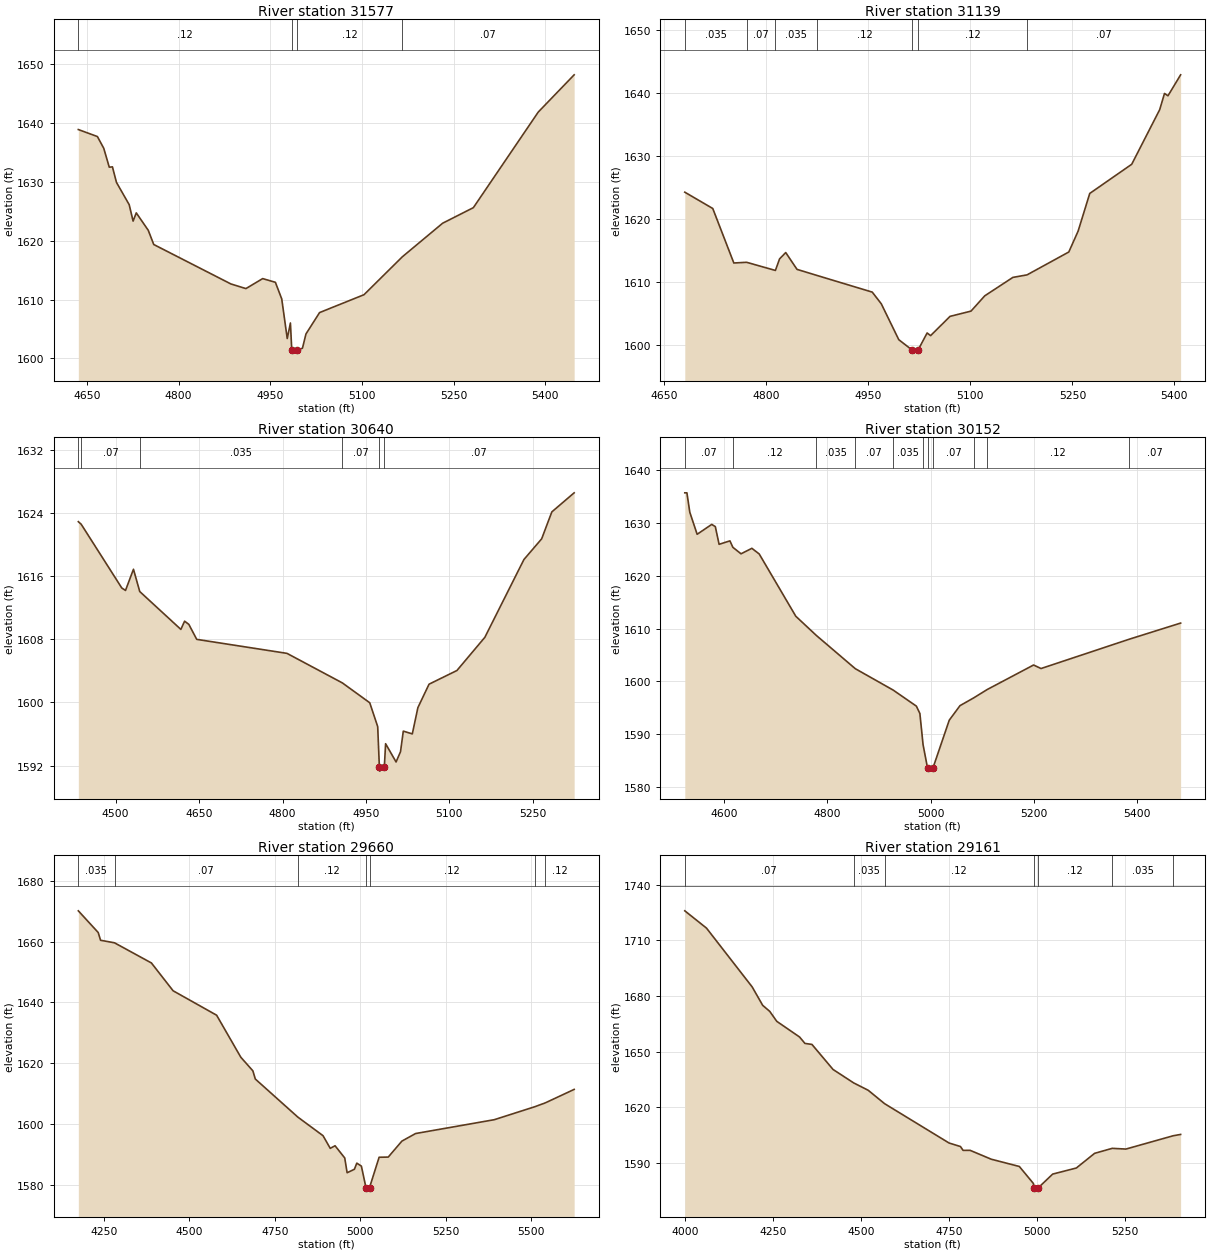
Type RM Length L Ch R = 1 ,31577   ,438,438,438
BEGIN DESCRIPTION:
FLAT ROCK CREEK_DS 55.0
END DESCRIPTION:
XS GIS Cut Line= 3
      2008024.96     13922824.99      2007675.08     13922724.97
        2007275.       13922925.
#Sta/Elev= 30
  4636.1 1638.92  4667.3 1637.73  4677.7 1635.73  4686.7 1632.52  4691.9 1632.57
  4698.5 1629.93  4719.3 1626.14  4725.7 1623.34  4730.9 1624.74  4750.5 1621.78
  4759.5 1619.36  4885.7 1612.65  4910.3 1611.86  4937.7 1613.56  4958.5 1612.93
  4968.9  1610.1  4977.9 1603.36  4983.1 1606.01  4985.3 1601.38  4985.8 1600.88
  4994.1 1601.38  5002.8 1601.72  5008.5 1604.14  5030.8 1607.78  5103.5 1610.82
  5166.1 1617.26  5232.1 1622.98  5282.4 1625.63  5388.6  1641.9  5447.3 1648.23
#Mann= 4 ,-1 , 0
  4636.1     .12       0  4985.3     .05       0  4994.1     .12       0
  5166.1     .07       0
Bank Sta=4985.3,4994.1
XS Rating Curve= 0 ,0
Exp/Cntr=0.3,0.1

Type RM Length L Ch R = 1 ,31139   ,499,499,499
BEGIN DESCRIPTION:
FLAT ROCK CREEK_DS 54.0
END DESCRIPTION:
XS GIS Cut Line= 3
      2007974.97     13922424.99      2007673.18     13922318.88
        2007275.       13922225.
#Sta/Elev= 30
  4680.1 1624.26  4721.2 1621.68  4752.2 1613.05    4771 1613.16  4813.3 1611.87
  4819.5 1613.71  4828.5  1614.7  4845.1 1612.04  4874.4 1611.08  4955.7 1608.44
    4969 1606.59  4994.7 1600.91  5014.2 1599.28  5014.7 1598.78  5023.1 1599.28
  5036.4 1601.97  5041.5 1601.55  5070.1  1604.6  5100.9 1605.43  5121.1 1607.85
  5162.5 1610.77  5183.3 1611.17  5244.7 1614.79  5258.4  1618.1  5275.5 1624.06
  5337.2 1628.68  5378.3 1637.32  5385.4 1639.89  5390.5 1639.52  5409.1 1642.84
#Mann= 7 ,-1 , 0
  4680.1    .035       0    4771     .07       0  4813.3    .035       0
  4874.4     .12       0  5014.2     .05       0  5023.1     .12       0
  5183.3     .07       0
Bank Sta=5014.2,5023.1
XS Rating Curve= 0 ,0
Exp/Cntr=0.3,0.1

Type RM Length L Ch R = 1 ,30640   ,488,488,488
BEGIN DESCRIPTION:
FLAT ROCK CREEK_DS 53.0
END DESCRIPTION:
XS GIS Cut Line= 3
      2008074.98     13922324.98      2007698.18     13921901.29
      2007375.04       13921875.
#Sta/Elev= 30
    4433 1622.87  4438.1 1622.55  4511.1 1614.48  4517.8 1614.17  4532.1 1616.85
  4543.4 1614.03  4617.3 1609.24    4624 1610.28  4631.6 1609.88  4645.8 1607.98
    4808 1606.21  4907.6 1602.47  4956.8 1599.96  4971.1 1596.94  4974.1 1591.81
  4974.6 1591.31    4983 1591.81  4985.3 1594.78  5004.1 1592.47  5012.1 1593.77
  5017.1 1596.37  5033.3 1596.02  5043.3 1599.34  5063.4 1602.31  5113.5 1604.04
  5163.7 1608.24  5233.9 1618.08  5265.8  1620.7  5284.1 1624.11  5324.2 1626.52
#Mann= 6 ,-1 , 0
    4433    .035       0  4438.1     .07       0  4543.4    .035       0
  4907.6     .07       0  4974.1     .05       0    4983     .07       0
Bank Sta=4974.1,4983
XS Rating Curve= 0 ,0
Exp/Cntr=0.3,0.1

Type RM Length L Ch R = 1 ,30152   ,492,492,492
BEGIN DESCRIPTION:
FLAT ROCK CREEK_DS 52.0
END DESCRIPTION:
XS GIS Cut Line= 3
        2008446.     13921977.68      2008098.47     13921651.98
       2007720.8     13921349.61
#Sta/Elev= 30
  4523.7 1635.73  4527.8 1635.73  4533.4 1632.05  4547.6 1627.88  4575.9 1629.75
  4582.8 1629.33  4590.1 1625.98  4611.1 1626.63  4616.8 1625.41  4632.6 1624.18
  4653.6 1625.22  4667.8 1624.15  4738.6 1612.36  4778.4 1608.72  4853.9 1602.42
  4927.2 1598.37  4972.1 1595.33  4978.9 1593.94  4985.1 1588.02  4993.9 1583.52
  4994.4 1583.02  5003.9 1583.52  5035.8 1592.67  5056.6 1595.42  5083.6 1596.92
  5109.2 1598.47  5199.1 1603.12  5213.5 1602.45  5384.5 1608.01  5483.8 1611.06
#Mann= 11 ,-1 , 0
  4523.7     .07       0  4616.8     .12       0  4778.4    .035       0
  4853.9     .07       0  4927.2    .035       0  4985.1     .07       0
  4993.9     .05       0  5003.9     .07       0  5083.6    .035       0
  5109.2     .12       0  5384.5     .07       0
Bank Sta=4993.9,5003.9
XS Rating Curve= 0 ,0
Exp/Cntr=0.3,0.1

Type RM Length L Ch R = 1 ,29660   ,499,499,499
BEGIN DESCRIPTION:
FLAT ROCK CREEK_DS 51.0
END DESCRIPTION:
XS GIS Cut Line= 3
      2008959.88     13921842.25      2008367.19     13921269.08
      2007741.18     13921279.77
#Sta/Elev= 30
  4175.5 1670.12  4233.6 1662.99  4240.6 1660.43  4281.4 1659.59  4389.3 1652.96
  4452.8  1643.8  4580.1 1635.76  4650.9 1621.92  4686.1 1617.45  4693.3 1614.75
  4817.7 1602.22  4891.4  1596.1  4912.5 1591.93  4926.6 1592.79  4954.9 1588.77
  4961.9  1583.9  4983.2 1585.05  4990.2 1587.07  5003.6 1586.08    5017 1579.01
  5017.5 1578.51  5027.4 1579.01  5055.5    1589  5082.2 1589.06  5122.2 1594.32
  5162.2 1596.81  5392.2 1601.36  5510.6 1605.62  5541.6  1606.9  5626.1 1611.34
#Mann= 7 ,-1 , 0
  4175.5    .035       0  4281.4     .07       0  4817.7     .12       0
    5017     .05       0  5027.4     .12       0  5510.6     .07       0
  5541.6     .12       0
Bank Sta=5017,5027.4
XS Rating Curve= 0 ,0
Exp/Cntr=0.3,0.1

Type RM Length L Ch R = 1 ,29161   ,498,498,498
BEGIN DESCRIPTION:
FLAT ROCK CREEK_DS 50.0
END DESCRIPTION:
XS GIS Cut Line= 3
      2009296.68     13920772.83      2008295.42     13920794.83
      2007930.51     13920980.22
#Sta/Elev= 30
  3998.5 1725.99  4060.2 1716.67  4190.2 1684.93  4220.2 1674.97  4240.2 1671.73
  4260.2 1666.35  4325.1 1657.89  4340.3 1654.44  4360.3 1653.88  4420.3 1640.38
    4479 1633.12  4520.3 1629.15    4567 1621.91  4750.4 1600.68  4782.8 1598.78
  4790.4  1596.7  4810.4 1596.72  4870.4 1591.94  4950.4 1588.01  4990.4 1578.84
  4992.5 1576.29    4993 1575.79    5003 1576.29  5045.3 1583.91  5112.6 1587.19
  5164.5  1595.1  5214.7  1597.8  5253.6 1597.41  5387.7 1604.57  5409.3 1605.31
#Mann= 7 ,-1 , 0
  3998.5     .07       0    4479    .035       0    4567     .12       0
  4992.5     .05       0    5003     .12       0  5214.7    .035       0
  5387.7     .07       0
Bank Sta=4992.5,5003
XS Rating Curve= 0 ,0
Exp/Cntr=0.3,0.1

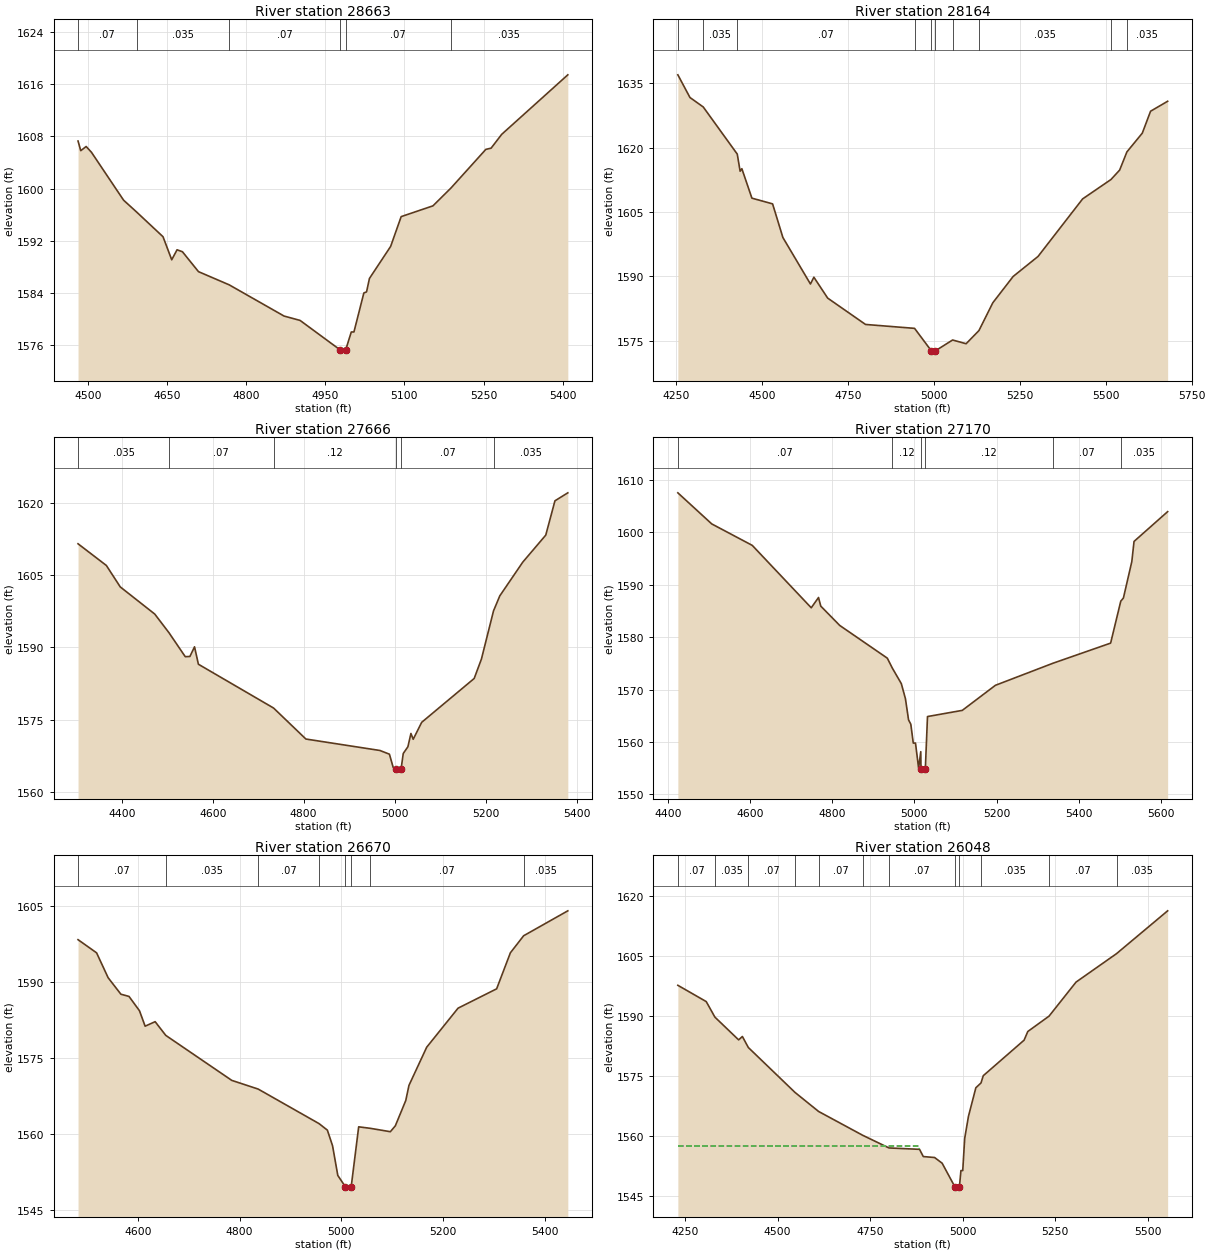
Type RM Length L Ch R = 1 ,28663   ,499,499,499
BEGIN DESCRIPTION:
FLAT ROCK CREEK_DS 49.0
END DESCRIPTION:
XS GIS Cut Line= 3
      2008550.15     13920304.09      2008038.72     13920388.17
      2007630.01     13920415.19
#Sta/Elev= 30
  4481.7 1607.28  4486.9  1605.8  4497.1 1606.44  4507.2 1605.55    4568 1598.22
  4592.6 1596.41  4642.7 1592.62  4659.2 1589.09  4669.3 1590.62  4679.5 1590.32
  4709.9 1587.27  4768.1 1585.25    4872 1580.47  4902.4  1579.8  4978.2 1575.29
  4978.7 1574.79  4988.8 1575.29  4999.4 1578.03  5004.4 1578.03  5023.2 1584.01
  5028.3 1584.17  5033.8 1586.23  5073.9 1591.13  5093.9  1595.7  5154.1 1597.35
  5188.1 1600.07  5254.3    1606  5264.3 1606.19  5284.3  1608.3  5409.6 1617.42
#Mann= 6 ,-1 , 0
  4481.7     .07       0  4592.6    .035       0  4768.1     .07       0
  4978.2     .05       0  4988.8     .07       0  5188.1    .035       0
Bank Sta=4978.2,4988.8
XS Rating Curve= 0 ,0
Exp/Cntr=0.3,0.1

Type RM Length L Ch R = 1 ,28164   ,498,498,498
BEGIN DESCRIPTION:
FLAT ROCK CREEK_DS 48.0
END DESCRIPTION:
XS GIS Cut Line= 3
      2008830.13     13919888.76      2008086.25     13919934.78
      2007455.56     13920189.27
#Sta/Elev= 30
  4254.7 1636.95  4289.9 1631.67  4328.6 1629.46  4427.6 1618.48  4435.9  1614.5
    4441 1615.08  4470.2 1608.22  4530.4 1606.89  4560.4 1599.05  4640.6 1588.22
  4650.6  1589.8  4690.7 1584.94  4800.9  1578.8  4943.6 1577.89  4992.8 1572.62
  4993.3 1572.12  5003.4 1572.62  5054.3 1575.18  5093.6 1574.31  5130.9 1577.37
  5171.4 1583.86  5230.5 1589.98  5302.9 1594.64  5432.7 1608.05  5515.3 1612.57
  5540.5 1614.77  5561.5 1618.99  5606.3 1623.36  5630.4 1628.47  5680.1 1630.79
#Mann= 10 ,-1 , 0
  4254.7     .07       0  4328.6    .035       0  4427.6     .07       0
  4943.6     .12       0  4992.8     .05       0  5003.4     .12       0
  5054.3     .07       0  5130.9    .035       0  5515.3     .07       0
  5561.5    .035       0
Bank Sta=4992.8,5003.4
XS Rating Curve= 0 ,0
Exp/Cntr=0.3,0.1

Type RM Length L Ch R = 1 ,27666   ,496,496,496
BEGIN DESCRIPTION:
FLAT ROCK CREEK_DS 47.0
END DESCRIPTION:
XS GIS Cut Line= 3
      2008696.02     13919623.53      2008013.84     13919484.52
      2007637.03     13919540.19
#Sta/Elev= 30
  4303.8 1611.53  4366.1 1607.02  4396.7 1602.56  4472.5 1596.92  4503.8 1593.04
  4539.6 1588.06  4549.8  1588.1    4560 1590.11  4568.5 1586.49  4733.9 1577.38
  4804.9 1570.94  4967.8 1568.56  4988.6 1567.79  4996.9 1565.03  5003.6 1564.77
  5004.1 1564.27  5014.3 1564.77    5019 1567.94  5029.2 1569.33  5035.9  1572.1
  5040.9 1570.89  5059.5 1574.41    5175 1583.53  5190.9 1587.56  5217.5 1597.58
  5231.3  1600.7  5281.9 1607.72  5332.4 1613.33  5352.6 1620.46  5380.9 1622.12
#Mann= 6 ,-1 , 0
  4303.8    .035       0  4503.8     .07       0  4733.9     .12       0
  5003.6     .05       0  5014.3     .07       0  5217.5    .035       0
Bank Sta=5003.6,5014.3
XS Rating Curve= 0 ,0
Exp/Cntr=0.3,0.1

Type RM Length L Ch R = 1 ,27170   ,500,500,500
BEGIN DESCRIPTION:
FLAT ROCK CREEK_DS 46.0
END DESCRIPTION:
XS GIS Cut Line= 3
       2008800.2     13919321.45      2008275.18     13919085.07
      2007692.56     13919286.71
#Sta/Elev= 30
  4424.2 1607.53  4506.7  1601.6  4605.4  1597.5  4748.9  1585.6  4766.6 1587.56
  4772.1 1585.92  4818.3 1582.23  4934.1 1575.99    4946 1574.14  4968.2 1571.13
  4978.2 1568.26  4985.8 1564.21  4991.3 1563.39  4997.3 1559.79  5002.7 1559.79
  5010.3    1555  5015.5 1558.15    5016 1554.94  5016.5 1554.44  5026.7 1554.94
  5031.9 1564.85  5116.6 1566.03  5197.2 1570.81  5337.3 1575.02  5477.7 1578.86
  5502.4 1586.86  5508.8 1587.46  5529.3 1594.42  5534.7 1598.26  5616.5 1603.94
#Mann= 6 ,-1 , 0
  4424.2     .07       0    4946     .12       0    5016     .05       0
  5026.7     .12       0  5337.3     .07       0  5502.4    .035       0
Bank Sta=5016,5026.7
XS Rating Curve= 0 ,0
Exp/Cntr=0.3,0.1

Type RM Length L Ch R = 1 ,26670   ,622,622,622
BEGIN DESCRIPTION:
FLAT ROCK CREEK_DS 45.0
END DESCRIPTION:
XS GIS Cut Line= 3
      2008862.71     13918758.95      2008358.11     13918641.57
       2007925.2     13918536.72
#Sta/Elev= 30
    4482 1598.28  4518.5 1595.69  4541.2 1590.79  4566.3 1587.54  4582.3  1587.1
  4602.9 1584.28    4614 1581.24  4633.7 1582.13  4654.6 1579.43  4784.4 1570.57
  4836.5 1568.85    4956 1562.06  4972.5 1560.77  4982.7 1557.69    4993 1551.85
  5007.7 1549.65  5008.2 1549.15  5019.4 1549.65  5034.1 1561.42  5056.6 1561.13
  5096.4 1560.46  5106.2 1561.62  5126.7  1566.6    5133 1569.58  5167.9  1577.1
  5229.6 1584.79  5305.5  1588.6  5332.5 1595.69  5358.6 1599.05  5445.5 1603.96
#Mann= 8 ,-1 , 0
    4482     .07       0  4654.6    .035       0  4836.5     .07       0
    4956    .035       0  5007.7    .035       0  5019.4    .035       0
  5056.6     .07       0  5358.6    .035       0
Bank Sta=5007.7,5019.4
XS Rating Curve= 0 ,0
Exp/Cntr=0.3,0.1

Type RM Length L Ch R = 1 ,26048   ,355,355,355
BEGIN DESCRIPTION:
FLAT ROCK CREEK_DS 44.0
END DESCRIPTION:
XS GIS Cut Line= 3
      2009086.28     13918213.87      2008330.33      13918072.8
      2007778.12     13918041.45
#Sta/Elev= 30
    4231 1597.68  4307.6 1593.62    4331 1589.74  4395.1 1584.06  4405.2 1584.91
  4421.2 1582.16  4547.2 1570.95    4611 1566.19  4730.1 1560.24  4800.9 1557.09
  4883.4 1556.74  4893.5 1554.94    4924  1554.7  4944.4 1553.28  4979.2 1547.31
  4979.7 1546.81    4991 1547.31  4995.1 1551.44    5000 1551.44  5005.3 1559.49
  5015.4 1564.96  5035.4 1572.11  5049.3 1573.31  5055.4 1575.12  5165.6 1583.99
  5175.6 1586.15    5233 1589.99  5305.8 1598.48  5415.1 1605.58  5553.1 1616.27
#Mann= 12 ,-1 , 0
    4231     .07       0    4331    .035       0  4421.2     .07       0
  4547.2    .035       0    4611     .07       0  4730.1    .035       0
  4800.9     .07       0  4979.2     .05       0    4991     .07       0
  5049.3    .035       0    5233     .07       0  5415.1    .035       0
#XS Ineff= 2 , 0
       0 4883.25 1557.59               0
Permanent Ineff=
       F       F
Bank Sta=4979.2,4991
XS Rating Curve= 0 ,0
Exp/Cntr=0.3,0.1

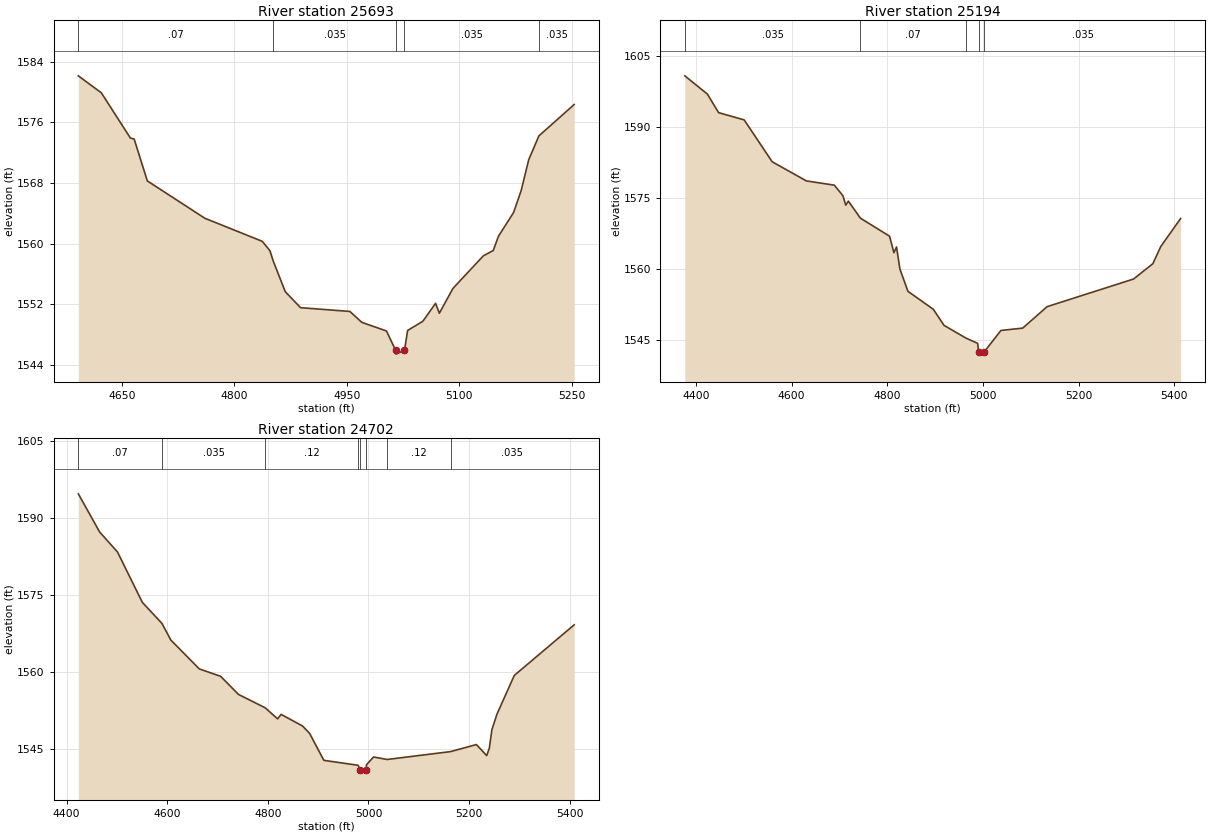
Type RM Length L Ch R = 1 ,25693   ,499,499,499
BEGIN DESCRIPTION:
FLAT ROCK CREEK_DS 43.0
END DESCRIPTION:
XS GIS Cut Line= 3
        2008925.       13917875.      2008525.87     13917790.36
      2008274.95     13917825.01
#Sta/Elev= 30
    4592 1582.12  4622.7 1579.88  4661.4 1573.93  4666.5 1573.79    4684 1568.28
  4760.7 1563.36  4837.3 1560.32  4847.6 1559.08    4852 1557.71    4868 1553.68
  4888.4 1551.58  4954.2 1551.08  4970.2 1549.64    5003 1548.51  5015.2 1545.96
  5015.7 1545.46    5027 1545.96  5031.2 1548.58  5051.4 1549.78  5068.5 1552.15
  5073.5 1550.85  5091.7 1554.12  5132.1  1558.4  5145.4 1559.11  5152.3 1560.98
  5172.5 1564.11  5182.6    1567  5192.7 1571.07  5206.3 1574.21  5253.3 1578.34
#Mann= 5 ,-1 , 0
    4592     .07       0    4852    .035       0  5015.2    .035       0
    5027    .035       0  5206.3    .035       0
Bank Sta=5015.2,5027
XS Rating Curve= 0 ,0
Exp/Cntr=0.3,0.1

Type RM Length L Ch R = 1 ,25194   ,492,492,492
BEGIN DESCRIPTION:
FLAT ROCK CREEK_DS 42.0
END DESCRIPTION:
XS GIS Cut Line= 3
      2009300.18     13917609.63      2008724.91     13917369.96
      2008324.97     13917475.01
#Sta/Elev= 30
  4376.8 1600.74  4424.1 1596.89  4447.4 1592.99    4501 1591.45  4559.5 1582.63
    4631  1578.6  4689.5  1577.7  4707.4 1575.48  4713.3  1573.5  4718.8 1574.34
  4743.9 1570.76  4804.9 1566.95  4814.1 1563.47  4819.5 1564.68  4826.6 1560.02
  4843.4 1555.33  4896.4 1551.55  4918.7 1548.17  4964.1 1545.51  4989.1 1544.37
  4991.2  1542.6  4991.7  1542.1  5003.1  1542.6  5037.8 1547.09  5083.3 1547.58
  5134.3  1552.1  5315.2 1557.93  5355.5 1561.16  5372.1 1564.79  5413.5 1570.68
#Mann= 5 ,-1 , 0
  4376.8    .035       0  4743.9     .07       0  4964.1    .035       0
  4991.2    .035       0  5003.1    .035       0
Bank Sta=4991.2,5003.1
XS Rating Curve= 0 ,0
Exp/Cntr=0.3,0.1

Type RM Length L Ch R = 1 ,24702   ,476,476,476
BEGIN DESCRIPTION:
FLAT ROCK CREEK_DS 41.0
END DESCRIPTION:
XS GIS Cut Line= 3
      2009224.97     13917324.97      2008824.85     13916909.94
      2008424.97     13916824.99
#Sta/Elev= 30
  4423.5 1594.65  4465.8 1587.24  4501.3 1583.35  4550.7 1573.56  4589.7 1569.46
  4607.3 1566.24  4663.9 1560.62  4706.3 1559.18  4741.8 1555.66  4794.7 1553.07
  4819.5 1550.91  4826.5 1551.78  4868.9 1549.54  4883.1  1548.1  4911.4 1542.85
  4979.5 1541.89  4983.4 1541.06  4983.9 1540.56  4995.3 1541.06  4996.2    1542
  5010.1  1543.5  5037.2 1543.02  5163.4 1544.55  5214.5 1545.92    5235 1543.77
  5240.2  1545.2  5245.3 1548.78  5255.4 1551.82  5289.8 1559.35  5408.8 1569.19
#Mann= 8 ,-1 , 0
  4423.5     .07       0  4589.7    .035       0  4794.7     .12       0
  4979.5    .035       0  4983.4    .035       0  4995.3    .035       0
  5037.2     .12       0  5163.4    .035       0
Bank Sta=4983.4,4995.3
XS Rating Curve= 0 ,0
Exp/Cntr=0.3,0.1