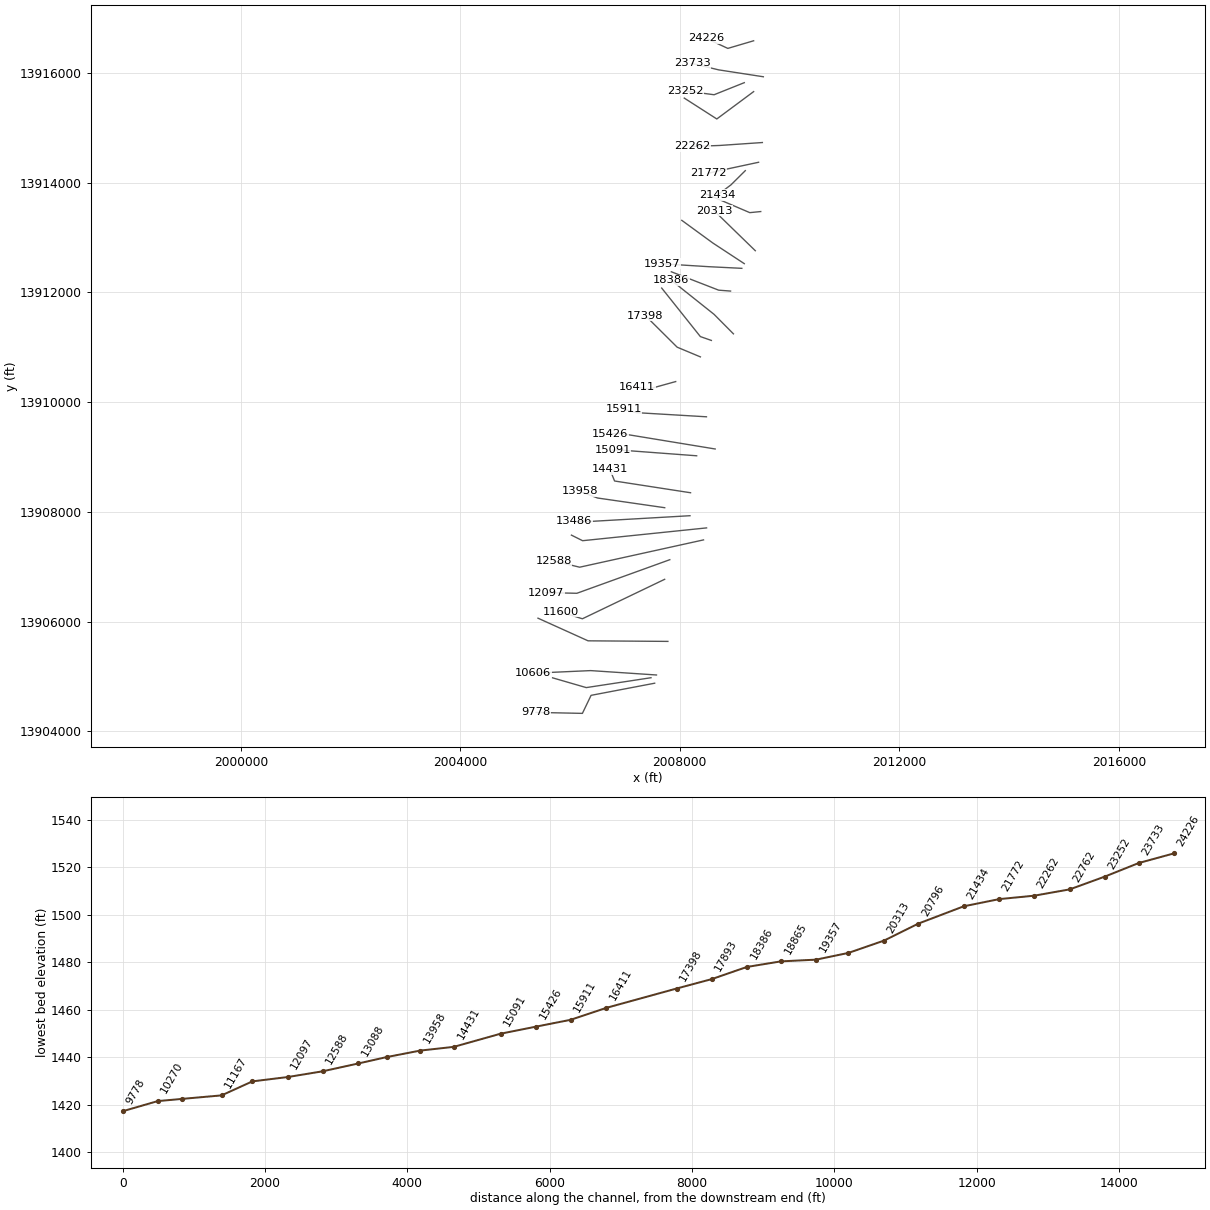
HEC-RAS study FLAT ROCK CREEK.prj: FLAT ROCK CREEK Base Level Engineering

--- FLAT ROCK CREEK.g01 (geometry) --- (continued)

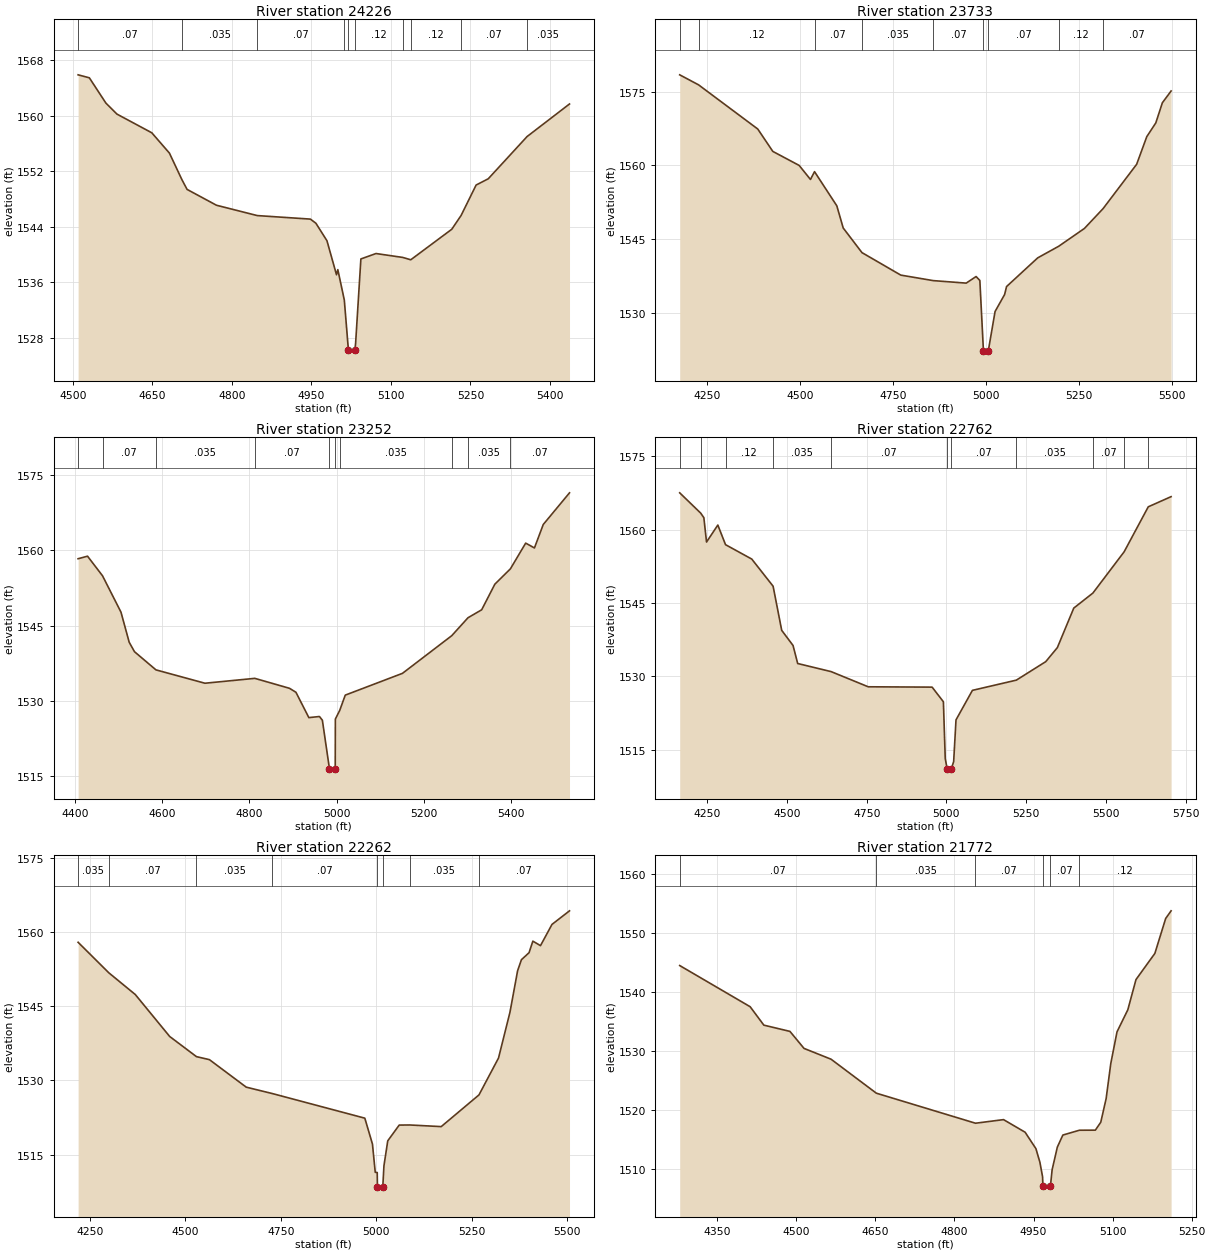
Type RM Length L Ch R = 1 ,24226   ,493,493,493
BEGIN DESCRIPTION:
FLAT ROCK CREEK_DS 40.0
END DESCRIPTION:
XS GIS Cut Line= 3
       2009345.3      13916588.8      2008875.21      13916449.9
      2008478.65      13916633.3
#Sta/Elev= 30
  4509.9 1565.91  4531.1 1565.48  4562.4 1561.83  4583.2 1560.25  4648.9 1557.56
  4682.2 1554.63  4705.7 1550.81  4715.5  1549.4  4770.9 1547.12  4847.8 1545.63
  4948.2 1545.12  4958.6 1544.52  4979.4    1542  4997.4  1537.1  4999.9 1537.84
  5012.1 1533.48  5019.8 1526.31  5020.3 1525.81  5032.2 1526.31  5033.4 1527.17
  5043.4 1539.38  5071.9 1540.16  5122.3  1539.6  5137.5 1539.26  5214.9 1543.66
  5232.5 1545.65  5260.8 1550.03  5283.7 1550.93    5357 1557.02    5437 1561.71
#Mann= 10 ,-1 , 0
  4509.9     .07       0  4705.7    .035       0  4847.8     .07       0
  5012.1     .12       0  5019.8     .05       0  5032.2     .12       0
  5122.3     .07       0  5137.5     .12       0  5232.5     .07       0
    5357    .035       0
Bank Sta=5019.8,5032.2
XS Rating Curve= 0 ,0
Exp/Cntr=0.3,0.1

Type RM Length L Ch R = 1 ,23733   ,481,481,481
BEGIN DESCRIPTION:
FLAT ROCK CREEK_DS 39.0
END DESCRIPTION:
XS GIS Cut Line= 3
      2009522.37     13915932.56      2008708.05     13916058.45
      2008225.01       13916175.
#Sta/Elev= 30
    4176 1578.42  4226.7 1576.38  4385.8 1567.39  4426.3 1562.83  4497.1 1559.98
  4527.5 1557.12  4538.4 1558.71  4598.3 1551.76  4615.5 1547.24  4665.9 1542.23
  4770.3 1537.65  4857.5 1536.53  4946.1 1536.02  4972.7 1537.36  4982.8 1536.56
  4992.4 1522.27  4992.9 1521.77  5005.6 1522.27  5023.7 1530.24  5049.3 1533.69
  5054.6 1535.32  5138.3 1541.16  5194.9 1543.53  5263.9 1547.15    5314 1551.18
  5404.3 1560.21  5431.5 1565.83  5455.8 1568.64  5473.4 1572.73  5496.9 1575.13
#Mann= 9 ,-1 , 0
    4176     .07       0  4226.7     .12       0  4538.4     .07       0
  4665.9    .035       0  4857.5     .07       0  4992.4     .05       0
  5005.6     .07       0  5194.9     .12       0    5314     .07       0
Bank Sta=4992.4,5005.6
XS Rating Curve= 0 ,0
Exp/Cntr=0.3,0.1

Type RM Length L Ch R = 1 ,23252   ,490,490,490
BEGIN DESCRIPTION:
FLAT ROCK CREEK_DS 38.0
END DESCRIPTION:
XS GIS Cut Line= 3
      2009175.04     13915825.02      2008624.64     13915604.85
      2008095.35      13915675.6
#Sta/Elev= 30
  4407.2 1558.31  4428.8 1558.82  4463.2 1554.91  4505.5 1547.67  4524.4 1541.66
  4536.5 1539.79  4585.7 1536.17    4698 1533.51  4812.4 1534.48  4891.9  1532.5
  4906.7 1531.71  4936.3 1526.66  4960.6 1526.88  4967.3 1526.14  4983.5  1516.5
    4984    1516  4996.8  1516.5  4997.1 1526.37  5007.1  1528.1  5019.8 1531.14
    5151 1535.48  5264.1 1542.99  5301.3 1546.56  5332.6 1548.14  5362.8 1553.24
  5398.5  1556.3  5433.5 1561.42  5453.6 1560.46  5473.8 1565.13    5534 1571.44
#Mann= 10 ,-1 , 0
  4407.2     .12       0  4463.2     .07       0  4585.7    .035       0
  4812.4     .07       0  4983.5     .05       0  4996.8     .07       0
  5007.1    .035       0  5264.1     .07       0  5301.3    .035       0
  5398.5     .07       0
Bank Sta=4983.5,4996.8
XS Rating Curve= 0 ,0
Exp/Cntr=0.3,0.1

Type RM Length L Ch R = 1 ,22762   ,500,500,500
BEGIN DESCRIPTION:
FLAT ROCK CREEK_DS 37.0
END DESCRIPTION:
XS GIS Cut Line= 3
      2009345.35     13915661.75      2008674.13     13915163.06
      2008081.41     13915543.68
#Sta/Elev= 30
  4163.8 1567.54  4229.6 1563.39  4239.5 1562.46  4247.9 1557.48  4283.3 1560.95
  4307.5 1556.94  4389.7    1554  4456.6 1548.45  4483.6 1539.43  4519.1 1536.34
  4533.7 1532.65  4638.6 1530.99  4754.8 1527.89  4955.1 1527.82  4990.5 1524.83
  4996.3 1513.21  5002.2 1511.15  5002.7 1510.65  5015.5 1511.15  5022.7  1512.6
    5030 1521.12  5081.5 1527.16  5219.2 1529.25  5311.4 1533.03  5347.8  1535.9
  5399.3 1543.98  5459.2 1547.05  5557.1 1555.48  5632.8 1564.68  5704.4 1566.76
#Mann= 11 ,-1 , 0
  4163.8     .12       0  4229.6     .07       0  4307.5     .12       0
  4456.6    .035       0  4638.6     .07       0  5002.2     .05       0
  5015.5     .07       0  5219.2    .035       0  5459.2     .07       0
  5557.1    .035       0  5632.8     .07       0
Bank Sta=5002.2,5015.5
XS Rating Curve= 0 ,0
Exp/Cntr=0.3,0.1

Type RM Length L Ch R = 1 ,22262   ,490,490,490
BEGIN DESCRIPTION:
FLAT ROCK CREEK_DS 36.0
END DESCRIPTION:
XS GIS Cut Line= 3
      2009504.43     13914733.49      2008725.06     13914679.97
      2008219.09     13914661.67
#Sta/Elev= 30
  4218.8 1557.98  4299.1 1551.81  4368.6  1547.4  4458.8  1538.9  4528.9 1534.82
  4562.9 1534.21  4659.3 1528.64  4727.9 1527.34    4970 1522.36    4990 1517.12
  4997.3  1511.4  5002.5 1511.35    5003 1508.49  5003.5 1507.99  5017.1 1508.49
  5020.1 1512.72  5030.1 1517.77  5060.1 1520.96  5087.9 1520.98  5170.2 1520.65
  5269.1 1527.07  5320.3 1534.54  5350.3 1543.82  5370.3 1552.21  5380.3 1554.45
  5400.3 1555.87  5410.3 1558.21  5430.3  1557.3  5460.4  1561.6  5506.3 1564.35
#Mann= 8 ,-1 , 0
  4218.8    .035       0  4299.1     .07       0  4528.9    .035       0
  4727.9     .07       0    5003     .05       0  5017.1     .07       0
  5087.9    .035       0  5269.1     .07       0
Bank Sta=5003,5017.1
XS Rating Curve= 0 ,0
Exp/Cntr=0.3,0.1

Type RM Length L Ch R = 1 ,21772   ,498,498,498
BEGIN DESCRIPTION:
FLAT ROCK CREEK_DS 35.0
END DESCRIPTION:
XS GIS Cut Line= 3
       2009435.6     13914373.53      2008730.48     13914222.56
      2008525.01       13914175.
#Sta/Elev= 30
  4278.9 1544.51  4412.5 1537.52  4438.5 1534.39    4488 1533.33  4514.7 1530.44
  4565.9 1528.61  4651.8 1522.84  4839.9 1517.74  4893.1 1518.35    4934 1516.21
  4954.5 1513.42    4962 1511.13  4967.1 1508.66  4967.8 1507.05  4968.3 1506.55
    4982 1507.05  4985.2 1509.82  4995.1 1513.68  5005.6 1515.73    5037 1516.55
  5067.2 1516.56  5077.5 1517.91  5087.7 1521.93  5096.5 1527.88  5108.3 1533.25
  5128.8    1537  5144.3 1542.13  5180.1 1546.57  5200.6  1552.5  5210.9  1553.8
#Mann= 6 ,-1 , 0
  4278.9     .07       0  4651.8    .035       0  4839.9     .07       0
  4967.8     .05       0    4982     .07       0    5037     .12       0
Bank Sta=4967.8,4982
XS Rating Curve= 0 ,0
Exp/Cntr=0.3,0.1

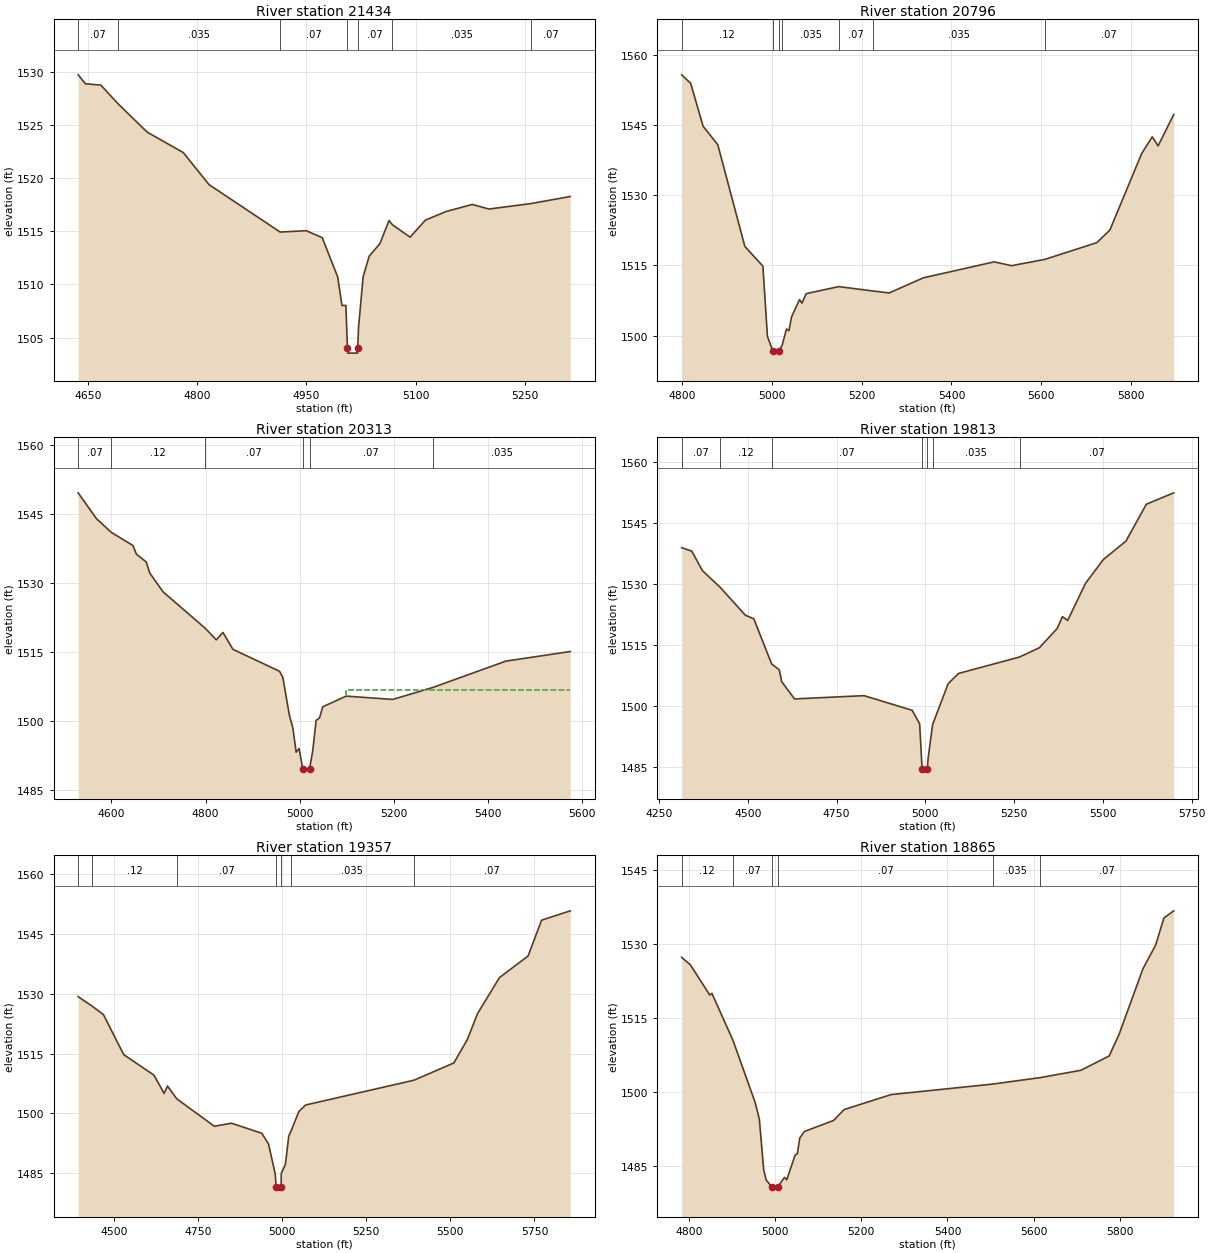
Type RM Length L Ch R = 1 ,21434   ,638,638,638
BEGIN DESCRIPTION:
FLAT ROCK CREEK_DS 34.0
END DESCRIPTION:
XS GIS Cut Line= 3
      2009193.38     13914220.79      2008932.34     13913961.68
      2008686.13     13913776.31
#Sta/Elev= 30
  4636.4 1529.74  4646.4  1528.9  4667.6 1528.77    4691 1527.03  4731.3 1524.34
  4780.8 1522.42  4816.2  1519.4    4914 1514.93  4949.8 1515.06  4971.7  1514.4
  4992.9 1510.71  4998.8 1508.02  5004.2 1508.02  5006.3 1504.03  5006.8 1503.53
    5020 1503.53  5020.5 1504.03  5021.6 1505.99  5027.9 1510.72  5036.2 1512.66
  5050.8 1513.83  5063.5 1516.02  5068.1 1515.62  5092.4 1514.45  5113.5 1516.06
  5142.4 1516.88  5177.8 1517.53  5200.7  1517.1  5257.8 1517.61  5312.4 1518.28
#Mann= 7 ,-1 , 0
  4636.4     .07       0    4691    .035       0    4914     .07       0
  5006.3     .05       0  5020.5     .07       0  5068.1    .035       0
  5257.8     .07       0
Bank Sta=5006.3,5020.5
XS Rating Curve= 0 ,0
Exp/Cntr=0.3,0.1

Type RM Length L Ch R = 1 ,20796   ,483,483,483
BEGIN DESCRIPTION:
FLAT ROCK CREEK_DS 33.0
END DESCRIPTION:
XS GIS Cut Line= 3
      2009475.03       13913475.      2009275.43     13913455.03
      2008452.99     13913807.54
#Sta/Elev= 30
  4799.4  1555.7  4819.5  1553.9  4847.2 1544.71  4879.8 1540.79  4940.1 1519.05
  4980.3 1514.82  4990.4 1499.82  5002.1 1496.74  5002.6 1496.24  5016.5 1496.74
  5023.4 1498.02  5032.8  1501.4  5038.3 1501.04    5044 1503.95  5061.8 1507.68
  5067.3 1506.92  5076.6 1508.95  5149.2 1510.45  5224.3 1509.53  5261.3  1509.1
  5337.5 1512.33  5495.2 1515.74  5533.6 1514.92  5607.9 1516.27  5723.7 1519.85
  5752.7 1522.55  5823.4 1538.88    5847 1542.46    5860 1540.52  5894.8 1547.23
#Mann= 7 ,-1 , 0
  4799.4     .12       0  5002.1     .05       0  5016.5     .12       0
  5023.4    .035       0  5149.2     .07       0  5224.3    .035       0
  5607.9     .07       0
Bank Sta=5002.1,5016.5
XS Rating Curve= 0 ,0
Exp/Cntr=0.3,0.1

Type RM Length L Ch R = 1 ,20313   ,500,500,500
BEGIN DESCRIPTION:
FLAT ROCK CREEK_DS 32.0
END DESCRIPTION:
XS GIS Cut Line= 3
      2009375.68     13912760.91      2009038.17     13913088.72
      2008626.75     13913489.98
#Sta/Elev= 30
  4529.5 1549.66  4568.3 1544.05  4600.1 1541.04    4646 1538.18  4653.2 1536.31
  4674.3 1534.59  4681.4 1532.23  4709.7 1528.12    4799 1520.21  4822.9 1517.66
  4837.1 1519.26  4858.2 1515.59  4957.2 1510.81  4964.2 1509.51  4978.3 1501.16
  4985.5  1498.5  4992.5 1493.19  4998.7 1493.99  5006.5 1489.57    5007 1489.07
  5021.1 1489.57  5027.9 1493.62  5034.9  1500.1  5042.1 1500.65  5049.1 1503.08
  5098.7  1505.4  5197.7 1504.68  5282.4 1507.27    5438 1513.02  5574.7 1515.11
#Mann= 6 ,-1 , 0
  4529.5     .07       0  4600.1     .12       0    4799     .07       0
  5006.5     .05       0  5021.1     .07       0  5282.4    .035       0
#XS Ineff= 2 , 0
       0                 5098.56       0 1506.81
Permanent Ineff=
       F       F
Bank Sta=5006.5,5021.1
XS Rating Curve= 0 ,0
Exp/Cntr=0.3,0.1

Type RM Length L Ch R = 1 ,19813   ,456,456,456
BEGIN DESCRIPTION:
FLAT ROCK CREEK_DS 31.0
END DESCRIPTION:
XS GIS Cut Line= 3
      2009174.96     13912525.03      2008601.27     13912901.88
       2008036.3      13913314.5
#Sta/Elev= 30
  4313.6 1538.97  4342.2 1538.11  4372.3 1533.29  4421.1  1529.3    4493 1522.33
  4516.9 1521.43  4567.2 1510.29  4588.7 1508.85  4595.3 1505.97  4631.5 1501.68
  4827.3 1502.49  4962.9 1498.87    4984 1495.54  4990.9 1484.38  4991.4 1483.88
  5005.6 1484.38  5007.7 1486.95  5020.5 1495.38  5064.1 1505.41  5093.4 1507.96
  5265.2 1512.01  5321.2  1514.3  5371.4 1519.05  5386.1 1521.97  5400.8 1521.02
    5451 1530.16  5501.2 1536.03    5565 1540.58  5622.4 1549.68  5699.6 1552.49
#Mann= 7 ,-1 , 0
  4313.6     .07       0  4421.1     .12       0  4567.2     .07       0
  4990.9     .05       0  5005.6     .07       0  5020.5    .035       0
  5265.2     .07       0
Bank Sta=4990.9,5005.6
XS Rating Curve= 0 ,0
Exp/Cntr=0.3,0.1

Type RM Length L Ch R = 1 ,19357   ,492,492,492
BEGIN DESCRIPTION:
FLAT ROCK CREEK_DS 30.0
END DESCRIPTION:
XS GIS Cut Line= 3
      2009130.21     13912439.64      2008524.56     13912469.82
      2007669.91     13912523.03
#Sta/Elev= 30
  4393.6 1529.24    4435 1526.89  4468.9 1524.73    4529 1514.73  4619.1 1509.58
  4649.1 1505.01  4659.1 1506.86  4686.8 1503.65  4798.5 1496.79  4849.4 1497.55
  4939.5 1495.02  4959.5 1492.36  4979.5 1484.77  4982.1 1481.54  4982.6 1481.04
  4996.9 1481.54  4997.3 1484.93  5009.6 1487.24  5019.6 1494.33  5025.4 1495.38
  5049.7 1500.48  5069.7 1502.11  5391.8 1508.32  5510.5 1512.65  5550.6 1518.54
  5580.7    1525  5646.2 1534.04    5731 1539.43    5771 1548.39  5856.3 1550.74
#Mann= 7 ,-1 , 0
  4393.6     .07       0    4435     .12       0  4686.8     .07       0
  4982.1     .05       0  4996.9     .07       0  5025.4    .035       0
  5391.8     .07       0
Bank Sta=4982.1,4996.9
XS Rating Curve= 0 ,0
Exp/Cntr=0.3,0.1

Type RM Length L Ch R = 1 ,18865   ,479,479,479
BEGIN DESCRIPTION:
FLAT ROCK CREEK_DS 29.0
END DESCRIPTION:
XS GIS Cut Line= 3
        2008925.       13912025.      2008708.13     13912041.56
      2007845.34     13912376.99
#Sta/Elev= 30
  4782.5 1527.31  4802.6 1525.81  4847.9 1519.66  4852.9    1520  4901.9 1510.45
    4953 1497.96    4963 1494.55  4973.1 1484.26  4978.8 1482.19  4991.6 1480.82
  4992.1 1480.32  5006.5 1480.82  5021.4 1482.71  5026.7 1482.22  5045.9 1487.16
  5051.3 1487.51    5057 1490.69  5067.7    1492  5135.6 1494.24  5160.1 1496.45
  5268.9 1499.48  5505.1 1501.61  5615.1 1502.92  5709.7  1504.4  5775.9 1507.32
  5799.4 1511.85  5853.8 1524.91  5883.7  1529.8  5902.8 1535.27  5925.7 1536.73
#Mann= 6 ,-1 , 0
  4782.5     .12       0  4901.9     .07       0  4991.6     .05       0
  5006.5     .07       0  5505.1    .035       0  5615.1     .07       0
Bank Sta=4991.6,5006.5
XS Rating Curve= 0 ,0
Exp/Cntr=0.3,0.1

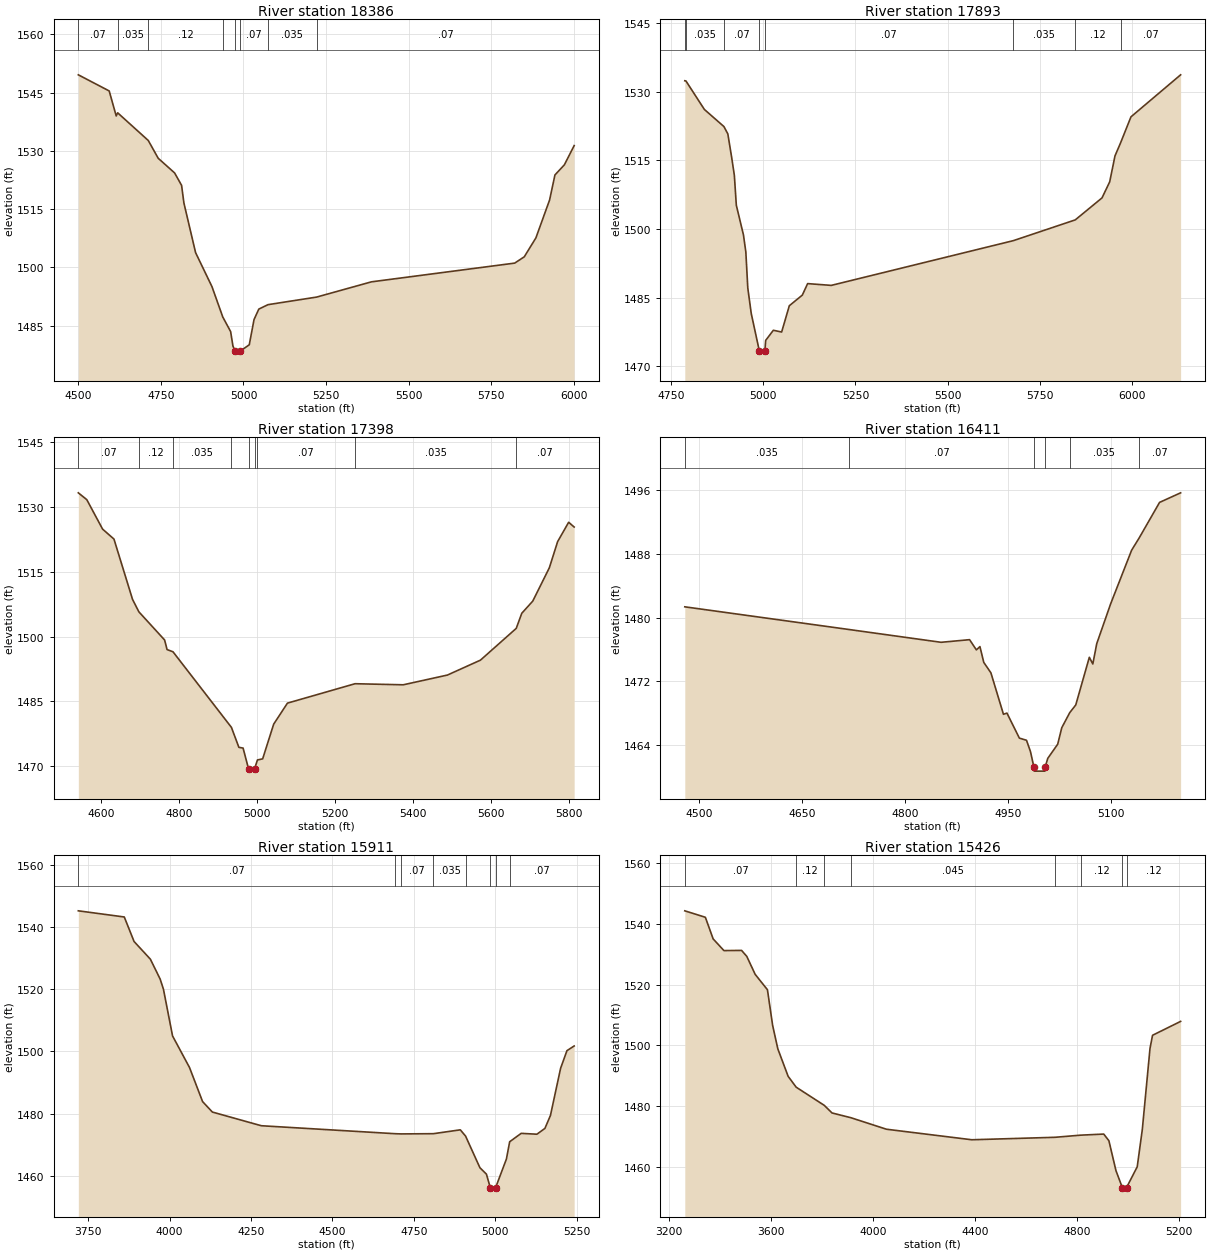
Type RM Length L Ch R = 1 ,18386   ,493,493,493
BEGIN DESCRIPTION:
FLAT ROCK CREEK_DS 28.0
END DESCRIPTION:
XS GIS Cut Line= 3
      2008977.29     13911245.03      2008625.01       13911600.
      2007841.85     13912224.22
#Sta/Elev= 30
  4499.9 1549.57  4593.4 1545.42  4614.6 1538.99  4619.1 1539.79  4711.7 1532.68
  4741.9 1528.09  4791.4 1524.34  4812.6 1521.14  4819.7 1516.57    4855 1503.83
  4904.6 1495.08  4937.4 1487.26  4961.1 1483.52  4968.2 1479.78  4974.8 1478.47
  4975.3 1477.97  4989.9 1478.47  5017.6 1480.12    5032  1486.6  5046.5  1489.3
  5074.4 1490.44  5221.7 1492.39  5387.6 1496.31  5821.5 1501.13  5850.4 1502.75
  5885.6 1507.61  5927.1 1517.36  5943.3 1523.81  5971.9 1526.42  6001.5 1531.36
#Mann= 8 ,-1 , 0
  4499.9     .07       0  4619.1    .035       0  4711.7     .12       0
  4937.4     .07       0  4974.8     .05       0  4989.9     .07       0
  5074.4    .035       0  5221.7     .07       0
Bank Sta=4974.8,4989.9
XS Rating Curve= 0 ,0
Exp/Cntr=0.3,0.1

Type RM Length L Ch R = 1 ,17893   ,495,495,495
BEGIN DESCRIPTION:
FLAT ROCK CREEK_DS 27.0
END DESCRIPTION:
XS GIS Cut Line= 3
      2008575.01       13911125.      2008374.63     13911195.12
      2007669.86     13912079.82
#Sta/Elev= 30
  4787.7 1532.44  4790.8  1532.4  4840.7 1526.17  4893.7 1522.42  4904.3 1520.82
  4914.8 1515.62    4922 1511.72  4927.3 1505.21  4946.6 1498.73  4953.1 1494.97
  4958.4 1487.08  4967.8  1481.5  4989.6 1473.35  4990.1 1472.85  5004.8 1473.35
  5006.8 1475.63  5027.6 1477.85  5050.1 1477.47  5070.9 1483.22  5106.1 1485.54
  5120.5 1488.06  5184.6 1487.67  5677.9 1497.46  5845.6    1502  5918.1 1506.81
  5938.9 1510.32  5953.3 1516.01  5968.3 1518.83  5996.6 1524.55  6131.1 1533.74
#Mann= 8 ,-1 , 0
  4787.7     .07       0  4790.8    .035       0  4893.7     .07       0
  4989.6     .05       0  5004.8     .07       0  5677.9    .035       0
  5845.6     .12       0  5968.3     .07       0
Bank Sta=4989.6,5004.8
XS Rating Curve= 0 ,0
Exp/Cntr=0.3,0.1

Type RM Length L Ch R = 1 ,17398   ,987,987,987
BEGIN DESCRIPTION:
FLAT ROCK CREEK_DS 26.0
END DESCRIPTION:
XS GIS Cut Line= 3
      2008374.98     13910825.01      2007951.56     13911001.94
      2007375.01     13911574.99
#Sta/Elev= 30
  4541.1 1533.25  4562.8 1531.67  4603.3 1524.86  4632.5 1522.55  4680.1 1508.61
  4696.4 1505.72  4762.4 1499.21  4768.7 1496.99  4783.9 1496.48  4933.8 1478.99
  4952.9 1474.38  4963.7  1474.2  4977.8 1469.37  4978.3 1468.87  4993.1 1469.37
  5000.5 1471.45  5013.9 1471.71  5042.2 1479.74  5077.5  1484.6  5250.9 1489.09
  5374.5 1488.84  5487.7 1491.09  5572.5 1494.54  5664.3 1501.89  5678.6 1505.39
  5706.8 1508.21  5749.3 1515.92  5770.5 1521.96  5798.8 1526.44  5812.9 1525.34
#Mann= 9 ,-1 , 0
  4541.1     .07       0  4696.4     .12       0  4783.9    .035       0
  4933.8     .12       0  4977.8     .05       0  4993.1     .12       0
  5000.5     .07       0  5250.9    .035       0  5664.3     .07       0
Bank Sta=4977.8,4993.1
XS Rating Curve= 0 ,0
Exp/Cntr=0.3,0.1

Type RM Length L Ch R = 1 ,16411   ,500,500,500
BEGIN DESCRIPTION:
FLAT ROCK CREEK_DS 25.0
END DESCRIPTION:
XS GIS Cut Line= 3
      2007925.05     13910375.01      2007423.33     13910235.69
      2007224.99       13910275.
#Sta/Elev= 30
  4479.3 1481.34  4719.1 1478.49    4853 1476.89  4894.5 1477.22  4904.4 1475.94
  4909.6 1476.35  4915.2 1474.37  4925.6 1473.06  4943.9 1467.86    4949 1468.01
  4967.1 1464.87  4977.5  1464.6  4983.3 1463.18  4988.3 1461.23  4988.8 1460.73
  5004.2 1460.73  5004.7 1461.23  5008.5 1462.33    5023 1464.11  5028.9 1466.17
  5040.5 1468.06  5049.3 1469.03  5069.1 1475.01  5074.2 1474.17  5079.9 1476.72
  5100.2 1481.72  5130.8 1488.45  5141.7 1489.97  5171.5 1494.44  5202.2 1495.64
#Mann= 6 ,-1 , 0
  4479.3    .035       0  4719.1     .07       0  4988.3     .05       0
  5004.7     .07       0  5040.5    .035       0  5141.7     .07       0
Bank Sta=4988.3,5004.7
XS Rating Curve= 0 ,0
Exp/Cntr=0.3,0.1

Type RM Length L Ch R = 1 ,15911   ,485,485,485
BEGIN DESCRIPTION:
FLAT ROCK CREEK_DS 24.0
END DESCRIPTION:
XS GIS Cut Line= 3
       2008485.8      13909732.7      2007208.05     13909808.45
      2006974.97     13909875.01
#Sta/Elev= 30
    3720 1545.22  3861.1 1543.24  3891.1 1535.36  3941.2 1529.67  3971.2 1523.28
  3981.3 1520.03  4009.3 1504.99  4061.4 1494.82  4101.5 1483.87  4131.5  1480.5
  4281.8  1476.1  4693.5 1473.53  4711.2 1473.47  4810.1 1473.54  4892.9 1474.78
  4909.1 1472.75    4953  1462.6    4973 1460.53  4984.8 1456.21  4985.3 1455.71
  5001.3 1456.21  5034.4 1465.39  5044.4 1470.95  5079.8 1473.65    5128 1473.37
  5152.6 1475.24  5169.6  1479.4  5200.8 1494.58  5220.3 1500.25  5242.4 1501.75
#Mann= 8 ,-1 , 0
    3720     .07       0  4693.5    .035       0  4711.2     .07       0
  4810.1    .035       0  4909.1     .12       0  4984.8     .05       0
  5001.3     .12       0  5044.4     .07       0
Bank Sta=4984.8,5001.3
XS Rating Curve= 0 ,0
Exp/Cntr=0.3,0.1

Type RM Length L Ch R = 1 ,15426   ,498,498,498
BEGIN DESCRIPTION:
FLAT ROCK CREEK_DS 23.0
END DESCRIPTION:
XS GIS Cut Line= 3
      2008644.55     13909145.68      2006930.83      13909427.3
      2006725.04       13909425.
#Sta/Elev= 30
  3263.3 1544.22  3343.9  1542.1  3374.3 1535.01  3416.6 1531.16  3485.8 1531.22
  3506.1 1529.27  3539.1 1523.35  3587.1 1518.31  3607.4 1506.62  3627.7 1498.92
  3668.2 1489.87  3699.6 1486.31  3809.5 1480.35  3840.2 1477.84  3914.1 1476.28
  4053.3  1472.5  4387.7 1469.04  4713.5 1469.85  4813.9 1470.55  4904.6 1470.91
  4924.8 1468.72  4952.6 1458.87  4977.4 1453.33  4977.9 1452.83  4993.9 1453.33
  5035.8 1460.17  5055.8 1472.47  5085.8 1499.01  5095.8 1503.35  5205.8 1507.91
#Mann= 8 ,-1 , 0
  3263.3     .07       0  3699.6     .12       0  3809.5     .07       0
  3914.1    .045       0  4713.5     .07       0  4813.9     .12       0
  4977.4     .05       0  4993.9     .12       0
Bank Sta=4977.4,4993.9
XS Rating Curve= 0 ,0
Exp/Cntr=0.3,0.1

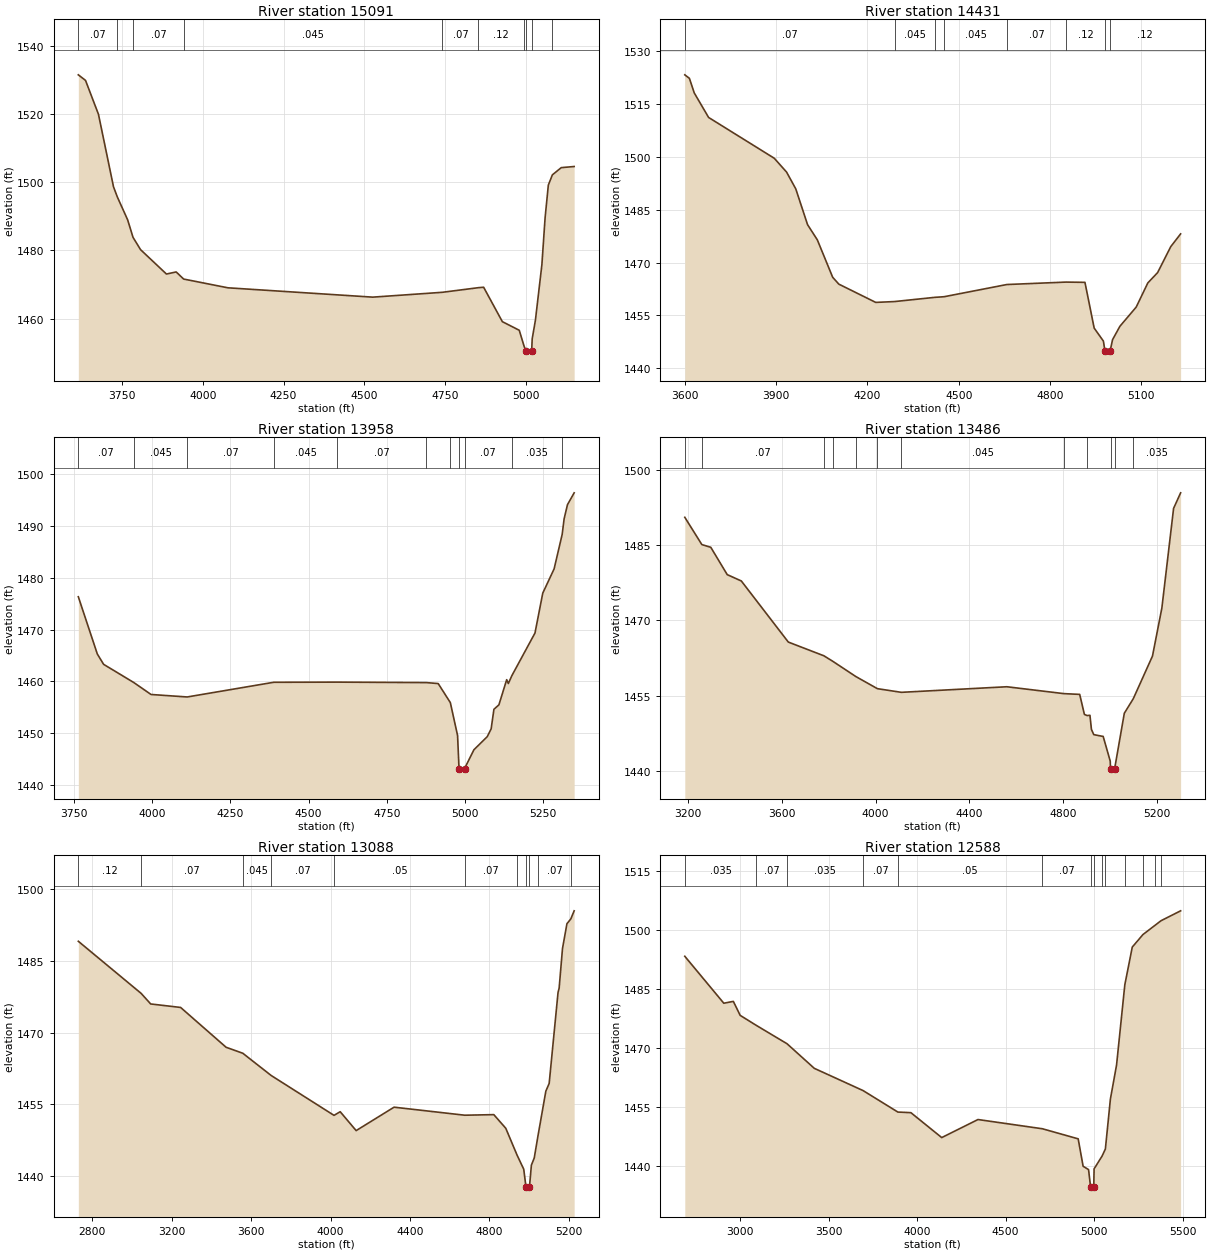
Type RM Length L Ch R = 1 ,15091   ,660,660,660
BEGIN DESCRIPTION:
FLAT ROCK CREEK_DS 22.0
END DESCRIPTION:
XS GIS Cut Line= 3
      2008307.24     13909021.75       2006925.4     13909125.17
        2006775.       13909125.
#Sta/Elev= 30
  3614.3 1531.54  3636.6  1529.9  3676.7 1519.95  3723.3 1498.67  3735.3 1495.66
    3767    1489  3783.7 1483.85  3807.1 1480.23  3887.3 1473.07  3917.4 1473.69
  3940.5  1471.6  4077.8 1469.03  4526.4 1466.29  4741.9 1467.71  4853.9 1469.07
    4870 1469.19    4928 1459.09  4980.3 1456.57  4995.5 1451.83  5002.2 1450.36
  5002.7 1449.86  5018.7 1450.36  5020.4 1454.05  5030.4 1459.54  5050.4 1475.79
  5060.4  1489.6  5070.4 1499.17  5082.9 1502.18  5110.4  1504.3  5150.4 1504.63
#Mann= 10 ,-1 , 0
  3614.3     .07       0  3735.3     .12       0  3783.7     .07       0
  3940.5    .045       0  4741.9     .07       0  4853.9     .12       0
  4995.5     .07       0  5002.2     .05       0  5018.7     .07       0
  5082.9     .12       0
Bank Sta=5002.2,5018.7
XS Rating Curve= 0 ,0
Exp/Cntr=0.3,0.1

Type RM Length L Ch R = 1 ,14431   ,473,473,473
BEGIN DESCRIPTION:
FLAT ROCK CREEK_DS 21.0
END DESCRIPTION:
XS GIS Cut Line= 3
      2008195.76     13908347.78      2006811.31     13908561.85
      2006724.99     13908775.03
#Sta/Elev= 30
  3599.1 1523.37  3614.3 1522.37  3630.2 1518.23  3677.4 1511.26  3893.3 1499.67
  3933.8 1495.75  3964.1 1490.98  4002.9  1480.8    4035 1476.49  4085.6 1465.84
  4105.8  1463.9  4227.2 1458.71    4289 1458.95  4420.5 1460.14  4452.3 1460.33
  4658.4 1463.79  4852.5 1464.48  4915.3 1464.41  4945.7 1451.41    4976 1447.72
  4981.3  1444.8  4981.8  1444.3  4997.8  1444.8  5006.1 1448.12  5030.3 1451.93
  5083.9 1457.38  5122.1 1464.24  5154.4 1467.19  5197.6 1474.56    5230 1478.18
#Mann= 8 ,-1 , 0
  3599.1     .07       0    4289    .045       0  4420.5     .07       0
  4452.3    .045       0  4658.4     .07       0  4852.5     .12       0
  4981.3     .05       0  4997.8     .12       0
Bank Sta=4981.3,4997.8
XS Rating Curve= 0 ,0
Exp/Cntr=0.3,0.1

Type RM Length L Ch R = 1 ,13958   ,472,472,472
BEGIN DESCRIPTION:
FLAT ROCK CREEK_DS 20.0
END DESCRIPTION:
XS GIS Cut Line= 3
      2007725.02       13908075.      2006501.61     13908251.69
      2006175.01       13908375.
#Sta/Elev= 30
  3763.9 1476.32  3824.5 1465.31  3844.7  1463.3  3941.3 1459.79  3996.3 1457.49
    4112 1457.01  4388.5 1459.84  4592.1 1459.87  4876.6 1459.78  4914.5 1459.59
  4953.2 1455.93  4976.4 1449.58    4981 1443.22  4981.5 1442.72  4998.7 1443.22
  5028.7 1446.84  5071.2 1449.36  5083.7 1450.86  5092.6 1454.64  5108.5 1455.49
  5133.4 1460.34  5138.7  1459.6  5149.7 1461.09  5223.9 1469.34  5248.8 1477.03
    5285 1481.69  5310.8 1488.34    5317 1491.34  5327.7 1494.06  5349.1 1496.35
#Mann= 11 ,-1 , 0
  3763.9     .07       0  3941.3    .045       0    4112     .07       0
  4388.5    .045       0  4592.1     .07       0  4876.6     .12       0
  4953.2     .07       0    4981     .05       0  4998.7     .07       0
  5149.7    .035       0  5310.8     .07       0
Bank Sta=4981,4998.7
XS Rating Curve= 0 ,0
Exp/Cntr=0.3,0.1

Type RM Length L Ch R = 1 ,13486   ,398,398,398
BEGIN DESCRIPTION:
FLAT ROCK CREEK_DS 19.0
END DESCRIPTION:
XS GIS Cut Line= 3
      2008185.59     13907929.08      2006375.08     13907824.97
      2006074.98       13907825.
#Sta/Elev= 30
  3186.5 1490.49  3259.2 1485.06  3297.3 1484.52  3367.4 1479.08  3427.5 1477.82
  3627.8 1465.66  3779.5 1462.93  3817.2 1461.84  3915.7  1458.8  4007.5 1456.39
  4109.5 1455.66  4559.2 1456.77  4802.7  1455.4  4869.9 1455.25  4889.9 1451.27
  4901.3 1451.04  4913.6 1451.09  4919.9 1448.28    4930 1447.24    4970 1446.88
    5000 1441.98  5001.2 1440.48  5001.7 1439.98  5018.9 1440.48  5060.1  1451.5
  5098.4  1454.4  5180.1 1462.87  5220.1 1472.42  5270.1 1492.26  5300.1 1495.36
#Mann= 12 ,-1 , 0
  3186.5    .035       0  3259.2     .07       0  3779.5    .045       0
  3817.2     .07       0  3915.7    .045       0  4007.5     .07       0
  4109.5    .045       0  4802.7     .07       0  4901.3     .12       0
  5001.2     .05       0  5018.9     .12       0  5098.4    .035       0
Bank Sta=5001.2,5018.9
XS Rating Curve= 0 ,0
Exp/Cntr=0.3,0.1

Type RM Length L Ch R = 1 ,13088   ,500,500,500
BEGIN DESCRIPTION:
FLAT ROCK CREEK_DS 18.0
END DESCRIPTION:
XS GIS Cut Line= 3
      2008487.72     13907706.86      2006228.75     13907473.45
      2006024.96     13907575.02
#Sta/Elev= 30
    2729 1489.13  3045.3 1478.24  3093.7 1476.02  3244.5 1475.29  3473.7 1466.96
  3557.8 1465.71  3701.1 1461.05  4017.5 1452.72  4048.7 1453.48  4129.1 1449.53
  4320.1 1454.43  4676.3 1452.75  4822.8 1452.87  4883.1 1450.02  4940.2 1444.39
  4973.6 1441.46  4984.8 1437.79  4985.3 1437.29  5002.6 1437.79  5012.2 1442.31
  5026.5 1443.79    5045 1448.34    5085 1457.78  5101.8  1459.4  5146.5 1478.43
  5152.1 1479.34  5168.9  1487.6  5191.3 1492.81  5210.8  1493.8  5227.7  1495.5
#Mann= 11 ,-1 , 0
    2729     .12       0  3045.3     .07       0  3557.8    .045       0
  3701.1     .07       0  4017.5     .05       0  4676.3     .07       0
  4940.2     .12       0  4984.8     .05       0  5002.6     .12       0
    5045     .07       0  5210.8    .035       0
Bank Sta=4984.8,5002.6
XS Rating Curve= 0 ,0
Exp/Cntr=0.3,0.1

Type RM Length L Ch R = 1 ,12588   ,491,491,491
BEGIN DESCRIPTION:
FLAT ROCK CREEK_DS 17.0
END DESCRIPTION:
XS GIS Cut Line= 3
      2008432.11     13907488.11      2006174.57     13906990.18
      2005699.72     13907106.11
#Sta/Elev= 30
  2688.2 1493.32  2908.5 1481.36  2962.4 1481.83    3001 1478.27  3092.6  1475.7
  3265.6 1471.04  3419.8 1464.77  3695.5  1459.1  3891.8 1453.63  3965.3 1453.48
  4139.4 1447.13  4344.2 1451.73    4708 1449.38  4910.2 1446.81  4938.1 1439.82
  4968.8 1438.98  4980.4  1434.5  4980.9    1434  4998.2  1434.5    5000 1439.16
  5045.8 1442.47  5063.8 1444.23  5092.2 1456.95    5127 1465.63  5173.6 1486.05
  5215.7 1495.66  5275.9 1498.85  5346.2 1501.28  5378.1 1502.38  5488.8  1504.9
#Mann= 14 ,-1 , 0
  2688.2    .035       0  3092.6     .07       0  3265.6    .035       0
  3695.5     .07       0  3891.8     .05       0    4708     .07       0
  4980.4     .05       0  4998.2     .07       0  5045.8     .12       0
  5063.8     .07       0  5173.6    .035       0  5275.9     .07       0
  5346.2    .035       0  5378.1     .07       0
Bank Sta=4980.4,4998.2
XS Rating Curve= 0 ,0
Exp/Cntr=0.3,0.1

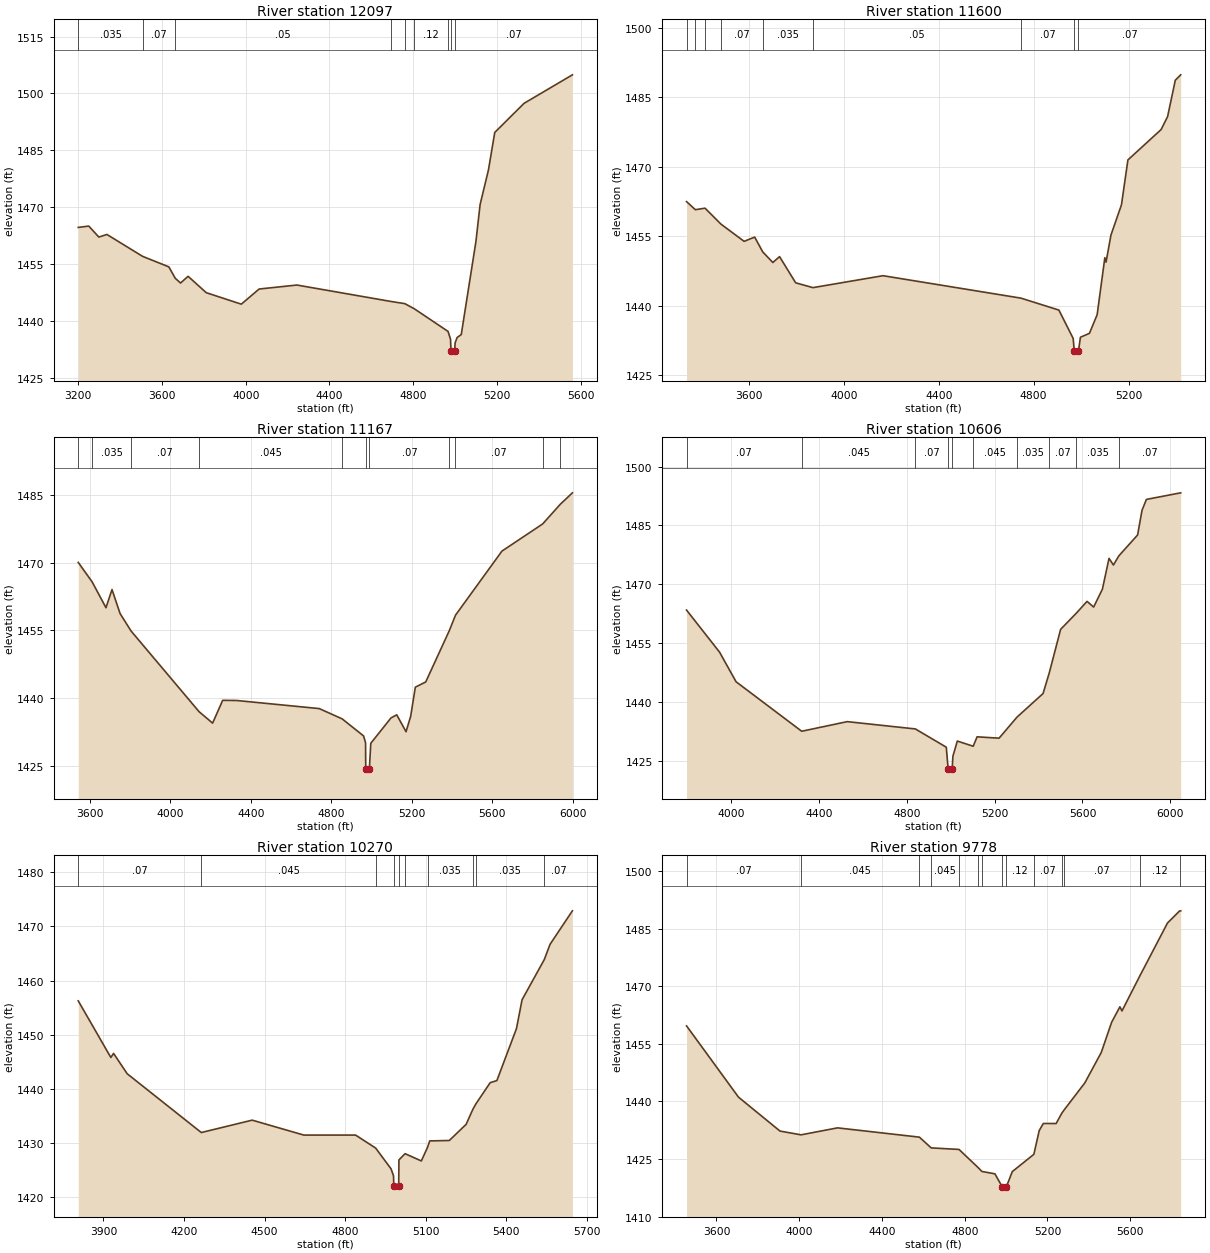
Type RM Length L Ch R = 1 ,12097   ,497,497,497
BEGIN DESCRIPTION:
FLAT ROCK CREEK_DS 16.0
END DESCRIPTION:
XS GIS Cut Line= 3
      2007817.56     13907127.01      2006124.55     13906514.81
      2005564.07      13906526.3
#Sta/Elev= 30
  3199.7  1464.7    3250 1465.06  3298.1 1462.16  3336.6 1462.85  3507.4 1457.07
  3632.5 1454.31  3663.4 1451.29  3688.5 1450.05  3724.5 1451.82  3811.2 1447.51
  3978.7 1444.48  4063.8 1448.47  4244.4 1449.52  4693.2  1445.2  4759.8 1444.62
  4804.9 1443.28  4966.5  1437.3  4978.3 1435.23  4980.5 1432.08    4981 1431.58
  4998.4 1432.08    5000 1434.25  5009.6 1435.68  5029.6 1436.48  5099.6 1460.97
  5119.6 1470.73  5159.6 1479.89  5189.6 1489.73  5329.6  1497.4  5560.6 1504.91
#Mann= 9 ,-1 , 0
  3199.7    .035       0  3507.4     .07       0  3663.4     .05       0
  4693.2     .12       0  4759.8     .07       0  4804.9     .12       0
  4966.5     .07       0  4980.5     .05       0  4998.4     .07       0
Bank Sta=4980.5,4998.4
XS Rating Curve= 0 ,0
Exp/Cntr=0.3,0.1

Type RM Length L Ch R = 1 ,11600   ,433,433,433
BEGIN DESCRIPTION:
FLAT ROCK CREEK_DS 15.0
END DESCRIPTION:
XS GIS Cut Line= 3
      2007723.79     13906769.36       2006224.8     13906049.92
      2005824.47     13906175.61
#Sta/Elev= 30
  3337.3 1462.49  3374.4 1460.74  3415.3 1461.07  3482.2 1457.63    3580  1453.9
  3624.4 1454.82  3658.5 1451.61    3701 1449.33  3729.2  1450.6  3797.2 1444.94
    3870  1443.9  4165.1 1446.48  4746.5 1441.63  4906.4 1439.05  4966.5 1432.92
    4971 1430.25  4971.5 1429.75  4988.9 1430.25    4997 1433.18  5035.1 1434.03
  5067.5 1438.05  5099.9 1450.37  5105.1 1449.42  5125.6 1455.25    5170  1461.8
  5197.1 1471.49  5337.3 1478.07  5364.4 1480.86  5396.8 1488.71  5419.6 1489.88
#Mann= 9 ,-1 , 0
  3337.3    .035       0  3374.4     .07       0  3415.3    .035       0
  3482.2     .07       0  3658.5    .035       0    3870     .05       0
  4746.5     .07       0    4971     .05       0  4988.9     .07       0
Bank Sta=4971,4988.9
XS Rating Curve= 0 ,0
Exp/Cntr=0.3,0.1

Type RM Length L Ch R = 1 ,11167   ,561,561,561
BEGIN DESCRIPTION:
FLAT ROCK CREEK_DS 14.0
END DESCRIPTION:
XS GIS Cut Line= 3
      2007782.82     13905637.41      2006327.96     13905647.83
      2005415.88     13906060.52
#Sta/Elev= 30
  3541.9 1470.07  3610.7 1465.78  3679.7 1460.04  3709.7 1464.06  3749.7 1458.76
  3804.1  1454.9  4142.3 1437.02  4209.7 1434.48  4259.7 1439.53  4329.7 1439.49
  4739.8  1437.7  4853.7 1435.42  4959.8 1431.65  4969.8 1430.16  4970.8 1424.35
  4971.3 1423.85  4988.8 1424.35  4995.8 1430.01  5096.2 1435.63  5124.8 1436.32
    5171 1432.58  5194.1    1436  5217.2 1442.44  5268.9  1443.6  5386.3 1454.98
  5416.8 1458.38  5647.6 1472.57    5850 1478.59  5938.2 1482.97  5997.9 1485.48
#Mann= 11 ,-1 , 0
  3541.9     .07       0  3610.7    .035       0  3804.1     .07       0
  4142.3    .045       0  4853.7     .07       0  4970.8     .05       0
  4988.8     .07       0  5386.3    .035       0  5416.8     .07       0
    5850    .035       0  5938.2     .07       0
Bank Sta=4970.8,4988.8
XS Rating Curve= 0 ,0
Exp/Cntr=0.3,0.1

Type RM Length L Ch R = 1 ,10606   ,336,336,336
BEGIN DESCRIPTION:
FLAT ROCK CREEK_DS 13.0
END DESCRIPTION:
XS GIS Cut Line= 3
      2007574.96       13905025.      2006375.02     13905104.99
      2005328.99      13905057.6
#Sta/Elev= 30
  3797.4 1463.42  3947.7  1452.7  4022.9 1445.14  4321.7 1432.52    4529 1434.97
  4839.1 1433.11    4980 1428.45  4988.4 1422.85  4988.9 1422.35  5006.6 1422.85
    5010 1426.14  5030.1 1430.02  5102.4  1428.7  5120.1  1431.1  5220.2 1430.75
  5302.2 1436.14  5420.5 1442.14  5448.8 1447.42  5500.5 1458.51  5572.6 1462.67
  5620.7 1465.64  5650.7 1464.19  5690.7 1468.76  5720.8 1476.61  5740.8 1474.91
  5765.4 1477.24  5850.9 1482.57  5870.9 1488.86  5890.9 1491.64  6047.1 1493.32
#Mann= 10 ,-1 , 0
  3797.4     .07       0  4321.7    .045       0  4839.1     .07       0
  4988.4     .05       0  5006.6     .07       0  5102.4    .045       0
  5302.2    .035       0  5448.8     .07       0  5572.6    .035       0
  5765.4     .07       0
Bank Sta=4988.4,5006.6
XS Rating Curve= 0 ,0
Exp/Cntr=0.3,0.1

Type RM Length L Ch R = 1 ,10270   ,492,492,492
BEGIN DESCRIPTION:
FLAT ROCK CREEK_DS 12.0
END DESCRIPTION:
XS GIS Cut Line= 3
      2007475.03       13904975.      2006295.09     13904794.96
      2005674.99       13904975.
#Sta/Elev= 30
  3806.4 1456.24  3927.8 1445.77  3937.9 1446.53  3988.5 1442.77  4264.4  1431.9
  4453.8 1434.19    4646 1431.43  4838.7 1431.43  4913.3 1429.03  4970.7 1425.19
  4979.9  1423.9  4980.9 1421.94  4981.4 1421.44  4999.1 1421.94    5000 1426.84
  5022.9 1427.99  5083.4 1426.65    5107 1429.23  5114.6 1430.35  5187.5 1430.43
    5250 1433.41  5275.4 1436.21  5286.9 1437.23  5339.7 1441.12  5364.5  1441.5
  5437.4  1451.1  5458.3 1456.44  5540.9 1463.86  5562.4 1466.68  5645.7 1472.88
#Mann= 10 ,-1 , 0
  3806.4     .07       0  4264.4    .045       0  4913.3     .07       0
  4980.9     .05       0  4999.1     .07       0  5022.9    .045       0
    5107    .035       0  5275.4     .07       0  5286.9    .035       0
  5540.9     .07       0
Bank Sta=4980.9,4999.1
XS Rating Curve= 0 ,0
Exp/Cntr=0.3,0.1

Type RM Length L Ch R = 1 ,9778    ,524,524,524
BEGIN DESCRIPTION:
FLAT ROCK CREEK_DS 11.0
END DESCRIPTION:
XS GIS Cut Line= 4
      2007541.97     13904874.98      2006383.06     13904653.74
      2006225.08     13904324.97      2005381.16     13904342.77
#Sta/Elev= 30
  3455.4  1459.7  3706.8 1441.12    3907  1432.3  4008.7 1431.31  4185.3 1433.13
  4581.1 1430.71  4638.1 1427.91  4772.5 1427.51  4863.6 1422.85  4883.3 1421.77
  4946.2 1421.15  4982.4 1417.67  4982.9 1417.17  5000.6 1417.67  5030.1 1421.74
  5134.3 1426.24  5160.1 1432.41  5180.1 1434.27  5241.9 1434.26  5269.3 1436.94
  5281.6 1437.87  5380.2 1444.81  5460.2 1452.78  5510.2 1460.64  5550.2 1464.67
  5560.2 1463.59  5647.2 1472.78  5780.2 1486.49  5838.9 1489.65  5844.1 1489.67
#Mann= 14 ,-1 , 0
  3455.4     .07       0  4008.7    .045       0  4581.1     .07       0
  4638.1    .045       0  4772.5    .035       0  4863.6     .07       0
  4883.3     .12       0  4982.4     .05       0  5000.6     .12       0
  5134.3     .07       0  5269.3     .12       0  5281.6     .07       0
  5647.2     .12       0  5838.9     .07       0
Bank Sta=4982.4,5000.6
XS Rating Curve= 0 ,0
Exp/Cntr=0.3,0.1