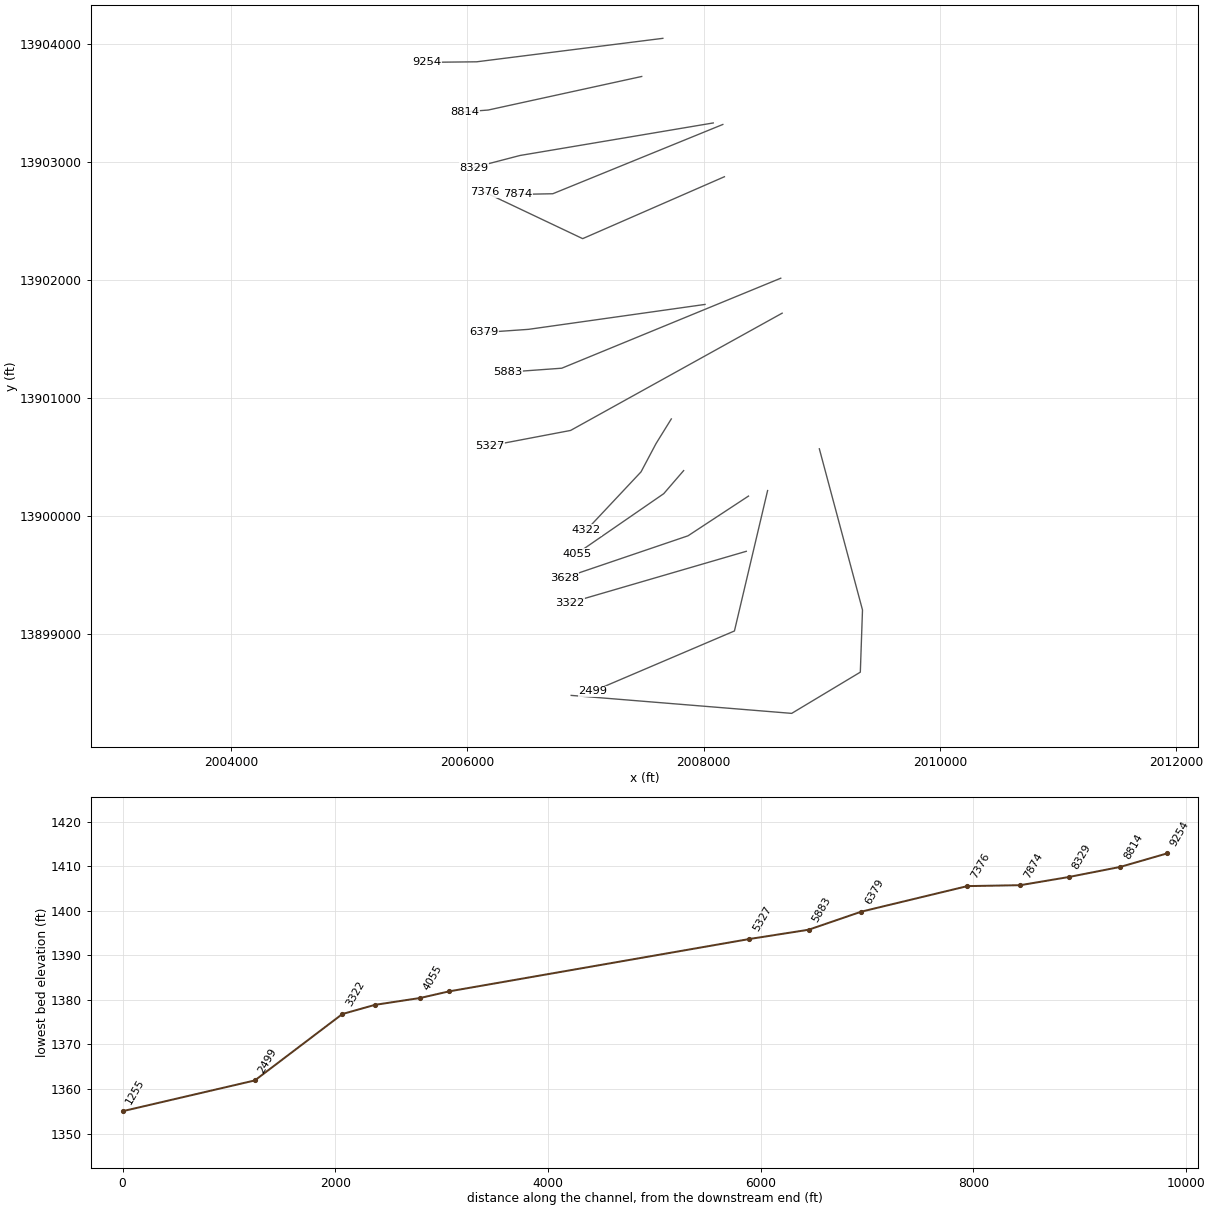
HEC-RAS study FLAT ROCK CREEK.prj: FLAT ROCK CREEK Base Level Engineering

--- FLAT ROCK CREEK.g01 (geometry) --- (continued)

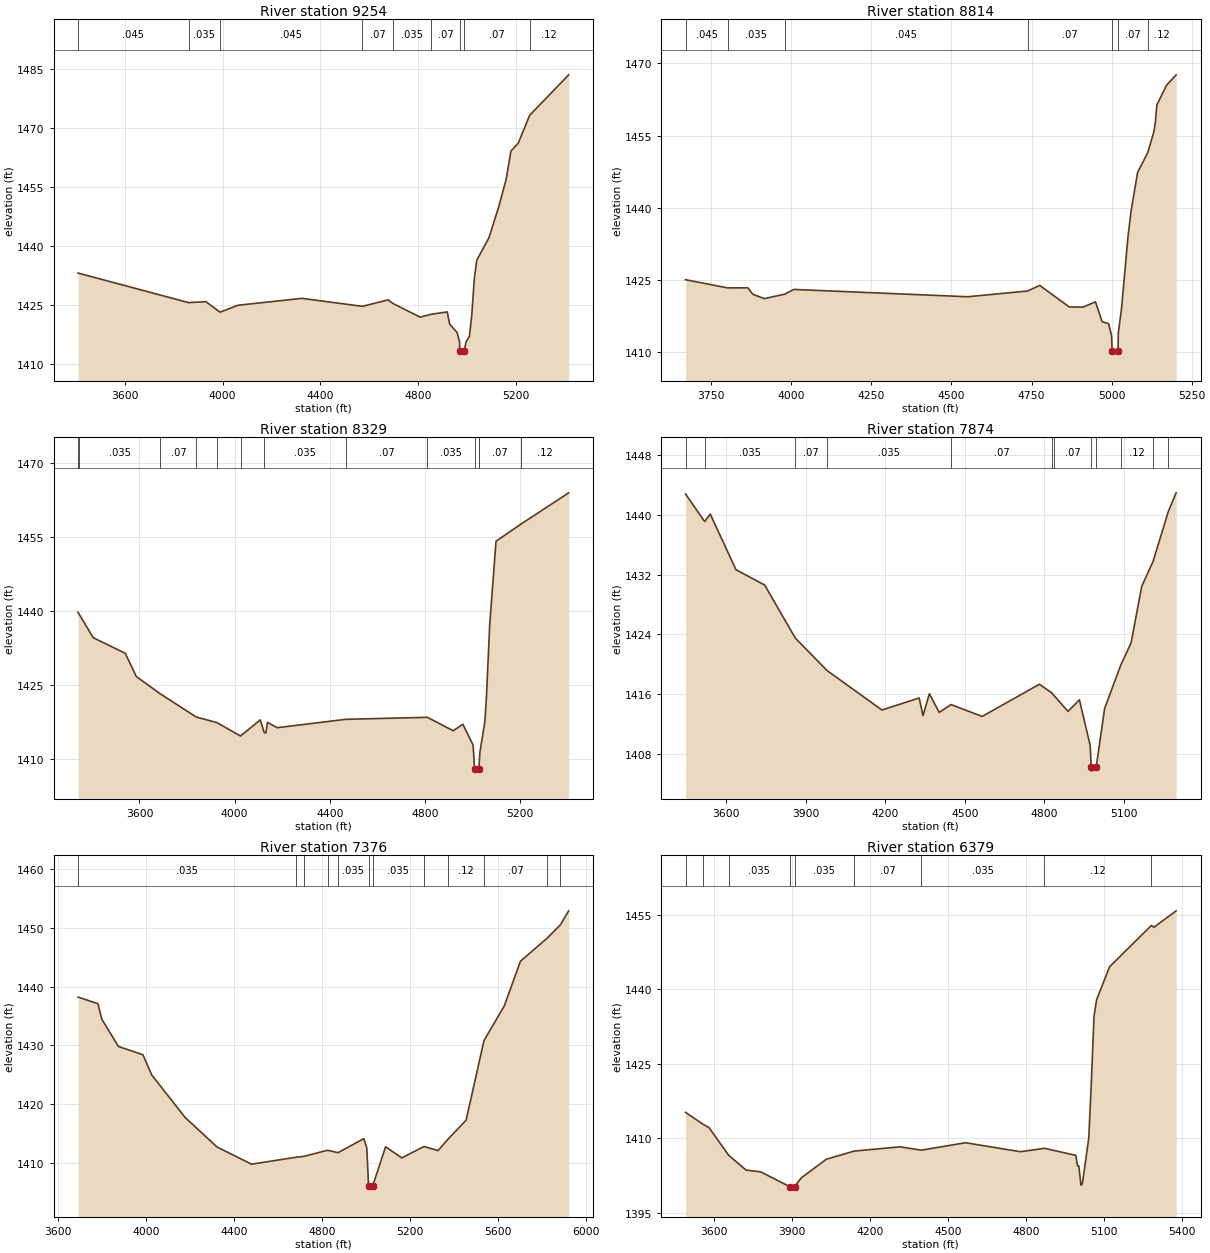
Type RM Length L Ch R = 1 ,9254    ,440,440,440
BEGIN DESCRIPTION:
FLAT ROCK CREEK_DS 10.0
END DESCRIPTION:
XS GIS Cut Line= 3
      2007653.76     13904048.18      2006077.96     13903849.22
       2005658.7     13903844.74
#Sta/Elev= 30
  3408.5  1433.2  3861.1 1425.69  3931.4 1425.94  3989.4 1423.26  4062.4 1425.02
  4324.5 1426.77  4572.2 1424.74  4677.3 1426.39  4697.4 1425.46  4808.3 1422.01
  4853.4 1422.73  4919.2 1423.33  4929.2 1420.21  4959.5 1418.13  4969.6 1415.71
  4970.5 1413.36    4971 1412.86  4988.7 1413.36  4995.8  1415.7  5009.8 1417.12
  5019.8 1422.69  5029.8 1431.61  5039.8 1436.45  5089.8 1442.17  5129.8 1450.03
  5159.8 1456.91  5179.8  1464.2  5209.8 1466.21  5256.4 1473.27  5416.1 1483.56
#Mann= 9 ,-1 , 0
  3408.5    .045       0  3861.1    .035       0  3989.4    .045       0
  4572.2     .07       0  4697.4    .035       0  4853.4     .07       0
  4970.5     .05       0  4988.7     .07       0  5256.4     .12       0
Bank Sta=4970.5,4988.7
XS Rating Curve= 0 ,0
Exp/Cntr=0.3,0.1

Type RM Length L Ch R = 1 ,8814    ,485,485,485
BEGIN DESCRIPTION:
FLAT ROCK CREEK_DS 9.0
END DESCRIPTION:
XS GIS Cut Line= 3
      2007474.95     13903724.87      2006175.94     13903440.39
      2005975.03       13903425.
#Sta/Elev= 30
  3670.2 1425.08  3801.2 1423.38  3864.7 1423.39    3880 1422.06  3915.8 1421.15
  3979.6 1422.07    4008 1423.06  4550.5 1421.54  4737.9 1422.73  4775.7 1423.89
  4867.9 1419.42  4911.1 1419.39  4949.8 1420.49  4970.2 1416.37  4990.7 1415.94
    5000 1413.39  5001.8 1410.33  5002.3 1409.83  5020.1 1410.33    5021 1414.05
    5031 1419.09  5051.1 1433.98  5061.1 1439.48  5081.2 1447.36  5112.9 1451.49
  5131.2 1455.62  5136.2  1457.5  5141.3 1461.38  5171.4 1465.46  5201.5 1467.63
#Mann= 7 ,-1 , 0
  3670.2    .045       0  3801.2    .035       0  3979.6    .045       0
  4737.9     .07       0  5001.8     .05       0  5020.1     .07       0
  5112.9     .12       0
Bank Sta=5001.8,5020.1
XS Rating Curve= 0 ,0
Exp/Cntr=0.3,0.1

Type RM Length L Ch R = 1 ,8329    ,455,455,455
BEGIN DESCRIPTION:
FLAT ROCK CREEK_DS 8.0
END DESCRIPTION:
XS GIS Cut Line= 3
      2008080.49     13903330.95      2006445.38     13903055.16
      2006053.76     13902953.12
#Sta/Elev= 30
  3341.8 1439.81  3344.4 1439.57  3405.4 1434.63    3540 1431.47  3586.8 1426.75
  3687.9 1423.23  3839.1 1418.53  3925.3 1417.41  4024.8 1414.69    4108 1417.95
  4124.2 1415.42  4131.2 1415.29  4138.4 1417.46  4178.9 1416.37  4467.3 1418.07
  4810.5 1418.48  4919.3 1415.75  4959.8 1417.07  5002.8 1412.85    5009 1408.06
  5009.5 1407.56  5027.3 1408.06  5028.2 1408.79  5031.4 1411.37  5052.1 1417.54
  5058.7 1422.36  5072.7 1437.32  5099.2  1454.2  5202.4 1457.62  5404.7 1464.02
#Mann= 13 ,-1 , 0
  3341.8     .07       0  3344.4    .035       0  3687.9     .07       0
  3839.1    .035       0  3925.3    .045       0  4024.8     .07       0
  4124.2    .035       0  4467.3     .07       0  4810.5    .035       0
    5009    .035       0  5027.3    .035       0  5028.2     .07       0
  5202.4     .12       0
Bank Sta=5009,5027.3
XS Rating Curve= 0 ,0
Exp/Cntr=0.3,0.1

Type RM Length L Ch R = 1 ,7874    ,498,498,498
BEGIN DESCRIPTION:
FLAT ROCK CREEK_DS 7.0
END DESCRIPTION:
XS GIS Cut Line= 3
      2008161.28     13903317.96      2006722.49     13902730.76
      2006425.04       13902725.
#Sta/Elev= 30
    3446 1442.77  3518.3 1439.09  3539.2 1440.09  3636.4 1432.65  3744.4 1430.61
  3860.3 1423.51  3980.2 1419.17  4187.2  1413.9  4327.6 1415.51  4342.1 1413.15
  4366.2 1416.08  4403.2 1413.58  4447.7 1414.63  4565.3 1413.04  4781.3 1417.34
  4828.1 1416.19  4836.7 1415.83  4889.3 1413.72  4932.5 1415.26  4972.9 1409.17
  4977.3 1406.23  4977.8 1405.73  4995.6 1406.23  5027.5 1414.09  5088.7 1419.93
  5127.5 1422.88  5167.5 1430.42  5210.5 1433.78  5268.4 1440.48  5297.5 1442.93
#Mann= 12 ,-1 , 0
    3446     .07       0  3518.3    .035       0  3860.3     .07       0
  3980.2    .035       0  4447.7     .07       0  4828.1    .035       0
  4836.7     .07       0  4977.3     .05       0  4995.6     .07       0
  5088.7     .12       0  5210.5     .07       0  5268.4     .12       0
Bank Sta=4977.3,4995.6
XS Rating Curve= 0 ,0
Exp/Cntr=0.3,0.1

Type RM Length L Ch R = 1 ,7376    ,997,997,997
BEGIN DESCRIPTION:
FLAT ROCK CREEK_DS 6.0
END DESCRIPTION:
XS GIS Cut Line= 3
      2008175.02     13902875.01      2006975.32     13902350.11
      2006143.95     13902745.04
#Sta/Elev= 30
  3690.5 1438.24  3780.6 1437.11  3798.5 1434.46  3874.1 1429.82  3985.2 1428.42
  4025.4 1424.97  4176.6 1417.75  4322.4 1412.69  4479.1 1409.77  4682.8 1410.96
  4718.1 1411.11  4824.2 1412.14    4872 1411.73  4989.4 1414.12  5002.9 1412.52
  5010.9 1406.02  5011.4 1405.52  5029.2 1406.02  5088.2 1412.74  5161.9 1410.84
  5263.1 1412.79  5326.5 1412.08  5370.4 1413.97  5454.3 1417.27  5535.4 1430.82
  5627.4 1436.71  5701.1 1444.34    5824 1448.32  5882.4 1450.53  5920.4 1452.93
#Mann= 12 ,-1 , 0
  3690.5    .035       0  4682.8     .07       0  4718.1    .035       0
  4824.2     .07       0    4872    .035       0  5010.9    .035       0
  5029.2    .035       0  5263.1     .07       0  5370.4     .12       0
  5535.4     .07       0    5824     .12       0  5882.4     .07       0
Bank Sta=5010.9,5029.2
XS Rating Curve= 0 ,0
Exp/Cntr=0.3,0.1

Type RM Length L Ch R = 1 ,6379    ,496,496,496
BEGIN DESCRIPTION:
FLAT ROCK CREEK_DS 5.0
END DESCRIPTION:
XS GIS Cut Line= 3
      2008010.98     13901792.48      2006516.54     13901581.18
      2006139.75     13901554.94
#Sta/Elev= 30
  3490.7 1415.25  3557.4 1412.87  3581.2 1412.16  3656.5 1406.61  3723.3 1403.63
  3779.5 1403.27  3891.5 1400.29    3892 1399.79  3909.9 1400.29  3936.5 1402.09
    4032  1405.8  4139.2 1407.45  4314.8  1408.3  4398.1 1407.64  4567.3 1409.13
  4779.4 1407.32  4871.2 1408.01  4991.5 1406.59  4998.3 1404.48  5003.3 1404.48
  5011.6  1400.6  5016.8 1400.84  5041.6 1410.08  5051.7 1421.53  5061.7 1434.57
  5071.7 1437.92  5121.8 1444.57  5282.6 1452.88  5292.2 1452.51  5377.7 1455.82
#Mann= 9 ,-1 , 0
  3490.7    .035       0  3557.4     .07       0  3656.5    .035       0
  3891.5     .05       0  3909.9    .035       0  4139.2     .07       0
  4398.1    .035       0  4871.2     .12       0  5282.6     .07       0
Bank Sta=3891.5,3909.9
XS Rating Curve= 0 ,0
Exp/Cntr=0.3,0.1

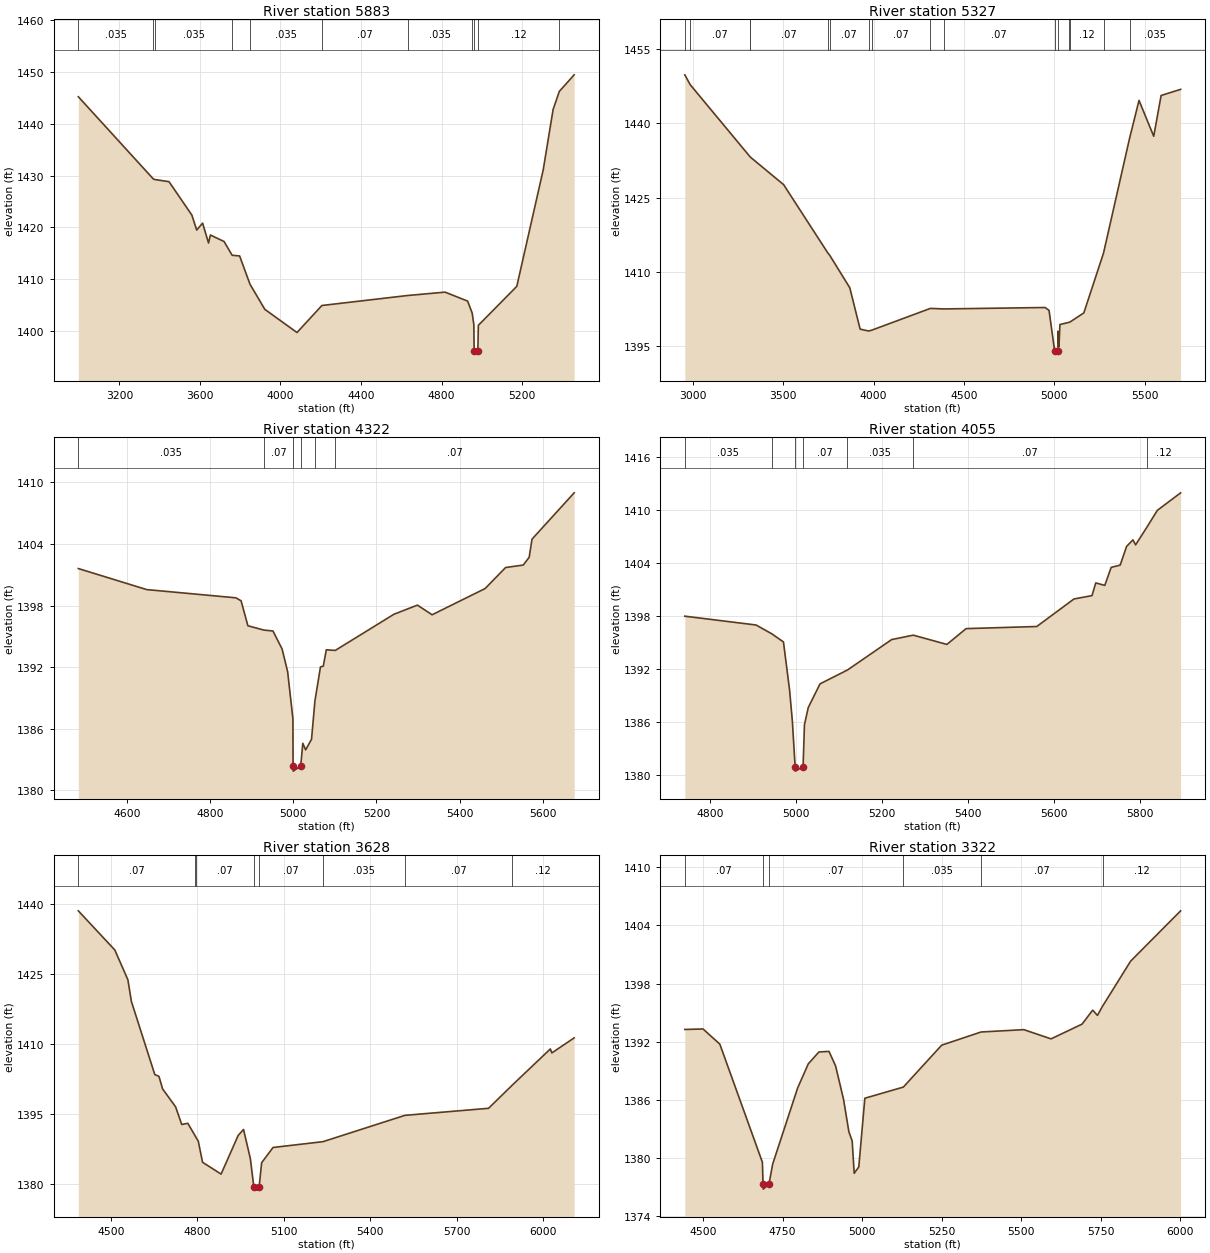
Type RM Length L Ch R = 1 ,5883    ,556,556,556
BEGIN DESCRIPTION:
FLAT ROCK CREEK_DS 4.0
END DESCRIPTION:
XS GIS Cut Line= 3
      2008651.62     13902014.67      2006798.42     13901251.76
      2006340.82     13901218.57
#Sta/Elev= 30
  2995.9 1445.25  3367.9 1429.39  3375.8 1429.26  3446.4 1428.84  3559.9 1422.39
  3583.9  1419.5  3613.2 1420.84  3642.6    1417  3651.9 1418.54  3719.8 1417.29
    3760 1414.63  3797.1  1414.5  3848.6 1409.04  3922.2 1404.19  4082.1 1399.71
  4205.8 1404.93  4631.8 1406.86  4817.6 1407.51  4929.6 1405.78  4952.2 1403.48
  4960.4 1401.26  4962.1 1396.23  4962.6 1395.73  4980.5 1396.23  4982.9  1401.1
  5173.9 1408.63    5305  1431.1  5354.3 1442.79  5385.1 1446.28  5458.8 1449.48
#Mann= 11 ,-1 , 0
  2995.9    .035       0  3367.9     .12       0  3375.8    .035       0
    3760     .07       0  3848.6    .035       0  4205.8     .07       0
  4631.8    .035       0  4952.2     .12       0  4962.1     .05       0
  4980.5     .12       0  5385.1     .07       0
Bank Sta=4962.1,4980.5
XS Rating Curve= 0 ,0
Exp/Cntr=0.3,0.1

Type RM Length L Ch R = 1 ,5327    ,2828,2828,2828
BEGIN DESCRIPTION:
FLAT ROCK CREEK_DS 3.0
END DESCRIPTION:
XS GIS Cut Line= 3
      2008663.46     13901718.28       2006873.1     13900724.22
       2006188.8     13900593.92
#Sta/Elev= 30
  2954.8 1449.77  2984.6 1447.79  3313.7 1433.35  3317.1  1433.2  3501.9 1427.62
    3748 1413.77  3756.8 1413.39  3868.1 1406.83  3925.3 1398.49  3972.5 1398.11
  3990.4 1398.29  4314.3 1402.67  4387.4 1402.56  4949.2 1402.85    4971 1402.26
  5001.7 1394.15  5002.2 1393.65  5020.1 1394.15  5020.6 1398.08  5025.6  1394.9
  5031.2 1399.42  5080.7 1399.85  5087.5 1399.94  5163.5 1401.76  5272.6 1413.85
  5416.4 1436.93  5468.9 1444.61  5550.4 1437.38  5591.1  1445.6  5699.2 1446.84
#Mann= 16 ,-1 , 0
  2954.8    .035       0  2984.6     .07       0  3313.7     .12       0
  3317.1     .07       0    3748     .12       0  3756.8     .07       0
  3972.5    .035       0  3990.4     .07       0  4314.3    .035       0
  4387.4     .07       0  5001.7     .05       0  5020.1     .07       0
  5080.7    .035       0  5087.5     .12       0  5272.6     .07       0
  5416.4    .035       0
Bank Sta=5001.7,5020.1
XS Rating Curve= 0 ,0
Exp/Cntr=0.3,0.1

Type RM Length L Ch R = 1 ,4322    ,267,267,267
BEGIN DESCRIPTION:
FLAT ROCK CREEK_DS 2.0
END DESCRIPTION:
XS GIS Cut Line= 4
      2007725.44     13900821.84      2007596.38     13900613.21
      2007469.15     13900372.94        2007007.     13899879.86
#Sta/Elev= 30
  4482.8  1401.6  4647.4 1399.55  4861.9 1398.75  4874.4 1398.46  4890.8 1396.03
  4929.2 1395.61  4951.1 1395.52  4973.1 1393.77  4986.4 1391.56  4999.1 1386.98
  4999.5 1382.38    5000 1381.88  5017.9 1382.38  5022.9 1384.59  5029.7 1383.95
  5043.9 1384.98    5052 1388.69  5065.4 1392.02  5072.2  1392.1  5079.4 1393.69
    5101 1393.63  5242.2 1397.15  5298.7 1398.04    5334  1397.1  5461.5 1399.65
  5510.9  1401.7  5553.3 1401.94  5567.5 1402.69  5574.4 1404.46  5675.8 1408.97
#Mann= 6 ,-1 , 0
  4482.8    .035       0  4929.2     .07       0  4999.5     .05       0
  5017.9     .07       0    5052     .12       0    5101     .07       0
Bank Sta=4999.5,5017.9
XS Rating Curve= 0 ,0
Exp/Cntr=0.3,0.1

Type RM Length L Ch R = 1 ,4055    ,427,427,427
BEGIN DESCRIPTION:
FLAT ROCK CREEK_DS 1.8
END DESCRIPTION:
XS GIS Cut Line= 3
      2007829.76     13900383.69      2007661.38     13900188.21
      2006925.23     13899679.53
#Sta/Elev= 30
    4742 1397.98  4907.7 1396.98    4944 1395.99  4971.4 1395.06  4985.6 1389.62
  4992.2 1386.03  4998.5 1380.92    4999 1380.42    5017 1380.92  5020.2 1385.68
    5029 1387.62  5056.4 1390.31  5120.2 1391.88    5223 1395.33  5273.1 1395.83
  5351.4 1394.78    5396 1396.57  5560.3 1396.81  5646.8 1399.93  5688.7 1400.31
  5697.5 1401.75  5718.5 1401.47  5733.3 1403.51  5754.3 1403.77  5769.2 1405.89
    5784 1406.63  5790.1 1406.06  5815.9 1408.03  5840.8 1409.98  5894.8 1411.96
#Mann= 7 ,-1 , 0
    4742    .035       0    4944     .07       0  4998.5     .05       0
    5017     .07       0  5120.2    .035       0  5273.1     .07       0
  5815.9     .12       0
Bank Sta=4998.5,5017
XS Rating Curve= 0 ,0
Exp/Cntr=0.3,0.1

Type RM Length L Ch R = 1 ,3628    ,306,306,306
BEGIN DESCRIPTION:
FLAT ROCK CREEK_DS 1.5
END DESCRIPTION:
XS GIS Cut Line= 3
       2008378.6     13900167.77      2007866.96     13899831.05
      2006819.01     13899474.33
#Sta/Elev= 30
  4387.5 1438.61  4514.1  1430.2  4559.4 1423.81  4571.4 1419.19  4652.7 1403.46
  4667.1 1403.08  4679.8 1400.38    4725 1396.52  4746.1 1392.75  4767.2    1393
  4791.9 1390.39  4795.8 1389.94  4803.3 1389.21  4818.4 1384.63  4882.6  1382.1
  4941.9  1390.4  4960.4 1391.68  4984.1 1385.42  4996.1 1379.37  4996.6 1378.87
  5014.6 1379.37  5023.2 1384.54  5062.8 1387.81  5236.1 1389.06  5520.3 1394.71
  5810.1 1396.22  5891.8 1401.16  6024.4 1408.96  6029.7 1408.11    6107 1411.34
#Mann= 8 ,-1 , 0
  4387.5     .07       0  4791.9    .035       0  4795.8     .07       0
  4996.1     .05       0  5014.6     .07       0  5236.1    .035       0
  5520.3     .07       0  5891.8     .12       0
Bank Sta=4996.1,5014.6
XS Rating Curve= 0 ,0
Exp/Cntr=0.3,0.1

Type RM Length L Ch R = 1 ,3322    ,823,823,823
BEGIN DESCRIPTION:
FLAT ROCK CREEK_DS 1.3
END DESCRIPTION:
XS GIS Cut Line= 2
        2008360.     13899699.59      2006864.09     13899262.69
#Sta/Elev= 30
  4442.6 1393.27  4499.9 1393.32  4552.7 1391.76  4686.5 1379.58  4688.6 1377.31
  4689.1 1376.81  4707.1 1377.31  4718.7 1379.38  4797.3 1387.24  4830.8 1389.73
  4864.2 1390.95  4895.8 1391.01  4916.6 1389.51  4941.6 1386.06  4958.3 1382.73
  4968.7 1381.77    4975 1378.44  4989.5  1379.1  5008.5 1386.18  5129.5 1387.33
    5250 1391.65  5373.8 1393.01  5508.2 1393.25  5593.8  1392.3  5691.2 1393.82
  5724.6 1395.26  5739.6 1394.72  5755.5 1395.66  5843.8 1400.31    6001  1405.5
#Mann= 6 ,-1 , 0
  4442.6     .07       0  4688.6     .05       0  4707.1     .07       0
  5129.5    .035       0  5373.8     .07       0  5755.5     .12       0
Bank Sta=4688.6,4707.1
XS Rating Curve= 0 ,0
Exp/Cntr=0.3,0.1

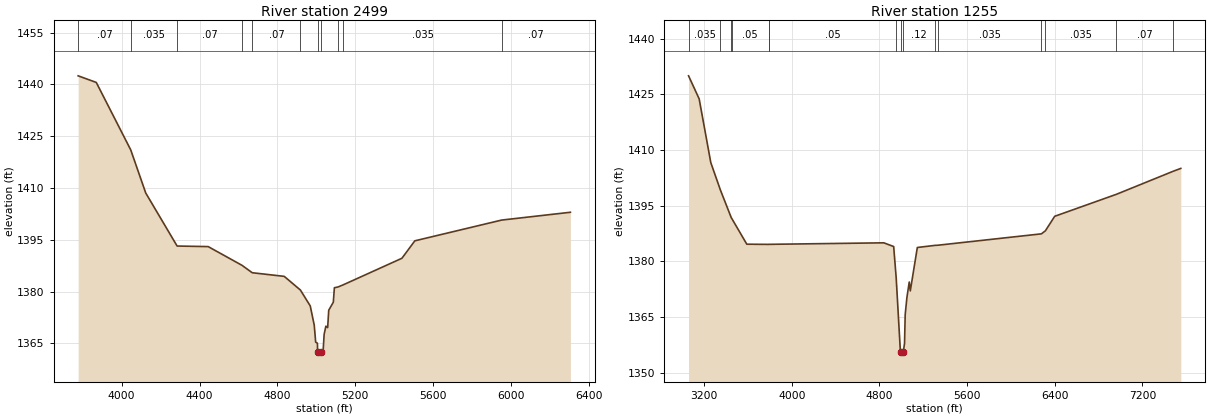
Type RM Length L Ch R = 1 ,2499    ,1244,1244,1244
BEGIN DESCRIPTION:
FLAT ROCK CREEK_DS 1.0
END DESCRIPTION:
XS GIS Cut Line= 3
      2008540.37     13900214.56      2008259.67     13899024.21
      2007060.68     13898512.04
#Sta/Elev= 30
    3777  1442.5    3870 1440.59  4046.8 1421.07    4124 1408.56    4285 1393.21
  4444.4 1393.05  4618.3 1387.62  4670.6 1385.48  4834.8 1384.43  4917.9 1380.47
  4968.4 1375.87  4988.9 1370.31  4996.3 1365.38  5005.3 1365.07  5006.3 1362.41
  5006.8 1361.91  5025.9 1362.41  5034.2 1362.58  5039.7 1367.62  5048.6 1370.01
  5057.8 1369.59  5063.3 1374.62  5086.9 1376.95  5092.3 1381.14  5111.2 1381.36
    5139 1382.01    5439 1389.67  5505.3 1394.72  5951.1 1400.73  6303.8 1402.99
#Mann= 11 ,-1 , 0
    3777     .07       0  4046.8    .035       0    4285     .07       0
  4618.3    .035       0  4670.6     .07       0  4917.9     .12       0
  5006.3     .05       0  5025.9     .12       0  5111.2     .07       0
    5139    .035       0  5951.1     .07       0
Bank Sta=5006.3,5025.9
XS Rating Curve= 0 ,0
Exp/Cntr=0.3,0.1

Type RM Length L Ch R = 1 ,1255    ,0,0,0
BEGIN DESCRIPTION:
FLAT ROCK CREEK_DS 0.0
END DESCRIPTION:
XS GIS Cut Line= 5
      2008978.24     13900568.48      2009343.45     13899202.27
      2009325.03     13898675.08      2008744.17     13898325.69
      2006878.13      13898478.1
#Sta/Elev= 30
  3058.3 1430.01  3155.1  1423.8  3261.2 1406.62  3349.4  1399.2  3448.9 1391.72
  3450.3 1391.68  3589.8 1384.63  3787.8 1384.58  3788.2 1384.59    4840    1385
    4930    1384  4953.1 1375.52  4990.1 1356.31    4998  1355.5  4998.5    1355
  5017.7  1355.5  5029.2 1357.95  5035.1 1365.66  5050.6 1370.22    5072 1374.44
  5081.7 1372.05  5145.8 1383.74  5306.7 1384.31  5332.8 1384.35  6277.9 1387.42
  6314.2 1388.23  6399.4 1392.15  6962.8 1398.08  7479.3 1404.27  7550.1 1405.06
#Mann= 15 ,-1 , 0
  3058.3    .035       0  3349.4     .05       0  3448.9     .07       0
  3450.3     .05       0  3787.8    .035       0  3788.2     .05       0
  4953.1     .12       0    4998     .05       0  5017.7     .12       0
  5306.7     .07       0  5332.8    .035       0  6277.9     .07       0
  6314.2    .035       0  6962.8     .07       0  7479.3     .05       0
Bank Sta=4998,5017.7
XS Rating Curve= 0 ,0
Exp/Cntr=0.3,0.1

Chan Stop Cuts=-1
Use User Specified Reach Order=0
Composite Channel Slope=5