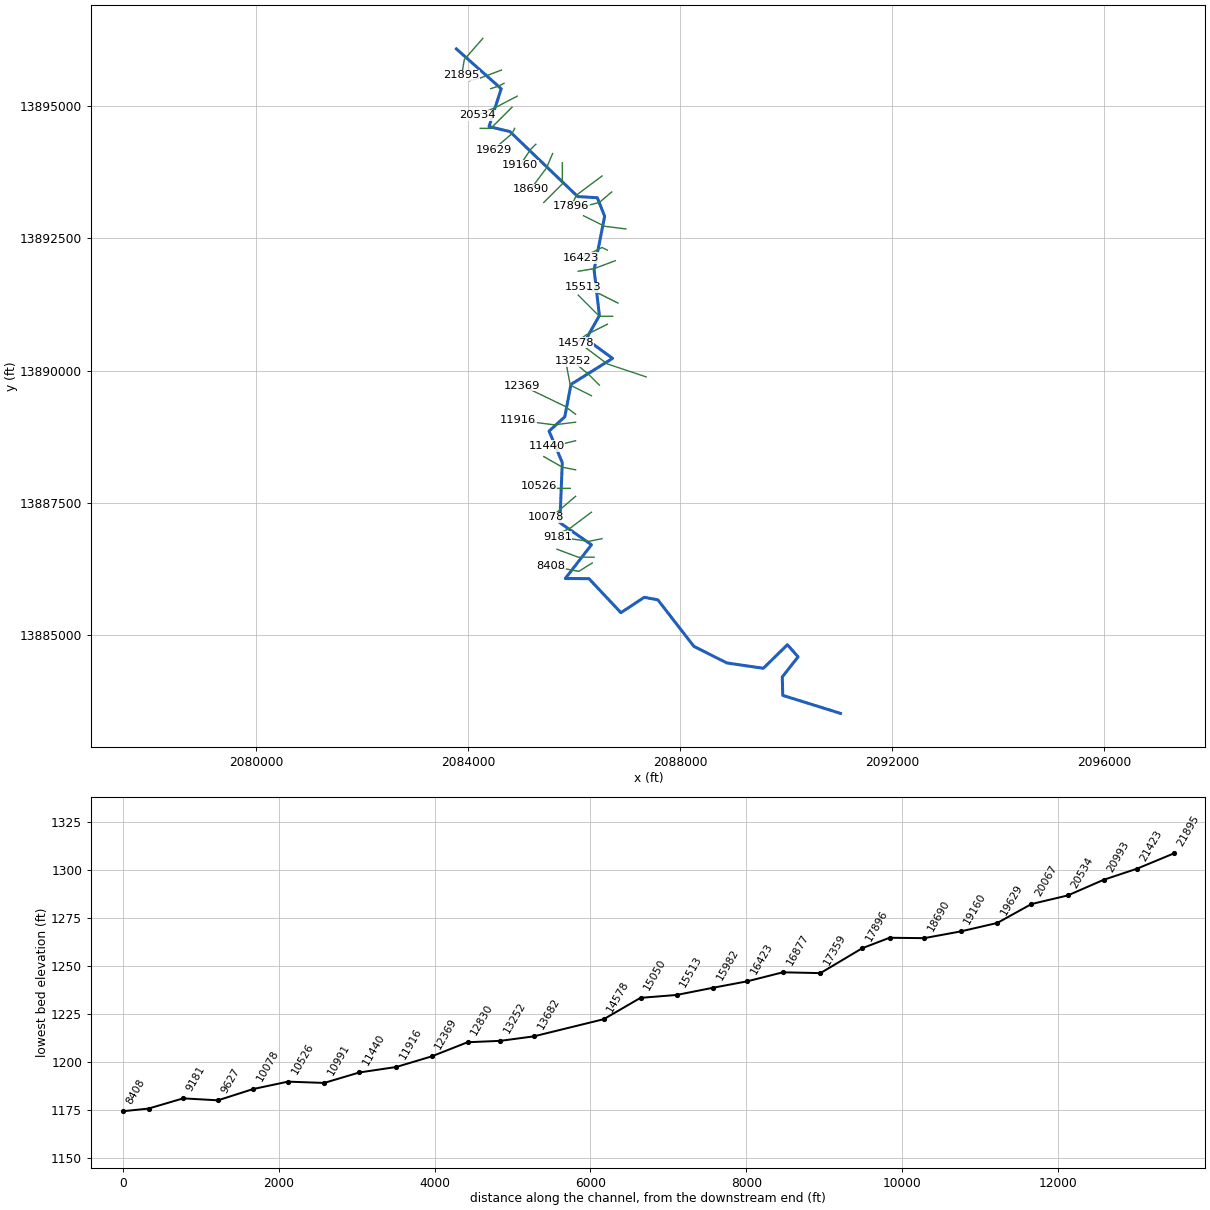
--- GOSS CREEK.prj (project) ---

Proj Title=GOSS CREEK Base Level Engineering
Current Plan=p01
Default Exp/Contr=0.3,0.1
English Units
Geom File=g01
Flow File=f01
Plan File=p01
BEGIN DESCRIPTION:
GOSS CREEK
END DESCRIPTION:

--- GOSS CREEK.p01 (plan) ---

Plan Title=Multiple Run
Short Identifier=Multiple
Geom File=g01
Flow File=f01
Subcritical Flow
K Sum by GR= 0
Std Step Tol= 0.01
Critical Tol= 0.01
Num of Std Step Trials= 20
Max Error Tol= 0.3
Flow Tol Ratio= 0.001
Split Flow NTrial= 30
Split Flow Tol= 0.02
Split Flow Ratio= 0.02
Log Output Level= 0
Friction Slope Method= 1
Unsteady Friction Slope Method= 2
Unsteady Bridges Friction Slope Method= 1
Parabolic Critical Depth
Global Vel Dist=  1 , 1 , 1
Global Log Level= 0
CheckData=True
Encroach Param= -1, 0, 0, 0
BEGIN DESCRIPTION:
Multiple Run
END DESCRIPTION:

--- GOSS CREEK.f01 (steady flow) ---

Flow Title=Multiple
Number of Profiles=7
Profile Names=10-year,25-year,50-year,1pct_min,100-year,1pct_plu,500-year
River Rch & RM= GOSS CREEK,Reach-1,21895
    2229    3940    5635    3899    7779   15521   14676
River Rch & RM= GOSS CREEK,Reach-1,16423
    2811    5011    7205    5007    9991   19934   19018
River Rch & RM= GOSS CREEK,Reach-1,10991
    2883    5131    7370    5114   10204   20359   19367
River Rch & RM= GOSS CREEK,Reach-1,6929
    3446    6165    8886    6182   12334   24610   23537
Boundary for River Rch & Prof#=GOSS CREEK,Reach-1,1
Up Type=0
Dn Type=3
Dn Slope=0.005
Boundary for River Rch & Prof#=GOSS CREEK,Reach-1,2
Up Type=0
Dn Type=3
Dn Slope=0.005
Boundary for River Rch & Prof#=GOSS CREEK,Reach-1,3
Up Type=0
Dn Type=3
Dn Slope=0.005
Boundary for River Rch & Prof#=GOSS CREEK,Reach-1,4
Up Type=0
Dn Type=3
Dn Slope=0.005
Boundary for River Rch & Prof#=GOSS CREEK,Reach-1,5
Up Type=0
Dn Type=3
Dn Slope=0.005
Boundary for River Rch & Prof#=GOSS CREEK,Reach-1,6
Up Type=0
Dn Type=3
Dn Slope=0.005
Boundary for River Rch & Prof#=GOSS CREEK,Reach-1,7
Up Type=0
Dn Type=3
Dn Slope=0.005

--- GOSS CREEK.g01 (geometry) ---

Geom Title=Existing Conditions

River Reach=GOSS CREEK,Reach-1
Reach XY= 30
      2083775.00     13896075.00      2084621.45     13895323.53
      2084391.41     13894608.20      2084784.80     13894514.52
      2086065.01     13893286.26      2086435.18     13893264.68
      2086573.62     13892915.34      2086374.91     13891902.31
      2086474.33     13891038.91      2086224.91     13890594.87
      2086723.31     13890230.64      2085938.26     13889738.65
      2085821.55     13889126.25      2085524.92     13888856.71
      2085774.32     13888261.08      2085728.45     13887126.25
      2086325.11     13886709.64      2085830.29     13886072.32
      2086277.29     13886069.90      2086881.12     13885426.82
      2087321.30     13885717.32      2087577.70     13885669.64
      2088257.87     13884791.30      2088880.53     13884477.38
      2089569.36     13884376.69      2090023.50     13884821.53
      2090225.07     13884593.29      2089926.62     13884213.17
      2089935.47     13883865.17      2091025.00     13883525.00

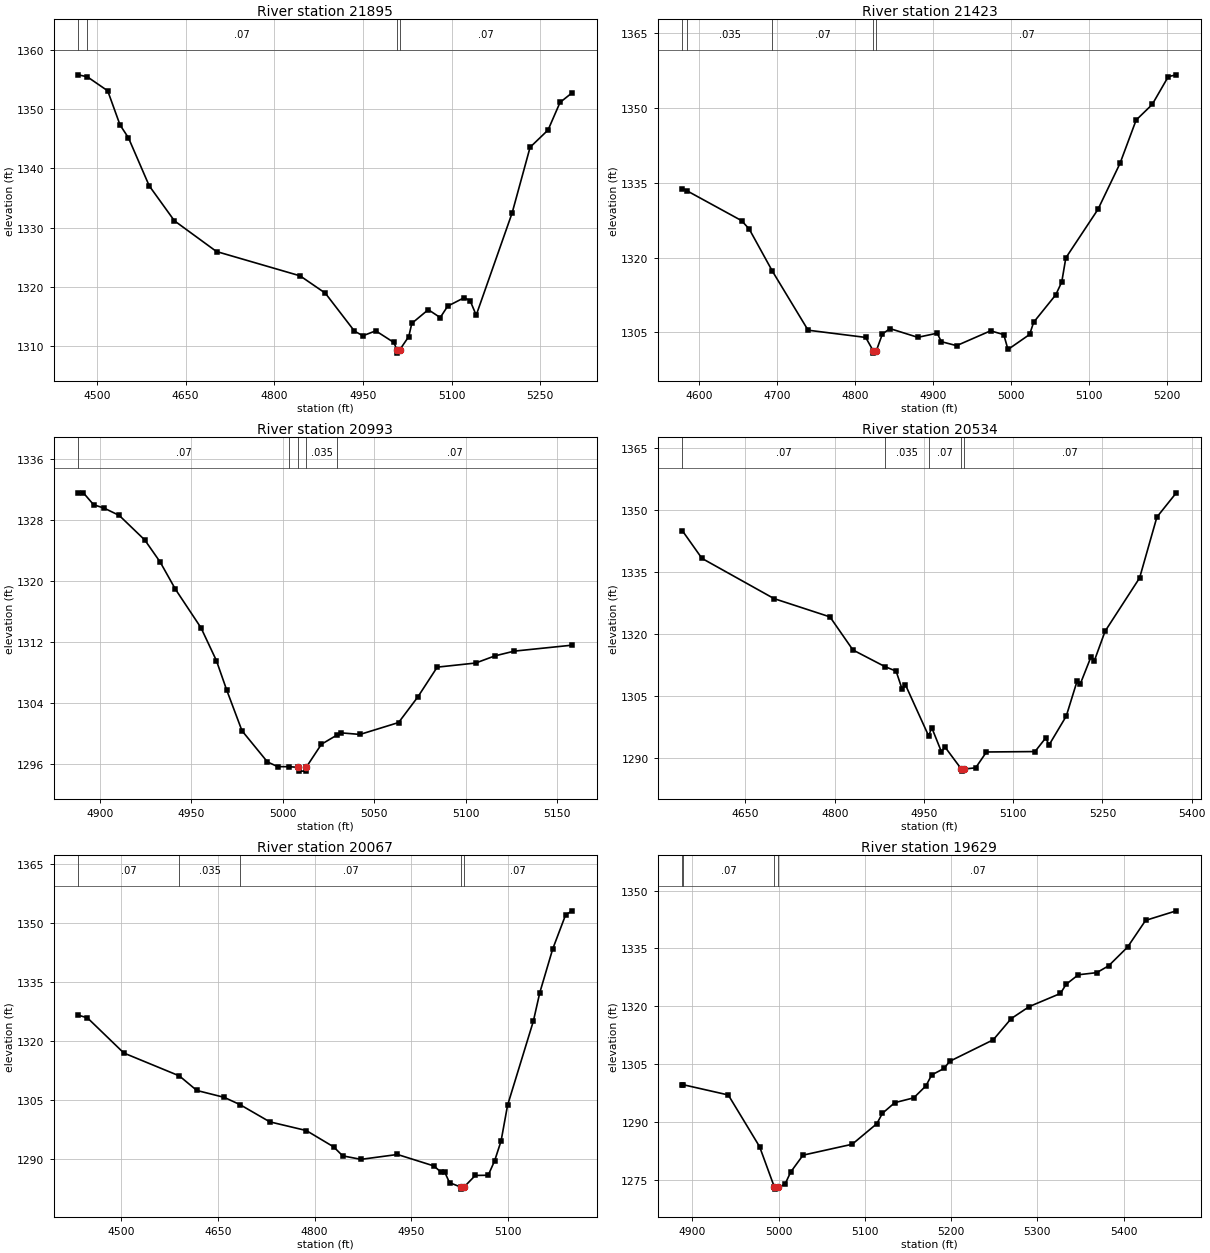
Type RM Length L Ch R = 1,21895,472,472,472
BEGIN DESCRIPTION:
GOSS CREEK 47.0
END DESCRIPTION:
XS GIS Cut Line= 3
      2084275.03     13896275.03      2083925.00     13895875.00
      2083875.00     13895574.98
#Sta/Elev= 30
  4468.2 1355.77  4483.5 1355.44  4518.1 1353.07  4538.9 1347.32  4553.2 1345.14
  4588.3 1337.05  4631.0 1331.14  4702.2 1325.96  4843.6 1321.86  4886.3 1318.94
  4935.7 1312.53  4949.9 1311.75  4971.7 1312.58  5002.3 1310.62  5007.8 1309.32
  5008.1 1308.82  5011.9 1309.32  5027.6 1311.62  5032.7 1313.84  5060.6 1316.15
  5080.8 1314.82  5093.5 1316.75  5121.4 1318.17  5131.5 1317.65  5141.7 1315.22
  5202.5 1332.47  5232.9 1343.55  5263.3 1346.46  5283.6 1351.12  5303.9 1352.73
#Mann=4,-1,0
  4468.2   0.035       0  4483.5    0.07       0  5007.8    0.05       0
  5011.9    0.07       0
Bank Sta=5007.8,5011.9
Exp/Cntr=0.3,0.1

Type RM Length L Ch R = 1,21423,430,430,430
BEGIN DESCRIPTION:
GOSS CREEK 46.0
END DESCRIPTION:
XS GIS Cut Line= 3
      2084625.04     13895675.01      2084225.00     13895525.00
      2084025.00     13895475.00
#Sta/Elev= 30
  4578.8 1333.88  4584.8 1333.41  4654.5 1327.45  4664.3 1325.78  4694.2 1317.28
  4739.9 1305.46  4813.8 1304.01  4823.3 1301.36  4823.5 1300.86  4827.5 1301.36
  4835.2 1304.70  4845.0 1305.78  4880.6 1304.03  4905.5 1304.86  4910.8 1303.16
  4930.4 1302.36  4974.0 1305.34  4990.9 1304.57  4996.3 1301.59  5024.1 1304.61
  5029.2 1307.05  5057.6 1312.56  5065.3 1315.15  5070.5 1319.97  5111.7 1329.70
  5140.0 1338.93  5160.7 1347.63  5181.3 1350.75  5201.9 1356.34  5212.2 1356.70
#Mann=5,-1,0
  4578.8    0.07       0  4584.8   0.035       0  4694.2    0.07       0
  4823.3    0.05       0  4827.5    0.07       0
Bank Sta=4823.3,4827.5
Exp/Cntr=0.3,0.1

Type RM Length L Ch R = 1,20993,459,459,459
BEGIN DESCRIPTION:
GOSS CREEK 45.0
END DESCRIPTION:
XS GIS Cut Line= 3
      2084675.03     13895425.01      2084575.00     13895375.00
      2084425.04     13895325.01
#Sta/Elev= 30
  4888.2 1331.51  4891.0 1331.51  4896.6 1329.95  4902.2 1329.52  4910.6 1328.55
  4924.6 1325.32  4933.0 1322.43  4941.3 1318.88  4955.3 1313.82  4963.7 1309.53
  4969.3 1305.69  4977.7 1300.32  4991.6 1296.24  4997.2 1295.62  5003.5 1295.61
  5008.3 1295.53  5008.7 1295.03  5012.5 1295.03  5012.8 1295.53  5021.1 1298.55
  5029.7 1299.77  5031.7 1300.05  5042.2 1299.84  5063.3 1301.40  5073.8 1304.75
  5084.4 1308.66  5105.4 1309.20  5116.0 1310.14  5126.5 1310.76  5158.1 1311.54
#Mann=5,-1,0
  4888.2    0.07       0  5003.5   0.035       0  5008.3    0.05       0
  5012.8   0.035       0  5029.7    0.07       0
Bank Sta=5008.3,5012.8
Exp/Cntr=0.3,0.1

Type RM Length L Ch R = 1,20534,467,467,467
BEGIN DESCRIPTION:
GOSS CREEK 44.0
END DESCRIPTION:
XS GIS Cut Line= 3
      2084923.36     13895182.80      2084525.00     13894975.00
      2084174.99     13894825.00
#Sta/Elev= 30
  4544.1 1344.97  4576.8 1338.33  4698.0 1328.60  4792.0 1324.18  4830.6 1316.18
  4884.5 1312.15  4903.2 1311.06  4913.3 1306.69  4918.9 1307.75  4957.9 1295.39
  4963.1 1297.40  4979.5 1291.52  4985.2 1292.74  5012.9 1287.38  5013.2 1286.88
  5017.4 1287.38  5036.9 1287.68  5055.1 1291.51  5136.7 1291.61  5154.8 1294.93
  5160.2 1293.18  5189.2 1300.18  5207.4 1308.64  5212.8 1307.96  5230.9 1314.54
  5236.4 1313.56  5254.5 1320.71  5312.5 1333.60  5341.6 1348.32  5374.2 1354.18
#Mann=5,-1,0
  4544.1    0.07       0  4884.5   0.035       0  4957.9    0.07       0
  5012.9    0.05       0  5017.4    0.07       0
Bank Sta=5012.9,5017.4
Exp/Cntr=0.3,0.1

Type RM Length L Ch R = 1,20067,438,438,438
BEGIN DESCRIPTION:
GOSS CREEK 43.0
END DESCRIPTION:
XS GIS Cut Line= 3
      2084825.01     13894975.01      2084425.00     13894575.00
      2084225.00     13894575.00
#Sta/Elev= 30
  4433.6 1326.62  4447.8 1325.94  4504.3 1316.99  4590.3 1311.18  4617.5 1307.47
  4659.9 1305.72  4684.3 1303.88  4730.6 1299.49  4787.2 1297.28  4829.6 1293.13
  4843.7 1290.84  4872.0 1289.95  4928.6 1291.19  4985.2 1288.27  4995.8 1286.73
  5001.8 1286.73  5009.3 1284.03  5027.1 1282.88  5027.4 1282.38  5031.6 1282.88
  5049.3 1285.86  5069.3 1285.91  5079.3 1289.60  5089.3 1294.66  5099.3 1303.69
  5139.3 1325.09  5149.3 1332.35  5169.3 1343.44  5189.3 1352.11  5199.3 1353.15
#Mann=5,-1,0
  4433.6    0.07       0  4590.3   0.035       0  4684.3    0.07       0
  5027.1    0.05       0  5031.6    0.07       0
Bank Sta=5027.1,5031.6
Exp/Cntr=0.3,0.1

Type RM Length L Ch R = 1,19629,469,469,469
BEGIN DESCRIPTION:
GOSS CREEK 42.0
END DESCRIPTION:
XS GIS Cut Line= 3
      2084874.98     13894574.97      2084825.00     13894475.00
      2084475.03     13894175.03
#Sta/Elev= 30
  4888.5 1299.61  4889.5 1299.61  4941.6 1296.96  4977.9 1283.54  4995.1 1273.01
  4995.5 1272.51  4999.8 1273.01  5007.4 1273.79  5014.0 1276.95  5028.3 1281.33
  5085.3 1284.16  5113.9 1289.50  5120.4 1292.21  5134.7 1294.96  5156.7 1296.21
  5170.9 1299.34  5177.5 1302.16  5191.8 1303.84  5198.4 1305.70  5248.9 1311.28
  5269.7 1316.78  5290.6 1319.90  5326.8 1323.31  5333.4 1325.69  5347.6 1328.17
  5369.0 1328.72  5382.8 1330.51  5404.7 1335.36  5425.6 1342.29  5461.2 1344.77
#Mann=4,-1,0
  4888.5   0.035       0  4889.5    0.07       0  4995.1    0.05       0
  4999.8    0.07       0
Bank Sta=4995.1,4999.8
Exp/Cntr=0.3,0.1

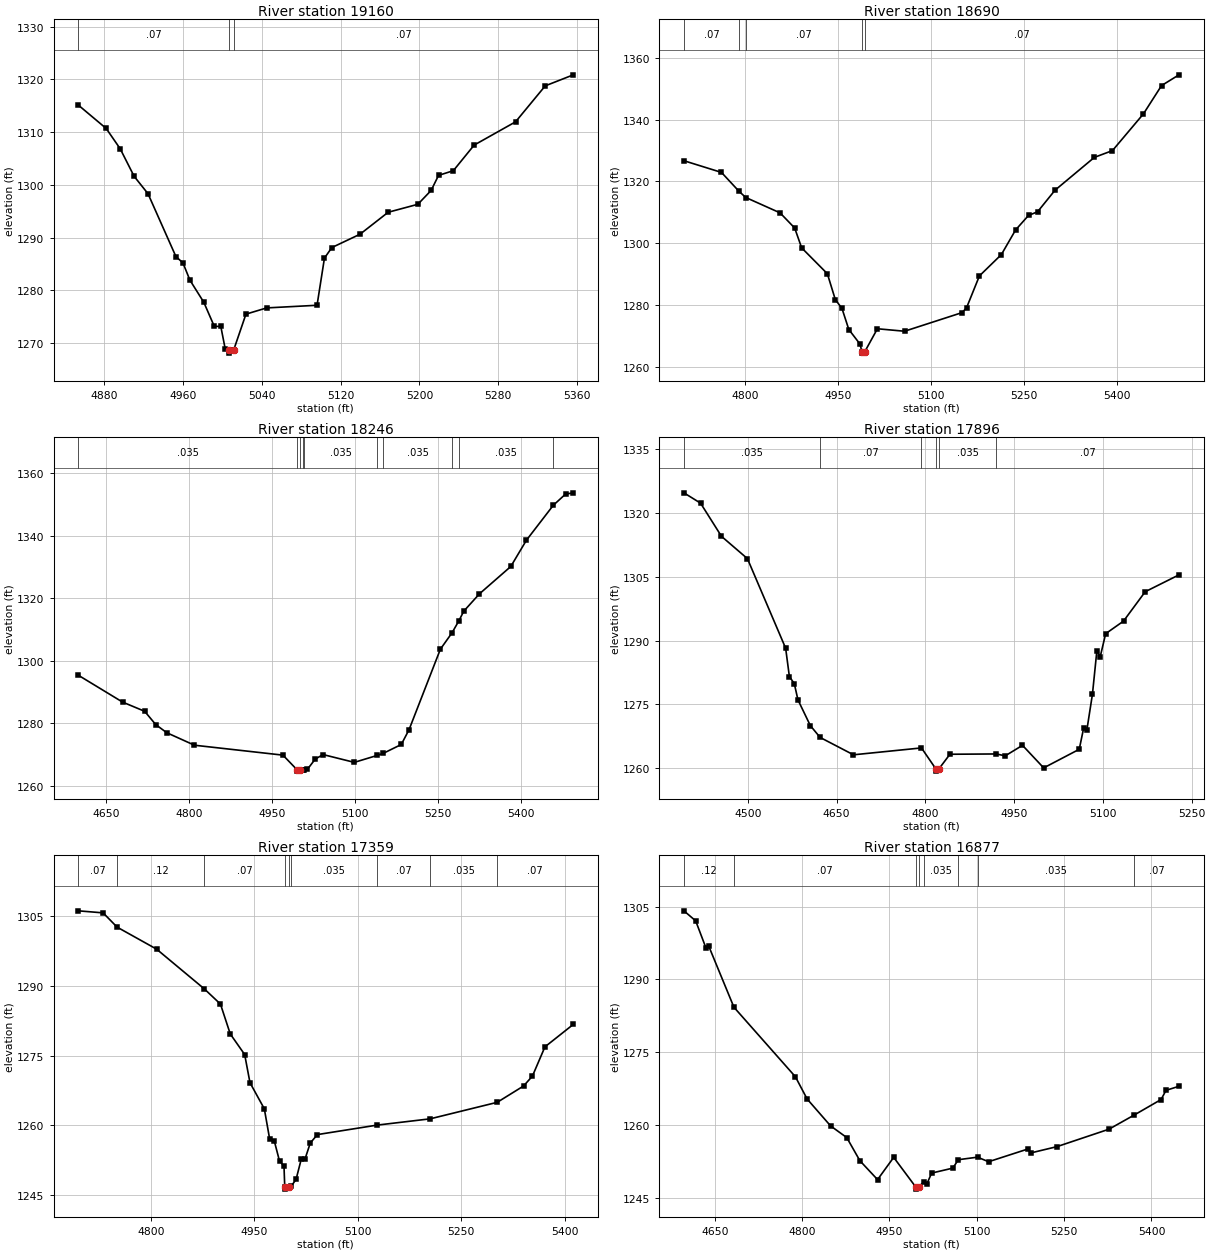
Type RM Length L Ch R = 1,19160,470,470,470
BEGIN DESCRIPTION:
GOSS CREEK 41.0
END DESCRIPTION:
XS GIS Cut Line= 3
      2085275.02     13894275.02      2085175.00     13894175.00
      2084975.00     13893875.01
#Sta/Elev= 30
  4854.1 1315.11  4882.4 1310.67  4896.6 1306.82  4910.7 1301.61  4924.8 1298.30
  4953.1 1286.39  4960.2 1285.20  4967.3 1281.92  4981.4 1277.72  4992.0 1273.16
  4998.6 1273.16  5003.1 1268.87  5006.7 1268.59  5007.0 1268.09  5011.5 1268.59
  5024.1 1275.48  5045.1 1276.66  5096.2 1277.16  5103.7 1286.10  5111.2 1288.10
  5139.8 1290.63  5168.3 1294.79  5198.4 1296.30  5211.9 1298.93  5219.4 1301.78
  5234.4 1302.67  5255.5 1307.52  5297.5 1311.93  5327.6 1318.75  5356.1 1320.84
#Mann=3,-1,0
  4854.1    0.07       0  5006.7    0.05       0  5011.5    0.07       0
Bank Sta=5006.7,5011.5
Exp/Cntr=0.3,0.1

Type RM Length L Ch R = 1,18690,444,444,444
BEGIN DESCRIPTION:
GOSS CREEK 40.0
END DESCRIPTION:
XS GIS Cut Line= 3
      2085592.12     13894099.66      2085475.00     13893825.00
      2085175.00     13893424.99
#Sta/Elev= 30
  4701.4 1326.71  4762.0 1322.93  4790.3 1316.83  4801.2 1314.83  4856.5 1309.87
  4880.1 1304.97  4891.3 1298.58  4932.8 1290.21  4945.6 1281.87  4956.4 1278.99
  4967.4 1272.20  4985.5 1267.48  4988.5 1265.07  4988.9 1264.57  4993.3 1265.07
  5013.5 1272.44  5057.3 1271.64  5150.0 1277.65  5157.3 1279.20  5178.1 1289.52
  5213.5 1296.40  5236.5 1304.37  5257.3 1309.04  5271.9 1310.22  5300.0 1317.18
  5363.5 1327.79  5392.7 1329.98  5442.7 1341.85  5471.9 1350.98  5500.0 1354.45
#Mann=5,-1,0
  4701.4    0.07       0  4790.3   0.035       0  4801.2    0.07       0
  4988.5    0.05       0  4993.3    0.07       0
Bank Sta=4988.5,4993.3
Exp/Cntr=0.3,0.1

Type RM Length L Ch R = 1,18246,350,350,350
BEGIN DESCRIPTION:
GOSS CREEK 39.0
END DESCRIPTION:
XS GIS Cut Line= 3
      2085775.00     13893925.03      2085775.00     13893525.00
      2085425.01     13893175.01
#Sta/Elev= 30
  4600.3 1295.42  4680.3 1286.84  4720.3 1283.89  4740.3 1279.64  4760.3 1277.04
  4810.3 1273.05  4970.3 1269.88  4995.4 1265.27  4995.7 1264.77  5000.3 1265.27
  5005.9 1265.28  5008.0 1265.29  5014.5 1265.34  5028.6 1268.61  5042.8 1270.06
  5099.3 1267.57  5140.7 1269.79  5151.6 1270.45  5184.2 1273.28  5198.3 1278.03
  5254.9 1303.74  5275.9 1308.96  5288.4 1312.83  5297.3 1315.91  5325.6 1321.44
  5382.2 1330.17  5410.5 1338.58  5459.1 1349.74  5481.2 1353.31  5495.3 1353.71
#Mann=10,-1,0
  4600.3   0.035       0  4995.4   0.035       0  5000.3   0.035       0
  5005.9    0.07       0  5008.0   0.035       0  5140.7    0.07       0
  5151.6   0.035       0  5275.9    0.07       0  5288.4   0.035       0
  5459.1    0.07       0
Bank Sta=4995.4,5000.3
Exp/Cntr=0.3,0.1

Type RM Length L Ch R = 1,17896,537,537,537
BEGIN DESCRIPTION:
GOSS CREEK 38.0
END DESCRIPTION:
XS GIS Cut Line= 3
      2086524.97     13893674.98      2086043.50     13893314.91
      2085939.66     13893103.78
#Sta/Elev= 30
  4392.0 1324.79  4420.1 1322.36  4455.5 1314.55  4499.3 1309.31  4563.9 1288.23
  4570.2 1281.57  4578.5 1279.90  4584.7 1276.08  4605.6 1270.03  4622.1 1267.25
  4678.5 1263.16  4793.4 1264.78  4817.8 1259.82  4818.2 1259.32  4822.7 1259.82
  4841.5 1263.29  4920.1 1263.36  4934.9 1262.91  4964.1 1265.39  4999.9 1260.08
  5060.0 1264.46  5067.3 1269.37  5072.9 1269.02  5082.3 1277.43  5089.8 1287.69
  5095.4 1286.22  5104.6 1291.65  5134.8 1294.61  5171.4 1301.52  5228.5 1305.49
#Mann=6,-1,0
  4392.0   0.035       0  4622.1    0.07       0  4793.4   0.035       0
  4817.8    0.05       0  4822.7   0.035       0  4920.1    0.07       0
Bank Sta=4817.8,4822.7
Exp/Cntr=0.3,0.1

Type RM Length L Ch R = 1,17359,482,482,482
BEGIN DESCRIPTION:
GOSS CREEK 37.0
END DESCRIPTION:
XS GIS Cut Line= 3
      2086706.69     13893373.94      2086475.00     13893175.00
      2086074.99     13893075.00
#Sta/Elev= 30
  4694.7 1306.17  4730.7 1305.73  4750.9 1302.67  4808.2 1297.93  4877.4 1289.38
  4900.8 1286.11  4915.0 1279.69  4935.9 1275.26  4943.6 1269.20  4964.4 1263.58
  4972.1 1257.11  4978.7 1256.75  4986.4 1252.35  4992.9 1251.28  4994.0 1246.81
  4994.4 1246.31  4999.6 1246.81  5003.2 1246.91  5010.4 1248.40  5018.1 1252.85
  5023.3 1252.75  5031.0 1256.22  5041.3 1258.04  5127.9 1260.08  5204.8 1261.43
  5302.0 1264.98  5340.2 1268.49  5353.1 1270.63  5371.2 1276.91  5412.4 1281.75
#Mann=9,-1,0
  4694.7    0.07       0  4750.9    0.12       0  4877.4    0.07       0
  4994.0    0.05       0  4999.6    0.07       0  5003.2   0.035       0
  5127.9    0.07       0  5204.8   0.035       0  5302.0    0.07       0
Bank Sta=4994,4999.6
Exp/Cntr=0.3,0.1

Type RM Length L Ch R = 1,16877,454,454,454
BEGIN DESCRIPTION:
GOSS CREEK 36.0
END DESCRIPTION:
XS GIS Cut Line= 3
      2086975.00     13892675.00      2086575.00     13892725.00
      2086175.03     13892924.99
#Sta/Elev= 30
  4596.9 1304.13  4617.1 1302.06  4634.7 1296.49  4639.7 1296.80  4682.8 1284.25
  4788.4 1269.91  4808.5 1265.33  4848.8 1259.78  4876.6 1257.37  4899.2 1252.59
  4929.5 1248.70  4957.2 1253.29  4994.7 1247.24  4995.1 1246.74  5000.3 1247.24
  5009.2 1248.23  5014.0 1247.77  5022.4 1250.05  5058.7 1251.07  5068.3 1252.81
  5101.2 1253.33  5120.2 1252.39  5187.3 1255.00  5192.9 1254.21  5237.6 1255.50
  5327.0 1259.10  5370.6 1262.04  5416.5 1265.22  5424.9 1267.11  5447.2 1267.95
#Mann=8,-1,0
  4596.9    0.12       0  4682.8    0.07       0  4994.7    0.05       0
  5000.3    0.07       0  5009.2   0.035       0  5068.3    0.07       0
  5101.2   0.035       0  5370.6    0.07       0
Bank Sta=4994.7,5000.3
Exp/Cntr=0.3,0.1

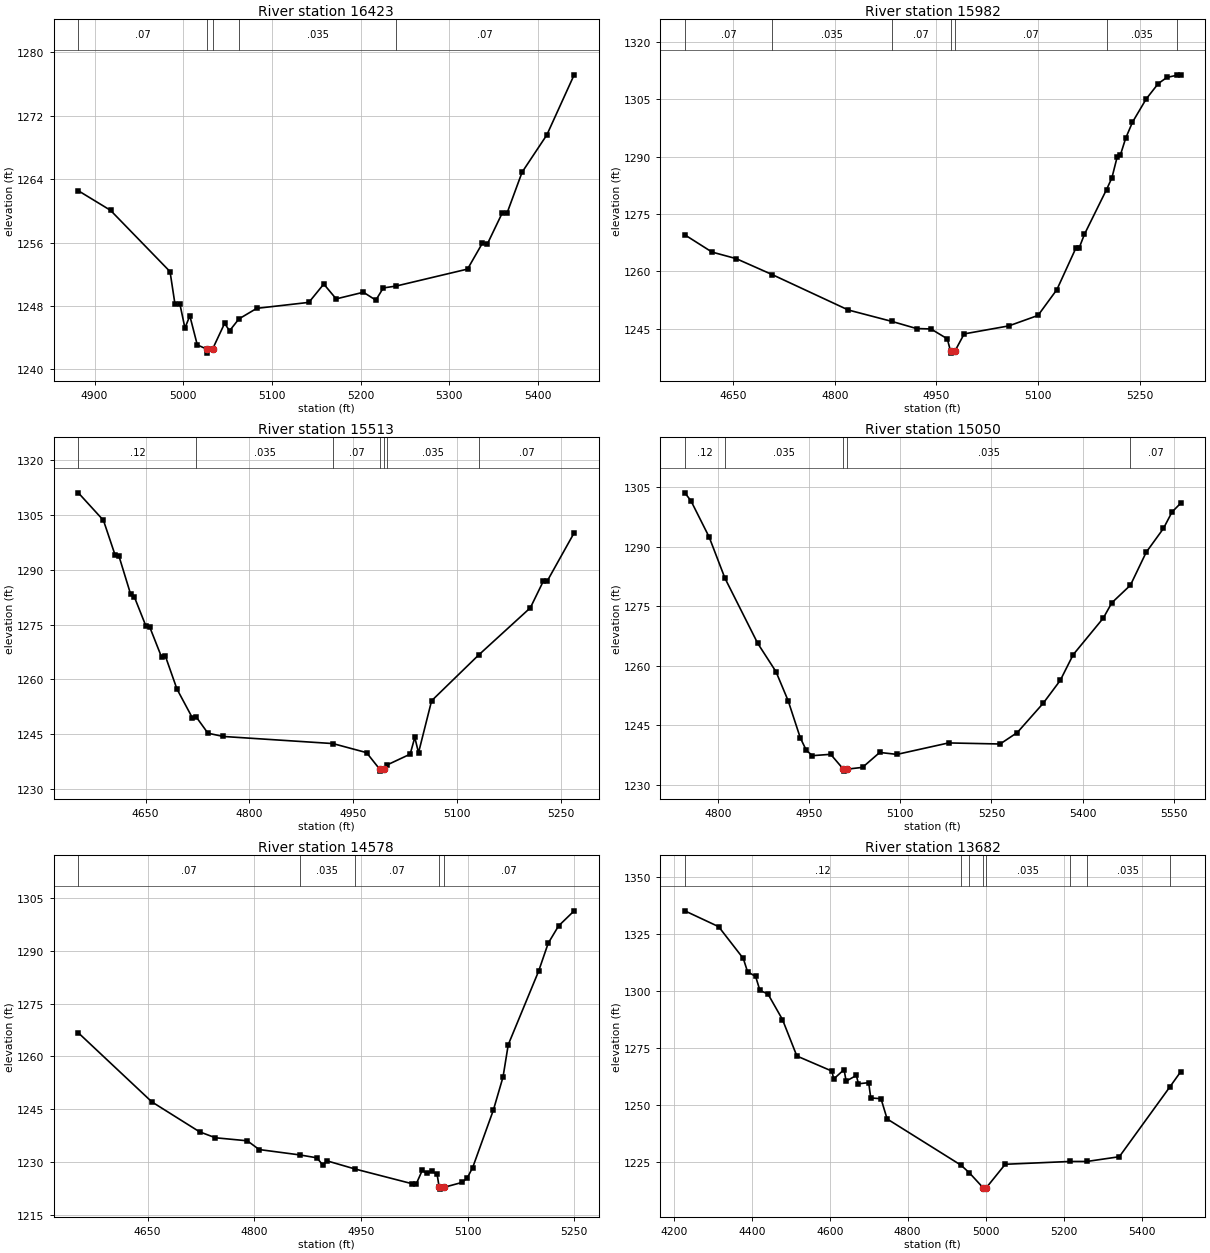
Type RM Length L Ch R = 1,16423,441,441,441
BEGIN DESCRIPTION:
GOSS CREEK 35.0
END DESCRIPTION:
XS GIS Cut Line= 3
      2086624.97     13892275.01      2086525.00     13892325.00
      2086124.99     13892124.99
#Sta/Elev= 30
  4881.7 1262.54  4918.0 1260.07  4985.1 1252.34  4990.7 1248.20  4996.3 1248.20
  5001.9 1245.22  5007.4 1246.77  5015.8 1243.10  5026.6 1242.56  5027.1 1242.06
  5033.0 1242.56  5046.6 1245.81  5052.2 1244.88  5062.8 1246.38  5082.9 1247.71
  5141.6 1248.46  5158.4 1250.77  5172.4 1248.90  5203.1 1249.74  5217.1 1248.74
  5225.5 1250.28  5240.0 1250.52  5320.5 1252.66  5337.3 1255.94  5342.9 1255.84
  5359.6 1259.73  5365.2 1259.77  5382.0 1264.88  5409.9 1269.58  5440.7 1277.16
#Mann=5,-1,0
  4881.7    0.07       0  5026.6    0.05       0  5033.0    0.07       0
  5062.8   0.035       0  5240.0    0.07       0
Bank Sta=5026.6,5033
Exp/Cntr=0.3,0.1

Type RM Length L Ch R = 1,15982,469,469,469
BEGIN DESCRIPTION:
GOSS CREEK 34.0
END DESCRIPTION:
XS GIS Cut Line= 3
      2086775.02     13892075.01      2086375.00     13891925.00
      2086074.96     13891874.99
#Sta/Elev= 30
  4578.8 1269.57  4618.9 1265.07  4654.5 1263.36  4707.8 1259.18  4820.0 1249.94
  4884.1 1246.97  4920.6 1245.10  4941.9 1244.99  4966.0 1242.42  4970.8 1239.18
  4971.3 1238.68  4977.2 1239.18  4990.9 1243.70  5056.7 1245.79  5099.8 1248.52
  5127.7 1255.27  5155.6 1266.07  5160.6 1266.18  5168.2 1269.66  5200.9 1281.39
  5208.8 1284.43  5216.4 1289.77  5221.4 1290.44  5229.1 1294.77  5239.2 1298.99
  5259.5 1305.07  5277.2 1309.06  5289.9 1310.67  5304.5 1311.23  5310.2 1311.35
#Mann=7,-1,0
  4578.8    0.07       0  4707.8   0.035       0  4884.1    0.07       0
  4970.8    0.05       0  4977.2    0.07       0  5200.9   0.035       0
  5304.5    0.07       0
Bank Sta=4970.8,4977.2
Exp/Cntr=0.3,0.1

Type RM Length L Ch R = 1,15513,463,463,463
BEGIN DESCRIPTION:
GOSS CREEK 33.0
END DESCRIPTION:
XS GIS Cut Line= 3
      2086824.98     13891275.01      2086425.00     13891475.00
      2086174.96     13891575.02
#Sta/Elev= 30
  4552.8 1311.03  4589.1 1303.50  4605.9 1294.02  4611.5 1293.72  4628.3 1283.34
  4633.8 1282.53  4650.6 1274.52  4656.2 1274.21  4673.0 1266.13  4678.6 1266.35
  4695.3 1257.36  4717.7 1249.44  4723.5 1249.63  4740.1 1245.27  4762.4 1244.38
  4920.6 1242.44  4969.3 1239.96  4988.4 1235.40  4988.9 1234.90  4994.9 1235.40
  4999.3 1236.62  5032.3 1239.54  5039.0 1244.12  5044.4 1239.93  5063.3 1254.15
  5131.3 1266.67  5206.0 1279.58  5224.8 1286.89  5230.2 1286.83  5269.3 1300.09
#Mann=7,-1,0
  4552.8    0.12       0  4723.5   0.035       0  4920.6    0.07       0
  4988.4   0.035       0  4994.9    0.07       0  4999.3   0.035       0
  5131.3    0.07       0
Bank Sta=4988.4,4994.9
Exp/Cntr=0.3,0.1

Type RM Length L Ch R = 1,15050,472,472,472
BEGIN DESCRIPTION:
GOSS CREEK 32.0
END DESCRIPTION:
XS GIS Cut Line= 3
      2086725.01     13891025.00      2086475.00     13891025.00
      2086075.00     13891425.00
#Sta/Elev= 30
  4745.5 1303.57  4755.5 1301.59  4785.5 1292.44  4811.5 1282.06  4865.5 1265.61
  4895.5 1258.48  4915.5 1251.16  4935.5 1241.79  4945.5 1238.62  4955.5 1237.30
  4985.5 1237.64  5006.3 1233.90  5006.8 1233.40  5012.9 1233.90  5037.9 1234.35
  5066.2 1238.11  5094.5 1237.62  5179.4 1240.51  5264.2 1240.24  5292.5 1243.13
  5334.9 1250.47  5363.2 1256.28  5384.4 1262.75  5433.9 1271.97  5448.1 1275.86
  5478.6 1280.28  5504.6 1288.59  5532.9 1294.58  5547.1 1298.74  5561.2 1300.94
#Mann=5,-1,0
  4745.5    0.12       0  4811.5   0.035       0  5006.3   0.035       0
  5012.9   0.035       0  5478.6    0.07       0
Bank Sta=5006.3,5012.9
Exp/Cntr=0.3,0.1

Type RM Length L Ch R = 1,14578,896,896,896
BEGIN DESCRIPTION:
GOSS CREEK 31.0
END DESCRIPTION:
XS GIS Cut Line= 3
      2086624.98     13890874.99      2086225.00     13890675.00
      2086024.99     13890524.99
#Sta/Elev= 30
  4552.6 1266.72  4656.0 1247.07  4723.1 1238.55  4745.4 1236.86  4790.2 1236.00
  4806.9 1233.51  4863.7 1231.99  4888.0 1231.16  4896.4 1229.11  4902.0 1230.31
  4941.8 1227.97  5021.7 1223.80  5027.9 1223.80  5036.2 1227.59  5042.5 1226.71
  5049.8 1227.34  5057.1 1226.48  5060.0 1222.75  5060.5 1222.25  5066.6 1222.75
  5092.5 1224.18  5099.8 1225.55  5107.1 1228.39  5136.2 1244.74  5149.8 1254.17
  5157.1 1263.33  5199.8 1284.25  5213.3 1292.21  5227.9 1297.14  5249.8 1301.43
#Mann=5,-1,0
  4552.6    0.07       0  4863.7   0.035       0  4941.8    0.07       0
  5060.0    0.05       0  5066.6    0.07       0
Bank Sta=5060,5066.6
Exp/Cntr=0.3,0.1

Type RM Length L Ch R = 1,13682,430,430,430
BEGIN DESCRIPTION:
GOSS CREEK 30.0
END DESCRIPTION:
XS GIS Cut Line= 3
      2087357.38     13889880.55      2086625.00     13890125.00
      2086225.00     13890425.00
#Sta/Elev= 30
  4228.2 1335.27  4315.0 1328.33  4378.3 1314.38  4389.2 1308.58  4409.9 1306.51
  4420.9 1300.40  4441.6 1298.81  4478.8 1287.62  4515.7 1271.64  4605.2 1265.06
  4610.5 1261.60  4636.8 1265.69  4642.1 1260.65  4668.4 1263.11  4673.7 1259.47
  4700.0 1259.96  4705.3 1253.27  4731.6 1252.92  4747.3 1244.06  4936.6 1223.82
  4957.9 1220.52  4994.1 1213.80  4994.6 1213.30  5001.2 1213.80  5050.3 1224.19
  5216.0 1225.42  5259.7 1225.42  5343.0 1227.50  5472.1 1257.96  5500.3 1264.70
#Mann=8,-1,0
  4228.2    0.12       0  4936.6    0.07       0  4957.9   0.035       0
  4994.1   0.035       0  5001.2   0.035       0  5216.0    0.07       0
  5259.7   0.035       0  5472.1    0.07       0
Bank Sta=4994.1,5001.2
Exp/Cntr=0.3,0.1

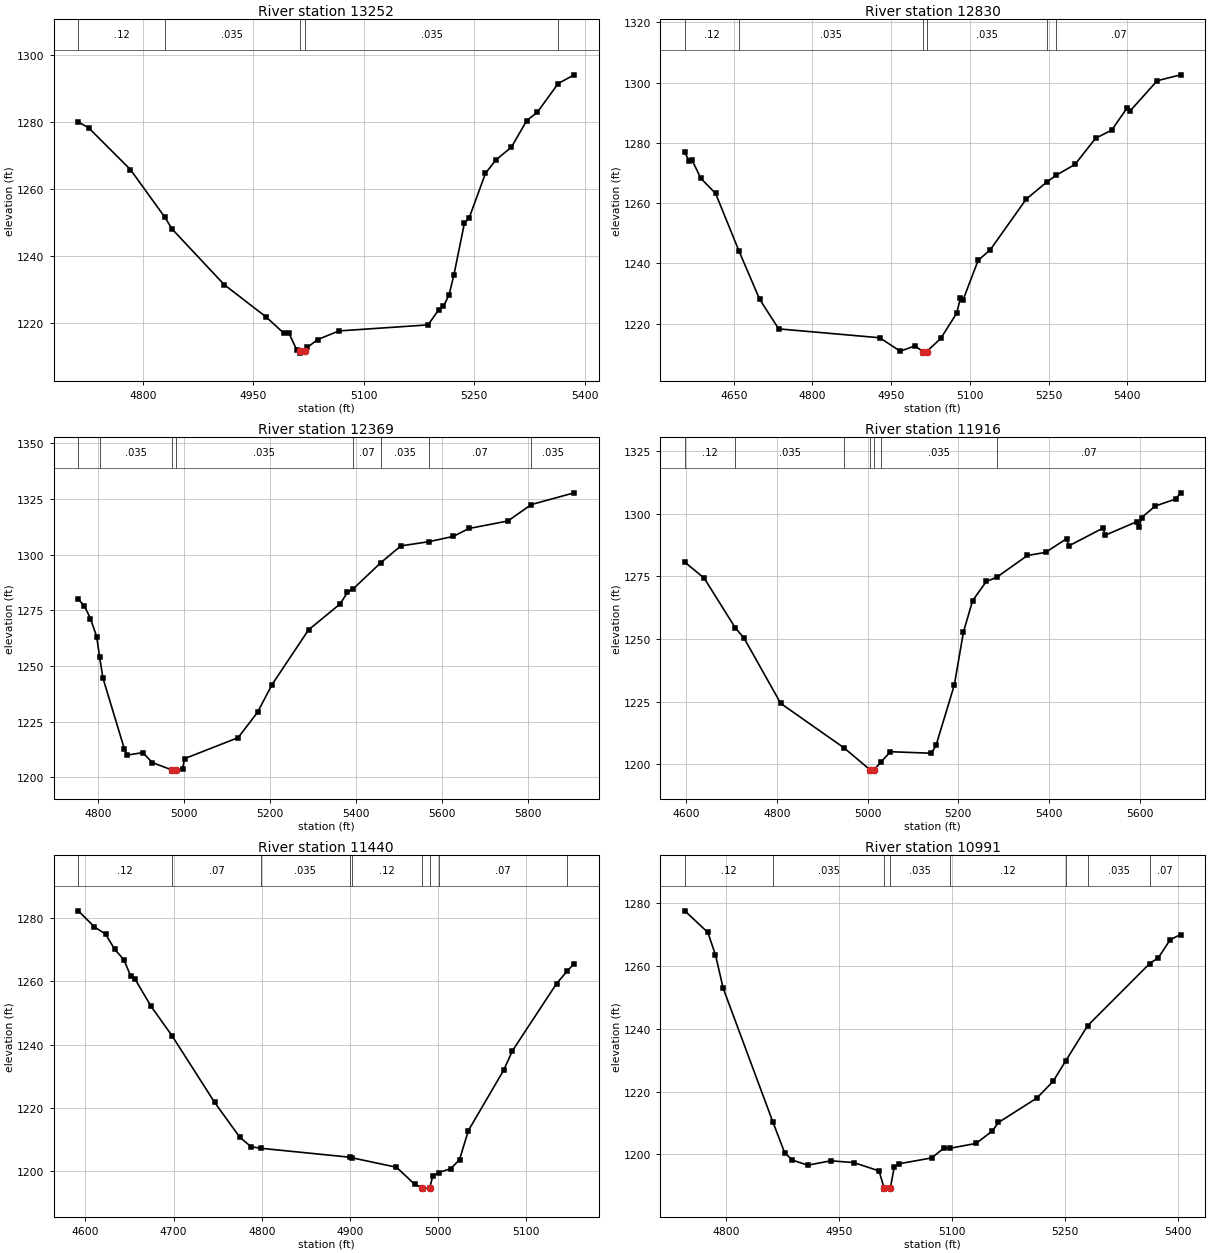
Type RM Length L Ch R = 1,13252,422,422,422
BEGIN DESCRIPTION:
GOSS CREEK 29.0
END DESCRIPTION:
XS GIS Cut Line= 3
      2086474.99     13889725.01      2086275.00     13889925.00
      2085975.03     13890174.98
#Sta/Elev= 30
  4712.6 1280.07  4726.7 1278.30  4783.3 1265.85  4830.2 1251.55  4839.9 1248.06
  4910.6 1231.44  4967.1 1221.85  4991.9 1216.86  4998.7 1216.86  5009.1 1211.97
  5013.3 1211.45  5013.8 1210.95  5020.5 1211.45  5023.4 1212.65  5037.7 1215.01
  5066.4 1217.59  5187.4 1219.39  5201.7 1223.80  5208.3 1224.90  5216.1 1228.44
  5222.6 1234.33  5236.9 1249.84  5243.4 1251.43  5265.5 1264.73  5279.8 1268.77
  5300.7 1272.52  5321.5 1280.50  5335.8 1282.95  5364.2 1291.57  5385.9 1294.17
#Mann=5,-1,0
  4712.6    0.12       0  4830.2   0.035       0  5013.3   0.035       0
  5020.5   0.035       0  5364.2    0.07       0
Bank Sta=5013.3,5020.5
Exp/Cntr=0.3,0.1

Type RM Length L Ch R = 1,12830,461,461,461
BEGIN DESCRIPTION:
GOSS CREEK 28.0
END DESCRIPTION:
XS GIS Cut Line= 3
      2086324.98     13889525.01      2085925.00     13889725.00
      2085831.70     13890214.20
#Sta/Elev= 30
  4556.6 1276.85  4565.0 1273.92  4570.5 1274.26  4587.3 1268.20  4615.3 1263.21
  4660.2 1243.98  4699.1 1228.15  4735.5 1218.26  4928.3 1215.31  4967.4 1210.83
  4995.4 1212.64  5010.4 1210.71  5010.9 1210.21  5017.6 1210.71  5044.5 1215.08
  5075.0 1223.49  5082.0 1228.48  5087.1 1227.89  5115.8 1240.99  5139.2 1244.58
  5207.4 1261.32  5247.3 1267.08  5265.0 1269.29  5300.7 1272.89  5339.7 1281.54
  5370.3 1284.22  5399.9 1291.61  5405.0 1290.50  5457.1 1300.63  5501.8 1302.59
#Mann=6,-1,0
  4556.6    0.12       0  4660.2   0.035       0  5010.4   0.035       0
  5017.6   0.035       0  5247.3    0.12       0  5265.0    0.07       0
Bank Sta=5010.4,5017.6
Exp/Cntr=0.3,0.1

Type RM Length L Ch R = 1,12369,453,453,453
BEGIN DESCRIPTION:
GOSS CREEK 27.0
END DESCRIPTION:
XS GIS Cut Line= 3
      2086024.96     13889175.03      2085825.00     13889325.00
      2085012.25     13889717.69
#Sta/Elev= 30
  4754.3 1279.91  4767.8 1277.20  4782.4 1271.36  4797.0 1263.19  4803.8 1253.99
  4811.5 1244.62  4861.5 1212.67  4867.8 1210.01  4904.3 1211.14  4926.1 1206.69
  4972.0 1203.32  4972.5 1202.82  4980.2 1203.32  4997.0 1203.99  5001.1 1208.41
  5125.8 1217.86  5170.8 1229.22  5204.7 1241.71  5289.5 1266.28  5362.9 1277.91
  5379.9 1283.10  5392.8 1284.60  5457.8 1296.49  5504.0 1303.97  5569.3 1305.86
  5626.2 1308.25  5662.2 1311.78  5752.6 1315.14  5807.5 1322.54  5906.9 1327.80
#Mann=8,-1,0
  4754.3    0.12       0  4803.8   0.035       0  4972.0   0.035       0
  4980.2   0.035       0  5392.8    0.07       0  5457.8   0.035       0
  5569.3    0.07       0  5807.5   0.035       0
Bank Sta=4972,4980.2
Exp/Cntr=0.3,0.1

Type RM Length L Ch R = 1,11916,476,476,476
BEGIN DESCRIPTION:
GOSS CREEK 26.0
END DESCRIPTION:
XS GIS Cut Line= 3
      2086024.96     13889024.99      2085625.00     13888975.00
      2084939.69     13889061.39
#Sta/Elev= 30
  4596.9 1280.63  4639.7 1274.23  4708.3 1254.42  4727.9 1250.25  4808.5 1224.29
  4947.8 1206.63  5005.8 1197.80  5006.3 1197.30  5014.3 1197.80  5029.3 1200.86
  5050.4 1205.04  5141.1 1204.43  5151.2 1207.59  5191.5 1231.66  5211.6 1252.75
  5231.8 1265.26  5262.0 1272.91  5285.2 1274.61  5352.7 1283.28  5393.1 1284.52
  5439.1 1289.99  5444.1 1287.10  5519.4 1294.19  5524.4 1291.35  5594.6 1296.81
  5599.6 1294.82  5604.7 1298.42  5635.0 1303.01  5679.9 1305.79  5690.7 1308.26
#Mann=7,-1,0
  4596.9    0.12       0  4708.3   0.035       0  4947.8    0.07       0
  5005.8    0.05       0  5014.3    0.07       0  5029.3   0.035       0
  5285.2    0.07       0
Bank Sta=5005.8,5014.3
Exp/Cntr=0.3,0.1

Type RM Length L Ch R = 1,11440,449,449,449
BEGIN DESCRIPTION:
GOSS CREEK 25.0
END DESCRIPTION:
XS GIS Cut Line= 3
      2086025.02     13888675.01      2085625.00     13888575.00
      2085475.03     13888575.00
#Sta/Elev= 30
  4591.9 1282.25  4610.0 1277.19  4622.8 1274.89  4633.2 1270.08  4643.5 1266.85
  4651.2 1261.72  4656.3 1260.66  4674.4 1252.10  4698.2 1242.81  4746.5 1221.77
  4774.9 1210.84  4787.8 1207.79  4799.0 1207.31  4899.8 1204.49  4902.5 1204.29
  4952.7 1201.33  4973.3 1195.94  4981.9 1194.92  4982.4 1194.42  4990.5 1194.92
  4993.9 1198.60  5000.6 1199.66  5014.2 1200.87  5024.2 1203.72  5034.2 1212.89
  5074.2 1231.92  5084.2 1238.08  5134.2 1259.27  5146.4 1263.27  5154.2 1265.59
#Mann=9,-1,0
  4591.9    0.12       0  4698.2    0.07       0  4799.0   0.035       0
  4899.8    0.07       0  4902.5    0.12       0  4981.9    0.05       0
  4990.5    0.12       0  5000.6    0.07       0  5146.4   0.035       0
Bank Sta=4981.9,4990.5
Exp/Cntr=0.3,0.1

Type RM Length L Ch R = 1,10991,465,465,465
BEGIN DESCRIPTION:
GOSS CREEK 24.0
END DESCRIPTION:
XS GIS Cut Line= 3
      2086024.96     13888125.01      2085775.00     13888175.00
      2085425.02     13888374.99
#Sta/Elev= 30
  4745.2 1277.52  4775.8 1270.64  4785.9 1263.50  4796.1 1252.91  4862.2 1210.26
  4877.7 1200.56  4887.9 1198.22  4908.3 1196.59  4938.9 1197.98  4969.5 1197.42
  5003.0 1194.76  5009.5 1189.47  5010.0 1188.97  5018.1 1189.47  5023.1 1195.97
  5029.6 1197.04  5072.8 1198.90  5088.6 1201.94  5097.0 1201.96  5131.8 1203.52
  5153.4 1207.49  5161.4 1210.17  5212.5 1217.96  5234.1 1223.31  5250.9 1229.86
  5279.8 1240.97  5361.9 1260.69  5373.7 1262.63  5389.5 1268.35  5403.2 1269.98
#Mann=8,-1,0
  4745.2    0.12       0  4862.2   0.035       0  5009.5   0.035       0
  5018.1   0.035       0  5097.0    0.12       0  5250.9    0.07       0
  5279.8   0.035       0  5361.9    0.07       0
Bank Sta=5009.5,5018.1
Exp/Cntr=0.3,0.1

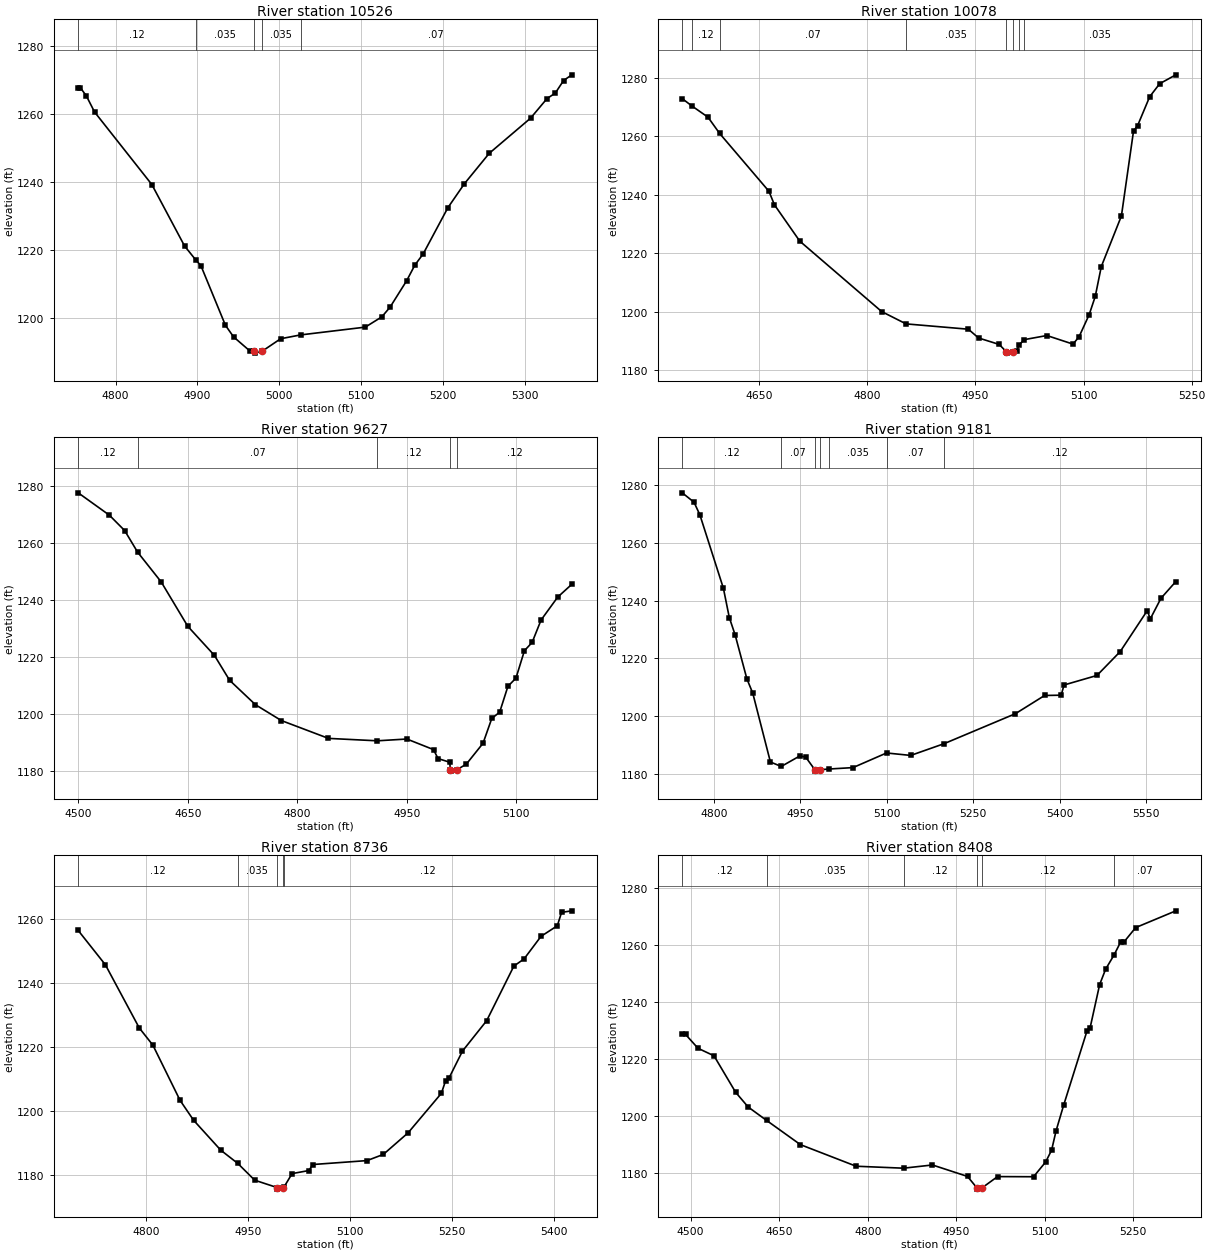
Type RM Length L Ch R = 1,10526,448,448,448
BEGIN DESCRIPTION:
GOSS CREEK 23.0
END DESCRIPTION:
XS GIS Cut Line= 3
      2085924.97     13887775.00      2085675.00     13887775.00
      2085325.03     13887825.00
#Sta/Elev= 30
  4754.3 1267.87  4756.8 1267.87  4764.3 1265.39  4774.3 1260.67  4844.3 1239.31
  4884.3 1221.21  4898.0 1217.10  4904.3 1215.41  4934.3 1197.83  4944.3 1194.41
  4964.3 1190.25  4969.8 1190.14  4970.3 1189.64  4978.8 1190.14  5001.8 1193.88
  5026.3 1195.01  5105.3 1197.30  5125.5 1200.33  5135.6 1203.19  5155.8 1210.95
  5165.9 1215.58  5176.0 1218.85  5206.3 1232.50  5226.5 1239.56  5256.8 1248.50
  5307.3 1258.85  5327.5 1264.64  5337.6 1266.25  5347.7 1269.95  5357.8 1271.63
#Mann=5,-1,0
  4754.3    0.12       0  4898.0   0.035       0  4969.8   0.035       0
  4978.8   0.035       0  5026.3    0.07       0
Bank Sta=4969.8,4978.8
Exp/Cntr=0.3,0.1

Type RM Length L Ch R = 1,10078,451,451,451
BEGIN DESCRIPTION:
GOSS CREEK 22.0
END DESCRIPTION:
XS GIS Cut Line= 3
      2086025.01     13887625.01      2085675.00     13887325.00
      2085475.00     13887225.00
#Sta/Elev= 30
  4543.4 1272.80  4556.3 1270.38  4579.1 1266.46  4595.3 1260.88  4663.6 1241.13
  4671.3 1236.47  4706.4 1224.07  4820.0 1199.98  4853.8 1195.77  4940.2 1193.95
  4954.4 1190.95  4983.0 1188.74  4992.8 1186.27  4993.3 1185.77  5001.8 1186.27
  5007.2 1186.43  5010.6 1188.60  5017.9 1190.39  5049.1 1191.79  5085.4 1188.85
  5093.8 1191.39  5107.8 1198.94  5116.2 1205.15  5124.6 1215.37  5152.5 1232.69
  5169.3 1261.73  5174.9 1263.54  5191.7 1273.45  5205.6 1277.91  5228.0 1280.94
#Mann=8,-1,0
  4543.4    0.07       0  4556.3    0.12       0  4595.3    0.07       0
  4853.8   0.035       0  4992.8   0.035       0  5001.8   0.035       0
  5010.6    0.07       0  5017.9   0.035       0
Bank Sta=4992.8,5001.8
Exp/Cntr=0.3,0.1

Type RM Length L Ch R = 1,9627,446,446,446
BEGIN DESCRIPTION:
GOSS CREEK 21.0
END DESCRIPTION:
XS GIS Cut Line= 3
      2086325.01     13887325.01      2085925.00     13887025.00
      2085765.74     13886950.34
#Sta/Elev= 30
  4500.0 1277.74  4542.7 1269.87  4563.6 1264.47  4581.3 1256.89  4613.6 1246.42
  4650.0 1230.82  4686.5 1220.58  4707.3 1211.83  4742.7 1203.24  4778.1 1197.68
  4842.7 1191.40  4909.5 1190.55  4950.0 1191.18  4986.5 1187.46  4992.7 1184.30
  5008.7 1183.02  5009.6 1180.39  5010.1 1179.89  5018.7 1180.39  5031.5 1182.37
  5054.3 1189.68  5066.3 1198.42  5077.1 1200.63  5088.4 1209.71  5099.4 1212.60
  5111.0 1222.24  5121.5 1225.13  5133.8 1233.03  5156.6 1241.09  5175.9 1245.58
#Mann=5,-1,0
  4500.0    0.12       0  4581.3    0.07       0  4909.5    0.12       0
  5009.6    0.05       0  5018.7    0.12       0
Bank Sta=5009.6,5018.7
Exp/Cntr=0.3,0.1

Type RM Length L Ch R = 1,9181,445,445,445
BEGIN DESCRIPTION:
GOSS CREEK 20.0
END DESCRIPTION:
XS GIS Cut Line= 3
      2086524.97     13886824.99      2086275.00     13886775.00
      2085679.47     13886856.50
#Sta/Elev= 30
  4745.4 1277.33  4765.8 1274.08  4776.0 1269.69  4816.8 1244.23  4827.0 1234.12
  4837.1 1228.12  4857.5 1212.87  4867.7 1207.92  4898.3 1184.07  4917.1 1182.53
  4949.3 1186.17  4959.5 1185.77  4975.3 1181.41  4975.8 1180.91  4984.5 1181.41
  4999.8 1181.64  5041.5 1182.13  5099.7 1187.20  5141.6 1186.35  5199.6 1190.43
  5323.3 1200.82  5373.8 1207.12  5402.5 1207.22  5407.5 1210.75  5464.6 1214.06
  5505.0 1222.35  5551.9 1236.54  5557.0 1233.63  5575.6 1240.80  5601.4 1246.60
#Mann=7,-1,0
  4745.4    0.12       0  4917.1    0.07       0  4975.3   0.035       0
  4984.5    0.07       0  4999.8   0.035       0  5099.7    0.07       0
  5199.6    0.12       0
Bank Sta=4975.3,4984.5
Exp/Cntr=0.3,0.1

Type RM Length L Ch R = 1,8736,328,328,328
BEGIN DESCRIPTION:
GOSS CREEK 19.0
END DESCRIPTION:
XS GIS Cut Line= 3
      2086375.00     13886475.00      2086075.00     13886475.00
      2085675.00     13886625.00
#Sta/Elev= 30
  4699.5 1256.33  4739.5 1245.63  4789.5 1225.88  4809.5 1220.53  4849.5 1203.31
  4869.5 1197.08  4909.5 1187.74  4934.5 1183.62  4959.5 1178.37  4992.4 1176.08
  4992.9 1175.58  5001.6 1176.08  5002.9 1176.32  5014.6 1180.43  5039.5 1181.39
  5044.9 1183.26  5125.0 1184.49  5149.0 1186.42  5185.5 1193.16  5234.5 1205.49
  5240.7 1209.40  5246.0 1210.36  5265.6 1218.68  5301.2 1228.16  5341.3 1245.21
  5356.4 1247.47  5381.3 1254.50  5405.3 1257.80  5411.6 1261.99  5426.7 1262.47
#Mann=5,-1,0
  4699.5    0.12       0  4934.5   0.035       0  4992.4   0.035       0
  5001.6   0.035       0  5002.9    0.12       0
Bank Sta=4992.4,5001.6
Exp/Cntr=0.3,0.1

Type RM Length L Ch R = 1,8408,686,686,686
BEGIN DESCRIPTION:
GOSS CREEK 18.0
END DESCRIPTION:
XS GIS Cut Line= 3
      2086339.80     13886365.89      2086085.58     13886207.53
      2085558.13     13886307.20
#Sta/Elev= 30
  4485.8 1228.51  4491.4 1228.51  4512.5 1223.64  4539.6 1221.00  4576.2 1208.21
  4597.5 1203.02  4628.7 1198.31  4686.0 1189.81  4780.4 1182.23  4860.7 1181.54
  4909.7 1182.67  4969.1 1178.65  4984.8 1174.69  4985.3 1174.19  4994.1 1174.69
  5020.0 1178.59  5081.0 1178.54  5101.4 1183.69  5111.6 1187.87  5119.2 1194.69
  5131.9 1203.60  5171.6 1229.75  5176.7 1230.71  5193.0 1246.02  5203.2 1251.44
  5217.1 1256.29  5229.0 1261.13  5234.1 1260.94  5254.0 1266.01  5322.1 1271.90
#Mann=6,-1,0
  4485.8    0.12       0  4628.7   0.035       0  4860.7    0.12       0
  4984.8    0.05       0  4994.1    0.12       0  5217.1    0.07       0
Bank Sta=4984.8,4994.1
Exp/Cntr=0.3,0.1