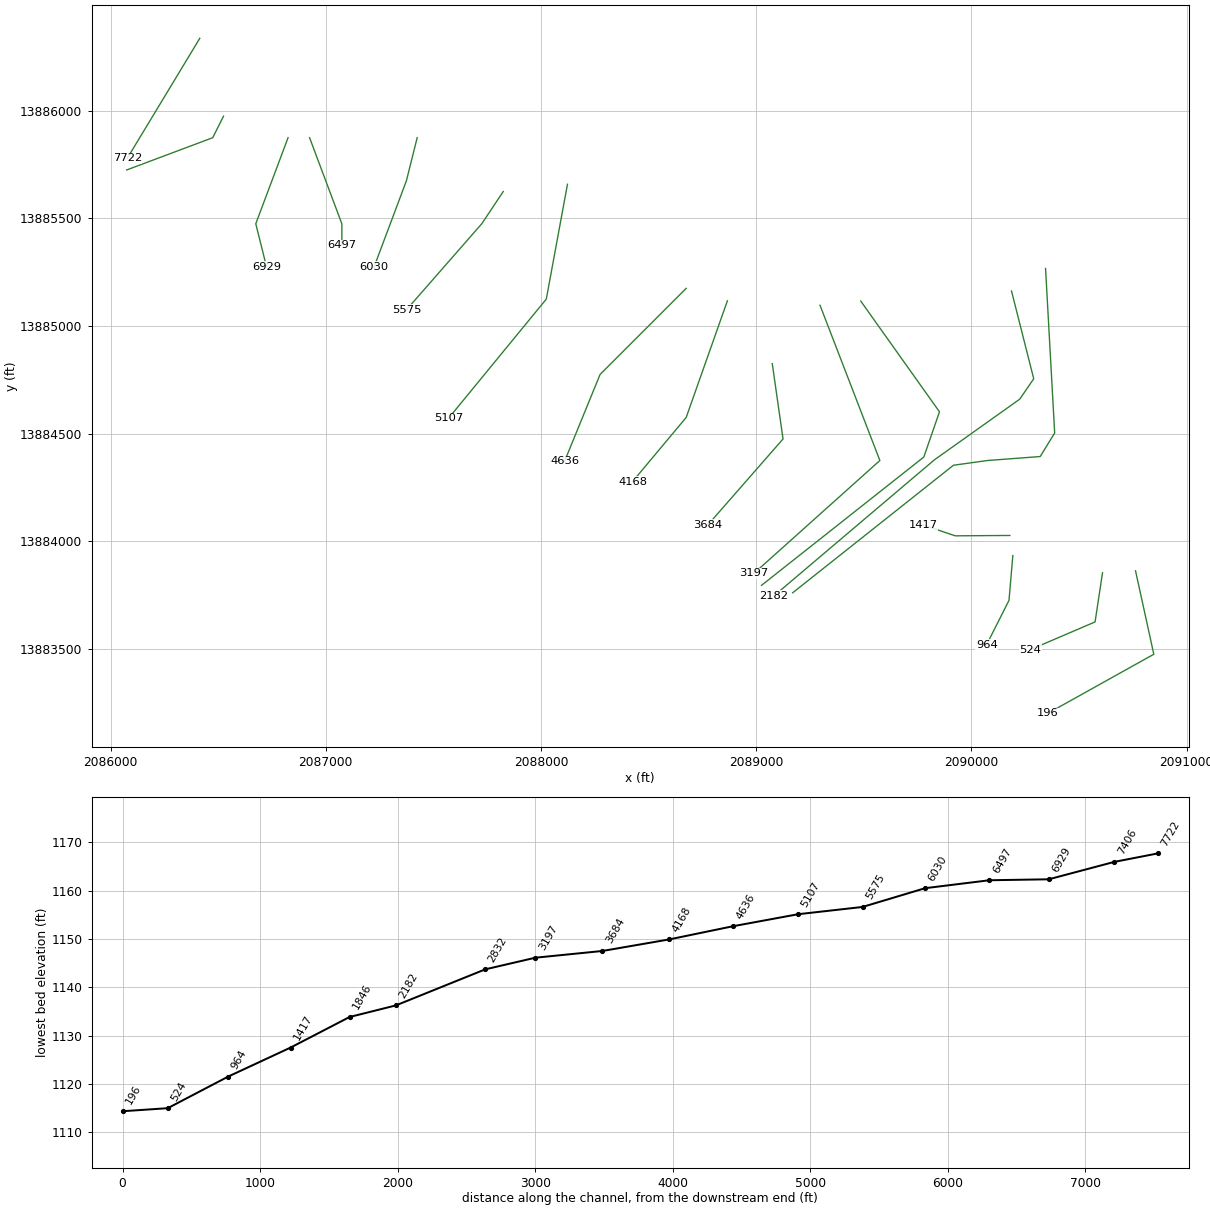
HEC-RAS study GOSS CREEK.prj: GOSS CREEK Base Level Engineering

--- GOSS CREEK.g01 (geometry) --- (continued)

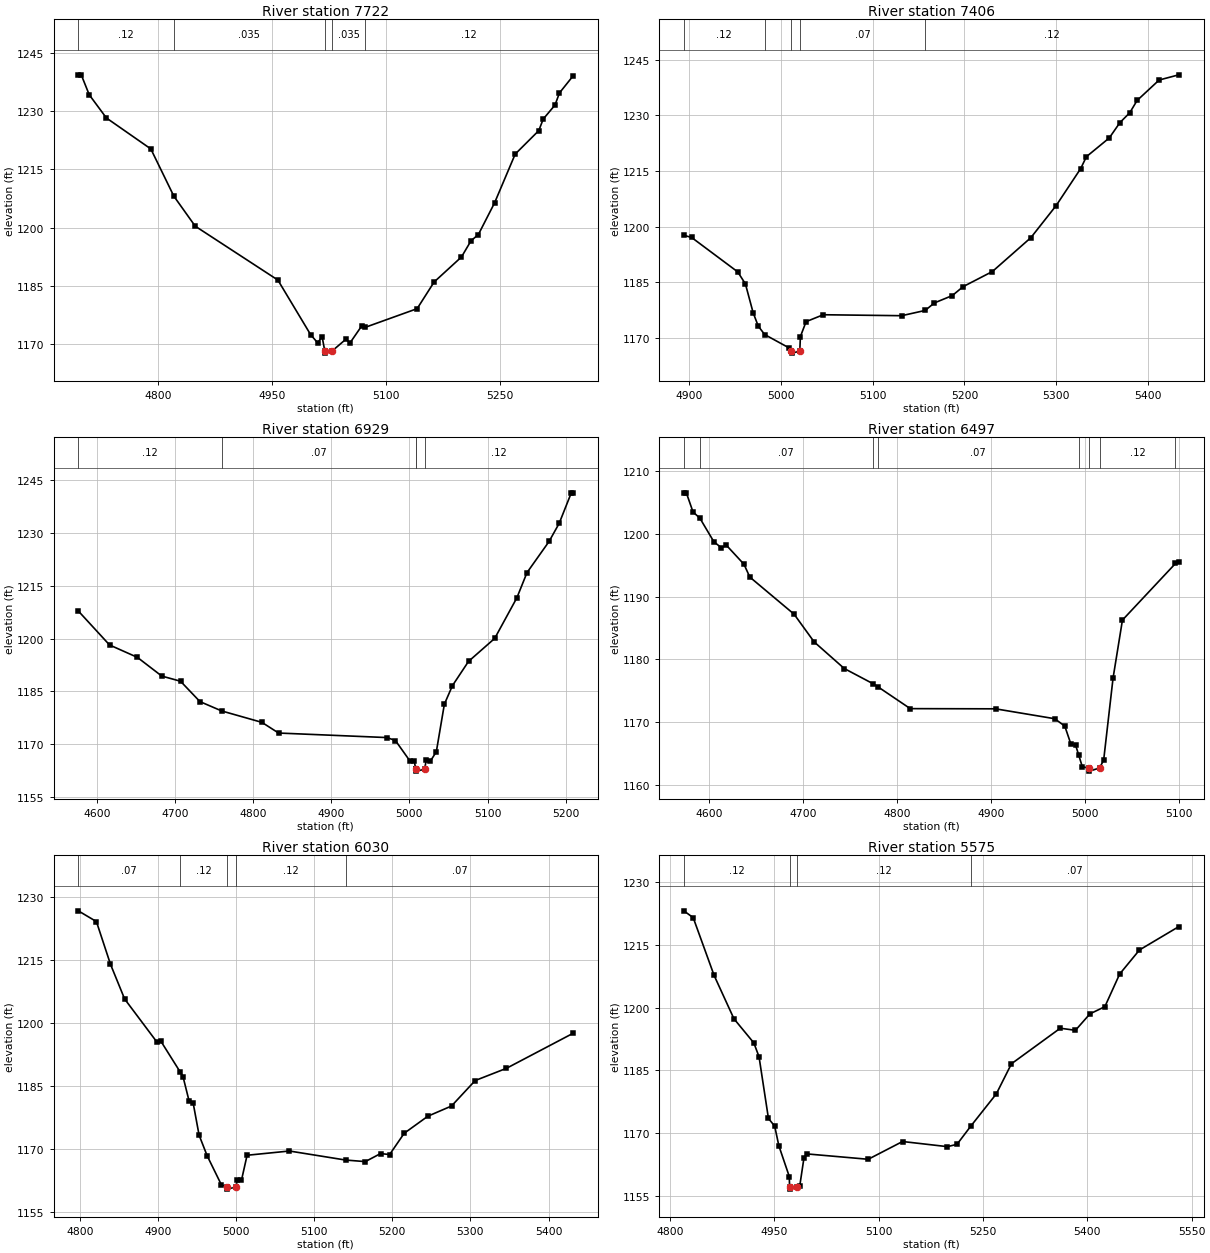
Type RM Length L Ch R = 1,7722,316,316,316
BEGIN DESCRIPTION:
GOSS CREEK 17.0
END DESCRIPTION:
XS GIS Cut Line= 2
      2086414.80     13886336.70      2086077.77     13885779.15
#Sta/Elev= 30
  4694.5 1239.30  4698.4 1239.30  4708.9 1234.17  4731.5 1228.20  4790.0 1220.23
  4820.3 1208.07  4848.4 1200.36  4957.2 1186.49  5000.3 1172.45  5009.6 1170.33
  5015.4 1171.94  5019.0 1168.19  5019.5 1167.69  5028.3 1168.19  5046.5 1171.23
  5052.3 1170.36  5067.8 1174.76  5072.5 1174.35  5140.5 1179.13  5162.9 1186.00
  5198.9 1192.44  5211.4 1196.59  5221.1 1198.20  5242.4 1206.34  5269.6 1218.91
  5300.6 1224.94  5306.5 1227.93  5322.0 1231.53  5327.8 1234.63  5346.0 1239.08
#Mann=5,-1,0
  4694.5    0.12       0  4820.3   0.035       0  5019.0   0.035       0
  5028.3   0.035       0  5072.5    0.12       0
Bank Sta=5019,5028.3
Exp/Cntr=0.3,0.1

Type RM Length L Ch R = 1,7406,477,477,477
BEGIN DESCRIPTION:
GOSS CREEK 16.0
END DESCRIPTION:
XS GIS Cut Line= 3
      2086525.02     13885975.04      2086475.00     13885875.00
      2086074.95     13885724.98
#Sta/Elev= 30
  4894.3 1197.67  4902.7 1197.11  4953.0 1187.83  4961.4 1184.59  4969.8 1176.83
  4975.4 1173.21  4982.4 1170.94  5008.8 1167.37  5011.3 1166.44  5011.8 1165.94
  5020.6 1166.44  5021.3 1170.41  5027.5 1174.42  5046.2 1176.28  5131.6 1176.02
  5157.2 1177.44  5167.2 1179.46  5186.8 1181.45  5198.4 1183.83  5230.4 1187.92
  5272.3 1197.04  5299.9 1205.70  5326.6 1215.66  5332.8 1218.85  5357.7 1223.90
  5369.3 1228.03  5380.0 1230.68  5388.0 1233.99  5412.0 1239.50  5433.4 1240.90
#Mann=5,-1,0
  4894.3    0.12       0  4982.4    0.07       0  5011.3    0.05       0
  5020.6    0.07       0  5157.2    0.12       0
Bank Sta=5011.3,5020.6
Exp/Cntr=0.3,0.1

Type RM Length L Ch R = 1,6929,432,432,432
BEGIN DESCRIPTION:
GOSS CREEK 15.0
END DESCRIPTION:
XS GIS Cut Line= 3
      2086824.99     13885874.98      2086675.00     13885475.00
      2086724.99     13885275.03
#Sta/Elev= 30
  4576.4 1207.88  4616.4 1198.21  4652.0 1194.69  4683.2 1189.37  4707.2 1187.90
  4732.1 1182.10  4759.9 1179.45  4811.3 1176.21  4832.7 1173.17  4971.5 1171.88
  4982.2 1171.03  5000.9 1165.18  5006.2 1165.18  5008.2 1162.95  5008.3 1162.84
  5008.8 1162.34  5019.5 1162.84  5021.6 1165.49  5026.8 1165.15  5034.5 1167.84
  5044.8 1181.38  5055.1 1186.64  5075.7 1193.54  5109.2 1200.08  5137.6 1211.64
  5150.5 1218.78  5178.8 1227.66  5191.7 1232.80  5207.2 1241.47  5209.7 1241.47
#Mann=5,-1,0
  4576.4    0.12       0  4759.9    0.07       0  5008.2    0.12       0
  5008.3    0.05       0  5019.5    0.12       0
Bank Sta=5008.3,5019.5
Exp/Cntr=0.3,0.1

Type RM Length L Ch R = 1,6497,467,467,467
BEGIN DESCRIPTION:
GOSS CREEK 14.0
END DESCRIPTION:
XS GIS Cut Line= 3
      2086925.00     13885874.99      2087075.00     13885475.00
      2087075.00     13885374.99
#Sta/Elev= 30
  4572.8 1206.54  4575.5 1206.54  4582.6 1203.49  4589.9 1202.50  4604.8 1198.74
  4612.8 1197.77  4618.2 1198.17  4636.9 1195.14  4643.1 1193.10  4690.3 1187.17
  4711.6 1182.76  4743.7 1178.51  4773.9 1176.12  4779.2 1175.63  4814.0 1172.11
  4904.8 1172.08  4967.9 1170.50  4978.6 1169.32  4984.9 1166.54  4990.2 1166.25
  4993.5 1164.66  4997.3 1162.82  5004.4 1162.64  5004.9 1162.14  5015.6 1162.64
  5020.0 1163.90  5030.0 1176.98  5040.0 1186.24  5096.5 1195.27  5100.0 1195.47
#Mann=8,-1,0
  4572.8    0.12       0  4589.9    0.07       0  4773.9   0.035       0
  4779.2    0.07       0  4993.5    0.12       0  5004.4    0.05       0
  5015.6    0.12       0  5096.5    0.07       0
Bank Sta=5004.4,5015.6
Exp/Cntr=0.3,0.1

Type RM Length L Ch R = 1,6030,455,455,455
BEGIN DESCRIPTION:
GOSS CREEK 13.0
END DESCRIPTION:
XS GIS Cut Line= 3
      2087425.00     13885875.01      2087375.00     13885675.00
      2087224.99     13885274.97
#Sta/Elev= 30
  4798.2 1226.73  4821.4 1224.17  4839.4 1214.01  4857.5 1205.75  4898.7 1195.53
  4903.9 1195.70  4928.7 1188.35  4932.2 1187.28  4939.9 1181.54  4945.1 1181.09
  4952.8 1173.34  4963.1 1168.44  4981.2 1161.57  4988.4 1161.00  4988.9 1160.50
  4999.7 1161.00  5001.8 1162.59  5007.0 1162.59  5014.2 1168.56  5068.4 1169.57
  5140.3 1167.42  5165.5 1167.05  5185.0 1168.96  5196.6 1168.73  5215.3 1173.80
  5245.6 1177.86  5275.8 1180.28  5306.1 1186.34  5346.1 1189.25  5431.6 1197.61
#Mann=5,-1,0
  4798.2    0.07       0  4928.7    0.12       0  4988.4    0.05       0
  4999.7    0.12       0  5140.3    0.07       0
Bank Sta=4988.4,4999.7
Exp/Cntr=0.3,0.1

Type RM Length L Ch R = 1,5575,468,468,468
BEGIN DESCRIPTION:
GOSS CREEK 12.0
END DESCRIPTION:
XS GIS Cut Line= 3
      2087825.00     13885625.00      2087725.00     13885475.00
      2087374.99     13885074.99
#Sta/Elev= 30
  4819.7 1223.19  4833.2 1221.56  4863.3 1207.73  4891.8 1197.37  4920.4 1191.60
  4927.9 1188.27  4941.4 1173.53  4950.4 1171.68  4956.4 1166.98  4971.4 1159.63
  4971.8 1157.12  4972.3 1156.62  4983.1 1157.12  4986.5 1157.45  4992.5 1164.10
  4997.0 1165.04  5084.9 1163.76  5134.3 1168.01  5198.8 1166.78  5212.6 1167.34
  5232.6 1171.73  5269.1 1179.40  5290.9 1186.61  5361.1 1195.11  5382.9 1194.61
  5403.8 1198.55  5425.2 1200.26  5446.5 1208.07  5475.0 1213.83  5531.5 1219.41
#Mann=4,-1,0
  4819.7    0.12       0  4971.8    0.05       0  4983.1    0.12       0
  5232.6    0.07       0
Bank Sta=4971.8,4983.1
Exp/Cntr=0.3,0.1

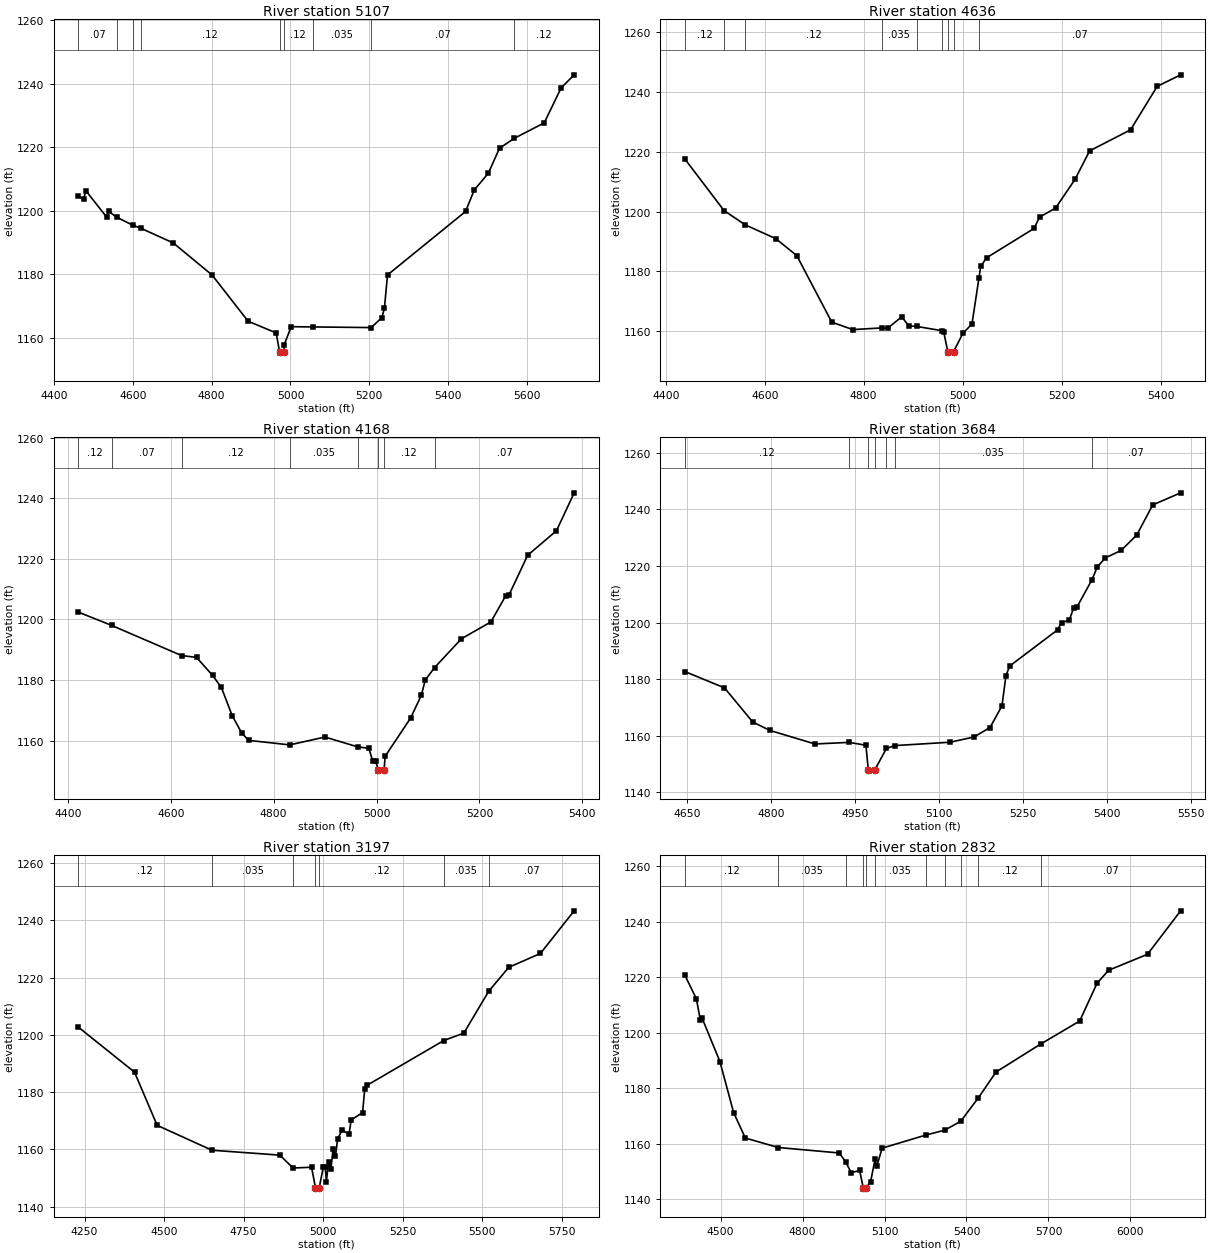
Type RM Length L Ch R = 1,5107,471,471,471
BEGIN DESCRIPTION:
GOSS CREEK 11.0
END DESCRIPTION:
XS GIS Cut Line= 3
      2088123.36     13885658.65      2088025.00     13885125.00
      2087571.26     13884571.83
#Sta/Elev= 30
  4461.8 1204.60  4475.5 1203.57  4480.5 1206.34  4533.6 1197.98  4538.6 1199.79
  4559.2 1197.93  4600.7 1195.36  4619.6 1194.50  4702.7 1189.82  4801.1 1179.73
  4892.6 1165.17  4963.8 1161.48  4972.3 1155.62  4972.8 1155.12  4983.6 1155.62
  4984.1 1157.72  5001.9 1163.45  5056.1 1163.37  5204.6 1163.17  5231.9 1166.28
  5238.4 1169.21  5246.3 1179.74  5444.4 1199.75  5466.6 1206.55  5501.8 1211.72
  5530.5 1219.66  5568.3 1222.81  5643.9 1227.63  5686.9 1238.67  5719.9 1242.78
#Mann=9,-1,0
  4461.8    0.07       0  4559.2    0.12       0  4600.7    0.07       0
  4619.6    0.12       0  4972.3    0.05       0  4983.6    0.12       0
  5056.1   0.035       0  5204.6    0.07       0  5568.3    0.12       0
Bank Sta=4972.3,4983.6
Exp/Cntr=0.3,0.1

Type RM Length L Ch R = 1,4636,468,468,468
BEGIN DESCRIPTION:
GOSS CREEK 10.0
END DESCRIPTION:
XS GIS Cut Line= 3
      2088675.01     13885175.01      2088275.00     13884775.00
      2088109.73     13884371.10
#Sta/Elev= 30
  4438.5 1217.59  4517.7 1200.34  4560.5 1195.55  4622.4 1190.93  4664.8 1185.26
  4735.5 1163.02  4777.9 1160.52  4836.6 1161.08  4848.6 1160.99  4876.9 1164.80
  4891.1 1161.75  4906.9 1161.58  4958.4 1160.15  4961.8 1159.72  4970.1 1153.15
  4970.6 1152.65  4981.8 1153.15  5000.7 1159.32  5018.9 1162.37  5033.0 1177.77
  5036.6 1181.63  5048.3 1184.53  5144.3 1194.33  5155.5 1198.12  5187.9 1201.17
  5227.2 1210.76  5256.6 1220.27  5339.4 1227.32  5393.2 1241.85  5440.6 1245.71
#Mann=9,-1,0
  4438.5    0.12       0  4517.7    0.07       0  4560.5    0.12       0
  4836.6   0.035       0  4906.9    0.07       0  4958.4    0.12       0
  4970.1    0.05       0  4981.8    0.12       0  5033.0    0.07       0
Bank Sta=4970.1,4981.8
Exp/Cntr=0.3,0.1

Type RM Length L Ch R = 1,4168,484,484,484
BEGIN DESCRIPTION:
GOSS CREEK 9.0
END DESCRIPTION:
XS GIS Cut Line= 3
      2088866.43     13885117.04      2088675.00     13884575.00
      2088425.42     13884276.69
#Sta/Elev= 30
  4420.3 1202.42  4485.0 1198.03  4621.0 1188.07  4650.1 1187.47  4681.1 1181.54
  4698.2 1177.60  4719.4 1168.21  4737.6 1162.58  4751.2 1160.06  4831.2 1158.57
  4899.7 1161.16  4963.3 1157.91  4985.0 1157.44  4992.5 1153.22  4998.4 1153.22
  5003.0 1150.40  5003.5 1149.90  5014.7 1150.40  5016.6 1154.79  5066.1 1167.40
  5086.9 1174.92  5094.7 1179.98  5112.8 1184.11  5165.0 1193.62  5222.2 1199.18
  5250.8 1207.73  5257.4 1208.07  5293.8 1221.22  5349.7 1229.29  5384.1 1241.82
#Mann=8,-1,0
  4420.3    0.12       0  4485.0    0.07       0  4621.0    0.12       0
  4831.2   0.035       0  4963.3    0.12       0  5003.0    0.05       0
  5014.7    0.12       0  5112.8    0.07       0
Bank Sta=5003,5014.7
Exp/Cntr=0.3,0.1

Type RM Length L Ch R = 1,3684,487,487,487
BEGIN DESCRIPTION:
GOSS CREEK 8.0
END DESCRIPTION:
XS GIS Cut Line= 3
      2089074.99     13884825.05      2089125.00     13884475.00
      2088775.01     13884075.01
#Sta/Elev= 30
  4646.4 1182.69  4717.2 1176.93  4767.7 1164.86  4798.0 1161.91  4878.8 1157.11
  4939.7 1157.67  4969.7 1156.67  4973.9 1148.02  4974.4 1147.52  4985.7 1148.02
  5006.4 1155.55  5021.5 1156.54  5120.1 1157.73  5162.8 1159.58  5191.2 1162.92
  5212.6 1170.57  5219.7 1181.28  5226.4 1184.65  5311.8 1197.40  5318.9 1199.98
  5332.7 1200.80  5340.3 1205.08  5346.9 1205.63  5373.0 1215.01  5383.0 1219.72
  5397.2 1222.85  5425.2 1225.44  5453.2 1230.91  5481.7 1241.53  5531.5 1245.80
#Mann=7,-1,0
  4646.4    0.12       0  4939.7   0.035       0  4973.9   0.035       0
  4985.7   0.035       0  5006.4    0.12       0  5021.5   0.035       0
  5373.0    0.07       0
Bank Sta=4973.9,4985.7
Exp/Cntr=0.3,0.1

Type RM Length L Ch R = 1,3197,365,365,365
BEGIN DESCRIPTION:
GOSS CREEK 7.0
END DESCRIPTION:
XS GIS Cut Line= 3
      2089296.96     13885096.18      2089575.00     13884375.00
      2088989.59     13883850.39
#Sta/Elev= 30
  4230.6 1202.69  4407.3 1186.96  4478.4 1168.40  4650.7 1159.71  4864.2 1158.00
  4905.7 1153.50  4963.9 1153.77  4976.2 1146.63  4976.7 1146.13  4988.0 1146.63
  5000.8 1153.80  5006.9 1153.80  5010.6 1148.79  5017.3 1155.75  5024.8 1153.26
  5031.5 1160.05  5039.0 1157.52  5045.8 1163.58  5060.0 1166.80  5081.7 1165.28
  5088.4 1170.25  5124.3 1172.87  5131.0 1180.93  5137.8 1182.34  5379.7 1198.00
  5442.7 1200.60  5521.4 1215.28  5584.0 1223.56  5683.5 1228.39  5789.6 1243.28
#Mann=7,-1,0
  4230.6    0.12       0  4650.7   0.035       0  4905.7    0.12       0
  4976.2    0.05       0  4988.0    0.12       0  5379.7   0.035       0
  5521.4    0.07       0
Bank Sta=4976.2,4988
Exp/Cntr=0.3,0.1

Type RM Length L Ch R = 1,2832,650,650,650
BEGIN DESCRIPTION:
GOSS CREEK 6.0
END DESCRIPTION:
XS GIS Cut Line= 4
      2089486.23     13885115.62      2089851.95     13884601.30
      2089779.17     13884391.10      2089025.04     13883794.87
#Sta/Elev= 30
  4368.9 1220.74  4411.3 1212.18  4426.0 1204.46  4432.2 1205.24  4497.4 1189.62
  4547.8 1171.19  4590.5 1162.10  4711.1 1158.69  4934.1 1156.73  4957.2 1153.64
  4978.2 1149.61  5009.0 1150.45  5021.9 1144.22  5022.4 1143.72  5033.7 1144.22
  5049.0 1146.39  5065.4 1154.49  5071.3 1151.88  5091.3 1158.46  5250.8 1163.16
  5321.0 1164.96  5379.0 1168.15  5443.6 1176.59  5508.1 1185.85  5670.9 1195.88
  5814.2 1204.19  5877.9 1217.78  5920.0 1222.45  6062.7 1228.22  6183.8 1243.84
#Mann=11,-1,0
  4368.9    0.12       0  4711.1   0.035       0  4957.2    0.07       0
  5021.9    0.05       0  5033.7    0.07       0  5065.4   0.035       0
  5250.8    0.07       0  5321.0    0.12       0  5379.0    0.07       0
  5443.6    0.12       0  5670.9    0.07       0
Bank Sta=5021.9,5033.7
Exp/Cntr=0.3,0.1

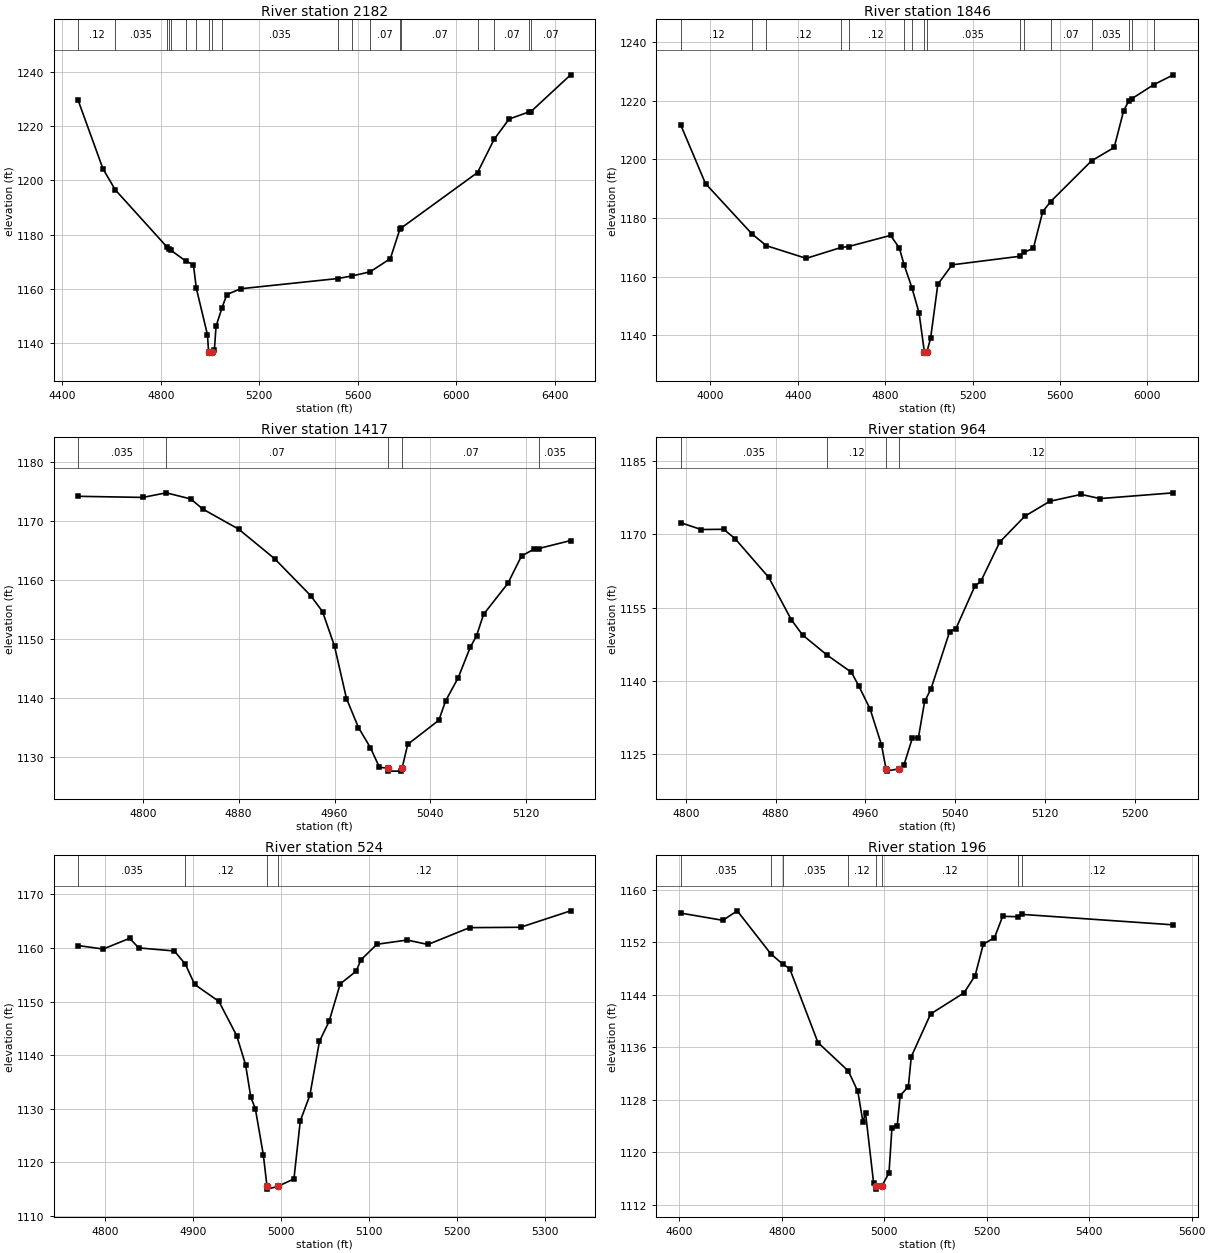
Type RM Length L Ch R = 1,2182,336,336,336
BEGIN DESCRIPTION:
GOSS CREEK 5.0
END DESCRIPTION:
XS GIS Cut Line= 5
      2090186.68     13885162.59      2090289.88     13884754.81
      2090224.82     13884659.91      2089828.64     13884378.31
      2089082.47     13883745.71
#Sta/Elev= 30
  4464.3 1229.56  4565.0 1204.31  4614.9 1196.56  4825.4 1175.40  4833.2 1174.87
  4839.4 1174.32  4901.5 1170.25  4932.5 1168.87  4944.2 1160.18  4989.3 1143.09
  4994.0 1136.76  4994.5 1136.26  5005.9 1136.76  5017.6 1137.50  5024.3 1146.18
  5048.5 1152.98  5068.1 1157.90  5124.6 1160.03  5519.1 1163.80  5577.3 1164.77
  5649.9 1166.27  5732.1 1171.14  5770.7 1181.95  5775.9 1182.43  6086.4 1202.94
  6153.6 1215.18  6214.3 1222.66  6293.5 1225.26  6303.2 1225.43  6464.3 1239.00
#Mann=19,-1,0
  4464.3    0.12       0  4614.9   0.035       0  4825.4    0.12       0
  4833.2   0.035       0  4839.4    0.12       0  4901.5   0.035       0
  4944.2    0.12       0  4994.0    0.05       0  5005.9    0.12       0
  5048.5   0.035       0  5519.1    0.07       0  5577.3   0.035       0
  5649.9    0.07       0  5770.7    0.12       0  5775.9    0.07       0
  6086.4   0.035       0  6153.6    0.07       0  6293.5   0.035       0
  6303.2    0.07       0
Bank Sta=4994,5005.9
Exp/Cntr=0.3,0.1

Type RM Length L Ch R = 1,1846,429,429,429
BEGIN DESCRIPTION:
GOSS CREEK 4.0
END DESCRIPTION:
XS GIS Cut Line= 6
      2090344.84     13885267.34      2090387.20     13884502.99
      2090320.07     13884393.47      2090075.00     13884375.00
      2089916.92     13884352.99      2089169.71     13883760.27
#Sta/Elev= 30
  3865.5 1211.56  3978.0 1191.71  4190.7 1174.53  4256.3 1170.53  4438.7 1166.20
  4598.1 1169.91  4632.5 1170.23  4824.7 1174.03  4864.8 1169.73  4887.0 1163.93
  4922.4 1156.17  4955.1 1147.59  4979.2 1134.37  4979.7 1133.87  4991.1 1134.37
  5007.8 1138.90  5041.0 1157.36  5106.2 1163.99  5414.9 1166.90  5433.7 1168.25
  5477.7 1169.57  5521.0 1182.15  5556.5 1185.52  5744.2 1199.47  5847.8 1204.02
  5891.1 1216.55  5915.4 1220.03  5929.1 1220.69  6027.9 1225.41  6118.6 1228.81
#Mann=16,-1,0
  3865.5    0.12       0  4190.7   0.035       0  4256.3    0.12       0
  4598.1    0.07       0  4632.5    0.12       0  4887.0    0.07       0
  4922.4   0.035       0  4979.2   0.035       0  4991.1   0.035       0
  5414.9    0.07       0  5433.7    0.12       0  5556.5    0.07       0
  5744.2   0.035       0  5915.4    0.07       0  5929.1   0.035       0
  6027.9    0.07       0
Bank Sta=4979.2,4991.1
Exp/Cntr=0.3,0.1

Type RM Length L Ch R = 1,1417,453,453,453
BEGIN DESCRIPTION:
GOSS CREEK 3.0
END DESCRIPTION:
XS GIS Cut Line= 3
      2090178.96     13884026.72      2089925.00     13884025.00
      2089776.14     13884075.33
#Sta/Elev= 30
  4746.0 1174.20  4800.0 1174.01  4819.5 1174.79  4840.0 1173.75  4850.0 1172.04
  4880.0 1168.62  4910.0 1163.61  4940.0 1157.36  4950.0 1154.63  4960.0 1148.76
  4970.0 1139.86  4980.0 1134.95  4990.0 1131.52  4997.5 1128.20  5004.5 1128.05
  5005.0 1127.55  5015.9 1127.55  5016.4 1128.05  5021.1 1132.09  5047.1 1136.19
  5052.7 1139.45  5063.3 1143.42  5073.3 1148.57  5078.6 1150.53  5084.4 1154.15
  5104.7 1159.42  5116.1 1164.06  5126.6 1165.24  5130.4 1165.33  5157.1 1166.69
#Mann=5,-1,0
  4746.0   0.035       0  4819.5    0.07       0  5004.5    0.05       0
  5016.4    0.07       0  5130.4   0.035       0
Bank Sta=5004.5,5016.4
Exp/Cntr=0.3,0.1

Type RM Length L Ch R = 1,964,440,440,440
BEGIN DESCRIPTION:
GOSS CREEK 2.0
END DESCRIPTION:
XS GIS Cut Line= 3
      2090192.80     13883932.93      2090175.00     13883725.00
      2090071.34     13883519.90
#Sta/Elev= 30
  4795.7 1172.35  4813.7 1170.97  4833.8 1171.01  4843.8 1169.13  4873.9 1161.17
  4894.0 1152.52  4904.0 1149.41  4926.0 1145.26  4947.5 1141.78  4954.2 1138.93
  4964.2 1134.24  4974.3 1126.93  4978.3 1122.06  4978.8 1121.56  4990.3 1122.06
  4994.4 1122.89  5001.9 1128.41  5007.2 1128.41  5012.7 1135.81  5018.3 1138.33
  5035.0 1150.08  5040.6 1150.71  5057.3 1159.32  5062.9 1160.43  5079.6 1168.40
  5101.9 1173.68  5124.2 1176.74  5152.1 1178.15  5168.8 1177.29  5234.2 1178.47
#Mann=4,-1,0
  4795.7   0.035       0  4926.0    0.12       0  4978.3    0.05       0
  4990.3    0.12       0
Bank Sta=4978.3,4990.3
Exp/Cntr=0.3,0.1

Type RM Length L Ch R = 1,524,328,328,328
BEGIN DESCRIPTION:
GOSS CREEK 1.0
END DESCRIPTION:
XS GIS Cut Line= 3
      2090609.47     13883853.08      2090575.00     13883625.00
      2090272.65     13883495.46
#Sta/Elev= 30
  4769.1 1160.47  4797.5 1159.82  4827.6 1161.82  4838.0 1160.03  4878.4 1159.46
  4891.0 1156.97  4901.5 1153.21  4929.0 1150.05  4949.2 1143.67  4959.3 1138.27
  4965.3 1132.17  4970.4 1130.06  4979.5 1121.44  4983.7 1115.52  4984.2 1115.02
  4995.7 1115.52  5014.3 1116.92  5021.5 1127.75  5032.4 1132.54  5043.3 1142.61
  5054.2 1146.30  5066.9 1153.32  5085.0 1155.69  5090.4 1157.80  5108.6 1160.71
  5143.0 1161.50  5166.6 1160.67  5213.8 1163.81  5271.8 1163.88  5328.7 1166.95
#Mann=4,-1,0
  4769.1   0.035       0  4891.0    0.12       0  4983.7    0.05       0
  4995.7    0.12       0
Bank Sta=4983.7,4995.7
Exp/Cntr=0.3,0.1

Type RM Length L Ch R = 1,196,0,0,0
BEGIN DESCRIPTION:
GOSS CREEK 0.0
END DESCRIPTION:
XS GIS Cut Line= 3
      2090762.96     13883862.32      2090847.88     13883474.71
      2090354.97     13883199.99
#Sta/Elev= 30
  4603.2 1156.48  4685.1 1155.38  4713.1 1156.83  4778.9 1150.25  4801.5 1148.73
  4815.4 1148.03  4870.7 1136.74  4929.9 1132.41  4948.5 1129.28  4958.4 1124.65
  4963.5 1126.00  4979.2 1115.38  4983.5 1114.89  4984.0 1114.39  4995.5 1114.89
  5009.3 1116.85  5015.1 1123.78  5025.3 1124.01  5031.1 1128.64  5047.1 1130.04
  5052.8 1134.59  5090.5 1141.10  5155.7 1144.32  5177.4 1146.95  5193.4 1151.75
  5215.1 1152.72  5231.1 1155.99  5261.8 1155.93  5268.6 1156.29  5564.3 1154.69
#Mann=8,-1,0
  4603.2   0.035       0  4778.9    0.07       0  4801.5   0.035       0
  4929.9    0.12       0  4983.5    0.05       0  4995.5    0.12       0
  5261.8   0.035       0  5268.6    0.12       0
Bank Sta=4983.5,4995.5
Exp/Cntr=0.3,0.1

Chan Stop Cuts=-1