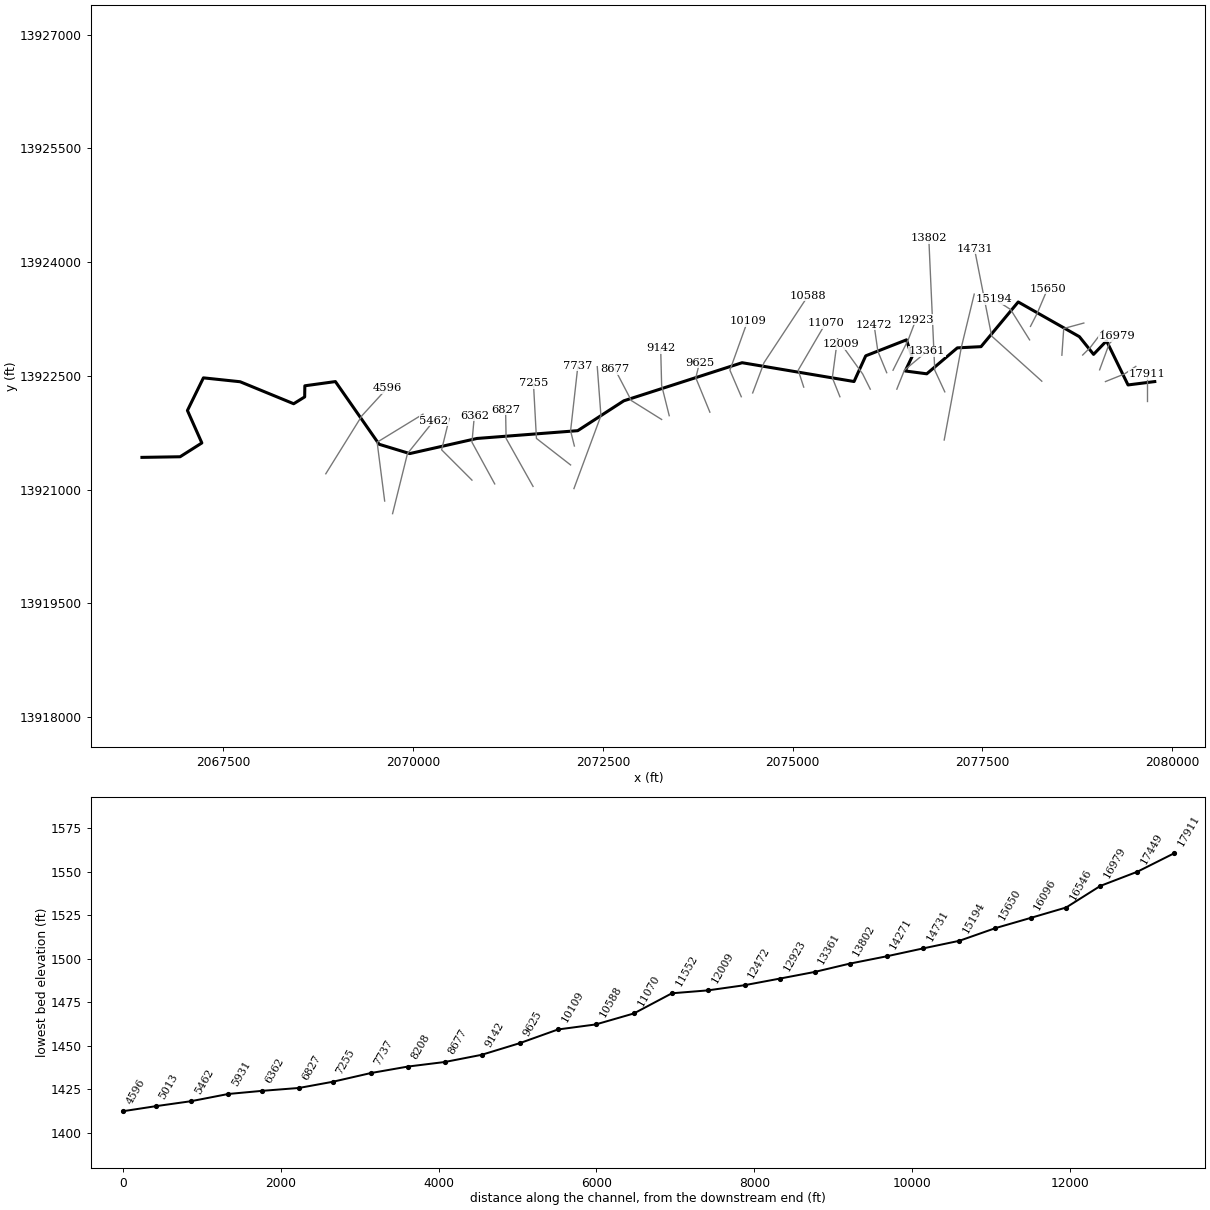
--- HAAG CREEK.prj (project) ---

Proj Title=HAAG CREEK Base Level Engineering
Current Plan=p01
Default Exp/Contr=0.3,0.1
English Units
Geom File=g01
Flow File=f01
Plan File=p01
Y Axis Title=Elevation
X Axis Title(PF)=Main Channel Distance
X Axis Title(XS)=Station
BEGIN DESCRIPTION:
HAAG CREEK
END DESCRIPTION:
DSS Export Rating Curves= 0
DSS Export Rating Curve Sorted= 0
DSS Export Volume Flow Curves= 0
DXF OffsetX= 0
DXF OffsetY= 0
DXF ScaleX= 1
DXF ScaleY= 10

--- HAAG CREEK.p01 (plan) ---

Plan Title=Multiple Run
Short Identifier=Multiple
Geom File=g01
Flow File=f01
Subcritical Flow
K Sum by GR= 0
Std Step Tol= 0.01
Critical Tol= 0.01
Num of Std Step Trials= 20
Max Error Tol= 0.3
Flow Tol Ratio= 0.001
Split Flow NTrial= 30
Split Flow Tol= 0.02
Split Flow Ratio= 0.02
Log Output Level= 0
Friction Slope Method= 1
Unsteady Friction Slope Method= 2
Unsteady Bridges Friction Slope Method= 1
Parabolic Critical Depth
Global Vel Dist=  1 , 1 , 1
Global Log Level= 0
CheckData=True
Encroach Param= -1, 0, 0, 0
BEGIN DESCRIPTION:
Multiple Run
END DESCRIPTION:

--- HAAG CREEK.f01 (steady flow) ---

Flow Title=Multiple
Program Version=4.10
Number of Profiles= 7
Profile Names=10-year,25-year,50-year,1pct_min,100-year,1pct_plu,500-year
River Rch & RM=HAAG CREEK,Reach-1         ,17911
    1091    1885    2659    1823    3638    7258    6742
River Rch & RM=HAAG CREEK,Reach-1         ,15650
    2179    3881    5579    3884    7750   15463   14835
River Rch & RM=HAAG CREEK,Reach-1         ,15194
    2472    4412    6354    4427    8833   17625   16940
River Rch & RM=HAAG CREEK,Reach-1         ,10588
    2779    4989    7209    5040   10055   20063   19410
River Rch & RM=HAAG CREEK,Reach-1         ,9142
    3729    6781    9886    6965   13898   27729   27256
River Rch & RM=HAAG CREEK,Reach-1         ,8208
    3949    7179   10462    7366   14697   29325   28784
River Rch & RM=HAAG CREEK,Reach-1         ,3677
    4065    7384   10757    7568   15101   30130   29536
Boundary for River Rch & Prof#=HAAG CREEK,Reach-1         , 1
Up Type= 0
Dn Type= 3
Dn Slope=0.005
Boundary for River Rch & Prof#=HAAG CREEK,Reach-1         , 2
Up Type= 0
Dn Type= 3
Dn Slope=0.005
Boundary for River Rch & Prof#=HAAG CREEK,Reach-1         , 3
Up Type= 0
Dn Type= 3
Dn Slope=0.005
Boundary for River Rch & Prof#=HAAG CREEK,Reach-1         , 4
Up Type= 0
Dn Type= 3
Dn Slope=0.005
Boundary for River Rch & Prof#=HAAG CREEK,Reach-1         , 5
Up Type= 0
Dn Type= 3
Dn Slope=0.005
Boundary for River Rch & Prof#=HAAG CREEK,Reach-1         , 6
Up Type= 0
Dn Type= 3
Dn Slope=0.005
Boundary for River Rch & Prof#=HAAG CREEK,Reach-1         , 7
Up Type= 0
Dn Type= 3
Dn Slope=0.005
DSS Import GetInterval= 0
DSS Import GetPeak= 0
DSS Import FillOption= 0

--- HAAG CREEK.g01 (geometry) ---

Geom Title=Existing Conditions

River Reach=HAAG CREEK,Reach-1
Reach XY= 30
      2079775.00     13922425.00      2079422.52     13922380.45
      2079138.68     13922961.74      2078968.20     13922783.77
      2078781.17     13923017.14      2077975.00     13923475.00
      2077484.80     13922885.48      2077172.55     13922869.54
      2076769.48     13922527.35      2076485.92     13922564.57
      2076575.29     13922752.15      2076502.38     13922975.44
      2075965.17     13922764.48      2075811.15     13922425.53
      2074335.49     13922673.81      2072776.58     13922171.17
      2072169.07     13921777.25      2070840.22     13921674.48
      2069954.96     13921475.05      2069551.16     13921597.85
      2068975.00     13922425.00      2068572.15     13922369.20
      2068569.99     13922222.46      2068425.01     13922132.53
      2067719.07     13922422.76      2067235.43     13922473.97
      2067024.61     13922043.34      2067214.84     13921615.30
      2066928.23     13921433.24      2066425.00     13921425.00

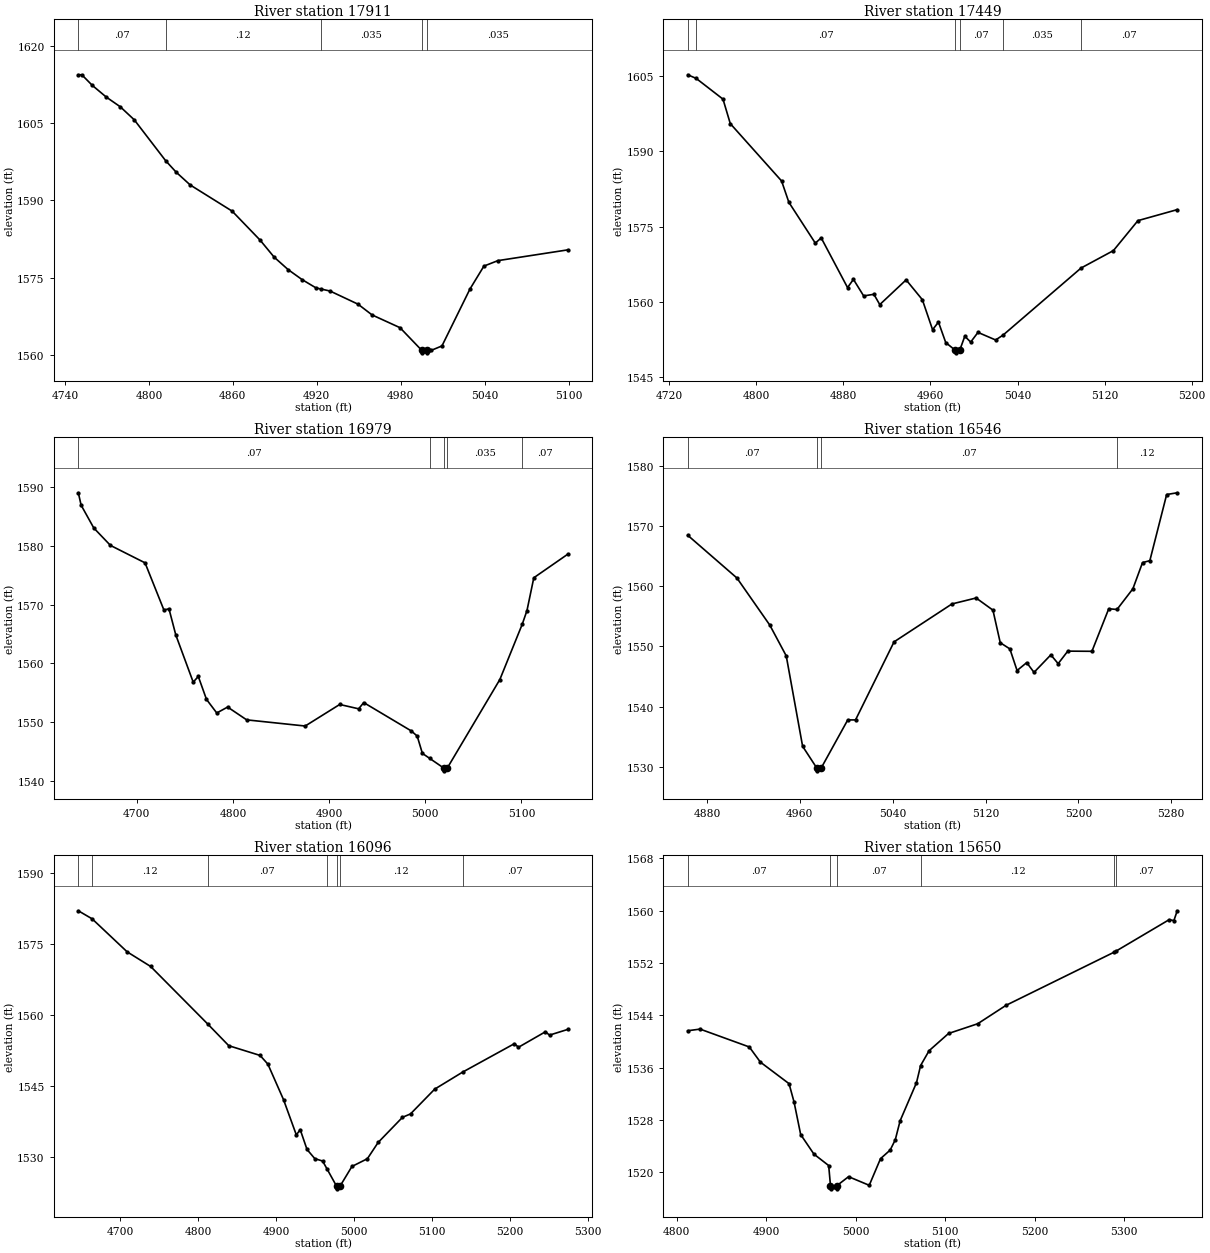
Type RM Length L Ch R = 1,17911,462,462,462
BEGIN DESCRIPTION:
HAAG CREEK 39.0
END DESCRIPTION:
XS GIS Cut Line= 3
      2079675.00     13922174.98      2079675.00     13922425.00
      2079675.00     13922524.98
#Sta/Elev= 30
  4749.5 1614.36  4752.0 1614.36  4759.5 1612.30  4769.5 1610.03  4779.5 1608.15
  4789.5 1605.62  4811.9 1597.70  4819.5 1595.45  4829.5 1592.98  4859.5 1587.90
  4879.5 1582.27  4889.5 1578.98  4899.5 1576.56  4909.5 1574.62  4919.5 1573.00
  4922.9 1572.80  4929.5 1572.40  4949.5 1569.85  4959.5 1567.77  4979.5 1565.29
  4995.0 1560.91  4995.3 1560.41  4998.8 1560.41  4999.0 1560.91  5002.0 1560.91
  5009.5 1561.75  5029.5 1572.78  5039.5 1577.24  5049.5 1578.30  5099.5 1580.39
#Mann=5,-1,0
  4749.5    0.07       0  4811.9    0.12       0  4922.9   0.035       0
  4995.0   0.035       0  4999.0   0.035       0
Bank Sta=4995,4999
Exp/Cntr=0.3,0.1

Type RM Length L Ch R = 1,17449,470,470,470
BEGIN DESCRIPTION:
HAAG CREEK 38.0
END DESCRIPTION:
XS GIS Cut Line= 3
      2079124.96     13922424.98      2079375.00     13922525.00
      2079525.02     13922625.01
#Sta/Elev= 30
  4737.1 1605.24  4744.8 1604.53  4769.5 1600.39  4776.2 1595.52  4823.3 1584.11
  4830.0 1579.86  4854.3 1571.73  4859.7 1572.78  4883.9 1562.89  4889.3 1564.52
  4898.7 1561.23  4908.1 1561.55  4913.5 1559.50  4937.7 1564.42  4952.6 1560.48
  4962.0 1554.50  4967.4 1556.02  4974.1 1551.94  4982.9 1550.40  4983.1 1549.90
  4986.9 1550.40  4991.6 1553.20  4997.0 1552.04  5003.7 1553.97  5019.9 1552.46
  5026.8 1553.44  5098.4 1566.78  5128.1 1570.25  5150.6 1576.21  5186.7 1578.40
#Mann=6,-1,0
  4737.1   0.035       0  4744.8    0.07       0  4982.9    0.05       0
  4986.9    0.07       0  5026.8   0.035       0  5098.4    0.07       0
Bank Sta=4982.9,4986.9
Exp/Cntr=0.3,0.1

Type RM Length L Ch R = 1,16979,433,433,433
BEGIN DESCRIPTION:
HAAG CREEK 37.0
END DESCRIPTION:
XS GIS Cut Line= 3
      2079048.03     13922579.86      2079175.00     13922925.00
      2079275.02     13923025.02
#Sta/Elev= 30
  4639.1 1589.06  4642.0 1586.95  4655.2 1583.06  4672.5 1580.10  4708.5 1577.13
  4728.1 1569.11  4733.4 1569.30  4740.5 1564.85  4758.6 1556.82  4763.9 1557.79
  4772.4 1553.89  4783.1 1551.57  4794.4 1552.58  4814.2 1550.40  4875.1 1549.35
  4911.0 1553.02  4930.7 1552.28  4936.0 1553.34  4985.5 1548.51  4991.6 1547.64
  4997.0 1544.69  5004.7 1543.83  5019.0 1542.22  5019.2 1541.72  5023.0 1542.22
  5077.6 1557.27  5100.9 1566.69  5105.8 1569.01  5112.9 1574.59  5148.3 1578.61
#Mann=5,-1,0
  4639.1    0.07       0  5004.7   0.035       0  5019.0    0.05       0
  5023.0   0.035       0  5100.9    0.07       0
Bank Sta=5019,5023
Exp/Cntr=0.3,0.1

Type RM Length L Ch R = 1,16546,450,450,450
BEGIN DESCRIPTION:
HAAG CREEK 36.0
END DESCRIPTION:
XS GIS Cut Line= 3
      2078825.00     13922775.00      2078925.00     13922875.00
      2079094.89     13923098.05
#Sta/Elev= 30
  4863.4 1568.47  4905.8 1561.37  4934.1 1553.55  4948.3 1548.43  4962.4 1533.41
  4974.5 1529.83  4974.8 1529.33  4978.5 1529.83  5001.3 1537.79  5008.0 1537.79
  5041.2 1550.76  5091.1 1557.06  5111.9 1558.05  5126.4 1556.03  5132.7 1550.62
  5141.0 1549.59  5147.2 1546.00  5155.5 1547.31  5161.8 1545.69  5176.3 1548.60
  5182.6 1547.14  5190.9 1549.22  5211.7 1549.19  5226.2 1556.26  5233.3 1556.14
  5247.0 1559.58  5255.3 1563.93  5261.6 1564.25  5276.1 1575.24  5285.2 1575.53
#Mann=4,-1,0
  4863.4    0.07       0  4974.5    0.05       0  4978.5    0.07       0
  5233.3    0.12       0
Bank Sta=4974.5,4978.5
Exp/Cntr=0.3,0.1

Type RM Length L Ch R = 1,16096,446,446,446
BEGIN DESCRIPTION:
HAAG CREEK 35.0
END DESCRIPTION:
XS GIS Cut Line= 3
      2078550.62     13922772.53      2078575.00     13923125.00
      2078839.67     13923197.01
#Sta/Elev= 30
  4646.4 1581.97  4664.1 1580.27  4709.0 1573.31  4739.1 1570.23  4812.4 1558.08
  4839.3 1553.52  4879.4 1551.47  4889.4 1549.64  4909.5 1542.14  4925.9 1534.71
  4930.9 1535.82  4939.6 1531.64  4949.6 1529.71  4959.6 1529.20  4965.3 1527.52
  4977.7 1523.84  4977.9 1523.34  4981.7 1523.84  4997.2 1528.06  5017.0 1529.69
  5030.8 1533.12  5062.0 1538.42  5072.3 1539.14  5103.3 1544.36  5139.1 1547.95
  5205.5 1553.95  5210.7 1553.19  5245.3 1556.46  5250.5 1555.75  5274.0 1556.96
#Mann=7,-1,0
  4646.4    0.07       0  4664.1    0.12       0  4812.4    0.07       0
  4965.3    0.12       0  4977.7    0.05       0  4981.7    0.12       0
  5139.1    0.07       0
Bank Sta=4977.7,4981.7
Exp/Cntr=0.3,0.1

Type RM Length L Ch R = 1,15650,456,456,456
BEGIN DESCRIPTION:
HAAG CREEK 34.0
END DESCRIPTION:
XS GIS Cut Line= 3
      2078136.55     13923152.74      2078225.00     13923325.00
      2078362.74     13923650.30
#Sta/Elev= 30
  4812.4 1541.65  4826.2 1541.90  4881.2 1539.17  4893.6 1536.85  4925.6 1533.56
  4931.2 1530.76  4938.6 1525.78  4953.4 1522.79  4969.9 1521.04  4971.9 1517.98
  4972.4 1517.48  4978.7 1517.48  4979.2 1517.98  4992.1 1519.34  5015.2 1518.02
  5027.8 1522.09  5038.6 1523.41  5044.3 1524.98  5049.7 1527.88  5068.0 1533.71
  5072.6 1536.33  5082.1 1538.60  5103.8 1541.23  5136.4 1542.72  5168.1 1545.54
  5289.1 1553.68  5290.4 1553.78  5350.2 1558.62  5355.6 1558.50  5359.3 1559.99
#Mann=6,-1,0
  4812.4    0.07       0  4971.9    0.05       0  4979.2    0.07       0
  5072.6    0.12       0  5289.1   0.035       0  5290.4    0.07       0
Bank Sta=4971.9,4979.2
Exp/Cntr=0.3,0.1

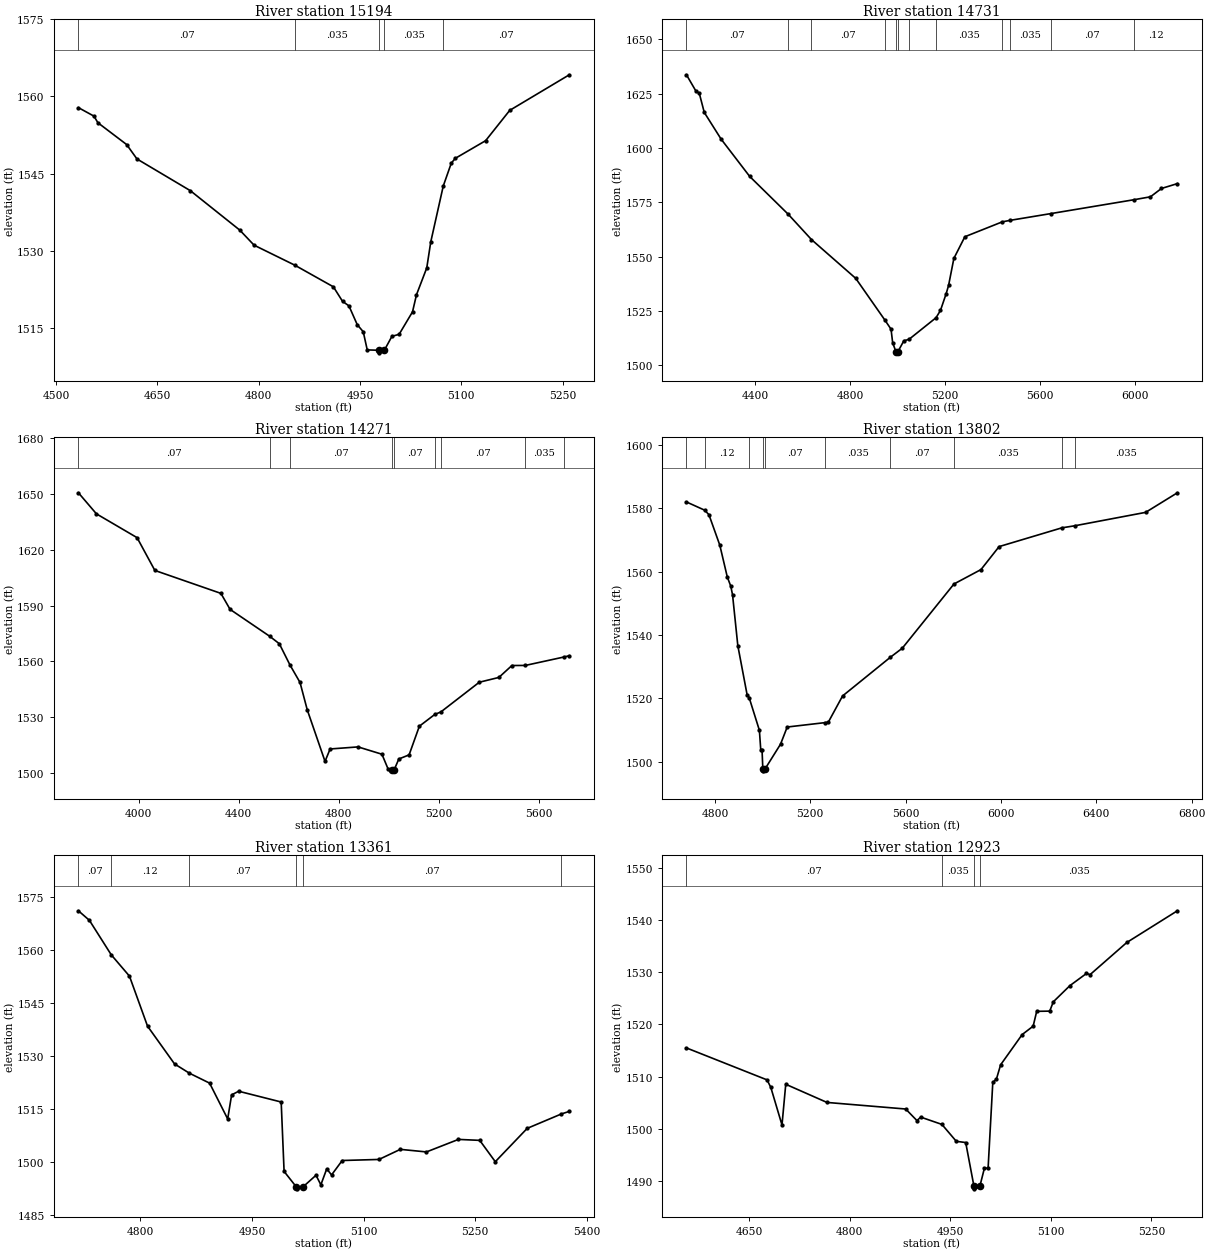
Type RM Length L Ch R = 1,15194,463,463,463
BEGIN DESCRIPTION:
HAAG CREEK 33.0
END DESCRIPTION:
XS GIS Cut Line= 3
      2078125.01     13922974.99      2077875.00     13923375.00
      2077660.94     13923513.37
#Sta/Elev= 30
  4533.3 1557.83  4556.3 1556.18  4562.2 1554.89  4604.7 1550.66  4620.0 1547.86
  4699.0 1541.70  4772.1 1534.05  4793.3 1531.12  4853.5 1527.24  4910.7 1523.03
  4924.2 1520.22  4933.7 1519.33  4946.0 1515.68  4954.9 1514.30  4960.8 1510.78
  4978.0 1510.71  4978.5 1510.21  4986.1 1510.71  4997.3 1513.41  5008.0 1513.81
  5027.8 1518.17  5033.7 1521.50  5048.9 1526.71  5054.8 1531.75  5073.3 1542.60
  5085.2 1547.05  5091.1 1547.98  5136.0 1551.41  5171.7 1557.30  5259.9 1564.21
#Mann=5,-1,0
  4533.3    0.07       0  4853.5   0.035       0  4978.0   0.035       0
  4986.1   0.035       0  5073.3    0.07       0
Bank Sta=4978,4986.1
Exp/Cntr=0.3,0.1

Type RM Length L Ch R = 1,14731,460,460,460
BEGIN DESCRIPTION:
HAAG CREEK 32.0
END DESCRIPTION:
XS GIS Cut Line= 3
      2078285.93     13922430.03      2077625.00     13923025.00
      2077397.89     13924180.01
#Sta/Elev= 30
  4110.7 1633.65  4150.5 1626.17  4164.7 1625.17  4185.7 1616.34  4256.7 1604.05
  4377.0 1586.90  4538.9 1569.54  4637.0 1557.87  4823.2 1540.05  4947.1 1520.68
  4971.9 1516.66  4978.7 1510.42  4992.6 1506.30  4993.1 1505.80  5000.7 1506.30
  5025.7 1511.34  5047.6 1512.01  5161.2 1521.94  5179.9 1525.30  5203.8 1532.97
  5214.0 1536.77  5236.3 1549.21  5282.6 1559.18  5439.9 1566.02  5471.6 1566.69
  5645.4 1569.84  5992.8 1576.17  6063.7 1577.54  6110.0 1581.37  6177.1 1583.61
#Mann=12,-1,0
  4110.7    0.07       0  4538.9    0.12       0  4637.0    0.07       0
  4947.1    0.12       0  4992.6    0.05       0  5000.7    0.12       0
  5047.6    0.07       0  5161.2   0.035       0  5439.9    0.07       0
  5471.6   0.035       0  5645.4    0.07       0  5992.8    0.12       0
Bank Sta=4992.6,5000.7
Exp/Cntr=0.3,0.1

Type RM Length L Ch R = 1,14271,469,469,469
BEGIN DESCRIPTION:
HAAG CREEK 31.0
END DESCRIPTION:
XS GIS Cut Line= 3
      2076999.44     13921654.01      2077225.00     13922875.00
      2077395.29     13923578.54
#Sta/Elev= 30
  3757.9 1650.55  3830.1 1639.24  3992.8 1626.46  4064.0 1608.86  4328.4 1596.55
  4365.2 1587.95  4523.6 1573.53  4562.3 1569.52  4604.9 1558.12  4645.2 1548.73
  4674.1 1534.05  4745.3 1506.35  4765.7 1513.02  4877.5 1514.13  4973.1 1510.20
  4997.0 1502.53  5013.8 1501.78  5014.3 1501.28  5022.0 1501.78  5040.7 1507.64
  5081.9 1509.85  5123.0 1525.25  5185.0 1531.58  5209.0 1532.89  5362.8 1548.84
  5441.3 1551.42  5493.5 1557.82  5547.0 1557.86  5700.7 1562.35  5723.4 1563.07
#Mann=9,-1,0
  3757.9    0.07       0  4523.6    0.12       0  4604.9    0.07       0
  5013.8    0.05       0  5022.0    0.07       0  5185.0    0.12       0
  5209.0    0.07       0  5547.0   0.035       0  5700.7    0.07       0
Bank Sta=5013.8,5022
Exp/Cntr=0.3,0.1

Type RM Length L Ch R = 1,13802,441,441,441
BEGIN DESCRIPTION:
HAAG CREEK 30.0
END DESCRIPTION:
XS GIS Cut Line= 3
      2077007.24     13922289.47      2076875.00     13922575.00
      2076796.32     13924318.06
#Sta/Elev= 30
  4680.7 1582.04  4756.8 1579.45  4775.0 1578.02  4820.7 1568.37  4852.1 1558.31
  4866.6 1555.44  4874.1 1552.69  4896.2 1536.63  4935.3 1521.05  4944.0 1520.14
  4986.7 1509.87  4992.6 1503.53  4997.9 1503.53  5001.2 1497.56  5001.7 1497.06
  5009.6 1497.56  5075.4 1505.48  5103.4 1510.91  5263.4 1512.31  5275.7 1512.42
  5335.7 1520.73  5536.7 1532.99  5586.0 1535.80  5802.9 1556.11  5916.3 1560.67
  5992.3 1567.93  6255.6 1573.86  6309.7 1574.51  6607.0 1578.75  6740.2 1584.94
#Mann=10,-1,0
  4680.7    0.07       0  4756.8    0.12       0  4944.0    0.07       0
  5001.2    0.05       0  5009.6    0.07       0  5263.4   0.035       0
  5536.7    0.07       0  5802.9   0.035       0  6255.6    0.07       0
  6309.7   0.035       0
Bank Sta=5001.2,5009.6
Exp/Cntr=0.3,0.1

Type RM Length L Ch R = 1,13361,438,438,438
BEGIN DESCRIPTION:
HAAG CREEK 29.0
END DESCRIPTION:
XS GIS Cut Line= 3
      2076375.01     13922325.04      2076475.00     13922575.00
      2076774.98     13922824.98
#Sta/Elev= 30
  4716.8 1571.12  4731.6 1568.41  4761.0 1558.62  4785.4 1552.60  4809.7 1538.42
  4846.0 1527.71  4866.0 1525.08  4893.1 1522.27  4917.4 1512.12  4922.7 1518.95
  4932.2 1519.97  4989.3 1516.92  4993.2 1497.25  5009.8 1492.81  5010.3 1492.31
  5018.3 1492.81  5036.1 1496.16  5042.6 1493.45  5050.5 1497.97  5057.0 1496.25
  5071.3 1500.34  5120.7 1500.64  5149.4 1503.50  5184.5 1502.77  5227.5 1506.32
  5256.1 1506.05  5277.0 1500.00  5319.9 1509.45  5365.9 1513.54  5376.5 1514.26
#Mann=6,-1,0
  4716.8    0.07       0  4761.0    0.12       0  4866.0    0.07       0
  5009.8    0.05       0  5018.3    0.07       0  5365.9   0.035       0
Bank Sta=5009.8,5018.3
Exp/Cntr=0.3,0.1

Type RM Length L Ch R = 1,12923,451,451,451
BEGIN DESCRIPTION:
HAAG CREEK 28.0
END DESCRIPTION:
XS GIS Cut Line= 3
      2076325.00     13922575.00      2076525.00     13922975.00
      2076626.56     13923241.28
#Sta/Elev= 30
  4556.4 1515.51  4676.6 1509.39  4682.2 1507.96  4698.9 1500.75  4704.5 1508.55
  4766.0 1505.07  4883.4 1503.81  4900.2 1501.59  4905.8 1502.26  4937.4 1500.86
  4958.9 1497.62  4972.9 1497.39  4985.2 1489.02  4985.7 1488.52  4994.0 1489.02
  5000.8 1492.48  5006.3 1492.48  5013.3 1508.90  5018.7 1509.54  5025.0 1512.28
  5057.1 1518.07  5073.5 1519.68  5078.8 1522.52  5098.2 1522.56  5103.6 1524.35
  5128.3 1527.44  5153.0 1529.77  5158.4 1529.55  5213.2 1535.71  5288.6 1541.78
#Mann=4,-1,0
  4556.4    0.07       0  4937.4   0.035       0  4985.2   0.035       0
  4994.0   0.035       0
Bank Sta=4985.2,4994
Exp/Cntr=0.3,0.1

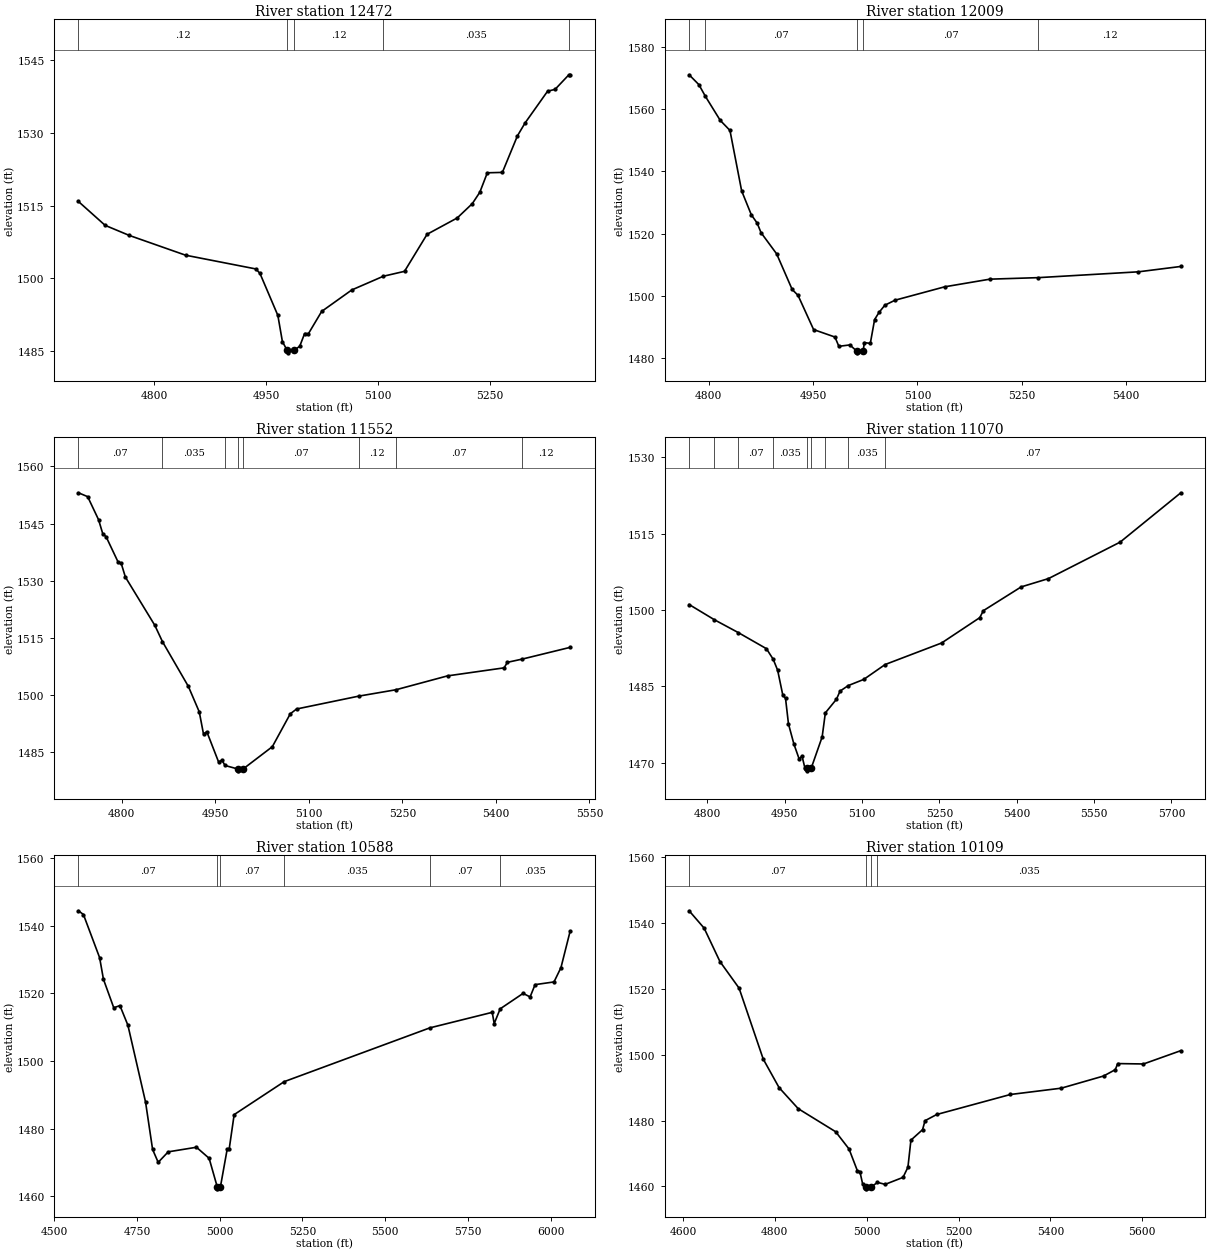
Type RM Length L Ch R = 1,12472,463,463,463
BEGIN DESCRIPTION:
HAAG CREEK 27.0
END DESCRIPTION:
XS GIS Cut Line= 3
      2076241.64     13922542.02      2076125.00     13922825.00
      2076075.00     13923174.97
#Sta/Elev= 30
  4698.1 1515.85  4733.9 1510.94  4766.2 1508.87  4841.9 1504.79  4936.2 1501.96
  4941.6 1501.04  4965.6 1492.40  4971.7 1487.01  4978.1 1485.19  4978.6 1484.69
  4986.9 1485.19  4994.9 1486.03  5001.5 1488.66  5006.7 1488.66  5024.4 1493.22
  5064.8 1497.64  5107.1 1500.46  5135.5 1501.47  5165.8 1509.10  5206.2 1512.46
  5226.4 1515.40  5236.5 1517.74  5246.6 1521.76  5266.8 1521.84  5287.0 1529.37
  5297.1 1531.99  5327.4 1538.55  5337.5 1538.94  5356.0 1541.94  5357.7 1541.94
#Mann=5,-1,0
  4698.1    0.12       0  4978.1    0.05       0  4986.9    0.12       0
  5107.1   0.035       0  5356.0    0.07       0
Bank Sta=4978.1,4986.9
Exp/Cntr=0.3,0.1

Type RM Length L Ch R = 1,12009,457,457,457
BEGIN DESCRIPTION:
HAAG CREEK 26.0
END DESCRIPTION:
XS GIS Cut Line= 3
      2076025.00     13922325.00      2075925.00     13922525.00
      2075642.69     13922917.02
#Sta/Elev= 30
  4771.8 1570.98  4785.8 1567.82  4795.3 1564.01  4816.5 1556.35  4830.5 1553.11
  4847.3 1533.70  4861.2 1526.03  4869.6 1523.36  4875.2 1520.28  4897.6 1513.49
  4919.9 1502.06  4928.3 1500.18  4950.7 1489.19  4981.4 1486.79  4987.0 1483.81
  5002.8 1484.26  5013.0 1482.22  5013.5 1481.72  5021.9 1482.22  5023.6 1485.02
  5032.2 1484.74  5038.4 1492.42  5044.7 1494.68  5053.1 1497.01  5067.8 1498.62
  5139.0 1502.91  5204.0 1505.37  5273.7 1505.86  5417.6 1507.73  5478.5 1509.45
#Mann=5,-1,0
  4771.8    0.12       0  4795.3    0.07       0  5013.0    0.05       0
  5021.9    0.07       0  5273.7    0.12       0
Bank Sta=5013,5021.9
Exp/Cntr=0.3,0.1

Type RM Length L Ch R = 1,11552,482,482,482
BEGIN DESCRIPTION:
HAAG CREEK 25.0
END DESCRIPTION:
XS GIS Cut Line= 3
      2075624.98     13922225.04      2075525.00     13922475.00
      2075593.20     13922989.99
#Sta/Elev= 30
  4730.4 1553.08  4745.2 1552.06  4762.7 1546.00  4769.4 1542.33  4774.8 1541.53
  4793.6 1535.03  4799.0 1534.54  4805.7 1530.94  4852.9 1518.27  4865.1 1514.00
  4906.7 1502.23  4924.2 1495.54  4931.0 1489.71  4936.3 1490.33  4955.2 1482.38
  4960.6 1482.86  4965.5 1481.46  4985.7 1480.55  4986.2 1480.05  4994.6 1480.55
  5041.4 1486.39  5070.2 1495.03  5080.3 1496.29  5179.7 1499.66  5239.8 1501.35
  5322.4 1504.99  5413.2 1507.10  5418.4 1508.55  5442.0 1509.39  5519.1 1512.48
#Mann=8,-1,0
  4730.4    0.07       0  4865.1   0.035       0  4965.5    0.07       0
  4985.7    0.05       0  4994.6    0.07       0  5179.7    0.12       0
  5239.8    0.07       0  5442.0    0.12       0
Bank Sta=4985.7,4994.6
Exp/Cntr=0.3,0.1

Type RM Length L Ch R = 1,11070,482,482,482
BEGIN DESCRIPTION:
HAAG CREEK 24.0
END DESCRIPTION:
XS GIS Cut Line= 3
      2075147.90     13922351.89      2075075.00     13922575.00
      2075436.93     13923195.67
#Sta/Elev= 30
  4764.9 1501.08  4813.9 1498.09  4860.4 1495.56  4914.7 1492.42  4927.9 1490.34
  4936.5 1488.19  4946.5 1483.31  4951.8 1482.67  4957.5 1477.65  4968.1 1473.69
  4978.4 1470.73  4983.7 1471.39  4989.1 1469.11  4992.5 1468.96  4993.0 1468.46
  5001.5 1468.96  5022.8 1475.12  5029.0 1479.83  5050.5 1482.50  5057.5 1484.10
  5073.4 1485.18  5103.4 1486.39  5144.9 1489.31  5254.3 1493.53  5328.3 1498.50
  5335.3 1499.87  5408.6 1504.53  5461.5 1506.16  5600.4 1513.31  5718.1 1522.99
#Mann=9,-1,0
  4764.9    0.07       0  4813.9   0.035       0  4860.4    0.07       0
  4927.9   0.035       0  4992.5   0.035       0  5001.5   0.035       0
  5029.0    0.07       0  5073.4   0.035       0  5144.9    0.07       0
Bank Sta=4992.5,5001.5
Exp/Cntr=0.3,0.1

Type RM Length L Ch R = 1,10588,479,479,479
BEGIN DESCRIPTION:
HAAG CREEK 23.0
END DESCRIPTION:
XS GIS Cut Line= 3
      2074475.02     13922275.04      2074625.00     13922675.00
      2075207.31     13923560.07
#Sta/Elev= 30
  4572.8 1544.45  4587.9 1543.34  4636.8 1530.58  4648.4 1524.18  4679.6 1515.74
  4698.2 1516.39  4722.3 1510.59  4775.7 1487.84  4797.0 1473.81  4813.9 1469.99
  4844.2 1473.10  4929.6 1474.46  4967.9 1471.19  4992.7 1462.65  4993.2 1462.15
  5001.9 1462.65  5022.6 1473.93  5028.6 1473.95  5043.6 1484.12  5195.0 1493.88
  5635.1 1509.79  5823.8 1514.39  5829.8 1511.07  5847.9 1515.43  5917.2 1520.00
  5938.3 1518.95  5953.4 1522.59  6010.6 1523.39  6031.6 1527.62  6059.4 1538.42
#Mann=6,-1,0
  4572.8    0.07       0  4992.7    0.05       0  5001.9    0.07       0
  5195.0   0.035       0  5635.1    0.07       0  5847.9   0.035       0
Bank Sta=4992.7,5001.9
Exp/Cntr=0.3,0.1

Type RM Length L Ch R = 1,10109,484,484,484
BEGIN DESCRIPTION:
HAAG CREEK 22.0
END DESCRIPTION:
XS GIS Cut Line= 3
      2074325.01     13922224.97      2074175.00     13922575.00
      2074408.30     13923224.34
#Sta/Elev= 30
  4613.3 1543.79  4646.0 1538.51  4680.4 1528.36  4722.1 1520.27  4774.7 1498.70
  4809.2 1490.03  4850.9 1483.63  4932.5 1476.61  4961.5 1471.38  4979.6 1464.80
  4985.1 1464.53  4991.4 1460.62  4998.9 1459.76  4999.4 1459.26  5009.4 1459.76
  5023.4 1461.23  5040.2 1460.62  5079.1 1462.74  5089.8 1465.83  5096.3 1474.06
  5121.6 1477.24  5127.1 1479.98  5152.5 1481.86  5312.9 1487.94  5423.7 1489.86
  5515.9 1493.56  5541.3 1495.48  5546.7 1497.34  5602.8 1497.22  5684.1 1501.27
#Mann=4,-1,0
  4613.3    0.07       0  4998.9    0.05       0  5009.4    0.07       0
  5023.4   0.035       0
Bank Sta=4998.9,5009.4
Exp/Cntr=0.3,0.1

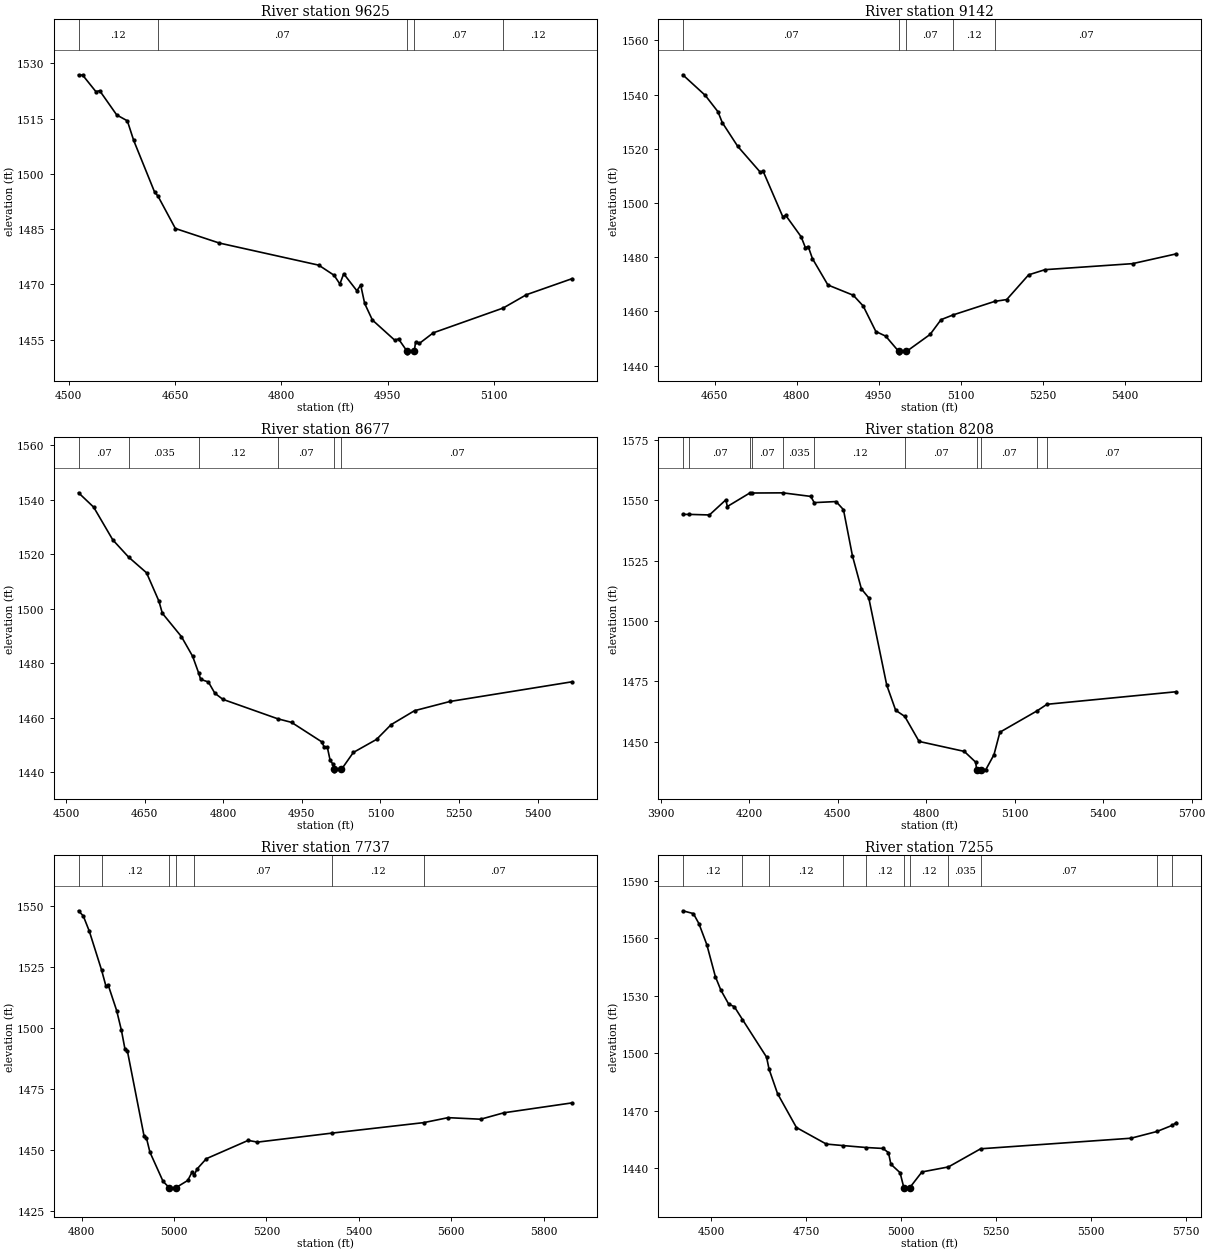
Type RM Length L Ch R = 1,9625,483,483,483
BEGIN DESCRIPTION:
HAAG CREEK 21.0
END DESCRIPTION:
XS GIS Cut Line= 3
      2073910.90     13922021.20      2073725.00     13922475.00
      2073775.01     13922675.04
#Sta/Elev= 30
  4513.7 1526.88  4519.6 1526.77  4538.2 1522.31  4543.6 1522.55  4567.6 1515.98
  4582.6 1514.38  4591.6 1509.04  4621.0 1495.07  4625.8 1493.95  4650.4 1485.15
  4712.3 1481.21  4852.8 1475.20  4874.4 1472.46  4882.6 1470.09  4888.0 1472.87
  4906.6 1468.25  4912.0 1469.80  4917.6 1464.80  4928.5 1460.31  4960.0 1454.84
  4965.4 1455.17  4977.2 1451.90  4977.7 1451.40  4987.7 1451.90  4989.4 1454.29
  4994.8 1453.95  5014.4 1456.83  5113.2 1463.57  5145.8 1467.17  5210.3 1471.53
#Mann=5,-1,0
  4513.7    0.12       0  4625.8    0.07       0  4977.2    0.05       0
  4987.7    0.07       0  5113.2    0.12       0
Bank Sta=4977.2,4987.7
Exp/Cntr=0.3,0.1

Type RM Length L Ch R = 1,9142,465,465,465
BEGIN DESCRIPTION:
HAAG CREEK 20.0
END DESCRIPTION:
XS GIS Cut Line= 3
      2073375.00     13921974.98      2073275.00     13922375.00
      2073262.47     13922864.91
#Sta/Elev= 30
  4591.9 1547.30  4633.1 1539.69  4656.3 1533.66  4664.1 1529.68  4692.4 1520.90
  4733.6 1511.37  4738.8 1511.75  4774.9 1494.88  4780.0 1495.48  4808.4 1487.52
  4816.1 1483.54  4821.3 1483.93  4829.0 1479.48  4857.3 1469.74  4903.7 1465.95
  4921.8 1462.00  4945.0 1452.57  4963.0 1450.86  4986.9 1445.20  4987.4 1444.70
  5000.9 1445.20  5044.2 1451.49  5064.2 1456.94  5086.1 1458.68  5162.4 1463.69
  5184.3 1464.36  5224.3 1473.47  5254.3 1475.39  5414.4 1477.61  5494.3 1481.22
#Mann=5,-1,0
  4591.9    0.07       0  4986.9    0.05       0  5000.9    0.07       0
  5086.1    0.12       0  5162.4    0.07       0
Bank Sta=4986.9,5000.9
Exp/Cntr=0.3,0.1

Type RM Length L Ch R = 1,8677,469,469,469
BEGIN DESCRIPTION:
HAAG CREEK 19.0
END DESCRIPTION:
XS GIS Cut Line= 3
      2073274.99     13921925.00      2072875.00     13922175.00
      2072658.30     13922591.51
#Sta/Elev= 30
  4524.1 1542.56  4553.0 1537.28  4589.5 1525.27  4619.7 1518.95  4653.8 1513.22
  4677.4 1502.83  4683.9 1498.39  4720.4 1489.79  4741.7 1482.60  4753.5 1476.30
  4757.0 1474.13  4771.7 1473.18  4784.1 1469.04  4799.4 1466.80  4903.9 1459.68
  4930.3 1458.36  4988.1 1451.20  4992.8 1449.21  4998.6 1449.21  5004.0 1444.42
  5009.7 1442.93  5011.3 1441.08  5011.8 1440.58  5025.4 1441.08  5048.2 1447.32
  5092.4 1452.10  5120.2 1457.51  5164.9 1462.64  5232.5 1466.02  5465.3 1473.24
#Mann=6,-1,0
  4524.1    0.07       0  4619.7   0.035       0  4753.5    0.12       0
  4903.9    0.07       0  5011.3    0.05       0  5025.4    0.07       0
Bank Sta=5011.3,5025.4
Exp/Cntr=0.3,0.1

Type RM Length L Ch R = 1,8208,471,471,471
BEGIN DESCRIPTION:
HAAG CREEK 18.0
END DESCRIPTION:
XS GIS Cut Line= 3
      2072119.24     13921013.41      2072475.00     13921975.00
      2072426.63     13922621.41
#Sta/Elev= 30
  3974.3 1544.08  3995.8 1544.09  4064.8 1543.85  4120.3 1550.09  4125.6 1547.35
  4202.9 1553.03  4208.0 1552.93  4314.1 1553.00  4408.3 1551.53  4420.2 1548.96
  4494.2 1549.40  4519.3 1546.03  4549.7 1526.95  4580.1 1513.25  4605.1 1509.53
  4665.9 1473.49  4696.3 1463.01  4727.2 1460.47  4775.7 1450.12  4928.9 1446.00
  4967.6 1441.54  4970.9 1438.45  4971.4 1437.95  4985.7 1438.45  5002.1 1438.48
  5029.7 1444.62  5049.7 1453.93  5175.2 1462.73  5209.4 1465.49  5647.8 1470.69
#Mann=11,-1,0
  3974.3   0.035       0  3995.8    0.07       0  4202.9   0.035       0
  4208.0    0.07       0  4314.1   0.035       0  4420.2    0.12       0
  4727.2    0.07       0  4970.9    0.05       0  4985.7    0.07       0
  5175.2    0.12       0  5209.4    0.07       0
Bank Sta=4970.9,4985.7
Exp/Cntr=0.3,0.1

Type RM Length L Ch R = 1,7737,482,482,482
BEGIN DESCRIPTION:
HAAG CREEK 17.0
END DESCRIPTION:
XS GIS Cut Line= 3
      2072125.00     13921574.99      2072075.00     13921775.00
      2072171.14     13922631.55
#Sta/Elev= 30
  4793.5 1548.24  4803.8 1546.11  4816.7 1539.94  4843.3 1523.98  4852.8 1517.37
  4857.9 1517.67  4876.0 1507.33  4886.3 1499.24  4894.0 1491.54  4899.2 1490.80
  4935.2 1455.99  4940.4 1455.12  4948.1 1449.20  4976.5 1437.26  4989.7 1434.71
  4990.2 1434.21  5004.5 1434.71  5029.9 1437.65  5039.7 1441.24  5043.9 1439.81
  5050.0 1442.34  5070.1 1446.57  5160.7 1454.08  5180.8 1453.37  5341.9 1457.06
  5540.5 1461.36  5593.4 1463.40  5663.8 1462.76  5714.1 1465.40  5861.6 1469.46
#Mann=7,-1,0
  4793.5    0.07       0  4843.3    0.12       0  4989.7    0.05       0
  5004.5    0.12       0  5043.9    0.07       0  5341.9    0.12       0
  5540.5    0.07       0
Bank Sta=4989.7,5004.5
Exp/Cntr=0.3,0.1

Type RM Length L Ch R = 1,7255,428,428,428
BEGIN DESCRIPTION:
HAAG CREEK 16.0
END DESCRIPTION:
XS GIS Cut Line= 3
      2072074.97     13921325.03      2071625.00     13921675.00
      2071585.38     13922403.98
#Sta/Elev= 30
  4425.5 1574.44  4453.5 1572.97  4468.0 1567.77  4488.8 1556.81  4511.4 1540.07
  4525.9 1533.00  4546.7 1525.62  4561.2 1524.39  4582.8 1517.64  4646.3 1497.99
  4652.9 1491.68  4675.2 1478.95  4725.0 1461.22  4803.7 1452.59  4846.5 1451.82
  4909.0 1450.78  4953.0 1450.30  4967.5 1448.09  4973.8 1442.07  4998.0 1437.63
  5008.1 1429.70  5008.6 1429.20  5023.1 1429.70  5055.6 1438.02  5125.5 1440.65
  5210.3 1450.12  5606.4 1455.64  5674.8 1459.16  5715.5 1462.41  5725.6 1463.82
#Mann=11,-1,0
  4425.5    0.12       0  4582.8    0.07       0  4652.9    0.12       0
  4846.5    0.07       0  4909.0    0.12       0  5008.1    0.05       0
  5023.1    0.12       0  5125.5   0.035       0  5210.3    0.07       0
  5674.8   0.035       0  5715.5    0.07       0
Bank Sta=5008.1,5023.1
Exp/Cntr=0.3,0.1

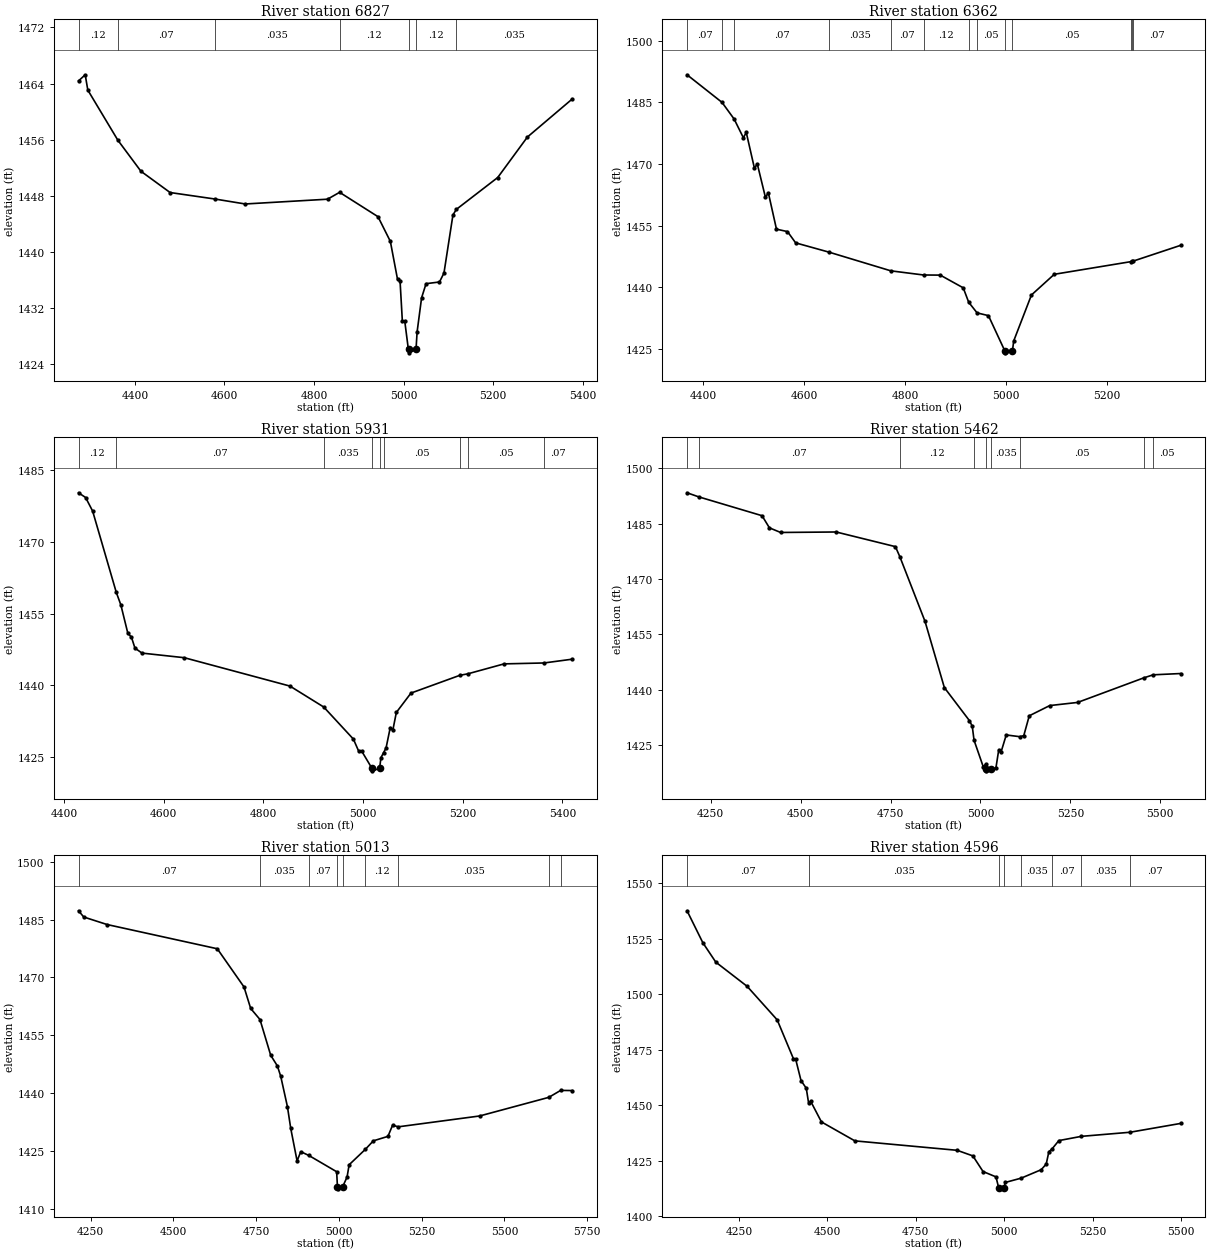
Type RM Length L Ch R = 1,6827,465,465,465
BEGIN DESCRIPTION:
HAAG CREEK 15.0
END DESCRIPTION:
XS GIS Cut Line= 3
      2071580.17     13921042.04      2071225.00     13921675.00
      2071218.22     13922051.23
#Sta/Elev= 30
  4274.3 1464.38  4289.2 1465.25  4295.0 1463.07  4362.0 1455.94  4413.6 1451.51
  4478.7 1448.48  4578.4 1447.56  4646.4 1446.85  4830.1 1447.53  4857.1 1448.51
  4942.8 1445.04  4970.4 1441.52  4986.4 1436.12  4992.1 1435.84  4997.2 1430.14
  5002.6 1430.14  5010.1 1426.40  5012.6 1426.15  5013.1 1425.65  5027.7 1426.15
  5030.1 1428.62  5040.1 1433.48  5050.1 1435.50  5080.1 1435.74  5090.1 1437.02
  5110.1 1445.28  5117.7 1446.08  5210.1 1450.62  5276.3 1456.38  5376.4 1461.80
#Mann=7,-1,0
  4274.3    0.12       0  4362.0    0.07       0  4578.4   0.035       0
  4857.1    0.12       0  5012.6    0.05       0  5027.7    0.12       0
  5117.7   0.035       0
Bank Sta=5012.6,5027.7
Exp/Cntr=0.3,0.1

Type RM Length L Ch R = 1,6362,431,431,431
BEGIN DESCRIPTION:
HAAG CREEK 14.0
END DESCRIPTION:
XS GIS Cut Line= 3
      2071074.99     13921075.01      2070775.00     13921625.00
      2070806.73     13921974.28
#Sta/Elev= 30
  4368.7 1491.72  4437.9 1485.00  4461.9 1480.94  4480.2 1476.38  4485.9 1477.68
  4502.1 1468.95  4507.7 1470.03  4523.9 1461.85  4529.6 1463.00  4545.7 1454.12
  4567.5 1453.53  4583.7 1450.78  4650.6 1448.49  4772.1 1443.97  4836.8 1442.96
  4869.9 1442.93  4915.4 1439.83  4926.2 1436.32  4942.8 1433.73  4965.3 1433.06
  4997.6 1424.50  4998.1 1424.00  5012.8 1424.50  5015.3 1426.90  5050.4 1438.09
  5095.6 1443.13  5248.3 1446.23  5249.0 1446.25  5252.0 1446.35  5345.9 1450.19
#Mann=13,-1,0
  4368.7    0.07       0  4437.9    0.12       0  4461.9    0.07       0
  4650.6   0.035       0  4772.1    0.07       0  4836.8    0.12       0
  4926.2    0.07       0  4942.8    0.05       0  4997.6    0.05       0
  5012.8    0.05       0  5248.3    0.07       0  5249.0    0.05       0
  5252.0    0.07       0
Bank Sta=4997.6,5012.8
Exp/Cntr=0.3,0.1

Type RM Length L Ch R = 1,5931,469,469,469
BEGIN DESCRIPTION:
HAAG CREEK 13.0
END DESCRIPTION:
XS GIS Cut Line= 3
      2070775.03     13921124.97      2070375.00     13921525.00
      2070476.01     13921937.89
#Sta/Elev= 30
  4428.9 1480.19  4443.1 1479.20  4457.2 1476.37  4504.7 1459.40  4513.8 1456.81
  4527.9 1450.86  4535.0 1450.10  4542.1 1447.79  4556.2 1446.75  4641.1 1445.79
  4853.2 1439.87  4921.0 1435.50  4980.5 1428.81  4991.1 1426.30  4997.2 1426.30
  5017.9 1422.69  5018.4 1422.19  5033.1 1422.69  5035.8 1424.93  5041.0 1425.96
  5046.1 1426.97  5054.5 1431.22  5059.7 1430.68  5066.7 1434.37  5096.1 1438.41
  5194.3 1442.12  5210.0 1442.42  5282.9 1444.50  5363.1 1444.69  5419.7 1445.48
#Mann=9,-1,0
  4428.9    0.12       0  4504.7    0.07       0  4921.0   0.035       0
  5017.9   0.035       0  5033.1   0.035       0  5041.0    0.05       0
  5194.3    0.07       0  5210.0    0.05       0  5363.1    0.07       0
Bank Sta=5017.9,5033.1
Exp/Cntr=0.3,0.1

Type RM Length L Ch R = 1,5462,449,449,449
BEGIN DESCRIPTION:
HAAG CREEK 12.0
END DESCRIPTION:
XS GIS Cut Line= 3
      2069728.60     13920682.62      2069925.00     13921475.00
      2070272.91     13921909.26
#Sta/Elev= 30
  4184.1 1493.38  4216.1 1492.29  4392.6 1487.17  4413.2 1483.88  4444.3 1482.63
  4598.7 1482.76  4763.5 1478.79  4775.9 1476.05  4845.9 1458.53  4899.6 1440.61
  4969.5 1431.64  4977.2 1430.13  4982.2 1426.34  5007.7 1419.18  5014.1 1419.82
  5014.4 1418.56  5014.9 1418.06  5029.8 1418.56  5042.9 1418.79  5050.9 1423.79
  5057.3 1423.16  5071.7 1427.78  5109.5 1427.31  5120.4 1427.58  5135.7 1432.97
  5192.7 1435.74  5270.2 1436.59  5453.7 1443.23  5480.3 1444.07  5556.9 1444.42
#Mann=9,-1,0
  4184.1   0.035       0  4216.1    0.07       0  4775.9    0.12       0
  4982.2   0.035       0  5014.4   0.035       0  5029.8   0.035       0
  5109.5    0.05       0  5453.7    0.07       0  5480.3    0.05       0
Bank Sta=5014.4,5029.8
Exp/Cntr=0.3,0.1

Type RM Length L Ch R = 1,5013,417,417,417
BEGIN DESCRIPTION:
HAAG CREEK 11.0
END DESCRIPTION:
XS GIS Cut Line= 3
      2069624.44     13920849.37      2069525.00     13921625.00
      2070129.62     13921995.14
#Sta/Elev= 30
  4213.8 1487.30  4229.6 1485.68  4300.1 1483.73  4632.8 1477.45  4713.5 1467.54
  4733.7 1461.96  4761.7 1459.10  4794.1 1449.83  4814.3 1447.05  4824.4 1444.37
  4844.6 1436.51  4854.6 1430.87  4873.8 1422.42  4884.9 1424.82  4909.5 1423.83
  4993.3 1419.62  4995.7 1415.68  4996.2 1415.18  5011.2 1415.68  5024.8 1418.26
  5031.0 1421.43  5079.9 1425.42  5104.1 1427.63  5148.2 1428.79  5162.2 1431.68
  5179.6 1431.27  5425.2 1434.08  5634.0 1438.91  5669.7 1440.71  5704.7 1440.67
#Mann=9,-1,0
  4213.8    0.07       0  4761.7   0.035       0  4909.5    0.07       0
  4995.7    0.05       0  5011.2    0.07       0  5079.9    0.12       0
  5179.6   0.035       0  5634.0    0.07       0  5669.7    0.05       0
Bank Sta=4995.7,5011.2
Exp/Cntr=0.3,0.1

Type RM Length L Ch R = 1,4596,470,470,470
BEGIN DESCRIPTION:
HAAG CREEK 10.0
END DESCRIPTION:
XS GIS Cut Line= 3
      2068848.41     13921208.72      2069325.00     13921975.00
      2069658.31     13922338.93
#Sta/Elev= 30
  4103.2 1537.56  4147.9 1523.15  4184.5 1514.42  4273.1 1503.52  4358.1 1488.41
  4404.1 1470.86  4410.0 1470.90  4425.4 1461.08  4440.3 1457.60  4446.7 1451.14
  4452.5 1451.81  4483.2 1442.43  4577.7 1433.89  4866.9 1429.64  4911.4 1427.12
  4940.1 1420.08  4976.7 1417.67  4984.3 1412.78  4984.8 1412.28  4999.8 1412.78
  5002.7 1415.15  5048.0 1417.10  5104.6 1420.90  5118.8 1423.45  5126.2 1428.99
  5134.8 1430.18  5154.5 1434.02  5218.2 1435.93  5355.5 1437.77  5499.1 1441.76
#Mann=8,-1,0
  4103.2    0.07       0  4446.7   0.035       0  4984.3    0.05       0
  4999.8   0.035       0  5048.0   0.035       0  5134.8    0.07       0
  5218.2   0.035       0  5355.5    0.07       0
Bank Sta=4984.3,4999.8
Exp/Cntr=0.3,0.1