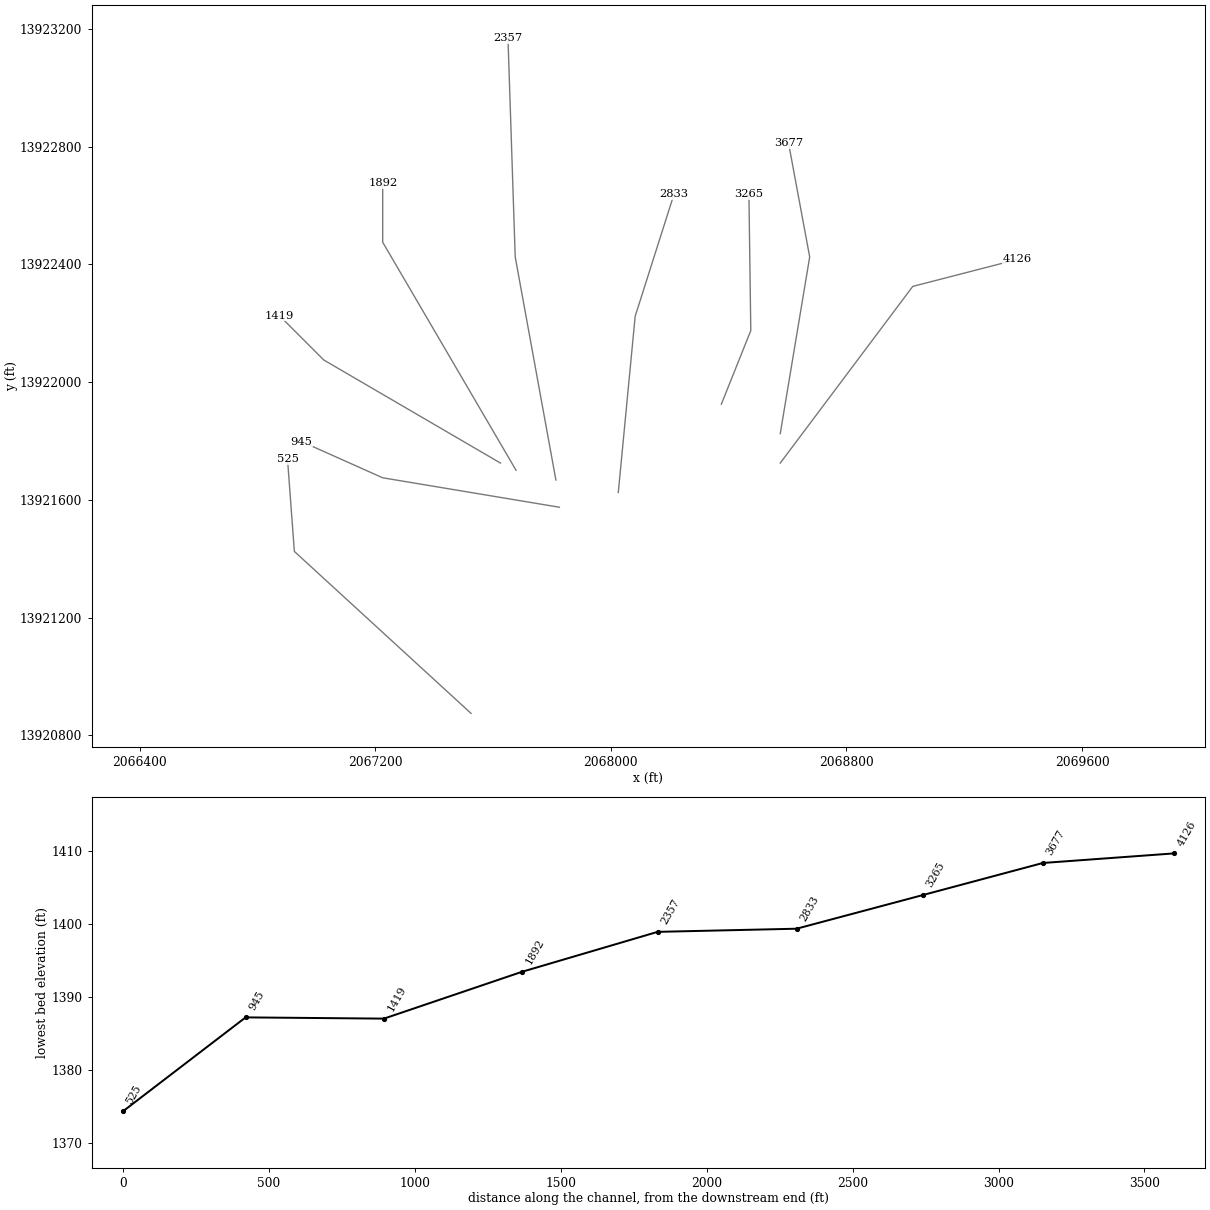
HEC-RAS study HAAG CREEK.prj: HAAG CREEK Base Level Engineering

--- HAAG CREEK.g01 (geometry) --- (continued)

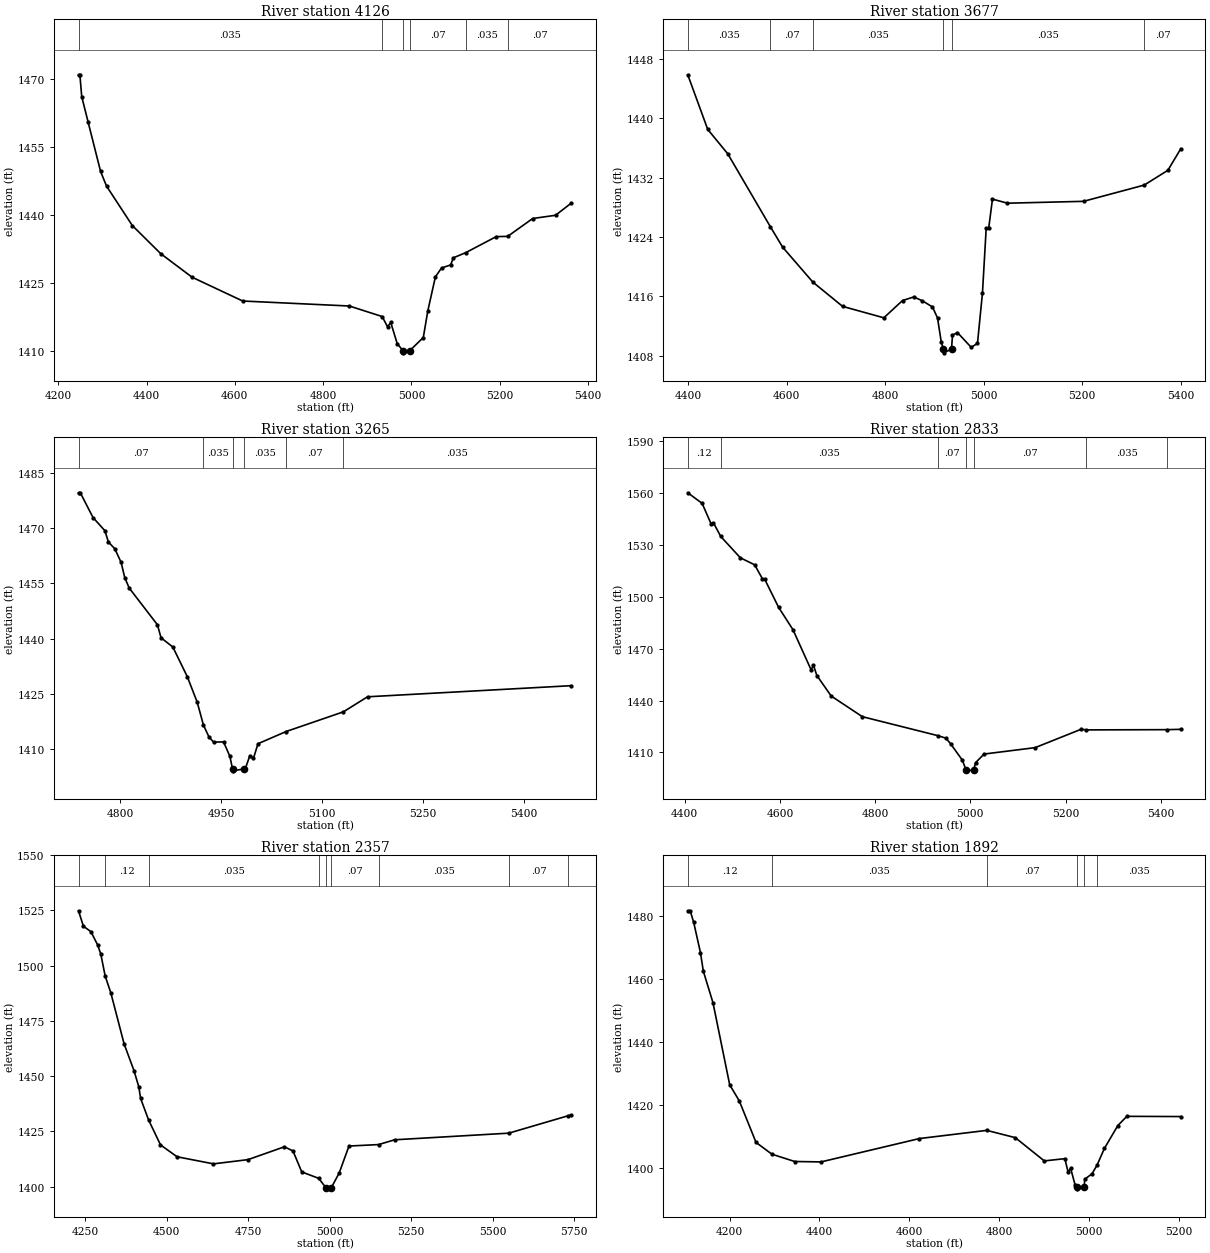
Type RM Length L Ch R = 1,4126,449,449,449
BEGIN DESCRIPTION:
HAAG CREEK 9.0
END DESCRIPTION:
XS GIS Cut Line= 3
      2068575.01     13921725.01      2069025.00     13922325.00
      2069380.09     13922416.60
#Sta/Elev= 30
  4245.8 1470.97  4248.9 1470.97  4253.1 1466.16  4267.7 1460.50  4295.8 1449.68
  4309.3 1446.44  4367.7 1437.75  4432.2 1431.54  4503.1 1426.36  4617.7 1421.12
  4859.3 1420.02  4933.6 1417.70  4945.8 1415.45  4953.1 1416.39  4967.7 1411.73
  4980.7 1410.20  4981.2 1409.70  4996.3 1410.20  5026.8 1413.07  5037.1 1418.98
  5054.2 1426.44  5068.1 1428.39  5088.7 1429.07  5094.9 1430.64  5123.0 1431.78
  5192.0 1435.31  5217.9 1435.36  5274.6 1439.30  5326.3 1440.01  5362.5 1442.73
#Mann=6,-1,0
  4245.8   0.035       0  4933.6    0.07       0  4980.7    0.05       0
  4996.3    0.07       0  5123.0   0.035       0  5217.9    0.07       0
Bank Sta=4980.7,4996.3
Exp/Cntr=0.3,0.1

Type RM Length L Ch R = 1,3677,412,412,412
BEGIN DESCRIPTION:
HAAG CREEK 8.0
END DESCRIPTION:
XS GIS Cut Line= 3
      2068575.01     13921825.04      2068675.00     13922425.00
      2068603.33     13922810.76
#Sta/Elev= 30
  4399.6 1445.85  4440.1 1438.49  4480.7 1435.21  4567.3 1425.37  4592.2 1422.62
  4653.6 1417.91  4713.8 1414.65  4797.5 1413.11  4835.5 1415.44  4858.3 1415.92
  4876.0 1415.39  4896.3 1414.57  4906.5 1413.09  4914.1 1409.84  4918.6 1408.89
  4919.1 1408.39  4934.9 1408.89  4936.9 1410.78  4947.0 1411.12  4974.9 1409.13
  4987.6 1409.67  4997.7 1416.43  5005.3 1425.19  5010.4 1425.19  5018.0 1429.10
  5048.5 1428.55  5202.8 1428.80  5326.0 1430.99  5374.0 1432.98  5400.2 1435.88
#Mann=6,-1,0
  4399.6   0.035       0  4567.3    0.07       0  4653.6   0.035       0
  4918.6   0.035       0  4934.9   0.035       0  5326.0    0.07       0
Bank Sta=4918.6,4934.9
Exp/Cntr=0.3,0.1

Type RM Length L Ch R = 1,3265,432,432,432
BEGIN DESCRIPTION:
HAAG CREEK 7.0
END DESCRIPTION:
XS GIS Cut Line= 3
      2068374.98     13921924.95      2068475.00     13922175.00
      2068468.63     13922637.95
#Sta/Elev= 30
  4737.9 1479.66  4740.6 1479.66  4759.5 1472.91  4777.0 1469.36  4782.4 1466.24
  4791.8 1464.43  4801.2 1460.71  4806.6 1456.56  4813.3 1453.71  4855.1 1443.75
  4860.5 1440.20  4878.0 1437.69  4899.5 1429.62  4914.3 1422.62  4923.5 1416.44
  4931.8 1413.17  4938.5 1411.83  4953.4 1411.85  4962.8 1407.92  4966.7 1404.49
  4967.2 1403.99  4983.0 1404.49  4985.7 1404.59  4992.4 1408.13  4997.8 1407.41
  5004.5 1411.37  5046.3 1414.69  5131.4 1420.05  5167.2 1424.14  5470.2 1427.17
#Mann=6,-1,0
  4737.9    0.07       0  4923.5   0.035       0  4966.7   0.035       0
  4983.0   0.035       0  5046.3    0.07       0  5131.4   0.035       0
Bank Sta=4966.7,4983
Exp/Cntr=0.3,0.1

Type RM Length L Ch R = 1,2833,476,476,476
BEGIN DESCRIPTION:
HAAG CREEK 6.0
END DESCRIPTION:
XS GIS Cut Line= 3
      2068025.00     13921625.01      2068082.34     13922223.46
      2068214.05     13922637.63
#Sta/Elev= 30
  4406.3 1560.03  4436.4 1553.93  4455.1 1542.21  4460.1 1542.73  4475.6 1534.79
  4516.8 1522.46  4546.9 1518.40  4562.8 1510.49  4567.8 1510.16  4597.2 1493.83
  4627.3 1480.94  4665.4 1457.76  4670.4 1460.40  4677.5 1454.45  4707.7 1442.59
  4773.1 1430.68  4931.6 1419.73  4948.8 1418.25  4958.8 1414.93  4983.4 1405.48
  4990.8 1399.89  4991.3 1399.39  5007.1 1399.89  5010.9 1404.08  5028.8 1409.09
  5136.0 1412.78  5232.7 1423.41  5243.1 1423.04  5413.2 1423.18  5442.1 1423.38
#Mann=7,-1,0
  4406.3    0.12       0  4475.6   0.035       0  4931.6    0.07       0
  4990.8    0.05       0  5007.1    0.07       0  5243.1   0.035       0
  5413.2    0.07       0
Bank Sta=4990.8,5007.1
Exp/Cntr=0.3,0.1

Type RM Length L Ch R = 1,2357,465,465,465
BEGIN DESCRIPTION:
HAAG CREEK 5.0
END DESCRIPTION:
XS GIS Cut Line= 3
      2067813.12     13921667.50      2067675.00     13922425.00
      2067650.39     13923167.40
#Sta/Elev= 30
  4229.6 1524.86  4244.6 1517.88  4267.7 1515.40  4288.1 1509.46  4297.9 1505.33
  4311.4 1495.35  4328.7 1487.75  4369.4 1464.66  4399.9 1452.46  4414.7 1445.10
  4420.2 1439.89  4444.7 1430.13  4481.2 1418.87  4532.0 1413.48  4643.8 1410.27
  4749.6 1412.18  4861.3 1417.99  4887.8 1416.11  4914.6 1406.62  4966.5 1403.73
  4988.9 1399.46  4989.4 1398.96  5005.3 1399.46  5029.6 1406.16  5059.6 1418.34
  5150.5 1419.00  5199.7 1421.17  5550.0 1424.17  5732.5 1432.07  5742.4 1432.31
#Mann=9,-1,0
  4229.6    0.07       0  4311.4    0.12       0  4444.7   0.035       0
  4966.5    0.07       0  4988.9    0.05       0  5005.3    0.07       0
  5150.5   0.035       0  5550.0    0.07       0  5732.5   0.035       0
Bank Sta=4988.9,5005.3
Exp/Cntr=0.3,0.1

Type RM Length L Ch R = 1,1892,473,473,473
BEGIN DESCRIPTION:
HAAG CREEK 4.0
END DESCRIPTION:
XS GIS Cut Line= 3
      2067677.75     13921700.66      2067225.00     13922475.00
      2067225.00     13922675.02
#Sta/Elev= 30
  4106.9 1481.78  4112.3 1481.78  4120.0 1478.14  4135.1 1468.51  4141.5 1462.62
  4163.0 1452.58  4200.2 1426.52  4221.6 1421.39  4258.8 1408.23  4294.1 1404.49
  4344.8 1402.17  4403.5 1402.04  4622.5 1409.46  4772.2 1412.05  4835.7 1409.74
  4900.2 1402.36  4946.0 1403.07  4953.1 1398.84  4958.8 1400.02  4968.8 1394.71
  4972.5 1393.99  4973.0 1393.49  4988.9 1393.99  4990.2 1396.55  5006.4 1398.26
  5017.6 1401.00  5033.9 1406.31  5063.9 1413.59  5083.9 1416.51  5203.9 1416.44
#Mann=6,-1,0
  4106.9    0.12       0  4294.1   0.035       0  4772.2    0.07       0
  4972.5    0.05       0  4988.9    0.07       0  5017.6   0.035       0
Bank Sta=4972.5,4988.9
Exp/Cntr=0.3,0.1

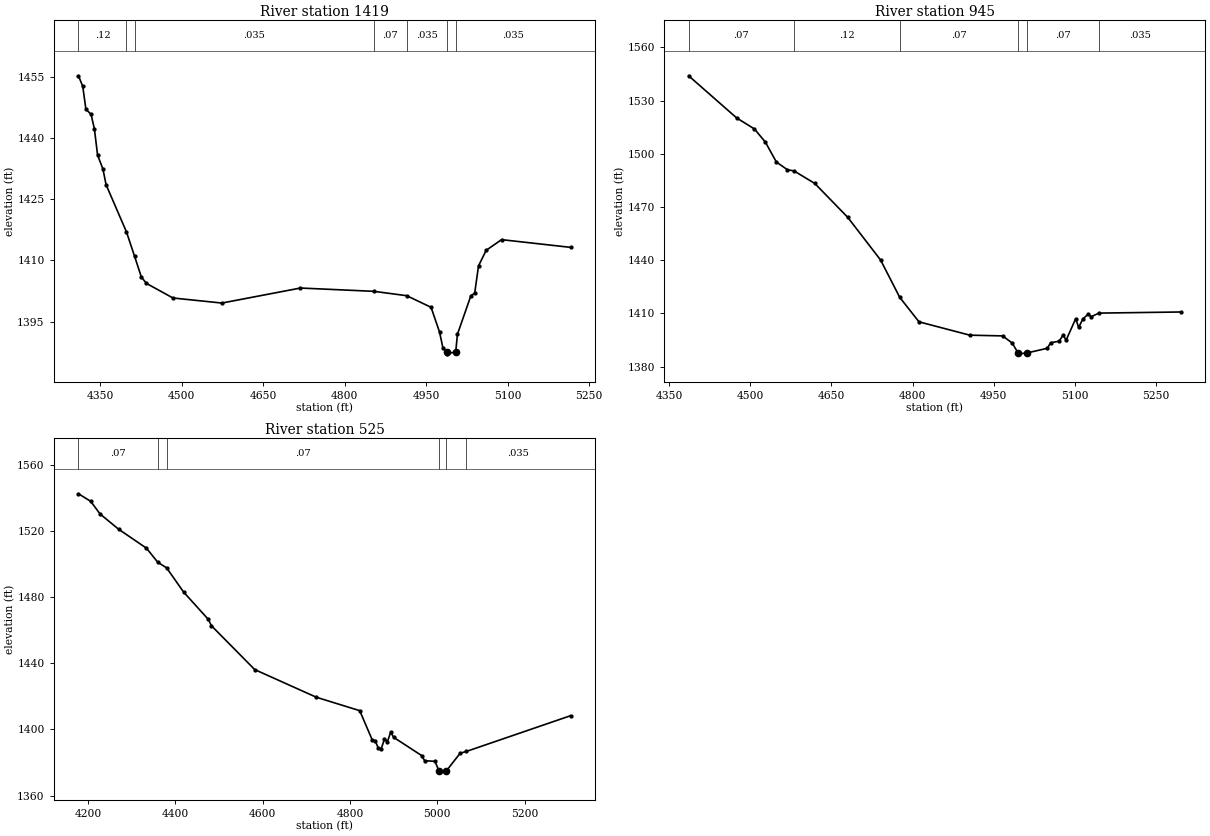
Type RM Length L Ch R = 1,1419,474,474,474
BEGIN DESCRIPTION:
HAAG CREEK 3.0
END DESCRIPTION:
XS GIS Cut Line= 3
      2067625.03     13921724.98      2067025.00     13922075.00
      2066874.99     13922225.01
#Sta/Elev= 30
  4309.5 1455.19  4317.4 1452.59  4323.2 1447.01  4332.7 1445.74  4338.9 1442.15
  4344.7 1435.77  4354.6 1432.33  4360.4 1428.50  4398.0 1416.92  4412.8 1411.01
  4425.3 1405.91  4434.8 1404.33  4483.6 1400.76  4573.7 1399.52  4718.5 1403.20
  4853.8 1402.39  4914.3 1401.32  4959.1 1398.48  4974.8 1392.39  4981.0 1388.51
  4988.1 1387.58  4988.6 1387.08  5004.6 1387.58  5007.7 1391.87  5032.4 1401.28
  5039.5 1401.95  5046.6 1408.65  5060.7 1412.44  5089.0 1415.05  5216.3 1413.16
#Mann=7,-1,0
  4309.5    0.12       0  4398.0    0.07       0  4412.8   0.035       0
  4853.8    0.07       0  4914.3   0.035       0  4988.1   0.035       0
  5004.6   0.035       0
Bank Sta=4988.1,5004.6
Exp/Cntr=0.3,0.1

Type RM Length L Ch R = 1,945,420,420,420
BEGIN DESCRIPTION:
HAAG CREEK 2.0
END DESCRIPTION:
XS GIS Cut Line= 3
      2067824.99     13921575.00      2067225.00     13921675.00
      2066949.80     13921797.99
#Sta/Elev= 30
  4386.2 1544.03  4474.9 1520.29  4507.9 1514.02  4528.1 1506.62  4548.4 1495.41
  4568.7 1491.07  4581.2 1490.36  4619.4 1483.32  4680.2 1464.25  4741.0 1440.16
  4776.5 1419.05  4812.0 1405.30  4905.8 1397.78  4966.6 1397.36  4984.3 1393.32
  4995.1 1387.75  4995.6 1387.25  5011.6 1387.75  5049.2 1390.39  5055.2 1393.49
  5071.1 1394.38  5078.4 1397.87  5083.9 1394.94  5101.6 1407.05  5107.1 1402.16
  5115.0 1406.95  5124.8 1409.63  5130.3 1408.18  5144.5 1410.22  5295.9 1410.85
#Mann=6,-1,0
  4386.2    0.07       0  4581.2    0.12       0  4776.5    0.07       0
  4995.1    0.05       0  5011.6    0.07       0  5144.5   0.035       0
Bank Sta=4995.1,5011.6
Exp/Cntr=0.3,0.1

Type RM Length L Ch R = 1,525,0,0,0
BEGIN DESCRIPTION:
HAAG CREEK 1.0
END DESCRIPTION:
XS GIS Cut Line= 3
      2067524.99     13920875.01      2066925.00     13921425.00
      2066901.79     13921737.31
#Sta/Elev= 30
  4178.2 1542.51  4206.2 1537.95  4227.8 1530.27  4270.4 1521.04  4333.9 1509.62
  4360.1 1501.03  4380.0 1497.76  4419.0 1483.08  4475.7 1466.54  4482.5 1462.78
  4581.8 1436.23  4723.0 1419.49  4822.3 1411.38  4850.6 1393.89  4857.4 1393.27
  4864.8 1388.82  4871.6 1388.39  4879.0 1394.29  4885.8 1392.68  4893.2 1398.37
  4899.9 1395.27  4964.1 1384.23  4970.9 1381.13  4994.6 1380.75  5003.9 1374.90
  5004.4 1374.40  5020.4 1374.90  5052.3 1385.67  5066.2 1386.71  5305.3 1408.36
#Mann=6,-1,0
  4178.2    0.07       0  4360.1    0.12       0  4380.0    0.07       0
  5003.9    0.05       0  5020.4    0.07       0  5066.2   0.035       0
Bank Sta=5003.9,5020.4
Exp/Cntr=0.3,0.1

Chan Stop Cuts=-1