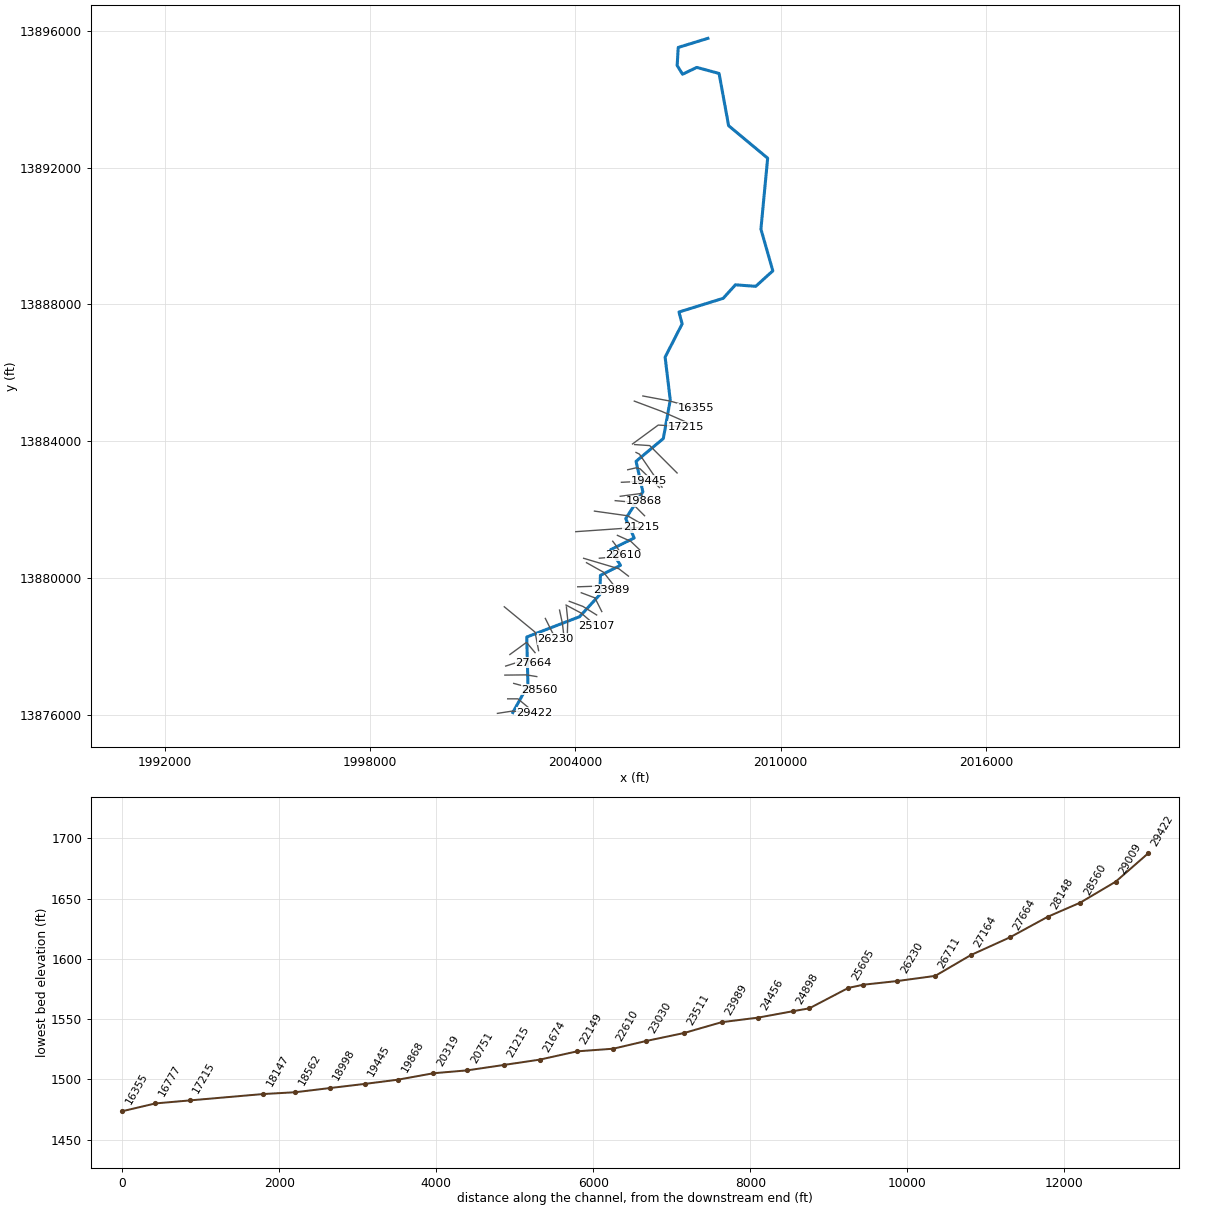
--- HOLLIDAY CREEK.prj (project) ---

Proj Title=HOLLIDAY CREEK Base Level Engineering
Current Plan=p01
Default Exp/Contr=0.3,0.1
English Units
Geom File=g01
Flow File=f01
Plan File=p01
Y Axis Title=Elevation
X Axis Title(PF)=Main Channel Distance
X Axis Title(XS)=Station
BEGIN DESCRIPTION:
HOLLIDAY CREEK
END DESCRIPTION:
DSS Export Rating Curves= 0
DSS Export Rating Curve Sorted= 0
DSS Export Volume Flow Curves= 0
DXF OffsetX= 0
DXF OffsetY= 0
DXF ScaleX= 1
DXF ScaleY= 10

--- HOLLIDAY CREEK.p01 (plan) ---

Plan Title=Multiple Run
Short Identifier=Multiple
Geom File=g01
Flow File=f01
Subcritical Flow
K Sum by GR= 0
Std Step Tol= 0.01
Critical Tol= 0.01
Num of Std Step Trials= 20
Max Error Tol= 0.3
Flow Tol Ratio= 0.001
Split Flow NTrial= 30
Split Flow Tol= 0.02
Split Flow Ratio= 0.02
Log Output Level= 0
Friction Slope Method= 1
Unsteady Friction Slope Method= 2
Unsteady Bridges Friction Slope Method= 1
Parabolic Critical Depth
Global Vel Dist=  1 , 1 , 1
Global Log Level= 0
CheckData=True
Encroach Param= -1, 0, 0, 0
BEGIN DESCRIPTION:
Multiple Run
END DESCRIPTION:

--- HOLLIDAY CREEK.f01 (steady flow) ---

Flow Title=Multiple
Program Version=4.10
Number of Profiles= 7
Profile Names=10-year,25-year,50-year,1pct_min,100-year,1pct_plu,500-year
River Rch & RM=HOLLIDAY CREEK,Reach-1         ,29422
     513     843    1149     763    1523    3039    2640
River Rch & RM=HOLLIDAY CREEK,Reach-1         ,26711
    1083    1869    2632    1800    3591    7165    6611
River Rch & RM=HOLLIDAY CREEK,Reach-1         ,25107
    2148    3807    5454    3778    7537   15039   14264
River Rch & RM=HOLLIDAY CREEK,Reach-1         ,19445
    2642    4723    6802    4734    9445   18845   18044
River Rch & RM=HOLLIDAY CREEK,Reach-1         ,16777
    2929    5264    7609    5312   10599   21148   20383
River Rch & RM=HOLLIDAY CREEK,Reach-1         ,16355
    3254    5870    8507    5952   11876   23696   22942
River Rch & RM=HOLLIDAY CREEK,Reach-1         ,14530
    3454    6245    9063    6349   12668   25276   24530
River Rch & RM=HOLLIDAY CREEK,Reach-1         ,13500
    3655    6615    9606    6732   13432   26799   26029
River Rch & RM=HOLLIDAY CREEK,Reach-1         ,10427
    4718    8610   12571    8849   17657   35230   34527
River Rch & RM=HOLLIDAY CREEK,Reach-1         ,5024
    4997    9131   13344    9399   18754   37418   36718
River Rch & RM=HOLLIDAY CREEK,Reach-1         ,1326
    5299    9697   14185   10000   19952   39809   39128
Boundary for River Rch & Prof#=HOLLIDAY CREEK,Reach-1         , 1
Up Type= 0
Dn Type= 3
Dn Slope=0.005
Boundary for River Rch & Prof#=HOLLIDAY CREEK,Reach-1         , 2
Up Type= 0
Dn Type= 3
Dn Slope=0.005
Boundary for River Rch & Prof#=HOLLIDAY CREEK,Reach-1         , 3
Up Type= 0
Dn Type= 3
Dn Slope=0.005
Boundary for River Rch & Prof#=HOLLIDAY CREEK,Reach-1         , 4
Up Type= 0
Dn Type= 3
Dn Slope=0.005
Boundary for River Rch & Prof#=HOLLIDAY CREEK,Reach-1         , 5
Up Type= 0
Dn Type= 3
Dn Slope=0.005
Boundary for River Rch & Prof#=HOLLIDAY CREEK,Reach-1         , 6
Up Type= 0
Dn Type= 3
Dn Slope=0.005
Boundary for River Rch & Prof#=HOLLIDAY CREEK,Reach-1         , 7
Up Type= 0
Dn Type= 3
Dn Slope=0.005
DSS Import GetInterval= 0
DSS Import GetPeak= 0
DSS Import FillOption= 0

--- HOLLIDAY CREEK.g01 (geometry) ---

Geom Title=Existing Conditions
Program Version=4.10

River Reach=HOLLIDAY CREEK  ,Reach-1
Reach XY= 30
        2002175.       13876075.      2002617.17      13876871.6
      2002582.43     13878281.35        2004125.       13878875.
      2004719.48     13879522.56      2004735.46     13880084.82
      2005321.69     13880376.73      2005036.08     13880835.05
      2005721.48     13881176.46      2005474.26     13881740.04
        2005975.       13882525.      2005776.22      13883414.5
      2006572.94     13884080.85       2006775.4     13885206.65
       2006625.5     13886459.79      2007122.83     13887430.97
      2007030.35      13887777.5      2008323.45     13888178.75
      2008680.85     13888572.94      2009273.45     13888528.75
      2009772.76     13888980.93      2009424.76     13890199.92
      2009621.55     13892273.75      2008480.46     13893222.55
       2008202.2     13894748.97      2007549.88     13894925.54
      2007134.58      13894726.2      2006977.17     13894980.97
      2007008.21     13895508.56        2007875.       13895775.

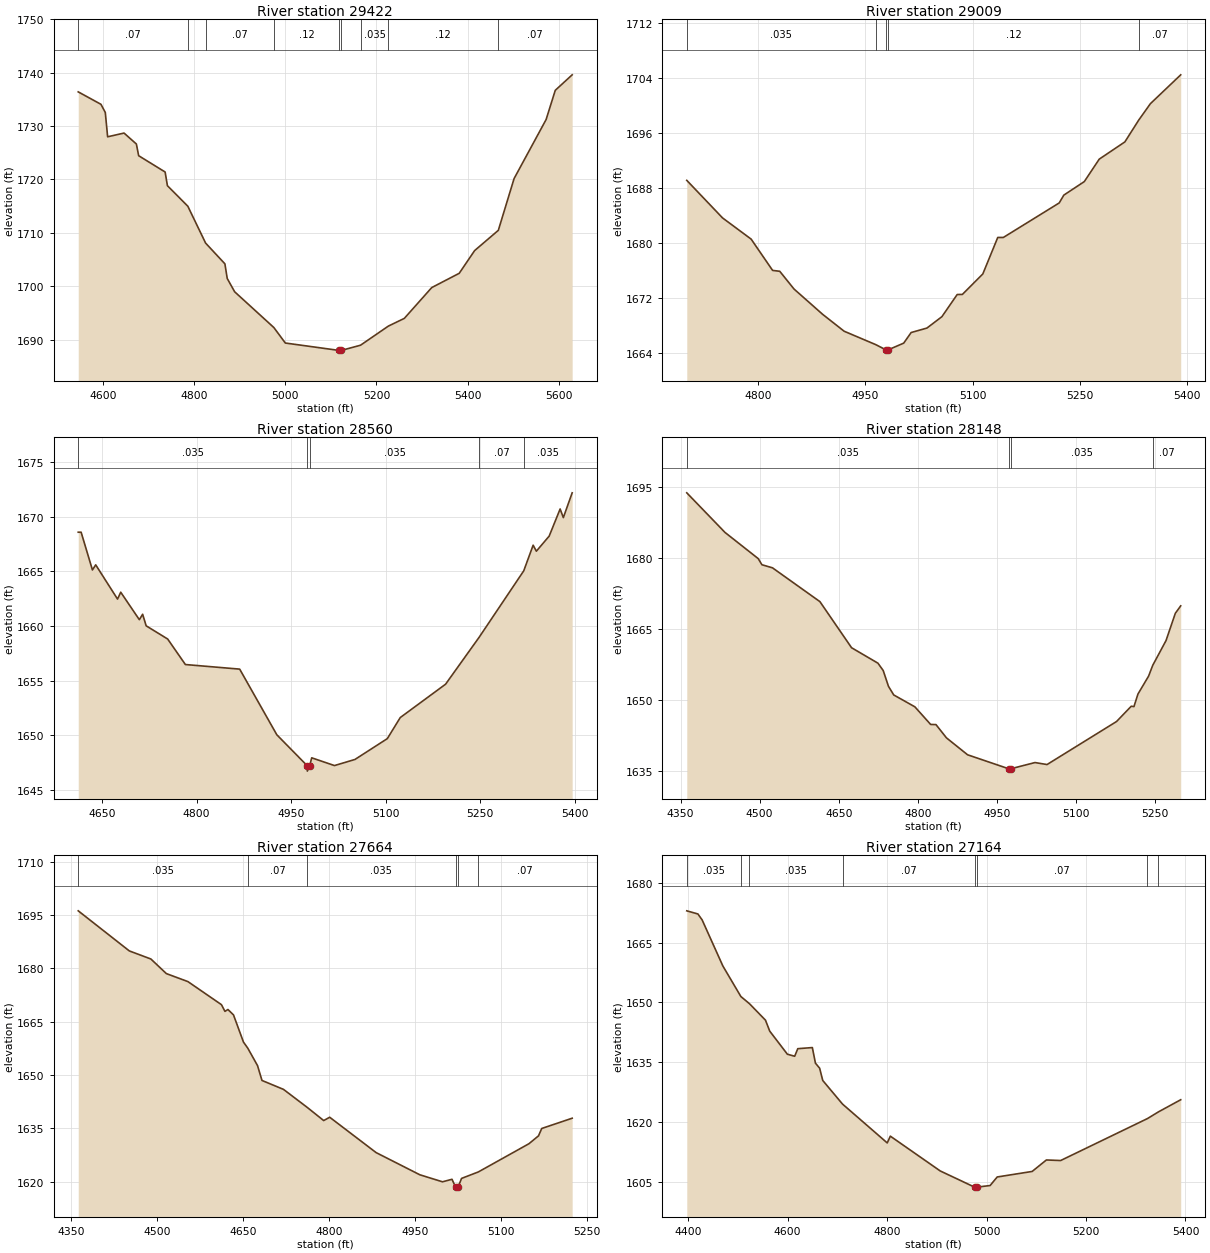
Type RM Length L Ch R = 1 ,29422   ,413,413,413
BEGIN DESCRIPTION:
HOLLIDAY CREEK 63.0
END DESCRIPTION:
XS GIS Cut Line= 3
      2001725.72     13876050.25      2002164.56     13876118.04
      2002801.94      13876060.7
#Sta/Elev= 30
  4545.5  1736.4  4595.4 1734.07  4604.9 1732.54    4610 1727.99    4646 1728.69
  4673.1 1726.64  4678.1 1724.45  4736.2  1721.4  4741.2 1718.84    4786    1715
    4825  1708.1  4867.4 1704.21  4872.5 1701.47  4888.8 1698.98  4974.8 1692.29
    5000 1689.39  5118.5    1688  5118.8  1687.5  5122.5    1688    5165 1688.98
  5226.1 1692.56  5261.1    1694  5321.3 1699.77  5381.6 1702.44  5415.4 1706.69
  5467.4 1710.48    5502 1720.17  5572.3 1731.22  5592.4 1736.69  5629.5 1739.59
#Mann= 9 ,-1 , 0
  4545.5     .07       0    4786    .035       0    4825     .07       0
  4974.8     .12       0  5118.5     .05       0  5122.5     .12       0
    5165    .035       0  5226.1     .12       0  5467.4     .07       0
Bank Sta=5118.5,5122.5
XS Rating Curve= 0 ,0
Exp/Cntr=0.3,0.1

Type RM Length L Ch R = 1 ,29009   ,449,449,449
BEGIN DESCRIPTION:
HOLLIDAY CREEK 62.0
END DESCRIPTION:
XS GIS Cut Line= 3
      2002024.96       13876475.        2002325.       13876475.
      2002625.03     13876224.97
#Sta/Elev= 30
  4700.3 1689.09  4750.3 1683.64  4790.3 1680.56  4820.3 1676.02  4830.3 1675.89
  4850.3 1673.31  4890.3 1669.64  4920.3 1667.19  4964.6 1665.24  4978.3 1664.51
  4978.6 1664.01  4982.1 1664.01  4982.3 1664.51  5003.6 1665.46    5014    1667
  5036.1 1667.65    5057  1669.3  5078.4 1672.52  5085.6 1672.53  5114.2  1675.5
  5135.1  1680.8  5142.9  1680.8    5221 1685.81  5227.5 1686.95  5256.1 1688.91
    5277 1692.17  5312.8 1694.67  5332.2 1697.84  5348.5 1700.22  5390.9 1704.41
#Mann= 5 ,-1 , 0
  4700.3    .035       0  4964.6     .12       0  4978.3     .05       0
  4982.3     .12       0  5332.2     .07       0
Bank Sta=4978.3,4982.3
XS Rating Curve= 0 ,0
Exp/Cntr=0.3,0.1

Type RM Length L Ch R = 1 ,28560   ,412,412,412
BEGIN DESCRIPTION:
HOLLIDAY CREEK 61.0
END DESCRIPTION:
XS GIS Cut Line= 3
      2002201.08     13876926.65        2002575.       13876825.
      2002960.61     13876736.18
#Sta/Elev= 30
  4612.4  1668.6    4617  1668.6  4634.9 1665.14  4640.1 1665.61  4674.7 1662.47
  4679.8  1663.1  4709.3 1660.58  4714.5 1661.08  4720.1 1660.02  4754.2 1658.81
  4782.3 1656.47  4868.4 1656.05  4927.3 1650.03  4975.4  1647.2  4975.7  1646.7
  4979.4  1647.2  4982.6 1647.92  5018.7 1647.21  5051.2 1647.77  5102.5 1649.68
    5123 1651.61  5194.9 1654.67  5248.2 1658.98  5318.8 1665.06  5333.7 1667.41
  5338.8 1666.86  5359.1 1668.24  5376.5 1670.73  5381.6 1669.94  5395.6 1672.21
#Mann= 5 ,-1 , 0
  4612.4    .035       0  4975.4    .035       0  4979.4    .035       0
  5248.2     .07       0  5318.8    .035       0
Bank Sta=4975.4,4979.4
XS Rating Curve= 0 ,0
Exp/Cntr=0.3,0.1

Type RM Length L Ch R = 1 ,28148   ,484,484,484
BEGIN DESCRIPTION:
HOLLIDAY CREEK 60.0
END DESCRIPTION:
XS GIS Cut Line= 3
       2001942.5     13877168.66        2002575.       13877175.
      2002875.03     13877124.99
#Sta/Elev= 30
  4361.9 1693.79  4434.4 1685.43  4497.4  1679.9  4504.4 1678.61  4524.4 1677.96
  4614.4 1670.82  4674.4 1661.09  4724.4 1657.83  4734.4 1656.28  4744.4 1652.94
  4754.4 1651.12  4794.4 1648.62  4824.4 1644.89  4834.4 1644.87  4854.4 1642.06
  4894.4 1638.49  4972.4 1635.54  4972.7 1635.04  4976.4 1635.54  5022.3 1636.85
  5045.1 1636.43  5176.9 1645.51  5204.8 1648.74  5209.9 1648.66  5217.5 1651.31
  5237.7  1655.1  5245.6 1657.39  5270.7 1662.59  5288.4 1668.36  5298.6 1669.93
#Mann= 4 ,-1 , 0
  4361.9    .035       0  4972.4    .035       0  4976.4    .035       0
  5245.6     .07       0
Bank Sta=4972.4,4976.4
XS Rating Curve= 0 ,0
Exp/Cntr=0.3,0.1

Type RM Length L Ch R = 1 ,27664   ,500,500,500
BEGIN DESCRIPTION:
HOLLIDAY CREEK 59.0
END DESCRIPTION:
XS GIS Cut Line= 3
      2001966.83     13877432.55        2002575.       13877625.
        2002775.       13877525.
#Sta/Elev= 30
  4362.1 1696.17  4451.2 1684.89  4488.8 1682.62  4515.8 1678.51  4553.4 1676.26
  4611.9 1669.77    4618 1667.88  4623.2 1668.41  4632.9 1666.89  4650.3 1659.24
  4657.8 1657.54  4674.8 1652.63  4682.6 1648.45  4720.1 1645.94  4761.2 1640.91
  4790.2 1637.17  4800.7  1638.1  4881.7 1628.15    4958 1621.91  4997.4 1619.94
    5014 1620.65  5020.4 1618.38  5020.6 1617.88  5024.4 1618.38  5030.7  1620.9
    5060 1622.72  5148.1 1630.64  5164.9 1632.87  5170.5 1634.94  5223.6 1637.83
#Mann= 6 ,-1 , 0
  4362.1    .035       0  4657.8     .07       0  4761.2    .035       0
  5020.4    .035       0  5024.4    .035       0    5060     .07       0
Bank Sta=5020.4,5024.4
XS Rating Curve= 0 ,0
Exp/Cntr=0.3,0.1

Type RM Length L Ch R = 1 ,27164   ,453,453,453
BEGIN DESCRIPTION:
HOLLIDAY CREEK 58.0
END DESCRIPTION:
XS GIS Cut Line= 3
      2002088.39     13877769.37        2002575.       13878125.
      2002824.98     13877825.02
#Sta/Elev= 30
  4397.3 1672.97  4419.7 1672.18  4428.2 1670.69  4469.9 1659.12  4506.1 1651.45
  4523.4 1649.65  4555.6 1645.51  4564.1 1642.77  4599.6 1636.97  4614.3 1636.46
  4620.5 1638.36  4649.8 1638.64    4656 1634.73  4664.5 1633.45  4670.7 1630.38
  4710.5 1624.45  4800.4  1614.7  4806.6  1616.4    4907 1607.66    4976  1603.6
  4976.3  1603.1    4980  1603.6  5007.2    1604  5021.5 1606.15  5091.8 1607.54
  5120.4 1610.42  5149.1 1610.28  5323.7 1620.82  5345.7 1622.49  5390.5 1625.54
#Mann= 8 ,-1 , 0
  4397.3    .035       0  4506.1     .07       0  4523.4    .035       0
  4710.5     .07       0    4976     .05       0    4980     .07       0
  5323.7     .12       0  5345.7     .07       0
Bank Sta=4976,4980
XS Rating Curve= 0 ,0
Exp/Cntr=0.3,0.1

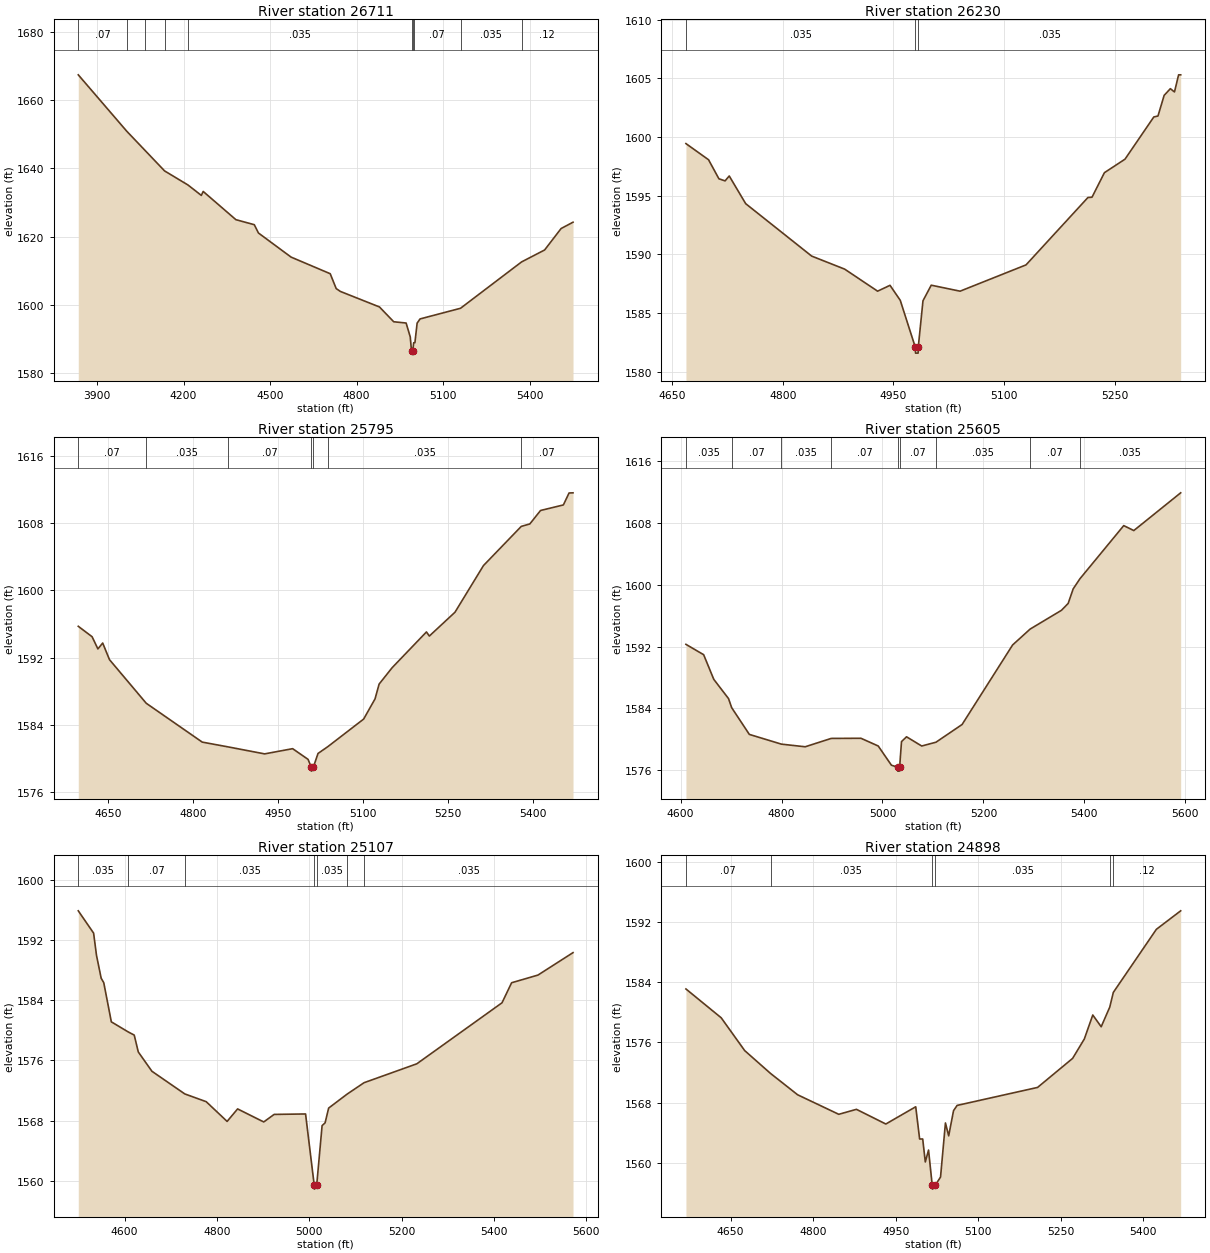
Type RM Length L Ch R = 1 ,26711   ,481,481,481
BEGIN DESCRIPTION:
HOLLIDAY CREEK 57.0
END DESCRIPTION:
XS GIS Cut Line= 3
      2001925.22     13879165.16        2002825.       13878425.
      2002928.65     13877883.94
#Sta/Elev= 30
  3834.9 1667.39  4003.2 1650.85  4066.2 1645.27  4134.2 1639.24  4215.3 1635.12
  4261.7 1632.06  4268.2 1633.22  4381.6 1624.95  4445.4 1623.48  4459.8 1621.05
  4573.1 1613.98  4708.7 1609.12  4729.5 1604.76  4743.9 1603.93  4879.5 1599.38
    4929 1595.04    4972 1594.67  4986.4 1590.59  4990.8 1586.35  4991.1 1585.85
  4994.8 1586.35  4998.3  1588.9  5002.5  1588.9  5010.2 1594.64  5020.4 1595.87
  5160.7 1598.99  5372.4 1612.57  5452.4 1616.07  5509.5 1622.35  5550.9 1624.21
#Mann= 10 ,-1 , 0
  3834.9     .07       0  4003.2     .12       0  4066.2    .035       0
  4134.2     .12       0  4215.3    .035       0  4990.8     .05       0
  4994.8    .035       0  4998.3     .07       0  5160.7    .035       0
  5372.4     .12       0
Bank Sta=4990.8,4994.8
XS Rating Curve= 0 ,0
Exp/Cntr=0.3,0.1

Type RM Length L Ch R = 1 ,26230   ,435,435,435
BEGIN DESCRIPTION:
HOLLIDAY CREEK 56.0
END DESCRIPTION:
XS GIS Cut Line= 3
      2003125.02     13878824.96        2003275.       13878525.
      2003425.01     13878224.98
#Sta/Elev= 30
  4668.8 1599.45  4699.5 1598.07  4713.5 1596.45  4721.9 1596.27  4727.5 1596.69
  4749.8 1594.33  4839.3 1589.86    4884 1588.75  4928.7 1586.87  4945.5 1587.37
  4959.4 1586.09  4979.8 1582.09  4980.1 1581.59  4983.6 1581.59  4983.8 1582.09
  4990.2 1586.05  5001.4 1587.38  5040.5 1586.87  5129.9 1589.11  5213.8 1594.85
  5219.4 1594.88  5236.2 1596.97  5264.1 1598.12  5303.2 1601.72  5308.8  1601.8
  5317.2 1603.56  5325.6 1604.13  5331.2 1603.85  5336.8 1605.31  5339.6 1605.31
#Mann= 3 ,-1 , 0
  4668.8    .035       0  4979.8    .035       0  4983.8    .035       0
Bank Sta=4979.8,4983.8
XS Rating Curve= 0 ,0
Exp/Cntr=0.3,0.1

Type RM Length L Ch R = 1 ,25795   ,190,190,190
BEGIN DESCRIPTION:
HOLLIDAY CREEK 55.0
END DESCRIPTION:
XS GIS Cut Line= 3
      2003540.23     13879068.82        2003625.       13878675.
      2003679.23     13878208.08
#Sta/Elev= 30
  4597.1 1595.74  4621.5  1594.5  4631.7 1593.05  4640.2 1593.75  4652.2 1591.77
    4717 1586.59  4815.8 1581.97  4860.8 1581.41  4925.9 1580.57  4975.3 1581.19
  5002.5 1579.92    5008 1579.02  5008.3 1578.52    5012 1579.02  5020.1 1580.62
  5037.6 1581.44  5100.6 1584.71  5120.7 1587.11  5127.9 1588.87  5150.9 1590.82
  5211.4 1595.07  5216.5 1594.58  5261.7 1597.41    5312 1602.96  5378.7 1607.62
  5393.8 1607.91  5412.7 1609.51    5453 1610.17    5463 1611.59    5470 1611.61
#Mann= 7 ,-1 , 0
  4597.1     .07       0    4717    .035       0  4860.8     .07       0
    5008     .05       0    5012     .07       0  5037.6    .035       0
  5378.7     .07       0
Bank Sta=5008,5012
XS Rating Curve= 0 ,0
Exp/Cntr=0.3,0.1

Type RM Length L Ch R = 1 ,25605   ,498,498,498
BEGIN DESCRIPTION:
HOLLIDAY CREEK 54.0
END DESCRIPTION:
XS GIS Cut Line= 3
       2003740.9      13879159.9      2003780.97     13878772.67
      2003762.78     13878182.25
#Sta/Elev= 30
  4610.7 1592.29  4645.8 1590.95  4665.9 1587.76  4695.1 1585.27  4701.3  1584.1
  4736.3 1580.64  4799.9 1579.38  4846.9 1579.04  4898.4 1580.12  4957.4 1580.14
  4991.6 1579.14  5017.7 1576.66    5030 1576.39  5030.3 1575.89  5033.8 1575.89
    5034 1576.39  5037.7 1579.71  5047.7 1580.33  5077.7 1579.14    5106 1579.63
  5157.7 1581.92  5257.8 1592.21  5292.6 1594.27  5354.5 1596.69  5367.8 1597.58
  5377.8 1599.47  5391.1 1600.77  5477.9 1607.65  5497.9 1607.01  5590.7 1611.89
#Mann= 9 ,-1 , 0
  4610.7    .035       0  4701.3     .07       0  4799.9    .035       0
  4898.4     .07       0    5030     .05       0    5034     .07       0
    5106    .035       0  5292.6     .07       0  5391.1    .035       0
Bank Sta=5030,5034
XS Rating Curve= 0 ,0
Exp/Cntr=0.3,0.1

Type RM Length L Ch R = 1 ,25107   ,209,209,209
BEGIN DESCRIPTION:
HOLLIDAY CREEK 53.5
END DESCRIPTION:
XS GIS Cut Line= 3
      2003730.22     13879215.36      2004172.28     13878980.67
      2004606.37     13878609.56
#Sta/Elev= 30
  4499.5 1595.87  4532.7 1592.91  4538.9 1589.98  4549.1 1586.92  4554.7 1586.33
  4571.1 1581.13  4607.7 1579.79  4620.7 1579.37  4629.5 1577.13    4659 1574.57
  4730.2 1571.56  4776.6 1570.53  4821.9 1567.91  4844.6 1569.57  4901.2 1567.84
  4923.8 1568.84  4991.8  1568.9  5010.6 1559.42    5011 1558.92  5015.9 1559.42
  5027.6 1567.35  5034.1 1567.72  5041.8 1569.68  5081.7 1571.53  5118.5 1573.05
  5232.8 1575.56  5417.3 1583.66  5438.1 1586.32  5495.2 1587.34  5571.1 1590.32
#Mann= 7 ,-1 , 0
  4499.5    .035       0  4607.7     .07       0  4730.2    .035       0
  5010.6    .035       0  5015.9    .035       0  5081.7     .07       0
  5118.5    .035       0
Bank Sta=5010.6,5015.9
XS Rating Curve= 0 ,0
Exp/Cntr=0.3,0.1

Type RM Length L Ch R = 1 ,24898   ,442,442,442
BEGIN DESCRIPTION:
HOLLIDAY CREEK 53.0
END DESCRIPTION:
XS GIS Cut Line= 3
      2003824.96     13879325.01        2004225.       13879175.
      2004624.97     13878925.02
#Sta/Elev= 30
  4568.9 1583.11    4633 1579.28  4675.7 1574.92  4722.6 1571.89  4771.9 1569.05
  4846.6 1566.46  4878.7 1567.12  4932.1 1565.17  4986.4 1567.46  4993.5 1563.18
  4999.1 1563.18  5003.8 1560.13  5009.7 1561.71  5016.4 1557.02  5016.9 1556.52
  5021.8 1557.02  5031.5 1558.13  5040.4 1565.31  5046.3  1563.6  5055.1 1566.94
  5061.6 1567.64  5207.8 1570.03  5271.5 1573.89  5292.7 1576.46  5308.1 1579.65
  5323.4 1578.09    5339 1580.71  5345.4 1582.65  5423.6 1591.03  5467.8 1593.49
#Mann= 6 ,-1 , 0
  4568.9     .07       0  4722.6    .035       0  5016.4    .035       0
  5021.8    .035       0    5339     .07       0  5345.4     .12       0
Bank Sta=5016.4,5021.8
XS Rating Curve= 0 ,0
Exp/Cntr=0.3,0.1

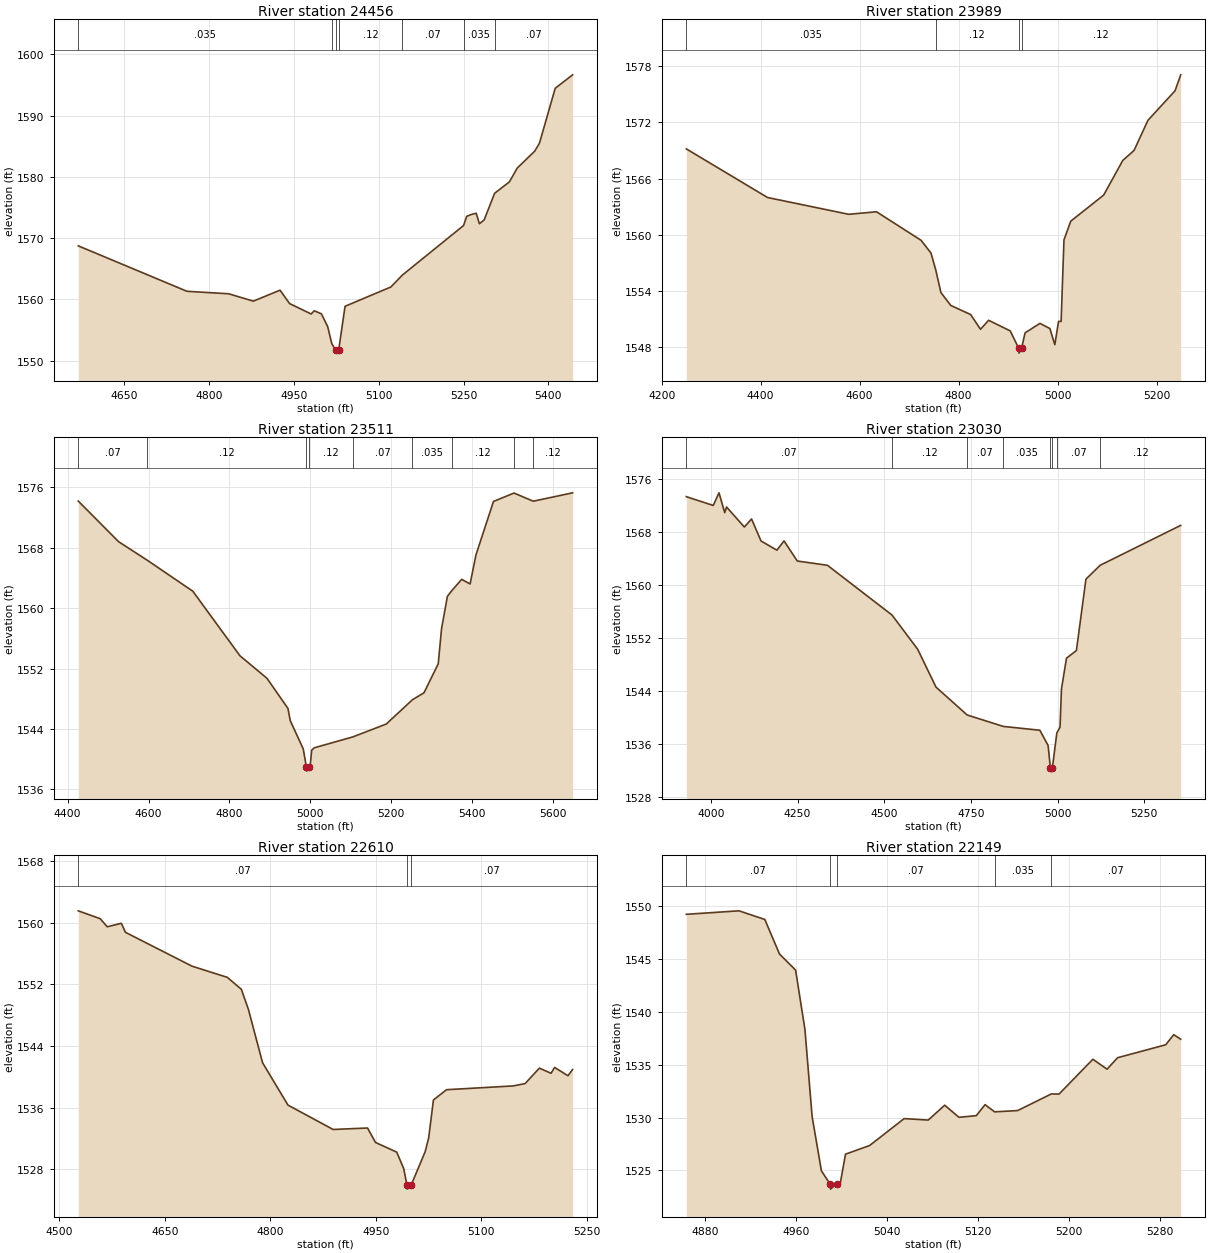
Type RM Length L Ch R = 1 ,24456   ,467,467,467
BEGIN DESCRIPTION:
HOLLIDAY CREEK 52.0
END DESCRIPTION:
XS GIS Cut Line= 3
      2004175.03     13879574.99        2004575.       13879425.
      2004775.01     13879024.98
#Sta/Elev= 30
  4568.5 1568.75  4760.7 1561.33  4834.6 1560.92  4878.2 1559.72  4925.4 1561.51
  4942.3 1559.32  4980.5 1557.62  4985.9 1558.15  4998.5 1557.65  5009.6 1555.58
  5016.9 1552.78  5023.7 1551.73  5024.1 1551.23  5029.1 1551.73  5040.4 1558.88
  5121.4 1562.03  5141.7 1563.97    5250 1572.07  5255.6 1573.58    5264 1573.88
  5272.4 1574.07    5278 1572.36  5286.4 1572.98  5304.9 1577.33  5331.1  1579.2
    5345 1581.46  5375.8 1584.21  5384.2 1585.51  5412.1 1594.48  5442.9 1596.68
#Mann= 7 ,-1 , 0
  4568.5    .035       0  5016.9     .12       0  5023.7    .035       0
  5029.1     .12       0  5141.7     .07       0    5250    .035       0
  5304.9     .07       0
Bank Sta=5023.7,5029.1
XS Rating Curve= 0 ,0
Exp/Cntr=0.3,0.1

Type RM Length L Ch R = 1 ,23989   ,478,478,478
BEGIN DESCRIPTION:
HOLLIDAY CREEK 51.0
END DESCRIPTION:
XS GIS Cut Line= 3
      2004070.99     13879748.52        2004825.       13879775.
       2005045.3     13879669.34
#Sta/Elev= 30
  4249.8 1569.16  4413.9 1563.98  4577.9 1562.19    4634 1562.46  4724.1 1559.42
  4744.1 1558.06  4753.8 1556.26  4764.1 1553.86  4784.1 1552.48  4824.2 1551.51
  4844.2 1549.94  4860.5  1550.9  4904.2 1549.77  4921.5  1547.9  4921.9  1547.4
    4927  1547.9  4934.2 1549.56  4964.3 1550.57  4984.3 1550.02  4994.3  1548.3
  5001.8 1550.78    5007 1550.78  5012.8 1559.47  5026.5 1561.46    5093 1564.24
  5131.6 1567.93  5154.3 1568.99  5182.5 1572.21  5237.2 1575.35  5248.6 1577.05
#Mann= 4 ,-1 , 0
  4249.8    .035       0  4753.8     .12       0  4921.5     .05       0
    4927     .12       0
Bank Sta=4921.5,4927
XS Rating Curve= 0 ,0
Exp/Cntr=0.3,0.1

Type RM Length L Ch R = 1 ,23511   ,481,481,481
BEGIN DESCRIPTION:
HOLLIDAY CREEK 50.0
END DESCRIPTION:
XS GIS Cut Line= 3
      2004327.98     13880453.37        2004825.       13880175.
      2005227.27     13879661.72
#Sta/Elev= 30
  4426.3  1574.2    4526 1568.82  4596.9 1566.36  4709.4 1562.26  4825.9 1553.71
  4892.8 1550.72  4944.6 1546.73  4950.3 1545.11  4982.3 1541.38  4990.3 1538.93
  4990.7 1538.43  4995.9 1538.93  4999.1 1538.93  5003.2  1541.2  5009.5 1541.52
  5104.8 1542.96  5187.6 1544.67  5252.1 1547.88  5280.7  1548.8    5316 1552.65
  5324.1 1557.28  5338.6 1561.58  5348.8 1562.29  5373.9 1563.83  5394.7 1563.22
  5409.1 1567.05  5452.5 1574.15  5503.3 1575.26  5550.7 1574.18  5648.1 1575.29
#Mann= 9 ,-1 , 0
  4426.3     .07       0  4596.9     .12       0  4990.3     .05       0
  4995.9     .12       0  5104.8     .07       0  5252.1    .035       0
  5348.8     .12       0  5503.3     .07       0  5550.7     .12       0
Bank Sta=4990.3,4995.9
XS Rating Curve= 0 ,0
Exp/Cntr=0.3,0.1

Type RM Length L Ch R = 1 ,23030   ,420,420,420
BEGIN DESCRIPTION:
HOLLIDAY CREEK 49.0
END DESCRIPTION:
XS GIS Cut Line= 3
      2004244.61     13880581.86        2005275.       13880275.
      2005553.62     13880061.05
#Sta/Elev= 30
    3929 1573.34  4006.6 1572.01  4023.3 1573.92  4039.8 1570.92    4045 1571.78
  4096.4 1568.75  4117.2 1569.97  4144.5 1566.64  4190.3 1565.25  4210.9 1566.65
  4249.2 1563.61  4336.3 1562.96  4522.5 1555.44  4596.6 1550.26  4649.4 1544.54
  4739.3 1540.33  4843.5  1538.6  4949.1 1538.02  4972.8 1535.72  4979.5 1532.34
  4979.9 1531.84  4985.2 1532.34    4998 1537.61  5007.3 1538.49  5011.4 1544.27
  5025.9 1548.92  5054.5 1550.07    5082 1560.87  5122.9 1562.96  5355.4    1569
#Mann= 8 ,-1 , 0
    3929     .07       0  4522.5     .12       0  4739.3     .07       0
  4843.5    .035       0  4979.5     .05       0  4985.2    .035       0
    4998     .07       0  5122.9     .12       0
Bank Sta=4979.5,4985.2
XS Rating Curve= 0 ,0
Exp/Cntr=0.3,0.1

Type RM Length L Ch R = 1 ,22610   ,461,461,461
BEGIN DESCRIPTION:
HOLLIDAY CREEK 48.0
END DESCRIPTION:
XS GIS Cut Line= 3
      2004703.92     13880584.13        2005175.       13880625.
      2005401.53     13880665.12
#Sta/Elev= 30
  4526.9 1561.52  4558.1  1560.5  4568.1 1559.45  4588.2  1559.9    4594 1558.73
  4688.6 1554.34  4738.8 1552.89  4758.8 1551.34  4768.9 1548.71    4789  1541.8
  4825.1 1536.31  4889.3 1533.15  4938.2 1533.34  4949.6 1531.46  4979.7 1530.21
  4989.7 1528.06  4994.3 1525.91  4994.8 1525.41  5000.1 1525.91  5020.1 1530.26
  5025.1 1532.04  5031.9 1536.98  5050.5 1538.31  5145.1  1538.8  5162.2  1539.1
  5182.5 1541.11  5199.1 1540.44  5204.2  1541.2  5223.2 1540.12  5229.8 1540.94
#Mann= 3 ,-1 , 0
  4526.9     .07       0  4994.3     .05       0  5000.1     .07       0
Bank Sta=4994.3,5000.1
XS Rating Curve= 0 ,0
Exp/Cntr=0.3,0.1

Type RM Length L Ch R = 1 ,22149   ,475,475,475
BEGIN DESCRIPTION:
HOLLIDAY CREEK 47.0
END DESCRIPTION:
XS GIS Cut Line= 3
      2005094.27     13881080.05        2005175.       13880975.
      2005337.71     13880719.85
#Sta/Elev= 30
  4863.5 1549.25  4909.9 1549.58  4932.6 1548.76  4945.5 1545.49  4959.7 1543.96
  4967.9 1538.34  4974.2  1530.1  4982.4 1524.95  4989.9 1523.72  4990.4 1523.22
  4995.7 1523.72  4998.9 1523.72  5003.6 1526.53  5024.8 1527.35  5055.2  1529.9
  5076.4 1529.76  5090.9 1531.17  5103.5 1530.02  5118.7 1530.18  5126.4 1531.22
  5134.9 1530.54  5155.1 1530.66  5184.8 1532.24  5191.5 1532.22  5221.3 1535.52
  5233.8 1534.58  5243.1 1535.67  5285.4 1536.89  5292.5 1537.85  5298.6 1537.42
#Mann= 5 ,-1 , 0
  4863.5     .07       0  4989.9     .05       0  4995.7     .07       0
  5134.9    .035       0  5184.8     .07       0
Bank Sta=4989.9,4995.7
XS Rating Curve= 0 ,0
Exp/Cntr=0.3,0.1

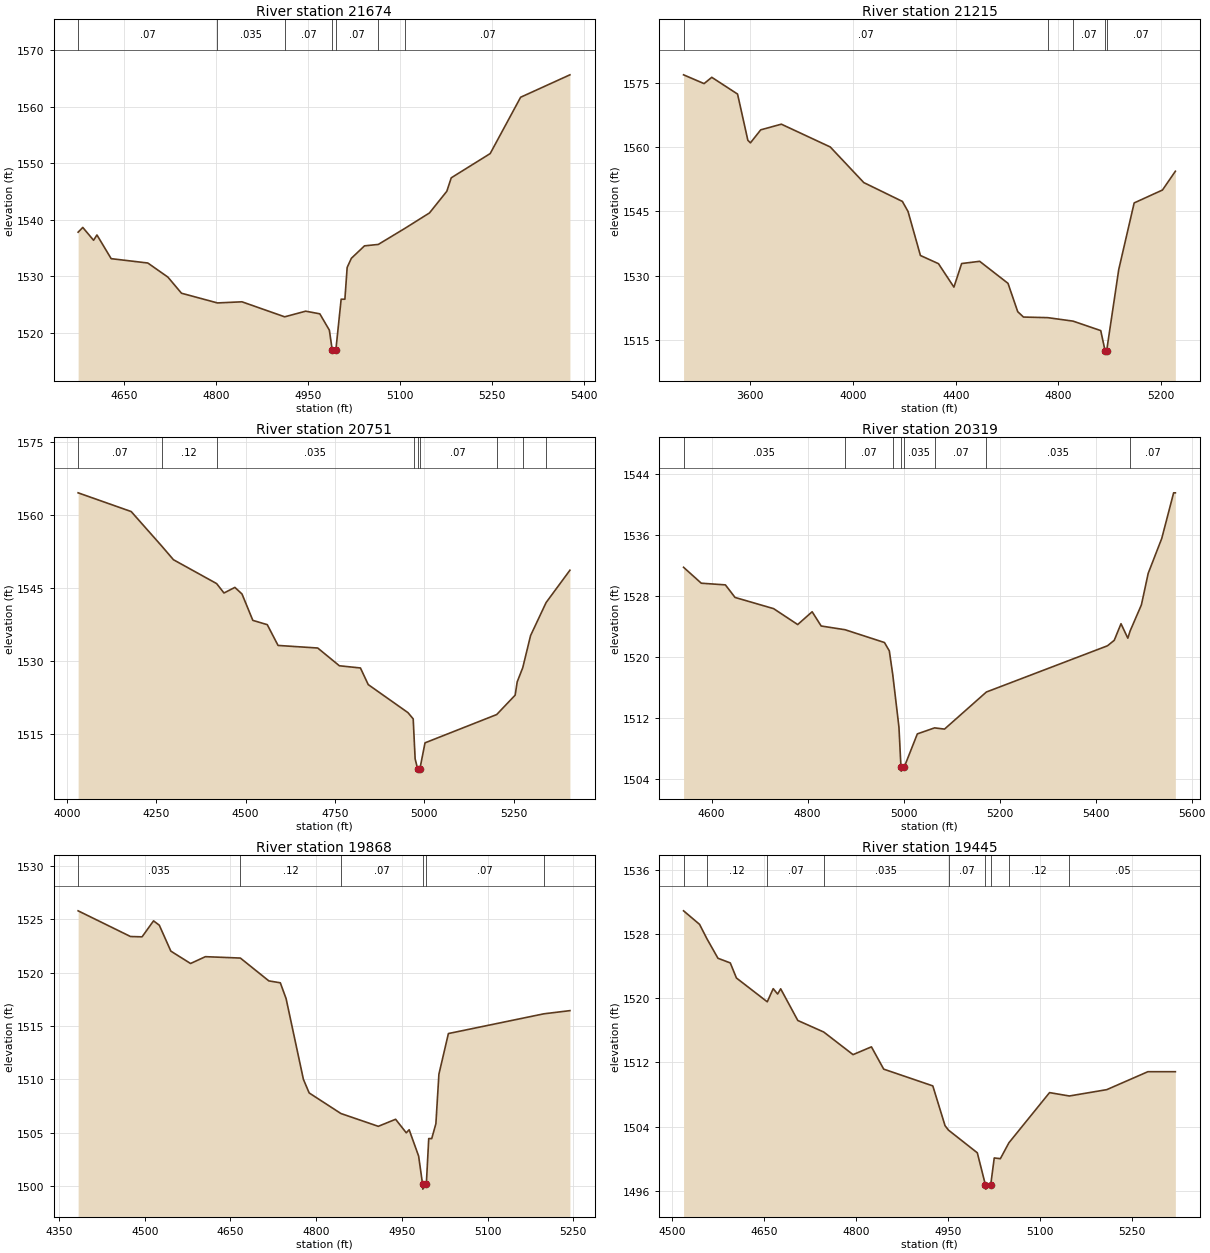
Type RM Length L Ch R = 1 ,21674   ,459,459,459
BEGIN DESCRIPTION:
HOLLIDAY CREEK 46.0
END DESCRIPTION:
XS GIS Cut Line= 3
      2005231.29     13881252.31        2005625.       13881075.
      2005893.07     13880819.24
#Sta/Elev= 30
  4574.5 1537.77  4582.1 1538.61  4599.7 1536.34  4605.2 1537.28  4628.4 1533.08
  4688.2 1532.31    4721 1529.81  4743.1 1526.96  4801.8 1525.24  4841.8 1525.44
  4911.5 1522.78  4945.7 1523.78  4968.8 1523.31  4984.4 1520.41  4989.1 1516.85
  4989.5 1516.35  4994.9 1516.85  5003.6  1525.9  5009.7  1525.9  5013.4 1531.53
  5020.3 1533.15  5041.7 1535.35  5064.2  1535.6  5107.5 1538.44  5147.7 1541.18
    5176 1545.02  5183.2  1547.4  5246.7 1551.69  5296.4 1561.67  5376.8 1565.64
#Mann= 7 ,-1 , 0
  4574.5     .07       0  4801.8    .035       0  4911.5     .07       0
  4989.1     .05       0  4994.9     .07       0  5064.2     .12       0
  5107.5     .07       0
Bank Sta=4989.1,4994.9
XS Rating Curve= 0 ,0
Exp/Cntr=0.3,0.1

Type RM Length L Ch R = 1 ,21215   ,464,464,464
BEGIN DESCRIPTION:
HOLLIDAY CREEK 45.0
END DESCRIPTION:
XS GIS Cut Line= 3
      2004015.44     13881359.63        2005675.       13881475.
      2005925.15     13881484.64
#Sta/Elev= 30
  3340.9 1576.87  3420.7 1574.82  3450.7 1576.29    3551 1572.38  3591.1 1561.59
  3601.1 1560.99  3641.2 1564.03  3721.4 1565.35  3911.8 1560.03  4042.2 1551.72
  4192.5 1547.32  4214.5 1544.97  4262.7  1534.7  4332.9 1532.79    4393 1527.32
  4423.1 1532.82  4493.2 1533.34  4603.5  1528.2  4641.3 1521.59  4663.6 1520.33
    4758 1520.19  4856.6 1519.38  4964.4 1517.17  4981.5 1512.41    4982 1511.91
  4987.3 1512.41  5034.5 1531.43  5094.5 1546.97  5204.6 1549.98  5254.8 1554.36
#Mann= 5 ,-1 , 0
  3340.9     .07       0    4758    .035       0  4856.6     .07       0
  4981.5     .05       0  4987.3     .07       0
Bank Sta=4981.5,4987.3
XS Rating Curve= 0 ,0
Exp/Cntr=0.3,0.1

Type RM Length L Ch R = 1 ,20751   ,432,432,432
BEGIN DESCRIPTION:
HOLLIDAY CREEK 44.0
END DESCRIPTION:
XS GIS Cut Line= 3
      2004560.58     13881960.33        2005525.       13881825.
      2005875.02     13881624.99
#Sta/Elev= 30
  4030.9 1564.51  4179.5 1560.67  4264.7 1553.62  4297.9 1550.79  4418.7  1545.9
  4439.3 1543.97  4469.8 1545.12  4489.8 1543.76  4520.1 1538.36  4560.5 1537.48
  4590.7 1533.22  4701.8 1532.69  4762.4 1529.05  4821.4  1528.6  4843.2 1525.19
  4954.3 1519.45  4969.1 1518.16  4970.8 1515.58  4974.5 1509.97  4981.3 1507.95
  4981.8 1507.45  4987.9 1507.95  5002.2 1513.25  5202.9 1519.05  5254.6 1523.03
  5260.3 1525.75  5275.8 1528.65  5297.7 1535.23  5341.2 1542.01  5407.9 1548.64
#Mann= 9 ,-1 , 0
  4030.9     .07       0  4264.7     .12       0  4418.7    .035       0
  4970.8     .07       0  4981.3     .05       0  4987.9     .07       0
  5202.9    .035       0  5275.8     .07       0  5341.2     .12       0
Bank Sta=4981.3,4987.9
XS Rating Curve= 0 ,0
Exp/Cntr=0.3,0.1

Type RM Length L Ch R = 1 ,20319   ,451,451,451
BEGIN DESCRIPTION:
HOLLIDAY CREEK 43.0
END DESCRIPTION:
XS GIS Cut Line= 3
      2005168.23     13882265.89        2005625.       13882225.
      2006025.01     13881824.99
#Sta/Elev= 30
  4541.8 1531.81  4578.7 1529.72  4628.9  1529.5    4649 1527.85  4729.3 1526.38
  4779.5 1524.29  4809.6 1525.97  4828.4  1524.1  4878.2 1523.61  4960.2 1521.93
  4970.3 1520.84  4977.4 1517.76  4990.4 1510.81  4994.6 1505.54  4995.1 1505.04
  5001.2 1505.54  5028.7 1509.93  5064.6 1510.72  5085.3 1510.56  5172.5 1515.43
  5424.7  1521.5  5438.8 1522.22  5452.9  1524.4  5467.1  1522.5  5471.9 1523.45
  5495.4 1526.88  5509.5 1531.01  5537.8 1535.61  5562.5 1541.59  5566.1 1541.59
#Mann= 8 ,-1 , 0
  4541.8    .035       0  4878.2     .07       0  4977.4    .035       0
  4994.6    .035       0  5001.2    .035       0  5064.6     .07       0
  5172.5    .035       0  5471.9     .07       0
Bank Sta=4994.6,5001.2
XS Rating Curve= 0 ,0
Exp/Cntr=0.3,0.1

Type RM Length L Ch R = 1 ,19868   ,423,423,423
BEGIN DESCRIPTION:
HOLLIDAY CREEK 42.0
END DESCRIPTION:
XS GIS Cut Line= 3
       2005314.1     13882394.36        2005925.       13882475.
       2006008.5     13882245.09
#Sta/Elev= 30
  4383.4 1525.81  4475.1  1523.4  4495.3 1523.37  4515.4 1524.87  4525.5 1524.46
  4545.7 1522.03  4580.2 1520.87  4606.2 1521.51  4667.4 1521.38  4717.2 1519.24
  4737.3 1519.06  4747.4 1517.58  4777.7 1510.01  4787.8 1508.73  4843.4  1506.8
  4908.8  1505.6  4939.1 1506.26  4957.8 1504.99  4962.8 1505.28  4979.4 1502.81
  4986.2 1500.21  4986.7 1499.71  4992.9 1500.21  4997.1 1504.45  5002.3 1504.45
  5009.6 1505.84  5014.9 1510.49  5031.5  1514.3  5198.5 1516.15  5244.2 1516.45
#Mann= 6 ,-1 , 0
  4383.4    .035       0  4667.4     .12       0  4843.4     .07       0
  4986.2     .05       0  4992.9     .07       0  5198.5    .035       0
Bank Sta=4986.2,4992.9
XS Rating Curve= 0 ,0
Exp/Cntr=0.3,0.1

Type RM Length L Ch R = 1 ,19445   ,447,447,447
BEGIN DESCRIPTION:
HOLLIDAY CREEK 41.0
END DESCRIPTION:
XS GIS Cut Line= 3
      2005348.92     13882802.73        2005825.       13882825.
      2006149.68     13882848.06
#Sta/Elev= 30
  4518.8 1530.92  4544.9 1529.23  4556.8 1527.45  4574.9    1525    4595 1524.42
    4605 1522.54  4655.3 1519.57    4665 1521.21  4672.2 1520.54  4677.2 1521.19
  4705.1 1517.24  4747.4  1515.8  4795.2 1512.98  4825.2 1513.95  4845.2 1511.17
  4925.3 1509.08  4945.3 1504.11  4950.9 1503.56  4997.9 1500.73  5011.2  1496.7
  5011.7  1496.2  5019.7  1496.7  5025.5 1500.09  5035.5    1500  5049.4 1501.98
  5115.7 1508.24    5148 1507.82    5209 1508.61  5276.1 1510.85  5320.9 1510.85
#Mann= 9 ,-1 , 0
  4518.8     .07       0  4556.8     .12       0  4655.3     .07       0
  4747.4    .035       0  4950.9     .07       0  5011.2     .05       0
  5019.7     .07       0  5049.4     .12       0    5148     .05       0
Bank Sta=5011.2,5019.7
XS Rating Curve= 0 ,0
Exp/Cntr=0.3,0.1

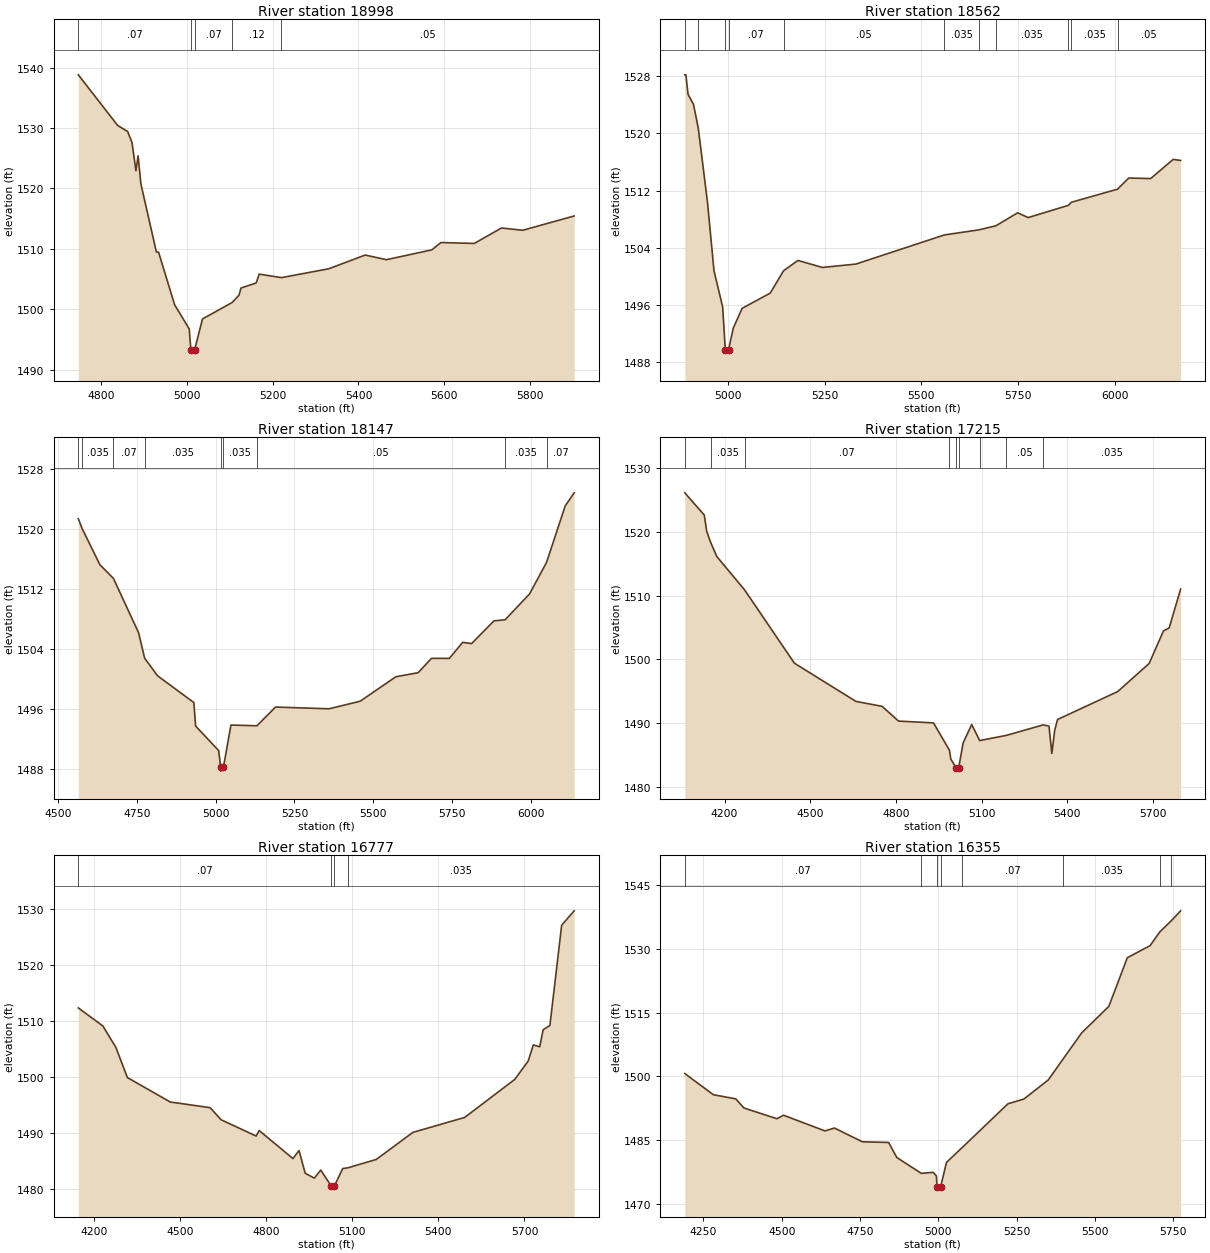
Type RM Length L Ch R = 1 ,18998   ,436,436,436
BEGIN DESCRIPTION:
HOLLIDAY CREEK 40.0
END DESCRIPTION:
XS GIS Cut Line= 4
      2005532.82     13883168.66        2005775.       13883225.
      2005893.93     13883196.44      2006458.76     13882648.93
#Sta/Elev= 30
    4746 1538.82  4837.8 1530.44  4861.2 1529.43  4871.4 1527.58  4880.4 1522.94
  4885.6  1525.4    4892 1520.79  4928.2 1509.49  4933.3 1509.46  4970.8 1500.75
  5004.9 1496.75  5008.8 1493.24  5009.3 1492.74  5017.4 1493.24  5035.8 1498.39
    5105 1501.12  5121.2 1502.34  5125.8 1503.52  5161.1 1504.35  5168.3 1505.82
  5220.3 1505.24  5330.8 1506.71  5415.7 1508.98  5465.4 1508.21  5571.3 1509.84
  5592.5 1511.05  5670.4  1510.9  5733.9 1513.46  5783.6 1513.08  5903.6 1515.45
#Mann= 5 ,-1 , 0
    4746     .07       0  5008.8     .05       0  5017.4     .07       0
    5105     .12       0  5220.3     .05       0
Bank Sta=5008.8,5017.4
XS Rating Curve= 0 ,0
Exp/Cntr=0.3,0.1

Type RM Length L Ch R = 1 ,18562   ,415,415,415
BEGIN DESCRIPTION:
HOLLIDAY CREEK 39.0
END DESCRIPTION:
XS GIS Cut Line= 3
      2005774.98     13883675.01        2005875.       13883625.
      2006535.72     13882659.09
#Sta/Elev= 30
  4888.2 1528.15    4891 1528.15  4896.6 1525.43  4910.6 1524.04    4923 1520.73
  4946.9 1510.35  4963.7 1500.81  4986.1 1495.74  4992.9  1489.8  4993.4  1489.3
  5001.5  1489.8  5013.5 1492.78  5036.4 1495.55  5109.1 1497.68  5143.8 1500.81
  5180.9 1502.24  5243.8 1501.26  5330.5 1501.73  5559.5  1505.8  5648.9 1506.51
  5692.7 1507.08    5749 1508.89    5776 1508.22  5880.1 1509.93  5887.9 1510.36
  6007.2 1512.19  6036.1 1513.74  6092.9 1513.67    6151 1516.34  6170.3  1516.2
#Mann= 11 ,-1 , 0
  4888.2    .035       0    4923     .07       0  4992.9     .05       0
  5001.5     .07       0  5143.8     .05       0  5559.5    .035       0
  5648.9     .05       0  5692.7    .035       0  5880.1     .05       0
  5887.9    .035       0  6007.2     .05       0
Bank Sta=4992.9,5001.5
XS Rating Curve= 0 ,0
Exp/Cntr=0.3,0.1

Type RM Length L Ch R = 1 ,18147   ,932,932,932
BEGIN DESCRIPTION:
HOLLIDAY CREEK 38.0
END DESCRIPTION:
XS GIS Cut Line= 3
      2005734.19     13883904.78        2006175.       13883875.
      2006975.01     13883074.99
#Sta/Elev= 30
  4564.4 1521.34  4576.8    1520  4632.8 1515.22  4675.8  1513.4  4755.6 1506.17
  4774.8 1502.79  4815.8 1500.45    4931 1496.89  4936.5 1493.77  5009.7  1490.5
  5016.1 1488.27  5016.6 1487.77  5024.7 1488.27  5048.6  1493.9    5131  1493.8
  5190.1 1496.29  5359.8 1496.06  5458.8 1497.07  5571.9 1500.32  5642.6 1500.86
    5685 1502.77  5741.6 1502.76    5784  1504.9  5812.3 1504.73    5883 1507.75
  5918.6  1507.9  5996.2 1511.34    6050 1515.53  6109.3 1523.05  6137.6 1524.78
#Mann= 9 ,-1 , 0
  4564.4     .07       0  4576.8    .035       0  4675.8     .07       0
  4774.8    .035       0  5016.1    .035       0  5024.7    .035       0
    5131     .05       0  5918.6    .035       0    6050     .07       0
Bank Sta=5016.1,5024.7
XS Rating Curve= 0 ,0
Exp/Cntr=0.3,0.1

Type RM Length L Ch R = 1 ,17215   ,438,438,438
BEGIN DESCRIPTION:
HOLLIDAY CREEK 37.0
END DESCRIPTION:
XS GIS Cut Line= 3
       2005671.7     13883922.13        2006425.       13884475.
      2007225.02       13884425.
#Sta/Elev= 30
  4060.9  1526.1  4129.1 1522.62  4137.5  1520.1    4151 1518.38    4173 1516.12
  4270.5 1510.88  4444.7  1499.4    4660 1493.42  4751.8 1492.64  4809.3 1490.33
  4931.6 1490.05  4987.5 1485.77  4992.2 1484.39    5011 1482.99  5011.5 1482.49
  5019.8 1482.99  5035.4 1486.91  5065.5  1489.8  5093.4 1487.28  5186.7 1488.09
  5315.3 1489.73    5336 1489.55    5346 1485.26    5356 1488.87    5366 1490.58
  5576.4 1494.95  5686.7 1499.36  5736.8 1504.46  5756.8 1504.93  5796.9 1511.02
#Mann= 9 ,-1 , 0
  4060.9     .07       0    4151    .035       0  4270.5     .07       0
  4987.5     .05       0    5011     .05       0  5019.8     .05       0
  5093.4     .07       0  5186.7     .05       0  5315.3    .035       0
Bank Sta=5011,5019.8
XS Rating Curve= 0 ,0
Exp/Cntr=0.3,0.1

Type RM Length L Ch R = 1 ,16777   ,422,422,422
BEGIN DESCRIPTION:
HOLLIDAY CREEK 36.0
END DESCRIPTION:
XS GIS Cut Line= 3
      2005724.97     13885175.01        2006525.       13884875.
      2007324.95     13884525.02
#Sta/Elev= 30
  4145.6 1512.36  4231.1 1509.13  4276.5  1505.3  4316.5 1499.92    4466 1495.55
  4604.9 1494.54  4643.1 1492.38  4765.1 1489.47  4775.8 1490.45  4893.2 1485.45
  4914.6 1486.89    4936 1482.83    4968 1481.95  4990.2  1483.4  5027.4 1480.49
  5027.9 1479.99  5037.3 1480.49  5066.7 1483.66  5086.5 1483.82  5183.6 1485.29
  5311.5 1490.13  5491.6 1492.79  5666.3 1499.59    5713 1502.86    5731 1505.75
  5753.2 1505.42  5765.3 1508.47  5788.7 1509.22  5829.6 1527.12  5873.2  1529.7
#Mann= 4 ,-1 , 0
  4145.6     .07       0  5027.4     .05       0  5037.3     .07       0
  5086.5    .035       0
Bank Sta=5027.4,5037.3
XS Rating Curve= 0 ,0
Exp/Cntr=0.3,0.1

Type RM Length L Ch R = 1 ,16355   ,430,430,430
BEGIN DESCRIPTION:
HOLLIDAY CREEK 35.0
END DESCRIPTION:
XS GIS Cut Line= 3
      2005975.03     13885324.99        2006775.       13885175.
      2007515.46      13884963.8
#Sta/Elev= 30
  4190.3 1500.67  4281.8 1495.69  4353.1 1494.73  4379.3 1492.58  4484.5 1490.06
  4505.7 1490.88  4637.9  1487.2  4668.5 1487.87  4757.5 1484.64  4841.4 1484.48
  4867.7 1480.94  4945.9 1477.22  4983.9 1477.47    4994 1476.61  4996.1 1474.02
  4996.6 1473.52  5007.3 1474.02  5026.3 1479.81  5075.7 1483.24  5222.6 1493.57
  5273.5 1494.68  5351.6 1499.18  5399.8  1504.2  5458.2 1510.23  5544.9 1516.46
    5604 1527.89  5676.8 1530.73  5707.3 1533.91  5744.7 1536.59  5774.2  1538.9
#Mann= 8 ,-1 , 0
  4190.3     .07       0  4945.9     .12       0  4996.1     .05       0
  5007.3     .12       0  5075.7     .07       0  5399.8    .035       0
  5707.3     .07       0  5744.7    .035       0
Bank Sta=4996.1,5007.3
XS Rating Curve= 0 ,0
Exp/Cntr=0.3,0.1