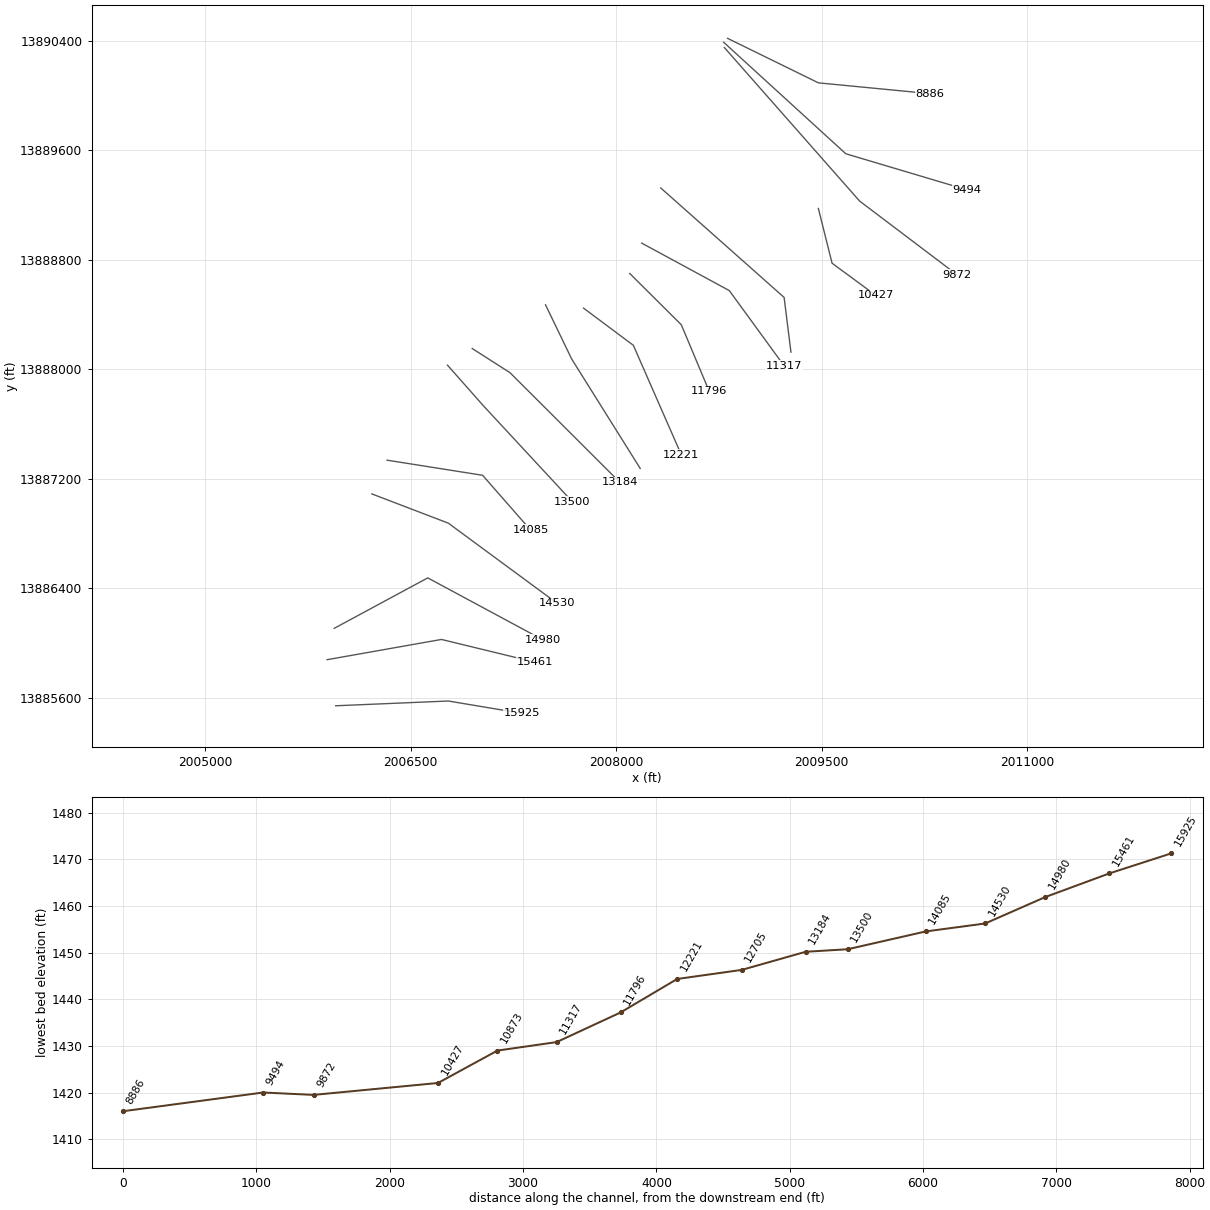
HEC-RAS study HOLLIDAY CREEK.prj: HOLLIDAY CREEK Base Level Engineering

--- HOLLIDAY CREEK.g01 (geometry) --- (continued)

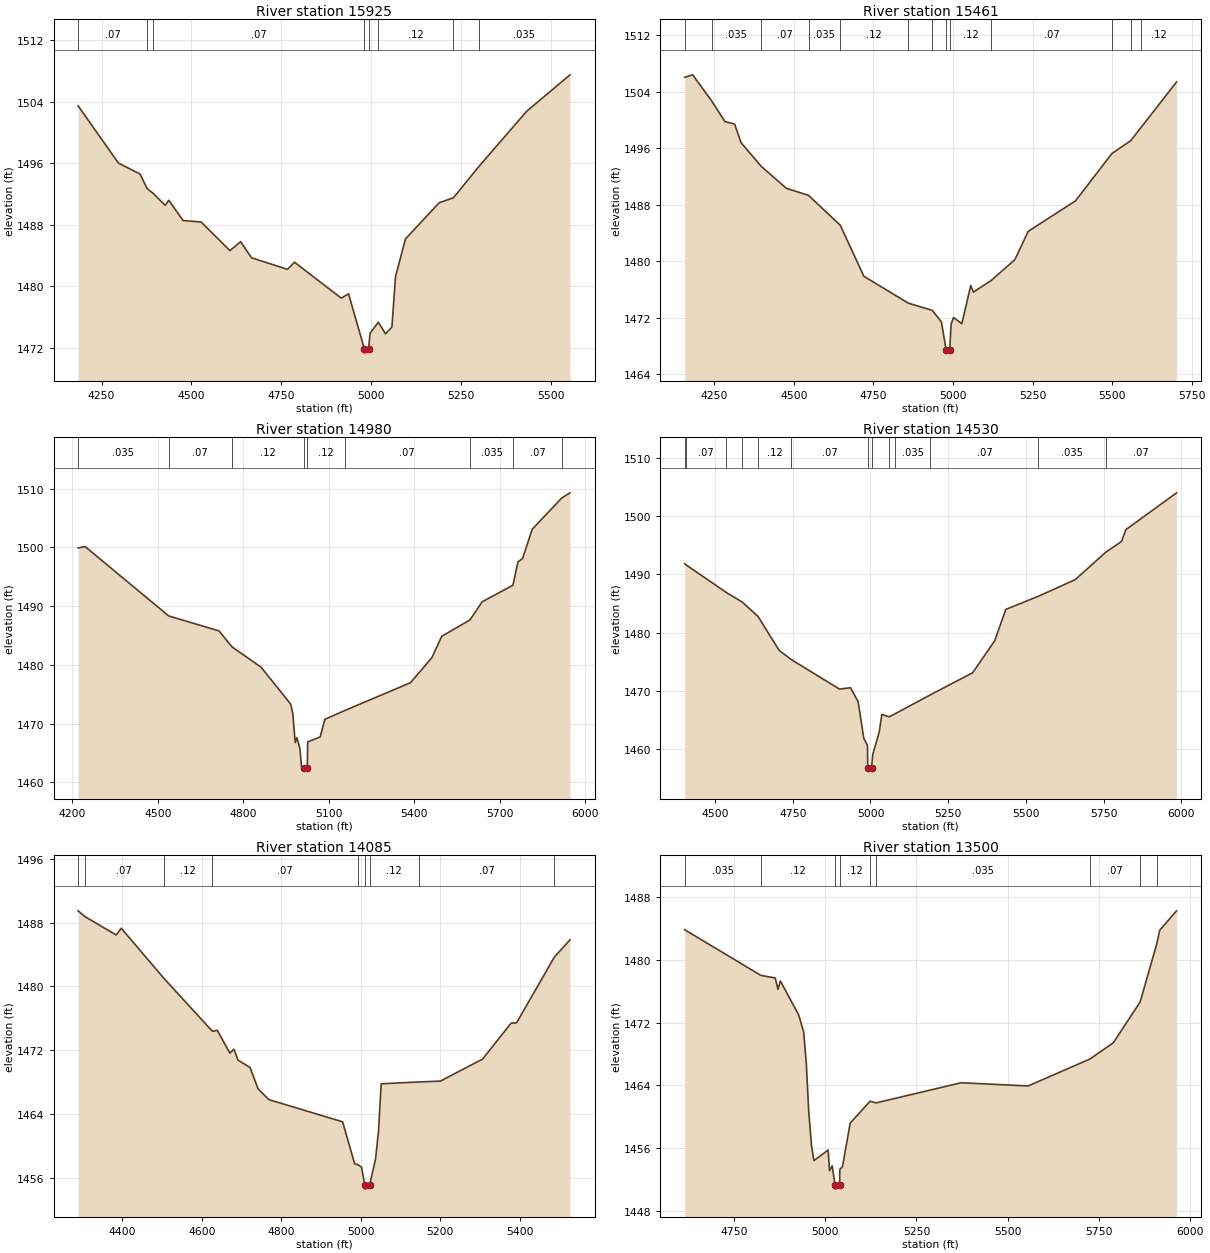
Type RM Length L Ch R = 1 ,15925   ,464,464,464
BEGIN DESCRIPTION:
HOLLIDAY CREEK 34.0
END DESCRIPTION:
XS GIS Cut Line= 3
      2005952.91     13885540.19        2006775.       13885575.
      2007314.06     13885484.64
#Sta/Elev= 30
  4184.8 1503.45    4297    1496    4357 1494.58  4376.8 1492.69  4393.4 1492.07
  4427.1 1490.51  4437.1 1491.16  4477.1 1488.52  4527.2 1488.33  4607.3 1484.61
  4637.3 1485.77  4667.3 1483.68  4767.4 1482.17  4787.4 1483.09  4917.5 1478.42
  4937.6 1478.99    4982 1471.77  4982.5 1471.27  4993.2 1471.77  4997.6 1473.86
  5020.7  1475.3  5040.5 1473.78  5058.3 1474.65  5068.5 1481.25  5096.1 1486.13
  5190.1 1490.84  5229.6 1491.48  5299.5  1495.5  5433.5 1502.74  5554.2 1507.48
#Mann= 8 ,-1 , 0
  4184.8     .07       0  4376.8    .035       0  4393.4     .07       0
    4982     .05       0  4993.2     .07       0  5020.7     .12       0
  5229.6     .07       0  5299.5    .035       0
Bank Sta=4982,4993.2
XS Rating Curve= 0 ,0
Exp/Cntr=0.3,0.1

Type RM Length L Ch R = 1 ,15461   ,481,481,481
BEGIN DESCRIPTION:
HOLLIDAY CREEK 33.0
END DESCRIPTION:
XS GIS Cut Line= 3
      2005890.46       13885877.        2006725.       13886025.
      2007403.62     13885859.81
#Sta/Elev= 30
  4156.7 1506.03  4181.6 1506.38  4241.1 1502.71  4283.2 1499.76  4313.6 1499.41
    4334 1496.77  4397.5 1493.41  4476.1 1490.32    4546 1489.31  4645.6 1485.09
  4719.9 1477.86  4859.8 1474.05  4935.1 1473.03  4963.6  1471.4  4978.2 1467.48
  4978.7 1466.98  4989.6 1467.48  4994.1 1471.07  5001.7 1472.03  5027.7 1471.14
  5055.7 1476.55  5064.3 1475.62  5120.1 1477.27  5194.6 1480.22  5236.3 1484.22
  5385.1 1488.54  5499.5 1495.24  5559.1 1497.08  5589.5 1498.84  5702.7 1505.37
#Mann= 13 ,-1 , 0
  4156.7     .07       0  4241.1    .035       0  4397.5     .07       0
    4546    .035       0  4645.6     .12       0  4859.8     .07       0
  4935.1     .12       0  4978.2     .05       0  4989.6     .12       0
  5120.1     .07       0  5499.5    .035       0  5559.1     .07       0
  5589.5     .12       0
Bank Sta=4978.2,4989.6
XS Rating Curve= 0 ,0
Exp/Cntr=0.3,0.1

Type RM Length L Ch R = 1 ,14980   ,450,450,450
BEGIN DESCRIPTION:
HOLLIDAY CREEK 32.0
END DESCRIPTION:
XS GIS Cut Line= 3
       2005942.5     13886106.14        2006625.       13886475.
      2007461.67     13886023.75
#Sta/Elev= 30
  4220.1 1499.89  4244.6 1500.12    4538 1488.32  4714.7 1485.77  4759.8 1483.07
  4862.2  1479.6  4965.9 1473.33  4973.2 1471.83  4982.1 1466.76  4987.8 1467.61
  4998.7 1465.71    5004 1462.63  5012.9 1462.41  5013.4 1461.91  5024.3 1462.41
  5025.9 1466.88  5069.7 1467.73  5085.9 1470.72    5155  1472.2  5386.7 1476.96
  5461.7 1481.22  5496.2 1484.85  5595.6 1487.65  5638.1 1490.72  5746.2 1493.55
  5763.8 1497.53  5779.9 1498.08  5813.9 1503.08  5917.7  1508.4  5946.5 1509.27
#Mann= 9 ,-1 , 0
  4220.1    .035       0    4538     .07       0  4759.8     .12       0
  5012.9     .05       0  5024.3     .12       0    5155     .07       0
  5595.6    .035       0  5746.2     .07       0  5917.7     .12       0
Bank Sta=5012.9,5024.3
XS Rating Curve= 0 ,0
Exp/Cntr=0.3,0.1

Type RM Length L Ch R = 1 ,14530   ,445,445,445
BEGIN DESCRIPTION:
HOLLIDAY CREEK 31.0
END DESCRIPTION:
XS GIS Cut Line= 3
       2006216.8     13887088.82        2006775.       13886875.
      2007567.54     13886290.19
#Sta/Elev= 30
  4402.3 1491.79  4406.1 1491.63  4536.6 1486.86  4587.9 1485.22  4638.8 1482.73
    4706 1476.96  4745.7 1475.36  4900.3 1470.32  4935.8 1470.55  4960.3 1468.17
  4978.6 1461.87  4990.4 1460.66  4991.4 1456.76  4991.9 1456.26  5003.4 1456.76
  5007.4 1459.12  5028.2 1462.96  5036.6 1465.98  5060.2 1465.57  5077.6 1466.04
  5192.6 1469.33  5328.9 1473.12  5399.9 1478.61  5435.4 1483.97  5540.6 1486.23
  5658.7 1489.07  5756.6 1493.75  5807.9 1495.62  5821.7 1497.64    5985 1503.95
#Mann= 13 ,-1 , 0
  4402.3     .12       0  4406.1     .07       0  4536.6    .035       0
  4587.9     .07       0  4638.8     .12       0  4745.7     .07       0
  4991.4     .05       0  5003.4     .07       0  5060.2     .12       0
  5077.6    .035       0  5192.6     .07       0  5540.6    .035       0
  5756.6     .07       0
Bank Sta=4991.4,5003.4
XS Rating Curve= 0 ,0
Exp/Cntr=0.3,0.1

Type RM Length L Ch R = 1 ,14085   ,585,585,585
BEGIN DESCRIPTION:
HOLLIDAY CREEK 30.0
END DESCRIPTION:
XS GIS Cut Line= 3
      2006327.95     13887335.33        2007025.       13887225.
      2007374.97     13886825.03
#Sta/Elev= 30
    4289 1489.49  4305.7 1488.78  4384.6 1486.46  4397.4 1487.31  4504.5 1481.03
  4626.8 1474.37  4639.1 1474.49  4670.7 1471.63  4680.9 1472.13    4691 1470.76
  4721.4 1469.83  4741.6 1467.15  4768.9 1465.79  4954.2 1463.01  4984.6 1457.73
  4991.8 1457.65  5001.8 1457.33    5010 1455.06  5010.5 1454.56  5022.1 1455.06
    5037 1458.33  5044.6 1461.89  5051.2 1467.78  5145.4 1468.01  5200.2 1468.12
  5306.5 1470.89  5377.7 1475.38  5391.9 1475.44  5486.9 1483.69  5526.2 1485.85
#Mann= 9 ,-1 , 0
    4289    .035       0  4305.7     .07       0  4504.5     .12       0
  4626.8     .07       0  4991.8     .12       0    5010     .05       0
  5022.1     .12       0  5145.4     .07       0  5486.9     .12       0
Bank Sta=5010,5022.1
XS Rating Curve= 0 ,0
Exp/Cntr=0.3,0.1

Type RM Length L Ch R = 1 ,13500   ,316,316,316
BEGIN DESCRIPTION:
HOLLIDAY CREEK 29.0
END DESCRIPTION:
XS GIS Cut Line= 3
       2006768.9     13888029.81      2007029.35     13887734.64
      2007678.62     13887033.28
#Sta/Elev= 30
  4614.1 1483.84  4823.3 1478.01  4862.4 1477.69    4870 1476.24  4876.6  1477.3
  4926.9 1472.97  4940.6 1470.77  4947.8 1466.69  4954.4 1460.68    4962 1456.27
  4968.7 1454.39  5007.7 1455.74  5011.4  1453.1  5018.7 1453.72  5026.7 1451.25
  5027.2 1450.75  5039.1 1451.25  5039.7 1453.25  5047.1 1453.64  5068.1 1459.17
  5122.5 1461.96  5139.1 1461.75  5372.5 1464.32  5556.3 1463.91  5726.3 1467.36
  5789.8 1469.41  5863.5 1474.62    5909 1482.02  5917.4 1483.79  5963.5 1486.25
#Mann= 9 ,-1 , 0
  4614.1    .035       0  4823.3     .12       0  5026.7     .05       0
  5039.1     .12       0  5122.5     .07       0  5139.1    .035       0
  5726.3     .07       0  5863.5    .035       0    5909     .12       0
Bank Sta=5026.7,5039.1
XS Rating Curve= 0 ,0
Exp/Cntr=0.3,0.1

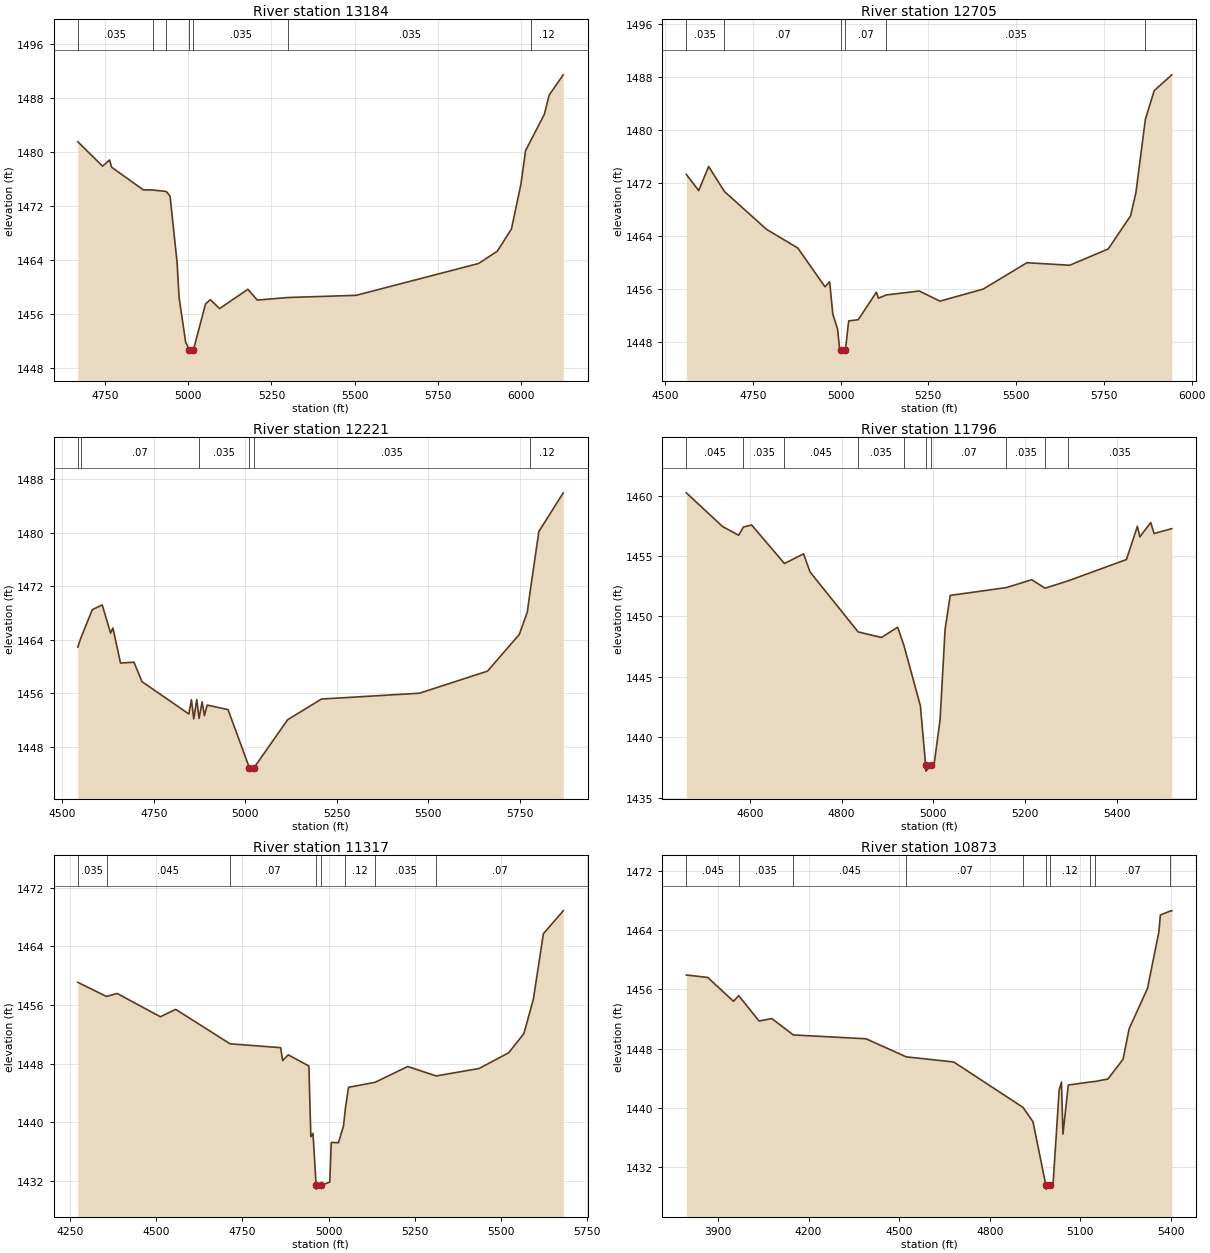
Type RM Length L Ch R = 1 ,13184   ,479,479,479
BEGIN DESCRIPTION:
HOLLIDAY CREEK 28.0
END DESCRIPTION:
XS GIS Cut Line= 3
      2006949.45     13888151.32        2007225.       13887975.
        2008025.       13887175.
#Sta/Elev= 30
  4668.1 1481.55  4742.4 1477.93  4763.5 1478.84  4769.7 1477.77  4864.6 1474.42
  4893.1 1474.39  4933.9 1474.17  4945.3 1473.47  4966.5  1463.6  4972.4 1458.44
  4992.3  1451.8  5003.1  1450.7  5003.6  1450.2  5015.6  1450.7  5051.8 1457.48
  5065.9 1458.13  5094.2 1456.81  5179.1 1459.67  5207.4 1458.07  5300.3 1458.45
  5504.3 1458.77    5872 1463.49  5928.6 1465.32    5971 1468.62  5999.3 1475.21
  6013.5 1480.24  6030.4 1481.85    6070 1485.64  6084.2 1488.46  6126.6 1491.47
#Mann= 7 ,-1 , 0
  4668.1    .035       0  4893.1     .07       0  4933.9    .035       0
  5003.1    .035       0  5015.6    .035       0  5300.3    .035       0
  6030.4     .12       0
Bank Sta=5003.1,5015.6
XS Rating Curve= 0 ,0
Exp/Cntr=0.3,0.1

Type RM Length L Ch R = 1 ,12705   ,484,484,484
BEGIN DESCRIPTION:
HOLLIDAY CREEK 27.0
END DESCRIPTION:
XS GIS Cut Line= 3
      2007484.21     13888470.74        2007675.       13888075.
      2008174.98     13887275.03
#Sta/Elev= 30
  4560.7  1473.3  4595.9 1470.86  4624.1  1474.5  4669.1 1470.73  4789.1 1465.01
  4878.4 1462.18  4955.6 1456.33  4968.9 1457.09  4977.8 1452.23  4991.5 1449.93
  4997.3 1446.86  5001.4 1446.82  5001.9 1446.32  5013.9 1446.82    5023 1451.19
  5050.2 1451.36    5102 1455.52  5107.9 1454.62  5130.5 1455.11  5224.1  1455.7
  5283.1 1454.17  5406.3 1455.99  5530.7 1459.97  5652.7 1459.59  5762.4 1462.05
  5826.1 1467.06  5841.4 1470.61  5868.1 1481.61  5893.3 1485.95  5943.4 1488.34
#Mann= 6 ,-1 , 0
  4560.7    .035       0  4669.1     .07       0  5001.4     .05       0
  5013.9     .07       0  5130.5    .035       0  5868.1     .12       0
Bank Sta=5001.4,5013.9
XS Rating Curve= 0 ,0
Exp/Cntr=0.3,0.1

Type RM Length L Ch R = 1 ,12221   ,425,425,425
BEGIN DESCRIPTION:
HOLLIDAY CREEK 26.0
END DESCRIPTION:
XS GIS Cut Line= 3
      2007761.97     13888446.46        2008125.       13888175.
      2008474.99     13887375.01
#Sta/Elev= 30
  4542.6  1462.9  4550.5 1464.22  4582.2 1468.51  4609.3 1469.21  4632.2    1465
  4638.5 1465.77  4659.3 1460.53  4696.2 1460.65  4717.7 1457.76  4846.1 1452.92
  4853.1 1455.05  4859.4 1452.19  4867.7 1455.07    4874 1452.26  4882.3 1454.73
  4888.6 1452.66    4896 1454.25  4953.2 1453.57  5011.4 1444.88  5011.9 1444.38
    5024 1444.88    5116 1452.06  5208.4 1455.15  5476.2 1456.02  5662.1 1459.32
    5749  1464.8  5770.9 1468.15  5779.6 1471.59  5802.5 1480.18  5869.1 1485.96
#Mann= 6 ,-1 , 0
  4542.6    .035       0  4550.5     .07       0    4874    .035       0
  5011.4    .035       0    5024    .035       0  5779.6     .12       0
Bank Sta=5011.4,5024
XS Rating Curve= 0 ,0
Exp/Cntr=0.3,0.1

Type RM Length L Ch R = 1 ,11796   ,479,479,479
BEGIN DESCRIPTION:
HOLLIDAY CREEK 25.0
END DESCRIPTION:
XS GIS Cut Line= 3
      2008098.78     13888699.93        2008475.       13888325.
      2008678.39     13887839.42
#Sta/Elev= 30
  4461.9 1460.23  4540.5 1457.45  4575.8 1456.72  4586.2  1457.4  4604.1 1457.57
  4675.6 1454.38  4717.3 1455.18  4731.4 1453.68  4836.2 1448.72    4887 1448.26
  4922.3 1449.11    4936 1447.59  4971.8  1442.6  4983.2  1437.7  4983.7  1437.2
  4995.9  1437.7  5002.2 1437.91  5014.7 1441.46  5025.6 1448.94  5036.8 1451.74
  5159.2 1452.39  5214.2 1453.04  5243.4 1452.34  5293.2 1452.94  5420.7 1454.71
  5444.5 1457.46  5449.9 1456.59  5473.7 1457.77  5480.9 1456.86  5519.5 1457.27
#Mann= 10 ,-1 , 0
  4461.9    .045       0  4586.2    .035       0  4675.6    .045       0
  4836.2    .035       0    4936     .07       0  4983.2     .05       0
  4995.9     .07       0  5159.2    .035       0  5243.4     .07       0
  5293.2    .035       0
Bank Sta=4983.2,4995.9
XS Rating Curve= 0 ,0
Exp/Cntr=0.3,0.1

Type RM Length L Ch R = 1 ,11317   ,444,444,444
BEGIN DESCRIPTION:
HOLLIDAY CREEK 24.0
END DESCRIPTION:
XS GIS Cut Line= 3
      2008185.64     13888922.11        2008825.       13888575.
      2009225.01     13888024.99
#Sta/Elev= 30
  4272.7 1459.09  4355.9 1457.16  4386.7 1457.57  4512.1 1454.39  4556.4  1455.4
  4714.1  1450.7    4861 1450.17  4866.7 1448.41  4882.8 1449.19  4942.7 1447.67
  4948.4 1438.01  4954.7 1438.46  4963.8 1431.36  4964.3 1430.86  4976.8 1431.36
  5003.3 1431.82  5007.6 1437.24  5028.4 1437.19  5043.1 1439.49  5048.7 1441.92
  5057.8 1444.76  5134.7 1445.44  5229.3  1447.6  5311.9 1446.31  5436.5 1447.33
  5522.2 1449.48  5566.3  1452.1  5593.7 1456.79  5622.7 1465.72  5680.3 1468.85
#Mann= 8 ,-1 , 0
  4272.7    .035       0  4355.9    .045       0  4714.1     .07       0
  4963.8     .05       0  4976.8     .07       0  5048.7     .12       0
  5134.7    .035       0  5311.9     .07       0
Bank Sta=4963.8,4976.8
XS Rating Curve= 0 ,0
Exp/Cntr=0.3,0.1

Type RM Length L Ch R = 1 ,10873   ,446,446,446
BEGIN DESCRIPTION:
HOLLIDAY CREEK 23.0
END DESCRIPTION:
XS GIS Cut Line= 3
      2008324.99     13889325.01        2009225.       13888525.
        2009275.     13888124.99
#Sta/Elev= 30
  3795.5 1457.94  3866.2 1457.61  3951.5 1454.39  3968.9 1455.15  4036.3 1451.73
  4078.6 1452.06  4149.7 1449.85  4390.5 1449.33  4523.7 1446.89  4680.7  1446.2
    4910 1440.08  4943.2 1438.14    4986 1429.54  4986.5 1429.04  4999.1 1429.54
  5009.8 1429.82  5029.9  1442.4  5037.5 1443.49  5042.5 1436.47  5060.1 1443.09
  5132.5  1443.5  5148.7 1443.57  5191.2  1443.9  5241.5 1446.57  5261.7  1450.7
  5322.2 1456.11    5360 1463.74    5365 1466.04  5398.2 1466.58  5402.8  1466.6
#Mann= 10 ,-1 , 0
  3795.5    .045       0  3968.9    .035       0  4149.7    .045       0
  4523.7     .07       0    4910     .12       0    4986     .05       0
  4999.1     .12       0  5132.5    .035       0  5148.7     .07       0
  5398.2    .035       0
Bank Sta=4986,4999.1
XS Rating Curve= 0 ,0
Exp/Cntr=0.3,0.1

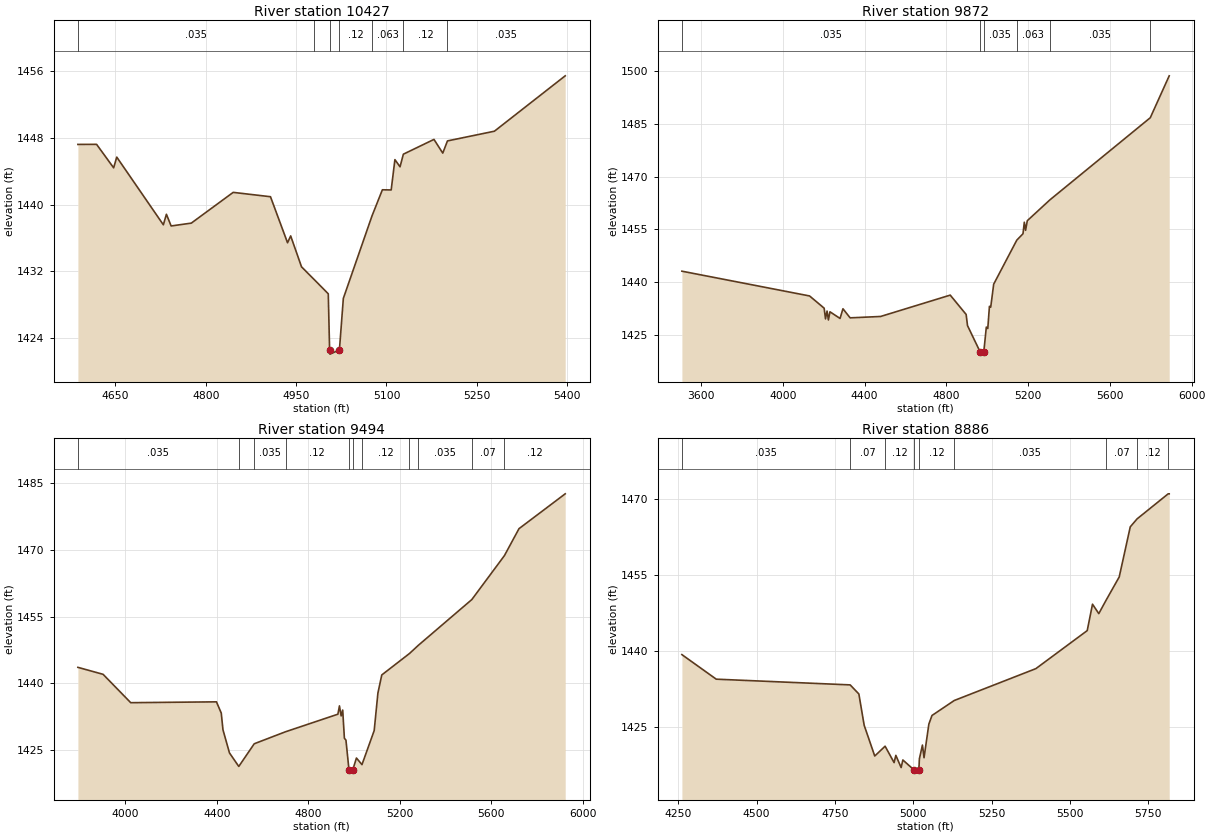
Type RM Length L Ch R = 1 ,10427   ,933,933,933
BEGIN DESCRIPTION:
HOLLIDAY CREEK 22.0
END DESCRIPTION:
XS GIS Cut Line= 3
      2009474.99     13889175.04        2009575.       13888775.
      2009894.08     13888539.88
#Sta/Elev= 30
  4587.9  1447.2  4618.9 1447.21  4647.2  1444.4  4652.4 1445.68  4729.7 1437.58
  4734.8 1438.84  4742.6 1437.44  4776.1 1437.78  4845.6 1441.46  4907.5 1440.94
  4935.8 1435.43    4941 1436.25    4959 1432.55  4980.4    1431  5003.4 1429.32
  5005.6  1422.6  5006.1  1422.1  5021.9  1422.6  5028.4 1428.77  5075.9 1438.63
  5093.2 1441.77  5107.8 1441.75    5114 1445.38  5122.5 1444.52    5128 1446.03
  5178.8  1447.8  5193.4 1446.16  5201.2 1447.62  5279.1 1448.78  5396.6 1455.41
#Mann= 7 ,-1 , 0
  4587.9    .035       0  4980.4     .12       0  5005.6     .05       0
  5021.9     .12       0  5075.9    .063       0    5128     .12       0
  5201.2    .035       0
Bank Sta=5005.6,5021.9
XS Rating Curve= 0 ,0
Exp/Cntr=0.3,0.1

Type RM Length L Ch R = 1 ,9872    ,378,378,378
BEGIN DESCRIPTION:
HOLLIDAY CREEK 21.0
END DESCRIPTION:
XS GIS Cut Line= 3
       2008789.3     13890350.97      2009775.44     13889229.73
      2010484.77     13888691.85
#Sta/Elev= 30
  3506.8 1443.12  4131.3 1436.08  4202.5 1432.61  4209.1 1429.57  4216.7 1431.79
  4223.4 1429.26  4230.9 1431.58  4280.3 1429.69  4294.5 1432.44  4329.6 1429.86
  4478.6 1430.25  4819.2 1436.32    4897 1430.82  4903.7 1427.65  4966.6 1420.05
  4967.1 1419.55  4983.1 1420.05  4995.7 1427.23  5002.9 1426.84  5010.9 1433.13
  5017.2 1432.89  5031.7 1439.43  5144.8 1451.95  5175.1 1453.76  5181.5 1457.04
  5187.8 1454.75  5196.1 1457.47  5307.3 1463.42  5797.6 1486.73  5890.2 1498.64
#Mann= 6 ,-1 , 0
  3506.8    .035       0  4966.6    .035       0  4983.1    .035       0
  5144.8    .063       0  5307.3    .035       0  5797.6     .12       0
Bank Sta=4966.6,4983.1
XS Rating Curve= 0 ,0
Exp/Cntr=0.3,0.1

Type RM Length L Ch R = 1 ,9494    ,1051,1051,1051
BEGIN DESCRIPTION:
HOLLIDAY CREEK 20.0
END DESCRIPTION:
XS GIS Cut Line= 3
      2008783.94     13890389.93        2009675.       13889575.
      2010559.88     13889311.14
#Sta/Elev= 30
  3792.5 1443.63  3902.6 1442.06  4023.5 1435.68  4398.4 1435.87  4419.4 1433.34
  4426.8  1429.6  4455.2 1424.39    4496 1421.34  4563.6 1426.44  4700.4 1429.14
  4929.4 1433.09  4936.2 1434.96  4943.6 1432.71  4950.4 1434.02  4957.8 1427.68
  4964.6 1427.26  4977.9 1420.56  4978.4 1420.06  4994.4 1420.56  5010.5 1423.23
  5034.7 1421.75  5088.1  1429.4  5104.4 1437.85  5121.3 1441.92  5242.4 1446.74
  5281.5  1448.6  5515.1 1458.88  5657.6 1468.76  5721.3 1474.82  5923.4 1482.66
#Mann= 11 ,-1 , 0
  3792.5    .035       0    4496     .12       0  4563.6    .035       0
  4700.4     .12       0  4977.9     .05       0  4994.4     .12       0
  5034.7     .12       0  5242.4     .07       0  5281.5    .035       0
  5515.1     .07       0  5657.6     .12       0
Bank Sta=4977.9,4994.4
XS Rating Curve= 0 ,0
Exp/Cntr=0.3,0.1

Type RM Length L Ch R = 1 ,8886    ,316,316,316
BEGIN DESCRIPTION:
HOLLIDAY CREEK 19.0
END DESCRIPTION:
XS GIS Cut Line= 3
      2008812.39     13890418.68      2009475.45     13890093.27
      2010288.75     13890014.63
#Sta/Elev= 30
  4261.4 1439.26    4371 1434.41  4798.6 1433.28  4826.3 1431.49  4843.3  1425.3
    4877 1419.23  4910.1 1421.17  4938.8 1417.93  4944.4 1419.36  4961.3 1416.95
  4966.8 1418.45  5001.2 1416.55  5001.7 1416.05  5017.9 1416.55  5019.6 1418.69
  5029.3 1421.39  5034.4 1418.89  5049.8 1425.54  5059.8 1427.24  5130.9  1430.2
  5391.4 1436.49  5555.3    1444  5572.2 1449.22  5592.3 1447.36  5615.2 1449.96
  5657.5  1454.6  5692.8  1464.5  5714.5 1466.07  5813.8 1471.02  5817.1 1471.02
#Mann= 9 ,-1 , 0
  4261.4    .035       0  4798.6     .07       0  4910.1     .12       0
  5001.2     .05       0  5017.9     .12       0  5130.9    .035       0
  5615.2     .07       0  5714.5     .12       0  5813.8     .07       0
Bank Sta=5001.2,5017.9
XS Rating Curve= 0 ,0
Exp/Cntr=0.3,0.1