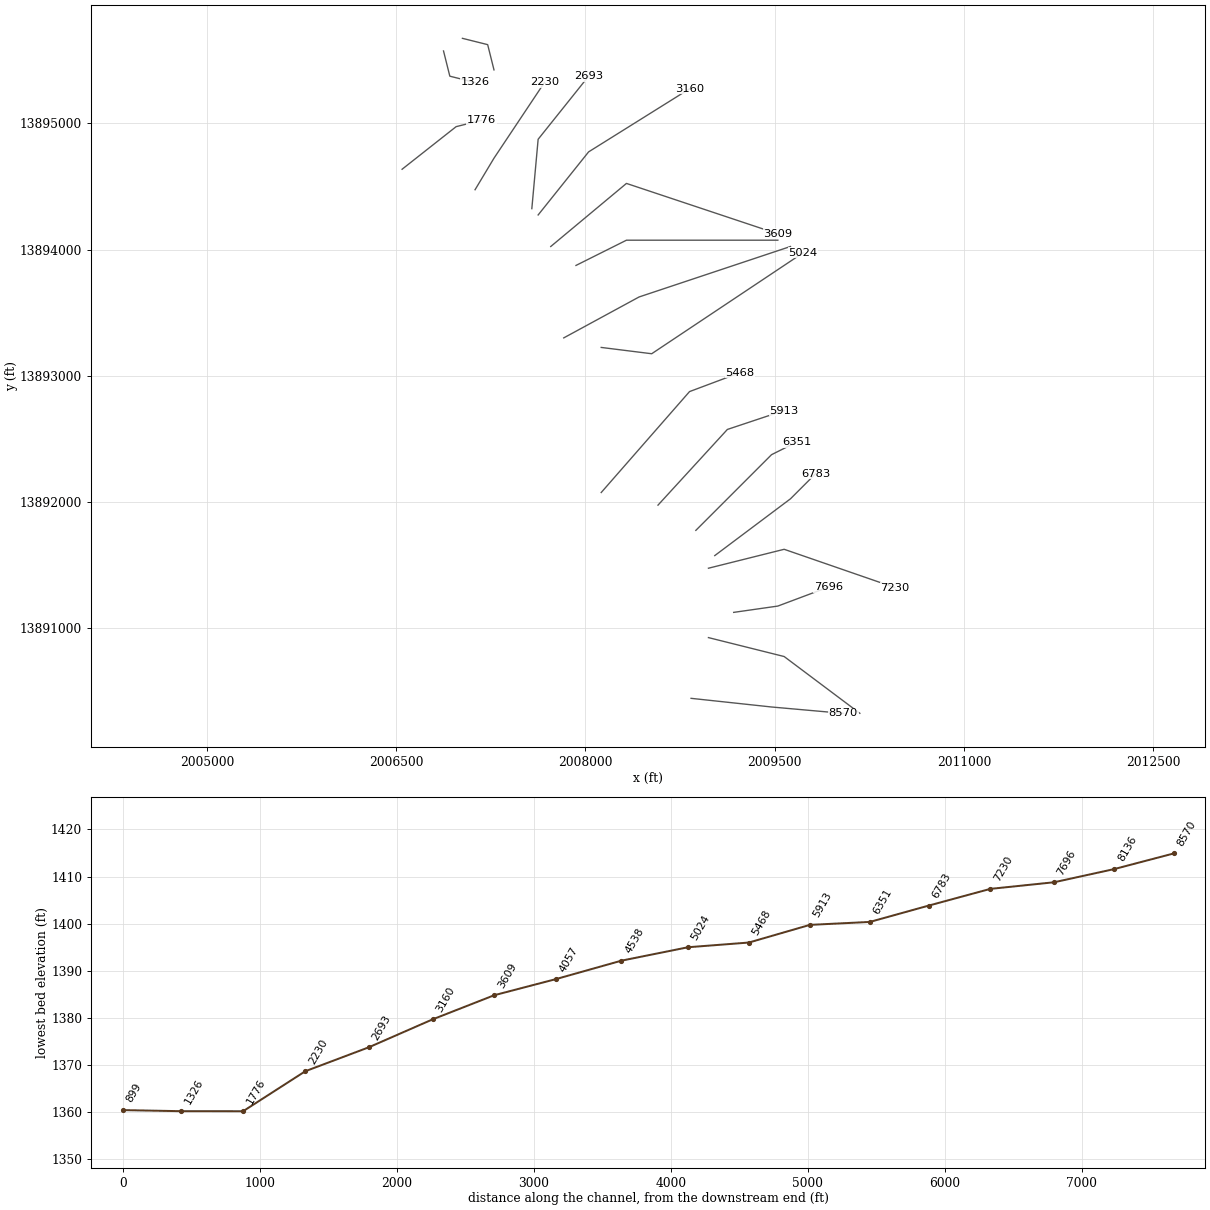
HEC-RAS study HOLLIDAY CREEK.prj: HOLLIDAY CREEK Base Level Engineering

--- HOLLIDAY CREEK.g01 (geometry) --- (continued)

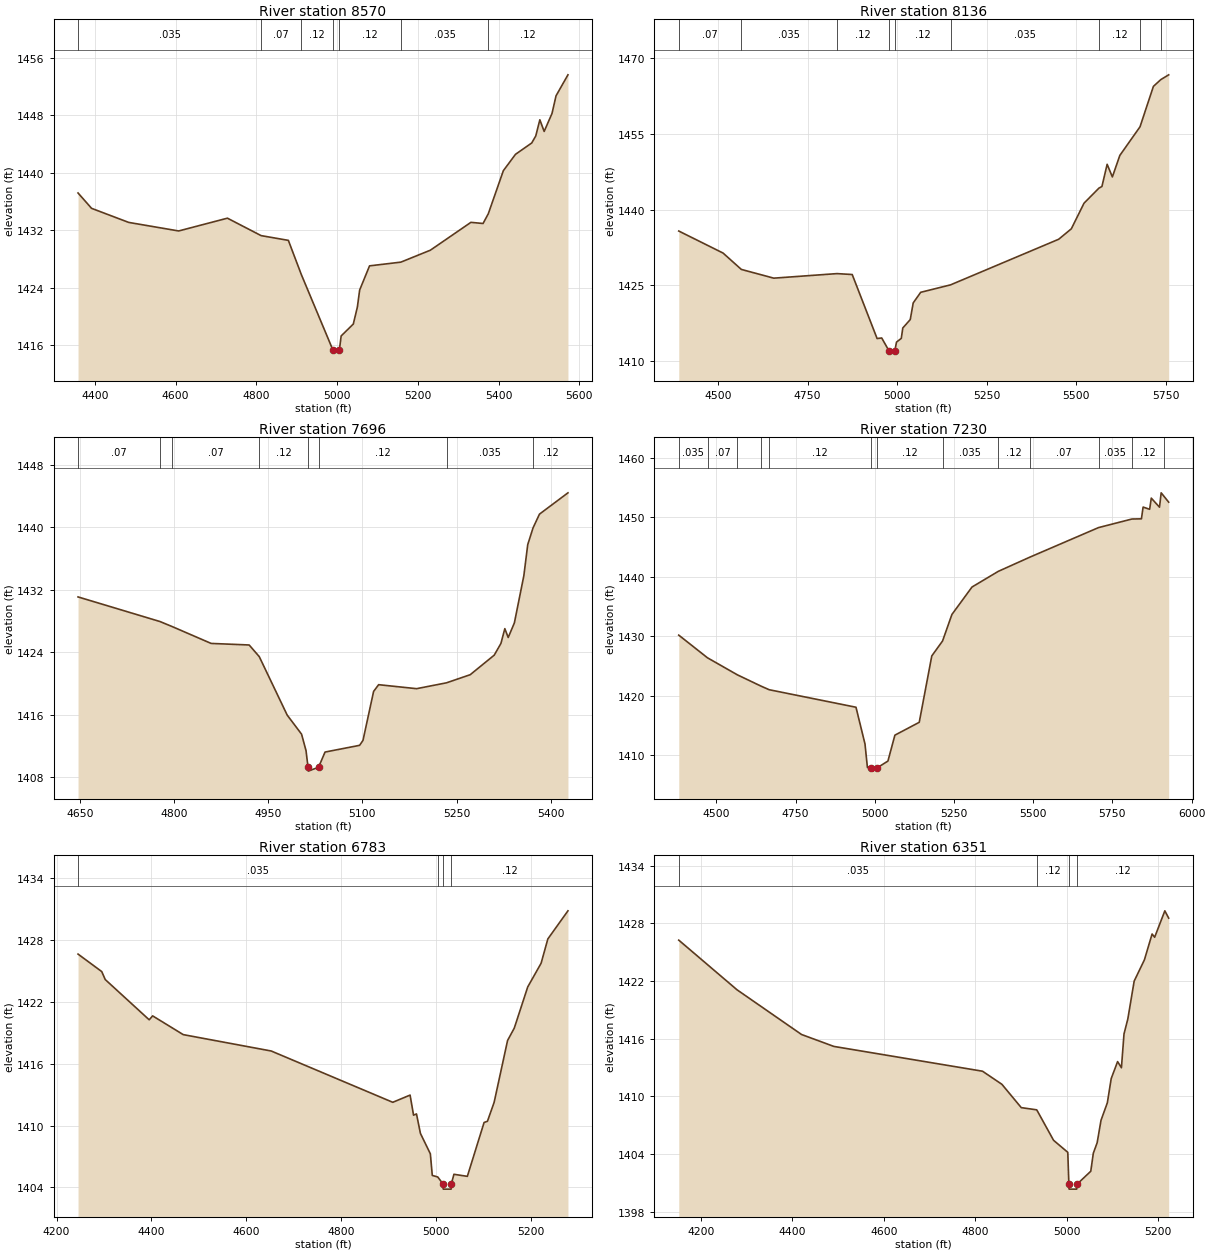
Type RM Length L Ch R = 1 ,8570    ,434,434,434
BEGIN DESCRIPTION:
HOLLIDAY CREEK 18.0
END DESCRIPTION:
XS GIS Cut Line= 3
      2008837.19     13890443.64        2009475.       13890375.
      2010044.36     13890324.41
#Sta/Elev= 30
  4358.5 1437.21    4392 1435.07    4484 1433.11  4607.7 1431.92  4728.4  1433.7
  4811.9 1431.27  4879.3 1430.61  4911.4 1425.85  4989.1 1415.41  4989.6 1414.91
  5005.8 1415.41    5010  1417.3  5040.1 1418.96  5050.2 1421.33  5055.8 1423.69
  5080.3 1427.06  5157.9 1427.58  5230.9 1429.24  5331.3 1433.12  5361.4 1432.96
  5374.4 1434.32  5411.6 1440.31  5441.7 1442.59  5481.9 1444.17  5491.9 1445.15
    5502  1447.4  5512.7 1445.78  5532.1 1448.28  5542.1 1450.74  5571.6 1453.66
#Mann= 7 ,-1 , 0
  4358.5    .035       0  4811.9     .07       0  4911.4     .12       0
  4989.1     .05       0  5005.8     .12       0  5157.9    .035       0
  5374.4     .12       0
Bank Sta=4989.1,5005.8
XS Rating Curve= 0 ,0
Exp/Cntr=0.3,0.1

Type RM Length L Ch R = 1 ,8136    ,440,440,440
BEGIN DESCRIPTION:
HOLLIDAY CREEK 17.0
END DESCRIPTION:
XS GIS Cut Line= 3
        2008975.       13890925.        2009575.       13890775.
      2010175.02     13890324.98
#Sta/Elev= 30
  4389.9 1435.76  4513.6  1431.4  4564.7 1428.16  4655.3 1426.43  4831.9 1427.33
  4874.4 1427.15  4943.9 1414.48  4956.8 1414.59  4976.8 1412.09  4977.3 1411.59
  4993.5 1412.09  4998.1 1413.77  5011.5 1414.51  5015.7 1416.57  5036.5 1418.23
  5044.8 1421.53  5065.7 1423.63    5149  1425.1  5451.1 1434.13  5486.5  1436.2
  5521.9 1441.27  5563.7 1444.26  5571.9 1444.57  5586.5 1448.97  5601.1 1446.47
  5621.9 1450.72  5678.3 1456.39  5715.7 1464.39  5736.1 1465.72  5758.4 1466.68
#Mann= 9 ,-1 , 0
  4389.9     .07       0  4564.7    .035       0  4831.9     .12       0
  4976.8     .05       0  4993.5     .12       0    5149    .035       0
  5563.7     .12       0  5678.3     .07       0  5736.1     .12       0
Bank Sta=4976.8,4993.5
XS Rating Curve= 0 ,0
Exp/Cntr=0.3,0.1

Type RM Length L Ch R = 1 ,7696    ,466,466,466
BEGIN DESCRIPTION:
HOLLIDAY CREEK 16.0
END DESCRIPTION:
XS GIS Cut Line= 3
      2009175.04     13891125.01        2009525.       13891175.
      2009924.99       13891325.
#Sta/Elev= 30
  4646.9 1431.07  4777.5 1427.92  4797.4 1427.26    4859 1425.12  4919.6 1424.92
  4935.7 1423.43  4980.2 1415.95  5003.1 1413.51  5010.2 1411.41  5013.4 1409.28
  5013.9 1408.78  5030.2 1409.28  5040.5 1411.22  5095.6 1412.08    5101 1412.72
  5117.9 1418.98  5125.9 1419.84  5186.4 1419.33  5234.1 1420.08  5271.9 1421.12
  5310.1 1423.62  5320.8 1425.12    5327 1427.01  5332.4 1425.88  5342.2 1427.74
  5357.3 1433.78  5363.5 1437.76  5371.9 1439.89  5382.2 1441.66  5427.6 1444.39
#Mann= 8 ,-1 , 0
  4646.9     .07       0  4777.5     .12       0  4797.4     .07       0
  4935.7     .12       0  5013.4     .05       0  5030.2     .12       0
  5234.1    .035       0  5371.9     .12       0
Bank Sta=5013.4,5030.2
XS Rating Curve= 0 ,0
Exp/Cntr=0.3,0.1

Type RM Length L Ch R = 1 ,7230    ,447,447,447
BEGIN DESCRIPTION:
HOLLIDAY CREEK 15.0
END DESCRIPTION:
XS GIS Cut Line= 3
      2008974.96     13891474.99        2009575.       13891625.
      2010451.49     13891321.95
#Sta/Elev= 30
  4381.6 1430.21  4472.3  1426.4  4566.3 1423.55    4641 1421.65  4667.1 1421.04
  4940.8  1418.1  4969.2 1411.94  4976.9 1407.98  4989.1 1407.87  4989.6 1407.37
    5006 1407.87  5041.6 1409.06  5063.6 1413.41  5140.4 1415.57    5180 1426.72
    5214 1429.23  5243.5 1433.68  5306.9 1438.29  5389.8 1440.92    5490 1443.32
  5706.1 1448.27  5811.5 1449.71  5841.5 1449.74  5846.8 1451.72  5867.4 1451.34
  5872.6 1453.22  5898.5  1451.7  5903.8 1454.11  5911.4 1453.61  5927.5 1452.54
#Mann= 13 ,-1 , 0
  4381.6    .035       0  4472.3     .07       0  4566.3     .12       0
    4641    .035       0  4667.1     .12       0  4989.1     .05       0
    5006     .12       0    5214    .035       0  5389.8     .12       0
    5490     .07       0  5706.1    .035       0  5811.5     .12       0
  5911.4     .07       0
Bank Sta=4989.1,5006
XS Rating Curve= 0 ,0
Exp/Cntr=0.3,0.1

Type RM Length L Ch R = 1 ,6783    ,432,432,432
BEGIN DESCRIPTION:
HOLLIDAY CREEK 14.0
END DESCRIPTION:
XS GIS Cut Line= 3
      2009025.03     13891575.02        2009625.       13892025.
      2009824.99     13892224.99
#Sta/Elev= 30
  4245.3 1426.66  4295.3 1424.96  4302.6 1424.19  4395.3 1420.28  4402.6 1420.66
  4467.1 1418.84  4652.6 1417.25  4908.8 1412.27  4945.3 1412.97  4952.6 1411.02
  4958.8 1411.14  4967.1 1409.25    4988 1407.27  4992.1 1405.17  5003.6 1405.02
  5014.8 1404.34  5015.3 1403.84  5031.8 1403.84  5032.3 1404.34  5037.7 1405.28
    5066 1405.08  5101.3 1410.31  5108.4 1410.43  5122.5 1412.27  5150.8 1418.27
    5165 1419.48  5193.3 1423.47  5221.5 1425.77  5235.7 1428.13  5278.1 1430.86
#Mann= 4 ,-1 , 0
  4245.3    .035       0  5003.6     .12       0  5014.8    .035       0
  5032.3     .12       0
Bank Sta=5014.8,5032.3
XS Rating Curve= 0 ,0
Exp/Cntr=0.3,0.1

Type RM Length L Ch R = 1 ,6351    ,438,438,438
BEGIN DESCRIPTION:
HOLLIDAY CREEK 13.0
END DESCRIPTION:
XS GIS Cut Line= 3
      2008875.02     13891775.02        2009475.       13892375.
      2009674.99     13892474.99
#Sta/Elev= 30
  4151.5 1426.26  4278.8  1421.1  4420.2 1416.44  4490.9  1415.2  4816.2 1412.62
  4858.6 1411.26    4901 1408.83  4934.9  1408.6  4971.7 1405.43  5002.8 1404.18
  5005.2 1400.85  5005.7 1400.35  5022.3 1400.35  5022.8 1400.85  5053.1 1402.21
  5058.7 1404.09  5067.1 1405.18  5075.5 1407.51  5089.4 1409.34  5097.8 1411.85
  5111.8 1413.62  5120.2 1412.98  5125.8 1416.49  5134.2 1418.06  5148.1    1422
  5170.5 1424.21  5187.3  1426.9  5192.9 1426.56  5215.2 1429.31  5223.6 1428.55
#Mann= 4 ,-1 , 0
  4151.5    .035       0  4934.9     .12       0  5005.2     .05       0
  5022.8     .12       0
Bank Sta=5005.2,5022.8
XS Rating Curve= 0 ,0
Exp/Cntr=0.3,0.1

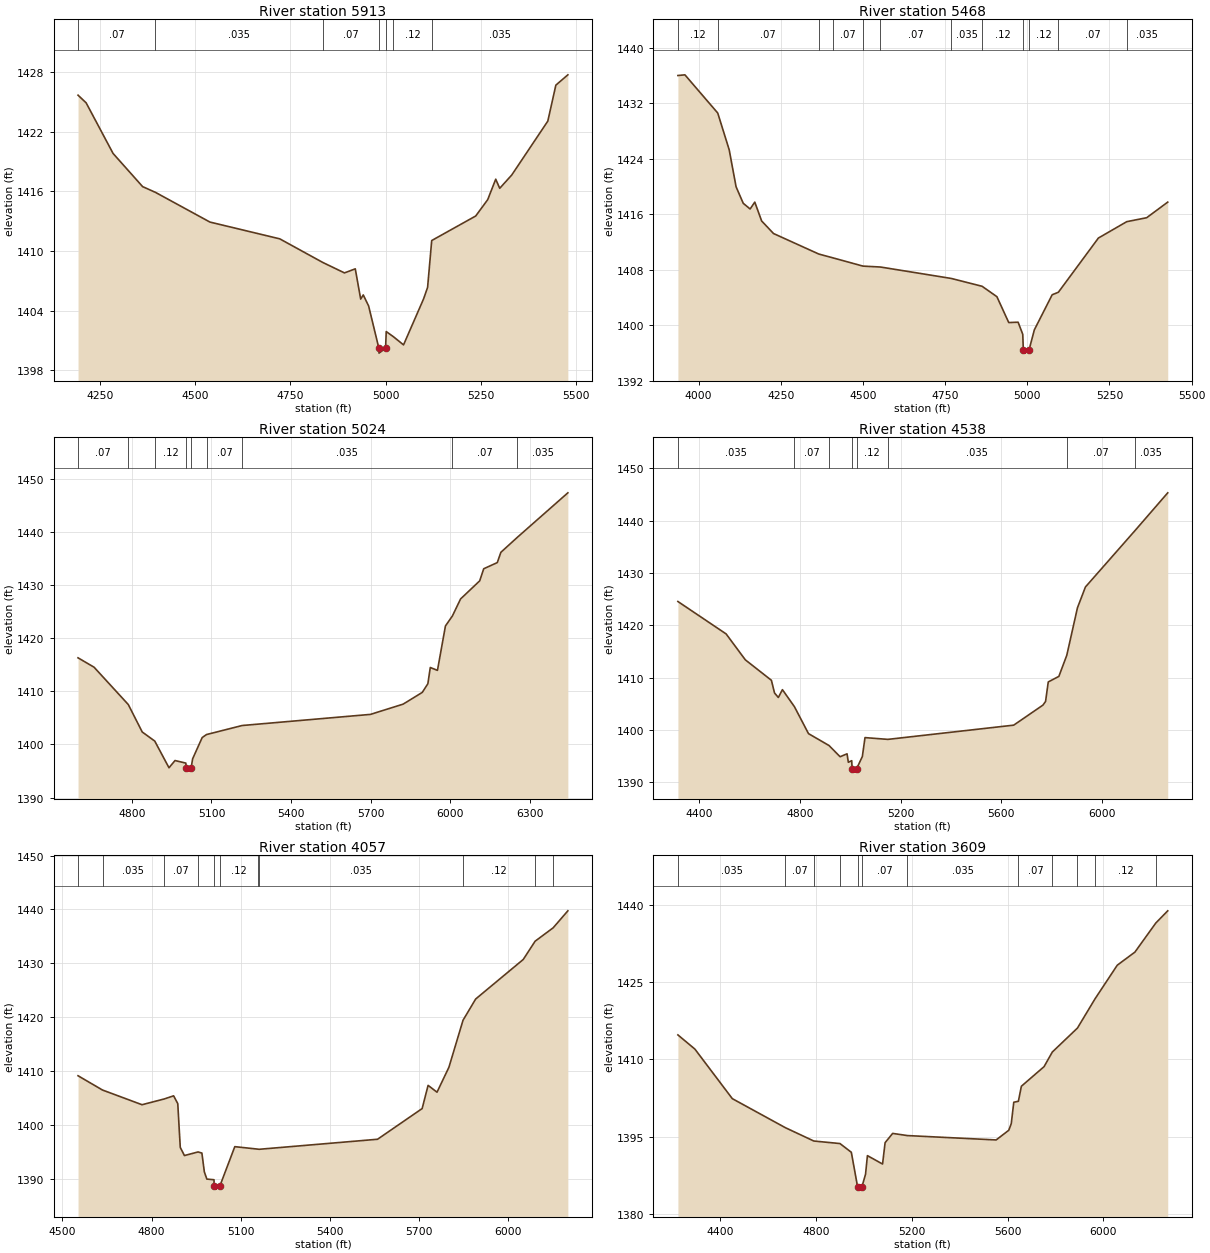
Type RM Length L Ch R = 1 ,5913    ,445,445,445
BEGIN DESCRIPTION:
HOLLIDAY CREEK 12.0
END DESCRIPTION:
XS GIS Cut Line= 3
      2008574.98     13891974.98        2009125.       13892575.
      2009574.99       13892725.
#Sta/Elev= 30
  4191.3  1425.7  4212.6 1424.93  4283.5 1419.83  4361.2 1416.49    4395 1415.91
  4538.2 1412.92  4721.9 1411.23  4835.1 1408.85  4892.1  1407.8  4920.5 1408.21
  4934.7 1405.16  4941.5 1405.58  4955.6 1404.47  4982.5 1400.22    4983 1399.72
  5000.2 1400.22  5001.9 1401.89  5020.9 1401.37  5047.4 1400.55  5100.1 1405.18
  5110.7 1406.34  5121.5 1411.06  5237.2 1413.53  5268.8 1415.18  5289.9 1417.24
  5300.4 1416.32    5332 1417.66  5426.9 1423.09    5448 1426.71  5479.6 1427.75
#Mann= 7 ,-1 , 0
  4191.3     .07       0    4395    .035       0  4835.1     .07       0
  4982.5     .05       0  5000.2     .07       0  5020.9     .12       0
  5121.5    .035       0
Bank Sta=4982.5,5000.2
XS Rating Curve= 0 ,0
Exp/Cntr=0.3,0.1

Type RM Length L Ch R = 1 ,5468    ,444,444,444
BEGIN DESCRIPTION:
HOLLIDAY CREEK 11.0
END DESCRIPTION:
XS GIS Cut Line= 3
      2008125.01     13892075.01        2008825.       13892875.
        2009225.       13893025.
#Sta/Elev= 30
    3937 1436.01  3958.3 1436.11  4058.2  1430.6  4093.1 1425.29    4114 1419.96
  4135.8 1417.58  4156.7 1416.76  4170.9 1417.75  4191.8 1415.03  4227.9 1413.22
  4365.7 1410.26  4408.7 1409.71  4500.1 1408.52  4553.2 1408.39  4768.8 1406.74
  4862.5 1405.61  4907.5 1404.11  4943.5 1400.38    4972 1400.43  4986.2 1398.68
  4987.8 1396.47  4988.3 1395.97  5005.5 1396.47  5021.4 1399.33  5075.7 1404.39
  5094.5 1404.75  5216.3 1412.57  5302.5 1414.93  5363.1  1415.5  5427.2 1417.75
#Mann= 12 ,-1 , 0
    3937     .12       0  4058.2     .07       0  4365.7    .035       0
  4408.7     .07       0  4500.1    .035       0  4553.2     .07       0
  4768.8    .035       0  4862.5     .12       0  4987.8     .05       0
  5005.5     .12       0  5094.5     .07       0  5302.5    .035       0
Bank Sta=4987.8,5005.5
XS Rating Curve= 0 ,0
Exp/Cntr=0.3,0.1

Type RM Length L Ch R = 1 ,5024    ,486,486,486
BEGIN DESCRIPTION:
HOLLIDAY CREEK 10.0
END DESCRIPTION:
XS GIS Cut Line= 3
      2008124.97       13893225.        2008525.       13893175.
      2009725.03     13893975.02
#Sta/Elev= 30
  4597.3 1416.28  4657.8 1414.51  4786.7 1407.49  4839.2 1402.33  4886.4 1400.62
    4940  1395.6  4962.6 1396.96  5003.4 1396.48  5004.8 1395.47  5005.3 1394.97
  5023.1 1395.47    5029 1397.28    5065 1401.28  5081.4 1401.85  5215.8 1403.55
    5699 1405.64  5822.2 1407.57  5894.3 1409.78  5915.3 1411.41  5924.4 1414.46
  5951.4 1413.92  5981.5 1422.27  6007.7 1424.15  6038.5 1427.35  6110.6 1430.76
  6125.7 1433.03  6176.8 1434.19  6190.3 1436.12  6252.8 1438.96  6442.7 1447.31
#Mann= 9 ,-1 , 0
  4597.3     .07       0  4786.7    .035       0  4886.4     .12       0
  5004.8     .05       0  5023.1     .12       0  5081.4     .07       0
  5215.8    .035       0  6007.7     .07       0  6252.8    .035       0
Bank Sta=5004.8,5023.1
XS Rating Curve= 0 ,0
Exp/Cntr=0.3,0.1

Type RM Length L Ch R = 1 ,4538    ,481,481,481
BEGIN DESCRIPTION:
HOLLIDAY CREEK 9.0
END DESCRIPTION:
XS GIS Cut Line= 3
      2007827.94      13893300.6        2008425.       13893625.
        2009625.       13894025.
#Sta/Elev= 30
  4316.3 1424.55  4507.8 1418.35  4583.9  1413.4  4687.4 1409.49  4699.9 1407.06
    4715  1406.2  4731.2  1407.7  4778.9 1404.44  4834.7 1399.29  4916.1 1397.02
  4960.2 1394.87  4987.7 1395.43  4992.9 1393.81  5006.3 1394.12  5007.7 1392.62
  5008.2 1392.12  5026.1 1392.62  5048.5 1394.92    5059 1398.53  5149.8 1398.19
  5649.3 1400.91  5765.3 1404.74  5775.8 1405.45  5786.4 1409.17  5828.5 1410.23
    5860 1414.27  5902.3 1423.34  5933.9 1427.32    6131 1438.12  6260.7 1445.33
#Mann= 8 ,-1 , 0
  4316.3    .035       0  4778.9     .07       0  4916.1     .12       0
  5007.7     .05       0  5026.1     .12       0  5149.8    .035       0
    5860     .07       0    6131    .035       0
Bank Sta=5007.7,5026.1
XS Rating Curve= 0 ,0
Exp/Cntr=0.3,0.1

Type RM Length L Ch R = 1 ,4057    ,448,448,448
BEGIN DESCRIPTION:
HOLLIDAY CREEK 8.0
END DESCRIPTION:
XS GIS Cut Line= 3
      2007925.01       13893875.        2008325.       13894075.
      2009524.99       13894075.
#Sta/Elev= 30
  4552.9 1409.19  4635.3 1406.54  4768.1 1403.82    4843 1404.89  4874.3 1405.47
  4888.3 1404.03  4896.7 1395.91  4910.7  1394.4  4956.6 1395.07  4969.4 1394.86
  4977.7 1391.37  4986.1 1390.04  5010.1 1389.92  5010.9 1388.68  5011.4 1388.18
  5029.3 1388.68  5080.1 1396.05  5157.7 1395.59  5161.5 1395.56  5560.1 1397.42
  5710.1 1403.11  5730.1 1407.41  5760.1 1406.14  5800.1 1410.76  5847.6 1419.48
  5890.1 1423.41  6050.1 1430.74    6090 1434.12  6150.6  1436.6  6200.1 1439.75
#Mann= 11 ,-1 , 0
  4552.9     .07       0  4635.3    .035       0    4843     .07       0
  4956.6     .12       0  5010.9     .05       0  5029.3     .12       0
  5157.7     .07       0  5161.5    .035       0  5847.6     .12       0
    6090     .07       0  6150.6    .035       0
Bank Sta=5010.9,5029.3
XS Rating Curve= 0 ,0
Exp/Cntr=0.3,0.1

Type RM Length L Ch R = 1 ,3609    ,449,449,449
BEGIN DESCRIPTION:
HOLLIDAY CREEK 7.0
END DESCRIPTION:
XS GIS Cut Line= 3
      2007724.99       13894025.        2008325.       13894525.
      2009524.96     13894125.01
#Sta/Elev= 30
  4223.3 1414.75  4294.3 1411.99  4450.5 1402.36  4671.5 1396.73  4791.1 1394.12
  4900.2 1393.63  4947.7 1391.93  4973.6 1385.27  4974.1 1384.77  4992.1 1385.27
    5007 1387.65  5014.9 1391.28  5078.1 1389.65  5088.7  1393.8  5120.3  1395.6
  5182.2 1395.18  5552.5 1394.33  5605.2 1396.21  5615.7 1397.51  5626.2 1401.66
  5645.4 1401.85  5657.9 1404.77  5752.7 1408.58  5787.1 1411.42  5892.1 1416.08
  5965.5 1421.76  6058.4  1428.3  6132.2 1430.85  6219.4  1436.5  6269.2 1438.87
#Mann= 12 ,-1 , 0
  4223.3    .035       0  4671.5     .07       0  4791.1    .035       0
  4900.2     .07       0  4973.6     .05       0  4992.1     .07       0
  5182.2    .035       0  5645.4     .07       0  5787.1     .12       0
  5892.1     .07       0  5965.5     .12       0  6219.4    .035       0
Bank Sta=4973.6,4992.1
XS Rating Curve= 0 ,0
Exp/Cntr=0.3,0.1

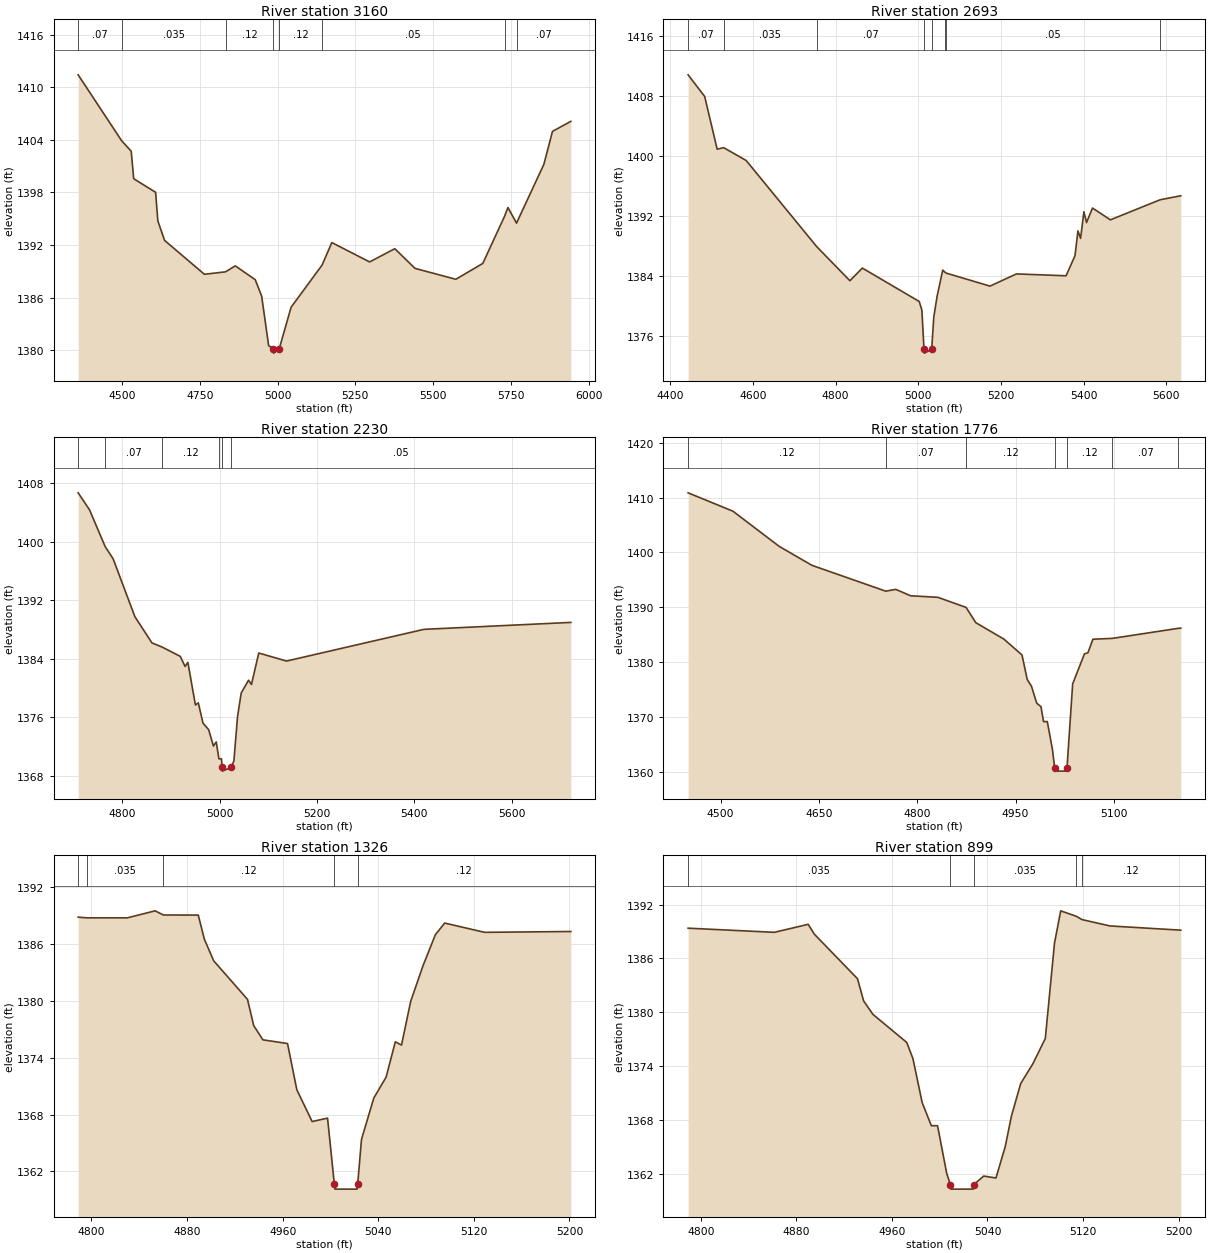
Type RM Length L Ch R = 1 ,3160    ,467,467,467
BEGIN DESCRIPTION:
HOLLIDAY CREEK 6.0
END DESCRIPTION:
XS GIS Cut Line= 3
      2007625.01     13894275.01        2008025.       13894775.
      2008825.01       13895275.
#Sta/Elev= 30
    4359 1411.42  4498.6  1403.9  4529.5  1402.7  4537.5 1399.56  4607.9 1398.01
  4615.1 1394.75  4636.7 1392.52  4764.8 1388.65  4832.7 1388.93    4864 1389.61
  4928.1 1388.04  4948.9 1386.15  4971.3  1380.5  4986.8 1380.15  4987.3 1379.65
  5005.3 1380.15  5043.5 1384.89    5143  1389.7  5174.4 1392.27  5295.9 1390.06
  5376.7 1391.57  5442.1 1389.32    5573 1388.08  5659.7 1389.89  5729.5 1395.26
  5740.5 1396.27  5768.1 1394.49    5856  1401.2  5883.7 1404.96  5942.7 1406.11
#Mann= 8 ,-1 , 0
    4359     .07       0  4498.6    .035       0  4832.7     .12       0
  4986.8     .05       0  5005.3     .12       0    5143     .05       0
  5729.5     .12       0  5768.1     .07       0
Bank Sta=4986.8,5005.3
XS Rating Curve= 0 ,0
Exp/Cntr=0.3,0.1

Type RM Length L Ch R = 1 ,2693    ,463,463,463
BEGIN DESCRIPTION:
HOLLIDAY CREEK 5.0
END DESCRIPTION:
XS GIS Cut Line= 3
        2007575.     13894325.04        2007625.       13894875.
      2008024.97     13895374.97
#Sta/Elev= 30
  4442.9 1410.87    4483 1407.98  4513.2 1400.94  4529.1 1401.14  4583.4 1399.43
  4754.1 1387.93  4834.5 1383.37  4864.6 1385.06  5002.3  1380.6  5008.7 1379.46
  5013.9  1374.2  5014.4  1373.7  5032.4  1374.2  5037.6 1378.54  5045.6  1381.3
  5059.2 1384.79  5063.9 1384.54  5067.4 1384.39  5173.6 1382.65  5237.6 1384.28
  5357.7 1384.03  5379.3  1386.7  5386.5 1390.03  5392.9 1389.03  5400.9 1392.58
  5407.3 1391.14  5421.7 1393.08    5465  1391.5  5585.2 1394.18  5635.4 1394.72
#Mann= 8 ,-1 , 0
  4442.9     .07       0  4529.1    .035       0  4754.1     .07       0
  5013.9     .05       0  5032.4     .07       0  5063.9     .12       0
  5067.4     .05       0  5585.2     .07       0
Bank Sta=5013.9,5032.4
XS Rating Curve= 0 ,0
Exp/Cntr=0.3,0.1

Type RM Length L Ch R = 1 ,2230    ,454,454,454
BEGIN DESCRIPTION:
HOLLIDAY CREEK 4.0
END DESCRIPTION:
XS GIS Cut Line= 3
      2007124.99     13894474.98        2007275.       13894725.
      2007675.01     13895325.02
#Sta/Elev= 30
  4708.9 1406.72  4732.2  1404.4  4764.4 1399.36  4780.8 1397.68  4825.5 1389.76
  4860.5 1386.18  4881.3 1385.61  4918.8 1384.33  4928.6 1382.95  4934.4 1383.51
  4949.9 1377.67  4955.8 1377.97  4965.5 1375.19  4977.1  1374.3  4986.9 1372.06
  4992.7 1372.62  4998.2  1370.3  5003.5  1370.3  5004.7 1369.12  5005.2 1368.62
  5023.3 1369.12    5029 1370.02  5036.5 1376.09    5044 1379.31  5059.1 1381.07
  5065.1 1380.48  5080.1 1384.79  5137.2 1383.69  5419.6 1388.03  5721.6 1388.98
#Mann= 6 ,-1 , 0
  4708.9    .035       0  4764.4     .07       0  4881.3     .12       0
  4998.2     .07       0  5004.7     .05       0  5023.3     .05       0
Bank Sta=5004.7,5023.3
XS Rating Curve= 0 ,0
Exp/Cntr=0.3,0.1

Type RM Length L Ch R = 1 ,1776    ,450,450,450
BEGIN DESCRIPTION:
HOLLIDAY CREEK 3.0
END DESCRIPTION:
XS GIS Cut Line= 3
      2006546.68      13894637.4        2006975.       13894975.
      2007174.97     13895024.99
#Sta/Elev= 30
  4450.5 1410.86  4518.9 1407.51  4589.4  1401.1  4639.4 1397.64    4752 1392.93
  4767.3 1393.26  4789.9 1392.09  4831.5 1391.81  4874.5 1389.97  4889.3 1387.19
  4932.2 1384.19  4959.8  1381.3  4967.8 1376.82  4974.2 1375.61  4982.3  1372.5
  4988.7 1371.88  4992.7 1369.15  4998.4 1369.15  5006.2  1364.1  5009.7 1360.62
  5010.2 1360.12  5027.9 1360.12  5028.4 1360.62  5037.1 1376.03  5055.1 1381.51
  5060.3 1381.68    5068 1384.17  5097.6 1384.32  5198.4 1386.16    5202 1386.18
#Mann= 7 ,-1 , 0
  4450.5     .12       0    4752     .07       0  4874.5     .12       0
  5009.7     .05       0  5028.4     .12       0  5097.6     .07       0
  5198.4     .05       0
Bank Sta=5009.7,5028.4
XS Rating Curve= 0 ,0
Exp/Cntr=0.3,0.1

Type RM Length L Ch R = 1 ,1326    ,427,427,427
BEGIN DESCRIPTION:
HOLLIDAY CREEK 2.0
END DESCRIPTION:
XS GIS Cut Line= 3
        2006875.       13895575.        2006925.       13895375.
      2007124.99       13895325.
#Sta/Elev= 30
  4788.9 1388.82  4796.2 1388.75  4830.1 1388.75  4853.3 1389.49  4860.2 1389.05
  4889.4 1389.04  4894.5  1386.5  4902.3 1384.22  4930.6 1380.15  4935.8 1377.38
  4943.5 1375.88  4964.1 1375.49  4971.9 1370.61  4984.7 1367.26  4997.6 1367.62
  5003.3 1360.63  5003.8 1360.13  5022.3 1360.13  5022.8 1360.63    5026 1365.37
  5036.3 1369.74  5046.6 1371.94  5054.3 1375.67  5059.5 1375.33  5067.2 1379.95
  5077.5  1383.7  5087.8 1386.96  5095.6  1388.2  5129.1 1387.22  5201.2 1387.31
#Mann= 5 ,-1 , 0
  4788.9     .07       0  4796.2    .035       0  4860.2     .12       0
  5003.3     .05       0  5022.8     .12       0
Bank Sta=5003.3,5022.8
XS Rating Curve= 0 ,0
Exp/Cntr=0.3,0.1

Type RM Length L Ch R = 1 ,899     ,0,0,0
BEGIN DESCRIPTION:
HOLLIDAY CREEK 1.0
END DESCRIPTION:
XS GIS Cut Line= 3
      2007024.95     13895675.01        2007225.       13895625.
      2007275.01     13895424.96
#Sta/Elev= 30
  4789.4 1389.37  4861.6 1388.91  4889.9  1389.8  4895.1  1388.7  4931.2 1383.75
  4936.3 1381.29  4944.1 1379.79  4972.4 1376.67  4977.6 1374.87  4985.3 1369.99
    4993 1367.41  4998.2 1367.41  5005.9 1362.09    5009 1360.86  5009.5 1360.36
    5028 1360.36  5028.5 1360.86  5036.8 1361.81  5047.1  1361.6  5054.9 1365.11
    5060 1368.46  5067.8  1372.1  5078.1 1374.32  5088.4 1377.11  5096.1 1387.72
  5101.3  1391.3  5114.4 1390.69    5119 1390.33  5142.5 1389.62  5201.8 1389.15
#Mann= 5 ,-1 , 0
  4789.4    .035       0    5009    .035       0  5028.5    .035       0
  5114.4     .12       0    5119     .12       0
Bank Sta=5009,5028.5
XS Rating Curve= 0 ,0
Exp/Cntr=0.3,0.1

Chan Stop Cuts=-1
Use User Specified Reach Order=0
Composite Channel Slope=5