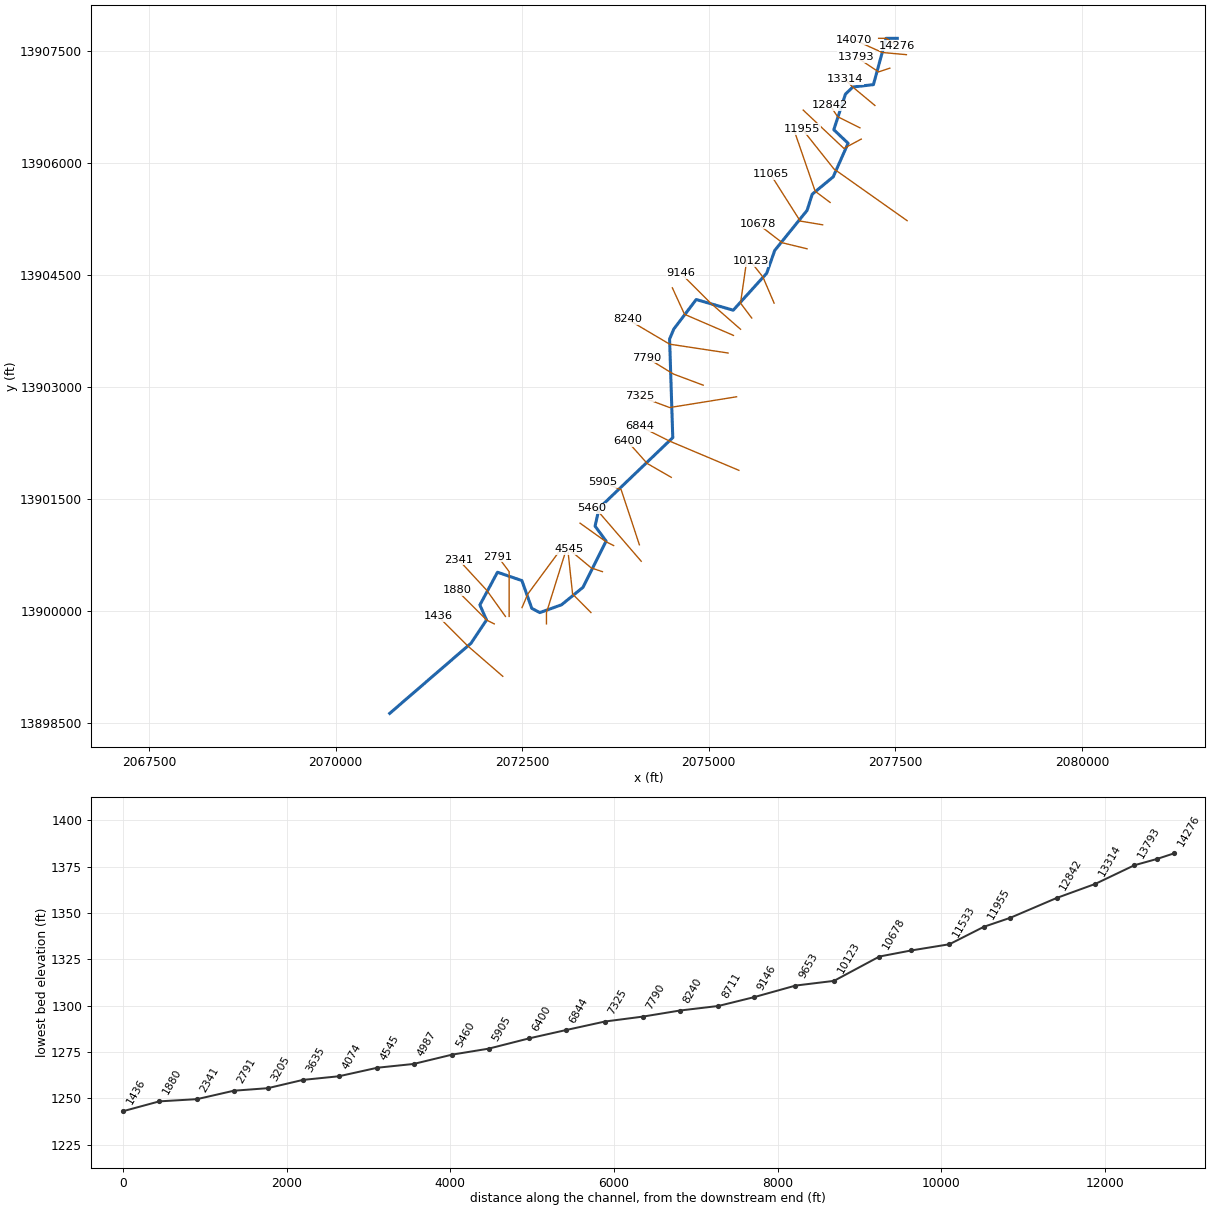
--- JACOBS CREEK.prj (project) ---

Proj Title=JACOBS CREEK Base Level Engineering
Current Plan=p01
Default Exp/Contr=0.3,0.1
English Units
Geom File=g01
Flow File=f01
Plan File=p01
Y Axis Title=Elevation
X Axis Title(PF)=Main Channel Distance
X Axis Title(XS)=Station
BEGIN DESCRIPTION:
JACOBS CREEK
END DESCRIPTION:
DSS Export Rating Curves= 0
DSS Export Rating Curve Sorted= 0
DSS Export Volume Flow Curves= 0
DXF OffsetX= 0
DXF OffsetY= 0
DXF ScaleX= 1
DXF ScaleY= 10

--- JACOBS CREEK.p01 (plan) ---

Plan Title=Multiple Run
Short Identifier=Multiple
Geom File=g01
Flow File=f01
Subcritical Flow
K Sum by GR= 0
Std Step Tol= 0.01
Critical Tol= 0.01
Num of Std Step Trials= 20
Max Error Tol= 0.3
Flow Tol Ratio= 0.001
Split Flow NTrial= 30
Split Flow Tol= 0.02
Split Flow Ratio= 0.02
Log Output Level= 0
Friction Slope Method= 1
Unsteady Friction Slope Method= 2
Unsteady Bridges Friction Slope Method= 1
Parabolic Critical Depth
Global Vel Dist=  1 , 1 , 1
Global Log Level= 0
CheckData=True
Encroach Param= -1, 0, 0, 0
BEGIN DESCRIPTION:
Multiple Run
END DESCRIPTION:

--- JACOBS CREEK.f01 (steady flow) ---

Flow Title=Multiple
Number of Profiles=7
Profile Names=10-year,25-year,50-year,1pct_min,100-year,1pct_plu,500-year
River Rch & RM= JACOBS CREEK,Reach-1,14276
    1229    2126    3001    2057    4104    8188    7583
River Rch & RM= JACOBS CREEK,Reach-1,11955
    2165    3869    5579    3898    7778   15519   14957
River Rch & RM= JACOBS CREEK,Reach-1,10123
    2449    4400    6366    4461    8901   17760   17220
River Rch & RM= JACOBS CREEK,Reach-1,8711
    2924    5291    7692    5411   10796   21542   21053
River Rch & RM= JACOBS CREEK,Reach-1,6844
    3322    6009    8729    6129   12229   24400   23763
Boundary for River Rch & Prof#=JACOBS CREEK,Reach-1,1
Up Type=0
Dn Type=3
Dn Slope=0.005
Boundary for River Rch & Prof#=JACOBS CREEK,Reach-1,2
Up Type=0
Dn Type=3
Dn Slope=0.005
Boundary for River Rch & Prof#=JACOBS CREEK,Reach-1,3
Up Type=0
Dn Type=3
Dn Slope=0.005
Boundary for River Rch & Prof#=JACOBS CREEK,Reach-1,4
Up Type=0
Dn Type=3
Dn Slope=0.005
Boundary for River Rch & Prof#=JACOBS CREEK,Reach-1,5
Up Type=0
Dn Type=3
Dn Slope=0.005
Boundary for River Rch & Prof#=JACOBS CREEK,Reach-1,6
Up Type=0
Dn Type=3
Dn Slope=0.005
Boundary for River Rch & Prof#=JACOBS CREEK,Reach-1,7
Up Type=0
Dn Type=3
Dn Slope=0.005

--- JACOBS CREEK.g01 (geometry) ---

Geom Title=Existing Conditions
Program Version=4.10

River Reach=JACOBS CREEK    ,Reach-1
Reach XY= 30
        2077525.       13907675.        2077375.       13907675.
      2077205.42     13907054.42      2076930.43     13907022.83
      2076830.82     13906927.31      2076674.47     13906449.88
      2076866.03     13906268.35      2076667.14     13905818.83
      2076385.39      13905585.1      2076316.84     13905368.95
      2075883.14     13904831.06        2075775.       13904525.
      2075327.43      13904030.4      2074831.13     13904173.33
      2074530.84     13903777.29      2074474.57     13903643.33
      2074517.19     13902321.59      2073530.82     13901377.31
      2073476.04     13901135.44      2073624.12     13900934.87
      2073314.35       13900315.       2073027.3     13900080.83
      2072735.52     13899976.08      2072628.23     13900032.99
      2072495.48     13900405.37      2072168.79      13900517.2
      2071933.05     13900078.29      2072021.88     13899876.63
      2071814.24     13899565.32        2070725.       13898625.

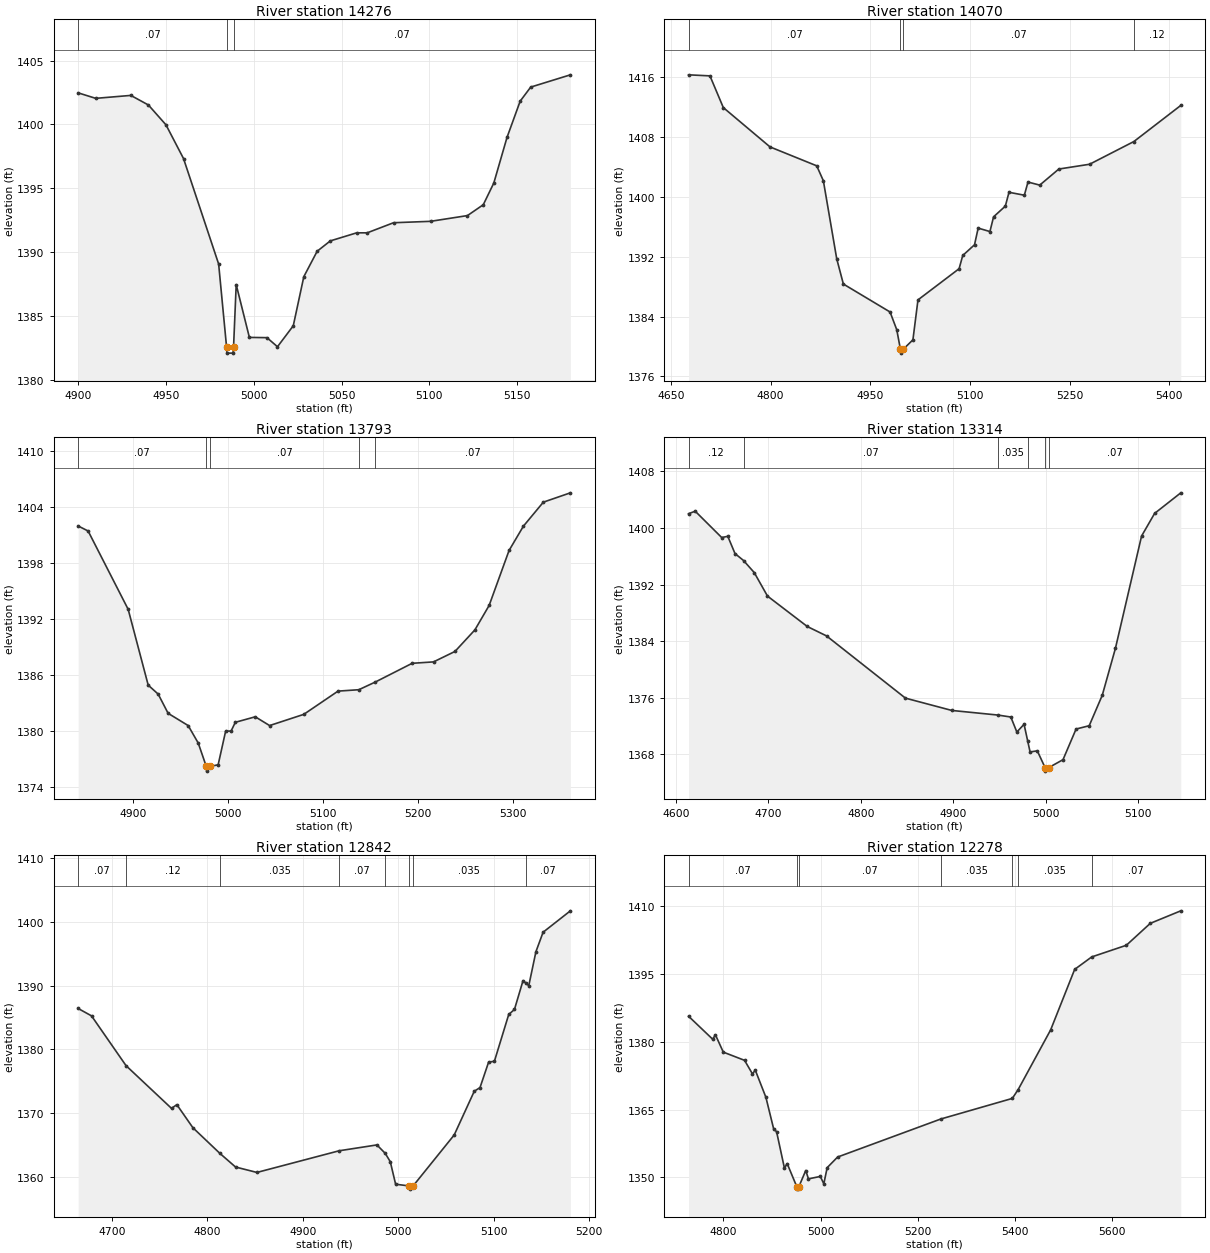
Type RM Length L Ch R = 1 ,14276   ,206,206,206
BEGIN DESCRIPTION:
JACOBS CREEK 31.0
END DESCRIPTION:
XS GIS Cut Line= 3
        2077275.       13907675.        2077375.       13907675.
      2077525.02     13907574.99
#Sta/Elev= 30
    4900 1402.47    4910 1402.04    4930 1402.27    4940 1401.52    4950 1399.97
    4960 1397.33    4980 1389.08  4984.5 1382.61  4984.7 1382.11  4988.2 1382.11
  4988.5 1382.61    4990 1387.47  4997.5 1383.34  5007.5 1383.32  5013.5 1382.61
  5022.5 1384.25  5028.5 1388.09  5036.1 1390.08  5043.6 1390.89  5058.6 1391.52
  5064.6 1391.52  5079.6 1392.31  5100.7 1392.42  5121.7 1392.87  5130.7 1393.72
  5136.7 1395.42  5144.2 1398.98  5151.7 1401.82  5157.7 1402.92  5180.3 1403.88
#Mann= 3 ,-1 , 0
    4900     .07       0  4984.5     .05       0  4988.5     .07       0
Bank Sta=4984.5,4988.5
XS Rating Curve= 0 ,0
Exp/Cntr=0.3,0.1

Type RM Length L Ch R = 1 ,14070   ,277,277,277
BEGIN DESCRIPTION:
JACOBS CREEK 30.5
END DESCRIPTION:
XS GIS Cut Line= 3
       2077647.1     13907456.14      2077324.89     13907485.04
      2076944.05     13907655.88
#Sta/Elev= 30
  4676.5 1416.34  4708.7  1416.2  4728.8 1411.96  4799.1  1406.7  4869.4 1404.17
  4879.4 1402.17  4899.5 1391.74  4909.5 1388.36  4979.8 1384.62  4989.9 1382.24
  4995.4 1379.62  4995.7 1379.12  4999.4 1379.62  5014.2  1380.9  5021.8 1386.24
  5083.7 1390.41  5089.2 1392.18  5106.9 1393.61  5112.4 1395.84  5130.1 1395.38
  5135.6 1397.35  5153.3 1398.78  5158.8 1400.63  5181.9 1400.24  5187.4    1402
  5205.1 1401.59  5233.8 1403.74  5280.1 1404.38  5346.8 1407.42  5417.4 1412.25
#Mann= 4 ,-1 , 0
  4676.5     .07       0  4995.4     .05       0  4999.4     .07       0
  5346.8     .12       0
Bank Sta=4995.4,4999.4
XS Rating Curve= 0 ,0
Exp/Cntr=0.3,0.1

Type RM Length L Ch R = 1 ,13793   ,479,479,479
BEGIN DESCRIPTION:
JACOBS CREEK 30.0
END DESCRIPTION:
XS GIS Cut Line= 3
      2077424.97     13907274.99        2077275.       13907225.
      2076975.03     13907424.98
#Sta/Elev= 30
  4841.9 1401.98  4852.4 1401.44  4894.6 1393.05  4915.7 1384.93  4926.2 1383.97
  4936.7 1381.91  4957.8  1380.6  4968.4 1378.73  4976.9 1376.22  4977.2 1375.72
  4980.9 1376.22  4989.4  1376.4  4997.3 1380.01    5003 1380.01  5007.5 1380.95
  5028.5 1381.54  5043.6  1380.6  5079.6  1381.8  5115.7 1384.29  5137.6 1384.44
  5154.9 1385.26  5193.8 1387.27  5216.3 1387.42  5238.9 1388.54  5259.9 1390.85
  5274.9 1393.47  5295.9 1399.36    5311 1401.96    5332 1404.53  5360.5 1405.53
#Mann= 5 ,-1 , 0
  4841.9     .07       0  4976.9     .05       0  4980.9     .07       0
  5137.6    .035       0  5154.9     .07       0
Bank Sta=4976.9,4980.9
XS Rating Curve= 0 ,0
Exp/Cntr=0.3,0.1

Type RM Length L Ch R = 1 ,13314   ,472,472,472
BEGIN DESCRIPTION:
JACOBS CREEK 29.0
END DESCRIPTION:
XS GIS Cut Line= 3
      2077225.04     13906774.97        2076925.       13907025.
      2076824.99     13907125.01
#Sta/Elev= 30
  4613.9 1402.03  4621.1 1402.38  4649.7 1398.66  4656.3 1398.83  4664.1 1396.39
  4673.3 1395.41  4684.9  1393.7  4699.2 1390.38  4742.2 1386.08    4763 1384.75
  4848.3 1375.95  4898.4 1374.21  4948.1 1373.56  4962.2 1373.28  4968.7 1371.16
  4976.5 1372.25  4980.3 1369.96    4983 1368.34  4990.8  1368.5  4999.2 1366.13
  4999.5 1365.63  5003.2 1366.13  5018.6 1367.25  5032.7 1371.58  5046.9 1372.05
    5061 1376.35  5075.2 1382.97  5103.5 1398.87  5117.6 1402.07  5145.9 1404.98
#Mann= 6 ,-1 , 0
  4613.9     .12       0  4673.3     .07       0  4948.1    .035       0
  4980.3     .07       0  4999.2     .05       0  5003.2     .07       0
Bank Sta=4999.2,5003.2
XS Rating Curve= 0 ,0
Exp/Cntr=0.3,0.1

Type RM Length L Ch R = 1 ,12842   ,564,564,564
BEGIN DESCRIPTION:
JACOBS CREEK 28.0
END DESCRIPTION:
XS GIS Cut Line= 3
      2077024.99     13906475.01        2076725.       13906625.
      2076624.99     13906775.02
#Sta/Elev= 30
  4664.6  1386.4  4678.6 1385.24  4714.8 1377.42  4762.4 1370.72    4768  1371.3
  4784.8 1367.68  4813.1 1363.65  4829.5 1361.51  4851.9 1360.66    4938 1364.06
  4977.6 1364.98  4986.3 1363.66  4991.6 1362.35  4997.2 1358.81  5011.5 1358.54
  5011.8 1358.04  5015.5 1358.54  5058.6 1366.55  5079.6 1373.41  5085.6 1373.98
  5094.6 1377.97  5100.7 1378.12  5115.7 1385.46  5121.7 1386.25  5130.7 1390.78
  5133.3 1390.43  5136.7 1389.98  5144.2 1395.32  5151.7 1398.37  5180.3 1401.73
#Mann= 8 ,-1 , 0
  4664.6     .07       0  4714.8     .12       0  4813.1    .035       0
    4938     .07       0  4986.3    .035       0  5011.5    .035       0
  5015.5    .035       0  5133.3     .07       0
Bank Sta=5011.5,5015.5
XS Rating Curve= 0 ,0
Exp/Cntr=0.3,0.1

Type RM Length L Ch R = 1 ,12278   ,323,323,323
BEGIN DESCRIPTION:
JACOBS CREEK 27.0
END DESCRIPTION:
XS GIS Cut Line= 3
      2077042.18     13906324.29      2076809.56      13906199.3
      2076264.45     13906713.16
#Sta/Elev= 30
  4728.4 1385.64    4778 1380.56  4783.7 1381.53  4799.9  1377.7  4843.7 1375.88
    4860 1372.87  4865.7 1373.73  4887.6  1367.7  4903.8 1360.61  4909.5 1360.13
  4925.7 1352.05  4931.4 1353.04  4951.3 1347.89  4951.6 1347.39  4955.3 1347.89
  4969.6 1351.51  4975.2 1349.66  4999.6  1350.2  5006.8 1348.56  5013.7 1352.14
  5035.2 1354.49  5247.8 1362.91  5394.8 1367.46  5406.7 1369.39  5473.7 1382.62
  5523.1    1396  5558.2 1398.76  5629.5 1401.34  5678.8 1406.19  5741.6 1408.96
#Mann= 7 ,-1 , 0
  4728.4     .07       0  4951.3     .05       0  4955.3     .07       0
  5247.8    .035       0  5394.8     .07       0  5406.7    .035       0
  5558.2     .07       0
Bank Sta=4951.3,4955.3
XS Rating Curve= 0 ,0
Exp/Cntr=0.3,0.1

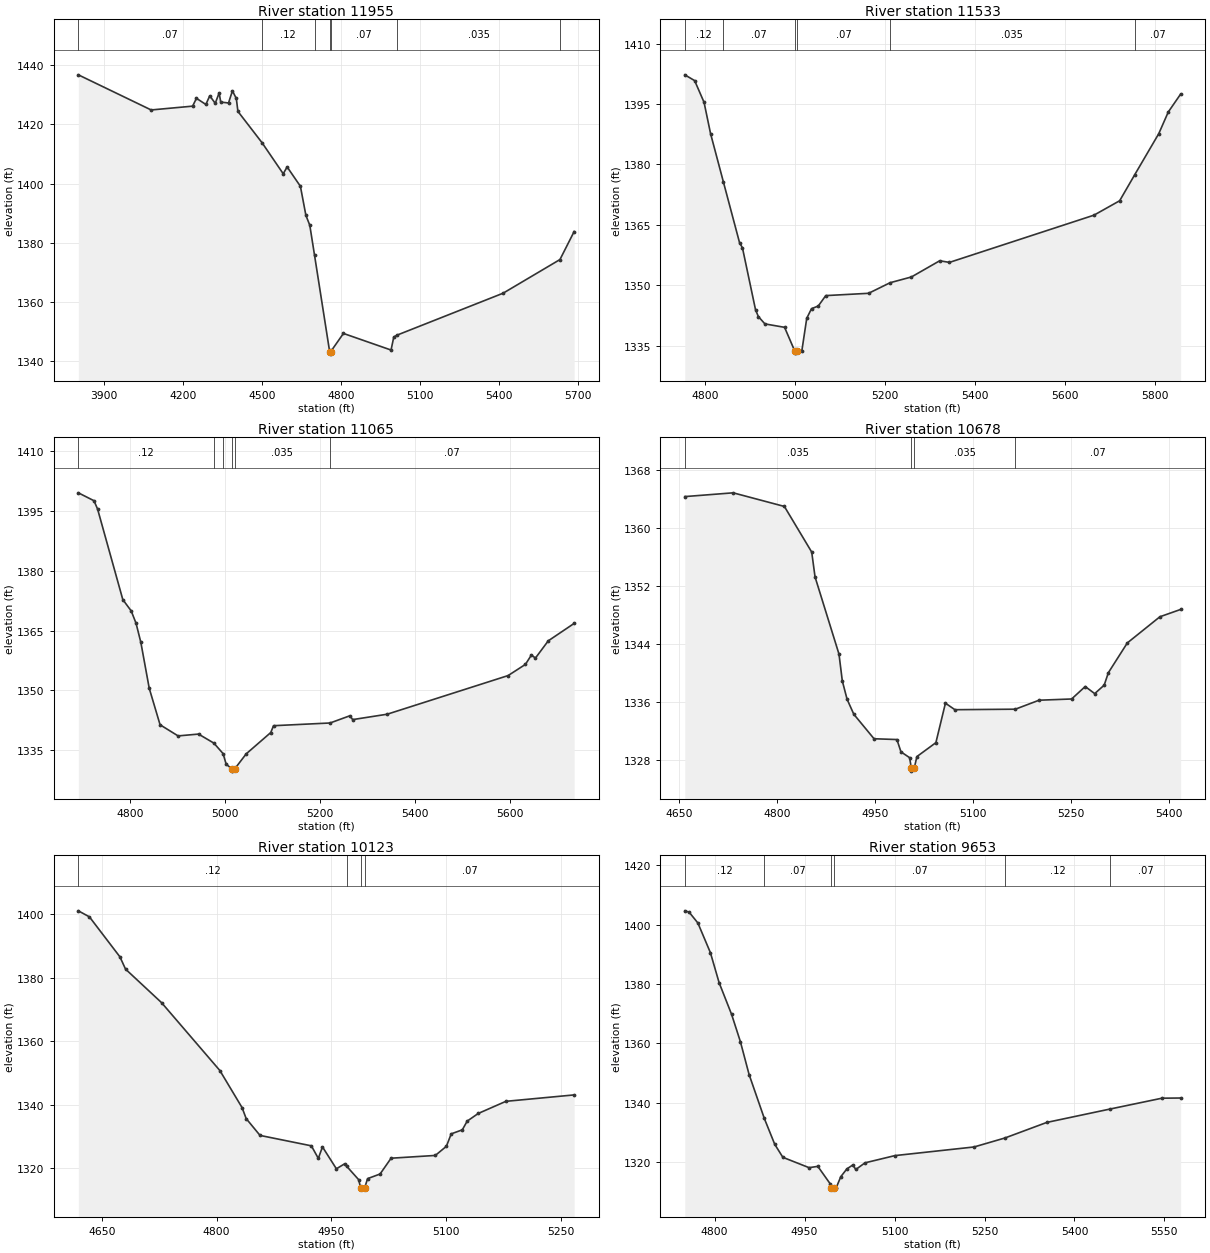
Type RM Length L Ch R = 1 ,11955   ,422,422,422
BEGIN DESCRIPTION:
JACOBS CREEK 26.0
END DESCRIPTION:
XS GIS Cut Line= 3
      2077656.76     13905230.56        2076675.       13905925.
       2076250.5     13906459.76
#Sta/Elev= 30
  3801.8 1436.82  4078.7 1424.92  4236.3 1426.21    4251 1428.86  4286.7 1426.78
  4301.5 1429.71  4322.4 1427.17  4337.2 1430.69  4343.3 1427.58  4372.9 1427.29
  4387.7 1431.39  4402.5 1428.81  4408.6 1424.43  4500.6 1413.79  4580.9  1403.3
  4595.7 1405.62  4646.2 1399.06  4667.1  1389.2  4681.9 1385.86  4699.9 1375.72
  4757.4 1343.04  4757.6 1342.54  4761.4 1343.04  4809.8 1349.21  4990.8 1343.59
  5001.3    1348  5015.1 1348.69  5416.9 1362.84  5633.1 1374.24  5687.1 1383.74
#Mann= 7 ,-1 , 0
  3801.8     .07       0  4500.6     .12       0  4699.9     .07       0
  4757.4     .05       0  4761.4     .07       0  5015.1    .035       0
  5633.1     .07       0
Bank Sta=4757.4,4761.4
XS Rating Curve= 0 ,0
Exp/Cntr=0.3,0.1

Type RM Length L Ch R = 1 ,11533   ,468,468,468
BEGIN DESCRIPTION:
JACOBS CREEK 25.0
END DESCRIPTION:
XS GIS Cut Line= 3
      2076625.04     13905474.97        2076425.       13905625.
       2076146.7     13906430.95
#Sta/Elev= 30
    4755 1402.24  4776.9  1400.8  4797.8 1395.42  4812.3 1387.64  4840.8 1375.65
  4876.9 1360.49  4883.2 1359.28  4912.3 1343.89  4918.6 1342.19  4933.2 1340.37
  4976.9 1339.52  4999.6 1333.61  4999.9 1333.11  5004.3 1333.61  5015.4 1333.75
  5026.2 1341.76  5036.8 1344.15  5051.8 1344.81  5068.5  1347.4  5163.7 1347.97
  5211.6  1350.6    5259 1352.03  5321.9 1356.05  5343.6 1355.65    5665 1367.38
  5722.1 1370.96  5755.6 1377.42  5809.1 1387.63  5830.2    1393  5857.7 1397.45
#Mann= 6 ,-1 , 0
    4755     .12       0  4840.8     .07       0  4999.6     .05       0
  5004.3     .07       0  5211.6    .035       0  5755.6     .07       0
Bank Sta=4999.6,5004.3
XS Rating Curve= 0 ,0
Exp/Cntr=0.3,0.1

Type RM Length L Ch R = 1 ,11065   ,387,387,387
BEGIN DESCRIPTION:
JACOBS CREEK 24.0
END DESCRIPTION:
XS GIS Cut Line= 3
      2076525.01       13905175.        2076225.       13905225.
      2075827.56     13905851.06
#Sta/Elev= 30
  4690.3 1399.53  4723.3 1397.55  4730.9 1395.46  4784.1 1372.76  4801.8 1369.92
    4812 1366.83  4822.1 1362.06  4839.8 1350.54  4862.7 1341.37  4900.7 1338.58
  4943.8 1339.04  4976.2 1336.77  4995.6 1334.14  5002.1 1331.48  5014.9 1330.25
  5015.3 1329.75  5019.7 1330.25  5044.4 1334.09  5096.1 1339.42    5102 1341.14
  5221.2 1341.82    5263 1343.63  5268.9 1342.67  5341.7 1344.02  5596.7 1353.71
  5633.2 1356.51  5645.9 1358.87  5654.3 1358.09  5681.4 1362.42    5736 1366.79
#Mann= 6 ,-1 , 0
  4690.3     .12       0  4976.2     .07       0  4995.6    .035       0
  5014.9    .035       0  5019.7    .035       0  5221.2     .07       0
Bank Sta=5014.9,5019.7
XS Rating Curve= 0 ,0
Exp/Cntr=0.3,0.1

Type RM Length L Ch R = 1 ,10678   ,555,555,555
BEGIN DESCRIPTION:
JACOBS CREEK 23.0
END DESCRIPTION:
XS GIS Cut Line= 3
      2076316.18     13904853.54       2075985.5     13904934.01
      2075654.09      13905188.7
#Sta/Elev= 30
  4658.9 1364.39  4732.9 1364.91  4811.2 1363.03    4853 1356.73  4858.1  1353.3
  4894.7 1342.65  4899.8 1338.94  4907.1 1336.41  4917.4 1334.34  4948.3 1330.96
  4983.3 1330.85  4989.5 1329.15  5002.7 1328.35  5005.2 1326.99  5005.6 1326.49
    5010 1326.99  5013.9  1328.5  5042.9 1330.42  5057.5 1335.87    5072 1334.97
  5164.4 1335.04  5200.7 1336.28  5250.5 1336.45  5271.3 1338.17  5285.8 1337.19
  5300.3 1338.36  5306.7 1340.08  5335.7 1344.19  5385.5  1347.8  5417.2 1348.81
#Mann= 4 ,-1 , 0
  4658.9    .035       0  5005.2    .035       0    5010    .035       0
  5164.4     .07       0
Bank Sta=5005.2,5010
XS Rating Curve= 0 ,0
Exp/Cntr=0.3,0.1

Type RM Length L Ch R = 1 ,10123   ,470,470,470
BEGIN DESCRIPTION:
JACOBS CREEK 22.0
END DESCRIPTION:
XS GIS Cut Line= 3
        2075875.     13904124.99        2075725.       13904475.
      2075559.78     13904685.13
#Sta/Elev= 30
  4619.2 1401.03  4633.7 1399.13  4673.6 1386.52  4680.9 1382.67    4728  1372.1
  4804.2 1350.72  4833.2 1339.05  4838.6 1335.58  4856.7 1330.28  4923.8    1327
  4932.9 1323.04  4938.3 1326.67  4956.5 1319.77  4967.4 1321.35    4970 1320.55
  4985.5 1316.37  4988.2 1313.86  4988.6 1313.36  4993.6 1313.86  4997.3 1316.67
  5013.6 1318.12    5028  1323.1  5085.8 1323.97  5100.3 1326.85  5106.6 1330.77
  5121.1 1332.04  5127.5 1334.79  5141.9 1337.19  5178.1 1341.02  5267.3 1343.04
#Mann= 4 ,-1 , 0
  4619.2     .12       0    4970     .07       0  4988.2     .05       0
  4993.6     .07       0
Bank Sta=4988.2,4993.6
XS Rating Curve= 0 ,0
Exp/Cntr=0.3,0.1

Type RM Length L Ch R = 1 ,9653    ,507,507,507
BEGIN DESCRIPTION:
JACOBS CREEK 21.0
END DESCRIPTION:
XS GIS Cut Line= 3
      2075574.97     13903925.04        2075425.       13904125.
      2075507.47     13904695.82
#Sta/Elev= 30
  4750.3 1404.68  4757.5 1404.24  4772.1 1400.58    4793 1390.57  4807.5 1380.46
  4828.4 1369.72    4843 1360.55  4857.5 1349.47  4882.9 1334.65  4900.3 1325.92
  4913.8 1321.55  4957.5 1318.06  4972.1  1318.5    4993 1312.53  4994.4 1311.32
  4994.8 1310.82  4999.8 1311.32  5002.8 1311.32  5010.4 1315.02  5020.5 1317.64
  5030.4 1318.97  5035.4 1317.44  5050.8 1319.69  5100.7 1322.13  5232.6 1325.04
  5284.1 1328.07  5353.9 1333.32  5459.3 1337.83  5545.9 1341.49    5577 1341.55
#Mann= 6 ,-1 , 0
  4750.3     .12       0  4882.9     .07       0  4994.4     .05       0
  4999.8     .07       0  5284.1     .12       0  5459.3     .07       0
Bank Sta=4994.4,4999.8
XS Rating Curve= 0 ,0
Exp/Cntr=0.3,0.1

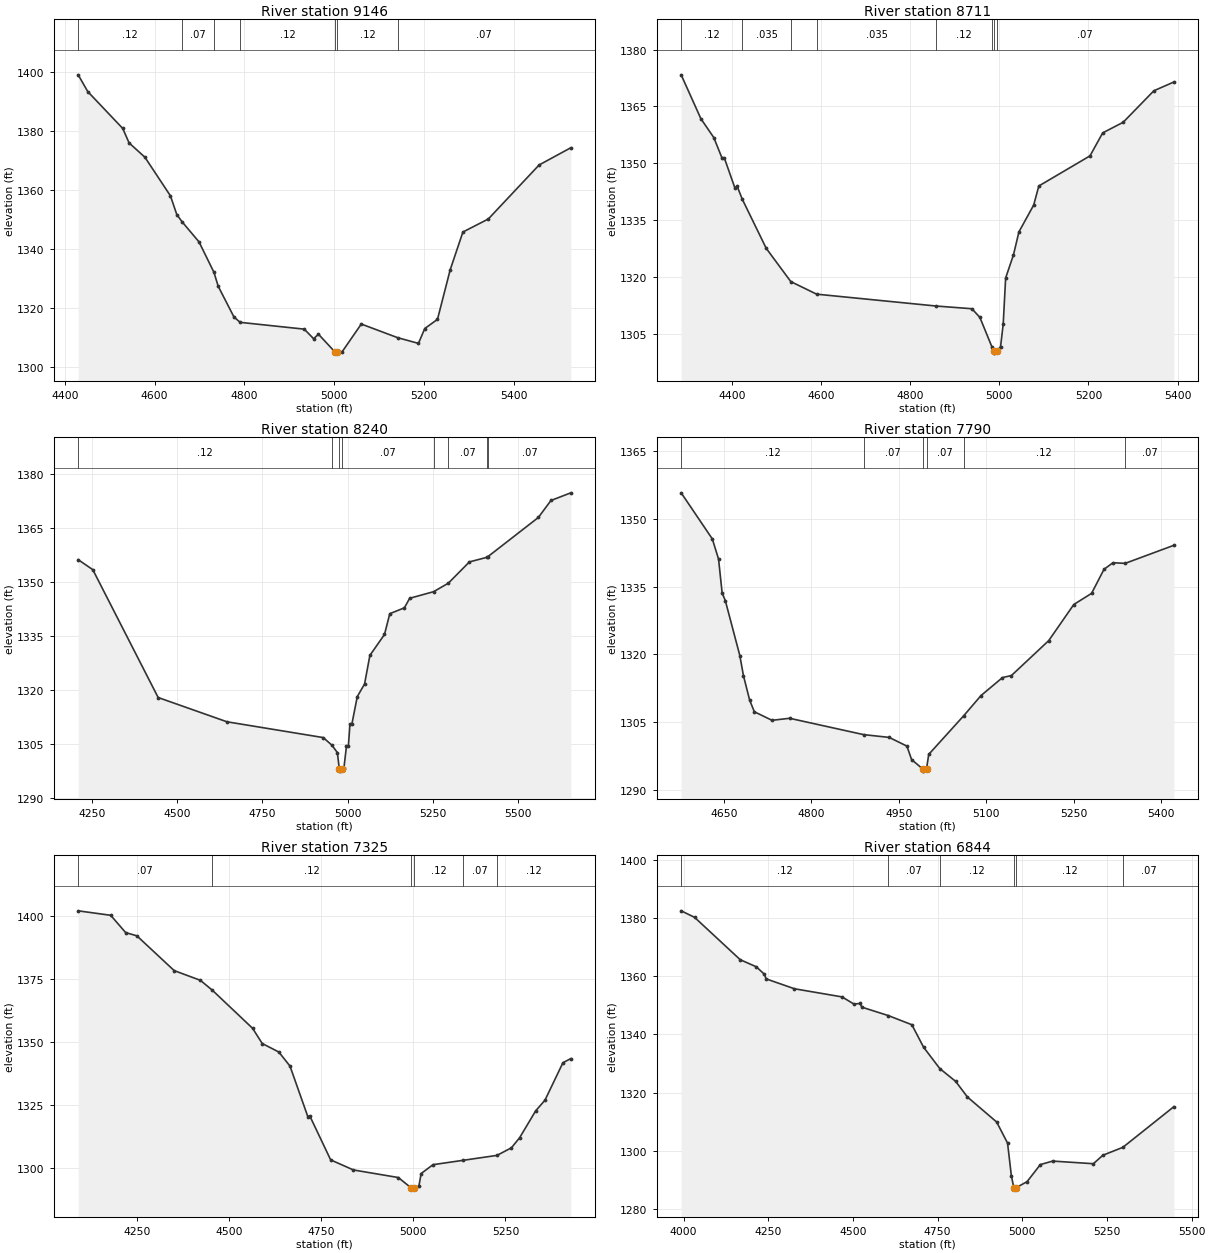
Type RM Length L Ch R = 1 ,9146    ,435,435,435
BEGIN DESCRIPTION:
JACOBS CREEK 20.0
END DESCRIPTION:
XS GIS Cut Line= 3
      2075425.02     13903774.99        2075025.       13904125.
      2074625.01     13904524.99
#Sta/Elev= 30
  4429.9 1398.91  4451.3 1393.22  4529.1 1380.74  4543.3 1375.83  4578.5 1370.98
  4635.4 1357.88  4649.6 1351.52  4661.7 1349.02    4699 1342.28  4732.3 1331.96
  4741.7 1327.25  4776.8 1316.83  4790.7    1315  4933.4  1312.7  4954.3 1309.45
    4965 1310.99  5001.1 1305.07  5001.6 1304.57  5006.6 1305.07    5018 1305.08
  5060.4 1314.43  5141.5  1309.8  5187.7 1307.87  5201.8 1312.91  5230.1 1316.02
  5258.4 1332.82  5286.7 1345.62  5343.3 1350.04  5456.4 1368.35  5527.1  1374.2
#Mann= 7 ,-1 , 0
  4429.9     .12       0  4661.7     .07       0  4732.3    .035       0
  4790.7     .12       0  5001.1     .05       0  5006.6     .12       0
  5141.5     .07       0
Bank Sta=5001.1,5006.6
XS Rating Curve= 0 ,0
Exp/Cntr=0.3,0.1

Type RM Length L Ch R = 1 ,8711    ,471,471,471
BEGIN DESCRIPTION:
JACOBS CREEK 19.0
END DESCRIPTION:
XS GIS Cut Line= 3
      2075330.35     13903692.37        2074675.       13903975.
      2074511.24     13904330.61
#Sta/Elev= 30
  4286.3 1373.36  4330.5 1361.77  4359.5 1356.78  4377.6 1351.47    4383 1351.45
  4406.5 1343.57    4412 1343.87  4423.4 1340.49  4477.1 1327.52  4532.2 1318.73
  4590.1 1315.41  4858.6 1312.27  4938.5 1311.56  4956.4 1309.27  4983.9 1301.33
  4987.8 1300.33  4988.3 1299.83  4994.2 1300.33  5002.8 1301.54  5008.7 1307.48
  5014.2 1319.69  5031.7 1325.77    5044 1331.87  5077.1 1338.95  5088.6 1343.99
  5203.4 1351.95  5231.9 1358.02  5277.8 1360.82  5346.7 1369.15  5391.5 1371.46
#Mann= 8 ,-1 , 0
  4286.3     .12       0  4423.4    .035       0  4532.2     .07       0
  4590.1    .035       0  4858.6     .12       0  4983.9     .07       0
  4987.8     .05       0  4994.2     .07       0
Bank Sta=4987.8,4994.2
XS Rating Curve= 0 ,0
Exp/Cntr=0.3,0.1

Type RM Length L Ch R = 1 ,8240    ,450,450,450
BEGIN DESCRIPTION:
JACOBS CREEK 18.0
END DESCRIPTION:
XS GIS Cut Line= 3
      2075257.49     13903456.24        2074475.       13903575.
      2073909.31     13903909.61
#Sta/Elev= 30
    4208 1356.11    4251 1353.33  4443.2 1317.81  4645.4 1311.07  4928.7 1306.68
  4953.9 1304.58  4970.1 1302.53    4976 1297.86  4976.5 1297.36  4982.5 1297.86
  4989.3 1298.17  4996.9 1304.26  5002.4 1304.26  5007.3 1310.48  5013.1 1310.56
  5028.7 1318.07  5050.1 1321.56  5065.8 1329.52  5108.7 1335.32  5124.3  1341.1
  5167.2 1342.73  5182.8 1345.38    5253 1347.21  5296.4 1349.57  5358.3 1355.48
    5410 1356.77    5413 1356.96  5561.1 1367.83  5598.2 1372.55  5656.7 1374.68
#Mann= 8 ,-1 , 0
    4208     .12       0  4953.9     .07       0    4976     .05       0
  4982.5     .07       0    5253    .035       0  5296.4     .07       0
    5410    .035       0    5413     .07       0
Bank Sta=4976,4982.5
XS Rating Curve= 0 ,0
Exp/Cntr=0.3,0.1

Type RM Length L Ch R = 1 ,7790    ,465,465,465
BEGIN DESCRIPTION:
JACOBS CREEK 17.0
END DESCRIPTION:
XS GIS Cut Line= 3
      2074925.03     13903024.99        2074525.       13903175.
      2074168.57     13903392.91
#Sta/Elev= 30
  4576.9 1355.77  4630.3 1345.56    4641  1341.1  4647.2 1333.54  4652.6  1331.9
  4677.5 1319.71  4683.7 1315.27  4694.4 1309.81  4702.4 1307.26  4732.7 1305.36
  4762.9 1305.81  4889.8 1302.19  4933.8 1301.57  4964.1 1299.64  4972.1 1296.66
    4991  1294.6  4991.5  1294.1  4997.7  1294.6  5001.5 1297.81  5061.2 1306.33
  5091.2 1310.85    5128 1314.83  5143.4 1315.29  5207.3 1323.02  5250.3 1331.02
  5280.8 1333.49  5302.2 1338.84  5317.6 1340.28  5338.4 1340.14  5421.9 1344.14
#Mann= 6 ,-1 , 0
  4576.9     .12       0  4889.8     .07       0    4991     .05       0
  4997.7     .07       0  5061.2     .12       0  5338.4     .07       0
Bank Sta=4991,4997.7
XS Rating Curve= 0 ,0
Exp/Cntr=0.3,0.1

Type RM Length L Ch R = 1 ,7325    ,481,481,481
BEGIN DESCRIPTION:
JACOBS CREEK 16.0
END DESCRIPTION:
XS GIS Cut Line= 3
      2075372.04     13902869.44        2074475.       13902725.
      2074074.99       13902875.
#Sta/Elev= 30
  4091.4 1402.11  4179.6 1400.33  4220.1 1393.46  4250.5 1392.17  4351.7 1378.34
  4422.7 1374.48  4455.4 1370.51  4564.5 1355.36  4590.4 1349.35  4635.4 1345.97
  4665.7 1340.37  4714.1 1320.26  4719.2  1320.6    4776 1303.07  4837.8 1299.06
  4959.5 1296.05  4994.1 1291.94  4994.6 1291.44  5000.9 1291.94  5015.1  1292.6
  5021.4 1297.65  5053.4 1301.16  5136.1 1302.92    5227 1304.86  5266.1 1307.88
  5288.4  1311.9    5332 1322.61  5356.9 1326.77  5405.8 1341.72  5427.2 1343.35
#Mann= 6 ,-1 , 0
  4091.4     .07       0  4455.4     .12       0  4994.1     .05       0
  5000.9     .12       0  5136.1     .07       0    5227     .12       0
Bank Sta=4994.1,5000.9
XS Rating Curve= 0 ,0
Exp/Cntr=0.3,0.1

Type RM Length L Ch R = 1 ,6844    ,444,444,444
BEGIN DESCRIPTION:
JACOBS CREEK 15.0
END DESCRIPTION:
XS GIS Cut Line= 3
       2075403.3     13901883.33        2074475.       13902275.
      2074074.96     13902475.02
#Sta/Elev= 30
  3992.6 1382.47  4032.1 1380.24    4167 1365.66  4214.4 1363.23  4238.1 1360.69
  4243.5 1359.07  4327.2 1355.67  4467.8 1352.87  4502.4 1350.43  4520.7 1350.61
  4526.1 1349.35  4604.8 1346.43  4673.8  1343.3  4708.4 1335.58  4756.2 1328.24
  4803.3 1323.81  4837.8 1318.46  4924.2 1309.86  4956.4  1302.6  4967.6 1291.37
  4974.9 1287.28  4975.4 1286.78  4981.9 1287.28  5014.1 1289.36  5053.2 1295.22
  5089.6 1296.42  5209.8 1295.52  5237.7 1298.42    5297 1301.16  5447.4 1315.12
#Mann= 6 ,-1 , 0
  3992.6     .12       0  4604.8     .07       0  4756.2     .12       0
  4974.9     .05       0  4981.9     .12       0    5297     .07       0
Bank Sta=4974.9,4981.9
XS Rating Curve= 0 ,0
Exp/Cntr=0.3,0.1

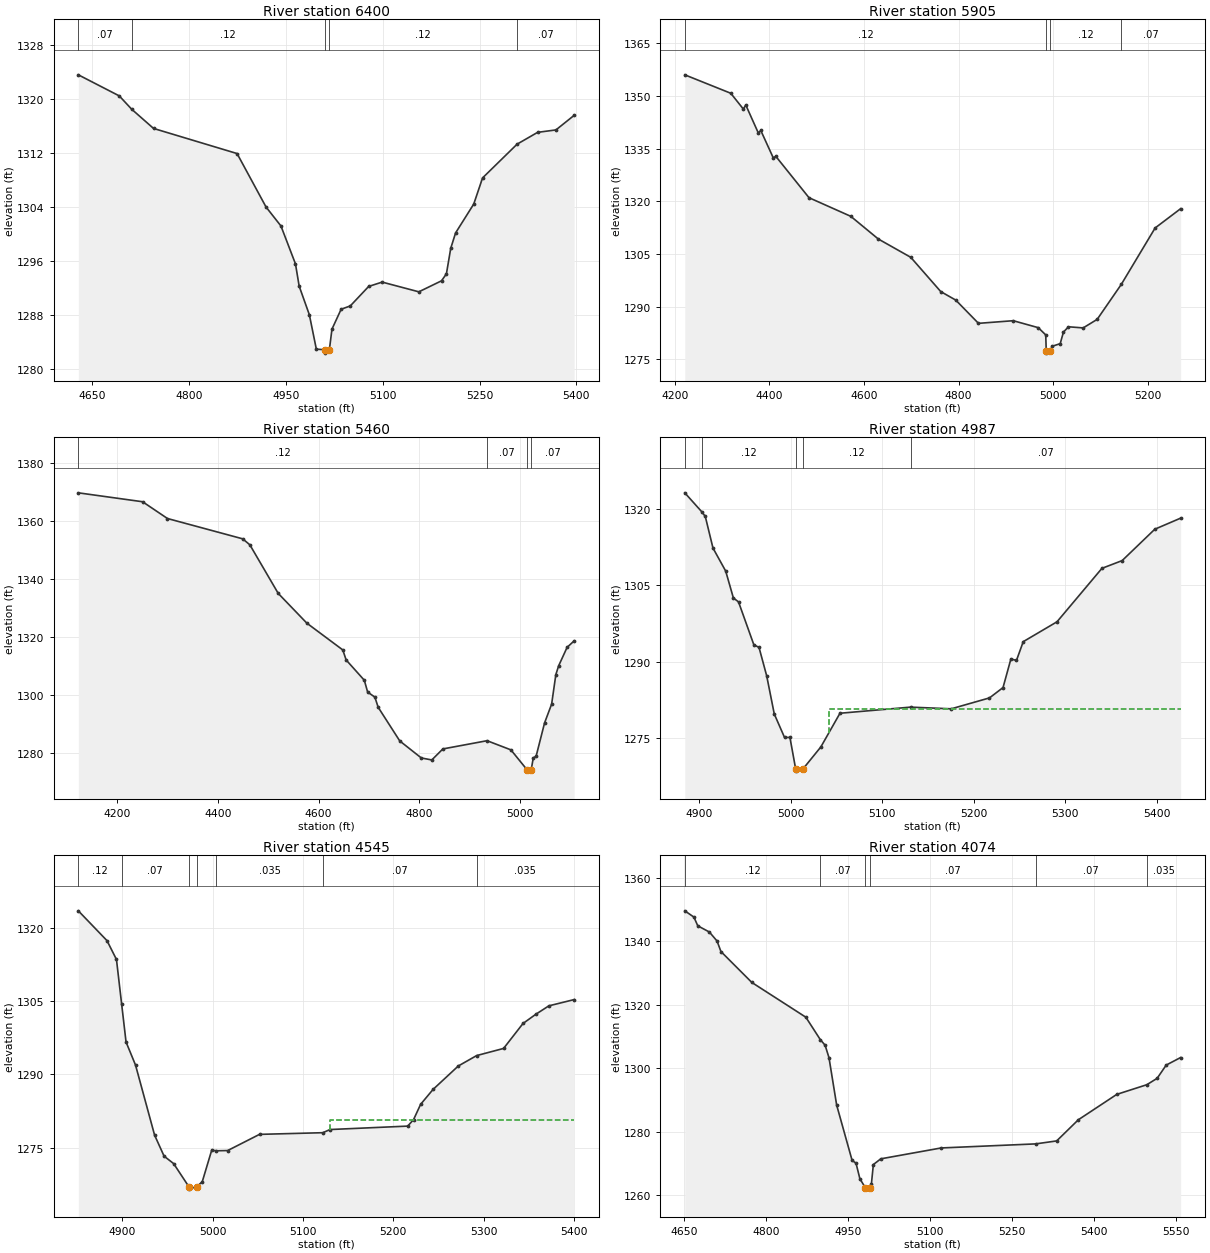
Type RM Length L Ch R = 1 ,6400    ,495,495,495
BEGIN DESCRIPTION:
JACOBS CREEK 14.0
END DESCRIPTION:
XS GIS Cut Line= 3
      2074497.03     13901789.59        2074175.       13901975.
      2073911.26     13902271.08
#Sta/Elev= 30
  4628.4 1323.59  4691.8 1320.47    4711  1318.5  4744.9 1315.65  4874.3 1311.93
  4919.2 1304.01  4942.3  1301.2  4964.8 1295.58  4970.5 1292.29  4986.3 1288.05
  4997.1 1282.96  5010.2 1282.87  5010.7 1282.37  5017.3 1282.87  5021.3 1285.92
  5035.5 1288.87  5049.7 1289.36  5078.2 1292.25  5099.1 1292.89  5155.9 1291.45
    5191 1293.08  5198.6 1294.11  5205.3 1297.89  5212.8 1300.17    5241 1304.46
  5254.6 1308.32  5308.1 1313.32  5339.9 1315.07  5368.3 1315.43  5396.5 1317.59
#Mann= 5 ,-1 , 0
  4628.4     .07       0    4711     .12       0  5010.2     .05       0
  5017.3     .12       0  5308.1     .07       0
Bank Sta=5010.2,5017.3
XS Rating Curve= 0 ,0
Exp/Cntr=0.3,0.1

Type RM Length L Ch R = 1 ,5905    ,445,445,445
BEGIN DESCRIPTION:
JACOBS CREEK 13.0
END DESCRIPTION:
XS GIS Cut Line= 3
      2074069.97     13900885.83        2073825.       13901625.
      2073574.97     13901725.01
#Sta/Elev= 30
  4221.3 1356.04  4318.5 1350.79    4345  1346.3  4350.2 1347.45  4376.7 1339.48
  4381.9  1340.2  4408.4 1332.37  4413.6 1332.85  4483.8 1321.06  4572.1 1315.76
  4630.2 1309.31  4698.9 1304.09  4762.3 1294.33    4794 1291.91    4842 1285.29
  4915.5 1286.04  4968.4 1284.06  4984.2    1282  4985.3 1277.31  4985.8 1276.81
  4993.6 1277.31  4997.4 1278.74  5014.8 1279.51  5021.6  1282.8  5032.3 1284.31
  5063.3 1283.99  5092.9 1286.42  5143.8 1296.36  5215.4 1312.44  5269.3 1317.93
#Mann= 4 ,-1 , 0
  4221.3     .12       0  4985.3     .05       0  4993.6     .12       0
  5143.8     .07       0
Bank Sta=4985.3,4993.6
XS Rating Curve= 0 ,0
Exp/Cntr=0.3,0.1

Type RM Length L Ch R = 1 ,5460    ,473,473,473
BEGIN DESCRIPTION:
JACOBS CREEK 12.0
END DESCRIPTION:
XS GIS Cut Line= 3
      2074094.27     13900664.59        2073525.       13901325.
        2073425.       13901375.
#Sta/Elev= 30
  4123.5 1369.66    4251 1366.58  4300.4 1360.79  4449.6 1353.78  4463.8 1351.71
  4520.1 1334.94  4576.9 1324.67  4648.2 1315.43  4654.8 1311.98  4690.9 1304.96
  4697.5 1300.88  4711.8 1299.15  4718.4 1295.63  4761.2 1284.02    4804 1278.14
  4824.8 1277.46  4846.7 1281.26  4934.4  1284.1  4981.7 1280.94  5013.6  1274.1
  5014.1  1273.6    5022  1274.1  5026.1 1278.16  5031.7 1278.73  5048.5 1290.24
  5062.5 1296.72  5070.9 1306.94  5076.5 1309.98  5093.2 1316.33  5107.2 1318.56
#Mann= 4 ,-1 , 0
  4123.5     .12       0  4934.4     .07       0  5013.6     .05       0
    5022     .07       0
Bank Sta=5013.6,5022
XS Rating Curve= 0 ,0
Exp/Cntr=0.3,0.1

Type RM Length L Ch R = 1 ,4987    ,442,442,442
BEGIN DESCRIPTION:
JACOBS CREEK 11.0
END DESCRIPTION:
XS GIS Cut Line= 3
      2073725.02     13900874.99        2073625.       13900925.
      2073275.03     13901174.98
#Sta/Elev= 30
  4884.3 1323.17  4902.9 1319.44  4906.7 1318.53  4915.1 1312.33    4929 1307.81
  4937.4 1302.53    4943 1301.77  4959.8 1293.33  4965.4 1292.84  4973.8 1287.25
  4982.1 1279.76  4993.3 1275.16  4999.2 1275.16  5005.4 1269.05  5005.9 1268.55
  5013.8 1269.05    5033  1273.3  5053.9 1279.91    5131 1281.11  5175.5 1280.78
  5217.3 1282.92  5232.1 1284.95  5240.7 1290.56  5246.8 1290.28  5254.2 1293.96
  5291.1 1297.86  5340.2 1308.35  5362.3 1309.87    5398 1316.03  5426.2  1318.2
#Mann= 5 ,-1 , 0
  4884.3     .07       0  4902.9     .12       0  5005.4     .05       0
  5013.8     .12       0    5131     .07       0
#XS Ineff= 2 , 0
       0                 5041.82       0 1280.77
Permanent Ineff=
       F       F
Bank Sta=5005.4,5013.8
XS Rating Curve= 0 ,0
Exp/Cntr=0.3,0.1

Type RM Length L Ch R = 1 ,4545    ,471,471,471
BEGIN DESCRIPTION:
JACOBS CREEK 10.0
END DESCRIPTION:
XS GIS Cut Line= 3
      2073575.05     13900524.98        2073425.       13900575.
      2073124.98     13900825.02
#Sta/Elev= 30
  4851.5 1323.49  4883.2 1317.39  4893.7 1313.53  4899.4 1304.45  4904.3 1296.64
  4914.8 1291.91  4935.9 1277.57  4946.4 1273.27    4957 1271.74  4973.8 1267.02
  4974.3 1266.52  4982.3 1267.02  4988.6 1268.01  4999.1 1274.49  5004.4 1274.37
  5016.8 1274.42    5052 1277.73    5122 1278.07  5130.1 1278.72    5216 1279.42
  5222.5 1280.76  5230.3 1283.88    5244 1286.92    5272 1291.73  5292.3 1293.86
  5322.1 1295.32  5343.6 1300.43  5357.9 1302.33  5372.2 1304.04  5400.2 1305.32
#Mann= 7 ,-1 , 0
  4851.5     .12       0  4899.4     .07       0  4973.8     .05       0
  4982.3     .07       0  5004.4    .035       0    5122     .07       0
  5292.3    .035       0
#XS Ineff= 2 , 0
       0                 5129.57       0 1280.77
Permanent Ineff=
       F       F
Bank Sta=4973.8,4982.3
XS Rating Curve= 0 ,0
Exp/Cntr=0.3,0.1

Type RM Length L Ch R = 1 ,4074    ,439,439,439
BEGIN DESCRIPTION:
JACOBS CREEK 9.0
END DESCRIPTION:
XS GIS Cut Line= 3
      2073420.66     13899977.08        2073175.       13900225.
      2073115.26     13900781.29
#Sta/Elev= 30
  4650.7 1349.65  4667.4 1347.67  4674.5 1344.92  4695.7 1342.97  4709.8 1340.13
  4716.9 1336.82  4773.5 1327.07  4872.5 1316.11    4899 1309.04  4907.8 1307.28
  4914.9 1303.35    4929 1288.37  4957.3 1270.94  4964.4 1270.11  4971.5 1265.18
  4981.3 1262.41  4981.8 1261.91  4989.9 1262.41  4992.6 1263.51  4996.2 1269.66
  5009.8 1271.46  5120.4 1274.89  5293.5 1276.17  5332.1 1277.11  5371.8 1283.78
  5442.2 1291.78  5497.3 1294.83  5516.2 1296.85  5532.8 1301.02  5559.2  1303.4
#Mann= 6 ,-1 , 0
  4650.7     .12       0    4899     .07       0  4981.3    .035       0
  4989.9     .07       0  5293.5     .07       0  5497.3    .035       0
Bank Sta=4981.3,4989.9
XS Rating Curve= 0 ,0
Exp/Cntr=0.3,0.1

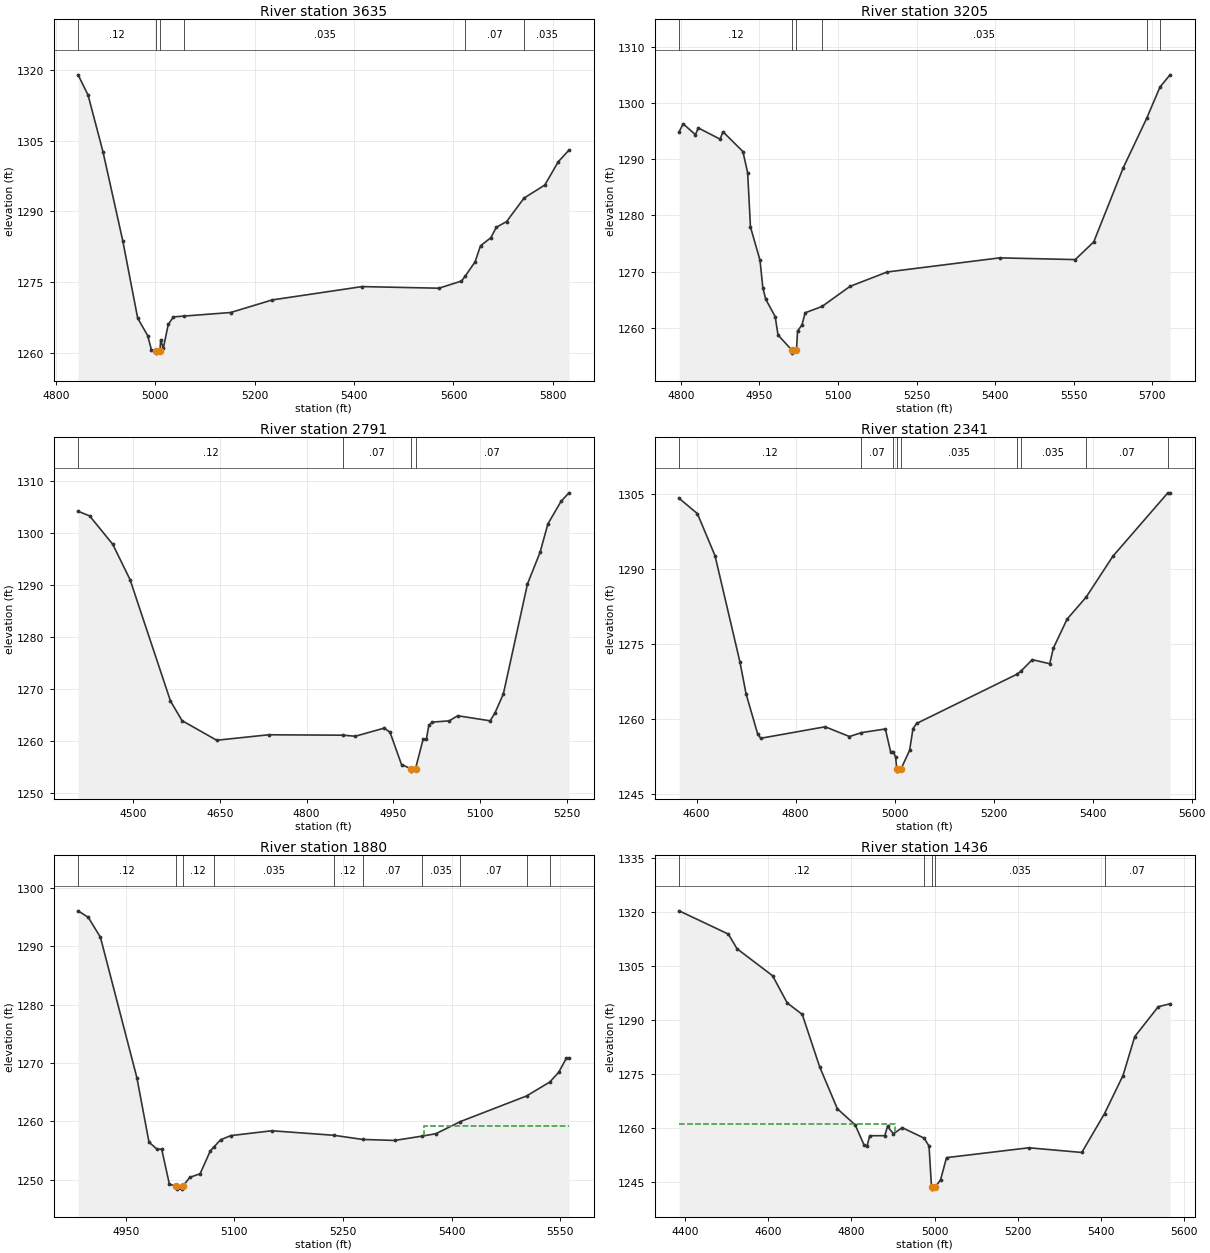
Type RM Length L Ch R = 1 ,3635    ,430,430,430
BEGIN DESCRIPTION:
JACOBS CREEK 8.0
END DESCRIPTION:
XS GIS Cut Line= 3
        2072825.     13899824.96        2072825.       13899975.
        2073075.     13900775.01
#Sta/Elev= 30
  4844.4 1318.93  4864.4 1314.66  4894.4 1302.67  4934.4 1283.74  4964.4 1267.35
  4984.4 1263.68  4991.9 1260.71  5000.6 1260.45  5001.1 1259.95  5009.2 1260.45
  5010.7  1262.8  5015.9 1260.95  5025.9 1266.04  5036.3 1267.63  5057.2  1267.8
  5151.6 1268.56  5235.4 1271.23  5416.1 1274.05  5570.7 1273.71  5616.2 1275.22
  5624.2 1276.35  5643.5 1279.28  5654.5  1282.7  5675.4 1284.42  5686.4 1286.63
  5706.9 1287.82  5742.2 1292.82  5783.9 1295.57  5811.1 1300.52  5832.6 1302.98
#Mann= 6 ,-1 , 0
  4844.4     .12       0  5000.6     .05       0  5009.2     .12       0
  5057.2    .035       0  5624.2     .07       0  5742.2    .035       0
Bank Sta=5000.6,5009.2
XS Rating Curve= 0 ,0
Exp/Cntr=0.3,0.1

Type RM Length L Ch R = 1 ,3205    ,414,414,414
BEGIN DESCRIPTION:
JACOBS CREEK 7.0
END DESCRIPTION:
XS GIS Cut Line= 3
      2072497.04     13900043.01        2072575.       13900225.
      2073014.11     13900820.41
#Sta/Elev= 30
  4796.5  1294.9  4804.1 1296.33  4827.6 1294.39  4833.1 1295.59  4874.8 1293.59
  4880.2 1294.92  4918.3 1291.39  4927.4  1287.6  4932.8 1277.94    4951 1272.02
  4956.4 1267.13  4961.8 1265.11    4980 1261.98  4985.4 1258.72  5012.1 1255.98
  5012.6 1255.48  5020.7 1255.98  5022.7 1259.43  5031.1 1260.49  5037.3 1262.67
  5069.5 1263.79  5122.9 1267.37  5193.9 1269.93    5409 1272.45  5553.2 1272.14
  5588.6  1275.3    5645 1288.51  5689.6 1297.28  5715.1 1302.88  5734.3 1305.05
#Mann= 6 ,-1 , 0
  4796.5     .12       0  5012.1     .05       0  5020.7     .12       0
  5069.5    .035       0  5689.6     .07       0  5715.1    .035       0
Bank Sta=5012.1,5020.7
XS Rating Curve= 0 ,0
Exp/Cntr=0.3,0.1

Type RM Length L Ch R = 1 ,2791    ,450,450,450
BEGIN DESCRIPTION:
JACOBS CREEK 6.0
END DESCRIPTION:
XS GIS Cut Line= 3
        2072325.     13899925.04        2072325.       13900525.
      2072174.98     13900725.03
#Sta/Elev= 30
  4404.3  1304.1  4424.3  1303.2  4464.3 1297.75  4494.3 1290.94  4564.3  1267.6
  4584.3 1263.83  4644.3 1260.06  4734.3 1261.11  4863.4 1261.03  4884.3 1260.83
  4934.3 1262.39  4944.3 1261.62  4964.3 1255.39  4979.9 1254.62  4980.4 1254.12
  4988.6 1254.62  5001.8 1260.27  5007.4 1260.27  5011.6 1262.92  5017.8 1263.55
    5047 1263.79  5061.6 1264.77  5117.8  1263.8  5126.1  1265.3  5140.7 1268.98
  5182.4 1290.11  5204.3 1296.22  5217.8 1301.67  5240.7 1306.03  5254.3 1307.64
#Mann= 4 ,-1 , 0
  4404.3     .12       0  4863.4     .07       0  4979.9     .05       0
  4988.6     .07       0
Bank Sta=4979.9,4988.6
XS Rating Curve= 0 ,0
Exp/Cntr=0.3,0.1

Type RM Length L Ch R = 1 ,2341    ,461,461,461
BEGIN DESCRIPTION:
JACOBS CREEK 5.0
END DESCRIPTION:
XS GIS Cut Line= 3
      2072275.03     13899924.96        2072025.       13900275.
      2071644.46      13900687.8
#Sta/Elev= 30
  4564.7 1304.13  4601.6 1301.07  4637.2 1292.65  4687.6 1271.37  4699.9 1265.03
  4723.3 1257.02  4729.4 1256.14  4859.7 1258.44  4908.8 1256.49    4933 1257.27
  4981.3    1258  4991.8 1253.47  4996.9 1253.47  5001.9 1252.42  5004.3 1250.07
  5004.8 1249.57  5013.1 1250.07  5030.3 1253.73  5037.1 1258.07  5044.5 1259.11
  5246.7 1268.93  5254.4  1269.5  5278.1 1271.86  5313.3 1271.05  5320.6 1274.16
  5348.5 1279.99  5387.1  1284.4  5440.9 1292.55  5551.9 1305.23  5556.3 1305.23
#Mann= 9 ,-1 , 0
  4564.7     .12       0    4933     .07       0  4996.9    .035       0
  5004.3    .035       0  5013.1    .035       0  5246.7     .07       0
  5254.4    .035       0  5387.1     .07       0  5551.9    .035       0
Bank Sta=5004.3,5013.1
XS Rating Curve= 0 ,0
Exp/Cntr=0.3,0.1

Type RM Length L Ch R = 1 ,1880    ,444,444,444
BEGIN DESCRIPTION:
JACOBS CREEK 4.0
END DESCRIPTION:
XS GIS Cut Line= 3
      2072125.02     13899824.99        2072025.       13899875.
      2071625.01     13900274.99
#Sta/Elev= 30
  4884.3  1296.1  4898.3 1294.99  4915.1 1291.58  4965.4 1267.51  4982.2 1256.42
  4993.3 1255.22  4999.7 1255.22  5010.3 1249.22    5020 1248.87  5020.5 1248.37
  5028.3 1248.37  5028.8 1248.87  5038.6 1250.39  5052.7 1251.01  5066.8 1254.93
  5071.7 1255.59    5081 1256.84  5095.1 1257.55  5151.7 1258.38  5236.9 1257.61
  5277.1 1256.89  5321.4 1256.72  5359.4 1257.47    5378 1257.87    5412 1259.96
  5503.3 1264.35  5535.3 1266.74  5547.7 1268.42  5558.3 1270.86  5561.8 1270.86
#Mann= 10 ,-1 , 0
  4884.3     .12       0    5020     .05       0  5028.8     .12       0
  5071.7    .035       0  5236.9     .12       0  5277.1     .07       0
  5359.4    .035       0    5412     .07       0  5503.3    .035       0
  5535.3     .07       0
#XS Ineff= 2 , 0
       0                 5361.15       0 1259.25
Permanent Ineff=
       F       F
Bank Sta=5020,5028.8
XS Rating Curve= 0 ,0
Exp/Cntr=0.3,0.1

Type RM Length L Ch R = 1 ,1436    ,449,449,449
BEGIN DESCRIPTION:
JACOBS CREEK 3.0
END DESCRIPTION:
XS GIS Cut Line= 3
      2072239.16     13899122.25        2071775.       13899525.
      2071375.02     13899924.98
#Sta/Elev= 30
  4385.7 1320.39    4504 1313.93  4524.9 1309.85  4610.4 1302.35  4645.5 1294.81
  4681.7  1291.6  4723.4  1277.1  4766.1 1265.38  4808.9 1260.91  4829.8 1255.45
  4837.4 1255.01    4844 1257.89  4880.1  1257.9  4886.7 1260.48    4901 1258.42
  4921.9 1260.14  4974.4 1257.24  4986.5 1255.03  4992.5 1243.55    4993 1243.05
  5001.3 1243.55  5014.4 1245.71  5028.5  1251.8  5226.5 1254.54  5353.8 1253.24
  5408.4 1264.04  5452.8 1274.61  5481.1 1285.44  5537.6 1293.75  5565.9 1294.55
#Mann= 5 ,-1 , 0
  4385.7     .12       0  4974.4    .035       0  4992.5    .035       0
  5001.3    .035       0  5408.4     .07       0
#XS Ineff= 2 , 0
       0 4904.69 1261.08               0
Permanent Ineff=
       F       F
Bank Sta=4992.5,5001.3
XS Rating Curve= 0 ,0
Exp/Cntr=0.3,0.1