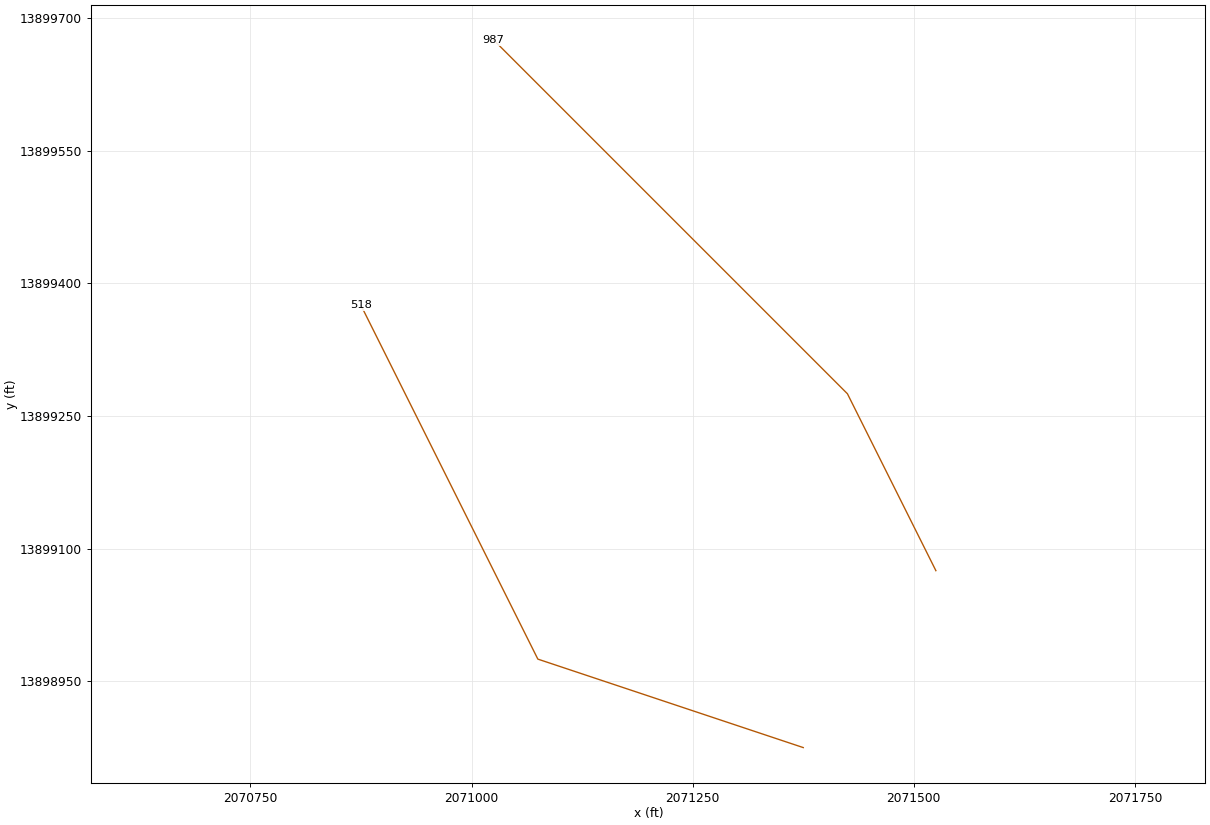
HEC-RAS study JACOBS CREEK.prj: JACOBS CREEK Base Level Engineering

--- JACOBS CREEK.g01 (geometry) --- (continued)

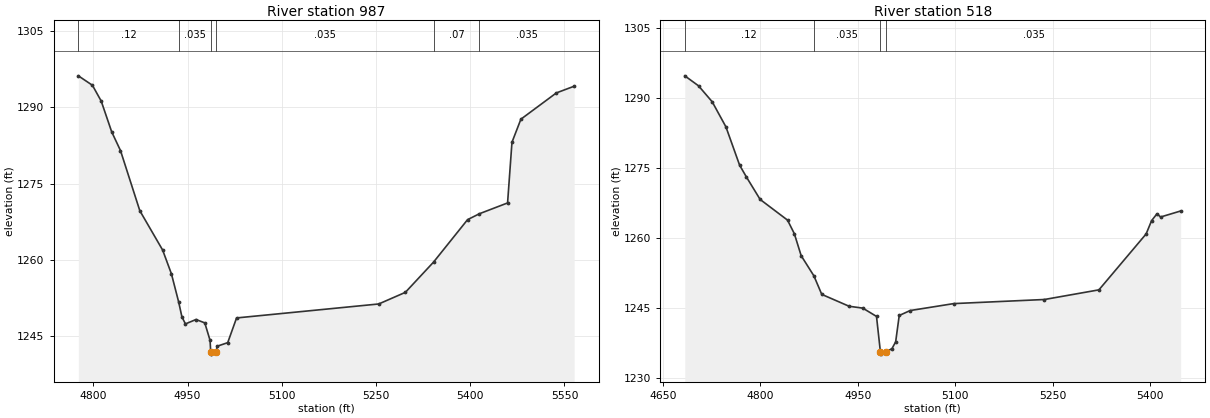
Type RM Length L Ch R = 1 ,987     ,469,469,469
BEGIN DESCRIPTION:
JACOBS CREEK 2.0
END DESCRIPTION:
XS GIS Cut Line= 3
      2071525.01     13899074.98        2071425.       13899275.
      2071025.01     13899674.99
#Sta/Elev= 30
  4776.1 1296.14  4798.5 1294.29  4812.5 1291.19  4829.2 1285.15  4843.2 1281.48
    4874 1269.67  4910.3 1261.96  4924.3 1257.29  4935.9 1251.73    4941 1248.84
  4946.6 1247.47  4963.4 1248.33  4977.4 1247.67  4985.8 1244.24  4986.8 1242.04
  4987.3 1241.54  4995.9 1242.04  4996.9 1243.08  5013.9 1243.79    5028 1248.64
  5254.3 1251.38  5296.7 1253.66  5341.6  1259.6  5395.7 1267.92  5414.7 1269.09
  5459.4  1271.2  5466.4  1283.1  5480.6 1287.63  5537.1 1292.79  5565.4  1294.1
#Mann= 6 ,-1 , 0
  4776.1     .12       0  4935.9    .035       0  4986.8    .035       0
  4995.9    .035       0  5341.6     .07       0  5414.7    .035       0
Bank Sta=4986.8,4995.9
XS Rating Curve= 0 ,0
Exp/Cntr=0.3,0.1

Type RM Length L Ch R = 1 ,518     ,0,0,0
BEGIN DESCRIPTION:
JACOBS CREEK 1.0
END DESCRIPTION:
XS GIS Cut Line= 3
      2071375.04     13898874.99        2071075.       13898975.
      2070874.99     13899375.02
#Sta/Elev= 30
  4683.7 1294.78  4704.8 1292.64  4725.9 1289.21    4747 1283.84  4768.1 1275.61
  4778.6 1273.07  4799.7 1268.26  4841.9 1263.82  4852.4  1260.9  4862.9 1256.19
  4882.5 1251.86  4894.6 1247.89  4936.7 1245.34  4957.8 1244.94  4978.9 1243.16
  4984.9 1235.57  4985.4 1235.07    4994 1235.57  5002.8 1236.27  5008.4 1237.71
  5013.9 1243.36  5030.7 1244.42  5097.8 1245.91  5237.5 1246.79  5321.4 1248.86
  5394.1 1260.86  5402.5 1263.71  5410.8 1265.18  5416.4 1264.49  5447.2 1265.78
#Mann= 4 ,-1 , 0
  4683.7     .12       0  4882.5    .035       0  4984.9    .035       0
    4994    .035       0
Bank Sta=4984.9,4994
XS Rating Curve= 0 ,0
Exp/Cntr=0.3,0.1

Chan Stop Cuts=-1
Use User Specified Reach Order=0
Composite Channel Slope=5