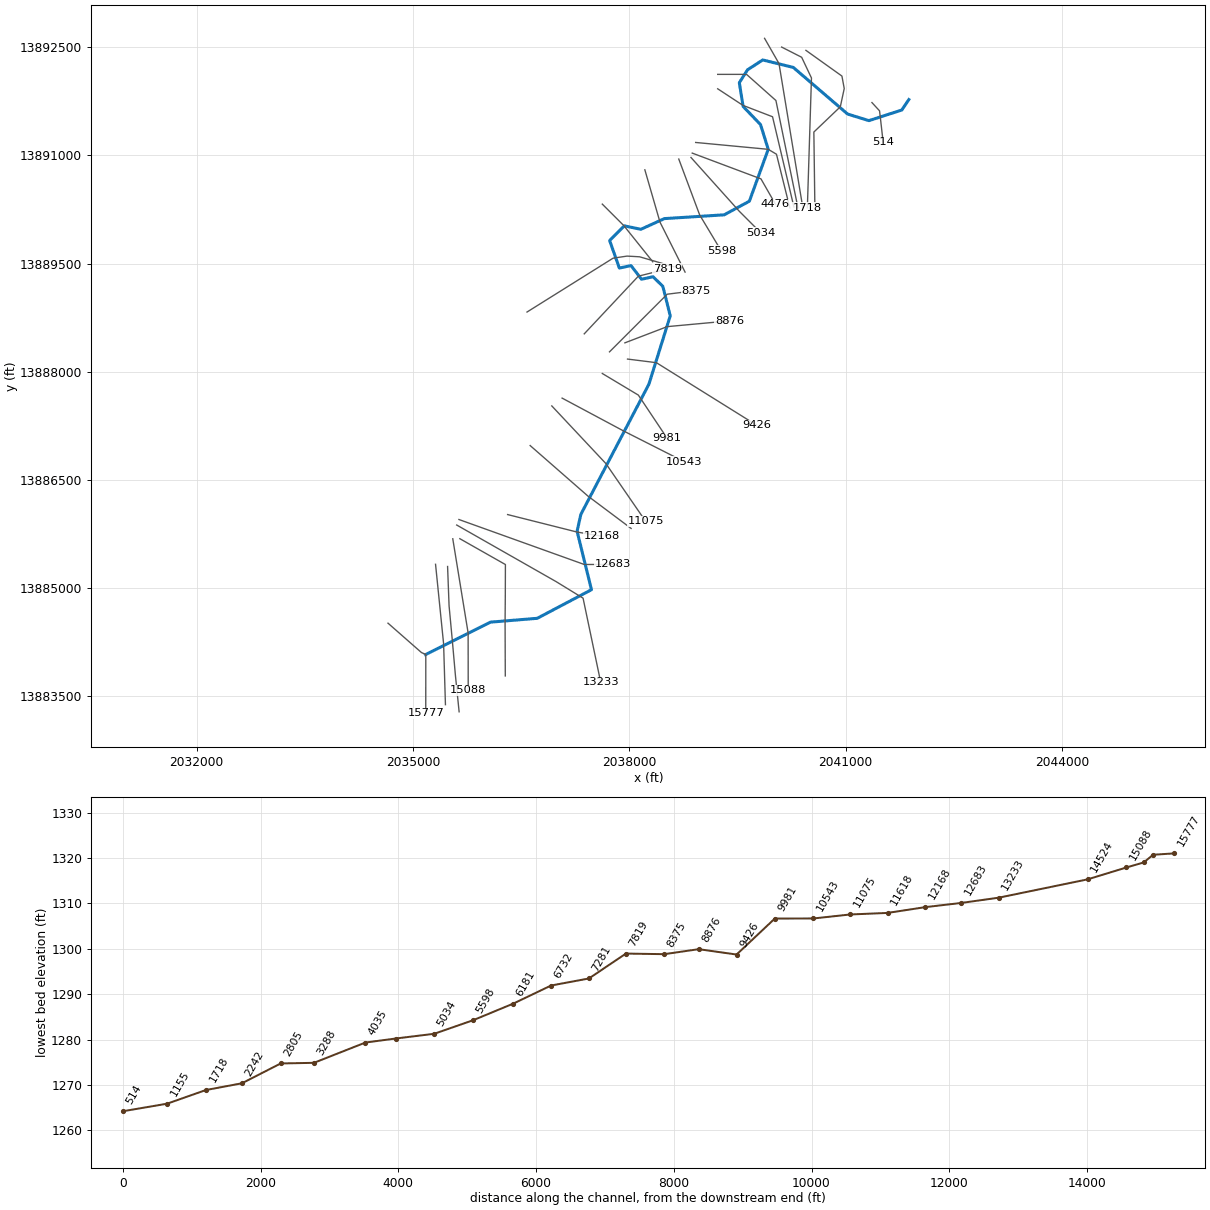
--- JOSHUA CREEK.prj (project) ---

Proj Title=JOSHUA CREEK Base Level Engineering
Current Plan=p01
Default Exp/Contr=0.3,0.1
English Units
Geom File=g01
Flow File=f01
Plan File=p01
Y Axis Title=Elevation
X Axis Title(PF)=Main Channel Distance
X Axis Title(XS)=Station
BEGIN DESCRIPTION:
JOSHUA CREEK
END DESCRIPTION:
DSS Export Rating Curves= 0
DSS Export Rating Curve Sorted= 0
DSS Export Volume Flow Curves= 0
DXF OffsetX= 0
DXF OffsetY= 0
DXF ScaleX= 1
DXF ScaleY= 10

--- JOSHUA CREEK.p01 (plan) ---

Plan Title=Multiple Run
Short Identifier=Multiple
Geom File=g01
Flow File=f01
Subcritical Flow
K Sum by GR= 0
Std Step Tol= 0.01
Critical Tol= 0.01
Num of Std Step Trials= 20
Max Error Tol= 0.3
Flow Tol Ratio= 0.001
Split Flow NTrial= 30
Split Flow Tol= 0.02
Split Flow Ratio= 0.02
Log Output Level= 0
Friction Slope Method= 1
Unsteady Friction Slope Method= 2
Unsteady Bridges Friction Slope Method= 1
Parabolic Critical Depth
Global Vel Dist=  1 , 1 , 1
Global Log Level= 0
CheckData=True
Encroach Param= -1, 0, 0, 0
BEGIN DESCRIPTION:
Multiple Run
END DESCRIPTION:

--- JOSHUA CREEK.f01 (steady flow) ---

Flow Title=Multiple
Program Version=4.10
Number of Profiles= 7
Profile Names=10-year,25-year,50-year,1pct_min,100-year,1pct_plu,500-year
River Rch & RM=JOSHUA CREEK,Reach-1         ,15777
   12388   22947   33856   24011   47909   95591   94995
River Rch & RM=JOSHUA CREEK,Reach-1         ,14524
   12938   23917   35246   24968   49818   99400   98505
River Rch & RM=JOSHUA CREEK,Reach-1         ,12683
   12993   24002   35353   25030   49942   99647   98637
River Rch & RM=JOSHUA CREEK,Reach-1         ,9426
   13070   24129   35524   25139   50159  100081   98968
River Rch & RM=JOSHUA CREEK,Reach-1         ,6181
   13008   23990   35295   24959   49799   99362   98112
River Rch & RM=JOSHUA CREEK,Reach-1         ,514
   13116   24191   35591   25168   50217  100196   98935
Boundary for River Rch & Prof#=JOSHUA CREEK,Reach-1         , 1
Up Type= 0
Dn Type= 3
Dn Slope=0.009
Boundary for River Rch & Prof#=JOSHUA CREEK,Reach-1         , 2
Up Type= 0
Dn Type= 3
Dn Slope=0.009
Boundary for River Rch & Prof#=JOSHUA CREEK,Reach-1         , 3
Up Type= 0
Dn Type= 3
Dn Slope=0.009
Boundary for River Rch & Prof#=JOSHUA CREEK,Reach-1         , 4
Up Type= 0
Dn Type= 3
Dn Slope=0.009
Boundary for River Rch & Prof#=JOSHUA CREEK,Reach-1         , 5
Up Type= 0
Dn Type= 3
Dn Slope=0.009
Boundary for River Rch & Prof#=JOSHUA CREEK,Reach-1         , 6
Up Type= 0
Dn Type= 3
Dn Slope=0.009
Boundary for River Rch & Prof#=JOSHUA CREEK,Reach-1         , 7
Up Type= 0
Dn Type= 3
Dn Slope=0.009
DSS Import GetInterval= 0
DSS Import GetPeak= 0
DSS Import FillOption= 0

--- JOSHUA CREEK.g01 (geometry) ---

Geom Title=Existing Conditions
Program Version=4.10

River Reach=JOSHUA CREEK    ,Reach-1
Reach XY= 30
        2035175.       13884075.        2036075.       13884525.
      2036723.35     13884578.16        2037475.       13884975.
      2037275.61     13885785.62      2037327.27     13886019.06
      2038271.46     13887826.47      2038567.22      13888775.1
      2038464.24     13889184.69      2038328.42      13889317.2
      2038168.55     13889282.64      2038023.38     13889471.87
      2037861.43     13889437.98      2037727.06     13889819.15
      2037931.03     13890023.38      2038159.83     13889975.37
       2038485.5     13890123.78       2039314.5     13890176.22
      2039664.24     13890365.32      2039925.82     13891085.07
      2039819.54     13891427.45      2039577.06     13891680.85
      2039524.96     13892009.66      2039638.62     13892188.24
      2039849.91     13892325.21       2040273.5     13892221.38
        2041025.       13891575.       2041321.7     13891483.08
      2041777.44     13891630.51        2041875.       13891775.

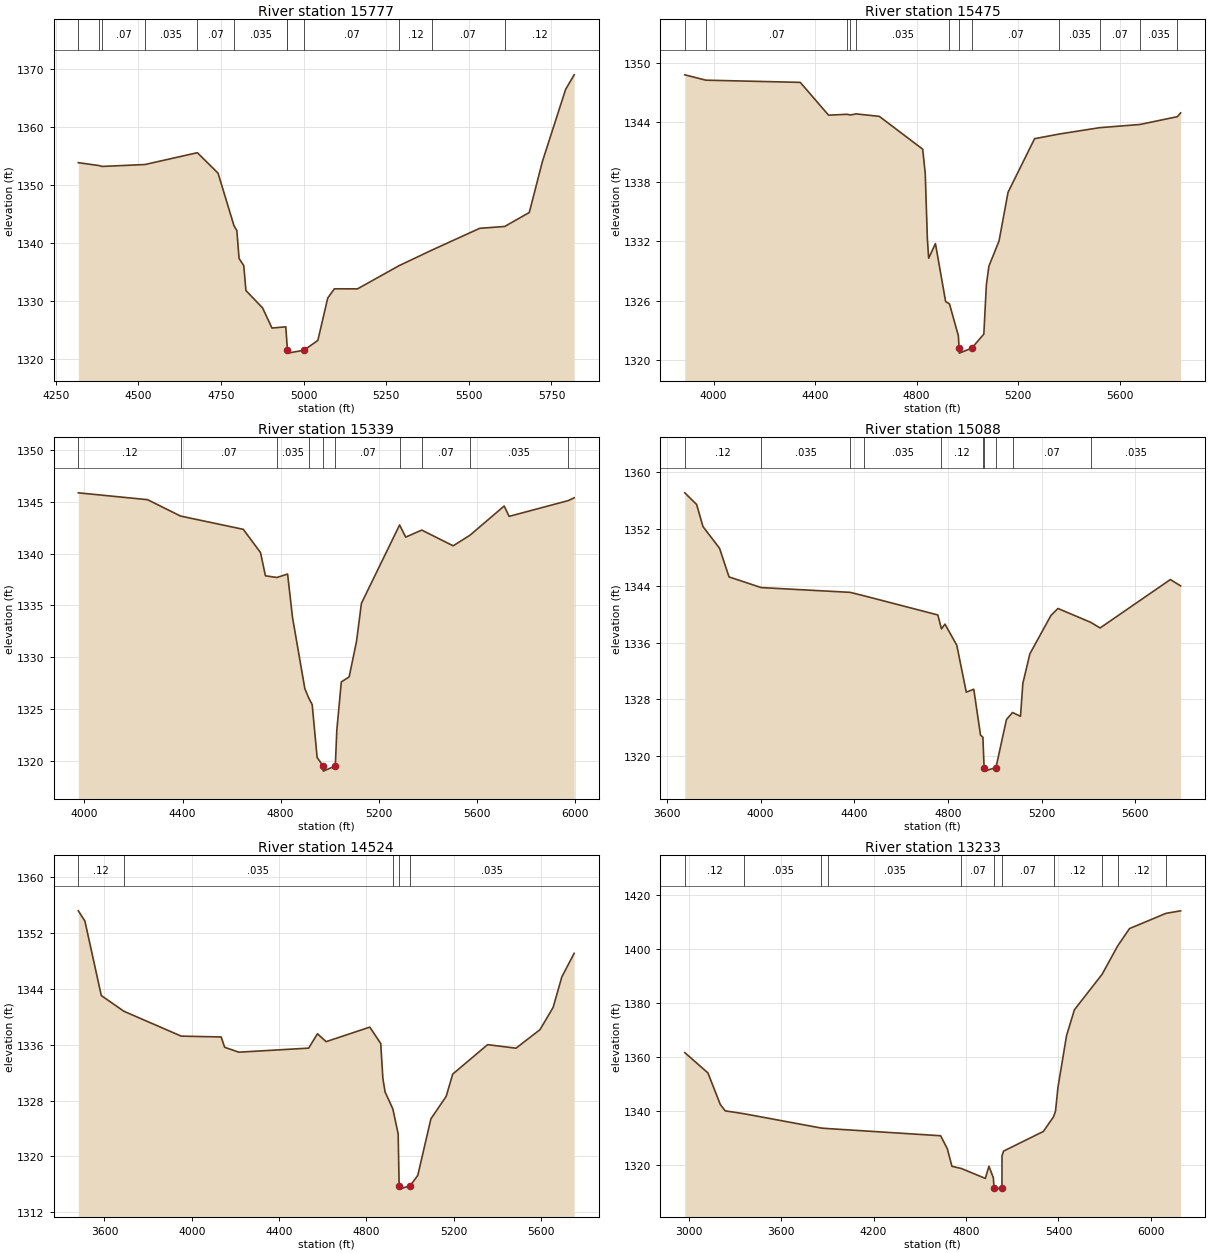
Type RM Length L Ch R = 1 ,15777   ,302,302,302
BEGIN DESCRIPTION:
JOSHUA CREEK 28.0
END DESCRIPTION:
XS GIS Cut Line= 4
      2034654.09     13884510.67      2035118.13     13884103.01
      2035178.06     13884076.76      2035177.56     13883259.16
#Sta/Elev= 30
  4317.9 1353.89  4380.5 1353.39  4390.3 1353.24  4519.5 1353.57  4678.2 1355.61
  4740.8 1352.08  4789.2 1342.98  4797.7 1342.17  4804.4 1337.36  4818.6 1336.12
  4825.2 1331.82  4875.5 1328.83    4904 1325.35  4945.8 1325.56  4950.6 1321.68
  4950.8 1321.52  4951.8 1321.02  5000.8 1321.52  5042.8 1323.21  5072.8 1330.53
  5092.8 1332.12  5162.8 1332.11  5288.9 1336.12  5387.3 1338.78  5532.8 1342.56
  5608.4 1342.88  5682.8 1345.29  5722.8 1354.15  5792.8 1366.54  5818.6 1369.05
#Mann= 12 ,-1 , 0
  4317.9     .07       0  4380.5    .035       0  4390.3     .07       0
  4519.5    .035       0  4678.2     .07       0  4789.2    .035       0
  4950.6     .07       0  4950.8     .05       0  5000.8     .07       0
  5288.9     .12       0  5387.3     .07       0  5608.4     .12       0
Bank Sta=4950.8,5000.8
XS Rating Curve= 0 ,0
Exp/Cntr=0.3,0.1

Type RM Length L Ch R = 1 ,15475   ,136,136,136
BEGIN DESCRIPTION:
JOSHUA CREEK 27.0
END DESCRIPTION:
XS GIS Cut Line= 3
      2035313.31     13885327.69        2035425.       13884225.
      2035450.47     13883379.81
#Sta/Elev= 30
  3886.7 1348.79  3969.9 1348.25  4341.7 1348.03  4453.3 1344.72  4525.5 1344.81
  4539.6 1344.74  4561.6 1344.85  4653.3  1344.6  4824.2 1341.29  4834.2 1338.84
  4842.7 1332.22  4847.7 1330.29  4874.4 1331.77  4914.6 1325.92  4929.8 1325.68
  4964.9 1322.46  4967.5 1321.22  4968.5 1320.72  5017.5 1321.22  5065.1 1322.64
  5075.1 1327.61  5085.1 1329.49  5125.1 1332.04  5160.6 1336.95  5265.2 1342.35
  5362.7 1342.82  5521.6 1343.46  5680.1 1343.78  5827.9 1344.57  5840.6 1344.95
#Mann= 12 ,-1 , 0
  3886.7    .035       0  3969.9     .07       0  4525.5    .035       0
  4539.6     .07       0  4561.6    .035       0  4929.8     .07       0
  4967.5     .05       0  5017.5     .07       0  5362.7    .035       0
  5521.6     .07       0  5680.1    .035       0  5827.9     .07       0
Bank Sta=4967.5,5017.5
XS Rating Curve= 0 ,0
Exp/Cntr=0.3,0.1

Type RM Length L Ch R = 1 ,15339   ,251,251,251
BEGIN DESCRIPTION:
JOSHUA CREEK 26.0
END DESCRIPTION:
XS GIS Cut Line= 5
      2035480.19     13885297.18      2035500.88     13884751.14
      2035545.69     13884272.13      2035588.47     13883789.35
      2035640.09     13883280.97
#Sta/Elev= 30
  3974.9 1345.86  4257.3  1345.2    4392 1343.62    4648 1342.34  4718.3  1340.1
  4738.4 1337.86  4785.3  1337.7  4828.8 1338.03  4848.9 1333.84  4899.1 1326.99
  4914.8 1326.09  4929.2 1325.44  4949.3 1320.35  4973.5 1319.53  4974.5 1319.03
  5023.5 1319.53  5029.7    1323    5048 1327.63  5079.9 1328.11    5110 1331.53
  5130.1 1335.21  5285.8 1342.76  5310.8 1341.59  5376.3 1342.27  5504.4 1340.75
  5573.4 1341.78  5712.6 1344.59  5732.7 1343.59    5974 1345.11  5998.1 1345.38
#Mann= 10 ,-1 , 0
  3974.9     .12       0    4392     .07       0  4785.3    .035       0
  4914.8     .07       0  4973.5     .05       0  5023.5     .07       0
  5285.8    .035       0  5376.3     .07       0  5573.4    .035       0
    5974     .07       0
Bank Sta=4973.5,5023.5
XS Rating Curve= 0 ,0
Exp/Cntr=0.3,0.1

Type RM Length L Ch R = 1 ,15088   ,564,564,564
BEGIN DESCRIPTION:
JOSHUA CREEK 25.5
END DESCRIPTION:
XS GIS Cut Line= 3
      2035552.11     13885681.51      2035764.95     13884375.13
      2035766.26     13883581.23
#Sta/Elev= 30
  3676.4 1357.07    3727 1355.43  3753.9 1352.33  3824.8 1349.27  3865.4 1345.24
  4002.7 1343.74  4382.6 1343.07  4443.5 1342.57    4757 1339.89  4772.5 1337.93
  4787.5  1338.6    4838 1335.63  4878.5 1329.03  4910.5 1329.44  4939.3    1323
  4949.5 1322.68  4954.6 1318.42  4955.6 1317.92  5005.2 1318.42  5050.1 1325.17
  5076.1 1326.17  5110.1 1325.63  5120.1 1330.26  5150.1 1334.42  5240.1 1339.82
  5270.1  1340.8  5410.1 1338.85  5450.1 1338.06  5750.1 1344.87  5793.9 1343.98
#Mann= 10 ,-1 , 0
  3676.4     .12       0  4002.7    .035       0  4382.6     .07       0
  4443.5    .035       0  4772.5     .12       0  4949.5    .035       0
  4954.6    .035       0  5005.2    .035       0  5076.1     .07       0
  5410.1    .035       0
Bank Sta=4954.6,5005.2
XS Rating Curve= 0 ,0
Exp/Cntr=0.3,0.1

Type RM Length L Ch R = 1 ,14524   ,1291,1291,1291
BEGIN DESCRIPTION:
JOSHUA CREEK 25.0
END DESCRIPTION:
XS GIS Cut Line= 5
      2035650.09     13885682.78      2036281.89      13885324.2
      2036280.42     13884884.71      2036277.35     13884530.78
      2036280.26     13883778.49
#Sta/Elev= 30
  3480.1 1355.19  3510.2 1353.73  3585.3 1343.05  3688.5  1340.8  3951.6 1337.23
  4134.7 1337.11  4150.6 1335.63  4215.8 1334.93  4535.8 1335.51  4575.8 1337.57
  4615.8 1336.44  4815.8 1338.52  4865.8 1336.18  4875.8 1331.16  4885.8 1329.23
  4921.4  1326.8  4945.8 1323.22  4950.2  1315.8  4951.2  1315.3  5001.4  1315.8
  5035.8 1317.28  5095.8 1325.37  5165.8  1328.6  5195.8 1331.79  5355.8 1336.01
  5485.8  1335.5  5595.8 1338.16  5655.8 1341.34  5695.8 1345.72  5752.3  1349.1
#Mann= 5 ,-1 , 0
  3480.1     .12       0  3688.5    .035       0  4921.4     .07       0
  4950.2    .035       0  5001.4    .035       0
Bank Sta=4950.2,5001.4
XS Rating Curve= 0 ,0
Exp/Cntr=0.3,0.1

Type RM Length L Ch R = 1 ,13233   ,550,550,550
BEGIN DESCRIPTION:
JOSHUA CREEK 24.0
END DESCRIPTION:
XS GIS Cut Line= 4
      2035606.73     13885872.43      2036983.36     13885088.15
      2037358.49     13884857.95       2037603.1     13883690.49
#Sta/Elev= 30
  2975.5 1361.74  3125.4 1354.25    3206 1342.55  3237.7 1340.21  3360.8 1339.13
    3862 1333.83  3906.6 1333.64  4635.4    1331  4679.1 1326.19  4708.9  1319.7
  4769.9 1318.89  4925.5 1315.23    4949 1319.72  4977.6 1315.44  4982.1 1311.76
  4983.1 1311.26  5033.4 1311.76  5033.7 1323.54  5043.9 1325.32  5302.2 1332.59
  5368.4 1338.03    5381  1340.1  5396.9 1348.93  5452.6 1368.03  5503.6 1377.58
  5683.3  1390.7  5784.7 1401.22  5861.2 1407.61  6097.8 1413.24  6192.8 1414.17
#Mann= 11 ,-1 , 0
  2975.5     .12       0  3360.8    .035       0    3862     .07       0
  3906.6    .035       0  4769.9     .07       0  4982.1     .05       0
  5033.4     .07       0  5368.4     .12       0  5683.3     .07       0
  5784.7     .12       0  6097.8     .07       0
Bank Sta=4982.1,5033.4
XS Rating Curve= 0 ,0
Exp/Cntr=0.3,0.1

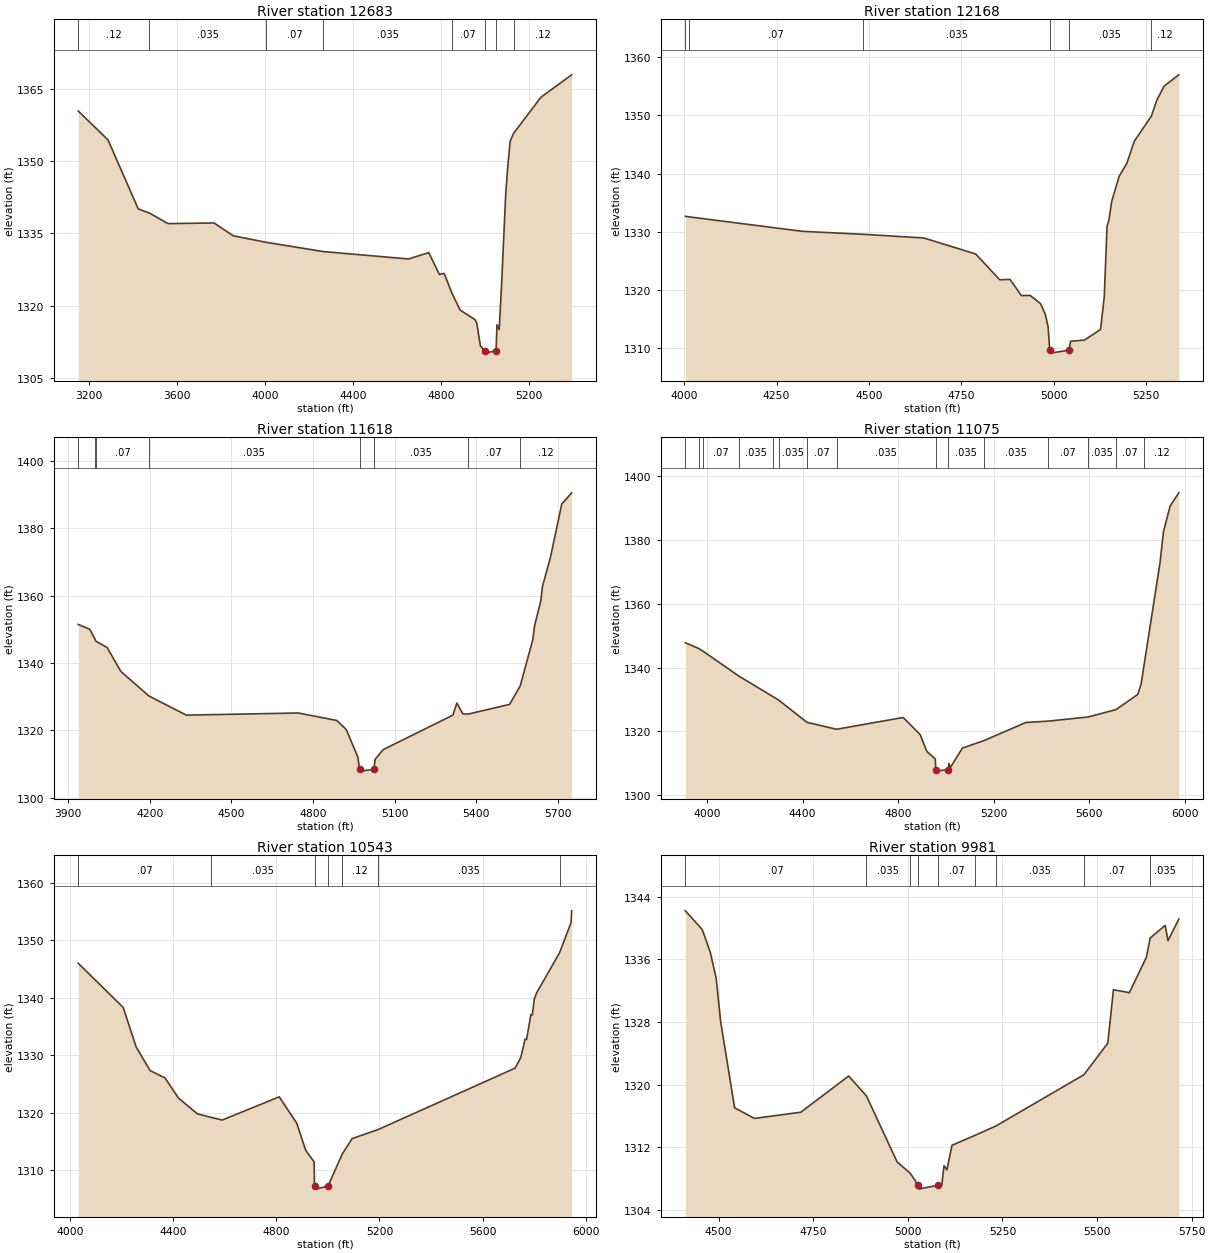
Type RM Length L Ch R = 1 ,12683   ,515,515,515
BEGIN DESCRIPTION:
JOSHUA CREEK 23.0
END DESCRIPTION:
XS GIS Cut Line= 3
      2035637.59     13885948.86        2037375.       13885325.
      2037774.98       13885325.
#Sta/Elev= 30
  3149.4 1360.49  3284.8 1354.49  3422.9  1340.1  3473.4 1339.25    3558 1337.05
  3767.8 1337.18  3854.7 1334.52    4003 1333.17  4264.9 1331.23  4652.6 1329.69
  4744.8 1331.01  4793.5 1326.46  4814.8 1326.69  4850.1 1322.62  4887.9 1319.05
  4954.6  1317.1  4963.5 1316.37  4980.1 1311.57  4999.5 1310.59  5000.5 1310.09
  5051.4 1310.59  5055.4    1316  5065.4    1315  5075.4 1323.39  5095.4 1343.36
  5105.4 1349.38  5115.4  1354.2  5131.4 1355.86  5255.4 1363.36  5395.4 1368.02
#Mann= 8 ,-1 , 0
  3149.4     .12       0  3473.4    .035       0    4003     .07       0
  4264.9    .035       0  4850.1     .07       0  4999.5     .05       0
  5051.4     .07       0  5131.4     .12       0
Bank Sta=4999.5,5051.4
XS Rating Curve= 0 ,0
Exp/Cntr=0.3,0.1

Type RM Length L Ch R = 1 ,12168   ,550,550,550
BEGIN DESCRIPTION:
JOSHUA CREEK 22.0
END DESCRIPTION:
XS GIS Cut Line= 3
      2036312.49     13886017.57        2037275.       13885775.
      2037614.09     13885718.36
#Sta/Elev= 30
    4003 1332.67  4013.5 1332.57  4320.3 1330.09    4485 1329.58    4649 1328.95
  4789.4  1326.2  4854.4 1321.77  4882.2 1321.84  4913.1 1319.05  4936.6 1319.09
  4964.7 1317.69  4977.6 1315.91  4985.3 1313.72  4989.9 1309.68  4990.9 1309.18
  5041.8 1309.68  5046.3 1311.21  5084.2 1311.43  5127.4 1313.25  5137.5 1318.88
    5145  1330.9  5150.1 1332.04  5157.8 1335.27  5178.1 1339.58  5198.4 1341.72
  5218.7 1345.55  5265.3  1349.9  5279.5 1352.56  5299.8 1355.05  5339.4 1356.96
#Mann= 6 ,-1 , 0
    4003    .035       0  4013.5     .07       0    4485    .035       0
  4989.9    .035       0  5041.8    .035       0  5265.3     .12       0
Bank Sta=4989.9,5041.8
XS Rating Curve= 0 ,0
Exp/Cntr=0.3,0.1

Type RM Length L Ch R = 1 ,11618   ,543,543,543
BEGIN DESCRIPTION:
JOSHUA CREEK 21.0
END DESCRIPTION:
XS GIS Cut Line= 3
      2036624.97     13886975.02        2037425.       13886275.
      2038024.96     13885825.03
#Sta/Elev= 30
    3937 1351.42  3979.3 1349.99  3998.1 1347.16  4001.7 1346.46  4043.3 1344.57
  4093.2 1337.52  4196.9 1330.19  4334.2 1324.51  4745.2 1325.15  4886.6 1322.94
  4921.7 1320.26  4964.5 1312.06  4970.7  1308.4  4971.7  1307.9  5022.7  1308.4
  5028.2 1311.42  5057.3 1314.27  5313.6 1324.51  5328.2  1328.1  5350.1  1324.9
  5369.6 1324.82  5521.9  1327.7  5560.8 1333.15  5607.3 1346.96  5613.6 1351.01
  5636.5  1358.4  5642.8 1362.71  5671.9 1371.29  5713.6 1387.15    5750 1390.47
#Mann= 8 ,-1 , 0
    3937     .07       0  3998.1     .12       0  4001.7     .07       0
  4196.9    .035       0  4970.7    .035       0  5022.7    .035       0
  5369.6     .07       0  5560.8     .12       0
Bank Sta=4970.7,5022.7
XS Rating Curve= 0 ,0
Exp/Cntr=0.3,0.1

Type RM Length L Ch R = 1 ,11075   ,532,532,532
BEGIN DESCRIPTION:
JOSHUA CREEK 20.0
END DESCRIPTION:
XS GIS Cut Line= 3
      2036925.03     13887524.96        2037675.       13886725.
      2038225.02     13885924.97
#Sta/Elev= 30
  3908.6 1347.81  3964.5    1346  3982.8 1345.15  4131.8  1337.4    4276 1330.89
  4299.9  1329.8  4418.1 1322.86    4542 1320.68  4821.2 1324.38  4892.1 1319.05
  4920.4 1313.72  4955.6 1311.39  4957.9 1308.06  4958.9 1307.56  5009.9 1308.06
  5012.6    1310  5018.7 1308.68  5069.4 1314.78  5159.5 1317.13  5335.3 1322.81
  5428.4 1323.23  5596.3 1324.54  5713.1 1326.86  5804.1 1331.61  5818.2 1334.95
    5830 1340.64  5896.8  1372.7  5911.7 1382.66  5939.6 1390.68    5976  1394.8
#Mann= 15 ,-1 , 0
  3908.6     .07       0  3964.5    .035       0  3982.8     .07       0
  4131.8    .035       0    4276     .07       0  4299.9    .035       0
  4418.1     .07       0    4542    .035       0  4957.9     .05       0
  5009.9    .035       0  5159.5    .035       0  5428.4     .07       0
  5596.3    .035       0  5713.1     .07       0    5830     .12       0
Bank Sta=4957.9,5009.9
XS Rating Curve= 0 ,0
Exp/Cntr=0.3,0.1

Type RM Length L Ch R = 1 ,10543   ,562,562,562
BEGIN DESCRIPTION:
JOSHUA CREEK 19.0
END DESCRIPTION:
XS GIS Cut Line= 3
      2037067.97     13887633.32        2037925.       13887175.
      2038763.99     13886749.96
#Sta/Elev= 30
  4032.7 1345.97  4207.2 1338.28  4256.8 1331.45  4311.3  1327.3  4369.5 1326.01
    4421 1322.53  4494.3 1319.79  4549.2 1319.14  4590.9  1318.7  4811.8 1322.73
  4879.8 1318.14  4914.3 1313.44  4946.9 1311.42  4948.5 1307.18  4949.5 1306.68
  5000.5 1307.18  5056.5 1312.82  5094.3 1315.47    5195 1317.04  5725.7 1327.72
    5748 1329.57  5764.6  1332.8  5770.2 1332.69  5786.9 1337.02  5792.5 1336.97
  5800.5 1339.79  5809.2 1340.81  5898.6 1347.84  5942.8 1353.06  5945.1 1355.09
#Mann= 7 ,-1 , 0
  4032.7     .07       0  4549.2    .035       0  4948.5    .035       0
  5000.5    .035       0  5056.5     .12       0    5195    .035       0
  5898.6     .07       0
Bank Sta=4948.5,5000.5
XS Rating Curve= 0 ,0
Exp/Cntr=0.3,0.1

Type RM Length L Ch R = 1 ,9981    ,555,555,555
BEGIN DESCRIPTION:
JOSHUA CREEK 18.0
END DESCRIPTION:
XS GIS Cut Line= 3
      2037625.03     13887974.98        2038125.       13887675.
      2038525.02     13887074.97
#Sta/Elev= 30
    4412  1342.2  4456.7 1339.81    4478 1336.89  4493.6 1333.54  4505.3 1328.05
  4542.2 1317.04  4594.7 1315.69  4717.1 1316.48  4843.5  1321.1  4890.3 1318.59
  4971.7 1310.13    5006  1308.7  5027.6 1307.16  5028.6 1306.66  5079.6 1307.16
  5089.7 1307.16  5095.7 1309.66  5103.2 1309.12  5116.7 1312.26  5177.2 1313.52
  5232.7 1314.72  5465.4 1321.27  5528.4 1325.29  5543.4 1332.12  5585.5 1331.75
  5630.5 1336.27  5640.5 1338.73  5680.1 1340.34  5687.6 1338.39  5716.2 1341.16
#Mann= 9 ,-1 , 0
    4412     .07       0  4890.3    .035       0    5006     .07       0
  5027.6    .035       0  5079.6     .07       0  5177.2     .12       0
  5232.7    .035       0  5465.4     .07       0  5640.5    .035       0
Bank Sta=5027.6,5079.6
XS Rating Curve= 0 ,0
Exp/Cntr=0.3,0.1

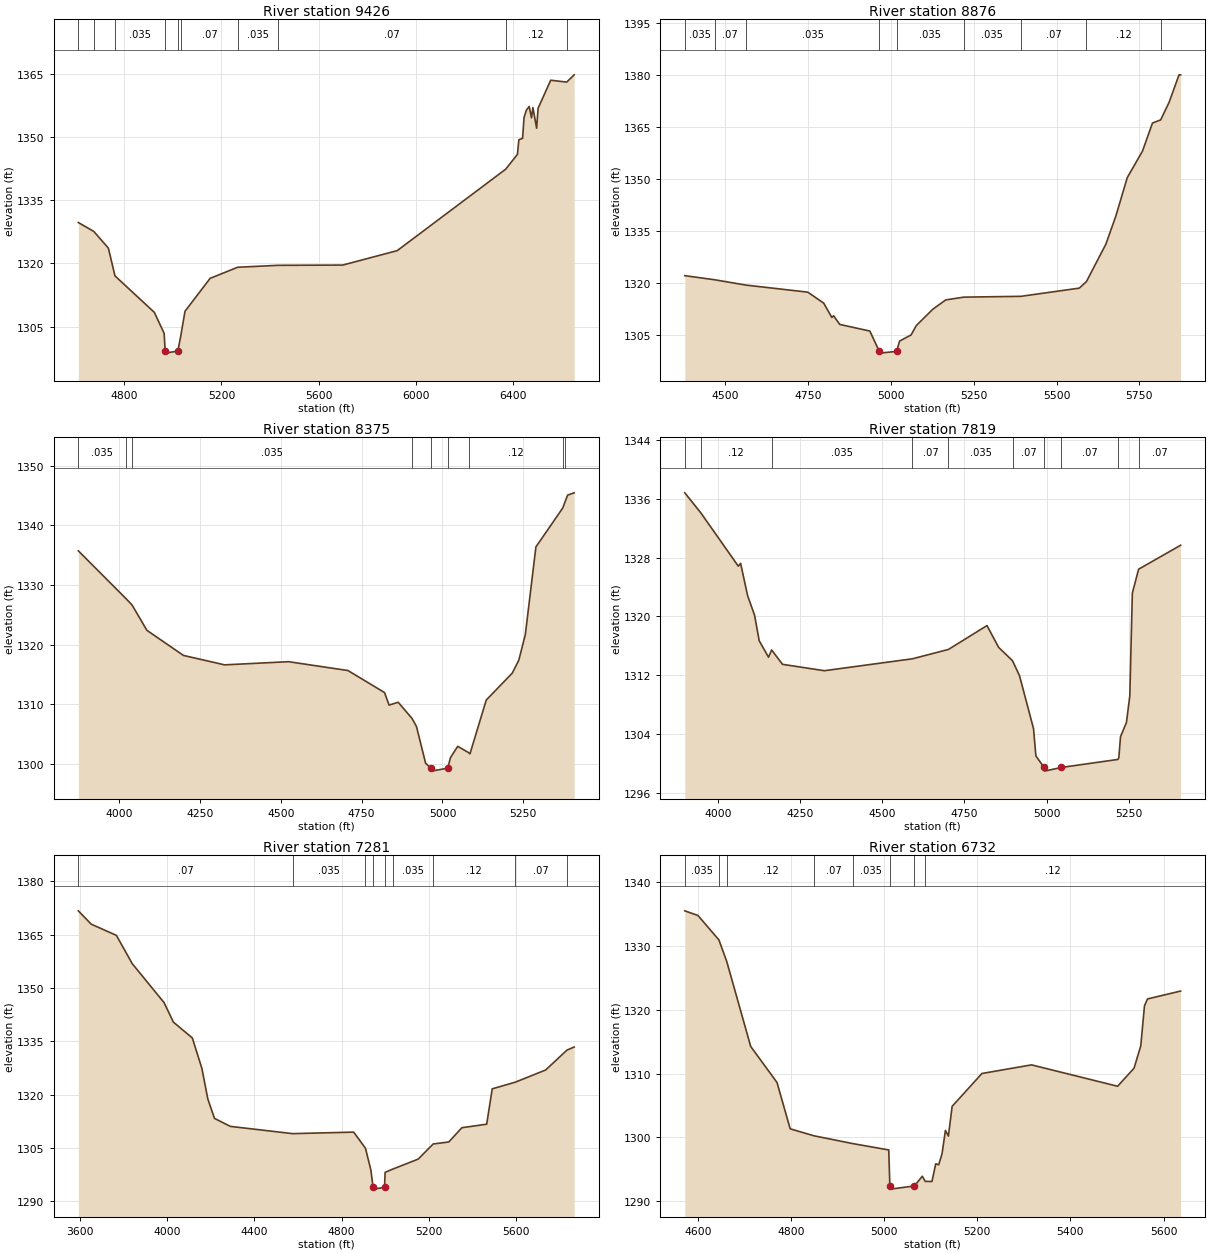
Type RM Length L Ch R = 1 ,9426    ,550,550,550
BEGIN DESCRIPTION:
JOSHUA CREEK 17.0
END DESCRIPTION:
XS GIS Cut Line= 3
      2037974.95     13888175.01        2038375.       13888125.
      2039762.04      13887259.1
#Sta/Elev= 30
  4611.5 1329.68  4675.2 1327.57    4735 1323.62  4762.1 1317.04    4924 1308.39
  4964.3 1303.42  4968.4 1299.23  4969.4 1298.73  5020.7 1299.23  5033.5 1303.08
    5050 1308.65  5153.3 1316.45  5266.4 1319.08  5431.9 1319.54  5698.2  1319.6
  5922.4 1323.02  6368.2 1342.32  6416.6 1345.83  6422.5  1349.3  6437.8 1349.66
  6443.7 1354.55  6452.9 1356.25  6464.9  1357.2  6474.4 1354.49  6480.2 1356.92
  6495.6 1352.04  6501.5 1356.75  6553.4 1363.41  6619.2 1362.97  6649.8 1364.69
#Mann= 10 ,-1 , 0
  4611.5    .035       0  4675.2     .07       0  4762.1    .035       0
  4968.4    .035       0  5020.7    .035       0  5033.5     .07       0
  5266.4    .035       0  5431.9     .07       0  6368.2     .12       0
  6619.2     .07       0
Bank Sta=4968.4,5020.7
XS Rating Curve= 0 ,0
Exp/Cntr=0.3,0.1

Type RM Length L Ch R = 1 ,8876    ,501,501,501
BEGIN DESCRIPTION:
JOSHUA CREEK 16.0
END DESCRIPTION:
XS GIS Cut Line= 3
      2037938.27      13888400.1        2038525.       13888625.
      2039389.66     13888704.89
#Sta/Elev= 30
  4377.8  1322.2  4467.7 1321.02    4562 1319.49  4749.1 1317.45    4797 1314.31
  4821.6 1310.18    4827 1310.66  4845.5 1308.17  4936.4 1306.26    4965 1300.41
    4966 1299.91  5017.3 1300.41  5026.2 1303.38    5061 1305.15  5076.5 1307.83
  5126.7 1312.56  5165.5 1315.22  5220.2 1316.02  5392.6 1316.25  5568.5 1318.61
    5590 1320.46  5648.9 1331.27    5679 1339.35  5713.4  1350.4  5759.4 1358.04
  5789.5  1366.1  5814.3 1367.02  5839.7 1372.06  5869.7 1379.98  5874.5 1379.98
#Mann= 9 ,-1 , 0
  4377.8    .035       0  4467.7     .07       0    4562    .035       0
    4965    .035       0  5017.3    .035       0  5220.2    .035       0
  5392.6     .07       0    5590     .12       0  5814.3     .07       0
Bank Sta=4965,5017.3
XS Rating Curve= 0 ,0
Exp/Cntr=0.3,0.1

Type RM Length L Ch R = 1 ,8375    ,556,556,556
BEGIN DESCRIPTION:
JOSHUA CREEK 15.0
END DESCRIPTION:
XS GIS Cut Line= 3
      2037724.97     13888274.97        2038525.       13889075.
      2038924.97       13889125.
#Sta/Elev= 30
  3873.1 1335.73  4021.9 1327.65  4039.4 1326.65  4085.3 1322.41  4198.4  1318.2
  4325.7 1316.62  4523.7 1317.15  4707.5 1315.67  4820.7 1311.98  4834.8 1309.88
  4863.1 1310.35  4906.1 1307.62  4919.7 1306.27  4947.9 1300.13  4964.2 1299.31
  4965.2 1298.81  5016.6 1299.31  5024.7 1301.06  5047.3 1302.97    5081 1301.91
  5085.1  1301.7  5135.5 1310.72  5216.1 1315.24  5236.3  1317.4  5256.5  1321.7
  5289.2 1336.38  5372.6 1342.93  5377.8 1343.71  5387.5 1345.07  5407.6 1345.45
#Mann= 9 ,-1 , 0
  3873.1    .035       0  4021.9     .07       0  4039.4    .035       0
  4906.1     .07       0  4964.2     .05       0  5016.6     .07       0
    5081     .12       0  5372.6    .035       0  5377.8     .12       0
Bank Sta=4964.2,5016.6
XS Rating Curve= 0 ,0
Exp/Cntr=0.3,0.1

Type RM Length L Ch R = 1 ,7819    ,538,538,538
BEGIN DESCRIPTION:
JOSHUA CREEK 14.0
END DESCRIPTION:
XS GIS Cut Line= 3
      2037374.98     13888524.98        2038125.       13889325.
      2038524.97     13889424.99
#Sta/Elev= 30
  3899.2  1336.8  3948.4 1334.05  4062.1 1326.82    4069 1327.21  4090.5 1322.79
  4111.5 1320.16  4125.6 1316.68    4154 1314.44  4163.5 1315.42  4196.5 1313.47
  4323.9  1312.6  4591.8 1314.22  4701.4 1315.49  4818.8 1318.74  4854.4 1315.77
  4896.5 1313.96  4917.9 1311.91  4960.4 1304.73  4967.7    1301  4992.8 1299.44
  4993.8 1298.94  5045.2 1299.44  5217.2 1300.53    5220 1300.74  5225.2 1303.63
  5243.2 1305.55  5253.5  1309.2  5261.2 1323.16  5280.3 1326.41  5408.1 1329.67
#Mann= 10 ,-1 , 0
  3899.2     .07       0  3948.4     .12       0  4163.5    .035       0
  4591.8     .07       0  4701.4    .035       0  4896.5     .07       0
  4992.8     .05       0  5045.2     .07       0  5217.2     .12       0
  5280.3     .07       0
Bank Sta=4992.8,5045.2
XS Rating Curve= 0 ,0
Exp/Cntr=0.3,0.1

Type RM Length L Ch R = 1 ,7281    ,549,549,549
BEGIN DESCRIPTION:
JOSHUA CREEK 13.0
END DESCRIPTION:
XS GIS Cut Line= 5
      2036581.47      13888827.6        2037775.       13889575.
      2037968.36     13889603.67      2038141.77     13889594.05
      2038620.54     13889454.76
#Sta/Elev= 30
  3591.8  1371.7    3651 1367.95  3766.5  1364.8  3839.6 1356.82  3985.3  1345.9
  4028.2 1340.41  4115.1 1335.95    4159 1327.39  4186.1 1318.82  4216.8 1313.34
  4289.8 1311.09  4575.6 1309.05  4855.6 1309.48  4909.8 1304.96  4934.6 1298.83
    4945 1293.95    4946 1293.45  4997.4 1293.95    5000 1298.16  5035.3 1299.08
  5151.7 1301.89  5220.6 1306.14  5292.3 1306.71  5352.4 1310.72  5466.3 1311.71
  5491.7 1321.65  5597.5 1323.52  5736.8 1326.94    5835 1332.55  5867.8  1333.4
#Mann= 9 ,-1 , 0
  3591.8     .07       0  4575.6    .035       0  4909.8     .07       0
    4945     .05       0  4997.4     .07       0  5035.3    .035       0
  5220.6     .12       0  5597.5     .07       0    5835    .035       0
Bank Sta=4945,4997.4
XS Rating Curve= 0 ,0
Exp/Cntr=0.3,0.1

Type RM Length L Ch R = 1 ,6732    ,551,551,551
BEGIN DESCRIPTION:
JOSHUA CREEK 12.0
END DESCRIPTION:
XS GIS Cut Line= 3
      2037624.98     13890325.02        2037925.       13890025.
        2038325.     13889525.01
#Sta/Elev= 30
    4572 1335.51  4600.3 1334.78  4645.3 1330.95  4662.3 1327.52  4713.5 1314.26
    4770 1308.61  4798.3 1301.35  4849.2 1300.26    4933 1299.03  5009.9 1298.04
  5012.3  1292.4  5013.4  1291.9  5065.1  1292.4  5081.9 1293.92  5088.3 1293.11
  5102.7  1293.1  5110.8 1295.87  5117.2 1295.72  5124.4 1297.47  5131.6 1301.11
    5138 1300.21    5146 1304.87    5210 1310.02  5316.5 1311.37  5501.3 1308.02
  5536.6 1310.85    5551 1314.34    5559 1320.62  5565.4  1321.7  5636.6 1322.94
#Mann= 8 ,-1 , 0
    4572    .035       0  4645.3     .07       0  4662.3     .12       0
  4849.2     .07       0    4933    .035       0  5012.3    .035       0
  5065.1    .035       0  5088.3     .12       0
Bank Sta=5012.3,5065.1
XS Rating Curve= 0 ,0
Exp/Cntr=0.3,0.1

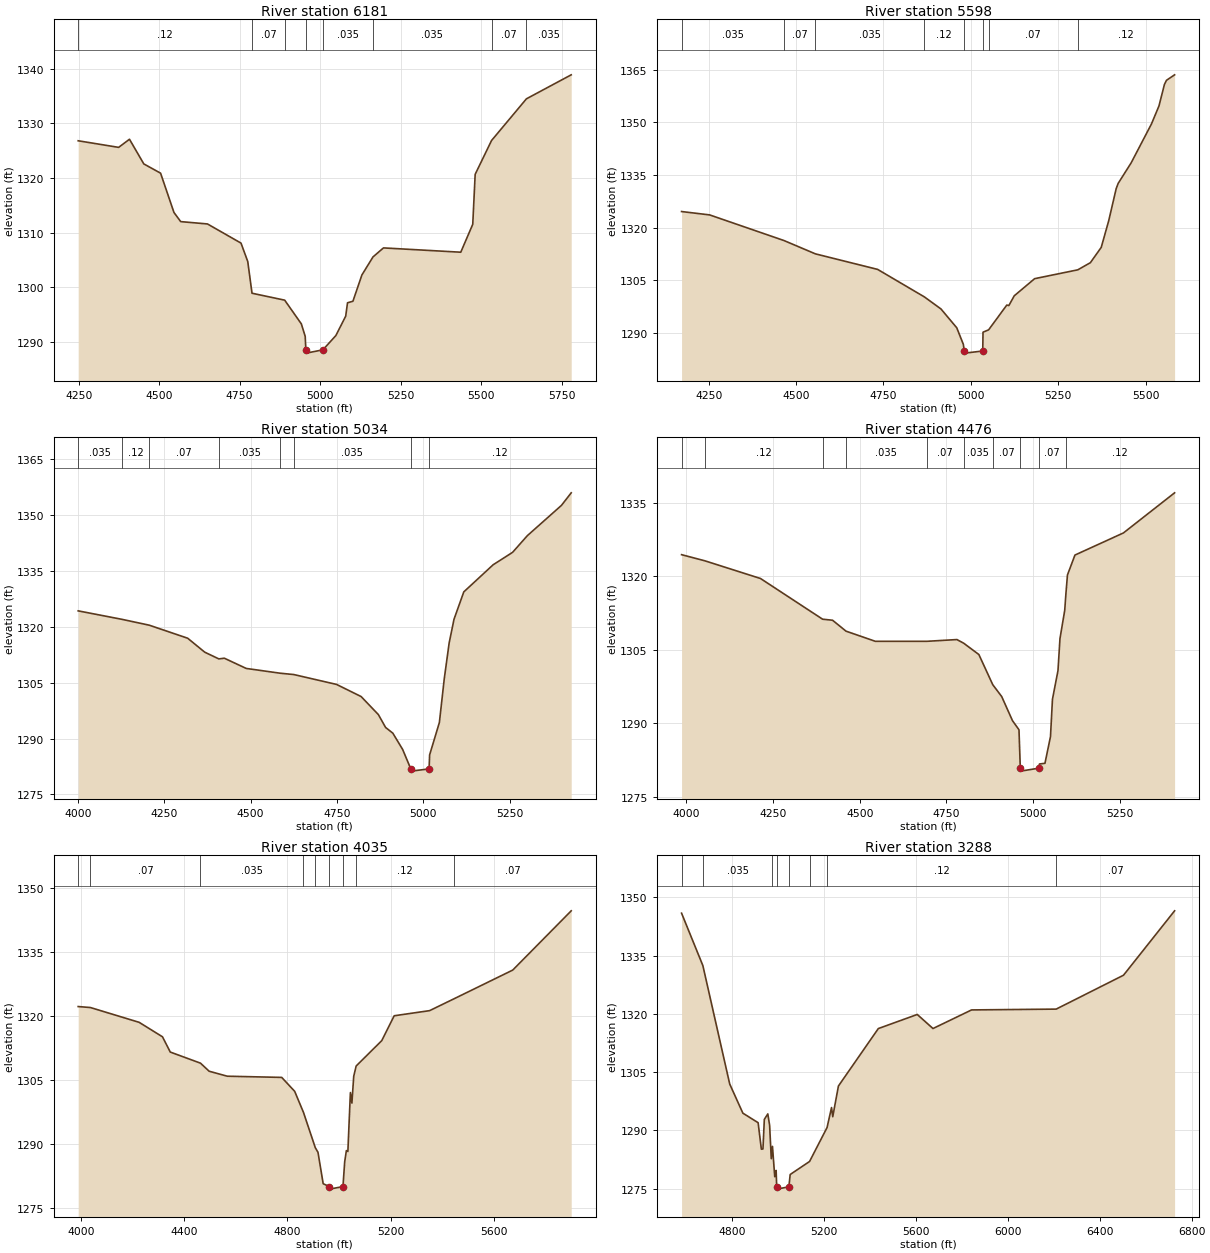
Type RM Length L Ch R = 1 ,6181    ,583,583,583
BEGIN DESCRIPTION:
JOSHUA CREEK 11.0
END DESCRIPTION:
XS GIS Cut Line= 3
      2038215.13     13890800.83        2038425.       13890075.
      2038772.92     13889381.66
#Sta/Elev= 30
  4248.6 1326.83  4374.3 1325.62  4407.9 1327.11  4452.4 1322.59  4504.5 1320.89
  4546.1 1313.68    4567 1312.01  4650.2 1311.58  4754.3 1308.07  4775.3 1304.69
  4788.5 1298.88    4890 1297.61  4941.7 1293.26  4953.7 1290.97  4955.7  1288.5
  4956.7  1287.9  5008.6  1288.5  5048.9 1291.12  5079.5 1294.68  5085.1 1297.13
  5101.9 1297.41  5129.8 1302.23  5164.3 1305.54  5196.8 1307.19  5436.9  1306.4
  5474.1 1311.52  5481.6 1320.68  5532.5 1326.88  5640.8 1334.52  5779.9 1338.92
#Mann= 8 ,-1 , 0
  4248.6     .12       0  4788.5     .07       0    4890    .035       0
  4955.7     .05       0  5008.6    .035       0  5164.3    .035       0
  5532.5     .07       0  5640.8    .035       0
Bank Sta=4955.7,5008.6
XS Rating Curve= 0 ,0
Exp/Cntr=0.3,0.1

Type RM Length L Ch R = 1 ,5598    ,564,564,564
BEGIN DESCRIPTION:
JOSHUA CREEK 10.0
END DESCRIPTION:
XS GIS Cut Line= 3
       2038685.4      13890950.2        2038975.       13890175.
      2039274.99     13889675.02
#Sta/Elev= 30
  4172.5 1324.61  4252.8 1323.65  4465.5 1316.34  4555.5 1312.54  4733.5 1308.11
  4866.9 1300.29  4914.6 1296.84  4959.9 1291.46  4978.7 1286.74  4981.3 1284.84
  4982.4 1284.24  5034.2 1284.84    5035 1290.21    5051 1290.88    5103 1297.94
  5108.9 1297.81  5124.4 1300.59  5182.7 1305.47  5306.1 1307.99  5342.1 1310.02
  5373.2 1314.39  5394.6 1321.98    5416 1331.15  5421.8 1332.66  5458.7 1338.47
    5517  1349.6  5538.4 1354.72    5554 1360.84  5559.8 1362.02  5583.1 1363.59
#Mann= 8 ,-1 , 0
  4172.5    .035       0  4465.5     .07       0  4555.5    .035       0
  4866.9     .12       0  4981.3     .05       0  5034.2     .12       0
    5051     .07       0  5306.1     .12       0
Bank Sta=4981.3,5034.2
XS Rating Curve= 0 ,0
Exp/Cntr=0.3,0.1

Type RM Length L Ch R = 1 ,5034    ,558,558,558
BEGIN DESCRIPTION:
JOSHUA CREEK 9.0
END DESCRIPTION:
XS GIS Cut Line= 3
      2038854.64     13890971.97        2039525.       13890225.
      2039824.98     13889925.02
#Sta/Elev= 30
  4000.5 1324.26  4127.1 1321.99  4206.2 1320.42  4317.6 1316.92  4366.9 1313.18
  4407.9 1311.37  4423.7 1311.56  4487.2 1308.81  4585.7 1307.53  4625.1 1307.17
  4748.9 1304.52  4819.9 1301.27  4869.8 1296.44  4890.9 1292.97  4911.8 1291.44
  4940.2 1287.08  4963.8 1281.86  4964.9 1281.26  5016.8 1281.86  5018.3 1285.61
  5046.6 1294.31  5060.7 1306.02  5074.9 1315.65    5089 1322.02  5117.3 1329.35
  5202.2 1336.62  5258.7 1339.97  5301.2 1344.42  5400.1 1352.56  5428.4 1355.93
#Mann= 8 ,-1 , 0
  4000.5    .035       0  4127.1     .12       0  4206.2     .07       0
  4407.9    .035       0  4585.7     .07       0  4625.1    .035       0
  4963.8     .05       0  5016.8     .12       0
Bank Sta=4963.8,5016.8
XS Rating Curve= 0 ,0
Exp/Cntr=0.3,0.1

Type RM Length L Ch R = 1 ,4476    ,441,441,441
BEGIN DESCRIPTION:
JOSHUA CREEK 8.0
END DESCRIPTION:
XS GIS Cut Line= 3
      2038872.01     13891032.71        2039825.       13890675.
      2040024.99     13890325.02
#Sta/Elev= 30
  3986.6 1324.46    4054  1323.2  4214.1 1319.59  4393.1 1311.27  4421.8 1311.06
  4460.5 1308.83  4545.2 1306.75  4693.1 1306.75  4780.2 1307.11  4799.6 1306.37
  4843.5 1304.05  4883.5 1297.89  4909.3 1295.46  4940.4 1290.53  4959.1 1288.67
  4962.9 1280.82    4964 1280.22  5015.9 1280.82  5018.2 1281.68    5034 1281.82
  5049.9 1287.28  5055.6 1294.91  5071.5 1300.77  5077.2 1307.29  5090.9 1313.07
  5094.3  1316.4  5098.8 1320.31  5120.4 1324.38  5260.1  1328.9  5407.6  1337.1
#Mann= 10 ,-1 , 0
  3986.6    .035       0    4054     .12       0  4393.1     .07       0
  4460.5    .035       0  4693.1     .07       0  4799.6    .035       0
  4883.5     .07       0  4962.9     .05       0  5015.9     .07       0
  5094.3     .12       0
Bank Sta=4962.9,5015.9
XS Rating Curve= 0 ,0
Exp/Cntr=0.3,0.1

Type RM Length L Ch R = 1 ,4035    ,747,747,747
BEGIN DESCRIPTION:
JOSHUA CREEK 7.0
END DESCRIPTION:
XS GIS Cut Line= 4
      2038919.72     13891180.28      2039925.82     13891085.07
      2040039.92     13891017.05      2040225.33     13890272.42
#Sta/Elev= 30
  3989.4 1322.13  4036.8  1321.9  4225.7 1318.43  4316.1 1315.04  4346.3 1311.46
  4463.4 1308.86  4496.9 1306.97  4567.3  1305.8  4778.2 1305.52  4828.4 1302.26
  4862.4 1297.34  4908.4 1289.04  4918.8 1287.96  4938.9  1280.6  4962.6 1279.93
  4963.7 1279.33  5015.6 1279.93  5022.3 1285.74  5028.8 1288.37  5034.6 1288.16
  5044.4 1301.97  5050.2  1299.5  5057.3 1305.79  5066.7 1308.19  5165.9 1314.14
  5214.1 1319.97  5351.4 1321.17  5445.7 1323.94  5673.6 1330.68  5900.2 1344.57
#Mann= 9 ,-1 , 0
  3989.4    .035       0  4036.8     .07       0  4463.4    .035       0
  4862.4     .12       0  4908.4     .07       0  4962.6     .05       0
  5015.6     .07       0  5066.7     .12       0  5445.7     .07       0
Bank Sta=4962.6,5015.6
XS Rating Curve= 0 ,0
Exp/Cntr=0.3,0.1

Type RM Length L Ch R = 1 ,3288    ,483,483,483
BEGIN DESCRIPTION:
JOSHUA CREEK 6.0
END DESCRIPTION:
XS GIS Cut Line= 4
      2039224.98     13891925.01      2039574.96     13891694.98
      2039985.55     13891536.91      2040281.63     13890285.63
#Sta/Elev= 30
  4581.2 1345.89  4673.8 1332.41  4790.6 1301.92  4847.8 1294.42  4914.2 1291.96
  4928.3 1285.14  4935.2 1285.19  4941.2 1292.81  4956.3 1294.22  4964.2 1291.31
  4971.4 1282.69  4976.6 1285.87  4986.5 1278.05  4992.5 1279.67    4995 1275.46
    4996 1274.86    5048 1275.46  5053.6 1278.62    5138 1281.98  5214.1 1290.72
  5233.5 1295.86  5238.8  1293.5  5263.5  1301.4    5437 1316.19  5606.4 1319.82
  5674.8  1316.2  5842.7 1320.99  6210.7  1321.2  6503.5 1329.92  6725.8  1346.5
#Mann= 8 ,-1 , 0
  4581.2     .07       0  4673.8    .035       0  4976.6     .12       0
    4995     .05       0    5048     .12       0    5138     .07       0
  5214.1     .12       0  6210.7     .07       0
Bank Sta=4995,5048
XS Rating Curve= 0 ,0
Exp/Cntr=0.3,0.1

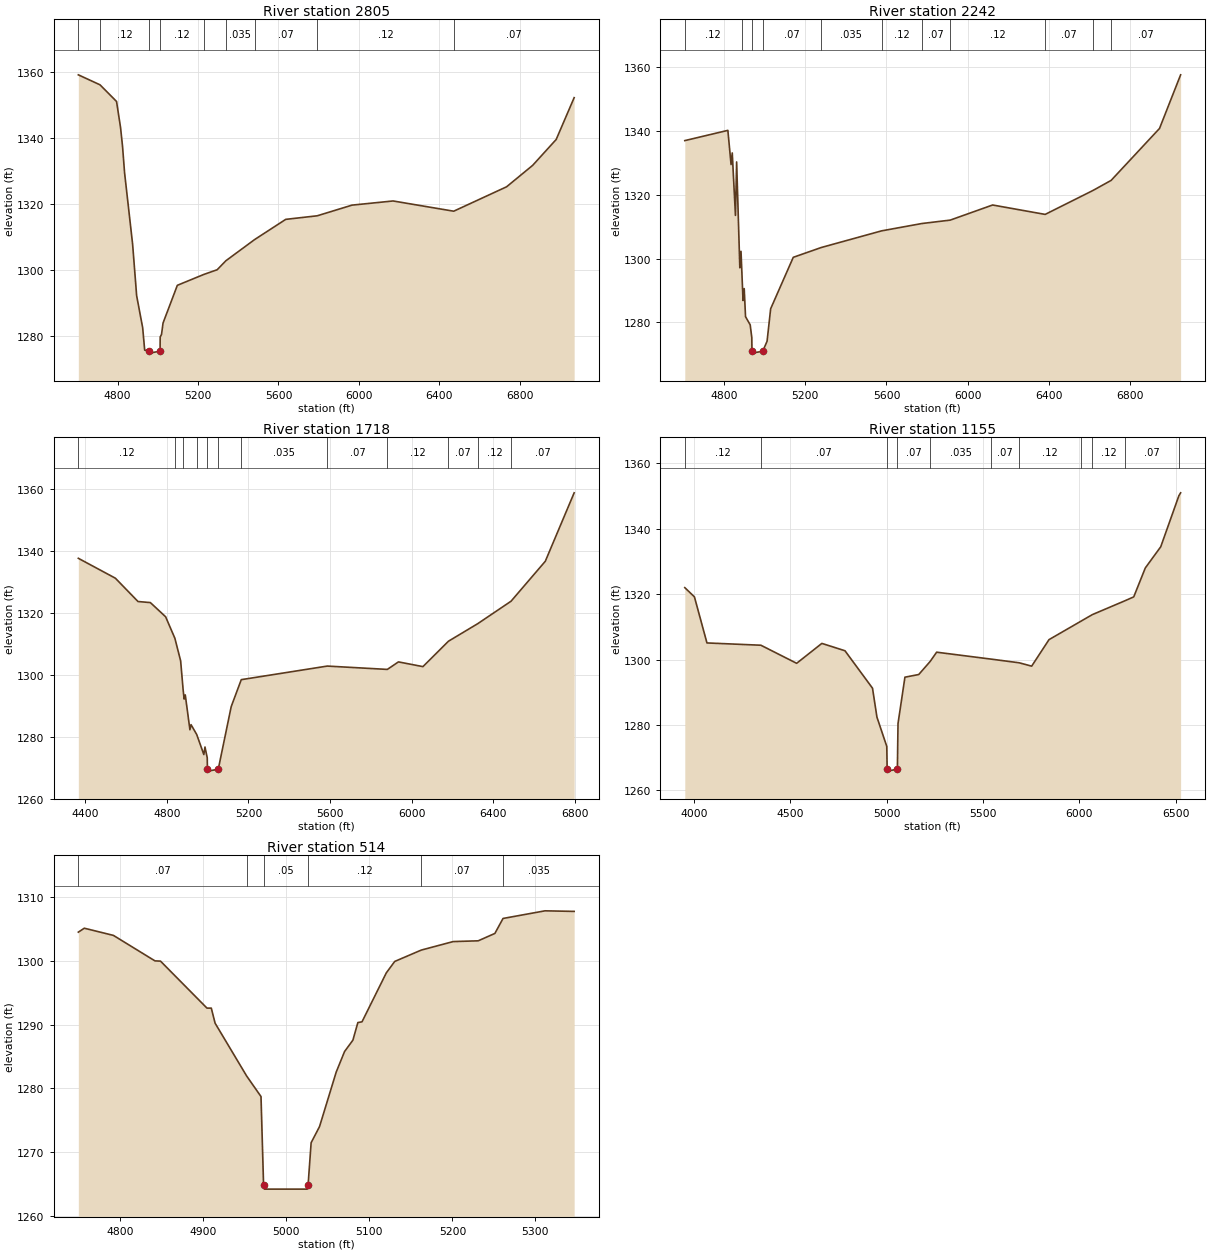
Type RM Length L Ch R = 1 ,2805    ,563,563,563
BEGIN DESCRIPTION:
JOSHUA CREEK 5.0
END DESCRIPTION:
XS GIS Cut Line= 4
      2039225.02       13892125.        2039625.       13892125.
       2040032.2     13891762.51      2040338.02     13890272.93
#Sta/Elev= 30
  4604.8 1359.02  4712.5    1356  4794.8 1350.95  4814.8 1343.05  4824.8 1337.26
  4834.8 1329.34  4874.8  1307.7  4894.8 1292.12  4924.8 1282.41  4934.8 1275.63
  4958.3 1275.32  4959.3 1274.72  5011.3 1275.32  5011.9  1279.6  5018.6 1280.41
  5026.1 1283.84  5097.2 1295.26  5228.3 1298.54  5295.3 1299.98  5338.6  1302.7
  5481.6 1309.12  5636.3 1315.24    5793 1316.32    5966 1319.55  6170.1 1320.81
  6471.6 1317.71  6734.5  1325.1  6864.3  1331.6  6981.3 1339.44  7070.6  1352.1
#Mann= 9 ,-1 , 0
  4604.8     .07       0  4712.5     .12       0  4958.3     .05       0
  5011.3     .12       0  5228.3     .07       0  5338.6    .035       0
  5481.6     .07       0    5793     .12       0  6471.6     .07       0
Bank Sta=4958.3,5011.3
XS Rating Curve= 0 ,0
Exp/Cntr=0.3,0.1

Type RM Length L Ch R = 1 ,2242    ,524,524,524
BEGIN DESCRIPTION:
JOSHUA CREEK 4.0
END DESCRIPTION:
XS GIS Cut Line= 3
      2039874.99     13892625.02        2040075.       13892275.
      2040407.42     13890260.27
#Sta/Elev= 30
  4605.4 1336.96  4817.8 1340.17  4833.6 1329.46  4839.4  1333.1  4855.2 1313.52
    4861 1330.27  4876.8  1297.1  4882.6 1302.26  4886.1 1296.86  4892.6 1286.84
  4898.4 1290.58  4904.9 1281.78  4927.9 1279.21  4935.8  1275.2  4936.6 1270.95
  4937.7 1270.35  4989.7 1270.95  5011.1 1274.06  5028.8 1284.25  5140.3 1300.38
  5278.1 1303.45  5575.7 1308.67  5774.1 1310.97  5914.2 1312.04  6123.4 1316.78
  6382.5 1313.83  6618.7 1321.35  6707.8 1324.49  6946.4 1340.77  7050.5 1357.58
#Mann= 11 ,-1 , 0
  4605.4     .12       0  4886.1     .07       0  4936.6     .05       0
  4989.7     .07       0  5278.1    .035       0  5575.7     .12       0
  5774.1     .07       0  5914.2     .12       0  6382.5     .07       0
  6618.7     .12       0  6707.8     .07       0
Bank Sta=4936.6,4989.7
XS Rating Curve= 0 ,0
Exp/Cntr=0.3,0.1

Type RM Length L Ch R = 1 ,1718    ,563,563,563
BEGIN DESCRIPTION:
JOSHUA CREEK 3.0
END DESCRIPTION:
XS GIS Cut Line= 4
      2040111.17     13892504.03      2040389.22     13892362.26
        2040525.       13892075.      2040468.05     13890273.54
#Sta/Elev= 30
  4365.5 1337.68  4547.1 1331.25  4658.3  1323.7  4718.8 1323.36  4793.6 1318.78
  4839.1 1311.82  4867.4  1304.5  4879.6 1295.16  4884.6 1292.15  4890.1  1293.5
  4912.9 1282.24  4918.4 1283.89  4946.3 1280.69  4981.2 1274.21  4986.7 1276.66
  4997.8 1273.19  4998.8 1269.46  4999.9 1268.86  5051.9 1269.46  5115.4 1289.72
  5164.8 1298.44  5586.9 1302.83  5881.3 1301.75  5935.8 1304.18  6055.9 1302.65
    6181 1310.86    6325 1316.55  6488.1  1323.8  6656.2 1336.72  6797.7 1358.85
#Mann= 12 ,-1 , 0
  4365.5     .12       0  4839.1     .07       0  4879.6     .12       0
  4946.3     .07       0  4998.8     .05       0  5051.9     .07       0
  5164.8    .035       0  5586.9     .07       0  5881.3     .12       0
    6181     .07       0    6325     .12       0  6488.1     .07       0
Bank Sta=4998.8,5051.9
XS Rating Curve= 0 ,0
Exp/Cntr=0.3,0.1

Type RM Length L Ch R = 1 ,1155    ,641,641,641
BEGIN DESCRIPTION:
JOSHUA CREEK 2.0
END DESCRIPTION:
XS GIS Cut Line= 6
       2040448.2     13892458.21      2040947.41     13892101.59
       2040979.4     13891928.36        2040925.       13891675.
      2040558.25     13891324.86      2040571.85     13890321.67
#Sta/Elev= 30
  3951.2 1321.99  4001.2 1319.17  4066.3 1305.07  4346.3 1304.37    4532 1298.84
  4662.9 1304.93  4782.9 1302.68  4925.9 1291.22  4948.9 1282.37    5000 1273.41
  5001.9 1266.45    5003 1265.85    5055 1266.45  5058.3  1280.4  5094.2 1294.59
    5166 1295.41  5225.4 1299.42  5258.8 1302.24  5543.2 1300.11  5687.2    1299
  5752.3 1297.97  5842.3 1306.08  6007.2 1311.69  6067.5 1313.74  6239.2 1318.04
  6282.3 1319.17  6342.3 1328.01  6422.4 1334.49  6516.6  1350.1  6525.7    1351
#Mann= 11 ,-1 , 0
  3951.2     .12       0  4346.3     .07       0  5001.9     .05       0
    5055     .07       0  5225.4    .035       0  5543.2     .07       0
  5687.2     .12       0  6007.2     .07       0  6067.5     .12       0
  6239.2     .07       0  6516.6     .12       0
Bank Sta=5001.9,5055
XS Rating Curve= 0 ,0
Exp/Cntr=0.3,0.1

Type RM Length L Ch R = 1 ,514     ,0,0,0
BEGIN DESCRIPTION:
JOSHUA CREEK 1.0
END DESCRIPTION:
XS GIS Cut Line= 4
      2041363.67     13891733.67      2041468.89     13891619.05
      2041480.16     13891524.62      2041519.38     13891180.14
#Sta/Elev= 30
  4749.3 1304.55  4756.5 1305.17  4791.6 1304.04  4841.6 1300.04  4848.3    1300
  4904.3 1292.62  4909.5 1292.62  4914.1 1290.25    4952 1281.98  4969.4 1278.73
  4972.5 1264.79  4973.6 1264.19    5025 1264.19  5026.1 1264.79  5029.8 1271.48
  5039.9 1274.01    5060 1282.57  5070.1 1285.81  5080.1 1287.58  5086.1 1290.35
  5091.1 1290.47  5120.4 1298.16  5130.5 1299.95  5162.4 1301.73  5200.9 1303.07
  5231.1 1303.19  5251.2 1304.35    5261  1306.7  5311.6  1307.9  5346.7 1307.81
#Mann= 6 ,-1 , 0
  4749.3     .07       0    4952     .12       0  4972.5     .05       0
  5026.1     .12       0  5162.4     .07       0    5261    .035       0
Bank Sta=4972.5,5026.1
XS Rating Curve= 0 ,0
Exp/Cntr=0.3,0.1

Chan Stop Cuts=-1
Use User Specified Reach Order=0
Composite Channel Slope=5