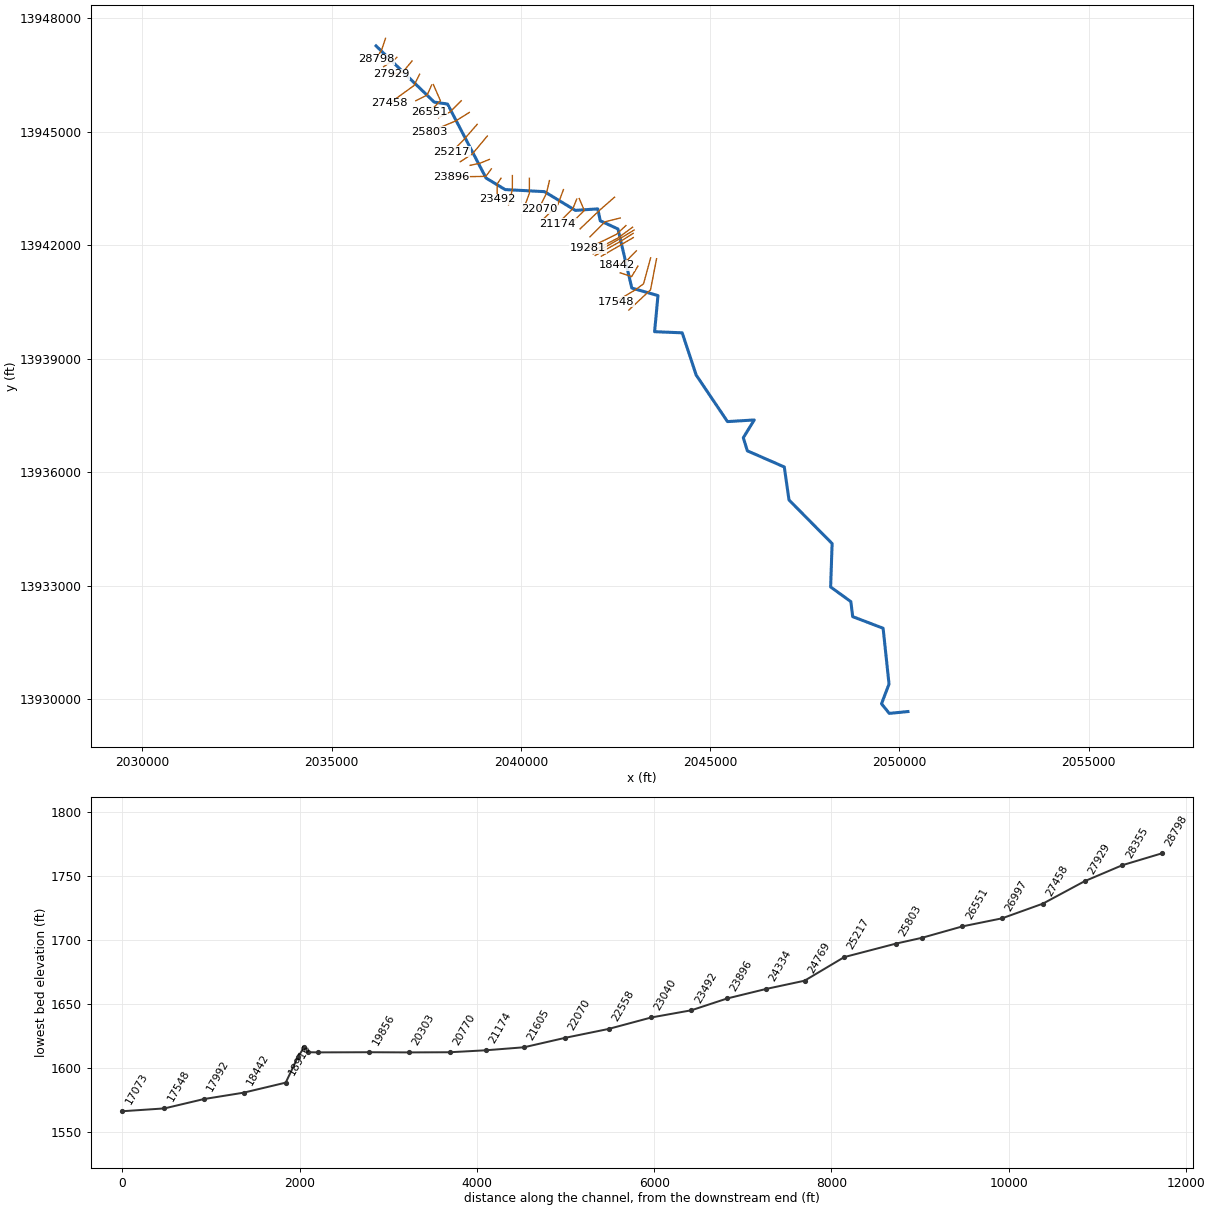
--- JUNG CREEK.prj (project) ---

Proj Title=JUNG CREEK Base Level Engineering
Current Plan=p01
Default Exp/Contr=0.3,0.1
English Units
Geom File=g01
Flow File=f01
Plan File=p01
Y Axis Title=Elevation
X Axis Title(PF)=Main Channel Distance
X Axis Title(XS)=Station
BEGIN DESCRIPTION:
JUNG CREEK
END DESCRIPTION:
DSS Export Rating Curves= 0
DSS Export Rating Curve Sorted= 0
DSS Export Volume Flow Curves= 0
DXF OffsetX= 0
DXF OffsetY= 0
DXF ScaleX= 1
DXF ScaleY= 10

--- JUNG CREEK.p01 (plan) ---

Plan Title=Multiple Run
Short Identifier=Multiple
Geom File=g01
Flow File=f01
Subcritical Flow
K Sum by GR= 0
Std Step Tol= 0.01
Critical Tol= 0.01
Num of Std Step Trials= 20
Max Error Tol= 0.3
Flow Tol Ratio= 0.001
Split Flow NTrial= 30
Split Flow Tol= 0.02
Split Flow Ratio= 0.02
Log Output Level= 0
Friction Slope Method= 1
Unsteady Friction Slope Method= 2
Unsteady Bridges Friction Slope Method= 1
Parabolic Critical Depth
Global Vel Dist=  1 , 1 , 1
Global Log Level= 0
CheckData=True
Encroach Param= -1, 0, 0, 0
BEGIN DESCRIPTION:
Multiple Run
END DESCRIPTION:

--- JUNG CREEK.f01 (steady flow) ---

Flow Title=Multiple
Number of Profiles=7
Profile Names=10-year,25-year,50-year,1pct_min,100-year,1pct_plu,500-year
River Rch & RM= JUNG CREEK,Reach-1,28798
     381     620     841     556    1109    2214    1909
River Rch & RM= JUNG CREEK,Reach-1,28355
     609    1021    1411     949    1894    3779    3379
River Rch & RM= JUNG CREEK,Reach-1,26094
    1196    2089    2965    2043    4076    8133    7641
River Rch & RM= JUNG CREEK,Reach-1,23492
    1251    2181    3091    2125    4241    8461    7916
River Rch & RM= JUNG CREEK,Reach-1,20303
    2063    3693    5326    3720    7422   14808   14309
River Rch & RM= JUNG CREEK,Reach-1,17548
    2522    4553    6604    4635    9248   18453   18012
River Rch & RM= JUNG CREEK,Reach-1,16010
    2803    5037    7283    5091   10158   20269   19623
River Rch & RM= JUNG CREEK,Reach-1,8786
    3063    5524    8006    5608   11189   22325   21701
River Rch & RM= JUNG CREEK,Reach-1,5574
    3161    5705    8272    5797   11566   23078   22452
River Rch & RM= JUNG CREEK,Reach-1,4228
    3253    5868    8505    5956   11884   23711   23036
Boundary for River Rch & Prof#=JUNG CREEK,Reach-1,1
Up Type=0
Dn Type=3
Dn Slope=0.005
Boundary for River Rch & Prof#=JUNG CREEK,Reach-1,2
Up Type=0
Dn Type=3
Dn Slope=0.005
Boundary for River Rch & Prof#=JUNG CREEK,Reach-1,3
Up Type=0
Dn Type=3
Dn Slope=0.005
Boundary for River Rch & Prof#=JUNG CREEK,Reach-1,4
Up Type=0
Dn Type=3
Dn Slope=0.005
Boundary for River Rch & Prof#=JUNG CREEK,Reach-1,5
Up Type=0
Dn Type=3
Dn Slope=0.005
Boundary for River Rch & Prof#=JUNG CREEK,Reach-1,6
Up Type=0
Dn Type=3
Dn Slope=0.005
Boundary for River Rch & Prof#=JUNG CREEK,Reach-1,7
Up Type=0
Dn Type=3
Dn Slope=0.005

--- JUNG CREEK.g01 (geometry) ---

Geom Title=Existing Conditions
Program Version=4.10

River Reach=JUNG CREEK      ,Reach-1
Reach XY= 30
        2036175.       13947275.      2037711.62     13945788.53
      2038061.72     13945738.36      2039080.58     13943780.58
      2039584.65     13943476.36      2040623.72     13943421.63
      2041440.02     13942925.66      2042031.77     13942966.56
      2042097.51     13942651.05      2042564.81     13942434.68
      2042930.73     13940872.45      2043621.46     13940673.54
      2043532.81     13939718.77      2044261.84     13939688.73
      2044630.83      13938572.7      2045458.29     13937341.63
      2046164.58     13937384.81      2045876.02     13936915.54
      2045983.01     13936568.62      2046958.52     13936142.05
      2047083.14     13935268.94      2048221.77     13934116.99
      2048183.02     13932968.66      2048717.24     13932581.21
      2048764.81     13932185.32      2049569.18     13931877.31
      2049725.28     13930402.15      2049526.94     13929880.71
       2049730.7     13929626.92        2050225.       13929675.

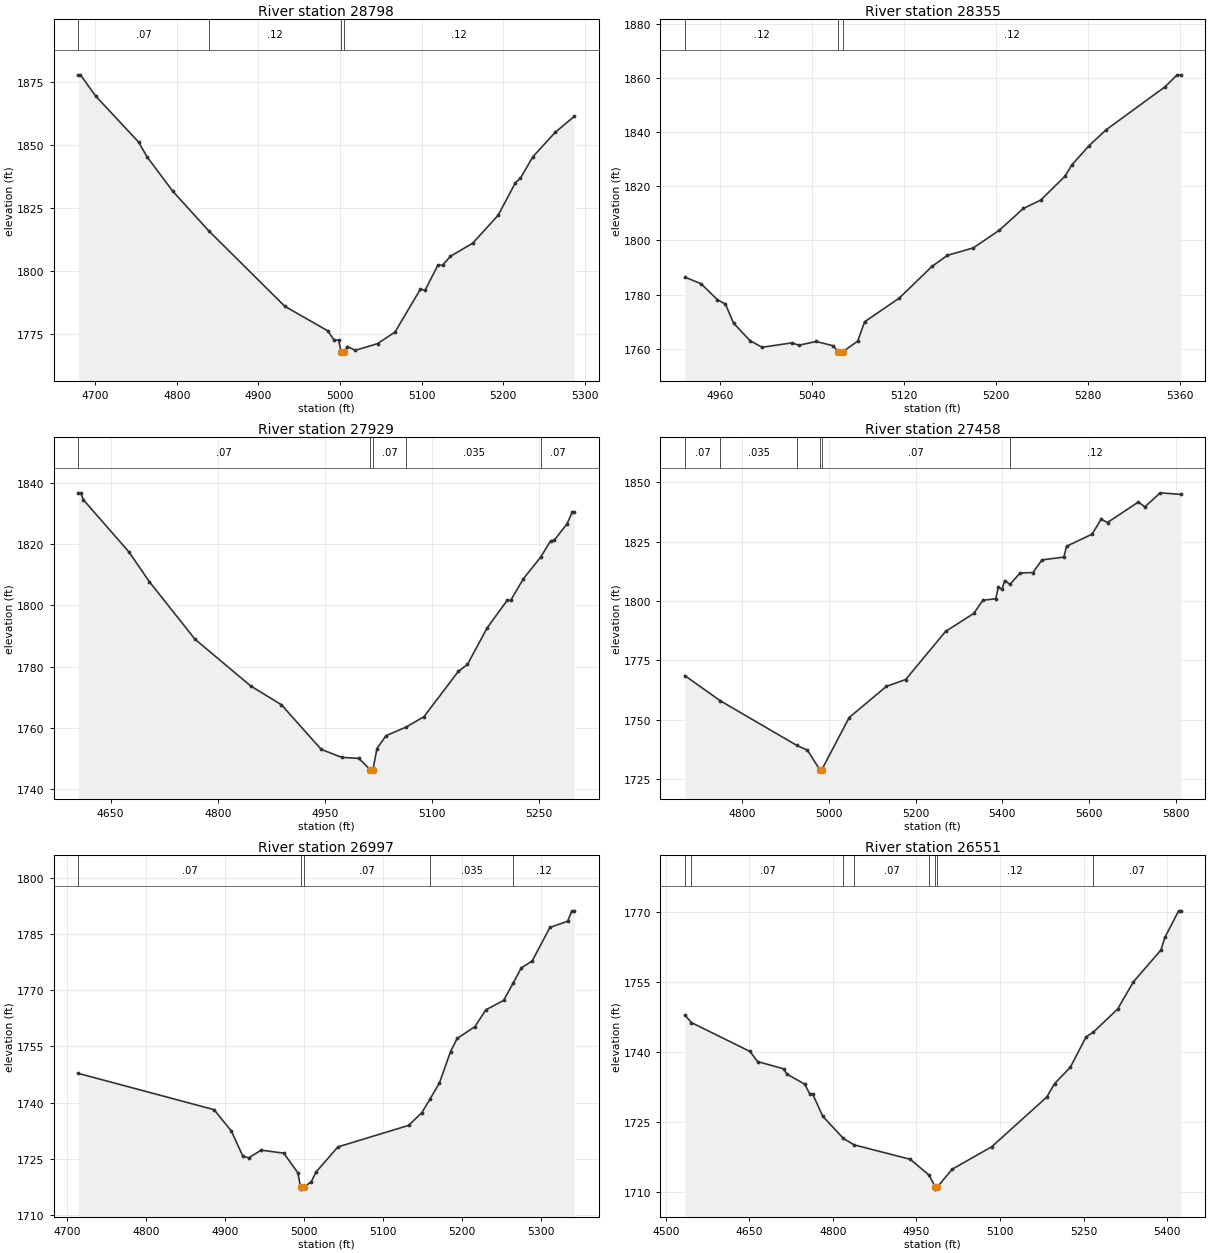
Type RM Length L Ch R = 1 ,28798   ,443,443,443
BEGIN DESCRIPTION:
JUNG CREEK 60.0
END DESCRIPTION:
XS GIS Cut Line= 3
      2036424.99     13947474.97        2036325.       13947175.
      2036175.03     13946925.04
#Sta/Elev= 30
  4679.4 1877.73    4682 1877.73  4700.5 1869.39  4753.2 1851.15  4763.7 1845.24
  4795.3 1831.61  4839.1 1816.04  4932.4 1786.14  4985.1 1776.41    4993 1772.72
  4998.5 1772.72  5001.4 1768.08  5001.6 1767.58  5005.4 1768.08  5009.2  1770.2
  5018.9 1768.69  5046.1 1771.34  5067.5 1775.92  5098.6 1792.87  5104.4  1792.5
    5120 1802.33  5125.8  1802.4  5135.5 1805.93  5162.8 1811.09  5193.9 1822.15
  5215.2 1835.06  5221.1 1836.74  5236.6 1845.35  5263.8 1854.94  5287.1 1861.24
#Mann= 4 ,-1 , 0
  4679.4     .07       0  4839.1     .12       0  5001.4     .05       0
  5005.4     .12       0
Bank Sta=5001.4,5005.4
XS Rating Curve= 0 ,0
Exp/Cntr=0.3,0.1

Type RM Length L Ch R = 1 ,28355   ,426,426,426
BEGIN DESCRIPTION:
JUNG CREEK 59.0
END DESCRIPTION:
XS GIS Cut Line= 3
      2036725.02     13946975.02        2036675.       13946925.
      2036374.99     13946724.99
#Sta/Elev= 30
  4929.3 1786.45  4943.5 1783.99  4957.6 1778.14  4964.7 1776.45  4971.7 1769.48
  4985.9 1763.05  4996.5 1760.56  5022.6 1762.18  5028.6 1761.31  5043.6  1762.7
  5058.6 1761.07  5062.6 1758.89  5062.9 1758.39  5066.6 1758.89  5079.7 1762.81
  5085.7 1769.96  5115.7 1778.64  5144.3 1790.39  5157.8 1794.49  5180.3 1797.25
  5202.8 1803.73  5223.9 1811.82  5238.9 1814.88  5259.9 1823.64  5265.9 1827.81
    5281    1835    5296  1840.9  5347.1 1856.72  5357.6 1861.12  5360.6 1861.12
#Mann= 3 ,-1 , 0
  4929.3     .12       0  5062.6     .05       0  5066.6     .12       0
Bank Sta=5062.6,5066.6
XS Rating Curve= 0 ,0
Exp/Cntr=0.3,0.1

Type RM Length L Ch R = 1 ,27929   ,471,471,471
BEGIN DESCRIPTION:
JUNG CREEK 58.0
END DESCRIPTION:
XS GIS Cut Line= 3
      2037125.02     13946875.02        2036875.       13946575.
      2036574.98       13946525.
#Sta/Elev= 30
  4604.7 1836.81    4608 1836.81  4611.9  1834.5  4675.7 1817.47  4704.3 1807.75
  4768.1 1788.99  4846.2 1773.71  4889.2 1767.57  4945.1 1752.97  4973.8 1750.38
  4997.8 1750.03  5013.5 1746.38  5013.8 1745.88  5017.5 1746.38  5023.1 1753.27
  5035.8 1757.46  5064.3 1760.32    5089 1763.68  5137.2 1778.49  5149.8 1780.72
  5177.7 1792.75  5205.6  1801.7  5210.7 1801.77  5228.4 1808.79  5252.3 1815.74
  5266.4 1821.12  5271.5 1821.33  5289.2  1826.6  5296.8 1830.51  5299.4 1830.51
#Mann= 5 ,-1 , 0
  4604.7     .07       0  5013.5     .05       0  5017.5     .07       0
  5064.3    .035       0  5252.3     .07       0
Bank Sta=5013.5,5017.5
XS Rating Curve= 0 ,0
Exp/Cntr=0.3,0.1

Type RM Length L Ch R = 1 ,27458   ,461,461,461
BEGIN DESCRIPTION:
JUNG CREEK 57.0
END DESCRIPTION:
XS GIS Cut Line= 3
        2037325.       13946525.        2037175.       13946225.
      2036522.26     13945752.35
#Sta/Elev= 30
  4668.9 1768.58  4750.3    1758  4926.8 1739.18  4951.2 1737.18  4979.9 1728.86
  4980.2 1728.36  4983.9 1728.86  5047.2  1750.9  5133.1 1764.06  5177.2  1766.9
  5269.2 1787.18  5334.1 1794.73    5355 1800.28  5384.4  1800.9  5390.6 1805.69
  5399.1 1804.96  5405.3 1808.56  5417.5    1807  5440.8 1811.76  5470.2 1811.94
  5491.1 1817.25  5541.4 1818.45  5547.6    1823  5606.4  1828.1  5627.2 1834.36
  5641.9    1833  5713.1 1841.63  5727.8 1839.58  5763.3 1845.49  5810.2 1844.83
#Mann= 6 ,-1 , 0
  4668.9     .07       0  4750.3    .035       0  4926.8     .07       0
  4979.9     .05       0  4983.9     .07       0  5417.5     .12       0
Bank Sta=4979.9,4983.9
XS Rating Curve= 0 ,0
Exp/Cntr=0.3,0.1

Type RM Length L Ch R = 1 ,26997   ,446,446,446
BEGIN DESCRIPTION:
JUNG CREEK 56.0
END DESCRIPTION:
XS GIS Cut Line= 3
      2037643.83     13946241.98        2037525.       13945975.
      2037225.04     13945825.02
#Sta/Elev= 30
  4714.2 1747.77    4886 1738.09  4907.9 1732.39  4922.3 1725.75  4929.8 1725.22
  4945.6  1727.3  4974.3 1726.48  4992.1 1721.24  4995.5 1717.39  4995.8 1716.89
  4999.5 1717.39  5009.2 1718.89  5014.8 1721.38  5042.8 1728.16  5132.2 1733.89
    5149 1737.29    5159 1740.81  5171.3 1745.23  5185.3 1753.58  5193.7 1757.08
  5216.1 1760.22    5230 1764.72  5252.4 1767.22  5264.7 1771.89  5274.8 1775.89
  5288.7 1777.78  5311.1  1786.7  5333.5 1788.36    5339 1791.14  5341.8 1791.14
#Mann= 5 ,-1 , 0
  4714.2     .07       0  4995.5     .05       0  4999.5     .07       0
    5159    .035       0  5264.7     .12       0
Bank Sta=4995.5,4999.5
XS Rating Curve= 0 ,0
Exp/Cntr=0.3,0.1

Type RM Length L Ch R = 1 ,26551   ,457,457,457
BEGIN DESCRIPTION:
JUNG CREEK 55.0
END DESCRIPTION:
XS GIS Cut Line= 3
      2037688.95     13946252.36        2037875.       13945825.
      2037574.98     13945524.98
#Sta/Elev= 30
    4534 1747.95  4545.8 1746.31  4651.1 1740.12  4664.7 1737.95  4711.5 1736.39
    4717 1735.28  4749.3 1733.12  4758.4 1731.03  4763.9 1730.93  4781.8 1726.22
  4818.6  1721.5    4838  1720.1  4938.8 1717.01  4972.4 1713.64  4983.7 1711.11
  4983.9 1710.61  4987.7 1711.11  5014.2 1714.88    5085 1719.68    5184 1730.34
  5198.1 1733.23  5226.4 1736.74  5254.7 1743.25  5267.4 1744.23  5311.2 1749.19
  5339.5 1755.03    5389 1761.86  5396.1 1764.55  5420.8 1770.26  5424.4 1770.26
#Mann= 8 ,-1 , 0
    4534     .12       0  4545.8     .07       0  4818.6     .12       0
    4838     .07       0  4972.4     .12       0  4983.7     .05       0
  4987.7     .12       0  5267.4     .07       0
Bank Sta=4983.7,4987.7
XS Rating Curve= 0 ,0
Exp/Cntr=0.3,0.1

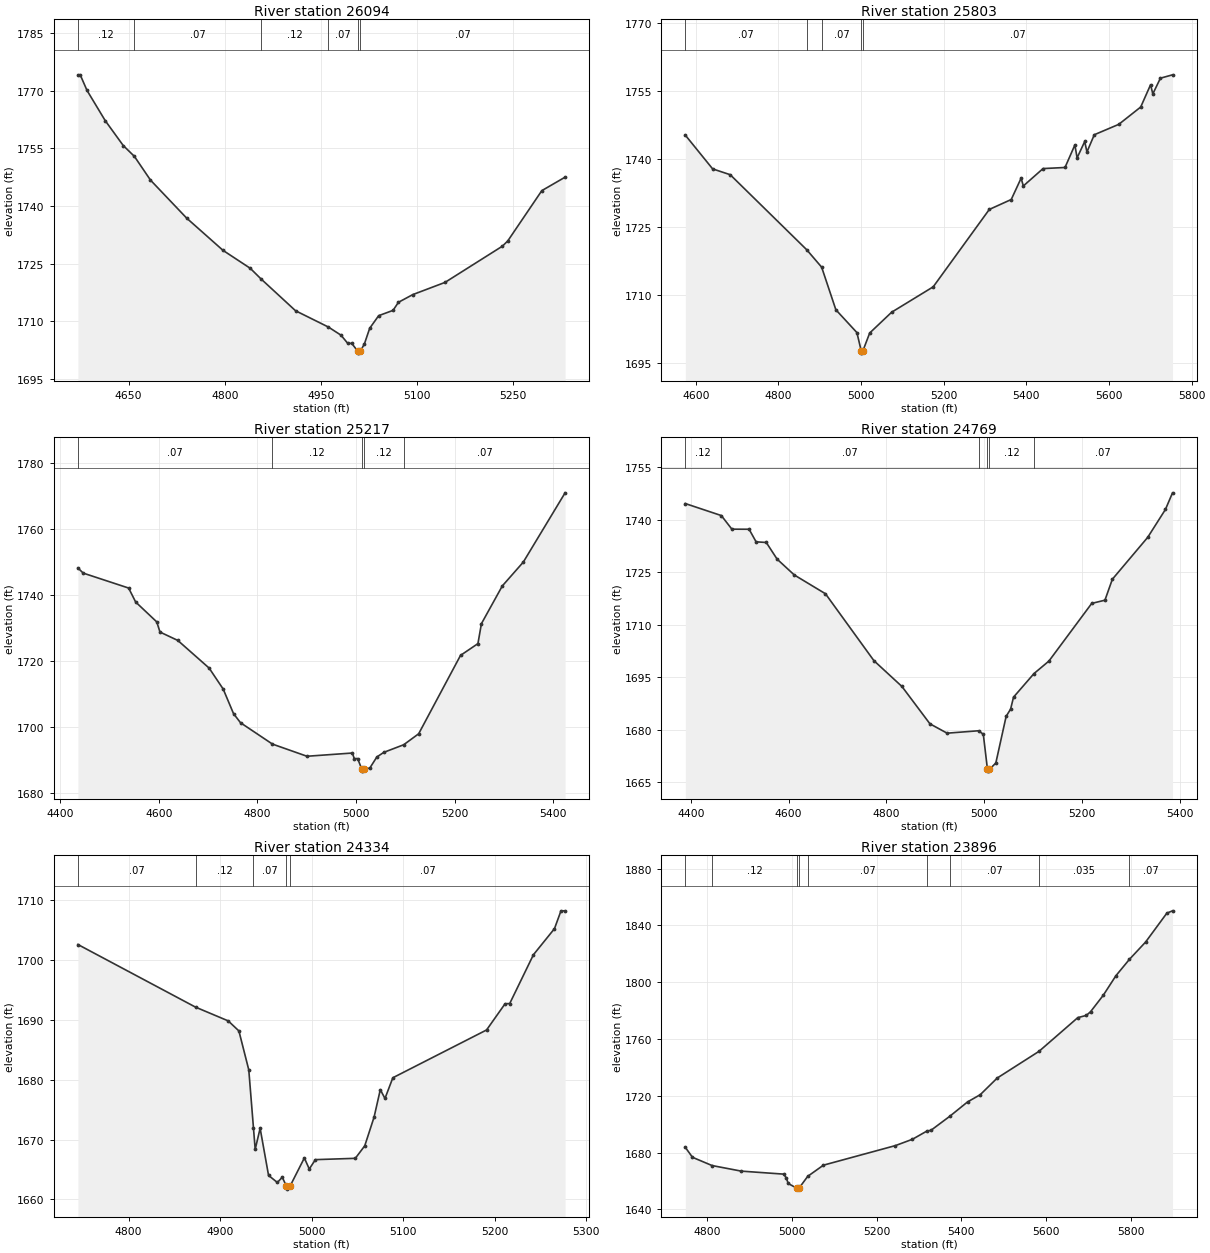
Type RM Length L Ch R = 1 ,26094   ,291,291,291
BEGIN DESCRIPTION:
JUNG CREEK 54.0
END DESCRIPTION:
XS GIS Cut Line= 3
      2038425.03     13945825.03        2038125.       13945525.
      2037825.01       13945375.
#Sta/Elev= 30
  4571.1 1774.14  4574.7 1774.14  4585.3 1770.08  4613.6 1762.24  4641.8 1755.73
  4659.2 1752.91  4684.3 1746.73  4740.8 1736.82  4797.4 1728.44  4839.8 1723.78
  4856.5 1721.03  4910.5 1712.72  4961.7 1708.48  4981.3 1706.37  4991.9 1704.23
  4998.2 1704.23  5007.4 1702.19  5007.6 1701.69  5011.4 1702.19  5017.8 1704.06
  5026.1 1708.16  5040.1 1711.44  5062.5 1712.82  5070.9 1714.92  5093.2 1716.92
  5143.5  1720.1    5233 1729.53  5241.4  1730.9  5294.5 1743.99  5330.8  1747.5
#Mann= 6 ,-1 , 0
  4571.1     .12       0  4659.2     .07       0  4856.5     .12       0
  4961.7     .07       0  5007.4     .05       0  5011.4     .07       0
Bank Sta=5007.4,5011.4
XS Rating Curve= 0 ,0
Exp/Cntr=0.3,0.1

Type RM Length L Ch R = 1 ,25803   ,586,586,586
BEGIN DESCRIPTION:
JUNG CREEK 53.0
END DESCRIPTION:
XS GIS Cut Line= 3
      2038636.84     13945514.61      2038279.23     13945290.56
      2037580.25     13944999.89
#Sta/Elev= 30
  4574.7 1745.26  4640.8 1737.82  4683.3 1736.54  4868.4    1720  4904.6 1716.15
    4939 1706.76  4989.9 1701.73  5000.4  1697.7  5000.7  1697.2  5004.4  1697.7
  5020.9 1701.64    5074 1706.22  5174.6 1711.82  5310.3 1728.88  5363.4 1731.07
  5387.3 1735.77  5392.7 1734.06  5440.4 1737.89  5493.5 1738.13  5517.4  1743.1
  5522.8 1740.25  5541.2 1743.86  5546.6 1741.55  5564.4 1745.35  5623.6 1747.64
  5676.7 1751.46  5700.6 1756.38    5706 1754.35  5724.4 1757.82  5753.7 1758.56
#Mann= 5 ,-1 , 0
  4574.7     .07       0  4868.4     .12       0  4904.6     .07       0
  5000.4     .05       0  5004.4     .07       0
Bank Sta=5000.4,5004.4
XS Rating Curve= 0 ,0
Exp/Cntr=0.3,0.1

Type RM Length L Ch R = 1 ,25217   ,448,448,448
BEGIN DESCRIPTION:
JUNG CREEK 52.0
END DESCRIPTION:
XS GIS Cut Line= 3
      2038845.21     13945200.29        2038475.       13944775.
      2038175.01     13944475.01
#Sta/Elev= 30
  4436.1 1748.12  4446.9 1746.55    4539 1742.03  4553.2 1737.81    4596 1731.79
  4602.6 1728.71  4638.7 1726.18  4702.3  1717.8  4730.8 1711.45  4751.7 1704.03
  4765.9 1701.27  4830.7  1694.8  4900.7 1691.12  4992.8  1692.1  4996.6 1690.41
  5003.5 1690.41  5012.1 1687.12  5012.3 1686.62  5016.1 1687.12  5028.2 1687.57
  5042.4  1690.9  5056.5  1692.3  5096.8  1694.6  5127.2 1697.92  5212.1 1721.65
  5247.4 1725.21  5254.5 1731.25  5296.9 1742.68  5339.4 1749.88  5424.2 1770.85
#Mann= 5 ,-1 , 0
  4436.1     .07       0  4830.7     .12       0  5012.1     .05       0
  5016.1     .12       0  5096.8     .07       0
Bank Sta=5012.1,5016.1
XS Rating Curve= 0 ,0
Exp/Cntr=0.3,0.1

Type RM Length L Ch R = 1 ,24769   ,435,435,435
BEGIN DESCRIPTION:
JUNG CREEK 51.0
END DESCRIPTION:
XS GIS Cut Line= 3
      2039112.55     13944891.23        2038725.       13944425.
      2038398.66     13944211.59
#Sta/Elev= 30
  4388.7 1744.67  4462.3 1741.24  4483.9 1737.35  4519.1 1737.33  4533.4 1733.73
  4554.2 1733.55  4576.4 1728.78  4611.5 1724.26  4675.3 1718.88  4774.3 1699.76
  4831.6 1692.38  4888.9  1681.7    4924 1679.03  4988.4 1679.72    4998 1678.71
  5006.5 1668.68  5006.8 1668.18  5010.5 1668.68  5023.6  1670.5  5044.7 1683.85
  5053.8  1685.9  5059.8 1689.33  5101.7 1696.08  5132.2 1699.65  5219.7 1716.13
  5246.7 1717.05  5261.9 1723.04  5334.2 1735.02  5370.4 1742.99  5384.9 1747.74
#Mann= 6 ,-1 , 0
  4388.7     .12       0  4462.3     .07       0  4988.4     .12       0
  5006.5     .05       0  5010.5     .12       0  5101.7     .07       0
Bank Sta=5006.5,5010.5
XS Rating Curve= 0 ,0
Exp/Cntr=0.3,0.1

Type RM Length L Ch R = 1 ,24334   ,438,438,438
BEGIN DESCRIPTION:
JUNG CREEK 50.0
END DESCRIPTION:
XS GIS Cut Line= 3
       2039168.1     13944273.19        2038925.       13944175.
      2038661.19     13944116.95
#Sta/Elev= 30
  4744.7 1702.63  4873.2 1692.16  4908.9 1689.86  4920.6 1688.18  4931.4 1681.67
  4936.5 1671.99  4938.4 1668.38  4943.8  1671.9    4953 1664.03  4962.6 1662.84
    4968 1663.72  4972.5 1662.23  4972.8 1661.73  4976.5 1662.23  4992.1 1666.94
  4997.5  1665.1  5004.2 1666.66  5047.8 1666.88  5058.1 1668.97  5068.3 1673.77
  5075.1 1678.36  5080.2 1676.89  5088.8 1680.35  5191.2 1688.34  5211.4 1692.72
  5216.5 1692.76  5242.4 1700.92  5265.4 1705.28  5272.5 1708.26    5277 1708.26
#Mann= 5 ,-1 , 0
  4744.7     .07       0  4873.2     .12       0  4936.5     .07       0
  4972.5     .05       0  4976.5     .07       0
Bank Sta=4972.5,4976.5
XS Rating Curve= 0 ,0
Exp/Cntr=0.3,0.1

Type RM Length L Ch R = 1 ,23896   ,404,404,404
BEGIN DESCRIPTION:
JUNG CREEK 49.0
END DESCRIPTION:
XS GIS Cut Line= 3
       2039220.2     13944023.19        2039075.       13943825.
      2038171.59     13943811.39
#Sta/Elev= 30
    4749 1683.75  4765.8 1676.74    4812 1670.93  4880.8    1667  4981.2 1664.88
  4987.4 1662.06  4991.6 1658.32  5012.7 1654.82  5012.9 1654.32  5016.7 1654.82
  5037.8 1663.35  5074.7 1671.18  5244.7 1684.98  5284.7 1689.42    5319 1695.23
  5328.2 1695.68  5372.6 1705.56  5414.7 1715.71  5444.7 1720.82  5484.7 1732.53
  5583.2 1751.31  5674.8 1775.07  5694.8 1776.61  5704.8  1779.2  5734.8 1790.79
  5764.8 1804.61  5796.7 1816.15  5834.8 1828.31  5884.8 1848.61  5898.2 1850.25
#Mann= 9 ,-1 , 0
    4749     .07       0    4812     .12       0  5012.7     .05       0
  5016.7     .12       0  5037.8     .07       0    5319    .035       0
  5372.6     .07       0  5583.2    .035       0  5796.7     .07       0
Bank Sta=5012.7,5016.7
XS Rating Curve= 0 ,0
Exp/Cntr=0.3,0.1

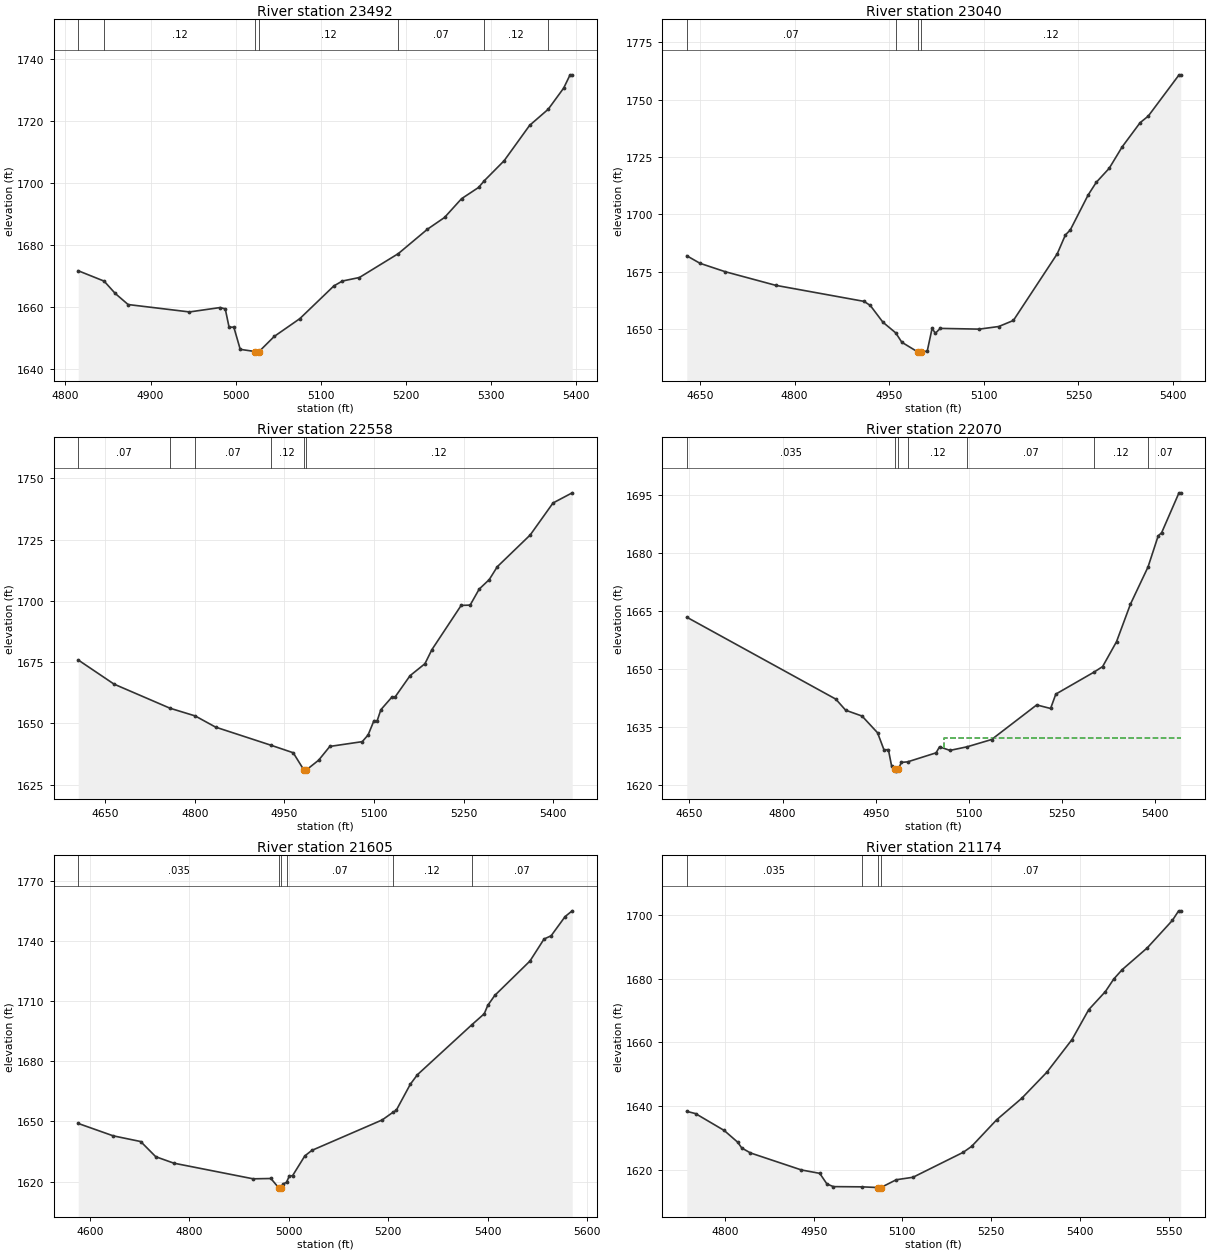
Type RM Length L Ch R = 1 ,23492   ,452,452,452
BEGIN DESCRIPTION:
JUNG CREEK 48.0
END DESCRIPTION:
XS GIS Cut Line= 3
      2039474.99     13943774.98        2039375.       13943625.
        2039375.     13943224.95
#Sta/Elev= 30
    4815  1671.7  4845.4 1668.35  4858.5 1664.36  4873.6 1660.79  4945.7  1658.4
  4981.7 1659.82  4987.7  1659.4  4992.2 1653.48  4997.8 1653.48  5005.3 1646.32
  5023.2  1645.6  5023.4  1645.1  5027.4  1645.6  5045.3  1650.5  5075.3 1656.23
  5115.3  1666.8  5125.3 1668.38  5145.3 1669.52    5191 1677.23  5225.3 1685.13
  5245.3  1688.9  5265.3 1694.97  5285.3  1698.6    5292 1700.76  5315.3 1707.22
  5345.3 1718.66  5367.1 1723.85  5385.3  1730.7  5392.8 1734.97  5395.3 1734.97
#Mann= 7 ,-1 , 0
    4815     .07       0  4845.4     .12       0  5023.2     .05       0
  5027.4     .12       0    5191     .07       0    5292     .12       0
  5367.1     .07       0
Bank Sta=5023.2,5027.4
XS Rating Curve= 0 ,0
Exp/Cntr=0.3,0.1

Type RM Length L Ch R = 1 ,23040   ,482,482,482
BEGIN DESCRIPTION:
JUNG CREEK 47.0
END DESCRIPTION:
XS GIS Cut Line= 3
      2039775.75     13943846.11        2039775.       13943475.
        2039675.     13943075.02
#Sta/Elev= 30
  4628.9 1681.93    4650 1678.63    4690 1674.97    4770 1669.04    4910 1662.05
    4920 1660.26    4940 1652.97  4960.3 1648.32    4970 1644.23  4995.4 1639.99
  4995.7 1639.49  4999.7 1639.99  5010.3 1640.37    5018 1650.29  5023.2 1648.15
  5030.9 1650.27  5092.8 1649.95  5123.7 1651.09  5146.9 1653.72  5216.5  1682.8
  5229.4    1691  5237.1 1693.15  5265.4 1708.38  5278.3 1713.91  5298.9 1720.06
  5319.5 1729.42  5347.9 1739.93  5360.8  1742.8  5409.7 1760.79  5412.3 1760.79
#Mann= 4 ,-1 , 0
  4628.9     .07       0  4960.3     .12       0  4995.4     .05       0
  4999.7     .12       0
Bank Sta=4995.4,4999.7
XS Rating Curve= 0 ,0
Exp/Cntr=0.3,0.1

Type RM Length L Ch R = 1 ,22558   ,488,488,488
BEGIN DESCRIPTION:
JUNG CREEK 46.0
END DESCRIPTION:
XS GIS Cut Line= 3
        2040225.     13943774.97        2040225.       13943375.
      2040074.99     13942974.97
#Sta/Elev= 30
  4604.6 1675.88  4664.6 1666.03  4758.2 1656.21  4800.5 1653.05  4834.6 1648.49
  4926.6 1641.16  4964.6 1638.03  4982.4 1631.03  4982.7 1630.53  4986.7 1631.03
  5007.2    1635  5025.9 1640.61  5080.2 1642.56    5090 1645.29  5099.8 1651.12
  5105.1 1651.02  5111.4  1655.6  5130.1 1660.81  5135.4 1660.86  5160.3 1669.49
  5185.2 1674.37  5196.8 1680.09  5245.8 1698.15  5260.9 1698.29    5276 1704.81
  5292.9  1708.7  5306.3 1713.93  5361.5 1726.91  5399.7 1739.96  5431.8  1744.1
#Mann= 6 ,-1 , 0
  4604.6     .07       0  4758.2     .12       0  4800.5     .07       0
  4926.6     .12       0  4982.4     .05       0  4986.7     .12       0
Bank Sta=4982.4,4986.7
XS Rating Curve= 0 ,0
Exp/Cntr=0.3,0.1

Type RM Length L Ch R = 1 ,22070   ,465,465,465
BEGIN DESCRIPTION:
JUNG CREEK 45.0
END DESCRIPTION:
XS GIS Cut Line= 3
      2040754.93      13943714.2        2040675.       13943375.
        2040475.     13942975.01
#Sta/Elev= 30
  4645.7 1663.43  4885.8 1642.24  4901.7 1639.37  4928.1 1637.86  4953.1 1633.53
  4963.4 1629.12  4970.5 1629.18  4975.6 1625.01  4981.7 1624.12    4982 1623.62
  4986.1 1624.12  4991.6 1625.88  5001.5 1626.02  5047.3 1628.35  5052.9 1629.91
  5069.7 1628.98  5097.5 1629.92  5136.7 1631.79  5209.4 1640.74  5231.8 1639.82
  5240.2 1643.54  5301.7 1649.22  5315.6 1650.66    5338  1657.1  5360.4  1666.8
  5388.7  1676.4  5405.1 1684.45  5410.7 1685.29  5438.6 1695.59  5441.4 1695.59
#Mann= 7 ,-1 , 0
  4645.7    .035       0  4981.7    .035       0  4986.1    .035       0
  5001.5     .12       0  5097.5     .07       0  5301.7     .12       0
  5388.7     .07       0
#XS Ineff= 2 , 0
       0                 5059.33       0 1632.17
Permanent Ineff=
       F       F
Bank Sta=4981.7,4986.1
XS Rating Curve= 0 ,0
Exp/Cntr=0.3,0.1

Type RM Length L Ch R = 1 ,21605   ,431,431,431
BEGIN DESCRIPTION:
JUNG CREEK 44.0
END DESCRIPTION:
XS GIS Cut Line= 3
        2041125.       13943475.        2040975.       13943075.
      2040574.99     13942674.99
#Sta/Elev= 30
  4576.9 1648.97  4647.2  1642.8  4702.4 1639.96  4732.7 1632.39  4769.1 1629.17
  4928.5 1621.37  4964.1 1621.53  4980.5 1616.73  4980.8 1616.23    4985 1616.73
    4989  1618.8  4995.6 1619.67  5001.4 1622.89  5007.6 1622.89  5032.4 1632.81
  5046.5 1635.55  5187.9 1650.73    5209 1654.45  5216.2 1655.57  5244.5 1668.57
  5258.7 1673.28  5368.2 1698.22    5393 1703.66  5400.1 1707.85  5414.2 1712.82
  5484.9 1729.96  5513.2 1740.94  5527.4 1742.54  5555.6 1752.14  5569.8 1754.99
#Mann= 6 ,-1 , 0
  4576.9    .035       0  4980.5     .05       0    4985    .035       0
  4995.6     .07       0    5209     .12       0  5368.2     .07       0
Bank Sta=4980.5,4985
XS Rating Curve= 0 ,0
Exp/Cntr=0.3,0.1

Type RM Length L Ch R = 1 ,21174   ,404,404,404
BEGIN DESCRIPTION:
JUNG CREEK 43.0
END DESCRIPTION:
XS GIS Cut Line= 3
      2041474.99     13943224.98        2041375.       13942975.
      2040975.02     13942575.02
#Sta/Elev= 30
  4735.5 1638.34  4750.3 1637.64  4798.8 1632.33  4821.6 1628.64  4828.4 1626.83
  4843.2 1625.26  4929.3 1619.91  4960.3 1618.84  4972.4 1615.51  4983.2 1614.67
  5031.4  1614.6  5059.1 1614.38  5059.4 1613.88  5063.6 1614.38  5089.6 1616.83
  5117.9 1617.61  5202.7 1625.45  5216.9 1627.31  5259.3 1635.69  5301.7 1642.45
  5344.2 1650.66  5386.6 1660.91  5414.9 1670.32  5443.1 1676.02  5457.3 1679.98
  5471.4  1682.9  5513.9 1689.77  5556.3  1698.4  5566.9 1701.41  5570.4 1701.41
#Mann= 4 ,-1 , 0
  4735.5    .035       0  5031.4     .07       0  5059.1    .035       0
  5063.6     .07       0
Bank Sta=5059.1,5063.6
XS Rating Curve= 0 ,0
Exp/Cntr=0.3,0.1

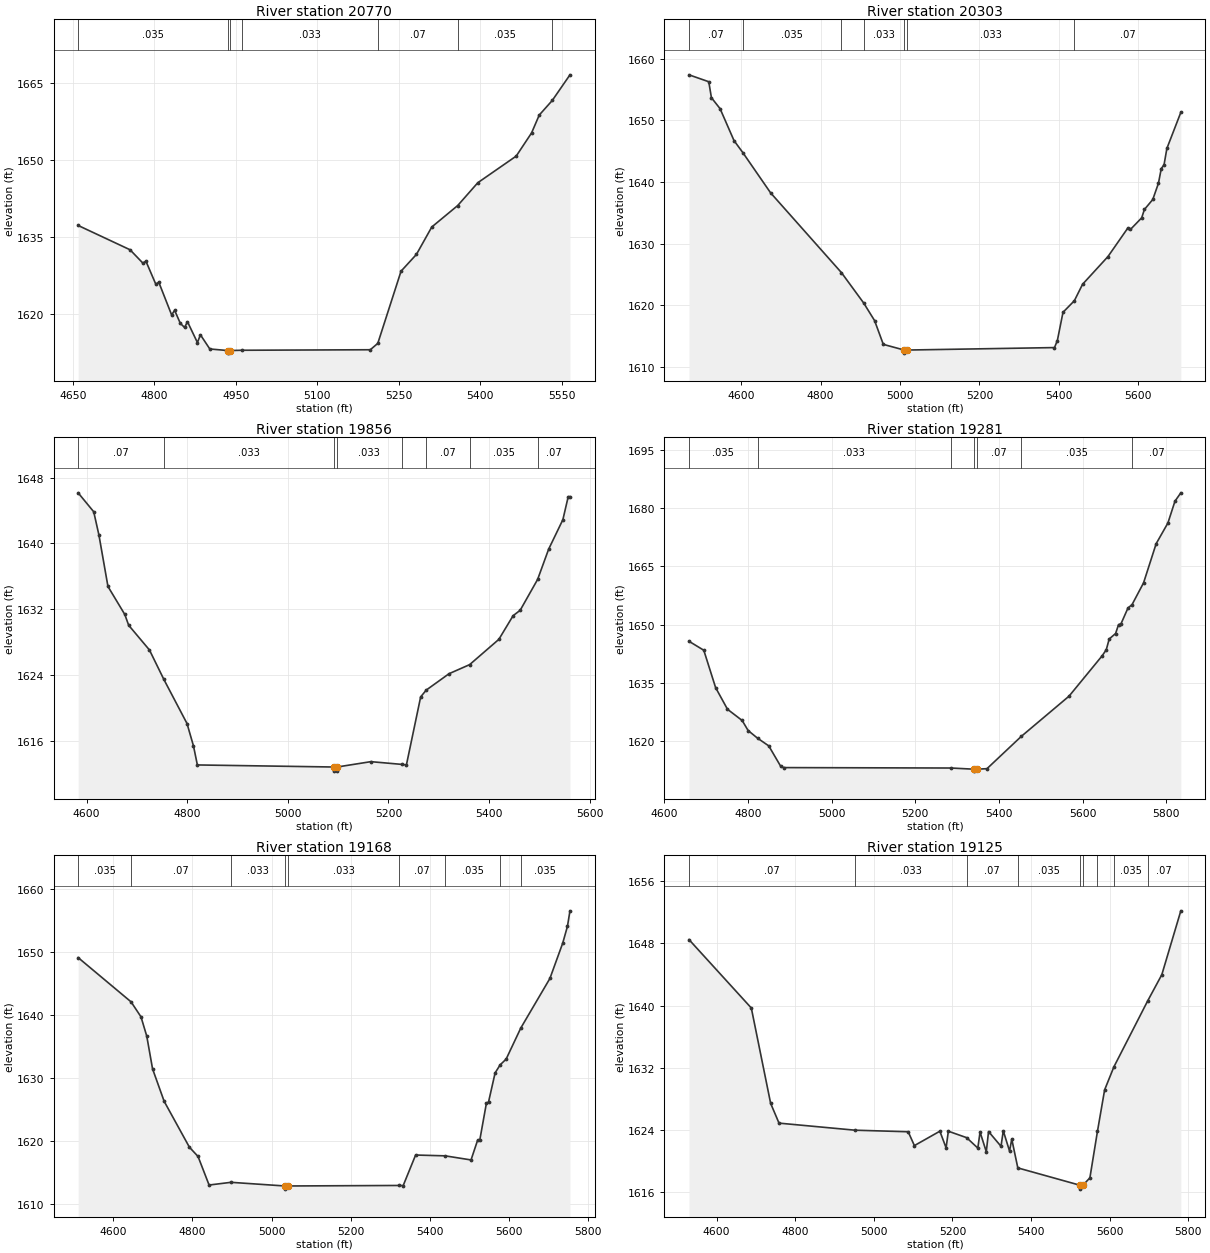
Type RM Length L Ch R = 1 ,20770   ,467,467,467
BEGIN DESCRIPTION:
JUNG CREEK 42.0
END DESCRIPTION:
XS GIS Cut Line= 3
       2041543.1     13943238.52        2041675.       13942925.
      2041275.01     13942525.01
#Sta/Elev= 30
  4659.6 1637.25  4755.2 1632.51  4778.9  1629.9  4784.4 1630.29  4802.7 1625.78
  4808.1 1626.19  4831.8  1619.8  4837.3  1620.7  4847.8 1618.16  4855.6 1617.36
    4861 1618.47  4879.3 1614.41  4884.8 1615.93  4902.1 1613.16  4935.4 1612.85
  4935.7 1612.35  4939.9 1612.85  4960.6 1612.91  5197.7 1613.01  5211.5 1614.26
  5254.3 1628.33  5282.6  1631.6  5310.9 1636.95  5358.7 1641.14  5395.7 1645.59
  5466.4 1650.78  5494.7  1655.3  5508.8 1658.78  5532.8 1661.63  5565.4 1666.63
#Mann= 7 ,-1 , 0
  4659.6    .035       0  4935.4    .033       0  4939.9    .035       0
  4960.6    .033       0  5211.5     .07       0  5358.7    .035       0
  5532.8     .07       0
Bank Sta=4935.4,4939.9
XS Rating Curve= 0 ,0
Exp/Cntr=0.3,0.1

Type RM Length L Ch R = 1 ,20303   ,447,447,447
BEGIN DESCRIPTION:
JUNG CREEK 41.0
END DESCRIPTION:
XS GIS Cut Line= 3
      2042474.99       13943275.        2042075.       13942925.
      2041563.98     13942436.42
#Sta/Elev= 30
  4468.5 1657.36  4518.3 1656.24    4525 1653.65  4546.8 1651.87  4581.9 1646.69
  4603.9 1644.76    4674 1638.22  4852.5 1625.27  4908.4 1620.35  4935.9 1617.49
  4957.8 1613.64  5010.4 1612.72  5010.9 1612.22  5017.5 1612.72  5388.9 1613.12
  5396.1 1614.26  5410.3 1618.84  5438.9 1620.72  5459.6 1623.39  5523.5 1627.88
  5572.9 1632.45  5580.1 1632.28  5608.4 1634.16  5615.3 1635.52  5636.4 1637.14
  5650.6 1639.76  5657.8 1642.16  5664.7 1642.75  5671.9 1645.42    5707 1651.27
#Mann= 7 ,-1 , 0
  4468.5     .07       0  4603.9    .035       0  4852.5     .07       0
  4908.4    .033       0  5010.4    .033       0  5017.5    .033       0
  5438.9     .07       0
Bank Sta=5010.4,5017.5
XS Rating Curve= 0 ,0
Exp/Cntr=0.3,0.1

Type RM Length L Ch R = 1 ,19856   ,575,575,575
BEGIN DESCRIPTION:
JUNG CREEK 40.0
END DESCRIPTION:
XS GIS Cut Line= 3
      2042625.04     13942725.01        2042225.       13942625.
      2041825.03     13942225.03
#Sta/Elev= 30
    4583 1646.15    4614 1643.85  4624.3 1641.04  4642.3 1634.78  4675.8 1631.38
  4683.5 1630.07  4724.8 1627.07  4753.5 1623.49  4799.5 1618.14  4812.4 1615.41
  4820.1 1613.11  5090.8 1612.86  5091.3 1612.36  5097.5 1612.36    5098 1612.86
  5165.1 1613.51  5226.3 1613.18  5235.8 1613.12  5264.1 1621.37  5275.2  1622.2
  5320.6 1624.19  5361.5 1625.29  5419.6 1628.36  5447.9 1631.23    5462 1631.89
  5496.7 1635.64  5518.6 1639.31  5546.9 1642.89  5557.5 1645.68    5561 1645.68
#Mann= 8 ,-1 , 0
    4583     .07       0  4753.5    .033       0  5090.8    .033       0
    5098    .033       0  5226.3    .035       0  5275.2     .07       0
  5361.5    .035       0  5496.7     .07       0
Bank Sta=5090.8,5098
XS Rating Curve= 0 ,0
Exp/Cntr=0.3,0.1

Type RM Length L Ch R = 1 ,19281   ,113,113,113
BEGIN DESCRIPTION:
JUNG CREEK 39.0
END DESCRIPTION:
XS GIS Cut Line= 3
      2042774.97     13942524.97      2042525.75     13942294.03
      2041775.02     13941925.01
#Sta/Elev= 30
  4658.7 1645.68  4694.1 1643.37  4722.4 1633.74  4750.8 1628.17  4785.9 1625.28
  4800.1  1622.7  4822.6 1620.73  4849.5 1618.74  4877.8 1613.53  4885.2 1613.15
  5285.6 1613.04  5339.7 1612.74  5340.2 1612.24    5347 1612.74  5371.4 1612.87
  5453.4 1621.18  5567.6 1631.54  5646.7 1641.92  5656.7  1643.5  5663.7 1646.27
    5679 1647.68  5686.1 1649.98  5691.7 1650.13  5708.6 1654.25  5718.4 1655.13
  5745.9 1660.73    5776 1670.81  5804.1 1676.14    5821 1681.76    5835 1683.91
#Mann= 7 ,-1 , 0
  4658.7    .035       0  4822.6    .033       0  5285.6     .07       0
  5339.7    .033       0    5347     .07       0  5453.4    .035       0
  5718.4     .07       0
Bank Sta=5339.7,5347
XS Rating Curve= 0 ,0
Exp/Cntr=0.3,0.1

Type RM Length L Ch R = 1 ,19168   ,43,43,43
BEGIN DESCRIPTION:
JUNG CREEK 38.3
END DESCRIPTION:
XS GIS Cut Line= 3
       2042951.1     13942481.81      2042557.96     13942191.52
      2041888.79     13941844.71
#Sta/Elev= 30
  4511.3  1649.1    4645 1642.08  4670.1  1639.7  4684.7 1636.63  4699.3 1631.45
  4728.6  1626.3  4792.4 1619.02  4814.2 1617.55  4842.1 1613.02  4897.5 1613.45
  5033.5 1612.87    5034 1612.37  5040.8 1612.87  5322.2 1612.95  5332.4 1612.93
  5363.8 1617.78  5438.4 1617.65  5503.8    1617  5520.3 1620.11    5526 1620.19
  5542.5 1625.96  5548.1 1626.22  5564.6 1630.81  5577.4 1632.09  5592.4 1632.99
  5629.5 1637.93    5703 1645.79  5735.4  1651.4  5747.3 1654.05  5753.7 1656.52
#Mann= 9 ,-1 , 0
  4511.3    .035       0    4645     .07       0  4897.5    .033       0
  5033.5    .033       0  5040.8    .033       0  5322.2     .07       0
  5438.4    .035       0  5577.4     .07       0  5629.5    .035       0
Bank Sta=5033.5,5040.8
XS Rating Curve= 0 ,0
Exp/Cntr=0.3,0.1

Type RM Length L Ch R = 1 ,19125   ,72,72,72
BEGIN DESCRIPTION:
JUNG CREEK 38.2
END DESCRIPTION:
XS GIS Cut Line= 3
      2042990.48     13942406.14      2042588.64     13942161.79
      2041909.82     13941774.96
#Sta/Elev= 30
  4529.7 1648.49  4688.3 1639.69  4737.5 1627.42  4758.8 1624.88  4952.5 1623.97
  5087.5 1623.77  5103.3 1621.99  5168.1 1623.84    5184  1621.7  5189.7 1623.84
  5236.3 1623.01  5264.7 1621.67  5270.4 1623.73  5286.3  1621.2    5292  1623.8
  5323.7  1621.9  5329.5 1623.89  5345.4 1621.29  5351.1 1622.82  5366.5 1619.12
  5524.7 1616.89  5525.2 1616.39    5532 1616.89  5549.9 1617.84  5569.1 1623.81
  5587.4 1629.16    5611 1632.12  5696.8 1640.59  5732.9 1643.97  5781.3 1652.19
#Mann= 9 ,-1 , 0
  4529.7     .07       0  4952.5    .033       0  5236.3     .07       0
  5366.5    .035       0  5524.7    .033       0    5532    .035       0
  5569.1     .07       0    5611    .035       0  5696.8     .07       0
Bank Sta=5524.7,5532
XS Rating Curve= 0 ,0
Exp/Cntr=0.3,0.1

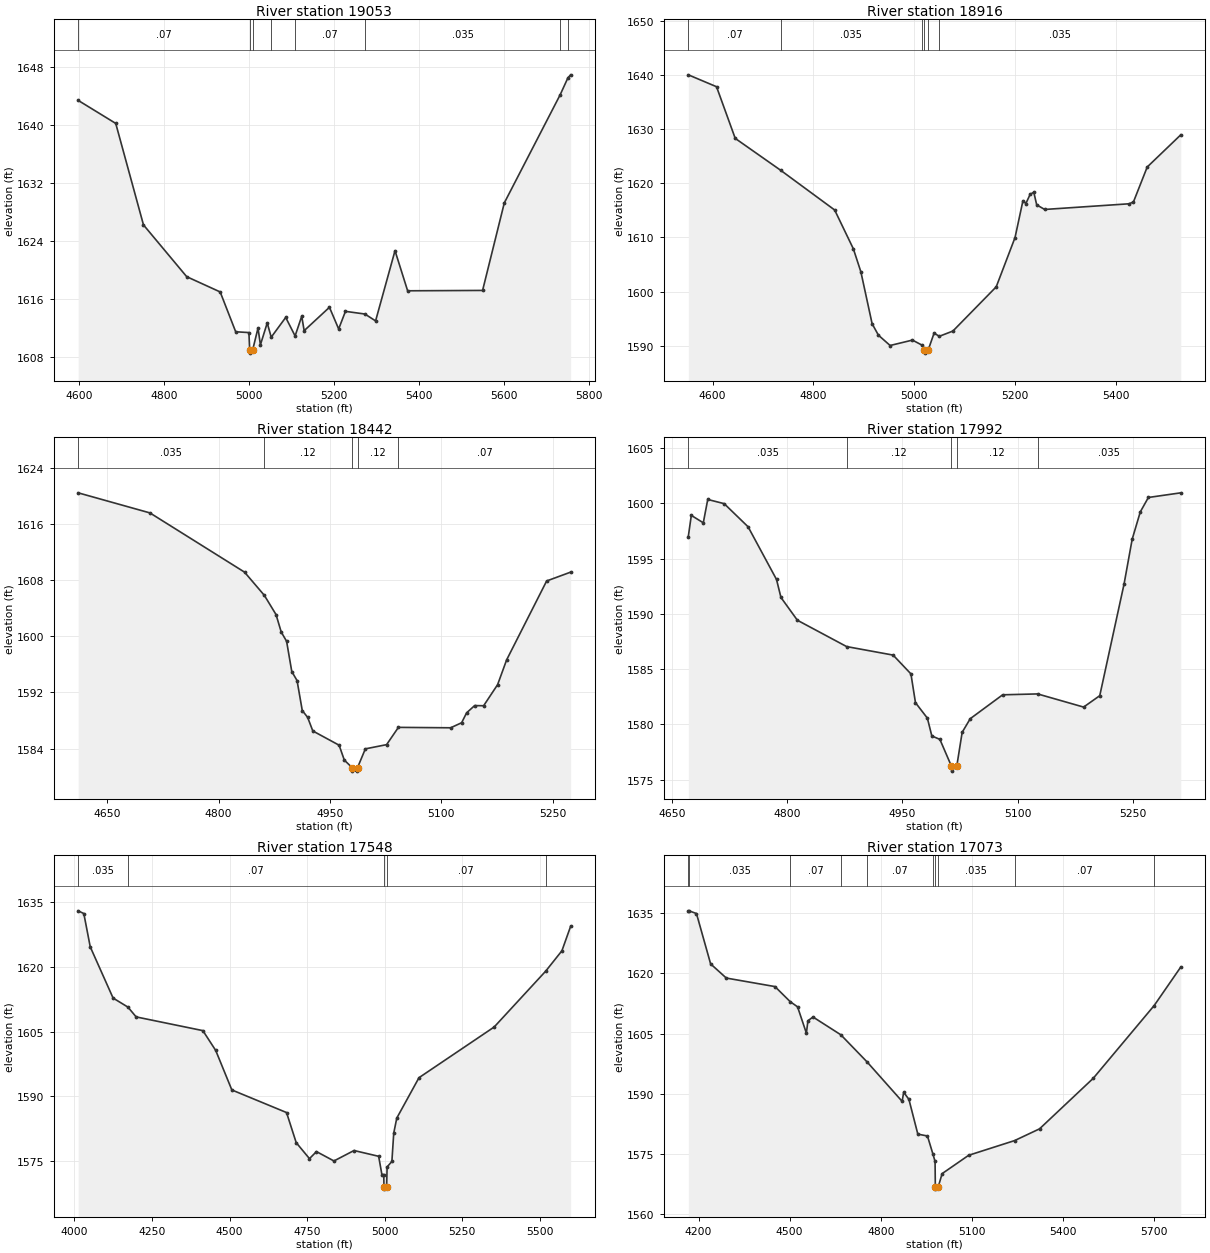
Type RM Length L Ch R = 1 ,19053   ,137,137,137
BEGIN DESCRIPTION:
JUNG CREEK 38.1
END DESCRIPTION:
XS GIS Cut Line= 3
      2042964.88     13942317.16      2042625.37     13942102.27
      2041963.94     13941733.88
#Sta/Elev= 30
  4598.2 1643.42  4686.6 1640.24  4751.9 1626.22  4853.6 1619.07  4932.4 1616.96
  4968.9 1611.46    5000 1611.35  5001.8 1609.01  5002.3 1608.51  5009.1 1609.01
  5021.4 1611.97  5027.1 1609.66  5043.1 1612.68  5052.5 1610.71  5086.6 1613.44
  5108.7 1610.88  5124.3 1613.61    5130 1611.61  5189.5 1614.84  5211.2 1611.85
  5227.2 1614.28    5273 1613.91  5298.1 1612.96  5343.8 1622.66  5373.5 1617.12
  5549.9 1617.17    5601 1629.26  5732.5  1644.2  5750.8 1646.55  5757.1 1646.95
#Mann= 8 ,-1 , 0
  4598.2     .07       0  5001.8     .05       0  5009.1     .07       0
  5052.5    .033       0  5108.7     .07       0    5273    .035       0
  5732.5     .07       0  5750.8    .035       0
Bank Sta=5001.8,5009.1
XS Rating Curve= 0 ,0
Exp/Cntr=0.3,0.1

Type RM Length L Ch R = 1 ,18916   ,474,474,474
BEGIN DESCRIPTION:
JUNG CREEK 38.0
END DESCRIPTION:
XS GIS Cut Line= 3
      2042970.19     13942207.22        2042575.       13941975.
      2042126.49     13941714.19
#Sta/Elev= 30
  4551.7 1640.07  4607.7 1637.87  4644.8 1628.32  4734.7 1622.44  4842.1 1615.08
  4879.2  1607.9  4894.1 1603.65  4916.4 1594.06  4928.9 1591.94  4952.1 1590.03
  4996.4 1591.03    5016 1590.07  5020.1 1589.12  5020.6 1588.62  5027.4 1589.12
  5039.4 1592.32  5049.7 1591.73  5076.7  1592.7  5162.7 1600.88    5200 1609.99
  5215.7  1616.8  5221.5 1616.28  5229.9 1617.96  5237.2 1618.37    5243 1616.03
  5258.8 1615.18  5426.5 1616.23    5435 1616.58  5462.3 1623.03  5528.9 1628.98
#Mann= 6 ,-1 , 0
  4551.7     .07       0  4734.7    .035       0    5016     .07       0
  5020.1    .035       0  5027.4     .07       0  5049.7    .035       0
Bank Sta=5020.1,5027.4
XS Rating Curve= 0 ,0
Exp/Cntr=0.3,0.1

Type RM Length L Ch R = 1 ,18442   ,450,450,450
BEGIN DESCRIPTION:
JUNG CREEK 37.0
END DESCRIPTION:
XS GIS Cut Line= 3
      2043050.04     13941856.51        2042775.       13941575.
      2042525.02     13941475.01
#Sta/Elev= 30
  4611.1 1620.41  4707.7 1617.55    4835 1609.12  4861.7 1605.81  4877.4 1603.08
  4884.4 1600.59  4891.6 1599.28  4898.6 1594.97  4905.7 1593.68  4912.7 1589.42
  4919.9 1588.45  4926.9 1586.51  4962.3 1584.48  4969.3 1582.36  4979.8 1581.29
  4980.3 1580.79  4986.6 1580.79  4987.1 1581.29  4997.6 1583.96  5026.2 1584.56
  5042.1 1587.02  5112.4 1586.96  5127.2 1587.68  5133.9 1589.09  5144.7 1590.12
  5156.8  1590.1  5175.6  1593.1  5187.8 1596.64  5241.6 1607.86  5273.9 1609.12
#Mann= 5 ,-1 , 0
  4611.1    .035       0  4861.7     .12       0  4979.8     .05       0
  4987.1     .12       0  5042.1     .07       0
Bank Sta=4979.8,4987.1
XS Rating Curve= 0 ,0
Exp/Cntr=0.3,0.1

Type RM Length L Ch R = 1 ,17992   ,444,444,444
BEGIN DESCRIPTION:
JUNG CREEK 36.0
END DESCRIPTION:
XS GIS Cut Line= 3
      2043091.74     13941453.77        2042925.       13941175.
      2042624.96     13941275.01
#Sta/Elev= 30
  4671.3 1596.99  4675.2  1598.9  4690.8 1598.23  4696.6 1600.34    4718 1599.96
  4749.1 1597.87  4786.1 1593.11  4791.9 1591.48  4813.3 1589.42  4877.4 1587.04
  4937.9 1586.27  4961.1 1584.57    4967 1581.97  4982.5 1580.57  4988.3 1578.96
  4998.8 1578.65  5013.5 1576.28    5014 1575.78  5020.9 1576.28  5027.8 1579.29
  5038.3 1580.52  5080.5 1582.68    5126 1582.76  5185.9 1581.57  5206.9  1582.6
  5238.6 1592.71  5249.1 1596.74  5259.7 1599.22  5270.2 1600.52  5312.4 1600.94
#Mann= 5 ,-1 , 0
  4671.3    .035       0  4877.4     .12       0  5013.5     .05       0
  5020.9     .12       0    5126    .035       0
Bank Sta=5013.5,5020.9
XS Rating Curve= 0 ,0
Exp/Cntr=0.3,0.1

Type RM Length L Ch R = 1 ,17548   ,475,475,475
BEGIN DESCRIPTION:
JUNG CREEK 35.0
END DESCRIPTION:
XS GIS Cut Line= 4
      2043428.54     13941672.52      2043241.03       13940985.
        2043025.       13940825.       2042504.9     13940516.24
#Sta/Elev= 30
  4012.5 1633.01  4030.7 1632.38  4051.4 1624.66    4125 1612.79  4172.8 1610.69
  4199.3 1608.42  4414.2 1605.24  4455.6 1600.64  4507.5 1591.49  4683.7 1586.25
  4714.8 1579.28  4757.5 1575.57  4780.1  1577.2  4836.4 1575.03  4901.1 1577.45
  4980.4 1576.11  4990.8 1571.89  4996.9 1571.89  4997.5    1569    4998  1568.5
  5006.1    1569  5007.6 1573.65    5023 1574.91    5029 1581.49  5038.8 1584.97
  5110.3 1594.33  5352.5 1606.08  5518.7 1619.05  5570.7 1623.75  5598.8 1629.43
#Mann= 5 ,-1 , 0
  4012.5    .035       0  4172.8     .07       0  4997.5     .05       0
  5006.1     .07       0  5518.7     .12       0
Bank Sta=4997.5,5006.1
XS Rating Curve= 0 ,0
Exp/Cntr=0.3,0.1

Type RM Length L Ch R = 1 ,17073   ,457,457,457
BEGIN DESCRIPTION:
JUNG CREEK 34.0
END DESCRIPTION:
XS GIS Cut Line= 3
      2043584.78     13941648.18        2043425.       13940825.
      2042852.14     13940290.56
#Sta/Elev= 30
  4166.2 1635.54  4168.6 1635.54  4193.1 1634.86  4239.7 1622.33  4291.4 1618.81
  4451.6 1616.69  4501.6 1612.95    4526 1611.65  4555.1  1605.1  4560.1 1608.18
  4576.9 1609.12  4668.4  1604.7  4754.5 1597.98  4870.4 1588.13  4875.5 1590.38
  4892.7 1588.64  4922.1 1579.98  4953.8 1579.51  4972.2 1574.93  4978.9 1573.17
  4979.8 1566.79  4980.3 1566.29    4989 1566.79  5002.2 1570.15  5089.5 1574.71
  5240.9 1578.37    5323 1581.29  5499.9 1593.87  5700.5 1611.97  5788.2 1621.56
#Mann= 10 ,-1 , 0
  4166.2     .07       0  4168.6    .035       0  4501.6     .07       0
  4668.4    .035       0  4754.5     .07       0  4972.2    .035       0
  4979.8    .035       0    4989    .035       0  5240.9     .07       0
  5700.5    .035       0
Bank Sta=4979.8,4989
XS Rating Curve= 0 ,0
Exp/Cntr=0.3,0.1