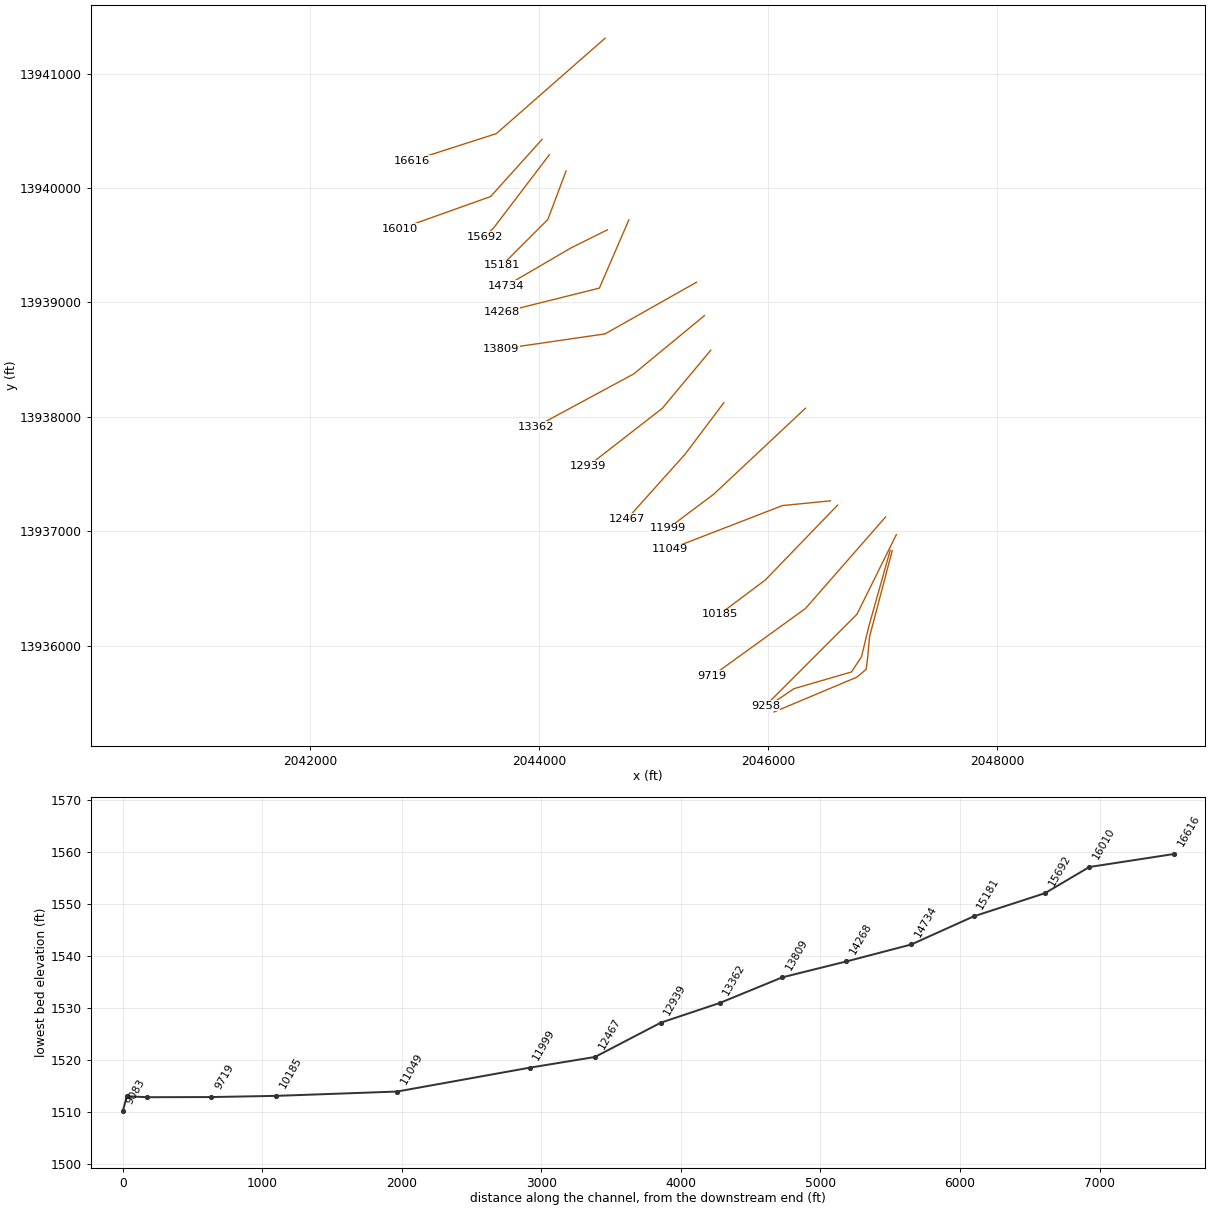
HEC-RAS study JUNG CREEK.prj: JUNG CREEK Base Level Engineering

--- JUNG CREEK.g01 (geometry) --- (continued)

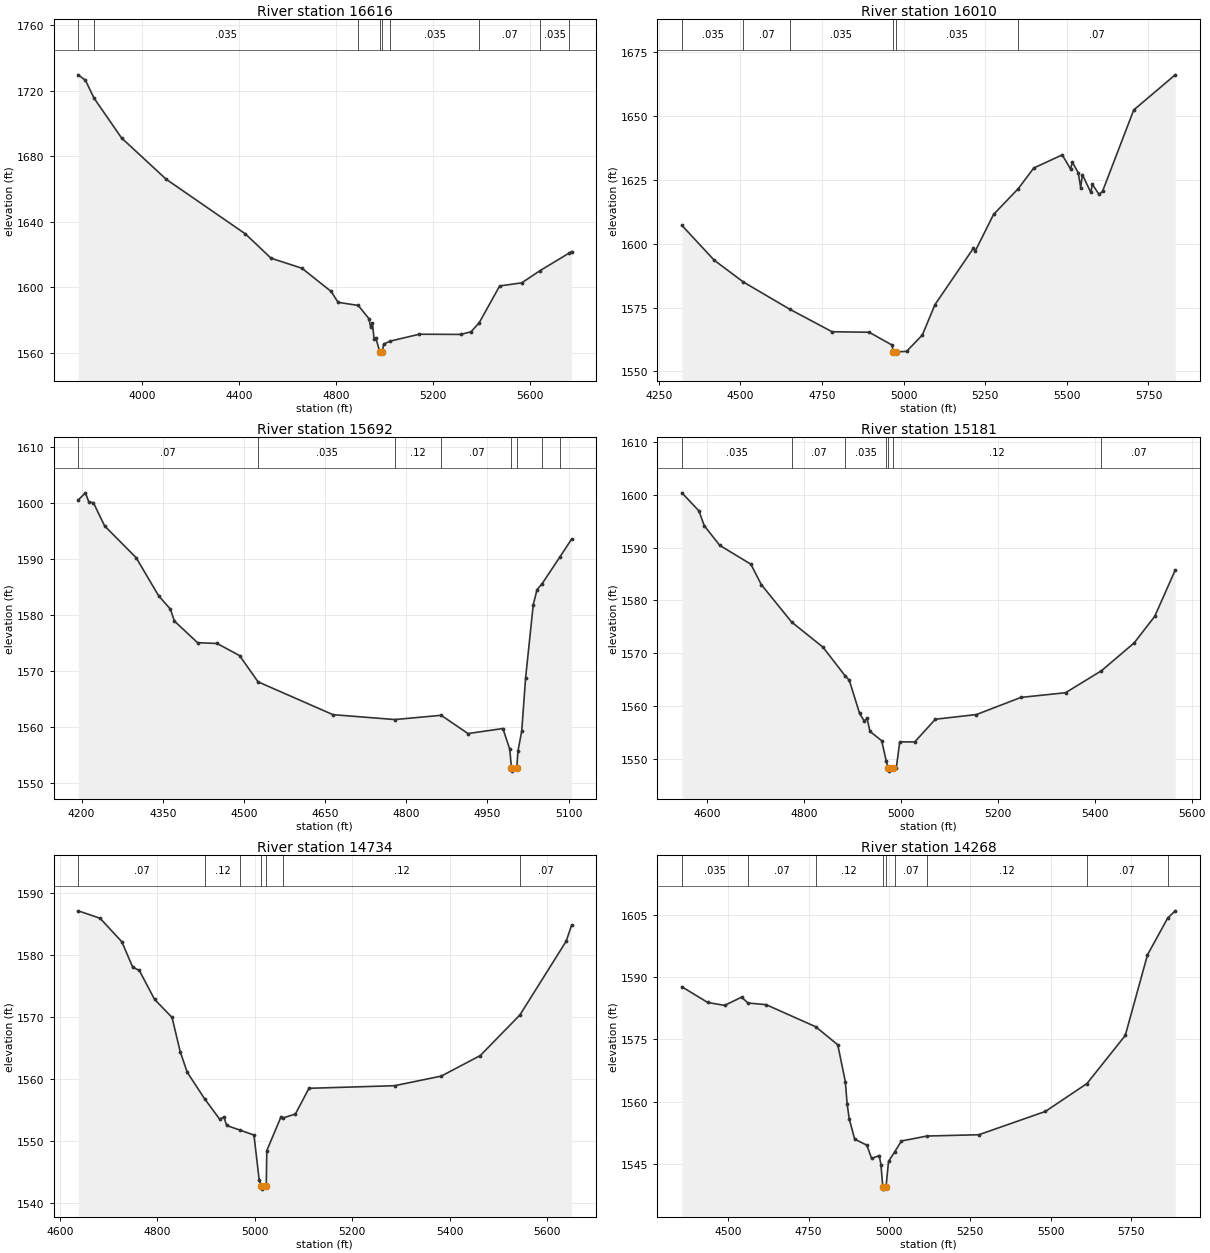
Type RM Length L Ch R = 1 ,16616   ,606,606,606
BEGIN DESCRIPTION:
JUNG CREEK 33.0
END DESCRIPTION:
XS GIS Cut Line= 3
      2044574.39     13941307.93        2043625.       13940475.
      2042890.32     13940238.47
#Sta/Elev= 30
    3737 1729.72  3766.8 1726.39  3802.2 1715.51  3915.8 1691.15  4099.9 1665.91
  4426.3 1632.55  4532.6 1617.64  4659.8 1611.54  4780.3 1597.32  4808.8 1590.71
  4892.2 1588.79  4935.9 1580.76  4943.5  1575.4  4950.2 1577.94  4957.7  1568.1
  4964.4 1569.08  4981.4 1560.15  4981.9 1559.65    4991 1560.15  4996.7 1565.13
  5023.9 1566.99  5144.3 1571.21  5315.2 1571.08  5357.2  1572.7  5390.7 1578.14
  5475.5 1600.71  5566.5  1602.6  5641.3 1609.99  5762.2 1620.82  5771.8 1621.65
#Mann= 9 ,-1 , 0
    3737     .07       0  3802.2    .035       0  4892.2     .07       0
  4981.4     .05       0    4991     .07       0  5023.9    .035       0
  5390.7     .07       0  5641.3    .035       0  5762.2     .07       0
Bank Sta=4981.4,4991
XS Rating Curve= 0 ,0
Exp/Cntr=0.3,0.1

Type RM Length L Ch R = 1 ,16010   ,318,318,318
BEGIN DESCRIPTION:
JUNG CREEK 32.0
END DESCRIPTION:
XS GIS Cut Line= 3
      2044024.99     13940424.99        2043575.       13939925.
      2042785.27     13939643.38
#Sta/Elev= 30
  4320.8 1607.21  4419.8 1593.55  4509.1 1585.02  4651.6 1574.32  4780.8 1565.53
  4894.4 1565.34  4965.4 1560.24  4967.3 1557.65  4967.8 1557.15    4977 1557.65
  5008.9 1557.83  5057.2 1564.22    5096 1576.16  5213.9 1598.29  5219.2 1597.11
  5275.5 1611.51  5351.2 1621.63  5398.8 1629.71  5485.9 1634.84  5511.4 1629.25
  5516.7 1631.99  5534.9 1627.82  5542.2 1622.03  5547.5 1627.14    5573  1620.2
  5578.3 1623.27  5598.5 1619.36  5609.2 1620.55  5704.8 1652.44  5831.9 1666.21
#Mann= 6 ,-1 , 0
  4320.8    .035       0  4509.1     .07       0  4651.6    .035       0
  4967.3    .035       0    4977    .035       0  5351.2     .07       0
Bank Sta=4967.3,4977
XS Rating Curve= 0 ,0
Exp/Cntr=0.3,0.1

Type RM Length L Ch R = 1 ,15692   ,511,511,511
BEGIN DESCRIPTION:
JUNG CREEK 31.0
END DESCRIPTION:
XS GIS Cut Line= 3
      2044088.25     13940290.55      2043602.14     13939651.67
      2043524.96     13939574.97
#Sta/Elev= 30
  4193.8 1600.48  4207.2 1601.75  4213.5  1600.1  4221.8    1600  4242.6 1595.85
  4300.8 1590.19  4342.4 1583.39  4364.1 1581.01  4371.5 1578.88  4414.4 1575.02
  4450.5 1574.88  4492.1 1572.71  4526.1 1568.04  4664.6 1562.18    4779 1561.31
  4864.6 1562.07  4914.1 1558.81  4978.6 1559.71  4991.4 1555.98  4994.4 1552.61
  4994.9 1552.11  5004.2 1552.61  5006.4 1555.68  5013.4 1559.26  5020.5 1568.68
  5034.7 1581.81  5041.7 1584.49  5050.6 1585.48  5083.6 1590.26  5105.4 1593.48
#Mann= 8 ,-1 , 0
  4193.8     .07       0  4526.1    .035       0    4779     .12       0
  4864.6     .07       0  4994.4     .05       0  5004.2     .07       0
  5050.6    .035       0  5083.6     .07       0
Bank Sta=4994.4,5004.2
XS Rating Curve= 0 ,0
Exp/Cntr=0.3,0.1

Type RM Length L Ch R = 1 ,15181   ,447,447,447
BEGIN DESCRIPTION:
JUNG CREEK 30.0
END DESCRIPTION:
XS GIS Cut Line= 3
      2044234.09     13940148.19        2044075.       13939725.
      2043674.99     13939324.99
#Sta/Elev= 30
  4548.3 1600.37  4583.4 1596.95  4594.4 1594.14  4626.5 1590.41  4690.6 1586.85
    4712    1583  4774.8 1575.88  4839.5 1571.12  4885.4 1565.66  4893.6 1564.89
  4914.9 1558.58  4924.8 1557.09  4930.2  1557.7  4936.3 1555.17  4960.4 1553.42
    4970 1549.53  4974.1 1548.15  4974.6 1547.65  4983.9 1548.15  4990.6 1548.23
  4997.7  1553.2  5028.7 1553.18  5071.1 1557.48    5156 1558.37  5247.9 1561.62
  5339.8  1562.5  5413.8 1566.66  5481.2 1571.92  5523.7 1576.95  5566.1 1585.73
#Mann= 7 ,-1 , 0
  4548.3    .035       0  4774.8     .07       0  4885.4    .035       0
    4970     .12       0  4974.1     .05       0  4983.9     .12       0
  5413.8     .07       0
Bank Sta=4974.1,4983.9
XS Rating Curve= 0 ,0
Exp/Cntr=0.3,0.1

Type RM Length L Ch R = 1 ,14734   ,466,466,466
BEGIN DESCRIPTION:
JUNG CREEK 29.0
END DESCRIPTION:
XS GIS Cut Line= 3
      2044595.22     13939634.32        2044275.       13939475.
      2043709.87     13939144.77
#Sta/Elev= 30
  4637.9 1587.15  4682.8 1585.95  4727.5 1582.15  4749.8 1578.04  4763.2 1577.54
  4794.5 1572.87  4830.4 1569.95  4847.2 1564.43  4861.5 1561.11  4897.1 1556.84
  4928.5 1553.49  4936.8 1553.91  4942.4 1552.51  4970.8 1551.74  4998.5 1550.96
  5009.2 1543.76  5013.8 1542.74  5014.3 1542.24  5023.7 1542.74  5024.9 1548.46
  5053.5 1553.81    5059 1553.74  5083.6 1554.37  5111.4 1558.51  5286.9 1558.93
  5382.8 1560.48    5463  1563.8  5544.2 1570.35  5639.1 1582.24  5650.1  1584.8
#Mann= 7 ,-1 , 0
  4637.9     .07       0  4897.1     .12       0  4970.8     .07       0
  5013.8     .05       0  5023.7     .07       0    5059     .12       0
  5544.2     .07       0
Bank Sta=5013.8,5023.7
XS Rating Curve= 0 ,0
Exp/Cntr=0.3,0.1

Type RM Length L Ch R = 1 ,14268   ,459,459,459
BEGIN DESCRIPTION:
JUNG CREEK 28.0
END DESCRIPTION:
XS GIS Cut Line= 3
       2044782.7     13939721.12        2044525.       13939125.
       2043671.6     13938912.09
#Sta/Elev= 30
  4357.1 1587.67  4437.1 1583.89  4489.5 1583.19  4541.9 1585.17    4562 1583.76
  4617.9 1583.37  4772.1 1578.04  4840.2  1573.7  4863.7 1564.82  4869.1 1559.52
  4875.8 1555.86  4892.6    1551  4930.3 1549.55  4945.1 1546.35  4968.6 1547.05
    4974 1544.89  4979.8 1539.47  4980.3 1538.97  4989.7 1539.47  4997.5 1545.64
  5016.8 1547.96  5037.5 1550.56  5116.9 1551.75  5277.4 1552.06  5483.7 1557.67
  5612.5 1564.38  5731.3 1575.96  5800.1 1595.35  5862.6 1604.19  5886.1 1605.95
#Mann= 9 ,-1 , 0
  4357.1    .035       0    4562     .07       0  4772.1     .12       0
  4979.8     .05       0  4989.7     .12       0  5016.8     .07       0
  5116.9     .12       0  5612.5     .07       0  5862.6    .035       0
Bank Sta=4979.8,4989.7
XS Rating Curve= 0 ,0
Exp/Cntr=0.3,0.1

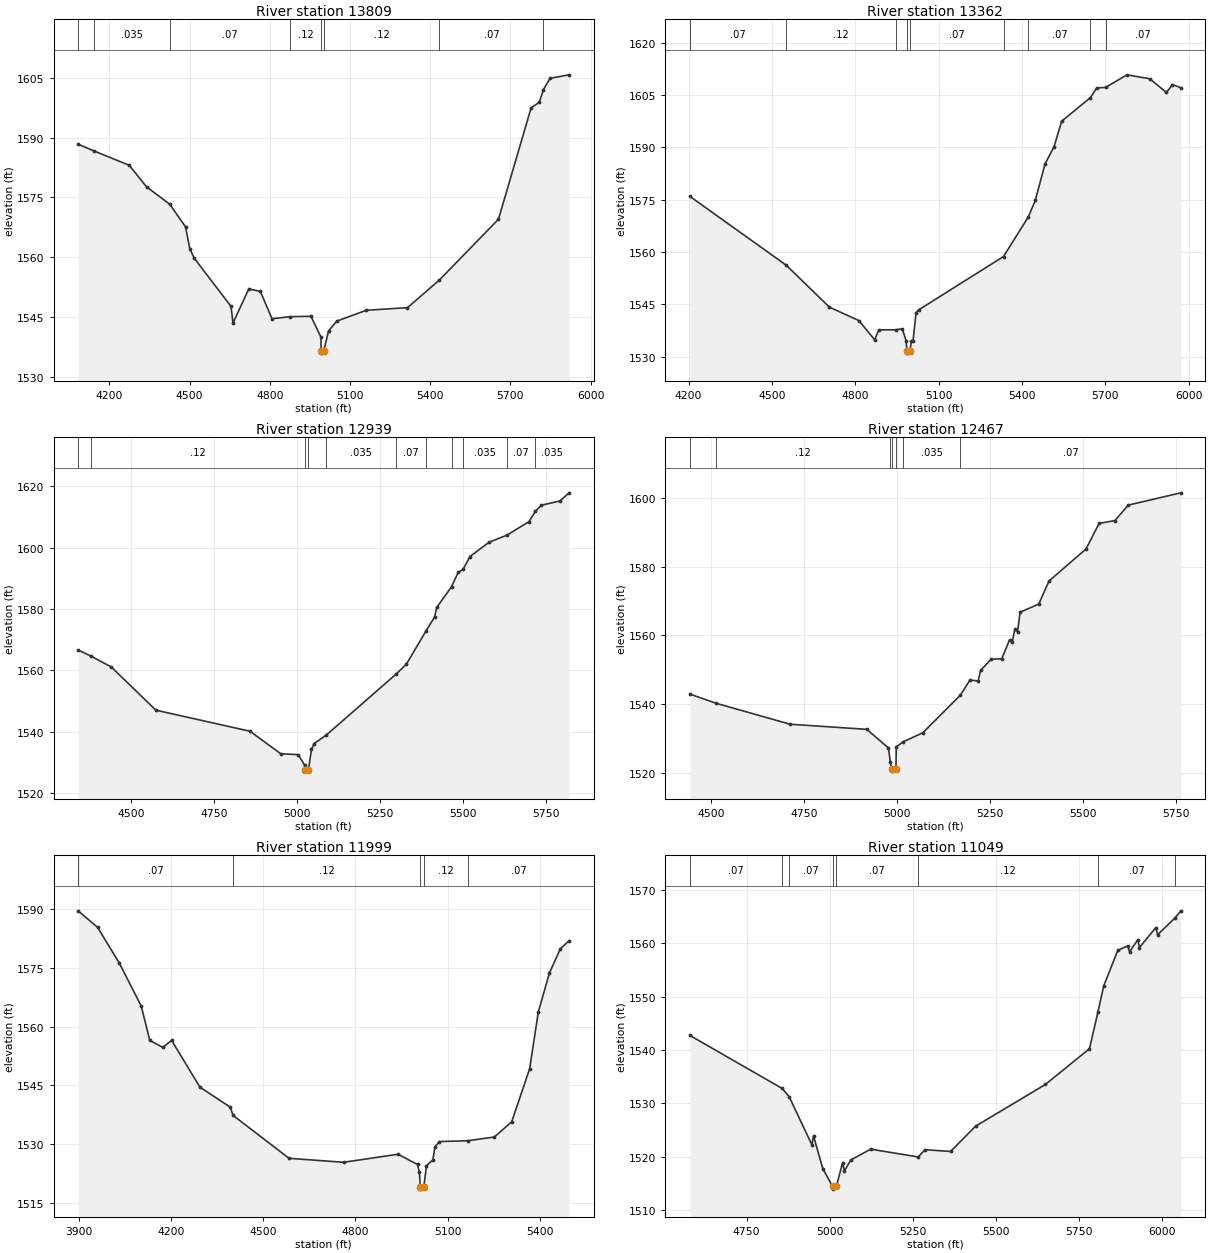
Type RM Length L Ch R = 1 ,13809   ,447,447,447
BEGIN DESCRIPTION:
JUNG CREEK 27.0
END DESCRIPTION:
XS GIS Cut Line= 3
      2045372.97     13939175.97        2044575.       13938725.
      2043664.65     13938592.64
#Sta/Elev= 30
    4083 1588.38  4143.9 1586.64  4274.1 1583.09  4339.1 1577.67  4425.7 1573.31
  4484.9 1567.62  4500.8 1562.14  4516.7 1559.82    4655 1547.65  4662.5 1543.48
  4721.7 1552.05    4765 1551.39  4808.3 1544.54  4875.1 1545.06  4954.1 1545.16
  4991.6 1539.92  4991.7 1536.41  4992.2 1535.91  5001.7 1536.41  5019.8 1541.47
  5050.1 1543.93  5161.3 1546.67  5315.1 1547.33  5434.9 1554.29  5655.6 1569.55
  5777.7 1597.53    5808 1598.89  5823.8  1602.1  5848.4 1604.92  5919.5  1605.8
#Mann= 8 ,-1 , 0
    4083     .07       0  4143.9    .035       0  4425.7     .07       0
  4875.1     .12       0  4991.7     .05       0  5001.7     .12       0
  5434.9     .07       0  5823.8     .12       0
Bank Sta=4991.7,5001.7
XS Rating Curve= 0 ,0
Exp/Cntr=0.3,0.1

Type RM Length L Ch R = 1 ,13362   ,423,423,423
BEGIN DESCRIPTION:
JUNG CREEK 26.0
END DESCRIPTION:
XS GIS Cut Line= 3
      2045442.41      13938884.3        2044825.       13938375.
      2043973.63     13937915.54
#Sta/Elev= 30
  4204.7 1575.95  4551.6 1556.21  4706.9 1544.18  4812.9 1540.34  4870.2 1534.79
  4884.6 1537.68  4945.6 1537.67  4969.2    1538  4983.6 1534.46  4985.9 1531.49
  4986.4 1530.99  4996.9 1531.49  5001.8 1534.38  5007.9 1534.38  5018.9 1542.56
  5027.8 1543.37    5334 1558.71  5423.5  1570.1  5448.2 1574.78  5483.4 1585.27
  5515.8 1590.22  5543.4 1597.53  5647.1 1604.31  5669.1 1607.06  5701.5 1607.22
  5778.5 1610.83  5860.4  1609.7  5920.4 1605.76  5942.3 1608.03  5972.5 1607.13
#Mann= 9 ,-1 , 0
  4204.7     .07       0  4551.6     .12       0  4945.6     .07       0
  4985.9     .05       0  4996.9     .07       0    5334    .035       0
  5423.5     .07       0  5647.1    .035       0  5701.5     .07       0
Bank Sta=4985.9,4996.9
XS Rating Curve= 0 ,0
Exp/Cntr=0.3,0.1

Type RM Length L Ch R = 1 ,12939   ,472,472,472
BEGIN DESCRIPTION:
JUNG CREEK 25.0
END DESCRIPTION:
XS GIS Cut Line= 3
        2045498.     13938582.25        2045075.       13938075.
      2044429.24     13937572.36
#Sta/Elev= 30
  4339.5 1566.66    4378 1564.67  4439.6 1561.12  4573.7 1547.05  4857.4 1540.18
  4949.9 1532.85  5003.1 1532.55  5021.7  1529.1  5022.5 1527.69    5023 1527.19
  5033.5 1527.69  5042.5  1534.3  5050.6 1536.17  5086.6  1538.9  5297.6 1558.81
  5328.4 1562.04  5387.5 1572.86  5413.5 1577.42  5419.8  1580.5  5464.3 1587.25
  5484.1  1591.9  5499.4 1592.92  5519.5 1597.08  5577.2 1601.73  5631.6 1604.09
  5697.6 1608.47    5717 1611.83  5734.7 1613.81  5790.8 1615.19  5818.3 1617.85
#Mann= 11 ,-1 , 0
  4339.5     .07       0    4378     .12       0  5022.5     .05       0
  5033.5     .12       0  5086.6    .035       0  5297.6     .07       0
  5387.5    .035       0  5464.3     .07       0  5499.4    .035       0
  5631.6     .07       0    5717    .035       0
Bank Sta=5022.5,5033.5
XS Rating Curve= 0 ,0
Exp/Cntr=0.3,0.1

Type RM Length L Ch R = 1 ,12467   ,468,468,468
BEGIN DESCRIPTION:
JUNG CREEK 24.0
END DESCRIPTION:
XS GIS Cut Line= 3
      2045612.57      13938123.9        2045275.       13937675.
      2044769.44      13937110.7
#Sta/Elev= 30
  4443.8 1542.96  4514.2 1540.29  4712.9 1534.21    4919 1532.72  4977.3 1527.32
  4982.3 1523.19  4986.4 1521.09  4986.9 1520.59  4997.5 1521.09  4998.2 1527.63
  5016.7 1529.08  5069.4 1531.71  5170.2 1542.61  5196.5 1547.06  5218.2 1546.76
  5224.9 1549.82  5253.3 1553.11  5281.7 1553.18  5302.6 1558.69  5310.1 1558.13
  5316.8 1561.72  5324.3 1561.07    5331 1566.73  5381.1 1569.08  5408.8  1575.8
  5508.2 1585.09  5543.3 1592.51    5586 1593.36  5621.9 1597.84  5763.1  1601.4
#Mann= 7 ,-1 , 0
  4443.8     .07       0  4514.2     .12       0  4982.3     .07       0
  4986.4     .05       0  4997.5     .07       0  5016.7    .035       0
  5170.2     .07       0
Bank Sta=4986.4,4997.5
XS Rating Curve= 0 ,0
Exp/Cntr=0.3,0.1

Type RM Length L Ch R = 1 ,11999   ,950,950,950
BEGIN DESCRIPTION:
JUNG CREEK 23.0
END DESCRIPTION:
XS GIS Cut Line= 3
        2046325.       13938075.        2045525.       13937325.
      2045124.99     13937024.99
#Sta/Elev= 30
  3897.9 1589.56  3961.6 1585.32  4032.5 1576.14  4103.3 1565.25  4131.2 1556.47
  4173.6  1554.7    4202  1556.5  4294.3 1544.54    4393 1539.44  4402.1 1537.33
    4584  1526.4  4761.2 1525.38  4938.1 1527.43  5001.8 1524.83    5008  1522.8
  5010.8 1519.03  5011.3 1518.53    5022 1519.03  5030.9  1524.5  5051.8 1526.02
    5058 1529.21  5072.6 1530.67  5165.8 1530.88  5251.8 1531.84    5308 1535.72
  5366.4 1549.25  5394.5 1563.71  5430.9 1573.72  5466.4  1579.9  5494.5 1581.94
#Mann= 5 ,-1 , 0
  3897.9     .07       0  4402.1     .12       0  5010.8     .05       0
    5022     .12       0  5165.8     .07       0
Bank Sta=5010.8,5022
XS Rating Curve= 0 ,0
Exp/Cntr=0.3,0.1

Type RM Length L Ch R = 1 ,11049   ,864,864,864
BEGIN DESCRIPTION:
JUNG CREEK 22.0
END DESCRIPTION:
XS GIS Cut Line= 3
      2046543.15     13937266.25        2046125.       13937225.
      2045138.46     13936843.26
#Sta/Elev= 30
  4579.6 1542.75  4857.4 1532.81  4878.2 1531.29  4946.7 1522.26  4951.7 1523.91
  4979.7 1517.77    5009 1514.44  5009.5 1513.94  5020.4 1514.44  5039.3 1518.91
  5044.7 1517.37  5063.9  1519.4  5123.8 1521.43    5267 1519.97  5287.3 1521.33
  5364.3    1521  5439.4 1525.73  5649.7 1533.56  5782.5 1540.27  5807.9 1547.13
  5825.4 1552.04  5867.8 1558.71  5897.7 1559.55  5903.1 1558.42  5927.7 1560.66
    5933 1559.23  5982.2 1562.97  5987.6 1561.63  6039.3 1564.74  6057.6 1566.11
#Mann= 8 ,-1 , 0
  4579.6     .07       0  4857.4     .12       0  4878.2     .07       0
    5009     .05       0  5020.4     .07       0    5267     .12       0
  5807.9     .07       0  6039.3     .12       0
Bank Sta=5009,5020.4
XS Rating Curve= 0 ,0
Exp/Cntr=0.3,0.1

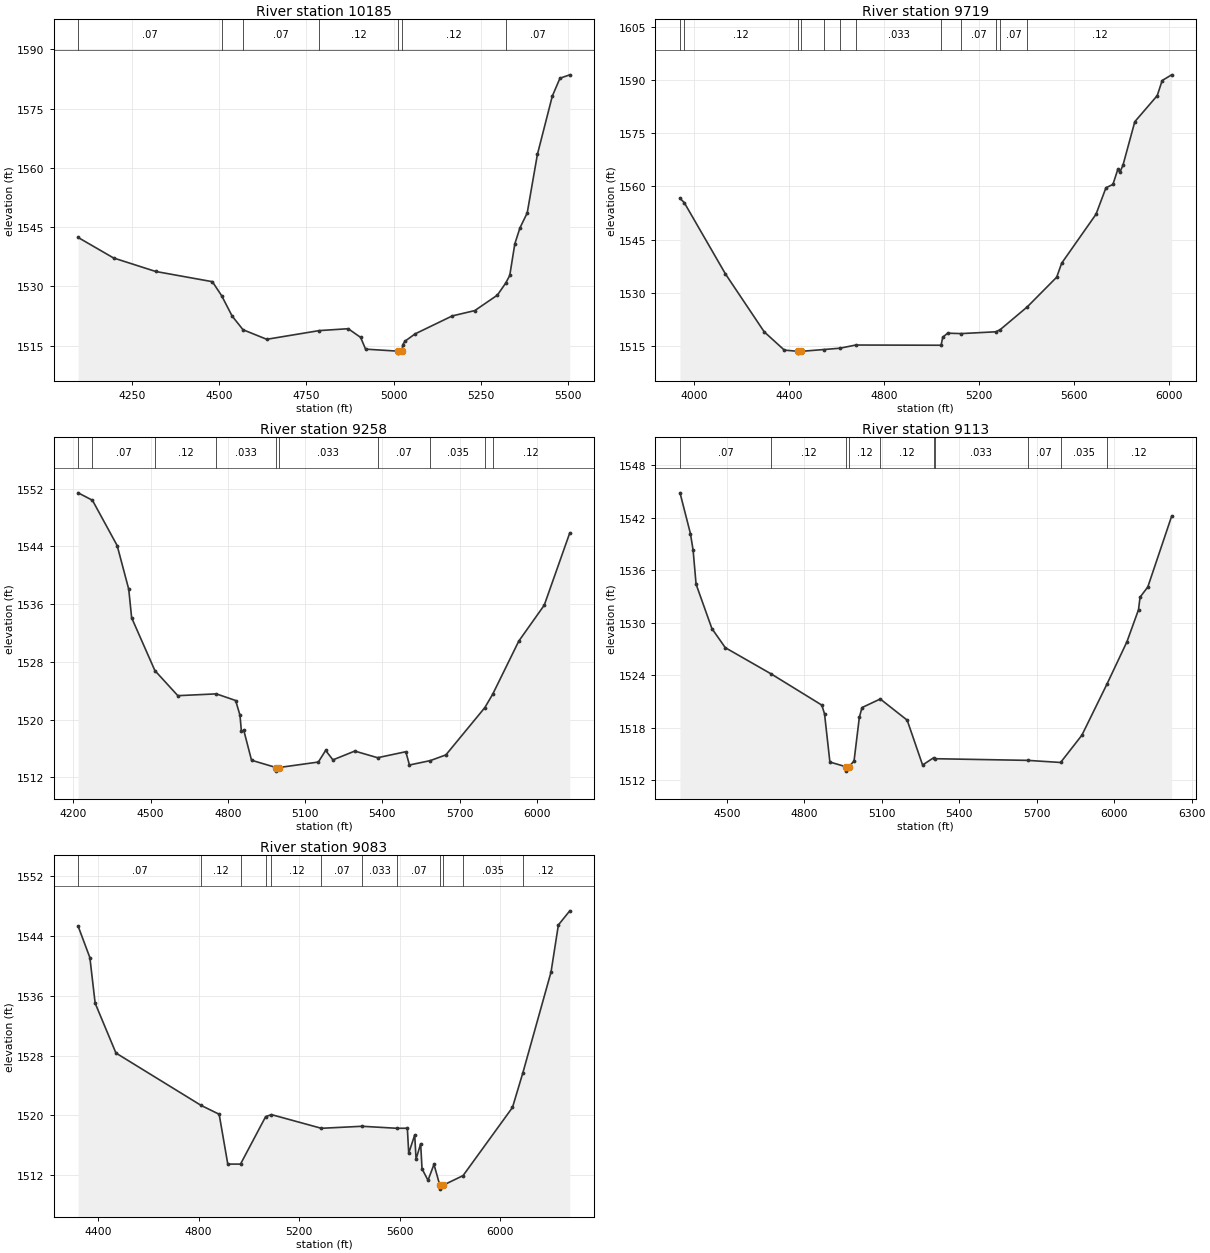
Type RM Length L Ch R = 1 ,10185   ,466,466,466
BEGIN DESCRIPTION:
JUNG CREEK 21.0
END DESCRIPTION:
XS GIS Cut Line= 3
      2046605.61     13937228.05        2045975.       13936575.
      2045575.02     13936275.01
#Sta/Elev= 30
  4096.8 1542.38  4198.3 1537.19  4318.7 1533.78  4481.2 1531.19  4507.7 1527.65
  4537.8 1522.49    4569 1519.03  4636.9 1516.61    4787 1518.81  4870.2 1519.29
  4905.7 1517.09  4919.9 1514.12  5012.4 1513.61  5012.9 1513.11  5023.9 1513.61
  5026.5 1515.26  5032.7 1516.13  5061.9 1517.99  5168.2 1522.53  5232.7 1523.88
  5297.3 1527.79  5320.7 1530.78  5332.7 1532.76  5347.3 1540.79  5361.9  1544.8
  5382.7 1548.58  5411.9  1563.4  5454.6 1578.16  5476.5 1582.68  5504.6 1583.54
#Mann= 7 ,-1 , 0
  4096.8     .07       0  4507.7     .12       0    4569     .07       0
    4787     .12       0  5012.4     .05       0  5023.9     .12       0
  5320.7     .07       0
Bank Sta=5012.4,5023.9
XS Rating Curve= 0 ,0
Exp/Cntr=0.3,0.1

Type RM Length L Ch R = 1 ,9719    ,461,461,461
BEGIN DESCRIPTION:
JUNG CREEK 20.0
END DESCRIPTION:
XS GIS Cut Line= 3
      2047025.01     13937125.01        2046325.       13936325.
      2045509.18     13935735.57
#Sta/Elev= 30
  3941.6 1556.63  3959.3 1555.45  4132.9 1535.27  4296.1  1518.9  4380.6 1513.74
  4439.4 1513.38  4439.9 1512.88  4450.9 1513.38  4547.4  1513.9  4614.7 1514.27
  4681.7 1515.17  5040.6 1515.11  5047.6 1517.38  5068.4 1518.52  5124.9  1518.4
  5270.4 1518.91  5288.7 1519.48  5403.6 1525.97  5527.2 1534.35  5548.1  1538.3
  5692.8 1552.15  5734.5 1559.62  5763.9 1560.57  5784.8 1564.89  5793.3 1563.98
  5806.5 1566.08    5856  1578.3  5950.4 1585.67  5971.2 1589.94  6011.1 1591.55
#Mann= 12 ,-1 , 0
  3941.6    .035       0  3959.3     .12       0  4439.4    .033       0
  4450.9     .12       0  4547.4    .033       0  4614.7     .07       0
  4681.7    .033       0  5040.6     .12       0  5124.9     .07       0
  5270.4    .035       0  5288.7     .07       0  5403.6     .12       0
Bank Sta=4439.4,4450.9
XS Rating Curve= 0 ,0
Exp/Cntr=0.3,0.1

Type RM Length L Ch R = 1 ,9258    ,145,145,145
BEGIN DESCRIPTION:
JUNG CREEK 19.0
END DESCRIPTION:
XS GIS Cut Line= 3
      2047119.52     13936971.15        2046775.       13936275.
      2045975.01     13935475.01
#Sta/Elev= 30
    4219 1551.43  4274.5  1550.4  4370.5 1544.12  4415.4 1538.07  4426.7 1534.11
  4516.9 1526.79    4606 1523.31  4755.5 1523.56  4830.3 1522.64  4847.2 1520.59
  4852.7 1518.36  4861.8 1518.52    4892 1514.36  4987.1 1513.35  4987.6 1512.85
  4998.7 1513.35  5151.3 1514.11  5179.6 1515.72  5207.9 1514.41  5292.7 1515.63
  5381.3 1514.71  5490.7 1515.54  5504.9  1513.7  5585.9 1514.31  5646.3  1515.1
  5797.5 1521.66  5827.9 1523.51  5929.1 1530.87  6028.1 1535.86  6127.1 1545.88
#Mann= 10 ,-1 , 0
    4219     .12       0  4274.5     .07       0  4516.9     .12       0
  4755.5    .033       0  4987.1    .033       0  4998.7    .033       0
  5381.3     .07       0  5585.9    .035       0  5797.5     .07       0
  5827.9     .12       0
Bank Sta=4987.1,4998.7
XS Rating Curve= 0 ,0
Exp/Cntr=0.3,0.1

Type RM Length L Ch R = 1 ,9113    ,30,30,30
BEGIN DESCRIPTION:
JUNG CREEK 18.2
END DESCRIPTION:
XS GIS Cut Line= 6
      2047065.77     13936833.87      2046881.09     13936177.56
      2046815.08     13935903.33      2046727.24     13935771.15
      2046225.06     13935624.96      2046010.72     13935480.09
#Sta/Elev= 30
  4318.2 1544.87  4358.6 1540.21    4369 1538.31  4380.5 1534.42  4441.7 1529.35
  4493.6 1527.16  4671.8 1524.15  4867.6 1520.59    4878 1519.59  4898.8 1514.08
  4960.9 1513.54  4961.4 1513.04  4972.5 1513.54  4992.3  1514.2  5012.9  1519.2
  5023.2 1520.31  5093.9 1521.29  5198.1 1518.87  5257.8 1513.74  5300.6 1514.57
  5305.9 1514.46  5665.4 1514.27  5792.4 1514.03  5874.8 1517.15  5971.7 1522.98
  6049.2 1527.83  6094.1  1531.5  6100.2 1532.94  6130.1  1534.1  6222.5  1542.2
#Mann= 10 ,-1 , 0
  4318.2     .07       0  4671.8     .12       0  4960.9    .033       0
  4972.5     .12       0  5093.9     .12       0  5300.6     .07       0
  5305.9    .033       0  5665.4     .07       0  5792.4    .035       0
  5971.7     .12       0
Bank Sta=4960.9,4972.5
XS Rating Curve= 0 ,0
Exp/Cntr=0.3,0.1

Type RM Length L Ch R = 1 ,9083    ,297,297,297
BEGIN DESCRIPTION:
JUNG CREEK 18.1
END DESCRIPTION:
XS GIS Cut Line= 6
      2047083.11     13936830.46      2046885.37     13936078.77
      2046868.87      13935894.9      2046855.45     13935794.27
        2046776.     13935726.29      2046050.88     13935421.31
#Sta/Elev= 30
  4321.3 1545.32    4368 1541.11    4389 1535.01  4471.7 1528.34  4809.9 1521.34
    4882 1520.15  4916.3 1513.48  4966.9 1513.48    5067 1519.84  5089.9  1520.1
  5288.3 1518.27  5449.8 1518.54  5589.5 1518.27  5630.2 1518.28  5635.6 1514.94
  5659.4 1517.37  5664.8 1514.15  5683.1 1516.21  5688.5 1512.85  5712.3 1511.31
    5736 1513.44  5759.4 1510.63  5759.9 1510.13    5771 1510.63  5851.7 1511.94
  6048.1 1521.06  6089.7 1525.73  6201.4 1539.18  6230.6 1545.48  6275.9 1547.37
#Mann= 12 ,-1 , 0
  4321.3     .07       0  4809.9     .12       0  4966.9     .07       0
    5067    .033       0  5089.9     .12       0  5288.3     .07       0
  5449.8    .033       0  5589.5     .07       0  5759.4     .05       0
    5771     .07       0  5851.7    .035       0  6089.7     .12       0
Bank Sta=5759.4,5771
XS Rating Curve= 0 ,0
Exp/Cntr=0.3,0.1