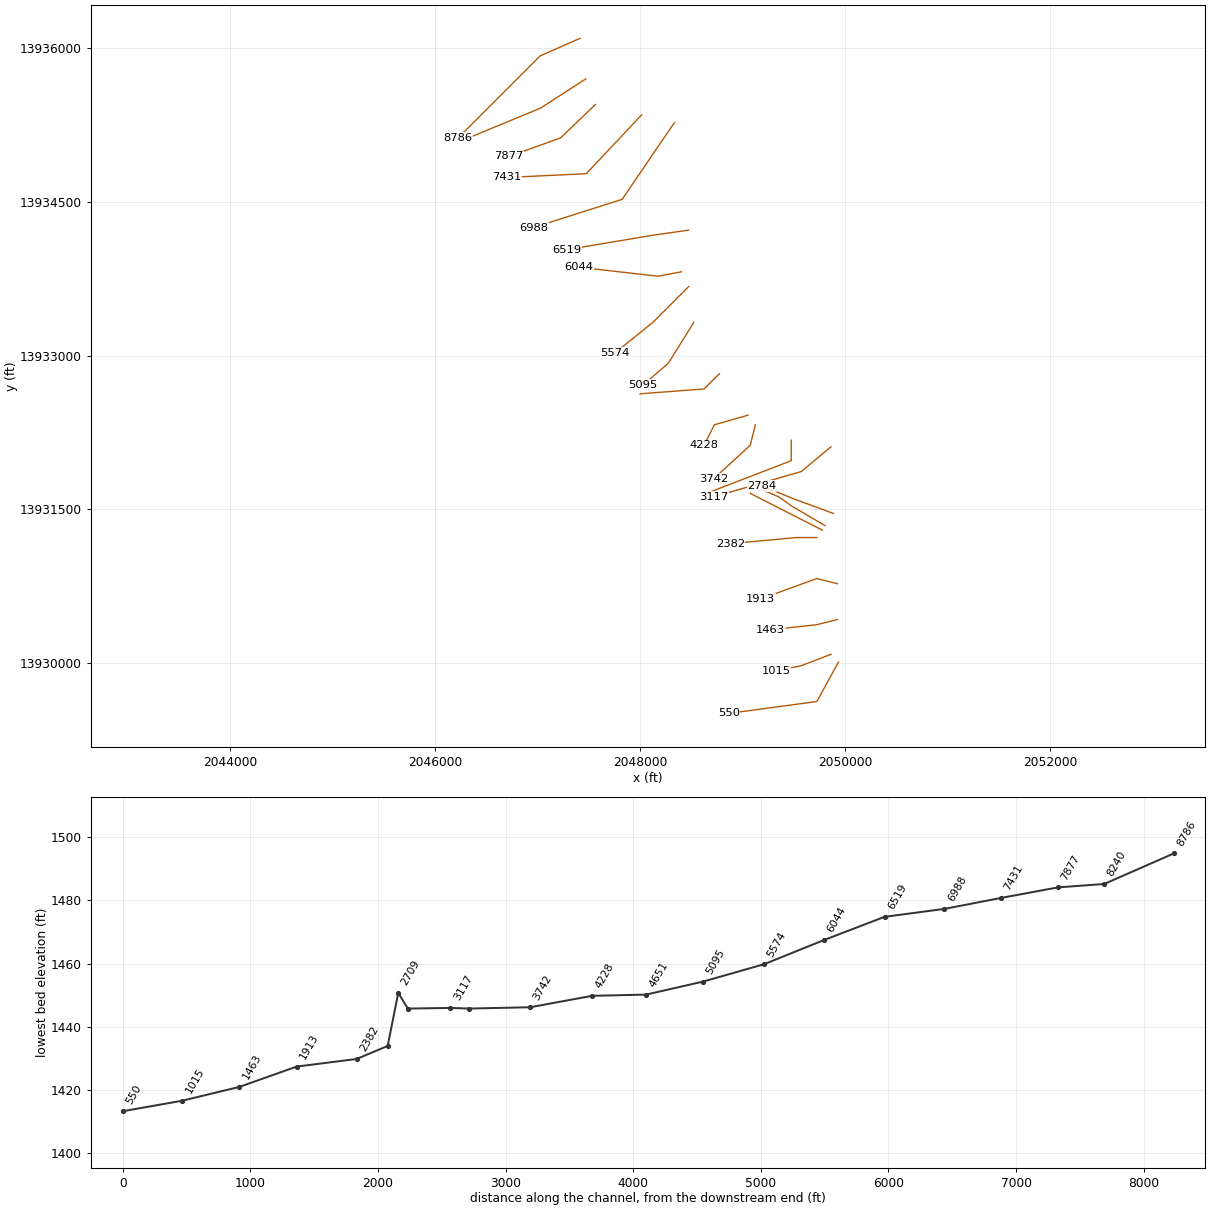
HEC-RAS study JUNG CREEK.prj: JUNG CREEK Base Level Engineering

--- JUNG CREEK.g01 (geometry) --- (continued)

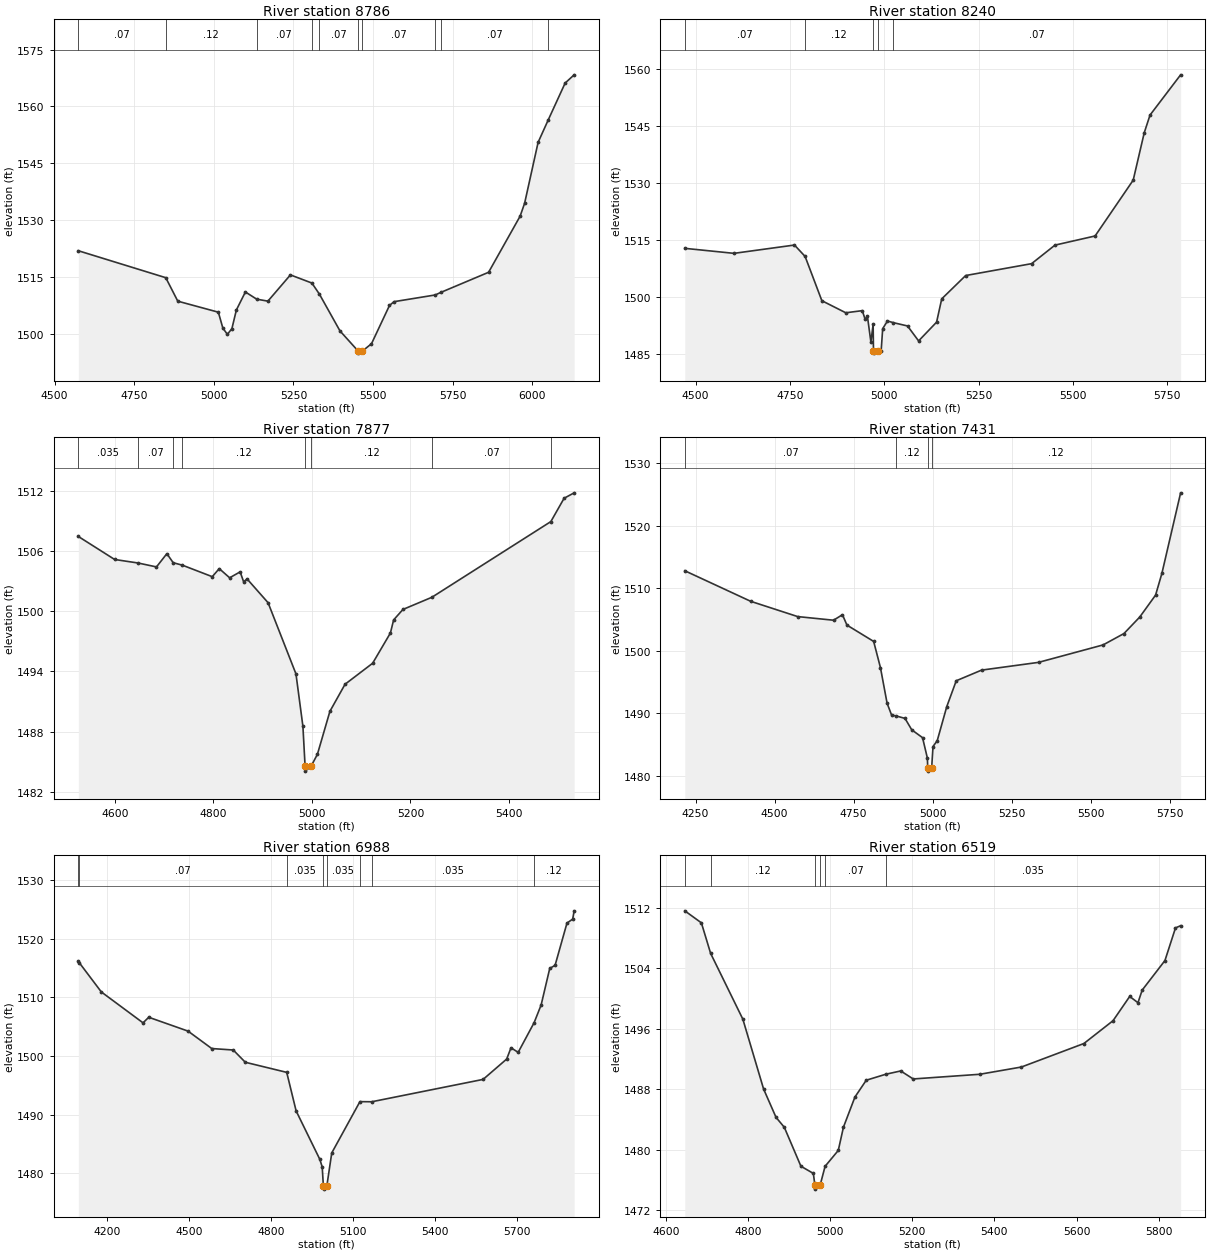
Type RM Length L Ch R = 1 ,8786    ,546,546,546
BEGIN DESCRIPTION:
JUNG CREEK 18.0
END DESCRIPTION:
XS GIS Cut Line= 3
      2047414.68     13936096.13        2047025.       13935925.
      2046224.98     13935124.98
#Sta/Elev= 30
  4574.4 1521.88    4849 1514.76  4886.7 1508.56  5014.1 1505.65  5028.3 1501.43
  5042.4 1499.81  5056.6 1501.29  5070.7 1506.24    5099 1510.99  5134.5 1509.09
  5169.7 1508.57  5240.4  1515.5  5307.8 1513.35  5331.3 1510.44    5396 1500.71
  5453.6 1495.34  5454.1 1494.84  5465.7 1495.34    5495 1497.32  5551.5 1507.43
  5565.7 1508.43  5695.1  1510.2  5712.5 1510.87  5862.7 1516.19  5961.7 1531.01
  5975.8 1534.41  6018.2 1550.51    6050 1556.43  6103.1 1566.17  6131.4 1568.34
#Mann= 10 ,-1 , 0
  4574.4     .07       0    4849     .12       0  5134.5     .07       0
  5307.8    .033       0  5331.3     .07       0  5453.6     .05       0
  5465.7     .07       0  5695.1    .035       0  5712.5     .07       0
    6050     .12       0
Bank Sta=5453.6,5465.7
XS Rating Curve= 0 ,0
Exp/Cntr=0.3,0.1

Type RM Length L Ch R = 1 ,8240    ,363,363,363
BEGIN DESCRIPTION:
JUNG CREEK 17.0
END DESCRIPTION:
XS GIS Cut Line= 3
      2047470.21     13935700.29      2047029.23     13935415.56
      2046300.05     13935113.47
#Sta/Elev= 30
  4471.3  1512.8  4601.7 1511.48    4762 1513.67  4790.2 1510.66  4834.6 1498.99
    4898 1495.81  4941.7 1496.37  4949.4 1494.06  4955.4 1494.84  4964.6 1488.09
  4970.5 1492.78  4971.4 1485.67  4971.9 1485.17  4983.5 1485.67  4991.7 1485.69
  4995.8 1491.62  5008.5 1493.64  5024.3  1493.2  5061.7 1492.33    5091 1488.39
  5138.7 1493.34  5152.3 1499.48  5215.8 1505.63  5390.5 1508.76  5452.5 1513.65
  5558.8 1516.06  5659.8 1530.78  5689.1 1543.29  5704.4 1547.94  5785.5 1558.55
#Mann= 5 ,-1 , 0
  4471.3     .07       0  4790.2     .12       0  4971.4     .05       0
  4983.5     .12       0  5024.3     .07       0
Bank Sta=4971.4,4983.5
XS Rating Curve= 0 ,0
Exp/Cntr=0.3,0.1

Type RM Length L Ch R = 1 ,7877    ,446,446,446
BEGIN DESCRIPTION:
JUNG CREEK 16.0
END DESCRIPTION:
XS GIS Cut Line= 3
      2047563.97      13935450.3        2047225.       13935125.
      2046720.21     13934943.34
#Sta/Elev= 30
  4525.9 1507.43  4599.6 1505.14  4647.2 1504.79  4684.5  1504.4  4705.6 1505.72
  4718.4 1504.82  4737.3 1504.57  4797.7 1503.43  4811.9 1504.23    4833 1503.32
  4854.3 1503.91  4861.3 1502.93  4868.5  1503.2    4911 1500.84  4967.6 1493.76
  4981.7 1488.54  4986.1 1484.59  4986.6 1484.09  4998.4 1484.59  5011.1 1485.76
  5036.5 1490.04  5067.2 1492.73  5123.2 1494.82  5159.3 1497.83  5165.8 1499.13
  5184.7 1500.17  5243.4 1501.38  5484.9 1508.91  5511.8 1511.23  5532.2 1511.77
#Mann= 8 ,-1 , 0
  4525.9    .035       0  4647.2     .07       0  4718.4    .035       0
  4737.3     .12       0  4986.1     .05       0  4998.4     .12       0
  5243.4     .07       0  5484.9     .12       0
Bank Sta=4986.1,4998.4
XS Rating Curve= 0 ,0
Exp/Cntr=0.3,0.1

Type RM Length L Ch R = 1 ,7431    ,443,443,443
BEGIN DESCRIPTION:
JUNG CREEK 15.0
END DESCRIPTION:
XS GIS Cut Line= 3
      2048015.33     13935349.58        2047475.       13934775.
      2046695.88     13934738.47
#Sta/Elev= 30
    4216 1512.79  4424.7  1507.9  4573.2 1505.46  4686.5 1504.88  4714.8 1505.76
    4729  1504.1  4813.5 1501.49    4835  1497.3    4856 1491.61  4870.2 1489.72
  4885.1 1489.57  4912.7 1489.18  4934.1 1487.35  4968.2  1486.1  4983.5 1482.83
  4984.6 1481.25  4985.1 1480.75    4997 1481.25  5001.3 1484.68  5014.7 1485.63
  5044.8 1491.06  5074.8  1495.2  5154.9  1496.9  5335.1 1498.14  5539.4 1500.93
  5605.4 1502.75  5655.4 1505.39  5705.5  1508.9  5725.5 1512.38  5784.7 1525.25
#Mann= 4 ,-1 , 0
    4216     .07       0  4885.1     .12       0  4984.6     .05       0
    4997     .12       0
Bank Sta=4984.6,4997
XS Rating Curve= 0 ,0
Exp/Cntr=0.3,0.1

Type RM Length L Ch R = 1 ,6988    ,469,469,469
BEGIN DESCRIPTION:
JUNG CREEK 14.0
END DESCRIPTION:
XS GIS Cut Line= 3
      2048334.78     13935273.18        2047825.       13934525.
      2046959.89     13934250.03
#Sta/Elev= 30
  4094.9 1516.13  4098.2 1515.89  4178.9  1510.9  4331.5 1505.63  4352.4 1506.58
  4496.1 1504.22  4582.8 1501.25  4661.4    1501  4705.5 1498.91  4856.9 1497.19
  4891.3 1490.62  4977.8 1482.38  4986.7 1481.08    4991 1477.79  4991.5 1477.29
  5003.5 1477.79  5021.6 1483.46  5124.6  1492.2  5167.9 1492.18    5575 1495.99
  5661.3 1499.46    5677 1501.38  5703.3  1500.6  5761.7 1505.67  5787.2 1508.67
  5818.7  1514.9  5838.3 1515.44  5881.7 1522.63  5902.6 1523.31    5908 1524.72
#Mann= 8 ,-1 , 0
  4094.9     .12       0  4098.2     .07       0  4856.9    .035       0
    4991    .035       0  5003.5    .035       0  5124.6     .12       0
  5167.9    .035       0  5761.7     .12       0
Bank Sta=4991,5003.5
XS Rating Curve= 0 ,0
Exp/Cntr=0.3,0.1

Type RM Length L Ch R = 1 ,6519    ,475,475,475
BEGIN DESCRIPTION:
JUNG CREEK 13.0
END DESCRIPTION:
XS GIS Cut Line= 3
      2048474.96     13934224.99        2048125.       13934175.
       2047282.7     13934033.61
#Sta/Elev= 30
    4646 1511.61  4686.4 1510.02  4708.9 1505.98  4787.4 1497.27  4837.9 1488.03
  4868.2 1484.28  4888.4 1482.96  4928.8 1477.81  4959.1 1476.86  4962.9 1475.28
  4963.4 1474.78  4975.5 1475.28  4987.7  1477.8  5019.8  1479.9  5032.4 1482.98
  5060.4 1486.97  5087.9 1489.19  5135.3 1489.98  5171.9 1490.42  5202.3 1489.36
  5364.6 1489.98  5465.9 1490.94    5618 1494.05    5689 1497.07  5729.6 1500.28
  5749.7 1499.45    5760 1501.12  5815.4 1505.03  5841.1 1509.35  5853.6 1509.64
#Mann= 6 ,-1 , 0
    4646     .07       0  4708.9     .12       0  4962.9     .05       0
  4975.5     .12       0  4987.7     .07       0  5135.3    .035       0
Bank Sta=4962.9,4975.5
XS Rating Curve= 0 ,0
Exp/Cntr=0.3,0.1

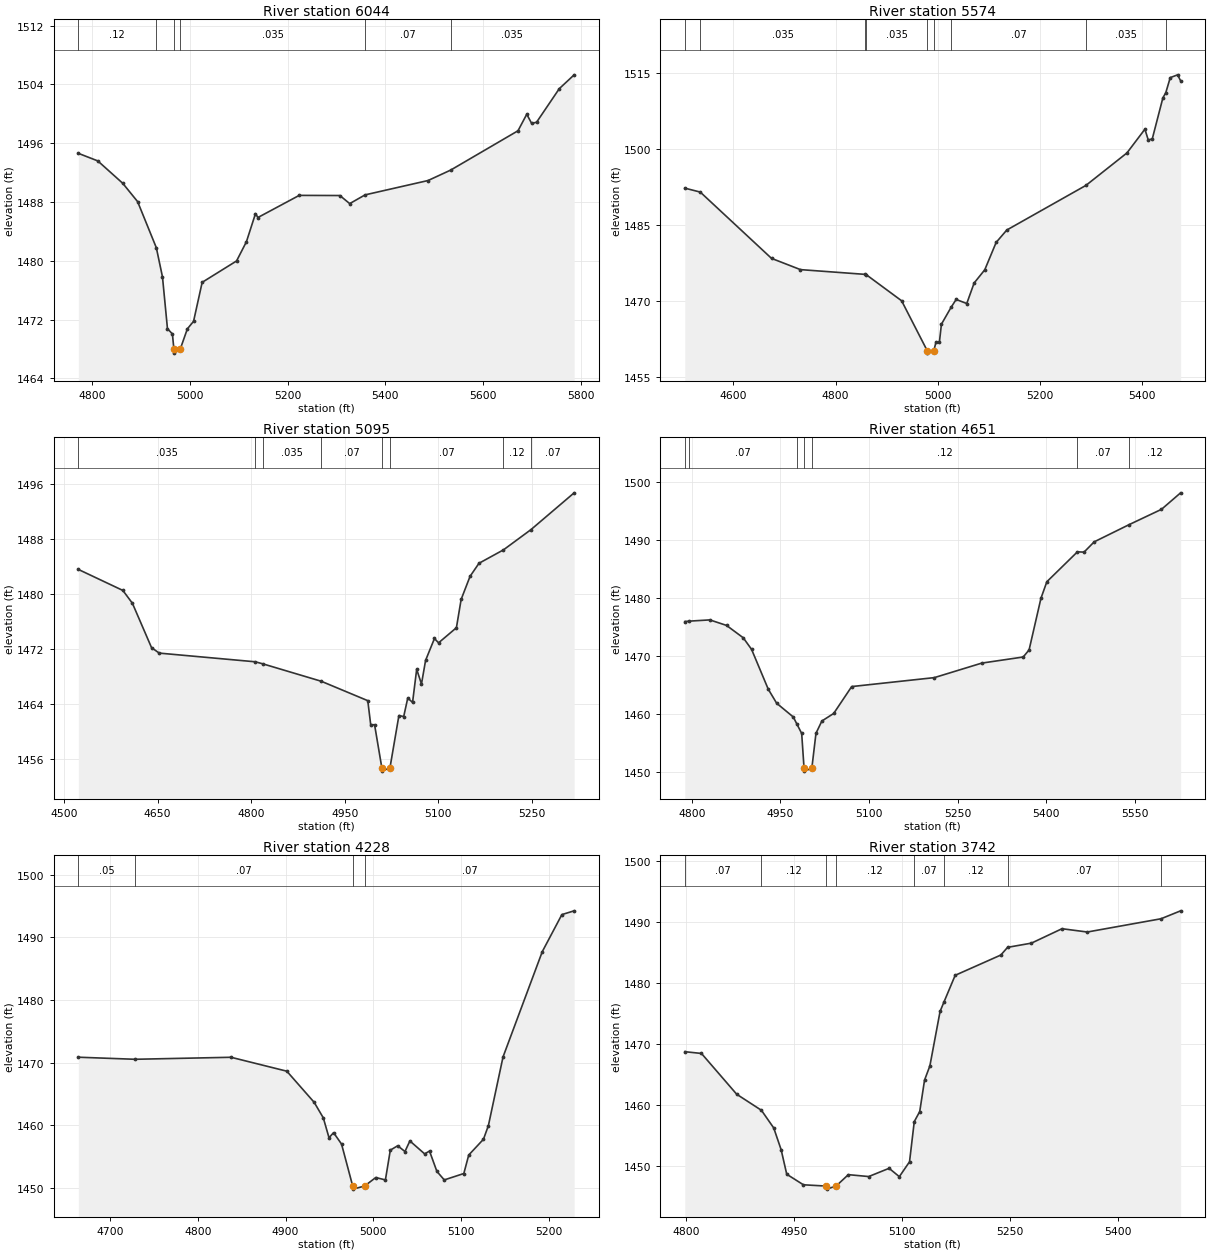
Type RM Length L Ch R = 1 ,6044    ,470,470,470
BEGIN DESCRIPTION:
JUNG CREEK 12.0
END DESCRIPTION:
XS GIS Cut Line= 3
      2048404.18     13933818.33        2048175.       13933775.
      2047398.65     13933863.32
#Sta/Elev= 30
  4771.9 1494.61  4811.7 1493.58  4862.7 1490.54  4893.2 1488.04  4931.5 1481.77
  4944.1  1477.8  4954.3 1470.75  4964.4 1470.04  4967.5 1467.93    4968 1467.43
  4980.2 1467.93    4995 1470.73  5007.7 1471.76  5025.3 1477.06  5095.7 1479.97
  5115.9 1482.59  5134.4 1486.41  5139.4 1485.88  5223.9 1488.89  5307.1 1488.87
  5327.2 1487.77  5358.7 1488.96  5487.5 1490.91  5533.8 1492.33  5671.6 1497.68
  5689.5 1499.93  5699.6 1498.67  5709.7 1498.85  5756.1 1503.41  5786.5 1505.29
#Mann= 6 ,-1 , 0
  4771.9     .12       0  4931.5    .035       0  4967.5    .035       0
  4980.2    .035       0  5358.7     .07       0  5533.8    .035       0
Bank Sta=4967.5,4980.2
XS Rating Curve= 0 ,0
Exp/Cntr=0.3,0.1

Type RM Length L Ch R = 1 ,5574    ,479,479,479
BEGIN DESCRIPTION:
JUNG CREEK 11.0
END DESCRIPTION:
XS GIS Cut Line= 3
      2048475.01     13933675.01        2048125.       13933325.
      2047754.95     13933026.69
#Sta/Elev= 30
    4505 1492.34  4535.3 1491.56  4674.7 1478.48  4731.3 1476.26  4856.9 1475.33
  4859.7 1475.29  4929.3 1470.11  4979.3 1460.28  4979.8 1459.78  4992.4 1460.28
  4996.4  1461.9  5003.2  1461.9  5007.2 1465.49    5026  1468.8    5036 1470.37
  5056.8 1469.57  5071.2 1473.62    5092 1476.22  5114.3 1481.63  5135.1 1484.07
    5290 1492.88  5370.2 1499.28  5405.4 1503.97  5411.9 1501.86  5419.8 1502.05
  5440.6 1510.16  5446.2 1511.15    5455 1514.15  5469.4  1514.7  5475.3 1513.51
#Mann= 9 ,-1 , 0
    4505     .07       0  4535.3    .035       0  4856.9     .07       0
  4859.7    .035       0  4979.3    .035       0  4992.4    .035       0
    5026     .07       0    5290    .035       0  5446.2     .07       0
Bank Sta=4979.3,4992.4
XS Rating Curve= 0 ,0
Exp/Cntr=0.3,0.1

Type RM Length L Ch R = 1 ,5095    ,444,444,444
BEGIN DESCRIPTION:
JUNG CREEK 10.0
END DESCRIPTION:
XS GIS Cut Line= 3
      2048525.01     13933325.02        2048275.       13932925.
      2048029.63     13932714.51
#Sta/Elev= 30
    4523 1483.54  4594.4 1480.49  4609.7 1478.63  4640.4 1472.19  4652.7  1471.4
  4806.7 1470.14  4818.9 1469.84  4912.4 1467.32  4987.1  1464.5  4991.8 1461.01
    4998 1461.01  5009.6 1454.78  5010.1 1454.28  5022.7 1454.78    5037 1462.34
  5044.7  1462.2  5051.2 1464.88  5058.9 1464.25  5065.5 1469.05  5073.2 1466.92
  5079.8 1470.35    5094 1473.52  5100.6 1472.89  5129.2 1475.08  5136.8 1479.19
  5151.1 1482.54  5165.4 1484.43  5204.7 1486.38  5248.7 1489.31    5318 1494.65
#Mann= 8 ,-1 , 0
    4523    .035       0  4806.7     .07       0  4818.9    .035       0
  4912.4     .07       0  5009.6     .05       0  5022.7     .07       0
  5204.7     .12       0  5248.7     .07       0
Bank Sta=5009.6,5022.7
XS Rating Curve= 0 ,0
Exp/Cntr=0.3,0.1

Type RM Length L Ch R = 1 ,4651    ,423,423,423
BEGIN DESCRIPTION:
JUNG CREEK 9.0
END DESCRIPTION:
XS GIS Cut Line= 3
        2048775.       13932825.        2048625.       13932675.
      2047999.03     13932627.44
#Sta/Elev= 30
  4787.9 1475.94  4794.4 1476.01  4830.3 1476.23  4858.6 1475.28  4886.9 1473.15
    4901 1471.16  4929.3 1464.29  4943.5 1461.88  4971.7 1459.51    4978 1458.25
  4985.9 1456.68  4989.9 1450.69  4990.4 1450.19  5003.1 1450.69  5010.1  1456.7
  5020.1 1458.82  5040.1 1460.12  5070.6 1464.75  5210.6 1466.29  5290.9 1468.79
  5361.1 1469.84  5371.1 1471.06  5391.2 1479.95  5401.2  1482.8    5453 1487.95
  5464.2  1487.9  5481.4 1489.67  5540.5 1492.63  5595.4 1495.27  5627.8 1498.11
#Mann= 7 ,-1 , 0
  4787.9     .05       0  4794.4     .07       0    4978     .12       0
  4989.9     .05       0  5003.1     .12       0    5453     .07       0
  5540.5     .12       0
Bank Sta=4989.9,5003.1
XS Rating Curve= 0 ,0
Exp/Cntr=0.3,0.1

Type RM Length L Ch R = 1 ,4228    ,486,486,486
BEGIN DESCRIPTION:
JUNG CREEK 8.0
END DESCRIPTION:
XS GIS Cut Line= 3
       2049053.5     13932419.02        2048725.       13932325.
        2048625.       13932125.
#Sta/Elev= 30
  4663.8 1470.85  4728.4 1470.52  4837.9 1470.84  4901.5 1468.62  4932.7 1463.65
  4943.1 1461.17  4949.6    1458  4954.8 1458.81  4963.9 1456.99  4976.6  1450.3
  4977.1  1449.8  4990.2  1450.3  5002.9 1451.65  5013.9 1451.27  5019.5 1456.02
  5027.9 1456.72  5036.2  1455.8  5041.8 1457.49  5058.6 1455.43  5064.2 1455.87
  5072.6 1452.63    5081 1451.27  5103.3 1452.29  5108.9 1455.24  5125.7 1457.76
  5131.3 1459.93    5148 1470.89  5192.8 1487.71  5215.1 1493.61  5229.1 1494.21
#Mann= 4 ,-1 , 0
  4663.8     .05       0  4728.4     .07       0  4976.6     .05       0
  4990.2     .07       0
Bank Sta=4976.6,4990.2
XS Rating Curve= 0 ,0
Exp/Cntr=0.3,0.1

Type RM Length L Ch R = 1 ,3742    ,477,477,477
BEGIN DESCRIPTION:
JUNG CREEK 7.0
END DESCRIPTION:
XS GIS Cut Line= 3
      2049125.01     13932325.04        2049075.       13932125.
      2048718.13     13931798.78
#Sta/Elev= 30
    4798 1468.69  4821.2  1468.4  4870.2 1461.72  4904.6 1459.09  4921.7  1456.2
    4932 1452.64  4939.8 1448.62    4963 1446.89  4994.8 1446.68  4995.3 1446.18
  5008.4 1446.68  5025.5 1448.55  5053.8 1448.24  5082.2 1449.59  5096.4 1448.22
  5110.6 1450.66  5117.2 1457.24  5124.8 1458.89  5131.5 1464.04  5138.9 1466.36
  5153.1 1475.29  5158.6 1476.85  5174.1  1481.2  5237.6 1484.52    5247 1485.78
  5280.2 1486.47  5322.7 1488.83  5357.9 1488.29  5460.4 1490.46  5487.7 1491.76
#Mann= 8 ,-1 , 0
    4798     .07       0  4904.6     .12       0  4994.8     .05       0
  5008.4     .12       0  5117.2     .07       0  5158.6     .12       0
    5247     .07       0  5460.4     .12       0
Bank Sta=4994.8,5008.4
XS Rating Curve= 0 ,0
Exp/Cntr=0.3,0.1

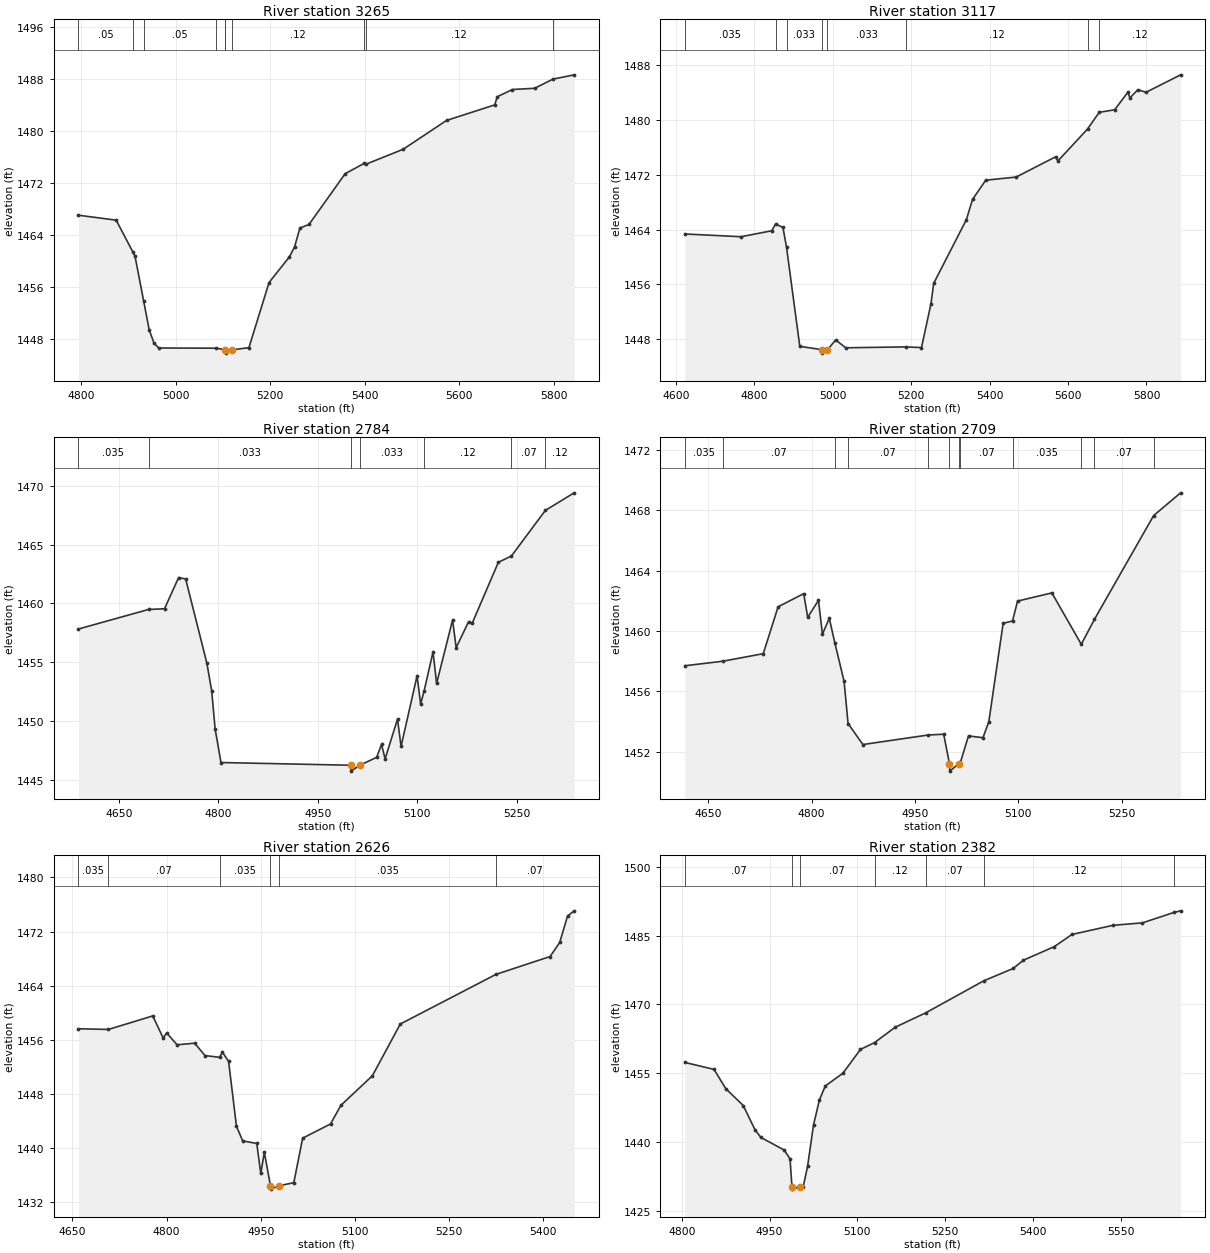
Type RM Length L Ch R = 1 ,3265    ,148,148,148
BEGIN DESCRIPTION:
JUNG CREEK 6.0
END DESCRIPTION:
XS GIS Cut Line= 3
        2049475.     13932175.04        2049475.       13931975.
      2048683.23      13931669.5
#Sta/Elev= 30
    4794 1467.01    4874 1466.25  4909.5 1461.33    4914 1460.66  4932.3 1453.75
    4944 1449.34    4954 1447.33    4964 1446.57  5085.9 1446.54  5104.6  1446.3
  5105.1 1446.28  5105.6 1445.78  5118.7 1446.28  5154.8 1446.62  5197.4 1456.65
  5240.6 1460.61  5251.3 1462.13  5262.7 1465.04  5281.9 1465.59  5358.5 1473.41
  5399.2 1475.01  5401.7 1474.84    5481 1477.16  5572.8  1481.6  5674.7 1483.99
    5680 1485.25  5712.2 1486.36  5759.2 1486.55  5797.6 1487.95  5842.7 1488.62
#Mann= 10 ,-1 , 0
    4794     .05       0  4909.5     .07       0  4932.3     .05       0
  5085.9    .033       0  5104.6     .12       0  5105.1     .05       0
  5118.7     .12       0  5399.2     .07       0  5401.7     .12       0
  5797.6     .07       0
Bank Sta=5105.1,5118.7
XS Rating Curve= 0 ,0
Exp/Cntr=0.3,0.1

Type RM Length L Ch R = 1 ,3117    ,333,333,333
BEGIN DESCRIPTION:
JUNG CREEK 5.2
END DESCRIPTION:
XS GIS Cut Line= 3
      2049862.41       13932110.      2049572.51     13931868.97
      2048720.25     13931622.82
#Sta/Elev= 30
    4623 1463.36  4766.5 1462.96  4844.6 1463.83  4854.5 1464.81  4873.2 1464.32
  4882.3 1461.44  4916.2 1446.96  4973.2 1446.47  4973.7 1445.97  4986.8 1446.47
  5007.8  1447.9  5033.1 1446.75  5186.7 1446.88  5226.4 1446.78  5250.5 1453.14
  5257.6 1456.16  5340.9 1465.45  5356.6 1468.41  5390.2 1471.21  5467.9 1471.67
  5568.8 1474.64    5574    1474  5649.7 1478.68  5679.7 1481.12  5718.9 1481.49
  5752.6 1484.05  5757.8 1483.22  5778.1 1484.42  5798.9 1484.04  5887.1 1486.59
#Mann= 8 ,-1 , 0
    4623    .035       0  4854.5     .07       0  4882.3    .033       0
  4973.2    .033       0  4986.8    .033       0  5186.7     .12       0
  5649.7     .07       0  5679.7     .12       0
Bank Sta=4973.2,4986.8
XS Rating Curve= 0 ,0
Exp/Cntr=0.3,0.1

Type RM Length L Ch R = 1 ,2784    ,75,75,75
BEGIN DESCRIPTION:
JUNG CREEK 5.1
END DESCRIPTION:
XS GIS Cut Line= 3
      2049886.98      13931459.9      2049501.17     13931601.87
      2049188.98     13931728.52
#Sta/Elev= 30
  4588.9 1457.83  4694.8 1459.49  4718.9 1459.55  4740.2  1462.2  4750.8 1462.08
  4782.8 1454.94    4790 1452.61  4795.3 1449.34  4804.1  1446.5  4999.9 1446.27
  5000.4 1445.77  5013.5 1446.27    5039 1446.94  5046.3 1448.04  5051.7 1446.81
  5070.4 1450.18  5075.8 1447.87  5099.9 1453.86  5105.3 1451.47  5110.7 1452.61
    5124 1455.89  5129.4 1453.21  5153.5  1458.6  5158.9 1456.25  5177.6 1458.45
    5183 1458.31  5222.5 1463.49  5242.3 1464.03  5293.5  1467.9  5336.9 1469.39
#Mann= 7 ,-1 , 0
  4588.9    .035       0  4694.8    .033       0  4999.9    .033       0
  5013.5    .033       0  5110.7     .12       0  5242.3     .07       0
  5293.5     .12       0
Bank Sta=4999.9,5013.5
XS Rating Curve= 0 ,0
Exp/Cntr=0.3,0.1

Type RM Length L Ch R = 1 ,2709    ,83,83,83
BEGIN DESCRIPTION:
JUNG CREEK 5.02
END DESCRIPTION:
XS GIS Cut Line= 4
      2049805.89       13931341.       2049474.5     13931535.21
      2049357.28     13931619.87      2049181.83     13931695.36
#Sta/Elev= 30
  4615.9  1457.7    4671    1458  4729.8  1458.5  4751.3  1461.6  4788.5 1462.47
  4794.3 1460.91  4809.9 1462.02  4815.7 1459.79  4825.6 1460.84  4833.6 1459.23
  4847.1 1456.67  4852.9 1453.88  4874.4 1452.49  4969.3 1453.12  4991.7 1453.17
    5000 1451.23  5000.5 1450.73  5013.7 1451.23    5016 1451.32  5027.7 1453.06
  5048.7 1452.94  5057.2    1454    5078 1460.51  5091.6 1460.66  5098.9 1461.98
  5148.7 1462.52  5191.4 1459.12  5210.5 1460.77  5296.5 1467.64  5335.6 1469.14
#Mann= 12 ,-1 , 0
  4615.9    .035       0    4671     .07       0  4833.6    .033       0
  4852.9     .07       0  4969.3    .035       0    5000    .035       0
  5013.7    .035       0    5016     .07       0  5091.6    .035       0
  5191.4     .12       0  5210.5     .07       0  5296.5     .12       0
Bank Sta=5000,5013.7
XS Rating Curve= 0 ,0
Exp/Cntr=0.3,0.1

Type RM Length L Ch R = 1 ,2626    ,244,244,244
BEGIN DESCRIPTION:
JUNG CREEK 5.01
END DESCRIPTION:
XS GIS Cut Line= 3
      2049778.36     13931297.52      2049474.95     13931452.28
      2049074.52     13931656.72
#Sta/Elev= 30
  4659.4 1457.64  4707.4 1457.54    4778 1459.54  4794.6 1456.27  4800.2 1457.02
  4816.8 1455.27  4844.7 1455.51  4861.3 1453.68  4884.4 1453.42  4889.1 1454.17
  4898.9 1452.81  4911.4 1443.23  4921.4 1441.07  4943.8 1440.69  4950.2 1436.25
  4955.8 1439.39  4965.6 1434.44  4966.1 1433.94  4979.3 1434.44  5002.8 1434.89
  5016.9 1441.47  5061.3 1443.57  5077.9 1446.33    5128 1450.69  5172.5 1458.34
  5324.8 1465.67  5411.3 1468.32  5426.6  1470.4  5439.1 1474.31  5449.6 1475.07
#Mann= 6 ,-1 , 0
  4659.4    .035       0  4707.4     .07       0  4884.4    .035       0
  4965.6    .035       0  4979.3    .035       0  5324.8     .07       0
Bank Sta=4965.6,4979.3
XS Rating Curve= 0 ,0
Exp/Cntr=0.3,0.1

Type RM Length L Ch R = 1 ,2382    ,469,469,469
BEGIN DESCRIPTION:
JUNG CREEK 5.0
END DESCRIPTION:
XS GIS Cut Line= 3
        2049725.       13931225.        2049525.       13931225.
      2048879.94     13931165.56
#Sta/Elev= 30
    4805 1457.39    4855 1455.87    4875 1451.69    4905    1448    4925 1442.74
    4935 1441.07    4975 1438.32    4985 1436.39  4988.2 1430.32  4988.7 1429.82
  5001.9 1430.32  5007.5 1430.35    5015 1434.83  5025.1 1443.79  5035.1 1449.19
  5045.2 1452.26  5075.3 1455.03  5105.4 1460.22  5129.6 1461.71  5164.6 1465.03
  5217.3  1468.2    5316 1475.13  5366.5 1477.83    5384 1479.63  5436.8 1482.58
    5467 1485.23  5537.2 1487.22  5587.5 1487.75  5641.2 1490.01  5652.8 1490.37
#Mann= 7 ,-1 , 0
    4805     .07       0  4988.2     .05       0  5001.9     .07       0
  5129.6     .12       0  5217.3     .07       0    5316     .12       0
  5641.2     .07       0
Bank Sta=4988.2,5001.9
XS Rating Curve= 0 ,0
Exp/Cntr=0.3,0.1

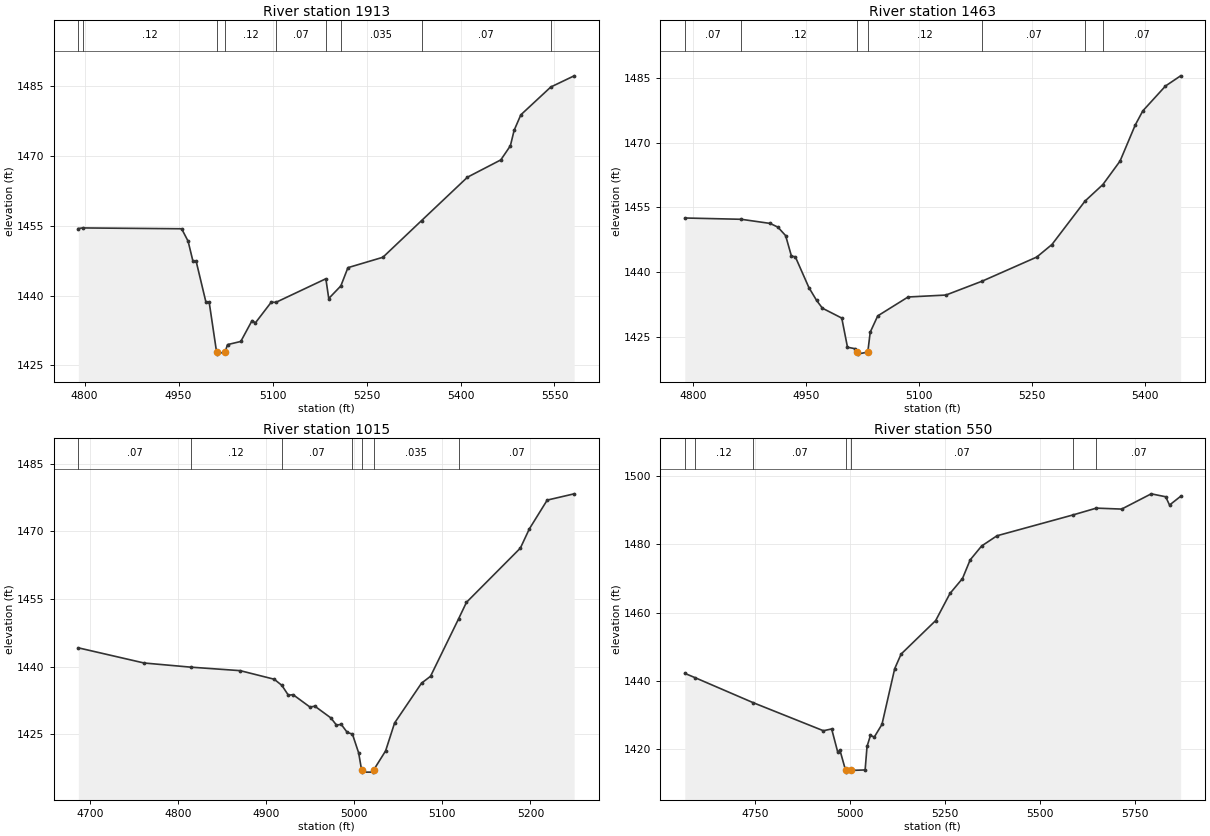
Type RM Length L Ch R = 1 ,1913    ,450,450,450
BEGIN DESCRIPTION:
JUNG CREEK 4.0
END DESCRIPTION:
XS GIS Cut Line= 3
      2049924.99       13930775.        2049725.       13930825.
      2049174.98     13930624.99
#Sta/Elev= 30
    4790 1454.38  4796.7 1454.51  4954.9 1454.33  4965.2 1451.66    4973 1447.33
  4978.1 1447.33  4993.6 1438.62  4998.8 1438.62  5010.6 1427.92  5011.1 1427.42
  5024.3 1427.92  5028.1 1429.46  5049.3 1430.14  5067.3 1434.63  5072.6 1434.13
  5097.9 1438.57  5105.3 1438.53  5185.1  1443.6  5189.7 1439.36    5209 1442.06
  5220.3 1445.98  5276.1 1448.21  5337.8 1456.08  5411.1  1465.4  5464.3 1469.11
  5479.6 1472.14  5485.6 1475.47  5496.3 1478.79  5544.1 1484.76  5581.4 1487.16
#Mann= 9 ,-1 , 0
    4790    .035       0  4796.7     .12       0  5010.6     .05       0
  5024.3     .12       0  5105.3     .07       0  5185.1     .12       0
    5209    .035       0  5337.8     .07       0  5544.1     .12       0
Bank Sta=5010.6,5024.3
XS Rating Curve= 0 ,0
Exp/Cntr=0.3,0.1

Type RM Length L Ch R = 1 ,1463    ,448,448,448
BEGIN DESCRIPTION:
JUNG CREEK 3.0
END DESCRIPTION:
XS GIS Cut Line= 3
      2049924.98     13930424.99        2049725.       13930375.
        2049275.       13930325.
#Sta/Elev= 30
    4789 1452.55    4864 1452.25  4902.4 1451.29  4912.7 1450.43    4923 1448.46
  4930.7 1443.72  4935.9 1443.54  4953.9 1436.42  4964.2 1433.42  4971.9 1431.63
  4997.6 1429.34  5005.2 1422.58  5015.3 1422.24  5018.4 1421.48  5018.9 1420.98
  5032.2 1421.48  5035.4 1426.07  5045.4 1429.85  5085.7 1434.23    5136 1434.68
    5184 1437.89  5256.7 1443.49  5276.9  1446.4  5320.9 1456.48  5344.6 1460.31
  5367.4 1465.75  5387.5 1474.08  5397.6 1477.38  5427.8 1483.16  5447.9 1485.52
#Mann= 7 ,-1 , 0
    4789     .07       0    4864     .12       0  5018.4     .05       0
  5032.2     .12       0    5184     .07       0  5320.9    .035       0
  5344.6     .07       0
Bank Sta=5018.4,5032.2
XS Rating Curve= 0 ,0
Exp/Cntr=0.3,0.1

Type RM Length L Ch R = 1 ,1015    ,465,465,465
BEGIN DESCRIPTION:
JUNG CREEK 2.0
END DESCRIPTION:
XS GIS Cut Line= 3
      2049862.53     13930085.68        2049575.       13929975.
      2049325.04     13929925.01
#Sta/Elev= 30
  4686.6 1444.18  4761.2 1440.82    4814  1439.9  4870.4 1439.12    4909 1437.22
  4917.7 1435.86  4925.1 1433.67  4930.4  1433.8  4949.7 1431.04  4955.1 1431.25
  4973.3 1428.65  4979.7 1427.05  4985.1 1427.21    4992 1425.41  4997.8 1425.06
  5004.9 1420.89  5008.2 1417.12  5008.7 1416.62  5021.5 1416.62    5022 1417.12
  5035.5 1421.33  5045.7 1427.52  5076.3 1436.35  5086.5 1437.87  5118.3 1450.58
  5127.3 1454.27  5188.5 1466.29  5198.7 1470.55    5219 1476.94  5249.6 1478.33
#Mann= 7 ,-1 , 0
  4686.6     .07       0    4814     .12       0  4917.7     .07       0
  4997.8    .035       0  5008.2    .035       0    5022    .035       0
  5118.3     .07       0
Bank Sta=5008.2,5022
XS Rating Curve= 0 ,0
Exp/Cntr=0.3,0.1

Type RM Length L Ch R = 1 ,550     ,0,0,0
BEGIN DESCRIPTION:
JUNG CREEK 1.0
END DESCRIPTION:
XS GIS Cut Line= 3
      2049935.48     13930009.31        2049725.       13929625.
      2048866.03     13929509.31
#Sta/Elev= 30
  4565.6 1442.24    4593 1440.96  4746.2 1433.62  4930.3 1425.43  4952.1 1425.95
  4968.2 1419.12  4973.9 1419.73  4988.8  1413.8  4989.3  1413.3  5002.7  1413.8
  5040.2 1413.94  5045.2 1420.82  5054.2 1424.05  5064.3 1423.58  5084.5 1427.29
    5118 1443.61  5134.9 1447.89  5225.8  1457.7  5263.5 1465.65  5296.4 1470.02
  5316.6 1475.48  5346.8 1479.56  5387.2 1482.55  5587.7 1488.67  5648.6 1490.65
  5715.3 1490.37  5793.1 1494.84  5831.2 1493.98  5841.3 1491.55  5870.5 1494.11
#Mann= 7 ,-1 , 0
  4565.6     .07       0    4593     .12       0  4746.2     .07       0
  4988.8     .05       0  5002.7     .07       0  5587.7    .035       0
  5648.6     .07       0
Bank Sta=4988.8,5002.7
XS Rating Curve= 0 ,0
Exp/Cntr=0.3,0.1

Chan Stop Cuts=-1
Use User Specified Reach Order=0
Composite Channel Slope=5