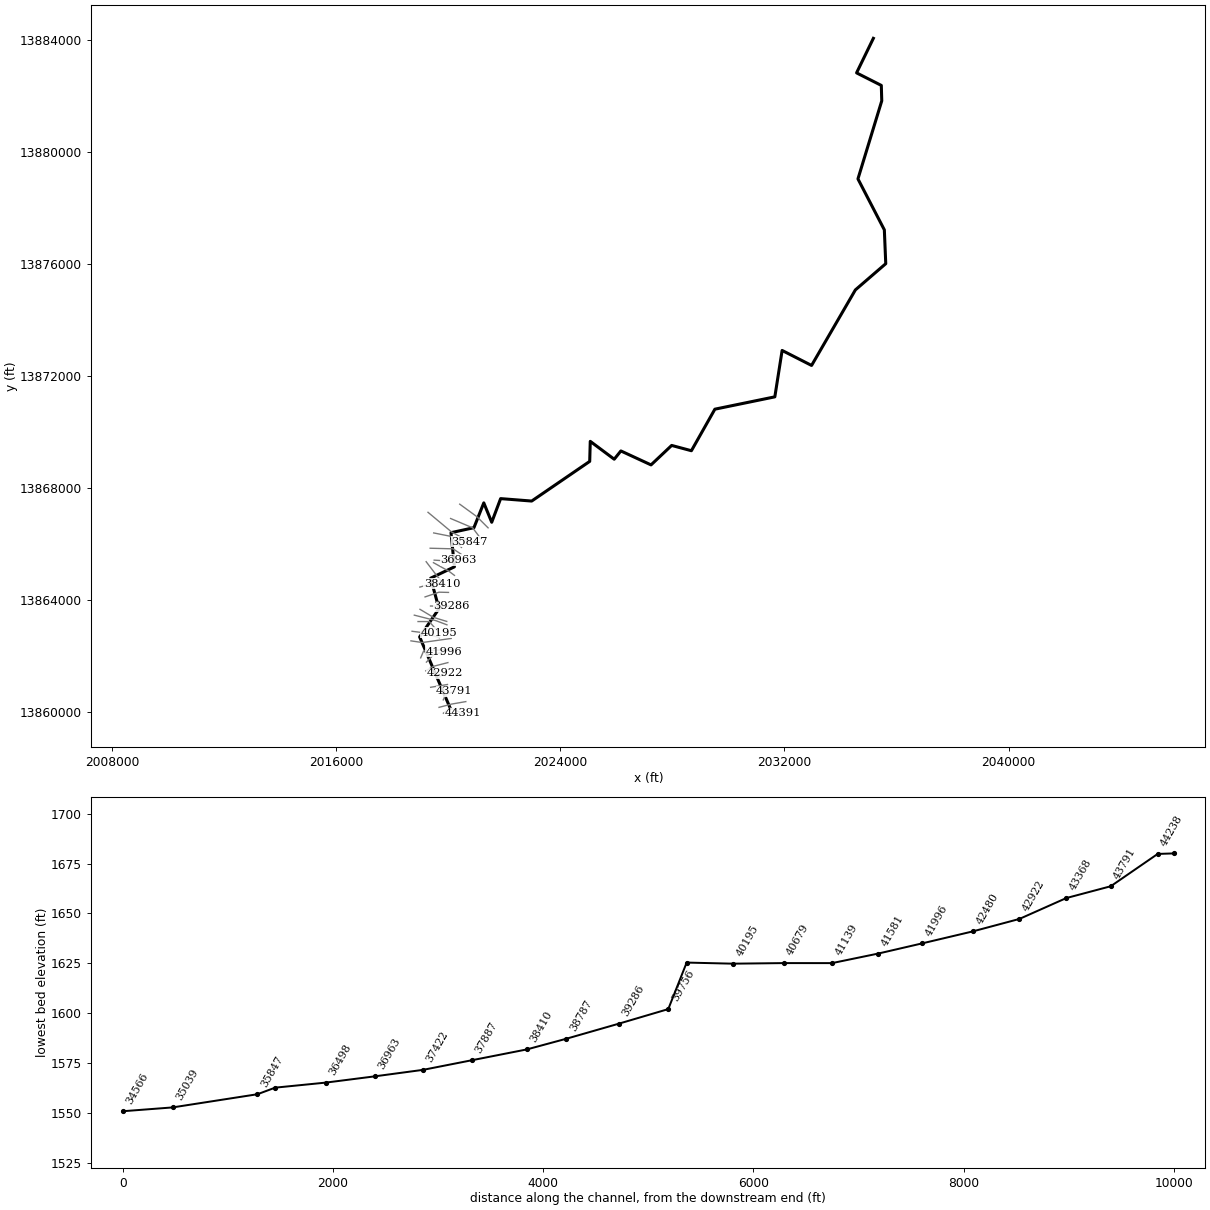
--- LITTLE JOSHUA CREEK.prj (project) ---

Proj Title=LITTLE JOSHUA CREEK Base Level Engineering
Current Plan=p01
Default Exp/Contr=0.3,0.1
English Units
Geom File=g01
Flow File=f01
Plan File=p01
Y Axis Title=Elevation
X Axis Title(PF)=Main Channel Distance
X Axis Title(XS)=Station
BEGIN DESCRIPTION:
LITTLE JOSHUA CREEK
END DESCRIPTION:
DSS File=dss
DSS Export Rating Curves= 0
DSS Export Rating Curve Sorted= 0
DSS Export Volume Flow Curves= 0
DXF OffsetX= 0
DXF OffsetY= 0
DXF ScaleX= 1
DXF ScaleY= 10

--- LITTLE JOSHUA CREEK.p01 (plan) ---

Plan Title=Multiple Run
Program Version=4.10
Short Identifier=Multiple Run
Geom File=g01
Flow File=f01
Subcritical Flow
K Sum by GR= 0
Std Step Tol= 0.01
Critical Tol= 0.01
Num of Std Step Trials= 20
Max Error Tol= 0.3
Flow Tol Ratio= 0.001
Split Flow NTrial= 30
Split Flow Tol= 0.02
Split Flow Ratio= 0.02
Log Output Level= 0
Friction Slope Method= 1
Unsteady Friction Slope Method= 2
Unsteady Bridges Friction Slope Method= 1
Parabolic Critical Depth
Global Vel Dist= 1 , 1 , 1
Global Log Level= 0
CheckData=True
Encroach Param=-1 ,0,0, 0
BEGIN DESCRIPTION:
Multiple Run
END DESCRIPTION:
Computation Interval=1HOUR
Output Interval=1HOUR
Run HTab= 0
Run UNet= 0
Run PostProcess= 0
Run WQNet= 0
UNET Theta= 1
UNET Theta Warmup= 1
UNET ZTol= 0.02
UNET ZSATol= 0.05
UNET MxIter= 20
UNET MaxInSteps= 0
UNET DtIC= 0
UNET DtMin= 0
UNET MaxCRTS= 20
UNET WFStab= 2
UNET SFStab= 1
UNET WFX= 1
UNET SFX= 1
UNET DSS MLevel= 4
UNET DZMax Abort= 100
UNET Convert EG Bridges= 0
UNET Use Existing IB Tables=-1
UNET Froude Reduction=False
UNET Froude Limit= 1
UNET Froude Power= 10
UNET Time Slicing=0,0, 5
UNET Junction Losses=0
Instantaneous Interval=1HOUR
DSS File=dss
Write IC File= 0
Write IC File at Sim End=0
Echo Input=False
Echo Parameters=False
Echo Output=False
Write Detailed= 0
WQ AD Non Conservative
WQ ULTIMATE=-1
WQ Max Comp Step=1HOUR
WQ Output Interval=15MIN
WQ Output Selected Increments= 0
WQ Output face flow=0
WQ Output face velocity=0
WQ Output face area=0
WQ Output face dispersion=0
WQ Output cell volume=0
WQ Output cell surface area=0
WQ Output cell continuity=0
WQ Output cumulative cell continuity=0
WQ Output face conc=0
WQ Output face dconc_dx=0
WQ Output face courant=0
WQ Output face peclet=0
WQ Output face adv mass=0
WQ Output face disp mass=0
WQ Output cell mass=0
WQ Output cell source sink temp=0
WQ Output cell source sink nsm=0
WQ Output MaxMinRange=-1
WQ Daily Max Min Mean=-1
WQ Daily Range=0
WQ Daily Time=0
WQ Create Restart=0
WQ Fixed Restart=0
WQ System Summary=0
WQ Use Fixed Temperature=0
Sorting and Armoring Iterations= 10
XS Update Threshold= 0.02
Hydraulics Update Threshold= 0.02
Energy Slope Method= 1
Volume Change Method= 0
XS Weighting Method= 0
Number of US Weighted Cross Sections= 1
Number of DS Weighted Cross Sections= 1
Upstream XS Weight=0.25
Main XS Weight=0.5
Downstream XS Weight=0.25
Number of DS XS's Weighted with US Boundary= 1
Upstream Boundary Weight= 1
Weight of XSs Associated with US Boundary= 0
Number of US XS's Weighted with DS Boundary= 1
Downstream Boundary Weight= 0.5
Weight of XSs Associated with DS Boundary= 0.5
Sediment Output Level= 4
Mass or Volume Output= 0
Output Increment Type= 1
Profile and TS Output Increment= 10
XS Output Flag= 0
XS Output Increment= 10
Disregard all LS=0
Disregard all Conn=0
Disregard all Breaches=0
Disregard all Pumps=0

--- LITTLE JOSHUA CREEK.f01 (steady flow) ---

Flow Title=Multiple
Program Version=4.10
Number of Profiles= 7
Profile Names=10-year,25-year,50-year,1pct_min,100-year,1pct_plu,500-year
River Rch & RM=LITTLE JOSHUA CR,Reach-1         ,44391
     589     965    1312     868    1732    3456    2977
River Rch & RM=LITTLE JOSHUA CR,Reach-1         ,44238
    1289    2226    3134    2139    4269    8517    7834
River Rch & RM=LITTLE JOSHUA CR,Reach-1         ,41139
    2180    3871    5552    3854    7690   15343   14603
River Rch & RM=LITTLE JOSHUA CR,Reach-1         ,37887
    3303    5939    8588    5996   11964   23872   23006
River Rch & RM=LITTLE JOSHUA CR,Reach-1         ,29008
    3717    6703    9711    6790   13548   27031   26121
River Rch & RM=LITTLE JOSHUA CR,Reach-1         ,24739
    3915    7071   10255    7176   14318   28568   27652
River Rch & RM=LITTLE JOSHUA CR,Reach-1         ,22313
    5575   10167   14843   10445   20841   41584   40693
River Rch & RM=LITTLE JOSHUA CR,Reach-1         ,16220
    5715   10414   15196   10686   21320   42540   41567
River Rch & RM=LITTLE JOSHUA CR,Reach-1         ,12005
    5872   10705   15624   10989   21925   43747   42760
River Rch & RM=LITTLE JOSHUA CR,Reach-1         ,10933
    8154   15047   22147   15695   31317   62485   62005
River Rch & RM=LITTLE JOSHUA CR,Reach-1         ,9270
    8195   15087   22170   15683   31293   62437   61734
River Rch & RM=LITTLE JOSHUA CR,Reach-1         ,4400
    8501   15646   22986   16253   32430   64706   63921
Boundary for River Rch & Prof#=LITTLE JOSHUA CR,Reach-1         , 1
Up Type= 0
Dn Type= 1
Dn Known WS=1333.57
Boundary for River Rch & Prof#=LITTLE JOSHUA CR,Reach-1         , 2
Up Type= 0
Dn Type= 1
Dn Known WS=1337.31
Boundary for River Rch & Prof#=LITTLE JOSHUA CR,Reach-1         , 3
Up Type= 0
Dn Type= 1
Dn Known WS=1340.46
Boundary for River Rch & Prof#=LITTLE JOSHUA CR,Reach-1         , 4
Up Type= 0
Dn Type= 1
Dn Known WS=1337.64
Boundary for River Rch & Prof#=LITTLE JOSHUA CR,Reach-1         , 5
Up Type= 0
Dn Type= 1
Dn Known WS=1343.85
Boundary for River Rch & Prof#=LITTLE JOSHUA CR,Reach-1         , 6
Up Type= 0
Dn Type= 1
Dn Known WS=1348.2
Boundary for River Rch & Prof#=LITTLE JOSHUA CR,Reach-1         , 7
Up Type= 0
Dn Type= 1
Dn Known WS=1348.17
DSS Import GetInterval= 0
DSS Import GetPeak= 0
DSS Import FillOption= 0

--- LITTLE JOSHUA CREEK.g01 (geometry) ---

Geom Title=Existing Conditions
Program Version=4.10

River Reach=LITTLE JOSHUA CR,Reach-1
Reach XY= 30
        2020075.       13860125.       2018982.2      13862675.3
       2019673.8      13863685.5        2019375.       13864775.
      2020222.95     13865180.84      2020101.14     13866401.94
      2020919.74     13866580.47      2021271.86      13867467.5
      2021554.86     13866774.59      2021872.71     13867619.88
      2022981.19     13867532.82      2025052.01     13868951.48
      2025071.38     13869667.51      2025926.68     13869028.08
      2026164.29      13869324.3      2027240.16     13868825.39
      2027976.56     13869521.26      2028681.15     13869331.94
      2029518.84     13870817.22      2031658.59      13871258.2
      2031918.81     13872917.19      2032969.82     13872380.41
      2034532.86     13875081.19      2035617.14     13876018.83
      2035566.76     13877228.23      2034624.61       13879050.
      2035474.48     13881840.22      2035458.57     13882391.77
      2034575.38     13882840.16        2035175.       13884075.

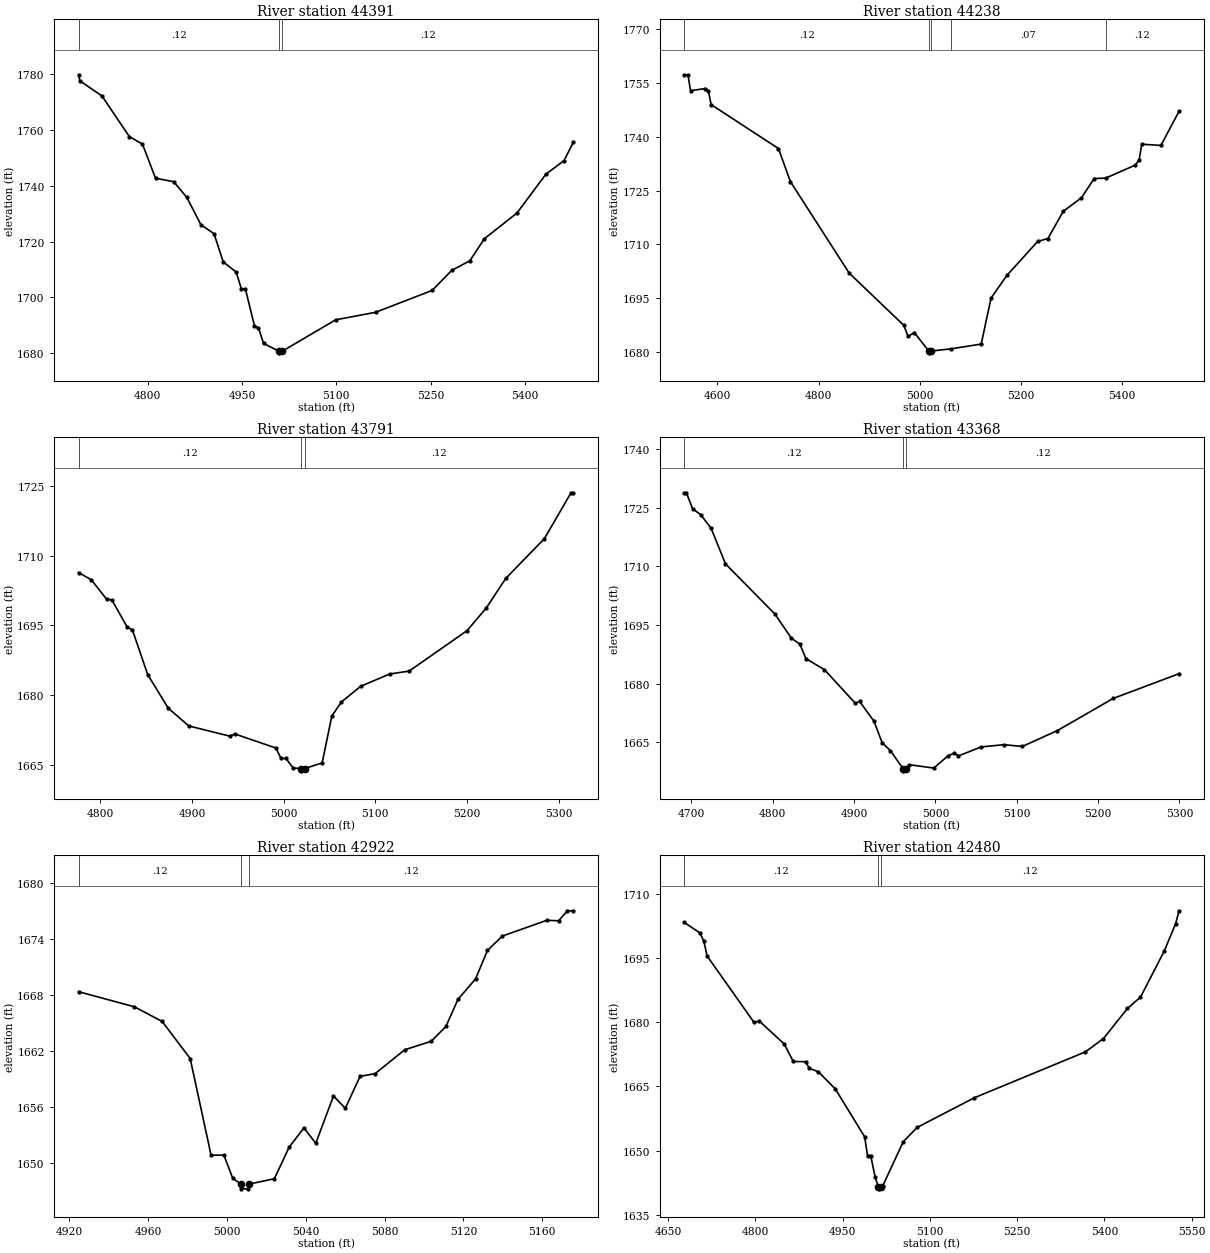
Type RM Length L Ch R = 1 ,44391   ,154,154,154
BEGIN DESCRIPTION:
LITTLE JOSHUA CREEK 90.0
END DESCRIPTION:
XS GIS Cut Line= 3
      2019829.66     13859947.81      2020074.62     13860137.96
      2020510.07     13859942.26
#Sta/Elev= 30
  4689.9 1779.75  4691.9 1777.59  4727.2 1772.13  4770.7 1757.59  4791.5 1754.92
  4812.3  1742.7  4841.2 1741.43  4862.1 1735.83  4884.7 1725.97  4905.5 1722.79
    4920 1712.72  4940.8 1709.02    4949 1702.97  4955.3 1703.08  4969.8 1689.83
  4976.1 1689.11  4984.3 1683.49  5009.4 1680.61  5009.6 1680.11  5013.4 1680.61
  5099.1 1691.95  5162.6 1694.64  5252.6 1702.48  5283.9 1709.69  5312.5 1713.07
  5335.7    1721  5387.5 1730.19  5433.8 1744.17  5462.4 1748.97  5477.4 1755.57
#Mann= 3 ,-1 , 0
  4689.9     .12       0  5009.4     .05       0  5013.4     .12       0
Bank Sta=5009.4,5013.4
XS Rating Curve= 0 ,0
Exp/Cntr=0.3,0.1

Type RM Length L Ch R = 1 ,44238   ,447,447,447
BEGIN DESCRIPTION:
LITTLE JOSHUA CREEK 89.0
END DESCRIPTION:
XS GIS Cut Line= 3
      2019674.76     13860157.65        2020125.       13860275.
       2020630.4     13860363.08
#Sta/Elev= 30
  4534.3 1757.22  4541.7 1757.11  4546.8 1752.79  4575.9 1753.39  4582.2 1752.64
  4587.3 1748.94  4720.6 1736.69  4744.1 1727.51  4860.4 1702.03  4968.6 1687.47
  4976.7 1684.42  4989.2 1685.48  5017.9 1680.35  5018.1 1679.85  5021.9 1680.35
  5060.7 1680.94  5121.4 1682.29  5140.9  1695.1  5172.1 1701.38    5233 1710.84
  5253.3 1711.66  5283.8 1719.26  5319.6 1722.99  5344.7 1728.35  5367.4 1728.46
  5425.9 1732.08  5433.7 1733.53  5438.8  1737.9  5476.7 1737.56  5512.6 1747.07
#Mann= 5 ,-1 , 0
  4534.3     .12       0  5017.9     .05       0  5021.9     .12       0
  5060.7     .07       0  5367.4     .12       0
Bank Sta=5017.9,5021.9
XS Rating Curve= 0 ,0
Exp/Cntr=0.3,0.1

Type RM Length L Ch R = 1 ,43791   ,423,423,423
BEGIN DESCRIPTION:
LITTLE JOSHUA CREEK 88.0
END DESCRIPTION:
XS GIS Cut Line= 3
      2019825.02     13860425.03        2019925.       13860625.
        2020225.       13860725.
#Sta/Elev= 30
  4776.4 1706.39  4790.3 1704.83  4807.1 1700.61  4812.7 1700.51  4829.5 1694.61
  4835.1 1694.03  4851.8 1684.39  4874.2 1677.16  4896.6 1673.33  4941.3 1671.13
  4946.9  1671.6  4991.6 1668.57  4997.2 1666.33  5002.6 1666.33  5010.5 1664.26
  5019.1 1664.15  5019.3 1663.65  5023.1 1664.15  5042.1 1665.36  5052.7 1675.49
  5063.2 1678.51  5084.3 1681.89  5115.9 1684.53    5137 1685.15  5200.2 1693.88
  5221.3 1698.79  5242.4 1705.13  5284.6 1713.72  5313.6 1723.59  5316.2 1723.59
#Mann= 3 ,-1 , 0
  4776.4     .12       0  5019.1     .05       0  5023.1     .12       0
Bank Sta=5019.1,5023.1
XS Rating Curve= 0 ,0
Exp/Cntr=0.3,0.1

Type RM Length L Ch R = 1 ,43368   ,446,446,446
BEGIN DESCRIPTION:
LITTLE JOSHUA CREEK 87.0
END DESCRIPTION:
XS GIS Cut Line= 3
      2019374.98       13860875.        2019675.       13860925.
        2019975.       13860975.
#Sta/Elev= 30
  4691.2 1728.82  4693.8 1728.82  4701.4 1724.76  4711.5 1723.21  4724.2 1719.74
  4741.9 1710.64  4802.7 1697.81    4823 1691.61  4833.2 1690.16  4840.8 1686.42
  4863.6 1683.58  4901.6 1674.99  4906.7  1675.5  4924.4 1670.43  4934.5 1664.91
  4944.7 1662.89  4960.4 1658.23  4960.7 1657.73  4964.4 1658.23  4967.5 1659.31
  4997.9 1658.44  5015.6 1661.59  5023.2 1662.29  5028.3 1661.54  5056.2 1663.85
  5084.1 1664.41  5106.9 1663.97    5150 1668.03  5218.4 1676.23  5299.5 1682.57
#Mann= 3 ,-1 , 0
  4691.2     .12       0  4960.4     .05       0  4964.4     .12       0
Bank Sta=4960.4,4964.4
XS Rating Curve= 0 ,0
Exp/Cntr=0.3,0.1

Type RM Length L Ch R = 1 ,42922   ,442,442,442
BEGIN DESCRIPTION:
LITTLE JOSHUA CREEK 86.0
END DESCRIPTION:
XS GIS Cut Line= 3
      2019674.98     13861224.98        2019725.       13861275.
      2019874.99     13861374.99
#Sta/Elev= 30
  4924.8 1668.34  4953.1 1666.73  4967.2 1665.16  4981.4  1661.2    4992 1650.87
  4998.5 1650.87    5003  1648.4  5007.1 1647.77  5007.3 1647.27  5010.8 1647.27
  5011.1 1647.77  5024.1 1648.35  5031.6 1651.72  5039.1 1653.78  5045.1 1652.14
  5054.1 1657.19  5060.1 1655.88  5067.6  1659.3  5075.2 1659.58  5090.2 1662.13
  5103.7 1663.04  5111.2 1664.65  5117.2 1667.51  5126.2 1669.72  5132.2 1672.76
  5139.8 1674.29  5162.3 1675.97  5168.3 1675.92  5172.8 1676.99  5175.8 1676.99
#Mann= 3 ,-1 , 0
  4924.8     .12       0  5007.1     .05       0  5011.1     .12       0
Bank Sta=5007.1,5011.1
XS Rating Curve= 0 ,0
Exp/Cntr=0.3,0.1

Type RM Length L Ch R = 1 ,42480   ,484,484,484
BEGIN DESCRIPTION:
LITTLE JOSHUA CREEK 85.0
END DESCRIPTION:
XS GIS Cut Line= 3
      2019201.87     13861462.38        2019475.       13861625.
      2019990.93     13861757.31
#Sta/Elev= 30
  4677.9 1703.35  4704.8  1700.9  4711.5 1698.98  4717.3 1695.48  4797.9 1679.96
  4806.9 1680.29  4849.7 1674.93  4865.3 1670.84  4886.7 1670.78  4892.6 1669.26
  4908.2 1668.44  4937.6 1664.41    4988  1653.2  4992.9 1648.83  4998.4 1648.83
  5006.1 1643.71  5011.6 1641.55  5011.8 1641.05  5015.6 1641.55  5018.7 1641.63
  5054.4 1652.09  5078.4 1655.43  5176.7 1662.36  5367.4 1673.08  5398.4 1676.19
  5439.7 1683.25  5462.1 1685.88  5502.9 1696.65  5522.3    1703  5528.4 1706.08
#Mann= 3 ,-1 , 0
  4677.9     .12       0  5011.6     .05       0  5015.6     .12       0
Bank Sta=5011.6,5015.6
XS Rating Curve= 0 ,0
Exp/Cntr=0.3,0.1

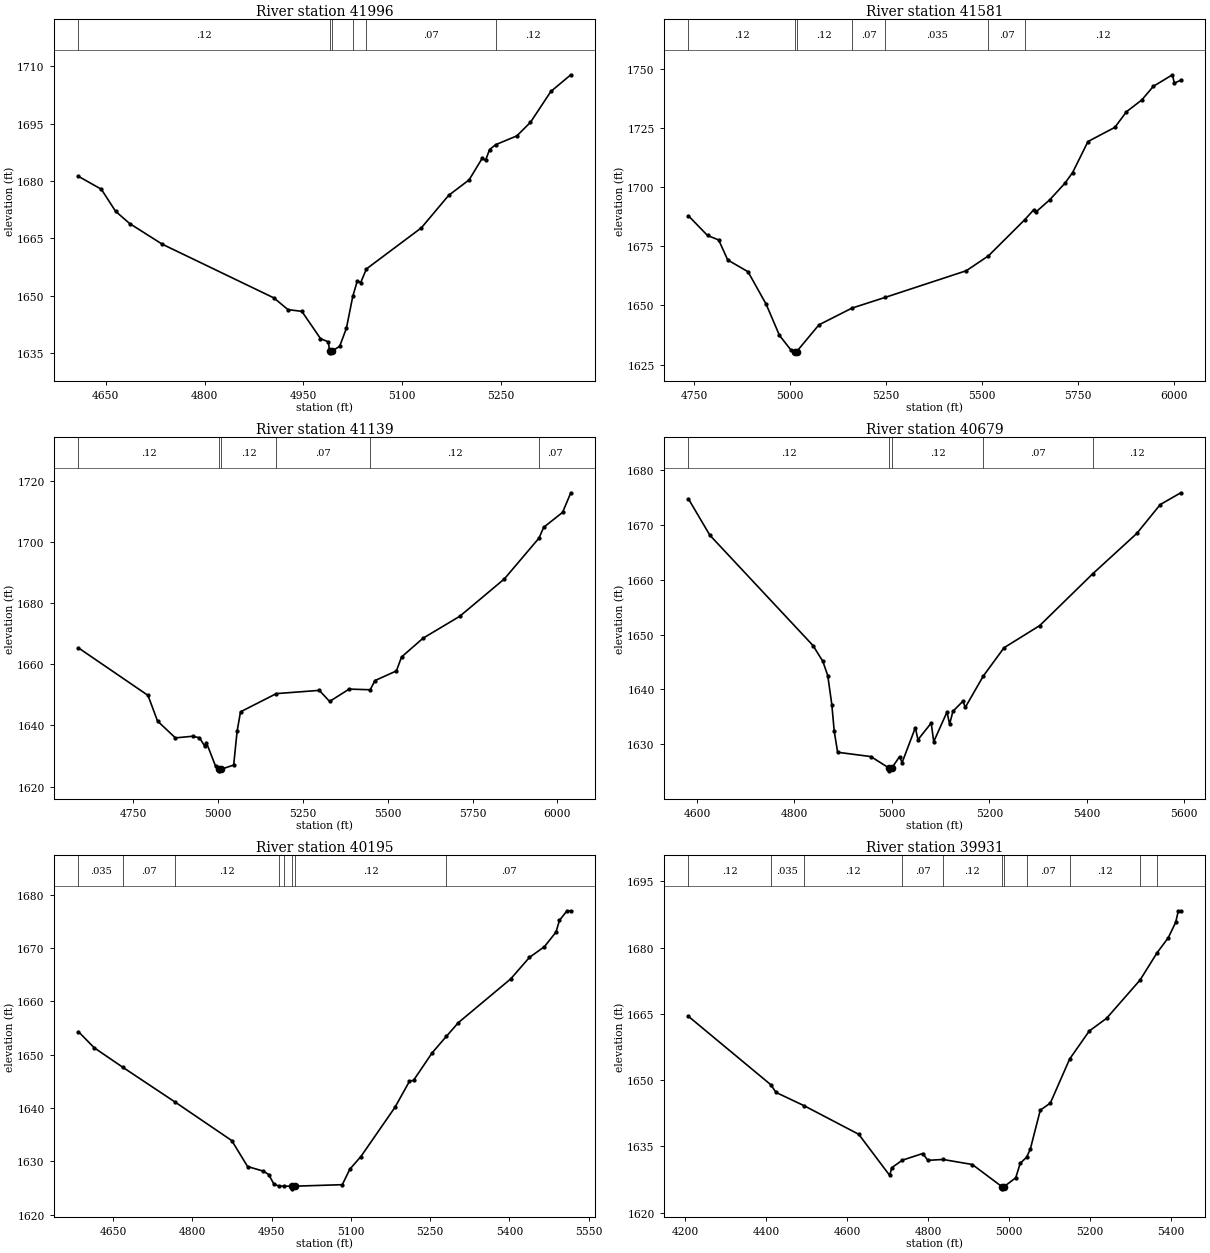
Type RM Length L Ch R = 1 ,41996   ,415,415,415
BEGIN DESCRIPTION:
LITTLE JOSHUA CREEK 84.0
END DESCRIPTION:
XS GIS Cut Line= 3
      2019225.02     13861775.02      2019488.34     13862048.33
      2019844.23     13862143.81
#Sta/Elev= 30
  4608.4 1681.22  4643.1 1677.85  4664.8 1672.07  4686.2 1668.86  4735.6 1663.47
  4905.4 1649.39  4926.7 1646.33  4947.8 1645.88  4976.1 1638.75  4987.9  1637.9
    4990 1635.52  4990.3 1635.02    4994 1635.52  5005.2 1636.72  5015.5 1641.47
  5025.2 1649.85    5032 1653.82  5037.2 1653.42  5045.9 1656.99  5129.4 1667.75
  5170.8 1676.24  5201.9  1680.3  5221.7 1685.93  5226.8 1685.38    5233 1688.24
  5242.1  1689.5  5274.4 1691.81  5295.1 1695.36  5326.1 1703.44  5356.4 1707.81
#Mann= 6 ,-1 , 0
  4608.4     .12       0    4990     .05       0    4994     .12       0
  5025.2    .035       0  5045.9     .07       0  5242.1     .12       0
Bank Sta=4990,4994
XS Rating Curve= 0 ,0
Exp/Cntr=0.3,0.1

Type RM Length L Ch R = 1 ,41581   ,442,442,442
BEGIN DESCRIPTION:
LITTLE JOSHUA CREEK 83.0
END DESCRIPTION:
XS GIS Cut Line= 3
      2019019.59      13861926.8        2019125.       13862175.
      2020136.39     13862230.95
#Sta/Elev= 30
  4734.9 1687.95  4784.5 1679.62  4813.6 1677.73  4837.2 1669.25    4890 1664.28
  4937.3 1650.52    4972 1637.32  5001.8 1631.16  5012.6 1630.45  5012.8 1629.95
  5016.6 1630.45  5074.7 1641.79  5160.8 1648.88  5247.7 1653.44  5458.7  1664.7
  5516.5 1671.02  5611.4 1686.37  5634.4 1690.52  5639.4 1689.46  5675.6 1694.66
  5715.6 1701.72  5735.7 1706.27  5775.7 1719.39  5845.8 1725.39  5875.9 1731.99
    5916    1737    5946 1742.76  5995.7 1747.64  6000.7 1744.09  6017.5 1745.34
#Mann= 7 ,-1 , 0
  4734.9     .12       0  5012.6     .05       0  5016.6     .12       0
  5160.8     .07       0  5247.7    .035       0  5516.5     .07       0
  5611.4     .12       0
Bank Sta=5012.6,5016.6
XS Rating Curve= 0 ,0
Exp/Cntr=0.3,0.1

Type RM Length L Ch R = 1 ,41139   ,460,460,460
BEGIN DESCRIPTION:
LITTLE JOSHUA CREEK 82.0
END DESCRIPTION:
XS GIS Cut Line= 3
      2018672.33     13862534.45        2019075.       13862475.
      2020108.98     13862621.24
#Sta/Elev= 30
  4588.2 1665.35  4793.1 1649.82  4821.2 1641.44  4873.9 1635.92  4924.5 1636.45
  4944.7 1635.96  4960.4 1633.23  4965.5 1634.32  4992.7 1626.57  5002.7 1625.64
  5003.1 1625.14    5008 1625.64  5045.7 1627.03  5055.8 1638.07  5065.9 1644.44
  5171.5  1650.4  5298.2 1651.46  5328.5 1647.83    5386 1651.88  5448.2 1651.66
  5462.1 1654.66  5525.5 1657.83  5540.6 1662.39  5604.2 1668.54  5712.3  1675.7
  5843.6 1687.91  5945.8 1701.28  5959.5 1704.79  6015.3 1709.69  6039.5 1716.09
#Mann= 6 ,-1 , 0
  4588.2     .12       0  5002.7     .05       0    5008     .12       0
  5171.5     .07       0  5448.2     .12       0  5945.8     .07       0
Bank Sta=5002.7,5008
XS Rating Curve= 0 ,0
Exp/Cntr=0.3,0.1

Type RM Length L Ch R = 1 ,40679   ,484,484,484
BEGIN DESCRIPTION:
LITTLE JOSHUA CREEK 81.0
END DESCRIPTION:
XS GIS Cut Line= 3
      2018711.44     13862877.32        2019125.       13862825.
      2019691.12     13862647.67
#Sta/Elev= 30
  4582.7 1674.75  4626.6 1668.13  4838.3    1648  4858.4 1645.12  4868.5 1642.51
  4876.8 1637.25  4881.8 1632.35  4888.7 1628.54    4957 1627.75  4994.3 1625.65
  4994.7 1625.15  4999.8 1625.65  5015.8 1627.75    5021 1626.65  5048.2 1633.03
  5053.5 1630.82  5080.7 1633.87  5085.9 1630.47  5113.1 1635.88  5118.4 1633.66
  5125.3 1636.01  5145.6 1637.84  5150.8 1636.75  5187.5 1642.43  5230.1  1647.6
  5303.4 1651.65  5411.7 1661.06  5502.5 1668.45  5550.6 1673.72  5592.8 1675.87
#Mann= 5 ,-1 , 0
  4582.7     .12       0  4994.3     .05       0  4999.8     .12       0
  5187.5     .07       0  5411.7     .12       0
Bank Sta=4994.3,4999.8
XS Rating Curve= 0 ,0
Exp/Cntr=0.3,0.1

Type RM Length L Ch R = 1 ,40195   ,439,439,439
BEGIN DESCRIPTION:
LITTLE JOSHUA CREEK 80.0
END DESCRIPTION:
XS GIS Cut Line= 3
      2018925.02       13863225.        2019325.       13863225.
      2019675.01     13862824.99
#Sta/Elev= 30
  4584.6 1654.32  4614.6 1651.29  4668.8 1647.63  4767.4 1641.13  4874.6 1633.91
  4904.6 1629.04  4934.6 1628.17  4944.6 1627.53  4954.6  1625.7  4964.5 1625.38
  4973.9 1625.36  4988.9 1625.36  4989.4 1624.86  4994.4 1625.36  5083.8 1625.64
    5098 1628.54  5118.9 1630.91  5183.4 1640.14  5210.9 1645.04  5218.5 1645.19
  5253.7 1650.35  5280.5 1653.43  5303.5 1656.03  5402.2  1664.2  5437.8 1668.24
  5466.3 1670.27  5488.1    1673  5494.7 1675.21    5509 1676.99  5516.1 1676.96
#Mann= 8 ,-1 , 0
  4584.6    .035       0  4668.8     .07       0  4767.4     .12       0
  4964.5     .07       0  4973.9     .12       0  4988.9     .05       0
  4994.4     .12       0  5280.5     .07       0
Bank Sta=4988.9,4994.4
XS Rating Curve= 0 ,0
Exp/Cntr=0.3,0.1

Type RM Length L Ch R = 1 ,39931   ,175,175,175
BEGIN DESCRIPTION:
LITTLE JOSHUA CREEK 79.5
END DESCRIPTION:
XS GIS Cut Line= 4
       2018791.6     13863453.93      2019433.76     13863290.03
      2019558.99     13863258.04      2019956.83     13863108.25
#Sta/Elev= 30
    4208 1664.45  4411.4 1648.99  4424.6 1647.23  4493.9 1644.23  4628.9 1637.76
  4705.4 1628.45  4710.6 1630.21  4737.1 1631.91  4787.2 1633.41  4799.8 1631.86
  4837.1 1632.06  4909.7 1630.92  4982.8 1625.91  4983.2 1625.41  4988.3 1625.91
  5017.1 1627.92    5028 1631.17  5043.8 1632.57  5052.9 1634.34  5077.7 1643.21
  5102.6 1644.83  5150.3  1654.8  5198.8 1661.14  5241.5 1664.01  5324.4 1672.68
  5366.5 1678.86  5394.1 1682.25  5412.5 1685.76    5419 1688.36  5425.1 1688.23
#Mann= 11 ,-1 , 0
    4208     .12       0  4411.4    .035       0  4493.9     .12       0
  4737.1     .07       0  4837.1     .12       0  4982.8     .05       0
  4988.3     .12       0  5043.8     .07       0  5150.3     .12       0
  5324.4     .07       0  5366.5     .12       0
Bank Sta=4982.8,4988.3
XS Rating Curve= 0 ,0
Exp/Cntr=0.3,0.1

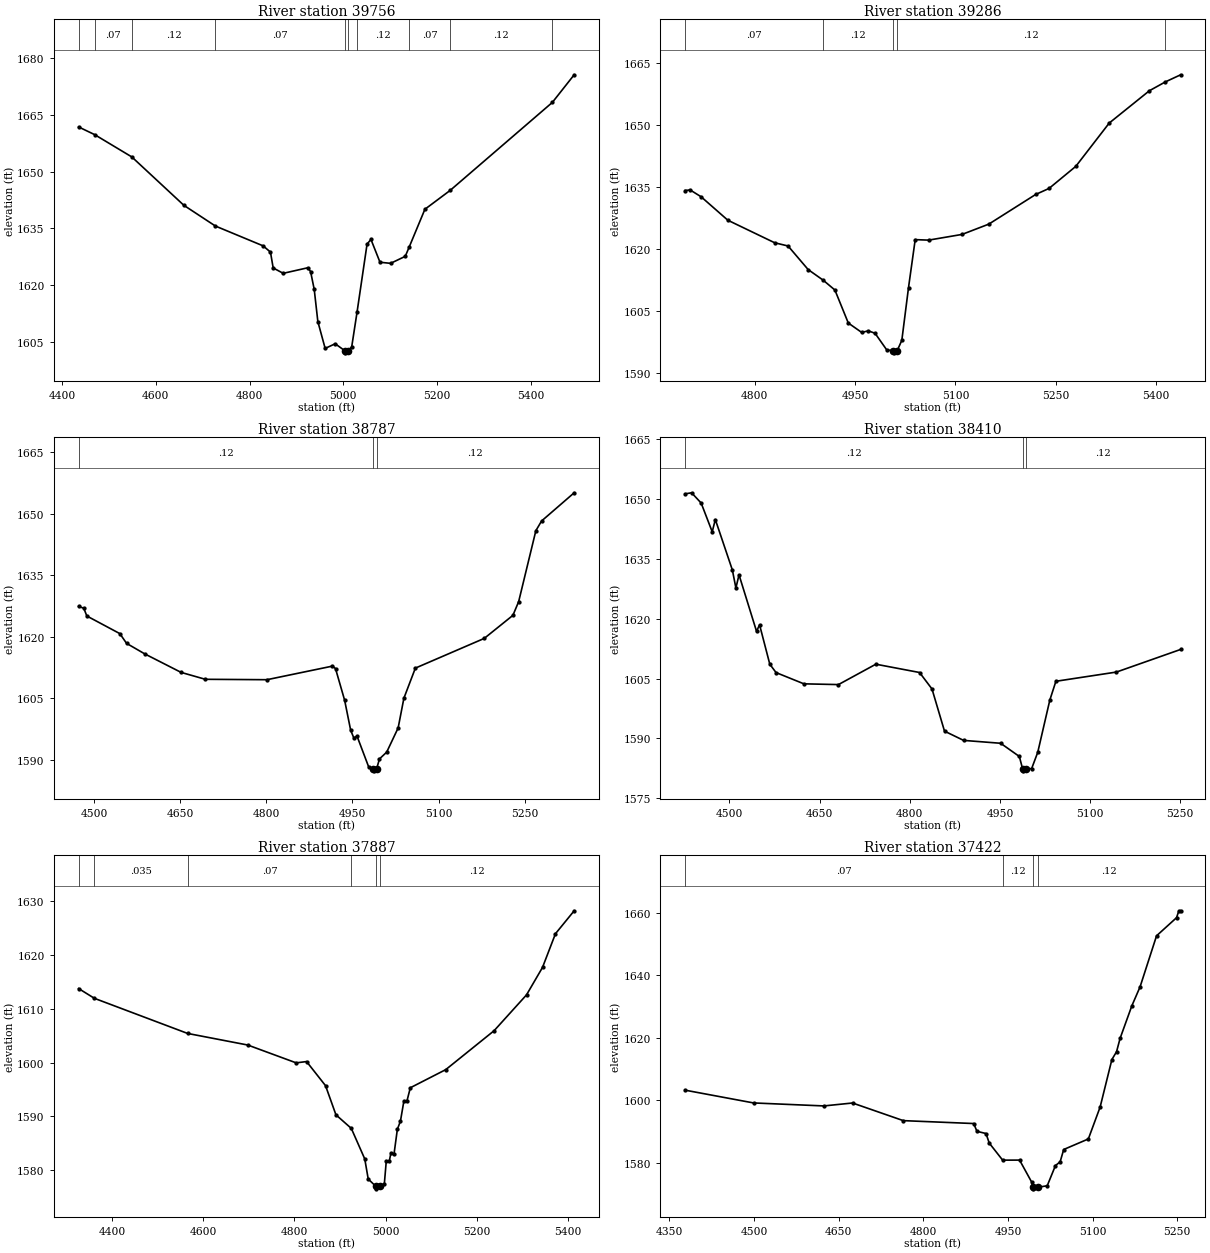
Type RM Length L Ch R = 1 ,39756   ,470,470,470
BEGIN DESCRIPTION:
LITTLE JOSHUA CREEK 79.0
END DESCRIPTION:
XS GIS Cut Line= 3
      2018993.52     13863662.93        2019475.       13863375.
       2019949.6     13863229.85
#Sta/Elev= 30
  4435.4 1661.84  4469.6 1659.81  4548.9 1653.91  4659.9 1641.12  4727.3 1635.63
  4829.1 1630.39  4844.7 1628.74  4850.5 1624.55  4871.9 1623.13  4924.4  1624.6
  4930.3 1623.61  4938.1 1618.86  4945.8 1610.37  4961.4 1603.27  4982.8  1604.5
    5004  1602.6  5004.5  1602.1  5009.7  1602.6    5018 1603.65  5029.4 1612.83
  5050.8 1630.86  5059.1  1632.1  5078.4 1626.06    5101 1625.77  5132.3 1627.62
    5141 1630.17  5174.2 1640.07    5228 1645.05  5446.2 1668.34  5492.7 1675.64
#Mann= 10 ,-1 , 0
  4435.4     .12       0  4469.6     .07       0  4548.9     .12       0
  4727.3     .07       0    5004     .05       0  5009.7     .07       0
  5029.4     .12       0    5141     .07       0    5228     .12       0
  5446.2     .07       0
Bank Sta=5004,5009.7
XS Rating Curve= 0 ,0
Exp/Cntr=0.3,0.1

Type RM Length L Ch R = 1 ,39286   ,499,499,499
BEGIN DESCRIPTION:
LITTLE JOSHUA CREEK 78.0
END DESCRIPTION:
XS GIS Cut Line= 3
      2019371.13      13863780.1        2019675.       13863775.
      2020111.68     13863775.76
#Sta/Elev= 30
    4696 1634.06  4703.5  1634.2  4719.9 1632.55  4759.9 1626.87  4829.9 1621.42
  4849.9 1620.64  4879.9 1614.94  4902.3 1612.38  4919.9 1609.99  4939.9 1602.01
  4959.9 1599.74  4969.9 1600.12  4979.9 1599.53  4997.4  1595.5    5007  1595.3
  5007.5  1594.8  5012.9  1595.3  5019.9 1597.82  5029.9 1610.58  5039.9 1622.18
  5059.9 1622.06  5109.9 1623.44  5149.9 1625.93  5219.9  1633.1  5239.9 1634.56
  5279.9  1639.9  5329.9 1650.38  5389.9 1658.19  5413.9 1660.34  5436.6 1662.05
#Mann= 5 ,-1 , 0
    4696     .07       0  4902.3     .12       0    5007     .05       0
  5012.9     .12       0  5413.9     .07       0
Bank Sta=5007,5012.9
XS Rating Curve= 0 ,0
Exp/Cntr=0.3,0.1

Type RM Length L Ch R = 1 ,38787   ,377,377,377
BEGIN DESCRIPTION:
LITTLE JOSHUA CREEK 77.0
END DESCRIPTION:
XS GIS Cut Line= 3
      2019175.84     13864105.62        2019675.       13864275.
      2020011.77     13864266.26
#Sta/Elev= 30
  4472.5  1627.4  4481.5 1626.94  4486.8 1625.05  4544.3 1620.75  4556.1 1618.37
  4587.8  1615.8  4651.1 1611.29  4693.4  1609.6  4800.8  1609.5  4915.1 1612.82
  4920.4 1612.21  4936.3 1604.48  4946.8 1597.17  4952.5 1595.22  4957.8 1595.77
  4978.5 1588.11  4986.2 1587.76  4986.7 1587.26  4992.1 1587.76    4997 1590.17
  5009.6 1591.82  5029.6 1597.74  5039.6 1604.98  5059.6 1612.33  5179.7 1619.58
  5229.7 1625.21  5239.7 1628.55  5269.7 1645.87  5279.7 1648.24  5336.5 1655.12
#Mann= 3 ,-1 , 0
  4472.5     .12       0  4986.2     .05       0  4992.1     .12       0
Bank Sta=4986.2,4992.1
XS Rating Curve= 0 ,0
Exp/Cntr=0.3,0.1

Type RM Length L Ch R = 1 ,38410   ,523,523,523
BEGIN DESCRIPTION:
LITTLE JOSHUA CREEK 76.0
END DESCRIPTION:
XS GIS Cut Line= 3
      2018989.25      13864457.2      2019536.08     13864609.09
      2019791.06     13864578.84
#Sta/Elev= 30
  4426.3 1651.32  4437.1 1651.59    4453 1649.02  4471.4 1641.81  4476.6 1644.88
  4504.9 1632.25  4510.8 1627.73    4516 1631.02  4545.1 1616.88  4550.2 1618.48
  4567.2 1608.62  4577.6 1606.52  4623.9  1603.7  4681.4 1603.51  4743.6 1608.62
  4816.3 1606.54    4837 1602.41  4857.8 1591.84  4889.6 1589.52  4951.2  1588.8
  4982.3 1585.49  4987.7 1582.39  4988.2 1581.89  4993.6 1582.39  5002.8 1582.47
  5012.9 1586.53    5033 1599.63  5043.1 1604.34  5143.8 1606.65  5250.6 1612.32
#Mann= 3 ,-1 , 0
  4426.3     .12       0  4987.7     .05       0  4993.6     .12       0
Bank Sta=4987.7,4993.6
XS Rating Curve= 0 ,0
Exp/Cntr=0.3,0.1

Type RM Length L Ch R = 1 ,37887   ,465,465,465
BEGIN DESCRIPTION:
LITTLE JOSHUA CREEK 75.0
END DESCRIPTION:
XS GIS Cut Line= 3
      2019214.91     13865364.29        2019625.       13864825.
      2019900.31     13864522.68
#Sta/Elev= 30
  4326.8 1613.78  4361.4 1611.96  4565.7 1605.42  4697.6 1603.26  4803.7 1599.94
  4826.5 1600.18  4868.1 1595.69  4890.9 1590.26  4924.6 1587.73  4954.1 1582.04
  4961.7 1578.29    4978 1576.97  4978.5 1576.47    4987 1576.97    4997 1577.38
  5001.2 1581.58  5007.7 1581.58  5011.4 1583.11  5018.2 1582.92  5025.6 1587.58
  5032.3 1589.07  5039.8 1592.79  5046.5 1592.81    5054  1595.3  5131.7 1598.68
  5237.8 1605.94  5308.7  1612.6  5343.8 1617.72  5372.2    1624  5413.2 1628.27
#Mann= 6 ,-1 , 0
  4326.8     .07       0  4361.4    .035       0  4565.7     .07       0
  4924.6     .12       0    4978     .05       0    4987     .12       0
Bank Sta=4978,4987
XS Rating Curve= 0 ,0
Exp/Cntr=0.3,0.1

Type RM Length L Ch R = 1 ,37422   ,459,459,459
BEGIN DESCRIPTION:
LITTLE JOSHUA CREEK 74.0
END DESCRIPTION:
XS GIS Cut Line= 3
      2019475.36     13865329.56        2020025.       13865025.
      2020225.02     13864874.99
#Sta/Elev= 30
  4377.7 1603.26    4499 1599.17  4623.7 1598.21  4674.5 1599.15  4764.5  1593.5
  4889.3 1592.57    4895 1590.08  4911.1 1589.37  4916.8 1586.32  4940.6 1580.84
  4970.6 1580.86  4992.3 1573.72  4993.6 1572.15  4994.1 1571.65  5002.6 1572.15
  5019.6 1572.63  5034.2 1579.11  5042.5  1580.3  5048.8 1584.25  5092.5 1587.63
  5113.4 1597.86  5134.2 1613.06  5142.5 1615.58  5148.8 1619.87  5169.6 1630.28
  5184.2 1636.37  5213.4 1652.71  5248.8 1658.51    5253 1660.73  5256.1 1660.73
#Mann= 4 ,-1 , 0
  4377.7     .07       0  4940.6     .12       0  4993.6     .05       0
  5002.6     .12       0
Bank Sta=4993.6,5002.6
XS Rating Curve= 0 ,0
Exp/Cntr=0.3,0.1

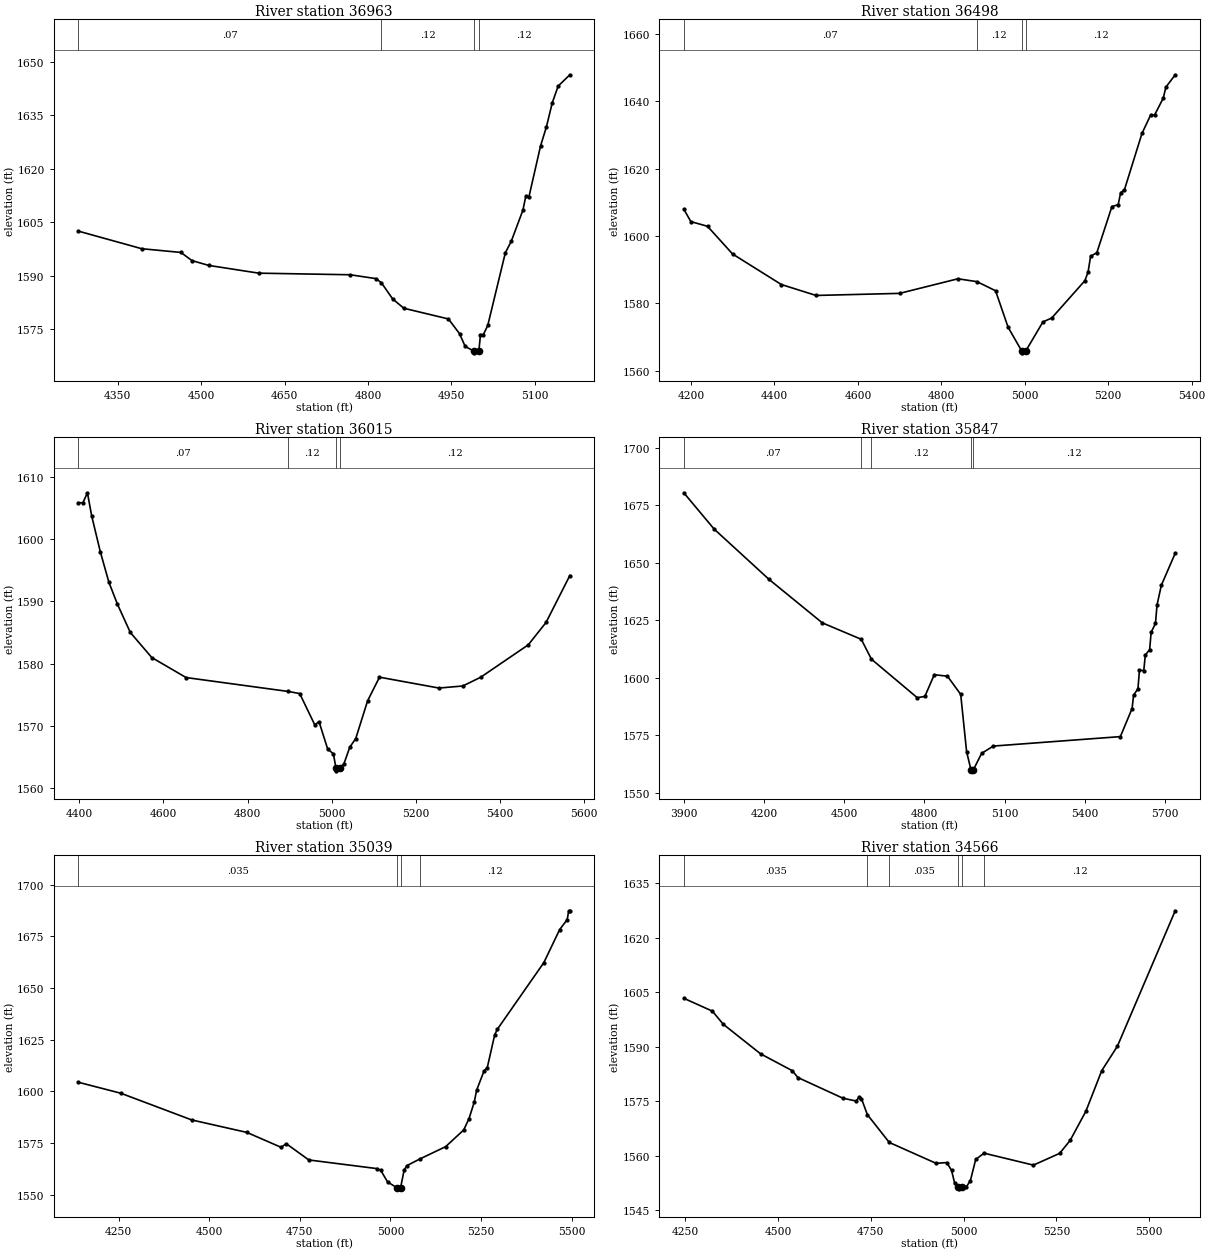
Type RM Length L Ch R = 1 ,36963   ,465,465,465
BEGIN DESCRIPTION:
LITTLE JOSHUA CREEK 73.0
END DESCRIPTION:
XS GIS Cut Line= 3
      2019501.31     13865420.73        2020225.       13865375.
      2020374.96     13865424.99
#Sta/Elev= 30
  4279.6 1602.52  4393.5 1597.59  4463.7 1596.55  4483.7 1594.26  4513.8 1592.91
  4603.6 1590.74  4768.1 1590.29  4814.4 1589.21  4824.2 1588.03  4844.4  1583.5
  4864.5  1580.9  4944.6  1577.9  4964.6 1573.76  4974.7 1570.19  4990.2  1568.9
  4990.7  1568.4  4999.3  1568.9  5002.2 1573.53  5007.4 1573.53  5015.3  1576.1
  5046.9 1596.48  5057.4 1599.63  5078.5 1608.43  5083.8 1612.44  5089.1 1612.02
  5110.1 1626.39  5120.7 1631.76  5131.2  1638.5  5141.8 1643.19  5162.8 1646.36
#Mann= 4 ,-1 , 0
  4279.6     .07       0  4824.2     .12       0  4990.2     .05       0
  4999.3     .12       0
Bank Sta=4990.2,4999.3
XS Rating Curve= 0 ,0
Exp/Cntr=0.3,0.1

Type RM Length L Ch R = 1 ,36498   ,483,483,483
BEGIN DESCRIPTION:
LITTLE JOSHUA CREEK 72.0
END DESCRIPTION:
XS GIS Cut Line= 3
       2019358.1     13865846.07        2020175.       13865825.
      2020474.98     13865625.01
#Sta/Elev= 30
  4182.8 1607.98  4199.7 1604.29  4239.7 1602.89  4299.7 1594.66  4416.6 1585.58
  4499.8 1582.33  4699.9 1582.95  4839.9 1587.29  4885.5 1586.43  4929.9 1583.73
    4960 1572.88  4992.9 1565.77  4993.4 1565.27  5002.1 1565.77  5043.5 1574.47
  5064.6 1575.63  5144.2 1586.75  5151.7 1589.33  5157.7 1593.97  5172.7 1595.06
  5208.8 1608.76  5223.8 1609.33  5229.8 1612.88  5238.8 1613.76  5280.9 1630.53
  5301.9 1636.05  5310.9 1635.94    5332 1641.04    5338 1644.23  5360.5 1647.94
#Mann= 4 ,-1 , 0
  4182.8     .07       0  4885.5     .12       0  4992.9     .05       0
  5002.1     .12       0
Bank Sta=4992.9,5002.1
XS Rating Curve= 0 ,0
Exp/Cntr=0.3,0.1

Type RM Length L Ch R = 1 ,36015   ,168,168,168
BEGIN DESCRIPTION:
LITTLE JOSHUA CREEK 71.0
END DESCRIPTION:
XS GIS Cut Line= 3
      2019483.97     13866392.95        2020075.       13866275.
      2020475.02     13865874.98
#Sta/Elev= 30
  4397.8 1605.91  4408.4 1605.88  4419.2  1607.5  4429.4 1603.75  4449.8 1598.01
  4470.2  1593.1  4490.6 1589.55  4521.2 1585.01  4572.2 1580.97  4653.8 1577.75
  4896.8 1575.51  4923.9 1575.17  4959.7 1570.14  4969.9 1570.64  4990.3 1566.26
    5004 1565.46    5010 1563.23  5010.5 1562.73  5019.2 1563.23  5028.8 1563.81
  5042.9 1566.53  5057.1 1567.92  5085.3    1574  5113.6 1577.81    5255 1576.06
  5311.6 1576.39    5354 1577.79  5467.2 1583.01  5509.6 1586.62  5566.2 1594.18
#Mann= 4 ,-1 , 0
  4397.8     .07       0  4896.8     .12       0    5010     .05       0
  5019.2     .12       0
Bank Sta=5010,5019.2
XS Rating Curve= 0 ,0
Exp/Cntr=0.3,0.1

Type RM Length L Ch R = 1 ,35847   ,808,808,808
BEGIN DESCRIPTION:
LITTLE JOSHUA CREEK 70.0
END DESCRIPTION:
XS GIS Cut Line= 3
      2019280.83     13867130.86      2020124.65     13866425.35
      2020774.99     13866075.01
#Sta/Elev= 30
  3900.1 1680.33  4013.4 1664.58  4219.1 1642.67  4418.2 1623.79  4564.2 1616.62
    4602    1608  4773.4 1591.25    4802 1591.79  4837.2 1601.24  4886.6 1600.58
  4936.1 1592.69  4958.2 1567.77  4974.4 1559.94  4974.9 1559.44  4983.7 1559.94
  5014.4 1567.04  5058.2 1570.21  5533.5 1574.32  5577.3 1586.54    5583 1592.42
  5599.2 1595.04  5604.9 1603.24  5621.1 1602.98  5626.8 1609.82    5643 1612.14
  5648.7 1619.69  5664.9 1623.53  5670.6 1631.52  5686.8 1640.12  5738.7 1654.04
#Mann= 5 ,-1 , 0
  3900.1     .07       0  4564.2    .035       0    4602     .12       0
  4974.4     .05       0  4983.7     .12       0
Bank Sta=4974.4,4983.7
XS Rating Curve= 0 ,0
Exp/Cntr=0.3,0.1

Type RM Length L Ch R = 1 ,35039   ,473,473,473
BEGIN DESCRIPTION:
LITTLE JOSHUA CREEK 69.0
END DESCRIPTION:
XS GIS Cut Line= 3
      2020087.33     13866909.43        2020875.       13866575.
      2021174.98     13866175.02
#Sta/Elev= 30
  4139.4 1604.37  4256.4 1599.07  4451.9 1586.16    4604 1580.13  4698.6 1572.91
  4712.7 1574.68    4775  1566.8  4962.5 1562.63  4973.4 1561.79  4992.4 1556.13
  5018.5 1553.33    5019 1552.83  5028.1 1553.33  5037.8 1561.79  5045.1 1564.02
  5081.9 1567.33  5152.4 1573.23  5202.4 1581.34    5217 1586.84  5231.6 1594.92
  5237.8 1600.49  5258.7    1610    5267 1611.24  5287.8 1627.35  5295.1 1630.02
  5423.3 1662.24    5467 1678.23  5487.8 1683.06    5492 1687.33  5495.1 1687.33
#Mann= 4 ,-1 , 0
  4139.4    .035       0  5018.5    .035       0  5028.1    .035       0
  5081.9     .12       0
Bank Sta=5018.5,5028.1
XS Rating Curve= 0 ,0
Exp/Cntr=0.3,0.1

Type RM Length L Ch R = 1 ,34566   ,327,327,327
BEGIN DESCRIPTION:
LITTLE JOSHUA CREEK 68.0
END DESCRIPTION:
XS GIS Cut Line= 3
      2020412.81      13867421.6        2021025.       13866975.
      2021425.02     13866574.98
#Sta/Elev= 30
  4246.5 1603.38  4323.5 1599.84  4352.7 1596.24  4453.1  1588.1  4538.9 1583.43
  4553.6 1581.57  4674.8 1575.88  4710.4  1575.1  4718.9 1576.19    4725 1575.75
  4740.8 1571.36  4799.9 1563.69  4925.9 1557.95  4954.8 1558.15  4967.6    1556
  4976.1 1552.42  4985.9 1551.42  4986.4 1550.92  4995.6 1551.42  5007.8 1551.52
  5018.4 1553.19  5032.6    1559  5055.1 1560.74  5188.1 1557.45  5258.8 1560.69
  5287.1 1564.26  5329.5  1572.3    5372 1583.43  5414.4 1590.21    5570 1627.47
#Mann= 6 ,-1 , 0
  4246.5    .035       0  4740.8     .12       0  4799.9    .035       0
  4985.9    .035       0  4995.6    .035       0  5055.1     .12       0
Bank Sta=4985.9,4995.6
XS Rating Curve= 0 ,0
Exp/Cntr=0.3,0.1