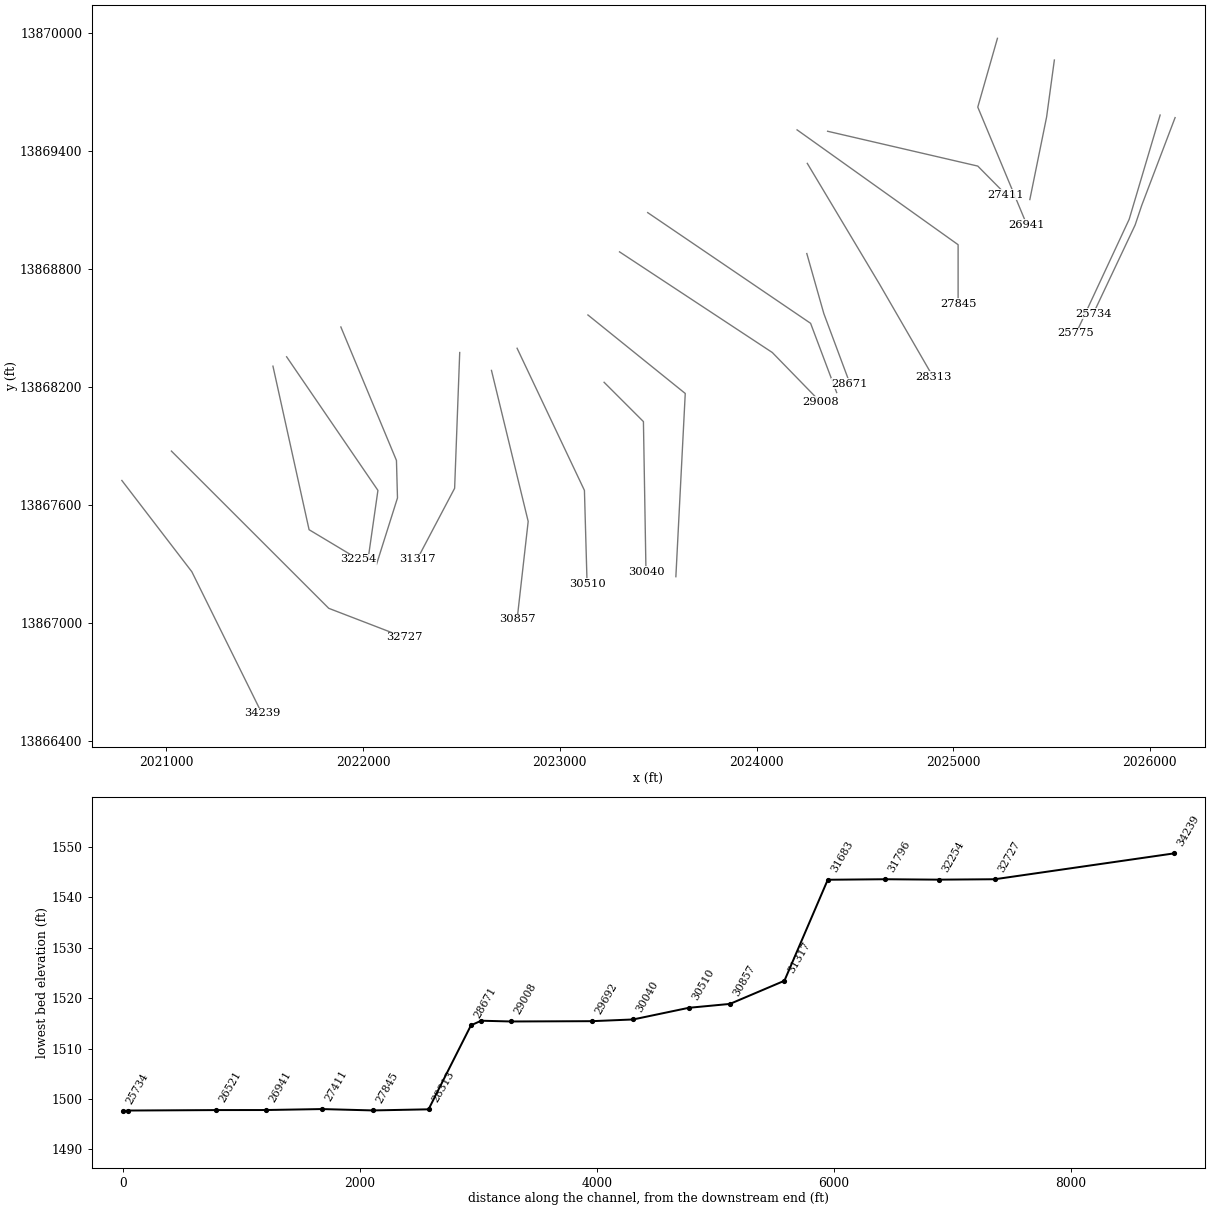
HEC-RAS study LITTLE JOSHUA CREEK.prj: LITTLE JOSHUA CREEK Base Level Engineering

--- LITTLE JOSHUA CREEK.g01 (geometry) --- (continued)

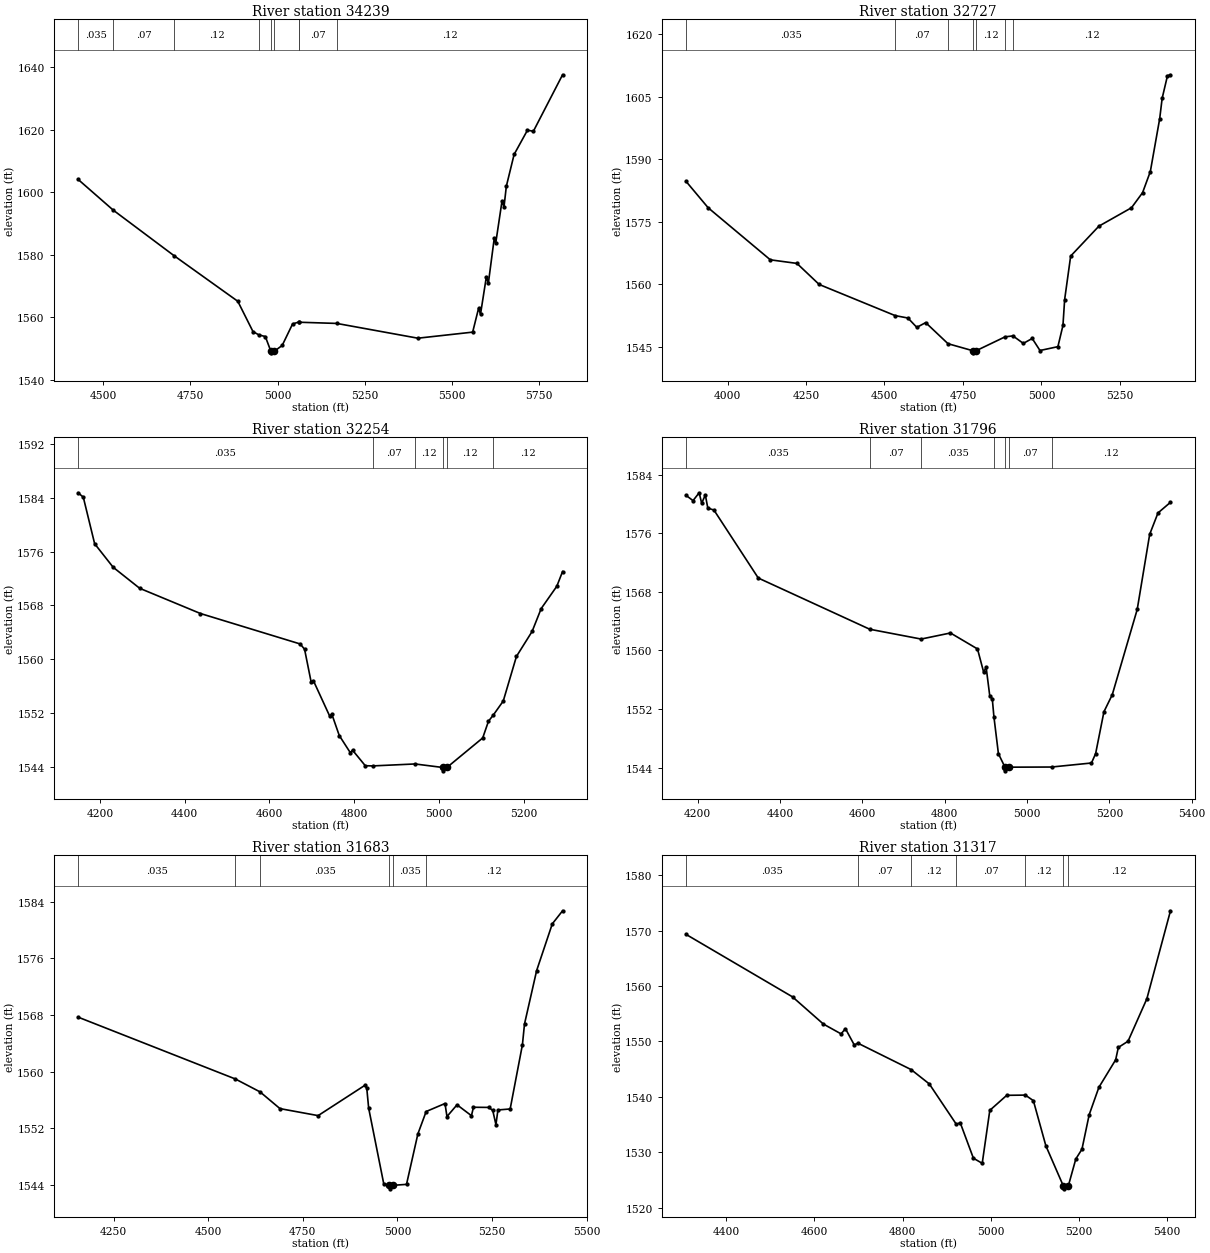
Type RM Length L Ch R = 1 ,34239   ,1512,1512,1512
BEGIN DESCRIPTION:
LITTLE JOSHUA CREEK 67.0
END DESCRIPTION:
XS GIS Cut Line= 3
      2020773.07      13867725.4      2021128.96       13867261.
      2021484.88     13866540.49
#Sta/Elev= 30
  4427.8 1604.11  4528.7 1594.27  4703.8 1579.65  4885.6 1565.15  4929.2 1555.45
    4946 1554.41  4964.5 1553.88  4980.4 1549.17  4980.9 1548.67  4990.2 1549.17
  5012.9 1551.04  5042.6  1557.9  5061.2 1558.55  5062.1 1558.45  5169.3 1558.07
  5401.7 1553.35  5558.8 1555.29  5575.7 1562.88  5581.3 1561.03  5598.1 1573.01
  5603.7 1570.86  5620.6 1585.23  5624.9 1583.75    5643 1597.24  5648.6 1595.29
  5655.3 1601.91  5677.6 1612.09  5715.9 1619.84  5732.8 1619.49  5816.5 1637.55
#Mann= 9 ,-1 , 0
  4427.8    .035       0  4528.7     .07       0  4703.8     .12       0
    4946     .07       0  4980.4     .05       0  4990.2     .07       0
  5061.2    .035       0  5062.1     .07       0  5169.3     .12       0
Bank Sta=4980.4,4990.2
XS Rating Curve= 0 ,0
Exp/Cntr=0.3,0.1

Type RM Length L Ch R = 1 ,32727   ,473,473,473
BEGIN DESCRIPTION:
LITTLE JOSHUA CREEK 66.0
END DESCRIPTION:
XS GIS Cut Line= 3
      2021025.01     13867874.99        2021825.       13867075.
      2022209.68     13866926.81
#Sta/Elev= 30
  3867.7 1584.69  3938.4 1578.34  4136.4 1565.86  4221.2    1565    4292 1559.95
  4534.1 1552.48  4574.8  1551.9  4603.1 1549.66  4631.4  1550.8  4702.5 1545.74
  4781.9 1544.05  4782.4 1543.55  4791.9 1544.05  4884.4 1547.39  4909.4 1547.61
  4942.5 1545.81  4970.8    1547  4995.5 1544.11  5052.6 1545.03  5068.7 1550.11
  5074.1 1556.33  5093.3 1566.76  5183.2 1573.93  5287.1 1578.35  5322.4 1581.97
  5347.1 1587.03    5377 1599.75  5384.8 1604.61  5401.7 1610.01  5411.3 1610.24
#Mann= 7 ,-1 , 0
  3867.7    .035       0  4534.1     .07       0  4702.5     .12       0
  4781.9     .05       0  4791.9     .12       0  4884.4    .033       0
  4909.4     .12       0
Bank Sta=4781.9,4791.9
XS Rating Curve= 0 ,0
Exp/Cntr=0.3,0.1

Type RM Length L Ch R = 1 ,32254   ,458,458,458
BEGIN DESCRIPTION:
LITTLE JOSHUA CREEK 65.0
END DESCRIPTION:
XS GIS Cut Line= 3
      2021541.29       13868307.        2021725.       13867475.
      2021975.01       13867325.
#Sta/Elev= 30
  4148.3 1584.72  4160.6 1584.07  4187.4 1577.16  4231.1 1573.67  4293.7 1570.55
  4437.1 1566.81  4672.6 1562.29  4682.9 1561.51  4698.6 1556.59  4703.7 1556.85
  4742.2 1551.59  4747.3 1551.87  4764.8 1548.71    4791 1546.15  4796.1 1546.54
  4826.2 1544.23  4843.6  1544.2  4943.6 1544.49  5008.9 1543.97  5009.4 1543.47
  5018.9 1543.97  5103.4 1548.35    5117 1550.83  5128.1 1551.72  5151.9 1553.83
    5183 1560.44    5220 1564.15  5241.4 1567.54  5278.3 1570.85  5291.9 1573.04
#Mann= 6 ,-1 , 0
  4148.3    .035       0  4843.6     .07       0  4943.6     .12       0
  5008.9     .05       0  5018.9     .12       0  5128.1     .12       0
Bank Sta=5008.9,5018.9
XS Rating Curve= 0 ,0
Exp/Cntr=0.3,0.1

Type RM Length L Ch R = 1 ,31796   ,479,479,479
BEGIN DESCRIPTION:
LITTLE JOSHUA CREEK 64.0
END DESCRIPTION:
XS GIS Cut Line= 3
      2021610.75     13868354.73        2022075.       13867675.
        2022025.       13867325.
#Sta/Elev= 30
  4171.7 1581.16  4188.8 1580.44  4203.7 1581.51  4209.8 1580.08  4218.7 1581.21
  4224.7 1579.42  4239.6 1579.15  4347.3 1569.87    4618 1562.88  4742.8 1561.54
    4814 1562.37  4879.7 1560.19  4894.6 1557.03  4900.7 1557.68  4909.5 1553.78
  4915.6  1553.4  4919.6 1550.92  4930.5 1545.89  4946.4 1544.05  4946.9 1543.55
  4956.5 1544.05  5059.5 1544.07  5156.5 1544.62  5166.6  1545.9  5186.8 1551.62
    5207 1553.94  5267.6 1565.58  5297.9 1575.84  5318.1 1578.76  5348.4 1580.21
#Mann= 7 ,-1 , 0
  4171.7    .035       0    4618     .07       0  4742.8    .035       0
  4919.6     .07       0  4946.4     .05       0  4956.5     .07       0
  5059.5     .12       0
Bank Sta=4946.4,4956.5
XS Rating Curve= 0 ,0
Exp/Cntr=0.3,0.1

Type RM Length L Ch R = 1 ,31683   ,366,366,366
BEGIN DESCRIPTION:
LITTLE JOSHUA CREEK 63.5
END DESCRIPTION:
XS GIS Cut Line= 4
      2021886.58     13868506.39      2022169.26     13867827.22
      2022174.47     13867636.55        2022068.     13867299.03
#Sta/Elev= 30
  4156.1  1567.7  4571.5 1558.97    4637 1557.14  4689.6 1554.78  4790.4 1553.79
    4914 1558.07    4919 1557.65    4924 1554.84    4964 1544.12    4979 1543.95
  4979.5 1543.45  4989.1 1543.95    5024 1544.08    5054  1551.2  5075.9 1554.37
  5125.7  1555.5  5130.9 1553.66  5157.5 1555.32  5195.6 1553.78  5200.9 1554.97
  5241.4 1554.95  5251.9 1554.52  5260.3 1552.52  5265.6 1554.59  5297.9 1554.73
  5330.3  1563.8  5335.8 1566.73  5367.9 1574.28  5409.2 1580.87  5436.4 1582.72
#Mann= 6 ,-1 , 0
  4156.1    .035       0  4571.5     .07       0    4637    .035       0
    4979    .035       0  4989.1    .035       0  5075.9     .12       0
Bank Sta=4979,4989.1
XS Rating Curve= 0 ,0
Exp/Cntr=0.3,0.1

Type RM Length L Ch R = 1 ,31317   ,460,460,460
BEGIN DESCRIPTION:
LITTLE JOSHUA CREEK 63.0
END DESCRIPTION:
XS GIS Cut Line= 3
       2022490.9     13868376.43      2022465.03     13867685.71
        2022275.     13867325.01
#Sta/Elev= 30
  4308.8 1569.31  4550.4 1558.04  4620.4 1553.14  4660.5 1551.37  4670.5  1552.3
  4690.5 1549.37  4698.7 1549.69  4819.4 1544.93  4860.6 1542.35  4922.2 1535.04
  4930.7 1535.37  4960.7 1528.95  4980.7 1528.03  4997.9 1537.58  5036.3 1540.29
  5078.5 1540.33  5096.7 1539.33  5125.1 1531.18  5164.8 1523.93  5165.3 1523.43
  5175.9 1523.93    5193 1528.82  5206.9 1530.57  5223.3 1536.79  5245.3 1541.73
  5283.4  1546.7  5289.4 1548.92  5311.4 1550.04  5354.1 1557.69  5407.7 1573.56
#Mann= 7 ,-1 , 0
  4308.8    .035       0  4698.7     .07       0  4819.4     .12       0
  4922.2     .07       0  5078.5     .12       0  5164.8     .05       0
  5175.9     .12       0
Bank Sta=5164.8,5175.9
XS Rating Curve= 0 ,0
Exp/Cntr=0.3,0.1

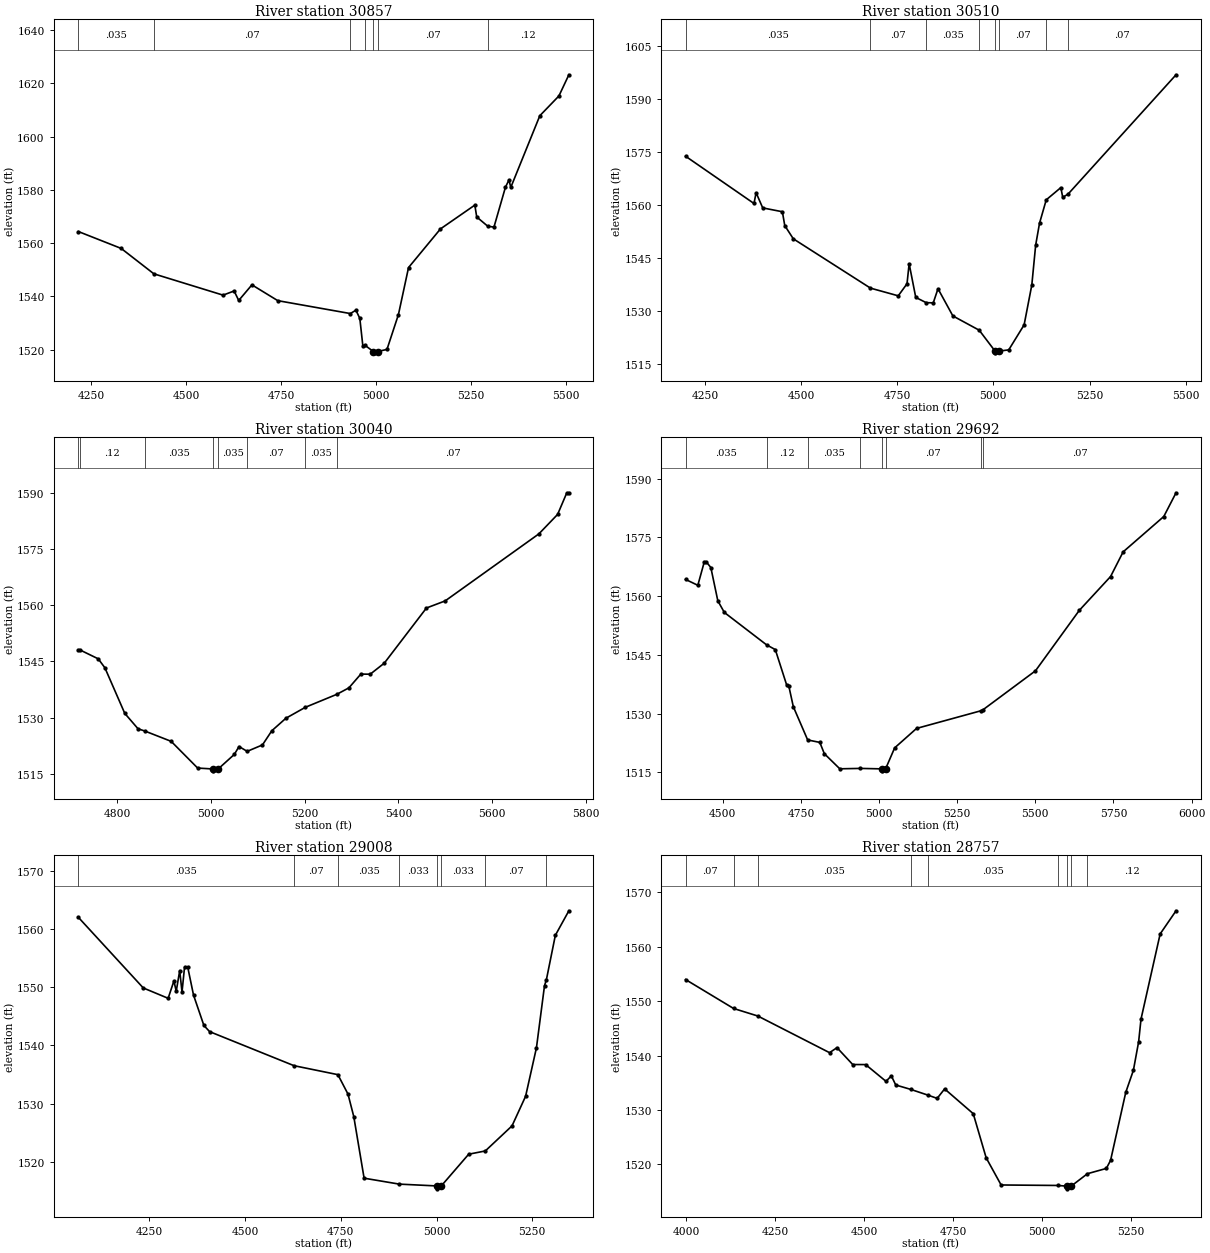
Type RM Length L Ch R = 1 ,30857   ,347,347,347
BEGIN DESCRIPTION:
LITTLE JOSHUA CREEK 62.0
END DESCRIPTION:
XS GIS Cut Line= 3
      2022652.39     13868285.35      2022839.03     13867517.08
      2022782.73     13867018.97
#Sta/Elev= 30
  4216.4 1564.35  4329.1 1558.02  4415.3 1548.48  4597.5 1540.49  4626.6 1542.05
  4638.7 1538.49  4673.5 1544.35  4741.6 1538.42  4932.7 1533.58  4947.4 1534.84
  4957.7 1531.75  4965.8 1521.26  4971.1 1521.69  4993.3 1519.34  4993.8 1518.84
  5004.5 1519.34  5029.2 1520.12  5059.4 1533.21    5086 1550.84  5170.1 1565.34
  5260.6 1574.27  5265.6 1569.82  5294.7 1566.34    5311 1566.02  5341.2 1580.96
  5350.4 1583.69  5355.4 1580.94  5431.8 1607.81  5482.1 1615.23  5508.3 1623.17
#Mann= 7 ,-1 , 0
  4216.4    .035       0  4415.3     .07       0  4932.7    .035       0
  4971.1     .07       0  4993.3     .05       0  5004.5     .07       0
  5294.7     .12       0
Bank Sta=4993.3,5004.5
XS Rating Curve= 0 ,0
Exp/Cntr=0.3,0.1

Type RM Length L Ch R = 1 ,30510   ,470,470,470
BEGIN DESCRIPTION:
LITTLE JOSHUA CREEK 61.0
END DESCRIPTION:
XS GIS Cut Line= 3
      2022782.63     13868398.12        2023125.       13867675.
      2023138.51     13867200.27
#Sta/Elev= 30
  4199.9  1573.8  4377.8  1560.4  4383.3 1563.45  4400.5 1559.15  4451.6 1558.06
  4457.8 1554.14    4480 1550.39  4680.6 1536.41  4752.8 1534.23  4775.6 1537.65
  4781.1 1543.34  4798.3 1533.78  4825.3  1532.3  4843.8 1532.23  4856.1 1536.24
  4894.8 1528.53  4963.3 1524.48  5004.4 1518.57  5004.9 1518.07  5015.6 1518.57
    5040 1518.91    5080    1526    5100 1537.31    5110 1548.59    5120 1554.79
  5137.5 1561.44  5175.4  1564.9  5180.4 1562.16    5194 1563.03  5474.9 1596.88
#Mann= 8 ,-1 , 0
  4199.9    .035       0  4680.6     .07       0  4825.3    .035       0
  4963.3     .07       0  5004.4     .05       0  5015.6     .07       0
  5137.5     .12       0    5194     .07       0
Bank Sta=5004.4,5015.6
XS Rating Curve= 0 ,0
Exp/Cntr=0.3,0.1

Type RM Length L Ch R = 1 ,30040   ,348,348,348
BEGIN DESCRIPTION:
LITTLE JOSHUA CREEK 60.0
END DESCRIPTION:
XS GIS Cut Line= 3
        2023225.       13868225.        2023425.       13868025.
      2023437.99     13867261.05
#Sta/Elev= 30
  4716.8 1548.13  4719.5 1548.13  4759.2 1545.71  4773.4 1543.31  4815.8 1531.13
  4844.1 1527.01  4858.3 1526.42  4914.8 1523.65  4971.4  1516.5    5004 1516.26
  5004.5 1515.76  5015.2 1516.26  5049.6 1520.15  5059.7 1522.26  5077.1 1520.97
  5109.7 1522.69  5129.7 1526.48  5159.7 1529.82  5201.4 1532.76  5268.4 1536.22
  5294.2 1537.95  5319.7 1541.63  5339.7  1541.6  5369.7 1544.55  5459.7  1559.3
  5499.7  1561.2  5699.7 1579.12  5739.7 1584.33  5759.3 1590.11  5763.7 1590.11
#Mann= 8 ,-1 , 0
  4716.8    .035       0  4719.5     .12       0  4858.3    .035       0
    5004    .035       0  5015.2    .035       0  5077.1     .07       0
  5201.4    .035       0  5268.4     .07       0
Bank Sta=5004,5015.2
XS Rating Curve= 0 ,0
Exp/Cntr=0.3,0.1

Type RM Length L Ch R = 1 ,29692   ,684,684,684
BEGIN DESCRIPTION:
LITTLE JOSHUA CREEK 59.0
END DESCRIPTION:
XS GIS Cut Line= 3
      2023142.82     13868567.45      2023637.64     13868168.12
      2023589.95      13867235.9
#Sta/Elev= 30
  4380.8 1564.29  4420.1 1562.79  4440.9 1568.81  4447.8  1568.7  4461.7 1567.33
  4484.1 1558.82  4504.9 1555.86  4639.8  1547.6    4668 1546.37  4704.8 1537.22
  4711.2 1537.07  4725.6  1531.8  4771.5 1523.31  4810.4 1522.68  4824.8  1519.8
  4874.3 1515.94  4940.4 1516.04  5009.5 1515.92    5010 1515.42  5020.8 1515.92
  5049.8 1521.28  5119.9 1526.25  5326.5 1530.77  5332.3    1531  5500.4 1540.96
  5640.6 1556.39  5740.7 1565.03  5780.8 1571.32  5910.9 1580.35  5950.1 1586.41
#Mann= 8 ,-1 , 0
  4380.8    .035       0  4639.8     .12       0  4771.5    .035       0
  4940.4     .07       0  5009.5     .05       0  5020.8     .07       0
  5326.5    .035       0  5332.3     .07       0
Bank Sta=5009.5,5020.8
XS Rating Curve= 0 ,0
Exp/Cntr=0.3,0.1

Type RM Length L Ch R = 1 ,29008   ,251,251,251
BEGIN DESCRIPTION:
LITTLE JOSHUA CREEK 58.0
END DESCRIPTION:
XS GIS Cut Line= 3
      2023303.46      13868888.6      2024080.35     13868376.46
      2024324.97     13868125.03
#Sta/Elev= 30
  4064.3 1562.01  4233.8 1549.88  4298.8  1548.1  4313.9 1551.09  4319.9 1549.31
    4329 1552.86    4335 1549.17  4341.6 1553.43    4350 1553.44  4365.1 1548.65
  4392.2 1543.43  4407.2 1542.37  4627.7 1536.52  4742.2 1534.98  4768.6 1531.64
  4783.7 1527.78  4810.7 1517.19  4902.7 1516.17  5000.2 1515.86  5000.7 1515.36
  5012.3 1515.86  5083.9 1521.31  5127.3 1521.87  5197.1 1526.18  5232.6 1531.27
  5260.9  1539.6    5282 1550.29  5286.7 1551.24  5310.3 1558.93  5345.6 1563.14
#Mann= 8 ,-1 , 0
  4064.3    .035       0  4627.7     .07       0  4742.2    .035       0
  4902.7    .033       0  5000.2    .033       0  5012.3    .033       0
  5127.3     .07       0  5286.7     .12       0
Bank Sta=5000.2,5012.3
XS Rating Curve= 0 ,0
Exp/Cntr=0.3,0.1

Type RM Length L Ch R = 1 ,28757   ,86,86,86
BEGIN DESCRIPTION:
LITTLE JOSHUA CREEK 57.0
END DESCRIPTION:
XS GIS Cut Line= 3
      2023446.67     13869088.26        2024275.       13868525.
      2024407.45     13868172.88
#Sta/Elev= 30
  3998.6 1553.97  4133.5 1548.65  4201.8 1547.26  4403.1 1540.53  4424.1 1541.45
  4468.2 1538.35  4504.5 1538.34  4561.7 1535.26  4576.7 1536.27  4589.1 1534.59
  4631.3 1533.78  4680.3 1532.71  4705.4 1532.13  4726.4 1533.87  4806.8 1529.32
  4843.1 1521.21  4885.1 1516.22    5044 1516.13  5069.8 1516.01  5070.3 1515.51
  5081.9 1516.01  5127.6 1518.29  5180.7 1519.26  5192.6 1520.74  5235.3 1533.25
  5256.7 1537.29  5271.4 1542.53  5278.1  1546.7  5331.9 1562.35  5376.5  1566.6
#Mann= 9 ,-1 , 0
  3998.6     .07       0  4133.5     .12       0  4201.8    .035       0
  4631.3     .07       0  4680.3    .035       0    5044    .033       0
  5069.8    .035       0  5081.9    .033       0  5127.6     .12       0
Bank Sta=5069.8,5081.9
XS Rating Curve= 0 ,0
Exp/Cntr=0.3,0.1

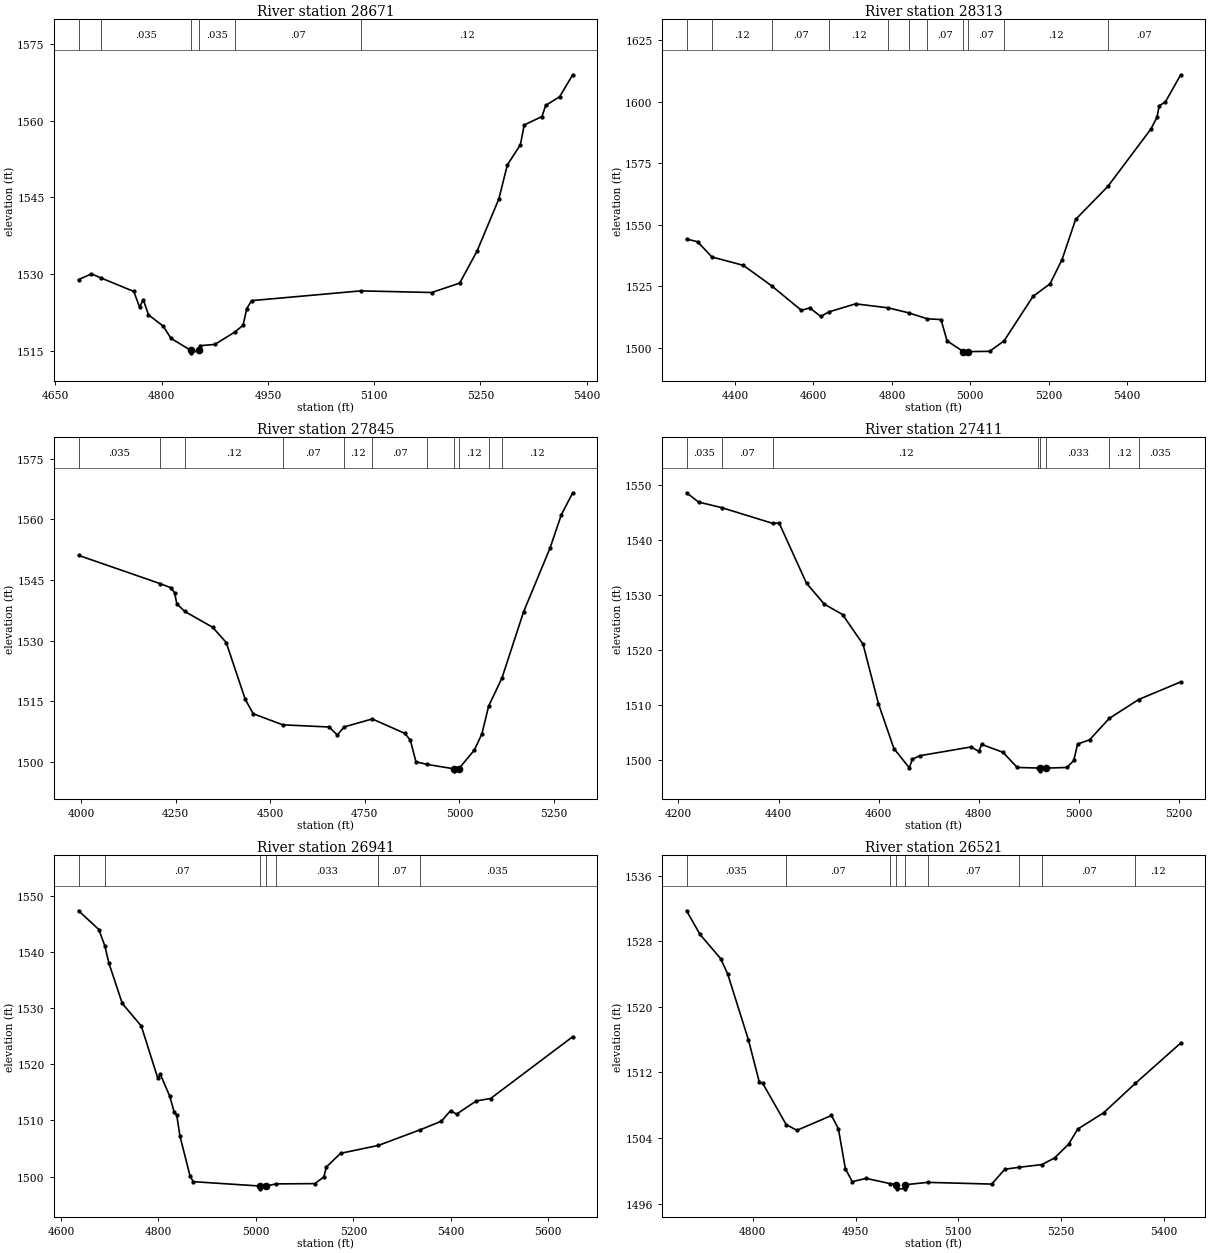
Type RM Length L Ch R = 1 ,28671   ,358,358,358
BEGIN DESCRIPTION:
LITTLE JOSHUA CREEK 56.5
END DESCRIPTION:
XS GIS Cut Line= 3
      2024255.72     13868879.97       2024342.1       13868575.
      2024474.91      13868218.5
#Sta/Elev= 30
  4682.8 1528.92    4701 1530.03    4714 1529.26  4760.7  1526.6  4768.9 1523.54
  4774.1 1524.98  4781.5 1522.03  4802.3 1519.81  4813.2 1517.43  4841.1  1515.1
  4841.6  1514.6  4853.2  1515.1  4854.3    1516    4875 1516.24  4903.5 1518.67
    4915    1520  4920.2 1523.26    4927  1524.8  5081.2 1526.71  5181.2 1526.39
  5220.7 1528.23  5245.2  1534.5    5276 1544.69  5287.9 1551.31  5306.4 1555.29
  5311.7 1559.13  5336.7 1560.77    5342 1562.94  5361.7 1564.65  5380.2 1568.94
#Mann= 6 ,-1 , 0
  4682.8     .07       0    4714    .035       0  4841.1     .05       0
  4853.2    .035       0  4903.5     .07       0  5081.2     .12       0
Bank Sta=4841.1,4853.2
XS Rating Curve= 0 ,0
Exp/Cntr=0.3,0.1

Type RM Length L Ch R = 1 ,28313   ,468,468,468
BEGIN DESCRIPTION:
LITTLE JOSHUA CREEK 56.0
END DESCRIPTION:
XS GIS Cut Line= 3
      2024258.22     13869338.74        2024625.       13868725.
      2024897.69     13868252.99
#Sta/Elev= 30
  4276.4 1544.22  4304.6 1543.12    4341 1536.94  4421.4 1533.52  4493.8 1525.15
  4569.2 1515.23  4590.6 1516.21  4618.6 1512.77  4639.9 1514.62  4707.4 1517.87
    4791 1516.24  4842.6 1514.22  4890.2 1511.79  4925.2 1511.48  4940.8  1502.8
  4982.4 1498.45  4982.9 1497.95  4994.5 1498.45  5049.1 1498.56    5086  1502.8
  5160.1 1520.96  5203.2 1525.99  5233.9 1535.87  5268.6 1552.22  5350.7 1565.62
  5460.1 1588.87  5475.9 1593.68  5481.7  1598.4  5497.5    1600  5536.5 1611.02
#Mann= 11 ,-1 , 0
  4276.4     .07       0    4341     .12       0  4493.8     .07       0
  4639.9     .12       0    4791    .035       0  4842.6     .12       0
  4890.2     .07       0  4982.4     .05       0  4994.5     .07       0
    5086     .12       0  5350.7     .07       0
Bank Sta=4982.4,4994.5
XS Rating Curve= 0 ,0
Exp/Cntr=0.3,0.1

Type RM Length L Ch R = 1 ,27845   ,434,434,434
BEGIN DESCRIPTION:
LITTLE JOSHUA CREEK 55.0
END DESCRIPTION:
XS GIS Cut Line= 3
      2024206.24     13869509.26        2025025.       13868925.
        2025025.     13868625.05
#Sta/Elev= 30
  3993.5 1551.11  4208.3 1544.13  4238.5 1543.05  4247.1 1541.82  4253.3 1539.09
  4274.2 1537.21  4347.9 1533.29  4383.6 1529.52    4434 1515.44  4454.9 1511.88
  4532.9 1509.13  4655.4 1508.59  4677.3  1506.6  4695.1  1508.6  4769.5 1510.58
  4855.5 1507.02  4870.2 1505.33    4885 1499.98  4914.9 1499.31  4985.9 1498.23
  4986.4 1497.73  4998.1 1498.23  5039.3 1502.87  5059.3 1506.88  5077.1 1513.77
  5112.3 1520.72  5169.3 1537.08  5239.3 1552.91  5269.3 1561.18  5299.3 1566.61
#Mann= 11 ,-1 , 0
  3993.5    .035       0  4208.3     .07       0  4274.2     .12       0
  4532.9     .07       0  4695.1     .12       0  4769.5     .07       0
  4914.9     .12       0  4985.9     .05       0  4998.1     .12       0
  5077.1     .07       0  5112.3     .12       0
Bank Sta=4985.9,4998.1
XS Rating Curve= 0 ,0
Exp/Cntr=0.3,0.1

Type RM Length L Ch R = 1 ,27411   ,470,470,470
BEGIN DESCRIPTION:
LITTLE JOSHUA CREEK 54.0
END DESCRIPTION:
XS GIS Cut Line= 3
      2024361.51     13869502.15        2025125.       13869325.
      2025267.92     13869180.38
#Sta/Elev= 30
  4216.1 1548.52  4240.2 1546.83  4286.7 1545.81  4388.6 1542.95    4401 1543.03
  4455.8 1532.07  4491.4 1528.28  4527.7  1526.4  4568.7 1520.99  4599.5 1510.18
  4630.3 1502.05  4661.1 1498.54  4667.1 1500.09  4681.6 1500.74  4784.3 1502.34
  4800.2 1501.52  4805.4  1502.8    4848 1501.38  4876.7 1498.61  4919.1 1498.51
  4921.9  1498.5  4922.4    1498  4934.1  1498.5    4976 1498.61  4989.6 1499.89
  4997.3 1502.87  5021.1 1503.63  5060.3 1507.51    5119 1510.95  5203.2 1514.16
#Mann= 8 ,-1 , 0
  4216.1    .035       0  4286.7     .07       0  4388.6     .12       0
  4919.1    .033       0  4921.9    .033       0  4934.1    .033       0
  5060.3     .12       0    5119    .035       0
Bank Sta=4921.9,4934.1
XS Rating Curve= 0 ,0
Exp/Cntr=0.3,0.1

Type RM Length L Ch R = 1 ,26941   ,420,420,420
BEGIN DESCRIPTION:
LITTLE JOSHUA CREEK 53.0
END DESCRIPTION:
XS GIS Cut Line= 3
      2025224.99     13869974.95        2025125.       13869625.
      2025375.02     13869024.96
#Sta/Elev= 30
    4636 1547.34  4677.6    1544  4689.9 1541.09  4698.4 1537.97  4725.7 1530.83
  4764.7 1526.82  4798.5 1517.54  4803.7 1518.23  4823.2 1514.29  4832.3 1511.46
  4837.5 1510.92    4844 1507.22  4864.8 1500.08  4871.3 1499.09  5008.1 1498.31
  5008.6 1497.81    5021 1498.31  5040.9 1498.69  5120.7 1498.74  5139.2 1499.91
  5144.6 1501.72  5173.8 1504.14  5251.1 1505.54  5337.6 1508.35  5380.7 1509.87
  5399.2 1511.73  5411.6 1511.12  5452.2 1513.47  5481.5  1513.9    5650 1524.91
#Mann= 7 ,-1 , 0
    4636    .035       0  4689.9     .07       0  5008.1     .05       0
    5021     .07       0  5040.9    .033       0  5251.1     .07       0
  5337.6    .035       0
Bank Sta=5008.1,5021
XS Rating Curve= 0 ,0
Exp/Cntr=0.3,0.1

Type RM Length L Ch R = 1 ,26521   ,746,746,746
BEGIN DESCRIPTION:
LITTLE JOSHUA CREEK 52.0
END DESCRIPTION:
XS GIS Cut Line= 3
       2025514.4     13869864.57        2025475.       13869575.
      2025389.68     13869154.71
#Sta/Elev= 30
  4703.4 1531.73  4723.1 1528.84  4753.4 1525.87  4763.5    1524  4793.8 1515.95
  4809.6 1510.82  4814.6 1510.67  4848.8 1505.64  4864.4 1504.94  4914.9 1506.75
    4925 1505.12  4935.1 1500.28  4945.2 1498.67  4965.4 1499.08  4999.6 1498.45
  5009.4  1498.3  5009.9  1497.8  5021.9  1497.8  5022.4  1498.3  5055.2 1498.59
  5148.7 1498.38  5167.8 1500.19  5188.6 1500.43  5221.9 1500.76  5240.5 1501.57
  5260.9 1503.24  5274.2 1505.09    5312 1507.08  5358.3 1510.67  5424.5 1515.59
#Mann= 9 ,-1 , 0
  4703.4    .035       0  4848.8     .07       0  4999.6    .033       0
  5009.4    .033       0  5022.4    .033       0  5055.2     .07       0
  5188.6    .035       0  5221.9     .07       0  5358.3     .12       0
Bank Sta=5009.4,5022.4
XS Rating Curve= 0 ,0
Exp/Cntr=0.3,0.1

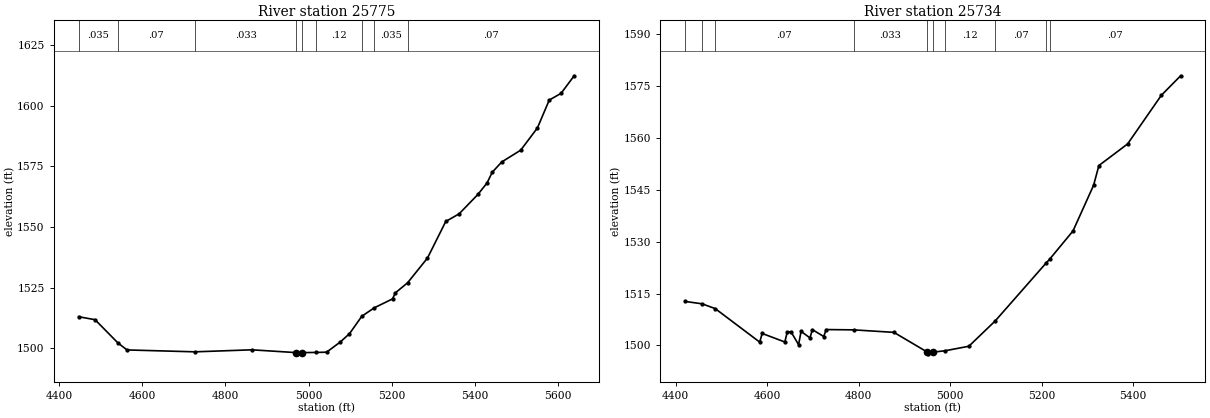
Type RM Length L Ch R = 1 ,25775   ,41,41,41
BEGIN DESCRIPTION:
LITTLE JOSHUA CREEK 51.0
END DESCRIPTION:
XS GIS Cut Line= 3
      2026052.21     13869584.64      2025894.85      13869054.4
      2025624.98     13868474.96
#Sta/Elev= 30
  4446.9 1513.02  4486.4 1511.79  4541.2 1502.25  4563.3 1499.32  4726.9 1498.54
  4863.8 1499.37  4971.1 1498.21  4971.6 1497.71  4984.1 1498.21  5018.2 1498.29
  5043.5 1498.39  5076.6 1502.61  5098.6 1506.02  5128.3 1513.22  5158.4 1516.71
  5202.2 1520.37  5208.9 1522.85  5238.4 1527.01  5286.2 1537.21  5330.3 1552.32
  5362.3 1555.44  5407.5 1563.44  5429.6  1568.2    5442 1572.59  5464.8 1576.84
  5510.6 1581.72  5550.8  1590.9  5579.2 1602.38  5607.6 1605.15  5639.2  1612.4
#Mann= 9 ,-1 , 0
  4446.9    .035       0  4541.2     .07       0  4726.9    .033       0
  4971.1    .033       0  4984.1    .033       0  5018.2     .12       0
  5128.3     .07       0  5158.4    .035       0  5238.4     .07       0
Bank Sta=4971.1,4984.1
XS Rating Curve= 0 ,0
Exp/Cntr=0.3,0.1

Type RM Length L Ch R = 1 ,25734   ,569,569,569
BEGIN DESCRIPTION:
LITTLE JOSHUA CREEK 50.5
END DESCRIPTION:
XS GIS Cut Line= 4
      2026128.27      13869571.6       2025958.7     13869125.31
        2025925.       13869025.      2025711.59     13868572.88
#Sta/Elev= 30
  4420.3 1512.72  4457.4 1512.03  4486.2 1510.64  4583.4 1500.96  4588.8 1503.46
  4638.3    1501  4643.7 1503.93    4652 1503.89  4668.4 1500.21  4673.8 1504.07
  4693.2 1502.18  4698.6 1504.56  4723.3 1502.58  4728.7 1504.59  4788.6  1504.5
  4876.7 1503.78  4949.8 1498.07  4950.3 1497.57  4962.8 1498.07  4988.5 1498.46
  5040.5 1499.76  5098.1 1507.07  5209.9 1523.89  5217.3 1524.95  5268.2 1533.09
  5313.2 1546.29  5324.8    1552  5387.6 1558.25  5461.4 1572.32  5503.5 1577.95
#Mann= 10 ,-1 , 0
  4420.3     .07       0  4457.4    .035       0  4486.2     .07       0
  4788.6    .033       0  4949.8     .05       0  4962.8    .033       0
  4988.5     .12       0  5098.1     .07       0  5209.9    .035       0
  5217.3     .07       0
Bank Sta=4949.8,4962.8
XS Rating Curve= 0 ,0
Exp/Cntr=0.3,0.1