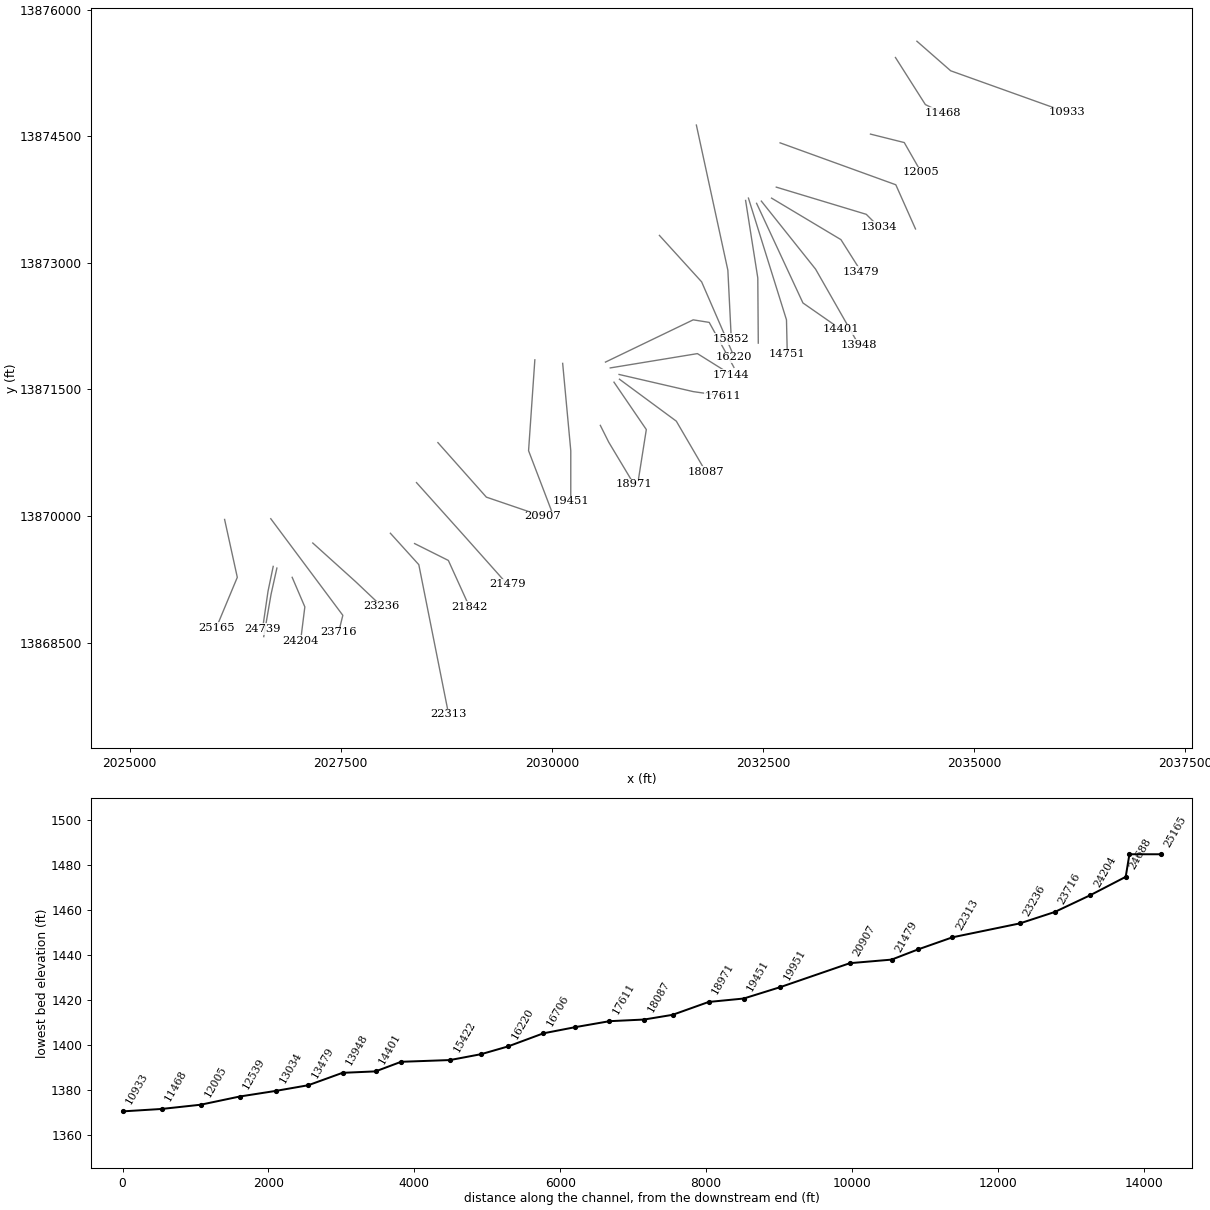
HEC-RAS study LITTLE JOSHUA CREEK.prj: LITTLE JOSHUA CREEK Base Level Engineering

--- LITTLE JOSHUA CREEK.g01 (geometry) --- (continued)

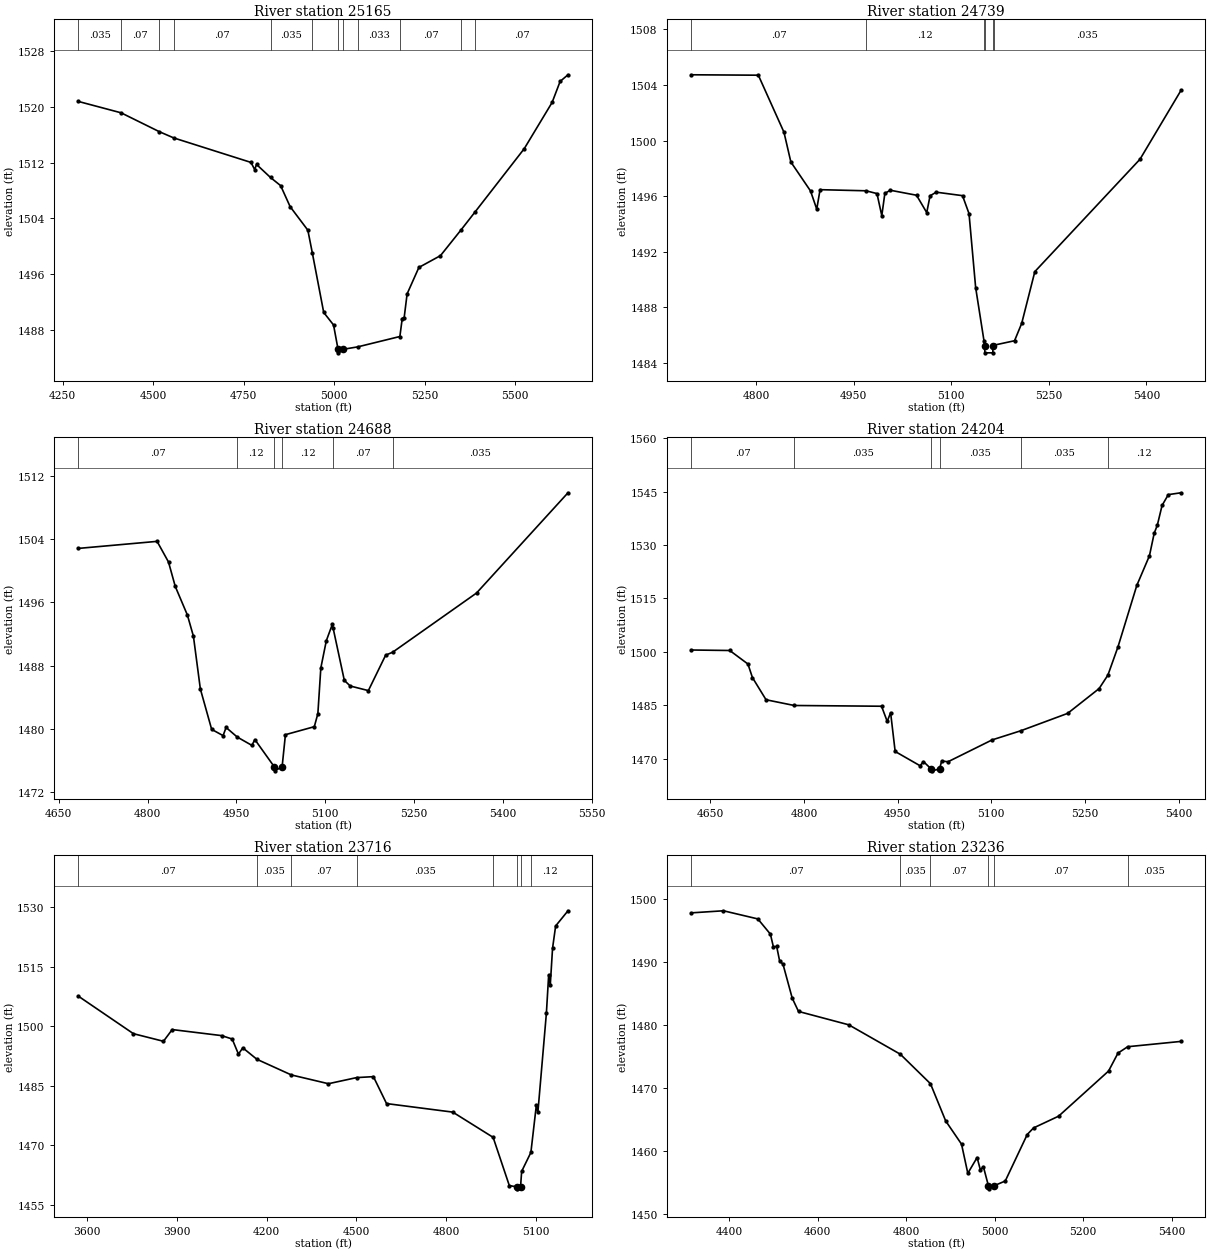
Type RM Length L Ch R = 1 ,25165   ,426,426,426
BEGIN DESCRIPTION:
LITTLE JOSHUA CREEK 50.0
END DESCRIPTION:
XS GIS Cut Line= 3
      2026124.62     13869960.67        2026275.       13869275.
      2026024.99     13868674.97
#Sta/Elev= 30
  4293.5 1520.77  4411.5 1519.14  4517.3 1516.43    4557 1515.54  4770.2 1512.03
  4780.4    1511  4785.5 1511.74  4824.1 1509.87  4852.1  1508.7  4878.3 1505.69
  4927.2 1502.32  4939.8    1499    4971 1490.53  4998.2 1488.73  5010.6 1485.24
  5011.1 1484.74  5023.6 1485.24  5064.5 1485.59  5181.3 1487.08  5187.8 1489.66
  5193.2  1489.8  5201.3 1493.19  5233.8 1496.98  5293.4 1498.67  5350.4 1502.37
  5389.2 1504.95  5524.7    1514  5601.6 1520.62  5623.8 1523.64  5645.5 1524.59
#Mann= 12 ,-1 , 0
  4293.5    .035       0  4411.5     .07       0  4517.3    .035       0
    4557     .07       0  4824.1    .035       0  4939.8     .07       0
  5010.6     .05       0  5023.6     .07       0  5064.5    .033       0
  5181.3     .07       0  5350.4    .035       0  5389.2     .07       0
Bank Sta=5010.6,5023.6
XS Rating Curve= 0 ,0
Exp/Cntr=0.3,0.1

Type RM Length L Ch R = 1 ,24739   ,51,51,51
BEGIN DESCRIPTION:
LITTLE JOSHUA CREEK 49.5
END DESCRIPTION:
XS GIS Cut Line= 3
      2026700.31     13869404.48      2026639.06     13869110.94
      2026573.68     13868662.75
#Sta/Elev= 30
  4700.2 1504.73  4803.3  1504.7  4842.7  1500.6  4853.3 1498.46  4883.5 1496.38
  4893.1 1495.07  4898.2 1496.47  4968.8 1496.39  4985.7 1496.19  4993.1  1494.6
  4997.8  1496.2  5006.1 1496.43  5046.5 1496.07  5062.2 1494.82  5067.3 1496.03
  5076.8 1496.29  5117.2 1496.04  5127.2 1494.75  5137.4 1489.43  5150.3 1485.58
  5151.1 1485.24  5151.6 1484.74  5163.7 1484.74  5164.2 1485.24  5165.5 1485.29
  5197.2 1485.61  5208.2 1486.86  5228.4 1490.58  5390.1 1498.66    5453  1503.6
#Mann= 6 ,-1 , 0
  4700.2     .07       0  4968.8     .12       0  5150.3     .07       0
  5151.1     .05       0  5164.2     .07       0  5165.5    .035       0
Bank Sta=5151.1,5164.2
XS Rating Curve= 0 ,0
Exp/Cntr=0.3,0.1

Type RM Length L Ch R = 1 ,24688   ,484,484,484
BEGIN DESCRIPTION:
LITTLE JOSHUA CREEK 49.0
END DESCRIPTION:
XS GIS Cut Line= 3
      2026743.98     13869384.79        2026675.       13869075.
      2026588.21     13868572.72
#Sta/Elev= 30
  4682.9 1502.81  4815.9  1503.7  4835.2 1501.09  4846.6 1498.01  4867.1 1494.39
  4877.3 1491.71    4889 1485.05  4908.1 1479.94  4927.4 1479.15  4932.5 1480.18
  4951.3 1478.97    4976 1477.92  4981.1 1478.65    5014  1475.2  5014.5  1474.7
  5027.1  1475.2  5032.7 1479.27  5081.5 1480.28  5087.5 1481.93  5092.5  1487.7
  5101.8 1491.15  5111.9  1493.2  5113.4 1492.69  5132.2 1486.13  5142.2 1485.42
  5172.8 1484.84    5202 1489.32  5213.8 1489.69  5355.5 1497.17    5510 1509.84
#Mann= 6 ,-1 , 0
  4682.9     .07       0  4951.3     .12       0    5014     .05       0
  5027.1     .12       0  5113.4     .07       0  5213.8    .035       0
Bank Sta=5014,5027.1
XS Rating Curve= 0 ,0
Exp/Cntr=0.3,0.1

Type RM Length L Ch R = 1 ,24204   ,488,488,488
BEGIN DESCRIPTION:
LITTLE JOSHUA CREEK 48.0
END DESCRIPTION:
XS GIS Cut Line= 3
        2026925.     13869274.99        2027075.       13868925.
        2027025.     13868524.99
#Sta/Elev= 30
  4619.7 1500.52  4681.3 1500.38  4710.4 1496.58  4717.6 1492.78  4739.4 1486.54
  4784.5 1484.93  4924.3 1484.72  4933.4 1480.45  4938.8 1482.93  4946.1 1472.01
    4986    1468  4991.4 1469.16    5004 1467.07  5004.5 1466.57  5017.1 1467.07
  5020.6 1469.34  5030.7 1469.12  5101.3 1475.26  5147.4 1477.84  5222.2 1482.71
  5272.6 1489.68  5286.7 1493.47  5302.8 1501.39    5333 1518.68  5353.2    1527
  5360.8 1533.32  5365.8 1535.58  5373.4 1541.13  5383.4 1544.17  5403.6 1544.69
#Mann= 6 ,-1 , 0
  4619.7     .07       0  4784.5    .035       0    5004    .035       0
  5017.1    .035       0  5147.4    .035       0  5286.7     .12       0
Bank Sta=5004,5017.1
XS Rating Curve= 0 ,0
Exp/Cntr=0.3,0.1

Type RM Length L Ch R = 1 ,23716   ,480,480,480
BEGIN DESCRIPTION:
LITTLE JOSHUA CREEK 47.0
END DESCRIPTION:
XS GIS Cut Line= 3
       2026671.5     13869969.34        2027525.       13868825.
      2027475.01     13868625.03
#Sta/Elev= 30
    3572 1507.59  3755.9 1498.14    3856 1496.23  3885.2 1499.18  4049.9 1497.66
  4085.3  1496.8  4106.2    1493  4120.8 1494.58  4167.7  1491.7  4282.7 1487.76
  4406.4 1485.55  4500.5 1487.09  4556.5 1487.33  4600.3 1480.55  4821.3  1478.4
  4955.9 1472.05  5009.9 1459.92  5034.3 1459.59  5034.8 1459.09  5047.4 1459.59
  5051.1 1463.49  5081.9 1468.25  5100.1 1480.14  5105.2 1478.32  5133.6 1503.28
  5141.3    1513  5146.5 1510.29  5154.2 1519.66  5164.5 1525.26  5205.7 1529.08
#Mann= 8 ,-1 , 0
    3572     .07       0  4167.7    .035       0  4282.7     .07       0
  4500.5    .035       0  4955.9     .07       0  5034.3     .05       0
  5047.4     .07       0  5081.9     .12       0
Bank Sta=5034.3,5047.4
XS Rating Curve= 0 ,0
Exp/Cntr=0.3,0.1

Type RM Length L Ch R = 1 ,23236   ,923,923,923
BEGIN DESCRIPTION:
LITTLE JOSHUA CREEK 46.0
END DESCRIPTION:
XS GIS Cut Line= 3
      2027169.11     13869681.42        2027675.       13869225.
      2027983.82     13868932.81
#Sta/Elev= 30
  4314.2 1497.73  4386.9 1498.06  4464.6 1496.77    4493 1494.36  4499.7 1492.36
  4507.2  1492.4  4513.9 1490.09  4521.4 1489.61  4542.3 1484.22  4556.5 1482.11
  4670.1 1479.99  4786.6 1475.33  4854.7 1470.66  4889.1 1464.76  4924.9 1461.08
  4939.1 1456.46  4960.1 1458.96  4967.5    1457  4974.3 1457.51  4985.6  1454.5
  4986.1    1454  4998.7  1454.5  5023.7 1455.24  5073.4 1462.61  5087.6 1463.65
  5144.2 1465.51  5257.1 1472.66  5278.5 1475.51  5300.4 1476.52  5420.7 1477.36
#Mann= 6 ,-1 , 0
  4314.2     .07       0  4786.6    .035       0  4854.7     .07       0
  4985.6     .05       0  4998.7     .07       0  5300.4    .035       0
Bank Sta=4985.6,4998.7
XS Rating Curve= 0 ,0
Exp/Cntr=0.3,0.1

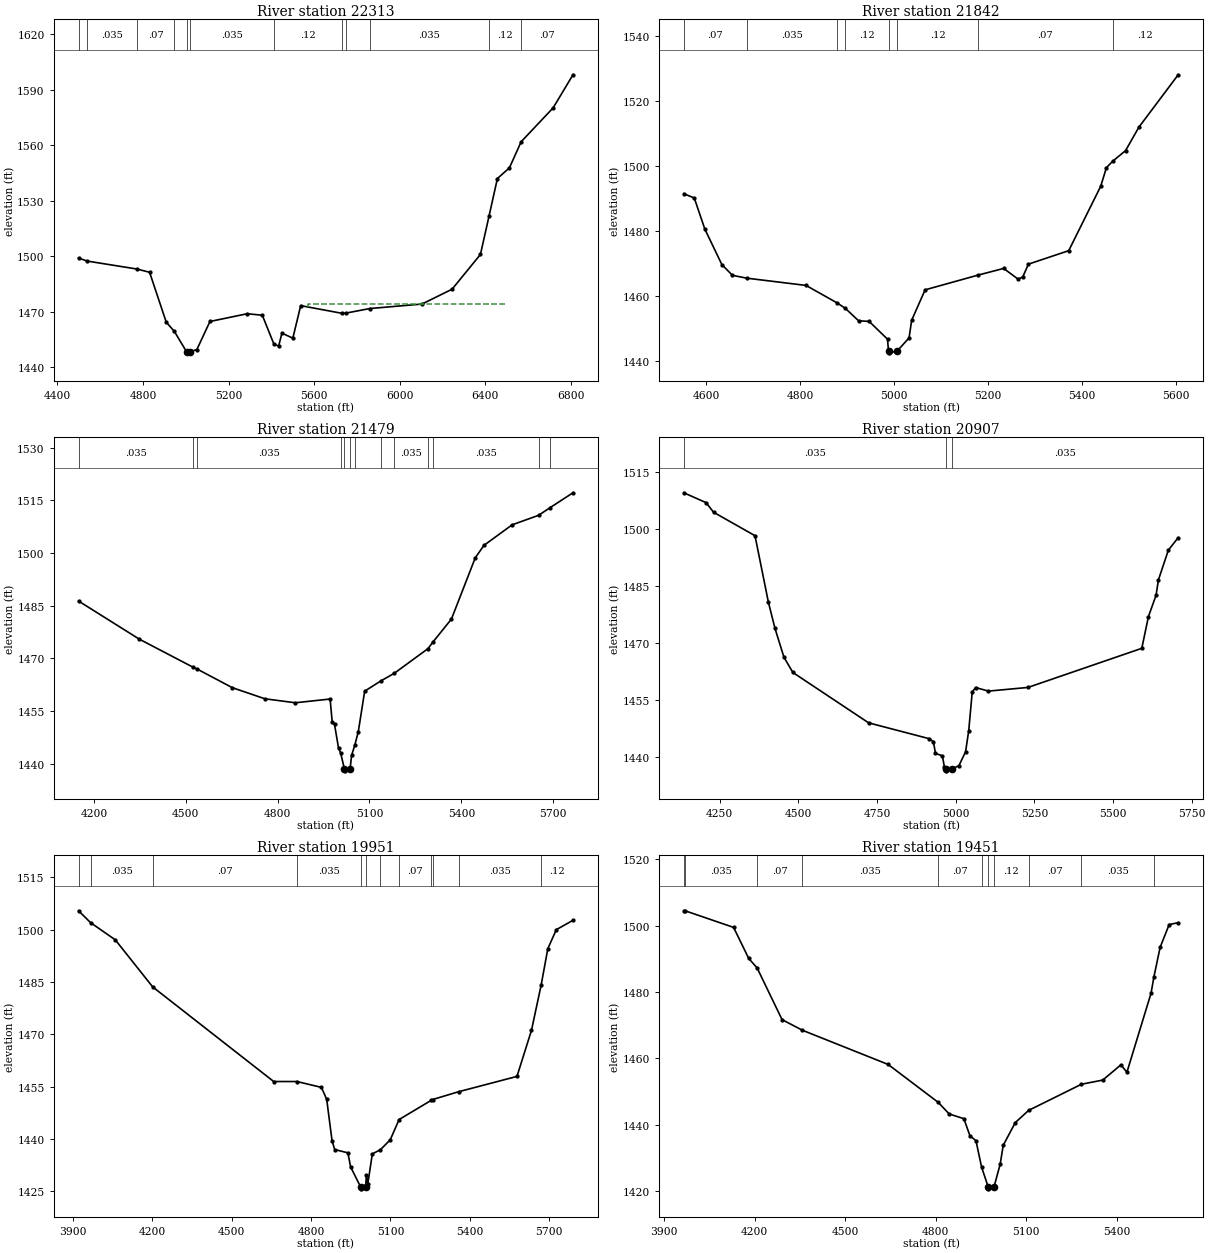
Type RM Length L Ch R = 1 ,22313   ,471,471,471
BEGIN DESCRIPTION:
LITTLE JOSHUA CREEK 44.0
END DESCRIPTION:
XS GIS Cut Line= 3
      2028088.22     13869797.18        2028425.       13869425.
      2028778.46     13867650.69
#Sta/Elev= 30
  4498.6 1499.09  4538.2 1497.45    4770 1493.16  4830.5 1491.39  4908.3 1464.44
  4946.5 1459.38  5003.8 1448.32  5004.3 1447.82  5017.7 1448.32  5051.5 1449.58
  5112.7 1464.77  5286.6 1468.96  5357.4 1468.16  5412.3 1452.36  5433.9 1451.55
  5449.2 1458.46  5500.2 1455.76  5536.9 1473.35    5732 1469.14  5747.4 1469.28
  5859.9 1471.77  6103.9  1474.2  6244.5 1482.22  6377.1 1501.02    6417 1521.61
  6456.4 1542.08  6512.6 1547.87  6567.4 1561.95  6716.9 1580.29  6809.7 1598.17
#Mann= 12 ,-1 , 0
  4498.6     .07       0  4538.2    .035       0    4770     .07       0
  4946.5    .035       0  5003.8    .035       0  5017.7    .035       0
  5412.3     .12       0    5732     .07       0  5747.4     .12       0
  5859.9    .035       0    6417     .12       0  6567.4     .07       0
#XS Ineff= 2 ,-1
 5289.17 5570.28 1468.55 5572.48    6500 1474.36
Permanent Ineff=
       F       F
Bank Sta=5003.8,5017.7
XS Rating Curve= 0 ,0
Exp/Cntr=0.3,0.1

Type RM Length L Ch R = 1 ,21842   ,363,363,363
BEGIN DESCRIPTION:
LITTLE JOSHUA CREEK 43.0
END DESCRIPTION:
XS GIS Cut Line= 3
      2028375.03     13869674.99        2028775.       13869475.
      2029024.99     13868925.03
#Sta/Elev= 30
    4553 1491.45  4575.3 1490.13  4597.7 1480.56    4634 1469.61  4656.4 1466.32
  4686.5 1465.45  4812.9 1463.21  4878.8 1457.84  4896.5 1456.15  4924.7 1452.32
  4947.1 1452.13  4986.2 1446.65  4988.3 1442.95  4988.8 1442.45  5006.4 1442.95
    5032 1447.06  5037.5 1452.47  5066.1 1461.85  5178.4 1466.37  5233.1 1468.44
  5263.8 1465.15  5273.7  1465.8  5285.8 1469.76  5371.5 1473.91  5439.6 1493.77
  5451.6 1499.45  5464.8 1501.43  5492.3 1504.71  5520.8 1511.96  5604.3 1528.07
#Mann= 8 ,-1 , 0
    4553     .07       0  4686.5    .035       0  4878.8     .07       0
  4896.5     .12       0  4988.3     .05       0  5006.4     .12       0
  5178.4     .07       0  5464.8     .12       0
Bank Sta=4988.3,5006.4
XS Rating Curve= 0 ,0
Exp/Cntr=0.3,0.1

Type RM Length L Ch R = 1 ,21479   ,572,572,572
BEGIN DESCRIPTION:
LITTLE JOSHUA CREEK 42.0
END DESCRIPTION:
XS GIS Cut Line= 3
      2028397.49     13870397.17      2028951.38     13869779.41
      2029473.47     13869192.94
#Sta/Elev= 30
  4149.8 1486.28  4347.9 1475.44  4525.1 1467.37  4538.1 1466.86  4652.1  1461.6
  4758.3 1458.44  4857.7  1457.3  4971.4 1458.37  4978.1 1451.94  4985.8 1451.14
    4999 1444.36  5005.7 1443.04  5018.2 1438.41  5018.7 1437.91  5036.6 1438.41
  5041.6 1442.31  5052.1 1445.25  5063.4 1449.03  5084.3 1460.61  5137.6 1463.55
  5180.3 1465.66  5291.2 1472.73  5308.4 1474.73  5367.7 1481.15  5445.5  1498.6
  5473.9 1502.15  5565.9    1508  5652.4 1510.71  5689.1 1512.85  5764.7 1517.13
#Mann= 13 ,-1 , 0
  4149.8    .035       0  4525.1    .063       0  4538.1    .035       0
  5005.7    .094       0  5018.2    .035       0  5036.6    .094       0
  5052.1    .035       0  5137.6    .094       0  5180.3    .035       0
  5291.2    .094       0  5308.4    .035       0  5652.4     .07       0
  5689.1    .035       0
Bank Sta=5018.2,5036.6
XS Rating Curve= 0 ,0
Exp/Cntr=0.3,0.1

Type RM Length L Ch R = 1 ,20907   ,956,956,956
BEGIN DESCRIPTION:
LITTLE JOSHUA CREEK 41.0
END DESCRIPTION:
XS GIS Cut Line= 3
      2028651.06      13870870.7        2029225.       13870225.
      2029894.52     13869996.63
#Sta/Elev= 30
    4136 1509.59  4206.7    1507  4230.6 1504.46  4362.3 1498.28  4404.9 1480.74
  4425.8 1473.86  4454.3 1466.26  4482.7 1462.24  4723.5 1448.97    4915 1444.82
  4929.2 1444.03  4935.9 1440.92  4957.7  1440.3  4964.4 1437.29  4969.3 1436.83
  4969.8 1436.33  4987.8 1436.83  5010.3 1437.68  5031.6 1441.38  5041.6 1446.95
  5052.7 1457.12  5063.3 1458.28  5104.3 1457.34  5229.6  1458.3  5591.6 1468.61
  5612.7 1476.98    5637  1482.6  5644.4 1486.62  5676.1  1494.5  5707.3 1497.77
#Mann= 3 ,-1 , 0
    4136    .035       0  4969.3    .035       0  4987.8    .035       0
Bank Sta=4969.3,4987.8
XS Rating Curve= 0 ,0
Exp/Cntr=0.3,0.1

Type RM Length L Ch R = 1 ,19951   ,500,500,500
BEGIN DESCRIPTION:
LITTLE JOSHUA CREEK 39.0
END DESCRIPTION:
XS GIS Cut Line= 3
      2029799.39     13871851.12        2029725.       13870775.
      2030007.07     13870036.09
#Sta/Elev= 30
  3920.9 1505.39  3966.2 1501.99  4059.7 1497.06  4201.2 1483.56  4658.8 1456.43
  4746.7 1456.43  4839.2 1454.75  4859.2 1451.32  4879.3 1439.51  4889.3 1436.93
  4939.4 1435.98  4949.5 1431.97  4987.7 1426.16  4988.2 1425.66  5006.4 1426.16
  5009.3 1429.66  5014.6 1427.08  5031.7 1435.68  5062.5 1436.89  5099.5 1439.72
  5132.9 1445.53  5253.6    1451  5259.4 1451.26  5357.7  1453.5  5578.7  1457.9
  5633.5  1471.1  5669.9    1484  5695.3 1494.51  5727.4 1499.97  5790.5 1502.66
#Mann= 12 ,-1 , 0
  3920.9     .07       0  3966.2    .035       0  4201.2     .07       0
  4746.7    .035       0  4987.7    .035       0  5006.4    .035       0
  5062.5     .12       0  5132.9     .07       0  5253.6     .12       0
  5259.4     .07       0  5357.7    .035       0  5669.9     .12       0
Bank Sta=4987.7,5006.4
XS Rating Curve= 0 ,0
Exp/Cntr=0.3,0.1

Type RM Length L Ch R = 1 ,19451   ,480,480,480
BEGIN DESCRIPTION:
LITTLE JOSHUA CREEK 38.0
END DESCRIPTION:
XS GIS Cut Line= 3
      2030128.96     13871809.34        2030225.       13870775.
        2030225.     13870174.98
#Sta/Elev= 30
  3965.6 1504.47  3970.5 1504.45  4130.6 1499.46  4180.9 1490.09  4208.5 1487.25
  4291.3 1471.64  4358.7 1468.44  4642.8 1458.13  4808.9 1446.69  4845.4 1443.18
  4893.9 1441.78    4914 1436.64  4934.1 1435.11  4952.8 1427.11  4974.9 1421.11
  4975.4 1420.61  4993.7 1421.11  5014.4 1428.09  5024.4 1433.75  5064.4 1440.59
  5108.6 1444.27  5283.8 1452.16  5354.4 1453.41  5414.4 1458.01  5434.4 1455.78
  5514.4 1479.61  5524.1 1484.63  5544.4 1493.43  5574.4 1500.31  5604.4 1500.88
#Mann= 11 ,-1 , 0
  3965.6     .07       0  3970.5    .035       0  4208.5     .07       0
  4358.7    .035       0  4808.9     .07       0  4952.8     .12       0
  4974.9     .05       0  4993.7     .12       0  5108.6     .07       0
  5283.8    .035       0  5524.1     .12       0
Bank Sta=4974.9,4993.7
XS Rating Curve= 0 ,0
Exp/Cntr=0.3,0.1

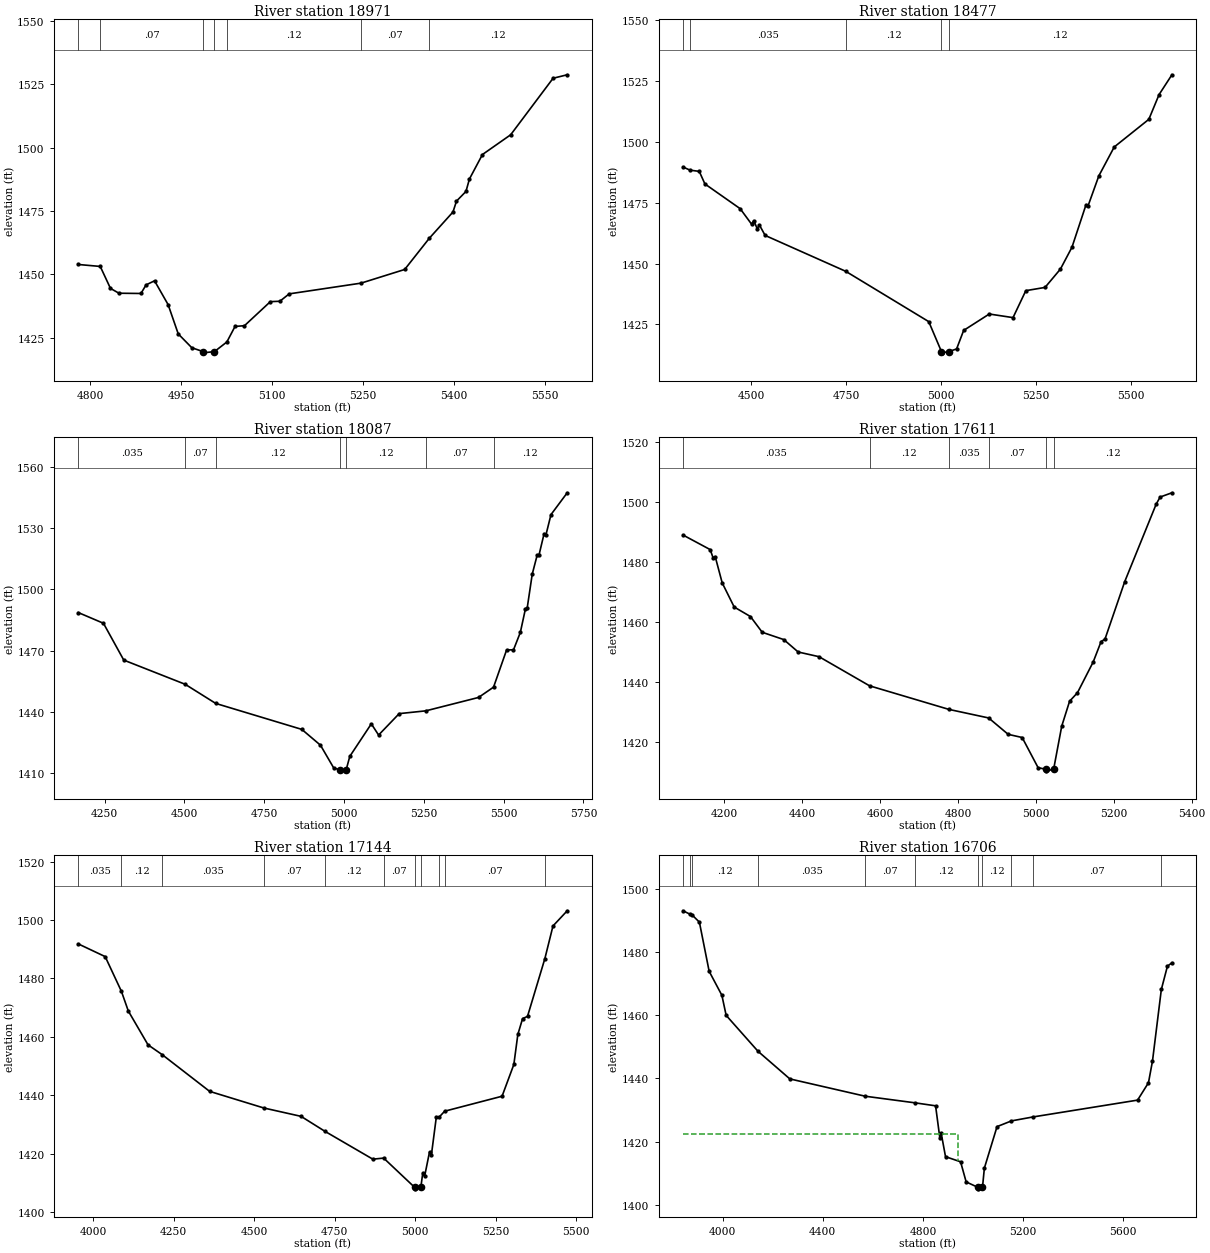
Type RM Length L Ch R = 1 ,18971   ,494,494,494
BEGIN DESCRIPTION:
LITTLE JOSHUA CREEK 37.0
END DESCRIPTION:
XS GIS Cut Line= 3
      2030574.99     13871075.02        2030675.       13870875.
      2030974.99     13870375.02
#Sta/Elev= 30
  4780.5 1453.95  4816.7 1453.18  4833.6 1444.51  4847.6 1442.61  4883.9 1442.51
  4892.3  1445.9  4906.3 1447.51  4928.7 1438.11  4945.4 1426.56  4967.8  1421.1
  4986.3 1419.59  4986.8 1419.09  5005.2 1419.59  5025.6 1423.37  5039.1 1429.51
  5054.7  1429.8  5097.4 1439.29    5113 1439.44  5128.5 1442.36    5247 1446.59
    5319 1451.98  5359.7 1464.31  5398.7 1474.66  5404.5 1478.96  5420.1 1482.76
  5425.9 1487.71  5447.3 1497.33  5493.9 1505.13  5563.9 1527.43  5587.2  1528.8
#Mann= 7 ,-1 , 0
  4780.5    .035       0  4816.7     .07       0  4986.3     .05       0
  5005.2     .07       0  5025.6     .12       0    5247     .07       0
  5359.7     .12       0
Bank Sta=4986.3,5005.2
XS Rating Curve= 0 ,0
Exp/Cntr=0.3,0.1

Type RM Length L Ch R = 1 ,18477   ,390,390,390
BEGIN DESCRIPTION:
LITTLE JOSHUA CREEK 36.0
END DESCRIPTION:
XS GIS Cut Line= 3
      2030736.76     13871586.68      2031119.82     13871025.44
        2031025.     13870424.98
#Sta/Elev= 30
  4320.5 1489.62  4338.9 1488.32  4363.3 1487.82  4378.2 1482.66    4471 1472.52
  4500.9  1466.2  4506.9 1467.61  4515.8 1464.33  4521.8 1465.79  4536.8 1461.54
    4749 1446.82  4967.6 1426.17  5001.1 1413.87  5001.6 1413.37    5020 1413.87
  5040.9 1414.96  5059.5 1422.57    5127  1429.3  5189.5 1427.82  5223.2 1438.88
  5273.8 1440.21  5314.3 1447.73  5344.7 1456.69  5381.8 1474.18  5386.9 1473.59
  5415.5 1485.99    5456 1497.83  5547.1 1509.17  5574.1 1519.33  5607.9 1527.45
#Mann= 5 ,-1 , 0
  4320.5     .07       0  4338.9    .035       0    4749     .12       0
  5001.1     .05       0    5020     .12       0
Bank Sta=5001.1,5020
XS Rating Curve= 0 ,0
Exp/Cntr=0.3,0.1

Type RM Length L Ch R = 1 ,18087   ,476,476,476
BEGIN DESCRIPTION:
LITTLE JOSHUA CREEK 35.0
END DESCRIPTION:
XS GIS Cut Line= 3
      2030801.58     13871621.68        2031475.       13871125.
        2031825.     13870524.99
#Sta/Elev= 30
  4167.9 1488.66  4246.7 1483.42  4310.3 1465.42  4502.6  1453.6  4598.3 1444.24
    4868 1431.54  4926.4 1423.82  4968.1 1412.64  4987.9 1411.78  4988.4 1411.28
  5006.9 1411.78  5018.3 1418.36  5085.7 1434.25  5108.5 1428.78    5173 1439.25
  5256.4 1440.61  5421.4 1447.15  5468.5 1452.19  5509.5 1470.41    5531 1470.42
  5552.5 1478.98  5568.2 1490.33    5574 1490.94  5589.7 1507.42  5605.4 1516.87
  5611.2 1516.98  5626.9 1527.26  5632.7 1526.67  5648.4 1536.54  5699.3 1547.22
#Mann= 7 ,-1 , 0
  4167.9    .035       0  4502.6     .07       0  4598.3     .12       0
  4987.9     .05       0  5006.9     .12       0  5256.4     .07       0
  5468.5     .12       0
Bank Sta=4987.9,5006.9
XS Rating Curve= 0 ,0
Exp/Cntr=0.3,0.1

Type RM Length L Ch R = 1 ,17611   ,467,467,467
BEGIN DESCRIPTION:
LITTLE JOSHUA CREEK 34.0
END DESCRIPTION:
XS GIS Cut Line= 3
      2030796.97       13871678.        2031675.       13871475.
      2032024.95     13871425.01
#Sta/Elev= 30
  4094.5 1488.93  4164.3 1484.08  4171.9 1481.29  4177.1 1481.78  4195.1 1473.02
  4225.9 1464.99  4267.6 1461.83  4297.8  1456.6  4353.1 1454.17  4390.1 1450.04
  4443.7 1448.48  4573.3  1438.8    4777 1430.96  4878.9 1428.12    4929 1422.67
  4964.9 1421.62  5005.8 1411.59  5026.5 1411.04    5027 1410.54  5045.6 1411.04
  5066.4 1425.38  5086.6 1433.68  5106.8  1436.5  5147.2 1446.74  5167.4 1453.49
  5177.5 1454.36    5228 1473.41  5308.8 1499.19  5318.9 1501.55  5349.2 1502.97
#Mann= 6 ,-1 , 0
  4094.5    .035       0  4573.3     .12       0    4777    .035       0
  4878.9     .07       0  5026.5     .05       0  5045.6     .12       0
Bank Sta=5026.5,5045.6
XS Rating Curve= 0 ,0
Exp/Cntr=0.3,0.1

Type RM Length L Ch R = 1 ,17144   ,438,438,438
BEGIN DESCRIPTION:
LITTLE JOSHUA CREEK 33.0
END DESCRIPTION:
XS GIS Cut Line= 3
      2030692.64     13871755.53        2031725.       13871925.
      2032125.02     13871674.99
#Sta/Elev= 30
  3953.8 1491.79  4037.3 1487.44  4087.6 1475.56  4109.1  1468.8  4170.3 1457.22
  4214.4 1453.85  4361.5 1441.29  4529.9 1435.59  4645.3 1432.73  4719.4 1427.61
  4868.2 1418.06  4901.8 1418.43  4998.1  1408.4  4998.6  1407.9  5017.2  1408.4
    5023 1413.16  5028.9 1412.16  5044.2 1420.55  5050.1 1419.58  5065.4 1432.57
    5073 1432.34  5091.2 1434.49  5269.4 1439.62    5306  1450.5  5318.4 1460.79
  5333.1  1466.2  5348.4 1466.97  5402.3 1486.76  5427.5 1497.94  5471.7 1503.14
#Mann= 11 ,-1 , 0
  3953.8    .035       0  4087.6     .12       0  4214.4    .035       0
  4529.9     .07       0  4719.4     .12       0  4901.8     .07       0
  4998.1     .05       0  5017.2     .07       0    5073     .12       0
  5091.2     .07       0  5402.3     .12       0
Bank Sta=4998.1,5017.2
XS Rating Curve= 0 ,0
Exp/Cntr=0.3,0.1

Type RM Length L Ch R = 1 ,16706   ,486,486,486
BEGIN DESCRIPTION:
LITTLE JOSHUA CREEK 32.0
END DESCRIPTION:
XS GIS Cut Line= 4
      2030635.95      13871824.6        2031675.       13872325.
      2031864.75     13872294.78      2032157.48     13871762.24
#Sta/Elev= 30
  3841.5 1492.97  3869.5 1491.89  3878.2 1491.63    3907 1489.38    3946 1473.85
  3996.8 1466.28  4013.9 1459.94  4141.2 1448.59  4268.3 1439.87  4569.4  1434.4
  4768.8 1432.31  4850.5 1431.37  4867.6 1421.16  4873.1 1422.63  4890.2 1415.31
  4950.4 1413.69  4972.6 1407.34  5018.8 1405.65  5019.3 1405.15  5037.9 1405.65
  5045.4  1411.7    5096  1424.8  5153.7 1426.61  5239.2 1427.85  5657.4 1433.17
  5700.9 1438.65    5717 1445.53  5752.3 1468.11  5776.7 1475.49  5794.6 1476.54
#Mann= 11 ,-1 , 0
  3841.5     .07       0  3869.5    .035       0  3878.2     .12       0
  4141.2    .035       0  4569.4     .07       0  4768.8     .12       0
  5018.8     .05       0  5037.9     .12       0  5153.7    .035       0
  5239.2     .07       0  5752.3     .12       0
#XS Ineff= 2 , 0
       0 4939.56  1422.6               0
Permanent Ineff=
       F       F
Bank Sta=5018.8,5037.9
XS Rating Curve= 0 ,0
Exp/Cntr=0.3,0.1

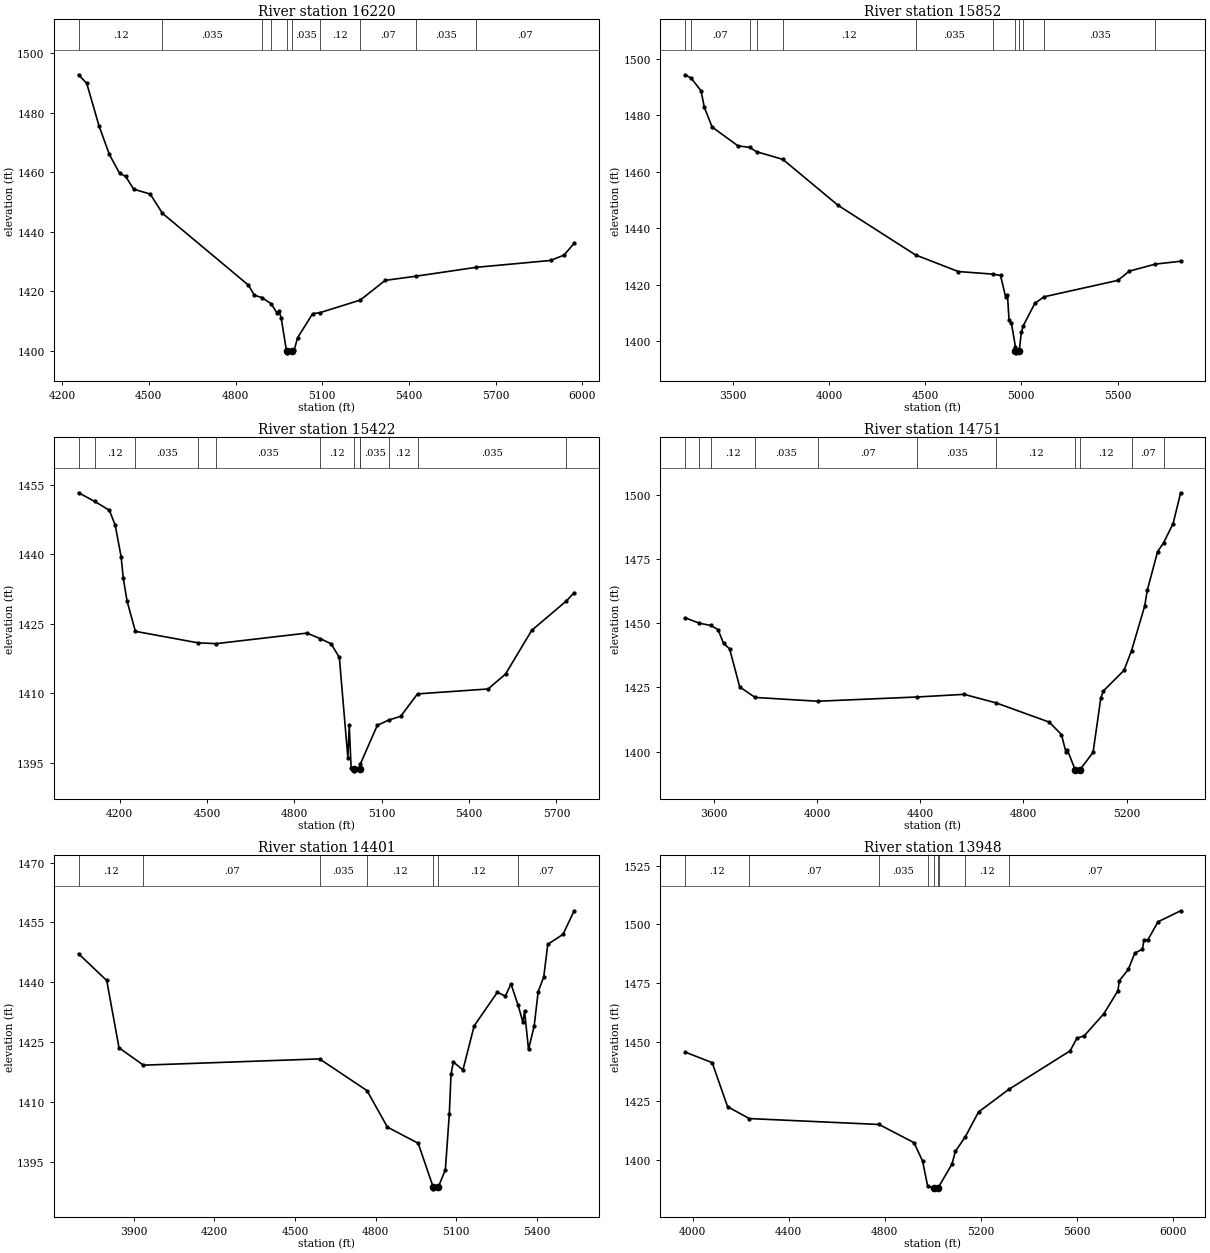
Type RM Length L Ch R = 1 ,16220   ,368,368,368
BEGIN DESCRIPTION:
LITTLE JOSHUA CREEK 31.0
END DESCRIPTION:
XS GIS Cut Line= 3
      2031274.99     13873325.01        2031775.       13872775.
      2032161.97     13871883.36
#Sta/Elev= 30
  4256.9 1492.72    4285 1489.82  4327.5 1475.54  4363.3 1465.95  4398.5 1459.63
  4419.4 1458.58  4447.8 1454.26  4504.6 1452.66  4547.1 1446.18  4844.5 1422.06
  4865.4 1418.64  4891.4 1417.88  4923.5 1415.78  4943.8 1412.64  4950.5 1413.32
    4958 1411.04  4976.6 1399.81  4977.1 1399.31  4996.2 1399.81  5002.9 1400.17
  5014.7 1404.36    5067 1412.47  5092.7 1412.82  5231.7 1417.03    5318 1423.65
    5424 1425.05  5633.3 1428.04  5890.3 1430.34  5937.2 1432.14  5972.2 1436.16
#Mann= 10 ,-1 , 0
  4256.9     .12       0  4547.1    .035       0  4891.4     .12       0
  4923.5    .035       0  4976.6    .035       0  4996.2    .035       0
  5092.7     .12       0  5231.7     .07       0    5424    .035       0
  5633.3     .07       0
Bank Sta=4976.6,4996.2
XS Rating Curve= 0 ,0
Exp/Cntr=0.3,0.1

Type RM Length L Ch R = 1 ,15852   ,426,426,426
BEGIN DESCRIPTION:
LITTLE JOSHUA CREEK 30.0
END DESCRIPTION:
XS GIS Cut Line= 3
      2031712.58     13874632.22      2032085.69     13872912.25
      2032126.43     13872098.24
#Sta/Elev= 30
  3252.7 1494.43  3284.4 1493.23  3335.8 1488.72  3352.2    1483  3393.1  1475.9
  3527.4 1469.25  3587.9 1468.69  3623.8 1467.17  3760.6 1464.45    4048 1448.14
  4450.1 1430.58  4672.2  1424.7  4854.5 1423.77  4891.8 1423.31  4917.8 1415.84
    4928 1416.27  4935.9 1407.65  4948.5 1406.38  4968.9 1398.12  4969.4 1396.38
  4969.9 1395.88    4989 1396.38  4999.6 1403.13  5010.4 1405.56    5070  1413.4
  5117.9 1415.74  5502.2 1421.57  5560.6 1424.83  5696.5 1427.33  5827.7 1428.34
#Mann= 12 ,-1 , 0
  3252.7    .035       0  3284.4     .07       0  3587.9     .12       0
  3623.8     .07       0  3760.6     .12       0  4450.1    .035       0
  4854.5     .07       0  4969.4     .05       0    4989     .07       0
  5010.4     .12       0  5117.9    .035       0  5696.5     .07       0
Bank Sta=4969.4,4989
XS Rating Curve= 0 ,0
Exp/Cntr=0.3,0.1

Type RM Length L Ch R = 1 ,15422   ,671,671,671
BEGIN DESCRIPTION:
LITTLE JOSHUA CREEK 29.0
END DESCRIPTION:
XS GIS Cut Line= 3
      2032295.83     13873739.11      2032440.28     13872820.49
      2032445.97     13872049.32
#Sta/Elev= 30
  4059.7 1453.22  4115.2 1451.34  4165.1 1449.46  4185.3 1446.23  4205.6 1439.41
    4213 1434.78  4225.8  1429.9  4254.5 1423.35  4468.3 1420.88  4531.1 1420.69
  4843.3 1422.97  4889.1 1421.77  4926.4 1420.67  4954.7 1417.71  4983.9  1396.1
  4988.7 1403.06  4995.1 1393.87  5005.3 1393.77  5005.8 1393.27  5024.9 1393.77
  5026.3 1394.68  5085.1  1403.1  5124.7 1404.23  5165.1 1405.02    5223 1409.86
  5465.1 1410.92  5525.1 1414.13  5615.1 1423.56  5733.9 1429.89  5760.8 1431.67
#Mann= 12 ,-1 , 0
  4059.7     .07       0  4115.2     .12       0  4254.5    .035       0
  4468.3     .07       0  4531.1    .035       0  4889.1     .12       0
  5005.3     .05       0  5024.9     .12       0  5026.3    .035       0
  5124.7     .12       0    5223    .035       0  5733.9     .07       0
Bank Sta=5005.3,5024.9
XS Rating Curve= 0 ,0
Exp/Cntr=0.3,0.1

Type RM Length L Ch R = 1 ,14751   ,350,350,350
BEGIN DESCRIPTION:
LITTLE JOSHUA CREEK 28.0
END DESCRIPTION:
XS GIS Cut Line= 3
      2032329.38     13873767.08      2032780.01     13872324.84
      2032789.58     13871915.75
#Sta/Elev= 30
    3489 1452.07  3544.5 1449.97  3588.5 1449.09  3616.9 1447.46  3637.9  1442.1
  3661.4 1439.99  3700.7 1425.16  3760.3 1421.07  4002.5 1419.59  4388.9 1421.25
  4570.3 1422.27  4694.4 1418.93  4899.8 1411.47  4947.5 1406.62  4964.8 1399.69
    4970 1400.73    5000 1392.99  5000.5 1392.49  5019.6 1392.99  5069.9 1399.69
  5099.9 1420.88  5109.9  1423.6  5189.9 1431.63  5219.1 1439.33  5269.9 1456.66
  5279.9 1462.77  5319.9 1477.84    5343 1481.25  5379.9 1488.73  5409.2 1500.75
#Mann= 11 ,-1 , 0
    3489     .12       0  3544.5     .07       0  3588.5     .12       0
  3760.3    .035       0  4002.5     .07       0  4388.9    .035       0
  4694.4     .12       0    5000     .05       0  5019.6     .12       0
  5219.1     .07       0    5343     .12       0
Bank Sta=5000,5019.6
XS Rating Curve= 0 ,0
Exp/Cntr=0.3,0.1

Type RM Length L Ch R = 1 ,14401   ,453,453,453
BEGIN DESCRIPTION:
LITTLE JOSHUA CREEK 27.0
END DESCRIPTION:
XS GIS Cut Line= 3
        2032426.     13873705.09        2032975.       13872525.
      2033421.36     13872214.29
#Sta/Elev= 30
  3694.2 1447.12  3798.8 1440.44  3844.6 1423.58  3935.3 1419.22  4591.4 1420.79
  4768.1 1412.85  4844.2 1403.69  4958.7 1399.65  5014.3 1388.73  5014.8 1388.23
  5033.9 1388.73  5059.9 1393.01  5074.7 1407.05    5081 1416.97  5089.6 1420.03
  5125.3 1418.01  5167.2 1429.07  5253.6  1437.5  5283.3 1436.52  5304.2 1439.58
  5331.1  1434.2  5348.8 1429.95  5354.9 1432.69  5369.7 1423.18  5390.7 1429.05
  5405.5 1437.61  5426.4 1441.37  5441.3  1449.5    5498    1452  5539.6 1457.91
#Mann= 7 ,-1 , 0
  3694.2     .12       0  3935.3     .07       0  4591.4    .035       0
  4768.1     .12       0  5014.3     .05       0  5033.9     .12       0
  5331.1     .07       0
Bank Sta=5014.3,5033.9
XS Rating Curve= 0 ,0
Exp/Cntr=0.3,0.1

Type RM Length L Ch R = 1 ,13948   ,469,469,469
BEGIN DESCRIPTION:
LITTLE JOSHUA CREEK 26.0
END DESCRIPTION:
XS GIS Cut Line= 3
      2032482.25     13873731.31        2033125.       13872925.
      2033636.71     13872028.27
#Sta/Elev= 30
  3969.1 1445.75  4081.8 1441.26  4145.9 1422.55  4236.2 1417.47  4776.9 1414.96
  4922.6 1407.21  4957.8 1399.44  4979.6 1388.61  5004.1 1388.09  5004.6 1387.59
  5023.8 1388.09  5024.6 1388.35  5080.8 1398.18  5094.6 1403.55  5135.9  1409.7
  5191.1 1420.27  5316.6 1429.84  5572.7 1446.28  5600.1 1451.54  5631.8 1452.73
  5712.4 1461.98  5771.5 1471.81  5777.2 1476.06  5814.7 1480.88    5842 1487.87
  5873.7 1489.48  5879.5 1493.24  5895.3 1493.32  5938.5 1501.14  6032.7 1505.83
#Mann= 9 ,-1 , 0
  3969.1     .12       0  4236.2     .07       0  4776.9    .035       0
  4979.6     .12       0  5004.1     .05       0  5023.8     .12       0
  5024.6     .07       0  5135.9     .12       0  5316.6     .07       0
Bank Sta=5004.1,5023.8
XS Rating Curve= 0 ,0
Exp/Cntr=0.3,0.1

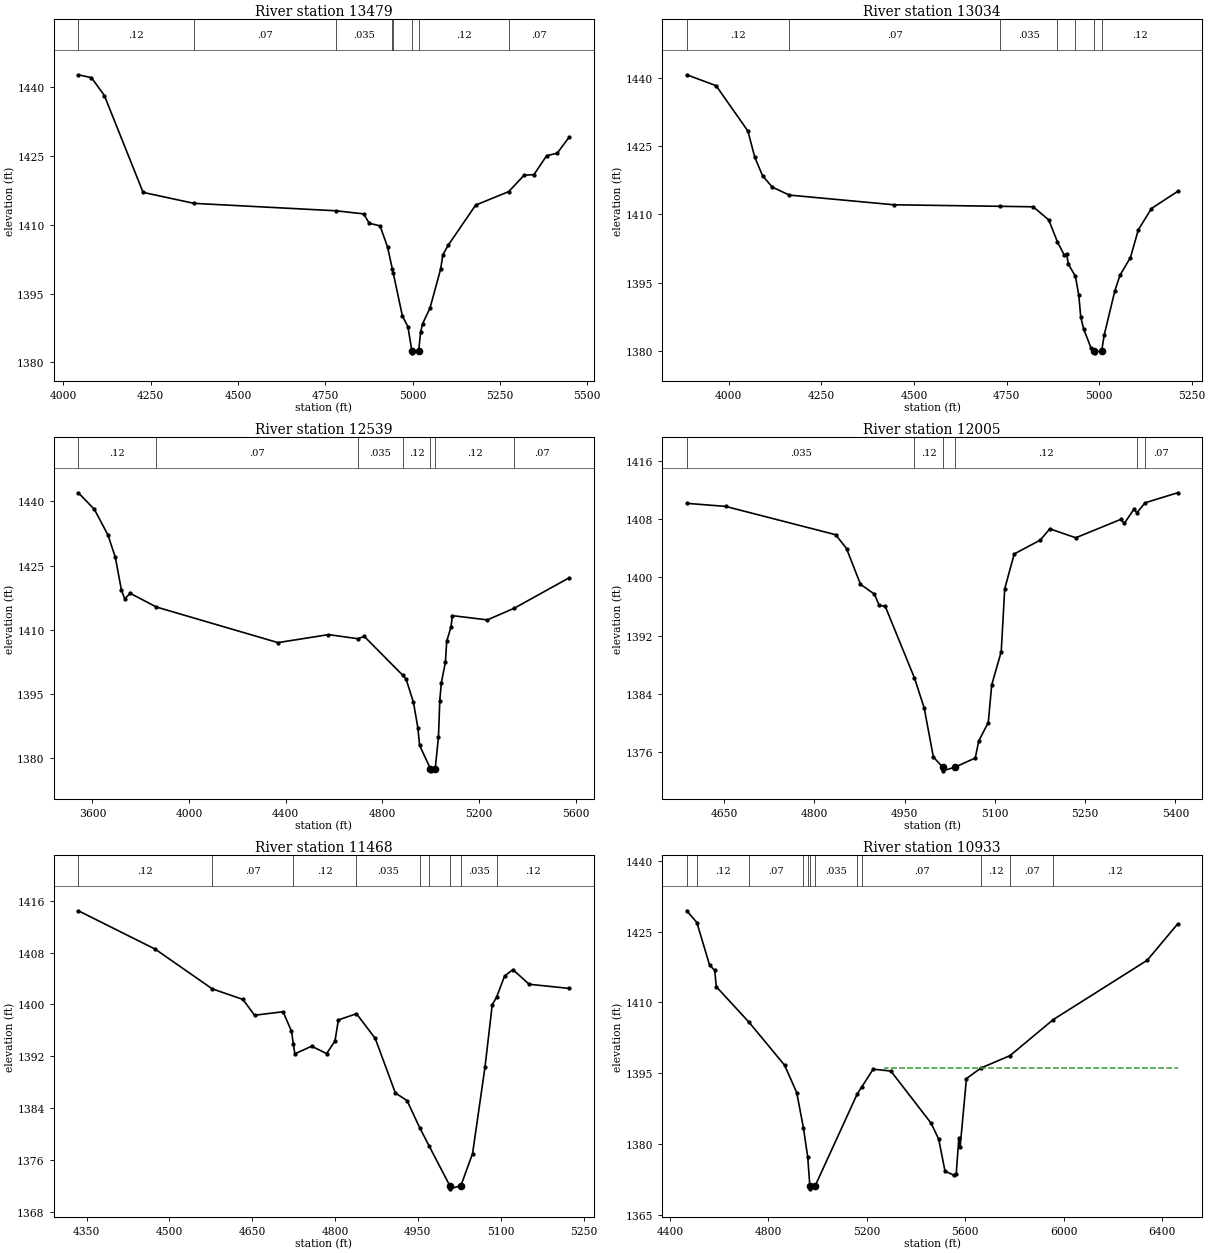
Type RM Length L Ch R = 1 ,13479   ,445,445,445
BEGIN DESCRIPTION:
LITTLE JOSHUA CREEK 25.0
END DESCRIPTION:
XS GIS Cut Line= 3
      2032603.41     13873766.57        2033425.       13873275.
      2033664.88     13872895.94
#Sta/Elev= 30
  4042.8  1442.7  4080.3 1442.07  4117.2 1438.18  4228.1 1417.06  4373.8 1414.67
  4780.9 1413.05  4860.4 1412.37  4875.7 1410.34  4906.9 1409.76  4928.3 1405.18
  4942.2 1400.33  4944.7  1399.5    4971 1390.09  4986.6 1387.81    4998 1382.58
  4998.5 1382.08  5017.7 1382.58  5023.1 1386.59    5029 1388.45  5050.2 1391.89
  5080.8 1400.44  5086.7 1403.43  5101.9 1405.52  5180.8 1414.29  5275.5 1417.23
  5319.7 1420.81  5347.7 1420.92  5384.2 1425.07  5414.4  1425.6  5448.8 1429.13
#Mann= 8 ,-1 , 0
  4042.8     .12       0  4373.8     .07       0  4780.9    .035       0
  4942.2     .07       0  4944.7     .12       0    4998     .05       0
  5017.7     .12       0  5275.5     .07       0
Bank Sta=4998,5017.7
XS Rating Curve= 0 ,0
Exp/Cntr=0.3,0.1

Type RM Length L Ch R = 1 ,13034   ,495,495,495
BEGIN DESCRIPTION:
LITTLE JOSHUA CREEK 24.0
END DESCRIPTION:
XS GIS Cut Line= 3
      2032659.17     13873896.84        2033725.       13873575.
        2033875.       13873425.
#Sta/Elev= 30
  3886.4 1440.62  3965.6 1438.23  4051.4 1428.28  4070.1  1422.5    4091 1418.46
  4117.4 1415.95  4163.6  1414.2  4446.1 1412.07  4731.1 1411.74  4822.2 1411.63
    4864 1408.74  4887.5 1403.91  4905.7 1401.05  4912.1 1401.25  4917.3 1398.99
    4936 1396.36  4945.1 1392.17  4950.3 1387.49    4958 1384.85  4978.1 1380.63
  4987.3 1380.06  4987.8 1379.56    5007 1380.06  5013.9 1383.53  5042.2 1393.09
  5056.3  1396.6  5084.6 1400.48  5105.8 1406.57  5141.2 1411.25  5211.9    1415
#Mann= 7 ,-1 , 0
  3886.4     .12       0  4163.6     .07       0  4731.1    .035       0
  4887.5     .07       0    4936     .12       0  4987.3     .05       0
    5007     .12       0
Bank Sta=4987.3,5007
XS Rating Curve= 0 ,0
Exp/Cntr=0.3,0.1

Type RM Length L Ch R = 1 ,12539   ,534,534,534
BEGIN DESCRIPTION:
LITTLE JOSHUA CREEK 23.0
END DESCRIPTION:
XS GIS Cut Line= 3
      2032704.49     13874421.45        2034075.       13873925.
      2034308.35     13873401.62
#Sta/Elev= 30
  3542.1 1441.99  3608.4  1438.1  3664.4 1432.14    3695  1426.9  3720.3 1419.22
  3734.1 1417.22  3756.3 1418.52  3864.9 1415.31  4367.7    1407  4576.8 1408.87
  4698.6 1407.91  4724.7 1408.46  4884.4 1399.36  4897.9 1398.49  4928.5 1393.02
  4946.6 1387.11  4953.8    1383  4998.7 1377.56  4999.2 1377.06  5018.5 1377.56
  5031.9    1385  5037.3 1393.45  5043.6  1397.6  5060.6 1402.42    5066 1407.32
  5083.8 1410.68  5089.3  1413.3  5234.1 1412.31  5344.9 1415.02  5572.8 1422.14
#Mann= 7 ,-1 , 0
  3542.1     .12       0  3864.9     .07       0  4698.6    .035       0
  4884.4     .12       0  4998.7     .05       0  5018.5     .12       0
  5344.9     .07       0
Bank Sta=4998.7,5018.5
XS Rating Curve= 0 ,0
Exp/Cntr=0.3,0.1

Type RM Length L Ch R = 1 ,12005   ,537,537,537
BEGIN DESCRIPTION:
LITTLE JOSHUA CREEK 22.0
END DESCRIPTION:
XS GIS Cut Line= 3
        2033775.       13874525.        2034175.       13874425.
      2034374.99     13874075.02
#Sta/Elev= 30
  4588.1 1410.16  4652.5 1409.74  4835.5 1405.85  4853.5 1403.95  4876.7 1399.04
  4899.9 1397.69  4907.6 1396.17  4917.9    1396  4966.4 1386.16  4982.4  1382.1
  4997.8 1375.32  5013.3 1373.92  5013.8 1373.42  5033.5 1373.92  5067.4 1375.18
  5073.1 1377.52    5089 1380.05  5094.7 1385.23  5110.5 1389.78  5116.3 1398.41
  5132.1 1403.21  5175.3 1405.11  5191.2 1406.66  5234.4 1405.43  5309.2 1407.96
    5315  1407.4  5330.8 1409.34    5336 1408.86  5349.3 1410.23  5403.5 1411.61
#Mann= 6 ,-1 , 0
  4588.1    .035       0  4966.4     .12       0  5013.3     .05       0
  5033.5     .12       0    5336    .035       0  5349.3     .07       0
Bank Sta=5013.3,5033.5
XS Rating Curve= 0 ,0
Exp/Cntr=0.3,0.1

Type RM Length L Ch R = 1 ,11468   ,535,535,535
BEGIN DESCRIPTION:
LITTLE JOSHUA CREEK 21.0
END DESCRIPTION:
XS GIS Cut Line= 3
       2034070.9     13875432.39        2034425.       13874875.
      2034630.18     13874774.55
#Sta/Elev= 30
  4335.3 1414.44  4474.4 1408.52  4577.7 1402.39  4633.2 1400.76  4654.3 1398.32
    4706 1398.86  4721.2 1395.84  4724.6 1393.87  4727.2 1392.36  4757.7 1393.54
  4784.8  1392.4    4800 1394.35  4806.1  1397.6  4838.9 1398.55  4872.8 1394.75
  4909.3 1386.32  4930.4 1385.15  4953.2 1380.99  4970.8 1378.08  5007.8 1372.03
  5008.3 1371.53    5028 1372.03  5049.1 1376.98  5071.6 1390.32  5084.7 1399.93
  5092.8 1401.15    5107 1404.36  5122.2 1405.36  5151.5  1403.1  5224.1 1402.46
#Mann= 9 ,-1 , 0
  4335.3     .12       0  4577.7     .07       0  4724.6     .12       0
  4838.9    .035       0  4953.2     .12       0  4970.8    .035       0
  5007.8    .035       0    5028    .035       0  5092.8     .12       0
Bank Sta=5007.8,5028
XS Rating Curve= 0 ,0
Exp/Cntr=0.3,0.1

Type RM Length L Ch R = 1 ,10933   ,544,544,544
BEGIN DESCRIPTION:
LITTLE JOSHUA CREEK 20.0
END DESCRIPTION:
XS GIS Cut Line= 3
      2034325.01     13875624.99        2034725.       13875275.
      2036101.19     13874782.36
#Sta/Elev= 30
  4468.7 1429.45  4509.7 1426.96  4561.2 1417.94  4582.1 1416.79  4588.7 1413.34
  4721.2 1405.82  4865.9 1396.69  4915.2 1390.87  4942.5 1383.38  4959.9 1377.19
  4968.7 1370.95  4969.2 1370.45    4989 1370.95  5161.3 1390.62  5180.2 1392.14
  5225.6 1395.84  5297.6 1395.44  5461.2 1384.36  5491.9 1380.96  5517.4  1374.2
  5553.5 1373.35  5563.1  1373.7  5573.6 1381.19  5578.9 1379.38  5604.4 1393.85
  5663.5 1396.09  5781.3 1398.71  5956.5 1406.34  6338.5 1418.95  6461.9 1426.64
#Mann= 12 ,-1 , 0
  4468.7     .07       0  4509.7     .12       0  4721.2     .07       0
  4942.5     .12       0  4959.9    .035       0  4968.7    .035       0
    4989    .035       0  5161.3     .12       0  5180.2     .07       0
  5663.5     .12       0  5781.3     .07       0  5956.5     .12       0
#XS Ineff= 2 , 0
       0                 5275.12       0 1396.02
Permanent Ineff=
       F       F
Bank Sta=4968.7,4989
XS Rating Curve= 0 ,0
Exp/Cntr=0.3,0.1