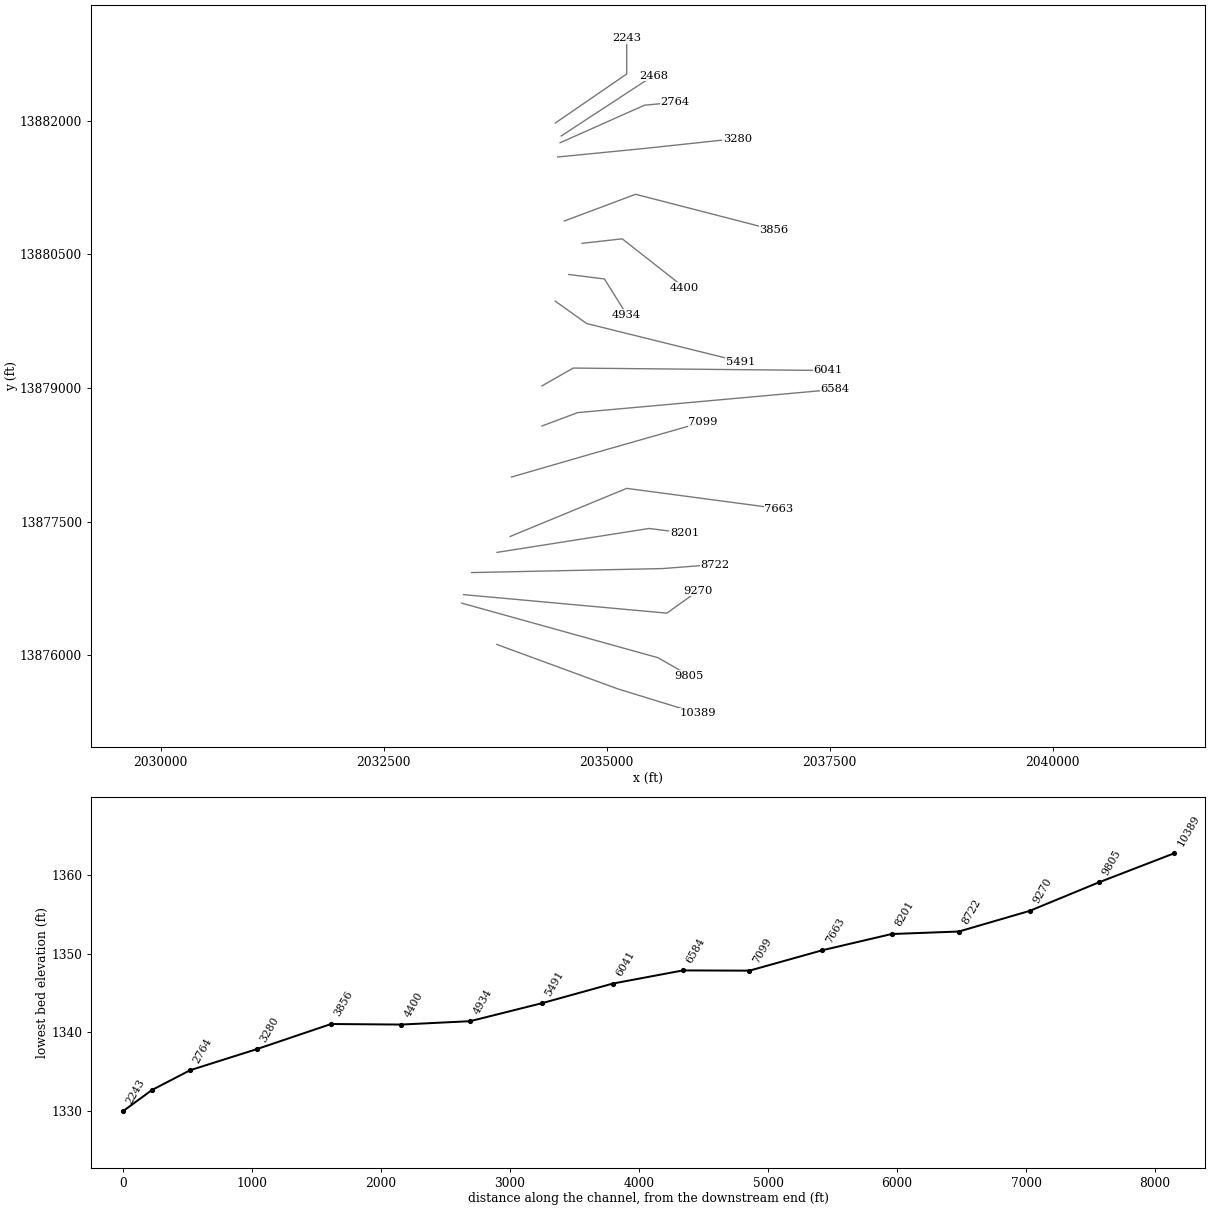
HEC-RAS study LITTLE JOSHUA CREEK.prj: LITTLE JOSHUA CREEK Base Level Engineering

--- LITTLE JOSHUA CREEK.g01 (geometry) --- (continued)

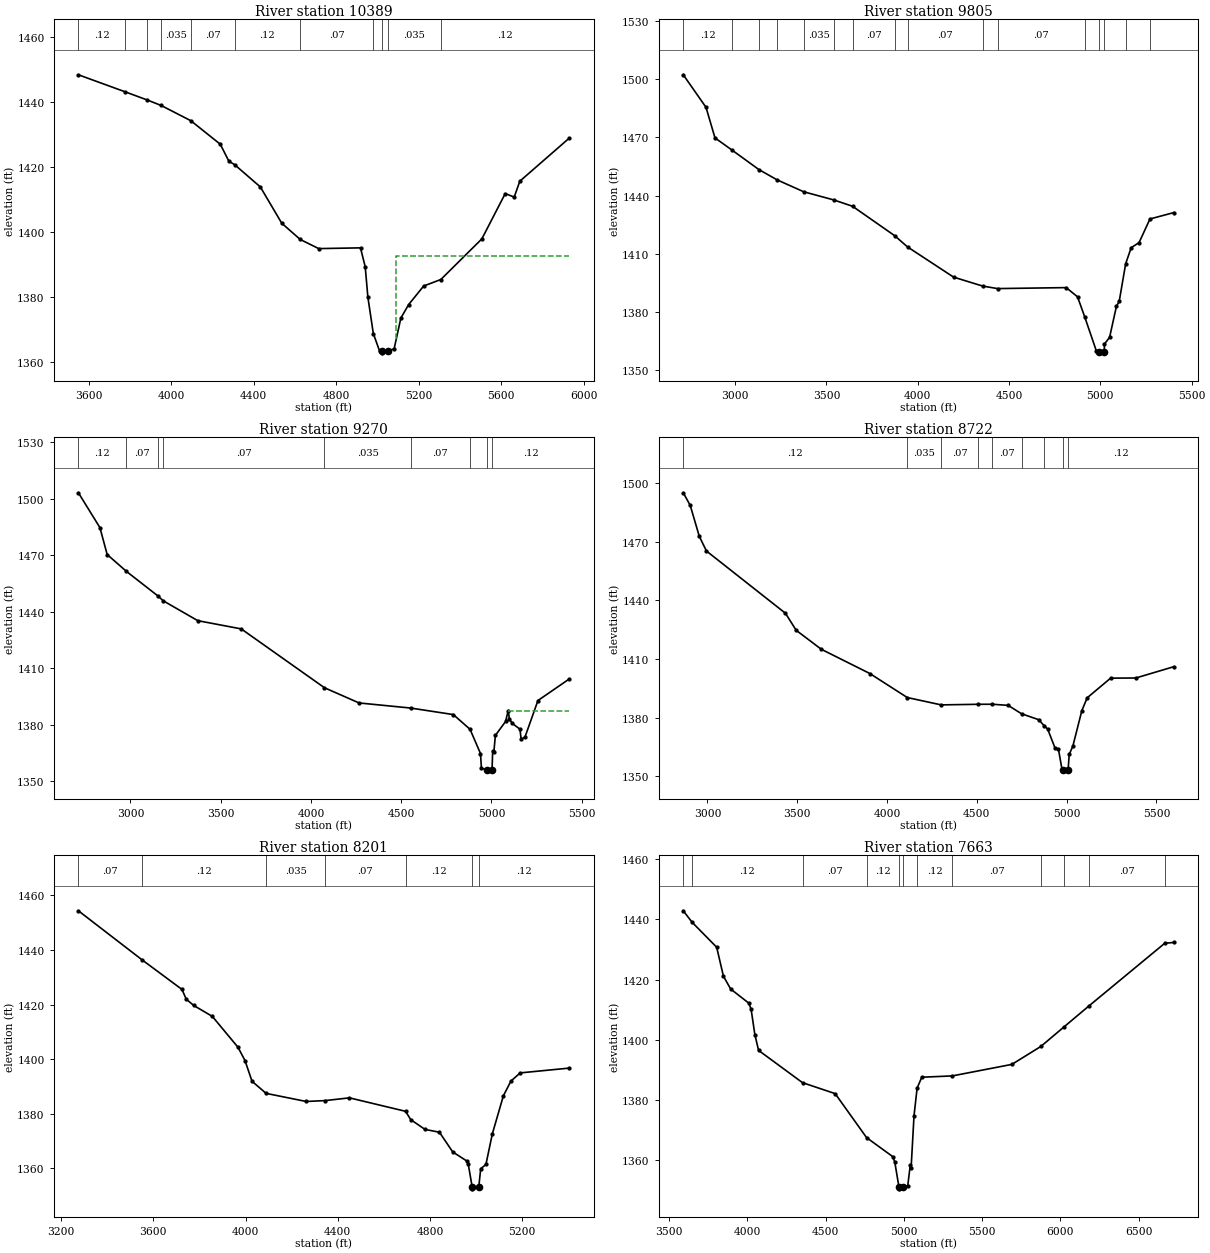
Type RM Length L Ch R = 1 ,10389   ,584,584,584
BEGIN DESCRIPTION:
LITTLE JOSHUA CREEK 19.0
END DESCRIPTION:
XS GIS Cut Line= 3
      2033768.83     13876123.51        2035125.       13875625.
      2036019.12     13875350.17
#Sta/Elev= 30
    3549 1448.48  3775.7 1443.23  3881.9 1440.74  3950.5 1439.02  4094.3 1434.33
  4237.4 1427.07  4279.3 1421.82  4306.8 1420.79  4431.6 1413.92  4535.8 1402.71
  4625.4 1397.71  4715.1  1394.9  4917.7 1395.13  4940.6 1389.28  4953.5 1379.92
  4979.9 1368.72  5010.3 1363.31    5022 1363.27  5022.5 1362.77  5049.4 1363.27
  5080.9 1364.03  5113.6 1373.51  5151.6 1377.67  5224.1 1383.37  5307.4 1385.37
  5506.5  1397.9    5620 1411.88  5663.4 1410.77  5690.6 1415.67  5929.3 1428.89
#Mann= 11 ,-1 , 0
    3549     .12       0  3775.7    .035       0  3881.9     .07       0
  3950.5    .035       0  4094.3     .07       0  4306.8     .12       0
  4625.4     .07       0  4979.9    .035       0    5022    .035       0
  5049.4    .035       0  5307.4     .12       0
#XS Ineff= 2 , 0
       0                    5091       0 1392.68
Permanent Ineff=
       F       F
Bank Sta=5022,5049.4
XS Rating Curve= 0 ,0
Exp/Cntr=0.3,0.1

Type RM Length L Ch R = 1 ,9805    ,535,535,535
BEGIN DESCRIPTION:
LITTLE JOSHUA CREEK 18.0
END DESCRIPTION:
XS GIS Cut Line= 3
      2033374.99     13876587.22        2035575.       13875975.
      2035924.98     13875775.01
#Sta/Elev= 30
  2716.1 1502.17  2840.7 1485.41  2889.8 1469.68  2985.1 1463.27  3130.1  1453.4
  3230.4 1448.07    3376 1441.95  3539.9 1437.77  3643.1  1434.5  3874.3 1419.32
  3944.1 1413.58  4196.5 1398.03  4355.2 1393.44  4437.2 1392.14  4812.9 1392.64
  4875.1 1387.91  4913.8 1377.75  4977.4 1360.27  4993.9 1359.57  4994.4 1359.07
  5021.3 1359.57  5022.7 1363.59  5050.8 1367.11  5088.2 1383.04  5103.4 1385.58
  5138.7 1404.93  5168.9 1413.18  5212.1 1415.79  5271.7 1427.96  5402.8 1431.26
#Mann= 16 ,-1 , 0
  2716.1     .12       0  2985.1     .07       0  3130.1     .12       0
  3230.4     .07       0    3376    .035       0  3539.9     .12       0
  3643.1     .07       0  3874.3     .12       0  3944.1     .07       0
  4355.2    .035       0  4437.2     .07       0  4913.8     .12       0
  4993.9     .05       0  5021.3     .12       0  5138.7    .035       0
  5271.7     .12       0
Bank Sta=4993.9,5021.3
XS Rating Curve= 0 ,0
Exp/Cntr=0.3,0.1

Type RM Length L Ch R = 1 ,9270    ,548,548,548
BEGIN DESCRIPTION:
LITTLE JOSHUA CREEK 17.0
END DESCRIPTION:
XS GIS Cut Line= 3
      2033396.28     13876682.66        2035675.       13876475.
      2036025.02     13876725.01
#Sta/Elev= 30
  2711.4 1503.11  2830.6 1484.63  2870.8 1470.33  2977.9 1461.34  3150.6 1448.43
  3181.5 1445.75  3372.8  1435.2  3613.8 1430.82  4074.7 1399.58  4266.5  1391.5
  4551.9  1388.8  4788.7 1385.33  4881.3 1377.52  4939.3 1364.63  4944.4  1356.8
  4975.8 1355.95  4976.3 1355.45  5003.2 1355.95  5006.9 1366.04  5013.1 1365.19
  5021.7 1374.26  5078.2 1381.66    5093 1387.48  5099.1 1383.22  5113.8 1380.76
  5158.1 1377.55  5164.2 1372.35  5185.1 1373.22  5257.6 1392.79  5429.7 1404.14
#Mann= 9 ,-1 , 0
  2711.4     .12       0  2977.9     .07       0  3150.6     .12       0
  3181.5     .07       0  4074.7    .035       0  4551.9     .07       0
  4881.3     .12       0  4975.8     .05       0  5003.2     .12       0
#XS Ineff= 2 , 0
       0                  5093.7       0 1387.24
Permanent Ineff=
       F       F
Bank Sta=4975.8,5003.2
XS Rating Curve= 0 ,0
Exp/Cntr=0.3,0.1

Type RM Length L Ch R = 1 ,8722    ,521,521,521
BEGIN DESCRIPTION:
LITTLE JOSHUA CREEK 16.0
END DESCRIPTION:
XS GIS Cut Line= 3
      2033486.15     13876930.11        2035625.       13876975.
      2036216.23     13877020.57
#Sta/Elev= 30
  2865.2 1494.91  2904.1 1488.43  2954.1 1472.75  2994.1 1465.17  3434.2 1433.35
  3494.2 1424.63  3634.2 1414.93  3904.3 1402.55  4112.8 1390.28  4301.5 1386.53
    4506 1386.83  4586.1 1386.86  4674.4 1386.28  4749.6 1381.97  4844.5 1378.97
  4874.5 1375.93  4894.5 1374.18  4934.5 1364.73  4954.5 1363.96  4974.5 1353.48
  4980.6 1353.33  4981.1 1352.83  5008.4 1353.33  5014.6 1361.25  5034.6 1365.37
  5084.8 1383.59  5114.8 1390.17  5245.2 1400.19  5385.6 1400.27  5597.5 1406.06
#Mann= 9 ,-1 , 0
  2865.2     .12       0  4112.8    .035       0  4301.5     .07       0
    4506    .035       0  4586.1     .07       0  4749.6     .12       0
  4874.5     .07       0  4980.6     .05       0  5008.4     .12       0
Bank Sta=4980.6,5008.4
XS Rating Curve= 0 ,0
Exp/Cntr=0.3,0.1

Type RM Length L Ch R = 1 ,8201    ,538,538,538
BEGIN DESCRIPTION:
LITTLE JOSHUA CREEK 15.0
END DESCRIPTION:
XS GIS Cut Line= 3
       2033771.1     13877156.77        2035475.       13877425.
        2035875.       13877375.
#Sta/Elev= 30
  3275.1 1454.34  3551.5 1436.36  3724.5 1425.53  3742.8 1421.98  3775.1 1419.68
  3856.1 1415.66  3967.4 1404.35  3997.8 1399.48  4028.2  1391.9  4089.3 1387.47
  4263.3  1384.5  4345.7 1384.83  4450.8 1385.83  4694.3  1380.9  4716.5 1377.85
  4778.6 1374.27  4841.1 1373.24  4898.6 1366.04  4959.5 1362.72  4966.2 1361.49
  4983.5 1353.01    4984 1352.51  5011.4 1353.01  5020.1 1359.85  5042.8 1361.46
  5070.5 1372.63  5118.4 1386.58  5151.2 1391.97  5191.5 1394.97  5403.1 1396.72
#Mann= 7 ,-1 , 0
  3275.1     .07       0  3551.5     .12       0  4089.3    .035       0
  4345.7     .07       0  4694.3     .12       0  4983.5     .05       0
  5011.4     .12       0
Bank Sta=4983.5,5011.4
XS Rating Curve= 0 ,0
Exp/Cntr=0.3,0.1

Type RM Length L Ch R = 1 ,7663    ,564,564,564
BEGIN DESCRIPTION:
LITTLE JOSHUA CREEK 14.0
END DESCRIPTION:
XS GIS Cut Line= 3
      2033917.68     13877335.14        2035225.       13877875.
      2036931.38     13877648.12
#Sta/Elev= 30
  3589.9 1442.89  3646.7 1439.05  3803.4 1430.77  3846.7 1421.11  3893.1 1416.87
  4008.9 1412.17  4023.5 1410.16  4047.4 1401.75  4071.3 1396.47    4352 1385.74
  4560.7  1382.1  4761.7 1367.46  4928.6 1361.16  4941.8 1359.35  4968.7 1350.94
  4969.2 1350.44  4996.7 1350.94  5024.5 1351.46  5040.9 1358.33    5046 1357.28
  5064.8 1374.78  5084.5 1383.91  5114.2 1387.55  5309.9 1387.99  5690.3 1391.82
  5875.5 1397.79  6024.1 1404.31  6182.7 1411.25  6667.3 1432.09  6725.7 1432.36
#Mann= 12 ,-1 , 0
  3589.9     .07       0  3646.7     .12       0    4352     .07       0
  4761.7     .12       0  4968.7     .05       0  4996.7     .12       0
  5084.5     .12       0  5309.9     .07       0  5875.5    .035       0
  6024.1     .12       0  6182.7     .07       0  6667.3     .12       0
Bank Sta=4968.7,4996.7
XS Rating Curve= 0 ,0
Exp/Cntr=0.3,0.1

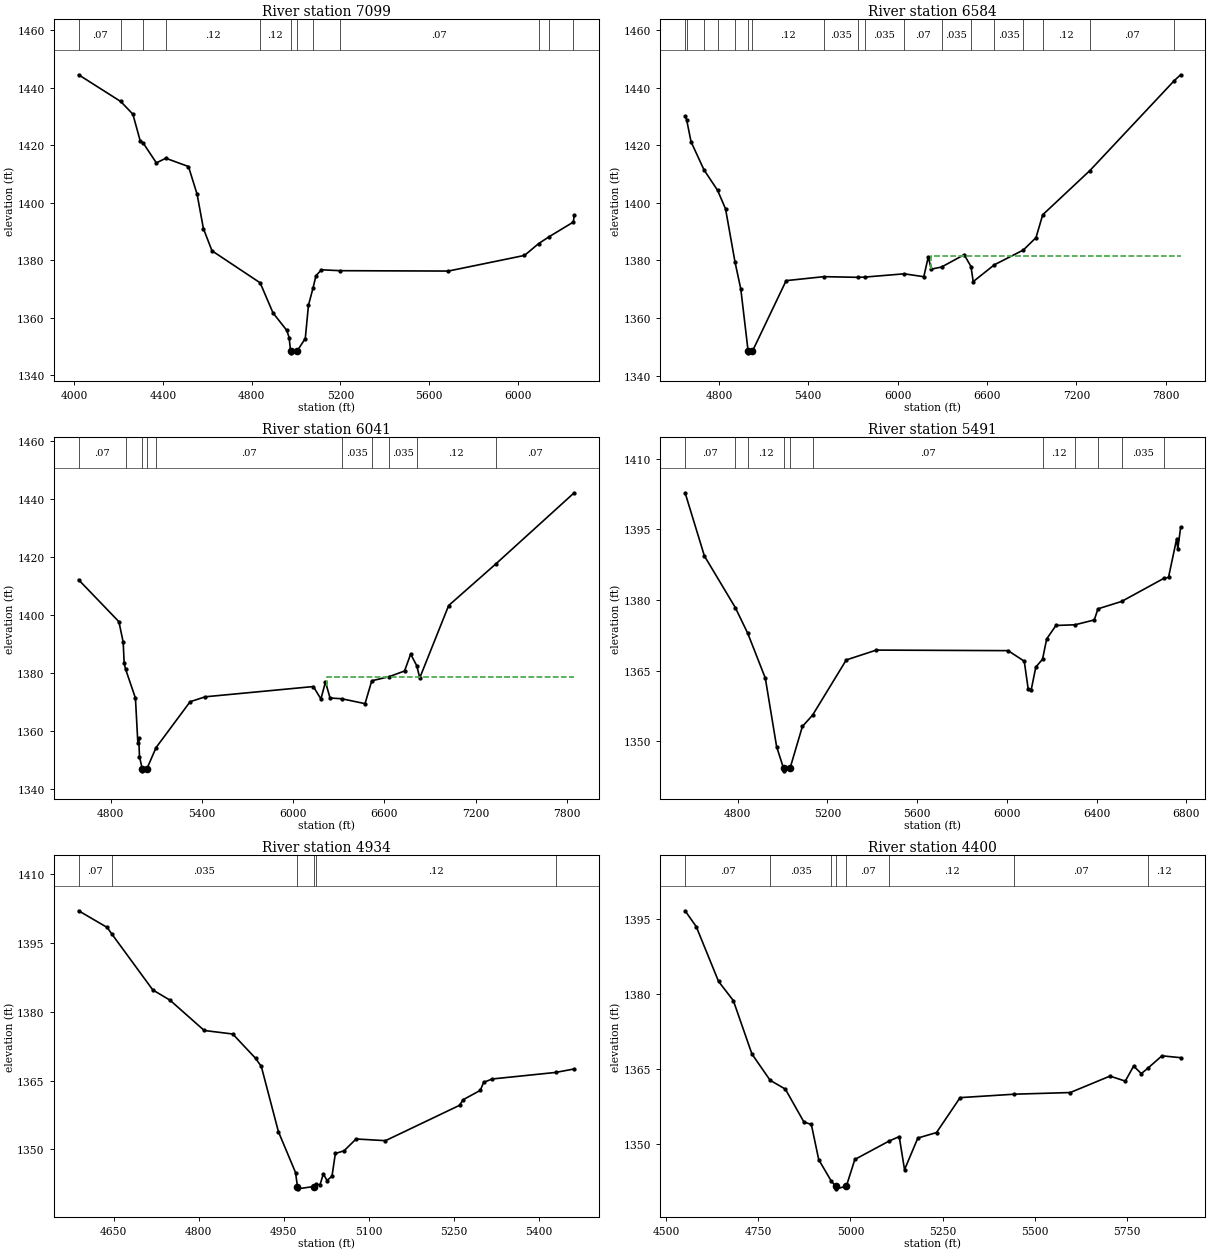
Type RM Length L Ch R = 1 ,7099    ,515,515,515
BEGIN DESCRIPTION:
LITTLE JOSHUA CREEK 13.0
END DESCRIPTION:
XS GIS Cut Line= 3
      2033933.76     13878002.48        2034875.       13878275.
      2036080.29     13878618.93
#Sta/Elev= 30
  4020.4 1444.55  4210.1 1435.26  4264.8 1430.85  4298.4 1421.43  4311.7 1420.77
  4370.7 1413.91  4413.4 1415.52  4515.5 1412.64  4554.3 1403.01  4582.7 1391.07
  4621.5 1383.33  4838.5  1372.2  4896.2 1361.77  4958.7 1355.63  4969.1 1353.15
  4975.8 1348.35  4976.3 1347.85  5003.9 1348.35  5041.9 1352.83  5056.2  1364.4
  5076.7 1370.37  5090.1 1374.69  5114.7 1376.73  5199.3 1376.42  5686.6 1376.29
  6029.8 1381.73  6093.4 1385.83  6140.9 1388.24  6250.2 1393.34  6253.7 1395.67
#Mann= 12 ,-1 , 0
  4020.4     .07       0  4210.1    .035       0  4311.7     .07       0
  4413.4     .12       0  4838.5     .12       0  4975.8     .05       0
  5003.9     .12       0  5076.7     .12       0  5199.3     .07       0
  6093.4     .12       0  6140.9    .035       0  6250.2     .12       0
Bank Sta=4975.8,5003.9
XS Rating Curve= 0 ,0
Exp/Cntr=0.3,0.1

Type RM Length L Ch R = 1 ,6584    ,543,543,543
BEGIN DESCRIPTION:
LITTLE JOSHUA CREEK 12.0
END DESCRIPTION:
XS GIS Cut Line= 3
      2034274.97     13878574.99        2034675.       13878725.
      2037561.93     13878985.53
#Sta/Elev= 30
  4573.2 1430.14  4583.2 1428.98  4613.3 1421.23  4700.3 1411.46  4791.3 1404.37
  4844.7 1397.91  4908.4 1379.39    4947 1370.08  4996.4 1348.38  4996.9 1347.88
  5024.5 1348.38  5251.5 1372.98  5504.2 1374.36  5733.6 1374.13  5777.6 1374.21
  6044.1 1375.35  6175.2 1374.34  6205.3 1381.21  6225.4 1376.97  6294.6 1377.71
  6446.3    1382  6491.9 1377.88    6507 1372.64  6648.7 1378.48  6843.3 1383.62
  6928.2 1387.91  6973.4 1395.87  7289.8 1411.23    7857 1442.54  7899.1 1444.54
#Mann= 18 ,-1 , 0
  4573.2     .07       0  4583.2    .035       0  4700.3     .07       0
  4791.3    .035       0  4908.4     .12       0  4996.4     .05       0
  5024.5     .12       0  5504.2    .035       0  5733.6     .07       0
  5777.6    .035       0  6044.1     .07       0  6294.6    .035       0
  6491.9     .07       0  6648.7    .035       0  6843.3     .07       0
  6973.4     .12       0  7289.8     .07       0    7857    .035       0
#XS Ineff= 2 , 0
       0                 6226.58       0 1381.39
Permanent Ineff=
       F       F
Bank Sta=4996.4,5024.5
XS Rating Curve= 0 ,0
Exp/Cntr=0.3,0.1

Type RM Length L Ch R = 1 ,6041    ,550,550,550
BEGIN DESCRIPTION:
LITTLE JOSHUA CREEK 11.0
END DESCRIPTION:
XS GIS Cut Line= 3
      2034275.01     13879025.01        2034625.       13879225.
      2037480.27     13879197.69
#Sta/Elev= 30
  4589.1 1412.09    4854 1397.65  4882.1 1390.57  4888.5 1383.41  4897.4 1381.35
  4962.7 1371.28  4978.5 1355.82  4984.3 1357.49  4989.3 1351.11  5008.2 1346.71
  5008.7 1346.21  5036.3 1346.71    5098 1354.21  5322.2 1370.05  5422.2 1371.75
  6132.3 1375.28  6182.3    1371  6212.3 1376.88  6242.3 1371.33  6319.6 1371.07
  6472.3 1369.38  6516.7 1377.27  6631.9  1378.7  6732.3 1380.65  6772.3 1386.48
  6812.1 1382.51  6832.3 1378.28  7022.3 1403.23  7332.1 1417.56  7847.6 1442.11
#Mann= 10 ,-1 , 0
  4589.1     .07       0  4897.4     .12       0  5008.2     .05       0
  5036.3     .12       0    5098     .07       0  6319.6    .035       0
  6516.7     .07       0  6631.9    .035       0  6812.1     .12       0
  7332.1     .07       0
#XS Ineff= 2 , 0
       0                  6219.9       0  1378.5
Permanent Ineff=
       F       F
Bank Sta=5008.2,5036.3
XS Rating Curve= 0 ,0
Exp/Cntr=0.3,0.1

Type RM Length L Ch R = 1 ,5491    ,557,557,557
BEGIN DESCRIPTION:
LITTLE JOSHUA CREEK 10.0
END DESCRIPTION:
XS GIS Cut Line= 3
      2034425.04     13879974.97        2034775.       13879725.
      2036501.62      13879296.8
#Sta/Elev= 30
  4565.3 1402.75  4651.3 1389.34  4788.9 1378.39  4844.7  1372.9  4922.9 1363.39
  4973.3 1348.83  5004.4 1344.21  5004.9 1343.71  5032.8 1344.21  5088.1 1353.13
  5133.3 1355.52  5283.9 1367.26  5417.8 1369.35  6005.1 1369.23  6077.2 1366.99
  6094.5 1361.15  6108.1 1360.91  6128.7 1365.73  6158.8 1367.43  6177.2 1371.73
  6218.6 1374.58  6303.5 1374.72  6389.3 1375.75  6405.8 1378.11  6511.4 1379.68
  6698.3 1384.55  6720.3  1384.8  6756.5 1392.94  6761.7 1390.85  6774.3 1395.42
#Mann= 11 ,-1 , 0
  4565.3     .07       0  4788.9    .035       0  4844.7     .12       0
  5004.4     .05       0  5032.8     .12       0  5133.3     .07       0
  6158.8     .12       0  6303.5    .035       0  6405.8     .07       0
  6511.4    .035       0  6698.3     .12       0
Bank Sta=5004.4,5032.8
XS Rating Curve= 0 ,0
Exp/Cntr=0.3,0.1

Type RM Length L Ch R = 1 ,4934    ,534,534,534
BEGIN DESCRIPTION:
LITTLE JOSHUA CREEK 9.0
END DESCRIPTION:
XS GIS Cut Line= 3
      2034575.02       13880275.        2034975.       13880225.
        2035225.       13879825.
#Sta/Elev= 30
    4588 1401.98  4638.4 1398.35  4646.1 1397.01    4719 1384.73  4749.2 1382.52
  4809.7 1375.91  4860.1 1375.14  4900.4 1369.84  4910.5 1368.07  4940.7 1353.86
  4970.9 1344.97  4974.3 1341.92  4974.8 1341.42  5002.8 1341.92  5006.4  1342.4
  5014.1 1342.29    5020 1344.68  5026.5 1343.23  5035.3 1344.18  5041.2 1349.12
  5056.5  1349.7  5077.8 1352.28  5129.7 1351.91  5260.6 1359.62  5266.5 1360.81
  5297.1 1362.87    5303 1364.62  5318.3 1365.35    5430 1366.77  5462.8 1367.53
#Mann= 6 ,-1 , 0
    4588     .07       0  4646.1    .035       0  4974.3    .035       0
  5002.8    .035       0  5006.4     .12       0    5430     .07       0
Bank Sta=4974.3,5002.8
XS Rating Curve= 0 ,0
Exp/Cntr=0.3,0.1

Type RM Length L Ch R = 1 ,4400    ,544,544,544
BEGIN DESCRIPTION:
LITTLE JOSHUA CREEK 8.0
END DESCRIPTION:
XS GIS Cut Line= 3
      2034724.97       13880625.        2035175.       13880675.
      2035874.98     13880125.02
#Sta/Elev= 30
  4551.9 1396.66  4582.1 1393.49  4642.5 1382.53  4682.7 1378.67    4733 1367.99
  4782.4 1362.72  4823.6 1360.96  4873.9 1354.37    4894 1353.88  4914.1 1346.83
  4947.8 1342.57  4960.3 1341.49  4960.8 1340.99  4988.8 1341.49  5011.9 1346.87
  5104.5 1350.55  5132.2 1351.45  5146.6 1344.83  5182.7 1351.16  5233.3 1352.26
  5297.2 1359.25  5444.6 1359.94  5595.8 1360.27  5703.3 1363.56  5744.9 1362.56
  5767.5 1365.57  5788.3 1364.06    5806 1365.14  5844.3 1367.62  5894.9 1367.25
#Mann= 8 ,-1 , 0
  4551.9     .07       0  4782.4    .035       0  4947.8     .07       0
  4960.3     .05       0  4988.8     .07       0  5104.5     .12       0
  5444.6     .07       0    5806     .12       0
Bank Sta=4960.3,4988.8
XS Rating Curve= 0 ,0
Exp/Cntr=0.3,0.1

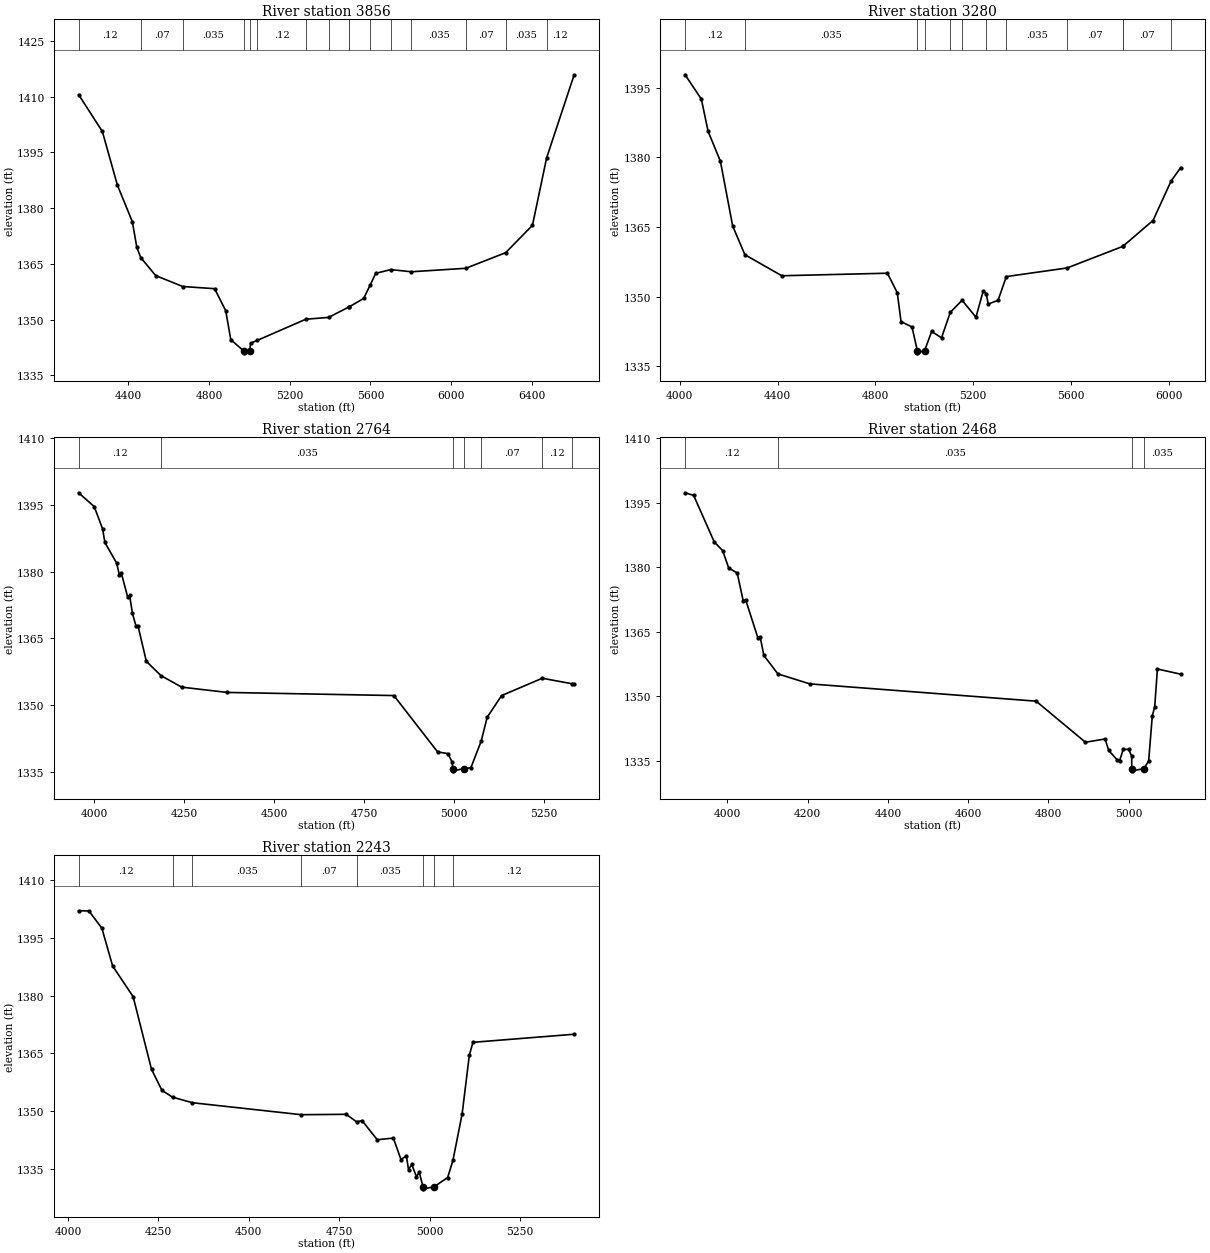
Type RM Length L Ch R = 1 ,3856    ,576,576,576
BEGIN DESCRIPTION:
LITTLE JOSHUA CREEK 7.0
END DESCRIPTION:
XS GIS Cut Line= 3
      2034524.98     13880874.99        2035325.       13881175.
        2036875.       13880775.
#Sta/Elev= 30
  4154.4 1410.57  4271.9 1400.66  4346.7 1386.17  4420.5 1376.37  4442.8 1369.43
    4462 1366.72  4536.2 1361.86    4670 1358.92  4828.1 1358.33  4883.3 1352.39
  4908.2 1344.62  4972.5 1341.56    4973 1341.06  5002.5 1341.56  5006.1 1343.63
  5040.2 1344.43  5280.1 1350.11  5392.9  1350.6  5494.8 1353.44  5495.5 1353.46
  5566.5  1355.7  5598.2 1359.23  5626.2 1362.45  5700.8 1363.47  5803.4 1362.89
  6072.4 1363.82  6270.1 1368.02    6403  1375.4  6473.1 1393.55  6609.6 1415.92
#Mann= 16 ,-1 , 0
  4154.4     .12       0    4462     .07       0    4670    .035       0
  4972.5    .035       0  5002.5    .035       0  5040.2     .12       0
  5280.1    .035       0  5392.9     .07       0  5494.8    .035       0
  5495.5     .07       0  5598.2     .12       0  5700.8     .07       0
  5803.4    .035       0  6072.4     .07       0  6270.1    .035       0
  6473.1     .12       0
Bank Sta=4972.5,5002.5
XS Rating Curve= 0 ,0
Exp/Cntr=0.3,0.1

Type RM Length L Ch R = 1 ,3280    ,516,516,516
BEGIN DESCRIPTION:
LITTLE JOSHUA CREEK 6.0
END DESCRIPTION:
XS GIS Cut Line= 3
      2034451.36     13881593.48      2035412.82     13881688.09
       2036467.5     13881800.93
#Sta/Elev= 30
  4021.5 1397.81  4088.1 1392.55  4115.6  1385.6  4165.8 1379.19  4216.1 1365.21
  4265.9 1359.02    4417 1354.48  4849.1 1355.03  4889.3 1350.82  4904.7 1344.59
  4949.6 1343.44  4971.2 1338.36  4971.7 1337.86  5001.2 1338.36    5030 1342.47
  5070.3  1341.1  5106.2  1346.6  5154.5 1349.19  5211.1 1345.54  5241.2 1351.27
  5253.3  1350.6  5261.3 1348.38  5301.6 1349.19  5335.4  1354.3  5584.1 1356.16
  5810.6 1360.79  5812.7 1360.86  5935.2 1366.39  6009.3  1374.9  6048.3 1377.78
#Mann= 12 ,-1 , 0
  4021.5     .12       0  4265.9    .035       0  4971.2    .035       0
  5001.2    .035       0  5106.2     .12       0  5154.5    .035       0
  5253.3     .12       0  5335.4    .035       0  5584.1     .07       0
  5810.6    .035       0  5812.7     .07       0  6009.3    .035       0
Bank Sta=4971.2,5001.2
XS Rating Curve= 0 ,0
Exp/Cntr=0.3,0.1

Type RM Length L Ch R = 1 ,2764    ,296,296,296
BEGIN DESCRIPTION:
LITTLE JOSHUA CREEK 5.0
END DESCRIPTION:
XS GIS Cut Line= 3
      2034478.36      13881753.1        2035425.       13882175.
      2035766.08     13882206.24
#Sta/Elev= 30
  3955.9 1397.71  3999.4 1394.59  4022.7 1389.56  4028.9 1386.54  4061.7 1381.88
  4069.1 1379.28  4074.6 1379.66  4092.4 1374.27  4097.8 1374.65  4105.5 1370.62
  4115.6 1367.71  4121.1 1367.78  4144.3 1359.81  4184.8 1356.61  4242.7    1354
  4369.8 1352.81  4833.1 1352.11  4954.7 1339.44  4983.4 1339.05  4994.8 1337.24
  4997.3 1335.68  4997.8 1335.18  5027.4 1335.68  5047.3 1335.86    5076 1341.85
  5092.7 1347.23  5132.9 1352.11  5246.1    1356    5329 1354.76  5334.8 1354.73
#Mann= 7 ,-1 , 0
  3955.9     .12       0  4184.8    .035       0  4997.3    .035       0
  5027.4    .035       0    5076     .07       0  5246.1     .12       0
    5329     .07       0
Bank Sta=4997.3,5027.4
XS Rating Curve= 0 ,0
Exp/Cntr=0.3,0.1

Type RM Length L Ch R = 1 ,2468    ,225,225,225
BEGIN DESCRIPTION:
LITTLE JOSHUA CREEK 4.5
END DESCRIPTION:
XS GIS Cut Line= 2
      2034490.65     13881829.35      2035523.41     13882505.84
#Sta/Elev= 30
  3894.7 1397.32    3916 1396.71  3967.3  1385.9  3988.3 1383.86  4003.4 1379.81
  4024.5 1378.68  4039.6 1372.13  4045.6 1372.44  4075.8 1363.65  4081.8 1363.77
  4090.9  1359.5  4125.9  1355.2  4205.4 1352.88  4769.2 1348.86  4892.1 1339.31
    4941 1340.07  4950.1  1337.4  4971.2 1335.21  4977.2 1334.99  4986.3 1337.66
  4999.7 1337.64  5007.4 1336.09  5007.5 1333.16    5008 1332.66  5037.6 1333.16
  5049.6 1334.95  5058.7 1345.45  5064.7 1347.54  5071.4 1356.34  5129.3 1355.14
#Mann= 4 ,-1 , 0
  3894.7     .12       0  4125.9    .035       0  5007.5    .035       0
  5037.6    .035       0
Bank Sta=5007.5,5037.6
XS Rating Curve= 0 ,0
Exp/Cntr=0.3,0.1

Type RM Length L Ch R = 1 ,2243    ,556,556,556
BEGIN DESCRIPTION:
LITTLE JOSHUA CREEK 4.0
END DESCRIPTION:
XS GIS Cut Line= 3
      2034425.02     13881975.01        2035225.       13882525.
        2035225.     13882924.99
#Sta/Elev= 30
  4029.1 1401.94  4057.5  1401.9  4093.3 1397.45  4123.1 1387.66  4179.9  1379.7
  4230.7  1360.9  4259.7 1355.43    4289 1353.69  4343.9 1352.25  4645.2 1349.15
  4769.3 1349.25    4798 1347.32  4813.2 1347.62  4855.1 1342.67  4899.8  1343.1
  4920.8 1337.53  4935.6 1338.52  4941.7 1334.94  4950.5 1336.28  4963.5 1333.13
  4971.5  1334.2  4981.8 1330.46  4982.3 1329.96  5011.9 1330.46  5049.9 1332.89
  5064.5 1337.31  5089.9 1349.32  5109.9 1364.54  5119.9 1367.89  5399.9 1369.98
#Mann= 8 ,-1 , 0
  4029.1     .12       0    4289     .07       0  4343.9    .035       0
  4645.2     .07       0    4798    .035       0  4981.8    .035       0
  5011.9    .035       0  5064.5     .12       0
Bank Sta=4981.8,5011.9
XS Rating Curve= 0 ,0
Exp/Cntr=0.3,0.1