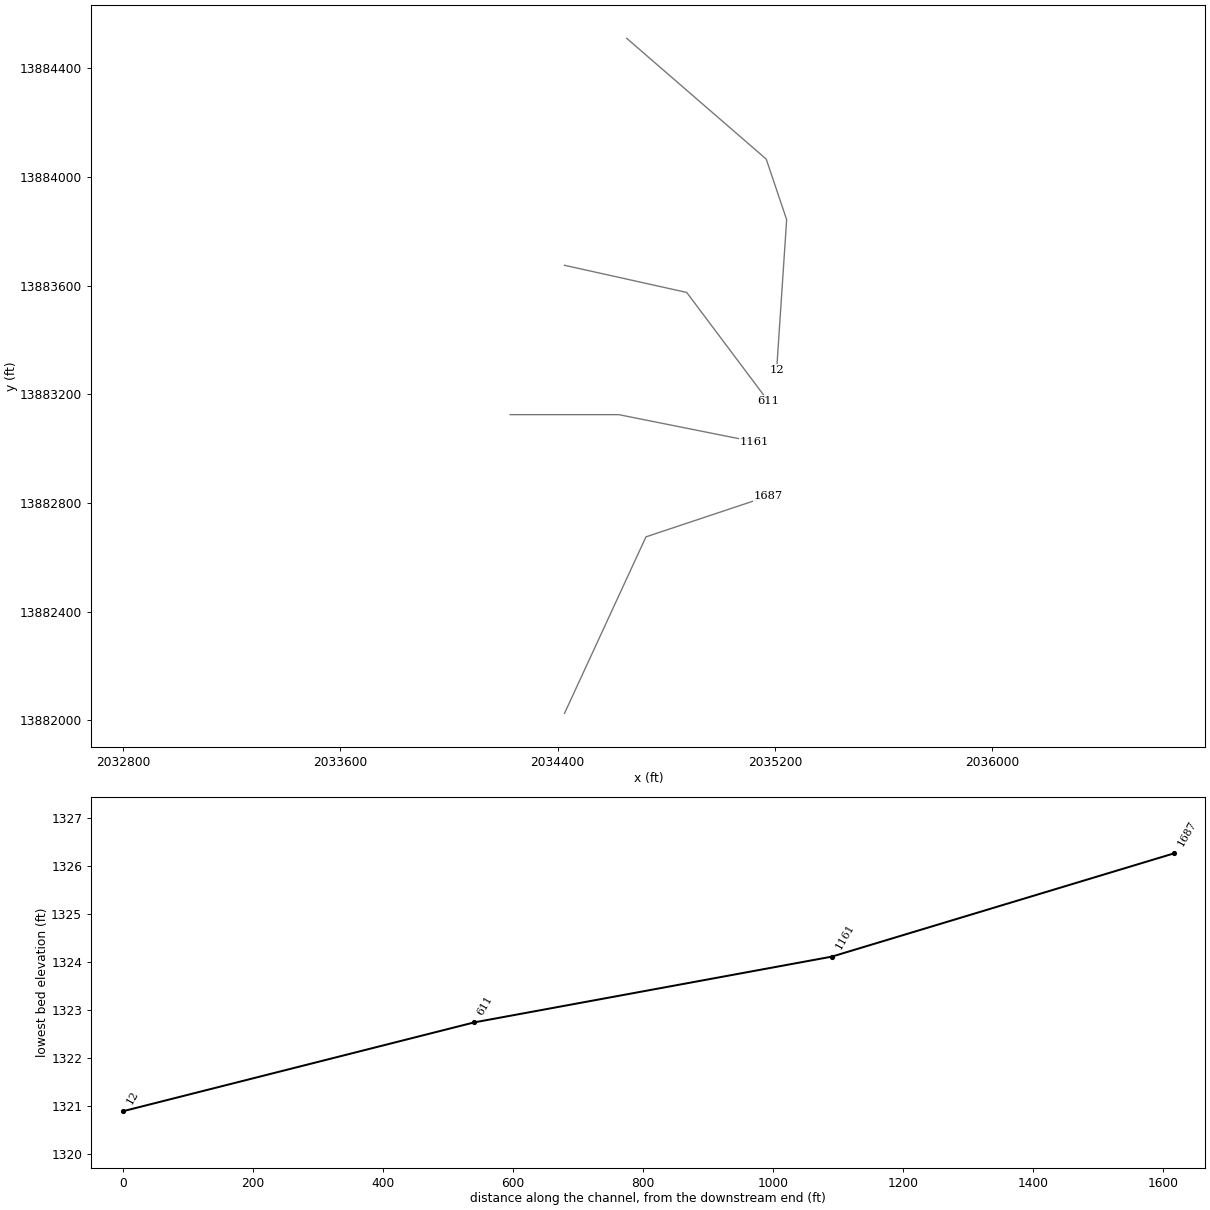
HEC-RAS study LITTLE JOSHUA CREEK.prj: LITTLE JOSHUA CREEK Base Level Engineering

--- LITTLE JOSHUA CREEK.g01 (geometry) --- (continued)

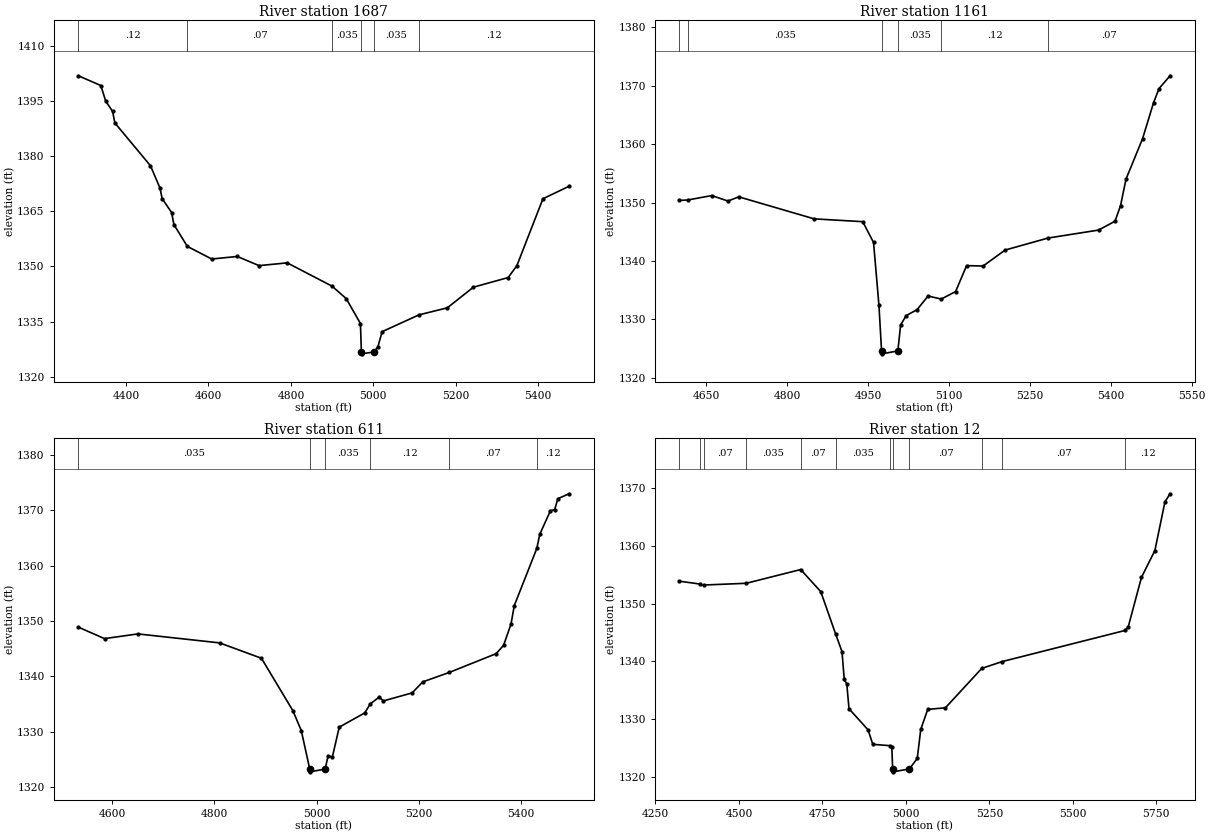
Type RM Length L Ch R = 1 ,1687    ,526,526,526
BEGIN DESCRIPTION:
LITTLE JOSHUA CREEK 3.0
END DESCRIPTION:
XS GIS Cut Line= 3
      2034425.02     13882025.03        2034725.       13882675.
        2035175.       13882825.
#Sta/Elev= 30
  4284.4  1401.8    4339 1399.14  4350.4 1394.99  4367.4 1392.11  4372.9 1388.99
  4459.2 1377.38  4482.2 1371.34  4487.7 1368.42  4510.6 1364.66  4516.1 1361.39
  4548.7 1355.45  4607.9 1352.03  4669.8 1352.72  4722.6 1350.23    4791 1350.98
  4899.7 1344.66  4934.2 1341.26  4968.6 1334.51    4971 1326.77  4971.5 1326.27
  5001.1 1326.77  5010.8 1328.12  5021.3 1332.29  5110.7 1336.86  5179.5 1338.77
  5242.7 1344.38    5327 1346.99  5348.1 1350.21  5411.4  1368.4  5474.6 1371.78
#Mann= 6 ,-1 , 0
  4284.4     .12       0  4548.7     .07       0  4899.7    .035       0
    4971    .035       0  5001.1    .035       0  5110.7     .12       0
Bank Sta=4971,5001.1
XS Rating Curve= 0 ,0
Exp/Cntr=0.3,0.1

Type RM Length L Ch R = 1 ,1161    ,550,550,550
BEGIN DESCRIPTION:
LITTLE JOSHUA CREEK 2.0
END DESCRIPTION:
XS GIS Cut Line= 3
        2034225.       13883125.        2034625.       13883125.
      2035124.99       13883025.
#Sta/Elev= 30
    4600 1350.38  4615.3 1350.45    4660 1351.21    4690 1350.27    4710 1350.99
    4850 1347.22    4940 1346.74    4960 1343.18    4970 1332.45  4974.9 1324.62
  4975.4 1324.12  5005.1 1324.62  5010.2 1329.05  5020.4 1330.65  5040.8 1331.69
  5061.2 1334.02  5085.5 1333.49  5112.2 1334.78  5132.6 1339.22  5163.2 1339.15
    5204 1341.88  5283.7 1343.94  5377.3  1345.3  5407.9 1346.82  5418.1 1349.49
  5428.3 1354.04  5458.9 1360.93  5479.3  1367.1  5489.5 1369.52  5509.9 1371.71
#Mann= 6 ,-1 , 0
    4600     .07       0  4615.3    .035       0  4974.9    .035       0
  5005.1    .035       0  5085.5     .12       0  5283.7     .07       0
Bank Sta=4974.9,5005.1
XS Rating Curve= 0 ,0
Exp/Cntr=0.3,0.1

Type RM Length L Ch R = 1 ,611     ,540,540,540
BEGIN DESCRIPTION:
LITTLE JOSHUA CREEK 1.0
END DESCRIPTION:
XS GIS Cut Line= 3
      2034425.03     13883674.99        2034875.       13883575.
      2035174.97     13883175.04
#Sta/Elev= 30
  4533.6  1348.9  4584.8 1346.83  4650.1 1347.68  4810.2 1346.06  4892.1 1343.28
  4953.6 1333.82  4970.2  1330.2  4986.7 1323.25  4987.2 1322.75  5016.9 1323.25
  5022.7 1325.65    5031 1325.41  5044.5 1330.83  5094.5  1333.4  5105.3 1335.03
  5122.7 1336.26    5131 1335.57  5187.3 1337.02  5208.1 1339.01  5260.1 1340.72
  5351.8 1344.11  5366.4 1345.62    5381 1349.48  5387.3 1352.79  5431.5 1363.14
  5437.3  1365.7  5458.1 1369.94  5466.4 1370.14  5472.7 1372.12  5494.5 1373.01
#Mann= 6 ,-1 , 0
  4533.6    .035       0  4986.7     .05       0  5016.9    .035       0
  5105.3     .12       0  5260.1     .07       0  5431.5     .12       0
Bank Sta=4986.7,5016.9
XS Rating Curve= 0 ,0
Exp/Cntr=0.3,0.1

Type RM Length L Ch R = 1 ,12      ,0,0,0
BEGIN DESCRIPTION:
LITTLE JOSHUA CREEK 0.0
END DESCRIPTION:
XS GIS Cut Line= 4
       2034654.1     13884510.65      2035167.88     13884065.91
      2035243.06       13883843.      2035206.16     13883289.71
#Sta/Elev= 30
  4321.9 1353.89  4383.4  1353.4  4394.9 1353.23  4522.1 1353.53  4685.1 1355.91
  4745.2 1352.08    4790 1344.71  4808.8 1341.69  4815.5 1336.89  4823.1 1336.12
  4829.7 1331.82  4886.7 1328.18    4901 1325.66  4953.9 1325.42  4957.9 1325.26
  4960.5  1321.4  4961.5  1320.9  5010.5  1321.4  5034.1 1323.21  5044.6 1328.23
  5065.5 1331.71  5118.5 1331.98  5227.3  1338.8    5289 1339.99  5656.1 1345.36
  5665.6 1345.91  5705.7 1354.57  5745.8  1359.2  5775.9 1367.61  5791.2 1369.02
#Mann= 12 ,-1 , 0
  4321.9     .07       0  4383.4    .035       0  4394.9     .07       0
  4522.1    .035       0  4685.1     .07       0    4790    .035       0
  4953.9     .07       0  4960.5     .05       0  5010.5     .07       0
  5227.3     .12       0    5289     .07       0  5656.1     .12       0
Bank Sta=4960.5,5010.5
XS Rating Curve= 0 ,0
Exp/Cntr=0.3,0.1

Chan Stop Cuts=-1
Use User Specified Reach Order=0
Composite Channel Slope=5