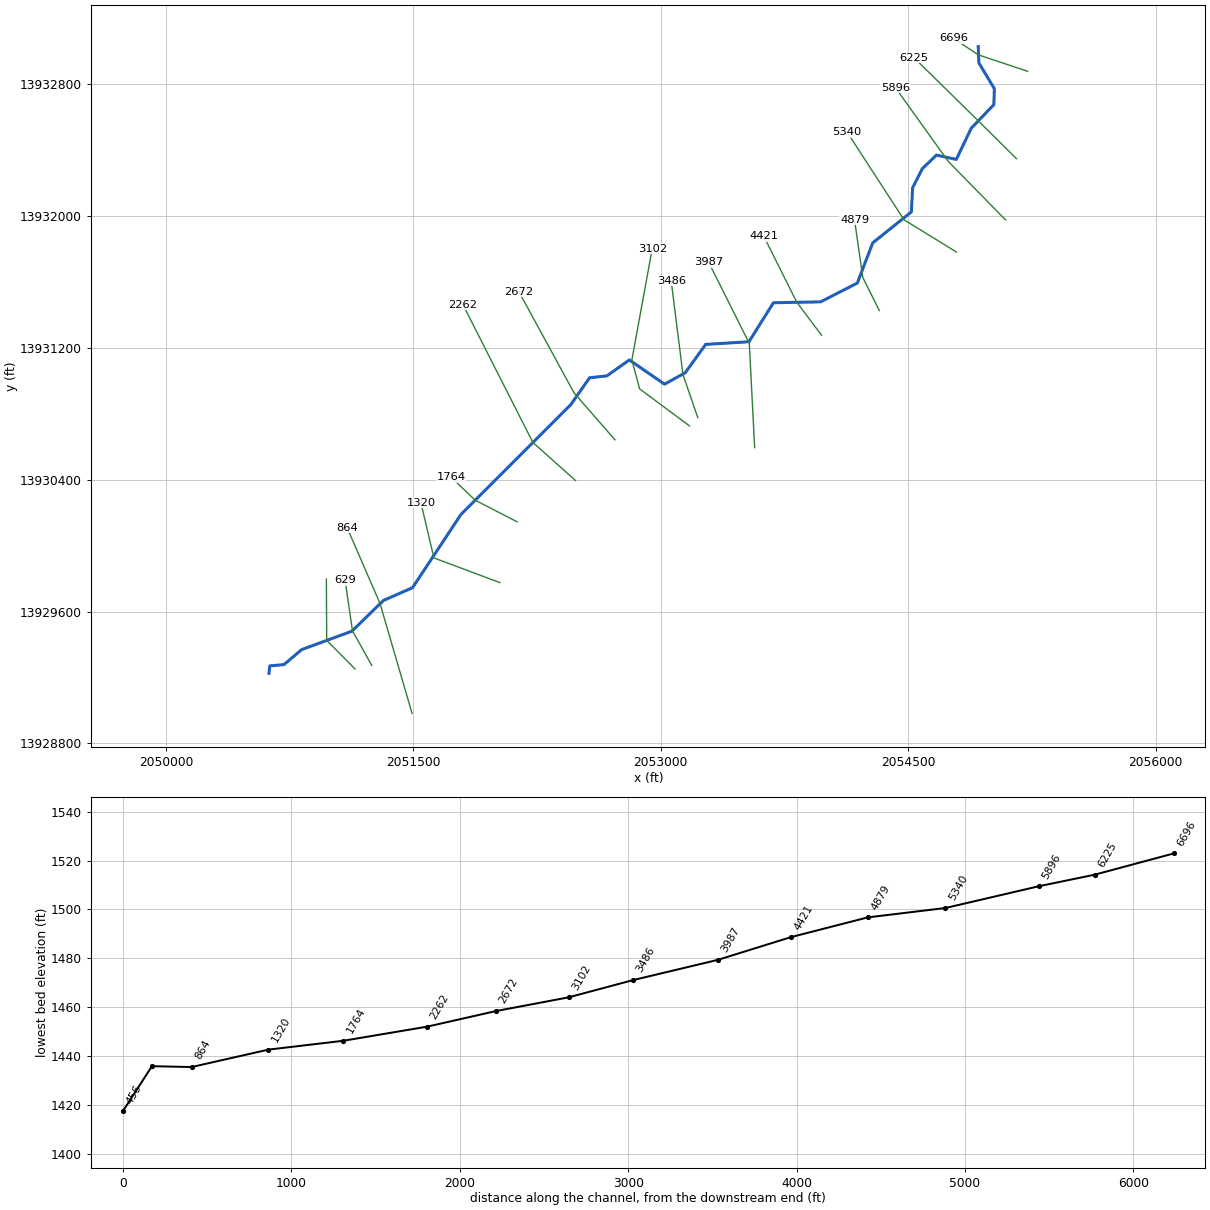
--- PLATTE CREEK.prj (project) ---

Proj Title=PLATTE CREEK Base Level Engineering
Current Plan=p01
Default Exp/Contr=0.3,0.1
English Units
Geom File=g01
Flow File=f01
Plan File=p01
BEGIN DESCRIPTION:
PLATTE CREEK
END DESCRIPTION:

--- PLATTE CREEK.p01 (plan) ---

Plan Title=Multiple Run
Short Identifier=Multiple
Geom File=g01
Flow File=f01
Subcritical Flow
K Sum by GR= 0
Std Step Tol= 0.01
Critical Tol= 0.01
Num of Std Step Trials= 20
Max Error Tol= 0.3
Flow Tol Ratio= 0.001
Split Flow NTrial= 30
Split Flow Tol= 0.02
Split Flow Ratio= 0.02
Log Output Level= 0
Friction Slope Method= 1
Unsteady Friction Slope Method= 2
Unsteady Bridges Friction Slope Method= 1
Parabolic Critical Depth
Global Vel Dist=  1 , 1 , 1
Global Log Level= 0
CheckData=True
Encroach Param= -1, 0, 0, 0
BEGIN DESCRIPTION:
Multiple Run
END DESCRIPTION:

--- PLATTE CREEK.f01 (steady flow) ---

Flow Title=Multiple
Number of Profiles=7
Profile Names=10-year,25-year,50-year,1pct_min,100-year,1pct_plu,500-year
River Rch & RM= PLATTE CREEK,Reach-1,6696
    1229    2145    3044    2097    4184    8348    7837
River Rch & RM= PLATTE CREEK,Reach-1,5340
    1609    2837    4053    2807    5601   11176   10613
Boundary for River Rch & Prof#=PLATTE CREEK,Reach-1,1
Up Type=0
Dn Type=3
Dn Slope=0.005
Boundary for River Rch & Prof#=PLATTE CREEK,Reach-1,2
Up Type=0
Dn Type=3
Dn Slope=0.005
Boundary for River Rch & Prof#=PLATTE CREEK,Reach-1,3
Up Type=0
Dn Type=3
Dn Slope=0.005
Boundary for River Rch & Prof#=PLATTE CREEK,Reach-1,4
Up Type=0
Dn Type=3
Dn Slope=0.005
Boundary for River Rch & Prof#=PLATTE CREEK,Reach-1,5
Up Type=0
Dn Type=3
Dn Slope=0.005
Boundary for River Rch & Prof#=PLATTE CREEK,Reach-1,6
Up Type=0
Dn Type=3
Dn Slope=0.005
Boundary for River Rch & Prof#=PLATTE CREEK,Reach-1,7
Up Type=0
Dn Type=3
Dn Slope=0.005

--- PLATTE CREEK.g01 (geometry) ---

Geom Title=Existing Conditions

River Reach=PLATTE CREEK,Reach-1
Reach XY= 30
      2054925.00     13933025.00      2054928.63     13932926.50
      2055022.74     13932769.44      2055019.60     13932672.57
      2054883.14     13932531.06      2054792.05     13932341.07
      2054671.58     13932367.19      2054585.76     13932284.73
      2054527.25     13932169.07      2054519.53     13932022.55
      2054285.39     13931835.10      2054192.06     13931591.49
      2053969.07     13931477.24      2053683.28     13931471.94
      2053534.82     13931235.47      2053272.53     13931219.55
      2053148.84     13931047.85      2053023.27     13930978.31
      2052809.64     13931125.11      2052673.50     13931028.63
      2052568.81     13931017.14      2052455.21     13930854.91
      2051788.63     13930188.21      2051495.47     13929744.62
      2051318.94     13929666.86      2051127.43     13929480.52
      2050822.77     13929368.93      2050716.51     13929278.45
      2050629.78     13929270.22      2050625.00     13929225.00

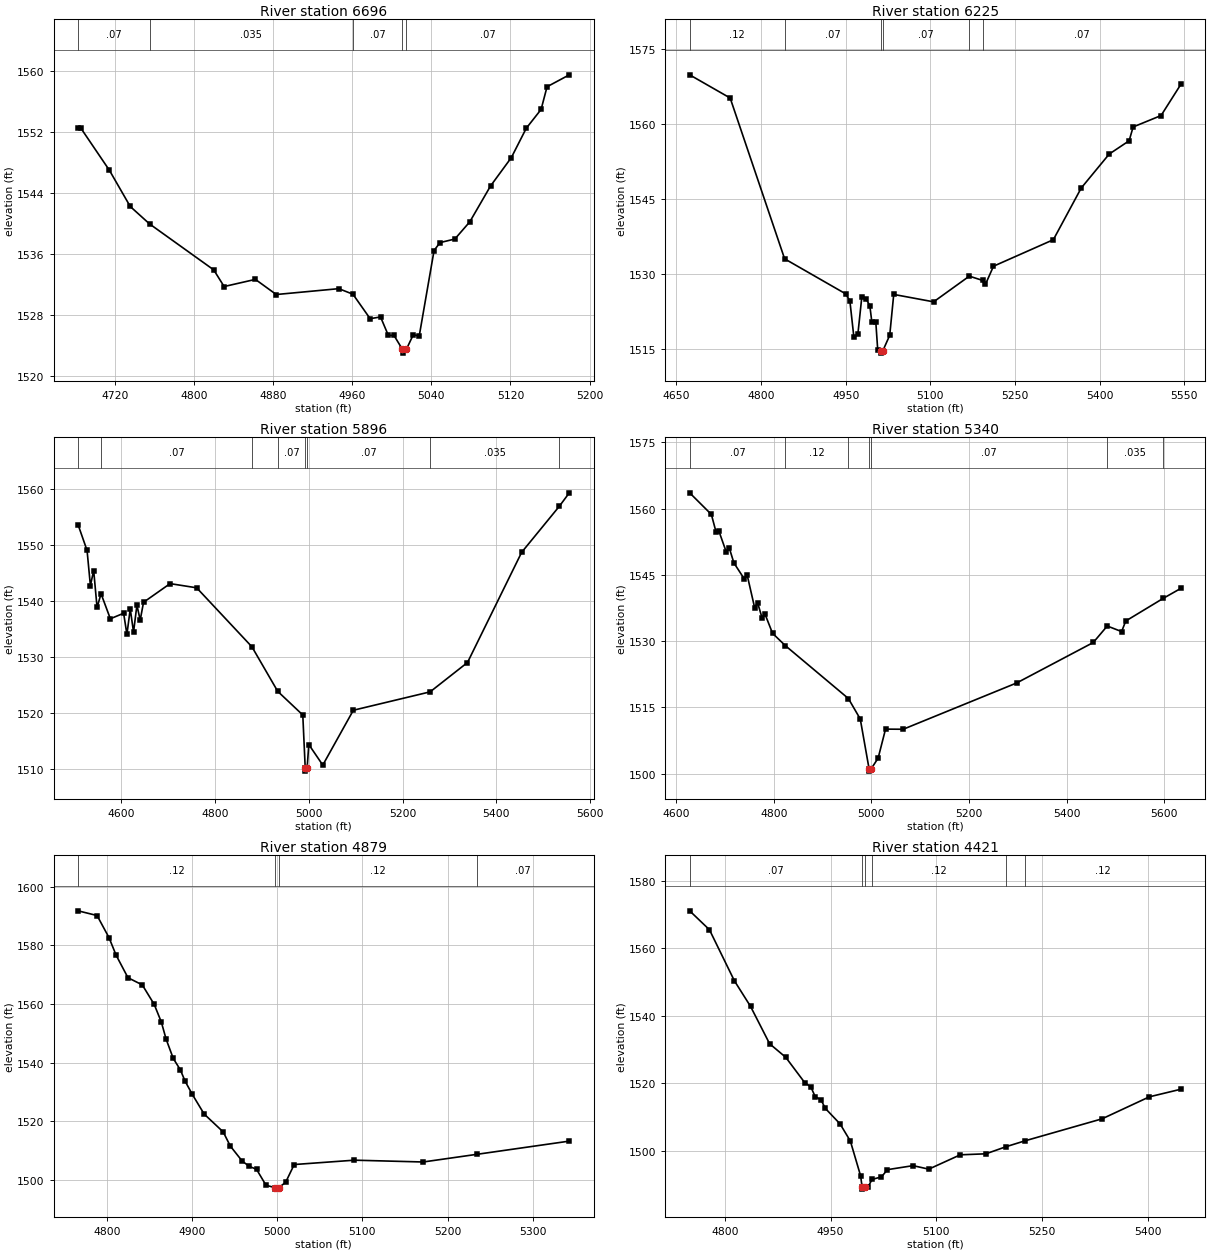
Type RM Length L Ch R = 1,6696,471,471,471
BEGIN DESCRIPTION:
PLATTE CREEK 15.0
END DESCRIPTION:
XS GIS Cut Line= 3
      2055225.02     13932874.99      2054925.00     13932975.00
      2054775.02     13933074.99
#Sta/Elev= 30
  4683.0 1552.56  4685.7 1552.56  4714.6 1547.01  4735.7 1542.24  4755.2 1539.95
  4820.1 1533.90  4830.6 1531.71  4862.2 1532.65  4883.3 1530.66  4946.5 1531.43
  4960.8 1530.70  4978.2 1527.48  4988.7 1527.71  4996.6 1525.28  5002.3 1525.28
  5010.8 1523.45  5011.0 1522.95  5014.8 1523.45  5021.8 1525.37  5027.8 1525.20
  5042.8 1536.45  5048.8 1537.49  5063.8 1537.96  5078.9 1540.22  5099.9 1544.94
  5120.9 1548.67  5136.0 1552.53  5151.0 1555.01  5157.0 1557.99  5179.5 1559.56
#Mann=5,-1,0
  4683.0    0.07       0  4755.2   0.035       0  4960.8    0.07       0
  5010.8    0.05       0  5014.8    0.07       0
Bank Sta=5010.8,5014.8
Exp/Cntr=0.3,0.1

Type RM Length L Ch R = 1,6225,329,329,329
BEGIN DESCRIPTION:
PLATTE CREEK 14.0
END DESCRIPTION:
XS GIS Cut Line= 3
      2055156.97     13932345.42      2054925.00     13932575.00
      2054536.74     13932956.36
#Sta/Elev= 30
  4673.4 1569.78  4745.2 1565.15  4841.7 1533.05  4950.3 1526.03  4957.4 1524.63
  4964.4 1517.47  4971.5 1517.96  4978.6 1525.50  4985.7 1525.12  4992.7 1523.70
  4996.3 1520.46  5003.3 1520.46  5006.8 1514.75  5011.9 1514.72  5012.1 1514.22
  5015.9 1514.72  5028.0 1517.78  5035.1 1525.94  5105.8 1524.46  5169.1 1529.59
  5192.5 1528.74  5197.7 1527.96  5211.9 1531.57  5318.0 1536.86  5367.4 1547.18
  5417.0 1553.96  5452.3 1556.61  5459.4 1559.37  5508.9 1561.65  5544.0 1567.88
#Mann=6,-1,0
  4673.4    0.12       0  4841.7    0.07       0  5011.9    0.05       0
  5015.9    0.07       0  5169.1   0.035       0  5192.5    0.07       0
Bank Sta=5011.9,5015.9
Exp/Cntr=0.3,0.1

Type RM Length L Ch R = 1,5896,556,556,556
BEGIN DESCRIPTION:
PLATTE CREEK 13.0
END DESCRIPTION:
XS GIS Cut Line= 3
      2055090.97     13931973.91      2054743.76     13932328.07
      2054423.08     13932775.56
#Sta/Elev= 30
  4508.8 1553.59  4527.9 1549.00  4535.0 1542.72  4542.0 1545.41  4549.2 1538.80
  4557.7 1541.26  4577.5 1536.78  4605.8 1537.77  4612.8 1533.99  4619.9 1538.54
  4626.9 1534.40  4634.1 1539.22  4641.1 1536.54  4648.2 1539.73  4704.8 1543.07
  4761.4 1542.32  4879.1 1531.77  4934.1 1523.80  4987.5 1519.57  4992.7 1510.03
  4992.9 1509.53  4996.7 1510.03  5000.3 1514.29  5030.1 1510.61  5095.2 1520.42
  5258.8 1523.71  5338.4 1528.96  5453.8 1548.67  5534.0 1556.90  5555.3 1559.31
#Mann=8,-1,0
  4508.8    0.12       0  4557.7    0.07       0  4879.1    0.12       0
  4934.1    0.07       0  4992.7    0.05       0  4996.7    0.07       0
  5258.8   0.035       0  5534.0    0.07       0
Bank Sta=4992.7,4996.7
Exp/Cntr=0.3,0.1

Type RM Length L Ch R = 1,5340,461,461,461
BEGIN DESCRIPTION:
PLATTE CREEK 12.0
END DESCRIPTION:
XS GIS Cut Line= 3
      2054792.37     13931779.46      2054475.00     13931975.00
      2054129.79     13932506.80
#Sta/Elev= 30
  4627.5 1563.59  4672.0 1558.70  4681.5 1554.76  4687.4 1554.94  4702.8 1550.11
  4708.6 1551.15  4718.2 1547.72  4739.5 1544.10  4745.3 1545.02  4760.7 1537.59
  4766.6 1538.75  4776.1 1535.22  4782.0 1536.12  4797.4 1531.79  4823.4 1529.02
  4952.8 1517.03  4977.2 1512.39  4995.3 1501.09  4995.6 1500.59  4999.4 1501.09
  5013.8 1503.53  5029.0 1510.10  5065.2 1510.07  5297.8 1520.55  5454.8 1529.71
  5483.4 1533.44  5512.9 1532.18  5521.3 1534.57  5598.3 1539.71  5634.3 1541.96
#Mann=7,-1,0
  4627.5    0.07       0  4823.4    0.12       0  4952.8    0.07       0
  4995.3    0.05       0  4999.4    0.07       0  5483.4   0.035       0
  5598.3    0.12       0
Bank Sta=4995.3,4999.4
Exp/Cntr=0.3,0.1

Type RM Length L Ch R = 1,4879,458,458,458
BEGIN DESCRIPTION:
PLATTE CREEK 11.0
END DESCRIPTION:
XS GIS Cut Line= 3
      2054324.98     13931425.04      2054225.00     13931625.00
      2054175.00     13931974.99
#Sta/Elev= 30
  4766.0 1591.82  4788.3 1590.21  4802.3 1582.67  4810.7 1576.64  4824.6 1568.97
  4841.4 1566.52  4855.4 1559.87  4863.8 1553.81  4869.4 1547.99  4877.8 1541.39
  4886.1 1537.52  4891.7 1533.63  4900.1 1529.15  4914.1 1522.40  4936.5 1516.28
  4944.8 1511.47  4958.8 1506.33  4967.2 1504.51  4975.6 1503.53  4986.8 1498.06
  4997.6 1497.25  4997.9 1496.75  5001.5 1496.75  5001.7 1497.25  5009.8 1499.07
  5019.9 1505.15  5090.6 1506.64  5171.4 1506.02  5234.8 1508.65  5343.1 1513.15
#Mann=4,-1,0
  4766.0    0.12       0  4997.6    0.05       0  5001.7    0.12       0
  5234.8    0.07       0
Bank Sta=4997.6,5001.7
Exp/Cntr=0.3,0.1

Type RM Length L Ch R = 1,4421,434,434,434
BEGIN DESCRIPTION:
PLATTE CREEK 10.0
END DESCRIPTION:
XS GIS Cut Line= 3
      2053974.99     13931275.01      2053825.00     13931475.00
      2053625.00     13931875.00
#Sta/Elev= 30
  4750.0 1571.12  4778.1 1565.51  4813.5 1550.38  4836.4 1542.80  4863.5 1531.72
  4886.4 1527.70  4913.5 1520.15  4921.9 1518.97  4928.1 1516.08  4936.4 1515.08
  4942.7 1512.53  4963.5 1507.96  4978.1 1502.88  4992.7 1492.53  4994.8 1489.13
  4995.1 1488.63  4998.9 1489.13  5002.8 1489.13  5008.9 1491.51  5022.3 1492.26
  5030.7 1494.40  5067.1 1495.59  5089.4 1494.55  5134.1 1498.80  5170.5 1499.10
  5199.0 1501.20  5225.5 1502.92  5335.4 1509.47  5402.5 1515.99  5447.2 1518.24
#Mann=6,-1,0
  4750.0    0.07       0  4994.8    0.05       0  4998.9    0.07       0
  5008.9    0.12       0  5199.0    0.07       0  5225.5    0.12       0
Bank Sta=4994.8,4998.9
Exp/Cntr=0.3,0.1

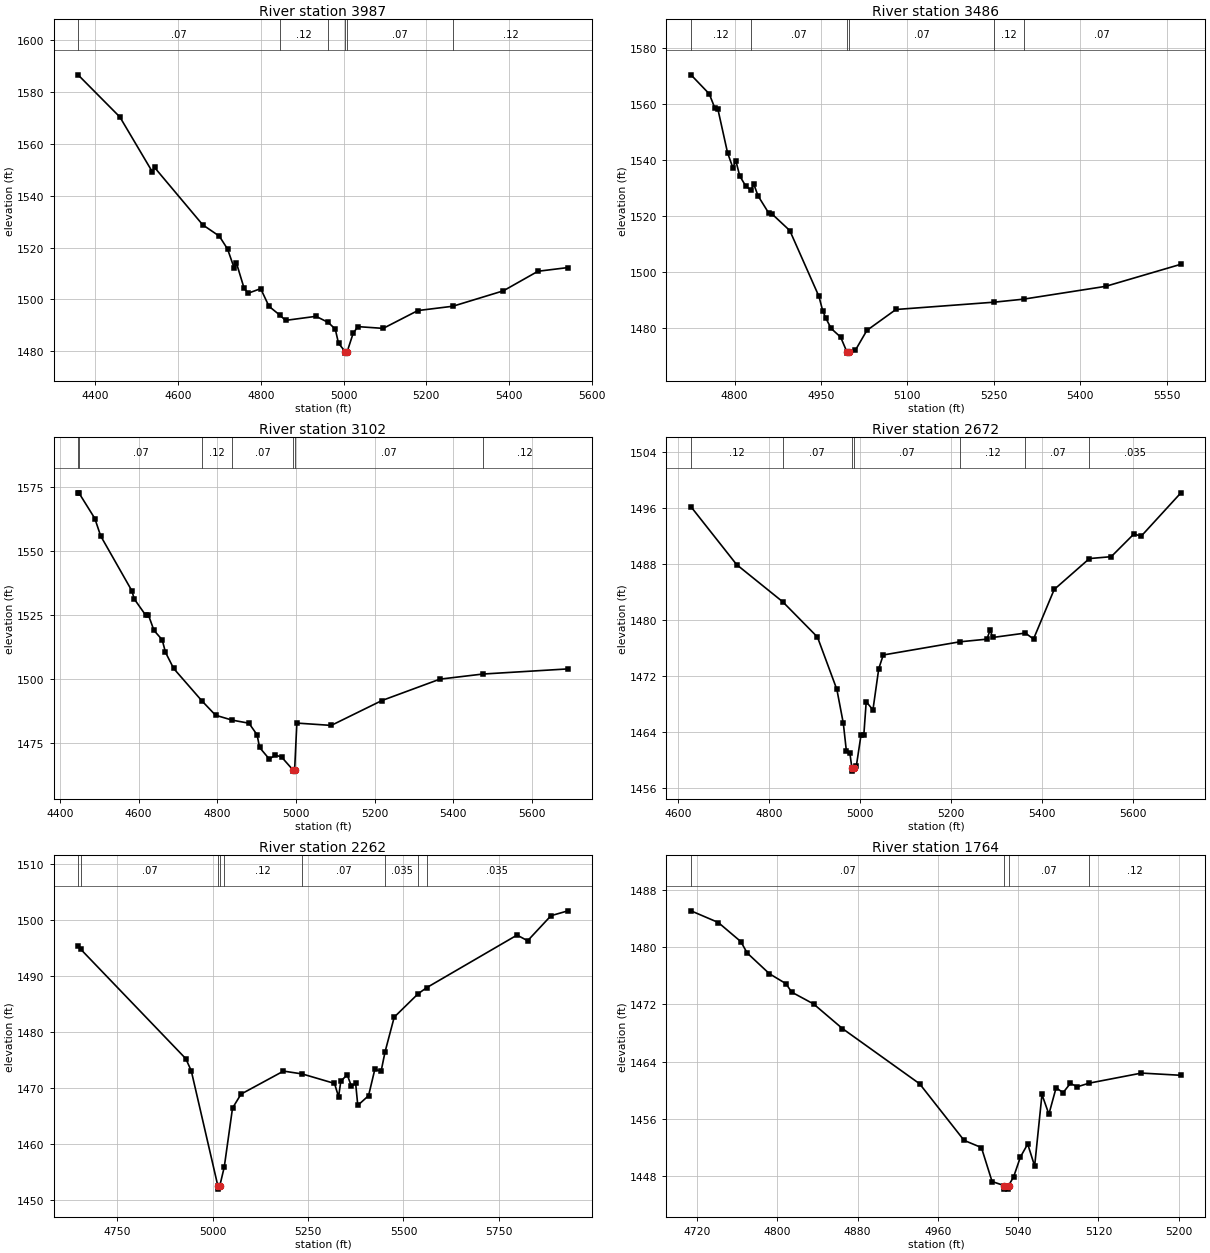
Type RM Length L Ch R = 1,3987,501,501,501
BEGIN DESCRIPTION:
PLATTE CREEK 9.0
END DESCRIPTION:
XS GIS Cut Line= 3
      2053569.41     13930593.94      2053536.99     13931225.86
      2053289.55     13931719.13
#Sta/Elev= 30
  4358.1 1586.62  4459.3 1570.35  4538.0 1549.15  4543.0 1550.92  4659.6 1528.78
  4699.6 1524.44  4719.6 1519.46  4735.8 1512.04  4740.8 1514.21  4759.7 1504.28
  4769.7 1502.43  4799.7 1504.18  4819.8 1497.37  4845.8 1494.00  4859.8 1491.94
  4933.5 1493.51  4962.8 1491.17  4980.0 1488.61  4987.9 1483.11  5004.5 1479.82
  5004.7 1479.32  5008.7 1479.82  5023.3 1486.96  5034.6 1489.54  5095.9 1488.86
  5179.7 1495.73  5264.4 1497.40  5386.3 1503.33  5470.1 1510.88  5542.7 1512.31
#Mann=6,-1,0
  4358.1    0.07       0  4845.8    0.12       0  4962.8    0.07       0
  5004.5    0.05       0  5008.7    0.07       0  5264.4    0.12       0
Bank Sta=5004.5,5008.7
Exp/Cntr=0.3,0.1

Type RM Length L Ch R = 1,3486,384,384,384
BEGIN DESCRIPTION:
PLATTE CREEK 8.0
END DESCRIPTION:
XS GIS Cut Line= 3
      2053224.99     13930775.03      2053135.00     13931035.63
      2053063.21     13931605.83
#Sta/Elev= 30
  4724.3 1570.32  4756.0 1563.53  4765.8 1558.43  4771.1 1557.99  4787.7 1542.59
  4796.9 1537.24  4802.2 1539.65  4808.9 1534.28  4819.5 1530.59  4828.3 1529.24
  4833.4 1531.31  4840.6 1527.19  4859.3 1521.00  4864.6 1520.76  4895.8 1514.78
  4946.4 1491.30  4952.9 1486.20  4958.2 1483.60  4967.6 1479.87  4984.1 1476.77
  4994.8 1471.57  4995.1 1471.07  4999.2 1471.57  5009.4 1472.01  5029.6 1479.17
  5080.0 1486.63  5251.1 1489.25  5301.6 1490.32  5444.1 1494.89  5574.7 1502.76
#Mann=6,-1,0
  4724.3    0.12       0  4828.3    0.07       0  4994.8    0.05       0
  4999.2    0.07       0  5251.1    0.12       0  5301.6    0.07       0
Bank Sta=4994.8,4999.2
Exp/Cntr=0.3,0.1

Type RM Length L Ch R = 1,3102,430,430,430
BEGIN DESCRIPTION:
PLATTE CREEK 7.0
END DESCRIPTION:
XS GIS Cut Line= 4
      2053174.97     13930725.02      2052872.23     13930949.60
      2052825.00     13931125.00      2052948.60     13931800.19
#Sta/Elev= 30
  4446.1 1572.59  4448.2 1572.59  4488.8 1562.57  4503.5 1555.80  4582.8 1534.38
  4589.0 1531.15  4618.2 1524.79  4624.5 1525.09  4639.1 1518.88  4659.9 1515.26
  4668.3 1510.35  4689.1 1504.05  4760.6 1491.45  4795.5 1485.81  4837.8 1483.89
  4880.4 1482.69  4901.1 1478.16  4907.4 1473.22  4932.2 1468.69  4947.4 1470.26
  4963.3 1469.49  4992.1 1464.49  4992.4 1463.99  4996.5 1464.49  5002.1 1482.74
  5089.5 1481.83  5218.2 1491.53  5365.6 1499.88  5474.4 1501.87  5691.1 1503.88
#Mann=7,-1,0
  4446.1    0.12       0  4448.2    0.07       0  4760.6    0.12       0
  4837.8    0.07       0  4992.1    0.05       0  4996.5    0.07       0
  5474.4    0.12       0
Bank Sta=4992.1,4996.5
Exp/Cntr=0.3,0.1

Type RM Length L Ch R = 1,2672,410,410,410
BEGIN DESCRIPTION:
PLATTE CREEK 6.0
END DESCRIPTION:
XS GIS Cut Line= 3
      2052722.90     13930640.60      2052475.00     13930925.00
      2052139.77     13931539.54
#Sta/Elev= 30
  4627.7 1496.15  4728.2 1487.88  4829.4 1482.58  4905.8 1477.54  4948.5 1470.05
  4962.7 1465.21  4969.4 1461.26  4977.0 1461.02  4981.4 1458.89  4981.7 1458.39
  4985.8 1458.89  4991.2 1459.08  5001.7 1463.60  5007.8 1463.60  5013.0 1468.30
  5027.8 1467.14  5040.6 1473.03  5050.5 1474.98  5218.8 1476.86  5278.4 1477.24
  5285.5 1478.56  5291.2 1477.48  5363.0 1478.11  5380.9 1477.26  5426.4 1484.34
  5503.8 1488.75  5551.7 1489.02  5601.6 1492.26  5617.7 1491.95  5705.0 1498.14
#Mann=7,-1,0
  4627.7    0.12       0  4829.4    0.07       0  4981.4    0.05       0
  4985.8    0.07       0  5218.8    0.12       0  5363.0    0.07       0
  5503.8   0.035       0
Bank Sta=4981.4,4985.8
Exp/Cntr=0.3,0.1

Type RM Length L Ch R = 1,2262,498,498,498
BEGIN DESCRIPTION:
PLATTE CREEK 5.0
END DESCRIPTION:
XS GIS Cut Line= 3
      2052483.31     13930394.07      2052225.00     13930625.00
      2051800.56     13931461.04
#Sta/Elev= 30
  4647.1 1495.38  4654.6 1494.77  4929.6 1475.26  4943.9 1473.09  5013.8 1452.48
  5014.1 1451.98  5018.3 1452.48  5030.3 1455.91  5052.0 1466.45  5074.3 1468.94
  5185.6 1473.05  5234.8 1472.54  5319.2 1470.85  5330.0 1468.46  5335.8 1471.23
  5352.5 1472.41  5363.7 1470.33  5374.7 1470.86  5380.3 1466.93  5408.5 1468.66
  5424.9 1473.34  5441.5 1473.06  5451.9 1476.52  5475.8 1482.68  5538.5 1486.86
  5560.5 1487.93  5797.7 1497.33  5825.5 1496.32  5886.7 1500.79  5931.2 1501.66
#Mann=9,-1,0
  4647.1    0.12       0  4654.6    0.07       0  5013.8    0.05       0
  5018.3    0.07       0  5030.3    0.12       0  5234.8    0.07       0
  5451.9   0.035       0  5538.5    0.07       0  5560.5   0.035       0
Bank Sta=5013.8,5018.3
Exp/Cntr=0.3,0.1

Type RM Length L Ch R = 1,1764,444,444,444
BEGIN DESCRIPTION:
PLATTE CREEK 4.0
END DESCRIPTION:
XS GIS Cut Line= 3
      2052129.14     13930144.06      2051875.00     13930275.00
      2051728.79     13930414.55
#Sta/Elev= 30
  4714.1 1485.05  4741.3 1483.42  4763.7 1480.76  4770.1 1479.16  4792.2 1476.27
  4808.7 1474.88  4814.4 1473.70  4836.2 1472.05  4865.0 1468.61  4941.8 1460.91
  4986.1 1453.01  5003.4 1452.00  5014.0 1447.26  5025.9 1446.70  5026.2 1446.20
  5030.1 1446.20  5030.4 1446.70  5035.4 1447.89  5042.3 1450.71  5049.5 1452.49
  5056.4 1449.42  5063.7 1459.41  5070.6 1456.66  5077.8 1460.36  5084.7 1459.66
  5092.0 1460.96  5098.9 1460.49  5110.9 1461.00  5162.8 1462.40  5202.1 1462.09
#Mann=4,-1,0
  4714.1    0.07       0  5025.9    0.05       0  5030.4    0.07       0
  5110.9    0.12       0
Bank Sta=5025.9,5030.4
Exp/Cntr=0.3,0.1

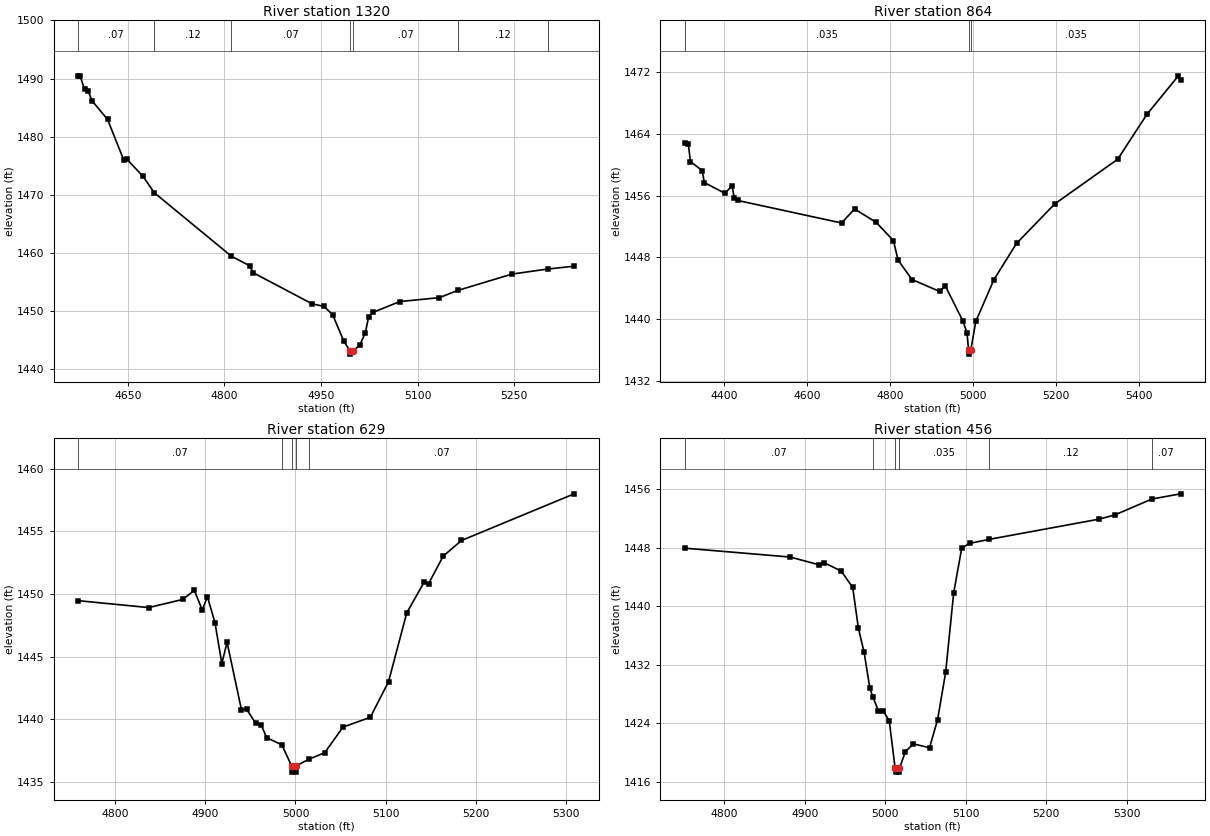
Type RM Length L Ch R = 1,1320,456,456,456
BEGIN DESCRIPTION:
PLATTE CREEK 3.0
END DESCRIPTION:
XS GIS Cut Line= 3
      2052025.03     13929774.99      2051625.00     13929925.00
      2051546.25     13930258.81
#Sta/Elev= 30
  4573.0 1490.47  4575.7 1490.47  4582.8 1488.12  4588.2 1487.86  4594.4 1486.16
  4618.4 1482.97  4643.3 1476.04  4648.7 1476.08  4673.6 1473.16  4690.9 1470.36
  4810.6 1459.44  4839.1 1457.79  4844.5 1456.59  4936.1 1451.24  4954.8 1450.79
  4968.2 1449.34  4985.1 1444.87  4995.3 1443.08  4995.6 1442.58  4999.8 1443.08
  5010.5 1444.21  5018.8 1446.24  5024.0 1449.02  5031.1 1449.78  5072.1 1451.62
  5133.8 1452.30  5162.1 1453.53  5246.8 1456.36  5302.6 1457.23  5343.2 1457.71
#Mann=7,-1,0
  4573.0    0.07       0  4690.9    0.12       0  4810.6    0.07       0
  4995.3    0.05       0  4999.8    0.07       0  5162.1    0.12       0
  5302.6   0.035       0
Bank Sta=4995.3,4999.8
Exp/Cntr=0.3,0.1

Type RM Length L Ch R = 1,864,235,235,235
BEGIN DESCRIPTION:
PLATTE CREEK 2.0
END DESCRIPTION:
XS GIS Cut Line= 3
      2051492.50     13928982.47      2051298.18     13929648.71
      2051099.05     13930107.67
#Sta/Elev= 30
  4306.0 1462.89  4314.4 1462.75  4319.6 1460.43  4347.9 1459.26  4353.1 1457.70
  4402.4 1456.32  4420.0 1457.27  4425.2 1455.68  4433.6 1455.38  4683.6 1452.46
  4714.9 1454.28  4767.0 1452.54  4808.6 1450.17  4819.6 1447.66  4853.1 1445.13
  4920.0 1443.58  4933.6 1444.29  4975.3 1439.80  4985.7 1438.24  4989.6 1435.95
  4990.0 1435.45  4994.8 1435.95  5006.9 1439.69  5050.8 1445.13  5105.0 1449.81
  5197.0 1454.93  5348.7 1460.73  5419.1 1466.55  5494.9 1471.55  5500.3 1471.01
#Mann=3,-1,0
  4306.0   0.035       0  4989.6   0.035       0  4994.8   0.035       0
Bank Sta=4989.6,4994.8
Exp/Cntr=0.3,0.1

Type RM Length L Ch R = 1,629,173,173,173
BEGIN DESCRIPTION:
PLATTE CREEK 1.5
END DESCRIPTION:
XS GIS Cut Line= 3
      2051248.44     13929272.66      2051131.17     13929482.86
      2051086.61     13929788.63
#Sta/Elev= 30
  4759.3 1449.47  4837.3 1448.92  4875.0 1449.57  4887.9 1450.29  4896.7 1448.73
  4902.4 1449.79  4910.8 1447.71  4918.4 1444.46  4924.2 1446.15  4940.1 1440.79
  4945.9 1440.81  4956.1 1439.68  4961.9 1439.58  4968.1 1438.55  4985.0 1437.97
  4995.7 1436.30  4996.2 1435.80  5000.6 1435.80  5001.0 1436.30  5014.6 1436.82
  5032.5 1437.35  5052.7 1439.39  5083.0 1440.17  5103.2 1443.01  5123.4 1448.50
  5142.7 1450.95  5147.7 1450.84  5163.9 1453.03  5184.1 1454.27  5309.0 1457.99
#Mann=5,-1,0
  4759.3    0.07       0  4985.0    0.12       0  4995.7    0.05       0
  5001.0    0.12       0  5014.6    0.07       0
Bank Sta=4995.7,5001
Exp/Cntr=0.3,0.1

Type RM Length L Ch R = 1,456,0,0,0
BEGIN DESCRIPTION:
PLATTE CREEK 1.0
END DESCRIPTION:
XS GIS Cut Line= 3
      2051146.55     13929251.67      2050975.00     13929425.00
      2050972.93     13929796.82
#Sta/Elev= 30
  4751.1 1447.93  4881.9 1446.72  4917.2 1445.68  4924.3 1445.94  4945.5 1444.79
  4959.6 1442.56  4966.7 1436.97  4973.8 1433.70  4980.9 1428.80  4984.7 1427.61
  4991.5 1425.72  4997.5 1425.72  5005.0 1424.34  5012.3 1417.85  5012.8 1417.35
  5017.2 1417.35  5017.6 1417.85  5025.0 1420.15  5035.0 1421.21  5055.0 1420.68
  5065.0 1424.51  5075.0 1430.97  5085.0 1441.83  5095.0 1447.96  5105.0 1448.59
  5129.4 1449.14  5265.0 1451.88  5285.0 1452.46  5331.1 1454.64  5366.8 1455.35
#Mann=6,-1,0
  4751.1    0.07       0  4984.7   0.035       0  5012.3   0.035       0
  5017.6   0.035       0  5129.4    0.12       0  5331.1    0.07       0
Bank Sta=5012.3,5017.6
Exp/Cntr=0.3,0.1

Chan Stop Cuts=-1