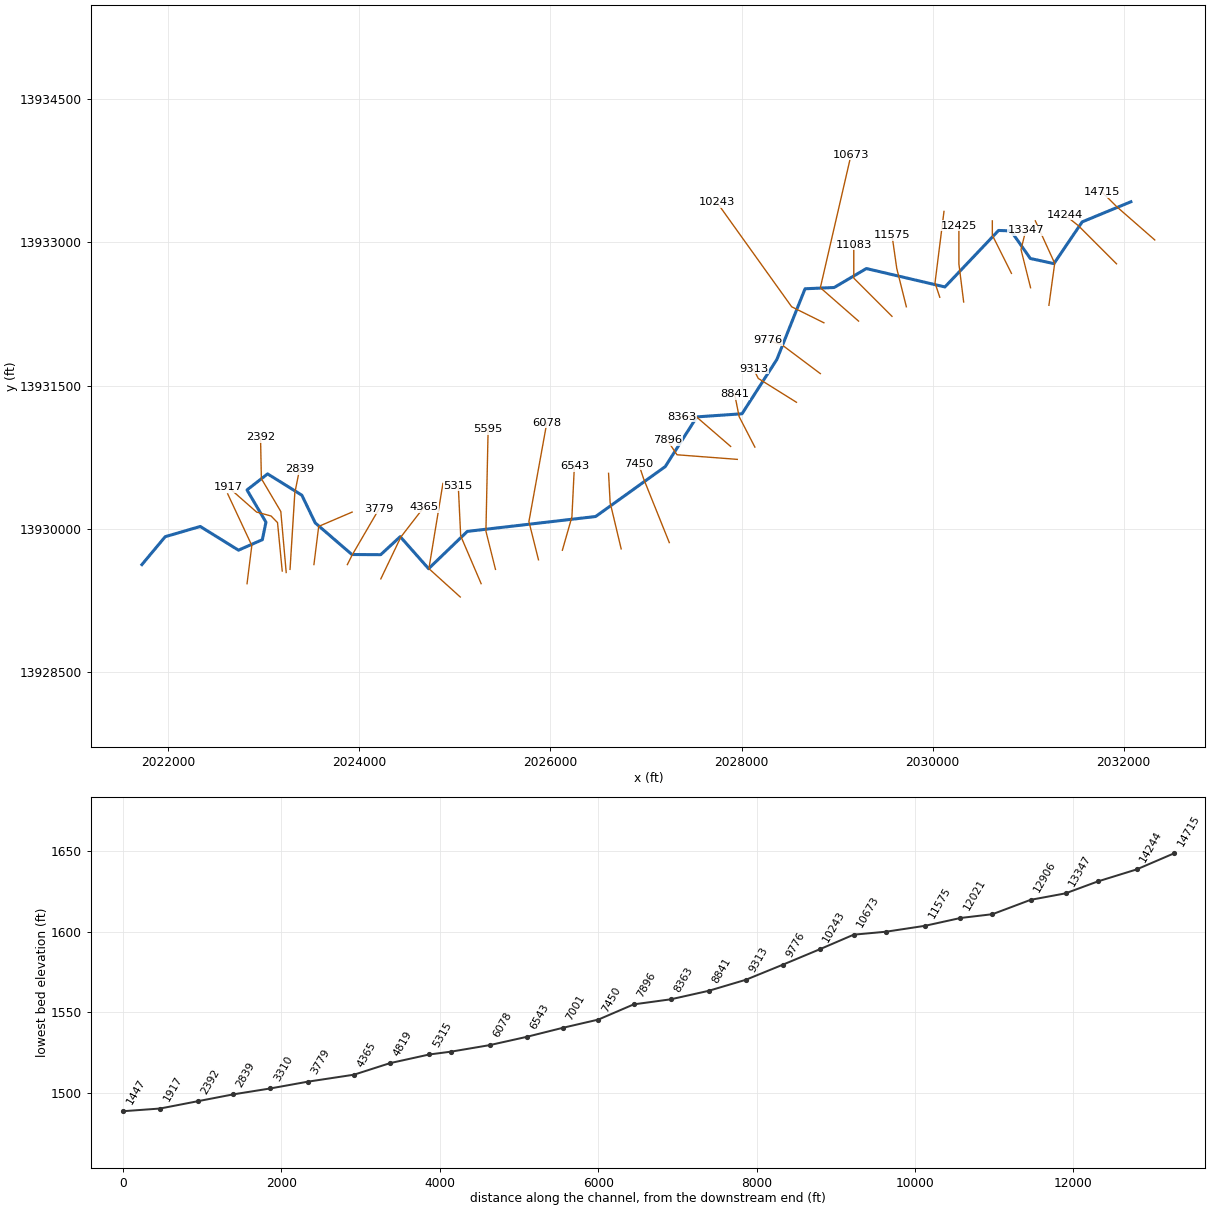
--- POLECAT SPRING CREEK.prj (project) ---

Proj Title=POLECAT SPRING CREEK Base Level Engineering
Current Plan=p01
Default Exp/Contr=0.3,0.1
English Units
Geom File=g01
Flow File=f01
Plan File=p01
BEGIN DESCRIPTION:
POLECAT SPRING CREEK
END DESCRIPTION:

--- POLECAT SPRING CREEK.p01 (plan) ---

Plan Title=Multiple Run
Short Identifier=Multiple
Geom File=g01
Flow File=f01
Subcritical Flow
K Sum by GR= 0
Std Step Tol= 0.01
Critical Tol= 0.01
Num of Std Step Trials= 20
Max Error Tol= 0.3
Flow Tol Ratio= 0.001
Split Flow NTrial= 30
Split Flow Tol= 0.02
Split Flow Ratio= 0.02
Log Output Level= 0
Friction Slope Method= 1
Unsteady Friction Slope Method= 2
Unsteady Bridges Friction Slope Method= 1
Parabolic Critical Depth
Global Vel Dist=  1 , 1 , 1
Global Log Level= 0
CheckData=True
Encroach Param= -1, 0, 0, 0
BEGIN DESCRIPTION:
Multiple Run
END DESCRIPTION:

--- POLECAT SPRING CREEK.f01 (steady flow) ---

Flow Title=Multiple
Number of Profiles=7
Profile Names=10-year,25-year,50-year,1pct_min,100-year,1pct_plu,500-year
River Rch & RM= POLECAT SPRING C,Reach-1,14715
    1557    2744    3916    2709    5405   10785   10221
River Rch & RM= POLECAT SPRING C,Reach-1,10243
    1782    3159    4526    3140    6266   12502   11925
River Rch & RM= POLECAT SPRING C,Reach-1,7450
    2365    4231    6099    4254    8489   16937   16324
River Rch & RM= POLECAT SPRING C,Reach-1,4819
    2367    4238    6111    4262    8503   16966   16352
Boundary for River Rch & Prof#=POLECAT SPRING C,Reach-1,1
Up Type=0
Dn Type=3
Dn Slope=0.005
Boundary for River Rch & Prof#=POLECAT SPRING C,Reach-1,2
Up Type=0
Dn Type=3
Dn Slope=0.005
Boundary for River Rch & Prof#=POLECAT SPRING C,Reach-1,3
Up Type=0
Dn Type=3
Dn Slope=0.005
Boundary for River Rch & Prof#=POLECAT SPRING C,Reach-1,4
Up Type=0
Dn Type=3
Dn Slope=0.005
Boundary for River Rch & Prof#=POLECAT SPRING C,Reach-1,5
Up Type=0
Dn Type=3
Dn Slope=0.005
Boundary for River Rch & Prof#=POLECAT SPRING C,Reach-1,6
Up Type=0
Dn Type=3
Dn Slope=0.005
Boundary for River Rch & Prof#=POLECAT SPRING C,Reach-1,7
Up Type=0
Dn Type=3
Dn Slope=0.005

--- POLECAT SPRING CREEK.g01 (geometry) ---

Geom Title=Existing Conditions

River Reach=POLECAT SPRING C,Reach-1
Reach XY= 30
      2032075.00     13933425.00      2031565.32     13933214.22
      2031269.74     13932777.08      2031022.70     13932830.83
      2030819.59     13933119.84      2030690.23     13933124.52
      2030128.67     13932532.69      2029306.63     13932725.46
      2028969.27     13932526.98      2028664.98     13932513.77
      2028369.48     13931772.56      2028005.37     13931204.52
      2027532.68     13931171.91      2027201.82     13930651.30
      2026473.54     13930128.54      2025130.52     13929972.65
      2024725.00     13929582.07      2024428.33     13929917.41
      2024223.54     13929728.54      2023922.55     13929730.47
      2023538.40     13930061.70      2023398.51     13930352.01
      2023040.22     13930574.76      2022824.58     13930406.70
      2023022.94     13930069.14      2022985.06     13929885.62
      2022735.48     13929775.93      2022335.49     13930024.06
      2021968.79     13929917.20      2021725.00     13929625.00

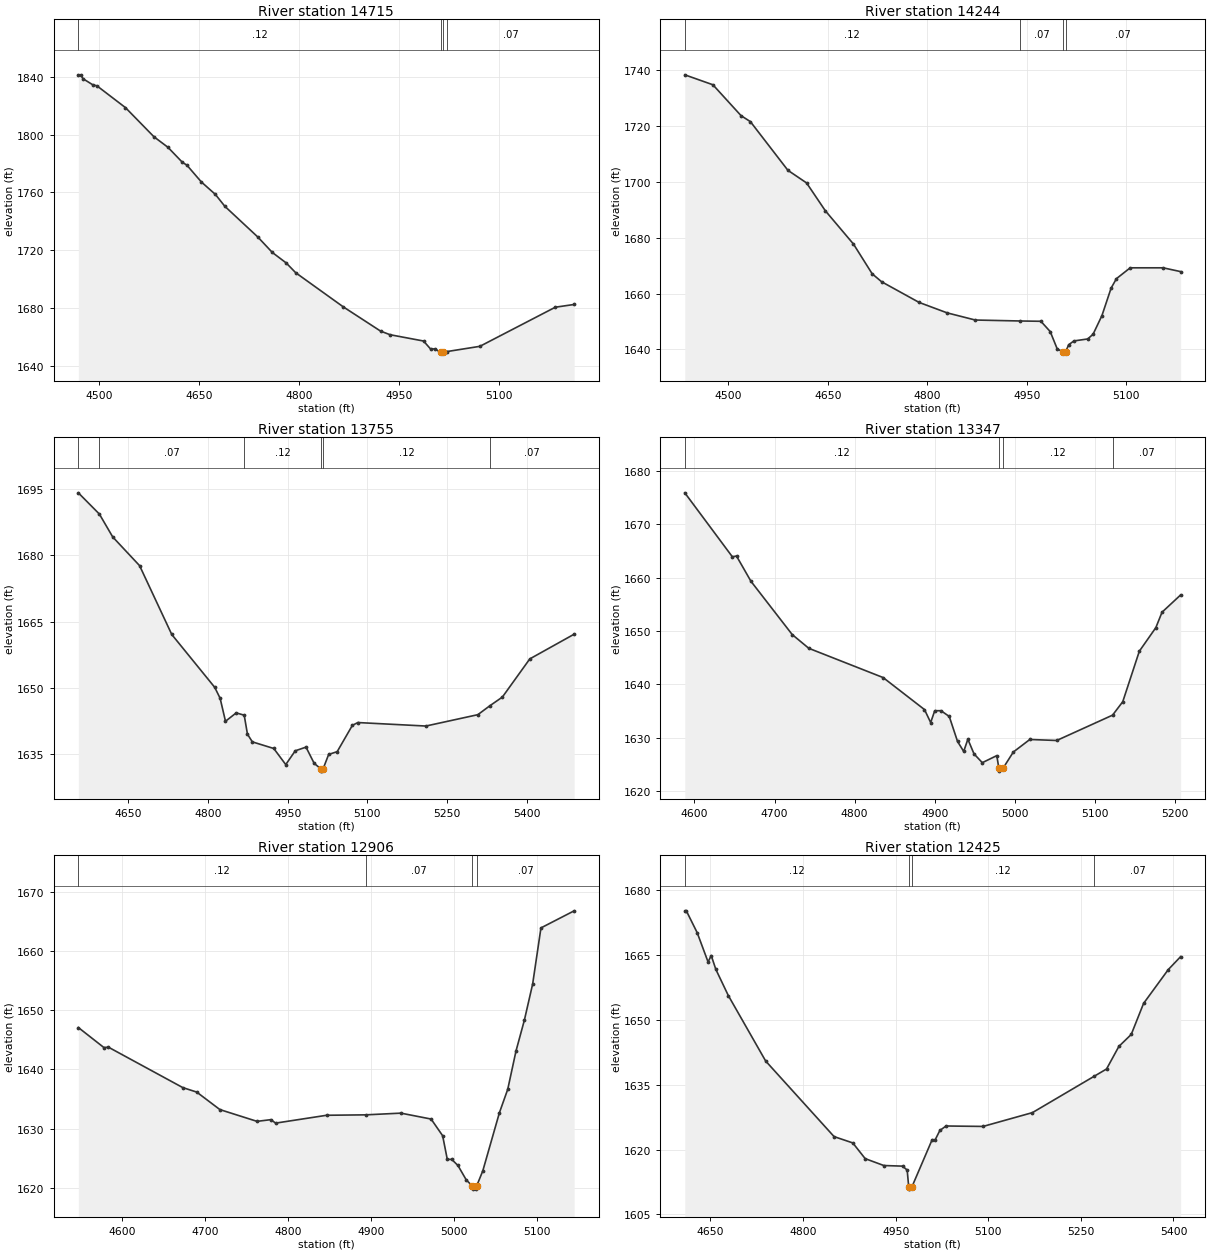
Type RM Length L Ch R = 1,14715,471,471,471
BEGIN DESCRIPTION:
POLECAT SPRING CREEK 32.0
END DESCRIPTION:
XS GIS Cut Line= 3
      2032325.00     13933025.00      2031925.00     13933375.00
      2031775.03     13933524.97
#Sta/Elev= 30
  4469.0 1841.36  4472.3 1841.36  4476.1 1838.64  4490.4 1834.53  4497.0 1833.70
  4539.7 1818.64  4582.4 1798.46  4603.3 1791.20  4625.1 1780.74  4631.8 1778.80
  4653.6 1767.11  4674.5 1758.55  4688.7 1750.31  4738.1 1729.06  4759.9 1718.34
  4780.8 1711.04  4795.0 1704.28  4866.2 1680.69  4922.2 1663.88  4936.4 1661.36
  4986.7 1656.99  4997.2 1651.50  5004.0 1651.50  5012.6 1649.10  5012.9 1648.60
  5016.6 1649.10  5021.8 1649.68  5071.2 1653.31  5184.4 1680.41  5212.6 1682.30
#Mann=4,-1,0
  4469.0    0.12       0  5012.6    0.05       0  5016.6    0.12       0
  5021.8    0.07       0
Bank Sta=5012.6,5016.6
Exp/Cntr=0.3,0.1

Type RM Length L Ch R = 1,14244,489,489,489
BEGIN DESCRIPTION:
POLECAT SPRING CREEK 31.0
END DESCRIPTION:
XS GIS Cut Line= 3
      2031925.00     13932775.00      2031525.00     13933175.00
      2031381.85     13933288.38
#Sta/Elev= 30
  4434.1 1738.36  4476.5 1734.80  4519.0 1723.73  4533.1 1721.59  4589.7 1704.15
  4617.9 1699.62  4646.2 1689.65  4688.7 1677.71  4716.9 1667.06  4731.1 1664.22
  4787.7 1656.81  4830.1 1653.06  4872.5 1650.50  4939.7 1650.16  4971.5 1650.05
  4985.6 1646.36  4996.3 1640.07  5005.0 1639.14  5005.3 1638.64  5009.0 1639.14
  5013.4 1641.64  5021.4 1643.01  5042.2 1643.72  5050.3 1645.42  5063.6 1652.06
  5077.5 1661.94  5085.5 1665.32  5106.3 1669.21  5156.0 1669.21  5182.4 1667.85
#Mann=4,-1,0
  4434.1    0.12       0  4939.7    0.07       0  5005.0    0.05       0
  5009.0    0.07       0
Bank Sta=5005,5009
Exp/Cntr=0.3,0.1

Type RM Length L Ch R = 1,13755,408,408,408
BEGIN DESCRIPTION:
POLECAT SPRING CREEK 30.0
END DESCRIPTION:
XS GIS Cut Line= 3
      2031217.14     13932340.90      2031277.70     13932780.35
      2031074.99     13933225.03
#Sta/Elev= 30
  4556.4 1694.16  4596.0 1689.35  4621.1 1684.17  4671.6 1677.68  4732.1 1662.11
  4812.9 1650.15  4823.0 1647.68  4833.1 1642.48  4853.3 1644.38  4868.3 1643.85
  4874.4 1639.56  4883.6 1637.82  4923.9 1636.32  4946.4 1632.68  4964.3 1635.80
  4984.5 1636.63  4999.8 1632.97  5012.5 1631.70  5012.8 1631.20  5016.6 1631.70
  5027.1 1634.98  5043.1 1635.60  5071.7 1641.56  5082.0 1642.19  5209.9 1641.40
  5307.6 1643.97  5330.1 1645.98  5353.7 1647.95  5405.3 1656.59  5488.7 1662.18
#Mann=6,-1,0
  4556.4    0.12       0  4596.0    0.07       0  4868.3    0.12       0
  5012.5    0.05       0  5016.6    0.12       0  5330.1    0.07       0
Bank Sta=5012.5,5016.6
Exp/Cntr=0.3,0.1

Type RM Length L Ch R = 1,13347,441,441,441
BEGIN DESCRIPTION:
POLECAT SPRING CREEK 29.0
END DESCRIPTION:
XS GIS Cut Line= 3
      2031025.01     13932524.97      2030925.00     13932925.00
      2030975.00     13933125.00
#Sta/Elev= 30
  4588.1 1675.84  4647.4 1663.88  4652.6 1664.02  4670.6 1659.30  4722.1 1649.33
  4742.8 1646.76  4835.5 1641.29  4887.1 1635.30  4894.8 1632.88  4899.9 1635.09
  4907.7 1635.09  4918.0 1634.01  4928.3 1629.35  4936.0 1627.47  4941.2 1629.76
  4948.9 1627.01  4959.2 1625.37  4977.3 1626.69  4979.9 1624.29  4980.3 1623.79
  4984.9 1624.29  4997.9 1627.36  5018.5 1629.71  5052.0 1629.52  5121.7 1634.26
  5134.4 1636.77  5155.1 1646.22  5175.7 1650.63  5183.4 1653.51  5206.6 1656.74
#Mann=4,-1,0
  4588.1    0.12       0  4979.9    0.05       0  4984.9    0.12       0
  5121.7    0.07       0
Bank Sta=4979.9,4984.9
Exp/Cntr=0.3,0.1

Type RM Length L Ch R = 1,12906,481,481,481
BEGIN DESCRIPTION:
POLECAT SPRING CREEK 28.0
END DESCRIPTION:
XS GIS Cut Line= 3
      2030825.00     13932674.99      2030625.00     13933075.00
      2030625.00     13933224.98
#Sta/Elev= 30
  4547.7 1647.09  4578.5 1643.70  4584.0 1643.76  4673.5 1636.93  4690.3 1636.17
  4718.2 1633.21  4762.9 1631.22  4779.7 1631.51  4785.3 1630.92  4846.8 1632.25
  4893.9 1632.32  4936.2 1632.61  4972.6 1631.61  4986.5 1628.79  4992.1 1624.79
  4997.4 1624.79  5004.9 1623.76  5014.9 1621.33  5022.4 1620.26  5022.8 1619.76
  5027.1 1619.76  5027.4 1620.26  5034.9 1622.87  5054.9 1632.69  5064.9 1636.64
  5074.9 1643.14  5084.9 1648.31  5094.9 1654.44  5104.9 1663.93  5144.9 1666.82
#Mann=4,-1,0
  4547.7    0.12       0  4893.9    0.07       0  5022.4    0.05       0
  5027.4    0.07       0
Bank Sta=5022.4,5027.4
Exp/Cntr=0.3,0.1

Type RM Length L Ch R = 1,12425,404,404,404
BEGIN DESCRIPTION:
POLECAT SPRING CREEK 27.0
END DESCRIPTION:
XS GIS Cut Line= 3
      2030324.99     13932375.04      2030275.00     13932775.00
      2030275.00     13933175.03
#Sta/Elev= 30
  4608.5 1675.12  4611.0 1675.12  4628.6 1670.06  4646.2 1663.31  4651.3 1664.80
  4658.8 1661.59  4679.0 1655.55  4739.5 1640.43  4850.3 1622.98  4880.6 1621.52
  4900.7 1617.89  4930.9 1616.30  4961.2 1616.16  4968.7 1615.25  4971.2 1611.35
  4971.6 1610.85  4976.3 1611.35  5009.1 1622.26  5014.1 1622.26  5021.6 1624.39
  5031.6 1625.43  5091.6 1625.33  5171.6 1628.52  5271.9 1636.94  5291.6 1638.59
  5311.6 1643.81  5331.6 1646.57  5351.6 1653.74  5391.6 1661.55  5411.6 1664.54
#Mann=4,-1,0
  4608.5    0.12       0  4971.2    0.05       0  4976.3    0.12       0
  5271.9    0.07       0
Bank Sta=4971.2,4976.3
Exp/Cntr=0.3,0.1

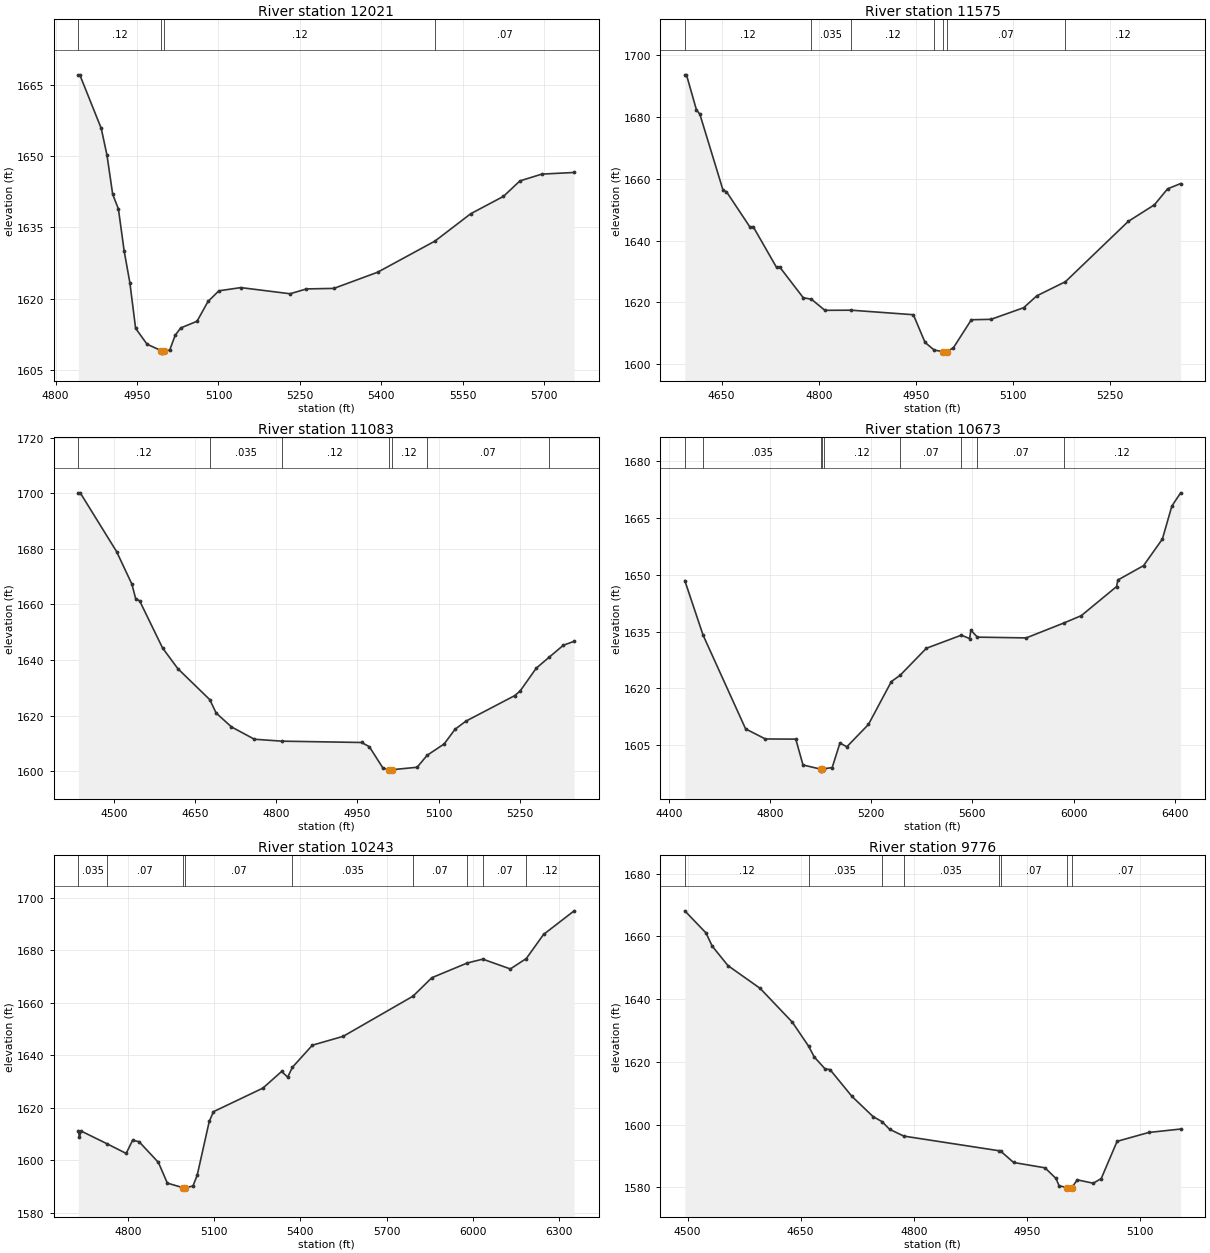
Type RM Length L Ch R = 1,12021,446,446,446
BEGIN DESCRIPTION:
POLECAT SPRING CREEK 26.0
END DESCRIPTION:
XS GIS Cut Line= 3
      2030075.01     13932424.96      2030025.00     13932575.00
      2030119.01     13933324.16
#Sta/Elev= 30
  4841.9 1667.18  4844.6 1667.18  4884.1 1655.88  4894.7 1650.22  4905.2 1641.97
  4915.7 1638.91  4926.3 1630.04  4936.8 1623.35  4947.4 1613.72  4968.4 1610.38
  4994.9 1608.99  4995.3 1608.49  5000.0 1608.99  5010.1 1609.10  5020.2 1612.23
  5030.3 1613.79  5060.5 1615.21  5080.7 1619.38  5100.8 1621.63  5141.2 1622.31
  5231.9 1621.01  5262.1 1622.03  5312.5 1622.14  5393.1 1625.55  5498.9 1632.13
  5564.5 1637.88  5624.9 1641.55  5655.2 1644.81  5695.5 1646.24  5755.1 1646.59
#Mann=4,-1,0
  4841.9    0.12       0  4994.9    0.05       0  5000.0    0.12       0
  5498.9    0.07       0
Bank Sta=4994.9,5000
Exp/Cntr=0.3,0.1

Type RM Length L Ch R = 1,11575,492,492,492
BEGIN DESCRIPTION:
POLECAT SPRING CREEK 25.0
END DESCRIPTION:
XS GIS Cut Line= 3
      2029724.99     13932325.02      2029625.00     13932725.00
      2029575.01     13933074.96
#Sta/Elev= 30
  4593.1 1693.49  4595.7 1693.49  4611.1 1682.16  4616.3 1680.82  4652.3 1656.15
  4657.5 1655.75  4693.6 1644.40  4698.7 1644.49  4734.8 1631.32  4740.0 1631.36
  4776.0 1621.55  4788.7 1621.04  4809.5 1617.47  4850.1 1617.51  4946.1 1616.05
  4964.2 1607.10  4978.4 1604.62  4992.3 1604.15  4992.8 1603.65  4997.8 1604.15
  5007.9 1605.36  5035.7 1614.43  5066.0 1614.56  5116.5 1618.31  5136.7 1622.14
  5181.0 1626.71  5278.1 1646.19  5318.5 1651.54  5338.7 1656.68  5358.9 1658.39
#Mann=7,-1,0
  4593.1    0.12       0  4788.7   0.035       0  4850.1    0.12       0
  4978.4    0.07       0  4992.3    0.05       0  4997.8    0.07       0
  5181.0    0.12       0
Bank Sta=4992.3,4997.8
Exp/Cntr=0.3,0.1

Type RM Length L Ch R = 1,11083,410,410,410
BEGIN DESCRIPTION:
POLECAT SPRING CREEK 24.0
END DESCRIPTION:
XS GIS Cut Line= 3
      2029574.97     13932225.03      2029175.00     13932625.00
      2029175.00     13932974.96
#Sta/Elev= 30
  4434.6 1700.18  4438.1 1700.18  4505.3 1679.01  4533.5 1667.31  4540.6 1661.99
  4547.7 1661.33  4590.1 1644.34  4618.4 1636.86  4677.4 1625.70  4689.1 1620.90
  4717.4 1615.90  4759.8 1611.46  4810.7 1610.77  4957.8 1610.29  4972.0 1608.77
  4996.7 1601.21  5007.5 1600.48  5007.9 1599.98  5013.0 1600.48  5060.2 1601.37
  5078.7 1605.68  5110.2 1609.78  5130.2 1615.05  5150.2 1617.96  5240.2 1627.14
  5250.2 1628.77  5280.2 1637.05  5304.0 1640.98  5330.2 1645.30  5350.2 1646.73
#Mann=7,-1,0
  4434.6    0.12       0  4677.4   0.035       0  4810.7    0.12       0
  5007.5    0.05       0  5013.0    0.12       0  5078.7    0.07       0
  5304.0    0.12       0
Bank Sta=5007.5,5013
Exp/Cntr=0.3,0.1

Type RM Length L Ch R = 1,10673,430,430,430
BEGIN DESCRIPTION:
POLECAT SPRING CREEK 23.0
END DESCRIPTION:
XS GIS Cut Line= 3
      2029225.03     13932174.98      2028825.00     13932525.00
      2029146.80     13933917.97
#Sta/Elev= 30
  4462.4 1648.51  4534.6 1634.10  4703.0 1609.29  4781.3 1606.63  4901.4 1606.59
  4929.9 1599.76  5001.4 1598.63  5001.9 1598.13  5007.0 1598.63  5013.7 1598.77
  5045.3 1599.07  5076.0 1605.55  5103.4 1604.57  5188.8 1610.47  5279.5 1621.82
  5314.0 1623.46  5417.9 1630.61  5556.2 1634.07  5588.9 1633.18  5594.0 1635.37
  5619.8 1633.55  5812.9 1633.35  5961.1 1637.27  6030.5 1639.22  6170.2 1646.92
  6175.3 1648.65  6276.9 1652.45  6351.4 1659.48  6389.0 1668.21  6423.6 1671.70
#Mann=9,-1,0
  4462.4    0.07       0  4534.6   0.035       0  5001.4   0.035       0
  5007.0   0.035       0  5013.7    0.12       0  5314.0    0.07       0
  5556.2    0.12       0  5619.8    0.07       0  5961.1    0.12       0
Bank Sta=5001.4,5007
Exp/Cntr=0.3,0.1

Type RM Length L Ch R = 1,10243,467,467,467
BEGIN DESCRIPTION:
POLECAT SPRING CREEK 22.0
END DESCRIPTION:
XS GIS Cut Line= 3
      2028862.05     13932157.53      2028525.00     13932325.00
      2027741.07     13933420.67
#Sta/Elev= 30
  4628.2 1611.25  4632.1 1608.74  4637.7 1611.14  4726.6 1606.37  4794.5 1602.62
  4816.9 1607.64  4839.3 1607.09  4906.5 1599.21  4937.6 1591.33  4993.1 1589.53
  4993.6 1589.03  4999.2 1589.53  5026.7 1590.22  5041.4 1594.32  5083.2 1614.77
  5097.9 1618.50  5269.9 1627.48  5335.0 1633.83  5355.9 1631.65  5372.5 1635.42
  5441.9 1643.82  5548.8 1647.18  5791.5 1662.46  5857.2 1669.50  5980.5 1675.11
  6034.3 1676.56  6129.9 1672.83  6185.5 1676.80  6245.4 1685.96  6351.8 1694.95
#Mann=9,-1,0
  4628.2   0.035       0  4726.6    0.07       0  4993.1    0.05       0
  4999.2    0.07       0  5372.5   0.035       0  5791.5    0.07       0
  5980.5    0.12       0  6034.3    0.07       0  6185.5    0.12       0
Bank Sta=4993.1,4999.2
Exp/Cntr=0.3,0.1

Type RM Length L Ch R = 1,9776,463,463,463
BEGIN DESCRIPTION:
POLECAT SPRING CREEK 21.0
END DESCRIPTION:
XS GIS Cut Line= 3
      2028824.97     13931625.02      2028425.00     13931925.00
      2028274.98     13931975.01
#Sta/Elev= 30
  4496.2 1668.12  4524.3 1661.08  4532.6 1656.87  4553.5 1650.66  4596.2 1643.41
  4638.9 1632.64  4660.7 1624.92  4668.0 1621.55  4682.6 1617.69  4688.9 1617.54
  4718.0 1609.00  4746.2 1602.52  4757.9 1600.96  4768.0 1598.50  4786.9 1596.33
  4913.1 1591.67  4915.3 1591.58  4932.6 1587.92  4974.3 1586.22  4988.9 1582.82
  4993.0 1580.49  5003.6 1579.93  5004.1 1579.43  5009.8 1579.93  5017.2 1582.39
  5038.3 1581.31  5048.9 1582.79  5070.0 1594.67  5112.1 1597.49  5154.3 1598.58
#Mann=8,-1,0
  4496.2    0.12       0  4660.7   0.035       0  4757.9    0.07       0
  4786.9   0.035       0  4913.1    0.12       0  4915.3    0.07       0
  5003.6    0.05       0  5009.8    0.07       0
Bank Sta=5003.6,5009.8
Exp/Cntr=0.3,0.1

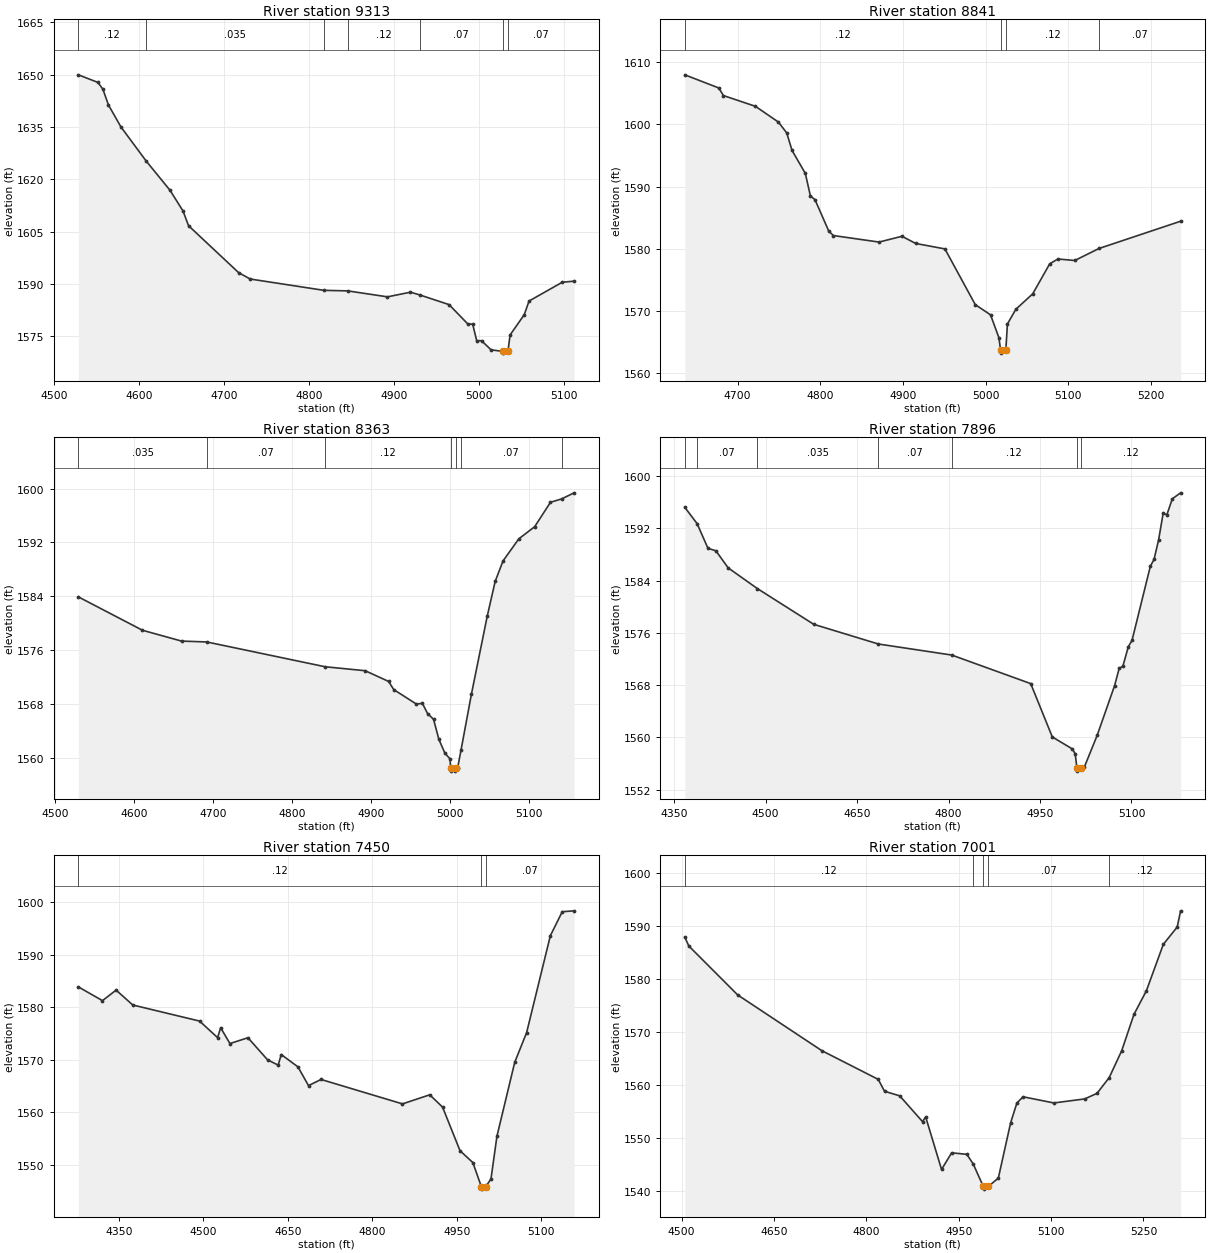
Type RM Length L Ch R = 1,9313,472,472,472
BEGIN DESCRIPTION:
POLECAT SPRING CREEK 20.0
END DESCRIPTION:
XS GIS Cut Line= 3
      2028575.01     13931324.99      2028175.00     13931575.00
      2028125.01     13931674.98
#Sta/Elev= 30
  4528.2 1649.95  4551.2 1647.78  4557.1 1645.84  4563.6 1641.32  4578.3 1635.02
  4608.0 1625.24  4636.1 1616.84  4651.4 1610.90  4657.9 1606.68  4716.9 1593.21
  4730.5 1591.39  4817.1 1588.15  4845.2 1587.99  4892.0 1586.28  4919.1 1587.62
  4929.9 1586.84  4964.5 1584.05  4986.4 1578.54  4992.3 1578.44  4997.0 1573.70
  5002.7 1573.70  5013.9 1571.09  5027.5 1570.64  5028.0 1570.14  5033.8 1570.64
  5036.3 1575.35  5053.0 1581.18  5058.6 1585.08  5097.7 1590.47  5111.7 1590.78
#Mann=7,-1,0
  4528.2    0.12       0  4608.0   0.035       0  4817.1    0.07       0
  4845.2    0.12       0  4929.9    0.07       0  5027.5    0.05       0
  5033.8    0.07       0
Bank Sta=5027.5,5033.8
Exp/Cntr=0.3,0.1

Type RM Length L Ch R = 1,8841,478,478,478
BEGIN DESCRIPTION:
POLECAT SPRING CREEK 19.0
END DESCRIPTION:
XS GIS Cut Line= 3
      2028139.86     13930855.43      2027975.00     13931175.00
      2027928.14     13931410.50
#Sta/Elev= 30
  4636.2 1607.97  4677.3 1605.86  4682.9 1604.64  4721.6 1602.91  4749.4 1600.38
  4759.5 1598.63  4765.9 1595.82  4782.0 1592.12  4788.1 1588.51  4793.7 1587.90
  4810.3 1582.86  4815.9 1582.14  4871.1 1581.09  4898.9 1582.02  4915.4 1580.87
  4950.8 1579.99  4987.5 1571.04  5006.0 1569.39  5016.2 1565.69  5018.1 1563.74
  5018.6 1563.24  5024.5 1563.74  5026.4 1567.92  5036.6 1570.29  5057.0 1572.77
  5077.6 1577.60  5087.5 1578.37  5107.9 1578.13  5137.2 1580.06  5235.9 1584.44
#Mann=4,-1,0
  4636.2    0.12       0  5018.1    0.05       0  5024.5    0.12       0
  5137.2    0.07       0
Bank Sta=5018.1,5024.5
Exp/Cntr=0.3,0.1

Type RM Length L Ch R = 1,8363,467,467,467
BEGIN DESCRIPTION:
POLECAT SPRING CREEK 18.0
END DESCRIPTION:
XS GIS Cut Line= 3
      2027886.39     13930862.38      2027525.00     13931175.00
      2027375.04     13931175.00
#Sta/Elev= 30
  4529.4 1583.91  4610.6 1578.94  4660.1 1577.33  4692.0 1577.20  4841.9 1573.51
  4892.6 1572.92  4922.2 1571.33  4928.8 1570.11  4957.4 1567.96  4965.0 1568.07
  4971.6 1566.55  4979.2 1565.68  4985.9 1562.71  4993.5 1560.66  5000.1 1559.79
  5000.7 1558.48  5001.2 1557.98  5006.7 1557.98  5007.2 1558.48  5009.7 1558.48
  5014.0 1561.14  5027.2 1569.48  5047.2 1581.07  5057.2 1586.21  5067.2 1589.27
  5087.2 1592.55  5107.2 1594.35  5127.2 1597.98  5141.2 1598.48  5157.2 1599.39
#Mann=7,-1,0
  4529.4   0.035       0  4692.0    0.07       0  4841.9    0.12       0
  5000.7    0.05       0  5007.2    0.12       0  5014.0    0.07       0
  5141.2   0.035       0
Bank Sta=5000.7,5007.2
Exp/Cntr=0.3,0.1

Type RM Length L Ch R = 1,7896,446,446,446
BEGIN DESCRIPTION:
POLECAT SPRING CREEK 17.0
END DESCRIPTION:
XS GIS Cut Line= 3
      2027955.85     13930726.97      2027325.00     13930775.00
      2027224.97     13930925.04
#Sta/Elev= 30
  4367.6 1595.20  4387.7 1592.72  4405.6 1588.93  4418.6 1588.55  4438.7 1585.94
  4486.6 1582.77  4579.1 1577.30  4685.0 1574.29  4805.3 1572.60  4934.8 1568.23
  4970.2 1560.07  5003.3 1558.22  5007.8 1557.46  5010.5 1555.34  5011.0 1554.84
  5017.0 1555.34  5022.8 1555.48  5043.8 1560.32  5072.4 1567.94  5079.9 1570.57
  5085.9 1570.89  5094.9 1573.89  5100.9 1574.84  5131.0 1586.20  5137.0 1587.23
  5144.5 1590.22  5152.0 1594.31  5158.0 1594.05  5167.0 1596.51  5180.6 1597.42
#Mann=7,-1,0
  4367.6    0.12       0  4387.7    0.07       0  4486.6   0.035       0
  4685.0    0.07       0  4805.3    0.12       0  5010.5    0.05       0
  5017.0    0.12       0
Bank Sta=5010.5,5017
Exp/Cntr=0.3,0.1

Type RM Length L Ch R = 1,7450,449,449,449
BEGIN DESCRIPTION:
POLECAT SPRING CREEK 16.0
END DESCRIPTION:
XS GIS Cut Line= 3
      2027244.02     13929855.43      2026975.00     13930525.00
      2026925.00     13930674.99
#Sta/Elev= 30
  4278.4 1583.89  4321.2 1581.27  4345.4 1583.27  4375.0 1580.44  4493.5 1577.38
  4525.5 1574.23  4530.9 1576.11  4547.4 1573.10  4579.3 1574.21  4614.2 1570.00
  4633.0 1569.00  4638.4 1571.01  4668.0 1568.67  4686.8 1565.10  4709.0 1566.27
  4853.5 1561.62  4901.9 1563.35  4924.6 1561.01  4955.6 1552.71  4978.4 1550.45
  4993.3 1545.90  4993.8 1545.40  5001.3 1545.90  5010.5 1547.32  5021.1 1555.47
  5052.7 1569.55  5073.8 1575.20  5115.9 1593.64  5137.0 1598.19  5158.1 1598.36
#Mann=3,-1,0
  4278.4    0.12       0  4993.3    0.05       0  5001.3    0.07       0
Bank Sta=4993.3,5001.3
Exp/Cntr=0.3,0.1

Type RM Length L Ch R = 1,7001,458,458,458
BEGIN DESCRIPTION:
POLECAT SPRING CREEK 15.0
END DESCRIPTION:
XS GIS Cut Line= 3
      2026740.55     13929789.46      2026625.00     13930275.00
      2026608.63     13930580.57
#Sta/Elev= 30
  4505.3 1587.94  4511.9 1586.26  4591.1 1577.02  4727.8 1566.47  4819.4 1561.04
  4829.6 1558.79  4854.3 1557.92  4891.3 1553.05  4896.4 1553.94  4922.2 1544.00
  4938.6 1547.15  4963.3 1546.86  4973.6 1545.04  4990.0 1540.78  4990.5 1540.28
  4998.2 1540.78  5014.4 1542.37  5034.4 1552.84  5044.5 1556.55  5054.5 1557.75
  5104.5 1556.58  5154.6 1557.34  5174.6 1558.39  5194.4 1561.37  5214.7 1566.45
  5234.7 1573.35  5254.8 1577.79  5282.3 1586.58  5304.8 1589.85  5310.4 1592.92
#Mann=5,-1,0
  4505.3    0.12       0  4973.6    0.07       0  4990.0    0.05       0
  4998.2    0.07       0  5194.4    0.12       0
Bank Sta=4990,4998.2
Exp/Cntr=0.3,0.1

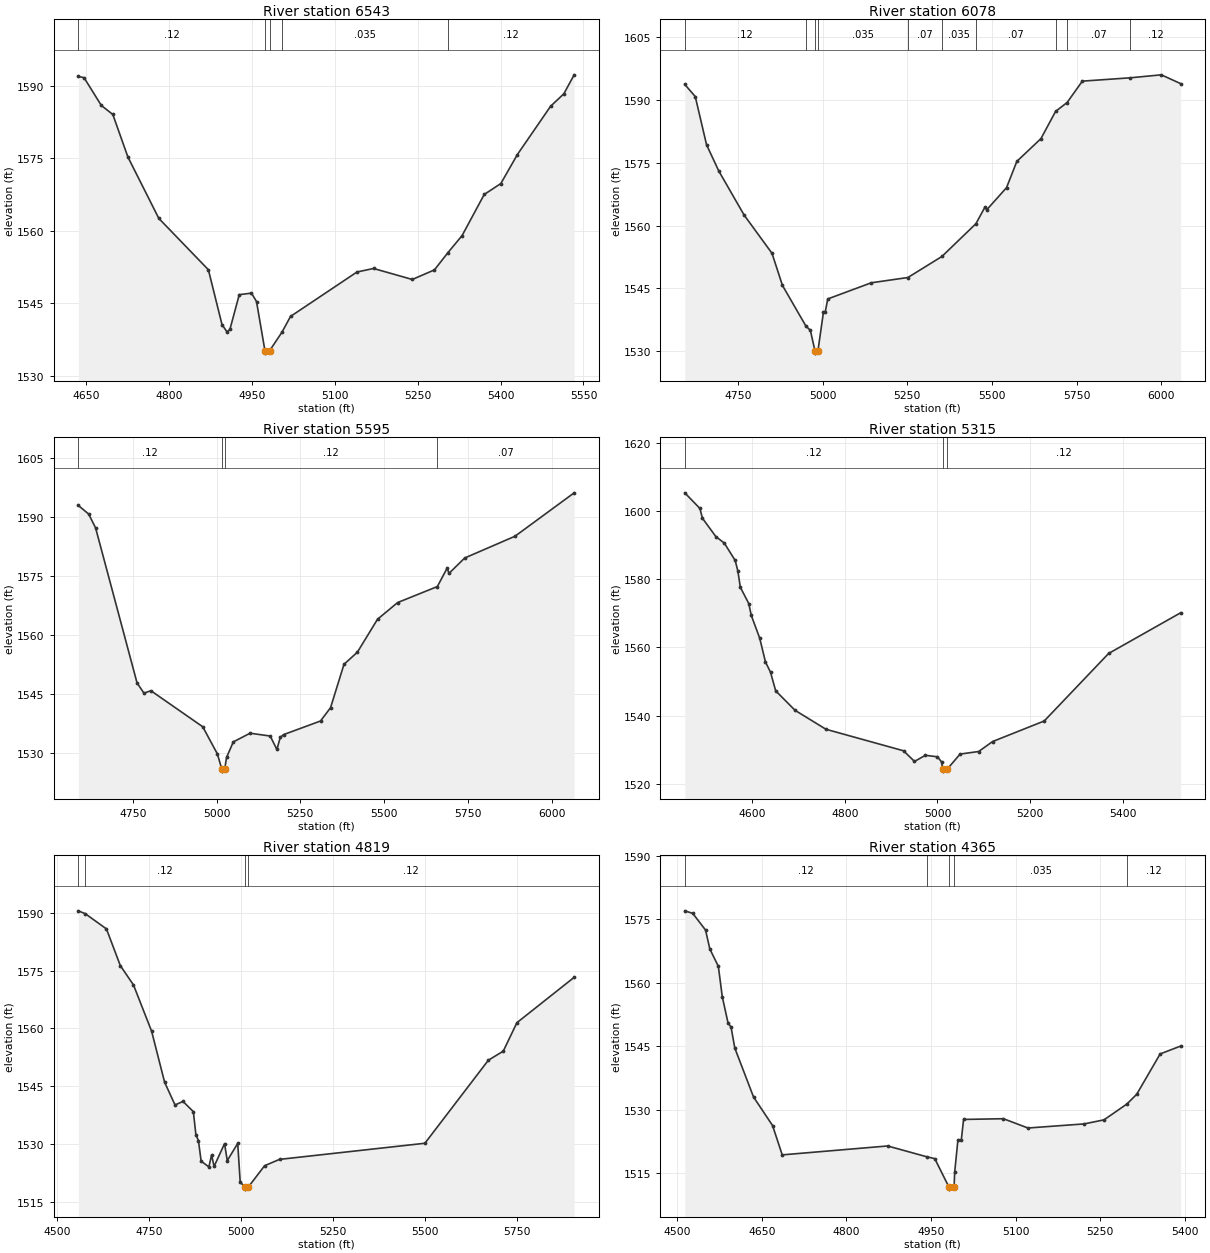
Type RM Length L Ch R = 1,6543,465,465,465
BEGIN DESCRIPTION:
POLECAT SPRING CREEK 14.0
END DESCRIPTION:
XS GIS Cut Line= 3
      2026125.00     13929774.99      2026225.00     13930125.00
      2026250.96     13930657.55
#Sta/Elev= 30
  4636.0 1592.02  4646.4 1591.74  4677.6 1585.99  4698.4 1584.12  4725.7 1575.30
  4781.6 1562.58  4871.3 1551.93  4896.0 1540.55  4905.1 1539.03  4910.3 1539.57
  4927.2 1546.76  4949.3 1547.08  4958.4 1545.34  4973.7 1535.14  4974.2 1534.64
  4982.1 1535.14  5004.2 1538.93  5020.0 1542.25  5140.2 1551.46  5170.2 1552.19
  5240.3 1549.91  5280.4 1551.90  5304.9 1555.49  5330.4 1559.01  5370.5 1567.54
  5400.5 1569.80  5430.5 1575.82  5490.6 1585.83  5514.5 1588.40  5533.2 1592.34
#Mann=5,-1,0
  4636.0    0.12       0  4973.7    0.05       0  4982.1    0.12       0
  5004.2   0.035       0  5304.9    0.12       0
Bank Sta=4973.7,4982.1
Exp/Cntr=0.3,0.1

Type RM Length L Ch R = 1,6078,483,483,483
BEGIN DESCRIPTION:
POLECAT SPRING CREEK 13.0
END DESCRIPTION:
XS GIS Cut Line= 3
      2025875.00     13929674.98      2025775.00     13930075.00
      2025962.56     13931111.23
#Sta/Elev= 30
  4592.3 1593.74  4623.2 1590.85  4656.7 1579.30  4692.8 1573.05  4767.6 1562.53
  4850.0 1553.39  4880.9 1545.71  4950.1 1536.02  4963.4 1534.97  4977.2 1530.03
  4977.7 1529.53  4985.7 1530.03  5002.1 1539.33  5007.2 1539.33  5014.8 1542.48
  5143.4 1546.34  5251.6 1547.60  5352.2 1552.63  5452.7 1560.46  5479.5 1564.44
  5484.6 1563.78  5543.2 1569.08  5573.7 1575.36  5644.9 1580.80  5688.2 1587.30
  5722.2 1589.42  5767.2 1594.53  5909.0 1595.33  6000.6 1596.04  6057.7 1593.94
#Mann=10,-1,0
  4592.3    0.12       0  4950.1   0.035       0  4977.2   0.035       0
  4985.7   0.035       0  5251.6    0.07       0  5352.2   0.035       0
  5452.7    0.07       0  5688.2    0.12       0  5722.2    0.07       0
  5909.0    0.12       0
Bank Sta=4977.2,4985.7
Exp/Cntr=0.3,0.1

Type RM Length L Ch R = 1,5595,280,280,280
BEGIN DESCRIPTION:
POLECAT SPRING CREEK 12.0
END DESCRIPTION:
XS GIS Cut Line= 3
      2025424.99     13929575.02      2025325.00     13929975.00
      2025348.15     13931041.46
#Sta/Elev= 30
  4587.8 1592.94  4618.7 1590.75  4639.3 1587.23  4763.0 1547.88  4783.6 1545.30
  4804.2 1545.92  4958.9 1536.77  5002.6 1529.87  5015.8 1526.01  5016.3 1525.51
  5024.3 1526.01  5030.1 1529.02  5050.1 1532.93  5100.1 1535.13  5160.1 1534.42
  5180.1 1531.01  5190.1 1534.06  5200.1 1534.78  5310.2 1538.23  5340.2 1541.62
  5380.2 1552.61  5420.2 1555.70  5480.2 1564.05  5540.2 1568.29  5658.7 1572.35
  5688.2 1577.07  5693.2 1575.68  5740.3 1579.60  5890.3 1585.12  6066.8 1596.14
#Mann=4,-1,0
  4587.8    0.12       0  5015.8    0.05       0  5024.3    0.12       0
  5658.7    0.07       0
Bank Sta=5015.8,5024.3
Exp/Cntr=0.3,0.1

Type RM Length L Ch R = 1,5315,496,496,496
BEGIN DESCRIPTION:
POLECAT SPRING CREEK 11.0
END DESCRIPTION:
XS GIS Cut Line= 3
      2025275.00     13929425.01      2025060.87     13929926.18
      2025035.72     13930450.18
#Sta/Elev= 30
  4455.0 1605.28  4487.6 1600.70  4493.1 1597.82  4522.1 1592.44  4540.3 1590.54
  4563.7 1585.45  4569.4 1582.41  4574.8 1577.60  4593.0 1572.83  4598.4 1569.36
  4616.6 1562.68  4629.0 1555.70  4639.9 1552.72  4651.0 1547.26  4692.8 1541.54
  4759.5 1535.98  4926.9 1529.67  4950.5 1526.55  4974.1 1528.35  5000.0 1527.91
  5008.8 1526.43  5011.5 1524.21  5012.0 1523.71  5020.5 1524.21  5048.9 1528.71
  5088.9 1529.46  5119.0 1532.38  5230.4 1538.41  5369.2 1558.19  5524.6 1570.12
#Mann=3,-1,0
  4455.0    0.12       0  5011.5    0.05       0  5020.5    0.12       0
Bank Sta=5011.5,5020.5
Exp/Cntr=0.3,0.1

Type RM Length L Ch R = 1,4819,454,454,454
BEGIN DESCRIPTION:
POLECAT SPRING CREEK 10.0
END DESCRIPTION:
XS GIS Cut Line= 3
      2025056.64     13929285.31      2024728.33     13929582.59
      2024875.00     13930475.01
#Sta/Elev= 30
  4557.1 1590.47  4576.4 1589.70  4633.5 1585.78  4671.2 1576.27  4707.0 1571.25
  4756.3 1559.24  4791.5 1546.05  4819.9 1540.14  4841.5 1541.07  4869.6 1538.42
  4876.6 1532.42  4883.4 1530.93  4890.8 1525.58  4911.8 1524.09  4919.2 1527.19
  4926.0 1524.22  4954.4 1530.12  4961.8 1525.72  4990.2 1530.18  4996.9 1520.22
  5009.4 1518.83  5009.9 1518.33  5018.6 1518.83  5063.3 1524.40  5103.8 1526.04
  5498.8 1530.22  5671.3 1551.75  5711.8 1554.10  5748.8 1561.47  5904.4 1573.23
#Mann=4,-1,0
  4557.1    0.07       0  4576.4    0.12       0  5009.4    0.05       0
  5018.6    0.12       0
Bank Sta=5009.4,5018.6
Exp/Cntr=0.3,0.1

Type RM Length L Ch R = 1,4365,586,586,586
BEGIN DESCRIPTION:
POLECAT SPRING CREEK 9.0
END DESCRIPTION:
XS GIS Cut Line= 3
      2024224.99     13929474.99      2024435.00     13929914.05
      2024675.00     13930225.00
#Sta/Elev= 30
  4513.3 1577.05  4527.4 1576.45  4550.1 1572.50  4557.7 1568.02  4572.8 1563.91
  4579.8 1556.70  4589.9 1550.56  4595.4 1549.48  4602.0 1544.56  4635.2 1532.98
  4669.0 1526.21  4686.1 1519.27  4873.1 1521.38  4943.3 1518.79  4956.7 1518.38
  4981.8 1511.66  4982.3 1511.16  4991.0 1511.66  4992.0 1515.15  4997.8 1522.84
  5003.8 1522.84  5007.8 1527.66  5078.5 1527.83  5122.0 1525.63  5221.6 1526.60
  5256.9 1527.56  5297.5 1531.31  5314.9 1533.62  5356.5 1543.17  5392.8 1545.03
#Mann=5,-1,0
  4513.3    0.12       0  4943.3   0.035       0  4981.8   0.035       0
  4991.0   0.035       0  5297.5    0.12       0
Bank Sta=4981.8,4991
Exp/Cntr=0.3,0.1

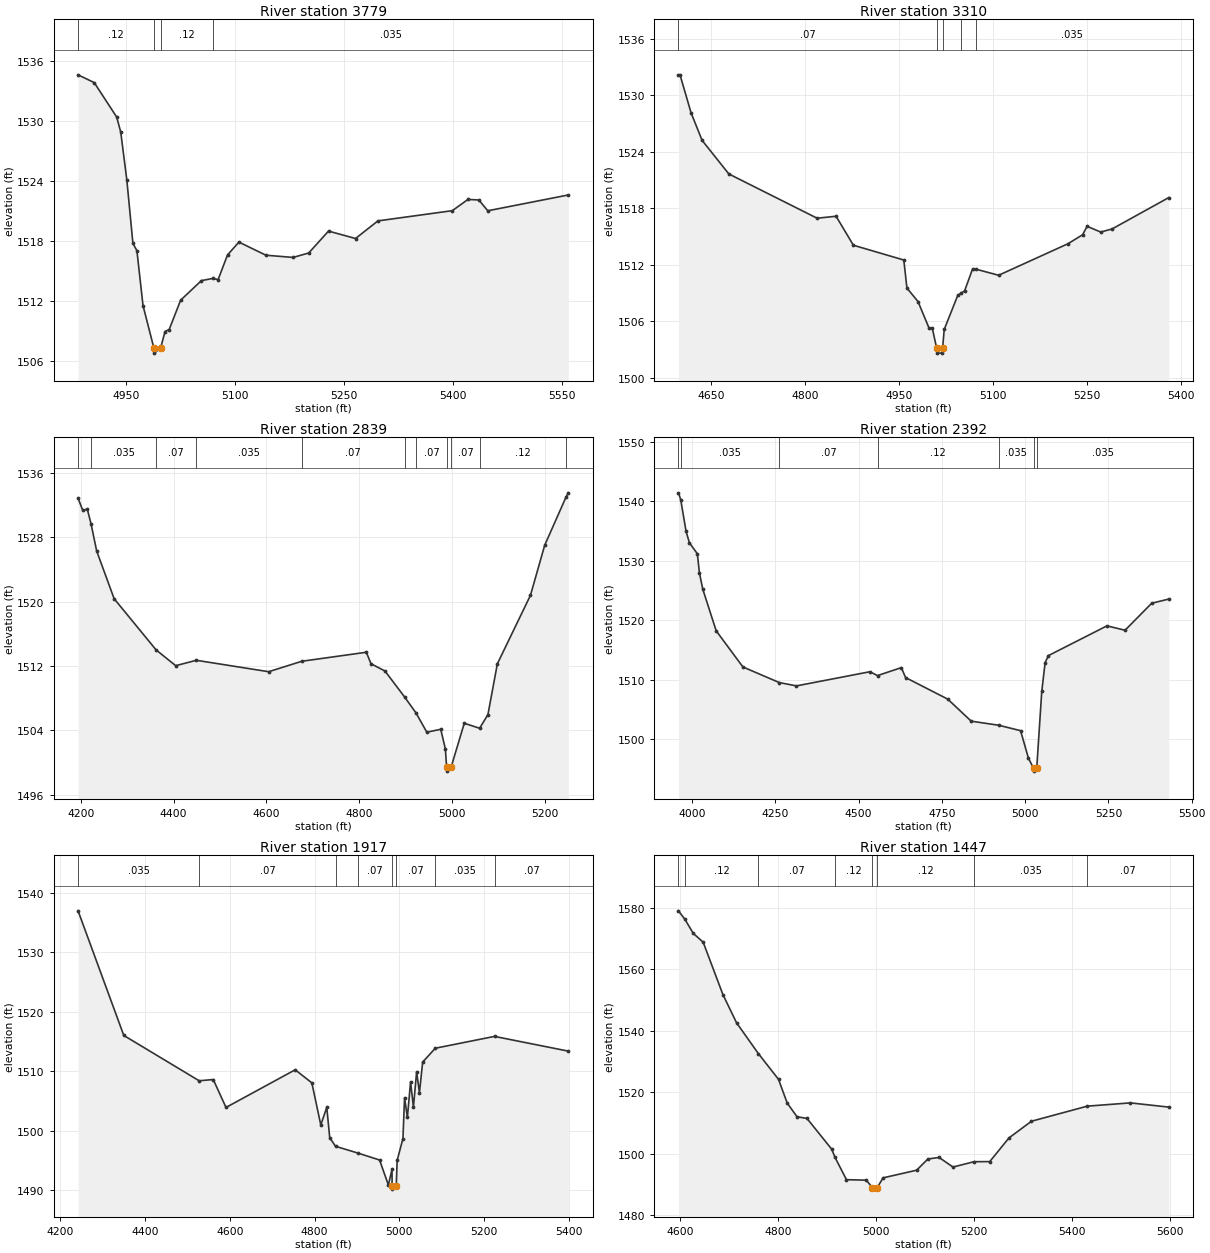
Type RM Length L Ch R = 1,3779,469,469,469
BEGIN DESCRIPTION:
POLECAT SPRING CREEK 8.0
END DESCRIPTION:
XS GIS Cut Line= 3
      2023875.01     13929625.01      2023925.00     13929725.00
      2024208.37     13930211.50
#Sta/Elev= 30
  4884.3 1534.60  4906.6 1533.82  4937.4 1530.39  4943.0 1528.90  4951.4 1524.11
  4959.8 1517.77  4965.3 1517.03  4973.7 1511.55  4988.7 1507.30  4989.2 1506.80
  4997.9 1507.30  5004.0 1508.96  5009.7 1509.16  5025.5 1512.09  5054.0 1514.04
  5069.5 1514.26  5077.1 1514.15  5090.0 1516.61  5105.7 1517.89  5142.9 1516.58
  5180.2 1516.36  5201.7 1516.80  5229.0 1518.99  5266.2 1518.25  5297.0 1520.01
  5399.4 1521.03  5420.9 1522.15  5435.9 1522.10  5448.2 1521.02  5559.1 1522.60
#Mann=4,-1,0
  4884.3    0.12       0  4988.7    0.05       0  4997.9    0.12       0
  5069.5   0.035       0
Bank Sta=4988.7,4997.9
Exp/Cntr=0.3,0.1

Type RM Length L Ch R = 1,3310,471,471,471
BEGIN DESCRIPTION:
POLECAT SPRING CREEK 7.0
END DESCRIPTION:
XS GIS Cut Line= 3
      2023525.00     13929624.99      2023575.00     13930025.00
      2023924.98     13930174.99
#Sta/Elev= 30
  4597.2 1532.19  4599.7 1532.19  4617.4 1528.15  4635.0 1525.23  4677.8 1521.66
  4818.9 1516.96  4849.2 1517.17  4876.9 1514.09  4957.5 1512.52  4962.5 1509.54
  4980.2 1508.11  4997.8 1505.30  5003.0 1505.30  5010.1 1503.13  5010.6 1502.63
  5019.0 1502.63  5019.5 1503.13  5022.1 1505.14  5043.8 1508.77  5048.8 1508.99
  5054.7 1509.24  5067.4 1511.56  5072.7 1511.55  5109.1 1510.90  5219.7 1514.24
  5243.3 1515.20  5250.6 1516.10  5272.3 1515.49  5290.5 1515.82  5381.1 1519.15
#Mann=5,-1,0
  4597.2    0.07       0  5010.1    0.05       0  5019.5    0.07       0
  5048.8    0.12       0  5072.7   0.035       0
Bank Sta=5010.1,5019.5
Exp/Cntr=0.3,0.1

Type RM Length L Ch R = 1,2839,447,447,447
BEGIN DESCRIPTION:
POLECAT SPRING CREEK 6.0
END DESCRIPTION:
XS GIS Cut Line= 3
      2023275.00     13929574.99      2023325.00     13930375.00
      2023375.00     13930624.98
#Sta/Elev= 30
  4194.0 1532.86  4204.0 1531.37  4214.0 1531.49  4222.0 1529.67  4234.1 1526.30
  4271.7 1520.37  4362.2 1514.00  4404.4 1512.04  4448.9 1512.71  4604.8 1511.29
  4676.2 1512.59  4815.2 1513.71  4825.2 1512.28  4855.3 1511.38  4898.0 1508.12
  4922.4 1506.15  4945.5 1503.77  4975.5 1504.13  4985.5 1501.68  4988.2 1499.43
  4988.7 1498.93  4997.9 1499.43  5026.2 1504.88  5059.3 1504.26  5077.2 1505.96
  5097.5 1512.27  5168.9 1520.80  5199.5 1527.01  5245.8 1533.05  5250.5 1533.53
#Mann=11,-1,0
  4194.0    0.07       0  4222.0   0.035       0  4362.2    0.07       0
  4448.9   0.035       0  4676.2    0.07       0  4898.0    0.12       0
  4922.4    0.07       0  4988.2    0.05       0  4997.9    0.07       0
  5059.3    0.12       0  5245.8    0.07       0
Bank Sta=4988.2,4997.9
Exp/Cntr=0.3,0.1

Type RM Length L Ch R = 1,2392,475,475,475
BEGIN DESCRIPTION:
POLECAT SPRING CREEK 5.0
END DESCRIPTION:
XS GIS Cut Line= 4
      2023234.89     13929542.17      2023178.34     13930181.03
      2022975.00     13930525.00      2022966.24     13930956.18
#Sta/Elev= 30
  3959.0 1541.41  3965.9 1540.24  3981.9 1534.94  3992.0 1533.01  4015.7 1531.18
  4022.1 1527.92  4032.1 1525.22  4072.3 1518.24  4152.6 1512.17  4261.3 1509.56
  4313.2 1508.99  4534.1 1511.37  4556.7 1510.72  4628.2 1512.06  4641.0 1510.39
  4767.6 1506.77  4838.0 1503.07  4921.1 1502.38  4986.3 1501.47  5009.9 1496.85
  5025.1 1495.18  5025.6 1494.68  5034.8 1495.18  5049.9 1508.07  5059.9 1512.88
  5069.9 1514.08  5245.5 1519.07  5300.0 1518.34  5380.0 1522.87  5431.2 1523.57
#Mann=7,-1,0
  3959.0    0.12       0  3965.9   0.035       0  4261.3    0.07       0
  4556.7    0.12       0  4921.1   0.035       0  5025.1   0.035       0
  5034.8   0.035       0
Bank Sta=5025.1,5034.8
Exp/Cntr=0.3,0.1

Type RM Length L Ch R = 1,1917,470,470,470
BEGIN DESCRIPTION:
POLECAT SPRING CREEK 4.0
END DESCRIPTION:
XS GIS Cut Line= 5
      2023193.20     13929557.63      2023144.06     13930064.57
      2023076.50     13930133.92      2022925.00     13930175.00
      2022629.70     13930435.07
#Sta/Elev= 30
  4242.1 1537.00  4350.0 1516.02  4527.8 1508.39  4561.0 1508.60  4591.1 1503.90
  4754.3 1510.24  4793.6 1508.04  4814.7 1500.96  4828.8 1503.91  4835.8 1498.81
  4849.4 1497.36  4901.8 1496.23  4953.4 1495.05  4974.1 1490.85  4982.7 1493.48
  4983.0 1490.65  4983.5 1490.15  4992.7 1490.65  4994.8 1494.97  5008.5 1498.67
  5012.3 1505.55  5019.0 1502.24  5026.5 1508.20  5033.2 1503.93  5040.8 1509.92
  5047.4 1506.36  5055.0 1511.54  5084.8 1513.87  5224.5 1515.86  5398.7 1513.38
#Mann=8,-1,0
  4242.1   0.035       0  4527.8    0.07       0  4849.4    0.12       0
  4901.8    0.07       0  4983.0    0.05       0  4992.7    0.07       0
  5084.8   0.035       0  5224.5    0.07       0
Bank Sta=4983,4992.7
Exp/Cntr=0.3,0.1

Type RM Length L Ch R = 1,1447,426,426,426
BEGIN DESCRIPTION:
POLECAT SPRING CREEK 3.0
END DESCRIPTION:
XS GIS Cut Line= 3
      2022824.99     13929424.96      2022875.00     13929825.00
      2022622.47     13930365.90
#Sta/Elev= 30
  4596.9 1578.99  4610.1 1576.22  4627.2 1571.64  4647.3 1568.80  4687.6 1551.75
  4715.4 1542.58  4759.8 1532.58  4801.0 1524.18  4818.7 1516.48  4838.8 1512.00
  4859.0 1511.48  4909.4 1501.49  4916.3 1498.78  4939.6 1491.54  4979.9 1491.39
  4992.6 1488.97  4993.1 1488.47  5002.4 1488.97  5014.2 1492.13  5082.8 1494.63
  5105.7 1498.27  5128.5 1498.78  5156.9 1495.65  5199.8 1497.39  5231.8 1497.42
  5271.2 1505.14  5316.9 1510.55  5430.9 1515.46  5518.8 1516.52  5597.0 1515.15
#Mann=8,-1,0
  4596.9    0.07       0  4610.1    0.12       0  4759.8    0.07       0
  4916.3    0.12       0  4992.6    0.05       0  5002.4    0.12       0
  5199.8   0.035       0  5430.9    0.07       0
Bank Sta=4992.6,5002.4
Exp/Cntr=0.3,0.1