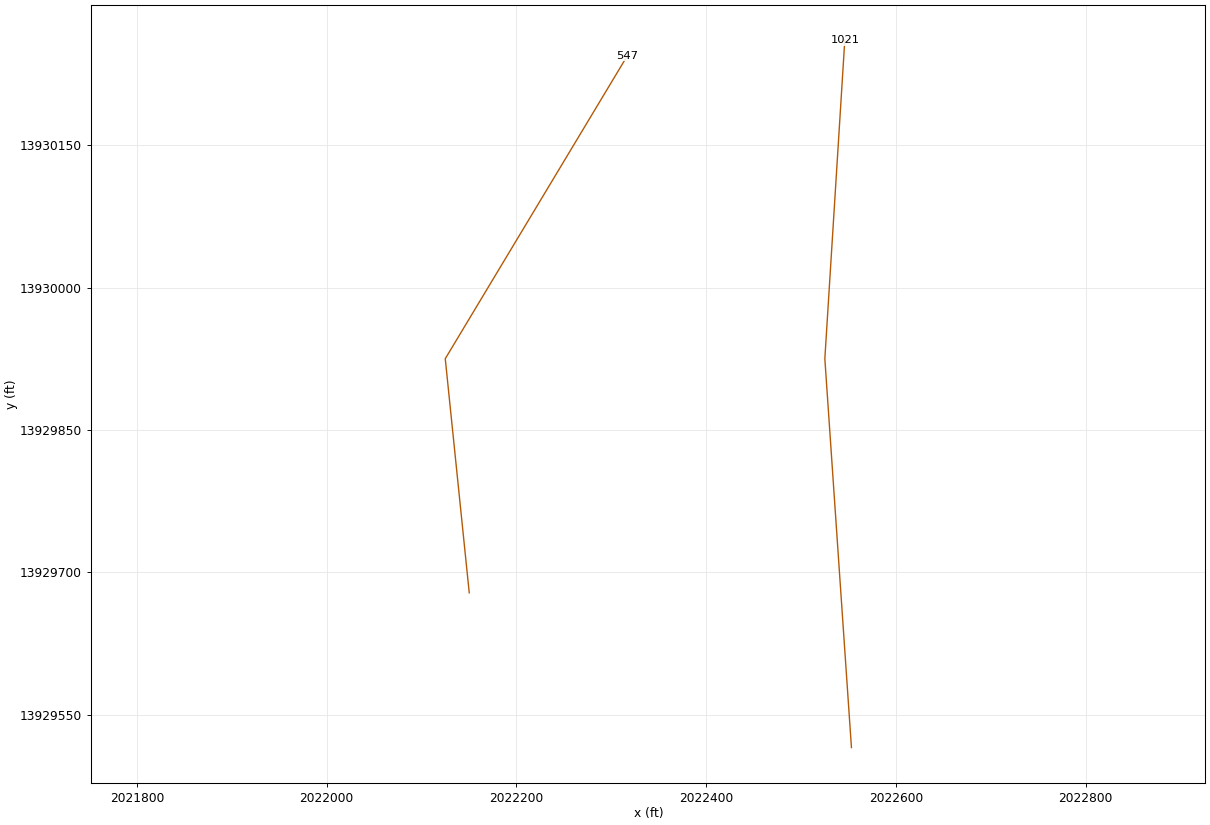
HEC-RAS study POLECAT SPRING CREEK.prj: POLECAT SPRING CREEK Base Level Engineering

--- POLECAT SPRING CREEK.g01 (geometry) --- (continued)

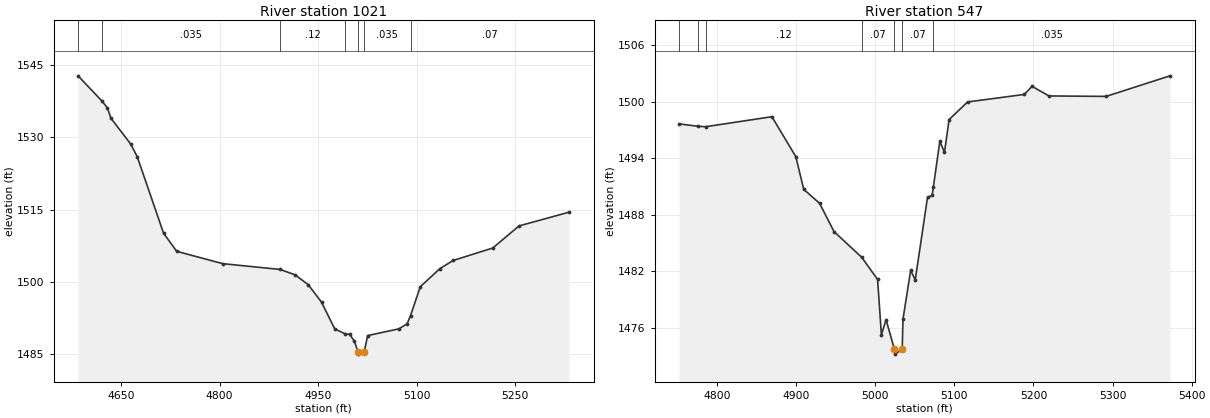
Type RM Length L Ch R = 1,1021,474,474,474
BEGIN DESCRIPTION:
POLECAT SPRING CREEK 2.0
END DESCRIPTION:
XS GIS Cut Line= 3
      2022553.04     13929515.21      2022525.00     13929925.00
      2022546.05     13930260.89
#Sta/Elev= 30
  4584.6 1542.83  4621.4 1537.51  4629.3 1536.15  4634.5 1534.03  4664.6 1528.65
  4674.6 1526.01  4714.7 1510.08  4734.7 1506.30  4804.9 1503.73  4892.4 1502.52
  4915.2 1501.39  4935.2 1499.33  4955.3 1495.69  4975.3 1490.16  4990.7 1489.15
  4997.9 1489.01  5005.4 1487.59  5010.5 1485.40  5011.0 1484.90  5020.3 1485.40
  5025.4 1488.76  5072.9 1490.16  5085.5 1491.20  5090.7 1492.93  5105.6 1498.94
  5135.6 1502.72  5155.7 1504.40  5215.8 1506.98  5255.9 1511.59  5331.9 1514.44
#Mann=7,-1,0
  4584.6    0.12       0  4621.4   0.035       0  4892.4    0.12       0
  4990.7   0.035       0  5010.5   0.035       0  5020.3   0.035       0
  5090.7    0.07       0
Bank Sta=5010.5,5020.3
Exp/Cntr=0.3,0.1

Type RM Length L Ch R = 1,547,0,0,0
BEGIN DESCRIPTION:
POLECAT SPRING CREEK 1.0
END DESCRIPTION:
XS GIS Cut Line= 3
      2022150.27     13929678.32      2022125.00     13929925.00
      2022316.91     13930244.29
#Sta/Elev= 30
  4752.1 1497.63  4776.4 1497.37  4785.8 1497.33  4869.4 1498.39  4899.6 1494.16
  4909.6 1490.70  4929.7 1489.21  4947.9 1486.22  4982.9 1483.50  5003.0 1481.15
  5007.8 1475.30  5013.7 1476.89  5024.3 1473.74  5024.8 1473.24  5034.1 1473.74
  5035.1 1476.94  5044.8 1482.11  5050.6 1481.11  5066.1 1489.84  5072.0 1490.06
  5073.5 1490.95  5081.7 1495.80  5087.5 1494.60  5093.4 1498.09  5116.7 1499.95
  5188.5 1500.75  5198.2 1501.61  5219.6 1500.59  5291.8 1500.54  5372.6 1502.72
#Mann=7,-1,0
  4752.1   0.035       0  4776.4    0.07       0  4785.8    0.12       0
  4982.9    0.07       0  5024.3    0.05       0  5034.1    0.07       0
  5073.5   0.035       0
Bank Sta=5024.3,5034.1
Exp/Cntr=0.3,0.1

Chan Stop Cuts=-1