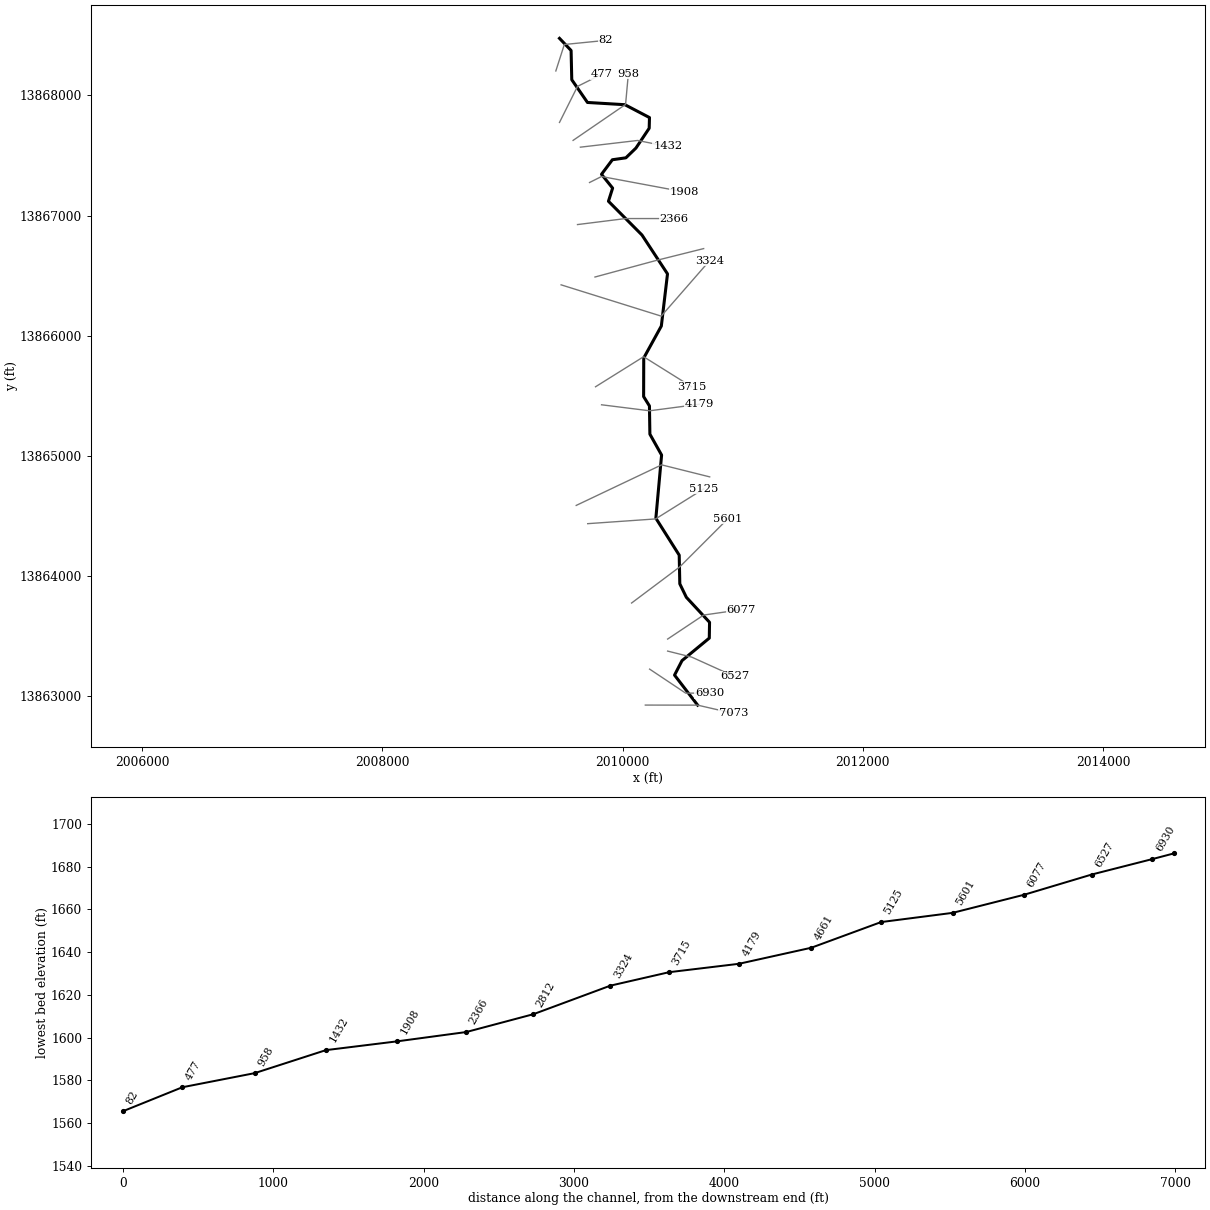
--- POSSUM CREEK.prj (project) ---

Proj Title=POSSUM CREEK Base Level Engineering
Current Plan=p01
Default Exp/Contr=0.3,0.1
English Units
Geom File=g01
Flow File=f01
Plan File=p01
BEGIN DESCRIPTION:
POSSUM CREEK
END DESCRIPTION:

--- POSSUM CREEK.p01 (plan) ---

Plan Title=Multiple Run
Short Identifier=Multiple
Geom File=g01
Flow File=f01
Subcritical Flow
K Sum by GR= 0
Std Step Tol= 0.01
Critical Tol= 0.01
Num of Std Step Trials= 20
Max Error Tol= 0.3
Flow Tol Ratio= 0.001
Split Flow NTrial= 30
Split Flow Tol= 0.02
Split Flow Ratio= 0.02
Log Output Level= 0
Friction Slope Method= 1
Unsteady Friction Slope Method= 2
Unsteady Bridges Friction Slope Method= 1
Parabolic Critical Depth
Global Vel Dist=  1 , 1 , 1
Global Log Level= 0
CheckData=True
Encroach Param= -1, 0, 0, 0
BEGIN DESCRIPTION:
Multiple Run
END DESCRIPTION:

--- POSSUM CREEK.f01 (steady flow) ---

Flow Title=Multiple
Number of Profiles=7
Profile Names=10-year,25-year,50-year,1pct_min,100-year,1pct_plu,500-year
River Rch & RM= POSSUM CREEK,Reach-1,7073
    1403    2437    3446    2362    4713    9403    8723
River Rch & RM= POSSUM CREEK,Reach-1,5601
    1797    3153    4487    3091    6168   12307   11538
Boundary for River Rch & Prof#=POSSUM CREEK,Reach-1,1
Up Type=0
Dn Type=3
Dn Slope=0.005
Boundary for River Rch & Prof#=POSSUM CREEK,Reach-1,2
Up Type=0
Dn Type=3
Dn Slope=0.005
Boundary for River Rch & Prof#=POSSUM CREEK,Reach-1,3
Up Type=0
Dn Type=3
Dn Slope=0.005
Boundary for River Rch & Prof#=POSSUM CREEK,Reach-1,4
Up Type=0
Dn Type=3
Dn Slope=0.005
Boundary for River Rch & Prof#=POSSUM CREEK,Reach-1,5
Up Type=0
Dn Type=3
Dn Slope=0.005
Boundary for River Rch & Prof#=POSSUM CREEK,Reach-1,6
Up Type=0
Dn Type=3
Dn Slope=0.005
Boundary for River Rch & Prof#=POSSUM CREEK,Reach-1,7
Up Type=0
Dn Type=3
Dn Slope=0.005

--- POSSUM CREEK.g01 (geometry) ---

Geom Title=Existing Conditions

River Reach=POSSUM CREEK,Reach-1
Reach XY= 30
      2010625.00     13862925.00      2010432.50     13863175.00
      2010494.62     13863295.47      2010721.75     13863483.02
      2010723.97     13863614.55      2010530.83     13863822.70
      2010476.36     13863934.65      2010471.45     13864173.53
      2010277.06     13864480.86      2010324.80     13865006.74
      2010227.35     13865180.52      2010223.62     13865415.34
      2010175.21     13865493.27      2010176.20     13865814.50
      2010322.65     13866080.52      2010373.95     13866514.56
      2010161.37     13866838.21      2009882.50     13867118.95
      2009917.16     13867228.40      2009824.64     13867343.41
      2009915.19     13867464.49      2010027.44     13867480.52
      2010111.38     13867561.76      2010221.53     13867726.50
      2010223.98     13867815.54      2010019.47     13867922.62
      2009707.86     13867941.27      2009577.18     13868130.45
      2009571.55     13868373.75      2009475.00     13868475.00

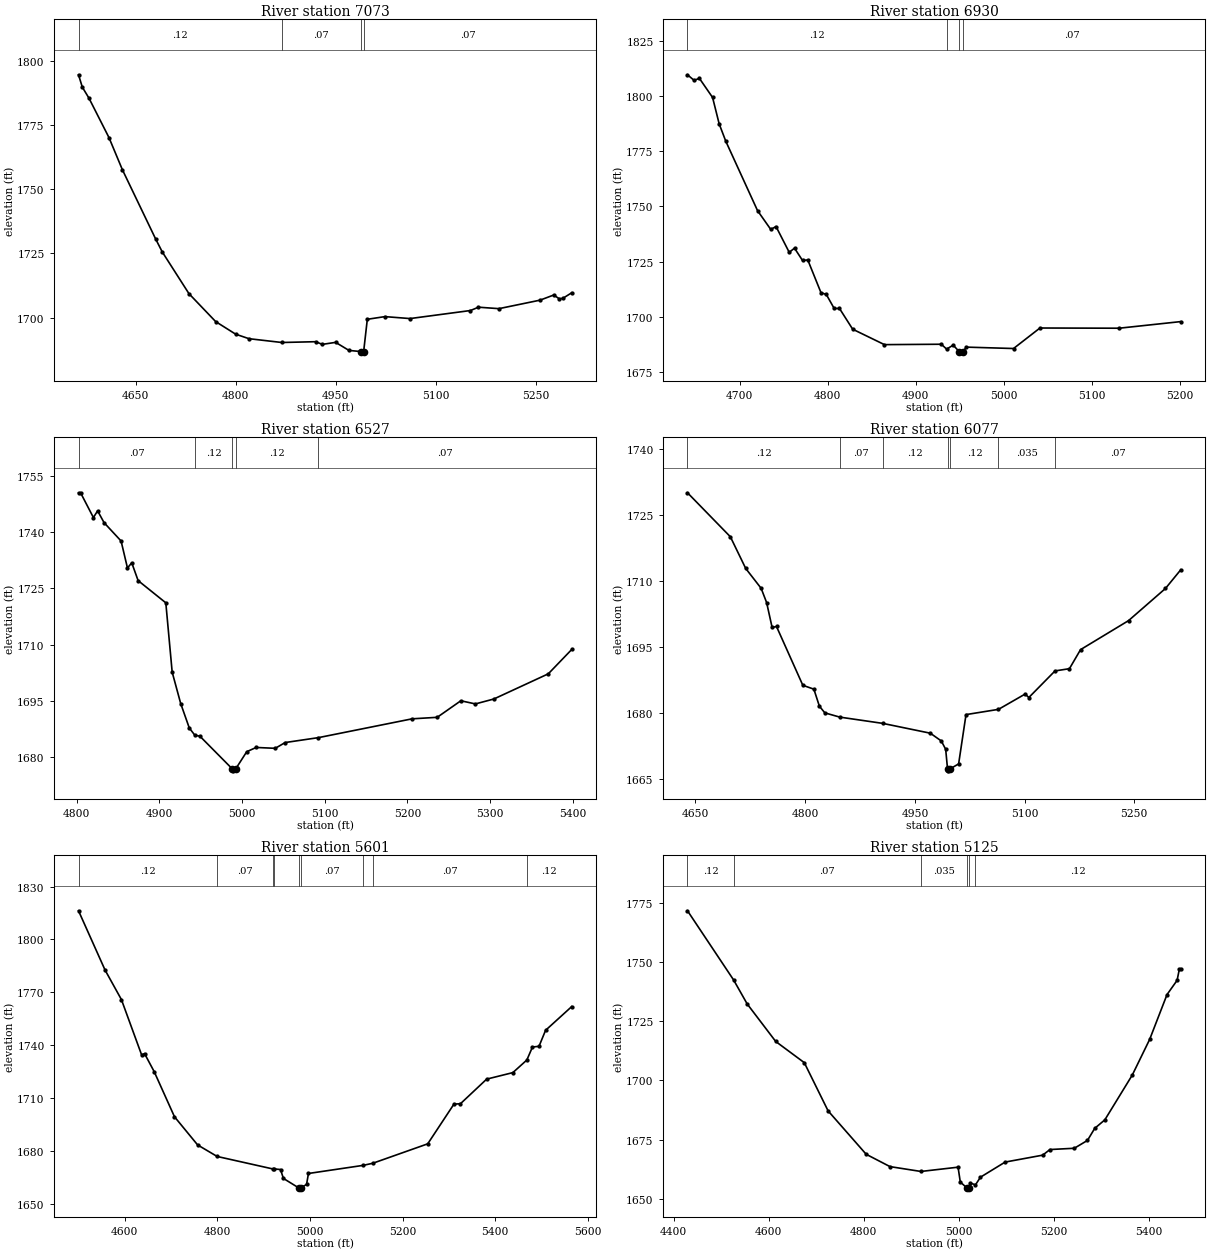
Type RM Length L Ch R = 1,7073,143,143,143
BEGIN DESCRIPTION:
POSSUM CREEK 16.0
END DESCRIPTION:
XS GIS Cut Line= 3
      2010189.30     13862925.62      2010625.00     13862925.00
      2010921.40     13862856.55
#Sta/Elev= 30
  4564.3 1794.55  4570.0 1789.73  4580.0 1785.43  4610.0 1770.08  4630.0 1757.63
  4680.0 1730.58  4690.0 1725.51  4730.0 1709.28  4770.0 1698.42  4800.0 1693.51
  4820.0 1691.75  4869.3 1690.27  4920.0 1690.58  4930.0 1689.54  4950.0 1690.32
  4970.0 1687.18  4988.0 1686.74  4988.2 1686.24  4992.0 1686.74  4997.5 1699.31
  5023.9 1700.35  5061.6 1699.59  5152.2 1702.72  5164.2 1704.02  5194.9 1703.45
  5256.6 1706.76  5277.1 1708.76  5285.5 1707.29  5290.7 1707.46  5304.2 1709.65
#Mann=4,-1,0
  4564.3    0.12       0  4869.3    0.07       0  4988.0    0.05       0
  4992.0    0.07       0
Bank Sta=4988,4992
Exp/Cntr=0.3,0.1

Type RM Length L Ch R = 1,6930,403,403,403
BEGIN DESCRIPTION:
POSSUM CREEK 15.0
END DESCRIPTION:
XS GIS Cut Line= 3
      2010225.03     13863224.98      2010525.00     13863025.00
      2010724.99     13863025.00
#Sta/Elev= 30
  4640.7 1809.70  4648.2 1807.17  4654.2 1808.09  4669.2 1799.42  4676.7 1787.42
  4684.2 1779.58  4720.3 1748.08  4735.3 1739.57  4741.3 1740.88  4756.3 1729.17
  4762.3 1731.07  4771.4 1725.49  4777.4 1725.71  4792.4 1710.86  4798.4 1710.09
  4807.4 1703.70  4813.4 1703.72  4828.4 1694.31  4864.5 1687.31  4929.1 1687.49
  4935.2 1685.28  4942.6 1687.09  4949.6 1684.09  4949.9 1683.59  4953.6 1684.09
  4957.6 1686.18  5011.2 1685.55  5041.2 1694.85  5131.2 1694.76  5201.2 1697.76
#Mann=4,-1,0
  4640.7    0.12       0  4935.2    0.07       0  4949.6    0.05       0
  4953.6    0.07       0
Bank Sta=4949.6,4953.6
Exp/Cntr=0.3,0.1

Type RM Length L Ch R = 1,6527,450,450,450
BEGIN DESCRIPTION:
POSSUM CREEK 14.0
END DESCRIPTION:
XS GIS Cut Line= 3
      2010375.05     13863374.99      2010575.00     13863325.00
      2010930.92     13863164.12
#Sta/Elev= 30
  4802.2 1750.46  4804.7 1750.46  4820.2 1743.86  4825.3 1745.65  4833.1 1742.50
  4853.7 1737.61  4861.4 1730.42  4866.6 1731.80  4874.3 1727.06  4907.8 1721.14
  4915.5 1702.67  4925.8 1694.31  4936.2 1687.79  4943.0 1685.84  4949.0 1685.61
  4988.3 1676.87  4988.5 1676.37  4992.3 1676.87  5005.7 1681.47  5017.1 1682.60
  5040.2 1682.37  5052.2 1683.91  5092.5 1685.22  5205.8 1690.23  5236.1 1690.63
  5264.7 1695.04  5282.3 1694.20  5304.6 1695.51  5370.5 1702.22  5398.9 1708.72
#Mann=5,-1,0
  4802.2    0.07       0  4943.0    0.12       0  4988.3    0.05       0
  4992.3    0.12       0  5092.5    0.07       0
Bank Sta=4988.3,4992.3
Exp/Cntr=0.3,0.1

Type RM Length L Ch R = 1,6077,476,476,476
BEGIN DESCRIPTION:
POSSUM CREEK 13.0
END DESCRIPTION:
XS GIS Cut Line= 3
      2010375.00     13863475.00      2010675.00     13863675.00
      2010985.70     13863719.33
#Sta/Elev= 30
  4639.1 1729.99  4697.7 1720.01  4718.7 1712.82  4739.8 1708.31  4747.3 1705.07
  4754.8 1699.43  4760.8 1699.65  4796.8 1686.31  4811.9 1685.43  4819.4 1681.58
  4826.9 1680.05  4847.3 1679.09  4906.0 1677.67  4971.1 1675.44  4986.1 1673.68
  4992.1 1671.79  4994.6 1667.40  4994.9 1666.90  4998.6 1667.40  5009.8 1668.47
  5019.9 1679.66  5064.3 1680.85  5100.7 1684.32  5105.8 1683.54  5141.6 1689.57
  5161.3 1690.08  5176.5 1694.40  5242.1 1700.98  5292.6 1708.28  5313.5 1712.52
#Mann=7,-1,0
  4639.1    0.12       0  4847.3    0.07       0  4906.0    0.12       0
  4994.6    0.05       0  4998.6    0.12       0  5064.3   0.035       0
  5141.6    0.07       0
Bank Sta=4994.6,4998.6
Exp/Cntr=0.3,0.1

Type RM Length L Ch R = 1,5601,476,476,476
BEGIN DESCRIPTION:
POSSUM CREEK 12.0
END DESCRIPTION:
XS GIS Cut Line= 3
      2010075.02     13863775.02      2010475.00     13864075.00
      2010875.03     13864475.03
#Sta/Elev= 30
  4499.9 1816.25  4557.2 1782.63  4592.6 1765.84  4636.3 1734.40  4642.6 1735.18
  4663.4 1724.93  4707.2 1699.35  4757.2 1683.35  4799.4 1676.80  4919.8 1669.71
  4921.6 1669.74  4936.3 1669.39  4942.6 1664.33  4975.9 1658.92  4976.2 1658.42
  4980.0 1658.92  4992.6 1660.94  4996.7 1667.14  5114.8 1671.74  5135.7 1672.94
  5254.4 1683.97  5311.0 1706.50  5325.1 1706.73  5381.7 1720.69  5438.3 1724.39
  5468.5 1731.53  5480.7 1738.92  5494.8 1739.32  5509.0 1748.40  5565.6 1761.90
#Mann=9,-1,0
  4499.9    0.12       0  4799.4    0.07       0  4919.8   0.035       0
  4921.6    0.07       0  4975.9    0.05       0  4980.0    0.07       0
  5114.8    0.12       0  5135.7    0.07       0  5468.5    0.12       0
Bank Sta=4975.9,4980
Exp/Cntr=0.3,0.1

Type RM Length L Ch R = 1,5125,464,464,464
BEGIN DESCRIPTION:
POSSUM CREEK 11.0
END DESCRIPTION:
XS GIS Cut Line= 3
      2009709.72     13864435.48      2010275.00     13864475.00
      2010675.03     13864725.02
#Sta/Elev= 30
  4429.4 1771.84  4526.5 1742.54  4555.0 1732.41  4615.1 1716.51  4675.3 1707.53
  4725.4 1687.12  4805.6 1668.74  4855.7 1663.52  4920.8 1661.47  4999.0 1663.28
  5003.7 1657.00  5017.0 1654.61  5017.3 1654.11  5021.1 1654.61  5025.0 1656.57
  5035.6 1655.80  5046.2 1659.05  5098.1 1665.44  5177.1 1668.37  5192.4 1670.75
  5243.7 1671.29  5271.4 1674.61  5286.7 1679.72  5308.0 1683.32  5365.8 1702.30
  5402.3 1717.36  5438.9 1736.36  5460.1 1742.38  5464.8 1747.07  5467.8 1747.07
#Mann=6,-1,0
  4429.4    0.12       0  4526.5    0.07       0  4920.8   0.035       0
  5017.0   0.035       0  5021.1   0.035       0  5035.6    0.12       0
Bank Sta=5017,5021.1
Exp/Cntr=0.3,0.1

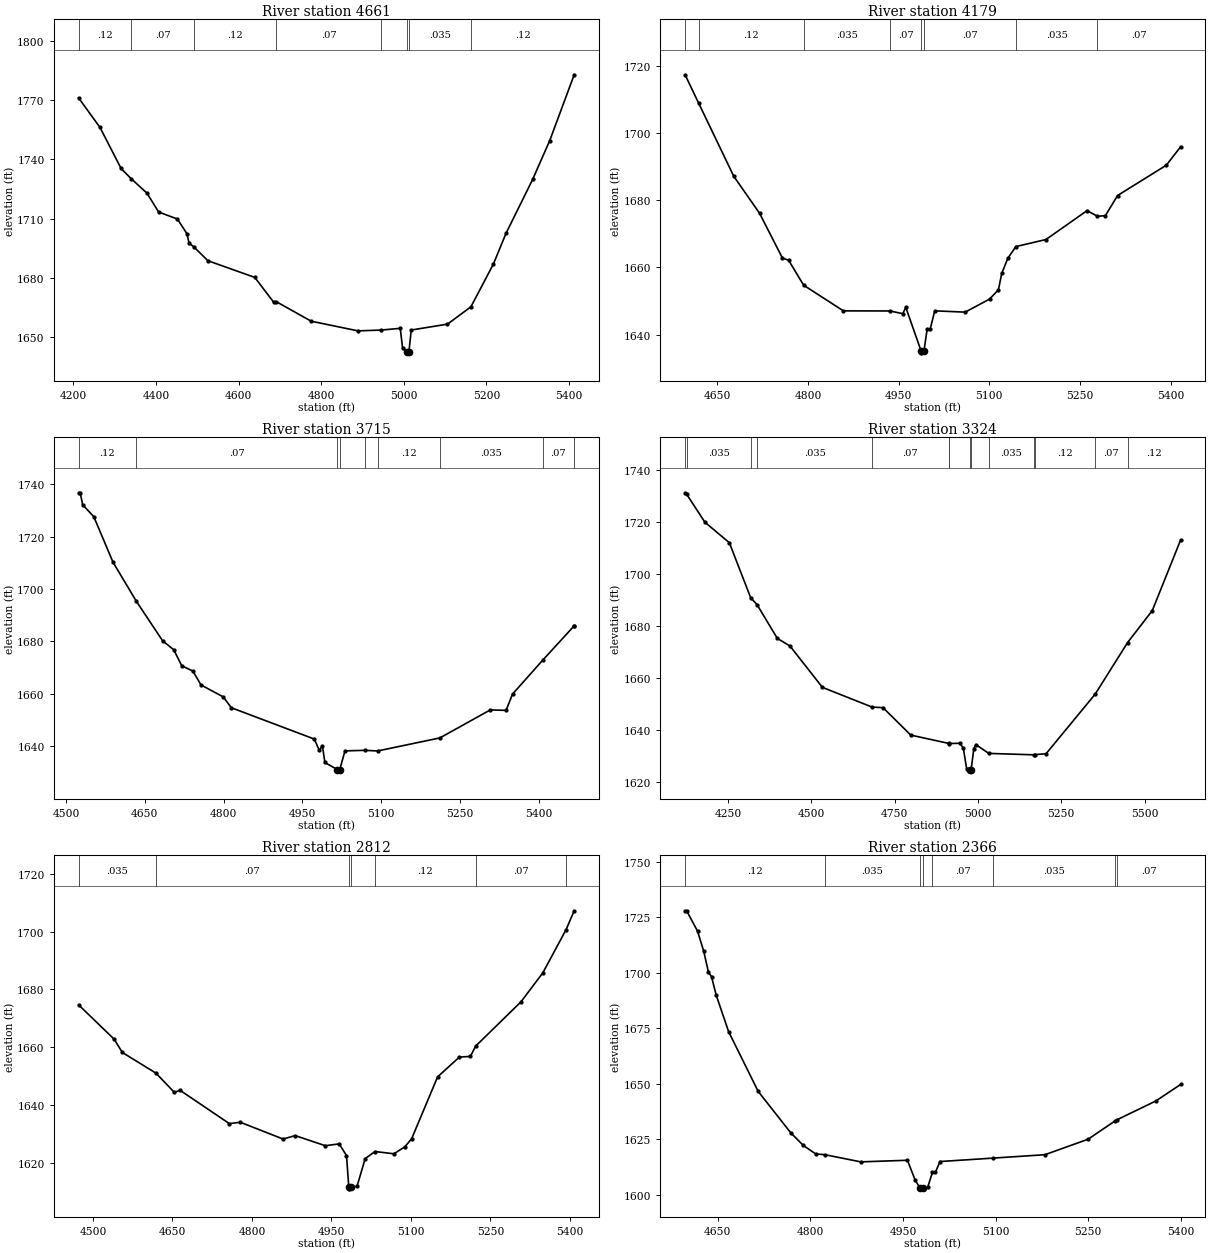
Type RM Length L Ch R = 1,4661,482,482,482
BEGIN DESCRIPTION:
POSSUM CREEK 10.0
END DESCRIPTION:
XS GIS Cut Line= 3
      2009614.19     13864587.39      2010325.00     13864925.00
      2010724.98     13864825.01
#Sta/Elev= 30
  4213.0 1771.05  4264.7 1756.14  4315.7 1735.38  4339.9 1730.25  4378.3 1722.91
  4406.6 1713.34  4452.0 1709.80  4474.8 1702.46  4480.3 1697.62  4491.9 1695.70
  4525.8 1688.71  4639.4 1680.25  4684.8 1667.75  4691.5 1667.97  4775.7 1658.11
  4889.2 1653.21  4944.9 1653.62  4991.3 1654.50  4997.1 1644.32  5008.1 1642.60
  5008.4 1642.10  5012.3 1642.60  5017.9 1653.64  5105.6 1656.62  5162.3 1665.38
  5216.4 1686.87  5247.3 1702.57  5311.7 1729.84  5353.0 1749.45  5412.2 1782.78
#Mann=8,-1,0
  4213.0    0.12       0  4339.9    0.07       0  4491.9    0.12       0
  4691.5    0.07       0  4944.9   0.035       0  5008.1   0.035       0
  5012.3   0.035       0  5162.3    0.12       0
Bank Sta=5008.1,5012.3
Exp/Cntr=0.3,0.1

Type RM Length L Ch R = 1,4179,464,464,464
BEGIN DESCRIPTION:
POSSUM CREEK 9.0
END DESCRIPTION:
XS GIS Cut Line= 3
      2009825.02     13865425.00      2010225.00     13865375.00
      2010638.54     13865429.41
#Sta/Elev= 30
  4596.5 1717.39  4619.2 1708.84  4677.1 1687.15  4719.9 1676.10  4757.7 1662.77
  4767.8 1662.18  4792.7 1654.72  4858.5 1647.08  4935.7 1647.05  4956.8 1646.24
  4961.8 1648.12  4987.2 1635.08  4987.5 1634.58  4991.8 1635.08  4997.1 1641.59
  5002.1 1641.59  5009.7 1647.09  5060.1 1646.70  5100.5 1650.60  5115.1 1653.36
  5120.6 1658.22  5130.7 1662.75  5143.9 1666.22  5193.8 1668.33  5261.8 1676.93
  5279.0 1675.25  5292.1 1675.43  5312.3 1681.43  5393.0 1690.46  5416.7 1695.95
#Mann=8,-1,0
  4596.5    0.07       0  4619.2    0.12       0  4792.7   0.035       0
  4935.7    0.07       0  4987.2    0.05       0  4991.8    0.07       0
  5143.9   0.035       0  5279.0    0.07       0
Bank Sta=4987.2,4991.8
Exp/Cntr=0.3,0.1

Type RM Length L Ch R = 1,3715,391,391,391
BEGIN DESCRIPTION:
POSSUM CREEK 8.0
END DESCRIPTION:
XS GIS Cut Line= 3
      2009774.96     13865574.98      2010175.00     13865825.00
      2010574.96     13865575.02
#Sta/Elev= 30
  4524.1 1736.68  4527.1 1736.68  4531.8 1732.11  4553.0 1727.55  4589.6 1710.19
  4633.6 1695.44  4683.9 1680.27  4705.2 1676.81  4720.5 1670.70  4741.7 1668.70
  4757.0 1663.41  4799.5 1658.85  4814.8 1654.72  4972.8 1642.78  4982.3 1638.46
  4988.2 1640.26  4992.9 1633.84  5016.5 1631.16  5016.8 1630.66  5021.2 1631.16
  5031.2 1638.27  5068.4 1638.48  5093.2 1638.24  5211.8 1643.21  5307.8 1653.89
  5337.8 1653.72  5350.2 1659.93  5407.6 1672.85  5466.5 1685.72  5467.5 1685.72
#Mann=9,-1,0
  4524.1    0.12       0  4633.6    0.07       0  5016.5    0.05       0
  5021.2    0.07       0  5068.4   0.035       0  5093.2    0.12       0
  5211.8   0.035       0  5407.6    0.07       0  5466.5    0.12       0
Bank Sta=5016.5,5021.2
Exp/Cntr=0.3,0.1

Type RM Length L Ch R = 1,3324,512,512,512
BEGIN DESCRIPTION:
POSSUM CREEK 7.0
END DESCRIPTION:
XS GIS Cut Line= 3
      2009488.37     13866423.32      2010321.67     13866162.91
      2010725.01     13866625.01
#Sta/Elev= 30
  4121.8 1731.07  4126.8 1730.45  4181.1 1719.79  4254.5 1711.90  4318.6 1690.77
  4337.6 1688.15  4398.5 1675.17  4436.2 1672.29  4533.7 1656.39  4682.4 1648.83
  4715.5 1648.60  4798.7 1638.07  4912.4 1634.88  4914.1 1634.82  4945.9 1634.93
  4956.4 1633.06  4966.4 1625.08  4974.9 1624.85  4975.3 1624.35  4979.8 1624.85
  4987.9 1632.90  4994.0 1634.41  5032.8 1631.04  5167.1 1630.50  5172.1 1630.60
  5204.3 1630.88  5352.0 1653.81  5448.9 1673.55  5523.2 1685.87  5608.2 1712.96
#Mann=14,-1,0
  4121.8    0.07       0  4126.8   0.035       0  4318.6    0.07       0
  4337.6   0.035       0  4682.4    0.07       0  4912.4   0.035       0
  4914.1    0.07       0  4974.9    0.05       0  4979.8    0.07       0
  5032.8   0.035       0  5167.1    0.07       0  5172.1    0.12       0
  5352.0    0.07       0  5448.9    0.12       0
Bank Sta=4974.9,4979.8
Exp/Cntr=0.3,0.1

Type RM Length L Ch R = 1,2812,446,446,446
BEGIN DESCRIPTION:
POSSUM CREEK 6.0
END DESCRIPTION:
XS GIS Cut Line= 3
      2009770.45     13866488.43      2010275.00     13866625.00
      2010674.99     13866725.00
#Sta/Elev= 30
  4472.9 1674.65  4539.8 1662.81  4555.4 1658.19  4618.9 1651.02  4653.7 1644.34
  4664.1 1645.12  4757.3 1633.57  4778.0 1634.04  4858.7 1628.23  4881.6 1629.42
  4938.4 1625.92  4964.5 1626.56  4978.3 1622.53  4982.7 1611.50  4983.1 1611.00
  4987.7 1611.50  4998.2 1611.89  5013.6 1621.48  5032.1 1623.91  5067.8 1623.13
  5088.4 1625.54  5101.3 1628.36  5150.2 1649.74  5191.4 1656.61  5212.1 1656.82
  5221.9 1660.37  5307.4 1675.69  5348.6 1685.70  5392.5 1700.64  5407.9 1707.22
#Mann=7,-1,0
  4472.9   0.035       0  4618.9    0.07       0  4982.7    0.05       0
  4987.7    0.07       0  5032.1    0.12       0  5221.9    0.07       0
  5392.5    0.12       0
Bank Sta=4982.7,4987.7
Exp/Cntr=0.3,0.1

Type RM Length L Ch R = 1,2366,458,458,458
BEGIN DESCRIPTION:
POSSUM CREEK 5.0
END DESCRIPTION:
XS GIS Cut Line= 3
      2009625.00     13866925.00      2010025.00     13866975.00
      2010424.99     13866975.00
#Sta/Elev= 30
  4596.9 1727.91  4599.4 1727.91  4617.1 1718.71  4627.1 1709.66  4634.7 1700.34
  4639.7 1698.25  4647.3 1689.91  4667.4 1673.49  4715.3 1646.57  4768.2 1627.88
  4788.4 1622.23  4808.5 1618.40  4823.7 1618.03  4881.6 1614.81  4957.2 1615.53
  4969.8 1606.57  4977.4 1603.16  4977.7 1602.66  4982.4 1603.16  4989.9 1603.29
  4997.8 1610.08  5002.5 1610.08  5010.0 1614.96  5096.4 1616.51  5180.0 1618.03
  5250.0 1625.01  5293.4 1633.19  5297.0 1633.79  5360.0 1642.26  5400.0 1649.68
#Mann=8,-1,0
  4596.9    0.12       0  4823.7   0.035       0  4977.4    0.05       0
  4982.4   0.035       0  4997.8    0.07       0  5096.4   0.035       0
  5293.4    0.12       0  5297.0    0.07       0
Bank Sta=4977.4,4982.4
Exp/Cntr=0.3,0.1

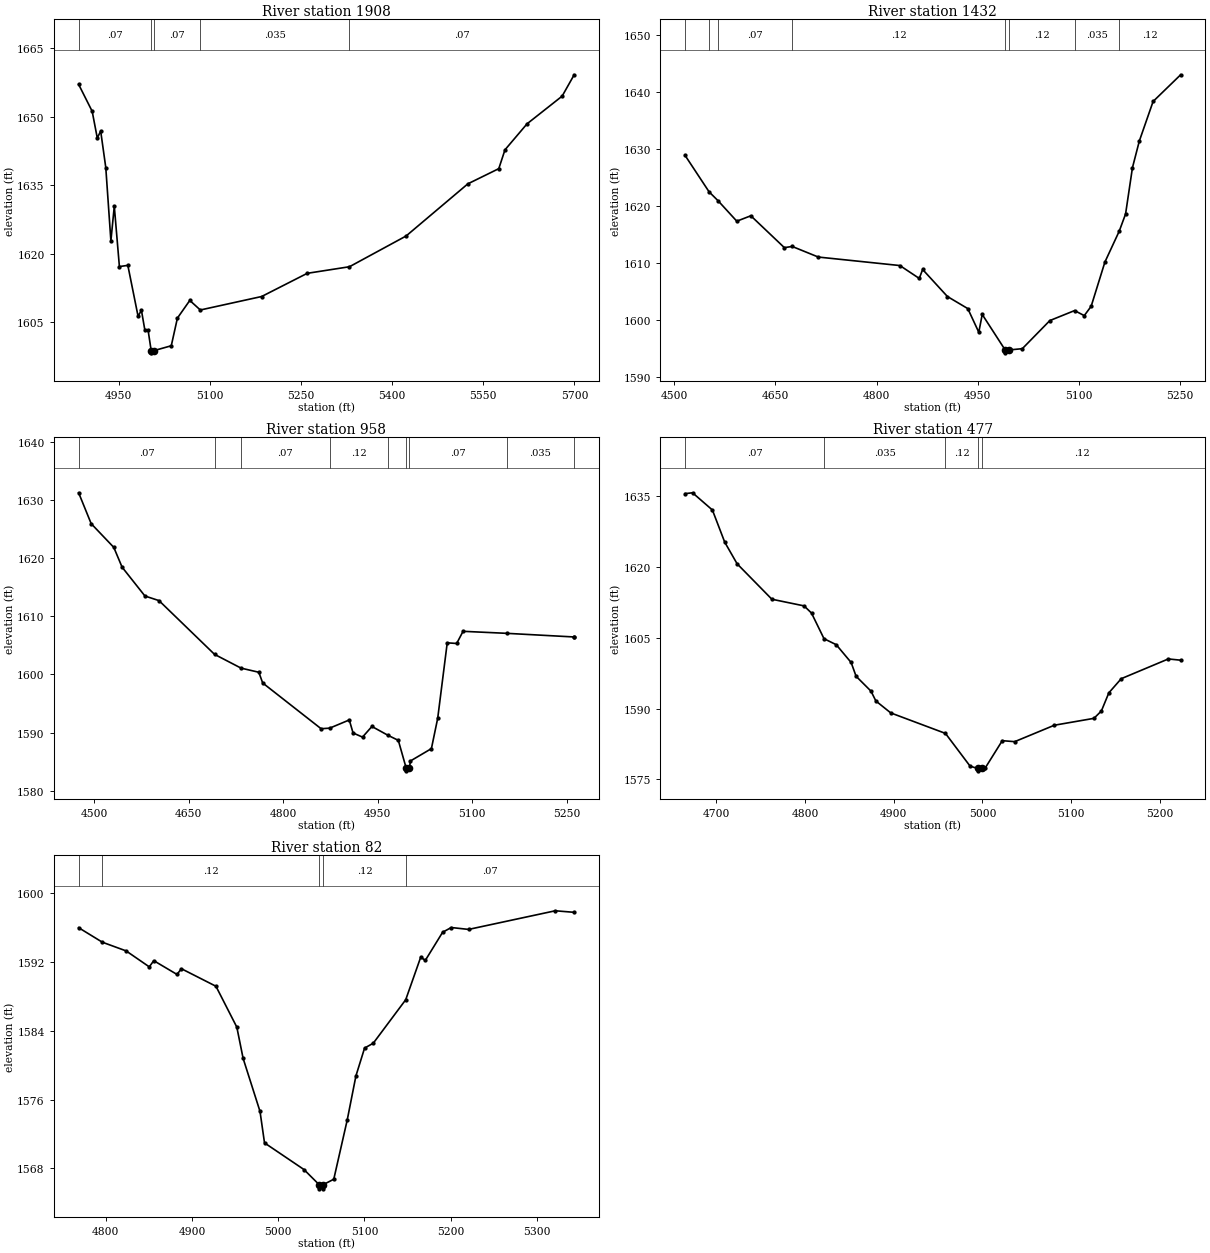
Type RM Length L Ch R = 1,1908,476,476,476
BEGIN DESCRIPTION:
POSSUM CREEK 4.0
END DESCRIPTION:
XS GIS Cut Line= 3
      2009725.03     13867275.01      2009825.00     13867325.00
      2010516.99     13867195.90
#Sta/Elev= 30
  4883.8 1657.03  4906.1 1651.14  4914.5 1645.30  4920.1 1646.82  4928.5 1638.83
  4936.9 1622.81  4942.5 1630.38  4950.9 1617.19  4964.8 1617.45  4981.6 1606.35
  4987.2 1607.60  4992.8 1603.30  4998.1 1603.30  5003.2 1598.82  5003.6 1598.32
  5008.2 1598.82  5036.3 1599.87  5046.4 1605.92  5066.8 1609.78  5084.1 1607.69
  5185.1 1610.64  5260.1 1615.71  5329.6 1617.15  5422.8 1623.87  5524.5 1635.28
  5575.4 1638.60  5585.6 1642.72  5621.9 1648.40  5679.7 1654.46  5699.5 1659.13
#Mann=5,-1,0
  4883.8    0.07       0  5003.2    0.05       0  5008.2    0.07       0
  5084.1   0.035       0  5329.6    0.07       0
Bank Sta=5003.2,5008.2
Exp/Cntr=0.3,0.1

Type RM Length L Ch R = 1,1432,474,474,474
BEGIN DESCRIPTION:
POSSUM CREEK 3.0
END DESCRIPTION:
XS GIS Cut Line= 3
      2009648.91     13867569.16      2010125.00     13867625.00
      2010375.00     13867575.00
#Sta/Elev= 30
  4516.2 1628.81  4551.8 1622.42  4565.2 1620.85  4592.8 1617.28  4613.6 1618.23
  4663.3 1612.64  4674.9 1612.85  4713.6 1610.99  4834.5 1609.50  4863.2 1607.24
  4868.2 1608.81  4904.9 1604.07  4935.1 1601.95  4951.4 1597.80  4956.5 1600.92
  4990.5 1594.69  4990.9 1594.19  4995.6 1594.69  5015.9 1594.92  5056.7 1599.85
  5093.3 1601.60  5107.7 1600.72  5117.9 1602.35  5138.3 1610.12  5159.5 1615.53
  5168.9 1618.54  5179.1 1626.67  5189.3 1631.35  5209.7 1638.28  5250.5 1642.96
#Mann=8,-1,0
  4516.2    0.07       0  4551.8   0.035       0  4565.2    0.07       0
  4674.9    0.12       0  4990.5    0.05       0  4995.6    0.12       0
  5093.3   0.035       0  5159.5    0.12       0
Bank Sta=4990.5,4995.6
Exp/Cntr=0.3,0.1

Type RM Length L Ch R = 1,958,481,481,481
BEGIN DESCRIPTION:
POSSUM CREEK 2.0
END DESCRIPTION:
XS GIS Cut Line= 3
      2009588.20     13867625.61      2010025.00     13867925.00
      2010048.19     13868180.60
#Sta/Elev= 30
  4475.5 1631.23  4495.4 1625.92  4531.3 1621.84  4544.4 1618.45  4580.7 1613.48
  4603.0 1612.69  4691.1 1603.45  4733.2 1601.08  4761.4 1600.37  4767.5 1598.53
  4860.2 1590.66  4873.8 1590.76  4904.9 1592.17  4910.9 1589.93  4925.9 1589.22
  4940.8 1591.05  4966.3 1589.53  4982.7 1588.66  4995.1 1583.92  4995.5 1583.42
  5000.2 1583.92  5002.0 1585.12  5035.2 1587.24  5045.2 1592.47  5060.3 1605.43
  5075.3 1605.32  5085.4 1607.41  5155.2 1607.06  5261.2 1606.44  5261.7 1606.39
#Mann=9,-1,0
  4475.5    0.07       0  4691.1    0.12       0  4733.2    0.07       0
  4873.8    0.12       0  4966.3    0.07       0  4995.1    0.05       0
  5000.2    0.07       0  5155.2   0.035       0  5261.2    0.07       0
Bank Sta=4995.1,5000.2
Exp/Cntr=0.3,0.1

Type RM Length L Ch R = 1,477,395,395,395
BEGIN DESCRIPTION:
POSSUM CREEK 1.0
END DESCRIPTION:
XS GIS Cut Line= 3
      2009474.99     13867774.98      2009625.00     13868075.00
      2009824.96     13868174.98
#Sta/Elev= 30
  4664.6 1635.54  4673.0 1635.72  4695.4 1632.07  4709.3 1625.26  4723.3 1620.67
  4762.5 1613.17  4798.8 1611.76  4807.2 1610.24  4821.3 1604.81  4835.1 1603.54
  4851.9 1599.77  4857.5 1596.85  4874.3 1593.70  4879.8 1591.62  4896.6 1589.09
  4958.3 1584.75  4986.1 1577.81  4994.7 1577.32  4995.1 1576.82  4999.8 1577.32
  5002.8 1577.32  5022.4 1583.21  5036.4 1583.00  5081.1 1586.48  5125.8 1587.94
  5134.2 1589.50  5142.6 1593.34  5156.6 1596.34  5209.7 1600.52  5223.6 1600.26
#Mann=5,-1,0
  4664.6    0.07       0  4821.3   0.035       0  4958.3    0.12       0
  4994.7    0.05       0  4999.8    0.12       0
Bank Sta=4994.7,4999.8
Exp/Cntr=0.3,0.1

Type RM Length L Ch R = 1,82,0,0,0
BEGIN DESCRIPTION:
POSSUM CREEK 0.0
END DESCRIPTION:
XS GIS Cut Line= 3
      2009444.51     13868203.45      2009515.27     13868423.66
      2009856.78     13868457.62
#Sta/Elev= 30
  4768.7 1596.01  4796.2 1594.32  4823.7 1593.31  4850.6 1591.45  4855.8 1592.17
  4882.7 1590.57  4887.9 1591.23  4927.9 1589.19  4952.1 1584.43  4959.4 1580.79
  4979.0 1574.61  4984.2 1570.95  5029.9 1567.85  5047.4 1566.10  5047.8 1565.60
  5052.2 1565.60  5052.5 1566.10  5064.5 1566.72  5080.1 1573.62  5090.2 1578.76
  5100.2 1581.99  5110.3 1582.56  5147.9 1587.62  5165.3 1592.58  5170.6 1592.20
  5190.7 1595.48  5200.7 1596.03  5220.8 1595.81  5321.3 1597.98  5343.2 1597.80
#Mann=5,-1,0
  4768.7   0.035       0  4796.2    0.12       0  5047.4    0.05       0
  5052.5    0.12       0  5147.9    0.07       0
Bank Sta=5047.4,5052.5
Exp/Cntr=0.3,0.1

Chan Stop Cuts=-1