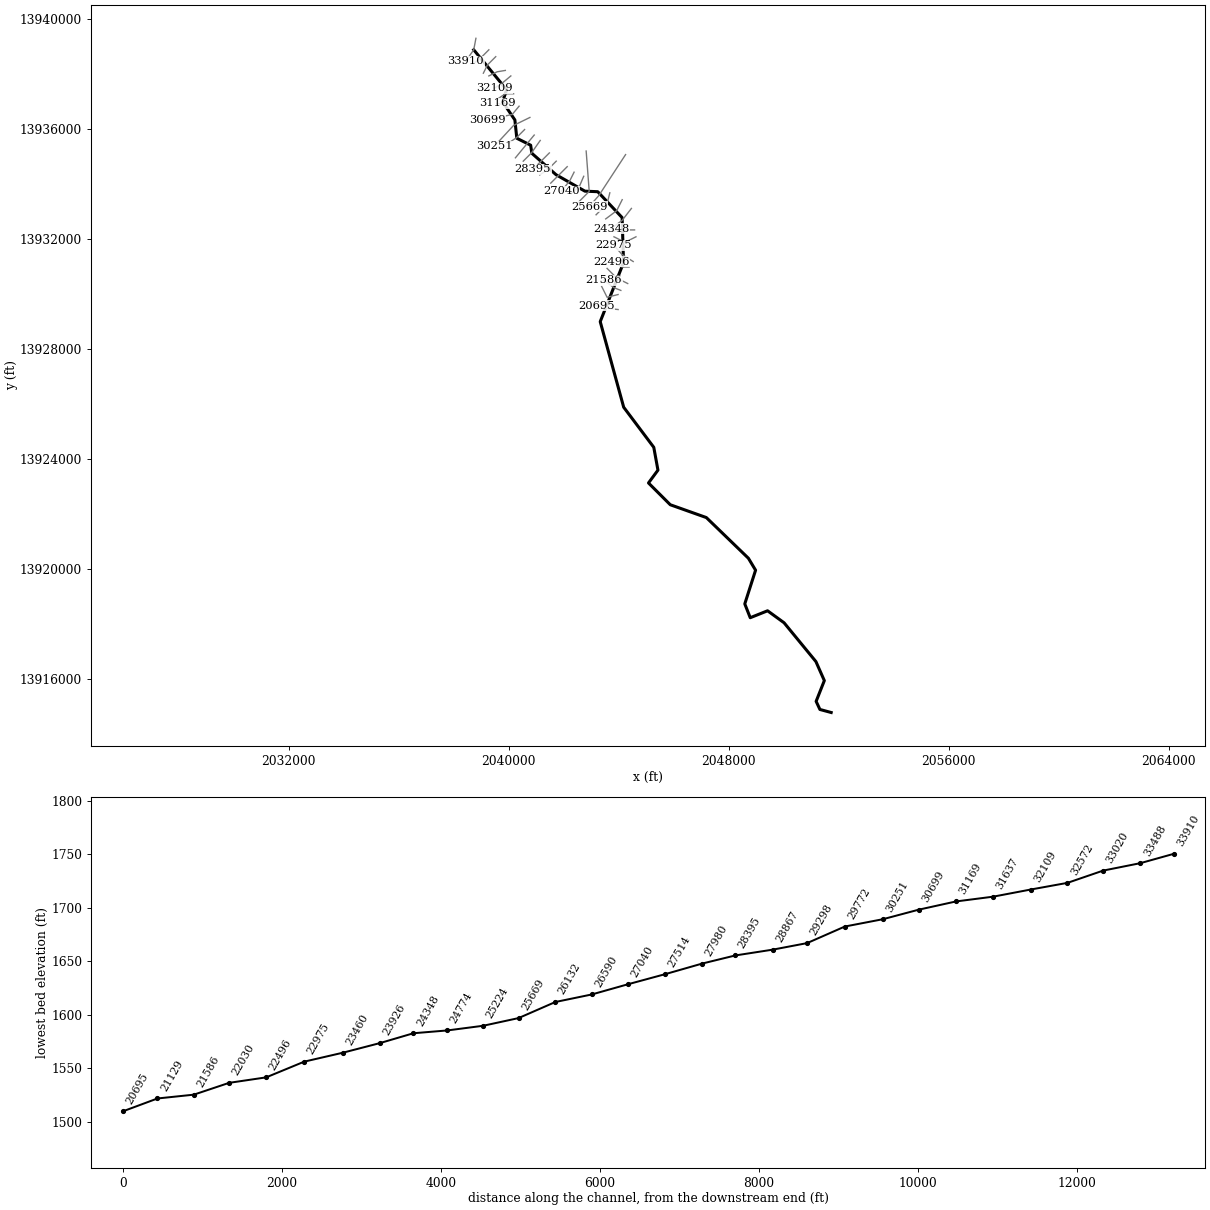
--- REEH CREEK.prj (project) ---

Proj Title=REEH CREEK Base Level Engineering
Current Plan=p01
Default Exp/Contr=0.3,0.1
English Units
Geom File=g01
Flow File=f01
Plan File=p01
Y Axis Title=Elevation
X Axis Title(PF)=Main Channel Distance
X Axis Title(XS)=Station
BEGIN DESCRIPTION:
REEH CREEK
END DESCRIPTION:
DSS Export Rating Curves= 0
DSS Export Rating Curve Sorted= 0
DSS Export Volume Flow Curves= 0
DXF OffsetX= 0
DXF OffsetY= 0
DXF ScaleX= 1
DXF ScaleY= 10

--- REEH CREEK.p01 (plan) ---

Plan Title=Multiple Run
Short Identifier=Multiple
Geom File=g01
Flow File=f01
Subcritical Flow
K Sum by GR= 0
Std Step Tol= 0.01
Critical Tol= 0.01
Num of Std Step Trials= 20
Max Error Tol= 0.3
Flow Tol Ratio= 0.001
Split Flow NTrial= 30
Split Flow Tol= 0.02
Split Flow Ratio= 0.02
Log Output Level= 0
Friction Slope Method= 1
Unsteady Friction Slope Method= 2
Unsteady Bridges Friction Slope Method= 1
Parabolic Critical Depth
Global Vel Dist=  1 , 1 , 1
Global Log Level= 0
CheckData=True
Encroach Param= -1, 0, 0, 0
BEGIN DESCRIPTION:
Multiple Run
END DESCRIPTION:

--- REEH CREEK.f01 (steady flow) ---

Flow Title=Multiple
Program Version=4.10
Number of Profiles= 7
Profile Names=10-year,25-year,50-year,1pct_min,100-year,1pct_plu,500-year
River Rch & RM=REEH CREEK,Reach-1         ,33910
     412     672     912     603    1204    2402    2076
River Rch & RM=REEH CREEK,Reach-1         ,33488
     828    1410    1967    1333    2659    5306    4820
River Rch & RM=REEH CREEK,Reach-1         ,29772
    1038    1780    2495    1698    3387    6759    6190
River Rch & RM=REEH CREEK,Reach-1         ,26590
    1401    2438    3452    2369    4727    9432    8793
River Rch & RM=REEH CREEK,Reach-1         ,20695
    1772    3121    4453    3077    6139   12249   11580
River Rch & RM=REEH CREEK,Reach-1         ,17929
    2643    4750    6871    4807    9592   19138   18556
River Rch & RM=REEH CREEK,Reach-1         ,17026
    2668    4794    6933    4849    9674   19303   18704
River Rch & RM=REEH CREEK,Reach-1         ,15662
    3410    6168    8960    6291   12552   25044   24447
River Rch & RM=REEH CREEK,Reach-1         ,14245
    3515    6346    9205    6451   12872   25682   24981
River Rch & RM=REEH CREEK,Reach-1         ,6857
    3517    6330    9162    6406   12781   25501   24683
Boundary for River Rch & Prof#=REEH CREEK,Reach-1         , 1
Up Type= 0
Dn Type= 3
Dn Slope=0.005
Boundary for River Rch & Prof#=REEH CREEK,Reach-1         , 2
Up Type= 0
Dn Type= 3
Dn Slope=0.005
Boundary for River Rch & Prof#=REEH CREEK,Reach-1         , 3
Up Type= 0
Dn Type= 3
Dn Slope=0.005
Boundary for River Rch & Prof#=REEH CREEK,Reach-1         , 4
Up Type= 0
Dn Type= 3
Dn Slope=0.005
Boundary for River Rch & Prof#=REEH CREEK,Reach-1         , 5
Up Type= 0
Dn Type= 3
Dn Slope=0.005
Boundary for River Rch & Prof#=REEH CREEK,Reach-1         , 6
Up Type= 0
Dn Type= 3
Dn Slope=0.005
Boundary for River Rch & Prof#=REEH CREEK,Reach-1         , 7
Up Type= 0
Dn Type= 3
Dn Slope=0.005
DSS Import GetInterval= 0
DSS Import GetPeak= 0
DSS Import FillOption= 0

--- REEH CREEK.g01 (geometry) ---

Geom Title=Existing Conditions
Program Version=4.10

River Reach=REEH CREEK      ,Reach-1
Reach XY= 30
        2038725.       13938875.      2039921.54      13937423.5
       2039776.1     13936984.64      2040221.66     13936323.28
      2040291.63     13935658.29      2040795.58     13935405.41
      2040838.36     13935111.66      2041718.84     13934332.88
      2042768.33      13933734.3      2043235.17     13933714.68
      2044121.46     13932773.54       2044173.9     13931135.55
      2043325.24      13928989.1      2044178.75     13925876.55
      2045272.93     13924419.14      2045424.46     13923588.86
      2045080.39     13923122.56       2045872.7     13922330.83
      2047184.68     13921864.22      2048714.22     13920384.68
      2048975.21     13919950.09      2048582.33      13918725.1
      2048780.73     13918222.38      2049411.14     13918474.46
      2050011.39     13918038.24      2051169.17      13916627.3
      2051475.51     13915935.17      2051177.26     13915180.94
        2051315.     13914885.63        2051725.       13914775.

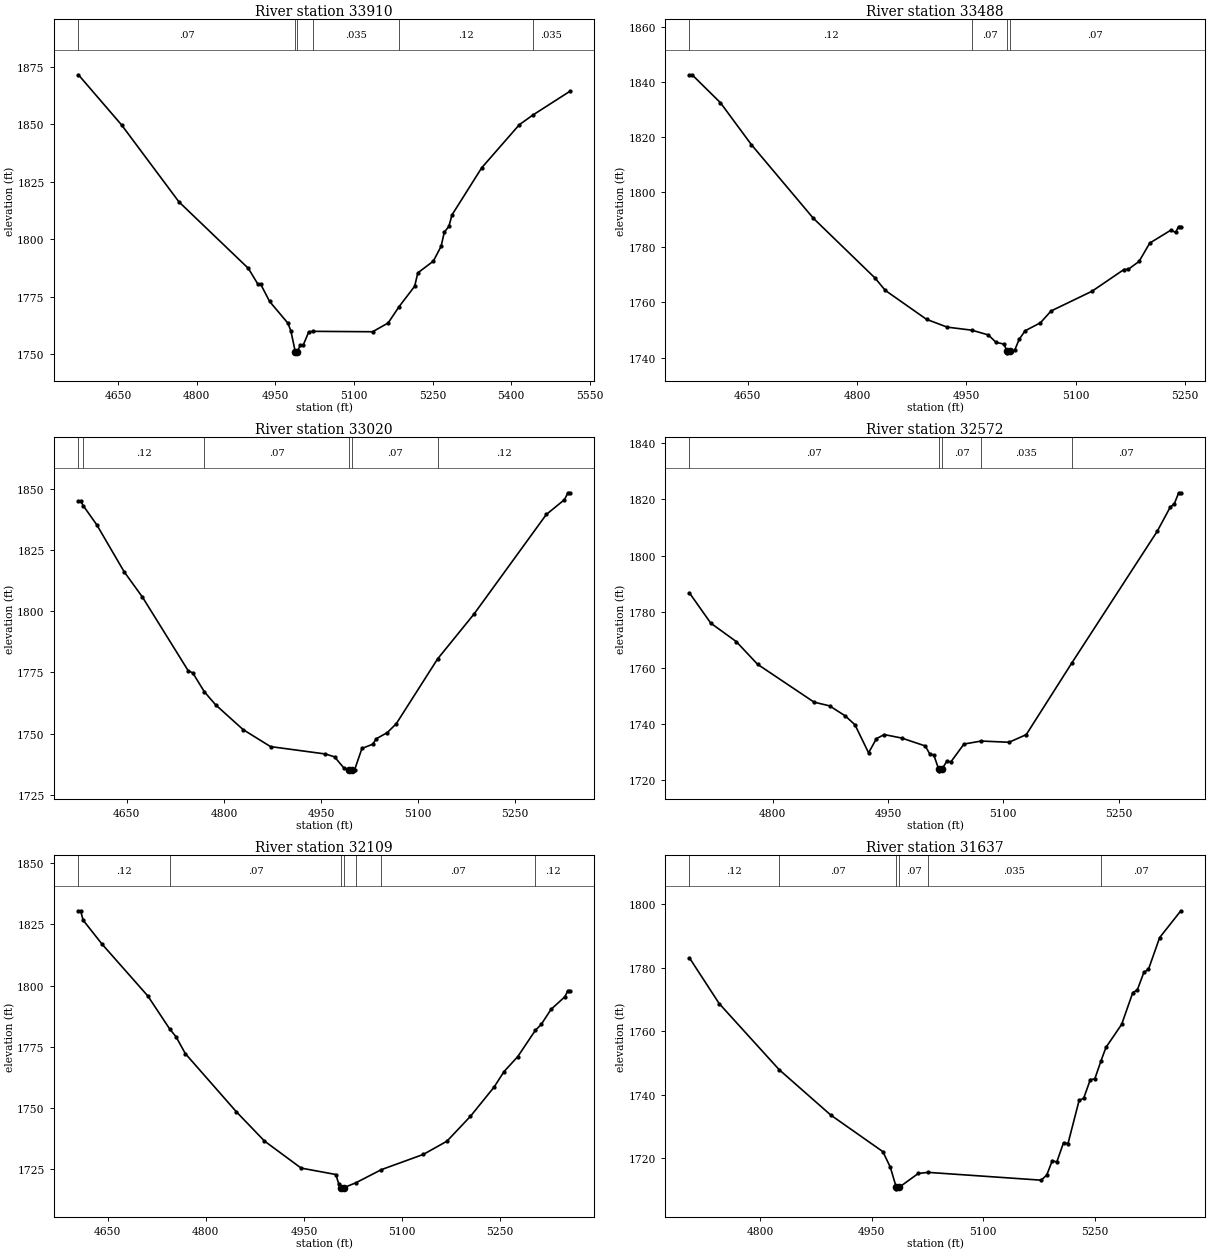
Type RM Length L Ch R = 1 ,33910   ,422,422,422
BEGIN DESCRIPTION:
REEH CREEK 70.0
END DESCRIPTION:
XS GIS Cut Line= 3
      2038805.01     13939293.52        2038725.       13938875.
      2038430.84     13938456.06
#Sta/Elev= 30
  4573.9 1871.65  4656.4 1849.76  4765.8 1816.26  4898.2  1787.3  4916.8 1780.29
  4921.9 1780.34  4938.9 1772.85    4974 1763.34  4979.6 1759.89  4987.8 1750.97
  4988.1 1750.47  4991.8 1750.97  4997.5 1753.86  5003.1 1753.86  5013.5 1759.58
  5021.3 1759.84  5135.5 1759.66  5165.1 1763.48  5186.2 1770.66  5215.7 1779.48
  5221.8 1785.33  5251.4 1790.43  5266.2 1796.89  5272.3 1803.05    5281 1805.56
  5287.1 1810.62  5343.8 1831.14  5415.4 1849.86  5440.8 1854.02  5511.9 1864.42
#Mann= 6 ,-1 , 0
  4573.9     .07       0  4987.8     .05       0  4991.8     .07       0
  5021.3    .035       0  5186.2     .12       0  5440.8    .035       0
Bank Sta=4987.8,4991.8
XS Rating Curve= 0 ,0
Exp/Cntr=0.3,0.1

Type RM Length L Ch R = 1 ,33488   ,468,468,468
BEGIN DESCRIPTION:
REEH CREEK 69.0
END DESCRIPTION:
XS GIS Cut Line= 3
      2039275.02     13938875.02        2038975.       13938575.
      2038774.99     13938424.99
#Sta/Elev= 30
  4570.2 1842.68  4573.8 1842.68  4612.7 1832.54  4655.1 1817.33  4739.9 1790.66
  4824.8 1768.89  4838.9 1764.39  4895.5 1753.88  4923.8 1751.05  4957.8 1749.93
  4980.3 1748.21    4991  1745.5  5001.8  1744.9    5006 1742.21  5006.3 1741.71
    5010 1742.21  5016.4 1742.59  5022.6 1746.62  5030.9 1749.73  5051.8 1752.62
  5066.4 1756.91  5122.6 1764.08  5166.4 1771.96  5172.6 1772.09  5187.2 1774.91
  5201.8 1781.56  5230.9 1786.27  5237.2 1785.43  5241.4 1787.58  5244.5 1787.58
#Mann= 4 ,-1 , 0
  4570.2     .12       0  4957.8     .07       0    5006     .05       0
    5010     .07       0
Bank Sta=5006,5010
XS Rating Curve= 0 ,0
Exp/Cntr=0.3,0.1

Type RM Length L Ch R = 1 ,33020   ,448,448,448
BEGIN DESCRIPTION:
REEH CREEK 68.0
END DESCRIPTION:
XS GIS Cut Line= 3
      2039525.02     13938625.02        2039225.       13938325.
        2039075.       13938025.
#Sta/Elev= 30
  4575.1 1844.82  4578.7 1844.82  4582.7    1843  4603.4 1835.28  4645.8 1816.07
  4674.1 1805.72  4744.8 1775.66  4751.9 1774.77  4769.8 1767.04  4787.3 1761.71
  4829.7  1751.6  4872.1 1744.66    4957 1741.64  4971.1 1740.47  4985.2 1736.02
  4993.8 1735.26  4994.1 1734.76  4997.8 1735.26  5002.2 1735.26  5013.4  1743.9
  5030.1 1745.64  5035.7 1747.88  5052.5 1750.35  5066.5    1754  5130.4 1780.48
  5186.7  1798.8  5298.5 1839.47  5326.4 1845.49    5332 1848.33  5334.8 1848.33
#Mann= 6 ,-1 , 0
  4575.1     .07       0  4582.7     .12       0  4769.8     .07       0
  4993.8     .05       0  4997.8     .07       0  5130.4     .12       0
Bank Sta=4993.8,4997.8
XS Rating Curve= 0 ,0
Exp/Cntr=0.3,0.1

Type RM Length L Ch R = 1 ,32572   ,463,463,463
BEGIN DESCRIPTION:
REEH CREEK 67.0
END DESCRIPTION:
XS GIS Cut Line= 3
      2039874.96     13938124.99        2039575.       13938075.
        2039275.       13937925.
#Sta/Elev= 30
  4691.6 1786.67  4719.4  1775.9  4752.4 1769.37  4780.3 1761.25  4853.8 1747.77
    4874 1746.45  4894.3 1742.89    4907 1739.71  4924.7 1729.73  4934.9 1734.76
    4945 1736.23  4967.8 1734.99  4998.5 1732.17  5004.1 1729.44  5009.7 1728.85
  5016.1 1723.81  5016.3 1723.31  5020.1 1723.81  5026.4 1726.72    5032 1726.56
  5048.8 1732.85  5071.3 1733.92  5107.5 1733.49  5129.9  1736.2    5189 1761.64
  5300.4 1808.65  5317.1 1817.14  5322.7 1818.51  5328.3 1822.35  5331.1 1822.35
#Mann= 5 ,-1 , 0
  4691.6     .07       0  5016.1     .05       0  5020.1     .07       0
  5071.3    .035       0    5189     .07       0
Bank Sta=5016.1,5020.1
XS Rating Curve= 0 ,0
Exp/Cntr=0.3,0.1

Type RM Length L Ch R = 1 ,32109   ,472,472,472
BEGIN DESCRIPTION:
REEH CREEK 66.0
END DESCRIPTION:
XS GIS Cut Line= 3
      2040075.01     13937925.01        2039775.       13937675.
      2039474.98     13937474.99
#Sta/Elev= 30
  4605.2 1830.58  4608.5 1830.58  4612.4 1826.75    4641 1817.07  4711.3  1795.8
  4744.9 1782.25  4754.3  1779.2  4768.6 1772.28  4846.7  1748.5  4889.6 1736.58
  4945.6 1725.54  4998.7 1722.92  5003.2 1718.97  5007.2 1717.57  5007.5 1717.07
  5011.2 1717.57  5029.5 1719.57  5068.3 1724.91  5132.4 1731.12  5168.5 1736.52
  5204.5 1746.71  5240.6 1758.62  5255.6 1764.88  5276.7 1771.04  5303.5 1781.72
  5312.7 1784.23  5327.7 1790.37  5348.8 1795.49  5353.3 1797.95  5356.3 1797.95
#Mann= 7 ,-1 , 0
  4605.2     .12       0  4744.9     .07       0  5007.2     .05       0
  5011.2     .07       0  5029.5    .035       0  5068.3     .07       0
  5303.5     .12       0
Bank Sta=5007.2,5011.2
XS Rating Curve= 0 ,0
Exp/Cntr=0.3,0.1

Type RM Length L Ch R = 1 ,31637   ,468,468,468
BEGIN DESCRIPTION:
REEH CREEK 65.0
END DESCRIPTION:
XS GIS Cut Line= 3
      2040175.05       13937275.        2039875.       13937275.
        2039575.       13937075.
#Sta/Elev= 30
    4705 1783.17    4745 1768.76  4825.5 1747.97    4895 1733.64    4965 1722.12
    4975 1717.23    4983  1710.9  4983.3  1710.4    4987  1710.9  5012.6 1715.24
  5025.8 1715.59  5177.8 1713.13  5185.3 1714.73  5192.8 1719.31  5198.8 1718.84
  5207.9 1724.95  5213.9 1724.68  5228.9 1738.31  5234.9 1738.89  5243.9 1744.82
  5249.9 1745.03    5258 1750.55  5264.9 1754.95    5286 1762.21    5301 1772.23
    5307 1773.02    5316 1778.68    5322 1779.52  5337.1 1789.56  5365.6 1798.01
#Mann= 6 ,-1 , 0
    4705     .12       0  4825.5     .07       0    4983     .05       0
    4987     .07       0  5025.8    .035       0    5258     .07       0
Bank Sta=4983,4987
XS Rating Curve= 0 ,0
Exp/Cntr=0.3,0.1

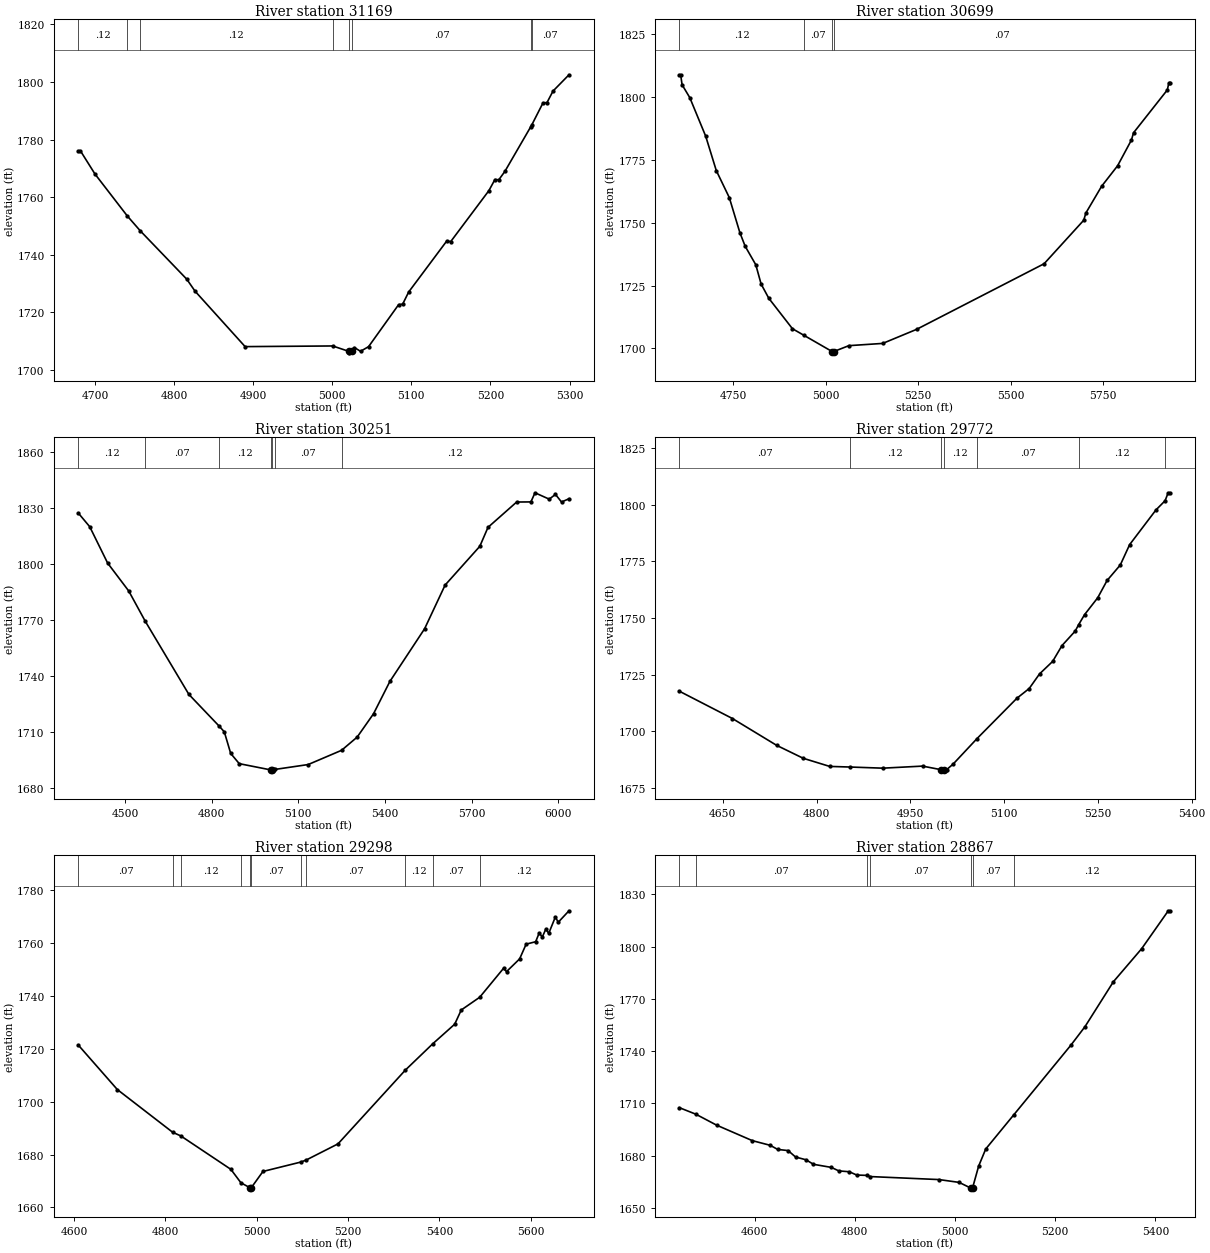
Type RM Length L Ch R = 1 ,31169   ,470,470,470
BEGIN DESCRIPTION:
REEH CREEK 64.0
END DESCRIPTION:
XS GIS Cut Line= 3
      2040174.97     13936974.99        2039875.       13936875.
      2039575.03     13936924.99
#Sta/Elev= 30
    4679 1776.08  4681.6 1776.08    4700 1768.03  4740.8 1753.49  4757.1 1748.35
    4816 1731.52  4826.5 1727.35  4889.8 1708.09  5000.5 1708.32  5021.1 1706.43
  5021.3 1705.93  5025.1 1706.43  5028.1 1707.75  5035.7 1706.46  5045.9 1708.08
  5083.9 1722.67    5089 1722.84  5096.6 1727.06  5144.7 1744.76  5149.8 1744.58
    5198 1762.26  5205.6  1766.1  5210.6 1766.06  5218.2 1768.93  5251.1 1784.53
  5252.2 1785.06  5266.4 1792.73  5271.5 1792.86  5279.1 1796.85  5299.3 1802.51
#Mann= 8 ,-1 , 0
    4679     .12       0  4740.8     .07       0  4757.1     .12       0
  5000.5     .07       0  5021.1     .05       0  5025.1     .07       0
  5251.1    .035       0  5252.2     .07       0
Bank Sta=5021.1,5025.1
XS Rating Curve= 0 ,0
Exp/Cntr=0.3,0.1

Type RM Length L Ch R = 1 ,30699   ,448,448,448
BEGIN DESCRIPTION:
REEH CREEK 63.0
END DESCRIPTION:
XS GIS Cut Line= 3
      2040375.01     13936825.02        2040125.       13936525.
      2039213.26     13936318.34
#Sta/Elev= 30
  4605.1 1808.87  4608.4 1808.87  4612.3  1804.9  4633.1 1799.77  4676.1 1784.42
  4704.7 1770.74  4739.8 1760.01  4768.5    1746  4782.8  1740.6  4811.4 1733.27
  4825.8 1725.58  4846.6 1719.91  4910.4 1707.81  4941.3  1705.2  5017.8 1698.71
    5018 1698.21  5021.8 1698.71  5062.9 1701.07  5154.3 1701.96  5245.6 1707.54
  5590.3 1733.67  5697.4 1750.99  5703.1 1753.85  5745.7 1764.51  5788.8 1772.65
  5826.2  1782.9  5831.9 1785.79  5923.3 1802.86  5927.1 1805.58  5930.5 1805.58
#Mann= 4 ,-1 , 0
  4605.1     .12       0  4941.3     .07       0  5017.8     .05       0
  5021.8     .07       0
Bank Sta=5017.8,5021.8
XS Rating Curve= 0 ,0
Exp/Cntr=0.3,0.1

Type RM Length L Ch R = 1 ,30251   ,479,479,479
BEGIN DESCRIPTION:
REEH CREEK 62.0
END DESCRIPTION:
XS GIS Cut Line= 3
      2040768.77     13936415.54        2040175.       13936125.
      2039470.18     13935363.45
#Sta/Elev= 30
  4338.8 1827.27  4378.1 1820.01    4440 1800.57  4513.1 1785.62  4570.5 1769.37
  4721.5 1730.24  4827.1 1713.14    4844 1710.23  4866.2 1698.66  4895.8 1693.19
  5004.9 1689.85  5005.2 1689.35  5008.9 1689.85  5019.2  1690.1  5134.5 1692.72
    5250 1700.33    5304  1707.4  5360.7 1719.89  5417.4 1737.22  5537.6 1765.41
  5608.5 1788.77  5728.7 1809.52  5757.1 1819.68  5856.3 1833.23  5905.6 1833.29
  5919.8 1838.18  5969.1 1834.76  5990.6 1837.32  6011.6 1833.24  6037.5 1834.98
#Mann= 7 ,-1 , 0
  4338.8     .12       0  4570.5     .07       0  4827.1     .12       0
  5004.9     .05       0  5008.9     .12       0  5019.2     .07       0
    5250     .12       0
Bank Sta=5004.9,5008.9
XS Rating Curve= 0 ,0
Exp/Cntr=0.3,0.1

Type RM Length L Ch R = 1 ,29772   ,474,474,474
BEGIN DESCRIPTION:
REEH CREEK 61.0
END DESCRIPTION:
XS GIS Cut Line= 3
      2040574.99     13935974.99        2040275.       13935675.
        2039975.       13935475.
#Sta/Elev= 30
  4580.5 1717.65  4665.3  1705.6    4736 1693.76  4778.5 1688.05  4820.9 1684.45
  4852.6 1684.19  4905.8 1683.68  4969.4 1684.59  4999.2    1683  4999.5  1682.5
  5003.2    1683  5007.8    1683  5018.3 1685.47  5056.6 1696.76  5120.4 1714.57
    5140 1718.85  5156.5 1725.28  5177.5 1730.82  5192.5 1737.83  5213.6 1744.21
  5219.1 1747.05  5228.6 1751.48  5249.6 1758.92  5264.6 1766.56  5285.7 1773.39
  5300.7  1782.4  5342.8 1797.72  5357.4 1801.78  5362.3 1805.29  5365.3 1805.29
#Mann= 7 ,-1 , 0
  4580.5     .07       0  4852.6     .12       0  4999.2     .05       0
  5003.2     .12       0  5056.6     .07       0  5219.1     .12       0
  5357.4     .07       0
Bank Sta=4999.2,5003.2
XS Rating Curve= 0 ,0
Exp/Cntr=0.3,0.1

Type RM Length L Ch R = 1 ,29298   ,431,431,431
BEGIN DESCRIPTION:
REEH CREEK 60.0
END DESCRIPTION:
XS GIS Cut Line= 3
      2040924.99     13935774.99        2040675.       13935475.
      2040241.04     13934946.81
#Sta/Elev= 30
  4609.5 1721.39  4694.8 1704.59  4815.8 1688.44  4833.9 1687.03  4943.4 1674.39
  4965.4  1669.3  4984.3 1667.52  4984.6 1667.02  4988.3 1667.52  5013.6  1673.6
  5096.2 1677.14  5108.3 1677.93  5177.9 1684.04  5325.3 1711.95  5385.3 1721.91
  5433.4 1729.33  5447.7  1734.7  5488.1 1739.52  5540.3 1750.47  5546.8 1749.22
  5575.5 1754.04  5589.8 1759.63  5610.6 1760.53  5618.5  1763.9    5625 1762.27
  5632.8 1765.28  5639.3 1763.72  5653.7 1769.89  5660.1 1767.91  5683.6 1772.25
#Mann= 11 ,-1 , 0
  4609.5     .07       0  4815.8    .035       0  4833.9     .12       0
  4965.4     .07       0  4984.3     .05       0  4988.3     .07       0
  5096.2     .12       0  5108.3     .07       0  5325.3     .12       0
  5385.3     .07       0  5488.1     .12       0
Bank Sta=4984.3,4988.3
XS Rating Curve= 0 ,0
Exp/Cntr=0.3,0.1

Type RM Length L Ch R = 1 ,28867   ,472,472,472
BEGIN DESCRIPTION:
REEH CREEK 59.0
END DESCRIPTION:
XS GIS Cut Line= 3
       2041143.8     13935578.73        2040825.       13935125.
      2040524.99     13934824.99
#Sta/Elev= 30
  4450.2 1707.52  4482.9 1703.79  4524.2 1697.52  4595.6  1688.6  4631.4 1685.91
  4646.2 1683.55  4667.1 1682.89  4681.9 1679.19  4702.8  1677.6  4717.6 1675.01
  4753.3 1673.23  4768.2 1671.22  4789.1 1670.74  4803.9 1668.84  4823.5 1668.65
  4831.4 1667.96  4968.1 1666.24  5008.3 1664.62    5031 1661.42  5031.3 1660.92
    5035 1661.42  5047.2 1674.01  5061.3  1683.8  5117.7 1703.58    5231 1743.35
  5259.3 1754.04  5315.9 1779.82  5372.4 1798.83  5425.5  1820.6    5429  1820.6
#Mann= 7 ,-1 , 0
  4450.2     .12       0  4482.9     .07       0  4823.5     .12       0
  4831.4     .07       0    5031     .05       0    5035     .07       0
  5117.7     .12       0
Bank Sta=5031,5035
XS Rating Curve= 0 ,0
Exp/Cntr=0.3,0.1

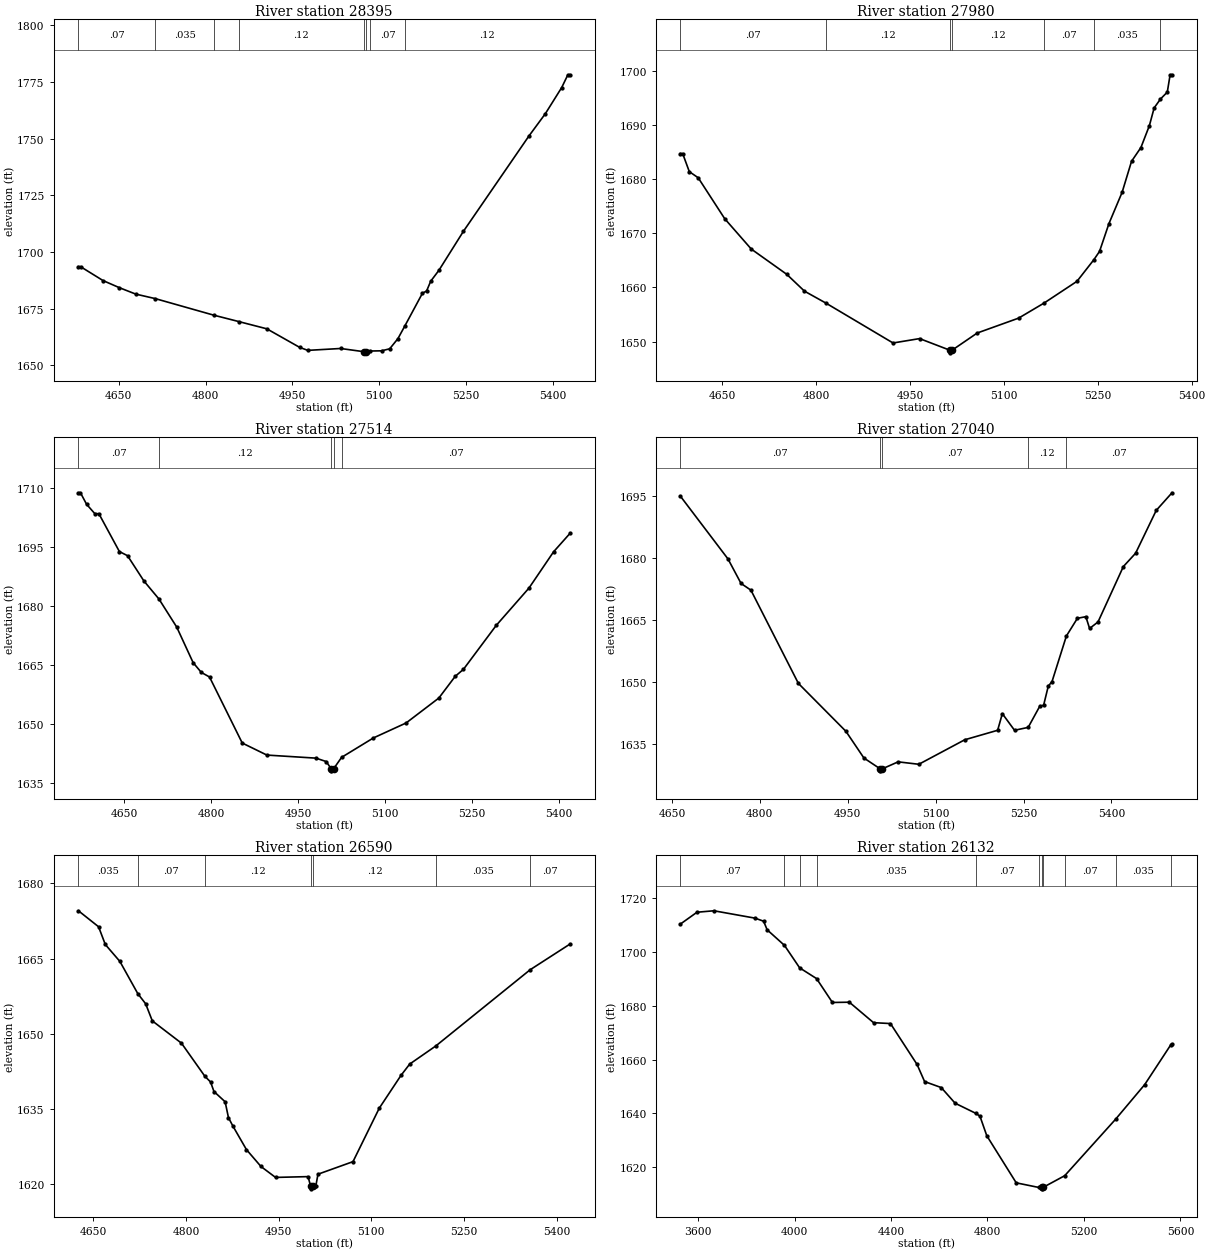
Type RM Length L Ch R = 1 ,28395   ,415,415,415
BEGIN DESCRIPTION:
REEH CREEK 58.0
END DESCRIPTION:
XS GIS Cut Line= 3
      2041475.03     13935125.03        2041175.       13934825.
      2040874.98     13934524.98
#Sta/Elev= 30
  4580.5 1693.52  4584.1 1693.52    4623 1687.37  4651.3 1684.22  4679.5  1681.4
  4713.3  1679.4  4814.2  1672.1  4856.9 1669.31  4905.8 1666.08  4962.4  1657.9
  4976.5 1656.57  5033.1  1657.4  5073.5 1655.98  5073.8 1655.48  5077.5 1655.98
  5084.6 1656.29  5103.8 1656.37  5117.9 1657.26  5132.1 1661.75    5144 1667.32
  5174.5 1681.81  5181.6 1682.77  5188.7 1687.09  5202.8 1691.87  5245.2 1709.12
  5358.4 1751.22  5386.6 1761.01  5414.9 1772.57  5425.5 1778.19  5429.1 1778.19
#Mann= 8 ,-1 , 0
  4580.5     .07       0  4713.3    .035       0  4814.2     .07       0
  4856.9     .12       0  5073.5     .05       0  5077.5     .12       0
  5084.6     .07       0    5144     .12       0
Bank Sta=5073.5,5077.5
XS Rating Curve= 0 ,0
Exp/Cntr=0.3,0.1

Type RM Length L Ch R = 1 ,27980   ,466,466,466
BEGIN DESCRIPTION:
REEH CREEK 57.0
END DESCRIPTION:
XS GIS Cut Line= 3
      2041724.99     13934824.99        2041425.       13934525.
        2041125.       13934325.
#Sta/Elev= 30
  4583.7 1684.73  4587.2 1684.73  4597.8 1681.39    4612 1680.26  4654.4 1672.69
  4696.8 1667.09  4753.4 1662.43  4781.7 1659.32  4815.4 1657.15  4923.1 1649.75
  4965.5 1650.56  5013.5 1648.43  5013.7 1647.93  5017.5 1648.43  5057.5 1651.59
  5123.6 1654.34  5164.2 1657.12  5216.8 1661.14  5243.7 1665.12  5252.8 1666.66
  5267.8 1671.79  5288.9 1677.59  5303.9  1683.3  5318.9 1685.85  5332.4 1689.89
    5340 1693.16  5350.1  1694.8    5361 1696.08  5365.5 1699.28  5368.5 1699.28
#Mann= 7 ,-1 , 0
  4583.7     .07       0  4815.4     .12       0  5013.5     .05       0
  5017.5     .12       0  5164.2     .07       0  5243.7    .035       0
  5350.1     .07       0
Bank Sta=5013.5,5017.5
XS Rating Curve= 0 ,0
Exp/Cntr=0.3,0.1

Type RM Length L Ch R = 1 ,27514   ,474,474,474
BEGIN DESCRIPTION:
REEH CREEK 56.0
END DESCRIPTION:
XS GIS Cut Line= 3
        2042125.       13934625.        2041825.       13934325.
      2041525.02     13934025.02
#Sta/Elev= 30
  4571.1 1708.75  4574.6 1708.75  4585.2 1705.82  4599.4 1703.44  4606.4 1703.43
  4641.8  1693.8  4655.9 1692.74  4684.2  1686.3  4710.1 1681.73  4740.8 1674.58
  4769.1 1665.54  4783.2 1663.06  4797.4 1661.89  4853.9 1645.09  4896.4 1642.03
  4981.2 1641.25  4998.9 1640.38  5007.5 1638.52  5007.8 1638.02  5011.5 1638.52
  5025.4 1641.45  5080.2 1646.38  5136.8  1650.2  5193.3 1656.54  5221.6 1662.07
  5235.8 1663.85  5292.3 1675.01  5348.9 1684.52  5391.3 1693.73  5419.6 1698.41
#Mann= 5 ,-1 , 0
  4571.1     .07       0  4710.1     .12       0  5007.5     .05       0
  5011.5     .12       0  5025.4     .07       0
Bank Sta=5007.5,5011.5
XS Rating Curve= 0 ,0
Exp/Cntr=0.3,0.1

Type RM Length L Ch R = 1 ,27040   ,450,450,450
BEGIN DESCRIPTION:
REEH CREEK 55.0
END DESCRIPTION:
XS GIS Cut Line= 3
      2042374.99     13934424.98        2042225.       13934125.
      2041911.16     13933731.52
#Sta/Elev= 30
  4664.6    1695  4745.6 1679.83    4768 1673.87  4784.8 1672.25  4865.8 1649.65
  4946.9 1638.04  4977.6 1631.57  5005.2 1628.96  5005.4 1628.46  5009.2 1628.96
    5036 1630.64  5071.3 1630.05  5149.7 1635.99  5205.8 1638.29  5213.8 1642.32
  5234.6 1638.29  5257.9 1638.99  5277.8 1644.15  5284.2 1644.33  5292.2 1648.99
  5298.6  1650.1  5323.1 1661.14  5341.9 1665.43  5356.3 1665.82  5362.7 1662.96
  5377.1 1664.55  5420.3 1677.97  5441.2  1681.2  5476.4 1691.58  5503.3 1695.85
#Mann= 5 ,-1 , 0
  4664.6     .07       0  5005.2     .05       0  5009.2     .07       0
  5257.9     .12       0  5323.1     .07       0
Bank Sta=5005.2,5009.2
XS Rating Curve= 0 ,0
Exp/Cntr=0.3,0.1

Type RM Length L Ch R = 1 ,26590   ,458,458,458
BEGIN DESCRIPTION:
REEH CREEK 54.0
END DESCRIPTION:
XS GIS Cut Line= 3
      2042724.99     13934274.97        2042575.       13933925.
      2042272.26     13933641.23
#Sta/Elev= 30
  4625.8 1674.54  4658.4 1671.35  4669.3 1667.81  4692.9 1664.43    4722 1657.98
  4734.6 1655.98  4745.4 1652.56  4792.6 1648.11  4830.5  1641.5  4839.7 1640.36
  4845.2 1638.46  4863.3 1636.41  4868.7 1633.23    4876 1631.53  4897.8 1626.86
  4921.3 1623.49  4944.9 1621.31  4997.5 1621.47  5001.8 1619.53  5002.1 1619.03
  5005.8 1619.53    5010 1619.53  5013.6 1621.95  5070.3 1624.46  5112.8 1635.13
    5148 1641.68  5162.1 1643.94  5204.3 1647.55    5357 1662.76  5421.5 1667.89
#Mann= 7 ,-1 , 0
  4625.8    .035       0    4722     .07       0  4830.5     .12       0
  5001.8     .05       0  5005.8     .12       0  5204.3    .035       0
    5357     .07       0
Bank Sta=5001.8,5005.8
XS Rating Curve= 0 ,0
Exp/Cntr=0.3,0.1

Type RM Length L Ch R = 1 ,26132   ,463,463,463
BEGIN DESCRIPTION:
REEH CREEK 53.0
END DESCRIPTION:
XS GIS Cut Line= 3
      2042813.95      13935193.3        2042925.       13933725.
      2042524.98     13933324.98
#Sta/Elev= 30
    3527 1710.44  3595.5 1714.82  3665.7 1715.36  3836.2 1712.62  3871.8 1711.48
  3886.3  1708.3  3958.2  1702.5  4021.2 1694.14  4091.3 1690.15  4157.1 1681.27
  4227.3 1681.37  4327.6 1673.76  4397.8 1673.43  4508.1 1658.22  4539.3 1651.86
  4608.4 1649.63  4665.8 1643.82  4750.5  1640.1  4768.8 1639.01  4797.2 1631.72
  4919.3 1614.21  5013.1 1612.49  5025.8 1612.48    5026 1611.98  5029.8 1612.48
  5120.4 1616.87  5331.2 1637.85    5452 1650.73  5560.1 1665.51  5565.2  1665.8
#Mann= 11 ,-1 , 0
    3527     .07       0  3958.2    .035       0  4021.2     .07       0
  4091.3    .035       0  4750.5     .07       0  5013.1     .12       0
  5025.8     .05       0  5029.8     .12       0  5120.4     .07       0
  5331.2    .035       0  5560.1     .07       0
Bank Sta=5025.8,5029.8
XS Rating Curve= 0 ,0
Exp/Cntr=0.3,0.1

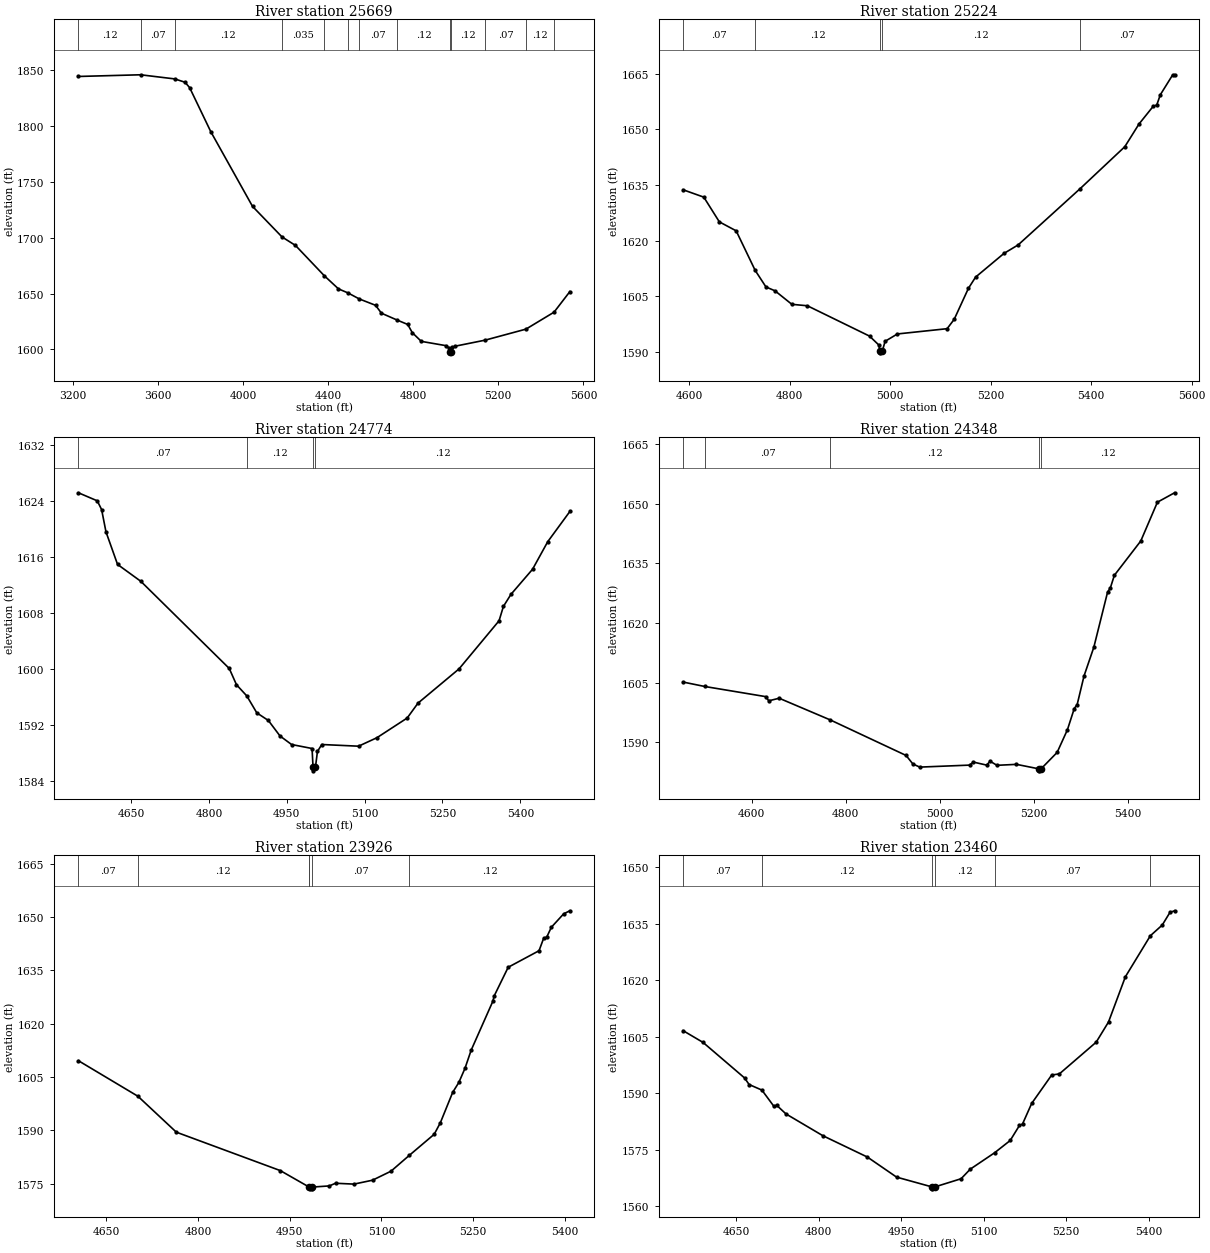
Type RM Length L Ch R = 1 ,25669   ,445,445,445
BEGIN DESCRIPTION:
REEH CREEK 52.0
END DESCRIPTION:
XS GIS Cut Line= 3
      2044247.96     13935064.84        2043275.       13933575.
        2042925.     13933175.01
#Sta/Elev= 30
  3225.6 1844.13  3517.9 1845.64  3678.8 1841.93    3727 1838.95  3748.6 1834.12
  3848.1  1794.7  4044.2 1727.95  4182.9 1700.61  4246.3    1693  4381.6 1665.94
  4448.4 1654.15  4492.9 1650.56  4546.2 1645.16  4622.8 1639.46  4650.5 1632.39
    4725  1626.2  4774.2 1622.32  4795.3 1615.04  4837.8 1607.21  4955.3 1603.33
  4969.2  1601.1  4974.1 1597.45  4974.4 1596.95  4978.6 1597.45  4982.3 1601.74
  4997.4 1602.91  5138.3 1608.31  5329.9 1618.15  5462.1 1633.32  5536.5 1651.74
#Mann= 13 ,-1 , 0
  3225.6     .12       0  3517.9     .07       0  3678.8     .12       0
  4182.9    .035       0  4381.6     .07       0  4492.9     .12       0
  4546.2     .07       0    4725     .12       0  4974.1     .05       0
  4978.6     .12       0  5138.3     .07       0  5329.9     .12       0
  5462.1     .07       0
Bank Sta=4974.1,4978.6
XS Rating Curve= 0 ,0
Exp/Cntr=0.3,0.1

Type RM Length L Ch R = 1 ,25224   ,450,450,450
BEGIN DESCRIPTION:
REEH CREEK 51.0
END DESCRIPTION:
XS GIS Cut Line= 3
      2043674.99     13933674.96        2043575.       13933275.
      2043174.97     13932874.97
#Sta/Elev= 30
    4588 1633.74  4629.2 1631.75  4660.1 1625.09  4693.6 1622.67  4731.4 1612.01
  4752.9 1607.54  4770.9  1606.5  4804.4 1602.86  4835.3 1602.47    4959 1594.29
  4977.1 1591.94    4980 1590.28  4980.3 1589.78  4984.5 1590.28    4990 1592.89
  5014.4 1594.87  5113.4 1596.29  5127.5 1598.82  5155.8 1607.17    5170 1610.19
  5226.5 1616.58  5254.8 1618.88  5378.2 1634.05    5467 1645.35  5495.2 1651.46
  5523.5 1656.24  5530.6 1656.59  5537.7 1659.36  5562.4 1664.74    5566 1664.74
#Mann= 5 ,-1 , 0
    4588     .07       0  4731.4     .12       0    4980     .05       0
  4984.5     .12       0  5378.2     .07       0
Bank Sta=4980,4984.5
XS Rating Curve= 0 ,0
Exp/Cntr=0.3,0.1

Type RM Length L Ch R = 1 ,24774   ,426,426,426
BEGIN DESCRIPTION:
REEH CREEK 50.0
END DESCRIPTION:
XS GIS Cut Line= 3
      2044124.99     13933424.97        2043925.       13933025.
      2043524.99     13932724.99
#Sta/Elev= 30
  4548.3 1625.13  4584.6 1623.98    4593 1622.73  4601.4 1619.55  4623.7  1614.9
  4668.5 1612.49    4839 1600.04  4852.9 1597.72  4872.8 1596.12  4892.1  1593.7
  4914.4 1592.61  4936.8  1590.4  4959.1 1589.18  4998.6 1588.61  5000.5 1585.92
  5000.8 1585.42  5005.1 1585.92    5009 1588.19  5017.4 1589.18  5088.2 1588.94
  5123.6 1590.15  5181.9 1592.96  5202.8 1595.09  5281.9 1599.98    5359 1606.85
  5367.4  1608.9  5381.9 1610.62  5423.6 1614.21  5452.8 1618.14  5495.5 1622.46
#Mann= 4 ,-1 , 0
  4548.3     .07       0  4872.8     .12       0  5000.5     .05       0
  5005.1     .12       0
Bank Sta=5000.5,5005.1
XS Rating Curve= 0 ,0
Exp/Cntr=0.3,0.1

Type RM Length L Ch R = 1 ,24348   ,422,422,422
BEGIN DESCRIPTION:
REEH CREEK 49.0
END DESCRIPTION:
XS GIS Cut Line= 3
      2044459.81     13933106.56        2044125.       13932675.
        2043725.       13932375.
#Sta/Elev= 30
  4453.8 1605.14  4499.7 1604.03  4629.8 1601.47  4636.1 1600.42  4658.3 1601.07
  4767.5 1595.59  4928.5 1586.67    4943 1584.52  4957.5 1583.74  5063.5 1584.24
  5071.9    1585    5100 1584.24  5107.3 1585.22  5121.9 1584.19  5163.5 1584.43
  5211.2  1583.3  5211.5  1582.8  5215.8  1583.3    5250 1587.43  5271.9 1593.13
  5286.5 1598.48  5292.7 1599.49  5307.3 1606.68  5328.1 1613.88  5357.3 1627.71
  5363.5  1628.9  5371.9 1632.01  5428.1 1640.64  5463.5  1650.4    5500 1652.77
#Mann= 5 ,-1 , 0
  4453.8     .12       0  4499.7     .07       0  4767.5     .12       0
  5211.2     .05       0  5215.8     .12       0
Bank Sta=5211.2,5215.8
XS Rating Curve= 0 ,0
Exp/Cntr=0.3,0.1

Type RM Length L Ch R = 1 ,23926   ,466,466,466
BEGIN DESCRIPTION:
REEH CREEK 48.0
END DESCRIPTION:
XS GIS Cut Line= 3
      2044574.95       13932325.        2044175.       13932325.
      2043774.96       13932275.
#Sta/Elev= 30
  4604.8 1609.61    4702 1599.62  4764.8 1589.52  4934.8 1578.71  4981.3 1574.14
  4982.4 1574.09  4982.8 1573.59  4986.8 1573.59  4987.1 1574.09  5014.8 1574.41
  5024.9 1575.16  5055.1 1574.92  5085.4 1576.02  5115.6 1578.55  5145.5    1583
  5186.2 1588.93  5196.2 1592.15  5216.4 1600.71  5226.5 1603.51  5236.5 1607.47
  5246.6 1612.57  5281.9 1626.27  5284.4 1627.89  5307.1 1635.88  5357.5 1640.53
    5365 1644.01  5370.1 1644.36  5377.6 1647.12  5397.8 1650.91  5407.9 1651.76
#Mann= 6 ,-1 , 0
  4604.8     .07       0    4702     .12       0  4981.3     .07       0
  4982.4     .05       0  4987.1     .07       0  5145.5     .12       0
Bank Sta=4982.4,4987.1
XS Rating Curve= 0 ,0
Exp/Cntr=0.3,0.1

Type RM Length L Ch R = 1 ,23460   ,485,485,485
BEGIN DESCRIPTION:
REEH CREEK 47.0
END DESCRIPTION:
XS GIS Cut Line= 3
      2044624.96     13932074.98        2044225.       13931875.
      2043824.99     13932075.01
#Sta/Elev= 30
    4553 1606.57  4589.3 1603.45  4664.8 1594.03  4673.1 1592.28  4696.4  1590.8
  4717.9 1586.56  4723.5 1586.74  4740.2 1584.48  4807.3  1578.7  4888.4 1573.03
  4941.5 1567.71  5006.2  1565.1  5006.6  1564.6  5010.9  1565.1  5058.9 1567.28
  5075.6 1569.82    5120 1574.18  5148.3 1577.43  5165.1 1581.41  5170.7  1581.8
  5187.4 1587.27  5223.8  1594.8  5237.8  1595.1  5304.8 1603.52  5327.2 1608.87
  5357.9 1620.87  5403.4 1631.76    5425 1634.59    5439 1637.94  5447.4 1638.38
#Mann= 6 ,-1 , 0
    4553     .07       0  4696.4     .12       0  5006.2     .05       0
  5010.9     .12       0    5120     .07       0  5403.4     .12       0
Bank Sta=5006.2,5010.9
XS Rating Curve= 0 ,0
Exp/Cntr=0.3,0.1

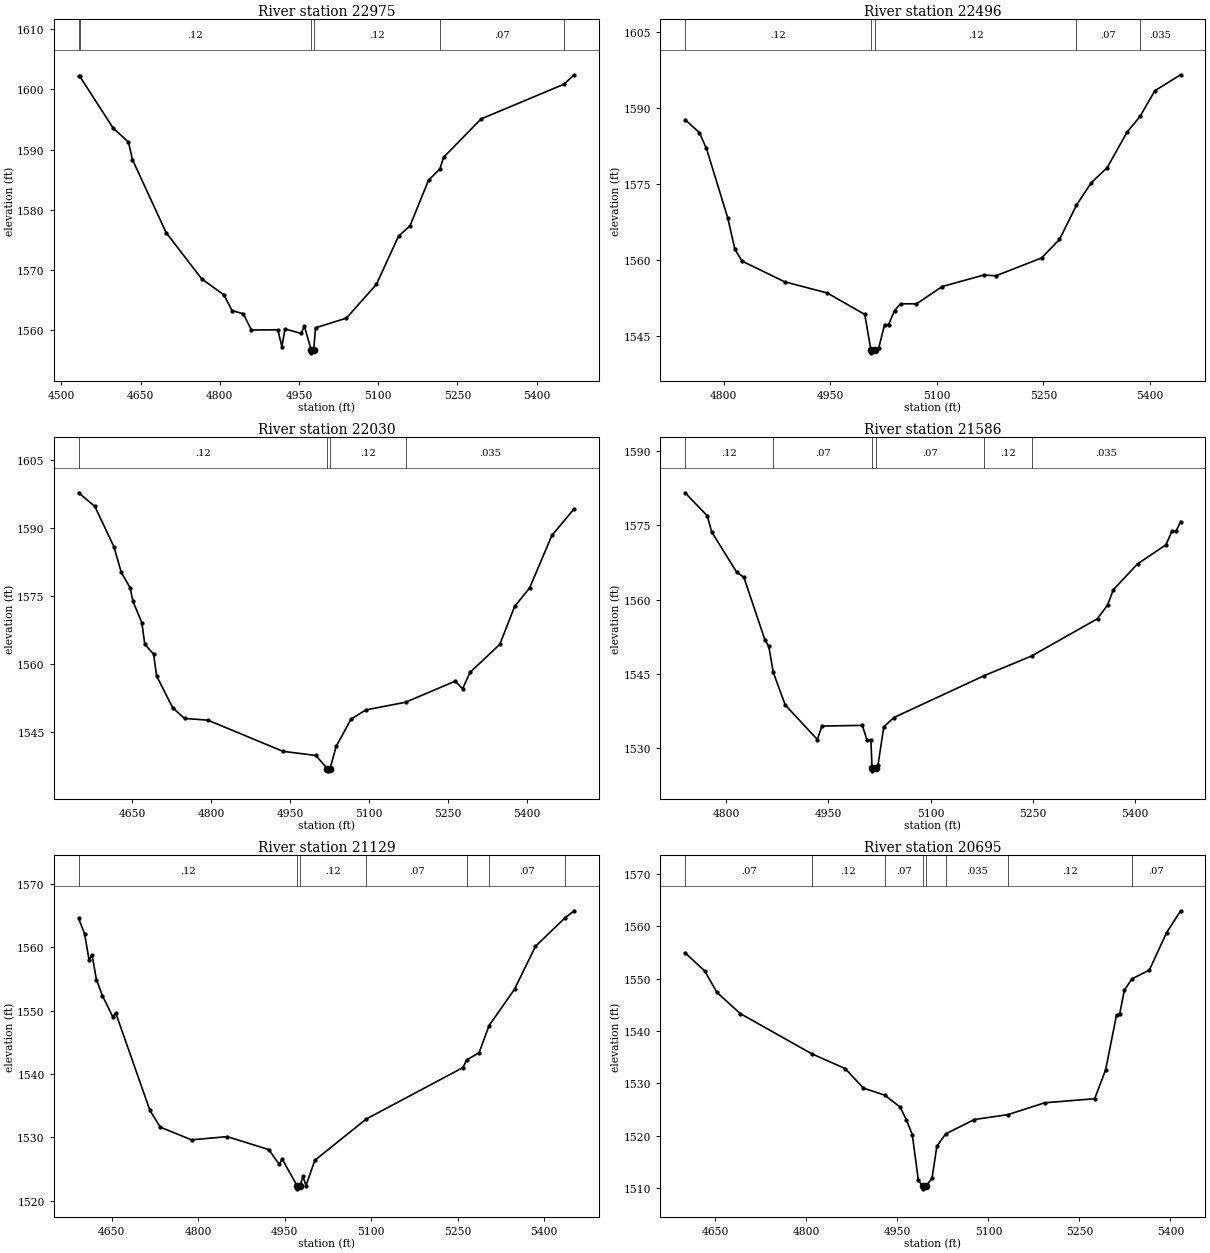
Type RM Length L Ch R = 1 ,22975   ,479,479,479
BEGIN DESCRIPTION:
REEH CREEK 46.0
END DESCRIPTION:
XS GIS Cut Line= 3
      2044524.99     13931175.01        2044125.       13931425.
      2043813.94     13931773.21
#Sta/Elev= 30
  4532.5 1602.16  4534.5 1602.16  4597.9 1593.55  4626.8 1591.24  4634.5 1588.32
  4698.2 1576.22  4765.4 1568.56  4807.8 1565.87  4823.2 1563.27  4844.4 1562.75
  4859.7 1560.06  4909.8 1560.09  4917.5  1557.3  4923.4 1560.24  4954.1 1559.48
    4960 1560.72  4972.9 1556.77  4973.2 1556.27  4977.7 1556.77  4981.2 1560.42
  5039.7 1562.03  5096.5 1567.63  5138.4 1575.62  5160.1 1577.34  5195.2 1584.89
  5216.9  1586.8  5223.6 1588.69  5294.7 1595.07  5451.6 1600.83  5471.1  1602.4
#Mann= 6 ,-1 , 0
  4532.5     .07       0  4534.5     .12       0  4972.9     .05       0
  4977.7     .12       0  5216.9     .07       0  5451.6     .12       0
Bank Sta=4972.9,4977.7
XS Rating Curve= 0 ,0
Exp/Cntr=0.3,0.1

Type RM Length L Ch R = 1 ,22496   ,466,466,466
BEGIN DESCRIPTION:
REEH CREEK 45.0
END DESCRIPTION:
XS GIS Cut Line= 3
        2044375.       13930975.        2044125.       13930975.
      2043725.01     13931174.99
#Sta/Elev= 30
  4745.8 1587.74  4765.8 1585.18  4775.8 1582.04  4805.8  1568.3  4815.8 1562.11
  4825.8 1559.74  4885.8 1555.64  4945.8 1553.42  4998.6 1549.17  5007.3 1542.07
  5007.7 1541.57  5012.3 1542.07  5018.2 1542.53  5026.5 1547.14  5032.1 1547.18
  5040.5 1549.92  5048.9 1551.28  5071.3 1551.27  5107.6  1554.7  5166.3 1556.98
  5183.1 1556.82  5247.4 1560.36  5272.5 1564.01  5296.4 1570.79  5317.2 1575.24
  5339.6 1578.23  5367.5 1585.24  5385.9 1588.38  5406.7 1593.46    5443 1596.62
#Mann= 5 ,-1 , 0
  4745.8     .12       0  5007.3     .05       0  5012.3     .12       0
  5296.4     .07       0  5385.9    .035       0
Bank Sta=5007.3,5012.3
XS Rating Curve= 0 ,0
Exp/Cntr=0.3,0.1

Type RM Length L Ch R = 1 ,22030   ,444,444,444
BEGIN DESCRIPTION:
REEH CREEK 44.0
END DESCRIPTION:
XS GIS Cut Line= 3
      2044325.01     13930374.99        2043925.       13930575.
        2043575.       13930925.
#Sta/Elev= 30
  4547.7  1597.7  4578.5  1594.7  4614.8 1585.81  4628.8 1580.15  4645.5 1576.81
  4651.1 1573.78  4667.9 1569.06  4673.5 1564.33  4690.3 1562.16  4695.9 1557.38
  4726.6 1550.33    4749    1548  4793.7  1547.6  4936.2 1540.75  4998.5 1539.84
  5020.7 1536.95  5021.1 1536.45  5025.7 1536.95  5037.4 1541.82  5065.6 1547.84
  5093.9 1549.87  5169.3 1551.56  5263.6  1556.2  5277.8 1554.53  5291.9 1558.15
  5348.5 1564.31  5376.8 1572.68    5405 1576.71  5447.5 1588.29  5489.9 1594.19
#Mann= 4 ,-1 , 0
  4547.7     .12       0  5020.7     .05       0  5025.7     .12       0
  5169.3    .035       0
Bank Sta=5020.7,5025.7
XS Rating Curve= 0 ,0
Exp/Cntr=0.3,0.1

Type RM Length L Ch R = 1 ,21586   ,457,457,457
BEGIN DESCRIPTION:
REEH CREEK 43.0
END DESCRIPTION:
XS GIS Cut Line= 3
      2044075.05     13930124.98        2043825.       13930225.
      2043456.34      13930495.4
#Sta/Elev= 30
  4740.1 1581.57  4772.5 1576.94  4779.2 1573.64  4815.5 1565.58  4826.3 1564.48
  4857.3 1551.78  4862.7 1550.58  4869.4 1545.28  4886.9  1538.7    4934 1531.73
  4940.7 1534.45    5000 1534.58  5006.7 1531.63  5012.5 1531.63  5014.2  1525.9
  5014.6  1525.4  5019.3  1525.9  5022.9 1526.57  5031.4 1534.27    5046 1536.15
  5178.6 1544.63  5248.1  1548.6  5344.8 1556.14  5359.4 1558.89  5367.9 1561.98
  5403.4  1567.2  5445.1 1571.06  5453.6 1573.76  5459.8 1573.81  5466.6 1575.75
#Mann= 6 ,-1 , 0
  4740.1     .12       0  4869.4     .07       0  5014.2     .05       0
  5019.3     .07       0  5178.6     .12       0  5248.1    .035       0
Bank Sta=5014.2,5019.3
XS Rating Curve= 0 ,0
Exp/Cntr=0.3,0.1

Type RM Length L Ch R = 1 ,21129   ,434,434,434
BEGIN DESCRIPTION:
REEH CREEK 42.0
END DESCRIPTION:
XS GIS Cut Line= 3
      2043974.99       13929975.        2043575.       13929875.
        2043375.     13930274.99
#Sta/Elev= 30
  4592.5 1564.58  4602.8 1562.15  4610.5 1558.07  4615.7 1558.83  4623.4  1554.9
  4633.7 1552.38  4651.8 1549.02  4656.9 1549.62  4716.2 1534.23  4734.2 1531.59
  4788.3 1529.59  4850.2  1530.1  4922.3 1528.05  4940.4 1525.72  4945.5 1526.56
  4971.3 1522.35  4971.7 1521.85  4976.4 1522.35  4981.6  1523.8  4986.8 1522.37
  5002.2 1526.36  5091.4 1532.88  5259.1 1541.01  5265.5 1542.22  5287.1 1543.35
  5304.3 1547.62  5348.6  1553.4  5384.9 1560.17  5435.9 1564.64    5452 1565.78
#Mann= 7 ,-1 , 0
  4592.5     .12       0  4971.3     .05       0  4976.4     .12       0
  5091.4     .07       0  5265.5     .12       0  5304.3     .07       0
  5435.9    .035       0
Bank Sta=4971.3,4976.4
XS Rating Curve= 0 ,0
Exp/Cntr=0.3,0.1

Type RM Length L Ch R = 1 ,20695   ,468,468,468
BEGIN DESCRIPTION:
REEH CREEK 41.0
END DESCRIPTION:
XS GIS Cut Line= 3
      2043977.17     13929429.44        2043575.       13929475.
      2043174.96     13929575.01
#Sta/Elev= 30
  4599.9 1554.94  4632.3 1551.45  4652.4 1547.38  4690.7 1543.34  4808.9 1535.64
  4863.8 1532.83  4893.9  1529.1  4929.2 1527.74  4954.3 1525.49  4964.8 1523.05
  4974.5 1520.22  4984.5  1511.5  4991.6 1510.36  4992.1 1509.86  4997.6 1510.36
  5007.2 1511.96    5015 1517.98  5029.4 1520.34  5076.8  1523.1  5131.9 1524.02
  5192.8 1526.29  5275.2 1527.07  5293.3 1532.58  5311.3 1543.07  5316.5 1543.27
  5324.2 1547.79  5336.7 1549.96  5365.4 1551.64  5393.8 1558.78    5417 1562.96
#Mann= 8 ,-1 , 0
  4599.9     .07       0  4808.9     .12       0  4929.2     .07       0
  4991.6     .05       0  4997.6     .07       0  5029.4    .035       0
  5131.9     .12       0  5336.7     .07       0
Bank Sta=4991.6,4997.6
XS Rating Curve= 0 ,0
Exp/Cntr=0.3,0.1