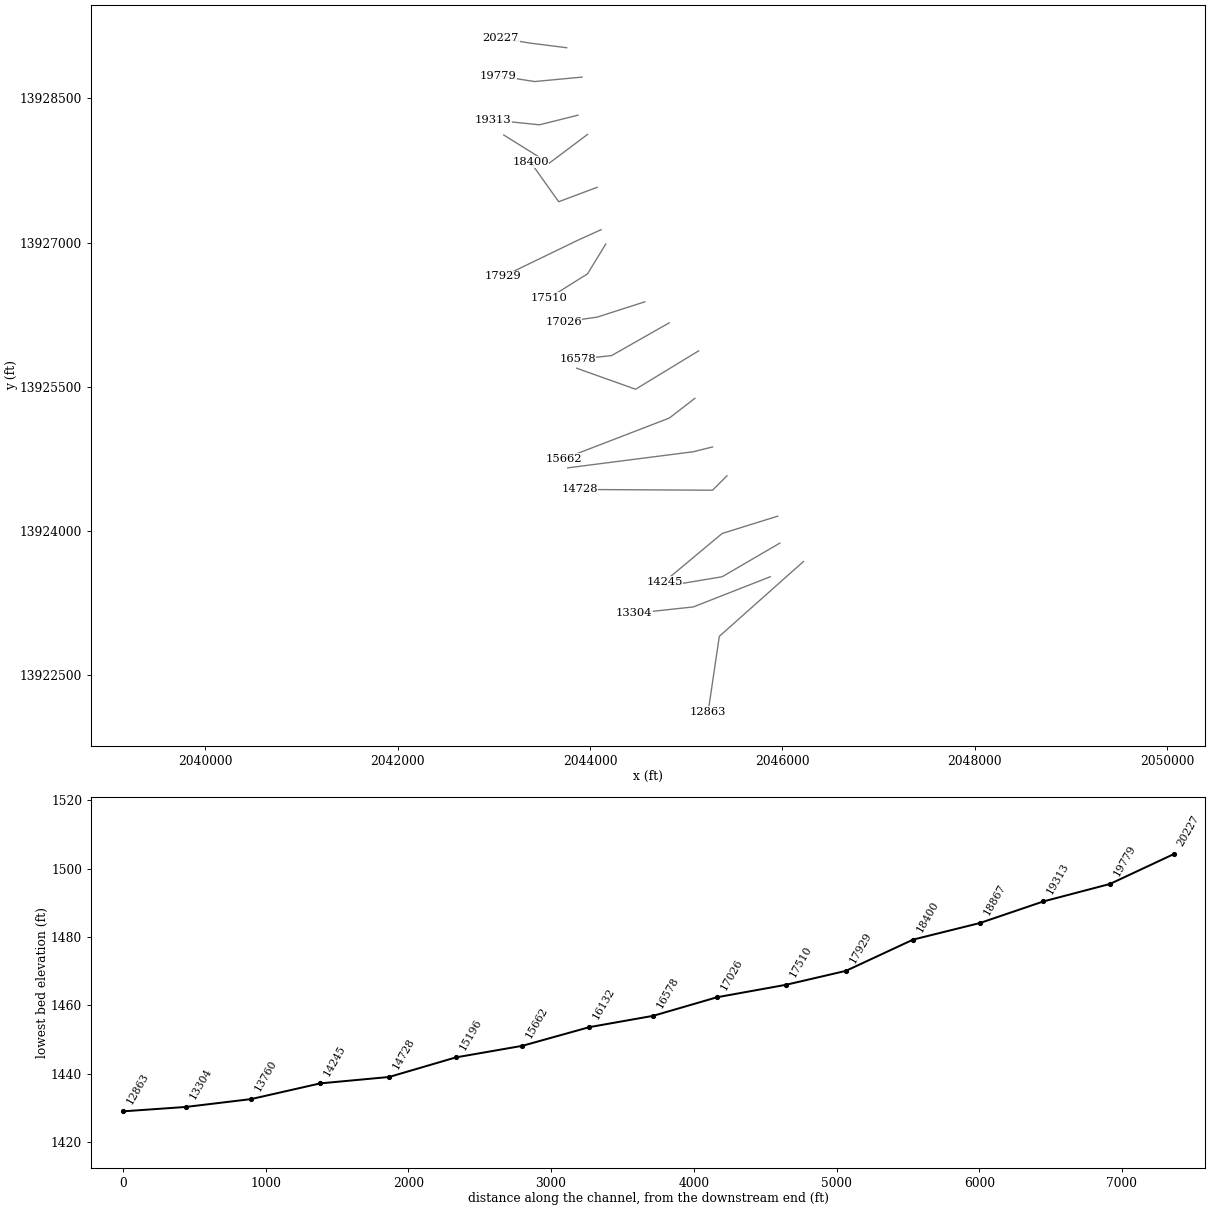
HEC-RAS study REEH CREEK.prj: REEH CREEK Base Level Engineering

--- REEH CREEK.g01 (geometry) --- (continued)

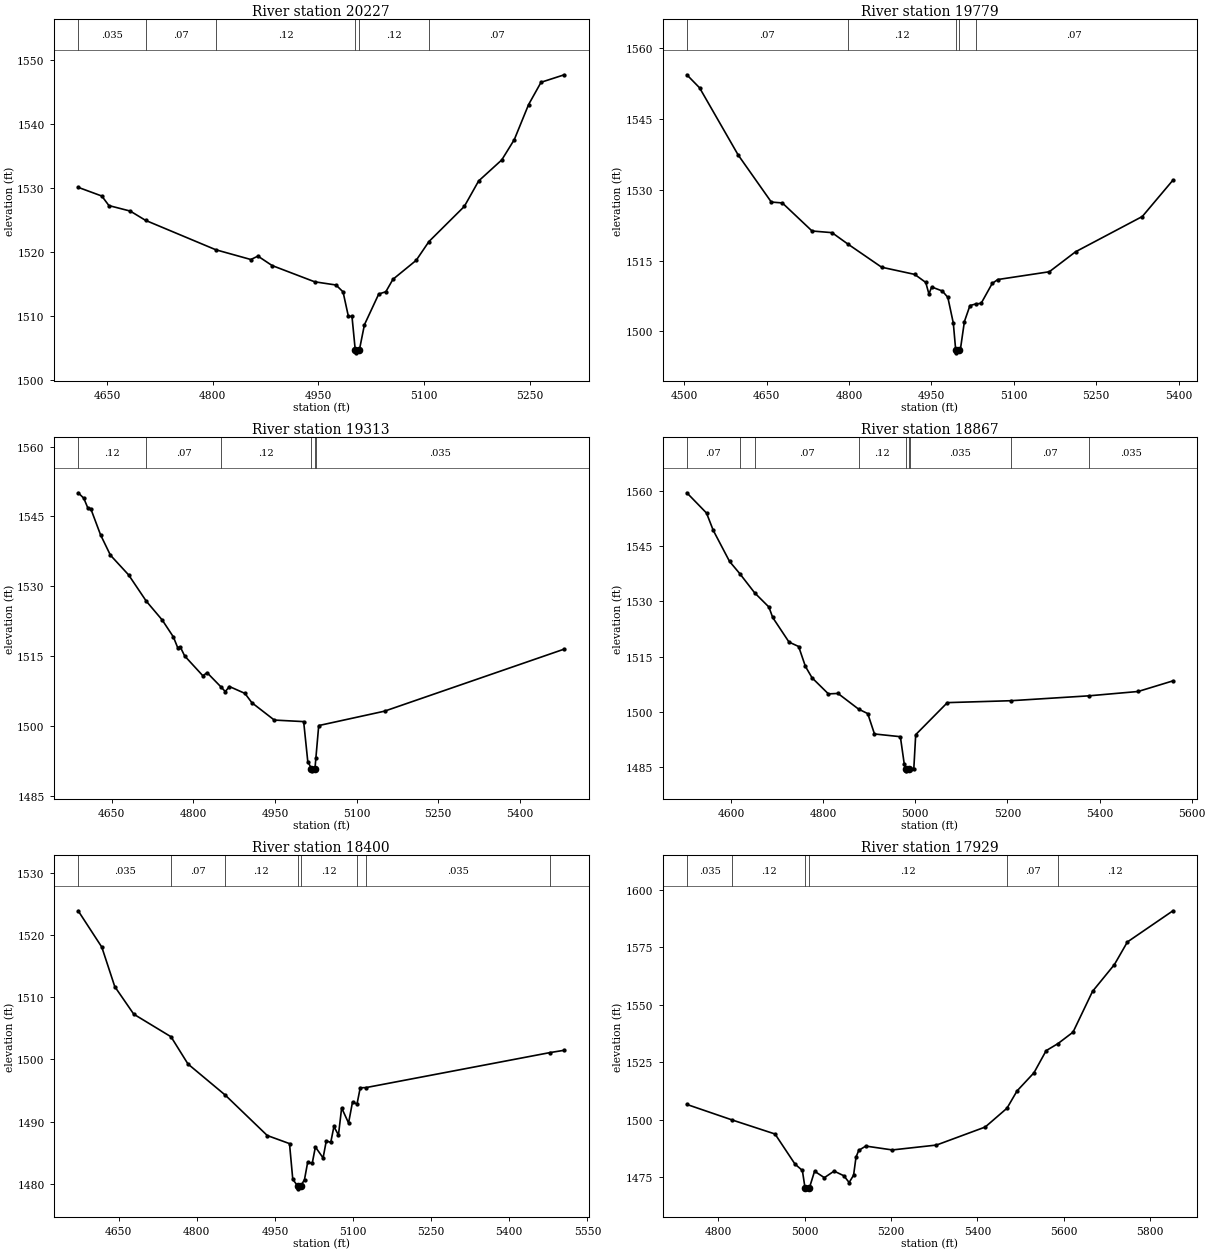
Type RM Length L Ch R = 1 ,20227   ,448,448,448
BEGIN DESCRIPTION:
REEH CREEK 40.0
END DESCRIPTION:
XS GIS Cut Line= 3
      2043758.38     13929026.67        2043375.       13929075.
      2043074.96     13929125.01
#Sta/Elev= 30
  4608.8 1530.07  4642.4 1528.71  4652.5 1527.22  4682.8 1526.36  4704.6 1524.91
  4804.4 1520.32  4854.1  1518.8  4864.2 1519.33  4884.3 1517.86  4944.8 1515.32
  4975.1 1514.82  4985.1 1513.75  4992.7 1509.92  4997.8 1509.92  5002.4 1504.73
  5002.9 1504.23  5008.4 1504.73  5015.5 1508.62  5035.8 1513.41  5045.9 1513.77
    5056 1515.71    5089 1518.67  5107.1  1521.6  5157.4 1527.09  5177.7 1531.06
  5210.6 1534.35  5228.4 1537.52  5248.7 1542.99  5266.4 1546.47  5299.4 1547.64
#Mann= 6 ,-1 , 0
  4608.8    .035       0  4704.6     .07       0  4804.4     .12       0
  5002.4     .05       0  5008.4     .12       0  5107.1     .07       0
Bank Sta=5002.4,5008.4
XS Rating Curve= 0 ,0
Exp/Cntr=0.3,0.1

Type RM Length L Ch R = 1 ,19779   ,466,466,466
BEGIN DESCRIPTION:
REEH CREEK 39.0
END DESCRIPTION:
XS GIS Cut Line= 3
      2043918.14     13928721.11        2043425.       13928675.
      2043039.83     13928734.97
#Sta/Elev= 30
  4504.8 1554.36    4528  1551.6  4598.3 1537.37  4658.6 1527.41  4678.7 1527.22
  4732.8 1521.28  4769.1 1520.93  4797.5 1518.56  4859.5 1513.61  4919.7 1512.09
  4939.8 1510.39  4945.6 1507.94  4950.6 1509.43    4970 1508.57    4980 1507.23
    4990 1501.77  4994.4 1495.98  4994.9 1495.48  5000.7 1495.98  5002.6 1495.98
  5010.2 1502.11  5020.3 1505.49  5031.1 1505.84  5040.6 1505.95  5060.8 1510.17
  5070.9    1511  5164.8 1512.65  5212.6 1516.88  5334.1 1524.35  5389.9 1532.05
#Mann= 5 ,-1 , 0
  4504.8     .07       0  4797.5     .12       0  4994.4     .05       0
  5000.7     .12       0  5031.1     .07       0
Bank Sta=4994.4,5000.7
XS Rating Curve= 0 ,0
Exp/Cntr=0.3,0.1

Type RM Length L Ch R = 1 ,19313   ,446,446,446
BEGIN DESCRIPTION:
REEH CREEK 38.0
END DESCRIPTION:
XS GIS Cut Line= 3
      2043875.01       13928325.        2043475.       13928225.
      2042995.65     13928274.32
#Sta/Elev= 30
    4588 1550.07  4598.3 1548.91    4606 1546.75  4611.2 1546.65  4629.2 1541.04
  4647.3 1536.68  4680.8 1532.44  4713.3  1526.8  4742.6 1522.76  4763.2 1519.11
    4771 1516.84  4776.1  1516.9  4783.9 1515.04  4817.4 1510.78  4825.1 1511.45
  4850.6  1508.4  4858.6 1507.39  4866.3 1508.47  4894.7    1507  4907.6 1504.99
  4948.8 1501.27  5002.8 1500.94  5010.4 1492.34  5017.2 1490.87  5017.7 1490.37
  5023.6 1490.87  5025.3 1493.14  5030.5 1500.09  5151.5 1503.18  5482.2 1516.51
#Mann= 6 ,-1 , 0
    4588     .12       0  4713.3     .07       0  4850.6     .12       0
  5017.2     .05       0  5023.6     .12       0  5025.3    .035       0
Bank Sta=5017.2,5023.6
XS Rating Curve= 0 ,0
Exp/Cntr=0.3,0.1

Type RM Length L Ch R = 1 ,18867   ,467,467,467
BEGIN DESCRIPTION:
REEH CREEK 37.0
END DESCRIPTION:
XS GIS Cut Line= 3
      2043974.97     13928124.98        2043575.       13927825.
      2043103.84     13928118.76
#Sta/Elev= 30
  4504.2 1559.45  4546.9 1553.96  4561.5 1549.27  4596.9 1540.84    4619 1537.54
  4651.6 1532.29  4682.3 1528.47  4690.6 1525.63    4726 1518.96  4746.9 1517.76
  4761.5 1512.39    4776 1509.27  4811.5 1504.91  4832.3 1505.03  4876.9 1500.79
  4896.9 1499.56  4911.5 1494.04  4967.7  1493.3    4976 1486.01  4979.1 1484.54
  4979.6 1484.04  4985.5 1484.54  4987.7 1484.62  4996.9 1484.63    5001 1493.85
  5069.7 1502.54    5208 1503.06  5376.6 1504.38  5483.8 1505.56  5559.4 1508.44
#Mann= 9 ,-1 , 0
  4504.2     .07       0    4619     .12       0  4651.6     .07       0
  4876.9     .12       0  4979.1    .035       0  4985.5     .12       0
  4987.7    .035       0    5208     .07       0  5376.6    .035       0
Bank Sta=4979.1,4985.5
XS Rating Curve= 0 ,0
Exp/Cntr=0.3,0.1

Type RM Length L Ch R = 1 ,18400   ,471,471,471
BEGIN DESCRIPTION:
REEH CREEK 36.0
END DESCRIPTION:
XS GIS Cut Line= 3
      2044075.01       13927575.        2043675.       13927425.
      2043381.66     13927837.53
#Sta/Elev= 30
  4572.2 1523.89  4617.6 1518.05  4642.5  1511.7    4679 1507.27  4750.5 1503.64
  4783.1 1499.26  4854.6 1494.27  4935.3 1487.77    4978 1486.47  4984.3 1480.71
  4993.5  1479.7    4994  1479.2    5000  1479.7  5006.8  1480.7  5012.9 1483.48
  5021.6 1483.29  5027.7 1485.93  5042.5 1484.17  5048.6  1486.9  5057.2 1486.67
  5063.3 1489.22    5072 1487.84  5078.1 1492.21  5091.4 1489.78    5099 1493.16
  5107.6 1492.82  5113.8 1495.44  5124.7 1495.47  5478.9 1501.11  5505.6 1501.47
#Mann= 8 ,-1 , 0
  4572.2    .035       0  4750.5     .07       0  4854.6     .12       0
  4993.5     .05       0    5000     .12       0  5107.6     .07       0
  5124.7    .035       0  5478.9     .07       0
Bank Sta=4993.5,5000
XS Rating Curve= 0 ,0
Exp/Cntr=0.3,0.1

Type RM Length L Ch R = 1 ,17929   ,419,419,419
BEGIN DESCRIPTION:
REEH CREEK 35.0
END DESCRIPTION:
XS GIS Cut Line= 3
      2044116.05     13927134.31        2043875.       13927025.
      2043100.04     13926650.02
#Sta/Elev= 30
  4727.3  1506.7    4833 1499.91  4931.5 1493.86  4977.7 1480.81  4994.8 1478.03
  5000.9 1470.55  5001.4 1470.05  5011.2 1470.55  5023.1  1477.7  5045.7  1474.9
  5068.3 1477.75  5090.9 1475.72  5103.1  1472.8  5113.4 1475.97    5119 1483.79
  5125.3 1486.73  5141.6 1488.62  5203.1 1486.94  5305.3 1489.06  5418.2 1496.89
  5468.6 1505.06  5491.9 1512.57  5531.1 1520.45  5559.3 1530.06  5586.5  1533.1
  5621.5 1538.08  5666.7  1555.8  5717.4 1567.45  5747.4 1577.25  5852.9 1590.79
#Mann= 6 ,-1 , 0
  4727.3    .035       0    4833     .12       0  5000.9     .05       0
  5011.2     .12       0  5468.6     .07       0  5586.5     .12       0
Bank Sta=5000.9,5011.2
XS Rating Curve= 0 ,0
Exp/Cntr=0.3,0.1

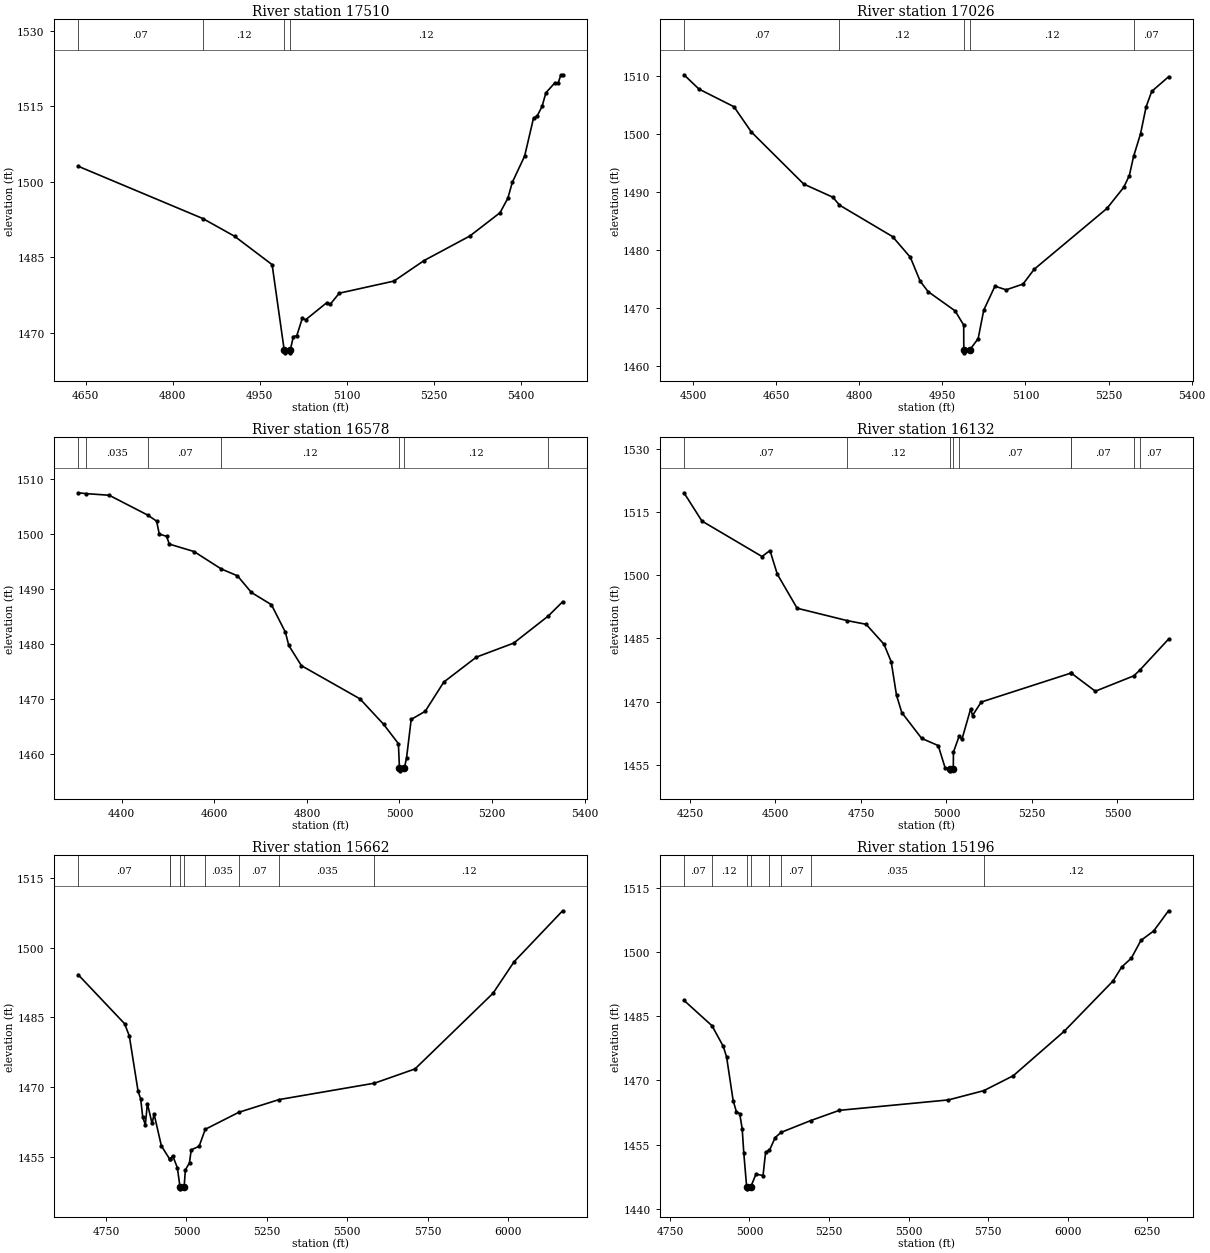
Type RM Length L Ch R = 1 ,17510   ,484,484,484
BEGIN DESCRIPTION:
REEH CREEK 34.0
END DESCRIPTION:
XS GIS Cut Line= 3
      2044164.63     13926984.97        2043975.       13926675.
      2043574.98     13926424.99
#Sta/Elev= 30
  4636.8 1503.09  4851.7 1492.69  4906.4 1489.17  4971.2 1483.52  4992.1 1466.48
  4992.6 1465.98  5001.9 1465.98  5002.4 1466.48  5007.8 1469.22  5013.7 1469.38
  5023.2 1472.84  5029.1 1472.57  5065.6 1475.97  5071.5 1475.65  5086.9 1477.84
  5181.2 1480.25  5233.1 1484.33  5312.1 1489.22    5364 1493.84  5377.5 1496.73
  5385.2  1499.9  5406.4  1505.1  5421.8  1512.7  5427.7 1513.02  5436.5 1514.98
    5443 1517.68  5458.3 1519.64  5464.2 1519.63  5468.9 1521.27  5471.9 1521.27
#Mann= 4 ,-1 , 0
  4636.8     .07       0  4851.7     .12       0  4992.1     .05       0
  5002.4     .12       0
Bank Sta=4992.1,5002.4
XS Rating Curve= 0 ,0
Exp/Cntr=0.3,0.1

Type RM Length L Ch R = 1 ,17026   ,448,448,448
BEGIN DESCRIPTION:
REEH CREEK 33.0
END DESCRIPTION:
XS GIS Cut Line= 3
      2044570.88      13926384.3        2044075.       13926225.
      2043724.99       13926175.
#Sta/Elev= 30
  4483.7 1510.21  4510.9 1507.74  4573.9 1504.71  4605.4 1500.35  4699.9 1491.39
  4752.5 1489.12  4764.3 1487.77  4860.1 1482.35  4892.2 1478.79    4910 1474.66
  4924.3 1472.87    4973 1469.56  4988.5 1467.11  4988.7 1462.83  4989.2 1462.33
  4999.4 1462.83  5014.6 1464.78  5024.7 1469.69  5044.9 1473.81  5065.1 1473.18
  5095.5 1474.17  5115.7 1476.72    5247  1487.2  5277.3 1490.83  5287.4 1492.86
  5295.1 1496.16  5307.6 1500.04  5317.7  1504.7  5327.8 1507.35  5358.1 1509.86
#Mann= 5 ,-1 , 0
  4483.7     .07       0  4764.3     .12       0  4988.7     .05       0
  4999.4     .12       0  5295.1     .07       0
Bank Sta=4988.7,4999.4
XS Rating Curve= 0 ,0
Exp/Cntr=0.3,0.1

Type RM Length L Ch R = 1 ,16578   ,446,446,446
BEGIN DESCRIPTION:
REEH CREEK 32.0
END DESCRIPTION:
XS GIS Cut Line= 3
      2044824.35     13926165.55        2044225.       13925825.
      2043869.76     13925787.11
#Sta/Elev= 30
  4305.8 1507.55  4322.6  1507.4    4373  1507.1  4456.5 1503.47  4475.4 1502.39
  4481.2 1500.02    4497 1499.62  4502.8  1498.2  4556.1 1496.85  4614.9 1493.68
  4650.1 1492.42  4680.1 1489.39  4723.4 1487.16  4753.6 1482.14  4760.9 1479.73
  4788.2 1476.05  4914.6 1470.01  4965.6 1465.38  4997.7 1461.84  4999.9 1457.39
  5000.4 1456.89  5010.6 1457.39  5015.3 1459.26  5025.3 1466.26  5055.5 1467.73
  5095.7 1473.06  5166.1 1477.61  5246.6 1480.16  5321.4  1485.1  5352.4  1487.7
#Mann= 7 ,-1 , 0
  4305.8     .07       0  4322.6    .035       0  4456.5     .07       0
  4614.9     .12       0  4999.9     .05       0  5010.6     .12       0
  5321.4     .07       0
Bank Sta=4999.9,5010.6
XS Rating Curve= 0 ,0
Exp/Cntr=0.3,0.1

Type RM Length L Ch R = 1 ,16132   ,470,470,470
BEGIN DESCRIPTION:
REEH CREEK 31.0
END DESCRIPTION:
XS GIS Cut Line= 3
      2045129.94      13925873.9        2044475.       13925475.
      2043862.52     13925693.35
#Sta/Elev= 30
  4232.4 1519.56    4285 1512.85  4460.7 1504.44    4484 1505.86  4505.3 1500.26
  4563.4 1492.17  4709.7 1489.23  4765.1 1488.36  4817.2 1483.65  4838.5 1479.49
    4854 1471.53  4869.5 1467.41  4927.6 1461.29  4976.1 1459.58  4996.3 1454.27
  5009.2 1454.09  5009.7 1453.59  5020.1 1454.09  5020.5 1458.04  5037.1 1461.79
  5045.5  1461.1    5071 1468.32  5076.3 1466.71  5101.8 1469.91  5364.1 1476.78
  5364.7  1476.8  5435.5 1472.48  5548.1 1476.13  5565.3 1477.46  5649.5 1484.83
#Mann= 9 ,-1 , 0
  4232.4     .07       0  4709.7     .12       0  5009.2     .05       0
  5020.1     .12       0  5037.1     .07       0  5364.1    .035       0
  5364.7     .07       0  5548.1     .12       0  5565.3     .07       0
Bank Sta=5009.2,5020.1
XS Rating Curve= 0 ,0
Exp/Cntr=0.3,0.1

Type RM Length L Ch R = 1 ,15662   ,466,466,466
BEGIN DESCRIPTION:
REEH CREEK 30.0
END DESCRIPTION:
XS GIS Cut Line= 3
      2045091.75     13925380.85        2044825.       13925175.
      2043732.84     13924754.39
#Sta/Elev= 30
  4662.8 1494.19  4807.7 1483.61  4822.2 1480.98  4849.4 1469.12  4857.5 1467.47
  4863.9 1463.54    4872 1461.88  4878.4 1466.47  4892.9 1462.17  4899.2  1464.2
  4921.9 1457.36  4947.5 1454.54  4949.2 1454.53  4957.2 1455.22  4971.7 1452.65
  4979.6 1448.62  4980.1 1448.12  4992.8 1448.62  4996.6 1452.19  5009.4 1453.75
  5014.7 1456.49  5039.4 1457.28  5058.4 1460.92  5162.8 1464.58  5287.9 1467.31
  5584.8 1470.84  5710.8  1473.9  5953.5 1490.17  6019.2 1496.96  6170.1 1507.91
#Mann= 9 ,-1 , 0
  4662.8     .07       0  4947.5     .12       0  4949.2     .07       0
  4979.6     .05       0  4992.8     .07       0  5058.4    .035       0
  5162.8     .07       0  5287.9    .035       0  5584.8     .12       0
Bank Sta=4979.6,4992.8
XS Rating Curve= 0 ,0
Exp/Cntr=0.3,0.1

Type RM Length L Ch R = 1 ,15196   ,468,468,468
BEGIN DESCRIPTION:
REEH CREEK 29.0
END DESCRIPTION:
XS GIS Cut Line= 3
      2045274.99       13924875.        2045075.       13924825.
      2043769.03      13924657.6
#Sta/Elev= 30
  4794.2 1488.69  4882.4 1482.76  4917.9 1477.94  4928.2 1475.48  4948.8  1465.3
  4959.1 1462.69  4969.4 1462.29  4977.2 1458.73  4982.3 1453.02  4991.2 1445.23
  4991.7 1444.73  5004.4 1445.23  5020.5 1448.16  5042.7 1447.83  5050.8  1453.3
    5063 1453.73    5081  1456.7  5099.5  1457.9  5192.2 1460.64  5282.6 1463.04
  5625.4 1465.47  5736.6 1467.63  5829.1 1471.11  5988.5 1481.43  6142.7 1493.21
  6169.8 1496.46  6200.1 1498.52  6230.3 1502.66  6270.7 1504.89    6317 1509.58
#Mann= 8 ,-1 , 0
  4794.2     .07       0  4882.4     .12       0  4991.2     .05       0
  5004.4     .12       0    5063    .035       0  5099.5     .07       0
  5192.2    .035       0  5736.6     .12       0
Bank Sta=4991.2,5004.4
XS Rating Curve= 0 ,0
Exp/Cntr=0.3,0.1

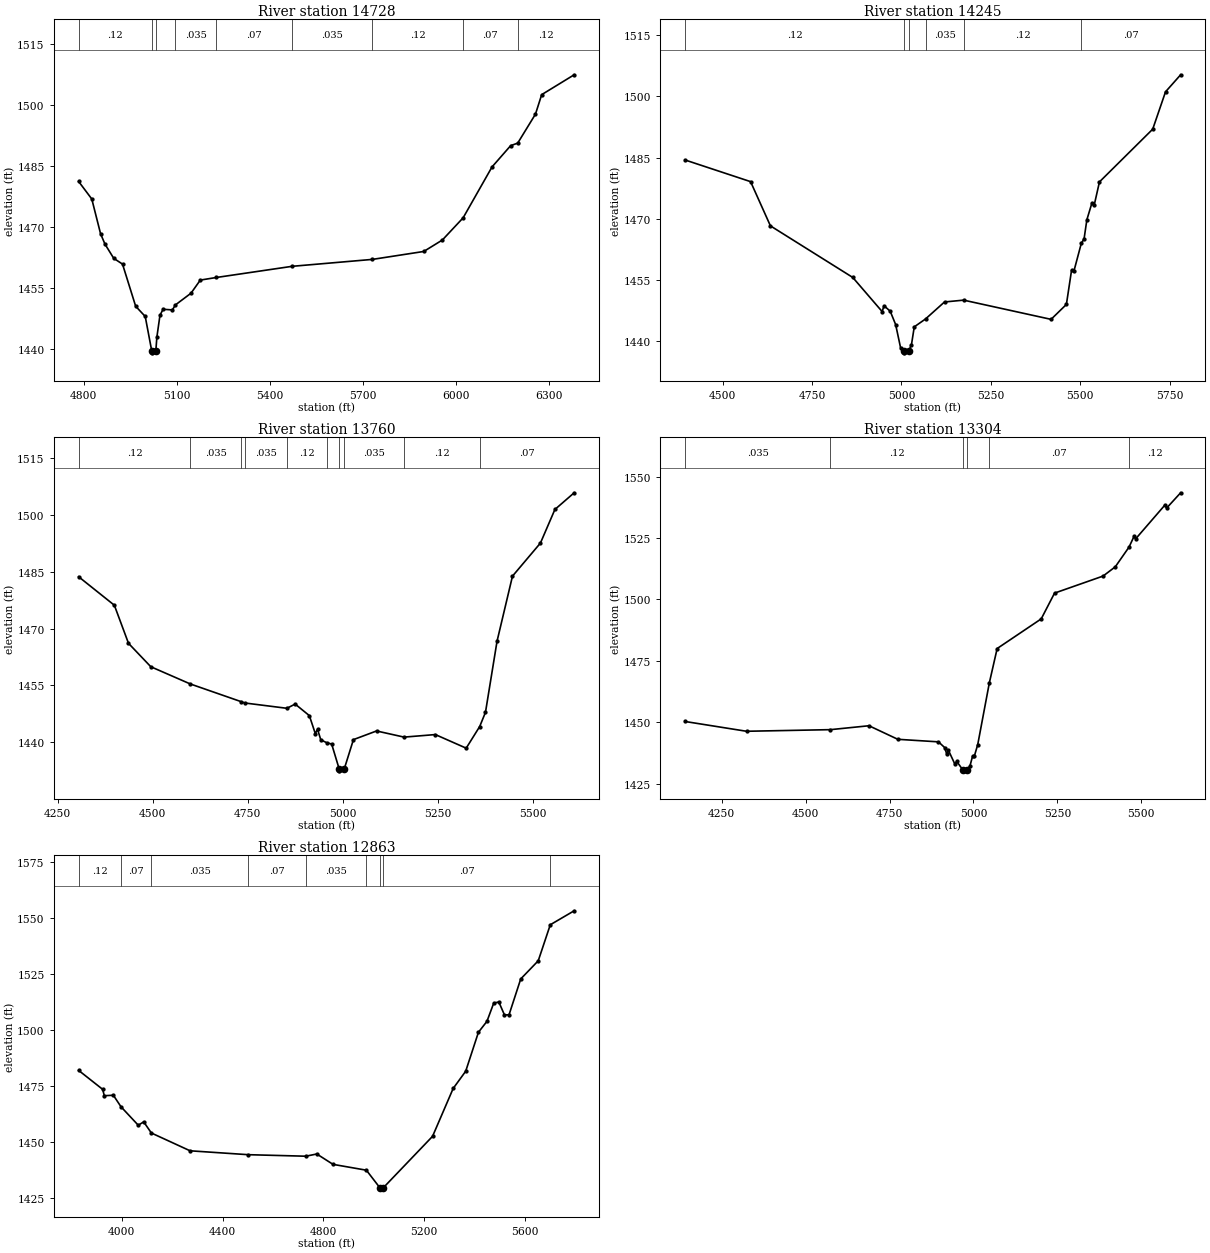
Type RM Length L Ch R = 1 ,14728   ,483,483,483
BEGIN DESCRIPTION:
REEH CREEK 28.0
END DESCRIPTION:
XS GIS Cut Line= 3
      2045424.98     13924574.98        2045275.       13924425.
      2043890.33     13924432.62
#Sta/Elev= 30
  4783.6 1481.16    4826 1476.85  4854.3  1468.3  4868.4 1465.76  4896.7 1462.25
    4925 1460.83  4967.4 1450.46  4998.2 1447.95  5019.1  1439.5  5019.6    1439
  5032.4  1439.5  5035.7 1442.86  5045.7 1448.24  5055.7 1449.72  5085.7 1449.56
  5095.5 1450.79  5145.7 1453.67  5175.7  1456.9  5227.5 1457.54    5472 1460.29
  5730.3 1461.99  5895.7 1463.94  5955.7 1466.76  6022.6 1472.22  6115.7 1484.74
  6175.7 1489.97  6198.5  1490.6  6255.7 1497.73  6275.7 1502.52  6380.4 1507.41
#Mann= 9 ,-1 , 0
  4783.6     .12       0  5019.1     .05       0  5032.4     .12       0
  5095.5    .035       0  5227.5     .07       0    5472    .035       0
  5730.3     .12       0  6022.6     .07       0  6198.5     .12       0
Bank Sta=5019.1,5032.4
XS Rating Curve= 0 ,0
Exp/Cntr=0.3,0.1

Type RM Length L Ch R = 1 ,14245   ,485,485,485
BEGIN DESCRIPTION:
REEH CREEK 27.0
END DESCRIPTION:
XS GIS Cut Line= 3
      2045952.86     13924155.15        2045375.       13923975.
      2044775.01     13923475.01
#Sta/Elev= 30
  4394.8  1484.4    4578 1479.09  4633.5 1468.25  4863.9  1455.6  4946.1 1447.23
  4951.3 1448.68  4968.7 1447.31  4983.8 1444.06  4997.5 1438.42  5007.1 1437.62
  5007.6 1437.12  5020.5 1437.62  5028.1 1439.13  5035.9 1443.49  5067.5 1445.43
  5120.5 1449.59    5174 1450.04  5418.6 1445.33  5461.5 1448.99  5475.9 1457.34
  5482.4 1457.11  5503.2 1463.96    5511 1465.08  5518.8 1469.76  5533.1 1473.91
  5539.6 1473.45    5554 1479.03    5703 1491.96  5738.8 1501.11  5781.1 1505.29
#Mann= 6 ,-1 , 0
  4394.8     .12       0  5007.1     .05       0  5020.5     .12       0
  5067.5    .035       0    5174     .12       0  5503.2     .07       0
Bank Sta=5007.1,5020.5
XS Rating Curve= 0 ,0
Exp/Cntr=0.3,0.1

Type RM Length L Ch R = 1 ,13760   ,456,456,456
BEGIN DESCRIPTION:
REEH CREEK 26.0
END DESCRIPTION:
XS GIS Cut Line= 3
        2045975.       13923875.        2045375.       13923525.
        2044775.       13923425.
#Sta/Elev= 30
  4305.5 1483.63  4399.4 1476.13  4436.6  1466.1  4495.3 1459.93  4599.3 1455.39
  4733.3 1450.72  4742.2 1450.39    4853 1448.99  4874.8  1450.1  4912.1 1447.06
  4927.8 1442.32  4933.6 1443.47  4942.2 1440.69  4957.5 1439.94  4970.8 1439.57
  4990.5 1433.02    4991 1432.52  5003.9 1433.02    5028 1440.74  5088.8 1443.02
  5161.2  1441.4  5243.4 1442.07  5324.5 1438.49    5360 1444.19  5375.2 1447.93
  5405.6 1466.65  5446.2 1483.79  5519.7  1492.5  5557.7 1501.34  5608.4 1505.74
#Mann= 10 ,-1 , 0
  4305.5     .12       0  4599.3    .035       0  4733.3     .12       0
  4742.2    .035       0    4853     .12       0  4957.5    .035       0
  4990.5    .035       0  5003.9    .035       0  5161.2     .12       0
    5360     .07       0
Bank Sta=4990.5,5003.9
XS Rating Curve= 0 ,0
Exp/Cntr=0.3,0.1

Type RM Length L Ch R = 1 ,13304   ,441,441,441
BEGIN DESCRIPTION:
REEH CREEK 25.0
END DESCRIPTION:
XS GIS Cut Line= 3
      2045875.02     13923525.01      2045075.33     13923211.09
      2044461.45      13923145.2
#Sta/Elev= 30
  4140.9 1450.32  4323.9 1446.34  4574.1    1447  4688.8 1448.59  4774.7 1443.07
  4895.9 1442.03  4914.4 1439.69  4920.3 1437.11  4925.7 1438.54  4944.8 1432.94
  4950.1 1434.13  4967.7 1430.73  4968.2 1430.23  4981.4 1430.73  4989.6  1432.2
  4997.5  1436.2  5002.7  1436.2  5012.8  1440.9  5047.5 1466.11  5070.7 1480.03
    5202  1492.1  5241.7 1502.59  5386.3 1509.53  5422.7  1513.3  5463.7 1521.34
  5478.4 1525.65  5483.4 1524.68  5570.5 1538.44  5575.5 1537.19  5617.4 1543.44
#Mann= 6 ,-1 , 0
  4140.9    .035       0  4574.1     .12       0  4967.7     .05       0
  4981.4     .12       0  5047.5     .07       0  5463.7     .12       0
Bank Sta=4967.7,4981.4
XS Rating Curve= 0 ,0
Exp/Cntr=0.3,0.1

Type RM Length L Ch R = 1 ,12863   ,858,858,858
BEGIN DESCRIPTION:
REEH CREEK 24.0
END DESCRIPTION:
XS GIS Cut Line= 3
      2046220.62     13923683.72      2045345.47     13922905.37
      2045229.08     13922119.34
#Sta/Elev= 30
  3828.8 1481.94    3924 1473.47  3930.7 1470.62  3966.6 1470.81  3996.9 1465.66
  4065.3 1457.41    4087  1458.9  4117.4 1453.92    4271 1445.96  4501.7 1444.22
    4730 1443.54  4773.6 1444.53    4838 1439.89  4970.3 1437.28  5023.7 1429.44
  5024.2 1428.94  5037.6 1429.44  5232.9 1452.45  5314.6 1473.86  5364.3 1481.57
  5414.8    1499  5448.6 1503.89  5475.5 1512.06  5495.7 1512.55  5518.1 1506.75
  5536.2 1506.82  5582.6 1522.86  5652.1 1530.99  5699.8  1547.1  5794.6 1553.36
#Mann= 9 ,-1 , 0
  3828.8     .12       0  3996.9     .07       0  4117.4    .035       0
  4501.7     .07       0    4730    .035       0  4970.3     .07       0
  5023.7     .05       0  5037.6     .07       0  5699.8     .12       0
Bank Sta=5023.7,5037.6
XS Rating Curve= 0 ,0
Exp/Cntr=0.3,0.1