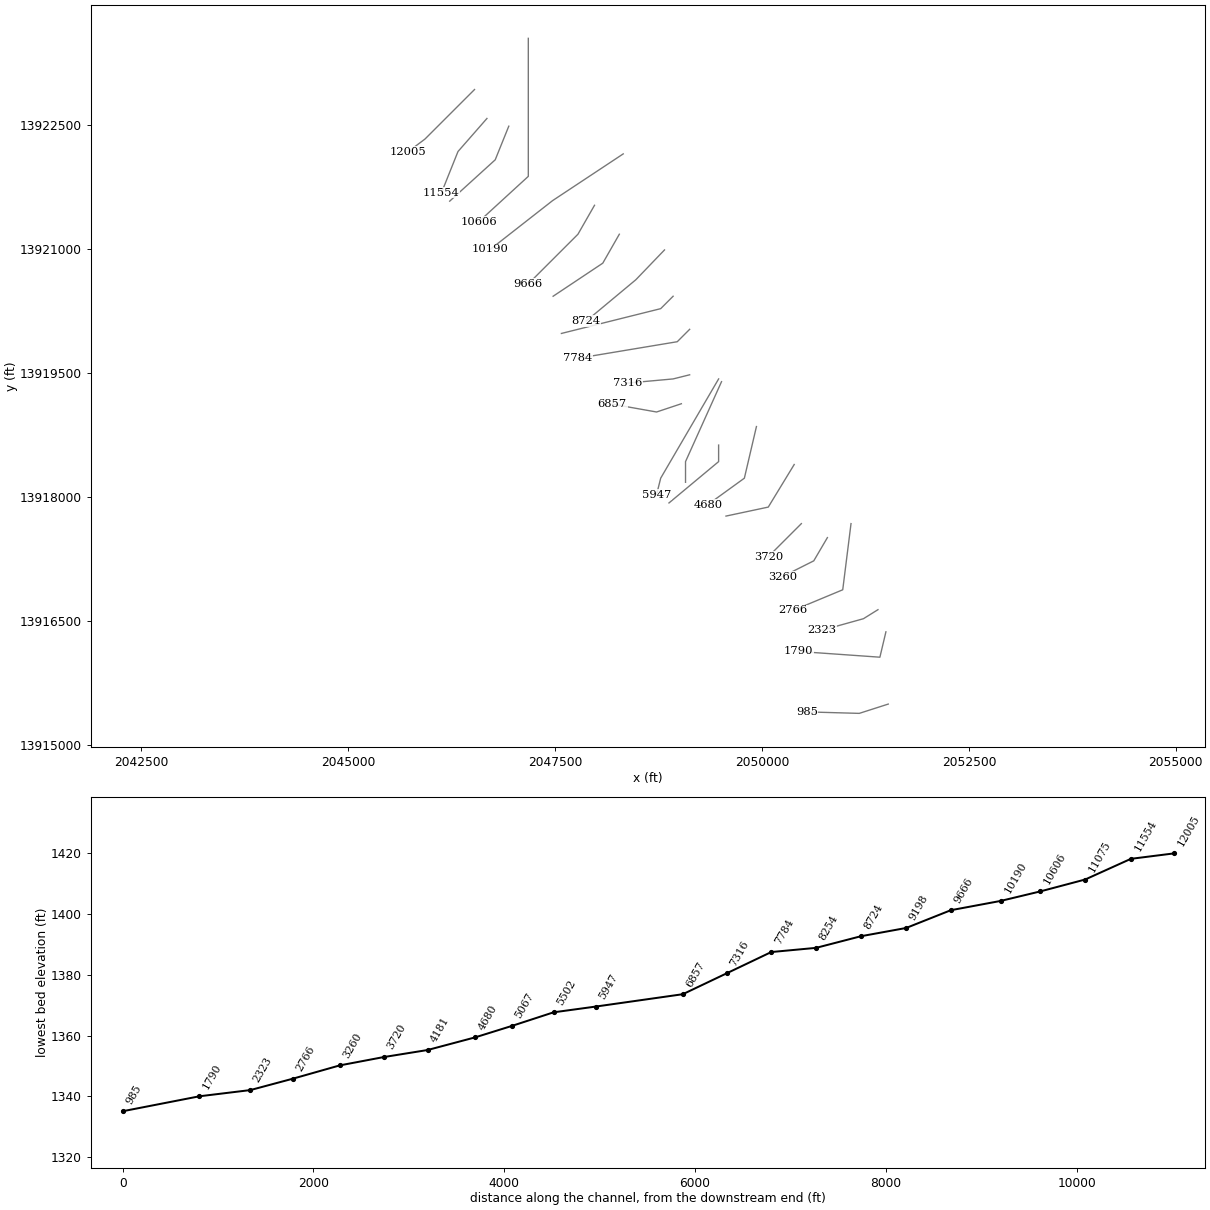
HEC-RAS study REEH CREEK.prj: REEH CREEK Base Level Engineering

--- REEH CREEK.g01 (geometry) --- (continued)

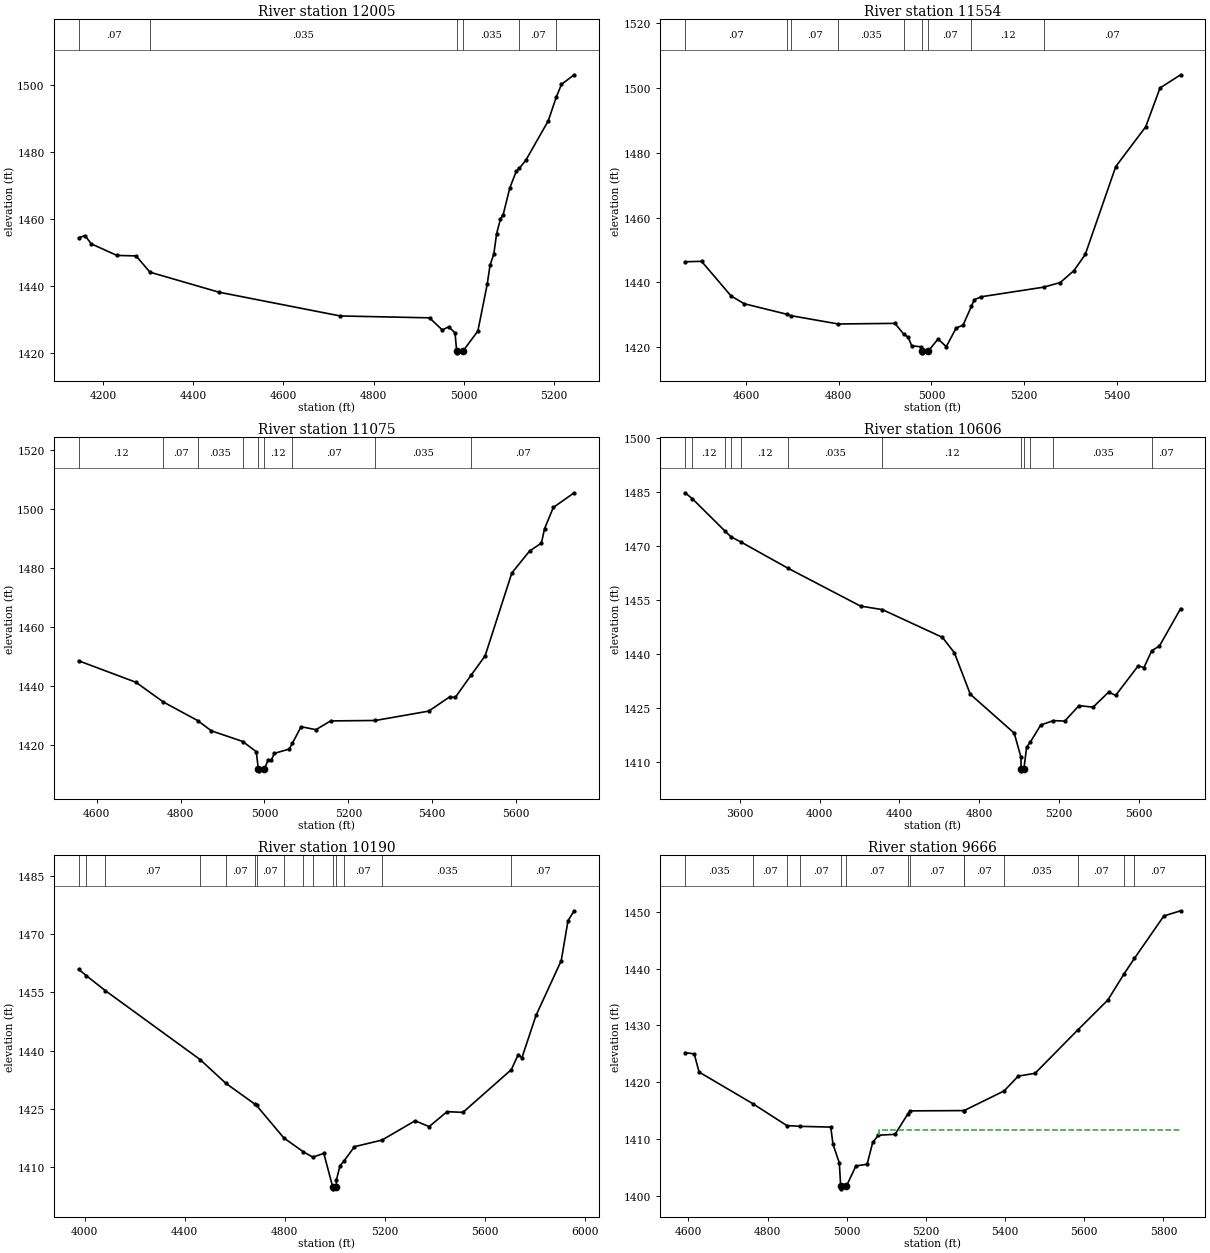
Type RM Length L Ch R = 1 ,12005   ,451,451,451
BEGIN DESCRIPTION:
REEH CREEK 23.0
END DESCRIPTION:
XS GIS Cut Line= 3
      2046524.98     13922924.98        2045925.       13922325.
        2045725.       13922175.
#Sta/Elev= 30
    4146 1454.43  4160.1 1455.01  4174.3 1452.56  4230.8 1449.12  4273.3 1448.97
  4304.1 1444.11  4457.1 1438.13  4725.8 1431.03  4923.8 1430.47  4952.1 1426.85
  4966.2 1427.78  4980.4 1425.99    4984 1420.51  4984.5 1420.01  4997.9 1420.51
    5031 1426.52  5051.8 1440.55    5058 1446.21  5066.4 1449.58  5072.6 1455.63
    5081 1459.96  5087.2 1461.34  5101.8 1469.27  5116.4 1474.34  5122.7 1475.13
  5137.2 1477.52  5187.2 1489.37  5204.5 1496.31  5216.4 1500.24  5244.5 1503.09
#Mann= 6 ,-1 , 0
    4146     .07       0  4304.1    .035       0    4984     .05       0
  4997.9    .035       0  5122.7     .07       0  5204.5     .12       0
Bank Sta=4984,4997.9
XS Rating Curve= 0 ,0
Exp/Cntr=0.3,0.1

Type RM Length L Ch R = 1 ,11554   ,479,479,479
BEGIN DESCRIPTION:
REEH CREEK 22.0
END DESCRIPTION:
XS GIS Cut Line= 3
      2046675.02     13922575.03        2046325.       13922175.
      2046124.98     13921674.96
#Sta/Elev= 30
  4468.1 1446.34  4503.7 1446.48  4567.3 1435.79  4595.8 1433.38  4687.7 1430.14
  4696.6  1429.7  4798.8 1427.13  4921.3 1427.32  4940.5 1423.94  4949.8 1423.06
  4957.4 1420.42  4978.3 1420.05  4978.8 1418.72  4979.3 1418.22  4992.9 1418.72
  5014.5 1422.51    5032 1420.12  5053.5 1425.89  5068.3 1426.76  5086.3 1432.56
  5092.5 1434.62  5107.3 1435.53  5242.4  1438.5  5278.3 1439.93  5307.9 1443.63
  5332.2 1448.59  5398.1 1475.74  5462.8 1488.03  5493.7 1500.01  5538.2 1504.08
#Mann= 9 ,-1 , 0
  4468.1     .07       0  4687.7    .035       0  4696.6     .07       0
  4798.8    .035       0  4940.5     .07       0  4978.8     .05       0
  4992.9     .07       0  5086.3     .12       0  5242.4     .07       0
Bank Sta=4978.8,4992.9
XS Rating Curve= 0 ,0
Exp/Cntr=0.3,0.1

Type RM Length L Ch R = 1 ,11075   ,469,469,469
BEGIN DESCRIPTION:
REEH CREEK 21.0
END DESCRIPTION:
XS GIS Cut Line= 3
      2046938.96     13922481.56        2046775.       13922075.
      2046224.99     13921574.99
#Sta/Elev= 30
  4556.9  1448.6  4693.4 1441.35  4759.1 1434.66  4841.1 1428.37  4873.1 1424.95
  4948.5 1421.32  4980.5 1417.87  4985.5 1411.91    4986 1411.41  4999.7 1411.91
  5009.1  1415.2  5016.6 1415.05  5023.3  1417.3  5059.1 1418.77  5066.3 1420.66
  5087.5 1426.33  5122.7 1425.32  5157.8 1428.28  5264.6 1428.43  5391.6 1431.59
  5441.3 1436.36  5455.1 1436.22  5492.4 1443.66  5526.1 1450.24  5589.9 1478.26
  5632.2 1485.69  5660.5 1488.38    5668 1493.26  5688.9 1500.42  5738.6 1505.38
#Mann= 9 ,-1 , 0
  4556.9     .12       0  4759.1     .07       0  4841.1    .035       0
  4948.5     .12       0  4985.5     .05       0  4999.7     .12       0
  5066.3     .07       0  5264.6    .035       0  5492.4     .07       0
Bank Sta=4985.5,4999.7
XS Rating Curve= 0 ,0
Exp/Cntr=0.3,0.1

Type RM Length L Ch R = 1 ,10606   ,416,416,416
BEGIN DESCRIPTION:
REEH CREEK 20.0
END DESCRIPTION:
XS GIS Cut Line= 3
      2047175.06     13923544.08        2047175.       13921875.
      2046575.01     13921325.01
#Sta/Elev= 30
    3326 1484.85  3362.9 1483.17  3524.8 1474.26  3557.4 1472.54  3607.2 1471.12
  3841.9 1463.85  4205.1 1453.33  4314.5 1452.35  4615.1 1444.64  4675.1 1440.37
  4755.1 1428.81  4975.1 1417.99    5009 1411.28  5009.3    1408  5009.8  1407.5
  5023.5    1408  5037.3 1414.09  5056.1 1415.53  5108.2 1420.25  5171.6 1421.47
  5228.5 1421.34  5299.4 1425.64  5370.3 1425.21    5448 1429.39  5483.4 1428.49
  5596.6 1436.73    5625 1436.22  5664.4 1440.94  5702.7  1442.2    5809 1452.64
#Mann= 12 ,-1 , 0
    3326    .035       0  3362.9     .12       0  3524.8     .07       0
  3557.4    .035       0  3607.2     .12       0  3841.9    .035       0
  4314.5     .12       0  5009.3     .05       0  5023.5     .12       0
  5056.1     .07       0  5171.6    .035       0  5664.4     .07       0
Bank Sta=5009.3,5023.5
XS Rating Curve= 0 ,0
Exp/Cntr=0.3,0.1

Type RM Length L Ch R = 1 ,10190   ,524,524,524
BEGIN DESCRIPTION:
REEH CREEK 19.0
END DESCRIPTION:
XS GIS Cut Line= 3
      2048322.11     13922146.62      2047468.57     13921581.44
      2046714.85     13920991.56
#Sta/Elev= 30
  3976.3 1460.95  4006.5 1459.36  4082.8 1455.48  4461.6 1437.71  4564.8 1431.57
  4680.6 1426.21  4687.5 1425.85  4796.5 1417.49  4874.4 1413.91  4912.3 1412.54
  4956.3  1413.5  4991.9 1404.86  4992.4 1404.36  5006.4 1404.86  5006.6 1406.65
  5021.1  1410.3  5036.4 1411.48  5078.9 1415.23  5189.2 1416.94  5321.2 1421.91
  5377.3 1420.41    5449 1424.26  5512.5 1424.08    5706  1435.1  5733.6    1439
    5748 1438.12  5804.5 1449.06  5905.4  1463.2  5932.5 1473.53  5957.1 1476.06
#Mann= 15 ,-1 , 0
  3976.3     .07       0  4006.5    .035       0  4082.8     .07       0
  4461.6    .035       0  4564.8     .07       0  4680.6    .035       0
  4687.5     .07       0  4796.5    .035       0  4874.4     .07       0
  4912.3     .12       0  4991.9     .05       0  5006.4     .12       0
  5036.4     .07       0  5189.2    .035       0    5706     .07       0
Bank Sta=4991.9,5006.4
XS Rating Curve= 0 ,0
Exp/Cntr=0.3,0.1

Type RM Length L Ch R = 1 ,9666    ,468,468,468
BEGIN DESCRIPTION:
REEH CREEK 18.0
END DESCRIPTION:
XS GIS Cut Line= 3
      2047975.02     13921525.04        2047775.       13921175.
      2047174.99     13920574.99
#Sta/Elev= 30
  4591.8 1425.23  4614.9    1425  4627.1 1421.81  4762.5 1416.27  4848.6 1412.41
  4882.8 1412.27  4959.7 1412.14  4965.4 1409.11  4981.3 1405.86  4984.8 1401.79
  4985.3 1401.29  4999.4 1401.79  5023.2 1405.31  5051.5 1405.61  5065.7 1409.44
  5079.8 1410.71  5122.2 1410.87    5154 1414.41  5160.3 1414.99  5295.5 1415.04
  5296.8 1415.05  5397.5 1418.49  5433.4  1421.1  5475.8 1421.59  5583.3 1429.18
  5659.6 1434.46  5701.1 1439.12  5726.9  1441.8  5801.1 1449.24  5843.5 1450.15
#Mann= 14 ,-1 , 0
  4591.8    .035       0  4762.5     .07       0  4848.6    .035       0
  4882.8     .07       0  4984.8     .05       0  4999.4     .07       0
    5154    .035       0  5160.3     .07       0  5295.5    .035       0
  5296.8     .07       0  5397.5    .035       0  5583.3     .07       0
  5701.1    .035       0  5726.9     .07       0
#XS Ineff= 2 , 0
       0                    5081       0 1411.66
Permanent Ineff=
       F       F
Bank Sta=4984.8,4999.4
XS Rating Curve= 0 ,0
Exp/Cntr=0.3,0.1

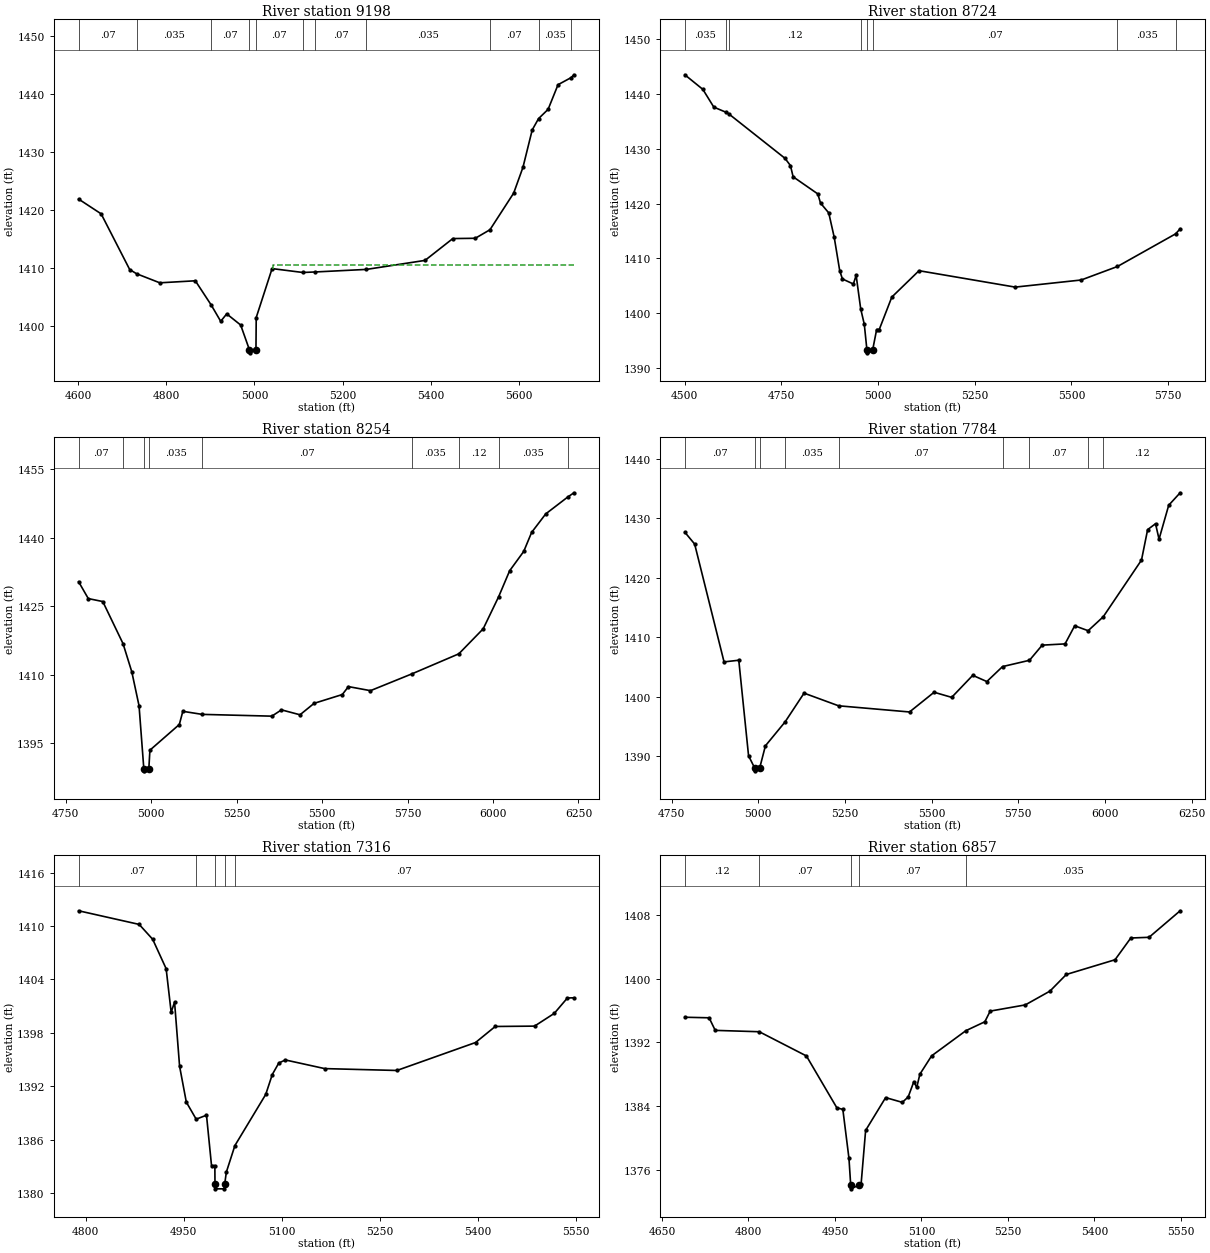
Type RM Length L Ch R = 1 ,9198    ,474,474,474
BEGIN DESCRIPTION:
REEH CREEK 17.0
END DESCRIPTION:
XS GIS Cut Line= 3
      2048274.98     13921174.97        2048075.       13920825.
      2047474.99     13920424.99
#Sta/Elev= 30
  4600.9 1421.92    4652 1419.38  4716.8 1409.79  4732.5 1409.06  4785.1  1407.5
  4865.8 1407.85  4901.8 1403.68  4923.4 1400.87    4937 1402.15  4968.7 1400.23
  4988.7 1395.94  4989.2 1395.44  5003.4 1395.94    5004 1401.52    5040 1409.95
  5109.8 1409.28  5138.1 1409.37  5254.2 1409.81  5387.1 1411.36  5450.2 1415.12
  5501.2 1415.17  5534.5 1416.64  5588.4 1422.96  5609.4 1427.39  5630.4 1433.83
  5644.8 1435.78  5666.5 1437.38    5689 1441.62  5718.4 1442.83  5725.1 1443.33
#Mann= 11 ,-1 , 0
  4600.9     .07       0  4732.5    .035       0  4901.8     .07       0
  4988.7     .05       0  5003.4     .07       0  5109.8    .035       0
  5138.1     .07       0  5254.2    .035       0  5534.5     .07       0
  5644.8    .035       0  5718.4     .07       0
#XS Ineff= 2 , 0
       0                 5040.96       0  1410.6
Permanent Ineff=
       F       F
Bank Sta=4988.7,5003.4
XS Rating Curve= 0 ,0
Exp/Cntr=0.3,0.1

Type RM Length L Ch R = 1 ,8724    ,470,470,470
BEGIN DESCRIPTION:
REEH CREEK 16.0
END DESCRIPTION:
XS GIS Cut Line= 3
      2048820.89     13920984.99        2048475.       13920625.
      2047874.97     13920124.97
#Sta/Elev= 30
  4500.8 1443.53  4547.4 1440.86  4575.7 1437.62  4607.3 1436.68  4614.7 1436.37
  4759.6 1428.27  4773.8 1426.94  4780.7 1424.89  4844.5 1421.76  4851.5 1420.09
  4872.8 1418.29    4887 1413.81  4901.1 1407.75  4908.1 1406.22  4936.4  1405.3
  4943.6 1406.87  4955.4 1400.75  4964.7 1397.93  4971.5 1393.22    4972 1392.72
  4986.2 1393.22  4996.6 1396.98  5003.3 1396.98  5035.8 1402.91  5106.1 1407.73
  5354.7 1404.73  5525.3 1406.03  5619.1  1408.5  5769.3 1414.46  5781.1 1415.38
#Mann= 8 ,-1 , 0
  4500.8    .035       0  4607.3     .07       0  4614.7     .12       0
  4955.4     .07       0  4971.5     .05       0  4986.2     .07       0
  5619.1    .035       0  5769.3     .07       0
Bank Sta=4971.5,4986.2
XS Rating Curve= 0 ,0
Exp/Cntr=0.3,0.1

Type RM Length L Ch R = 1 ,8254    ,470,470,470
BEGIN DESCRIPTION:
REEH CREEK 15.0
END DESCRIPTION:
XS GIS Cut Line= 3
      2048925.02     13920425.02        2048775.       13920275.
      2047574.99       13919975.
#Sta/Elev= 30
  4787.6 1430.35  4815.9 1426.66  4858.3 1426.01  4917.6 1416.77  4943.2 1410.59
  4964.4 1403.15  4978.3 1389.39  4978.8 1388.89    4993 1389.39  4996.2 1393.42
  5082.2 1399.05  5092.5 1401.94  5149.1 1401.27  5352.8 1400.88  5381.1 1402.26
  5435.3 1401.18  5476.5 1403.69    5559 1405.62    5577 1407.36  5641.4 1406.47
  5763.2 1410.17    5900 1414.55  5971.3 1420.04  6016.4 1427.06  6048.6 1432.76
  6089.8    1437    6113 1441.18  6154.2 1445.23  6218.8 1448.94  6236.7 1449.86
#Mann= 9 ,-1 , 0
  4787.6     .07       0  4917.6    .035       0  4978.3    .035       0
    4993    .035       0  5149.1     .07       0  5763.2    .035       0
    5900     .12       0  6016.4    .035       0  6218.8     .07       0
Bank Sta=4978.3,4993
XS Rating Curve= 0 ,0
Exp/Cntr=0.3,0.1

Type RM Length L Ch R = 1 ,7784    ,468,468,468
BEGIN DESCRIPTION:
REEH CREEK 14.0
END DESCRIPTION:
XS GIS Cut Line= 3
      2049124.99     13920024.99        2048975.       13919875.
      2047774.98       13919675.
#Sta/Elev= 30
    4788 1427.68  4816.3 1425.69  4901.1 1405.85  4943.6 1406.13  4971.8 1390.05
  4989.2 1388.01  4989.7 1387.51    5004 1388.01  5020.4 1391.72  5077.2 1395.75
  5131.9 1400.59  5231.4 1398.46  5436.1 1397.42    5507 1400.74  5557.7 1399.88
  5618.5 1403.59  5659.1 1402.54  5704.4 1405.06  5782.1 1406.12  5818.8 1408.67
  5884.7 1408.88  5912.5 1411.93  5951.3  1411.1  5994.8 1413.44  6105.2 1422.99
  6122.9 1428.12  6145.7 1429.11  6155.8 1426.51  6183.7 1432.22  6216.7 1434.32
#Mann= 9 ,-1 , 0
    4788     .07       0  4989.2     .05       0    5004     .07       0
  5077.2    .035       0  5231.4     .07       0  5704.4    .035       0
  5782.1     .07       0  5951.3    .035       0  5994.8     .12       0
Bank Sta=4989.2,5004
XS Rating Curve= 0 ,0
Exp/Cntr=0.3,0.1

Type RM Length L Ch R = 1 ,7316    ,459,459,459
BEGIN DESCRIPTION:
REEH CREEK 13.0
END DESCRIPTION:
XS GIS Cut Line= 3
      2049124.97     13919474.99        2048925.       13919425.
      2048374.99       13919375.
#Sta/Elev= 30
  4789.1 1411.71  4881.8 1410.18  4902.5 1408.51  4923.1 1405.21  4930.8 1400.31
    4936 1401.46  4943.7 1394.25    4954 1390.23  4969.1 1388.31  4984.9 1388.76
  4992.6  1383.1  4997.7  1383.1  4997.9 1380.99  4998.4 1380.49  5012.2 1380.49
  5012.7 1380.99  5015.3 1382.37  5028.4 1385.35  5075.6 1391.09  5085.6 1393.32
  5095.6 1394.62  5105.7 1394.96  5165.9 1393.99  5276.4 1393.78  5396.9 1396.92
    5427 1398.72  5487.2 1398.76  5517.4 1400.19  5537.5 1401.92  5547.5 1401.94
#Mann= 5 ,-1 , 0
  4789.1     .07       0  4969.1    .035       0  4997.9    .035       0
  5012.7    .035       0  5028.4     .07       0
Bank Sta=4997.9,5012.7
XS Rating Curve= 0 ,0
Exp/Cntr=0.3,0.1

Type RM Length L Ch R = 1 ,6857    ,910,910,910
BEGIN DESCRIPTION:
REEH CREEK 12.0
END DESCRIPTION:
XS GIS Cut Line= 3
      2049024.96     13919124.99        2048725.       13919025.
      2048190.68     13919120.11
#Sta/Elev= 30
  4689.7 1395.17  4731.8  1395.1  4742.4 1393.52  4818.8 1393.35  4900.5 1390.31
  4953.2 1383.81  4963.7 1383.59  4974.3 1377.45  4977.3 1374.12  4977.8 1373.62
  4992.4 1374.12  4995.3 1374.17  5003.2 1380.96  5037.9 1385.08  5066.8 1384.48
    5077 1385.16  5086.8 1387.08  5091.8 1386.35  5097.3 1388.02  5117.6 1390.32
    5177 1393.48  5209.9  1394.6  5219.2 1395.94  5280.1 1396.72  5322.8 1398.45
  5351.2 1400.54  5435.7 1402.39    5463 1405.12  5494.7 1405.21  5548.6 1408.54
#Mann= 5 ,-1 , 0
  4689.7     .12       0  4818.8     .07       0  4977.3     .05       0
  4992.4     .07       0    5177    .035       0
Bank Sta=4977.3,4992.4
XS Rating Curve= 0 ,0
Exp/Cntr=0.3,0.1

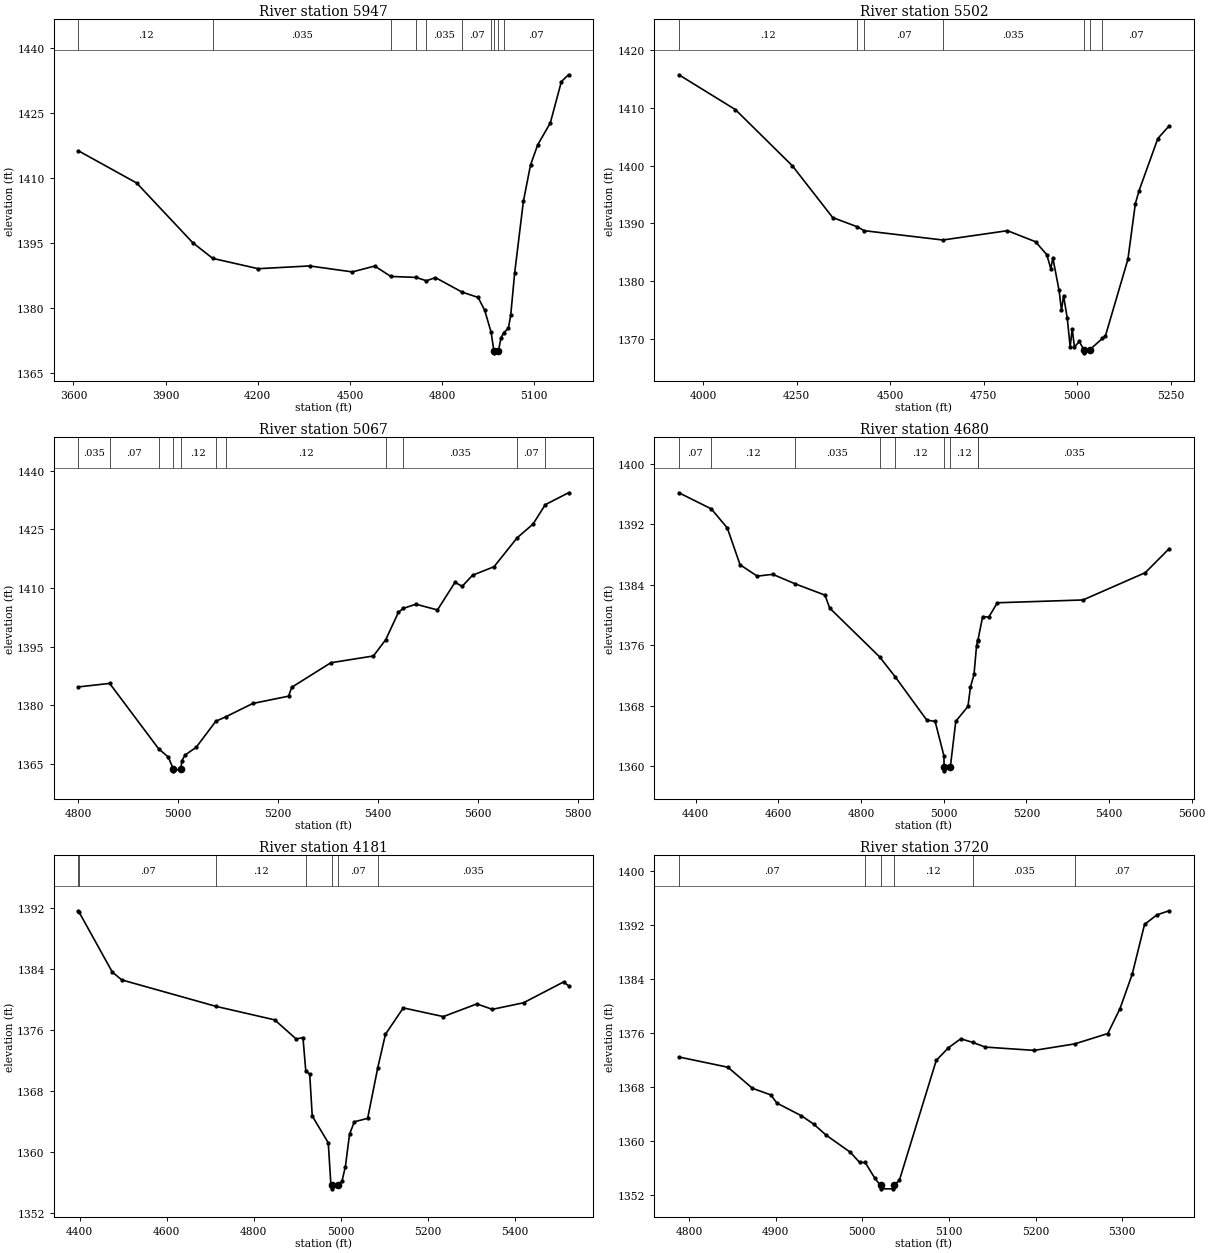
Type RM Length L Ch R = 1 ,5947    ,445,445,445
BEGIN DESCRIPTION:
REEH CREEK 11.0
END DESCRIPTION:
XS GIS Cut Line= 3
      2049475.01     13919425.02        2048775.       13918225.
        2048725.     13918025.02
#Sta/Elev= 30
  3616.2 1416.27    3806 1408.82  3987.9 1395.06  4053.4  1391.4  4201.3 1389.01
  4368.7 1389.65  4507.7 1388.27  4580.8 1389.62  4633.3 1387.22  4714.9    1387
  4749.2 1386.22  4778.5 1386.95  4865.2  1383.6  4917.4 1382.37  4938.9 1379.37
  4959.7 1374.31  4968.6 1370.06  4969.1 1369.56  4983.7 1370.06  4991.8 1373.04
  5001.3 1374.25  5015.8 1375.23  5023.5 1378.28  5036.4 1388.07  5064.7 1404.57
  5087.9 1412.97  5111.1 1417.61  5152.4 1422.72  5188.4 1432.27  5211.6 1433.84
#Mann= 10 ,-1 , 0
  3616.2     .12       0  4053.4    .035       0  4633.3     .12       0
  4714.9     .07       0  4749.2    .035       0  4865.2     .07       0
  4959.7    .035       0  4968.6    .035       0  4983.7    .035       0
  5001.3     .07       0
Bank Sta=4968.6,4983.7
XS Rating Curve= 0 ,0
Exp/Cntr=0.3,0.1

Type RM Length L Ch R = 1 ,5502    ,435,435,435
BEGIN DESCRIPTION:
REEH CREEK 10.0
END DESCRIPTION:
XS GIS Cut Line= 3
      2049510.08     13919391.68        2049075.       13918425.
        2049075.     13918174.97
#Sta/Elev= 30
  3935.4 1415.68  4086.3 1409.67  4238.8 1399.95  4346.4 1391.02  4411.1 1389.45
  4430.9 1388.75  4640.8 1387.14  4813.6 1388.75  4888.6 1386.84  4918.7 1384.61
  4929.4 1382.19  4934.9 1384.04  4951.6 1378.42    4958 1374.97  4963.5 1377.52
  4973.5  1373.6  4981.2 1368.68  4986.6 1371.79  4992.7 1368.63  5005.5 1369.63
  5017.9 1368.15  5018.4 1367.65    5033 1368.15  5067.2 1370.13  5075.5 1370.59
  5135.5  1383.8  5155.5 1393.44  5165.5 1395.69  5215.5 1404.67  5245.5 1406.84
#Mann= 7 ,-1 , 0
  3935.4     .12       0  4411.1    .035       0  4430.9     .07       0
  4640.8    .035       0  5017.9    .035       0    5033    .035       0
  5067.2     .07       0
Bank Sta=5017.9,5033
XS Rating Curve= 0 ,0
Exp/Cntr=0.3,0.1

Type RM Length L Ch R = 1 ,5067    ,387,387,387
BEGIN DESCRIPTION:
REEH CREEK 9.0
END DESCRIPTION:
XS GIS Cut Line= 3
        2049475.     13918624.96        2049475.       13918425.
      2048874.99     13917924.99
#Sta/Elev= 30
  4800.1 1384.67  4862.7 1385.57    4961 1368.79  4980.1 1366.73    4990 1363.69
  4990.5 1363.19  5005.2 1363.69  5007.2 1365.76  5013.7 1367.24  5035.9 1369.21
  5075.1 1375.87  5096.3 1377.09  5149.1 1380.43  5220.7  1382.3  5227.2 1384.58
  5305.3 1390.85  5390.6 1392.59  5415.4 1396.78  5440.7 1403.77  5450.3 1404.77
  5475.8 1405.84  5518.8 1404.37  5553.9 1411.43  5568.3 1410.42  5589.1 1413.26
    5632 1415.43  5678.4 1422.85  5710.1 1426.35  5734.6 1431.32  5781.1 1434.36
#Mann= 11 ,-1 , 0
  4800.1    .035       0  4862.7     .07       0    4961     .12       0
    4990     .05       0  5005.2     .12       0  5075.1    .035       0
  5096.3     .12       0  5415.4     .07       0  5450.3    .035       0
  5678.4     .07       0  5734.6    .035       0
Bank Sta=4990,5005.2
XS Rating Curve= 0 ,0
Exp/Cntr=0.3,0.1

Type RM Length L Ch R = 1 ,4680    ,499,499,499
BEGIN DESCRIPTION:
REEH CREEK 8.0
END DESCRIPTION:
XS GIS Cut Line= 3
       2049932.1      13918849.1      2049786.17     13918224.58
      2049345.16     13917905.11
#Sta/Elev= 30
  4359.4 1396.16  4437.8 1394.03  4476.6  1391.5  4507.4 1386.64    4549 1385.14
  4586.4 1385.38  4641.3 1384.11  4712.8 1382.63  4724.2 1380.92  4844.8 1374.48
  4883.4 1371.78  4959.2  1366.1  4979.3 1365.94  5000.7 1361.36  5000.9  1359.9
  5001.4  1359.4  5016.1  1359.9  5029.3 1365.95  5058.7 1367.91  5064.9  1370.5
  5073.4 1372.14  5079.6 1375.97  5082.6 1376.63  5083.2 1376.76  5094.3 1379.79
    5109 1379.72  5129.9 1381.62  5337.1 1381.99  5487.9  1385.6  5545.3 1388.76
#Mann= 9 ,-1 , 0
  4359.4     .07       0  4437.8     .12       0  4641.3    .035       0
  4844.8     .07       0  4883.4     .12       0  5000.9     .05       0
  5016.1     .12       0  5082.6     .07       0  5083.2    .035       0
Bank Sta=5000.9,5016.1
XS Rating Curve= 0 ,0
Exp/Cntr=0.3,0.1

Type RM Length L Ch R = 1 ,4181    ,461,461,461
BEGIN DESCRIPTION:
REEH CREEK 7.0
END DESCRIPTION:
XS GIS Cut Line= 3
      2050388.45     13918389.99        2050075.       13917875.
      2049563.93     13917766.25
#Sta/Elev= 30
  4397.1 1391.68  4398.5 1391.53    4475 1383.65  4496.6 1382.62  4713.2 1379.15
  4847.8 1377.38  4897.3 1374.87  4912.8 1375.06  4919.2 1370.72  4928.3 1370.23
  4934.1 1364.78  4970.9 1361.26  4976.8 1355.88  4978.7 1355.73  4979.2 1355.23
    4994 1355.73  5002.5 1356.27  5010.2 1358.15  5019.7 1362.38  5030.7 1364.02
  5061.3 1364.47  5084.6 1371.12  5102.2 1375.49  5143.1 1378.95  5235.1 1377.81
    5312 1379.47  5347.6 1378.76  5419.2 1379.62  5511.2 1382.35  5522.5 1381.85
#Mann= 7 ,-1 , 0
  4397.1     .12       0  4398.5     .07       0  4713.2     .12       0
  4919.2     .07       0  4978.7     .05       0    4994     .07       0
  5084.6    .035       0
Bank Sta=4978.7,4994
XS Rating Curve= 0 ,0
Exp/Cntr=0.3,0.1

Type RM Length L Ch R = 1 ,3720    ,460,460,460
BEGIN DESCRIPTION:
REEH CREEK 6.0
END DESCRIPTION:
XS GIS Cut Line= 3
      2050474.99     13917674.99        2050325.       13917525.
      2050074.98     13917274.98
#Sta/Elev= 30
  4788.3 1372.46  4844.9 1370.94  4873.1 1367.82  4894.4 1366.83  4901.4 1365.62
  4929.7 1363.74  4943.9  1362.5    4958 1360.89  4986.3 1358.31  4996.9 1356.81
  5003.3 1356.81  5014.6 1354.44    5021  1353.4  5021.5  1352.9  5035.9  1352.9
  5036.4  1353.4  5042.8 1354.18  5085.3 1371.95  5099.4 1373.83  5113.6 1375.16
  5127.3 1374.63  5141.8 1373.93  5198.4 1373.44  5245.1  1374.4  5283.3 1375.94
  5297.4 1379.64  5311.5 1384.75  5325.7 1392.12  5339.8 1393.53    5354 1394.15
#Mann= 6 ,-1 , 0
  4788.3     .07       0  5003.3     .12       0    5021     .05       0
  5036.4     .12       0  5127.3    .035       0  5245.1     .07       0
Bank Sta=5021,5036.4
XS Rating Curve= 0 ,0
Exp/Cntr=0.3,0.1

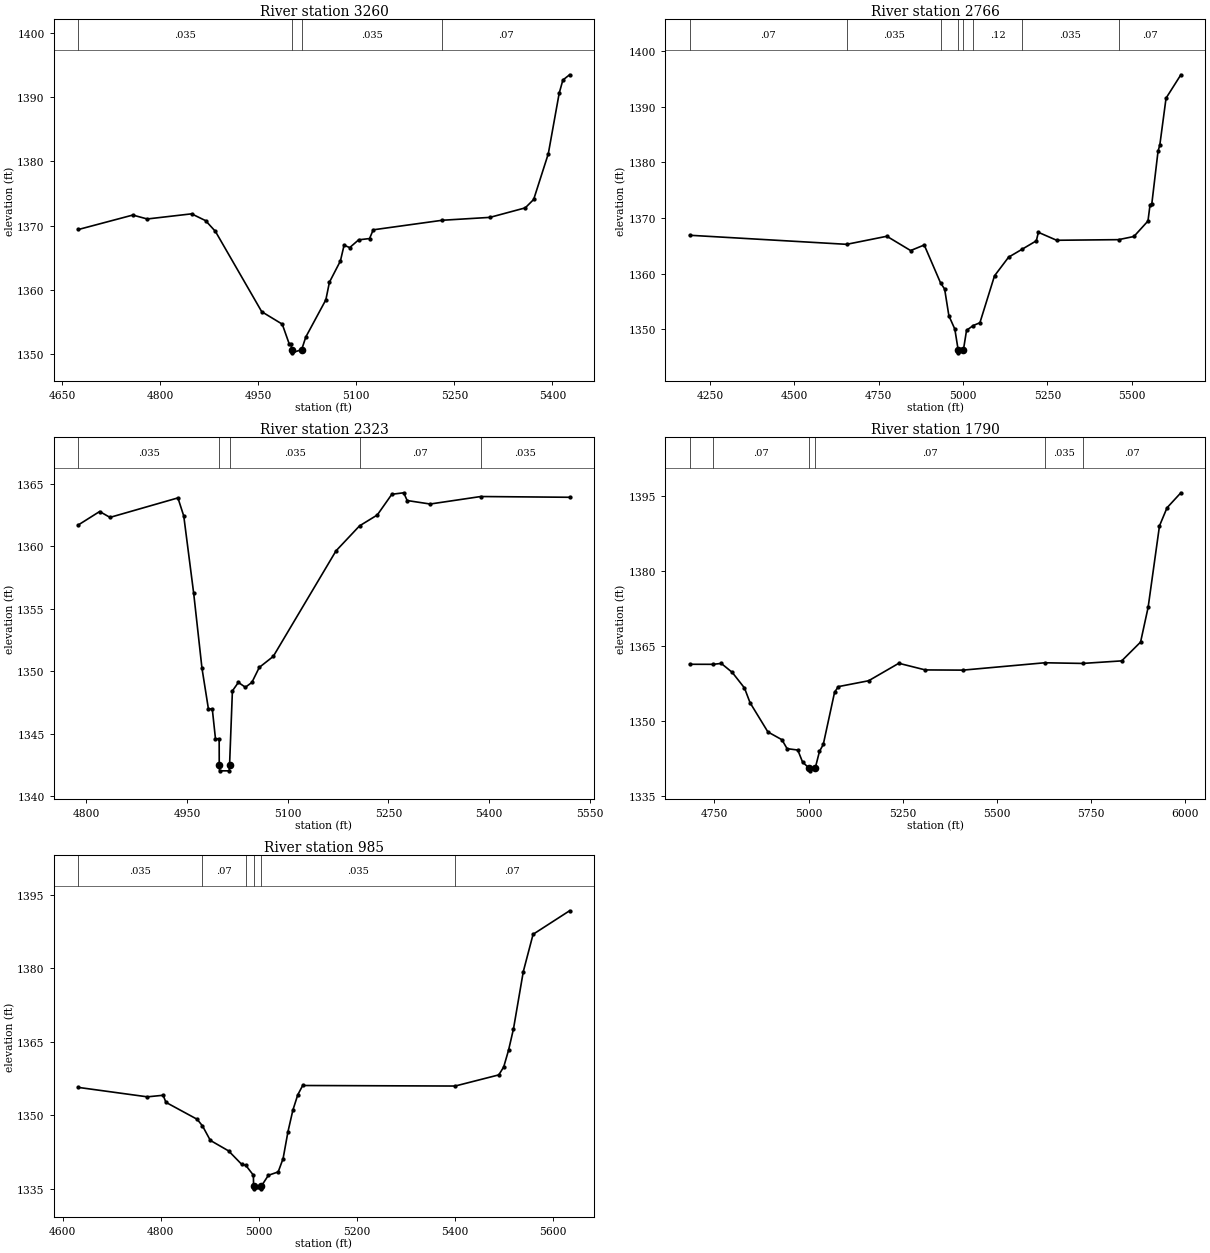
Type RM Length L Ch R = 1 ,3260    ,494,494,494
BEGIN DESCRIPTION:
REEH CREEK 5.0
END DESCRIPTION:
XS GIS Cut Line= 3
      2050789.65     13917505.84        2050625.       13917225.
      2050244.47      13917033.6
#Sta/Elev= 30
  4674.7 1369.38  4757.9 1371.63    4780 1371.02  4847.9 1371.82  4869.3 1370.76
  4884.3 1369.09  4955.2 1356.57  4986.6 1354.63  4997.3 1351.54  5000.2 1351.54
  5000.9 1350.66  5001.4 1350.16  5016.3 1350.66  5022.6 1352.62  5053.3 1358.42
  5058.8 1361.17  5075.6 1364.48  5081.2 1366.93  5089.8 1366.56  5103.5 1367.77
  5120.2 1367.97  5125.8 1369.33  5231.5 1370.82  5304.4 1371.27  5358.4 1372.75
  5371.3 1374.06  5393.7 1381.19  5410.4 1390.64    5416 1392.67  5426.2 1393.49
#Mann= 4 ,-1 , 0
  4674.7    .035       0  5000.9    .035       0  5016.3    .035       0
  5231.5     .07       0
Bank Sta=5000.9,5016.3
XS Rating Curve= 0 ,0
Exp/Cntr=0.3,0.1

Type RM Length L Ch R = 1 ,2766    ,443,443,443
BEGIN DESCRIPTION:
REEH CREEK 4.0
END DESCRIPTION:
XS GIS Cut Line= 3
        2051075.     13917674.97        2050975.       13916875.
        2050375.       13916625.
#Sta/Elev= 30
  4189.5 1366.89  4654.8 1365.26    4774 1366.71  4844.5 1364.14  4884.8 1365.14
  4933.1 1358.34  4945.3 1357.22  4957.9 1352.42  4975.5 1350.03  4985.5 1346.26
    4986 1345.76  5000.9 1346.26  5010.3 1349.81  5030.2 1350.67  5049.9 1351.17
  5093.2  1359.6  5134.9 1362.95  5174.2 1364.35  5217.2 1365.89  5223.2 1367.42
  5277.4 1365.99    5461  1366.1  5506.5 1366.67  5548.2 1369.45  5554.2  1372.3
  5559.6 1372.55    5578 1381.97  5583.4 1383.15  5601.8 1391.53  5645.7 1395.73
#Mann= 8 ,-1 , 0
  4189.5     .07       0  4654.8    .035       0  4933.1     .07       0
  4985.5     .05       0  5000.9     .07       0  5030.2     .12       0
  5174.2    .035       0    5461     .07       0
Bank Sta=4985.5,5000.9
XS Rating Curve= 0 ,0
Exp/Cntr=0.3,0.1

Type RM Length L Ch R = 1 ,2323    ,533,533,533
BEGIN DESCRIPTION:
REEH CREEK 3.0
END DESCRIPTION:
XS GIS Cut Line= 3
      2051400.72     13916634.28        2051225.       13916525.
      2050720.17      13916384.3
#Sta/Elev= 30
  4788.5 1361.72  4820.1 1362.79  4835.5 1362.32  4936.6 1363.88  4945.3 1362.43
  4960.1 1356.23  4972.4 1350.25  4981.9 1347.02  4987.8 1346.96  4992.5  1344.6
    4998  1344.6  4998.1 1342.53  4998.6 1342.03    5013 1342.03  5013.5 1342.53
  5017.7 1348.43  5026.6 1349.11    5037 1348.72  5046.7 1349.11  5057.7 1350.31
  5078.5 1351.19  5171.9 1359.64  5206.9 1361.64  5233.3 1362.51    5255 1364.17
  5272.7 1364.29  5277.8 1363.67    5312 1363.39  5387.3 1363.99  5519.5 1363.93
#Mann= 5 ,-1 , 0
  4788.5    .035       0  4998.1    .035       0  5013.5    .035       0
  5206.9     .07       0  5387.3    .035       0
Bank Sta=4998.1,5013.5
XS Rating Curve= 0 ,0
Exp/Cntr=0.3,0.1

Type RM Length L Ch R = 1 ,1790    ,805,805,805
BEGIN DESCRIPTION:
REEH CREEK 2.0
END DESCRIPTION:
XS GIS Cut Line= 3
      2051496.83     13916366.39      2051424.05     13916059.61
       2050438.4     13916129.18
#Sta/Elev= 30
  4684.7 1361.31  4746.8  1361.3  4768.4 1361.48  4797.5 1359.69    4830 1356.57
  4844.8 1353.62  4892.2 1347.77  4929.3 1346.22  4943.1 1344.43  4971.5 1344.15
  4984.2 1341.74  5002.1 1340.49  5002.6 1339.99  5017.6 1340.49  5029.1 1343.89
  5039.1 1345.26  5069.2 1355.74  5079.2 1356.84  5159.4 1358.01  5239.6 1361.51
  5309.8 1360.18  5410.1 1360.14  5626.7 1361.61  5727.6 1361.48  5831.1 1361.99
  5881.2 1365.75  5901.3 1372.73  5931.4 1389.01  5951.4 1392.62  5988.1 1395.62
#Mann= 6 ,-1 , 0
  4684.7    .035       0  4746.8     .07       0  5002.1     .05       0
  5017.6     .07       0  5626.7    .035       0  5727.6     .07       0
Bank Sta=5002.1,5017.6
XS Rating Curve= 0 ,0
Exp/Cntr=0.3,0.1

Type RM Length L Ch R = 1 ,985     ,0,0,0
BEGIN DESCRIPTION:
REEH CREEK 1.0
END DESCRIPTION:
XS GIS Cut Line= 3
      2051525.04     13915492.68      2051174.56     13915380.18
      2050540.61     13915398.09
#Sta/Elev= 30
  4631.9 1355.72  4772.6  1353.8  4804.8 1354.12  4810.5 1352.68  4874.2 1349.23
  4885.1 1347.88  4901.1 1344.93  4938.5 1342.78  4965.3 1340.03  4973.4 1339.86
    4989 1337.84  4989.4 1335.56  4989.9 1335.06  5004.4 1335.06  5004.9 1335.56
  5019.6 1337.82  5039.6 1338.51  5049.6 1341.22  5059.6 1346.72  5069.6  1351.1
  5079.6 1354.22  5089.6 1356.11  5400.7    1356  5489.8 1358.27  5499.8 1359.88
  5509.8 1363.33  5519.8 1367.66  5539.8 1379.31  5559.8 1386.91  5634.2  1391.7
#Mann= 6 ,-1 , 0
  4631.9    .035       0  4885.1     .07       0  4973.4    .035       0
  4989.4    .035       0  5004.9    .035       0  5400.7     .07       0
Bank Sta=4989.4,5004.9
XS Rating Curve= 0 ,0
Exp/Cntr=0.3,0.1

Chan Stop Cuts=-1
Use User Specified Reach Order=0
Composite Channel Slope=5