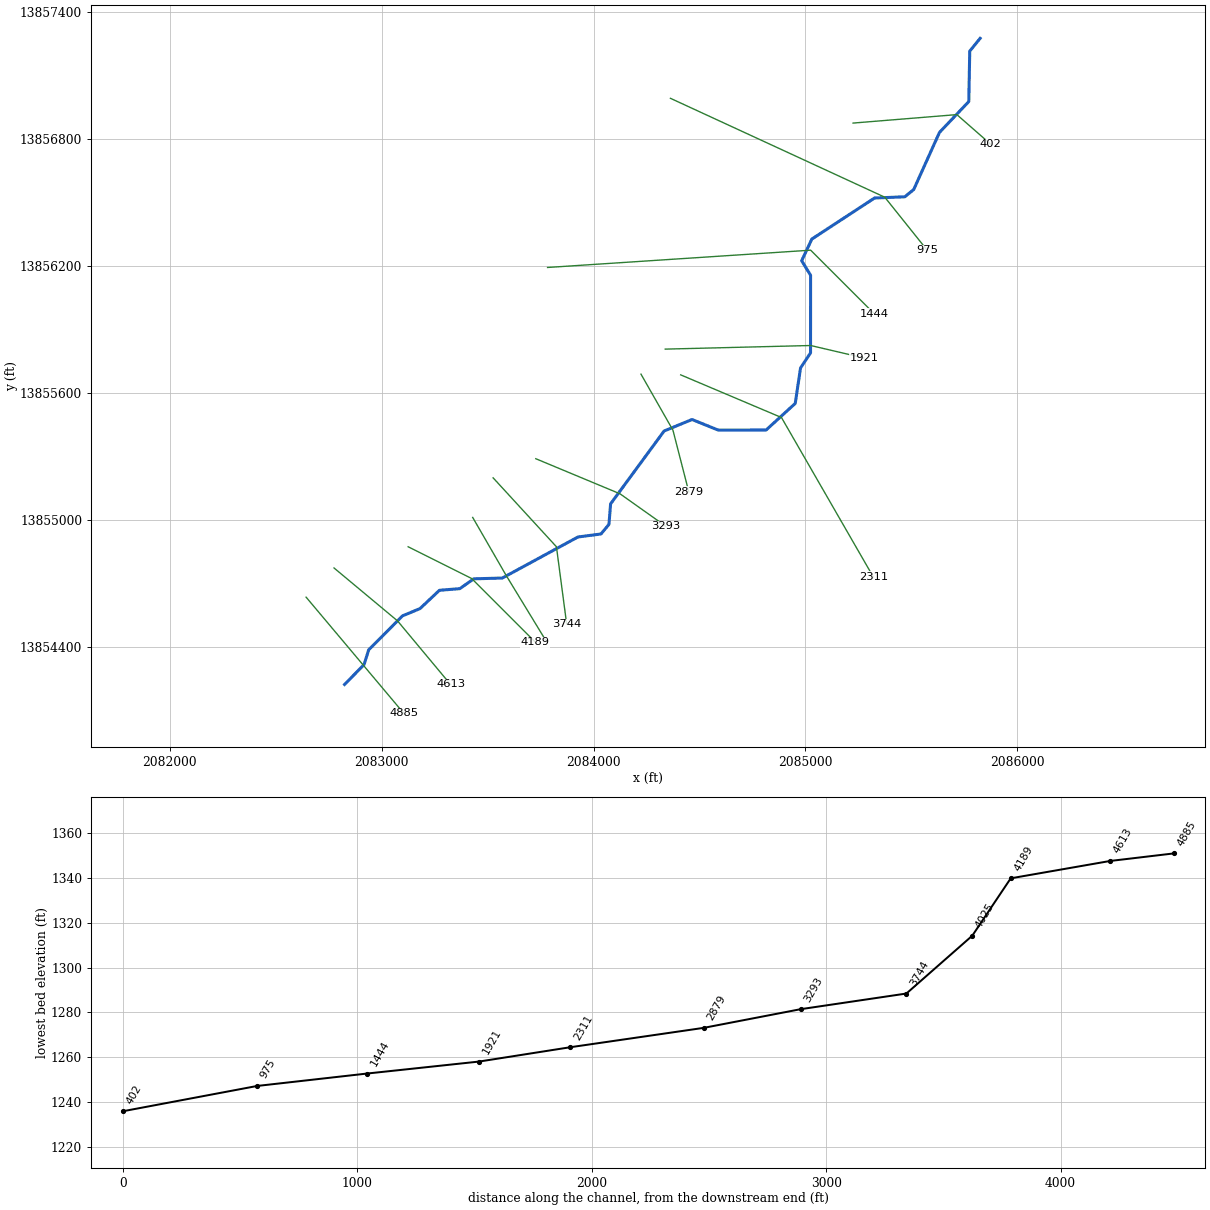
--- ROCK CREEK.prj (project) ---

Proj Title=ROCK CREEK Base Level Engineering
Current Plan=p01
Default Exp/Contr=0.3,0.1
English Units
Geom File=g01
Flow File=f01
Plan File=p01
BEGIN DESCRIPTION:
ROCK CREEK
END DESCRIPTION:

--- ROCK CREEK.p01 (plan) ---

Plan Title=Multiple Run
Short Identifier=Multiple
Geom File=g01
Flow File=f01
Subcritical Flow
K Sum by GR= 0
Std Step Tol= 0.01
Critical Tol= 0.01
Num of Std Step Trials= 20
Max Error Tol= 0.3
Flow Tol Ratio= 0.001
Split Flow NTrial= 30
Split Flow Tol= 0.02
Split Flow Ratio= 0.02
Log Output Level= 0
Friction Slope Method= 1
Unsteady Friction Slope Method= 2
Unsteady Bridges Friction Slope Method= 1
Parabolic Critical Depth
Global Vel Dist=  1 , 1 , 1
Global Log Level= 0
CheckData=True
Encroach Param= -1, 0, 0, 0
BEGIN DESCRIPTION:
Multiple Run
END DESCRIPTION:

--- ROCK CREEK.f01 (steady flow) ---

Flow Title=Multiple
Number of Profiles=7
Profile Names=10-year,25-year,50-year,1pct_min,100-year,1pct_plu,500-year
River Rch & RM= ROCK CREEK,Reach-1,4885
    1452    2495    3503    2383    4755    9487    8661
Boundary for River Rch & Prof#=ROCK CREEK,Reach-1,1
Up Type=0
Dn Type=3
Dn Slope=0.005
Boundary for River Rch & Prof#=ROCK CREEK,Reach-1,2
Up Type=0
Dn Type=3
Dn Slope=0.005
Boundary for River Rch & Prof#=ROCK CREEK,Reach-1,3
Up Type=0
Dn Type=3
Dn Slope=0.005
Boundary for River Rch & Prof#=ROCK CREEK,Reach-1,4
Up Type=0
Dn Type=3
Dn Slope=0.005
Boundary for River Rch & Prof#=ROCK CREEK,Reach-1,5
Up Type=0
Dn Type=3
Dn Slope=0.005
Boundary for River Rch & Prof#=ROCK CREEK,Reach-1,6
Up Type=0
Dn Type=3
Dn Slope=0.005
Boundary for River Rch & Prof#=ROCK CREEK,Reach-1,7
Up Type=0
Dn Type=3
Dn Slope=0.005

--- ROCK CREEK.g01 (geometry) ---

Geom Title=Existing Conditions

River Reach=ROCK CREEK,Reach-1
Reach XY= 30
      2082825.00     13854225.00      2082916.89     13854318.93
      2082938.63     13854388.21      2083098.18     13854548.70
      2083181.04     13854583.18      2083272.58     13854669.46
      2083369.02     13854677.36      2083434.67     13854723.61
      2083569.48     13854727.36      2083926.59     13854921.17
      2084035.16     13854935.36      2084072.93     13854980.69
      2084080.54     13855077.42      2084333.19     13855421.33
      2084464.94     13855475.78      2084588.92     13855425.69
      2084814.57     13855426.05      2084952.14     13855551.47
      2084977.27     13855719.06      2085024.48     13855790.22
      2085024.67     13856156.78      2084982.53     13856225.01
      2085030.70     13856327.54      2085326.56     13856521.24
      2085469.33     13856526.99      2085511.56     13856561.36
      2085633.14     13856831.06      2085771.46     13856976.46
      2085775.96     13857214.60      2085825.00     13857275.00

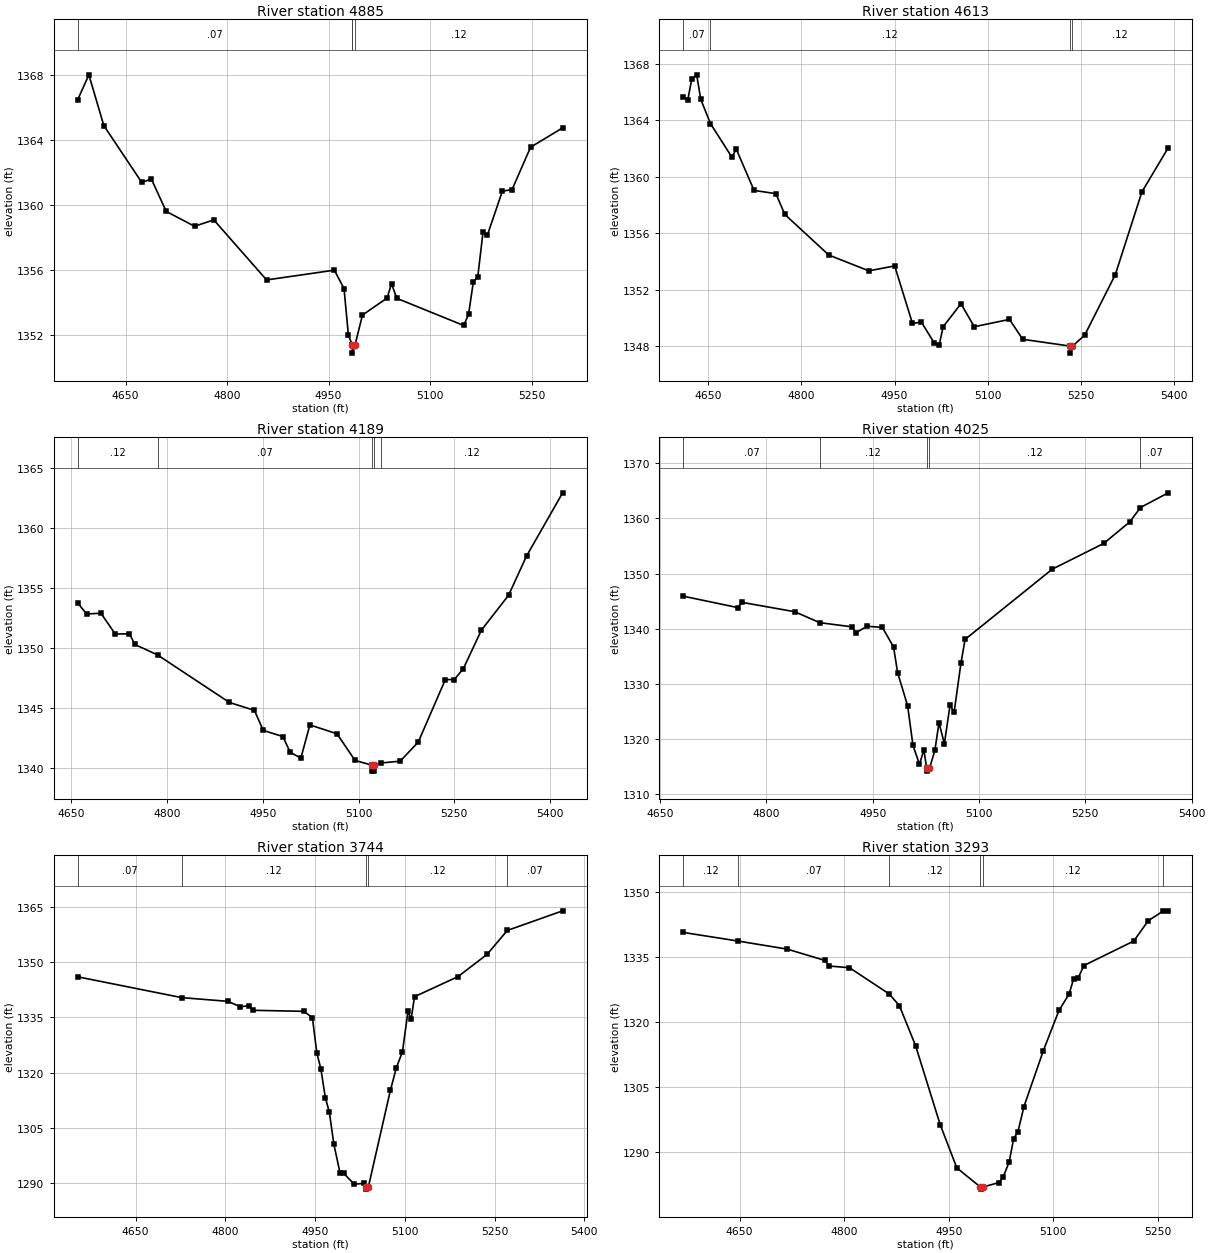
Type RM Length L Ch R = 1,4885,272,272,272
BEGIN DESCRIPTION:
ROCK CREEK 11.0
END DESCRIPTION:
XS GIS Cut Line= 2
      2082643.27     13854637.13      2083104.61     13854088.52
#Sta/Elev= 30
  4579.2 1366.47  4595.6 1367.99  4617.7 1364.87  4673.7 1361.38  4688.0 1361.58
  4710.0 1359.59  4751.8 1358.68  4780.3 1359.07  4858.3 1355.38  4958.5 1355.98
  4972.8 1354.85  4979.3 1351.98  4984.7 1351.41  4985.0 1351.38  4985.3 1350.88
  4989.0 1351.38  5000.1 1353.22  5036.5 1354.27  5043.0 1355.15  5050.8 1354.25
  5149.7 1352.58  5156.9 1353.26  5164.0 1355.26  5170.5 1355.56  5178.3 1358.32
  5184.8 1358.14  5206.9 1360.84  5221.2 1360.93  5248.6 1363.54  5296.0 1364.73
#Mann=4,-1,0
  4579.2    0.07       0  4984.7    0.12       0  4985.0    0.05       0
  4989.0    0.12       0
Bank Sta=4985,4989
Exp/Cntr=0.3,0.1

Type RM Length L Ch R = 1,4613,424,424,424
BEGIN DESCRIPTION:
ROCK CREEK 10.0
END DESCRIPTION:
XS GIS Cut Line= 3
      2082774.98     13854775.01      2083075.00     13854525.00
      2083324.97     13854225.03
#Sta/Elev= 30
  4609.7 1365.64  4616.9 1365.47  4623.4 1366.96  4631.2 1367.23  4637.7 1365.50
  4653.3 1363.78  4687.8 1361.40  4695.0 1361.96  4723.6 1359.04  4758.8 1358.81
  4773.1 1357.34  4844.0 1354.46  4908.5 1353.34  4950.1 1353.69  4978.8 1349.61
  4993.1 1349.71  5013.9 1348.23  5021.7 1348.07  5028.2 1349.38  5056.9 1351.01
  5078.3 1349.38  5135.0 1349.90  5156.4 1348.49  5232.5 1348.01  5232.8 1347.51
  5236.5 1348.01  5256.0 1348.77  5305.5 1353.07  5348.4 1358.94  5390.7 1362.06
#Mann=4,-1,0
  4609.7    0.07       0  4653.3    0.12       0  5232.5    0.05       0
  5236.5    0.12       0
Bank Sta=5232.5,5236.5
Exp/Cntr=0.3,0.1

Type RM Length L Ch R = 1,4189,164,164,164
BEGIN DESCRIPTION:
ROCK CREEK 9.0
END DESCRIPTION:
XS GIS Cut Line= 3
      2083125.04     13854874.98      2083425.00     13854725.00
      2083724.98     13854425.02
#Sta/Elev= 30
  4660.1 1353.77  4674.0 1352.87  4696.4 1352.93  4718.8 1351.20  4741.1 1351.22
  4749.5 1350.33  4785.0 1349.46  4897.6 1345.50  4936.8 1344.84  4950.7 1343.17
  4981.5 1342.66  4992.7 1341.36  5009.6 1340.86  5023.7 1343.63  5066.2 1342.89
  5094.5 1340.67  5120.7 1340.28  5121.0 1339.78  5124.5 1339.78  5124.7 1340.28
  5135.7 1340.46  5165.2 1340.61  5193.5 1342.20  5235.9 1347.40  5250.0 1347.41
  5264.2 1348.32  5292.4 1351.52  5334.9 1354.42  5363.2 1357.70  5419.7 1362.96
#Mann=5,-1,0
  4660.1    0.12       0  4785.0    0.07       0  5120.7    0.05       0
  5124.7    0.07       0  5135.7    0.12       0
Bank Sta=5120.7,5124.7
Exp/Cntr=0.3,0.1

Type RM Length L Ch R = 1,4025,281,281,281
BEGIN DESCRIPTION:
ROCK CREEK 7.5
END DESCRIPTION:
XS GIS Cut Line= 3
      2083429.79     13855013.33      2083588.17     13854738.73
      2083779.11     13854425.43
#Sta/Elev= 30
  4683.0 1345.89  4759.8 1343.83  4765.6 1344.78  4840.2 1343.08  4875.4 1341.10
  4920.7 1340.35  4926.4 1339.27  4942.2 1340.46  4963.8 1340.23  4979.5 1336.70
  4985.3 1332.02  4999.3 1326.08  5006.9 1318.88  5016.1 1315.44  5022.3 1318.11
  5026.2 1314.72  5026.4 1314.22  5030.2 1314.72  5037.8 1317.99  5043.6 1322.98
  5051.2 1319.19  5059.1 1326.11  5065.0 1324.93  5074.6 1333.81  5080.4 1338.07
  5203.4 1350.79  5276.0 1355.45  5312.8 1359.36  5327.8 1361.95  5366.9 1364.61
#Mann=5,-1,0
  4683.0    0.07       0  4875.4    0.12       0  5026.2    0.05       0
  5030.2    0.12       0  5327.8    0.07       0
Bank Sta=5026.2,5030.2
Exp/Cntr=0.3,0.1

Type RM Length L Ch R = 1,3744,451,451,451
BEGIN DESCRIPTION:
ROCK CREEK 8.0
END DESCRIPTION:
XS GIS Cut Line= 3
      2083526.14     13855200.32      2083825.00     13854875.00
      2083873.32     13854509.64
#Sta/Elev= 30
  4553.5 1346.03  4727.2 1340.39  4804.4 1339.38  4825.4 1337.90  4839.6 1338.22
  4846.4 1336.95  4931.4 1336.67  4945.6 1334.96  4953.0 1325.36  4959.8 1321.03
  4967.2 1313.29  4974.0 1309.25  4981.4 1300.66  4991.9 1292.75  4997.8 1292.75
  5015.4 1289.80  5032.0 1290.00  5035.0 1288.95  5035.3 1288.45  5039.0 1288.95
  5076.0 1315.29  5086.0 1321.42  5096.1 1325.72  5105.4 1336.74  5110.5 1334.49
  5116.3 1340.65  5188.9 1346.08  5237.4 1352.10  5271.4 1358.61  5363.8 1363.93
#Mann=5,-1,0
  4553.5    0.07       0  4727.2    0.12       0  5035.0    0.05       0
  5039.0    0.12       0  5271.4    0.07       0
Bank Sta=5035,5039
Exp/Cntr=0.3,0.1

Type RM Length L Ch R = 1,3293,414,414,414
BEGIN DESCRIPTION:
ROCK CREEK 7.0
END DESCRIPTION:
XS GIS Cut Line= 3
      2083727.50     13855290.62      2084125.00     13855125.00
      2084341.04     13854971.92
#Sta/Elev= 30
  4569.4 1340.72  4648.1 1338.73  4718.4 1336.87  4772.5 1334.26  4778.5 1332.97
  4807.7 1332.58  4864.4 1326.55  4879.2 1323.85  4902.5 1314.58  4937.7 1296.39
  4961.6 1286.39  4995.3 1281.98  4995.6 1281.48  4999.3 1281.98  5022.2 1283.00
  5028.3 1284.34  5036.8 1287.78  5043.1 1293.13  5049.2 1294.67  5057.9 1300.52
  5085.8 1313.47  5108.3 1322.78  5122.6 1326.47  5129.2 1330.04  5135.4 1330.14
  5144.0 1333.09  5215.4 1338.73  5236.3 1343.45  5257.1 1345.60  5264.8 1345.71
#Mann=6,-1,0
  4569.4    0.12       0  4648.1    0.07       0  4864.4    0.12       0
  4995.3    0.05       0  4999.3    0.12       0  5257.1    0.07       0
Bank Sta=4995.3,4999.3
Exp/Cntr=0.3,0.1

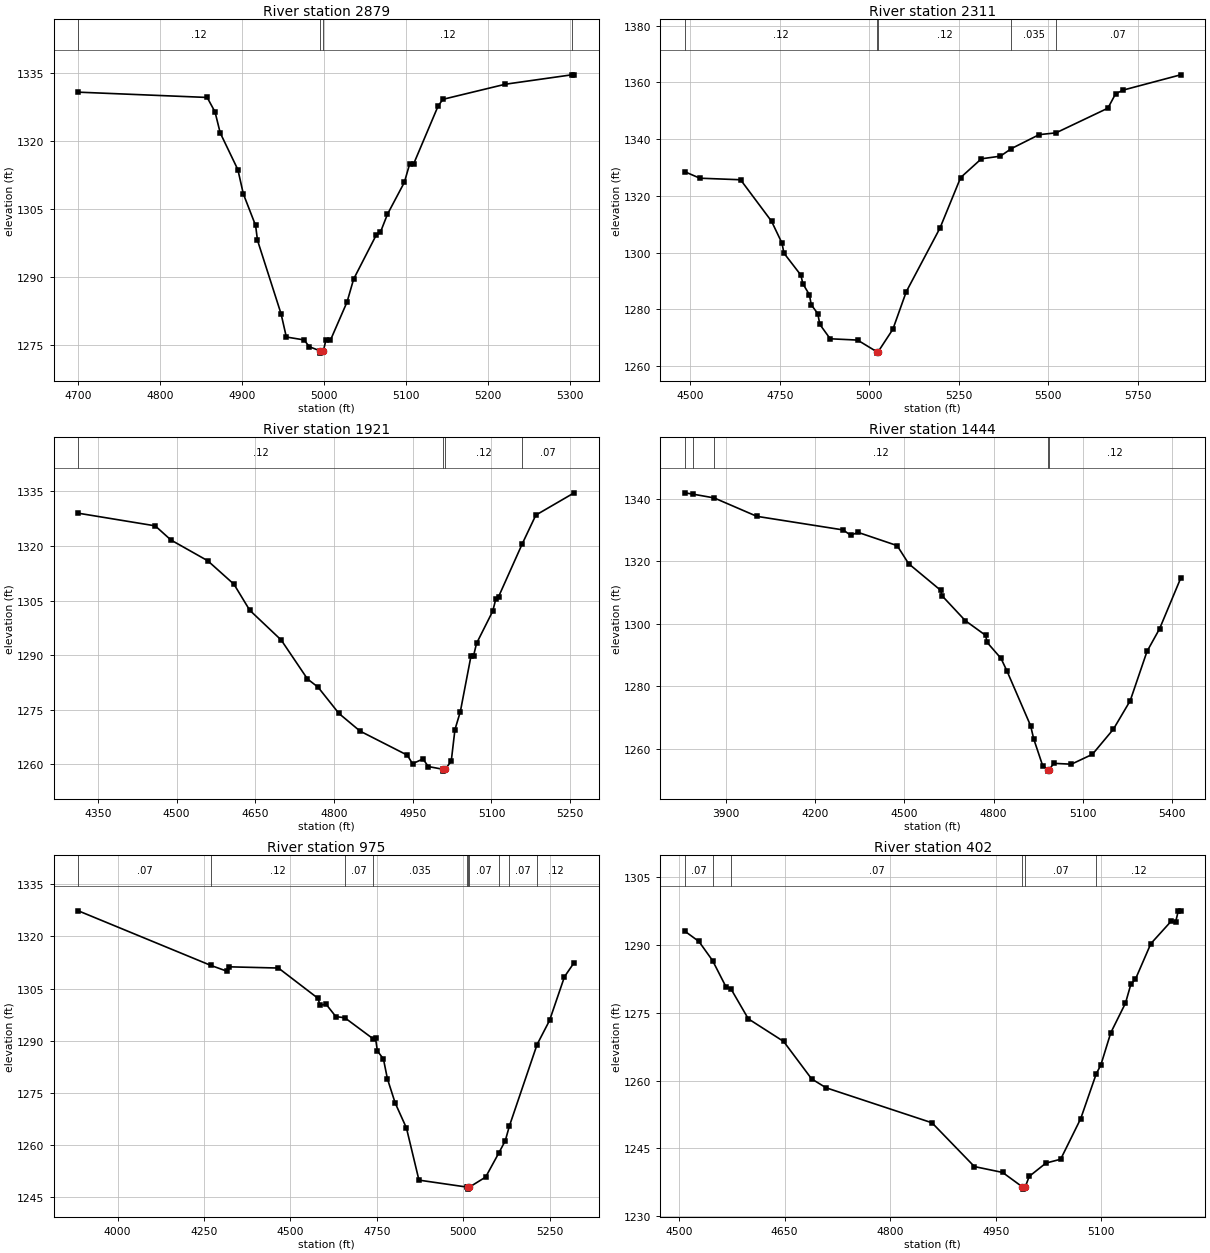
Type RM Length L Ch R = 1,2879,568,568,568
BEGIN DESCRIPTION:
ROCK CREEK 6.0
END DESCRIPTION:
XS GIS Cut Line= 3
      2084224.05     13855689.92      2084375.00     13855425.00
      2084449.75     13855134.37
#Sta/Elev= 30
  4700.0 1330.81  4857.2 1329.64  4866.8 1326.44  4873.1 1321.82  4894.7 1313.67
  4901.3 1308.35  4916.3 1301.35  4918.6 1298.09  4947.4 1281.82  4953.8 1276.71
  4975.4 1276.07  4981.9 1274.56  4995.0 1273.65  4995.2 1273.15  4999.0 1273.65
  5002.0 1275.96  5007.5 1275.96  5027.9 1284.45  5035.9 1289.50  5063.4 1299.21
  5068.6 1299.86  5077.2 1303.84  5097.8 1310.88  5104.1 1314.84  5109.3 1315.03
  5139.1 1327.79  5144.9 1329.23  5221.2 1332.57  5302.0 1334.64  5305.0 1334.64
#Mann=4,-1,0
  4700.0    0.12       0  4995.0    0.05       0  4999.0    0.12       0
  5302.0    0.07       0
Bank Sta=4995,4999
Exp/Cntr=0.3,0.1

Type RM Length L Ch R = 1,2311,390,390,390
BEGIN DESCRIPTION:
ROCK CREEK 5.0
END DESCRIPTION:
XS GIS Cut Line= 3
      2084411.53     13855686.45      2084887.25     13855485.05
      2085320.66     13854732.65
#Sta/Elev= 30
  4484.9 1328.52  4526.9 1326.24  4640.7 1325.69  4727.2 1311.05  4756.3 1303.35
  4761.8 1299.81  4809.1 1292.06  4814.6 1289.04  4832.8 1285.16  4838.2 1281.58
  4856.5 1278.43  4861.9 1274.70  4891.0 1269.60  4967.5 1269.14  5021.0 1265.04
  5021.2 1264.54  5025.0 1265.04  5066.1 1272.97  5103.4 1286.18  5197.7 1308.67
  5255.4 1326.47  5313.2 1333.08  5366.4 1334.01  5397.2 1336.69  5474.7 1341.60
  5521.6 1342.23  5666.6 1350.94  5688.2 1356.01  5709.7 1357.33  5869.8 1362.70
#Mann=5,-1,0
  4484.9    0.12       0  5021.0    0.05       0  5025.0    0.12       0
  5397.2   0.035       0  5521.6    0.07       0
Bank Sta=5021,5025
Exp/Cntr=0.3,0.1

Type RM Length L Ch R = 1,1921,477,477,477
BEGIN DESCRIPTION:
ROCK CREEK 4.0
END DESCRIPTION:
XS GIS Cut Line= 3
      2084338.61     13855807.97      2085025.00     13855825.00
      2085276.13     13855766.30
#Sta/Elev= 30
  4313.0 1328.98  4459.4 1325.51  4489.4 1321.62  4559.5 1315.92  4609.5 1309.46
  4639.5 1302.33  4699.5 1294.14  4749.5 1283.45  4769.5 1281.22  4809.5 1273.97
  4849.6 1269.14  4939.6 1262.53  4949.6 1260.18  4969.6 1261.48  4979.6 1259.40
  5007.9 1258.64  5008.1 1258.14  5011.9 1258.64  5023.4 1260.91  5030.4 1269.54
  5040.7 1274.49  5060.8 1289.63  5065.9 1289.84  5071.5 1293.21  5102.3 1302.05
  5108.4 1305.48  5113.6 1306.07  5158.9 1320.66  5184.5 1328.46  5257.5 1334.58
#Mann=4,-1,0
  4313.0    0.12       0  5007.9    0.05       0  5011.9    0.12       0
  5158.9    0.07       0
Bank Sta=5007.9,5011.9
Exp/Cntr=0.3,0.1

Type RM Length L Ch R = 1,1444,469,469,469
BEGIN DESCRIPTION:
ROCK CREEK 3.0
END DESCRIPTION:
XS GIS Cut Line= 3
      2083783.09     13856193.38      2085025.00     13856275.00
      2085325.03     13855974.97
#Sta/Elev= 30
  3760.9 1341.97  3787.6 1341.56  3859.6 1340.34  4003.3 1334.44  4294.0 1330.08
  4319.1 1328.38  4344.1 1329.30  4475.6 1325.06  4514.4 1319.26  4622.0 1310.75
  4627.0 1308.97  4704.8 1301.04  4773.4 1296.31  4778.4 1294.05  4825.1 1288.95
  4845.1 1284.93  4924.8 1267.37  4935.3 1263.14  4965.4 1254.57  4983.4 1253.31
  4983.7 1252.81  4987.4 1253.31  5003.0 1255.30  5062.1 1255.03  5132.8 1258.19
  5203.5 1266.24  5260.1 1275.37  5316.6 1291.15  5359.0 1298.43  5429.8 1314.56
#Mann=5,-1,0
  3760.9    0.12       0  3787.6    0.07       0  3859.6    0.12       0
  4983.4    0.05       0  4987.4    0.12       0
Bank Sta=4983.4,4987.4
Exp/Cntr=0.3,0.1

Type RM Length L Ch R = 1,975,573,573,573
BEGIN DESCRIPTION:
ROCK CREEK 2.0
END DESCRIPTION:
XS GIS Cut Line= 3
      2084362.98     13856991.98      2085375.00     13856525.00
      2085574.99     13856275.02
#Sta/Elev= 30
  3886.2 1327.35  4269.5 1311.65  4316.5 1309.97  4322.0 1311.24  4465.2 1310.89
  4579.9 1302.16  4585.4 1300.17  4602.9 1300.50  4631.3 1296.92  4657.3 1296.58
  4738.9 1290.55  4746.1 1290.68  4751.6 1287.02  4769.0 1284.74  4780.5 1279.04
  4803.0 1272.06  4835.6 1264.87  4871.8 1249.87  5010.5 1247.87  5012.3 1247.78
  5012.6 1247.28  5016.5 1247.78  5064.8 1250.75  5102.7 1257.65  5121.6 1261.20
  5133.4 1265.41  5213.6 1288.88  5249.7 1295.81  5292.9 1308.39  5320.9 1312.46
#Mann=10,-1,0
  3886.2    0.07       0  4269.5    0.12       0  4657.3    0.07       0
  4738.9   0.035       0  5010.5    0.07       0  5012.3   0.035       0
  5016.5    0.07       0  5102.7   0.035       0  5133.4    0.07       0
  5213.6    0.12       0
Bank Sta=5012.3,5016.5
Exp/Cntr=0.3,0.1

Type RM Length L Ch R = 1,402,0,0,0
BEGIN DESCRIPTION:
ROCK CREEK 1.0
END DESCRIPTION:
XS GIS Cut Line= 3
      2085225.05     13856875.00      2085715.12     13856914.95
      2085875.02     13856774.98
#Sta/Elev= 30
  4508.3 1293.07  4528.3 1290.80  4547.7 1286.58  4566.6 1280.81  4573.8 1280.32
  4598.5 1273.68  4648.7 1268.67  4688.4 1260.40  4708.9 1258.43  4859.4 1250.68
  4919.6 1241.00  4959.7 1239.70  4987.7 1236.51  4988.0 1236.01  4991.9 1236.51
  4997.4 1238.82  5021.2 1241.77  5042.1 1242.62  5070.6 1251.60  5092.8 1261.58
  5099.1 1263.42  5113.3 1270.60  5134.2 1277.16  5141.8 1281.31  5148.4 1282.47
  5170.2 1290.31  5198.7 1295.21  5205.4 1295.10  5209.2 1297.57  5212.5 1297.57
#Mann=6,-1,0
  4508.3    0.07       0  4547.7   0.035       0  4573.8    0.07       0
  4987.7    0.05       0  4991.9    0.07       0  5092.8    0.12       0
Bank Sta=4987.7,4991.9
Exp/Cntr=0.3,0.1

Chan Stop Cuts=-1