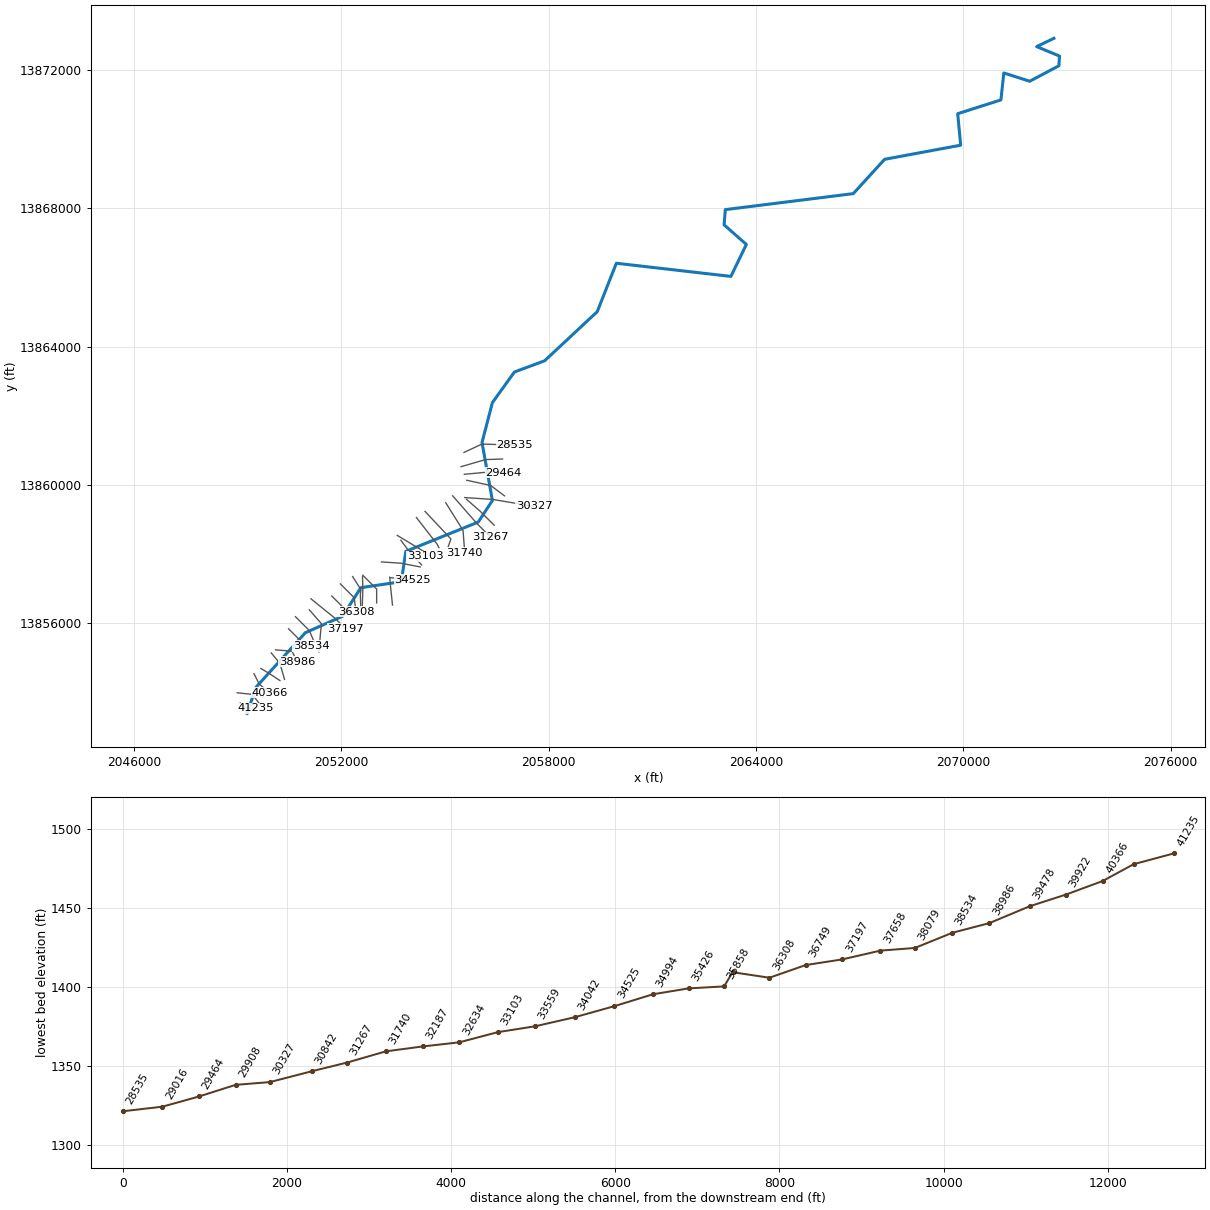
--- SABINAS CREEK.prj (project) ---

Proj Title=SABINAS CREEK Base Level Engineering
Current Plan=p01
Default Exp/Contr=0.3,0.1
English Units
Geom File=g01
Flow File=f01
Plan File=p01
Y Axis Title=Elevation
X Axis Title(PF)=Main Channel Distance
X Axis Title(XS)=Station
BEGIN DESCRIPTION:
SABINAS CREEK
END DESCRIPTION:
DSS Export Rating Curves= 0
DSS Export Rating Curve Sorted= 0
DSS Export Volume Flow Curves= 0
DXF OffsetX= 0
DXF OffsetY= 0
DXF ScaleX= 1
DXF ScaleY= 10

--- SABINAS CREEK.p01 (plan) ---

Plan Title=Multiple Run
Short Identifier=Multiple
Geom File=g01
Flow File=f01
Subcritical Flow
K Sum by GR= 0
Std Step Tol= 0.01
Critical Tol= 0.01
Num of Std Step Trials= 20
Max Error Tol= 0.3
Flow Tol Ratio= 0.001
Split Flow NTrial= 30
Split Flow Tol= 0.02
Split Flow Ratio= 0.02
Log Output Level= 0
Friction Slope Method= 1
Unsteady Friction Slope Method= 2
Unsteady Bridges Friction Slope Method= 1
Parabolic Critical Depth
Global Vel Dist=  1 , 1 , 1
Global Log Level= 0
CheckData=True
Encroach Param= -1, 0, 0, 0
BEGIN DESCRIPTION:
Multiple Run
END DESCRIPTION:

--- SABINAS CREEK.f01 (steady flow) ---

Flow Title=Multiple
Program Version=4.10
Number of Profiles= 7
Profile Names=10-year,25-year,50-year,1pct_min,100-year,1pct_plu,500-year
River Rch & RM=SABINAS CREEK,Reach-1         ,41235
     831    1386    1909    1277    2548    5083    4480
River Rch & RM=SABINAS CREEK,Reach-1         ,38534
    2166    3811    5436    3752    7486   14936   14044
River Rch & RM=SABINAS CREEK,Reach-1         ,32634
    2397    4238    6063    4196    8373   16706   15798
River Rch & RM=SABINAS CREEK,Reach-1         ,31740
    2646    4698    6742    4677    9332   18621   17697
River Rch & RM=SABINAS CREEK,Reach-1         ,31267
    4117    7455   10838    7607   15178   30285   29471
River Rch & RM=SABINAS CREEK,Reach-1         ,27200
    4798    8724   12718    8946   17850   35615   34804
River Rch & RM=SABINAS CREEK,Reach-1         ,23165
    5368    9800   14325   10099   20150   40205   39471
River Rch & RM=SABINAS CREEK,Reach-1         ,22716
    6319   11582   16974   11991   23926   47738   47058
River Rch & RM=SABINAS CREEK,Reach-1         ,17231
    6502   11912   17450   12320   24581   49045   48285
River Rch & RM=SABINAS CREEK,Reach-1         ,14530
    6678   12216   17877   12604   25149   50178   49270
River Rch & RM=SABINAS CREEK,Reach-1         ,9297
    6692   12238   17905   12621   25182   50245   49311
River Rch & RM=SABINAS CREEK,Reach-1         ,8795
    7339   13441   19683   13883   27700   55268   54304
River Rch & RM=SABINAS CREEK,Reach-1         ,3378
    7553   13832   20257   14286   28504   56873   55868
Boundary for River Rch & Prof#=SABINAS CREEK,Reach-1         , 1
Up Type= 0
Dn Type= 3
Dn Slope=0.003
Boundary for River Rch & Prof#=SABINAS CREEK,Reach-1         , 2
Up Type= 0
Dn Type= 3
Dn Slope=0.003
Boundary for River Rch & Prof#=SABINAS CREEK,Reach-1         , 3
Up Type= 0
Dn Type= 3
Dn Slope=0.003
Boundary for River Rch & Prof#=SABINAS CREEK,Reach-1         , 4
Up Type= 0
Dn Type= 3
Dn Slope=0.003
Boundary for River Rch & Prof#=SABINAS CREEK,Reach-1         , 5
Up Type= 0
Dn Type= 3
Dn Slope=0.003
Boundary for River Rch & Prof#=SABINAS CREEK,Reach-1         , 6
Up Type= 0
Dn Type= 3
Dn Slope=0.003
Boundary for River Rch & Prof#=SABINAS CREEK,Reach-1         , 7
Up Type= 0
Dn Type= 3
Dn Slope=0.003
DSS Import GetInterval= 0
DSS Import GetPeak= 0
DSS Import FillOption= 0

--- SABINAS CREEK.g01 (geometry) ---

Geom Title=Existing Conditions
Program Version=4.10

River Reach=SABINAS CREEK   ,Reach-1
Reach XY= 30
        2049275.       13853375.      2049532.86     13854131.17
      2050961.76     13855711.38      2052038.63     13856188.45
      2052567.98     13857015.99      2053738.25     13857188.61
      2053868.94     13858066.86      2055964.82     13858915.29
      2056374.62     13859540.16      2056074.19     13861220.43
        2056375.       13862375.      2057011.78     13863261.38
      2057884.68     13863585.76      2059408.54     13865008.25
      2059961.76     13866411.39       2063277.3     13866030.09
       2063724.8     13866956.74      2063080.83      13867522.7
      2063115.18     13867964.53      2066819.07     13868427.26
      2067726.43     13869421.93      2069927.55     13869830.73
      2069841.24     13870742.23      2071091.68     13871141.64
      2071176.03     13871921.86       2071925.1     13871682.28
      2072769.56     13872130.18      2072788.64     13872411.68
      2072125.93     13872685.49        2072625.       13872925.

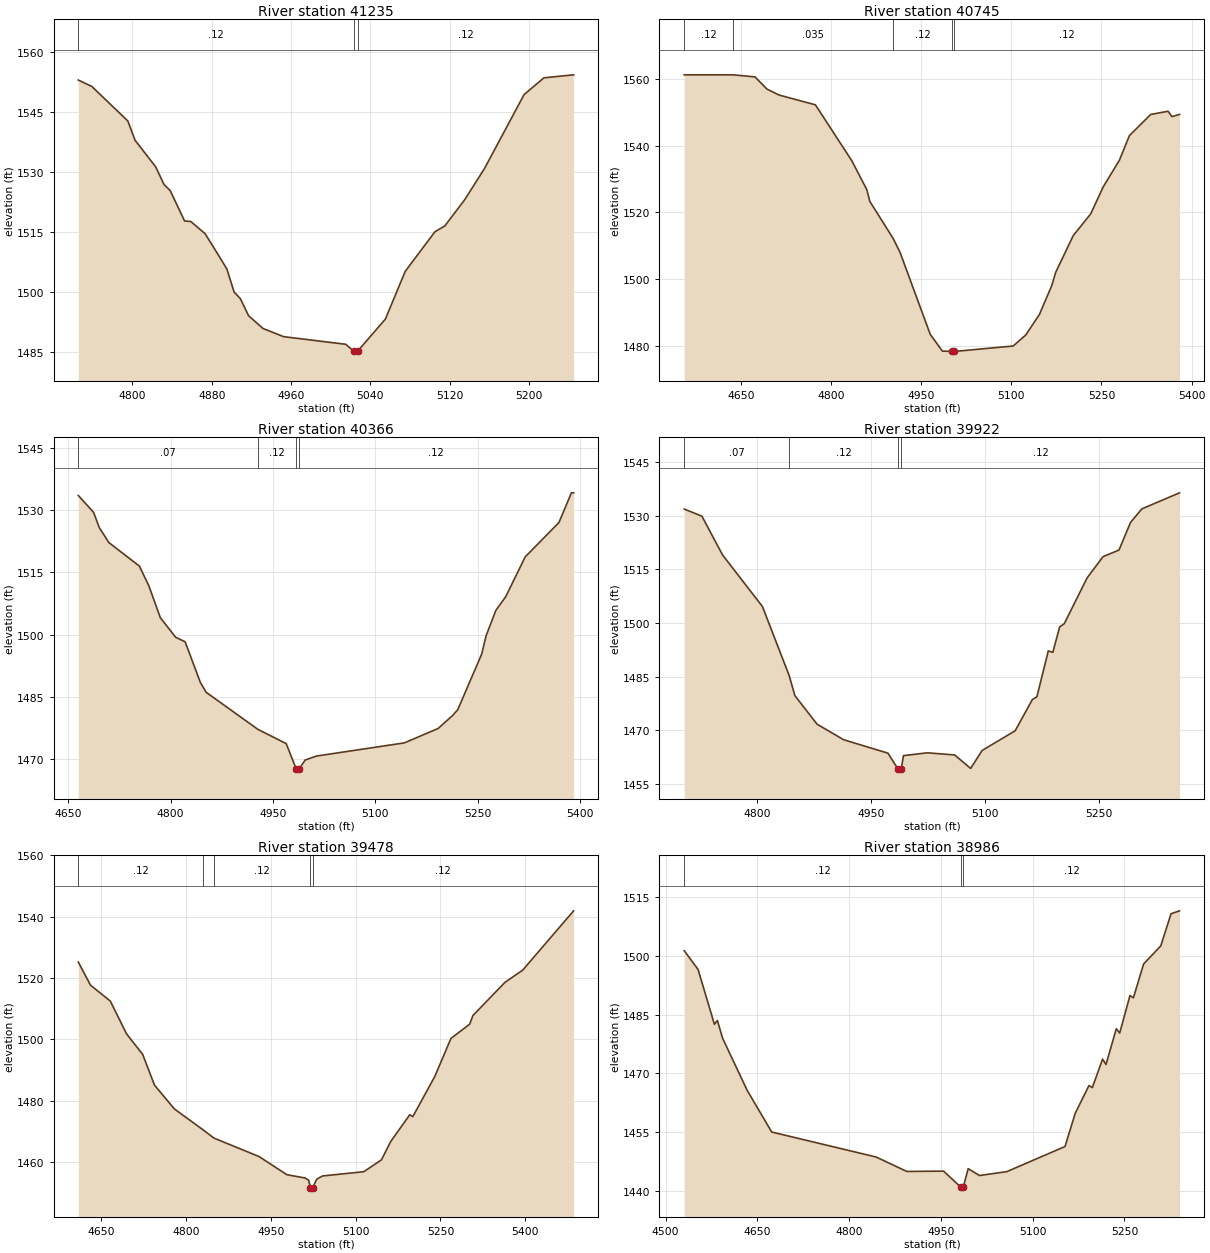
Type RM Length L Ch R = 1 ,41235   ,490,490,490
BEGIN DESCRIPTION:
SABINAS CREEK 83.0
END DESCRIPTION:
XS GIS Cut Line= 3
      2049074.99     13853675.01        2049275.       13853525.
      2049524.99       13853525.
#Sta/Elev= 30
  4745.3 1552.97  4758.9 1551.38  4795.3 1542.73  4802.6  1537.9  4823.4 1531.26
  4831.8 1526.84    4838 1525.33  4852.6  1517.7  4858.9 1517.57  4873.4 1514.49
    4888 1508.66  4895.3 1505.66  4902.6  1499.9  4908.9 1498.26  4917.2 1493.99
  4931.8 1490.79  4952.6 1488.75  5015.3 1486.84  5023.3 1485.13  5023.6 1484.63
  5027.3 1485.13  5055.3 1493.16  5075.3 1505.09  5105.3 1515.01  5115.3 1516.47
  5135.3 1523.01  5155.3 1530.82  5195.3 1549.34  5215.3 1553.53  5245.3 1554.28
#Mann= 3 ,-1 , 0
  4745.3     .12       0  5023.3     .05       0  5027.3     .12       0
Bank Sta=5023.3,5027.3
XS Rating Curve= 0 ,0
Exp/Cntr=0.3,0.1

Type RM Length L Ch R = 1 ,40745   ,379,379,379
BEGIN DESCRIPTION:
SABINAS CREEK 82.0
END DESCRIPTION:
XS GIS Cut Line= 3
      2048987.91     13853971.16      2049425.44     13853926.02
      2049658.09     13853620.46
#Sta/Elev= 30
    4556 1561.25  4637.3 1561.25  4673.7 1560.63  4693.8 1556.95  4713.9 1555.18
  4774.2 1552.26  4834.6 1535.54  4859.7 1526.82  4864.7 1523.32  4903.6 1512.16
    4915 1508.02  4965.2 1483.45  4985.4 1478.42  5001.4 1478.31  5001.7 1477.81
  5005.4 1478.31  5103.2 1479.95    5124 1483.23  5146.8 1489.38  5167.6 1498.18
  5173.9 1502.03    5203 1513.02  5232.1 1519.56  5252.9 1527.64  5279.9 1535.66
  5296.5 1543.02  5331.9 1549.37  5360.9 1550.33  5367.2 1548.72  5379.9 1549.39
#Mann= 5 ,-1 , 0
    4556     .12       0  4637.3    .035       0  4903.6     .12       0
  5001.4     .05       0  5005.4     .12       0
Bank Sta=5001.4,5005.4
XS Rating Curve= 0 ,0
Exp/Cntr=0.3,0.1

Type RM Length L Ch R = 1 ,40366   ,444,444,444
BEGIN DESCRIPTION:
SABINAS CREEK 81.0
END DESCRIPTION:
XS GIS Cut Line= 3
      2049474.99     13854525.03        2049625.       13854225.
      2049925.03     13853974.97
#Sta/Elev= 30
  4664.8 1533.51  4687.2 1529.45  4695.6 1525.76  4709.6 1522.17  4754.3 1516.51
  4768.3 1511.72    4785 1504.09  4807.4 1499.38  4821.4 1498.27  4843.7 1488.49
  4852.1 1486.13  4928.1 1477.18  4969.5 1473.76  4984.3 1467.63  4984.5 1467.13
  4988.3 1467.63  4997.4 1469.81  5013.9 1470.76  5142.8 1473.93  5192.2  1477.4
  5213.1 1480.48  5220.9 1481.89    5256  1495.3  5262.5 1499.73  5276.9 1505.87
  5291.2 1509.11  5319.8 1518.72  5369.3    1527  5387.5 1534.15  5390.8 1534.15
#Mann= 4 ,-1 , 0
  4664.8     .07       0  4928.1     .12       0  4984.3     .05       0
  4988.3     .12       0
Bank Sta=4984.3,4988.3
XS Rating Curve= 0 ,0
Exp/Cntr=0.3,0.1

Type RM Length L Ch R = 1 ,39922   ,444,444,444
BEGIN DESCRIPTION:
SABINAS CREEK 80.0
END DESCRIPTION:
XS GIS Cut Line= 3
      2049675.04     13854674.98        2049925.       13854525.
      2050225.04     13854324.98
#Sta/Elev= 30
  4704.2 1531.89  4727.5  1529.9  4754.7 1519.05  4807.2 1504.63  4842.4 1485.32
  4849.9 1479.73  4879.1 1471.74  4914.1  1467.4  4972.4 1463.64  4985.9 1459.12
  4986.2 1458.62  4989.9 1459.12  4992.8 1462.95  5024.2 1463.74  5060.3 1463.14
  5081.3 1459.37  5096.4  1464.4  5139.9  1469.9  5162.5 1478.63  5168.5 1479.41
  5183.5 1492.22  5189.5 1491.85  5198.5 1498.96  5204.5 1499.83  5234.6 1512.64
  5255.6 1518.59  5276.6 1520.43  5291.7 1528.13  5306.7 1531.94  5356.3 1536.43
#Mann= 4 ,-1 , 0
  4704.2     .07       0  4842.4     .12       0  4985.9     .05       0
  4989.9     .12       0
Bank Sta=4985.9,4989.9
XS Rating Curve= 0 ,0
Exp/Cntr=0.3,0.1

Type RM Length L Ch R = 1 ,39478   ,492,492,492
BEGIN DESCRIPTION:
SABINAS CREEK 79.0
END DESCRIPTION:
XS GIS Cut Line= 3
        2049975.       13855125.        2050225.       13854825.
      2050358.99     13854358.26
#Sta/Elev= 30
  4609.5 1525.25    4631 1517.72  4666.1 1512.52  4694.8 1501.83  4723.4 1495.12
  4744.2 1485.12  4779.4 1477.34  4829.9 1470.56  4849.4 1467.83  4929.1 1461.81
  4978.5 1455.88  5010.4 1454.82  5016.9 1454.11  5020.1 1451.68  5020.3 1451.18
  5024.1 1451.68  5031.2 1454.42  5041.6 1455.48  5114.5 1456.86  5145.7 1460.73
  5162.2 1466.76  5195.9 1475.46  5201.1 1474.81    5240 1487.91  5268.6 1500.32
  5301.7 1504.98  5307.5  1507.8  5364.1 1518.62  5395.4 1522.59  5485.6 1541.95
#Mann= 5 ,-1 , 0
  4609.5     .12       0  4829.9     .07       0  4849.4     .12       0
  5020.1     .05       0  5024.1     .12       0
Bank Sta=5020.1,5024.1
XS Rating Curve= 0 ,0
Exp/Cntr=0.3,0.1

Type RM Length L Ch R = 1 ,38986   ,452,452,452
BEGIN DESCRIPTION:
SABINAS CREEK 78.0
END DESCRIPTION:
XS GIS Cut Line= 3
      2050102.51     13855214.22        2050575.       13855175.
      2050724.99     13854875.03
#Sta/Elev= 30
  4530.5  1501.3  4553.1 1496.55  4579.8 1482.56  4584.8  1483.5  4593.2    1479
  4633.3 1465.72  4673.5 1455.07  4844.1  1448.7  4894.2 1445.02  4954.4  1445.1
  4982.5 1441.01  4982.8 1440.51  4986.5 1441.01  4994.6 1445.73    5013 1443.98
  5057.7 1444.97  5152.8 1451.37  5169.5 1459.84  5191.9 1466.91  5197.5 1466.41
  5214.2 1473.66  5219.8 1472.29  5236.6  1481.4  5242.2 1480.31    5259 1489.89
  5264.6  1489.3  5281.3 1497.93  5309.3 1502.53  5326.1 1510.74    5340 1511.48
#Mann= 3 ,-1 , 0
  4530.5     .12       0  4982.5     .05       0  4986.5     .12       0
Bank Sta=4982.5,4986.5
XS Rating Curve= 0 ,0
Exp/Cntr=0.3,0.1

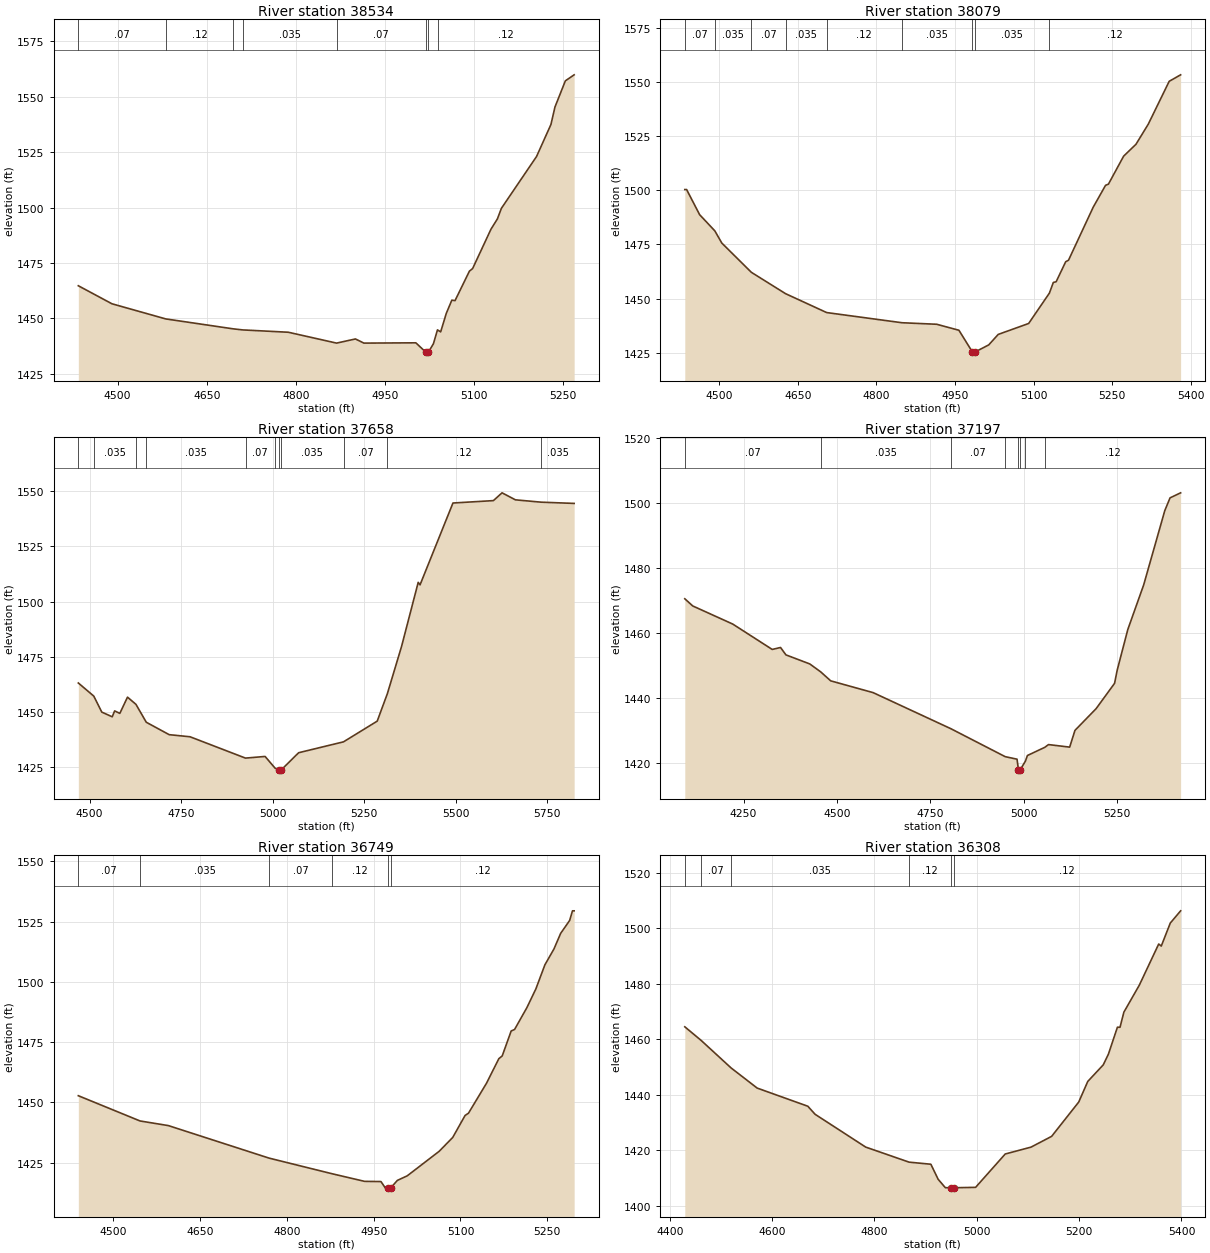
Type RM Length L Ch R = 1 ,38534   ,455,455,455
BEGIN DESCRIPTION:
SABINAS CREEK 77.0
END DESCRIPTION:
XS GIS Cut Line= 3
      2050474.97     13855825.03        2050875.       13855425.
      2051125.01     13855324.99
#Sta/Elev= 30
  4433.8 1464.77  4490.4 1456.64    4581 1449.81  4694.4 1445.34  4710.6 1444.85
  4787.4  1443.8  4868.7  1438.9  4900.5 1440.77  4914.7  1438.9  5002.2 1439.03
  5018.7 1434.88    5019 1434.38  5023.5 1434.88  5031.8 1438.62  5038.6 1444.87
  5039.9 1444.65    5044 1443.96  5053.4 1452.26  5062.8 1458.27  5068.2 1458.06
  5092.4 1471.35  5097.8 1472.52  5128.8 1490.32  5139.5  1494.9  5146.3 1499.71
  5205.5 1523.08  5229.7 1537.51  5236.5 1545.41    5254  1557.2  5268.8 1559.91
#Mann= 8 ,-1 , 0
  4433.8     .07       0    4581     .12       0  4694.4     .07       0
  4710.6    .035       0  4868.7     .07       0  5018.7     .05       0
  5023.5     .07       0  5039.9     .12       0
Bank Sta=5018.7,5023.5
XS Rating Curve= 0 ,0
Exp/Cntr=0.3,0.1

Type RM Length L Ch R = 1 ,38079   ,421,421,421
BEGIN DESCRIPTION:
SABINAS CREEK 76.0
END DESCRIPTION:
XS GIS Cut Line= 3
        2050675.       13856175.        2051075.       13855775.
      2051225.01     13855424.98
#Sta/Elev= 30
  4434.3 1500.32  4437.8 1500.32  4462.6 1488.73  4491.7 1481.23    4505 1475.61
  4561.3 1462.12  4626.6 1452.25  4705.1 1443.52    4849 1438.82  4915.1 1438.12
  4957.6 1435.35  4983.4 1425.29  4983.8 1424.79  4988.2 1425.29  5014.5 1428.59
  5032.6 1433.43  5090.7 1438.48  5130.3  1452.5  5137.8 1457.43  5143.2 1457.76
  5161.4 1466.99  5166.8  1467.7    5214 1492.21  5237.5 1502.28    5243 1502.82
    5272 1515.74  5295.6 1521.24  5319.1 1530.54    5359 1550.31  5380.8  1553.3
#Mann= 9 ,-1 , 0
  4434.3     .07       0  4491.7    .035       0  4561.3     .07       0
  4626.6    .035       0  4705.1     .12       0    4849    .035       0
  4983.4    .035       0  4988.2    .035       0  5130.3     .12       0
Bank Sta=4983.4,4988.2
XS Rating Curve= 0 ,0
Exp/Cntr=0.3,0.1

Type RM Length L Ch R = 1 ,37658   ,461,461,461
BEGIN DESCRIPTION:
SABINAS CREEK 75.0
END DESCRIPTION:
XS GIS Cut Line= 3
      2051074.99     13856375.01        2051425.       13855975.
      2051352.53     13855155.22
#Sta/Elev= 30
    4469 1463.08  4511.2 1457.13  4533.1 1449.87  4561.6 1447.75  4568.2 1450.42
  4582.4  1449.3  4603.3 1456.65  4626.4  1453.4  4654.6 1445.28  4717.2 1439.64
  4774.2 1438.69  4925.7 1429.01  4979.2 1429.77  5006.5 1424.45  5018.1 1423.61
  5018.5 1423.11    5023 1423.61  5070.8 1431.45  5193.4 1436.39  5285.5 1445.78
  5313.1 1458.18  5351.9 1479.59  5397.5 1508.72  5402.5 1507.58  5492.4 1544.69
  5602.9 1545.78  5626.5 1549.31  5663.1 1546.13  5733.5 1545.07  5823.5 1544.51
#Mann= 11 ,-1 , 0
    4469     .07       0  4511.2    .035       0  4626.4     .07       0
  4654.6    .035       0  4925.7     .07       0  5006.5    .035       0
  5018.1     .05       0    5023    .035       0  5193.4     .07       0
  5313.1     .12       0  5733.5    .035       0
Bank Sta=5018.1,5023
XS Rating Curve= 0 ,0
Exp/Cntr=0.3,0.1

Type RM Length L Ch R = 1 ,37197   ,448,448,448
BEGIN DESCRIPTION:
SABINAS CREEK 74.0
END DESCRIPTION:
XS GIS Cut Line= 3
      2051123.39     13856693.36        2051825.       13856125.
        2052125.       13855825.
#Sta/Elev= 30
  4092.7 1470.59    4114 1468.38  4221.1 1462.81  4326.7 1455.01    4349 1455.61
  4363.4 1453.34  4427.3 1450.55  4456.5 1448.11  4483.3 1445.35  4596.8 1441.73
  4805.2 1430.62  4950.3 1422.04    4982 1421.26  4985.8 1418.09  4986.2 1417.59
    4991 1418.09  5004.4 1420.65  5009.8 1422.39  5056.3 1424.91  5066.3 1425.75
  5122.9 1424.97  5137.1 1430.12  5193.6 1436.79  5243.1 1444.59  5250.2 1448.67
  5278.5 1461.13  5320.9 1474.82  5377.5 1497.69  5391.6 1501.62  5419.9 1503.17
#Mann= 8 ,-1 , 0
  4092.7     .07       0  4456.5    .035       0  4805.2     .07       0
  4950.3    .035       0  4985.8    .035       0    4991    .035       0
  5004.4     .07       0  5056.3     .12       0
Bank Sta=4985.8,4991
XS Rating Curve= 0 ,0
Exp/Cntr=0.3,0.1

Type RM Length L Ch R = 1 ,36749   ,441,441,441
BEGIN DESCRIPTION:
SABINAS CREEK 73.0
END DESCRIPTION:
XS GIS Cut Line= 3
      2051724.97     13856775.03        2052125.       13856375.
      2052375.02     13856224.99
#Sta/Elev= 30
  4439.3 1452.73  4546.1 1442.25  4594.9 1440.34  4769.3 1426.83  4878.4 1420.34
  4934.3  1417.2  4962.6 1417.12  4969.7 1414.58  4974.1 1414.48  4974.5 1413.98
  4979.4 1414.48  4990.9  1417.6  5007.9 1419.48  5063.3 1429.69  5086.7 1435.44
    5108 1444.54  5113.9 1445.48    5145 1457.89  5166.4 1468.11  5172.2 1469.23
  5187.7 1479.59  5193.6 1480.21  5214.9 1489.28  5230.5 1497.09    5246 1507.02
  5261.6 1513.57  5273.3 1520.09  5288.8 1525.43  5293.7 1529.43  5296.6 1529.43
#Mann= 6 ,-1 , 0
  4439.3     .07       0  4546.1    .035       0  4769.3     .07       0
  4878.4     .12       0  4974.1     .05       0  4979.4     .12       0
Bank Sta=4974.1,4979.4
XS Rating Curve= 0 ,0
Exp/Cntr=0.3,0.1

Type RM Length L Ch R = 1 ,36308   ,450,450,450
BEGIN DESCRIPTION:
SABINAS CREEK 72.0
END DESCRIPTION:
XS GIS Cut Line= 3
      2051975.01     13857124.99        2052375.       13856725.
        2052425.     13856324.98
#Sta/Elev= 30
  4429.5 1464.52  4461.1 1459.67    4520 1449.68  4570.9 1442.42  4669.9 1435.87
    4684 1432.98    4783 1421.13  4867.8  1415.7  4910.3 1414.95  4924.5 1409.53
  4938.6 1406.48  4950.1 1406.47  4950.5 1405.97  4955.4 1406.47  4997.7 1406.61
  5055.6 1418.64    5106 1421.12  5146.3 1425.01  5199.2 1437.38  5216.9 1444.82
  5247.1 1450.79  5257.2 1454.65  5274.8 1464.37  5279.9 1464.36  5287.4  1469.8
  5317.7 1479.59  5355.5 1494.39  5360.5 1493.65  5378.1 1501.94  5398.3 1506.36
#Mann= 6 ,-1 , 0
  4429.5    .035       0  4461.1     .07       0    4520    .035       0
  4867.8     .12       0  4950.1     .05       0  4955.4     .12       0
Bank Sta=4950.1,4955.4
XS Rating Curve= 0 ,0
Exp/Cntr=0.3,0.1

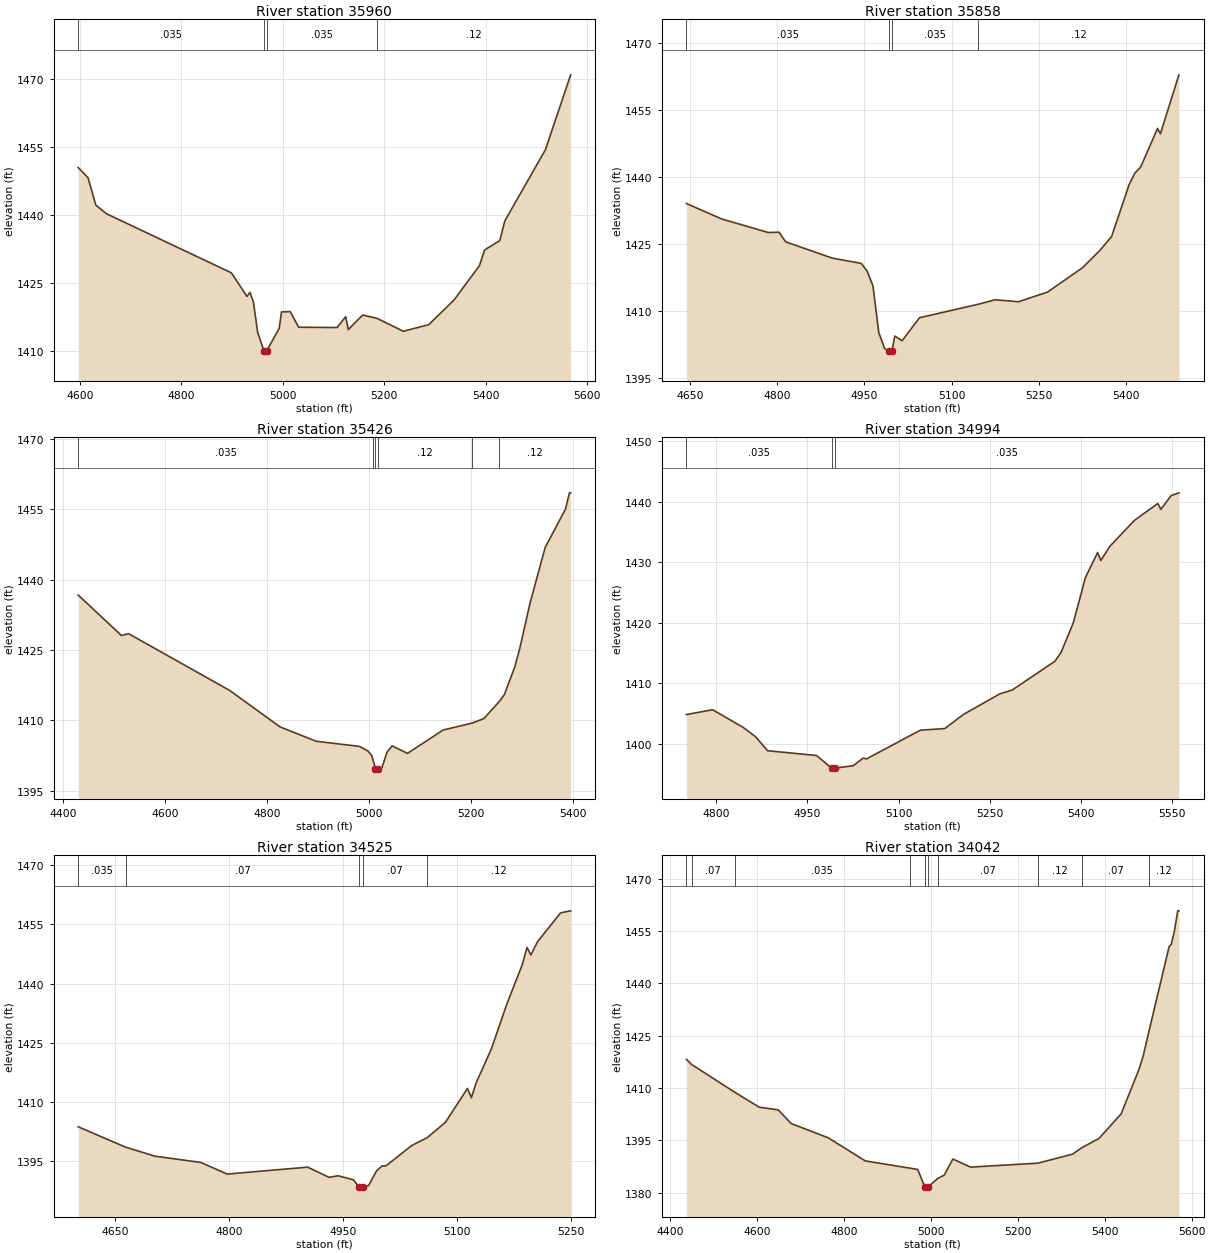
Type RM Length L Ch R = 1 ,35960   ,102,102,102
BEGIN DESCRIPTION:
SABINAS CREEK 71.5
END DESCRIPTION:
XS GIS Cut Line= 5
      2052330.19     13857337.39      2052544.77     13856996.03
      2052569.45     13856946.67      2052552.68     13856821.78
      2052564.82     13856435.27
#Sta/Elev= 30
  4596.8 1450.43  4616.3 1448.16  4631.6 1442.13  4652.8 1440.21    4899 1427.17
  4929.6 1421.98  4935.5 1422.87  4942.2 1420.82  4950.8 1414.01  4963.1 1409.95
  4963.5 1409.45  4968.5 1409.95  4993.2 1414.92  4997.7 1418.54  5014.8 1418.63
  5031.6 1415.17  5107.3  1415.1  5124.3 1417.49  5129.4 1414.64  5157.8 1417.87
  5185.8 1417.14    5238 1414.28    5288 1415.73  5338.1  1421.2  5388.1 1428.77
  5398.1 1432.22  5428.1 1434.29  5438.1 1438.65  5518.1 1454.35  5567.9 1470.89
#Mann= 4 ,-1 , 0
  4596.8    .035       0  4963.1    .035       0  4968.5    .035       0
  5185.8     .12       0
Bank Sta=4963.1,4968.5
XS Rating Curve= 0 ,0
Exp/Cntr=0.3,0.1

Type RM Length L Ch R = 1 ,35858   ,432,432,432
BEGIN DESCRIPTION:
SABINAS CREEK 71.0
END DESCRIPTION:
XS GIS Cut Line= 3
      2052615.91     13857335.73        2052625.       13856975.
      2052608.91     13856489.21
#Sta/Elev= 30
    4644 1434.02  4704.8 1430.55  4784.8 1427.52  4803.1 1427.59  4814.8 1425.42
  4894.8 1421.78  4944.8 1420.59  4954.8 1418.85  4964.8 1415.55  4974.8 1405.07
  4984.8 1401.51  4992.1 1400.98  4992.6 1400.48  4997.5 1400.98  5002.3 1404.31
  5014.9 1403.25  5044.9 1408.42  5145.4 1411.42  5174.9 1412.44    5215    1412
    5265 1414.17    5325 1419.61    5355  1423.5  5375.1  1426.6  5405.1 1438.19
  5415.1 1440.84  5425.1 1442.19  5454.1 1450.85  5459.1 1449.66  5490.9 1462.87
#Mann= 4 ,-1 , 0
    4644    .035       0  4992.1    .035       0  4997.5    .035       0
  5145.4     .12       0
Bank Sta=4992.1,4997.5
XS Rating Curve= 0 ,0
Exp/Cntr=0.3,0.1

Type RM Length L Ch R = 1 ,35426   ,435,435,435
BEGIN DESCRIPTION:
SABINAS CREEK 70.0
END DESCRIPTION:
XS GIS Cut Line= 3
      2052624.97     13857375.03        2053025.       13856975.
        2053025.     13856575.03
#Sta/Elev= 30
  4429.7  1436.7  4514.6 1428.09  4528.7 1428.47  4726.7  1416.4  4825.7 1408.63
  4896.4 1405.58  4981.3 1404.48  4997.9  1403.5  5005.4 1402.53  5008.4 1401.38
  5012.7 1399.72  5013.1 1399.22  5017.7 1399.22  5018.1 1399.72  5025.4 1399.96
  5035.4 1403.26  5045.4 1404.59  5075.4    1403  5145.4 1407.97  5202.8 1409.46
  5225.4 1410.42  5255.7 1414.07  5265.4 1415.51  5285.4 1421.28  5295.4 1425.24
  5315.4 1434.83  5345.4 1446.82  5385.4 1455.03  5392.9 1458.46  5395.4 1458.46
#Mann= 6 ,-1 , 0
  4429.7    .035       0  5008.4     .12       0  5012.7    .035       0
  5018.1     .12       0  5202.8     .07       0  5255.7     .12       0
Bank Sta=5012.7,5018.1
XS Rating Curve= 0 ,0
Exp/Cntr=0.3,0.1

Type RM Length L Ch R = 1 ,34994   ,469,469,469
BEGIN DESCRIPTION:
SABINAS CREEK 69.0
END DESCRIPTION:
XS GIS Cut Line= 3
      2053403.34     13857317.95        2053425.       13857075.
      2053483.24     13856512.22
#Sta/Elev= 30
  4751.3 1404.84  4794.4 1405.64  4844.6 1402.72  4864.7 1401.21  4884.8 1398.87
  4965.1 1398.08    4990    1396  4990.4  1395.5    4995  1395.5  4995.4    1396
  5025.4 1396.39  5042.1 1397.66  5047.1  1397.5  5135.9 1402.26  5176.2 1402.53
  5206.3 1404.83  5266.7 1408.27  5286.8 1408.88  5357.1 1413.64  5367.2 1415.08
  5387.3 1419.97  5407.4 1427.48  5427.4  1431.6  5432.5 1430.28  5447.6 1432.63
  5487.8  1436.9  5526.3 1439.69  5531.3 1438.72  5548.2 1440.99    5561 1441.45
#Mann= 3 ,-1 , 0
  4751.3    .035       0    4990    .035       0  4995.4    .035       0
Bank Sta=4990,4995.4
XS Rating Curve= 0 ,0
Exp/Cntr=0.3,0.1

Type RM Length L Ch R = 1 ,34525   ,483,483,483
BEGIN DESCRIPTION:
SABINAS CREEK 68.0
END DESCRIPTION:
XS GIS Cut Line= 3
      2053424.16     13857304.16        2053825.       13857275.
      2054068.15      13857242.6
#Sta/Elev= 30
  4601.9 1403.78  4664.3 1398.61    4703 1396.33  4763.2 1394.75  4797.6 1391.81
  4903.5 1393.56  4931.7 1390.98  4943.6 1391.38  4963.7 1390.35    4971  1388.5
  4971.4    1388  4976.5  1388.5  4983.8 1388.96  4993.8 1392.57  5001.3 1393.87
  5006.3 1393.87  5040.4 1399.06  5060.5 1401.01  5084.5 1404.89  5113.5 1413.48
  5118.6 1411.12  5124.9 1414.89    5145 1423.52  5165.2 1434.82  5185.4 1444.73
  5191.8 1449.16  5196.8 1447.26  5205.6  1450.6  5235.8 1457.89  5249.1 1458.41
#Mann= 5 ,-1 , 0
  4601.9    .035       0  4664.3     .07       0    4971     .05       0
  4976.5     .07       0  5060.5     .12       0
Bank Sta=4971,4976.5
XS Rating Curve= 0 ,0
Exp/Cntr=0.3,0.1

Type RM Length L Ch R = 1 ,34042   ,483,483,483
BEGIN DESCRIPTION:
SABINAS CREEK 67.0
END DESCRIPTION:
XS GIS Cut Line= 3
       2053164.4     13857760.75        2053725.       13857725.
      2054285.32     13857616.28
#Sta/Elev= 30
  4438.3  1418.2  4450.1 1416.75    4549 1408.81  4605.7 1404.49  4649.3 1403.72
  4679.4 1399.79  4764.5  1395.7  4849.7 1389.08  4951.5 1387.02    4970 1386.64
  4987.2 1381.49  4987.7 1380.99  4992.8 1381.49  5016.6  1384.1    5031 1384.99
    5051 1389.61  5091.7  1387.3  5246.6 1388.44    5326 1391.01  5347.5 1392.87
  5387.1 1395.53  5438.1 1402.61  5478.8 1415.26    5489 1419.34  5503.1 1426.89
  5548.2 1450.51  5553.2  1451.2  5560.3 1454.91  5568.1  1460.8  5570.8  1460.8
#Mann= 10 ,-1 , 0
  4438.3    .035       0  4450.1     .07       0    4549    .035       0
  4951.5     .12       0  4987.2     .05       0  4992.8     .12       0
  5016.6     .07       0  5246.6     .12       0  5347.5     .07       0
  5503.1     .12       0
Bank Sta=4987.2,4992.8
XS Rating Curve= 0 ,0
Exp/Cntr=0.3,0.1

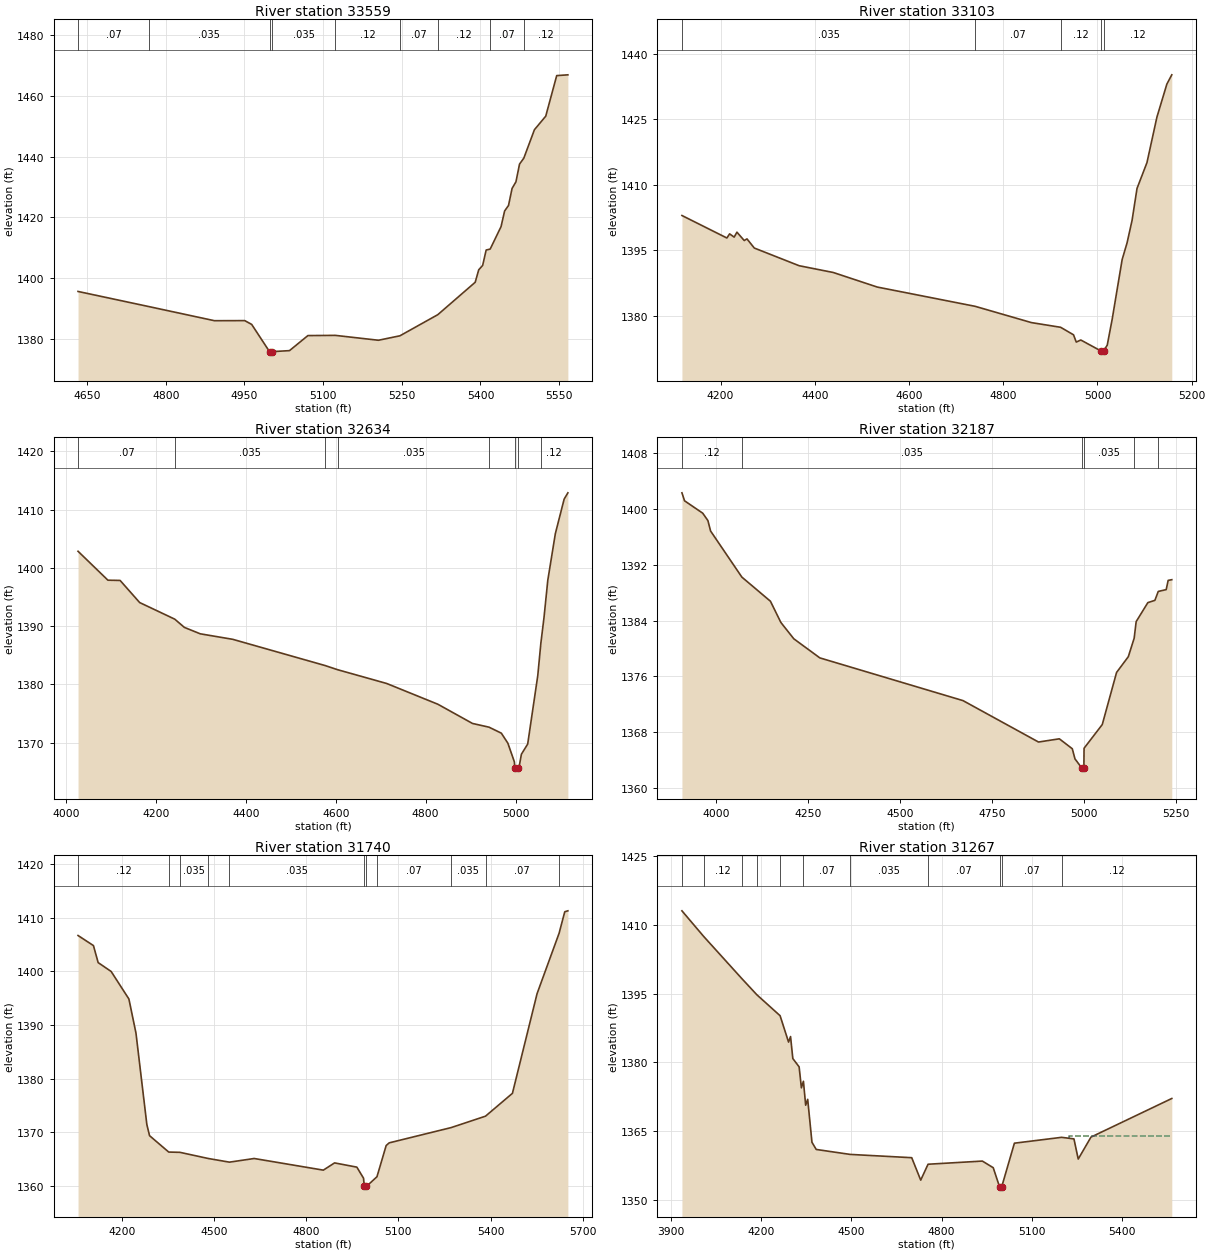
Type RM Length L Ch R = 1 ,33559   ,456,456,456
BEGIN DESCRIPTION:
SABINAS CREEK 66.0
END DESCRIPTION:
XS GIS Cut Line= 3
      2053724.96     13858389.51      2053949.75     13858089.22
      2054324.98     13857675.02
#Sta/Elev= 30
  4632.7 1395.57  4767.3  1390.6  4892.9 1385.93  4950.6 1385.96  4963.8 1384.71
  4997.8 1375.75  4998.2 1375.25  5003.4 1375.75  5035.9 1376.07    5071 1381.03
  5123.2  1381.1  5205.5 1379.49  5246.5 1380.96  5318.7 1387.92    5390  1398.6
  5396.7 1402.69  5404.2 1404.15  5410.9 1409.21  5418.6 1409.54  5439.3 1416.94
  5446.1 1422.09  5453.5 1423.89  5460.3 1429.51  5467.7  1431.7  5474.5 1437.52
  5482.7 1439.49  5502.9 1448.85  5524.5 1453.32  5545.4 1466.68  5566.7 1466.94
#Mann= 9 ,-1 , 0
  4632.7     .07       0  4767.3    .035       0  4997.8    .035       0
  5003.4    .035       0  5123.2     .12       0  5246.5     .07       0
  5318.7     .12       0  5418.6     .07       0  5482.7     .12       0
Bank Sta=4997.8,5003.4
XS Rating Curve= 0 ,0
Exp/Cntr=0.3,0.1

Type RM Length L Ch R = 1 ,33103   ,469,469,469
BEGIN DESCRIPTION:
SABINAS CREEK 65.0
END DESCRIPTION:
XS GIS Cut Line= 3
       2053619.9     13858530.18        2054375.       13858075.
        2054425.       13857925.
#Sta/Elev= 30
  4117.9    1403  4213.3 1397.86  4219.1  1398.8  4228.8 1398.06  4234.6 1399.19
  4250.1 1397.28    4256 1397.65  4271.5 1395.56  4366.6 1391.52  4439.1 1389.97
  4532.5 1386.64  4740.4 1382.23  4859.8 1378.51  4921.7 1377.44  4949.1 1375.72
  4954.9 1374.06  4964.6 1374.53  5007.3 1372.03  5007.7 1371.53    5013 1372.03
  5020.7 1373.35  5031.2  1379.3  5052.3 1392.92  5062.8 1396.75  5073.4  1401.9
  5083.9 1409.19    5105 1415.09  5126.1 1425.48  5147.2 1433.04  5157.7 1435.17
#Mann= 5 ,-1 , 0
  4117.9    .035       0  4740.4     .07       0  4921.7     .12       0
  5007.3     .05       0    5013     .12       0
Bank Sta=5007.3,5013
XS Rating Curve= 0 ,0
Exp/Cntr=0.3,0.1

Type RM Length L Ch R = 1 ,32634   ,447,447,447
BEGIN DESCRIPTION:
SABINAS CREEK 64.0
END DESCRIPTION:
XS GIS Cut Line= 3
      2054175.43     13859047.57        2054775.       13858275.
      2054824.98     13858175.03
#Sta/Elev= 30
  4026.8 1402.86  4093.3 1397.89  4120.4 1397.85  4163.9 1394.05  4241.9  1391.2
  4263.4 1389.78  4298.7 1388.68  4371.1 1387.73  4576.3 1383.23  4604.9  1382.5
  4713.3 1380.15  4827.3 1376.58  4904.3 1373.28  4941.1 1372.64  4968.5 1371.61
    4983 1369.89  4997.5 1366.68  4998.4 1365.59  4998.9 1365.09  5004.7 1365.59
  5007.5 1365.59  5013.1 1367.99  5027.1 1369.74  5049.5 1381.48  5056.4 1387.06
  5063.4 1391.48  5071.8 1397.86  5088.6 1405.88  5108.2 1411.82  5116.5  1412.9
#Mann= 8 ,-1 , 0
  4026.8     .07       0  4241.9    .035       0  4576.3     .07       0
  4604.9    .035       0  4941.1     .07       0  4998.4     .05       0
  5004.7     .07       0  5056.4     .12       0
Bank Sta=4998.4,5004.7
XS Rating Curve= 0 ,0
Exp/Cntr=0.3,0.1

Type RM Length L Ch R = 1 ,32187   ,447,447,447
BEGIN DESCRIPTION:
SABINAS CREEK 63.0
END DESCRIPTION:
XS GIS Cut Line= 3
      2054424.97     13859225.03        2055175.       13858425.
      2055095.57     13858203.75
#Sta/Elev= 30
  3907.8 1402.26  3914.9 1401.12  3964.3 1399.35  3978.4 1398.29  3985.7  1396.8
  4070.7 1390.21  4148.4 1386.76  4176.7 1383.73  4211.9 1381.39  4282.7 1378.66
    4672 1372.55  4877.2 1366.63  4933.8 1367.09    4969 1365.67  4976.3 1364.22
  4994.1 1362.97  4994.6 1362.47  5000.5 1362.97    5001 1365.74  5050.5 1369.13
  5089.4 1376.58  5121.3 1378.83  5137.2 1381.47  5142.7 1383.85  5174.4 1386.56
  5193.6 1386.89  5202.7 1388.16  5224.3 1388.42  5229.6 1389.74  5239.5 1389.84
#Mann= 6 ,-1 , 0
  3907.8     .12       0  4070.7    .035       0  4994.1    .035       0
  5000.5    .035       0  5137.2     .12       0  5202.7    .035       0
Bank Sta=4994.1,5000.5
XS Rating Curve= 0 ,0
Exp/Cntr=0.3,0.1

Type RM Length L Ch R = 1 ,31740   ,473,473,473
BEGIN DESCRIPTION:
SABINAS CREEK 62.0
END DESCRIPTION:
XS GIS Cut Line= 3
      2055024.98     13859475.03        2055525.       13858675.
        2055575.     13858024.95
#Sta/Elev= 30
  4056.6 1406.68  4106.8  1404.8  4122.1 1401.63  4164.5 1399.97  4222.3 1394.84
  4245.3 1388.49  4280.7 1371.45  4289.5 1369.36    4352  1366.3  4388.5 1366.25
  4480.9  1365.1  4549.7 1364.42  4630.3  1365.1  4855.6 1362.93  4892.1 1364.28
  4964.7 1363.49  4986.5 1361.42  4988.9 1359.89  4989.4 1359.39  4995.9 1359.89
  5030.2  1361.7  5060.2 1367.52  5070.2 1368.02  5271.6 1370.86  5383.7 1372.99
  5471.4 1377.25  5551.7 1395.84  5623.3 1407.08  5641.9 1411.11    5652 1411.28
#Mann= 11 ,-1 , 0
  4056.6     .12       0    4352     .07       0  4388.5    .035       0
  4480.9     .07       0  4549.7    .035       0  4988.9    .035       0
  4995.9    .035       0  5030.2     .07       0  5271.6    .035       0
  5383.7     .07       0  5623.3     .12       0
Bank Sta=4988.9,4995.9
XS Rating Curve= 0 ,0
Exp/Cntr=0.3,0.1

Type RM Length L Ch R = 1 ,31267   ,425,425,425
BEGIN DESCRIPTION:
SABINAS CREEK 61.0
END DESCRIPTION:
XS GIS Cut Line= 3
      2055225.01     13859674.99        2055925.       13858875.
      2056325.01     13858474.99
#Sta/Elev= 30
  3936.5 1413.12  4008.4 1407.55  4135.6 1398.31  4185.3 1394.79  4262.9 1390.19
    4291 1384.43  4297.6 1385.64  4305.2 1380.83  4326.1 1379.02  4333.7 1374.43
  4340.4 1375.86  4347.9 1370.63  4354.6 1371.92  4368.8 1362.53    4383 1360.96
  4495.6 1359.88  4700.5 1359.16  4730.4 1354.25  4754.8 1357.73  4935.4 1358.42
  4971.5 1356.97  4992.6 1352.79  4993.1 1352.29  4999.7 1352.79  5041.9 1362.33
  5198.8 1363.61  5239.9 1363.27  5254.1 1358.86  5296.5 1363.66  5565.2  1372.1
#Mann= 11 ,-1 , 0
  3936.5     .07       0  4008.4     .12       0  4135.6    .035       0
  4185.3     .07       0  4262.9    .035       0  4340.4     .07       0
  4495.6    .035       0  4754.8     .07       0  4992.6     .05       0
  4999.7     .07       0  5198.8     .12       0
#XS Ineff= 2 , 0
       0                 5223.14       0 1363.92
Permanent Ineff=
       F       F
Bank Sta=4992.6,4999.7
XS Rating Curve= 0 ,0
Exp/Cntr=0.3,0.1

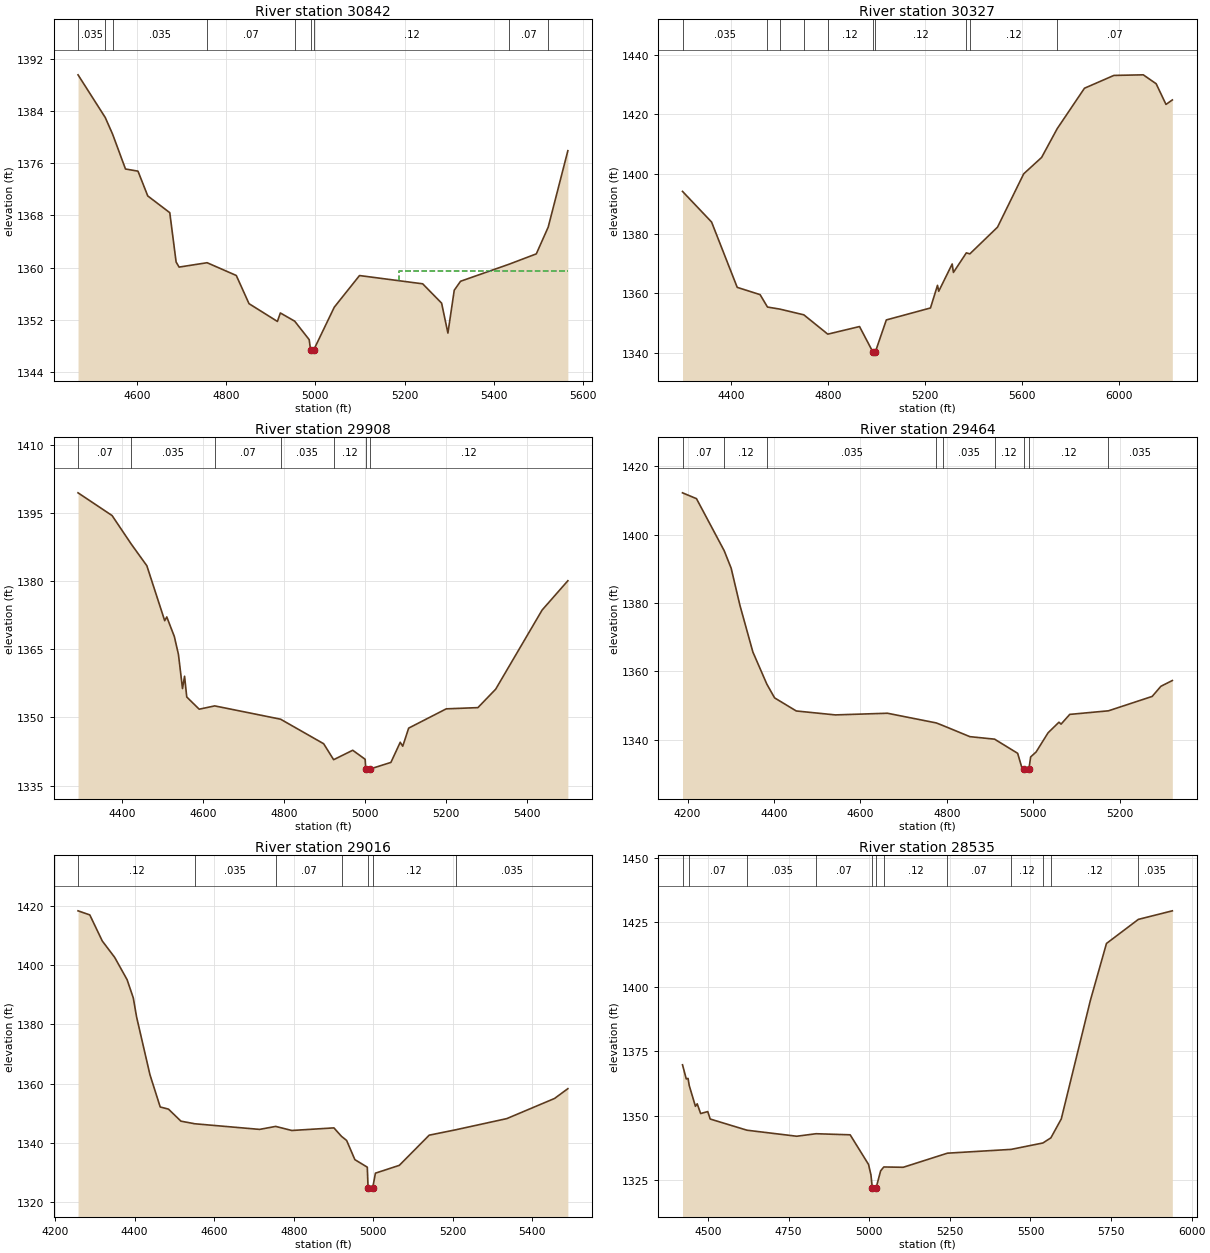
Type RM Length L Ch R = 1 ,30842   ,515,515,515
BEGIN DESCRIPTION:
SABINAS CREEK 60.0
END DESCRIPTION:
XS GIS Cut Line= 3
      2055624.98     13859575.02        2056025.       13859225.
      2056424.99     13858825.01
#Sta/Elev= 30
  4468.5 1389.61  4529.5 1383.05    4546 1380.48  4574.8 1375.14  4602.8 1374.81
  4624.7    1371    4674 1368.43  4688.2 1360.85  4694.9 1360.07  4757.6 1360.74
    4823 1358.78  4851.5 1354.45  4915.1 1351.72  4921.7 1353.02  4953.8 1351.76
  4986.3 1348.92  4989.3 1347.35  4989.8 1346.85  4996.5 1347.35  5042.5 1353.91
    5099 1358.77  5240.5  1357.5  5282.9 1354.53    5297 1349.93  5311.2 1356.51
  5325.3 1357.89  5434.8 1360.53    5495  1362.1  5521.7 1366.22  5565.7 1377.95
#Mann= 9 ,-1 , 0
  4468.5    .035       0  4529.5     .07       0    4546    .035       0
  4757.6     .07       0  4953.8     .12       0  4989.3     .05       0
  4996.5     .12       0  5434.8     .07       0  5521.7     .12       0
#XS Ineff= 2 , 0
       0                 5188.15       0  1359.5
Permanent Ineff=
       F       F
Bank Sta=4989.3,4996.5
XS Rating Curve= 0 ,0
Exp/Cntr=0.3,0.1

Type RM Length L Ch R = 1 ,30327   ,419,419,419
BEGIN DESCRIPTION:
SABINAS CREEK 59.0
END DESCRIPTION:
XS GIS Cut Line= 3
      2055575.02       13859625.      2056376.83     13859571.86
      2057580.86     13859370.61
#Sta/Elev= 30
  4197.8 1394.14    4318 1383.87  4423.9 1361.98  4518.5 1359.54    4549 1355.38
  4600.3 1354.69  4699.3 1352.77  4798.2  1346.3  4929.4 1348.85  4983.8 1340.44
  4984.3 1339.94  4995.2 1340.44  5040.1 1351.06  5222.6 1355.07  5251.6 1362.66
  5256.7 1360.67  5312.3 1369.82  5317.4 1366.98  5370.8 1373.54  5385.3  1373.2
  5499.6 1382.15  5607.8 1400.02  5681.9 1405.52  5746.3 1415.16    5859 1428.71
  5980.5    1433    6102  1433.2  6155.3 1430.21  6195.9 1423.28  6222.1 1424.79
#Mann= 10 ,-1 , 0
  4197.8    .035       0    4549     .07       0  4600.3    .035       0
  4699.3     .07       0  4798.2     .12       0  4983.8     .05       0
  4995.2     .12       0  5370.8     .07       0  5385.3     .12       0
  5746.3     .07       0
Bank Sta=4983.8,4995.2
XS Rating Curve= 0 ,0
Exp/Cntr=0.3,0.1

Type RM Length L Ch R = 1 ,29908   ,444,444,444
BEGIN DESCRIPTION:
SABINAS CREEK 58.0
END DESCRIPTION:
XS GIS Cut Line= 3
      2055632.97     13860125.95        2056325.       13859975.
        2056725.       13859675.
#Sta/Elev= 30
  4292.1 1399.52  4376.1 1394.51  4423.4 1388.22  4461.9 1383.44  4505.9 1371.33
    4511 1372.16  4529.6 1367.86  4539.8  1363.9  4549.8 1356.37  4554.9 1359.09
  4560.3 1354.51    4591 1351.82  4629.3 1352.55  4791.7 1349.62    4898 1344.21
  4922.6 1340.69  4969.7 1342.77  5000.4 1340.78  5001.8 1338.67  5002.3 1338.17
  5013.5 1338.67  5063.9 1340.09  5086.9 1344.53  5093.1 1343.66  5107.7 1347.65
  5200.4  1351.9  5278.5 1352.17  5322.3 1356.23  5436.9 1373.68  5500.4 1380.14
#Mann= 7 ,-1 , 0
  4292.1     .07       0  4423.4    .035       0  4629.3     .07       0
  4791.7    .035       0  4922.6     .12       0  5001.8     .05       0
  5013.5     .12       0
Bank Sta=5001.8,5013.5
XS Rating Curve= 0 ,0
Exp/Cntr=0.3,0.1

Type RM Length L Ch R = 1 ,29464   ,448,448,448
BEGIN DESCRIPTION:
SABINAS CREEK 57.0
END DESCRIPTION:
XS GIS Cut Line= 3
      2055562.87     13860298.99        2056375.       13860375.
      2056691.42     13860346.29
#Sta/Elev= 30
  4188.4 1412.23  4220.7 1410.53  4284.9  1395.3    4301 1390.18  4321.1 1379.41
  4351.2 1365.69  4383.6 1356.27  4401.5 1352.26  4451.7 1348.43  4542.1 1347.28
  4662.6 1347.77  4775.8 1344.93  4791.8 1344.13  4853.4 1340.92  4910.5 1340.19
  4963.9 1336.05  4973.9 1331.75  4978.1 1331.34  4978.6 1330.84  4989.8 1331.34
    4994    1335  5006.6 1336.44  5034.2 1342.04  5059.4 1345.14  5064.4 1344.59
  5084.4 1347.43    5174 1348.48  5275.2 1352.69  5295.3 1355.65  5321.8 1357.34
#Mann= 9 ,-1 , 0
  4188.4     .07       0  4284.9     .12       0  4383.6    .035       0
  4775.8     .07       0  4791.8    .035       0  4910.5     .12       0
  4978.1     .05       0  4989.8     .12       0    5174    .035       0
Bank Sta=4978.1,4989.8
XS Rating Curve= 0 ,0
Exp/Cntr=0.3,0.1

Type RM Length L Ch R = 1 ,29016   ,481,481,481
BEGIN DESCRIPTION:
SABINAS CREEK 56.0
END DESCRIPTION:
XS GIS Cut Line= 3
      2055466.55      13860519.6        2056175.       13860725.
      2056668.49     13860741.99
#Sta/Elev= 30
  4257.7 1418.32  4287.3 1416.94  4318.6 1408.15  4349.8 1402.61    4381 1395.08
  4396.6 1388.93  4404.9 1382.49  4438.5 1362.98  4464.3 1352.09  4485.1 1351.36
  4516.4  1347.3  4551.1 1346.42  4714.2 1344.52  4754.5 1345.53  4795.1 1344.15
    4901 1345.03  4920.1 1342.16  4932.9 1340.79  4953.7  1334.3  4984.9 1331.76
  4986.8 1324.85  4987.3 1324.35  4998.6 1324.85  5005.3 1329.74  5065.4 1332.38
  5140.5 1342.57  5207.7  1344.4  5335.5 1348.16  5455.6 1354.96  5489.1 1358.27
#Mann= 7 ,-1 , 0
  4257.7     .12       0  4551.1    .035       0  4754.5     .07       0
  4920.1     .12       0  4986.8     .05       0  4998.6     .12       0
  5207.7    .035       0
Bank Sta=4986.8,4998.6
XS Rating Curve= 0 ,0
Exp/Cntr=0.3,0.1

Type RM Length L Ch R = 1 ,28535   ,454,454,454
BEGIN DESCRIPTION:
SABINAS CREEK 55.0
END DESCRIPTION:
XS GIS Cut Line= 3
      2055553.95     13860932.98        2056075.       13861175.
      2057019.21     13861144.77
#Sta/Elev= 30
  4420.9  1369.7  4432.6 1364.22  4438.1 1364.41  4441.8 1361.65    4461  1353.6
  4466.5 1354.57  4477.2  1350.8  4499.2 1351.56  4506.8 1348.67    4621 1344.33
  4775.1    1342  4835.2 1342.97  4940.9 1342.55  4997.9 1331.06  5005.4 1326.98
  5009.5 1321.99    5010 1321.49  5021.4 1321.99  5035.4 1328.58  5045.2 1330.08
  5105.5 1329.96  5242.6 1335.43    5440  1336.9  5538.6 1339.38  5563.4 1341.37
  5595.7 1348.73  5685.8 1394.62  5735.8 1416.74  5834.7 1426.08  5940.1  1429.4
#Mann= 12 ,-1 , 0
  4420.9     .12       0  4441.8     .07       0    4621    .035       0
  4835.2     .07       0  5009.5     .05       0  5021.4     .07       0
  5045.2     .12       0  5242.6     .07       0    5440     .12       0
  5538.6     .07       0  5563.4     .12       0  5834.7    .035       0
Bank Sta=5009.5,5021.4
XS Rating Curve= 0 ,0
Exp/Cntr=0.3,0.1