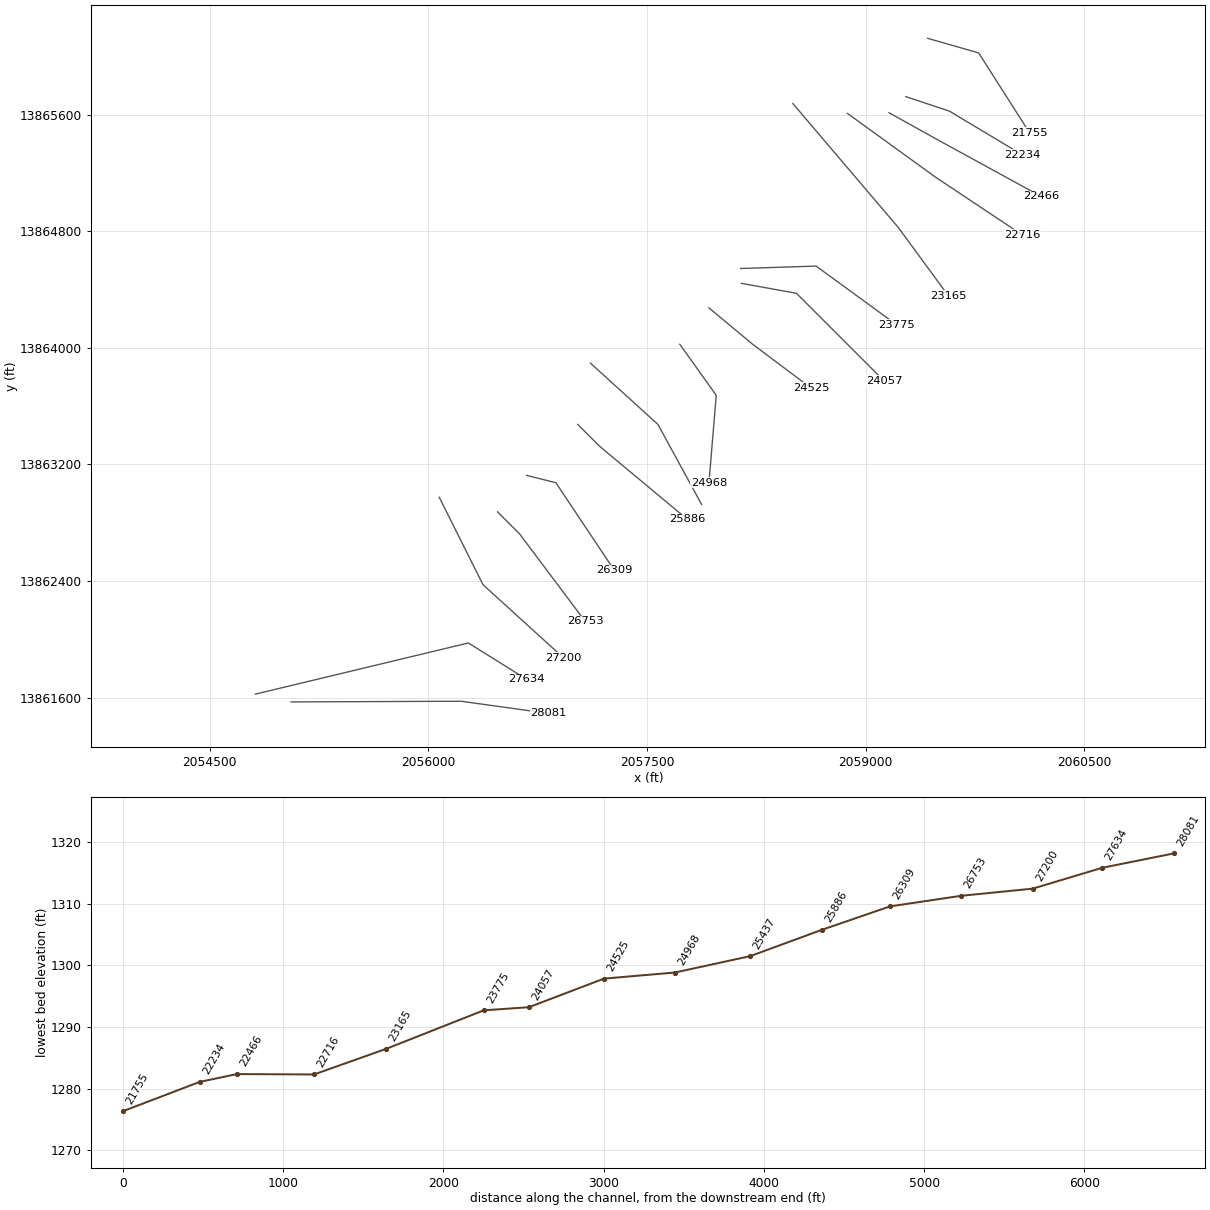
HEC-RAS study SABINAS CREEK.prj: SABINAS CREEK Base Level Engineering

--- SABINAS CREEK.g01 (geometry) --- (continued)

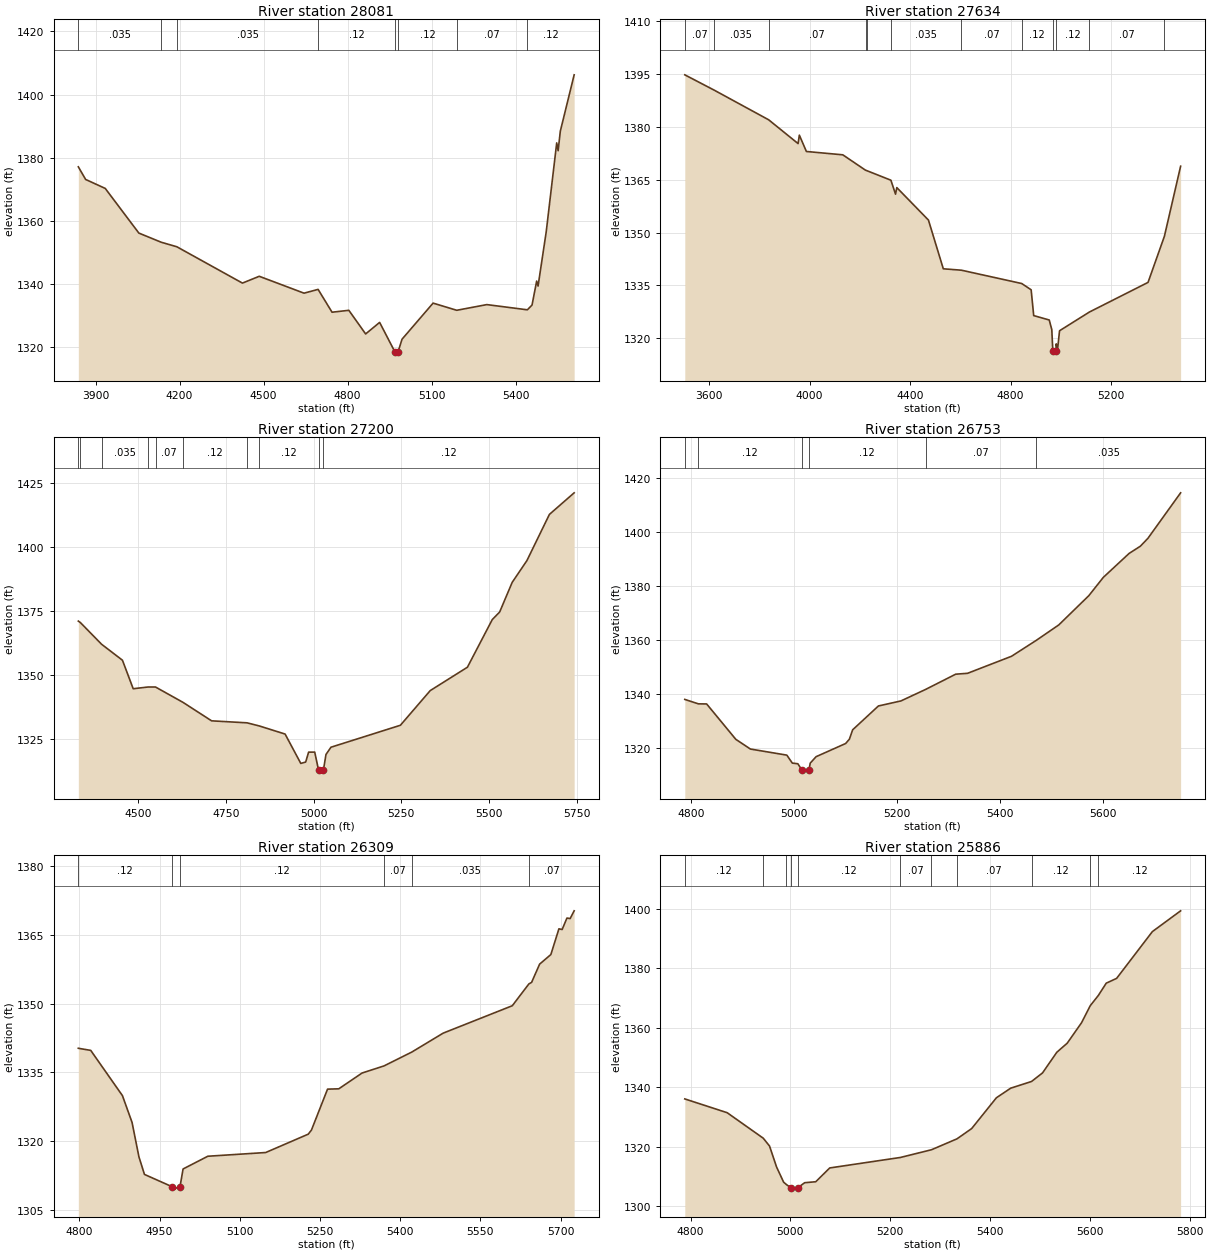
Type RM Length L Ch R = 1 ,28081   ,447,447,447
BEGIN DESCRIPTION:
SABINAS CREEK 54.0
END DESCRIPTION:
XS GIS Cut Line= 3
      2055058.94     13861570.48        2056225.       13861575.
      2056823.98     13861491.74
#Sta/Elev= 30
  3838.3 1377.13  3864.4 1373.13  3934.4 1370.29  4054.4 1356.15  4134.1 1353.25
  4190.1 1351.81  4424.4  1340.3  4484.4 1342.46  4644.4 1337.11  4694.6 1338.31
  4744.4 1331.08  4804.4 1331.68  4864.4  1324.2  4914.4 1327.85  4968.3 1318.62
  4968.8 1318.12  4980.5 1318.62  4994.4 1322.53  5105.3 1333.96  5189.8 1331.69
  5297.2 1333.49    5442 1331.84  5458.7 1333.35  5475.2 1340.95  5480.2 1339.36
  5509.2 1356.47  5546.8 1384.71  5551.9 1382.25  5559.7 1388.43  5609.1 1406.27
#Mann= 8 ,-1 , 0
  3838.3    .035       0  4134.1     .07       0  4190.1    .035       0
  4694.6     .12       0  4968.3     .05       0  4980.5     .12       0
  5189.8     .07       0    5442     .12       0
Bank Sta=4968.3,4980.5
XS Rating Curve= 0 ,0
Exp/Cntr=0.3,0.1

Type RM Length L Ch R = 1 ,27634   ,434,434,434
BEGIN DESCRIPTION:
SABINAS CREEK 53.0
END DESCRIPTION:
XS GIS Cut Line= 3
      2054814.32     13861623.94        2056275.       13861975.
      2056675.02     13861724.99
#Sta/Elev= 30
  3503.2 1394.76  3619.5 1390.44  3837.1    1382  3954.2 1375.25  3959.3 1377.64
  3987.3 1373.01  4132.3 1372.06  4222.7  1367.7  4226.7  1367.6  4323.7 1364.86
  4342.2  1360.9  4347.3 1362.76  4473.2 1353.55  4532.4 1339.72  4604.6 1339.32
  4844.6 1335.54  4882.1 1333.76  4892.3 1326.44  4954.1 1325.19  4964.3 1322.47
  4968.5 1316.29    4969 1315.79  4980.7 1316.29  4981.9 1318.42  4987.1 1316.78
  4995.2 1322.14    5114 1327.45  5347.5 1335.86  5412.6 1348.94  5477.2 1368.83
#Mann= 12 ,-1 , 0
  3503.2     .07       0  3619.5    .035       0  3837.1     .07       0
  4222.7    .035       0  4226.7     .12       0  4323.7    .035       0
  4604.6     .07       0  4844.6     .12       0  4968.5     .05       0
  4980.7     .12       0    5114     .07       0  5412.6     .12       0
Bank Sta=4968.5,4980.7
XS Rating Curve= 0 ,0
Exp/Cntr=0.3,0.1

Type RM Length L Ch R = 1 ,27200   ,447,447,447
BEGIN DESCRIPTION:
SABINAS CREEK 52.0
END DESCRIPTION:
XS GIS Cut Line= 3
      2056075.01     13862974.98        2056375.       13862375.
        2056925.       13861875.
#Sta/Elev= 30
  4329.2 1370.97  4335.2 1370.38  4395.4 1361.95    4455  1355.7  4485.7 1344.57
  4528.3 1345.25  4549.3 1345.24  4627.4 1339.28  4709.3 1332.04  4810.4 1331.26
  4845.4 1330.04  4918.9 1326.88  4963.7 1315.41  4977.6 1315.96    4986 1319.82
  5003.4 1319.83  5014.2 1312.91  5014.7 1312.41  5028.3 1312.91  5035.5 1318.91
  5049.7 1321.74  5247.7 1330.31  5332.8 1343.84  5438.9 1352.97  5509.8 1371.57
  5530.8 1374.51  5566.6  1386.1  5608.5 1394.57  5672.7 1412.61  5743.3 1421.04
#Mann= 10 ,-1 , 0
  4329.2     .07       0  4335.2     .12       0  4395.4    .035       0
  4528.3     .12       0  4549.3     .07       0  4627.4     .12       0
  4810.4     .07       0  4845.4     .12       0  5014.2     .05       0
  5028.3     .12       0
Bank Sta=5014.2,5028.3
XS Rating Curve= 0 ,0
Exp/Cntr=0.3,0.1

Type RM Length L Ch R = 1 ,26753   ,444,444,444
BEGIN DESCRIPTION:
SABINAS CREEK 51.0
END DESCRIPTION:
XS GIS Cut Line= 3
      2056475.01     13862874.99        2056625.       13862725.
      2057074.99     13862125.01
#Sta/Elev= 30
  4787.8 1337.84  4814.2  1336.2  4830.2 1336.16  4886.8 1323.04  4915.1 1319.44
  4985.8 1317.18  4996.4 1314.23  5007.2 1313.98  5014.7 1311.75  5015.2 1311.25
  5028.8 1311.75  5031.2 1314.22  5042.6 1316.61  5099.9 1321.49  5107.2  1323.1
  5113.5 1326.57  5163.5 1335.41  5207.2 1337.28  5255.2 1341.56  5313.5  1347.2
  5336.4 1347.52  5421.8 1353.84  5470.2 1359.79  5513.5 1365.47  5571.8 1376.32
  5599.9  1383.1  5649.9 1391.97  5671.8 1394.66  5686.4 1397.57  5749.9 1414.45
#Mann= 6 ,-1 , 0
  4787.8     .07       0  4814.2     .12       0  5014.7     .05       0
  5028.8     .12       0  5255.2     .07       0  5470.2    .035       0
Bank Sta=5014.7,5028.8
XS Rating Curve= 0 ,0
Exp/Cntr=0.3,0.1

Type RM Length L Ch R = 1 ,26309   ,423,423,423
BEGIN DESCRIPTION:
SABINAS CREEK 50.0
END DESCRIPTION:
XS GIS Cut Line= 3
      2056674.97     13863125.01        2056875.       13863075.
        2057275.       13862475.
#Sta/Elev= 30
  4798.2 1340.28  4821.4 1339.82  4880.7 1329.94  4898.7 1324.08  4911.6 1316.55
  4921.9 1312.74  4974.1 1310.03  4974.6 1309.53  4988.3 1310.03  4994.1 1313.93
  5040.4 1316.71  5148.6 1317.52  5228.2 1321.53  5234.2 1322.43  5264.3 1331.36
  5285.3 1331.43  5328.9 1334.88  5369.9 1336.43  5421.8 1339.45  5480.6 1343.59
  5609.8 1349.57  5640.9 1354.34  5645.9 1354.66  5660.9 1358.65  5681.9 1360.74
    5697 1366.36    5703 1366.21    5712 1368.71    5718  1368.6  5725.5 1370.29
#Mann= 6 ,-1 , 0
  4798.2     .12       0  4974.1     .05       0  4988.3     .12       0
  5369.9     .07       0  5421.8    .035       0  5640.9     .07       0
Bank Sta=4974.1,4988.3
XS Rating Curve= 0 ,0
Exp/Cntr=0.3,0.1

Type RM Length L Ch R = 1 ,25886   ,449,449,449
BEGIN DESCRIPTION:
SABINAS CREEK 49.0
END DESCRIPTION:
XS GIS Cut Line= 3
      2057024.97     13863475.03        2057175.       13863325.
        2057775.       13862825.
#Sta/Elev= 30
  4788.4 1336.09  4873.3 1331.45  4945.6 1322.87  4958.1 1320.25  4972.3 1313.17
  4986.4 1308.08  4992.1 1307.27  5000.6 1306.25  5001.1 1305.75  5014.9 1306.25
  5028.6 1307.91  5050.7 1308.23  5078.7 1312.87  5220.3  1316.4  5282.5 1318.99
  5333.7 1322.67  5363.1 1326.13  5412.6 1336.48  5441.2  1339.7    5483 1341.96
    5505 1344.84  5533.6 1351.78  5554.4 1354.83  5583.1  1361.7  5600.6 1367.45
  5616.8 1370.89  5632.6 1375.02  5653.4 1376.63    5725 1392.36  5781.6 1399.35
#Mann= 11 ,-1 , 0
  4788.4     .12       0  4945.6     .07       0  4992.1     .12       0
  5000.6     .05       0  5014.9     .12       0  5220.3     .07       0
  5282.5     .12       0  5333.7     .07       0    5483     .12       0
  5600.6     .07       0  5616.8     .12       0
Bank Sta=5000.6,5014.9
XS Rating Curve= 0 ,0
Exp/Cntr=0.3,0.1

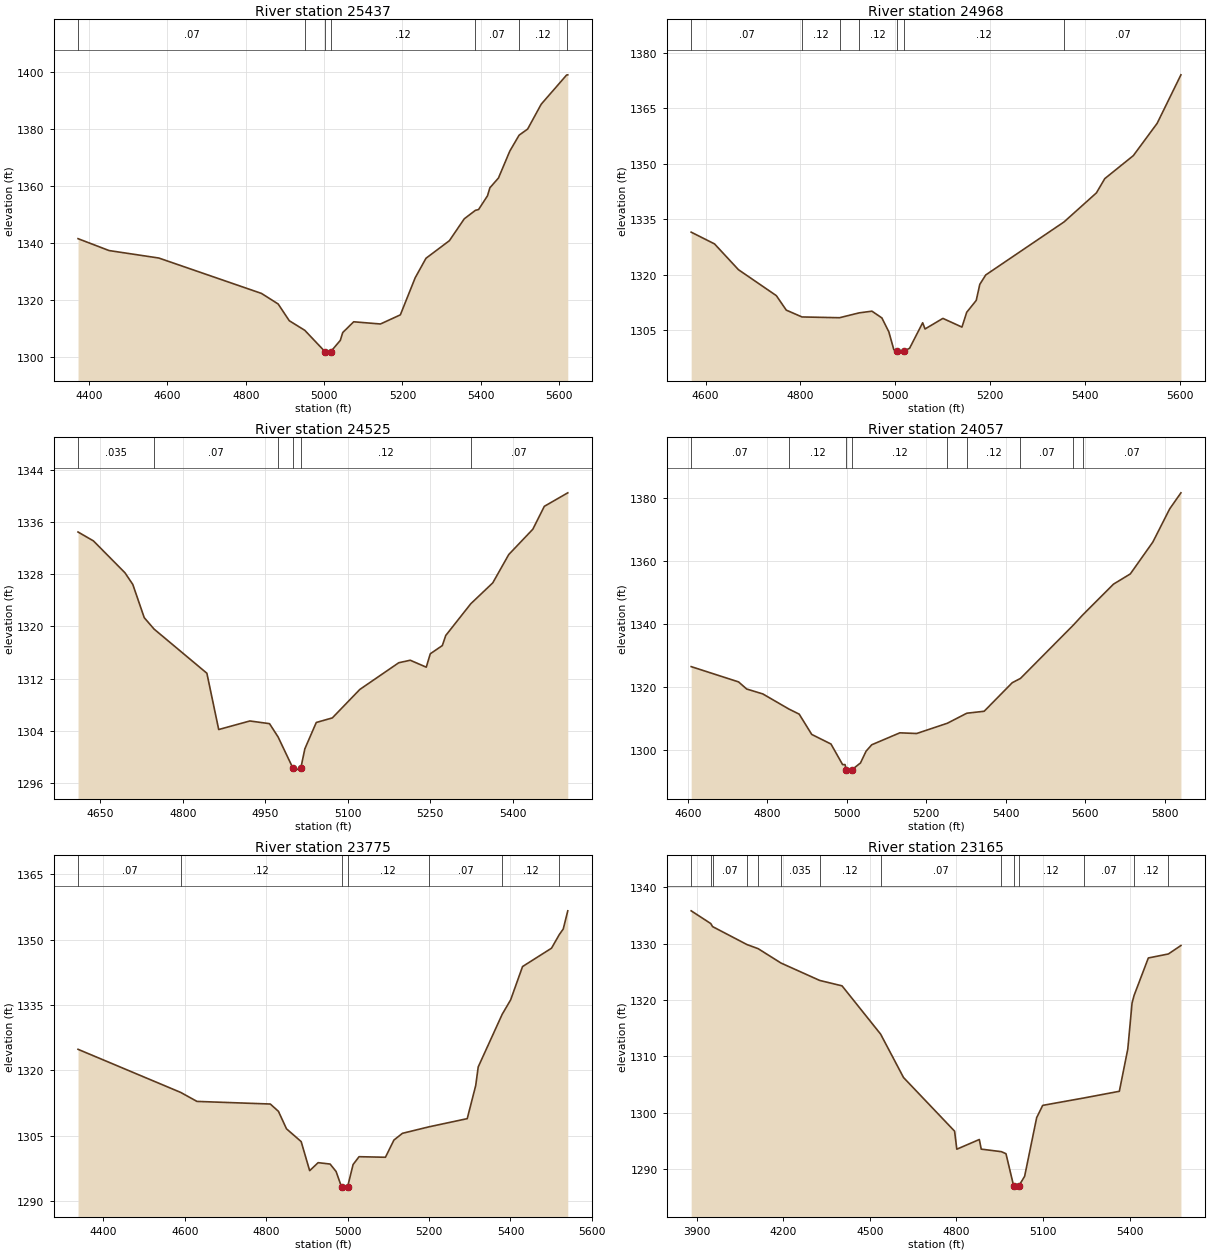
Type RM Length L Ch R = 1 ,25437   ,469,469,469
BEGIN DESCRIPTION:
SABINAS CREEK 48.0
END DESCRIPTION:
XS GIS Cut Line= 3
      2057112.91      13863894.8        2057575.       13863475.
        2057875.     13862925.01
#Sta/Elev= 30
  4371.5 1341.61  4450.8 1337.44  4577.9 1334.82    4840 1322.41  4882.6 1318.71
    4911 1312.84  4950.7 1309.46  5002.4 1301.97  5002.9 1301.47  5016.8 1301.97
  5041.4 1305.95  5047.5 1308.68  5075.5 1312.46  5143.9 1311.69  5194.7 1314.89
  5232.6  1327.9  5260.2 1334.74    5320 1340.91  5357.9 1348.57  5386.3 1351.54
  5394.5 1351.83  5417.3 1356.66  5423.4 1359.46  5445.3 1362.89  5474.2 1372.31
    5498 1377.91  5519.8 1380.05  5554.4 1388.76  5619.3    1399  5622.3 1399.07
#Mann= 7 ,-1 , 0
  4371.5     .07       0  4950.7     .12       0  5002.4     .05       0
  5016.8     .12       0  5386.3     .07       0    5498     .12       0
  5619.3     .07       0
Bank Sta=5002.4,5016.8
XS Rating Curve= 0 ,0
Exp/Cntr=0.3,0.1

Type RM Length L Ch R = 1 ,24968   ,443,443,443
BEGIN DESCRIPTION:
SABINAS CREEK 47.0
END DESCRIPTION:
XS GIS Cut Line= 3
      2057724.97     13864025.04        2057975.       13863675.
        2057925.     13863075.05
#Sta/Elev= 30
  4569.8 1331.52    4619 1328.35  4669.4 1321.38  4749.3 1314.36  4770.2 1310.45
  4803.3  1308.6  4882.5 1308.39  4923.7  1309.7  4950.8 1310.16  4971.7 1308.34
  4986.4 1304.57  4996.9 1299.77  5002.7 1299.32  5003.2 1298.82  5017.3 1299.32
  5030.1 1300.13  5057.7 1307.03  5062.7 1305.35  5100.3 1308.21  5140.5 1305.86
  5150.5 1309.86  5170.6 1313.07  5178.1 1317.41  5190.6 1319.95  5355.6 1334.28
  5423.9 1342.14  5441.5 1345.99  5501.7 1352.21  5551.9 1360.94    5602 1374.05
#Mann= 7 ,-1 , 0
  4569.8     .07       0  4803.3     .12       0  4882.5     .07       0
  4923.7     .12       0  5002.7     .05       0  5017.3     .12       0
  5355.6     .07       0
Bank Sta=5002.7,5017.3
XS Rating Curve= 0 ,0
Exp/Cntr=0.3,0.1

Type RM Length L Ch R = 1 ,24525   ,468,468,468
BEGIN DESCRIPTION:
SABINAS CREEK 46.0
END DESCRIPTION:
XS GIS Cut Line= 3
        2057925.       13864275.        2058225.       13864025.
      2058624.99     13863725.01
#Sta/Elev= 30
  4609.5 1334.45  4637.5 1333.09  4694.8 1328.21  4709.1 1326.42  4729.9 1321.33
  4747.8 1319.58  4843.8 1312.82  4865.3  1304.2  4921.9 1305.51  4957.7  1305.1
  4973.3 1303.06    5000 1298.33  5000.5 1297.83  5014.7 1298.33  5021.9 1301.24
  5042.7 1305.28  5071.9 1305.98  5121.9 1310.34  5192.7 1314.43  5213.6 1314.81
  5242.7 1313.75    5250  1315.8  5271.9 1317.06  5278.1  1318.6  5323.5 1323.45
  5363.6 1326.66  5392.7    1331  5436.5 1334.88  5457.3 1338.38    5500 1340.45
#Mann= 6 ,-1 , 0
  4609.5    .035       0  4747.8     .07       0  4973.3     .12       0
    5000     .05       0  5014.7     .12       0  5323.5     .07       0
Bank Sta=5000,5014.7
XS Rating Curve= 0 ,0
Exp/Cntr=0.3,0.1

Type RM Length L Ch R = 1 ,24057   ,282,282,282
BEGIN DESCRIPTION:
SABINAS CREEK 45.0
END DESCRIPTION:
XS GIS Cut Line= 3
      2058147.67     13864443.38        2058525.       13864375.
        2059125.       13863775.
#Sta/Elev= 30
  4608.6 1326.44  4727.8 1321.58  4748.2 1319.32  4788.8 1317.76  4854.4 1312.95
  4880.3 1311.33  4911.9 1304.87  4960.3 1301.82  4989.5 1295.28  4995.6 1295.28
  4998.9  1293.7  4999.4  1293.2  5013.6  1293.7  5034.5  1295.8  5048.6 1299.54
  5062.8 1301.58  5133.5 1305.38  5175.9 1305.17    5253 1308.43    5302 1311.62
  5345.6 1312.24  5416.3 1321.33    5437 1322.69  5569.8 1339.63  5593.4 1342.86
  5670.9 1352.67  5713.3 1355.93  5769.9 1366.05  5812.3 1376.61  5840.6 1381.72
#Mann= 9 ,-1 , 0
  4608.6     .07       0  4854.4     .12       0  4998.9     .05       0
  5013.6     .12       0    5253     .07       0    5302     .12       0
    5437     .07       0  5569.8     .12       0  5593.4     .07       0
Bank Sta=4998.9,5013.6
XS Rating Curve= 0 ,0
Exp/Cntr=0.3,0.1

Type RM Length L Ch R = 1 ,23775   ,610,610,610
BEGIN DESCRIPTION:
SABINAS CREEK 44.0
END DESCRIPTION:
XS GIS Cut Line= 3
      2058142.97      13864545.2       2058659.7     13864561.87
      2059213.95     13864157.64
#Sta/Elev= 30
  4337.8 1324.81  4589.9 1314.91    4630 1312.84  4810.1 1312.24  4830.1 1310.56
  4849.9 1306.54  4885.9 1303.61  4906.8 1296.93  4927.6 1298.77    4957 1298.45
  4971.7 1296.74  4985.1 1293.19  4985.6 1292.69  4999.9 1293.19  5013.4 1298.33
  5028.1 1300.14  5092.9 1300.01  5113.8 1303.97  5134.7 1305.51  5199.8    1307
  5293.8 1308.88  5314.7  1316.5  5320.8 1320.76  5379.8 1332.87  5400.4 1336.16
  5429.7 1343.82  5500.8 1348.03  5520.1 1351.18  5529.7 1352.45  5540.8 1356.62
#Mann= 7 ,-1 , 0
  4337.8     .07       0  4589.9     .12       0  4985.1     .05       0
  4999.9     .12       0  5199.8     .07       0  5379.8     .12       0
  5520.1     .07       0
Bank Sta=4985.1,4999.9
XS Rating Curve= 0 ,0
Exp/Cntr=0.3,0.1

Type RM Length L Ch R = 1 ,23165   ,449,449,449
BEGIN DESCRIPTION:
SABINAS CREEK 43.0
END DESCRIPTION:
XS GIS Cut Line= 3
      2058500.66      13865677.1        2059225.       13864825.
      2059566.59     13864358.69
#Sta/Elev= 30
  3881.4 1335.85  3949.3 1333.59  3955.5 1333.05  4075.1 1329.85  4113.4 1329.13
  4192.9 1326.57  4326.7 1323.49    4404 1322.53  4537.6 1313.96    4617 1306.25
  4793.8 1296.73  4801.5 1293.53  4879.5 1295.25  4886.1 1293.54  4955.8 1293.09
  4971.8 1292.73  4998.7 1286.94  4999.2 1286.44  5015.4 1286.94  5036.4 1288.71
  5078.1 1299.13    5099 1301.31  5241.4 1302.62  5364.5 1303.81  5393.8 1311.33
  5408.5 1319.47  5415.5 1320.82  5464.9 1327.48  5534.3 1328.19  5577.8 1329.69
#Mann= 14 ,-1 , 0
  3881.4     .07       0  3949.3    .035       0  3955.5     .07       0
  4075.1    .035       0  4113.4     .07       0  4192.9    .035       0
  4326.7     .12       0  4537.6     .07       0  4955.8     .12       0
  4998.7     .05       0  5015.4     .12       0  5241.4     .07       0
  5415.5     .12       0  5534.3     .07       0
Bank Sta=4998.7,5015.4
XS Rating Curve= 0 ,0
Exp/Cntr=0.3,0.1

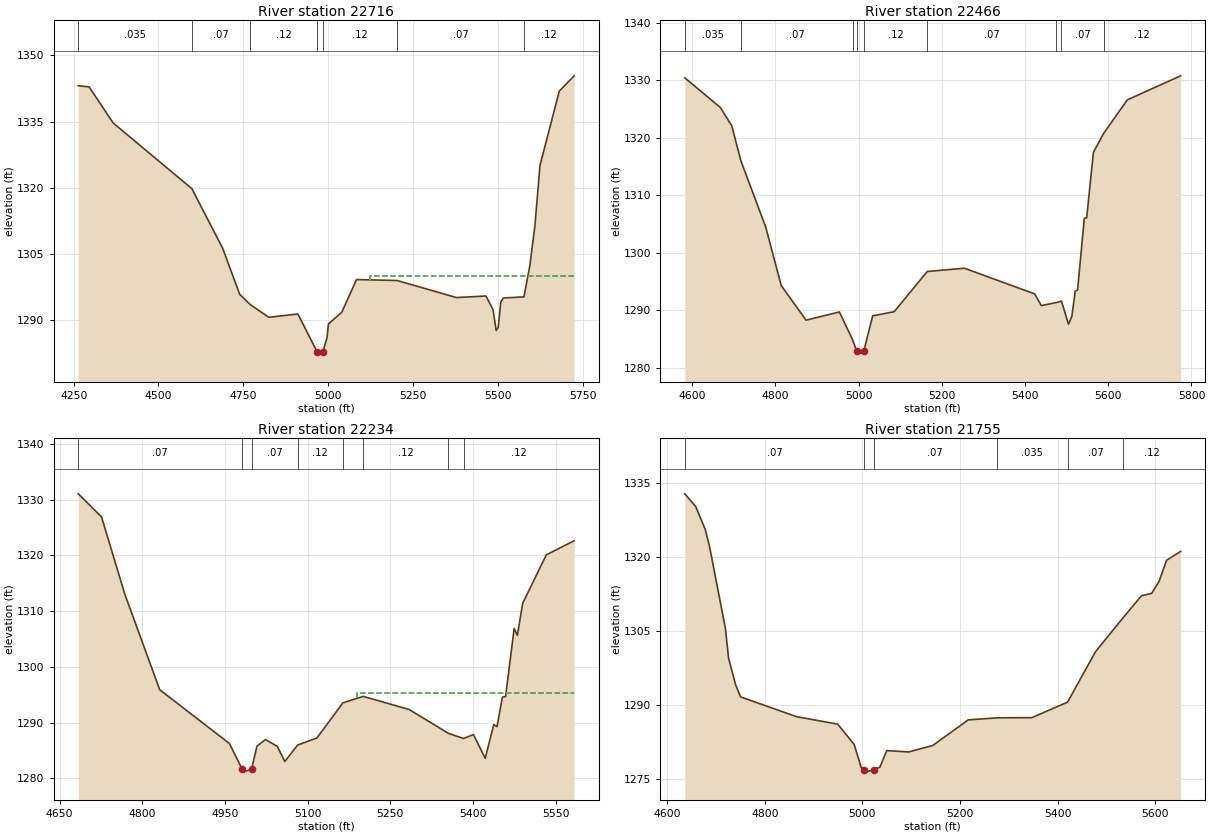
Type RM Length L Ch R = 1 ,22716   ,482,482,482
BEGIN DESCRIPTION:
SABINAS CREEK 42.0
END DESCRIPTION:
XS GIS Cut Line= 3
      2058875.38     13865609.47        2059475.       13865175.
      2060075.01     13864774.99
#Sta/Elev= 30
  4263.8 1343.11  4295.6 1342.85  4366.7 1334.66  4598.4  1319.8  4689.2  1306.3
  4739.4 1295.86  4770.6 1293.53  4825.3 1290.64  4911.1  1291.4  4967.7  1282.8
  4968.2  1282.3  4984.4  1282.8  4996.9 1286.02  5001.2 1289.14  5040.3 1291.78
  5083.9  1299.2  5203.6 1298.98  5378.3 1295.12  5465.5 1295.47  5486.5 1292.32
  5495.5 1287.64  5501.5 1288.36  5509.1 1294.08  5516.6 1295.02  5577.5 1295.27
  5594.7 1302.31  5609.7 1311.41  5624.7 1325.09  5681.8 1341.93  5725.4 1345.36
#Mann= 7 ,-1 , 0
  4263.8    .035       0  4598.4     .07       0  4770.6     .12       0
  4967.7     .05       0  4984.4     .12       0  5203.6     .07       0
  5577.5     .12       0
#XS Ineff= 2 , 0
       0                  5123.9       0 1299.93
Permanent Ineff=
       F       F
Bank Sta=4967.7,4984.4
XS Rating Curve= 0 ,0
Exp/Cntr=0.3,0.1

Type RM Length L Ch R = 1 ,22466   ,232,232,232
BEGIN DESCRIPTION:
SABINAS CREEK 41.5
END DESCRIPTION:
XS GIS Cut Line= 3
      2059160.02     13865614.15      2059525.44     13865411.18
      2060204.35      13865039.5
#Sta/Elev= 30
    4582 1330.41  4667.5 1325.25  4694.9 1322.07    4717 1315.95  4776.2 1304.53
  4813.9 1294.28  4873.4 1288.27  4953.7 1289.69  4985.2 1284.89  4995.4 1282.86
  4995.9 1282.36  5012.2 1282.86  5033.7 1289.02  5085.4 1289.74  5164.8 1296.73
  5254.2  1297.3    5423 1292.84  5439.1  1290.8  5474.7 1291.32  5487.5 1291.58
  5504.5 1287.57  5512.5 1288.93  5520.6  1293.3  5526.3 1293.54  5542.5 1305.98
  5548.2 1306.07  5564.3 1317.45    5589 1320.75  5645.8 1326.58    5774 1330.76
#Mann= 9 ,-1 , 0
    4582    .035       0    4717     .07       0  4985.2     .12       0
  4995.4     .05       0  5012.2     .12       0  5164.8     .07       0
  5474.7     .12       0  5487.5     .07       0    5589     .12       0
Bank Sta=4995.4,5012.2
XS Rating Curve= 0 ,0
Exp/Cntr=0.3,0.1

Type RM Length L Ch R = 1 ,22234   ,479,479,479
BEGIN DESCRIPTION:
SABINAS CREEK 41.0
END DESCRIPTION:
XS GIS Cut Line= 3
      2059275.02     13865724.99        2059575.       13865625.
      2060074.99       13865325.
#Sta/Elev= 30
  4684.1 1331.07  4726.2 1326.92  4768.4 1313.05  4831.7 1295.89  4958.1 1286.23
  4981.4 1281.59  4981.9 1281.09  4998.2 1281.59  5008.1 1285.76  5023.6 1286.94
    5045 1285.71  5058.6    1283  5081.8 1285.95  5116.9 1287.23    5164 1293.53
  5200.9 1294.69  5284.1 1292.34  5355.4 1288.05  5382.9 1287.13  5400.7 1287.84
  5422.1 1283.57  5437.6 1289.62  5443.5 1289.26  5453.2 1294.56    5459 1294.66
  5474.6 1306.89  5480.4 1305.68  5490.1 1311.43  5532.9 1320.11  5583.4 1322.65
#Mann= 8 ,-1 , 0
  4684.1     .07       0  4981.4     .05       0  4998.2     .07       0
  5081.8     .12       0    5164     .07       0  5200.9     .12       0
  5355.4     .07       0  5382.9     .12       0
#XS Ineff= 2 , 0
       0                 5189.87       0 1295.27
Permanent Ineff=
       F       F
Bank Sta=4981.4,4998.2
XS Rating Curve= 0 ,0
Exp/Cntr=0.3,0.1

Type RM Length L Ch R = 1 ,21755   ,470,470,470
BEGIN DESCRIPTION:
SABINAS CREEK 40.0
END DESCRIPTION:
XS GIS Cut Line= 3
      2059425.01       13866125.        2059775.       13866025.
      2060124.99     13865475.01
#Sta/Elev= 30
  4636.1 1332.77  4658.2 1330.23  4677.7 1325.63  4686.8 1322.09  4719.3 1305.48
  4725.8 1299.46  4740.1 1294.09  4750.5 1291.59  4864.9 1287.59  4949.4 1286.07
  4983.2 1281.94  4997.5 1277.27  5004.2 1276.84  5004.7 1276.34    5023 1276.84
  5035.7 1277.33    5050 1280.71  5094.9 1280.43    5144 1281.74  5216.8 1286.93
  5275.6 1287.35  5347.2 1287.39  5420.3 1290.52  5477.6 1300.76  5534.7 1307.71
  5571.6 1312.09  5592.8  1312.6    5608 1315.07  5623.2 1319.29    5652  1321.1
#Mann= 6 ,-1 , 0
  4636.1     .07       0  5004.2     .05       0    5023     .07       0
  5275.6    .035       0  5420.3     .07       0  5534.7     .12       0
Bank Sta=5004.2,5023
XS Rating Curve= 0 ,0
Exp/Cntr=0.3,0.1