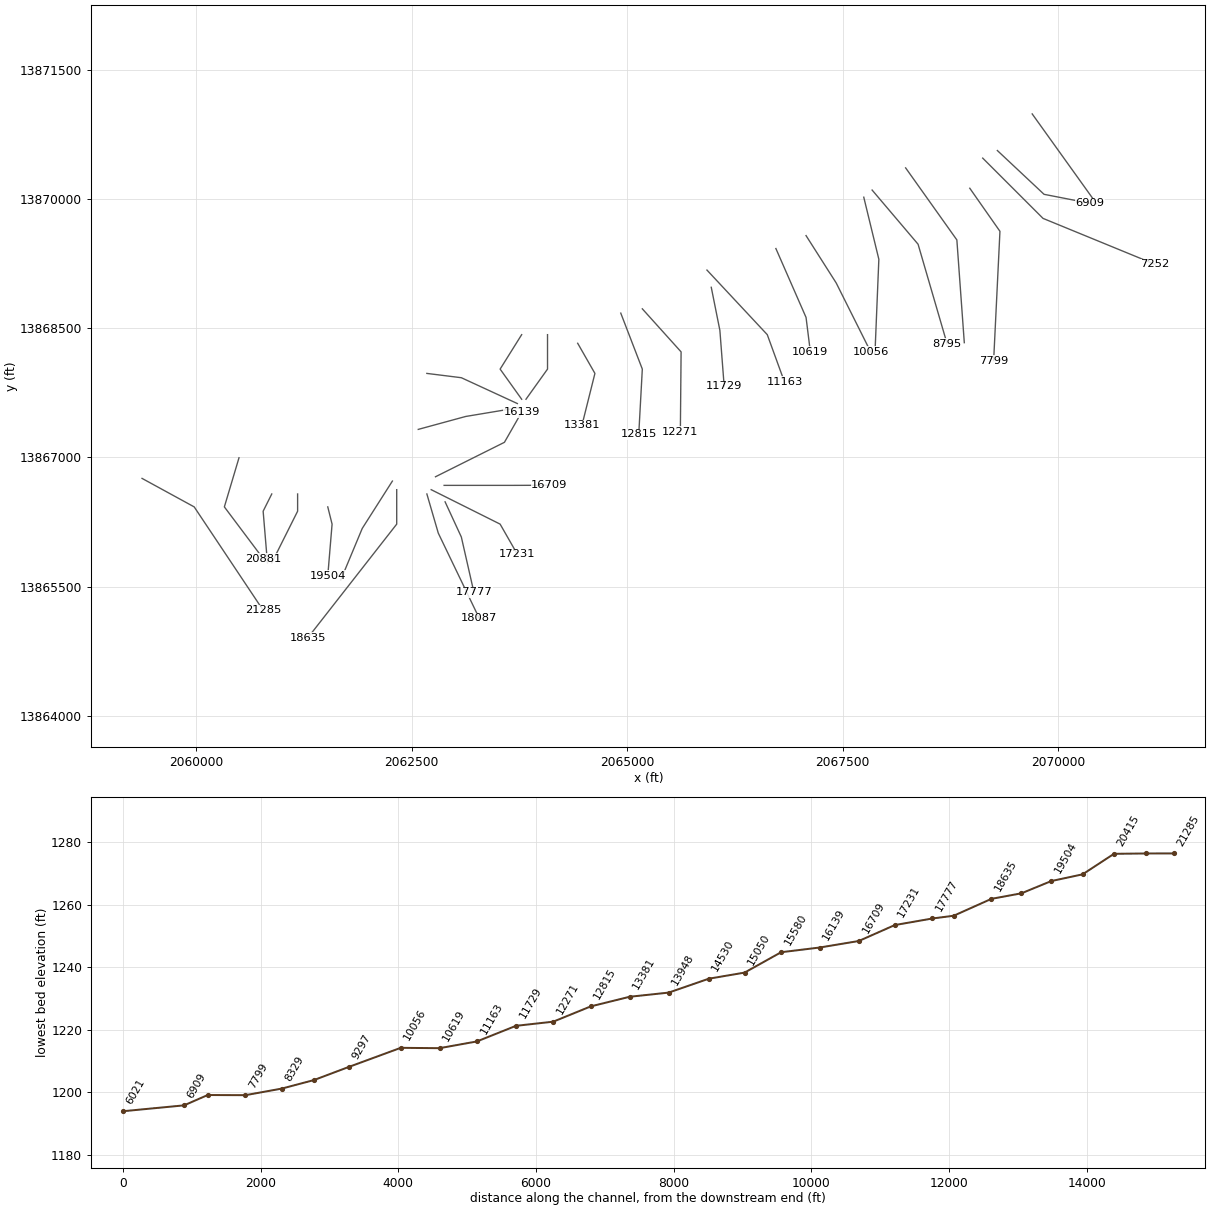
HEC-RAS study SABINAS CREEK.prj: SABINAS CREEK Base Level Engineering

--- SABINAS CREEK.g01 (geometry) --- (continued)

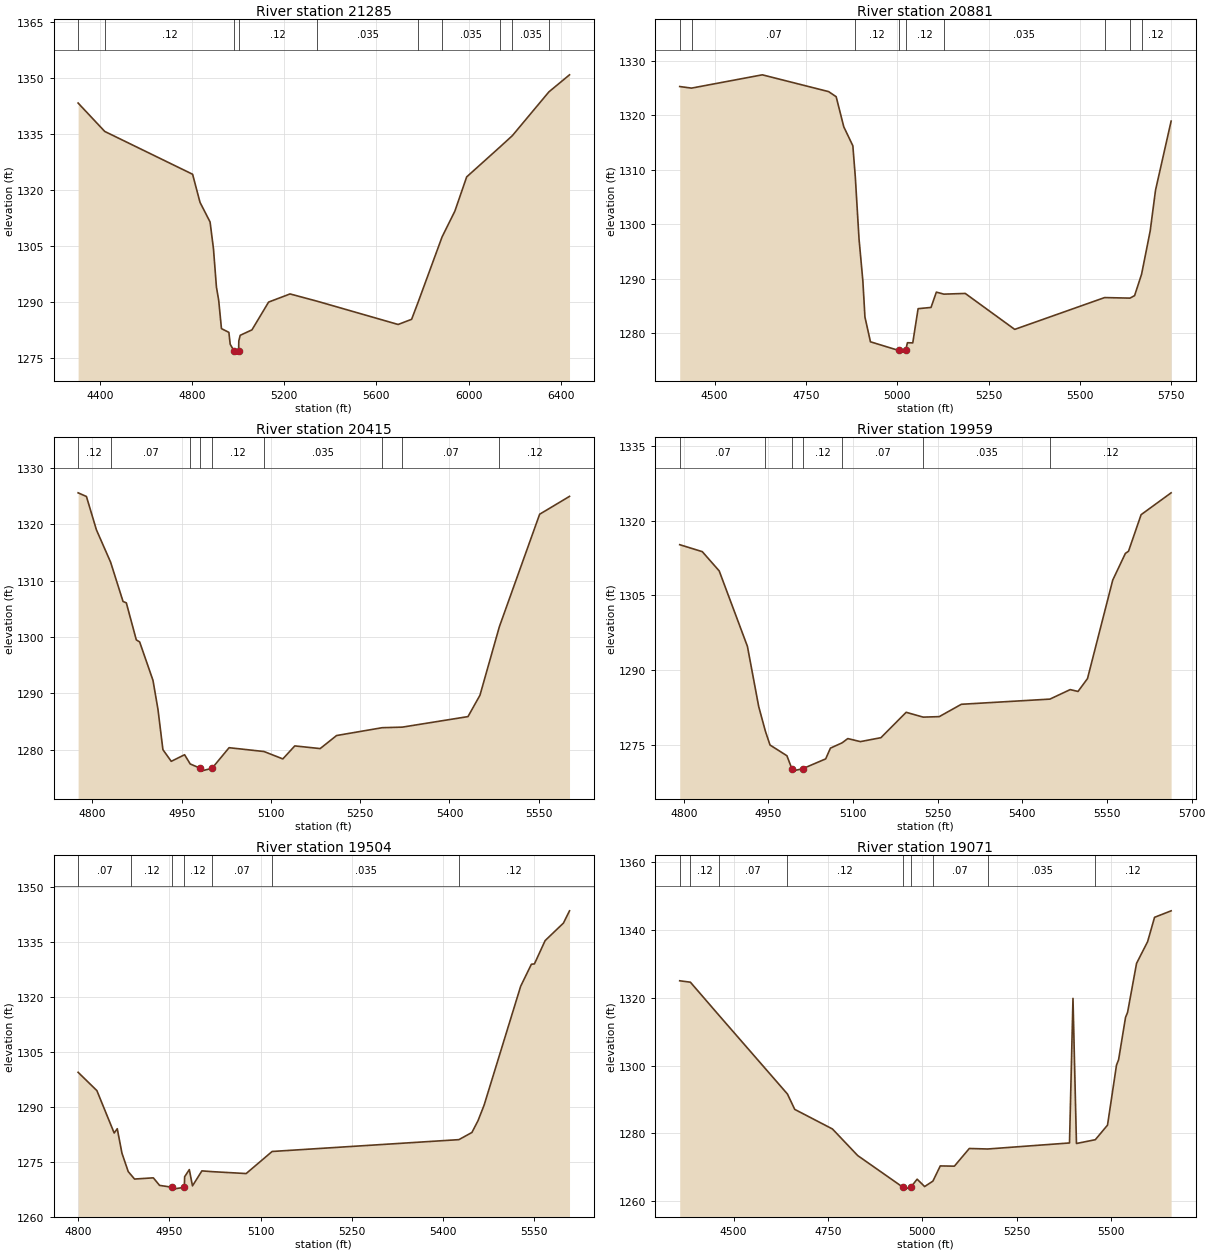
Type RM Length L Ch R = 1 ,21285   ,404,404,404
BEGIN DESCRIPTION:
SABINAS CREEK 39.0
END DESCRIPTION:
XS GIS Cut Line= 3
      2059369.87     13866755.89        2059975.       13866425.
      2060774.99     13865225.01
#Sta/Elev= 30
  4305.9 1343.27  4421.4 1335.67  4802.6 1324.21  4834.8 1316.69  4878.4 1311.44
    4893 1304.35    4906 1294.02  4915.8 1290.49  4927.8  1282.9    4960  1281.9
  4965.7 1278.72  4983.3 1276.84  4983.8 1276.34  5002.2 1276.84  5003.1 1279.61
  5009.1 1281.11  5060.2 1282.57  5132.3    1290  5225.4 1292.18  5344.3 1290.21
  5694.2 1284.01  5752.8 1285.39  5781.8 1290.11  5884.9 1307.44  5940.5 1314.35
  5991.6  1323.5  6135.7 1331.49  6189.8 1334.54  6348.4 1346.26  6437.8 1350.82
#Mann= 10 ,-1 , 0
  4305.9    .035       0  4421.4     .12       0  4983.3     .05       0
  5002.2     .12       0  5344.3    .035       0  5781.8     .07       0
  5884.9    .035       0  6135.7     .07       0  6189.8    .035       0
  6348.4     .07       0
Bank Sta=4983.3,5002.2
XS Rating Curve= 0 ,0
Exp/Cntr=0.3,0.1

Type RM Length L Ch R = 1 ,20881   ,466,466,466
BEGIN DESCRIPTION:
SABINAS CREEK 38.0
END DESCRIPTION:
XS GIS Cut Line= 3
       2060494.9     13866995.51        2060325.       13866425.
      2060775.02     13865824.97
#Sta/Elev= 30
  4404.3 1325.27  4436.7 1324.98  4630.4 1327.42  4811.9 1324.34  4832.6  1323.4
  4853.5 1317.87  4878.3 1314.39    4885 1308.68  4895.2 1297.28  4905.7 1289.56
  4911.4 1282.94  4926.5  1278.4  5003.4 1276.82  5003.9 1276.32  5022.8 1276.82
  5027.7 1278.23  5042.3  1278.2  5056.9 1284.48  5092.3 1284.71  5106.9 1287.52
  5127.5 1287.15    5186 1287.28  5321.4 1280.68  5567.5 1286.52    5637 1286.42
  5649.6 1286.88  5668.7  1290.8  5692.3 1298.75  5706.9 1306.24  5749.6 1318.92
#Mann= 9 ,-1 , 0
  4404.3    .035       0  4436.7     .07       0    4885     .12       0
  5003.4     .05       0  5022.8     .12       0  5127.5    .035       0
  5567.5     .12       0    5637     .07       0  5668.7     .12       0
Bank Sta=5003.4,5022.8
XS Rating Curve= 0 ,0
Exp/Cntr=0.3,0.1

Type RM Length L Ch R = 1 ,20415   ,456,456,456
BEGIN DESCRIPTION:
SABINAS CREEK 37.0
END DESCRIPTION:
XS GIS Cut Line= 3
        2060875.     13866574.99        2060775.       13866375.
        2060825.     13865774.98
#Sta/Elev= 30
    4776 1325.62    4790 1324.97  4806.7 1319.07  4830.6 1313.31  4851.5 1306.33
    4857 1306.09  4873.8 1299.51  4879.4 1299.15  4901.8 1292.33  4910.2 1287.17
  4918.5 1280.02  4932.5 1277.95  4954.9 1279.12  4964.4 1277.48  4981.5 1276.71
    4982 1276.21    5001 1276.71  5029.7 1280.37  5088.4 1279.69    5120 1278.38
  5140.1 1280.69  5182.7 1280.21  5210.3 1282.53  5286.9 1283.92  5320.7 1284.02
  5431.1 1285.89  5451.2 1289.68  5483.8 1301.84  5551.5 1321.82  5601.7 1324.99
#Mann= 9 ,-1 , 0
    4776     .12       0  4830.6     .07       0  4964.4     .12       0
  4981.5     .05       0    5001     .12       0  5088.4    .035       0
  5286.9     .12       0  5320.7     .07       0  5483.8     .12       0
Bank Sta=4981.5,5001
XS Rating Curve= 0 ,0
Exp/Cntr=0.3,0.1

Type RM Length L Ch R = 1 ,19959   ,455,455,455
BEGIN DESCRIPTION:
SABINAS CREEK 36.0
END DESCRIPTION:
XS GIS Cut Line= 3
        2061175.     13866575.04        2061175.       13866375.
      2060874.98     13865774.96
#Sta/Elev= 30
  4792.7 1315.15  4832.7 1313.75  4862.7 1309.88  4912.7 1294.72  4932.7 1282.62
  4944.6 1277.65  4952.7  1274.9  4982.7 1272.74  4991.4 1270.15  4991.9 1269.65
  5010.9 1270.15  5051.4 1272.11  5059.8 1274.27  5080.4 1275.33  5090.6 1276.19
  5112.9 1275.58  5149.3 1276.37    5194 1281.47  5224.2  1280.5  5252.7  1280.6
  5291.8 1283.08  5448.8 1284.12  5484.7 1286.03  5498.6 1285.66  5515.4 1288.25
  5560.1 1308.03  5582.5 1313.39  5588.1 1313.84  5610.4 1321.18  5663.6 1325.57
#Mann= 7 ,-1 , 0
  4792.7     .07       0  4944.6     .12       0  4991.4     .05       0
  5010.9     .12       0  5080.4     .07       0  5224.2    .035       0
  5448.8     .12       0
Bank Sta=4991.4,5010.9
XS Rating Curve= 0 ,0
Exp/Cntr=0.3,0.1

Type RM Length L Ch R = 1 ,19504   ,433,433,433
BEGIN DESCRIPTION:
SABINAS CREEK 35.0
END DESCRIPTION:
XS GIS Cut Line= 3
        2061525.     13866424.99        2061575.       13866225.
        2061525.     13865625.02
#Sta/Elev= 30
  4799.8 1299.37  4830.7 1294.37  4859.1 1282.81  4864.2 1283.98  4871.9 1277.31
  4882.2 1272.29  4887.2 1271.31  4892.6 1270.25  4923.5 1270.58  4933.8 1268.52
    4955    1268  4955.5  1267.5  4974.5    1268    4975 1270.88  4982.7 1272.83
  4987.9 1268.39  5003.4 1272.48  5019.9 1272.27  5076.2 1271.75  5118.9 1277.77
  5426.1    1281  5447.5 1282.96  5457.5 1286.17  5467.5  1290.4  5527.7 1322.86
  5545.3 1328.85  5550.3 1328.94  5567.9  1335.3    5598 1340.08    5608 1343.42
#Mann= 7 ,-1 , 0
  4799.8     .07       0  4887.2     .12       0    4955     .05       0
  4974.5     .12       0  5019.9     .07       0  5118.9    .035       0
  5426.1     .12       0
Bank Sta=4955,4974.5
XS Rating Curve= 0 ,0
Exp/Cntr=0.3,0.1

Type RM Length L Ch R = 1 ,19071   ,436,436,436
BEGIN DESCRIPTION:
SABINAS CREEK 34.0
END DESCRIPTION:
XS GIS Cut Line= 3
      2062274.97     13866724.96        2061925.       13866175.
      2061674.99     13865574.97
#Sta/Elev= 30
  4357.1 1325.01  4385.4 1324.59  4460.9 1314.86  4642.6 1291.62  4661.8  1287.1
  4761.8 1281.32  4828.6 1273.49  4949.2 1264.09  4949.7 1263.59  4968.8 1264.09
  4986.1 1266.52    5006 1264.35  5027.9 1265.95  5047.4 1270.43  5084.8 1270.36
  5124.3 1275.57  5172.9 1275.42  5389.8  1277.2    5399  1319.8  5408.2 1277.04
  5458.2 1278.16  5490.5 1282.46  5514.3 1300.16  5519.8 1301.71  5538.2 1314.21
  5543.6 1315.68  5567.4 1330.14  5596.7 1336.54  5615.1 1343.72    5659 1345.63
#Mann= 9 ,-1 , 0
  4357.1     .07       0  4385.4     .12       0  4460.9     .07       0
  4642.6     .12       0  4949.2     .05       0  4968.8     .12       0
  5027.9     .07       0  5172.9    .035       0  5458.2     .12       0
Bank Sta=4949.2,4968.8
XS Rating Curve= 0 ,0
Exp/Cntr=0.3,0.1

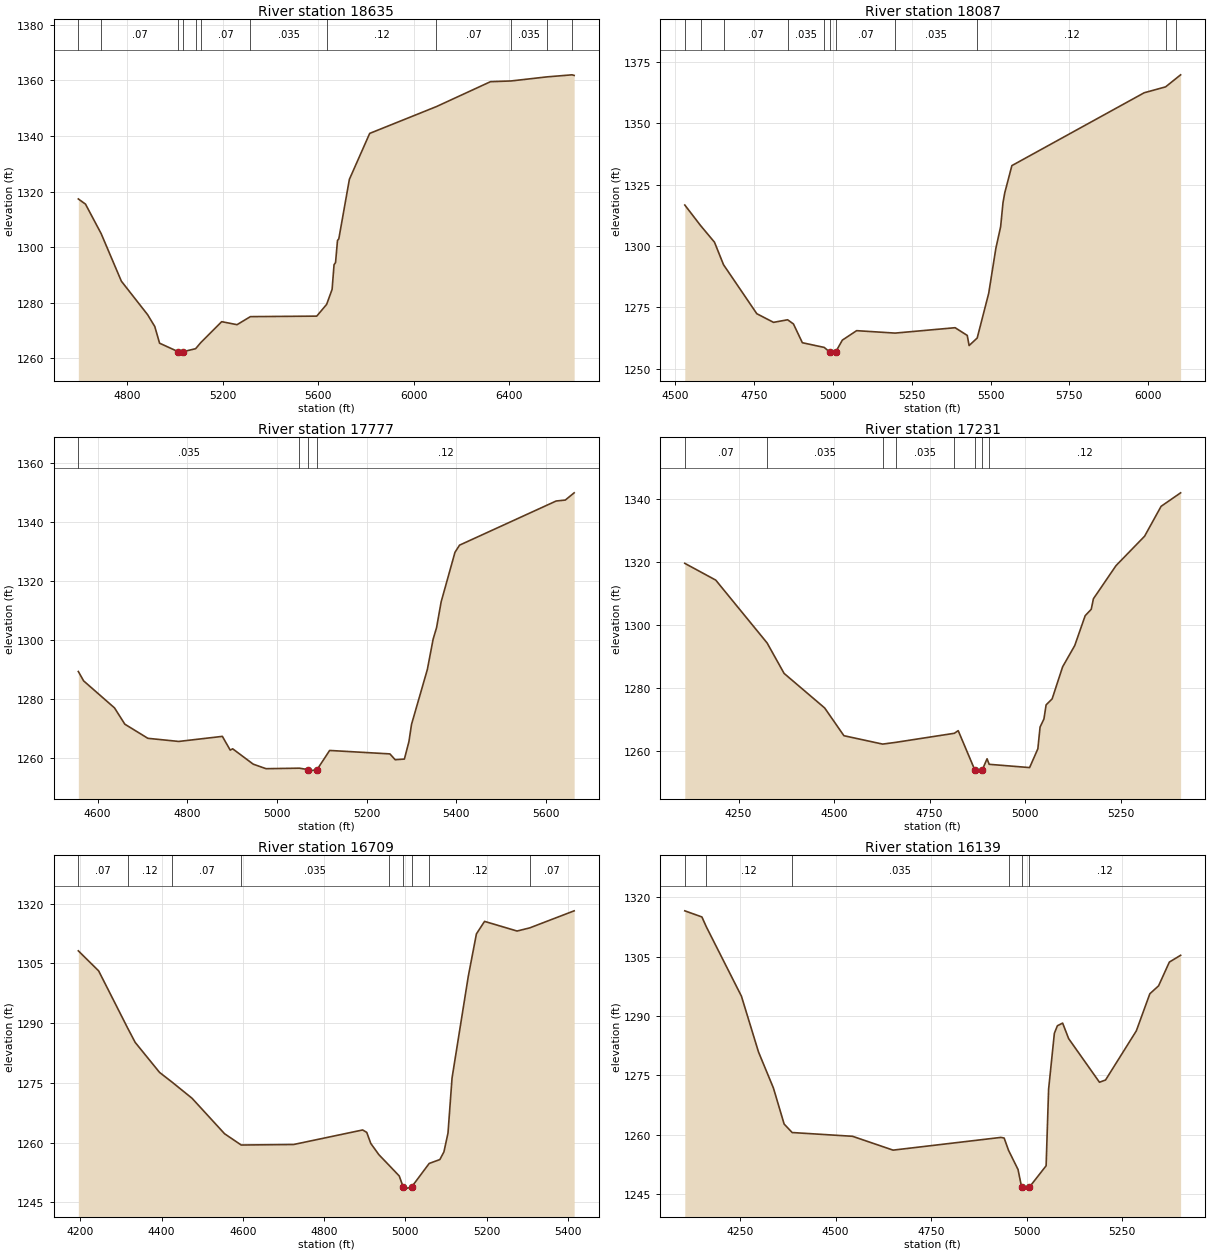
Type RM Length L Ch R = 1 ,18635   ,548,548,548
BEGIN DESCRIPTION:
SABINAS CREEK 33.0
END DESCRIPTION:
XS GIS Cut Line= 3
        2062325.     13866625.04        2062325.       13866225.
      2061293.51     13864905.21
#Sta/Elev= 30
  4595.8 1317.33  4625.8 1315.47  4691.3 1304.85  4775.8 1287.74  4885.8 1275.66
  4915.8 1271.39  4935.8  1265.4  5014.1 1262.32  5014.6 1261.82  5033.7 1262.32
  5086.7 1263.42  5108.9 1265.67  5195.7 1273.15  5259.9 1272.06    5316 1274.96
  5593.6 1275.14    5635 1279.37  5657.9 1284.79    5666 1293.65  5672.3 1294.43
  5680.4 1302.36    5686 1302.99  5730.2 1324.39  5815.2 1340.93  6094.7 1350.59
  6320.7 1359.55  6406.6 1359.81    6557 1361.28    6662 1362.02  6670.9 1361.81
#Mann= 12 ,-1 , 0
  4595.8     .12       0  4691.3     .07       0  5014.1     .05       0
  5033.7     .07       0  5086.7     .12       0  5108.9     .07       0
    5316    .035       0    5635     .12       0  6094.7     .07       0
  6406.6    .035       0    6557     .07       0    6662    .035       0
Bank Sta=5014.1,5033.7
XS Rating Curve= 0 ,0
Exp/Cntr=0.3,0.1

Type RM Length L Ch R = 1 ,18087   ,310,310,310
BEGIN DESCRIPTION:
SABINAS CREEK 32.0
END DESCRIPTION:
XS GIS Cut Line= 3
        2062675.       13866575.      2062807.39     13866120.47
      2063283.08     13865130.89
#Sta/Elev= 30
  4531.1 1316.68  4580.9 1308.36  4625.3 1301.53  4653.8  1292.4  4759.3 1272.46
  4812.3 1268.94  4856.9 1269.99  4875.4  1268.3  4903.7 1260.65  4973.1 1258.74
  4989.8 1256.92  4990.3 1256.42  5009.4 1256.92  5030.4 1261.71  5075.7 1265.56
  5197.6 1264.57  5387.8 1266.76  5426.3 1263.62  5432.2  1259.5  5457.8 1262.57
  5494.3 1280.78  5516.9 1299.02  5532.1 1307.87  5539.5 1317.57  5545.1 1321.62
  5567.7 1332.71    5987 1362.35  6054.9 1364.75  6087.5 1368.11  6102.5 1369.65
#Mann= 11 ,-1 , 0
  4531.1     .07       0  4580.9    .035       0  4653.8     .07       0
  4856.9    .035       0  4973.1     .07       0  4989.8     .05       0
  5009.4     .07       0  5197.6    .035       0  5457.8     .12       0
  6054.9    .035       0  6087.5     .07       0
Bank Sta=4989.8,5009.4
XS Rating Curve= 0 ,0
Exp/Cntr=0.3,0.1

Type RM Length L Ch R = 1 ,17777   ,546,546,546
BEGIN DESCRIPTION:
SABINAS CREEK 31.0
END DESCRIPTION:
XS GIS Cut Line= 3
      2062886.43     13866483.79        2063075.       13866075.
      2063220.25     13865435.78
#Sta/Elev= 30
  4556.9 1289.37  4568.8 1286.17  4637.6 1277.01  4660.6 1271.48    4712 1266.68
  4780.8 1265.62  4878.1 1267.34  4895.6 1262.68  4901.1 1263.12    4947  1257.9
  4975.4 1256.37  5050.1 1256.54  5069.6 1256.04  5070.1 1255.54  5089.2 1256.04
  5117.3 1262.56  5251.7 1261.39  5263.5 1259.41    5284 1259.63  5294.2 1265.61
  5299.9  1271.4  5335.2 1290.04  5348.1 1300.35  5355.8 1304.28    5366 1313.02
  5396.8 1329.83    5407 1332.27  5622.4 1347.26  5642.9 1347.59  5662.6 1350.04
#Mann= 4 ,-1 , 0
  4556.9    .035       0  5050.1     .12       0  5069.6    .035       0
  5089.2     .12       0
Bank Sta=5069.6,5089.2
XS Rating Curve= 0 ,0
Exp/Cntr=0.3,0.1

Type RM Length L Ch R = 1 ,17231   ,522,522,522
BEGIN DESCRIPTION:
SABINAS CREEK 30.0
END DESCRIPTION:
XS GIS Cut Line= 3
      2062725.02     13866624.99        2063525.       13866225.
      2063724.99     13865875.01
#Sta/Elev= 30
  4109.3 1319.62  4190.3 1314.28  4324.6 1294.28  4369.2 1284.56  4475.4 1273.55
  4525.7 1264.72    4627 1262.05  4661.2  1262.6  4814.6 1265.49  4824.8 1266.33
  4867.8 1253.94  4868.3 1253.44  4888.1 1253.94  4900.3 1257.37  4905.8 1255.61
  5011.6 1254.57  5033.2 1260.55    5039 1267.47  5049.1 1270.05  5054.8 1274.54
  5070.6 1276.46    5098 1286.66  5129.7 1293.43    5157 1302.94  5172.9 1304.99
  5178.6 1308.34  5237.7 1318.89  5312.5 1328.26  5355.7 1337.78  5406.8 1342.08
#Mann= 8 ,-1 , 0
  4109.3     .07       0  4324.6    .035       0    4627     .07       0
  4661.2    .035       0  4814.6     .07       0  4867.8     .05       0
  4888.1     .07       0  4905.8     .12       0
Bank Sta=4867.8,4888.1
XS Rating Curve= 0 ,0
Exp/Cntr=0.3,0.1

Type RM Length L Ch R = 1 ,16709   ,570,570,570
BEGIN DESCRIPTION:
SABINAS CREEK 29.0
END DESCRIPTION:
XS GIS Cut Line= 3
      2062874.96       13866675.        2063675.       13866675.
      2064095.55     13866676.43
#Sta/Elev= 30
  4194.9 1308.16  4244.9 1303.13  4316.1 1288.82  4334.9 1285.17  4394.9 1277.64
    4426 1275.18  4474.9 1271.15  4554.9 1262.25  4595.9 1259.42  4724.9 1259.55
  4894.9  1263.2  4904.9 1262.59  4914.9 1259.81  4934.9 1256.98  4960.1 1254.31
  4984.9 1251.65  4994.8 1248.85  4995.3 1248.35  5015.1 1248.85  5058.7  1254.8
  5084.9 1255.77  5094.9  1257.7  5104.9  1262.4  5114.9 1276.24  5154.9 1301.78
  5174.9 1312.41  5194.9 1315.55  5274.9 1313.13  5306.2 1313.92  5415.5  1318.2
#Mann= 9 ,-1 , 0
  4194.9     .07       0  4316.1     .12       0    4426     .07       0
  4595.9    .035       0  4960.1     .07       0  4994.8     .05       0
  5015.1     .07       0  5058.7     .12       0  5306.2     .07       0
Bank Sta=4994.8,5015.1
XS Rating Curve= 0 ,0
Exp/Cntr=0.3,0.1

Type RM Length L Ch R = 1 ,16139   ,559,559,559
BEGIN DESCRIPTION:
SABINAS CREEK 28.0
END DESCRIPTION:
XS GIS Cut Line= 3
      2062774.96     13866774.98        2063575.       13867175.
      2063775.01     13867525.01
#Sta/Elev= 30
  4105.5 1316.63  4150.3 1315.08  4161.9 1312.58  4253.7 1295.05  4298.4 1280.94
  4337.5 1271.81  4365.5 1262.71  4386.5 1260.57  4544.4 1259.62  4650.6 1256.12
  4932.9 1259.34  4941.3 1259.17  4952.8 1256.06  4977.6 1251.22    4987 1246.76
  4987.5 1246.26  5007.3 1246.76  5051.1 1252.17  5057.6 1271.51  5072.7 1285.67
  5080.6 1287.57  5094.3 1288.24  5110.1 1284.31  5190.7 1273.29  5206.6 1273.85
  5287.2 1286.28  5322.5 1295.65  5345.5 1297.68  5373.6 1303.67  5403.1 1305.39
#Mann= 6 ,-1 , 0
  4105.5     .07       0  4161.9     .12       0  4386.5    .035       0
  4952.8     .12       0    4987     .05       0  5007.3     .12       0
Bank Sta=4987,5007.3
XS Rating Curve= 0 ,0
Exp/Cntr=0.3,0.1

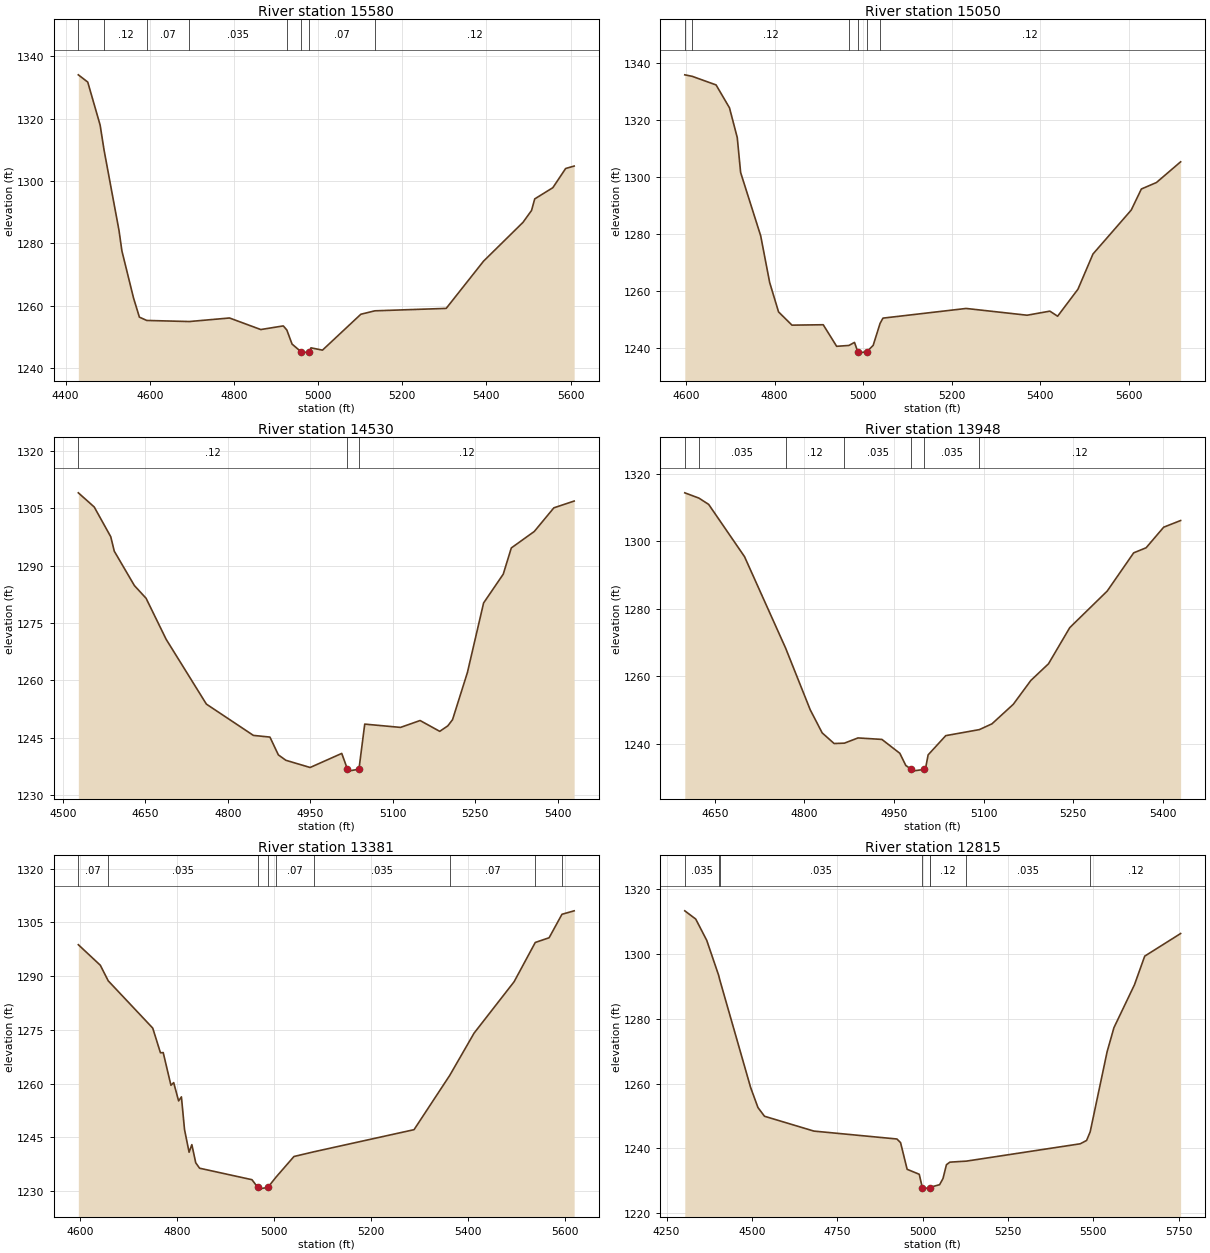
Type RM Length L Ch R = 1 ,15580   ,530,530,530
BEGIN DESCRIPTION:
SABINAS CREEK 27.0
END DESCRIPTION:
XS GIS Cut Line= 3
      2062575.02     13867325.01        2063125.       13867475.
      2063724.96     13867574.99
#Sta/Elev= 30
  4430.2  1334.1  4452.6 1331.77    4482 1317.97  4491.4 1309.91  4526.9 1284.11
  4533.8 1277.54  4561.5  1262.4  4575.3 1256.32  4592.7 1255.25    4694  1254.9
  4789.5 1256.04  4863.8 1252.33  4917.3  1253.5  4925.7 1252.18  4938.1 1247.67
    4959 1245.26  4959.5 1244.76  4979.4 1245.26    4983 1246.46  5010.4 1245.72
  5101.6 1257.24  5134.9 1258.34  5304.4 1259.12  5393.1 1274.27  5486.9 1286.74
  5507.2 1290.55  5514.8 1294.27  5557.9 1297.87  5588.3 1304.03  5608.5 1304.81
#Mann= 8 ,-1 , 0
  4430.2     .07       0  4491.4     .12       0  4592.7     .07       0
    4694    .035       0  4925.7     .07       0    4959     .05       0
  4979.4     .07       0  5134.9     .12       0
Bank Sta=4959,4979.4
XS Rating Curve= 0 ,0
Exp/Cntr=0.3,0.1

Type RM Length L Ch R = 1 ,15050   ,520,520,520
BEGIN DESCRIPTION:
SABINAS CREEK 26.0
END DESCRIPTION:
XS GIS Cut Line= 3
      2062674.99       13867975.        2063075.       13867925.
      2063724.99       13867625.
#Sta/Elev= 30
  4597.5 1335.82  4614.3 1335.29  4668.1 1332.28  4698.3 1324.27  4715.9 1313.83
  4723.5 1301.58  4768.8 1279.37    4789 1263.04  4809.1  1252.7  4839.4 1248.06
  4909.9  1248.2  4940.2 1240.64  4967.9 1240.94  4980.5 1242.01  4987.9 1238.75
  4988.4 1238.25  5008.3 1238.75  5022.6 1240.96  5038.2 1248.66  5044.7 1250.52
  5232.4 1253.91    5370 1251.54  5421.4 1252.97  5438.9 1251.19  5484.8 1260.66
  5518.7    1273    5605  1288.4  5627.9 1295.79  5661.9 1298.06  5716.5 1305.32
#Mann= 6 ,-1 , 0
  4597.5     .07       0  4614.3     .12       0  4967.9     .07       0
  4987.9     .05       0  5008.3     .07       0  5038.2     .12       0
Bank Sta=4987.9,5008.3
XS Rating Curve= 0 ,0
Exp/Cntr=0.3,0.1

Type RM Length L Ch R = 1 ,14530   ,582,582,582
BEGIN DESCRIPTION:
SABINAS CREEK 25.0
END DESCRIPTION:
XS GIS Cut Line= 3
        2063775.       13868425.        2063525.       13868025.
      2063774.99     13867675.01
#Sta/Elev= 30
  4528.3 1309.05  4557.2 1305.35  4587.3 1297.56  4593.7 1293.79  4630.3  1284.8
  4651.5 1281.49  4688.1 1270.74  4761.2 1253.82  4846.7 1245.64  4876.8  1245.2
  4892.1 1240.55  4905.7 1239.14  4949.9 1237.25  5007.4 1240.93  5017.8  1236.8
  5018.3  1236.3  5038.7  1236.8  5049.2 1248.59  5114.3 1247.73  5149.9 1249.53
  5185.6  1246.7  5200.3 1248.13  5208.9 1249.75  5235.9 1262.05  5265.4 1280.26
  5301.1 1287.78  5315.8 1294.64  5357.6 1298.95  5393.2 1305.13  5430.1  1306.9
#Mann= 3 ,-1 , 0
  4528.3     .12       0  5017.8     .05       0  5038.7     .12       0
Bank Sta=5017.8,5038.7
XS Rating Curve= 0 ,0
Exp/Cntr=0.3,0.1

Type RM Length L Ch R = 1 ,13948   ,567,567,567
BEGIN DESCRIPTION:
SABINAS CREEK 24.0
END DESCRIPTION:
XS GIS Cut Line= 3
        2064075.     13868424.99        2064075.       13868025.
        2063825.     13867675.01
#Sta/Elev= 30
  4599.9 1314.44  4623.6 1312.87  4639.9    1311  4699.9  1295.5  4768.7 1268.36
  4809.9 1250.06  4829.9 1243.21  4849.9 1240.05  4867.1 1240.16  4889.9 1241.71
  4929.9 1241.27  4959.9 1237.15  4969.9 1233.54  4979.4 1232.36  4979.9 1231.86
  5000.3 1232.36    5003 1232.74  5007.3 1236.69  5036.8 1242.39  5093.1 1244.18
  5114.2  1245.9  5149.8 1251.68  5179.3 1258.78  5208.8 1263.71  5244.4 1274.44
  5307.1 1285.29  5351.4 1296.63  5372.2 1298.13  5401.7 1304.25    5430 1306.22
#Mann= 7 ,-1 , 0
  4599.9     .07       0  4623.6    .035       0  4768.7     .12       0
  4867.1    .035       0  4979.4    .035       0  5000.3    .035       0
  5093.1     .12       0
Bank Sta=4979.4,5000.3
XS Rating Curve= 0 ,0
Exp/Cntr=0.3,0.1

Type RM Length L Ch R = 1 ,13381   ,566,566,566
BEGIN DESCRIPTION:
SABINAS CREEK 23.0
END DESCRIPTION:
XS GIS Cut Line= 3
        2064425.       13868325.        2064625.       13867975.
      2064474.99     13867374.98
#Sta/Elev= 30
  4596.8 1298.77  4642.1 1293.04  4658.4 1288.69  4750.1 1275.49    4766  1268.6
  4771.7 1268.65  4787.6 1259.53  4793.3 1260.26  4803.4 1255.16  4809.2 1256.29
  4815.6 1247.17    4825 1240.83  4830.7 1242.95  4838.7 1237.89  4846.6 1236.37
  4954.6 1233.16  4966.4 1231.03  4966.9 1230.53  4987.4 1231.03    5004 1233.86
  5041.1 1239.64    5082 1240.95  5288.5 1247.13  5362.2 1262.32  5412.2 1274.08
  5494.7 1288.44  5538.3  1299.4  5566.8 1300.71  5593.3 1307.27  5618.4 1308.23
#Mann= 9 ,-1 , 0
  4596.8     .07       0  4658.4    .035       0  4966.4    .035       0
  4987.4    .035       0    5004     .07       0    5082    .035       0
  5362.2     .07       0  5538.3    .035       0  5593.3     .07       0
Bank Sta=4966.4,4987.4
XS Rating Curve= 0 ,0
Exp/Cntr=0.3,0.1

Type RM Length L Ch R = 1 ,12815   ,544,544,544
BEGIN DESCRIPTION:
SABINAS CREEK 22.0
END DESCRIPTION:
XS GIS Cut Line= 3
      2064925.01     13868674.98        2065175.       13868025.
      2065133.78     13867269.92
#Sta/Elev= 30
  4303.3 1313.38  4335.4 1310.83  4367.6 1304.26  4402.5 1293.46  4405.8 1292.07
  4496.1 1258.85  4517.6 1252.64  4536.8 1249.95  4681.5 1245.37  4924.7 1242.93
  4935.4 1241.81  4954.7 1233.57  4990.1 1232.04  4999.2 1227.95  4999.7 1227.45
  5020.2 1227.95  5020.9 1227.99  5049.8 1228.82  5059.8 1230.74  5069.8 1234.98
  5079.8 1235.78  5128.5  1236.1  5461.9 1241.45  5480.4 1242.48  5490.9 1245.12
  5540.5 1269.85  5560.5  1277.3  5620.6 1290.53  5650.7 1299.39  5755.9 1306.37
#Mann= 8 ,-1 , 0
  4303.3    .035       0  4402.5     .07       0  4405.8    .035       0
  4999.2    .035       0  5020.2    .035       0  5020.9     .12       0
  5128.5    .035       0  5490.9     .12       0
Bank Sta=4999.2,5020.2
XS Rating Curve= 0 ,0
Exp/Cntr=0.3,0.1

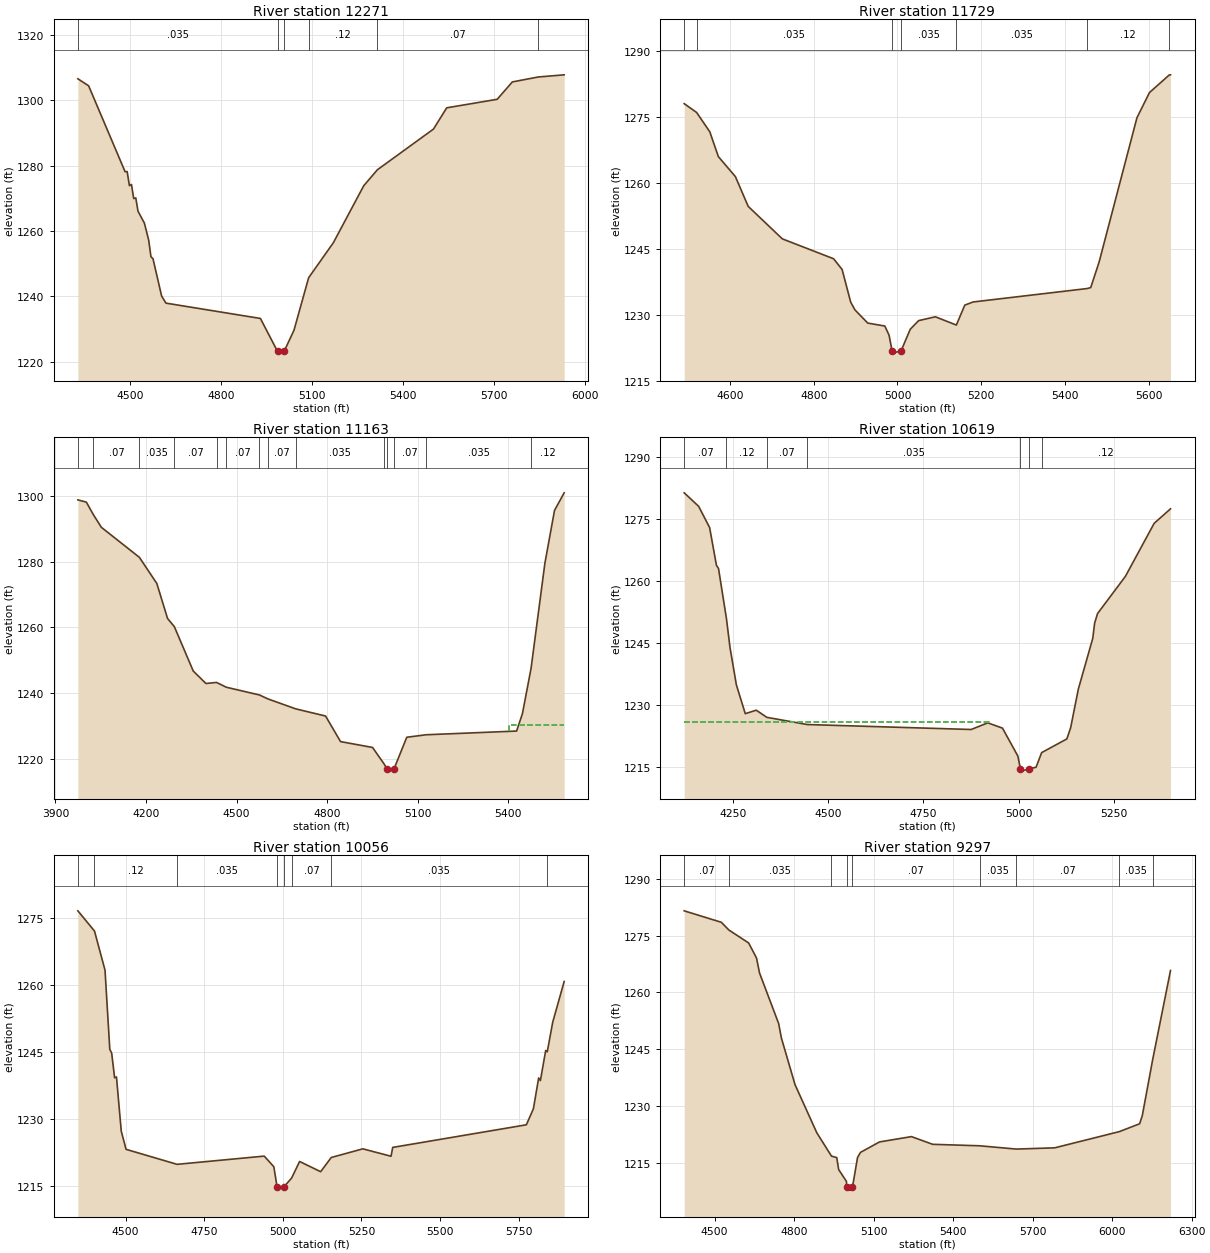
Type RM Length L Ch R = 1 ,12271   ,542,542,542
BEGIN DESCRIPTION:
SABINAS CREEK 21.0
END DESCRIPTION:
XS GIS Cut Line= 3
      2065175.01     13868724.99        2065625.       13868225.
      2065616.42     13867294.11
#Sta/Elev= 30
    4327 1306.62  4362.5 1304.47  4482.8 1278.14  4489.6  1278.2    4497 1273.87
  4503.8 1274.25  4511.2 1269.94    4518 1270.12  4525.4 1266.04  4546.4  1262.4
  4560.6 1257.19    4568 1252.13  4574.8 1251.47  4603.2 1240.07  4617.4 1237.89
    4929 1233.19  4985.6 1223.07  4986.1 1222.57    5007 1223.07  5039.7 1229.58
    5088 1245.66  5169.7 1256.42  5269.7 1273.85  5314.7 1278.74  5499.7 1291.21
  5543.3 1297.72  5709.7 1300.33  5759.7 1305.65  5845.3 1307.17  5930.6 1307.83
#Mann= 6 ,-1 , 0
    4327    .035       0  4985.6    .035       0    5007    .035       0
    5088     .12       0  5314.7     .07       0  5845.3     .12       0
Bank Sta=4985.6,5007
XS Rating Curve= 0 ,0
Exp/Cntr=0.3,0.1

Type RM Length L Ch R = 1 ,11729   ,566,566,566
BEGIN DESCRIPTION:
SABINAS CREEK 20.0
END DESCRIPTION:
XS GIS Cut Line= 3
      2065975.01     13868974.97        2066075.       13868475.
        2066125.     13867824.99
#Sta/Elev= 30
  4490.5 1278.04  4520.2 1276.03  4551.7 1271.62  4572.1 1265.98  4612.8 1261.43
  4643.4 1254.65    4725 1247.25  4847.4 1242.73  4867.8 1240.27  4888.2 1232.86
  4898.4 1231.09    4929 1228.08  4969.8 1227.41    4980  1225.3  4987.1 1221.74
  4987.6 1221.24  5008.6 1221.74  5030.5 1226.67  5050.5 1228.64  5090.6 1229.51
  5140.7 1227.63  5160.8 1232.17  5180.9 1232.89  5452.8 1235.94  5461.7 1236.16
  5481.8    1242  5572.1 1274.82  5602.1 1280.57  5649.6 1284.59  5652.3  1284.6
#Mann= 7 ,-1 , 0
  4490.5     .07       0  4520.2    .035       0  4987.1     .05       0
  5008.6    .035       0  5140.7    .035       0  5452.8     .12       0
  5649.6     .07       0
Bank Sta=4987.1,5008.6
XS Rating Curve= 0 ,0
Exp/Cntr=0.3,0.1

Type RM Length L Ch R = 1 ,11163   ,544,544,544
BEGIN DESCRIPTION:
SABINAS CREEK 19.0
END DESCRIPTION:
XS GIS Cut Line= 3
      2065925.02     13869174.98        2066625.       13868425.
      2066824.99     13867875.02
#Sta/Elev= 30
  3974.1 1298.77  4002.2  1298.1  4025.4 1294.29    4052 1290.43  4177.9  1281.3
  4235.7 1273.35  4271.3  1262.7  4293.9 1260.19  4356.4 1246.71  4398.4 1242.92
  4433.7 1243.24  4465.6 1241.79  4575.7 1239.43  4603.2 1238.25  4695.6 1235.21
  4794.8 1233.02  4844.4 1225.24  4950.4 1223.46  4988.8 1218.43  4999.2 1216.76
  4999.7 1216.26  5020.7 1216.76  5063.8 1226.56  5127.5 1227.32  5427.6 1228.45
  5446.9 1233.72  5475.6 1247.54  5521.4 1279.51  5553.3 1295.58  5585.2 1300.92
#Mann= 14 ,-1 , 0
  3974.1    .035       0  4025.4     .07       0  4177.9    .035       0
  4293.9     .07       0  4433.7    .035       0  4465.6     .07       0
  4575.7    .035       0  4603.2     .07       0  4695.6    .035       0
  4988.8     .07       0  4999.2     .05       0  5020.7     .07       0
  5127.5    .035       0  5475.6     .12       0
#XS Ineff= 2 , 0
       0                 5403.64       0 1230.36
Permanent Ineff=
       F       F
Bank Sta=4999.2,5020.7
XS Rating Curve= 0 ,0
Exp/Cntr=0.3,0.1

Type RM Length L Ch R = 1 ,10619   ,563,563,563
BEGIN DESCRIPTION:
SABINAS CREEK 18.0
END DESCRIPTION:
XS GIS Cut Line= 3
      2066724.98     13869425.04        2067075.       13868625.
        2067125.     13868224.97
#Sta/Elev= 30
  4122.2 1281.42  4160.1 1278.16  4188.9 1273.02  4206.8  1263.9  4212.3  1263.1
  4233.2 1250.93  4242.3 1244.07  4259.1 1234.98  4282.5    1228  4311.3 1228.84
  4339.2 1227.11  4445.1 1225.37  4875.4 1224.17  4919.1 1225.78  4957.6  1224.5
    4998 1217.74  5004.8  1214.6  5005.3  1214.1  5026.4  1214.6  5045.8 1215.05
  5060.4 1218.58  5126.5 1221.89  5136.5 1224.59  5156.7 1233.94  5194.5  1246.2
  5199.5 1249.92  5207.1 1252.21  5280.2 1261.21  5355.7 1274.04  5398.6 1277.55
#Mann= 7 ,-1 , 0
  4122.2     .07       0  4233.2     .12       0  4339.2     .07       0
  4445.1    .035       0  5004.8    .035       0  5026.4    .035       0
  5060.4     .12       0
#XS Ineff= 2 , 0
       0 4921.72  1225.9               0
Permanent Ineff=
       F       F
Bank Sta=5004.8,5026.4
XS Rating Curve= 0 ,0
Exp/Cntr=0.3,0.1

Type RM Length L Ch R = 1 ,10056   ,759,759,759
BEGIN DESCRIPTION:
SABINAS CREEK 17.0
END DESCRIPTION:
XS GIS Cut Line= 3
      2067074.98     13869575.03        2067425.       13869025.
      2067825.01     13868224.99
#Sta/Elev= 30
  4348.3 1276.51  4401.2 1271.99  4434.7 1263.22  4449.9  1245.5  4455.9 1244.65
  4465.2 1239.13  4471.1 1239.33  4486.3  1227.2  4501.6 1223.12  4663.8 1219.76
    4941  1221.6  4971.5 1219.22  4981.8 1214.71  4982.3 1214.21  5003.4 1214.71
    5028 1216.68  5053.4  1220.4  5120.4 1218.11    5154 1221.29  5254.6 1223.23
  5344.1 1221.57  5349.6 1223.55  5774.5 1228.61  5796.9  1232.2  5813.6  1239.1
  5819.2 1238.52    5836 1245.25    5841 1244.94  5858.3 1251.57  5894.7 1260.69
#Mann= 8 ,-1 , 0
  4348.3     .07       0  4401.2     .12       0  4663.8    .035       0
  4981.8    .035       0  5003.4    .035       0    5028     .07       0
    5154    .035       0    5841     .12       0
Bank Sta=4981.8,5003.4
XS Rating Curve= 0 ,0
Exp/Cntr=0.3,0.1

Type RM Length L Ch R = 1 ,9297    ,502,502,502
BEGIN DESCRIPTION:
SABINAS CREEK 16.0
END DESCRIPTION:
XS GIS Cut Line= 3
       2067744.7      13870021.2      2067919.74     13869300.24
      2067874.78     13868208.57
#Sta/Elev= 30
  4385.7 1281.53  4525.9  1278.5  4554.1 1276.47  4628.8 1273.05  4658.5 1269.08
  4669.9 1265.12    4742 1251.78  4752.3 1247.97  4803.7 1235.66    4886 1222.94
  4941.2 1216.79  4961.2 1216.39  4968.4 1213.23  4997.8 1210.11  4998.7 1208.57
  4999.2 1208.07  5020.4 1208.57  5039.6 1216.42  5050.7 1217.77  5122.6 1220.53
  5242.9 1221.93    5323  1219.9    5500 1219.51  5638.9 1218.64  5783.4 1218.97
  6027.2 1223.25  6103.7 1225.32  6113.7 1227.44  6153.4 1242.43  6220.2 1265.77
#Mann= 9 ,-1 , 0
  4385.7     .07       0  4554.1    .035       0  4941.2     .07       0
  4998.7     .05       0  5020.4     .07       0    5500    .035       0
  5638.9     .07       0  6027.2    .035       0  6153.4     .12       0
Bank Sta=4998.7,5020.4
XS Rating Curve= 0 ,0
Exp/Cntr=0.3,0.1

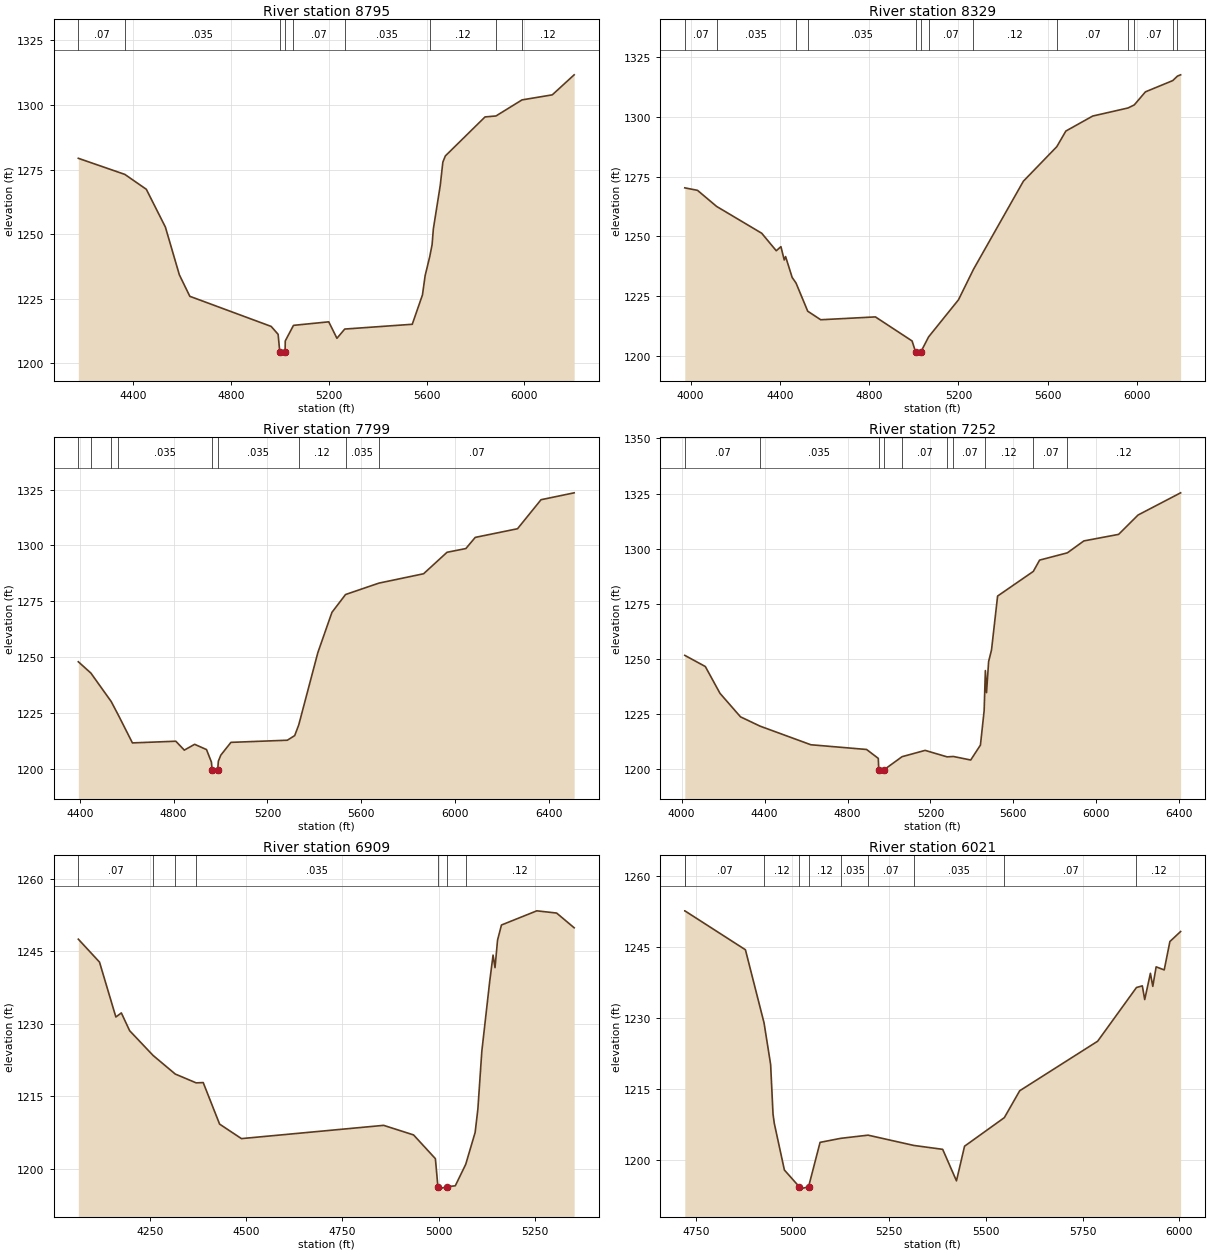
Type RM Length L Ch R = 1 ,8795    ,466,466,466
BEGIN DESCRIPTION:
Sabinas Creek 15.0
END DESCRIPTION:
XS GIS Cut Line= 3
      2067841.63       13870104.        2068375.       13869475.
      2068711.72     13868319.03
#Sta/Elev= 30
  4175.3 1279.35  4365.5 1273.12  4453.5 1267.35  4531.5 1252.72  4588.6 1234.25
  4631.5 1225.91  4964.3 1214.25  4992.8 1211.19  4999.5 1204.41    5000 1203.91
  5021.3 1204.41    5022 1208.64  5055.6 1214.66  5199.9 1216.03  5233.4 1209.65
  5265.3 1213.23  5541.6 1215.08  5583.3 1226.45  5594.4 1233.99  5613.1 1241.26
  5622.7 1245.89  5627.9 1252.01  5656.2 1268.91  5666.7 1277.85    5677 1280.27
  5839.4 1295.37  5884.1 1295.74  5990.6 1301.96  6114.5 1303.92    6204 1311.67
#Mann= 9 ,-1 , 0
  4175.3     .07       0  4365.5    .035       0  4999.5    .035       0
  5021.3    .035       0  5055.6     .07       0  5265.3    .035       0
  5613.1     .12       0  5884.1     .07       0  5990.6     .12       0
Bank Sta=4999.5,5021.3
XS Rating Curve= 0 ,0
Exp/Cntr=0.3,0.1

Type RM Length L Ch R = 1 ,8329    ,530,530,530
BEGIN DESCRIPTION:
Sabinas Creek 14.0
END DESCRIPTION:
XS GIS Cut Line= 3
      2068230.53     13870361.45        2068825.       13869525.
      2068911.32     13868331.89
#Sta/Elev= 30
  3973.7 1270.36  4030.7 1269.32  4116.1  1262.6  4318.5 1251.36  4383.7 1244.04
  4404.6 1245.76  4419.4 1240.17  4425.5  1241.6    4455 1232.85  4472.2 1230.54
  4524.7 1218.74  4582.9 1215.16  4828.1 1216.35  4992.5 1206.28  5008.2 1201.69
  5008.7 1201.19  5031.7 1201.69  5066.5 1207.99  5200.4 1223.51  5267.6 1236.25
  5491.2 1273.13    5641 1287.58  5681.7 1294.13    5802 1300.41  5960.5 1303.79
  5988.3 1305.07  6038.4 1310.54  6160.6 1315.24    6182 1317.13  6196.1 1317.66
#Mann= 13 ,-1 , 0
  3973.7     .07       0  4116.1    .035       0  4472.2     .07       0
  4524.7    .035       0  5008.2    .035       0  5031.7    .035       0
  5066.5     .07       0  5267.6     .12       0    5641     .07       0
  5960.5    .035       0  5988.3     .07       0  6160.6    .035       0
    6182     .07       0
Bank Sta=5008.2,5031.7
XS Rating Curve= 0 ,0
Exp/Cntr=0.3,0.1

Type RM Length L Ch R = 1 ,7799    ,547,547,547
BEGIN DESCRIPTION:
SABINAS CREEK 13.0
END DESCRIPTION:
XS GIS Cut Line= 3
      2068974.99     13870125.01        2069325.       13869625.
      2069251.83     13868123.92
#Sta/Elev= 30
  4393.9 1247.98  4447.5 1242.91  4533.8 1230.23    4565 1224.01  4624.5  1211.7
  4809.4 1212.45  4845.6 1208.47  4889.6 1211.07  4940.2 1208.72  4961.1 1203.13
  4964.2 1199.58  4964.7 1199.08  4987.7 1199.58  4990.7 1203.54  5001.2 1206.24
  5044.3 1211.94  5284.6  1212.9    5316 1214.97  5333.2 1219.72  5414.7 1252.06
  5474.8 1270.08  5532.8 1278.05  5675.1 1283.15  5865.3 1287.33  5965.4 1296.94
  6045.5  1298.6  6085.5 1303.59  6265.7 1307.46  6365.9 1320.44  6507.1 1323.52
#Mann= 9 ,-1 , 0
  4393.9     .07       0  4447.5     .12       0  4533.8     .07       0
    4565    .035       0  4964.2    .035       0  4987.7    .035       0
  5333.2     .12       0  5532.8    .035       0  5675.1     .07       0
Bank Sta=4964.2,4987.7
XS Rating Curve= 0 ,0
Exp/Cntr=0.3,0.1

Type RM Length L Ch R = 1 ,7252    ,343,343,343
BEGIN DESCRIPTION:
SABINAS CREEK 12.0
END DESCRIPTION:
XS GIS Cut Line= 3
      2069125.03     13870474.97        2069825.       13869775.
      2071121.68     13869242.68
#Sta/Elev= 30
  4015.1 1251.63  4114.1 1246.57  4184.8 1234.41  4283.8 1223.75  4377.9 1219.54
  4623.2 1211.09  4891.9 1208.95  4948.4 1204.91  4950.8 1199.63  4951.3 1199.13
  4974.3 1199.63  5063.1 1205.68  5174.4 1208.54  5280.2  1205.6  5310.5 1205.77
  5394.2 1204.17  5441.1 1210.95    5459 1226.58  5464.9 1244.72  5470.5 1234.71
  5480.6 1248.84  5494.5 1254.07  5523.9 1278.52  5696.1 1289.69  5726.5 1294.82
  5860.5 1298.12  5939.9 1303.52  6107.6 1306.49  6201.3 1315.26  6406.7 1325.33
#Mann= 10 ,-1 , 0
  4015.1     .07       0  4377.9    .035       0  4950.8    .035       0
  4974.3    .035       0  5063.1     .07       0  5280.2    .035       0
  5310.5     .07       0  5464.9     .12       0  5696.1     .07       0
  5860.5     .12       0
Bank Sta=4950.8,4974.3
XS Rating Curve= 0 ,0
Exp/Cntr=0.3,0.1

Type RM Length L Ch R = 1 ,6909    ,888,888,888
BEGIN DESCRIPTION:
SABINAS CREEK 11.0
END DESCRIPTION:
XS GIS Cut Line= 3
        2069295.     13870562.96      2069836.76     13870054.55
      2070370.13     13869950.38
#Sta/Elev= 30
  4064.8 1247.48  4119.7 1242.75  4162.2  1231.4  4176.4 1232.24  4197.9 1228.57
  4258.7 1223.46  4316.3 1219.61  4370.5 1217.79  4388.8 1217.85  4431.3 1209.27
    4488 1206.27  4856.9 1209.01  4934.6 1207.03  4991.2 1202.12  4997.7 1196.33
  4998.2 1195.83  5021.7 1196.33  5042.8 1196.52  5069.8 1200.94  5094.3 1207.54
  5101.4 1212.38  5111.6 1224.28    5132 1238.69  5140.8 1244.19  5145.9  1241.6
  5152.4 1247.27  5162.6 1250.41  5254.3 1253.34  5305.7 1252.88  5351.2 1249.84
#Mann= 7 ,-1 , 0
  4064.8     .07       0  4258.7     .12       0  4316.3     .07       0
  4370.5    .035       0  4997.7    .035       0  5021.7    .035       0
  5069.8     .12       0
Bank Sta=4997.7,5021.7
XS Rating Curve= 0 ,0
Exp/Cntr=0.3,0.1

Type RM Length L Ch R = 1 ,6021    ,388,388,388
BEGIN DESCRIPTION:
SABINAS CREEK 10.1
END DESCRIPTION:
XS GIS Cut Line= 2
      2069699.22     13870988.06      2070445.21     13869946.19
#Sta/Elev= 30
  4721.7 1252.63  4721.8 1252.63  4878.4 1244.42  4926.5 1229.01  4943.5 1220.25
  4949.7  1209.8    4953 1207.81  4979.1 1197.98  5017.5 1194.45    5018 1193.95
  5041.6 1194.45  5071.3 1203.81  5124.7 1204.66  5195.3 1205.33  5313.7 1203.16
  5388.2 1202.34  5423.8  1195.7  5444.7    1203  5547.5 1209.02  5587.2 1214.69
  5788.7 1225.14    5889 1236.46  5904.1 1236.81  5910.3 1233.92    5925 1239.46
  5931.2 1236.71  5939.8 1240.82  5960.7 1240.17  5975.4 1246.16  6003.1 1248.27
#Mann= 10 ,-1 , 0
  4721.7    .035       0  4721.8     .07       0  4926.5     .12       0
  5017.5     .05       0  5041.6     .12       0  5124.7    .035       0
  5195.3     .07       0  5313.7    .035       0  5547.5     .07       0
    5889     .12       0
Bank Sta=5017.5,5041.6
XS Rating Curve= 0 ,0
Exp/Cntr=0.3,0.1