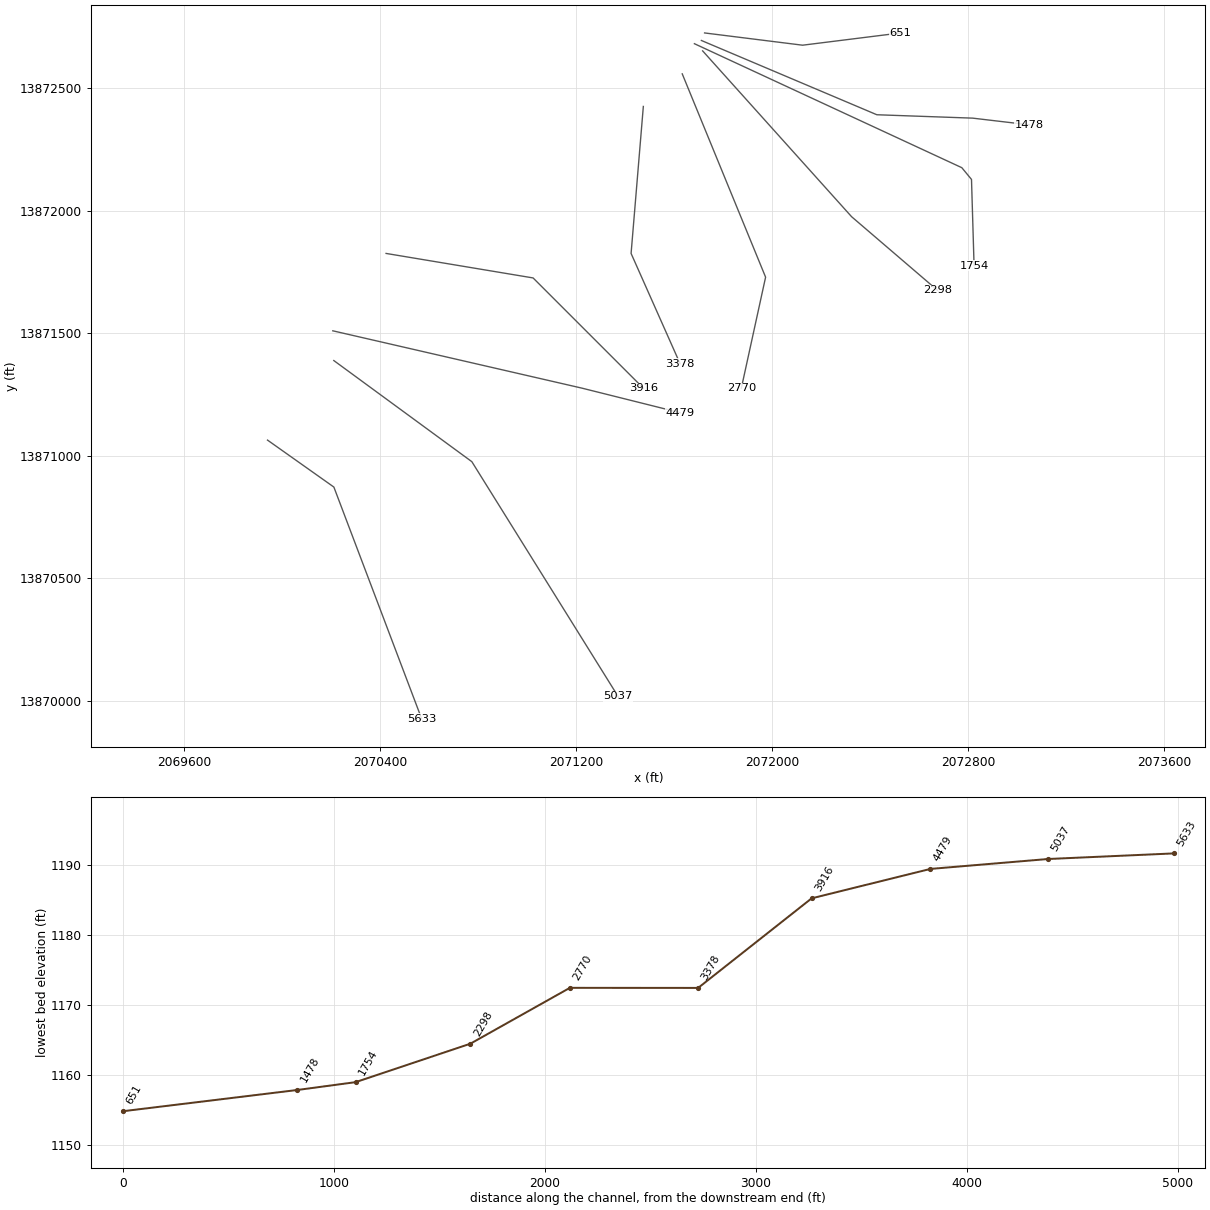
HEC-RAS study SABINAS CREEK.prj: SABINAS CREEK Base Level Engineering

--- SABINAS CREEK.g01 (geometry) --- (continued)

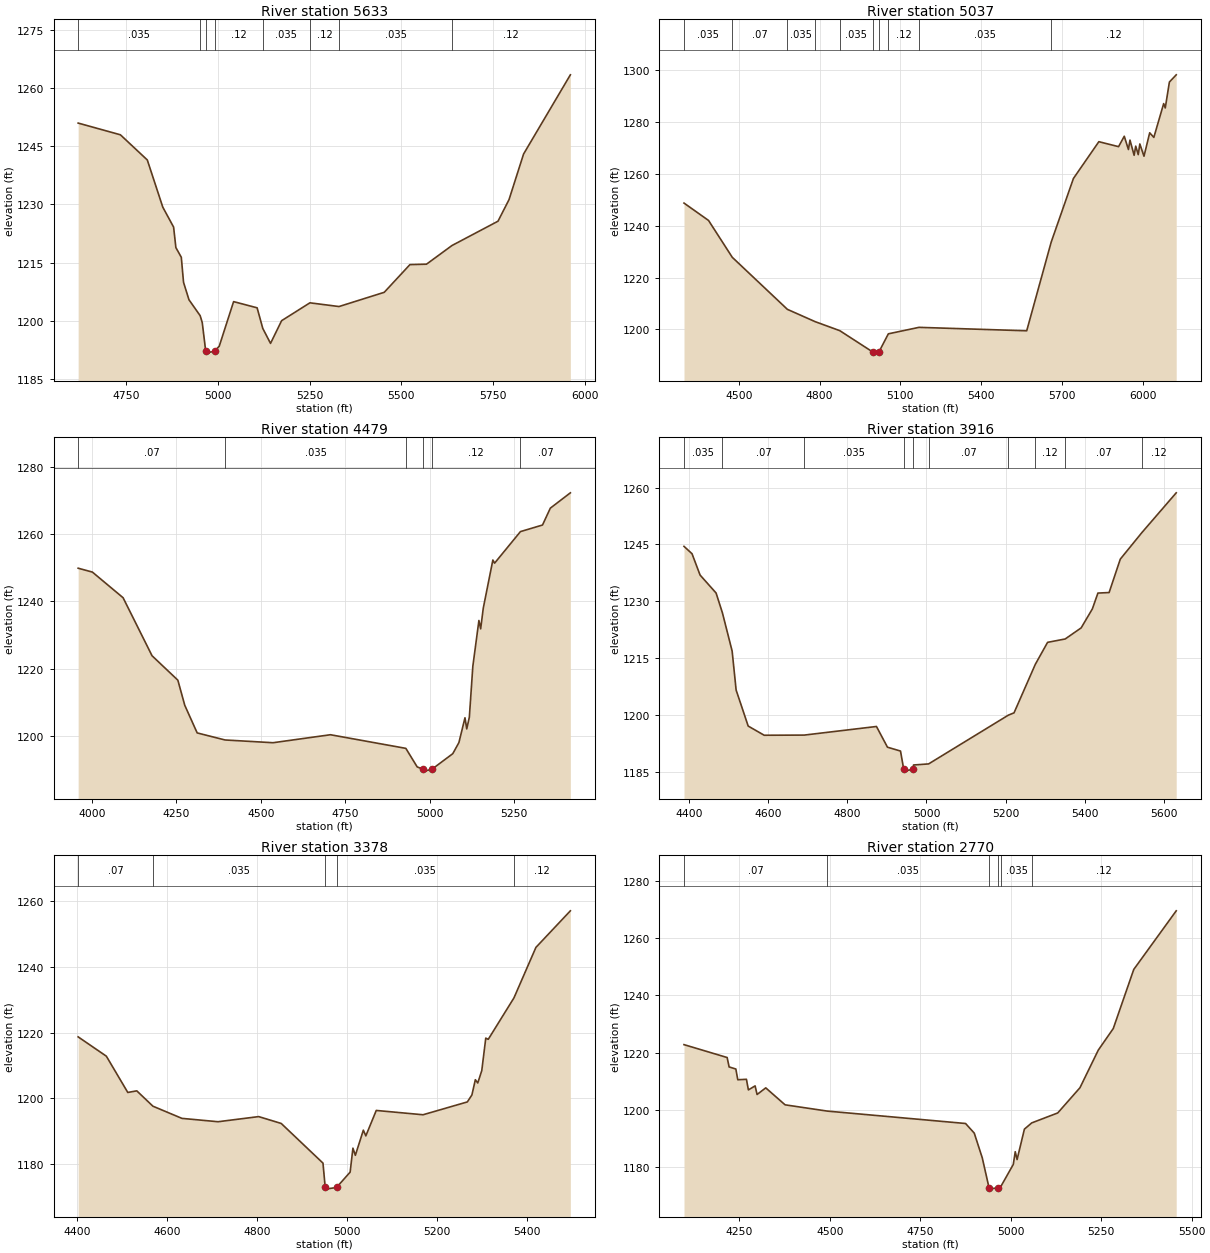
Type RM Length L Ch R = 1 ,5633    ,596,596,596
BEGIN DESCRIPTION:
SABINAS CREEK 10.0
END DESCRIPTION:
XS GIS Cut Line= 3
      2069940.94     13871063.07      2070211.82     13870871.37
      2070570.12     13869925.62
#Sta/Elev= 30
  4618.1 1250.99  4733.4 1247.97  4806.8 1241.48  4849.1 1229.31  4878.6 1224.17
  4884.8 1218.89  4899.6 1216.39  4905.7 1209.93  4920.5 1205.44  4951.1 1201.33
  4956.8 1199.53  4966.2 1192.18  4966.7 1191.68  4990.3 1192.18  5003.1 1193.46
  5042.3 1204.96  5106.5 1203.36  5121.9 1198.06  5143.1 1194.19  5173.3 1200.04
  5250.6 1204.65  5329.9 1203.69  5453.4 1207.36  5523.5  1214.5  5568.7 1214.61
  5638.2 1219.42  5763.8 1225.69  5793.9 1231.25  5833.6 1243.01  5961.3 1263.43
#Mann= 8 ,-1 , 0
  4618.1    .035       0  4951.1     .12       0  4966.2     .05       0
  4990.3     .12       0  5121.9    .035       0  5250.6     .12       0
  5329.9    .035       0  5638.2     .12       0
Bank Sta=4966.2,4990.3
XS Rating Curve= 0 ,0
Exp/Cntr=0.3,0.1

Type RM Length L Ch R = 1 ,5037    ,558,558,558
BEGIN DESCRIPTION:
SABINAS CREEK 9.0
END DESCRIPTION:
XS GIS Cut Line= 3
      2070211.51     13871387.81        2070775.       13870975.
      2071372.14     13870016.52
#Sta/Elev= 30
  4296.8 1248.74  4387.9 1242.04  4476.1 1227.82  4680.7 1207.76  4784.4 1202.99
  4875.1 1199.55  4996.8 1191.38  4997.3 1190.88  5020.9 1191.38  5055.6 1198.32
  5169.4 1200.82  5569.4 1199.49  5660.4 1233.71  5742.9 1258.23  5837.3 1272.41
  5910.5 1270.49  5931.7 1274.51  5947.1 1269.39  5952.9 1273.02  5968.3 1267.17
  5974.2  1270.7  5983.6 1267.42  5989.5 1271.54  6004.9  1266.8  6026.1 1275.84
  6041.5 1274.06    6078  1287.1  6083.9 1285.42  6099.3 1295.41  6124.6 1298.19
#Mann= 10 ,-1 , 0
  4296.8    .035       0  4476.1     .07       0  4680.7    .035       0
  4784.4     .12       0  4875.1    .035       0  4996.8    .035       0
  5020.9    .035       0  5055.6     .12       0  5169.4    .035       0
  5660.4     .12       0
Bank Sta=4996.8,5020.9
XS Rating Curve= 0 ,0
Exp/Cntr=0.3,0.1

Type RM Length L Ch R = 1 ,4479    ,563,563,563
BEGIN DESCRIPTION:
SABINAS CREEK 8.0
END DESCRIPTION:
XS GIS Cut Line= 3
      2070207.49     13871509.16        2071225.       13871275.
      2071624.98       13871175.
#Sta/Elev= 30
  3959.5  1249.9  4001.7 1248.74  4092.5  1241.1  4178.1 1223.83  4254.5 1216.55
    4275 1209.06  4311.7 1200.84  4394.1 1198.74  4536.1 1197.92    4706  1200.3
  4929.1 1196.24  4962.6 1190.73  4981.2 1189.96  4981.7 1189.46  5005.5 1189.96
    5068 1194.66  5086.1 1197.96  5104.1 1205.35  5109.3 1202.03    5117 1205.52
  5127.3 1220.66  5145.3 1234.33  5150.5 1231.84  5158.2    1238  5186.6 1252.34
  5191.7  1251.4  5268.2  1260.8  5333.5 1262.76  5356.6 1267.78  5415.9 1272.35
#Mann= 6 ,-1 , 0
  3959.5     .07       0  4394.1    .035       0  4929.1     .12       0
  4981.2     .05       0  5005.5     .12       0  5268.2     .07       0
Bank Sta=4981.2,5005.5
XS Rating Curve= 0 ,0
Exp/Cntr=0.3,0.1

Type RM Length L Ch R = 1 ,3916    ,538,538,538
BEGIN DESCRIPTION:
SABINAS CREEK 7.0
END DESCRIPTION:
XS GIS Cut Line= 3
      2070424.95     13871825.01        2071025.       13871725.
      2071474.99     13871275.01
#Sta/Elev= 30
  4386.9 1244.51  4407.2 1242.56  4427.5 1236.95    4468 1232.21  4484.1 1226.96
  4508.6 1216.91  4518.7 1206.63  4549.2 1197.13  4589.7 1194.71  4690.9 1194.75
  4873.6 1197.02  4901.4 1191.56  4934.4 1190.54  4942.5 1185.75    4943 1185.25
  4966.8 1185.75  4967.3 1186.87  5005.4 1187.15    5207    1200  5221.5 1200.62
  5275.3 1213.41  5306.3  1219.2  5350.8 1220.09  5391.2 1223.01  5419.5 1228.01
  5433.6 1232.19  5461.9 1232.33  5490.2 1241.14  5545.2 1248.19  5631.6 1258.62
#Mann= 10 ,-1 , 0
  4386.9    .035       0  4484.1     .07       0  4690.9    .035       0
  4942.5    .035       0  4966.8    .035       0  5005.4     .07       0
    5207    .035       0  5275.3     .12       0  5350.8     .07       0
  5545.2     .12       0
Bank Sta=4942.5,4966.8
XS Rating Curve= 0 ,0
Exp/Cntr=0.3,0.1

Type RM Length L Ch R = 1 ,3378    ,608,608,608
BEGIN DESCRIPTION:
SABINAS CREEK 6.0
END DESCRIPTION:
XS GIS Cut Line= 3
        2071475.     13872424.98        2071425.       13871825.
        2071625.       13871375.
#Sta/Elev= 30
  4402.3 1218.72    4465 1212.85  4512.7 1201.82  4532.7 1202.31  4568.6 1197.64
  4633.1 1193.94  4713.4 1192.92  4803.7 1194.48  4853.8  1192.4  4946.7 1180.34
  4951.7 1172.93  4952.2 1172.43  4976.8 1172.93  5007.1  1177.6  5013.3 1184.88
  5018.7 1182.71  5036.5 1190.36    5042 1188.62  5065.2 1196.35  5169.2 1195.04
  5267.7 1198.94  5277.9 1201.07  5285.5 1205.69  5290.9  1204.7  5299.8 1208.46
  5308.7 1218.34  5314.2 1217.97  5371.4 1230.58  5420.2 1245.92  5496.8 1257.04
#Mann= 5 ,-1 , 0
  4402.3     .07       0  4568.6    .035       0  4951.7    .035       0
  4976.8    .035       0  5371.4     .12       0
Bank Sta=4951.7,4976.8
XS Rating Curve= 0 ,0
Exp/Cntr=0.3,0.1

Type RM Length L Ch R = 1 ,2770    ,472,472,472
BEGIN DESCRIPTION:
SABINAS CREEK 5.0
END DESCRIPTION:
XS GIS Cut Line= 3
      2071633.78     13872557.97      2071974.05     13871728.11
        2071875.     13871275.02
#Sta/Elev= 30
  4096.7 1222.81    4216 1218.32  4221.4 1215.04    4240 1214.31  4245.4 1210.57
  4269.3 1210.73  4274.7 1207.03  4293.3 1208.43  4298.7 1205.42  4322.7 1207.74
  4376.1 1201.83  4493.1 1199.64  4875.1 1195.32  4899.1 1191.96  4921.3 1183.32
  4939.9 1172.94  4940.4 1172.44    4965 1172.94  4973.6 1173.59    5007 1181.05
  5012.4 1185.48  5017.5 1182.75  5037.7 1193.35    5058 1195.53  5129.9    1199
  5191.3 1207.79    5242 1220.91  5283.4 1228.43    5340 1249.02  5457.4 1269.46
#Mann= 6 ,-1 , 0
  4096.7     .07       0  4493.1    .035       0  4939.9    .035       0
    4965    .035       0  4973.6    .035       0    5058     .12       0
Bank Sta=4939.9,4965
XS Rating Curve= 0 ,0
Exp/Cntr=0.3,0.1

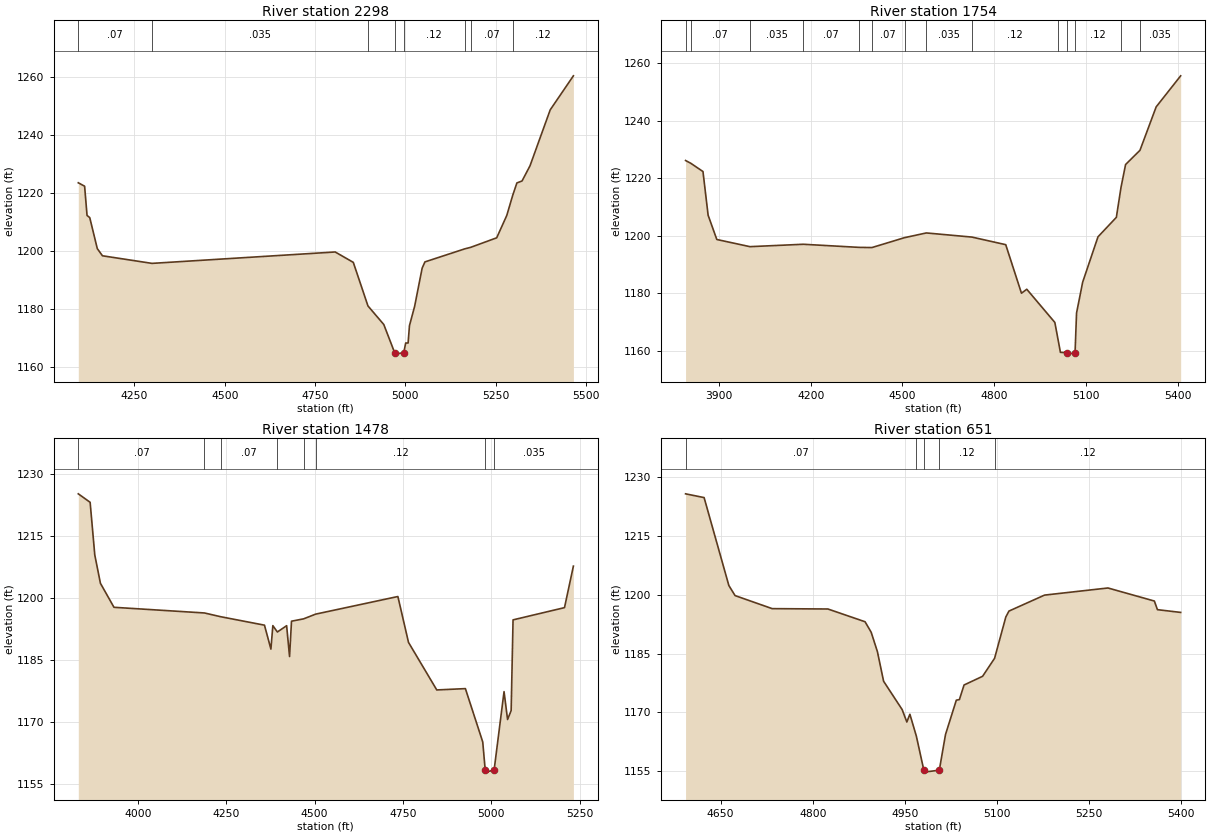
Type RM Length L Ch R = 1 ,2298    ,544,544,544
BEGIN DESCRIPTION:
SABINAS CREEK 4.0
END DESCRIPTION:
XS GIS Cut Line= 3
      2071717.11     13872651.72        2072325.       13871975.
      2072674.97     13871675.02
#Sta/Elev= 30
  4094.6 1223.54  4112.1 1222.36  4118.8 1212.28  4126.3 1211.53  4147.2 1200.83
  4161.5 1198.36  4298.6 1195.74  4805.8 1199.67  4855.9 1196.09  4896.5 1181.06
  4940.3 1174.66  4970.4 1164.94  4970.9 1164.44  4995.6 1164.94  5000.9 1168.27
  5007.6 1168.27  5011.4 1174.28  5025.7 1180.93  5046.5  1194.1  5054.2 1196.25
  5164.5 1200.75  5180.6 1201.26  5252.9 1204.56  5280.8 1212.28  5297.2 1219.21
  5308.8 1223.49  5323.1 1224.17  5345.1  1229.4    5401 1248.69  5465.2 1260.43
#Mann= 8 ,-1 , 0
  4094.6     .07       0  4298.6    .035       0  4896.5     .12       0
  4970.4     .05       0  4995.6     .12       0  5164.5     .12       0
  5180.6     .07       0  5297.2     .12       0
Bank Sta=4970.4,4995.6
XS Rating Curve= 0 ,0
Exp/Cntr=0.3,0.1

Type RM Length L Ch R = 1 ,1754    ,276,276,276
BEGIN DESCRIPTION:
SABINAS CREEK 3.0
END DESCRIPTION:
XS GIS Cut Line= 4
      2071683.41     13872681.12        2072775.       13872175.
      2072814.48     13872127.04        2072825.     13871775.04
#Sta/Elev= 30
  3791.3 1226.12  3807.9  1225.2  3848.2  1222.3    3865 1207.15  3893.4 1198.72
  4001.6 1196.23    4176 1197.06  4358.6 1195.98  4400.2 1195.92  4506.6 1199.35
  4577.9 1200.99    4727 1199.55  4837.3 1196.92  4888.7 1180.08  4906.1 1181.45
  4997.8 1169.93    5007 1164.69    5016 1159.56  5038.6 1159.44  5039.1 1158.94
  5063.8 1159.44  5068.7 1173.22  5088.7 1183.92  5138.7 1199.64  5198.7  1206.4
    5214 1216.85  5228.8 1224.72  5275.9 1229.67  5328.8 1244.74  5408.8 1255.51
#Mann= 14 ,-1 , 0
  3791.3    .035       0  3807.9     .07       0  4001.6    .035       0
    4176     .07       0  4358.6    .035       0  4400.2     .07       0
  4506.6     .12       0  4577.9    .035       0    4727     .12       0
    5007     .12       0  5038.6     .05       0  5063.8     .12       0
    5214     .12       0  5275.9    .035       0
Bank Sta=5038.6,5063.8
XS Rating Curve= 0 ,0
Exp/Cntr=0.3,0.1

Type RM Length L Ch R = 1 ,1478    ,827,827,827
BEGIN DESCRIPTION:
SABINAS CREEK 2.0
END DESCRIPTION:
XS GIS Cut Line= 4
      2071711.96     13872694.25      2072428.15     13872391.09
       2072819.2     13872377.26        2073050.     13872350.06
#Sta/Elev= 30
    3831 1225.14  3864.5 1223.09  3877.7 1210.34  3893.6 1203.51    3932 1197.69
  4188.1 1196.32  4233.6 1195.42    4358 1193.37  4376.2 1187.58  4381.7 1193.26
  4394.5 1191.72  4420.7 1193.24    4429 1185.78  4434.5 1194.33  4468.9  1194.9
  4502.9 1196.04  4735.6  1200.3  4765.7  1189.2  4845.7  1177.7  4926.7 1178.02
  4975.8 1165.12  4982.8 1158.32  4983.3 1157.82    5008 1158.32  5036.1 1177.29
  5046.1 1170.55  5056.2 1172.71  5061.6 1194.65  5207.2 1197.61  5232.4 1207.65
#Mann= 8 ,-1 , 0
    3831     .07       0  4188.1     .12       0  4233.6     .07       0
  4394.5     .12       0  4468.9     .07       0  4502.9     .12       0
  4982.8     .05       0    5008    .035       0
Bank Sta=4982.8,5008
XS Rating Curve= 0 ,0
Exp/Cntr=0.3,0.1

Type RM Length L Ch R = 1 ,651     ,0,0,0
BEGIN DESCRIPTION:
SABINAS CREEK 1.0
END DESCRIPTION:
XS GIS Cut Line= 3
        2071725.       13872725.        2072125.       13872675.
      2072524.97       13872725.
#Sta/Elev= 30
  4592.9 1225.75  4623.1 1224.79  4663.4 1202.37  4673.5  1199.8    4734 1196.47
  4824.7 1196.38  4885.2 1193.13  4895.2 1190.44  4905.3  1185.5  4915.4 1177.95
  4945.6 1170.73  4953.2 1167.56  4958.2 1169.54  4968.7 1163.97  4980.9 1155.28
  4981.4 1154.78  5006.1 1155.28  5016.2 1164.38  5033.8 1173.13  5038.8 1173.28
  5046.4    1177  5076.6 1179.22  5096.1 1183.81  5114.4 1194.34  5119.5 1195.85
  5177.4 1199.92  5280.7 1201.74  5356.3 1198.41  5361.3 1196.21  5399.1 1195.51
#Mann= 5 ,-1 , 0
  4592.9     .07       0  4968.7     .12       0  4980.9     .05       0
  5006.1     .12       0  5096.1     .12       0
Bank Sta=4980.9,5006.1
XS Rating Curve= 0 ,0
Exp/Cntr=0.3,0.1

Chan Stop Cuts=-1
Use User Specified Reach Order=0
Composite Channel Slope=5