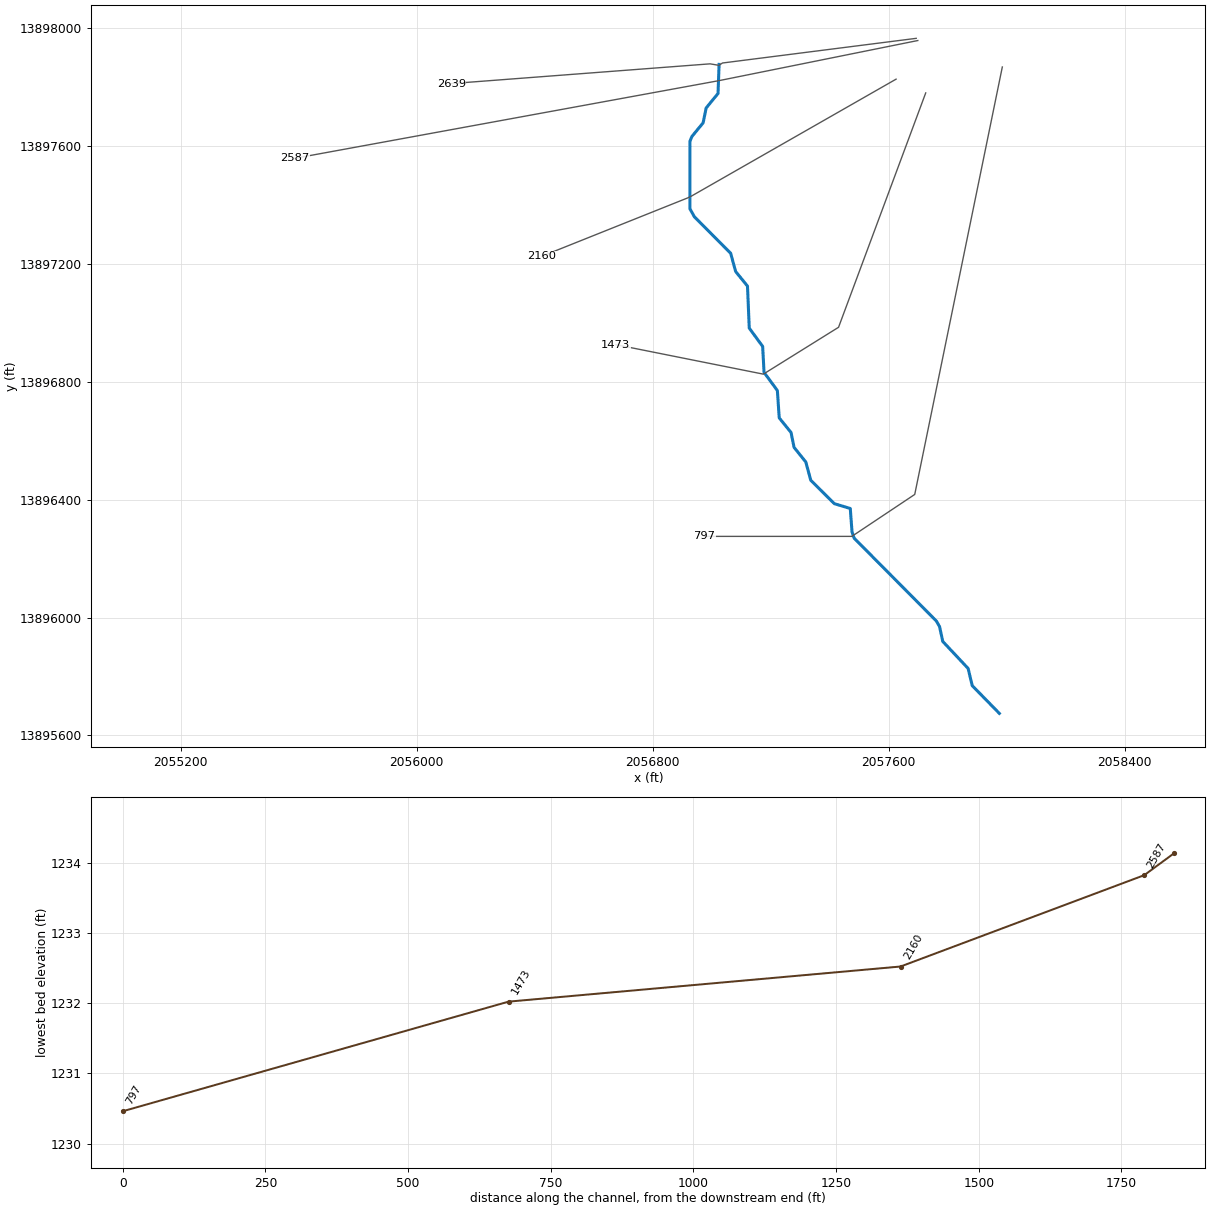
--- SISTER CREEK.prj (project) ---

Proj Title=SISTER CREEK Base Level Engineering
Current Plan=p01
Default Exp/Contr=0.3,0.1
English Units
Geom File=g01
Flow File=f01
Plan File=p01
Y Axis Title=Elevation
X Axis Title(PF)=Main Channel Distance
X Axis Title(XS)=Station
BEGIN DESCRIPTION:
SISTER CREEK
END DESCRIPTION:
DSS Export Rating Curves= 0
DSS Export Rating Curve Sorted= 0
DSS Export Volume Flow Curves= 0
DXF OffsetX= 0
DXF OffsetY= 0
DXF ScaleX= 1
DXF ScaleY= 10

--- SISTER CREEK.p01 (plan) ---

Plan Title=Multiple Run
Short Identifier=Multiple
Geom File=g01
Flow File=f01
Subcritical Flow
K Sum by GR= 0
Std Step Tol= 0.01
Critical Tol= 0.01
Num of Std Step Trials= 20
Max Error Tol= 0.3
Flow Tol Ratio= 0.001
Split Flow NTrial= 30
Split Flow Tol= 0.02
Split Flow Ratio= 0.02
Log Output Level= 0
Friction Slope Method= 1
Unsteady Friction Slope Method= 2
Unsteady Bridges Friction Slope Method= 1
Parabolic Critical Depth
Global Vel Dist=  1 , 1 , 1
Global Log Level= 0
CheckData=True
Encroach Param= -1, 0, 0, 0
BEGIN DESCRIPTION:
Multiple Run
END DESCRIPTION:

--- SISTER CREEK.f01 (steady flow) ---

Flow Title=Multiple
Program Version=4.10
Number of Profiles= 7
Profile Names=10-year,25-year,50-year,1pct_min,100-year,1pct_plu,500-year
River Rch & RM=SISTER CREEK,Reach-1         ,2639
   19831   37307   55661   39908   79628  158878  161217
Boundary for River Rch & Prof#=SISTER CREEK,Reach-1         , 1
Up Type= 0
Dn Type= 3
Dn Slope=0.005
Boundary for River Rch & Prof#=SISTER CREEK,Reach-1         , 2
Up Type= 0
Dn Type= 3
Dn Slope=0.005
Boundary for River Rch & Prof#=SISTER CREEK,Reach-1         , 3
Up Type= 0
Dn Type= 3
Dn Slope=0.005
Boundary for River Rch & Prof#=SISTER CREEK,Reach-1         , 4
Up Type= 0
Dn Type= 3
Dn Slope=0.005
Boundary for River Rch & Prof#=SISTER CREEK,Reach-1         , 5
Up Type= 0
Dn Type= 3
Dn Slope=0.005
Boundary for River Rch & Prof#=SISTER CREEK,Reach-1         , 6
Up Type= 0
Dn Type= 3
Dn Slope=0.005
Boundary for River Rch & Prof#=SISTER CREEK,Reach-1         , 7
Up Type= 0
Dn Type= 3
Dn Slope=0.005
DSS Import GetInterval= 0
DSS Import GetPeak= 0
DSS Import FillOption= 0

--- SISTER CREEK.g01 (geometry) ---

Geom Title=Existing Conditions
Program Version=4.10

River Reach=SISTER CREEK    ,Reach-1
Reach XY= 30
        2057025.       13897875.      2057021.37      13897776.5
      2056981.09     13897727.19      2056970.81     13897676.73
      2056933.09     13897631.08       2056926.2      13897614.5
      2056926.05     13897385.43      2056941.43     13897358.24
      2057064.24     13897234.68      2057081.14     13897172.83
      2057121.24     13897123.44      2057127.27     13896980.94
      2057172.64     13896919.02      2057177.35     13896830.97
      2057222.53     13896769.43      2057228.83     13896676.58
      2057268.88     13896627.18      2057279.16     13896576.72
       2057318.9     13896527.18      2057335.76      13896465.3
       2057415.6     13896385.89      2057469.74     13896369.53
      2057475.58     13896290.35      2057482.88     13896268.88
      2057761.37     13895988.21      2057772.47     13895968.95
      2057783.18     13895918.96      2057869.14     13895827.29
      2057883.11     13895768.93        2057975.       13895675.

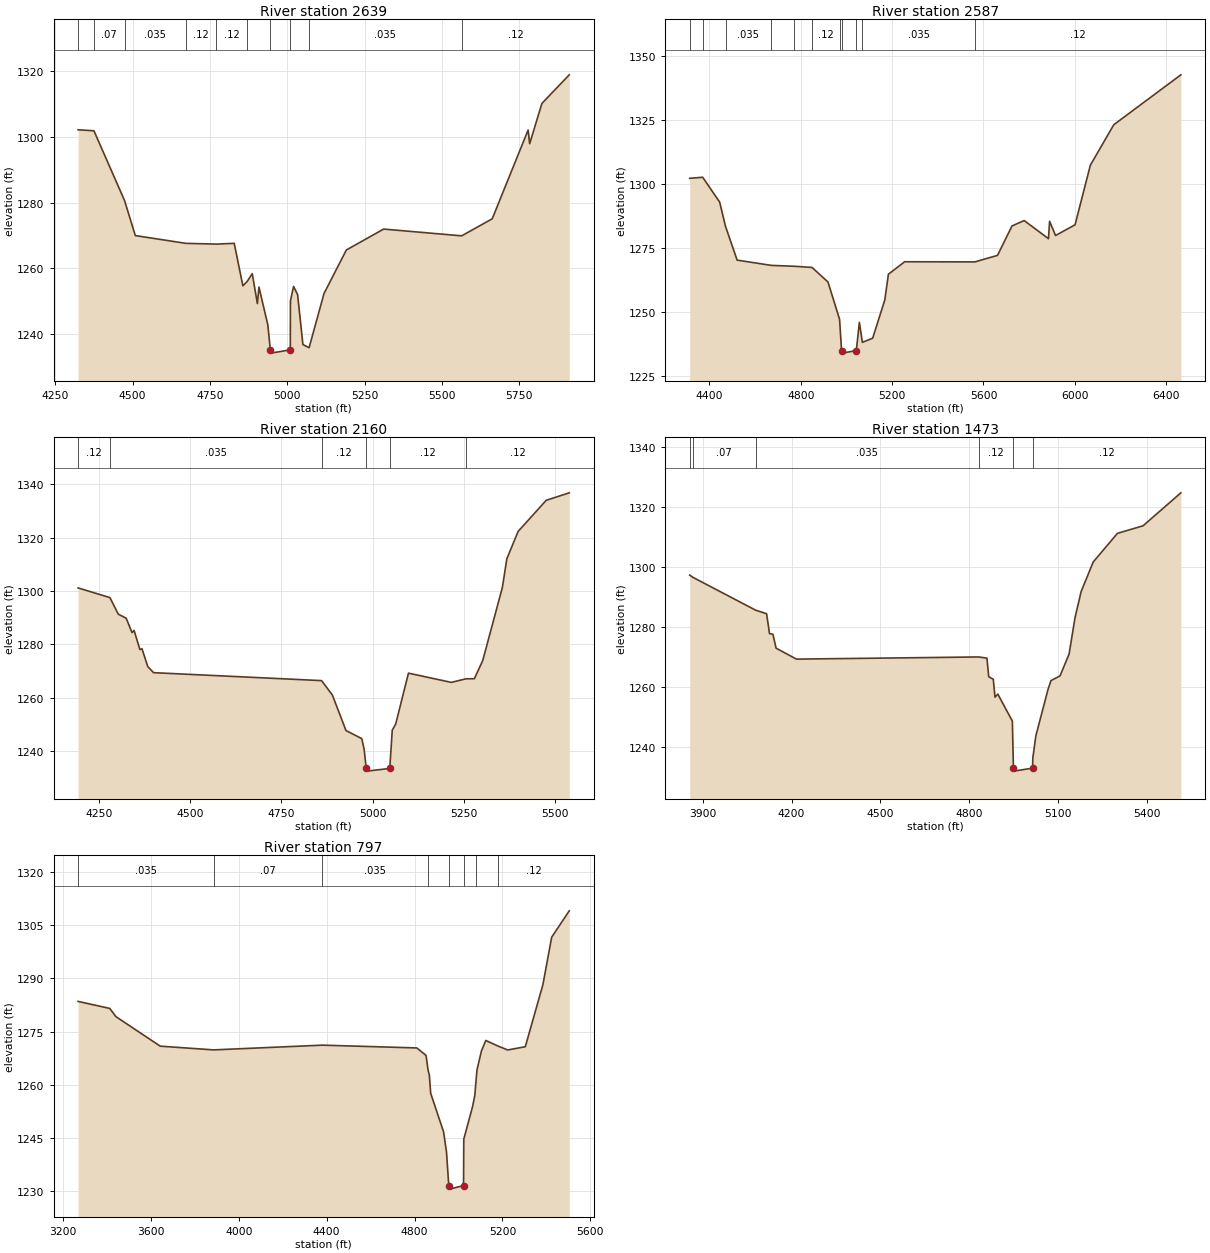
Type RM Length L Ch R = 1 ,2639    ,52,52,52
BEGIN DESCRIPTION:
SISTER CREEK 5.0
END DESCRIPTION:
XS GIS Cut Line= 5
      2057693.25     13897963.36      2057036.28     13897879.72
      2057024.83     13897871.76      2056994.33      13897876.9
      2056116.83     13897809.94
#Sta/Elev= 30
    4324 1302.18  4375.2 1301.88  4474.2  1280.6  4508.9 1269.95  4672.1 1267.58
  4771.1 1267.35  4828.5 1267.59  4856.5 1254.64    4870 1255.92  4886.8 1258.35
  4903.4 1249.23  4908.4 1254.27  4937.2 1242.71  4945.2 1235.13  4946.7 1234.13
  5009.7 1235.13  5010.2 1250.07  5020.3 1254.45  5033.3 1251.96  5050.5 1236.75
  5070.5 1235.79  5118.8 1252.32  5190.9 1265.56  5311.3 1271.93  5563.6 1269.87
  5662.3 1275.06  5778.3 1302.11  5783.3 1297.94  5822.8 1310.21  5911.2 1318.93
#Mann= 10 ,-1 , 0
    4324     .12       0  4375.2     .07       0  4474.2    .035       0
  4672.1     .12       0  4771.1     .12       0    4870     .12       0
  4945.2     .05       0  5009.7     .12       0  5070.5    .035       0
  5563.6     .12       0
Bank Sta=4945.2,5009.7
XS Rating Curve= 0 ,0
Exp/Cntr=0.3,0.1

Type RM Length L Ch R = 1 ,2587    ,427,427,427
BEGIN DESCRIPTION:
SISTER CREEK 4.0
END DESCRIPTION:
XS GIS Cut Line= 3
      2057698.64     13897955.92       2057025.7     13897820.16
      2055585.26     13897556.34
#Sta/Elev= 30
  4313.5  1302.1  4370.4 1302.51  4444.7 1292.82  4470.3 1283.36  4521.2 1270.15
  4670.2  1268.1  4770.1 1267.75  4849.3 1267.29  4919.1  1261.6  4969.9 1247.01
  4978.6 1234.82  4980.1 1233.82  5043.1 1234.82  5056.5 1245.83  5069.7 1238.03
  5114.8 1239.65  5167.9 1254.59  5183.7 1264.64  5254.9 1269.51  5562.1 1269.45
  5661.5    1272    5725  1283.5  5778.2  1285.6  5884.6 1278.53  5889.6 1285.32
  5915.7 1279.76  6001.1 1283.95  6068.2 1307.25  6170.7 1323.03  6464.4 1342.52
#Mann= 11 ,-1 , 0
  4313.5     .12       0  4370.4     .07       0  4470.3    .035       0
  4670.2     .12       0  4770.1     .12       0  4849.3     .12       0
  4969.9     .12       0  4978.6     .05       0  5043.1     .12       0
  5069.7    .035       0  5562.1     .12       0
Bank Sta=4978.6,5043.1
XS Rating Curve= 0 ,0
Exp/Cntr=0.3,0.1

Type RM Length L Ch R = 1 ,2160    ,687,687,687
BEGIN DESCRIPTION:
SISTER CREEK 3.0
END DESCRIPTION:
XS GIS Cut Line= 3
        2057625.       13897825.        2056925.       13897425.
      2056425.04     13897225.02
#Sta/Elev= 30
  4193.3 1301.18  4280.4 1297.56  4303.4 1291.33    4325 1289.83  4340.9 1284.44
  4346.6 1285.24  4362.5  1278.1  4368.2 1278.39  4384.1 1271.71  4399.9 1269.42
  4859.9 1266.44  4889.4 1261.05  4926.8 1247.73    4970  1244.7  4976.5 1240.66
  4982.1 1233.52  4983.6 1232.52  5046.6 1233.52  5053.4 1247.88  5062.8 1250.14
  5097.8 1269.24  5214.9 1265.78    5255 1267.11  5278.2 1267.16  5301.1 1273.95
  5354.9 1301.36  5367.1  1312.1    5398 1322.35  5474.8 1334.01    5538 1336.82
#Mann= 6 ,-1 , 0
  4193.3     .12       0  4280.4    .035       0  4859.9     .12       0
  4982.1     .05       0  5046.6     .12       0    5255     .12       0
Bank Sta=4982.1,5046.6
XS Rating Curve= 0 ,0
Exp/Cntr=0.3,0.1

Type RM Length L Ch R = 1 ,1473    ,676,676,676
BEGIN DESCRIPTION:
SISTER CREEK 2.0
END DESCRIPTION:
XS GIS Cut Line= 4
      2057725.45     13897778.36      2057429.94     13896983.82
        2057175.       13896825.      2056674.98       13896925.
#Sta/Elev= 30
  3856.2 1297.24  3866.6 1296.51    4079 1285.55  4115.8 1284.38  4125.6 1277.78
  4137.2 1277.54  4147.9 1272.91  4216.6 1269.28    4832    1270  4859.7 1269.59
  4865.6 1263.41    4881 1262.59  4886.8 1256.63  4896.3 1257.64  4945.4 1248.67
    4949 1233.02  4950.5 1232.02  5013.6 1233.02  5014.5 1236.41  5024.7 1243.75
  5065.5  1259.1  5075.7 1262.13  5106.3  1263.7  5136.8 1270.93  5157.2 1283.21
  5177.6 1291.76  5218.4  1301.6    5300 1311.11  5386.7 1313.64  5514.2  1324.6
#Mann= 6 ,-1 , 0
  3856.2     .12       0  3866.6     .07       0    4079    .035       0
    4832     .12       0    4949     .05       0  5013.6     .12       0
Bank Sta=4949,5013.6
XS Rating Curve= 0 ,0
Exp/Cntr=0.3,0.1

Type RM Length L Ch R = 1 ,797     ,0,0,0
BEGIN DESCRIPTION:
SISTER CREEK 1.0
END DESCRIPTION:
XS GIS Cut Line= 4
      2057985.11     13897866.21       2057688.2     13896417.18
        2057475.       13896275.        2056975.       13896275.
#Sta/Elev= 30
  3268.7 1283.51  3412.8 1281.53    3441  1279.2  3642.7 1270.86    3886 1269.81
  4380.5 1271.15  4810.3 1270.36  4852.4 1268.25  4861.4 1264.14  4867.4 1262.68
  4873.4 1257.54    4932 1246.69  4945.5 1240.92  4954.5 1232.56  4958.3 1231.46
  4959.8 1230.46  5022.9 1231.46  5024.1 1244.59  5064.1  1253.8  5074.1 1256.92
    5080 1261.17  5084.1 1264.12  5104.1 1269.44  5124.1 1272.47  5178.6 1270.93
  5224.1 1269.79  5304.1 1270.71  5384.1 1288.22  5424.1 1301.66  5504.1 1309.11
#Mann= 8 ,-1 , 0
  3268.7    .035       0    3886     .07       0  4380.5    .035       0
  4861.4     .12       0  4958.3     .05       0  5022.9     .12       0
    5080     .07       0  5178.6     .12       0
Bank Sta=4958.3,5022.9
XS Rating Curve= 0 ,0
Exp/Cntr=0.3,0.1

Chan Stop Cuts=-1
Use User Specified Reach Order=0
Composite Channel Slope=5