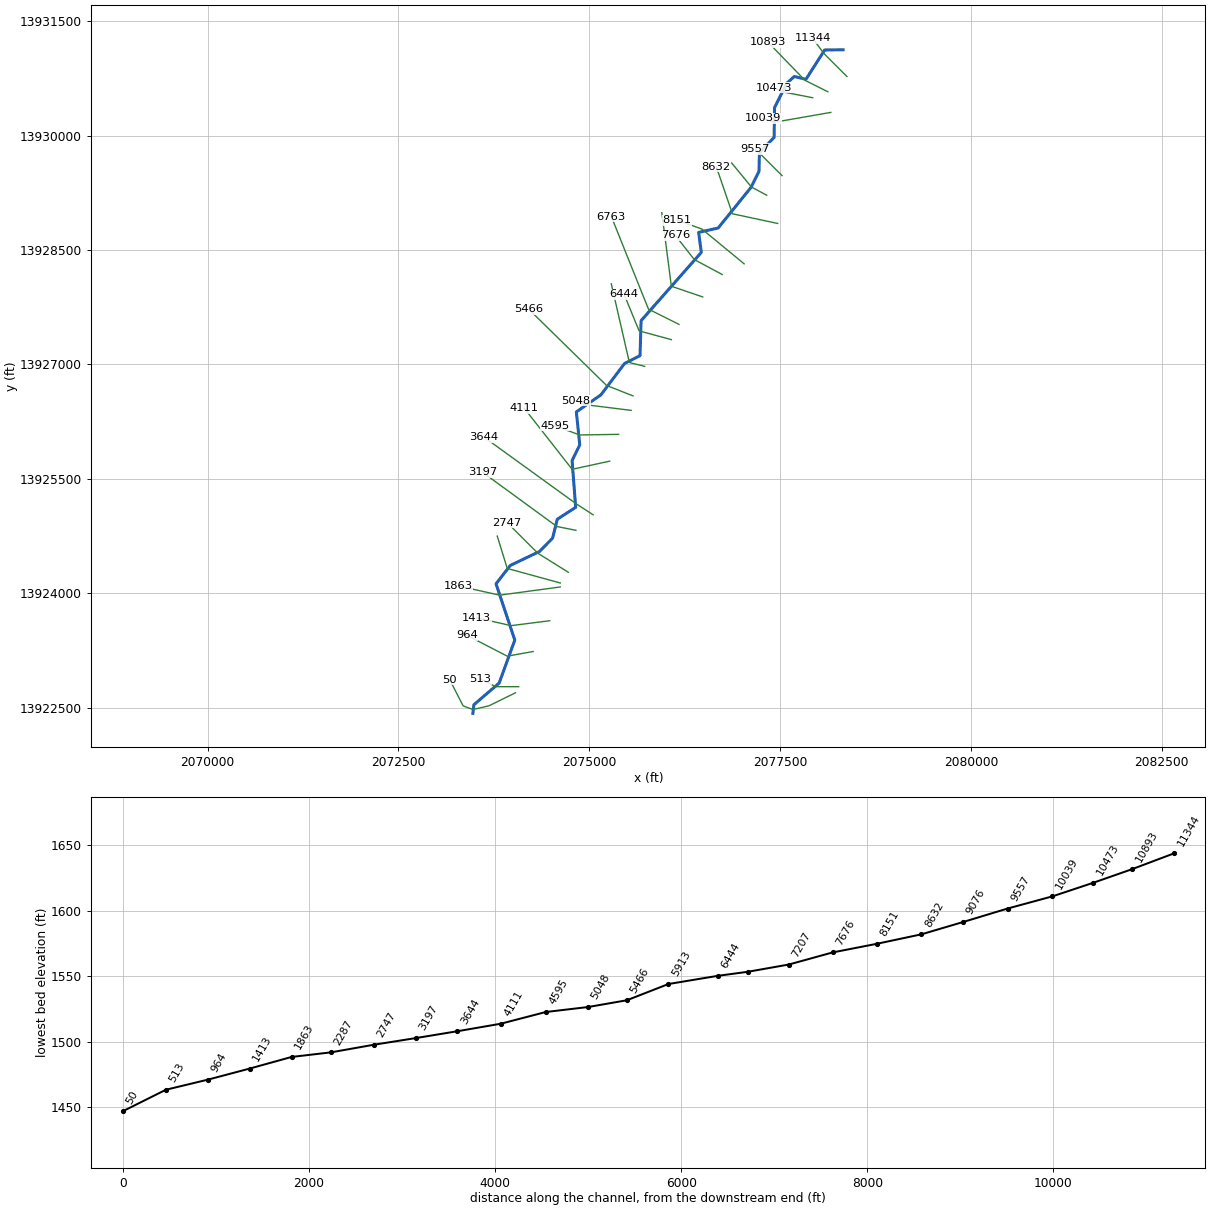
--- SOELL CREEK.prj (project) ---

Proj Title=SOELL CREEK Base Level Engineering
Current Plan=p01
Default Exp/Contr=0.3,0.1
English Units
Geom File=g01
Flow File=f01
Plan File=p01
BEGIN DESCRIPTION:
SOELL CREEK
END DESCRIPTION:

--- SOELL CREEK.p01 (plan) ---

Plan Title=Multiple Run
Short Identifier=Multiple
Geom File=g01
Flow File=f01
Subcritical Flow
K Sum by GR= 0
Std Step Tol= 0.01
Critical Tol= 0.01
Num of Std Step Trials= 20
Max Error Tol= 0.3
Flow Tol Ratio= 0.001
Split Flow NTrial= 30
Split Flow Tol= 0.02
Split Flow Ratio= 0.02
Log Output Level= 0
Friction Slope Method= 1
Unsteady Friction Slope Method= 2
Unsteady Bridges Friction Slope Method= 1
Parabolic Critical Depth
Global Vel Dist=  1 , 1 , 1
Global Log Level= 0
CheckData=True
Encroach Param= -1, 0, 0, 0
BEGIN DESCRIPTION:
Multiple Run
END DESCRIPTION:

--- SOELL CREEK.f01 (steady flow) ---

Flow Title=Multiple
Number of Profiles=7
Profile Names=10-year,25-year,50-year,1pct_min,100-year,1pct_plu,500-year
River Rch & RM= SOELL CREEK,Reach-1,11344
    1251    2182    3095    2133    4257    8493    7976
River Rch & RM= SOELL CREEK,Reach-1,7676
    1815    3208    4589    3182    6349   12669   12054
Boundary for River Rch & Prof#=SOELL CREEK,Reach-1,1
Up Type=0
Dn Type=3
Dn Slope=0.005
Boundary for River Rch & Prof#=SOELL CREEK,Reach-1,2
Up Type=0
Dn Type=3
Dn Slope=0.005
Boundary for River Rch & Prof#=SOELL CREEK,Reach-1,3
Up Type=0
Dn Type=3
Dn Slope=0.005
Boundary for River Rch & Prof#=SOELL CREEK,Reach-1,4
Up Type=0
Dn Type=3
Dn Slope=0.005
Boundary for River Rch & Prof#=SOELL CREEK,Reach-1,5
Up Type=0
Dn Type=3
Dn Slope=0.005
Boundary for River Rch & Prof#=SOELL CREEK,Reach-1,6
Up Type=0
Dn Type=3
Dn Slope=0.005
Boundary for River Rch & Prof#=SOELL CREEK,Reach-1,7
Up Type=0
Dn Type=3
Dn Slope=0.005

--- SOELL CREEK.g01 (geometry) ---

Geom Title=Existing Conditions

River Reach=SOELL CREEK,Reach-1
Reach XY= 30
      2078325.00     13931125.00      2078083.30     13931121.93
      2077838.24     13930738.11      2077685.62     13930774.40
      2077585.77     13930684.70      2077426.38     13930365.34
      2077421.46     13929976.46      2077228.54     13929773.54
      2077222.82     13929530.45      2077117.14     13929318.83
      2076688.32     13928788.37      2076432.36     13928731.32
      2076467.24     13928468.83      2075678.62     13927573.50
      2075664.53     13927115.17      2075461.70     13927011.60
      2075152.14     13926601.16      2074830.46     13926377.45
      2074874.96     13925945.03      2074774.55     13925738.82
      2074821.46     13925126.46      2074580.11     13924969.89
      2074519.48     13924722.57      2074348.47     13924548.01
      2073965.00     13924364.37      2073778.13     13924123.37
      2074023.80     13923385.51      2073819.17     13922822.69
      2073488.34     13922538.35      2073475.00     13922425.00

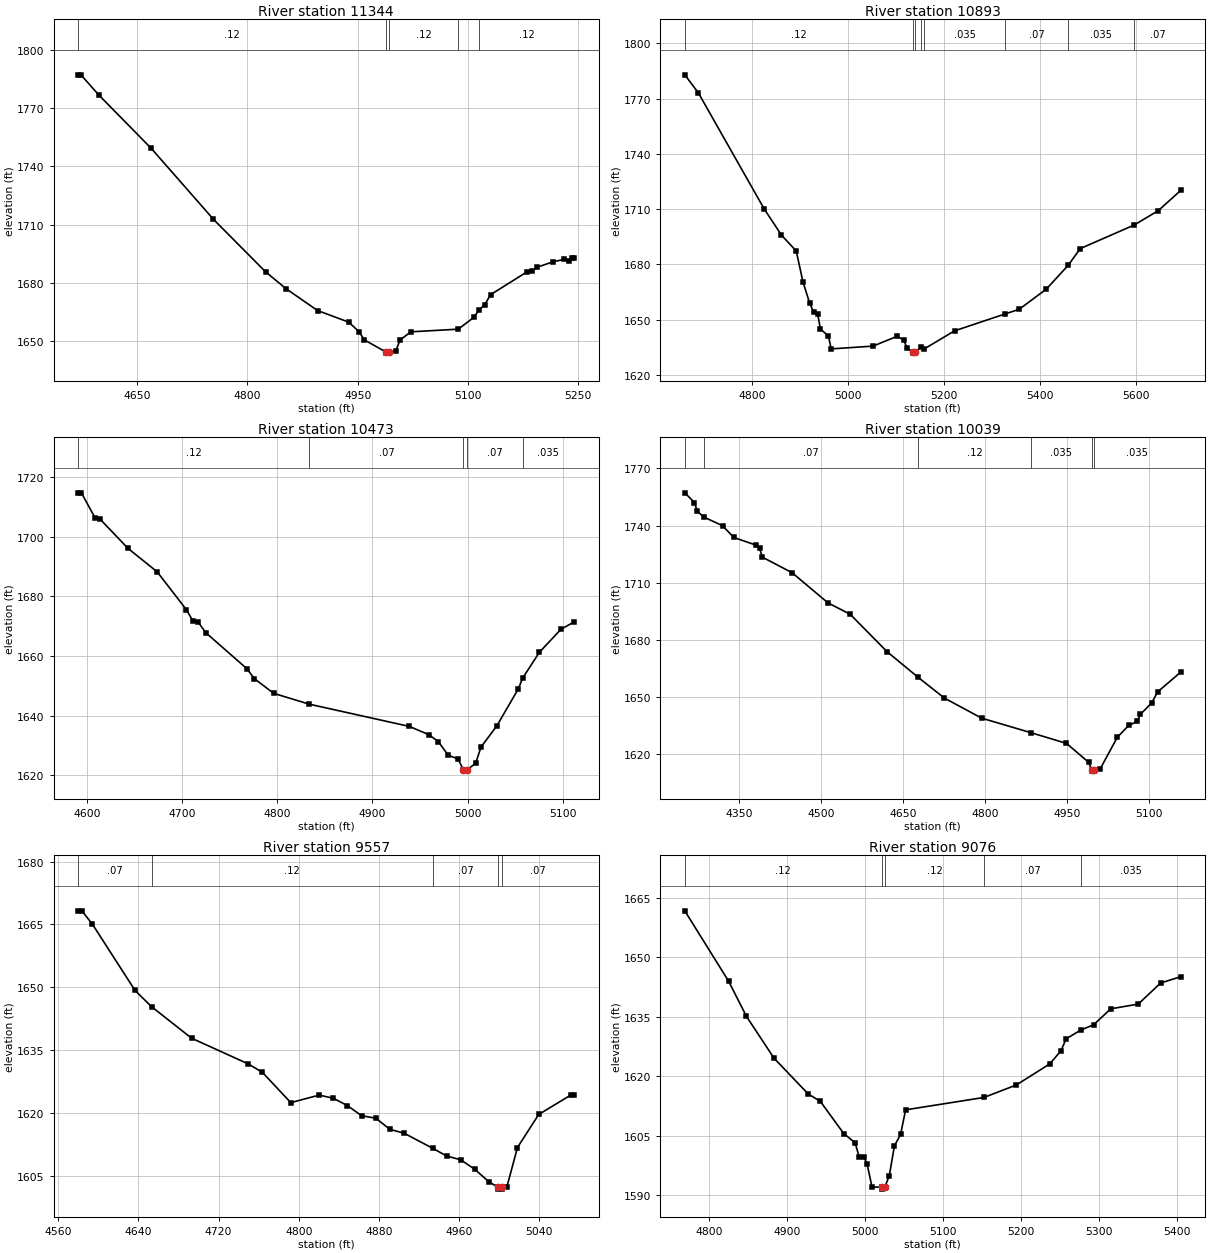
Type RM Length L Ch R = 1,11344,451,451,451
BEGIN DESCRIPTION:
SOELL CREEK 25.0
END DESCRIPTION:
XS GIS Cut Line= 3
      2078375.00     13930775.00      2078075.00     13931075.00
      2077924.98     13931275.03
#Sta/Elev= 30
  4570.1 1787.18  4573.6 1787.18  4598.4 1776.62  4669.1 1749.39  4753.9 1712.80
  4824.7 1685.80  4852.9 1677.01  4895.4 1665.88  4937.8 1659.89  4951.9 1654.95
  4959.0 1650.77  4988.8 1644.45  4989.1 1643.95  4992.8 1644.45  5001.7 1645.04
  5007.9 1650.83  5022.5 1654.92  5086.8 1656.28  5107.9 1662.34  5115.2 1666.25
  5122.5 1668.75  5130.8 1674.04  5180.8 1685.91  5187.1 1686.24  5194.4 1688.20
  5216.2 1691.02  5230.8 1692.19  5237.1 1691.43  5241.2 1692.81  5244.4 1692.81
#Mann=5,-1,0
  4570.1    0.12       0  4988.8    0.05       0  4992.8    0.12       0
  5086.8   0.035       0  5115.2    0.12       0
Bank Sta=4988.8,4992.8
Exp/Cntr=0.3,0.1

Type RM Length L Ch R = 1,10893,420,420,420
BEGIN DESCRIPTION:
SOELL CREEK 24.0
END DESCRIPTION:
XS GIS Cut Line= 3
      2078125.04     13930574.98      2077825.00     13930725.00
      2077340.31     13931225.67
#Sta/Elev= 30
  4660.7 1782.95  4688.7 1773.26  4825.7 1710.28  4862.0 1695.91  4892.7 1687.32
  4906.7 1670.59  4920.7 1658.94  4929.1 1654.11  4937.5 1652.88  4943.0 1644.99
  4959.8 1641.10  4965.4 1634.17  5052.6 1635.68  5102.3 1640.96  5116.4 1639.15
  5123.4 1634.50  5135.5 1632.37  5135.8 1631.87  5139.5 1632.37  5152.6 1635.02
  5158.8 1634.09  5222.4 1643.98  5327.5 1653.14  5356.9 1655.66  5413.5 1666.65
  5459.1 1679.60  5484.0 1688.62  5596.7 1701.46  5646.8 1709.28  5693.0 1720.16
#Mann=8,-1,0
  4660.7    0.12       0  5135.5    0.05       0  5139.5    0.12       0
  5152.6    0.07       0  5158.8   0.035       0  5327.5    0.07       0
  5459.1   0.035       0  5596.7    0.07       0
Bank Sta=5135.5,5139.5
Exp/Cntr=0.3,0.1

Type RM Length L Ch R = 1,10473,434,434,434
BEGIN DESCRIPTION:
SOELL CREEK 23.0
END DESCRIPTION:
XS GIS Cut Line= 3
      2077926.26     13930496.49      2077525.00     13930575.00
      2077424.98     13930625.01
#Sta/Elev= 30
  4591.1 1714.71  4594.3 1714.71  4608.5 1706.43  4613.6 1706.00  4643.3 1696.08
  4673.9 1688.22  4704.5 1675.58  4711.6 1671.64  4716.7 1671.48  4724.9 1667.85
  4768.2 1655.72  4775.8 1652.46  4796.2 1647.50  4833.7 1643.86  4938.8 1636.40
  4959.2 1633.64  4969.1 1631.33  4979.6 1626.73  4989.8 1625.52  4995.4 1621.92
  4995.7 1621.42  4999.4 1621.92  5008.4 1624.04  5013.9 1629.45  5030.7 1636.64
  5053.1 1648.97  5057.7 1652.60  5075.4 1661.30  5097.8 1668.92  5111.8 1671.46
#Mann=5,-1,0
  4591.1    0.12       0  4833.7    0.07       0  4995.4    0.05       0
  4999.4    0.07       0  5057.7   0.035       0
Bank Sta=4995.4,4999.4
Exp/Cntr=0.3,0.1

Type RM Length L Ch R = 1,10039,482,482,482
BEGIN DESCRIPTION:
SOELL CREEK 22.0
END DESCRIPTION:
XS GIS Cut Line= 3
      2078163.25     13930303.78      2077425.00     13930175.00
      2077275.01     13930225.00
#Sta/Elev= 30
  4250.6 1757.17  4268.3 1752.08  4273.4 1747.45  4286.2 1744.36  4319.9 1739.87
  4340.2 1733.76  4380.8 1729.74  4387.4 1728.10  4392.5 1723.43  4447.0 1715.26
  4512.7 1699.42  4553.3 1693.47  4620.5 1673.91  4678.0 1660.29  4725.9 1649.46
  4794.1 1638.93  4883.4 1631.39  4949.2 1625.72  4989.8 1615.78  4995.5 1611.66
  4995.7 1611.16  4999.5 1611.66  5010.5 1612.12  5042.2 1628.90  5063.2 1635.17
  5079.1 1637.26  5084.3 1640.90  5105.4 1647.01  5115.9 1652.72  5158.1 1663.05
#Mann=6,-1,0
  4250.6   0.035       0  4286.2    0.07       0  4678.0    0.12       0
  4883.4   0.035       0  4995.5   0.035       0  4999.5   0.035       0
Bank Sta=4995.5,4999.5
Exp/Cntr=0.3,0.1

Type RM Length L Ch R = 1,9557,481,481,481
BEGIN DESCRIPTION:
SOELL CREEK 21.0
END DESCRIPTION:
XS GIS Cut Line= 3
      2077524.99     13929475.01      2077225.00     13929775.00
      2077174.97     13929825.03
#Sta/Elev= 30
  4580.0 1668.25  4583.5 1668.25  4594.1 1665.05  4636.6 1649.26  4653.1 1645.38
  4693.1 1637.86  4749.7 1631.72  4763.8 1629.71  4792.1 1622.49  4820.4 1624.29
  4834.5 1623.54  4848.7 1621.78  4862.8 1619.37  4877.0 1618.77  4891.1 1616.12
  4905.3 1615.19  4934.1 1611.56  4947.7 1609.76  4961.8 1608.85  4976.0 1606.55
  4990.1 1603.56  4998.7 1602.36  4999.0 1601.86  5002.5 1601.86  5002.7 1602.36
  5007.8 1602.36  5018.4 1611.79  5039.6 1619.67  5071.4 1624.27  5075.0 1624.27
#Mann=5,-1,0
  4580.0    0.07       0  4653.1    0.12       0  4934.1    0.07       0
  4998.7    0.05       0  5002.7    0.07       0
Bank Sta=4998.7,5002.7
Exp/Cntr=0.3,0.1

Type RM Length L Ch R = 1,9076,444,444,444
BEGIN DESCRIPTION:
SOELL CREEK 20.0
END DESCRIPTION:
XS GIS Cut Line= 3
      2077324.66     13929217.86      2077125.00     13929325.00
      2076864.73     13929641.16
#Sta/Elev= 30
  4768.8 1661.70  4825.2 1643.88  4847.9 1635.08  4883.3 1624.53  4927.3 1615.47
  4942.5 1613.69  4972.7 1605.53  4987.3 1603.19  4992.6 1599.57  4998.6 1599.57
  5002.6 1597.89  5009.0 1592.04  5021.4 1592.01  5021.6 1591.51  5025.4 1592.01
  5031.2 1594.94  5037.7 1602.40  5045.6 1605.29  5052.1 1611.51  5152.6 1614.63
  5194.1 1617.78  5237.1 1623.10  5251.5 1626.44  5258.0 1629.42  5276.8 1631.62
  5293.3 1632.97  5315.3 1636.99  5350.5 1638.17  5379.2 1643.49  5404.9 1645.08
#Mann=5,-1,0
  4768.8    0.12       0  5021.4    0.05       0  5025.4    0.12       0
  5152.6    0.07       0  5276.8   0.035       0
Bank Sta=5021.4,5025.4
Exp/Cntr=0.3,0.1

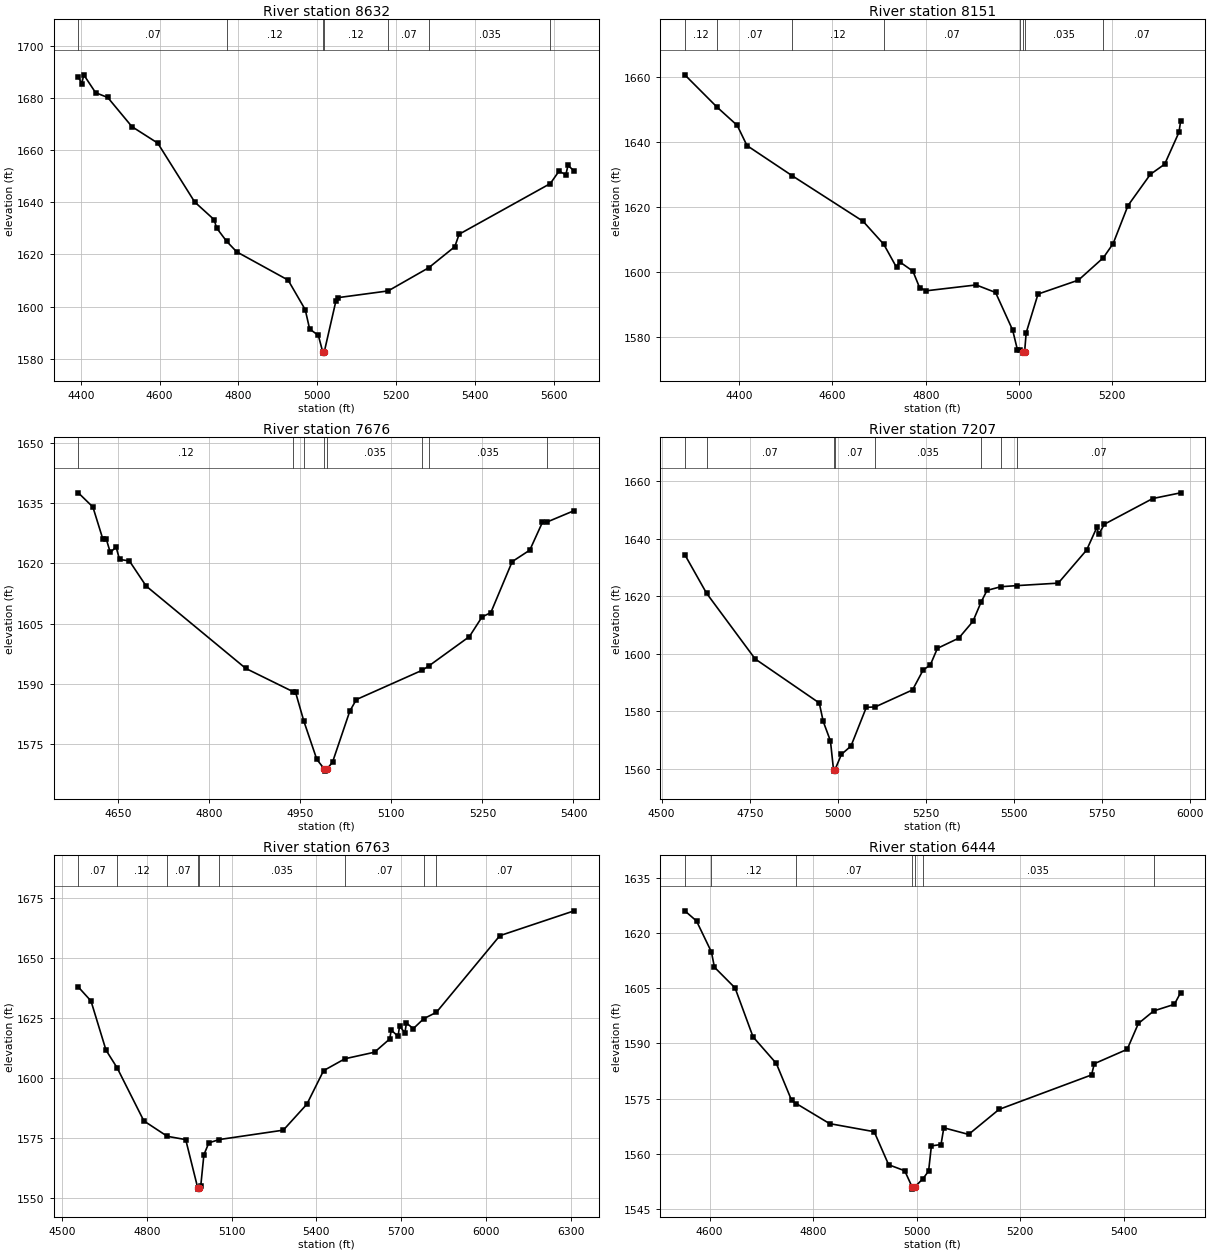
Type RM Length L Ch R = 1,8632,481,481,481
BEGIN DESCRIPTION:
SOELL CREEK 19.0
END DESCRIPTION:
XS GIS Cut Line= 3
      2077467.95     13928848.05      2076875.00     13928975.00
      2076663.74     13929591.41
#Sta/Elev= 30
  4393.9 1687.96  4402.6 1685.47  4407.7 1688.84  4437.8 1681.98  4468.5 1680.16
  4529.9 1668.98  4595.3 1662.68  4689.1 1640.11  4738.5 1633.33  4744.6 1630.18
  4770.2 1625.03  4795.8 1621.00  4926.1 1610.18  4969.6 1598.84  4980.7 1591.45
  5002.9 1588.98  5013.9 1582.69  5014.2 1582.19  5017.9 1582.69  5047.2 1602.03
  5053.1 1603.46  5179.9 1606.03  5282.7 1614.89  5349.1 1622.98  5360.0 1627.75
  5591.4 1647.17  5613.4 1651.91  5630.9 1650.58  5636.2 1654.15  5651.9 1651.99
#Mann=7,-1,0
  4393.9    0.07       0  4770.2    0.12       0  5013.9    0.05       0
  5017.9    0.12       0  5179.9    0.07       0  5282.7   0.035       0
  5591.4    0.07       0
Bank Sta=5013.9,5017.9
Exp/Cntr=0.3,0.1

Type RM Length L Ch R = 1,8151,475,475,475
BEGIN DESCRIPTION:
SOELL CREEK 18.0
END DESCRIPTION:
XS GIS Cut Line= 3
      2077027.85     13928319.39      2076475.00     13928775.00
      2076148.81     13928891.89
#Sta/Elev= 30
  4283.6 1660.59  4352.1 1650.73  4396.0 1645.02  4416.9 1638.81  4514.0 1629.51
  4665.8 1615.50  4710.2 1608.41  4737.5 1601.32  4743.9 1603.05  4772.6 1600.15
  4787.0 1595.05  4801.3 1594.11  4908.2 1595.91  4949.8 1593.59  4986.4 1582.02
  4996.8 1575.86  5002.4 1575.86  5008.0 1575.42  5008.3 1574.92  5012.1 1575.42
  5015.4 1581.17  5040.8 1593.10  5127.5 1597.40  5180.8 1604.28  5201.8 1608.63
  5233.7 1620.35  5281.6 1629.95  5312.3 1633.08  5343.1 1642.95  5346.5 1646.41
#Mann=8,-1,0
  4283.6    0.12       0  4352.1    0.07       0  4514.0    0.12       0
  4710.2    0.07       0  5002.4   0.035       0  5008.0    0.05       0
  5012.1   0.035       0  5180.8    0.07       0
Bank Sta=5008,5012.1
Exp/Cntr=0.3,0.1

Type RM Length L Ch R = 1,7676,469,469,469
BEGIN DESCRIPTION:
SOELL CREEK 17.0
END DESCRIPTION:
XS GIS Cut Line= 3
      2076741.35     13928178.79      2076375.00     13928375.00
      2076127.49     13928690.90
#Sta/Elev= 30
  4584.2 1637.54  4608.2 1634.01  4624.4 1626.13  4630.1 1626.13  4636.8 1622.71
  4646.4 1624.07  4652.1 1620.97  4668.3 1620.61  4695.9 1614.36  4860.0 1593.88
  4938.6 1588.04  4942.1 1587.93  4955.7 1580.78  4977.1 1571.25  4989.6 1568.83
  4989.9 1568.33  4993.8 1568.83  5003.0 1570.56  5031.5 1583.27  5042.3 1586.13
  5150.6 1593.41  5161.5 1594.47  5228.5 1601.79  5249.3 1606.67  5263.8 1607.75
  5299.0 1620.43  5328.0 1623.29  5348.8 1630.20  5356.7 1630.30  5401.1 1633.11
#Mann=8,-1,0
  4584.2    0.12       0  4938.6    0.07       0  4955.7   0.035       0
  4989.6   0.035       0  4993.8   0.035       0  5150.6    0.07       0
  5161.5   0.035       0  5356.7    0.07       0
Bank Sta=4989.6,4993.8
Exp/Cntr=0.3,0.1

Type RM Length L Ch R = 1,7207,444,444,444
BEGIN DESCRIPTION:
SOELL CREEK 16.0
END DESCRIPTION:
XS GIS Cut Line= 3
      2076486.13     13927884.52      2076075.00     13928025.00
      2075949.94     13928989.46
#Sta/Elev= 30
  4565.8 1634.44  4627.5 1621.02  4765.4 1598.16  4947.4 1582.83  4958.6 1576.41
  4979.1 1569.62  4987.8 1559.62  4988.0 1559.12  4992.0 1559.62  5010.4 1564.97
  5037.4 1567.85  5080.9 1581.31  5106.1 1581.46  5212.0 1587.37  5242.3 1594.33
  5262.4 1596.03  5282.6 1601.84  5343.1 1605.38  5383.4 1611.22  5406.6 1617.94
  5423.4 1622.01  5463.0 1623.29  5507.7 1623.66  5625.5 1624.53  5706.1 1636.05
  5735.2 1643.95  5740.2 1641.46  5756.5 1645.03  5893.6 1653.96  5972.8 1655.95
#Mann=8,-1,0
  4565.8    0.12       0  4627.5    0.07       0  4987.8    0.05       0
  4992.0    0.07       0  5106.1   0.035       0  5406.6    0.07       0
  5463.0   0.035       0  5507.7    0.07       0
Bank Sta=4987.8,4992
Exp/Cntr=0.3,0.1

Type RM Length L Ch R = 1,6763,319,319,319
BEGIN DESCRIPTION:
SOELL CREEK 15.0
END DESCRIPTION:
XS GIS Cut Line= 3
      2076175.03     13927524.98      2075775.00     13927725.00
      2075288.24     13928939.22
#Sta/Elev= 30
  4557.1 1637.95  4601.9 1632.12  4655.0 1611.60  4694.5 1604.19  4789.1 1582.03
  4872.0 1575.60  4937.3 1574.22  4979.8 1554.04  4980.1 1553.54  4984.1 1554.04
  4990.4 1554.71  5001.6 1567.88  5019.1 1572.86  5056.1 1574.25  5282.8 1578.17
  5366.2 1589.01  5425.4 1603.03  5501.2 1608.00  5605.7 1610.72  5659.5 1616.25
  5664.9 1619.94  5689.1 1617.37  5694.4 1621.64  5713.3 1618.82  5718.7 1622.93
  5742.9 1620.56  5779.9 1624.71  5824.8 1627.39  6049.4 1659.39  6312.5 1669.77
#Mann=9,-1,0
  4557.1    0.07       0  4694.5    0.12       0  4872.0    0.07       0
  4979.8    0.05       0  4984.1    0.07       0  5056.1   0.035       0
  5501.2    0.07       0  5779.9   0.035       0  5824.8    0.07       0
Bank Sta=4979.8,4984.1
Exp/Cntr=0.3,0.1

Type RM Length L Ch R = 1,6444,531,531,531
BEGIN DESCRIPTION:
SOELL CREEK 14.0
END DESCRIPTION:
XS GIS Cut Line= 3
      2076075.03     13927324.99      2075652.83     13927439.19
      2075455.11     13927920.49
#Sta/Elev= 30
  4552.0 1625.99  4574.6 1623.24  4603.5 1614.80  4609.2 1610.70  4649.1 1605.07
  4683.8 1591.80  4728.8 1584.58  4758.4 1574.54  4767.2 1573.71  4831.7 1568.26
  4917.8 1566.07  4945.7 1557.11  4976.8 1555.47  4991.3 1550.99  4991.6 1550.49
  4995.7 1550.99  5012.3 1553.37  5022.9 1555.38  5028.3 1562.22  5046.9 1562.59
  5052.3 1567.13  5100.2 1565.33  5159.0 1572.12  5337.6 1581.47  5343.0 1584.52
  5406.5 1588.42  5428.1 1595.43  5457.8 1598.84  5497.6 1600.62  5509.7 1603.79
#Mann=7,-1,0
  4552.0    0.07       0  4603.5    0.12       0  4767.2    0.07       0
  4991.3    0.05       0  4995.7    0.07       0  5012.3   0.035       0
  5457.8    0.07       0
Bank Sta=4991.3,4995.7
Exp/Cntr=0.3,0.1

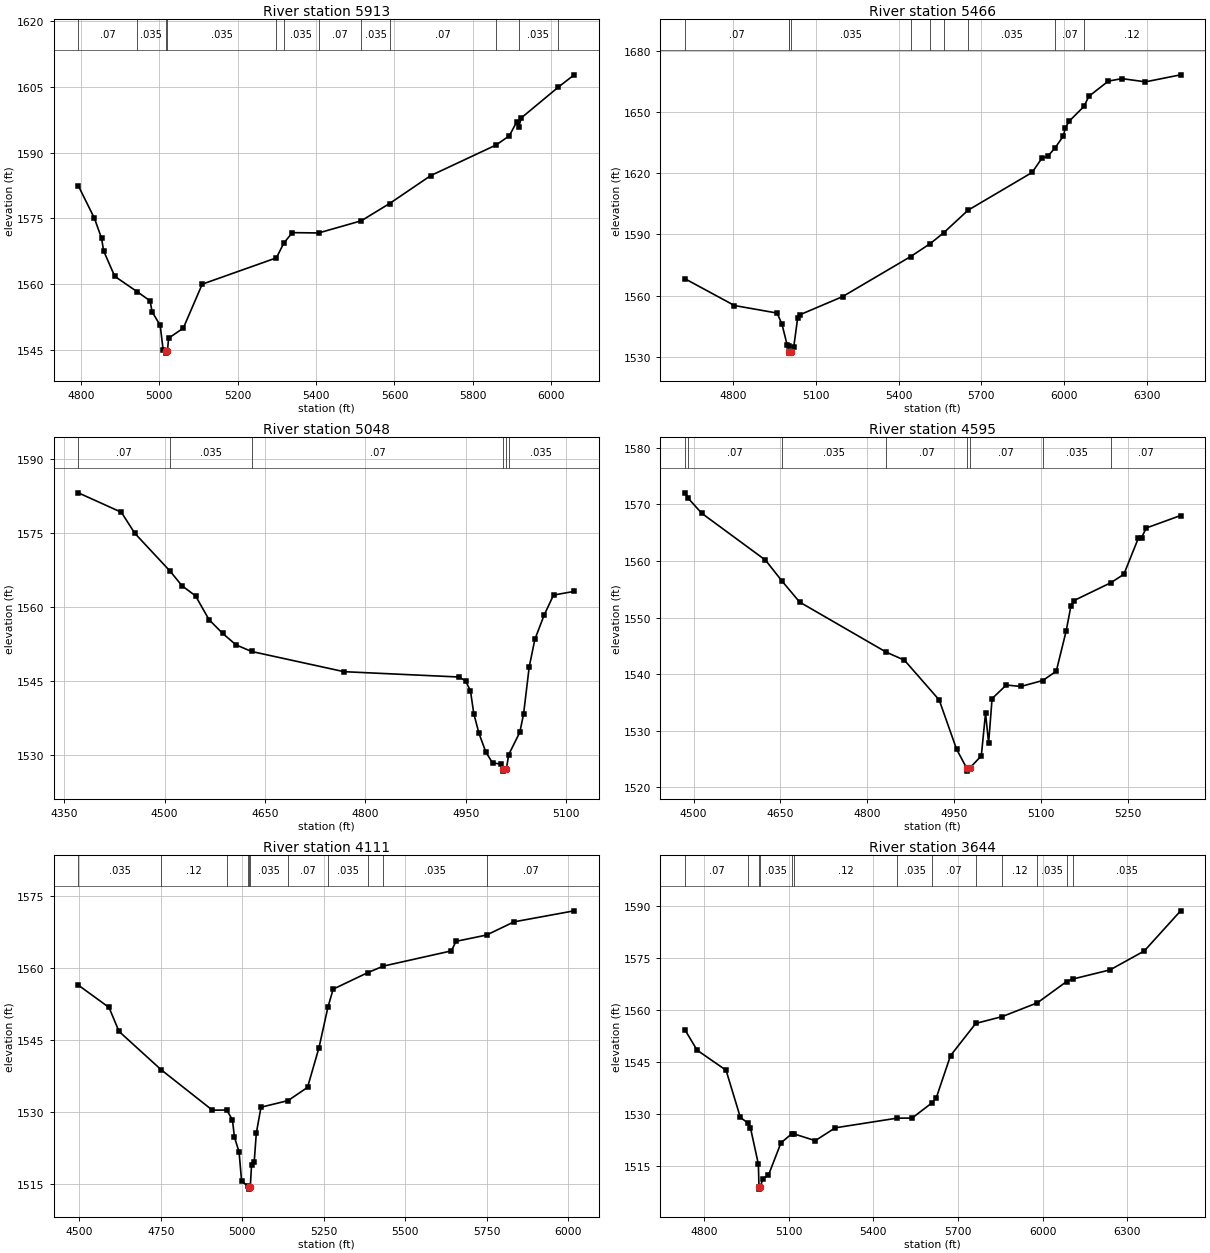
Type RM Length L Ch R = 1,5913,447,447,447
BEGIN DESCRIPTION:
SOELL CREEK 13.0
END DESCRIPTION:
XS GIS Cut Line= 3
      2075725.00     13926975.00      2075525.00     13927025.00
      2075288.24     13928056.42
#Sta/Elev= 30
  4793.9 1582.45  4835.1 1575.00  4853.2 1570.44  4858.3 1567.61  4886.7 1561.78
  4943.9 1558.26  4976.9 1556.17  4982.0 1553.67  5002.6 1550.59  5010.3 1544.86
  5016.7 1544.73  5017.0 1544.23  5021.1 1544.73  5024.1 1547.65  5061.6 1549.94
  5109.8 1559.98  5299.0 1565.99  5317.8 1569.35  5339.5 1571.75  5406.7 1571.68
  5515.5 1574.46  5587.6 1578.40  5692.7 1584.79  5859.0 1591.76  5892.7 1593.85
  5912.2 1597.09  5916.8 1595.81  5923.5 1597.96  6017.0 1604.92  6058.3 1607.80
#Mann=12,-1,0
  4793.9    0.07       0  4943.9   0.035       0  5016.7   0.035       0
  5021.1   0.035       0  5299.0    0.07       0  5317.8   0.035       0
  5406.7    0.07       0  5515.5   0.035       0  5587.6    0.07       0
  5859.0    0.12       0  5916.8   0.035       0  6017.0    0.07       0
Bank Sta=5016.7,5021.1
Exp/Cntr=0.3,0.1

Type RM Length L Ch R = 1,5466,418,418,418
BEGIN DESCRIPTION:
SOELL CREEK 12.0
END DESCRIPTION:
XS GIS Cut Line= 3
      2075572.10     13926587.63      2075225.00     13926725.00
      2074210.32     13927720.25
#Sta/Elev= 30
  4626.5 1568.30  4806.2 1555.15  4960.6 1551.45  4978.3 1545.97  4997.1 1535.74
  5003.5 1535.17  5004.5 1532.33  5004.9 1531.83  5009.2 1532.33  5021.0 1535.00
  5035.2 1549.24  5042.2 1550.57  5197.7 1559.52  5444.0 1579.14  5515.3 1585.52
  5563.3 1590.75  5651.7 1601.83  5883.7 1620.34  5919.1 1627.32  5940.2 1628.23
  5967.3 1632.49  5996.8 1638.22  6004.0 1642.26  6018.1 1645.48  6071.5 1652.72
  6088.8 1657.60  6159.5 1665.08  6209.0 1666.29  6293.8 1664.71  6421.1 1668.15
#Mann=10,-1,0
  4626.5    0.07       0  5003.5   0.035       0  5004.5    0.05       0
  5009.2   0.035       0  5444.0    0.07       0  5515.3   0.035       0
  5563.3    0.07       0  5651.7   0.035       0  5967.3    0.07       0
  6071.5    0.12       0
Bank Sta=5004.5,5009.2
Exp/Cntr=0.3,0.1

Type RM Length L Ch R = 1,5048,453,453,453
BEGIN DESCRIPTION:
SOELL CREEK 11.0
END DESCRIPTION:
XS GIS Cut Line= 3
      2075548.66     13926397.53      2074925.00     13926475.00
      2074824.96     13926525.02
#Sta/Elev= 30
  4371.3 1583.21  4435.5 1579.26  4455.6 1574.99  4508.5 1567.26  4526.1 1564.32
  4546.3 1562.27  4566.5 1557.42  4586.6 1554.66  4606.8 1552.31  4629.9 1550.97
  4768.0 1546.86  4939.3 1545.78  4949.4 1545.03  4956.8 1542.94  4961.8 1538.30
  4969.5 1534.32  4979.6 1530.57  4989.7 1528.31  5002.6 1528.08  5005.7 1527.15
  5006.1 1526.65  5010.5 1527.15  5013.8 1529.98  5030.5 1534.56  5036.1 1538.28
  5044.5 1547.84  5052.9 1553.41  5066.8 1558.37  5080.8 1562.43  5111.6 1563.18
#Mann=6,-1,0
  4371.3    0.07       0  4508.5   0.035       0  4629.9    0.07       0
  5005.7    0.05       0  5010.5    0.07       0  5013.8   0.035       0
Bank Sta=5005.7,5010.5
Exp/Cntr=0.3,0.1

Type RM Length L Ch R = 1,4595,484,484,484
BEGIN DESCRIPTION:
SOELL CREEK 10.0
END DESCRIPTION:
XS GIS Cut Line= 3
      2075384.17     13926083.29      2074875.00     13926075.00
      2074549.35     13926194.15
#Sta/Elev= 30
  4484.8 1572.06  4491.0 1571.06  4514.0 1568.45  4624.0 1560.17  4652.8 1556.44
  4683.0 1552.75  4832.6 1543.89  4864.0 1542.47  4924.0 1535.44  4954.0 1526.73
  4971.6 1523.36  4972.0 1522.86  4976.4 1523.36  4996.7 1525.56  5004.0 1533.11
  5009.3 1527.82  5015.3 1535.68  5039.8 1538.08  5065.0 1537.83  5102.8 1538.88
  5126.1 1540.52  5143.1 1547.60  5151.3 1551.99  5156.6 1553.01  5220.6 1556.18
  5242.8 1557.66  5268.0 1564.09  5273.4 1564.16  5281.5 1565.84  5340.8 1568.05
#Mann=8,-1,0
  4484.8   0.035       0  4491.0    0.07       0  4652.8   0.035       0
  4832.6    0.07       0  4971.6    0.05       0  4976.4    0.07       0
  5102.8   0.035       0  5220.6    0.07       0
Bank Sta=4971.6,4976.4
Exp/Cntr=0.3,0.1

Type RM Length L Ch R = 1,4111,467,467,467
BEGIN DESCRIPTION:
SOELL CREEK 9.0
END DESCRIPTION:
XS GIS Cut Line= 3
      2075267.01     13925731.74      2074775.00     13925625.00
      2074147.19     13926426.17
#Sta/Elev= 30
  4496.5 1556.37  4590.6 1551.73  4621.3 1546.74  4751.3 1538.72  4907.9 1530.34
  4951.7 1530.37  4969.3 1528.35  4975.4 1524.76  4989.7 1521.62  4997.4 1515.60
  5018.1 1514.46  5019.2 1514.41  5019.5 1513.91  5024.1 1514.41  5028.0 1518.94
  5036.1 1519.54  5042.5 1525.52  5056.9 1530.96  5140.1 1532.34  5199.7 1535.09
  5235.0 1543.38  5262.1 1551.72  5278.4 1555.54  5384.1 1558.96  5432.2 1560.33
  5640.9 1563.50  5655.4 1565.49  5749.1 1566.80  5833.5 1569.55  6017.8 1571.84
#Mann=11,-1,0
  4496.5   0.035       0  4751.3    0.12       0  4951.7    0.07       0
  5018.1   0.035       0  5019.2    0.05       0  5024.1   0.035       0
  5140.1    0.07       0  5262.1   0.035       0  5384.1    0.07       0
  5432.2   0.035       0  5749.1    0.07       0
Bank Sta=5019.2,5024.1
Exp/Cntr=0.3,0.1

Type RM Length L Ch R = 1,3644,447,447,447
BEGIN DESCRIPTION:
SOELL CREEK 8.0
END DESCRIPTION:
XS GIS Cut Line= 3
      2075049.97     13925028.60      2074825.00     13925175.00
      2073618.83     13926047.73
#Sta/Elev= 30
  4732.1 1554.34  4775.6 1548.38  4878.3 1542.57  4928.9 1528.94  4955.7 1527.29
  4964.7 1525.94  4992.9 1515.38  4995.0 1508.67  4995.4 1508.17  5000.0 1508.67
  5007.9 1511.14  5028.7 1512.23  5072.8 1521.54  5110.5 1524.14  5119.5 1524.14
  5194.3 1522.19  5265.4 1525.91  5483.9 1528.70  5537.6 1528.73  5608.4 1533.15
  5623.5 1534.64  5673.8 1546.79  5763.2 1556.11  5857.3 1558.10  5981.8 1562.08
  6085.0 1568.22  6106.3 1568.94  6239.1 1571.60  6360.6 1577.08  6489.3 1588.69
#Mann=13,-1,0
  4732.1    0.07       0  4955.7   0.035       0  4995.0   0.035       0
  5000.0   0.035       0  5110.5    0.07       0  5119.5    0.12       0
  5483.9   0.035       0  5608.4    0.07       0  5763.2   0.035       0
  5857.3    0.12       0  5981.8   0.035       0  6085.0    0.12       0
  6106.3   0.035       0
Bank Sta=4995,5000
Exp/Cntr=0.3,0.1

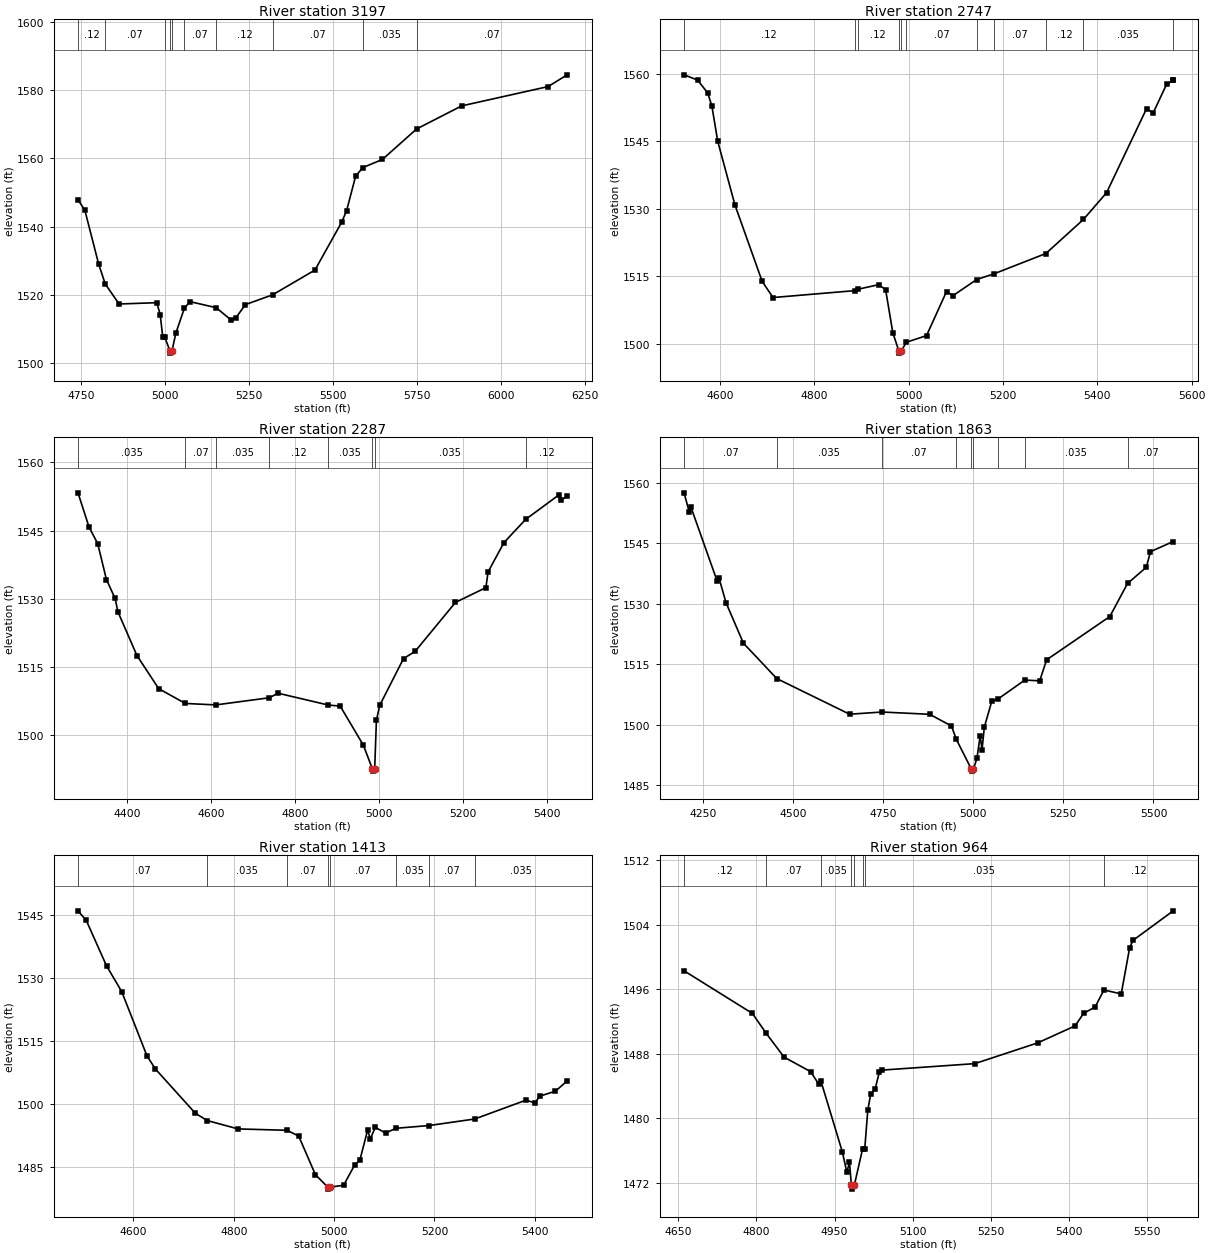
Type RM Length L Ch R = 1,3197,450,450,450
BEGIN DESCRIPTION:
SOELL CREEK 7.0
END DESCRIPTION:
XS GIS Cut Line= 3
      2074825.02     13924825.00      2074575.00     13924875.00
      2073604.69     13925584.14
#Sta/Elev= 30
  4740.6 1547.88  4761.0 1544.83  4801.8 1529.15  4821.7 1523.21  4863.0 1517.34
  4975.2 1517.72  4985.4 1514.24  4993.0 1507.67  4998.7 1507.67  5015.1 1503.44
  5015.4 1502.94  5020.1 1503.44  5032.2 1508.87  5057.4 1516.09  5074.0 1518.03
  5152.2 1516.26  5195.2 1512.75  5209.9 1513.18  5239.2 1517.16  5320.2 1520.03
  5446.2 1527.28  5525.7 1541.28  5540.4 1544.64  5567.4 1554.80  5589.1 1557.33
  5647.0 1559.69  5749.1 1568.64  5883.3 1575.40  6140.4 1581.05  6197.4 1584.50
#Mann=10,-1,0
  4740.6    0.12       0  4821.7    0.07       0  4998.7    0.12       0
  5015.1    0.05       0  5020.1    0.12       0  5057.4    0.07       0
  5152.2    0.12       0  5320.2    0.07       0  5589.1   0.035       0
  5749.1    0.07       0
Bank Sta=5015.1,5020.1
Exp/Cntr=0.3,0.1

Type RM Length L Ch R = 1,2747,460,460,460
BEGIN DESCRIPTION:
SOELL CREEK 6.0
END DESCRIPTION:
XS GIS Cut Line= 3
      2074725.02     13924274.98      2074325.00     13924525.00
      2073925.01     13924924.99
#Sta/Elev= 30
  4523.5 1559.80  4552.4 1558.63  4573.6 1555.76  4582.5 1552.88  4594.9 1545.03
  4631.4 1530.85  4689.2 1513.83  4712.2 1510.24  4885.0 1511.77  4892.0 1512.08
  4936.3 1513.10  4951.0 1511.98  4966.3 1502.39  4979.0 1498.37  4979.4 1497.87
  4984.4 1498.37  4994.9 1500.29  5037.7 1501.76  5080.1 1511.57  5094.2 1510.68
  5143.9 1514.24  5180.6 1515.51  5290.9 1520.04  5370.4 1527.61  5419.5 1533.56
  5504.3 1552.26  5518.5 1551.34  5546.8 1557.69  5560.8 1558.57  5560.9 1558.57
#Mann=11,-1,0
  4523.5    0.12       0  4885.0   0.035       0  4892.0    0.12       0
  4979.0    0.05       0  4984.4    0.12       0  4994.9    0.07       0
  5143.9    0.12       0  5180.6    0.07       0  5290.9    0.12       0
  5370.4   0.035       0  5560.8    0.12       0
Bank Sta=4979,4984.4
Exp/Cntr=0.3,0.1

Type RM Length L Ch R = 1,2287,424,424,424
BEGIN DESCRIPTION:
SOELL CREEK 5.0
END DESCRIPTION:
XS GIS Cut Line= 3
      2074620.27     13924134.51      2073925.00     13924325.00
      2073794.31     13924749.13
#Sta/Elev= 30
  4283.3 1553.30  4309.5 1545.79  4330.2 1542.13  4351.0 1534.21  4371.7 1530.05
  4378.3 1527.13  4423.6 1517.50  4475.4 1510.21  4539.0 1506.95  4611.3 1506.63
  4739.2 1508.21  4759.4 1509.21  4878.9 1506.61  4907.6 1506.36  4962.7 1497.78
  4984.2 1492.56  4984.7 1492.06  4989.7 1492.56  4993.8 1503.22  5001.6 1506.52
  5058.4 1516.83  5085.9 1518.40  5182.1 1529.19  5254.5 1532.44  5259.7 1535.90
  5297.6 1542.36  5349.0 1547.44  5428.3 1552.84  5433.6 1551.66  5448.0 1552.58
#Mann=8,-1,0
  4283.3   0.035       0  4539.0    0.07       0  4611.3   0.035       0
  4739.2    0.12       0  4878.9   0.035       0  4984.2   0.035       0
  4989.7   0.035       0  5349.0    0.12       0
Bank Sta=4984.2,4989.7
Exp/Cntr=0.3,0.1

Type RM Length L Ch R = 1,1863,450,450,450
BEGIN DESCRIPTION:
SOELL CREEK 4.0
END DESCRIPTION:
XS GIS Cut Line= 3
      2074620.28     13924082.42      2073825.00     13923975.00
      2073283.44     13924095.45
#Sta/Elev= 30
  4197.5 1557.53  4211.7 1552.86  4216.8 1553.94  4289.5 1535.62  4294.5 1536.44
  4313.8 1530.33  4362.1 1520.27  4454.7 1511.49  4656.9 1502.65  4746.9 1503.19
  4878.9 1502.63  4939.5 1499.73  4953.1 1496.40  4994.7 1489.04  4995.1 1488.54
  5000.3 1489.04  5010.2 1491.70  5019.2 1497.30  5024.3 1493.84  5030.7 1499.42
  5051.2 1505.83  5068.7 1506.42  5142.9 1511.11  5184.4 1510.93  5203.5 1516.13
  5379.0 1526.87  5428.0 1535.06  5480.0 1539.06  5491.7 1542.94  5554.8 1545.46
#Mann=9,-1,0
  4197.5    0.07       0  4454.7   0.035       0  4746.9    0.07       0
  4953.1   0.035       0  4994.7   0.035       0  5000.3   0.035       0
  5068.7    0.07       0  5142.9   0.035       0  5428.0    0.07       0
Bank Sta=4994.7,5000.3
Exp/Cntr=0.3,0.1

Type RM Length L Ch R = 1,1413,449,449,449
BEGIN DESCRIPTION:
SOELL CREEK 3.0
END DESCRIPTION:
XS GIS Cut Line= 3
      2074481.40     13923639.72      2073975.00     13923575.00
      2073522.15     13923678.79
#Sta/Elev= 30
  4489.5 1545.90  4506.0 1543.61  4546.4 1532.80  4576.6 1526.69  4627.0 1511.38
  4643.6 1508.29  4723.3 1497.74  4746.8 1496.00  4808.5 1494.00  4906.2 1493.67
  4929.4 1492.30  4962.7 1483.13  4987.1 1480.17  4987.6 1479.67  4992.7 1480.17
  5018.9 1480.58  5041.1 1485.44  5051.3 1486.55  5066.9 1493.75  5072.1 1491.62
  5082.1 1494.37  5102.6 1493.03  5123.3 1494.15  5189.2 1494.80  5280.3 1496.36
  5382.6 1500.85  5400.1 1500.20  5410.4 1501.81  5441.2 1502.98  5464.6 1505.42
#Mann=8,-1,0
  4489.5    0.07       0  4746.8   0.035       0  4906.2    0.07       0
  4987.1    0.05       0  4992.7    0.07       0  5123.3   0.035       0
  5189.2    0.07       0  5280.3   0.035       0
Bank Sta=4987.1,4992.7
Exp/Cntr=0.3,0.1

Type RM Length L Ch R = 1,964,451,451,451
BEGIN DESCRIPTION:
SOELL CREEK 2.0
END DESCRIPTION:
XS GIS Cut Line= 3
      2074264.37     13923236.07      2073925.00     13923175.00
      2073396.29     13923448.76
#Sta/Elev= 30
  4660.8 1498.31  4792.2 1493.02  4818.9 1490.53  4853.2 1487.59  4904.0 1485.80
  4920.1 1484.21  4924.1 1484.58  4965.0 1475.85  4973.7 1473.32  4978.8 1474.54
  4982.4 1471.72  4982.9 1471.22  4988.1 1471.72  5003.9 1476.19  5008.1 1476.19
  5013.9 1480.98  5019.5 1483.02  5028.1 1483.65  5036.0 1485.70  5041.6 1485.99
  5219.6 1486.79  5340.3 1489.36  5412.3 1491.47  5428.8 1493.03  5450.9 1493.82
  5467.8 1495.92  5501.1 1495.45  5517.3 1501.18  5523.6 1502.08  5601.0 1505.75
#Mann=8,-1,0
  4660.8    0.12       0  4818.9    0.07       0  4924.1   0.035       0
  4982.4   0.035       0  4988.1   0.035       0  5003.9    0.07       0
  5008.1   0.035       0  5467.8    0.12       0
Bank Sta=4982.4,4988.1
Exp/Cntr=0.3,0.1

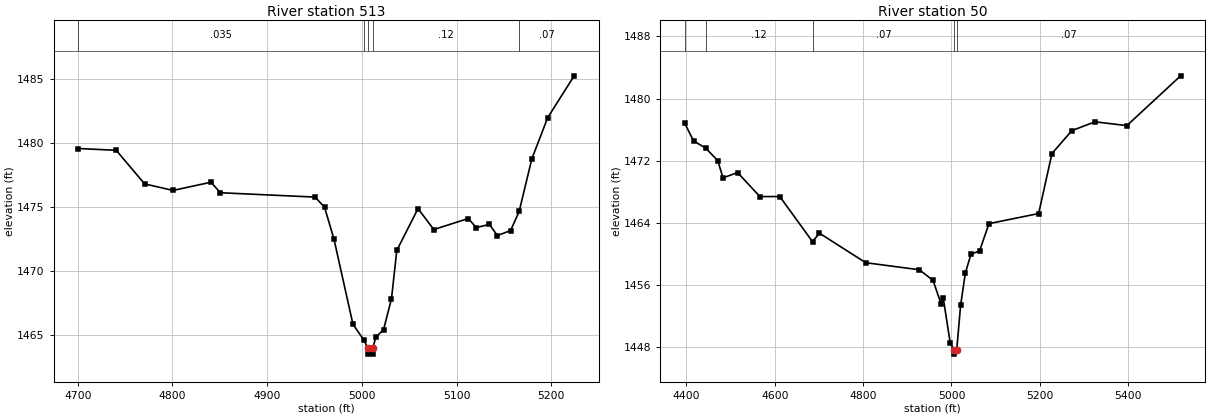
Type RM Length L Ch R = 1,513,463,463,463
BEGIN DESCRIPTION:
SOELL CREEK 1.0
END DESCRIPTION:
XS GIS Cut Line= 3
      2074074.98     13922775.00      2073775.00     13922775.00
      2073574.98     13922875.01
#Sta/Elev= 30
  4700.6 1479.55  4740.6 1479.41  4770.6 1476.79  4800.6 1476.28  4840.6 1476.92
  4850.6 1476.10  4950.6 1475.76  4960.6 1474.97  4970.6 1472.47  4990.6 1465.84
  5002.3 1464.59  5006.1 1464.01  5006.6 1463.51  5011.4 1463.51  5011.8 1464.01
  5014.6 1464.82  5022.9 1465.42  5031.3 1467.83  5036.9 1471.60  5059.3 1474.86
  5076.0 1473.23  5112.4 1474.09  5120.8 1473.38  5134.7 1473.63  5143.1 1472.76
  5157.1 1473.15  5166.1 1474.64  5179.5 1478.74  5196.2 1481.95  5224.2 1485.22
#Mann=5,-1,0
  4700.6   0.035       0  5002.3    0.12       0  5006.1   0.035       0
  5011.8    0.12       0  5166.1    0.07       0
Bank Sta=5006.1,5011.8
Exp/Cntr=0.3,0.1

Type RM Length L Ch R = 1,50,0,0,0
BEGIN DESCRIPTION:
SOELL CREEK 0.0
END DESCRIPTION:
XS GIS Cut Line= 5
      2074032.65     13922695.06      2073686.17     13922524.46
      2073474.30     13922475.29      2073346.77     13922524.25
      2073172.30     13922864.19
#Sta/Elev= 30
  4396.3 1476.81  4416.0 1474.56  4443.6 1473.62  4470.9 1472.01  4482.8 1469.79
  4515.8 1470.48  4566.3 1467.38  4611.3 1467.39  4685.4 1461.58  4701.1 1462.67
  4805.8 1458.87  4927.4 1457.96  4958.2 1456.59  4976.4 1453.59  4981.5 1454.28
  4997.1 1448.55  5006.0 1447.60  5006.5 1447.10  5011.8 1447.60  5020.7 1453.40
  5031.4 1457.55  5044.2 1459.98  5063.5 1460.38  5084.9 1463.90  5197.3 1465.20
  5227.4 1472.92  5272.3 1475.87  5324.8 1477.01  5397.0 1476.52  5518.7 1482.93
#Mann=5,-1,0
  4396.3   0.035       0  4443.6    0.12       0  4685.4    0.07       0
  5006.0    0.05       0  5011.8    0.07       0
Bank Sta=5006,5011.8
Exp/Cntr=0.3,0.1

Chan Stop Cuts=-1