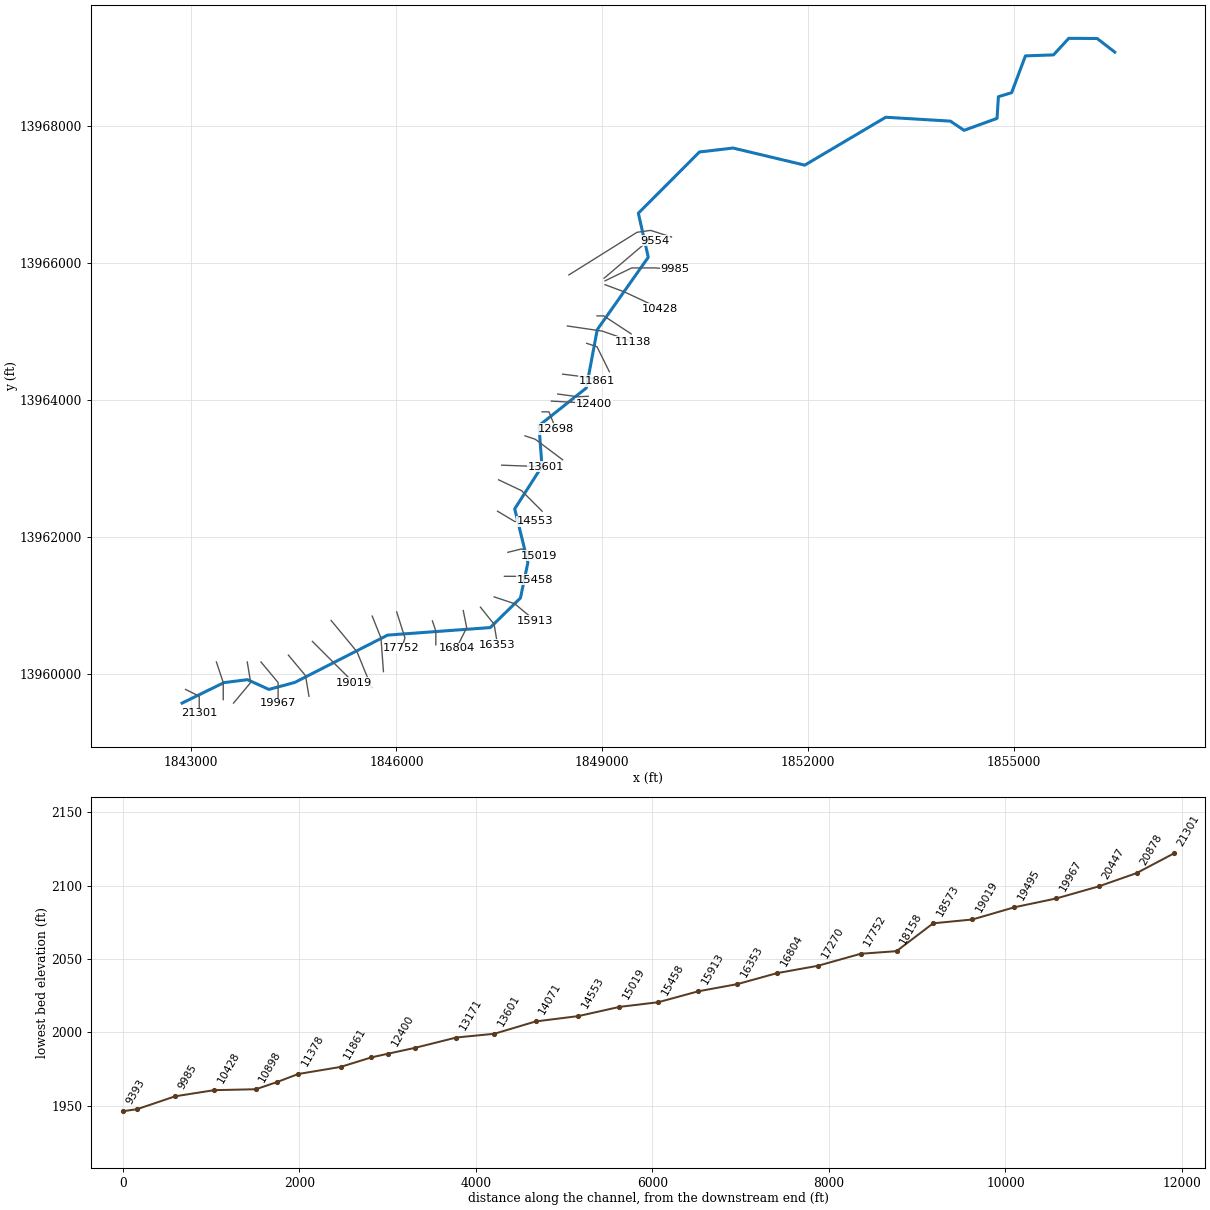
--- Spring Creek.prj (project) ---

Proj Title=Spring Creek_US Base Level Engineering
Current Plan=p01
Default Exp/Contr=0.3,0.1
English Units
Geom File=g01
Flow File=f01
Plan File=p01
Y Axis Title=Elevation
X Axis Title(PF)=Main Channel Distance
X Axis Title(XS)=Station
BEGIN DESCRIPTION:
Spring Creek
END DESCRIPTION:
DSS Export Rating Curves= 0
DSS Export Rating Curve Sorted= 0
DSS Export Volume Flow Curves= 0
DXF OffsetX= 0
DXF OffsetY= 0
DXF ScaleX= 1
DXF ScaleY= 10

--- Spring Creek.p01 (plan) ---

Plan Title=Multiple Run
Program Version=4.10
Short Identifier=Multiple
Geom File=g01
Flow File=f01
Subcritical Flow
K Sum by GR= 0
Std Step Tol= 0.01
Critical Tol= 0.01
Num of Std Step Trials= 20
Max Error Tol= 0.3
Flow Tol Ratio= 0.001
Split Flow NTrial= 30
Split Flow Tol= 0.02
Split Flow Ratio= 0.02
Log Output Level= 0
Friction Slope Method= 1
Unsteady Friction Slope Method= 2
Unsteady Bridges Friction Slope Method= 1
Parabolic Critical Depth
Global Vel Dist= 1 , 1 , 1
Global Log Level= 0
CheckData=True
Encroach Param=-1 ,0,0, 0
BEGIN DESCRIPTION:
Multiple Run
END DESCRIPTION:
Computation Interval=1HOUR
Output Interval=1HOUR
Run HTab= 0
Run UNet= 0
Run PostProcess= 0
Run WQNet= 0
UNET Theta= 1
UNET Theta Warmup= 1
UNET ZTol= 0.02
UNET ZSATol= 0.05
UNET MxIter= 20
UNET MaxInSteps= 0
UNET DtIC= 0
UNET DtMin= 0
UNET MaxCRTS= 20
UNET WFStab= 2
UNET SFStab= 1
UNET WFX= 1
UNET SFX= 1
UNET DSS MLevel= 4
UNET DZMax Abort= 100
UNET Convert EG Bridges= 0
UNET Use Existing IB Tables=-1
UNET Froude Reduction=False
UNET Froude Limit= 1
UNET Froude Power= 10
UNET Time Slicing=0,0, 5
UNET Junction Losses=0
Instantaneous Interval=1HOUR
Write IC File= 0
Write IC File at Sim End=0
Echo Input=False
Echo Parameters=False
Echo Output=False
Write Detailed= 0
WQ AD Non Conservative
WQ ULTIMATE=-1
WQ Max Comp Step=1HOUR
WQ Output Interval=15MIN
WQ Output Selected Increments= 0
WQ Output face flow=0
WQ Output face velocity=0
WQ Output face area=0
WQ Output face dispersion=0
WQ Output cell volume=0
WQ Output cell surface area=0
WQ Output cell continuity=0
WQ Output cumulative cell continuity=0
WQ Output face conc=0
WQ Output face dconc_dx=0
WQ Output face courant=0
WQ Output face peclet=0
WQ Output face adv mass=0
WQ Output face disp mass=0
WQ Output cell mass=0
WQ Output cell source sink temp=0
WQ Output cell source sink nsm=0
WQ Output MaxMinRange=-1
WQ Daily Max Min Mean=-1
WQ Daily Range=0
WQ Daily Time=0
WQ Create Restart=0
WQ Fixed Restart=0
WQ System Summary=0
WQ Use Fixed Temperature=0
Sorting and Armoring Iterations= 10
XS Update Threshold= 0.02
Hydraulics Update Threshold= 0.02
Energy Slope Method= 1
Volume Change Method= 0
XS Weighting Method= 0
Number of US Weighted Cross Sections= 1
Number of DS Weighted Cross Sections= 1
Upstream XS Weight=0.25
Main XS Weight=0.5
Downstream XS Weight=0.25
Number of DS XS's Weighted with US Boundary= 1
Upstream Boundary Weight= 1
Weight of XSs Associated with US Boundary= 0
Number of US XS's Weighted with DS Boundary= 1
Downstream Boundary Weight= 0.5
Weight of XSs Associated with DS Boundary= 0.5
Sediment Output Level= 4
Mass or Volume Output= 0
Output Increment Type= 1
Profile and TS Output Increment= 10
XS Output Flag= 0
XS Output Increment= 10
Disregard all LS=0
Disregard all Conn=0
Disregard all Breaches=0
Disregard all Pumps=0

--- Spring Creek.f01 (steady flow) ---

Flow Title=Multiple
Program Version=4.10
Number of Profiles= 7
Profile Names=10-year,25-year,50-year,1pct_min,100-year,1pct_plu,500-year
River Rch & RM=Spring Creek,Reach-1         ,21301
     365     580     772     499     995    1985    1628
River Rch & RM=Spring Creek,Reach-1         ,19495
    1209    2078    2909    1967    3925    7831    7064
River Rch & RM=Spring Creek,Reach-1         ,13171
    1271    2189    3069    2078    4145    8271    7476
River Rch & RM=Spring Creek,Reach-1         ,11138
    1503    2611    3683    2506    5001    9978    9119
River Rch & RM=Spring Creek,Reach-1         ,9100
    2261    4019    5754    3971    7922   15807   14860
River Rch & RM=Spring Creek,Reach-1         ,7742
    2772    4962    7138    4943    9864   19680   18643
River Rch & RM=Spring Creek,Reach-1         ,1384
    2939    5273    7597    5268   10512   20974   19919
Boundary for River Rch & Prof#=Spring Creek,Reach-1         , 1
Up Type= 0
Dn Type= 3
Dn Slope=0.009
Boundary for River Rch & Prof#=Spring Creek,Reach-1         , 2
Up Type= 0
Dn Type= 3
Dn Slope=0.009
Boundary for River Rch & Prof#=Spring Creek,Reach-1         , 3
Up Type= 0
Dn Type= 3
Dn Slope=0.009
Boundary for River Rch & Prof#=Spring Creek,Reach-1         , 4
Up Type= 0
Dn Type= 3
Dn Slope=0.009
Boundary for River Rch & Prof#=Spring Creek,Reach-1         , 5
Up Type= 0
Dn Type= 3
Dn Slope=0.009
Boundary for River Rch & Prof#=Spring Creek,Reach-1         , 6
Up Type= 0
Dn Type= 3
Dn Slope=0.009
Boundary for River Rch & Prof#=Spring Creek,Reach-1         , 7
Up Type= 0
Dn Type= 3
Dn Slope=0.009
DSS Import GetInterval= 0
DSS Import GetPeak= 0
DSS Import FillOption= 0

--- Spring Creek.g01 (geometry) ---

Geom Title=Existing Conditions
Program Version=4.10

River Reach=Spring Creek    ,Reach-1
Reach XY= 30
        1842875.       13959575.       1843485.5     13959873.78
      1843828.42     13959917.21       1844140.2      13959774.5
      1844518.96     13959876.63      1845871.69     13960566.93
      1847369.14     13960677.05      1847808.57     13961108.24
      1847917.44       13961625.      1847725.52     13962409.78
      1848122.94     13963030.85      1848078.76     13963623.44
      1848769.17      13964172.7       1848928.6     13965023.51
      1849672.76     13966080.93      1849528.27     13966723.64
      1850418.94     13967616.86      1850909.78     13967674.48
      1851954.97     13967425.04      1853135.44     13968123.95
       1854078.4     13968067.17      1854278.31     13967933.02
      1854758.85     13968107.92      1854778.54     13968423.56
      1854971.83     13968482.61      1855172.56     13969019.48
      1855582.01     13969033.99      1855804.63     13969275.39
      1856218.89      13969273.2        1856475.       13969075.

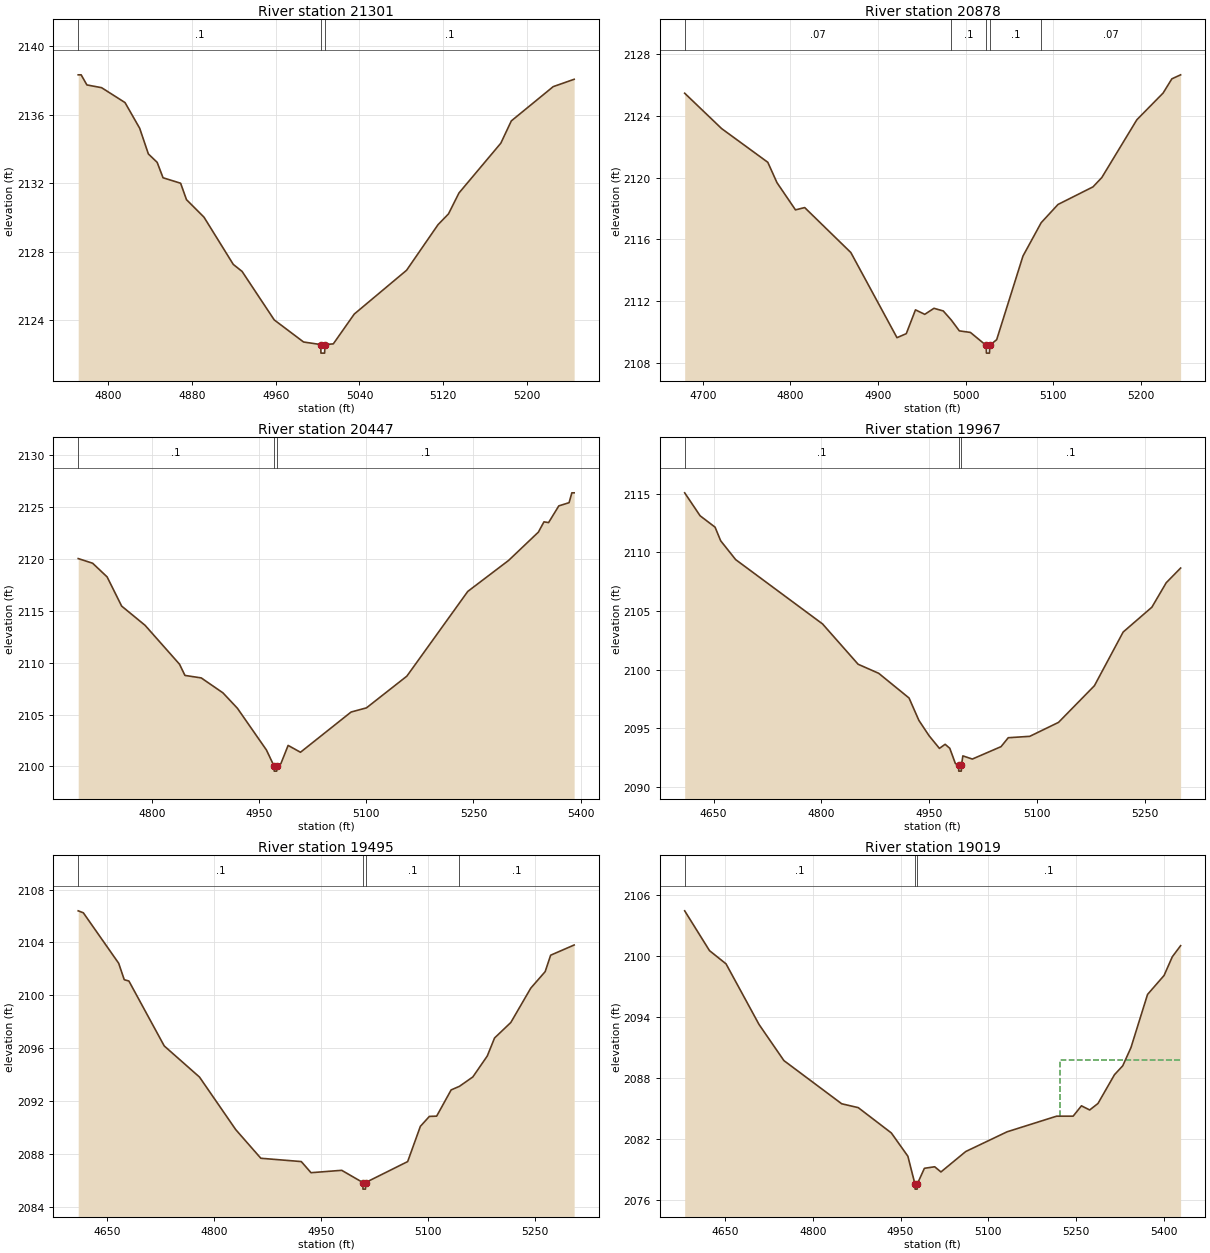
Type RM Length L Ch R = 1 ,21301   ,423,423,423
BEGIN DESCRIPTION:
Spring Creek 47.0
END DESCRIPTION:
XS GIS Cut Line= 3
      1842925.04     13959774.98        1843125.       13959675.
        1843125.     13959424.96
#Sta/Elev= 30
  4771.4 2138.33  4774.2 2138.33  4779.7 2137.74  4793.7 2137.58  4816.1 2136.71
  4830.1 2135.21  4838.4 2133.71  4846.8 2133.22  4852.4 2132.32  4869.2    2132
  4874.8 2131.04  4891.5 2130.02  4919.5 2127.26  4927.9 2126.85  4958.6 2124.02
  4986.6 2122.73    5003 2122.58  5003.2 2122.08  5006.7 2122.08    5007 2122.58
    5015 2122.62    5035 2124.36    5085 2126.92    5115 2129.58    5125 2130.21
    5135 2131.43    5175 2134.34    5185 2135.64    5225 2137.64    5245 2138.07
#Mann= 3 ,-1 , 0
  4771.4      .1       0    5003     .05       0    5007      .1       0
Bank Sta=5003,5007
XS Rating Curve= 0 ,0
Exp/Cntr=0.3,0.1

Type RM Length L Ch R = 1 ,20878   ,431,431,431
BEGIN DESCRIPTION:
Spring Creek 46.0
END DESCRIPTION:
XS GIS Cut Line= 3
        1843375.     13960175.01        1843475.       13959875.
        1843475.     13959625.03
#Sta/Elev= 30
  4679.2 2125.46  4721.4 2123.17  4774.1 2120.99  4784.6 2119.67  4805.7 2117.91
  4816.2 2118.06  4868.9 2115.15  4921.6 2109.64  4932.2  2109.9  4942.7 2111.44
  4953.3 2111.15  4963.8 2111.54  4974.4 2111.37  4983.6 2110.78  4992.8 2110.08
  5005.4 2109.98  5023.4 2109.14  5023.7 2108.64  5027.2 2108.64  5027.4 2109.14
  5035.4 2109.51  5065.4 2114.92  5086.2 2117.08  5105.4 2118.26  5145.4  2119.4
  5155.4    2120  5195.4 2123.74  5225.4 2125.47  5235.4 2126.39  5245.4 2126.65
#Mann= 5 ,-1 , 0
  4679.2     .07       0  4983.6      .1       0  5023.4     .05       0
  5027.4      .1       0  5086.2     .07       0
Bank Sta=5023.4,5027.4
XS Rating Curve= 0 ,0
Exp/Cntr=0.3,0.1

Type RM Length L Ch R = 1 ,20447   ,480,480,480
BEGIN DESCRIPTION:
Spring Creek 45.0
END DESCRIPTION:
XS GIS Cut Line= 3
        1843825.     13960174.97        1843875.       13959875.
      1843625.01     13959575.02
#Sta/Elev= 30
  4696.5 2120.05  4716.7  2119.6    4737 2118.28  4757.3 2115.47  4790.2 2113.61
  4838.4 2109.86    4846 2108.78  4868.8 2108.54  4899.2  2107.1  4919.5 2105.61
  4960.1 2101.59  4970.7 2100.05    4971 2099.55  4974.5 2099.55  4974.7 2100.05
  4980.3 2100.26  4990.5 2102.03  5007.8 2101.37  5078.7 2105.25  5100.2 2105.65
  5156.8 2108.71  5242.1 2116.88  5299.3 2119.87    5341  2122.6  5348.8 2123.59
  5355.3 2123.52  5369.6 2125.13    5384 2125.44  5387.9 2126.39  5391.1 2126.39
#Mann= 3 ,-1 , 0
  4696.5      .1       0  4970.7     .05       0  4974.7      .1       0
Bank Sta=4970.7,4974.7
XS Rating Curve= 0 ,0
Exp/Cntr=0.3,0.1

Type RM Length L Ch R = 1 ,19967   ,472,472,472
BEGIN DESCRIPTION:
Spring Creek 44.0
END DESCRIPTION:
XS GIS Cut Line= 3
      1844024.98     13960175.02        1844275.       13959875.
        1844275.     13959575.04
#Sta/Elev= 30
  4609.7 2115.09  4631.2 2113.13    4652 2112.16  4659.8    2111  4680.7 2109.39
  4801.7  2103.9  4851.2 2100.46  4879.8 2099.69  4922.1 2097.58  4935.8 2095.67
  4950.1 2094.35  4964.4 2093.28  4972.3 2093.63  4978.8 2093.29  4986.6 2091.99
  4991.1 2091.84  4991.3 2091.34  4994.8 2091.34  4995.1 2091.84    4997 2092.64
  5010.2 2092.37  5050.2 2093.43  5060.2 2094.19  5090.2 2094.31  5130.2  2095.5
  5180.2 2098.63  5220.2 2103.21  5260.2 2105.33  5280.2 2107.42  5300.2 2108.67
#Mann= 3 ,-1 , 0
  4609.7      .1       0  4991.1     .05       0  4995.1      .1       0
Bank Sta=4991.1,4995.1
XS Rating Curve= 0 ,0
Exp/Cntr=0.3,0.1

Type RM Length L Ch R = 1 ,19495   ,476,476,476
BEGIN DESCRIPTION:
Spring Creek 43.0
END DESCRIPTION:
XS GIS Cut Line= 3
      1844424.97     13960275.04        1844675.       13959975.
        1844725.       13959675.
#Sta/Elev= 30
    4610 2106.39  4617.2 2106.24  4666.7 2102.43  4674.5 2101.19    4681 2101.09
  4730.5 2096.19  4779.9 2093.84  4830.7 2089.87  4865.8 2087.71  4922.5 2087.46
  4936.1 2086.62  4979.1  2086.8  5008.7 2085.88  5008.9 2085.38  5012.4 2085.38
  5012.7 2085.88  5071.5 2087.46  5089.3 2090.12  5101.9 2090.87  5112.1 2090.89
  5132.4 2092.87    5144 2093.14  5162.8 2093.85    5183 2095.43  5193.2 2096.79
    5216 2097.96  5243.9 2100.55  5264.1  2101.8  5271.8 2103.04  5304.7 2103.81
#Mann= 4 ,-1 , 0
    4610      .1       0  5008.7     .05       0  5012.7      .1       0
    5144      .1       0
Bank Sta=5008.7,5012.7
XS Rating Curve= 0 ,0
Exp/Cntr=0.3,0.1

Type RM Length L Ch R = 1 ,19019   ,446,446,446
BEGIN DESCRIPTION:
Spring Creek 42.0
END DESCRIPTION:
XS GIS Cut Line= 3
      1844774.97     13960475.03        1845075.       13960175.
      1845375.02     13959874.98
#Sta/Elev= 30
  4580.5 2104.43    4623 2100.51  4651.3 2099.21  4707.8 2093.24  4750.3 2089.69
  4849.2 2085.44  4877.5 2085.06  4934.1 2082.57  4962.4 2080.28  4974.5 2077.54
  4974.8 2077.04  4978.3 2077.04  4978.5 2077.54  4990.7 2079.09  5008.3 2079.24
    5019 2078.73  5061.4 2080.74  5132.1 2082.68  5216.9 2084.22  5245.2 2084.22
  5259.4 2085.24  5273.5 2084.83  5287.7 2085.47  5315.9  2088.3  5330.1 2089.18
  5344.2 2090.98  5372.5  2096.2  5400.8 2098.07  5414.9 2099.91  5429.1    2101
#Mann= 3 ,-1 , 0
  4580.5      .1       0  4974.5     .05       0  4978.5      .1       0
#XS Ineff= 2 , 0
                         5222.38         2089.79
Permanent Ineff=
       F       F
Bank Sta=4974.5,4978.5
XS Rating Curve= 0 ,0
Exp/Cntr=0.3,0.1

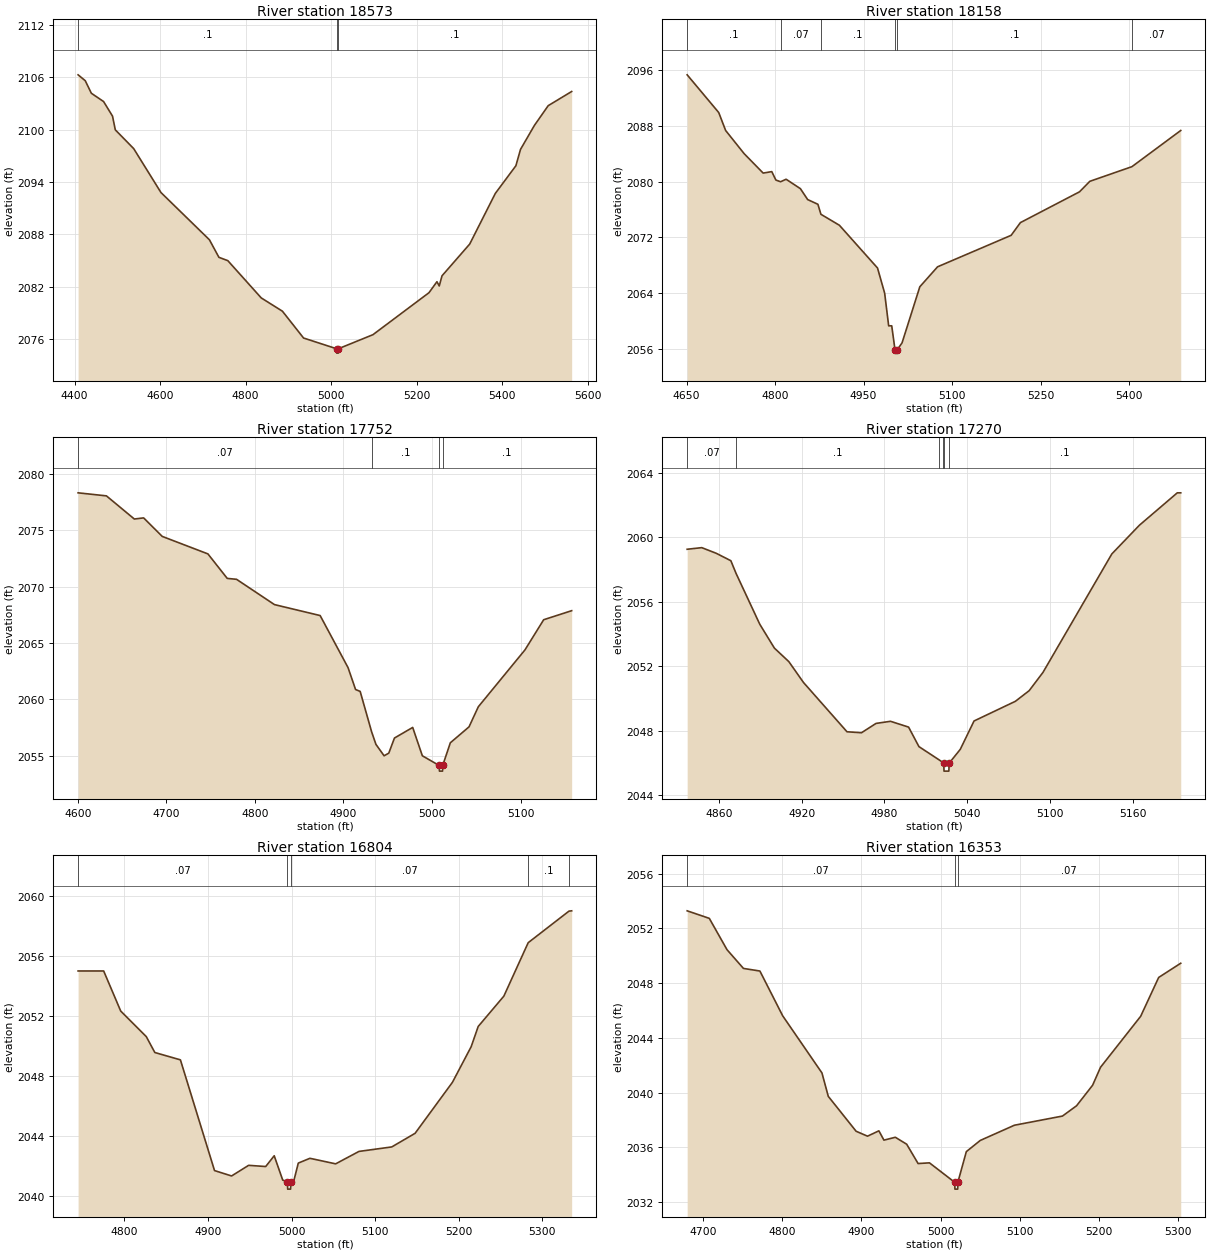
Type RM Length L Ch R = 1 ,18573   ,415,415,415
BEGIN DESCRIPTION:
Spring Creek 41.0
END DESCRIPTION:
XS GIS Cut Line= 3
      1845047.78     13960780.93        1845425.       13960325.
      1845637.18     13959804.21
#Sta/Elev= 30
  4408.2 2106.28  4424.9 2105.61  4439.2 2104.17  4467.8 2103.22  4488.7 2101.55
  4495.2 2099.98  4538.2 2097.83    4602  2092.8  4715.3 2087.39  4737.5 2085.38
  4758.3    2085  4836.5 2080.73    4886 2079.21  4935.4 2076.14  5012.7 2074.91
  5012.9 2074.41  5016.4 2074.41  5016.7 2074.91  5097.6 2076.52  5228.7 2081.33
  5247.3 2082.59  5252.7  2082.1  5259.1 2083.26  5323.9  2086.9  5383.8  2092.7
  5431.9 2095.87  5442.7 2097.74  5475.1 2100.48  5507.5 2102.75  5562.3 2104.37
#Mann= 3 ,-1 , 0
  4408.2      .1       0  5012.7     .05       0  5016.7      .1       0
Bank Sta=5012.7,5016.7
XS Rating Curve= 0 ,0
Exp/Cntr=0.3,0.1

Type RM Length L Ch R = 1 ,18158   ,406,406,406
BEGIN DESCRIPTION:
Spring Creek 40.0
END DESCRIPTION:
XS GIS Cut Line= 3
      1845647.46     13960844.68        1845775.       13960525.
      1845811.14     13960034.01
#Sta/Elev= 30
    4651 2095.28  4704.5 2089.88  4716.2 2087.31  4747.6 2083.99  4779.8 2081.21
  4794.4 2081.42  4801.4 2080.21  4809.4 2079.97  4818.7 2080.33  4842.9 2078.98
  4855.2 2077.42  4872.6 2076.74  4877.7 2075.31    4909 2073.74  4973.6 2067.62
  4985.7 2064.02  4992.5 2059.34  4997.7 2059.34  5003.2 2055.93  5003.5 2055.43
  5007.2 2055.93  5015.2  2056.9  5045.3 2064.93  5075.4 2067.79  5200.1  2072.3
  5215.8 2074.12    5316 2078.53  5333.4 2080.03  5404.8 2082.13  5487.5 2087.31
#Mann= 6 ,-1 , 0
    4651      .1       0  4809.4     .07       0  4877.7      .1       0
  5003.2     .05       0  5007.2      .1       0  5404.8     .07       0
Bank Sta=5003.2,5007.2
XS Rating Curve= 0 ,0
Exp/Cntr=0.3,0.1

Type RM Length L Ch R = 1 ,17752   ,482,482,482
BEGIN DESCRIPTION:
Spring Creek 39.0
END DESCRIPTION:
XS GIS Cut Line= 3
      1846004.34     13960905.53        1846125.       13960525.
      1846075.01     13960375.02
#Sta/Elev= 30
  4600.4  2078.3  4632.4 2078.03  4663.9 2075.98  4674.4 2076.08  4695.4 2074.44
    4747 2072.89  4768.8 2070.72  4779.3 2070.64  4822.1  2068.4  4873.7 2067.43
  4905.2 2062.82  4913.7 2060.88  4918.9 2060.71  4931.8 2057.14  4936.7 2056.02
  4945.9 2055.01  4951.2 2055.24  4957.6 2056.58  4978.2 2057.52  4989.1 2055.01
  5008.1 2054.15  5008.4 2053.65  5011.9 2053.65  5012.1 2054.15  5020.7 2056.16
  5041.8 2057.57  5052.3 2059.35    5105 2064.39  5126.1 2067.06  5157.7 2067.86
#Mann= 4 ,-1 , 0
  4600.4     .07       0  4931.8      .1       0  5008.1     .05       0
  5012.1      .1       0
Bank Sta=5008.1,5012.1
XS Rating Curve= 0 ,0
Exp/Cntr=0.3,0.1

Type RM Length L Ch R = 1 ,17270   ,466,466,466
BEGIN DESCRIPTION:
Spring Creek 38.0
END DESCRIPTION:
XS GIS Cut Line= 3
      1846524.99     13960775.04        1846575.       13960625.
        1846575.     13960424.96
#Sta/Elev= 30
  4836.8 2059.26  4847.4 2059.36  4857.9 2059.01  4868.5 2058.55  4872.3 2057.76
  4889.5 2054.61  4900.1 2053.13  4910.6 2052.29  4921.2    2051  4952.8 2047.94
  4963.3 2047.88  4973.9 2048.46  4984.4 2048.59  4997.5 2048.23    5005 2047.02
  5019.8 2046.19  5022.5 2046.03    5023    2046  5023.2  2045.5  5026.7  2045.5
    5027    2046    5035 2046.85    5045 2048.61    5075 2049.83    5085 2050.49
    5095 2051.62    5145 2058.97    5165 2060.75  5192.5 2062.76    5195 2062.76
#Mann= 6 ,-1 , 0
  4836.8     .07       0  4872.3      .1       0  5019.8     .07       0
  5022.5      .1       0    5023     .05       0    5027      .1       0
Bank Sta=5023,5027
XS Rating Curve= 0 ,0
Exp/Cntr=0.3,0.1

Type RM Length L Ch R = 1 ,16804   ,451,451,451
BEGIN DESCRIPTION:
Spring Creek 37.0
END DESCRIPTION:
XS GIS Cut Line= 3
      1846974.99     13960925.03        1847025.       13960675.
        1846875.     13960374.99
#Sta/Elev= 30
  4744.6 2055.02  4775.2 2055.02  4795.6 2052.34  4826.2 2050.63  4836.4 2049.57
    4867 2049.08  4907.8 2041.68  4928.2 2041.32  4948.6 2042.03    4969 2041.95
  4979.2 2042.67  4989.4 2041.04    4995 2040.94  4995.3 2040.44  4998.8 2040.44
    4999 2040.94  5002.4 2040.94    5008 2042.18  5021.9  2042.5  5052.7 2042.13
  5080.6 2042.96  5119.8 2043.26  5147.7 2044.17  5192.4 2047.58  5214.8 2049.96
  5223.2 2051.31  5253.9 2053.34    5283 2056.91  5331.8 2059.02    5335 2059.04
#Mann= 5 ,-1 , 0
  4744.6     .07       0    4995     .05       0    4999     .07       0
    5283      .1       0  5331.8     .07       0
Bank Sta=4995,4999
XS Rating Curve= 0 ,0
Exp/Cntr=0.3,0.1

Type RM Length L Ch R = 1 ,16353   ,440,440,440
BEGIN DESCRIPTION:
Spring Creek 36.0
END DESCRIPTION:
XS GIS Cut Line= 3
      1847225.01     13960974.98        1847425.       13960725.
        1847475.     13960424.97
#Sta/Elev= 30
  4679.5 2053.28  4707.5 2052.73  4729.9 2050.44  4750.7 2049.07  4771.5 2048.88
  4800.3 2045.61    4850 2041.43    4858 2039.72  4893.2 2037.17  4907.6 2036.81
    4922  2037.2  4928.4 2036.52  4942.8 2036.73  4957.2 2036.22  4971.6 2034.81
    4986 2034.86  5017.9 2033.44  5018.2 2032.94  5021.7 2032.94  5021.9 2033.44
  5032.6 2035.68  5050.3  2036.5  5093.4 2037.61  5154.2 2038.28    5172 2039.03
  5192.3 2040.53  5202.4 2041.85  5253.1 2045.57  5275.9 2048.41  5303.8 2049.45
#Mann= 3 ,-1 , 0
  4679.5     .07       0  5017.9     .05       0  5021.9     .07       0
Bank Sta=5017.9,5021.9
XS Rating Curve= 0 ,0
Exp/Cntr=0.3,0.1

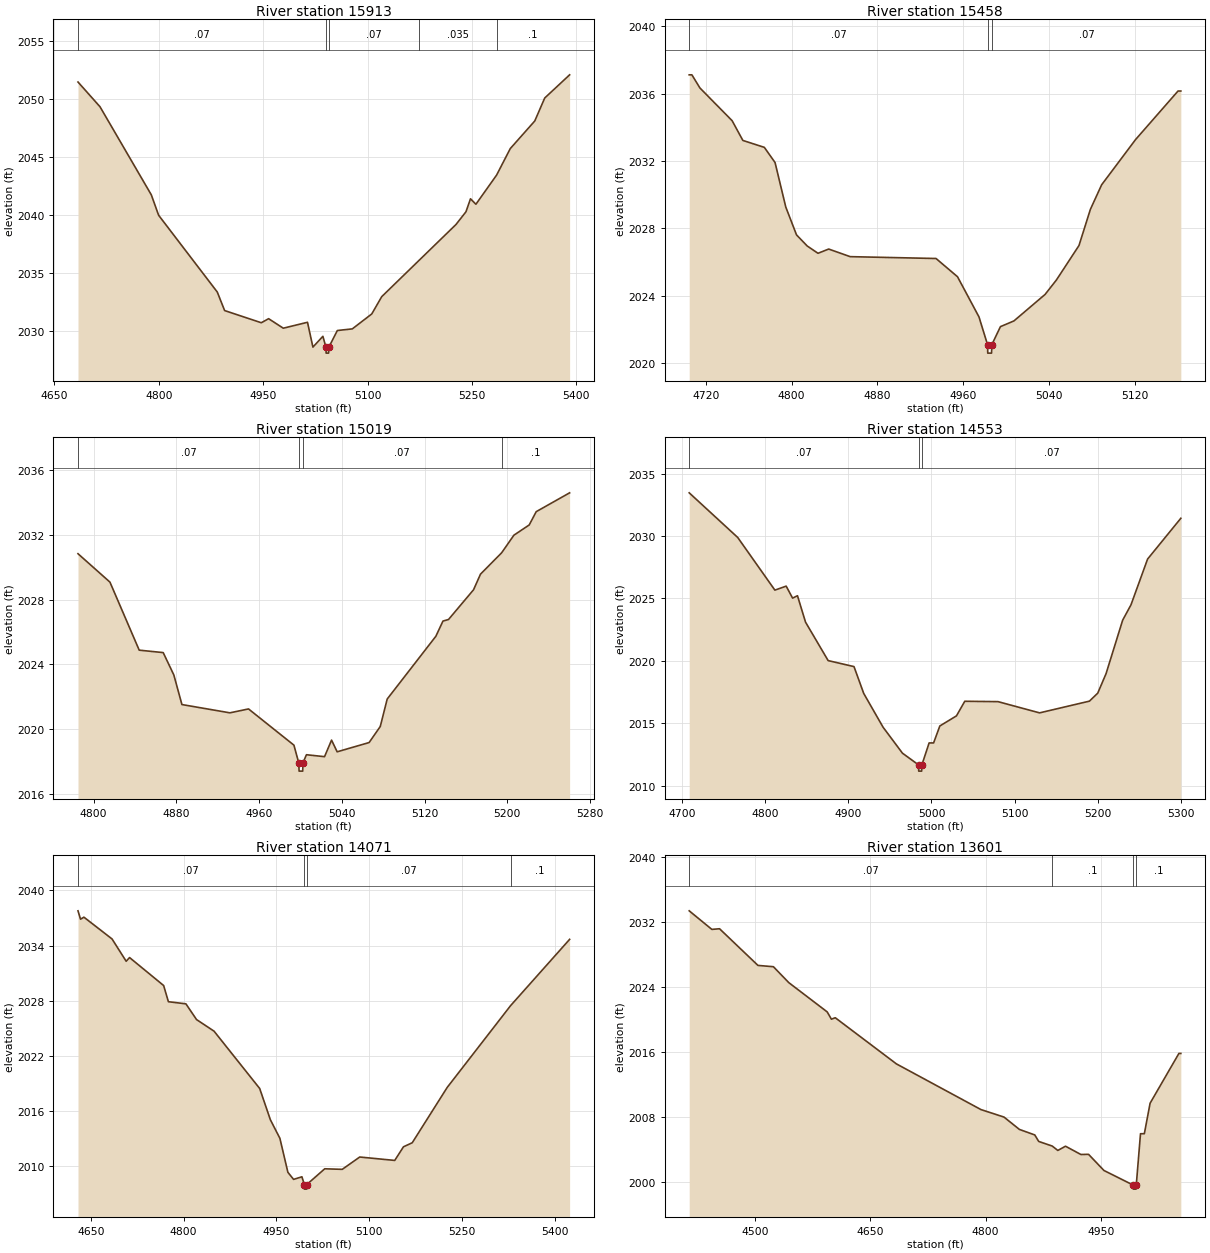
Type RM Length L Ch R = 1 ,15913   ,455,455,455
BEGIN DESCRIPTION:
Spring Creek 35.0
END DESCRIPTION:
XS GIS Cut Line= 3
      1847425.04     13961124.99        1847725.       13961025.
        1848025.       13960775.
#Sta/Elev= 30
  4683.8 2051.46  4715.4 2049.33  4789.2 2041.73  4799.7 2039.97    4884 2033.35
  4894.6 2031.75  4947.3  2030.7  4957.8 2031.05  4978.9 2030.23  5013.7 2030.74
  5021.5  2028.6  5035.8 2029.53  5040.3 2028.58  5040.5 2028.08    5044 2028.08
  5044.3 2028.58  5056.6 2030.03  5078.1 2030.17  5106.1 2031.46  5120.4 2032.95
  5173.4 2036.04  5227.1 2039.17  5241.5 2040.27    5248 2041.39  5255.8 2040.92
  5285.5 2043.43  5305.2 2045.72  5340.4  2048.1  5354.7 2050.08  5390.5 2052.08
#Mann= 5 ,-1 , 0
  4683.8     .07       0  5040.3     .05       0  5044.3     .07       0
  5173.4    .035       0  5285.5      .1       0
Bank Sta=5040.3,5044.3
XS Rating Curve= 0 ,0
Exp/Cntr=0.3,0.1

Type RM Length L Ch R = 1 ,15458   ,439,439,439
BEGIN DESCRIPTION:
Spring Creek 34.0
END DESCRIPTION:
XS GIS Cut Line= 3
      1847575.02       13961425.        1847875.       13961425.
      1848025.01       13961375.
#Sta/Elev= 30
  4704.6 2037.11  4707.1 2037.11  4714.6 2036.33  4744.6 2034.39  4754.6 2033.22
  4774.6 2032.81  4784.6 2031.91  4794.6 2029.27  4804.6 2027.62  4814.6 2026.96
  4824.6 2026.53  4834.6 2026.78  4854.6 2026.33  4934.6 2026.22  4954.6 2025.14
  4974.6 2022.76  4982.6 2021.11  4982.8 2020.61  4986.3 2020.61  4986.6 2021.11
  4994.6 2022.18  5007.2 2022.52  5036.2 2024.09  5046.7 2024.94  5067.8 2026.99
  5078.4 2029.13  5088.9 2030.59  5120.5 2033.27  5160.1 2036.15  5162.7 2036.15
#Mann= 3 ,-1 , 0
  4704.6     .07       0  4982.6     .05       0  4986.6     .07       0
Bank Sta=4982.6,4986.6
XS Rating Curve= 0 ,0
Exp/Cntr=0.3,0.1

Type RM Length L Ch R = 1 ,15019   ,466,466,466
BEGIN DESCRIPTION:
Spring Creek 33.0
END DESCRIPTION:
XS GIS Cut Line= 3
      1847625.03     13961775.01        1847825.       13961825.
      1848075.02     13961724.99
#Sta/Elev= 30
  4784.9 2030.82  4815.8 2029.07  4844.1 2024.88  4867.3 2024.73  4877.6 2023.35
  4885.4 2021.53  4931.8 2021.02  4949.8 2021.26  4993.7 2019.03  4998.4 2017.93
  4998.7 2017.43  5002.2 2017.43  5002.4 2017.93  5005.8 2018.44  5023.3 2018.32
  5030.1 2019.34  5035.5 2018.62  5066.4 2019.19  5077.2 2020.18  5083.9 2021.87
    5131 2025.74  5137.8 2026.67  5143.2 2026.77  5167.4  2028.6  5174.1 2029.56
  5194.6 2030.88  5206.4 2031.96  5221.2 2032.59    5228 2033.41  5260.3 2034.57
#Mann= 4 ,-1 , 0
  4784.9     .07       0  4998.4     .05       0  5002.4     .07       0
  5194.6      .1       0
Bank Sta=4998.4,5002.4
XS Rating Curve= 0 ,0
Exp/Cntr=0.3,0.1

Type RM Length L Ch R = 1 ,14553   ,482,482,482
BEGIN DESCRIPTION:
Spring Creek 32.0
END DESCRIPTION:
XS GIS Cut Line= 3
      1847474.96     13962375.02        1847725.       13962225.
      1848025.01       13962225.
#Sta/Elev= 30
  4708.5 2033.47  4766.9 2029.89  4811.6 2025.67  4825.2 2025.99  4832.9 2025.03
  4838.8 2025.22  4848.5  2023.1  4875.7 2020.02  4906.8 2019.54  4918.5 2017.39
  4941.8 2014.68  4965.1  2012.6  4984.5 2011.66  4984.7 2011.16  4988.2 2011.16
  4988.5 2011.66  4997.2 2013.42  5002.6 2013.42  5010.1 2014.78  5030.1 2015.59
  5040.1 2016.76  5080.1 2016.73  5130.1 2015.83  5190.1 2016.77  5200.1 2017.41
  5210.1 2018.97  5230.1 2023.26  5240.1 2024.49  5260.1 2028.16  5300.1 2031.43
#Mann= 3 ,-1 , 0
  4708.5     .07       0  4984.5     .05       0  4988.5     .07       0
Bank Sta=4984.5,4988.5
XS Rating Curve= 0 ,0
Exp/Cntr=0.3,0.1

Type RM Length L Ch R = 1 ,14071   ,470,470,470
BEGIN DESCRIPTION:
Spring Creek 31.0
END DESCRIPTION:
XS GIS Cut Line= 3
      1847489.76     13962833.35        1847825.       13962675.
      1848124.98     13962375.02
#Sta/Elev= 30
  4629.3 2037.78  4633.4 2036.87  4638.9 2037.09  4684.4 2034.72  4707.2  2032.3
  4712.7  2032.7  4767.8 2029.66  4775.5  2027.9  4803.8 2027.67    4821 2025.96
  4849.3  2024.7  4923.1 2018.47  4940.4 2015.07  4955.8 2013.05  4968.7 2009.36
  4977.9 2008.59  4991.4 2008.87  4995.3 2008.03  4995.5 2007.53    4999 2007.53
  4999.3 2008.03  5028.3 2009.74  5056.6 2009.68  5084.9 2011.02  5141.5 2010.65
  5155.6 2012.13  5169.8 2012.57  5226.3 2018.58  5328.8 2027.47  5424.3 2034.68
#Mann= 4 ,-1 , 0
  4629.3     .07       0  4995.3     .05       0  4999.3     .07       0
  5328.8      .1       0
Bank Sta=4995.3,4999.3
XS Rating Curve= 0 ,0
Exp/Cntr=0.3,0.1

Type RM Length L Ch R = 1 ,13601   ,430,430,430
BEGIN DESCRIPTION:
Spring Creek 30.0
END DESCRIPTION:
XS GIS Cut Line= 3
      1847535.52     13963046.88        1848125.       13963025.
      1848175.02       13963025.
#Sta/Elev= 30
  4414.3 2033.41  4443.8 2031.12  4453.8  2031.2  4503.8 2026.68  4523.9 2026.52
  4543.9 2024.56  4593.9 2020.95  4599.4 2020.05  4604.4 2020.23    4684 2014.54
    4794 2008.91  4824.1 2007.98  4844.1 2006.46  4864.1 2005.78  4869.2 2004.98
  4886.8 2004.41  4894.1 2003.87  4904.1 2004.39  4924.1 2003.37  4934.1 2003.39
  4954.1  2001.4  4992.2  1999.6  4992.4  1999.1  4995.9  1999.1  4996.2  1999.6
  5001.7 2005.93  5006.7 2005.93  5014.2 2009.69  5051.7 2015.83  5054.2 2015.83
#Mann= 4 ,-1 , 0
  4414.3     .07       0  4886.8      .1       0  4992.2     .05       0
  4996.2      .1       0
Bank Sta=4992.2,4996.2
XS Rating Curve= 0 ,0
Exp/Cntr=0.3,0.1

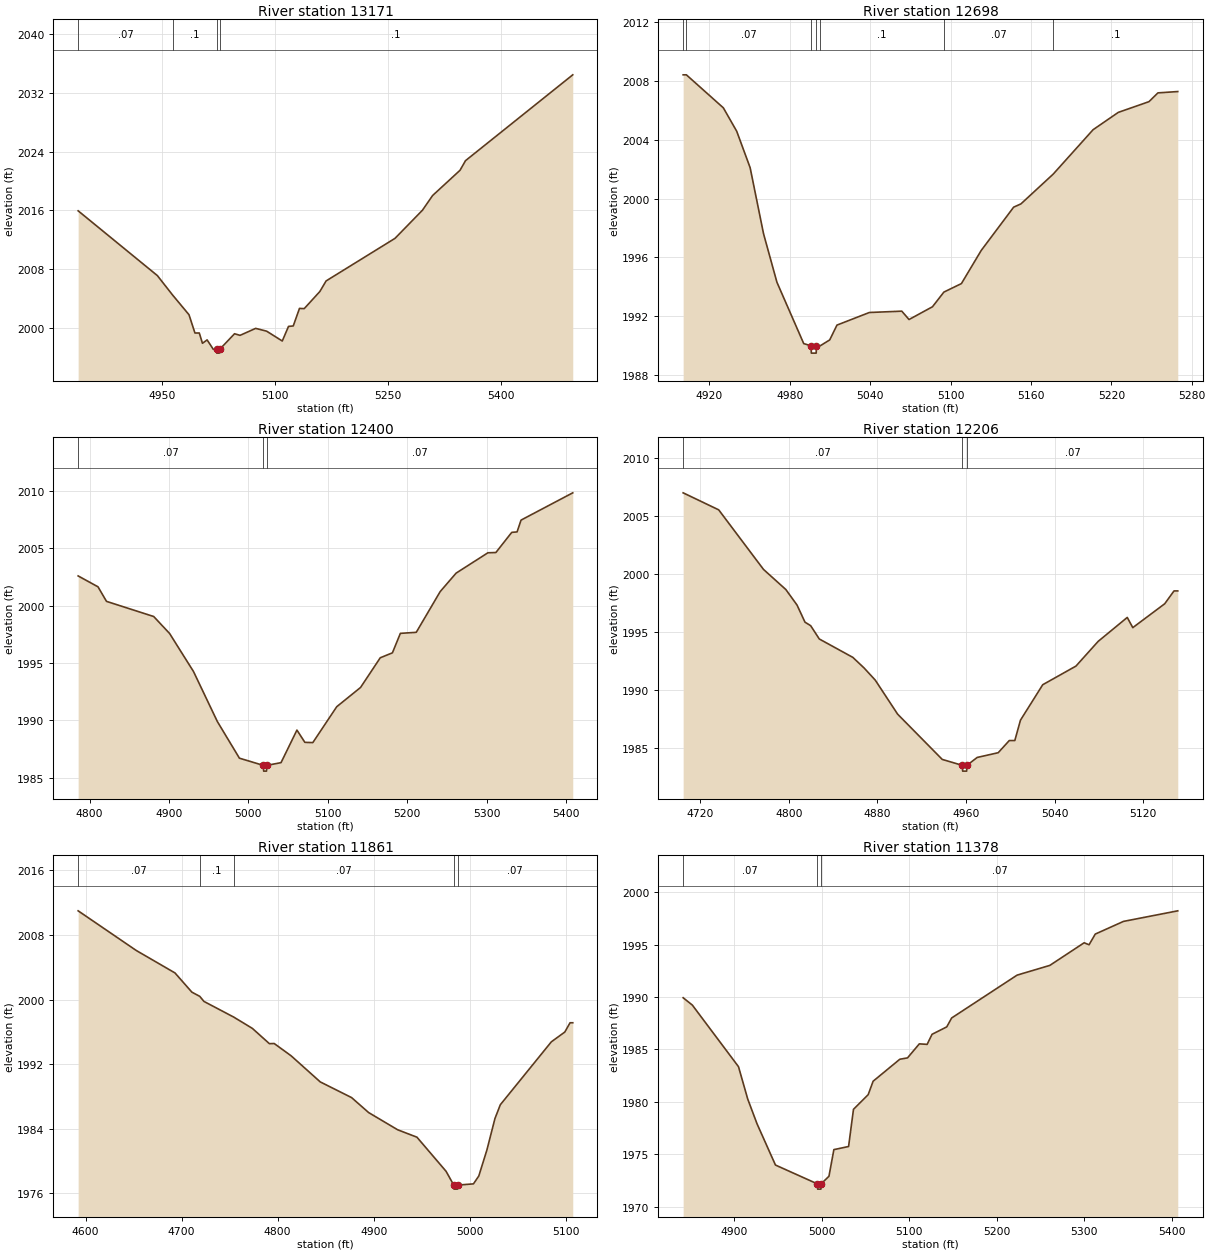
Type RM Length L Ch R = 1 ,13171   ,473,473,473
BEGIN DESCRIPTION:
Spring Creek 29.0
END DESCRIPTION:
XS GIS Cut Line= 3
      1847875.05     13963474.98        1848025.       13963425.
      1848425.03     13963124.98
#Sta/Elev= 30
    4838 2015.94  4943.4 2007.12  4963.7 2004.47  4985.5 2001.79  4993.4  1999.3
  4999.2  1999.3  5003.4  1997.9  5009.6 1998.36  5017.9 1997.07  5022.1 1997.06
  5022.4 1996.56  5025.9 1996.56  5026.2 1997.06  5046.1  1999.2  5053.4 1998.98
  5074.2 1999.93  5088.8 1999.55  5109.6 1998.21  5117.9  2000.2  5124.2 2000.26
  5132.5 2002.65  5138.8 2002.62  5159.6 2004.95  5167.9 2006.39  5259.6 2012.19
  5296.1 2016.02  5309.6 2018.02  5346.1 2021.46  5353.4 2022.77  5496.1 2034.46
#Mann= 4 ,-1 , 0
    4838     .07       0  4963.7      .1       0  5022.1     .05       0
  5026.2      .1       0
Bank Sta=5022.1,5026.2
XS Rating Curve= 0 ,0
Exp/Cntr=0.3,0.1

Type RM Length L Ch R = 1 ,12698   ,298,298,298
BEGIN DESCRIPTION:
Spring Creek 28.0
END DESCRIPTION:
XS GIS Cut Line= 3
      1848125.03       13963825.        1848225.       13963825.
      1848324.99     13963575.02
#Sta/Elev= 30
  4900.4 2008.43  4902.8 2008.43  4930.4 2006.18  4940.4 2004.58  4950.4  2002.1
  4960.4  1997.6  4970.4 1994.29  4990.4 1990.11  4995.8 1989.96  4996.1 1989.46
  4999.7 1989.46  4999.9 1989.96  5002.7 1989.96  5009.8 1990.36  5015.2 1991.37
  5039.4 1992.23  5063.6 1992.32    5069 1991.75  5086.5 1992.62    5095 1993.62
  5108.1  1994.2  5122.9 1996.46  5147.1 1999.41  5152.5 1999.63  5176.6 2001.66
  5206.4 2004.69  5225.2 2005.87  5248.1  2006.6  5254.8  2007.2  5269.6 2007.29
#Mann= 7 ,-1 , 0
  4900.4      .1       0  4902.8     .07       0  4995.8     .05       0
  4999.9     .07       0  5002.7      .1       0    5095     .07       0
  5176.6      .1       0
Bank Sta=4995.8,4999.9
XS Rating Curve= 0 ,0
Exp/Cntr=0.3,0.1

Type RM Length L Ch R = 1 ,12400   ,194,194,194
BEGIN DESCRIPTION:
Spring Creek 27.1
END DESCRIPTION:
XS GIS Cut Line= 2
      1848260.06     13963981.81      1848881.63     13963946.07
#Sta/Elev= 30
  4785.7 2002.59  4810.7 2001.64  4821.4 2000.37  4880.8 1999.05  4900.8 1997.57
  4930.9 1994.25  4960.9 1989.89  4988.7 1986.69  5018.9 1986.06  5019.2 1985.56
  5022.8 1985.56  5023.1 1986.06  5041.1  1986.3  5061.1 1989.14  5071.1 1988.07
  5081.1 1988.05  5111.2 1991.18  5141.2 1992.86    5166 1995.45  5181.3 1995.88
  5191.3 1997.58  5211.3 1997.67  5241.4 2001.22  5261.4 2002.83  5301.5 2004.61
  5311.5 2004.63  5331.5 2006.39  5338.2 2006.43  5343.2 2007.46  5408.3 2009.84
#Mann= 3 ,-1 , 0
  4785.7     .07       0  5018.9     .05       0  5023.1     .07       0
Bank Sta=5018.9,5023.1
XS Rating Curve= 0 ,0
Exp/Cntr=0.3,0.1

Type RM Length L Ch R = 1 ,12206   ,345,345,345
BEGIN DESCRIPTION:
Spring Creek 27.0
END DESCRIPTION:
XS GIS Cut Line= 3
      1848353.18     13964085.03      1848649.89     13964044.93
       1848796.8     13964052.19
#Sta/Elev= 30
  4704.7    2007  4736.8 2005.53  4777.2 2000.39  4797.4 1998.65  4807.5 1997.31
  4814.7 1995.83  4819.8 1995.53  4827.6 1994.38  4857.9 1992.79    4868 1991.88
  4878.1 1990.83  4898.3 1987.89  4938.6 1983.98  4956.7 1983.47    4957 1982.97
  4960.6 1982.97  4960.9 1983.47  4970.1 1984.15  4989.1 1984.56  4999.1 1985.61
  5004.1 1985.61  5009.2 1987.37  5029.3 1990.43  5059.3 1992.04  5079.3 1994.17
  5105.6 1996.24  5110.6 1995.36  5139.4 1997.42  5147.8 1998.53  5151.2 1998.53
#Mann= 3 ,-1 , 0
  4704.7     .07       0  4956.7     .05       0  4960.9     .07       0
Bank Sta=4956.7,4960.9
XS Rating Curve= 0 ,0
Exp/Cntr=0.3,0.1

Type RM Length L Ch R = 1 ,11861   ,483,483,483
BEGIN DESCRIPTION:
Spring Creek 26.0
END DESCRIPTION:
XS GIS Cut Line= 3
      1848424.98       13964375.        1848825.       13964325.
      1848924.97     13964275.02
#Sta/Elev= 30
  4592.3 2010.98  4652.8 2006.07  4693.1 2003.29  4710.7 2000.91  4718.9 2000.39
  4723.3 1999.76  4754.3 1997.82  4773.7 1996.42  4791.4 1994.53  4796.4 1994.55
    4814 1993.03  4844.3  1989.8    4877 1987.85  4894.7    1986  4924.9 1983.87
    4945 1982.95  4975.3 1978.73  4983.3 1977.02  4983.6 1976.52  4987.2 1976.52
  4987.5 1977.02  5003.8 1977.17  5009.4 1978.15  5017.8 1981.36  5026.2 1985.26
  5031.8 1986.97  5084.9 1994.76  5098.9 1995.97  5104.4 1997.12  5107.2 1997.12
#Mann= 5 ,-1 , 0
  4592.3     .07       0  4718.9      .1       0  4754.3     .07       0
  4983.3     .05       0  4987.5     .07       0
Bank Sta=4983.3,4987.5
XS Rating Curve= 0 ,0
Exp/Cntr=0.3,0.1

Type RM Length L Ch R = 1 ,11378   ,240,240,240
BEGIN DESCRIPTION:
Spring Creek 25.0
END DESCRIPTION:
XS GIS Cut Line= 3
      1848775.05     13964824.98        1848925.       13964775.
      1849105.62     13964410.57
#Sta/Elev= 30
  4841.9 1989.93  4852.4 1989.23  4905.1 1983.35  4915.6 1980.27  4926.2 1977.91
  4947.3 1973.96  4995.2 1972.16  4995.5 1971.66  4999.2 1971.66  4999.4 1972.16
  5008.4 1972.89    5014 1975.43  5030.8 1975.73  5036.4 1979.28  5053.2 1980.68
  5058.8 1981.96  5089.3 1984.06  5098.1 1984.19  5111.6 1985.53  5120.5 1985.48
  5126.1 1986.44  5142.9 1987.15  5148.5    1988  5223.2 1992.09  5260.6 1993.02
  5299.8 1995.18  5305.4 1994.99  5312.5 1996.01  5344.7 1997.22  5406.7 1998.23
#Mann= 3 ,-1 , 0
  4841.9     .07       0  4995.2     .05       0  4999.4     .07       0
Bank Sta=4995.2,4999.4
XS Rating Curve= 0 ,0
Exp/Cntr=0.3,0.1

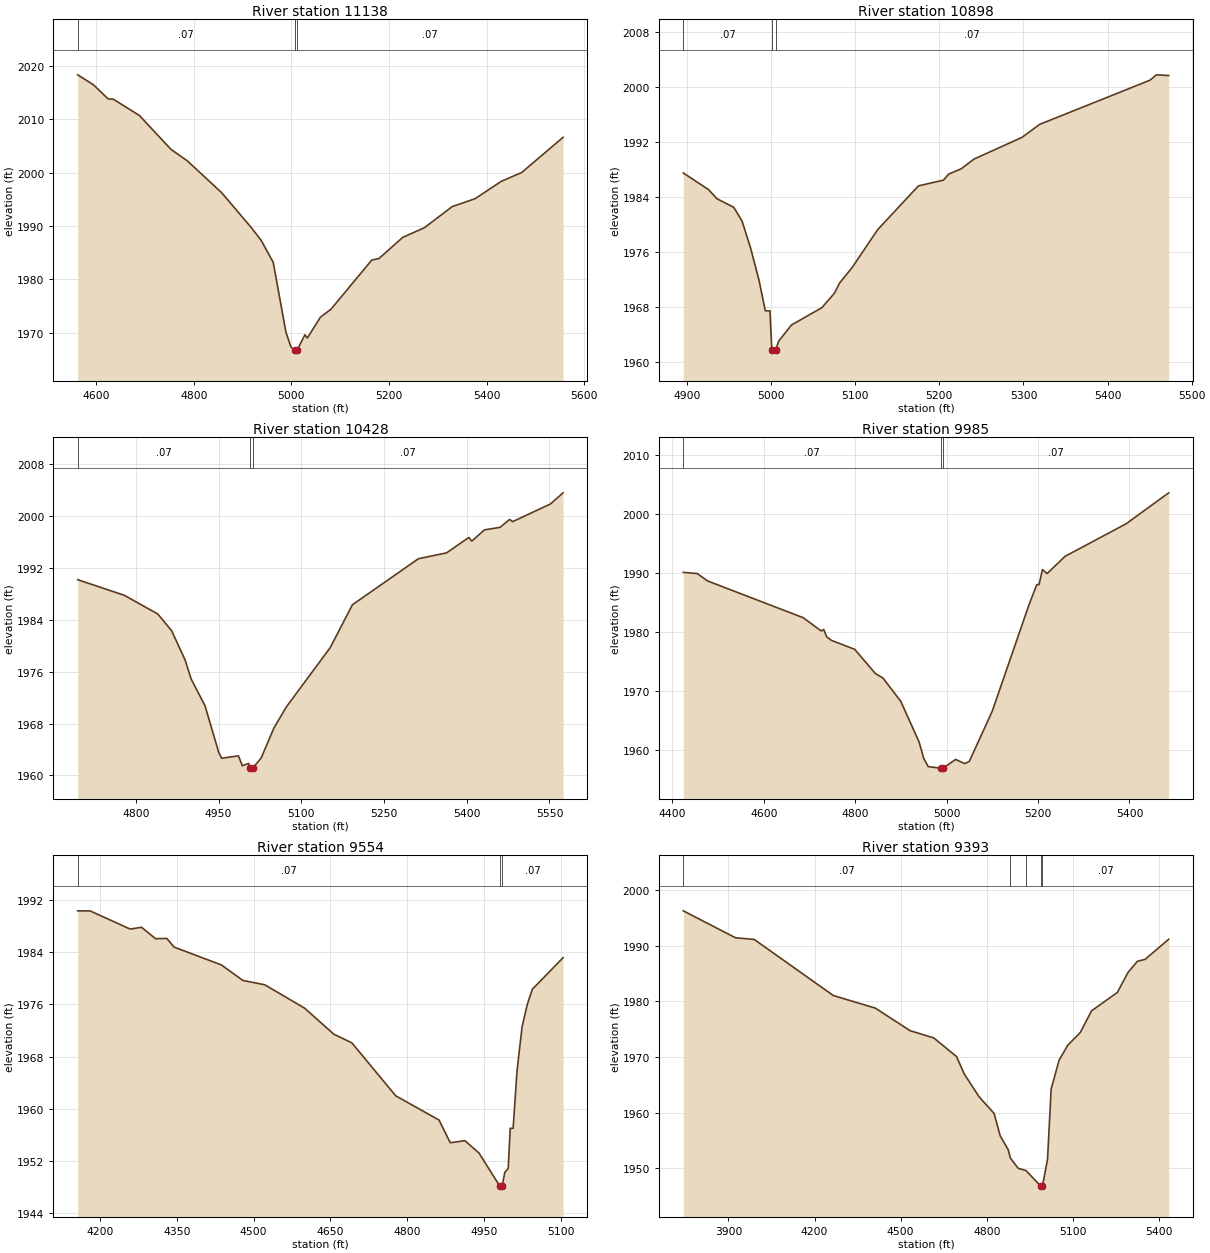
Type RM Length L Ch R = 1 ,11138   ,240,240,240
BEGIN DESCRIPTION:
Mapping XS 8304a54b
END DESCRIPTION:
XS GIS Cut Line= 3
      1848493.15     13965078.07      1849001.86     13965003.42
      1849454.95     13964845.44
#Sta/Elev= 30
  4562.4 2018.38  4594.6 2016.52  4624.9 2013.85    4635 2013.83  4688.7 2010.76
  4753.5 2004.39  4786.6 2002.26  4857.4 1996.25    4918  1989.7  4938.2 1987.31
  4962.9 1983.17  4988.8  1970.1  4998.9 1967.36  5006.7 1966.65    5007 1966.15
    5011 1966.15  5011.3 1966.65  5027.7 1969.59  5032.7 1968.99  5059.5  1972.9
  5080.9 1974.37  5164.6 1983.61  5179.3  1983.9  5228.2 1987.88  5272.5 1989.69
  5329.4 1993.65  5376.4 1995.14  5429.4 1998.37  5471.7 2000.05  5556.4 2006.65
#Mann= 3 ,-1 , 0
  4562.4     .07       0  5006.7     .05       0  5011.3     .07       0
Bank Sta=5006.7,5011.3
XS Rating Curve= 0 ,0
Exp/Cntr=0.3,0.1

Type RM Length L Ch R = 1 ,10898   ,470,470,470
BEGIN DESCRIPTION:
Spring Creek 24.0
END DESCRIPTION:
XS GIS Cut Line= 3
      1848925.01       13965225.        1849025.       13965225.
      1849423.58     13964962.77
#Sta/Elev= 30
  4895.6 1987.53  4925.6  1985.1  4935.6 1983.77  4955.6 1982.52  4965.6 1980.47
  4975.6 1976.59  4985.6  1971.9  4993.1 1967.44  4998.6 1967.44  5000.8 1961.78
  5001.1 1961.28  5005.1 1961.28  5005.4 1961.78  5009.1 1963.05  5024.2 1965.38
  5060.3  1967.9  5075.4 1970.03  5081.4 1971.49  5096.5 1973.78  5126.7 1979.27
  5175.1 1985.64  5204.9 1986.48  5211.1 1987.36    5226 1988.13  5241.1 1989.54
  5298.3 1992.71  5319.4 1994.61  5450.5 2001.04    5458 2001.82  5472.7 2001.72
#Mann= 3 ,-1 , 0
  4895.6     .07       0  5000.8     .05       0  5005.4     .07       0
Bank Sta=5000.8,5005.4
XS Rating Curve= 0 ,0
Exp/Cntr=0.3,0.1

Type RM Length L Ch R = 1 ,10428   ,443,443,443
BEGIN DESCRIPTION:
Spring Creek 23.0
END DESCRIPTION:
XS GIS Cut Line= 3
      1849042.79     13965680.44        1849325.       13965575.
      1849849.53     13965329.75
#Sta/Elev= 30
  4694.4 1990.18  4779.1 1987.77  4839.7 1984.89  4864.7 1982.33  4888.9 1977.87
  4900.3 1974.85  4925.3 1970.76  4950.2 1963.56  4955.6 1962.66  4985.9 1963.03
    4993  1961.5  5004.3 1961.86  5007.5 1961.17  5007.8 1960.67  5012.2 1961.17
  5027.2  1962.7    5050 1967.27  5072.9 1970.58  5152.4 1979.71  5192.6 1986.31
  5312.3 1993.41  5363.5 1994.32  5403.7 1996.69  5409.2 1996.13  5432.1 1997.86
  5460.4 1998.25  5477.8 1999.47  5483.3 1999.13  5551.8 2001.85  5574.7 2003.57
#Mann= 3 ,-1 , 0
  4694.4     .07       0  5007.5     .05       0  5012.2     .07       0
Bank Sta=5007.5,5012.2
XS Rating Curve= 0 ,0
Exp/Cntr=0.3,0.1

Type RM Length L Ch R = 1 ,9985    ,431,431,431
BEGIN DESCRIPTION:
Spring Creek 22.0
END DESCRIPTION:
XS GIS Cut Line= 5
      1849042.44     13965736.79      1849431.66       13965925.
        1849575.       13965925.        1849775.       13965925.
      1850060.23     13965902.44
#Sta/Elev= 30
    4424 1990.11  4454.5 1989.91  4477.1 1988.66    4686 1982.45  4725.6  1980.2
  4731.2 1980.44  4737.9 1979.18  4748.2  1978.6  4798.9 1977.09  4844.1    1973
  4860.5 1972.25  4899.7 1968.29  4939.7 1961.43  4949.7 1958.69  4959.7 1957.24
  4987.3 1956.98  4987.6 1956.48  4992.1 1956.98  5019.7 1958.46  5039.7 1957.75
  5049.7 1958.14  5099.7  1966.6  5179.7 1984.51  5197.2 1988.04  5202.2 1988.04
  5209.7 1990.59  5219.7  1989.9    5259 1992.82  5392.6 1998.33  5485.8 2003.57
#Mann= 3 ,-1 , 0
    4424     .07       0  4987.3     .05       0  4992.1     .07       0
Bank Sta=4987.3,4992.1
XS Rating Curve= 0 ,0
Exp/Cntr=0.3,0.1

Type RM Length L Ch R = 1 ,9554    ,161,161,161
BEGIN DESCRIPTION:
Spring Creek 21.0
END DESCRIPTION:
XS GIS Cut Line= 3
      1849029.25     13965775.74        1849675.       13966325.
      1849774.95       13966325.
#Sta/Elev= 30
  4156.6 1990.35  4181.2 1990.33  4259.2 1987.55  4281.2 1987.83  4308.6 1986.08
  4330.6 1986.12  4344.9 1984.79  4437.1 1982.06  4479.2 1979.68  4521.7 1979.02
  4599.6 1975.44  4656.8 1971.44  4691.9 1970.12  4777.6    1962  4862.1 1958.29
  4884.1  1954.8  4912.5 1955.13  4940.1 1953.24  4980.5  1948.2  4980.9  1947.7
  4985.3  1948.2  4990.6 1950.28  4997.2 1950.87  5001.1 1957.02  5006.8 1957.02
  5014.3 1965.73  5024.3 1972.59  5034.3 1975.97  5044.3 1978.33  5104.3 1983.17
#Mann= 3 ,-1 , 0
  4156.6     .07       0  4980.5     .05       0  4985.3     .07       0
Bank Sta=4980.5,4985.3
XS Rating Curve= 0 ,0
Exp/Cntr=0.3,0.1

Type RM Length L Ch R = 1 ,9393    ,293,293,293
BEGIN DESCRIPTION:
Mapping XS 27bb91d0
END DESCRIPTION:
XS GIS Cut Line= 4
      1848515.61     13965823.57      1849508.64     13966445.08
      1849706.55     13966472.86      1850011.07     13966375.97
#Sta/Elev= 30
  3742.9 1996.27  3924.8 1991.43  3989.9 1991.13  4265.5 1981.06  4411.7  1978.8
  4533.2 1974.74  4615.2 1973.45  4694.7  1970.1  4721.8 1966.95  4773.6 1962.85
  4825.5 1959.89  4846.7 1955.88  4874.7 1953.37  4882.3 1951.88  4909.6 1950.02
  4936.2 1949.64  4989.1 1946.79  4989.4 1946.29  4993.9 1946.79  5011.7 1951.65
  5024.3 1964.27  5052.1 1969.46  5082.4 1972.15    5126 1974.43  5165.1 1978.32
  5254.9 1981.61  5292.4 1985.23  5324.6  1987.2  5351.6 1987.56  5433.8 1991.17
#Mann= 5 ,-1 , 0
  3742.9     .07       0  4882.3    .035       0  4936.2     .07       0
  4989.1     .05       0  4993.9     .07       0
Bank Sta=4989.1,4993.9
XS Rating Curve= 0 ,0
Exp/Cntr=0.3,0.1