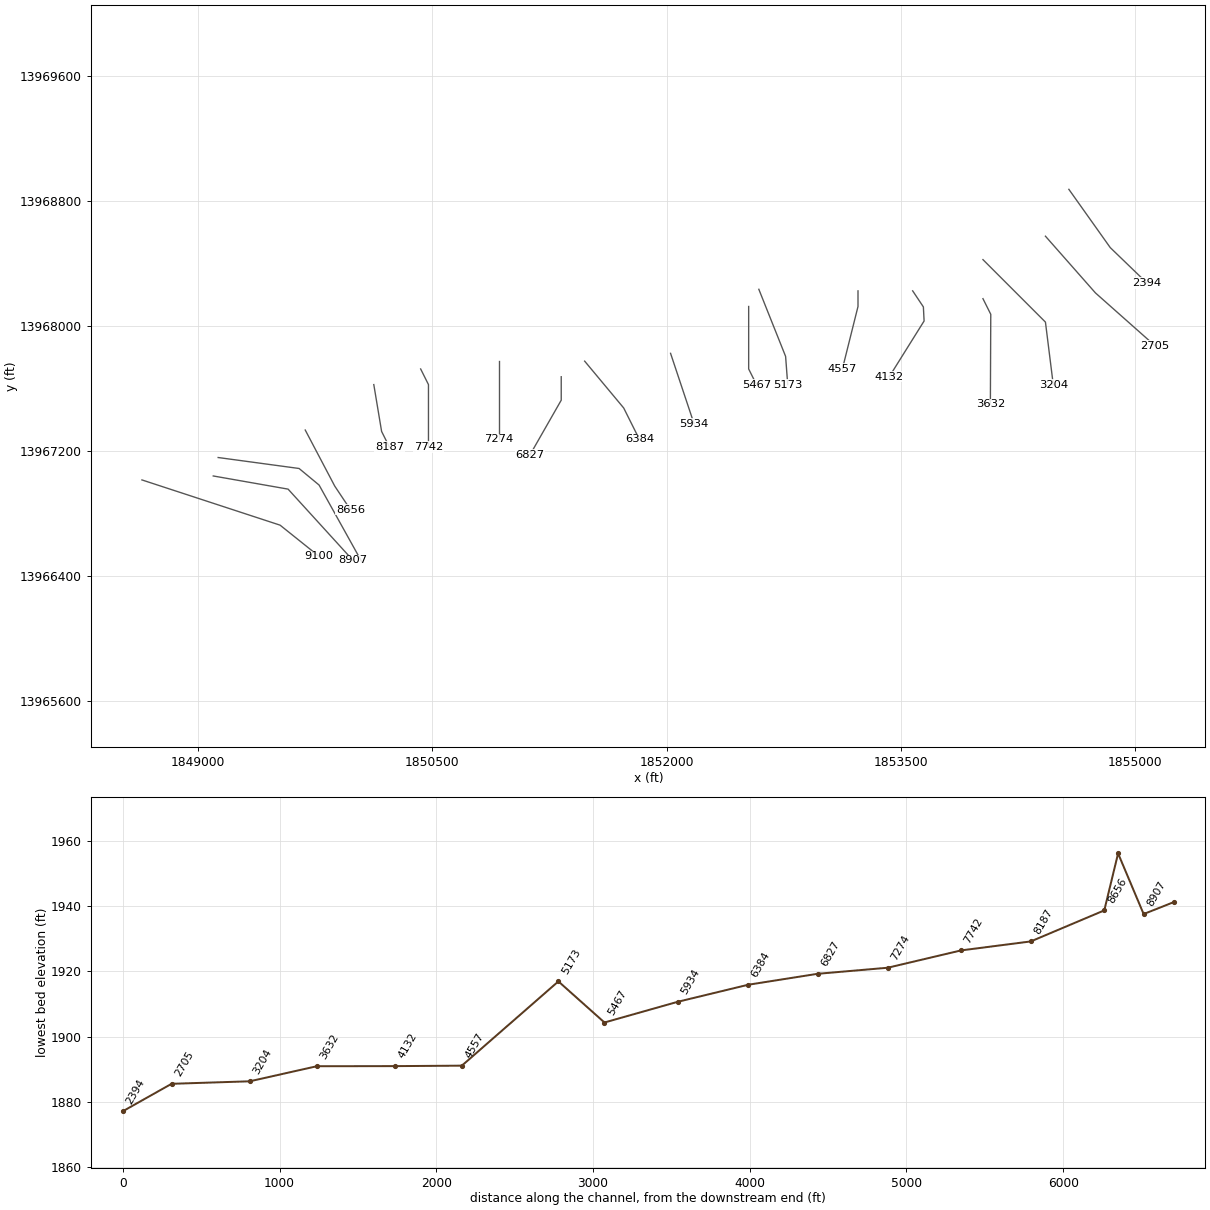
HEC-RAS study Spring Creek.prj: Spring Creek_US Base Level Engineering

--- Spring Creek.g01 (geometry) --- (continued)

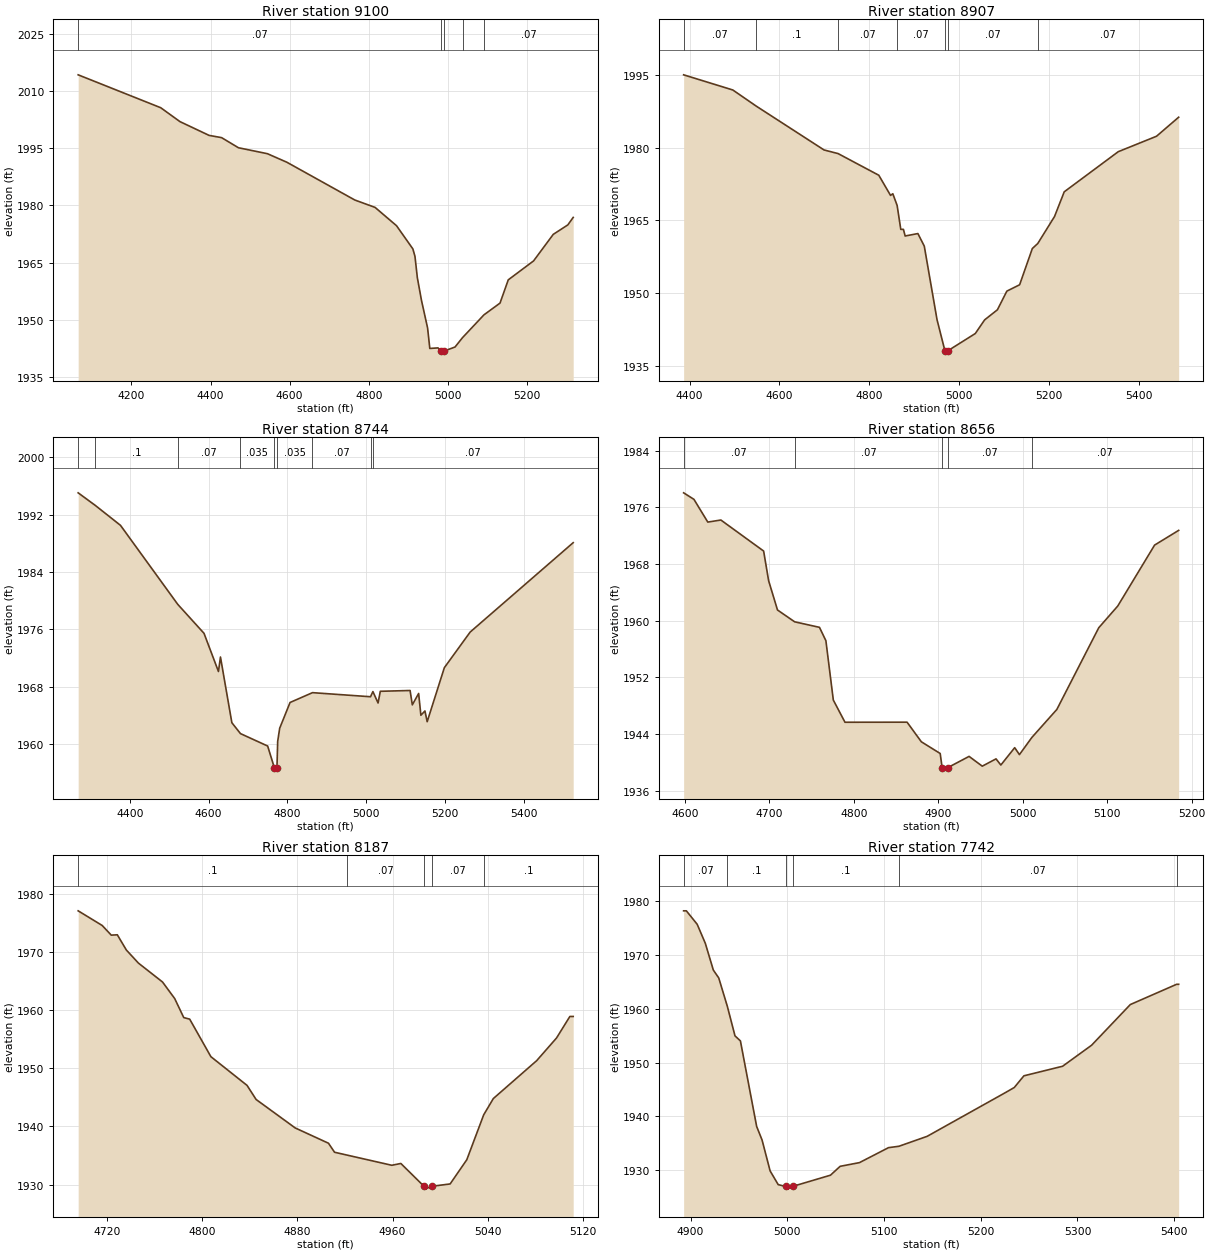
Type RM Length L Ch R = 1 ,9100    ,193,193,193
BEGIN DESCRIPTION:
Spring Creek 20.0
END DESCRIPTION:
XS GIS Cut Line= 3
      1848640.55     13967014.54        1849525.       13966725.
      1849775.01     13966524.99
#Sta/Elev= 30
  4065.6 2014.23  4274.2 2005.61  4322.8 2001.97  4396.4 1998.36    4428 1997.77
  4470.6 1995.12  4543.8 1993.56  4592.8 1991.33  4764.7 1981.42  4815.8 1979.49
    4870 1974.69  4911.3 1968.61  4916.6 1966.66  4922.6 1961.07  4933.1  1955.1
  4948.5 1947.89  4954.1 1942.53    4975 1942.67  4982.3  1941.8  4982.8  1941.3
  4989.1  1941.8  5017.8  1942.9  5036.7 1945.35  5090.9 1951.33  5131.5 1954.41
  5152.3  1960.5  5216.3 1965.47    5266 1972.42  5302.8  1974.9  5316.4 1976.86
#Mann= 5 ,-1 , 0
  4065.6     .07       0  4982.3     .05       0  4989.1     .07       0
  5036.7    .035       0  5090.9     .07       0
Bank Sta=4982.3,4989.1
XS Rating Curve= 0 ,0
Exp/Cntr=0.3,0.1

Type RM Length L Ch R = 1 ,8907    ,163,163,163
BEGIN DESCRIPTION:
Mapping XS 02af6a3c
END DESCRIPTION:
XS GIS Cut Line= 3
      1849097.17     13967039.89      1849576.27     13966955.63
      1849990.64      13966500.7
#Sta/Elev= 30
  4386.7 1995.07  4496.2 1991.94  4547.8 1988.64  4699.2 1979.56  4730.5 1978.81
  4821.1 1974.34  4847.2 1970.18  4852.3 1970.52  4861.9  1968.1    4870 1963.17
  4875.9 1963.17  4879.7  1961.8  4908.1  1962.3  4922.3 1959.71  4950.7 1944.52
  4968.2 1938.12  4968.7 1937.62    4975 1938.12  5035.8 1941.66  5056.7 1944.49
  5085.1 1946.57  5106.1 1950.42  5134.5 1951.73  5162.8 1959.21  5174.9 1960.25
  5212.2 1965.82  5233.8 1970.92    5354  1979.2  5439.2 1982.39  5488.5 1986.32
#Mann= 7 ,-1 , 0
  4386.7     .07       0  4547.8      .1       0  4730.5     .07       0
  4861.9     .07       0  4968.2     .05       0    4975     .07       0
  5174.9     .07       0
Bank Sta=4968.2,4975
XS Rating Curve= 0 ,0
Exp/Cntr=0.3,0.1

Type RM Length L Ch R = 1 ,8744    ,88,88,88
BEGIN DESCRIPTION:
Mapping XS 86e2f898
END DESCRIPTION:
XS GIS Cut Line= 4
      1849128.71     13967157.96      1849646.69     13967087.78
      1849774.69     13966981.79      1850050.19     13966486.67
#Sta/Elev= 30
  4269.3 1995.04  4311.9 1993.32  4376.6 1990.51  4521.9 1979.49  4588.5 1975.45
  4625.1 1970.13  4630.2 1972.15  4659.1 1962.99    4681 1961.47  4749.9 1959.74
  4766.7 1956.74  4767.2 1956.24  4773.5 1956.74  4775.3 1960.38  4780.4 1962.22
  4806.7 1965.81  4863.6 1967.18  5010.8 1966.61  5016.8 1967.33  5029.9 1965.74
  5035.6 1967.37  5111.1 1967.48  5116.8 1965.48  5132.8 1967.07  5138.5 1964.03
  5148.8 1964.63  5154.5 1963.13    5198 1970.66  5263.5 1975.63  5524.8 1988.09
#Mann= 9 ,-1 , 0
  4269.3     .07       0  4311.9      .1       0  4521.9     .07       0
    4681    .035       0  4766.7     .05       0  4773.5    .035       0
  4863.6     .07       0  5010.8    .035       0  5016.8     .07       0
Bank Sta=4766.7,4773.5
XS Rating Curve= 0 ,0
Exp/Cntr=0.3,0.1

Type RM Length L Ch R = 1 ,8656    ,469,469,469
BEGIN DESCRIPTION:
Spring Creek 19.0
END DESCRIPTION:
XS GIS Cut Line= 3
      1849686.03     13967334.02        1849875.       13966975.
        1849975.       13966825.
#Sta/Elev= 30
  4598.6 1978.04  4610.8 1977.12  4627.2 1973.91  4642.7  1974.2  4693.3 1969.82
  4699.2 1965.64  4709.7  1961.5    4730 1959.83  4759.4 1959.05    4767 1957.16
  4775.8 1948.78  4789.6 1945.65  4863.1 1945.66    4880 1942.89  4902.3 1941.24
  4904.6 1939.25  4905.1 1938.75  4911.4 1939.25  4936.5 1940.83  4952.1 1939.45
  4968.4 1940.48  4974.1 1939.61  4990.5 1942.06  4996.1 1941.08  5010.8  1943.5
  5040.4 1947.46    5090 1958.99  5112.5 1962.06  5156.1 1970.66  5184.6 1972.74
#Mann= 5 ,-1 , 0
  4598.6     .07       0    4730     .07       0  4904.6     .05       0
  4911.4     .07       0  5010.8     .07       0
Bank Sta=4904.6,4911.4
XS Rating Curve= 0 ,0
Exp/Cntr=0.3,0.1

Type RM Length L Ch R = 1 ,8187    ,445,445,445
BEGIN DESCRIPTION:
Spring Creek 18.0
END DESCRIPTION:
XS GIS Cut Line= 3
      1850125.01     13967624.96        1850175.       13967325.
        1850225.       13967225.
#Sta/Elev= 30
  4695.9 1977.06  4716.1 1974.54  4723.7 1972.88  4728.8 1972.94  4736.4 1970.32
  4746.5 1968.08  4766.8 1964.82    4777 1961.98  4784.6 1958.71  4789.6 1958.44
  4807.4 1951.99  4837.8 1947.05  4845.4 1944.63  4878.3 1939.73  4906.2 1937.11
  4911.3 1935.56  4921.8 1935.07  4959.4 1933.32    4967 1933.63  4986.4 1929.72
  4986.9 1929.22  4993.4 1929.72  5008.4 1930.11  5022.4 1934.27  5036.6 1941.99
  5044.7 1944.79  5081.1  1951.3  5097.8  1955.2    5109  1958.9  5111.8  1958.9
#Mann= 5 ,-1 , 0
  4695.9      .1       0  4921.8     .07       0  4986.4     .05       0
  4993.4     .07       0  5036.6      .1       0
Bank Sta=4986.4,4993.4
XS Rating Curve= 0 ,0
Exp/Cntr=0.3,0.1

Type RM Length L Ch R = 1 ,7742    ,468,468,468
BEGIN DESCRIPTION:
Spring Creek 17.0
END DESCRIPTION:
XS GIS Cut Line= 3
        1850425.       13967725.        1850475.       13967625.
        1850475.       13967225.
#Sta/Elev= 30
  4892.8 1978.21  4895.6 1978.21  4906.8 1975.71  4915.2 1972.18  4923.5  1967.2
  4929.1 1965.73    4938 1960.44  4945.9 1954.96  4951.5 1954.02  4968.3 1938.11
  4973.9 1935.59  4982.2 1929.85  4990.6 1927.29  4998.3 1926.96  4998.8 1926.46
  5005.4 1926.96  5044.6 1929.05  5054.6  1930.7  5074.6 1931.39  5104.6 1934.17
  5115.4 1934.43  5144.6 1936.28  5224.6 1944.32  5234.6 1945.35  5244.6 1947.53
  5284.6 1949.31  5314.6 1953.22  5354.6 1960.78  5402.5 1964.55  5404.6 1964.55
#Mann= 6 ,-1 , 0
  4892.8     .07       0    4938      .1       0  4998.3     .05       0
  5005.4      .1       0  5115.4     .07       0  5402.5      .1       0
Bank Sta=4998.3,5005.4
XS Rating Curve= 0 ,0
Exp/Cntr=0.3,0.1

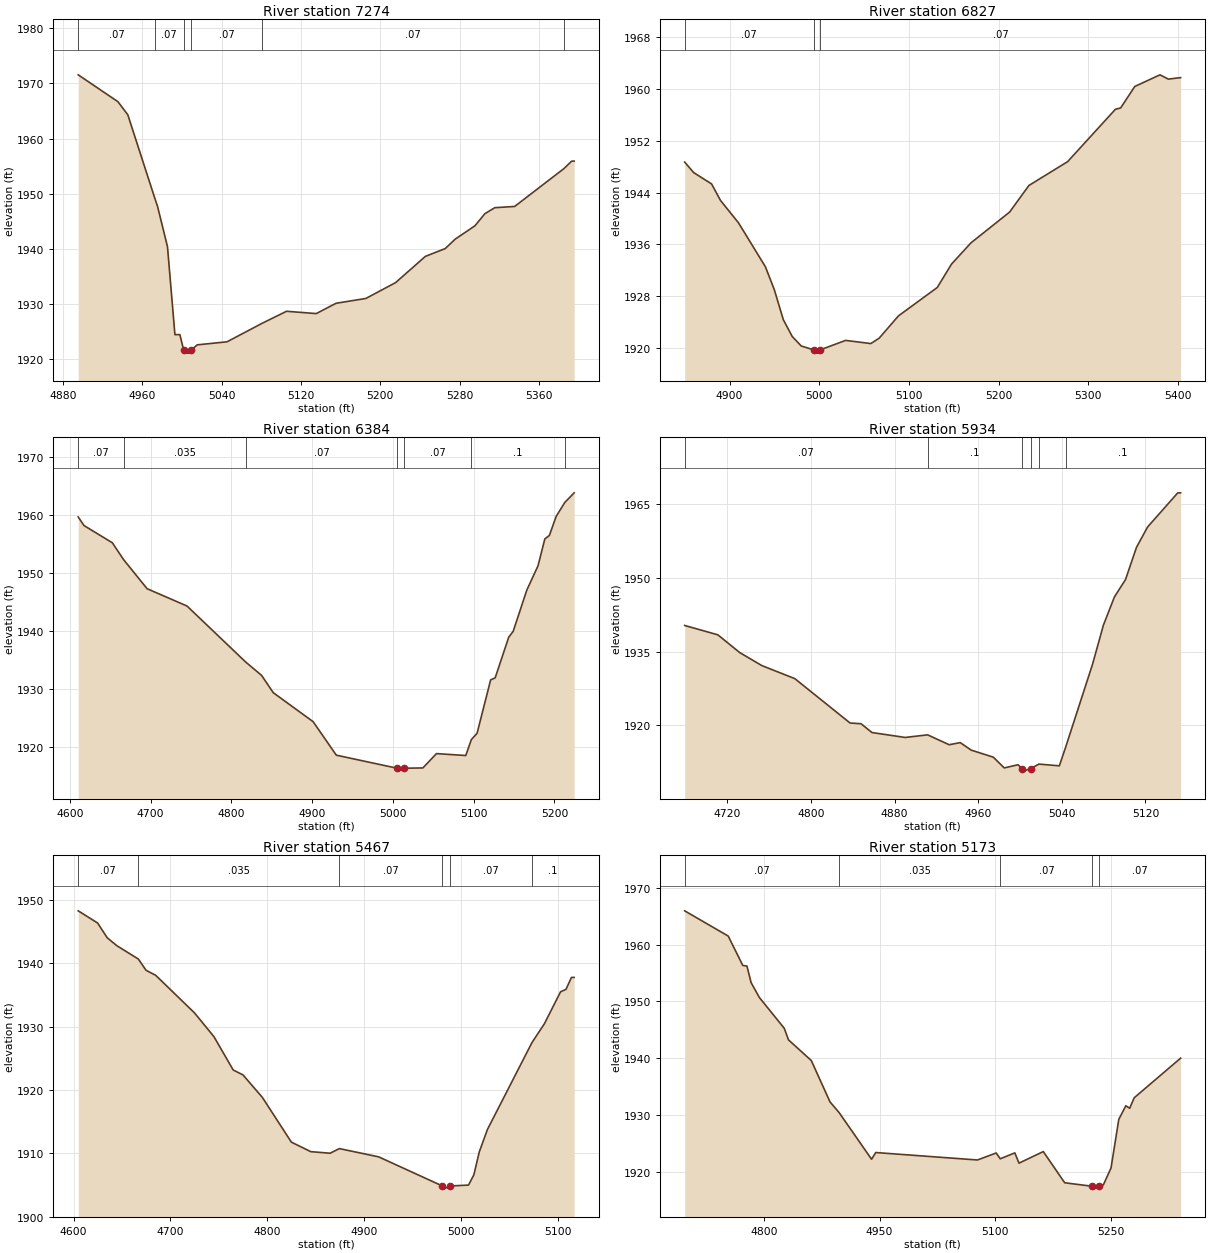
Type RM Length L Ch R = 1 ,7274    ,447,447,447
BEGIN DESCRIPTION:
Spring Creek 16.0
END DESCRIPTION:
XS GIS Cut Line= 3
        1850925.     13967775.03        1850925.       13967675.
        1850925.     13967275.03
#Sta/Elev= 30
  4895.4 1971.54  4935.4 1966.68  4945.4 1964.31  4972.4 1949.32  4975.4  1947.7
  4985.4 1940.43  4992.9 1924.49  4997.9 1924.49  5001.8 1921.64  5002.3 1921.14
  5008.5 1921.14    5009 1921.64  5015.4 1922.64  5045.4 1923.19  5080.5 1926.51
  5105.4 1928.72  5135.4  1928.3  5155.4 1930.17  5185.4 1931.04  5215.4 1933.91
  5245.4 1938.66  5265.4 1940.07  5275.4 1941.77  5295.4  1944.2  5305.4 1946.39
  5315.4 1947.48  5335.4  1947.7  5385.2 1954.57  5392.9 1955.91  5395.4 1955.91
#Mann= 6 ,-1 , 0
  4895.4     .07       0  4972.4     .07       0  5001.8     .05       0
    5009     .07       0  5080.5     .07       0  5385.2      .1       0
Bank Sta=5001.8,5009
XS Rating Curve= 0 ,0
Exp/Cntr=0.3,0.1

Type RM Length L Ch R = 1 ,6827    ,443,443,443
BEGIN DESCRIPTION:
Spring Creek 15.0
END DESCRIPTION:
XS GIS Cut Line= 3
        1851325.       13967675.        1851325.       13967525.
        1851125.     13967175.01
#Sta/Elev= 30
    4850 1948.68    4860 1947.07    4880 1945.32    4890 1942.77    4910 1939.34
    4940 1932.58    4950 1929.03    4960 1924.43    4970 1921.83    4980 1920.38
  4993.9 1919.78  4994.4 1919.28  5000.6 1919.28  5001.1 1919.78  5029.5 1921.24
  5057.6 1920.75  5066.9 1921.58  5088.5 1925.02  5131.7 1929.38  5147.6 1932.98
  5169.2 1936.24  5212.4 1940.99  5233.9 1945.08  5277.1 1948.75  5330.4 1956.81
  5336.2 1957.01    5352 1960.32  5380.1 1962.11  5389.4 1961.45  5403.1 1961.68
#Mann= 3 ,-1 , 0
    4850     .07       0  4993.9     .05       0  5001.1     .07       0
Bank Sta=4993.9,5001.1
XS Rating Curve= 0 ,0
Exp/Cntr=0.3,0.1

Type RM Length L Ch R = 1 ,6384    ,450,450,450
BEGIN DESCRIPTION:
Spring Creek 14.0
END DESCRIPTION:
XS GIS Cut Line= 3
        1851475.     13967774.99        1851725.       13967475.
      1851824.99     13967275.01
#Sta/Elev= 30
  4610.3 1959.71  4617.5 1958.23  4652.6 1955.26  4666.5 1952.36  4695.6 1947.35
    4745 1944.37  4817.5 1934.74  4837.4 1932.41  4851.8 1929.44  4901.2 1924.44
  4929.9 1918.67  5005.2 1916.42  5005.7 1915.92  5013.2 1916.42  5037.1 1916.47
  5053.9 1918.94  5090.2 1918.61  5097.1 1921.35  5104.2 1922.44    5121 1931.64
  5126.6 1931.99  5143.4    1939  5148.9    1940  5165.7 1947.08  5179.7 1951.31
  5188.1 1955.93  5193.7 1956.52  5202.1  1959.8  5212.8 1962.21  5224.4 1963.87
#Mann= 7 ,-1 , 0
  4610.3     .07       0  4666.5    .035       0  4817.5     .07       0
  5005.2     .05       0  5013.2     .07       0  5097.1      .1       0
  5212.8     .07       0
Bank Sta=5005.2,5013.2
XS Rating Curve= 0 ,0
Exp/Cntr=0.3,0.1

Type RM Length L Ch R = 1 ,5934    ,467,467,467
BEGIN DESCRIPTION:
Spring Creek 13.0
END DESCRIPTION:
XS GIS Cut Line= 3
      1852024.99     13967825.03        1852125.       13967525.
      1852175.01     13967374.98
#Sta/Elev= 30
  4679.2 1940.31  4710.9 1938.41  4731.9 1934.79    4753 1932.15  4784.6 1929.49
  4837.4 1920.47  4847.9 1920.32  4858.4 1918.53  4890.1 1917.53  4911.6 1918.06
  4932.2 1916.05  4942.8 1916.48  4953.3 1914.95  4974.4 1913.52  4984.9 1911.33
  4998.1 1911.98  5001.9 1911.18  5002.4 1910.68  5010.2 1911.18    5018 1912.11
  5037.6 1911.76  5043.7  1915.6  5069.3 1932.39  5079.8 1940.41  5090.3 1946.12
  5100.9 1949.65  5111.4 1956.21    5122 1960.34  5150.9 1967.29  5153.6 1967.29
#Mann= 6 ,-1 , 0
  4679.2     .07       0  4911.6      .1       0  5001.9     .05       0
  5010.2      .1       0    5018     .07       0  5043.7      .1       0
Bank Sta=5001.9,5010.2
XS Rating Curve= 0 ,0
Exp/Cntr=0.3,0.1

Type RM Length L Ch R = 1 ,5467    ,294,294,294
BEGIN DESCRIPTION:
Spring Creek 12.0
END DESCRIPTION:
XS GIS Cut Line= 3
        1852525.     13968124.96        1852525.       13967725.
      1852575.02     13967624.97
#Sta/Elev= 30
  4604.8 1948.29  4624.8 1946.37  4634.8 1944.02  4644.8 1942.77  4666.9 1940.67
  4674.8  1938.9  4684.8  1938.1  4724.8 1932.17  4744.8 1928.43  4764.8 1923.14
  4774.8 1922.38  4794.8 1918.83  4824.8 1911.75  4844.8 1910.25  4864.8    1910
  4874.3 1910.73  4914.8 1909.43  4980.6 1904.83  4981.1 1904.33  4988.9 1904.83
  5007.6 1904.97  5013.1 1906.59  5018.7 1910.21  5027.1 1913.75  5073.1 1927.49
  5085.8 1930.43  5102.6  1935.5  5108.2 1935.89  5113.8 1937.77  5116.6 1937.77
#Mann= 6 ,-1 , 0
  4604.8     .07       0  4666.9    .035       0  4874.3     .07       0
  4980.6     .05       0  4988.9     .07       0  5073.1      .1       0
Bank Sta=4980.6,4988.9
XS Rating Curve= 0 ,0
Exp/Cntr=0.3,0.1

Type RM Length L Ch R = 1 ,5173    ,616,616,616
BEGIN DESCRIPTION:
Spring Creek 11.0
END DESCRIPTION:
XS GIS Cut Line= 3
      1852590.07     13968235.04      1852761.51     13967805.37
        1852775.     13967624.99
#Sta/Elev= 30
  4697.1 1965.93  4753.6 1961.49  4772.5 1956.32  4777.9 1956.21  4783.3 1953.29
    4794 1950.68  4826.3 1945.26  4831.8 1943.22  4861.4 1939.58  4885.7  1932.3
  4897.4 1930.44  4939.6 1922.21    4945 1923.39    5077 1922.08  5101.3 1923.31
  5106.6 1922.29  5125.5 1923.33  5130.9 1921.52  5162.4 1923.56  5190.2 1918.07
  5226.1 1917.45  5226.6 1916.95  5234.5 1917.45  5240.3 1917.68  5250.3 1920.67
  5260.4 1929.23  5269.5 1931.62  5274.5 1931.18  5280.4 1933.03  5340.6    1940
#Mann= 5 ,-1 , 0
  4697.1     .07       0  4897.4    .035       0  5106.6     .07       0
  5226.1    .035       0  5234.5     .07       0
Bank Sta=5226.1,5234.5
XS Rating Curve= 0 ,0
Exp/Cntr=0.3,0.1

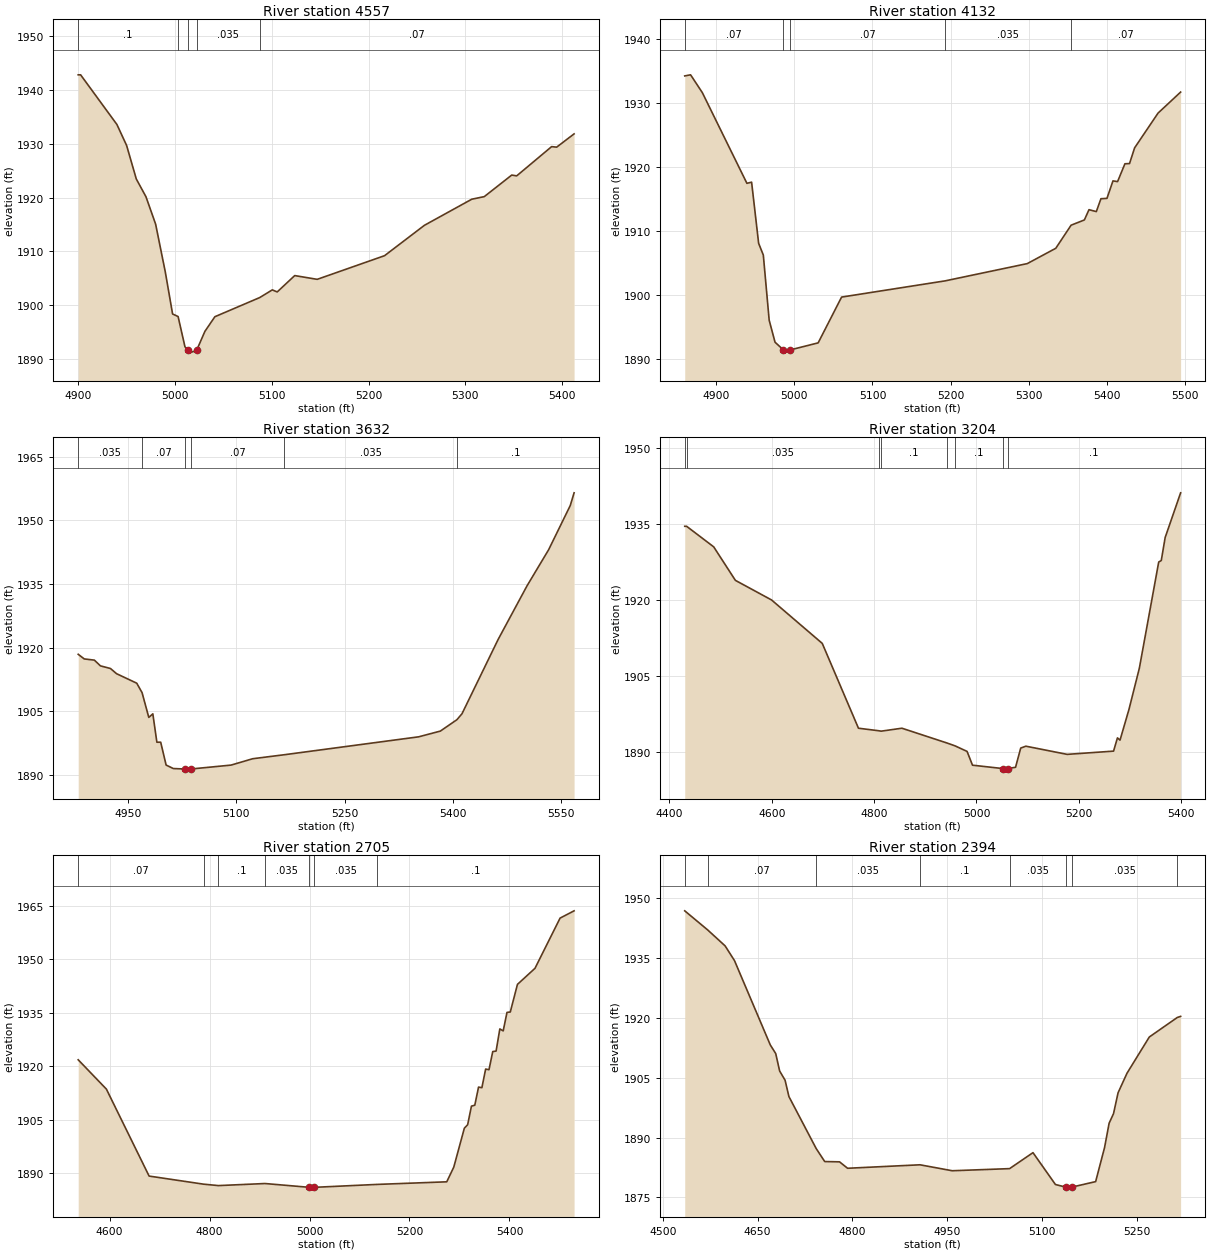
Type RM Length L Ch R = 1 ,4557    ,425,425,425
BEGIN DESCRIPTION:
Spring Creek 10.0
END DESCRIPTION:
XS GIS Cut Line= 3
        1853225.     13968224.99        1853225.       13968125.
        1853125.       13967725.
#Sta/Elev= 30
  4900.1 1942.83  4902.6 1942.83  4940.1 1933.59  4950.1  1929.7  4960.1 1923.47
  4970.1 1920.16  4980.1 1915.05  4990.1 1906.15  4997.6 1898.36  5003.3 1897.88
  5010.4 1892.26  5013.8 1891.58  5014.3 1891.08  5022.4 1891.58    5031 1895.13
  5041.3 1897.85  5087.6 1901.41  5100.6 1902.84  5105.7 1902.46  5123.8  1905.5
    5147  1904.8  5216.6  1909.2  5257.8 1914.85  5306.7  1919.7  5319.6 1920.18
    5348 1924.19  5353.1 1924.04  5389.2 1929.48  5394.4 1929.38  5412.4 1931.85
#Mann= 5 ,-1 , 0
  4900.1      .1       0  5003.3    .035       0  5013.8     .05       0
  5022.4    .035       0  5087.6     .07       0
Bank Sta=5013.8,5022.4
XS Rating Curve= 0 ,0
Exp/Cntr=0.3,0.1

Type RM Length L Ch R = 1 ,4132    ,500,500,500
BEGIN DESCRIPTION:
Spring Creek 9.0
END DESCRIPTION:
XS GIS Cut Line= 4
      1853575.02     13968224.97      1853643.56     13968122.17
      1853648.15     13968032.04      1853425.02     13967675.03
#Sta/Elev= 30
  4859.7 1934.17  4867.2 1934.34  4882.2 1931.57  4939.3 1917.42  4945.3  1917.6
  4954.3 1908.07  4960.3 1906.23  4967.8 1896.07  4975.3 1892.64  4986.1 1891.44
  4986.6 1890.94  4994.7 1891.44  5030.5 1892.54  5060.5 1899.68  5193.1 1902.21
  5298.2  1904.9  5334.7 1907.29  5354.3 1910.89  5371.3 1911.71  5377.2 1913.31
  5386.6 1913.01  5392.5 1915.02  5400.2 1915.07  5407.9  1917.8  5413.8 1917.69
  5423.2 1920.47  5429.1  1920.5  5435.6 1922.95  5465.6 1928.37  5494.5 1931.65
#Mann= 5 ,-1 , 0
  4859.7     .07       0  4986.1     .05       0  4994.7     .07       0
  5193.1    .035       0  5354.3     .07       0
Bank Sta=4986.1,4994.7
XS Rating Curve= 0 ,0
Exp/Cntr=0.3,0.1

Type RM Length L Ch R = 1 ,3632    ,428,428,428
BEGIN DESCRIPTION:
Spring Creek 8.0
END DESCRIPTION:
XS GIS Cut Line= 3
      1854024.99     13968175.02        1854075.       13968075.
      1854072.48     13967499.73
#Sta/Elev= 30
  4880.8 1918.42  4889.2 1917.33  4903.2 1917.05  4911.6  1915.7  4925.5 1915.08
  4933.9 1913.86  4961.9 1911.62  4969.3 1909.39  4978.6 1903.56  4984.2  1904.4
  4989.8 1897.72  4995.1 1897.72  5002.6 1892.34  5012.6 1891.52  5028.2 1891.41
  5028.7 1890.91  5036.5 1890.91    5037 1891.41  5092.6 1892.33  5122.6 1893.83
  5166.4 1894.77  5352.6 1898.99  5382.6 1900.34  5405.6 1903.03  5412.6 1904.43
  5462.6  1921.9  5502.6 1934.52  5532.6 1943.04  5562.6 1953.46  5567.9 1956.45
#Mann= 6 ,-1 , 0
  4880.8    .035       0  4969.3     .07       0  5028.2     .05       0
    5037     .07       0  5166.4    .035       0  5405.6      .1       0
Bank Sta=5028.2,5037
XS Rating Curve= 0 ,0
Exp/Cntr=0.3,0.1

Type RM Length L Ch R = 1 ,3204    ,499,499,499
BEGIN DESCRIPTION:
Spring Creek 7.0
END DESCRIPTION:
XS GIS Cut Line= 3
      1854024.99     13968425.01        1854425.       13968025.
        1854475.     13967625.02
#Sta/Elev= 30
    4430 1934.49  4433.7 1934.49  4486.6 1930.44    4529 1923.84  4599.7 1919.98
  4698.7 1911.43  4769.4 1894.73    4809 1894.23  4813.9 1894.15  4854.3 1894.73
  4942.6 1891.81    4958 1891.26  4981.6 1890.16  4992.2 1887.45  5051.8 1886.78
  5052.3 1886.28  5060.6 1886.78  5076.3 1887.04  5086.4 1890.82  5096.5 1891.19
  5177.1 1889.58  5267.8 1890.22  5275.4 1892.83  5280.4 1892.38    5298 1898.47
  5318.2 1906.56    5356 1927.45    5361 1927.75  5368.6 1932.28  5398.8 1941.08
#Mann= 8 ,-1 , 0
    4430     .07       0  4433.7    .035       0    4809     .07       0
  4813.9      .1       0  4942.6    .035       0    4958      .1       0
  5051.8     .05       0  5060.6      .1       0
Bank Sta=5051.8,5060.6
XS Rating Curve= 0 ,0
Exp/Cntr=0.3,0.1

Type RM Length L Ch R = 1 ,2705    ,311,311,311
BEGIN DESCRIPTION:
Spring Creek 6.0
END DESCRIPTION:
XS GIS Cut Line= 3
      1854425.02     13968574.98      1854745.14      13968211.8
      1855125.01       13967875.
#Sta/Elev= 30
  4537.4 1921.78  4593.8 1913.55  4679.2 1889.17  4788.2  1886.9  4817.9  1886.5
    4911 1887.08  4999.9 1886.01  5000.4 1885.51  5009.3 1886.01  5134.9 1886.83
  5274.5 1887.56  5288.6 1891.69  5309.7 1902.59  5316.3 1903.57  5323.9 1908.78
  5330.6 1909.05  5338.1 1914.12  5344.8 1913.96  5352.3 1919.18    5359    1919
  5366.5 1924.08  5373.2 1924.22  5380.7 1930.44  5387.4 1929.88    5395 1935.07
  5401.6 1935.18  5415.9 1942.92    5451 1947.43  5501.2 1961.51  5529.2 1963.55
#Mann= 7 ,-1 , 0
  4537.4     .07       0  4788.2    .035       0  4817.9      .1       0
    4911    .035       0  4999.9    .035       0  5009.3    .035       0
  5134.9      .1       0
Bank Sta=4999.9,5009.3
XS Rating Curve= 0 ,0
Exp/Cntr=0.3,0.1

Type RM Length L Ch R = 1 ,2394    ,588,588,588
BEGIN DESCRIPTION:
Spring Creek 5.0
END DESCRIPTION:
XS GIS Cut Line= 3
        1854575.     13968874.99       1854839.9     13968501.99
        1855075.       13968275.
#Sta/Elev= 30
  4534.7 1946.75  4570.9 1941.98  4598.6 1937.97  4613.4 1934.29    4670 1913.19
  4678.6 1911.02  4684.8 1906.66  4693.4 1904.35  4699.5 1900.25  4742.7 1887.22
  4756.1 1883.99  4779.5 1883.92  4792.3 1882.31  4906.8 1883.18  4957.8 1881.69
  5048.5 1882.22  5085.5 1886.22    5121 1878.25  5137.4 1877.59  5137.9 1877.09
  5146.8 1877.59  5184.6 1878.97  5198.7  1887.5  5205.9 1893.58  5212.9    1896
  5220.1 1901.22  5234.2  1906.1  5269.5 1915.17  5313.7 1920.05    5319 1920.33
#Mann= 8 ,-1 , 0
  4534.7    .035       0  4570.9     .07       0  4742.7    .035       0
  4906.8      .1       0  5048.5    .035       0  5137.4     .05       0
  5146.8    .035       0  5313.7     .07       0
Bank Sta=5137.4,5146.8
XS Rating Curve= 0 ,0
Exp/Cntr=0.3,0.1