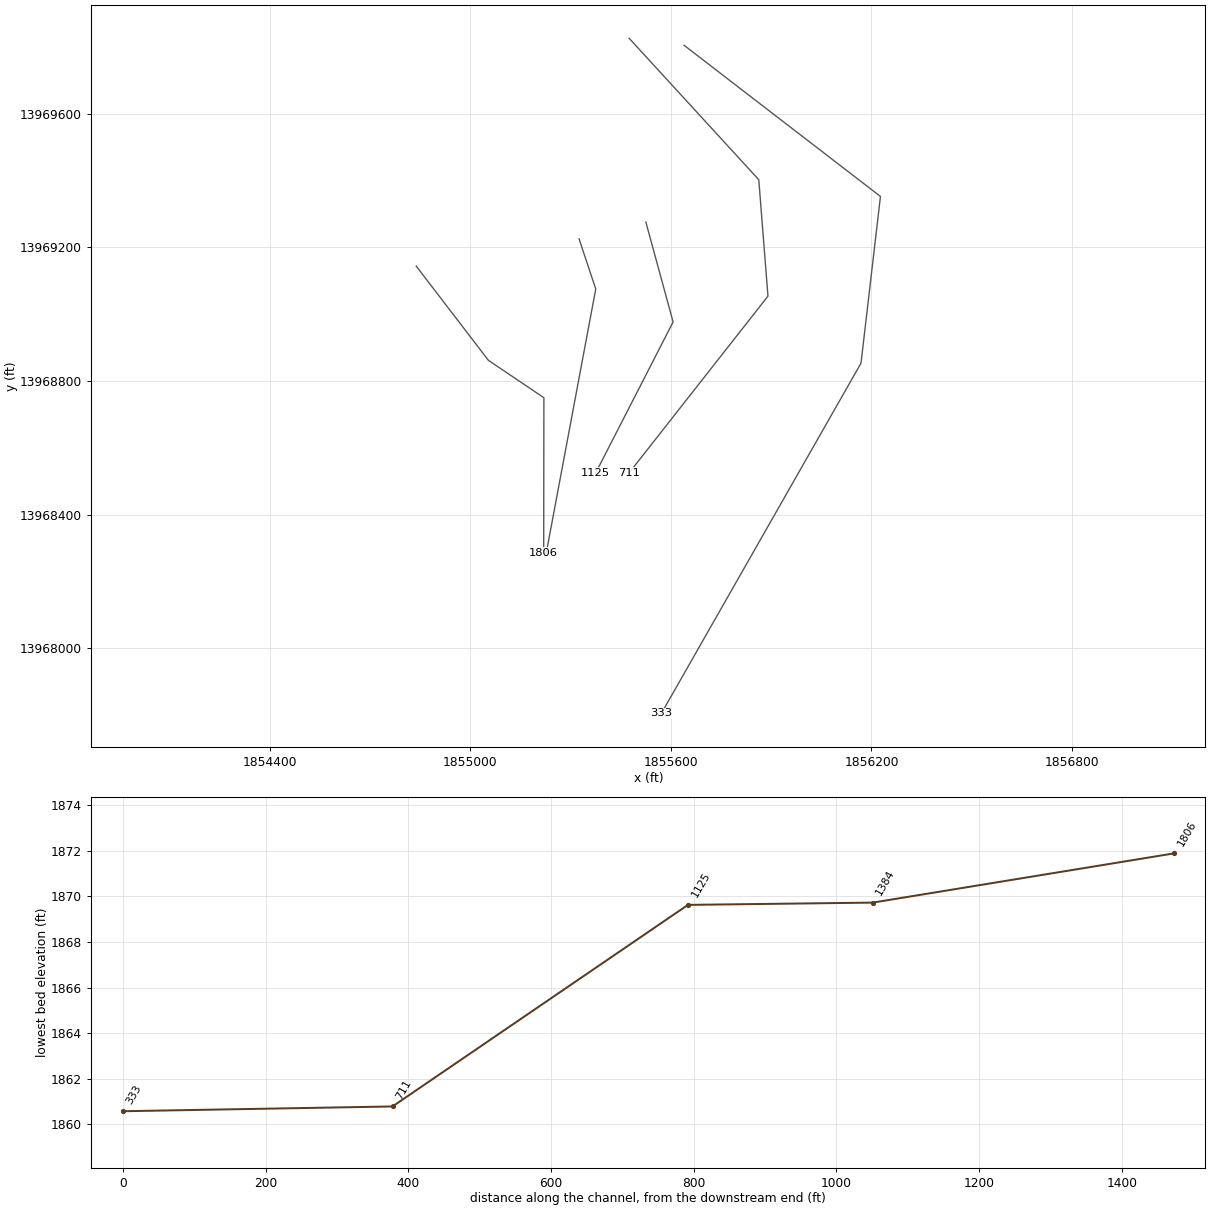
HEC-RAS study Spring Creek.prj: Spring Creek_US Base Level Engineering

--- Spring Creek.g01 (geometry) --- (continued)

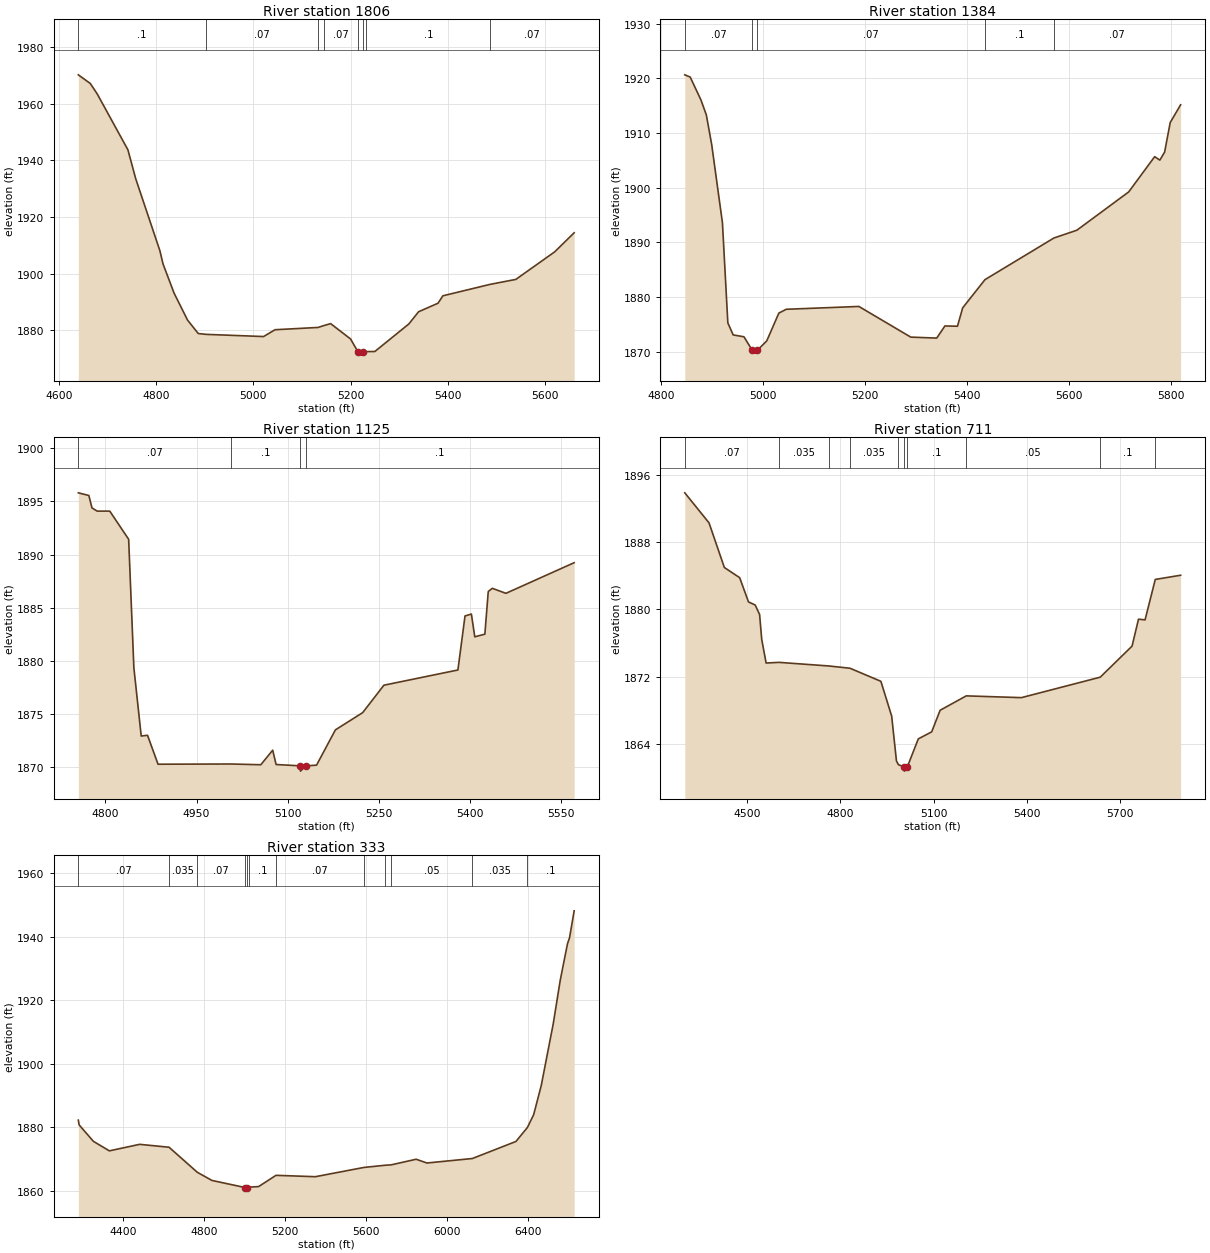
Type RM Length L Ch R = 1 ,1806    ,422,422,422
BEGIN DESCRIPTION:
Spring Creek 4.0
END DESCRIPTION:
XS GIS Cut Line= 4
      1854837.94     13969143.24      1855053.74     13968861.61
      1855219.82     13968749.67      1855219.26     13968284.96
#Sta/Elev= 30
    4640 1970.25  4664.6 1967.19  4679.1 1963.43    4742 1943.74    4758 1933.55
  4807.8 1908.06  4814.2 1903.42  4836.9 1893.11  4864.6 1883.58  4886.7 1878.81
  4902.8 1878.52    5021 1877.75  5044.6 1880.16  5133.2 1880.97  5144.7 1881.61
  5158.9 1882.32  5199.9  1876.9    5215 1872.39  5215.5 1871.89  5224.5 1872.39
  5232.6 1872.44  5249.8 1872.46  5319.8  1882.2  5339.8 1886.51  5379.8 1889.53
  5389.8 1892.15  5486.8 1896.19  5539.8 1897.94  5619.8 1907.69  5659.8 1914.43
#Mann= 8 ,-1 , 0
    4640      .1       0  4902.8     .07       0  5133.2      .1       0
  5144.7     .07       0    5215     .05       0  5224.5     .07       0
  5232.6      .1       0  5486.8     .07       0
Bank Sta=5215,5224.5
XS Rating Curve= 0 ,0
Exp/Cntr=0.3,0.1

Type RM Length L Ch R = 1 ,1384    ,259,259,259
BEGIN DESCRIPTION:
Spring Creek 3.0
END DESCRIPTION:
XS GIS Cut Line= 3
      1855324.99     13969225.02        1855375.       13969075.
        1855225.     13968274.98
#Sta/Elev= 30
  4846.6 1920.64  4857.2 1920.23  4878.2 1916.06  4888.8 1913.32  4899.3 1907.91
  4920.4 1893.58    4931 1875.26  4941.5 1873.06  4962.6 1872.72  4978.9 1870.23
  4979.4 1869.73  4988.5 1870.23  5007.3 1871.97    5031 1877.05  5045.4 1877.75
  5187.9 1878.27  5289.6 1872.66  5340.5 1872.48  5356.6  1874.7  5381.2 1874.65
  5391.4 1878.01  5435.1 1883.17  5570.3 1890.79  5615.2 1892.21  5716.9 1899.22
  5767.8 1905.67    5778 1905.04  5787.3  1906.5  5798.3 1911.91  5818.7 1915.16
#Mann= 5 ,-1 , 0
  4846.6     .07       0  4978.9     .05       0  4988.5     .07       0
  5435.1      .1       0  5570.3     .07       0
Bank Sta=4978.9,4988.5
XS Rating Curve= 0 ,0
Exp/Cntr=0.3,0.1

Type RM Length L Ch R = 1 ,1125    ,414,414,414
BEGIN DESCRIPTION:
Spring Creek 2.0
END DESCRIPTION:
XS GIS Cut Line= 3
        1855525.     13969274.99      1855606.45     13968976.37
      1855374.99     13968524.98
#Sta/Elev= 30
  4755.3  1895.8  4772.6 1895.55  4777.8 1894.38  4786.4 1894.08  4807.1 1894.08
  4838.2 1891.43  4846.8 1879.35  4858.9 1872.93  4869.3    1873  4886.6 1870.28
  5007.6  1870.3  5055.9 1870.23  5075.5  1871.6  5081.1 1870.25  5120.7 1870.13
  5121.2 1869.63  5130.3 1870.13  5147.7 1870.19  5178.8 1873.51  5223.7 1875.13
  5258.7 1877.71  5380.6 1879.14  5392.3 1884.22  5402.8  1884.4  5408.4 1882.26
    5425 1882.51  5430.6 1886.52  5437.2 1886.82  5459.7 1886.35  5572.1 1889.23
#Mann= 4 ,-1 , 0
  4755.3     .07       0  5007.6      .1       0  5120.7     .05       0
  5130.3      .1       0
Bank Sta=5120.7,5130.3
XS Rating Curve= 0 ,0
Exp/Cntr=0.3,0.1

Type RM Length L Ch R = 1 ,711     ,378,378,378
BEGIN DESCRIPTION:
Spring Creek 1.0
END DESCRIPTION:
XS GIS Cut Line= 4
      1855475.03     13969824.97      1855862.81     13969401.94
      1855890.29     13969053.56      1855475.01     13968525.02
#Sta/Elev= 30
    4299 1893.84    4377 1890.27  4426.3 1884.97  4475.6 1883.76    4504 1880.88
  4525.6 1880.51  4539.7 1879.39  4546.5 1876.44  4560.7 1873.62  4602.2  1873.7
  4763.3 1873.27  4830.7    1873    4930 1871.45  4964.7 1867.32  4980.1 1861.99
  4986.5 1861.54  5005.4 1861.28  5005.9 1860.78    5015 1861.28  5050.4 1864.61
  5093.5 1865.45  5120.6 1868.01  5204.7 1869.72  5382.1 1869.51  5635.8 1871.94
  5738.2 1875.63    5759 1878.83  5780.1 1878.75  5812.9 1883.55  5894.5 1884.05
#Mann= 10 ,-1 , 0
    4299     .07       0  4602.2    .035       0  4763.3     .07       0
  4830.7    .035       0  4986.5      .1       0  5005.4     .05       0
    5015      .1       0  5204.7     .05       0  5635.8      .1       0
  5812.9     .07       0
Bank Sta=5005.4,5015
XS Rating Curve= 0 ,0
Exp/Cntr=0.3,0.1

Type RM Length L Ch R = 1 ,333     ,0,0,0
BEGIN DESCRIPTION:
Spring Creek 0.0
END DESCRIPTION:
XS GIS Cut Line= 4
      1855639.29     13969804.12      1856226.84     13969351.93
      1856168.69     13968853.08      1855571.42     13967805.19
#Sta/Elev= 30
  4179.6 1882.28  4183.4 1880.79  4254.1  1875.6  4332.9 1872.61  4482.4 1874.66
  4627.8 1873.75  4767.2 1865.88  4839.4 1863.31  5003.4 1861.07  5003.9 1860.57
  5013.7 1861.07    5021 1861.19  5070.2 1861.37  5156.4 1864.91  5350.8 1864.48
  5591.4  1867.4  5696.8 1868.09  5724.8  1868.2  5848.7 1869.97    5902 1868.79
  6126.5  1870.2  6341.9 1875.57  6398.5 1879.97  6429.3 1883.99  6466.7 1893.13
  6525.8  1912.5  6560.6 1926.27  6596.4 1937.75  6606.5 1939.62  6629.4 1948.12
#Mann= 12 ,-1 , 0
  4179.6     .07       0  4627.8    .035       0  4767.2     .07       0
  5003.4     .05       0  5013.7     .07       0    5021      .1       0
  5156.4     .07       0  5591.4     .05       0  5696.8     .07       0
  5724.8     .05       0  6126.5    .035       0  6398.5      .1       0
Bank Sta=5003.4,5013.7
XS Rating Curve= 0 ,0
Exp/Cntr=0.3,0.1

Chan Stop Cuts=-1
Use User Specified Reach Order=0
Composite Channel Slope=5