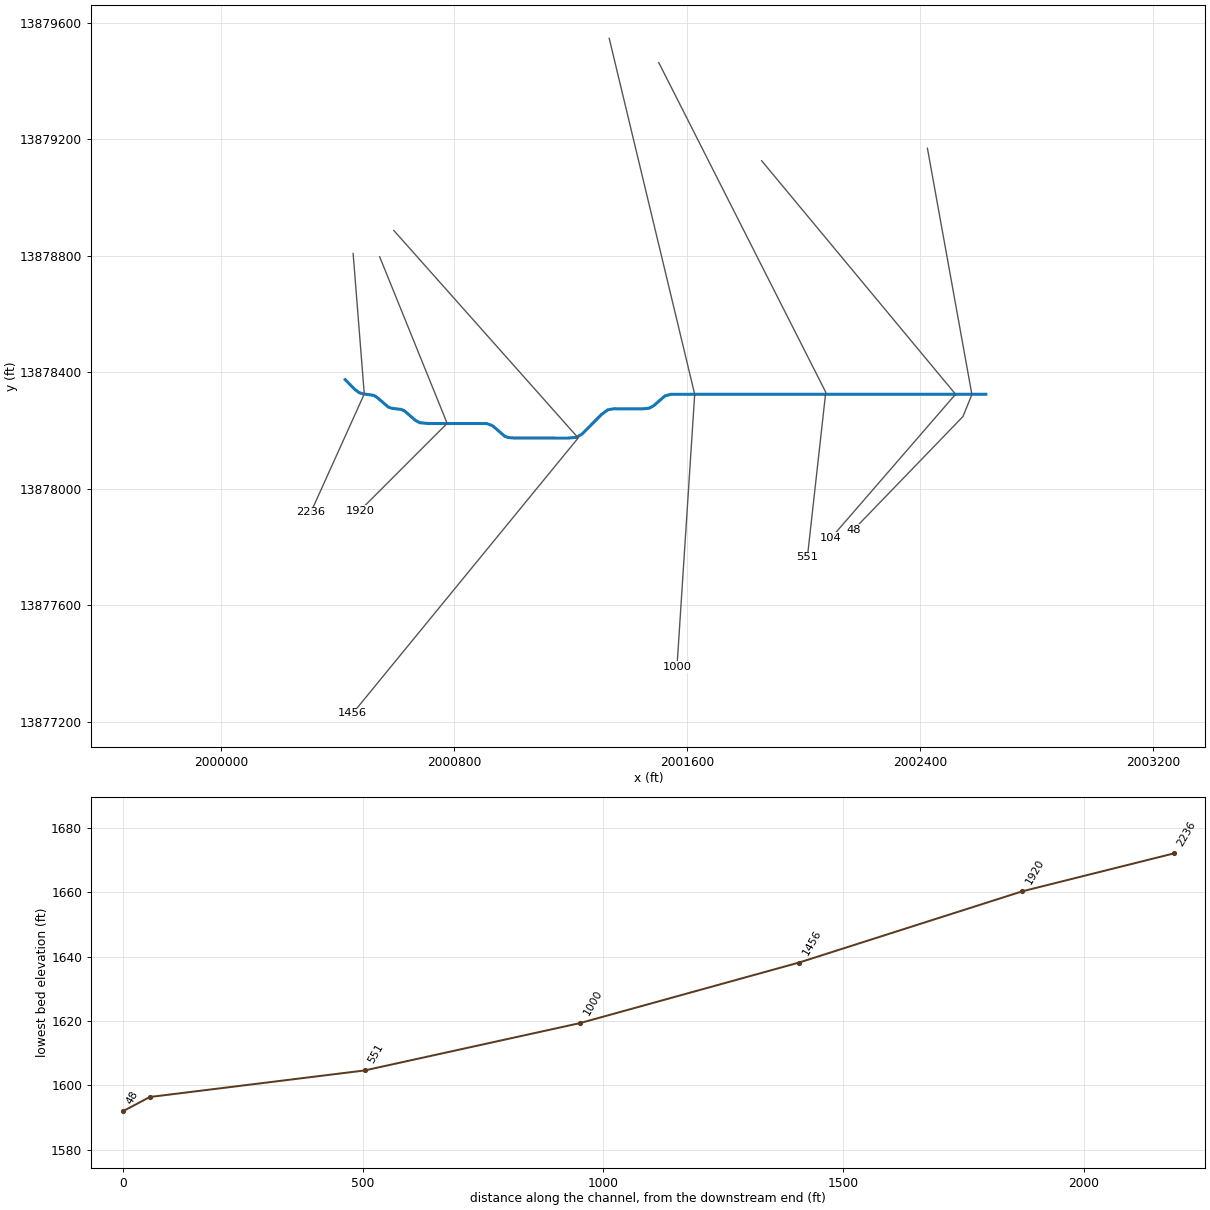
--- Stream0002_DS.prj (project) ---

Proj Title=Stream0002_DS Base Level Engineering
Current Plan=p01
Default Exp/Contr=0.3,0.1
English Units
Geom File=g01
Flow File=f01
Plan File=p01
BEGIN DESCRIPTION:
Stream0002_DS
END DESCRIPTION:

--- Stream0002_DS.p01 (plan) ---

Plan Title=Multiple Run
Short Identifier=Multiple
Geom File=g01
Flow File=f01
Subcritical Flow
K Sum by GR= 0
Std Step Tol= 0.01
Critical Tol= 0.01
Num of Std Step Trials= 20
Max Error Tol= 0.3
Flow Tol Ratio= 0.001
Split Flow NTrial= 30
Split Flow Tol= 0.02
Split Flow Ratio= 0.02
Log Output Level= 0
Friction Slope Method= 1
Unsteady Friction Slope Method= 2
Unsteady Bridges Friction Slope Method= 1
Parabolic Critical Depth
Global Vel Dist=  1 , 1 , 1
Global Log Level= 0
CheckData=True
Encroach Param= -1, 0, 0, 0
BEGIN DESCRIPTION:
Multiple Run
END DESCRIPTION:

--- Stream0002_DS.f01 (steady flow) ---

Flow Title=Multiple
Number of Profiles=7
Profile Names=10-year,25-year,50-year,1pct_min,100-year,1pct_plu,500-year
River Rch & RM= Stream0002_DS,Reach-1,2236
     684    1149    1588    1069    2133    4256    3798
Boundary for River Rch & Prof#=Stream0002_DS,Reach-1,1
Up Type=0
Dn Type=3
Dn Slope=0.005
Boundary for River Rch & Prof#=Stream0002_DS,Reach-1,2
Up Type=0
Dn Type=3
Dn Slope=0.005
Boundary for River Rch & Prof#=Stream0002_DS,Reach-1,3
Up Type=0
Dn Type=3
Dn Slope=0.005
Boundary for River Rch & Prof#=Stream0002_DS,Reach-1,4
Up Type=0
Dn Type=3
Dn Slope=0.005
Boundary for River Rch & Prof#=Stream0002_DS,Reach-1,5
Up Type=0
Dn Type=3
Dn Slope=0.005
Boundary for River Rch & Prof#=Stream0002_DS,Reach-1,6
Up Type=0
Dn Type=3
Dn Slope=0.005
Boundary for River Rch & Prof#=Stream0002_DS,Reach-1,7
Up Type=0
Dn Type=3
Dn Slope=0.005

--- Stream0002_DS.g01 (geometry) ---

Geom Title=Existing Conditions

River Reach=Stream0002_DS,Reach-1
Reach XY= 30
      2000425.00     13878375.00      2000458.07     13878341.41
      2000472.64     13878330.67      2000485.66     13878326.60
      2000523.33     13878320.96      2000534.57     13878313.96
      2000572.80     13878281.07      2000584.84     13878276.81
      2000615.15     13878273.17      2000627.18     13878268.88
      2000665.33     13878235.80      2000680.93     13878227.24
      2000709.82     13878224.56      2000911.08     13878224.32
      2000931.06     13878216.86      2000972.67     13878180.75
      2000984.66     13878176.38      2001006.66     13878174.61
      2001190.20     13878174.51      2001219.14     13878177.07
      2001238.31     13878188.40      2001304.86     13878255.35
      2001326.47     13878271.44      2001347.66     13878275.17
      2001445.13     13878274.68      2001469.06     13878277.27
      2001484.64     13878285.86      2001522.67     13878319.25
      2001543.27     13878324.79      2002625.00     13878325.00

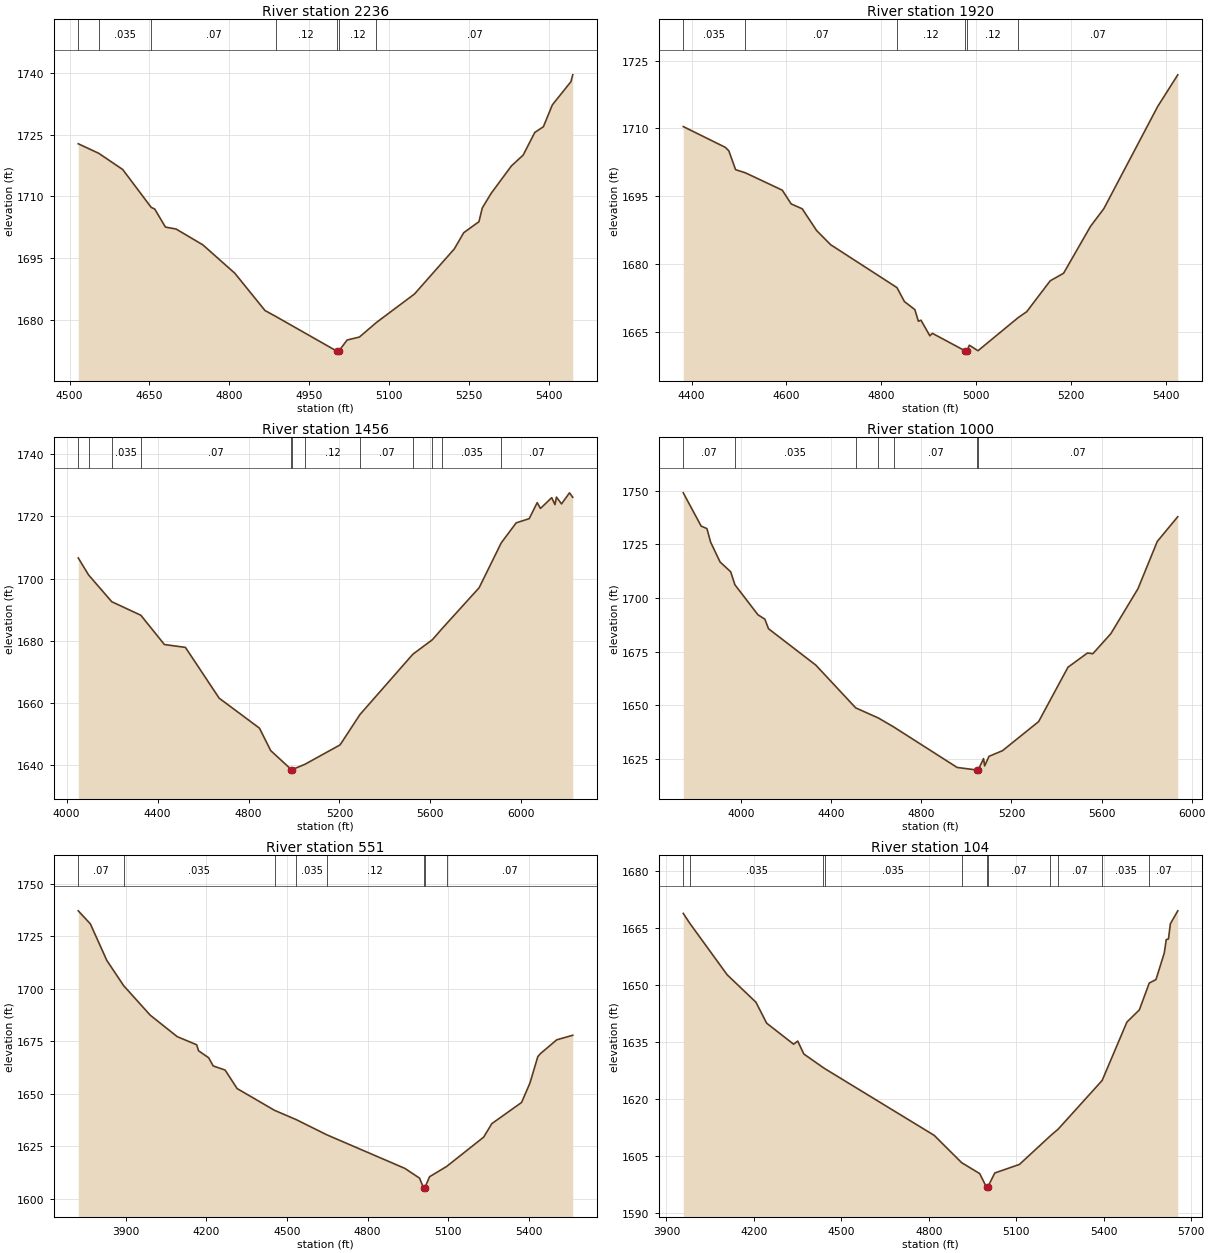
Type RM Length L Ch R = 1,2236,316,316,316
BEGIN DESCRIPTION:
Stream0002_DS 5.0
END DESCRIPTION:
XS GIS Cut Line= 3
      2000452.10     13878808.26      2000490.40     13878325.97
      2000307.16     13877920.02
#Sta/Elev= 30
  4516.2 1722.76  4554.7 1720.45  4599.7 1716.53  4653.2 1707.38  4659.9 1706.96
  4680.0 1702.60  4700.0 1702.13  4750.2 1698.31  4810.4 1691.43  4867.1 1682.41
  4887.5 1680.97  5001.8 1672.60  5002.0 1672.10  5005.8 1672.60  5021.4 1675.27
  5044.5 1675.99  5076.5 1679.52  5148.0 1686.41  5222.9 1697.33  5240.5 1701.24
  5269.1 1703.90  5275.4 1707.23  5292.2 1710.79  5330.2 1717.41  5352.2 1720.02
  5374.1 1725.51  5390.2 1726.88  5407.0 1732.16  5442.0 1737.79  5445.4 1739.44
#Mann=7,-1,0
  4516.2    0.07       0  4554.7   0.035       0  4653.2    0.07       0
  4887.5    0.12       0  5001.8    0.05       0  5005.8    0.12       0
  5076.5    0.07       0
Bank Sta=5001.8,5005.8
Exp/Cntr=0.3,0.1

Type RM Length L Ch R = 1,1920,464,464,464
BEGIN DESCRIPTION:
Stream0002_DS 4.0
END DESCRIPTION:
XS GIS Cut Line= 3
      2000543.24     13878797.14      2000775.00     13878225.00
      2000474.97     13877924.97
#Sta/Elev= 30
  4382.6 1710.41  4471.2 1705.82  4478.6 1705.05  4492.8 1700.88  4513.5 1700.18
  4591.2 1696.34  4609.9 1693.30  4633.1 1692.23  4663.5 1687.41  4693.0 1684.28
  4832.7 1674.79  4848.4 1671.70  4870.4 1669.92  4877.9 1667.34  4883.3 1667.58
  4902.0 1664.13  4907.4 1664.67  4976.3 1660.79  4976.6 1660.29  4980.3 1660.79
  4985.1 1662.04  5003.4 1660.82  5088.3 1668.17  5106.0 1669.45  5155.5 1676.29
  5183.7 1677.96  5240.3 1688.32  5268.6 1692.27  5381.7 1714.82  5424.2 1721.86
#Mann=6,-1,0
  4382.6   0.035       0  4513.5    0.07       0  4832.7    0.12       0
  4976.3    0.05       0  4980.3    0.12       0  5088.3    0.07       0
Bank Sta=4976.3,4980.3
Exp/Cntr=0.3,0.1

Type RM Length L Ch R = 1,1456,456,456,456
BEGIN DESCRIPTION:
Stream0002_DS 3.0
END DESCRIPTION:
XS GIS Cut Line= 3
      2000591.88     13878887.38      2001225.00     13878175.00
      2000450.70     13877229.18
#Sta/Elev= 30
  4051.1 1706.61  4096.8 1701.13  4198.5 1692.56  4326.5 1688.21  4430.1 1678.81
  4522.5 1677.90  4670.9 1661.60  4848.2 1651.97  4897.5 1644.78  4988.4 1638.67
  4988.6 1638.17  4992.4 1638.67  5048.5 1640.37  5203.0 1646.60  5290.0 1656.31
  5523.1 1675.71  5609.1 1680.37  5651.0 1683.88  5814.5 1697.04  5911.8 1711.44
  5977.5 1717.88  6034.9 1719.23  6070.1 1724.37  6084.4 1722.51  6133.9 1725.97
  6148.3 1723.73  6154.7 1726.15  6177.0 1723.97  6212.2 1727.52  6226.5 1726.09
#Mann=12,-1,0
  4051.1   0.035       0  4096.8    0.07       0  4198.5   0.035       0
  4326.5    0.07       0  4988.4    0.05       0  4992.4    0.07       0
  5048.5    0.12       0  5290.0    0.07       0  5523.1   0.035       0
  5609.1    0.07       0  5651.0   0.035       0  5911.8    0.07       0
Bank Sta=4988.4,4992.4
Exp/Cntr=0.3,0.1

Type RM Length L Ch R = 1,1000,449,449,449
BEGIN DESCRIPTION:
Stream0002_DS 2.0
END DESCRIPTION:
XS GIS Cut Line= 3
      2001331.43     13879547.13      2001625.00     13878325.00
      2001564.15     13877388.67
#Sta/Elev= 30
  3743.2 1748.95  3822.6 1733.46  3848.2 1732.30  3864.6 1726.00  3906.6 1716.74
  3953.7 1712.18  3972.4 1706.15  4074.5 1692.18  4105.4 1690.11  4121.6 1685.66
  4331.5 1668.73  4508.6 1648.81  4609.0 1644.10  4677.0 1639.94  4959.0 1621.05
  5048.2 1619.84  5048.5 1619.34  5052.2 1619.84  5076.2 1625.16  5081.2 1621.76
  5100.3 1626.22  5160.4 1628.87  5320.8 1642.41  5451.0 1667.73  5538.0 1674.38
  5561.3 1674.01  5641.4 1683.37  5761.7 1704.28  5847.5 1726.32  5938.4 1737.83
#Mann=7,-1,0
  3743.2    0.07       0  3972.4   0.035       0  4508.6    0.07       0
  4609.0   0.035       0  4677.0    0.07       0  5048.2    0.05       0
  5052.2    0.07       0
Bank Sta=5048.2,5052.2
Exp/Cntr=0.3,0.1

Type RM Length L Ch R = 1,551,447,447,447
BEGIN DESCRIPTION:
Stream0002_DS 1.0
END DESCRIPTION:
XS GIS Cut Line= 3
      2001501.57     13879463.79      2002075.00     13878331.94
      2002011.98     13877765.86
#Sta/Elev= 30
  3724.2 1737.05  3769.1 1730.86  3830.3 1713.46  3893.2 1701.39  3991.9 1687.37
  4092.0 1677.18  4164.5 1673.29  4171.3 1670.45  4209.0 1667.11  4225.7 1663.24
  4270.2 1661.26  4314.8 1652.46  4453.8 1642.10  4535.2 1637.63  4647.4 1630.49
  4938.4 1614.47  4993.0 1609.82  5008.1 1605.09  5008.3 1604.59  5012.1 1605.09
  5030.2 1610.49  5093.6 1615.37  5231.4 1629.35  5261.6 1635.75  5372.3 1645.84
  5403.6 1655.13  5432.7 1667.68  5442.7 1669.12  5503.1 1675.66  5562.6 1677.83
#Mann=8,-1,0
  3724.2    0.07       0  3893.2   0.035       0  4453.8    0.07       0
  4535.2   0.035       0  4647.4    0.12       0  5008.1    0.05       0
  5012.1    0.12       0  5093.6    0.07       0
Bank Sta=5008.1,5012.1
Exp/Cntr=0.3,0.1

Type RM Length L Ch R = 1,104,56,56,56
BEGIN DESCRIPTION:
Stream0002_DS 0.1
END DESCRIPTION:
XS GIS Cut Line= 3
      2001854.87     13879126.85      2002520.77     13878325.00
      2002093.18     13877831.21
#Sta/Elev= 30
  3957.7 1668.78  3980.5 1666.14  4108.1 1652.67  4207.1 1645.43  4243.5 1639.95
  4336.0 1634.42  4350.1 1635.24  4371.1 1631.84  4437.3 1628.29  4444.0 1627.95
  4818.0 1610.47  4912.2 1603.29  4974.0 1600.43  4997.4 1596.84  4997.6 1596.34
  5001.4 1596.84  5025.8 1600.58  5110.3 1602.83  5216.5 1610.35  5243.5 1612.13
  5394.0 1624.90  5478.8 1640.23  5521.5 1643.44  5555.4 1650.48  5578.5 1651.40
  5607.1 1658.42  5613.7 1661.89  5621.3 1662.07  5627.9 1666.05  5653.2 1669.46
#Mann=11,-1,0
  3957.7    0.07       0  3980.5   0.035       0  4437.3    0.12       0
  4444.0   0.035       0  4912.2    0.07       0  4997.4    0.05       0
  5001.4    0.07       0  5216.5    0.12       0  5243.5    0.07       0
  5394.0   0.035       0  5555.4    0.07       0
Bank Sta=4997.4,5001.4
Exp/Cntr=0.3,0.1

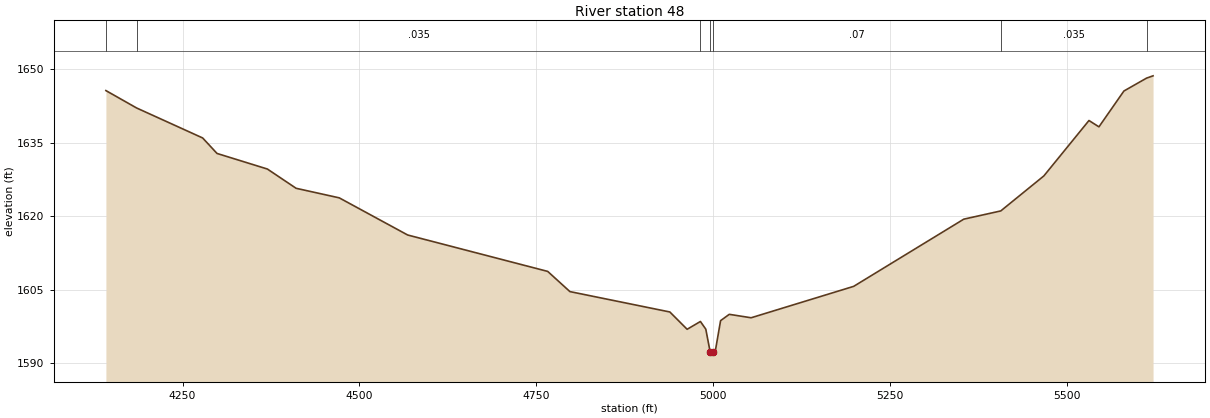
Type RM Length L Ch R = 1,48,0,0,0
BEGIN DESCRIPTION:
Stream0002_DS 0.0
END DESCRIPTION:
XS GIS Cut Line= 4
      2002424.14     13879169.64      2002576.84     13878324.10
      2002546.28     13878248.60      2002171.30     13877860.40
#Sta/Elev= 30
  4141.7 1645.69  4185.1 1642.14  4278.5 1636.02  4298.8 1632.86  4370.0 1629.68
  4410.6 1625.75  4471.6 1623.80  4568.3 1616.22  4766.3 1608.79  4797.7 1604.67
  4939.0 1600.51  4963.4 1596.98  4982.2 1598.57  4989.8 1597.00  4995.9 1592.41
  4996.2 1591.91  4999.9 1592.41  5003.1 1592.41  5010.7 1598.74  5023.0 1600.03
  5053.9 1599.33  5198.9 1605.74  5354.5 1619.45  5406.8 1621.13  5467.7 1628.27
  5531.5 1639.58  5545.6 1638.29  5580.9 1645.60  5612.9 1648.23  5622.1 1648.70
#Mann=7,-1,0
  4141.7    0.12       0  4185.1   0.035       0  4982.2    0.07       0
  4995.9    0.05       0  4999.9    0.07       0  5406.8   0.035       0
  5612.9    0.07       0
Bank Sta=4995.9,4999.9
Exp/Cntr=0.3,0.1

Chan Stop Cuts=-1