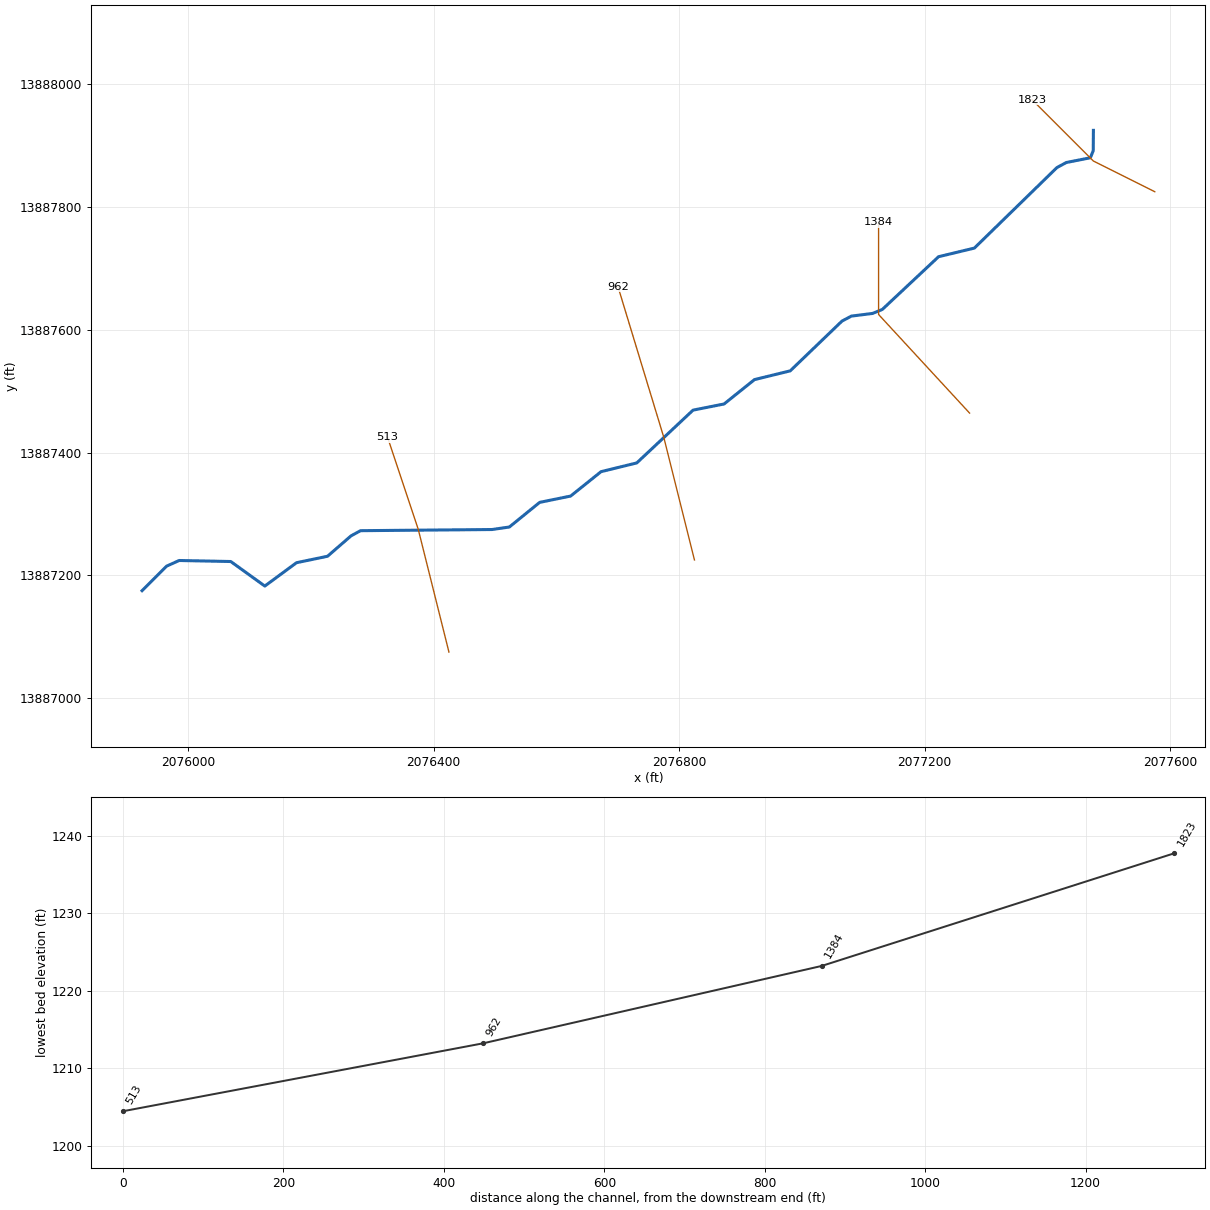
--- Stream0003_DS.prj (project) ---

Proj Title=Stream0003_DS Base Level Engineering
Current Plan=p01
Default Exp/Contr=0.3,0.1
English Units
Geom File=g01
Flow File=f01
Plan File=p01
BEGIN DESCRIPTION:
Stream0003_DS
END DESCRIPTION:

--- Stream0003_DS.p01 (plan) ---

Plan Title=Multiple Run
Short Identifier=Multiple
Geom File=g01
Flow File=f01
Subcritical Flow
K Sum by GR= 0
Std Step Tol= 0.01
Critical Tol= 0.01
Num of Std Step Trials= 20
Max Error Tol= 0.3
Flow Tol Ratio= 0.001
Split Flow NTrial= 30
Split Flow Tol= 0.02
Split Flow Ratio= 0.02
Log Output Level= 0
Friction Slope Method= 1
Unsteady Friction Slope Method= 2
Unsteady Bridges Friction Slope Method= 1
Parabolic Critical Depth
Global Vel Dist=  1 , 1 , 1
Global Log Level= 0
CheckData=True
Encroach Param= -1, 0, 0, 0
BEGIN DESCRIPTION:
Multiple Run
END DESCRIPTION:

--- Stream0003_DS.f01 (steady flow) ---

Flow Title=Multiple
Number of Profiles=7
Profile Names=10-year,25-year,50-year,1pct_min,100-year,1pct_plu,500-year
River Rch & RM= Stream0003_DS,Reach-1,1823
     369     582     772     499     996    1987    1632
River Rch & RM= Stream0003_DS,Reach-1,1384
     512     827    1113     729    1454    2901    2447
Boundary for River Rch & Prof#=Stream0003_DS,Reach-1,1
Up Type=0
Dn Type=3
Dn Slope=0.005
Boundary for River Rch & Prof#=Stream0003_DS,Reach-1,2
Up Type=0
Dn Type=3
Dn Slope=0.005
Boundary for River Rch & Prof#=Stream0003_DS,Reach-1,3
Up Type=0
Dn Type=3
Dn Slope=0.005
Boundary for River Rch & Prof#=Stream0003_DS,Reach-1,4
Up Type=0
Dn Type=3
Dn Slope=0.005
Boundary for River Rch & Prof#=Stream0003_DS,Reach-1,5
Up Type=0
Dn Type=3
Dn Slope=0.005
Boundary for River Rch & Prof#=Stream0003_DS,Reach-1,6
Up Type=0
Dn Type=3
Dn Slope=0.005
Boundary for River Rch & Prof#=Stream0003_DS,Reach-1,7
Up Type=0
Dn Type=3
Dn Slope=0.005

--- Stream0003_DS.g01 (geometry) ---

Geom Title=Existing Conditions

River Reach=Stream0003_DS,Reach-1
Reach XY= 30
      2077475.00     13887925.00      2077474.72     13887891.89
      2077470.08     13887880.33      2077430.80     13887872.59
      2077415.46     13887864.28      2077281.05     13887733.16
      2077222.72     13887719.13      2077131.04     13887633.18
      2077115.20     13887626.71      2077080.64     13887622.35
      2077065.33     13887614.20      2076981.05     13887533.16
      2076922.81     13887518.90      2076873.27     13887479.19
      2076822.71     13887469.15      2076731.05     13887383.16
      2076672.81     13887368.90      2076623.28     13887329.16
      2076572.82     13887318.88      2076523.45     13887278.75
      2076495.15     13887274.64      2076280.93     13887272.76
      2076265.33     13887264.20      2076227.17     13887231.09
      2076176.64     13887220.58      2076125.01     13887182.53
      2076069.53     13887222.52      2075985.46     13887224.18
      2075965.05     13887215.01      2075925.00     13887175.00

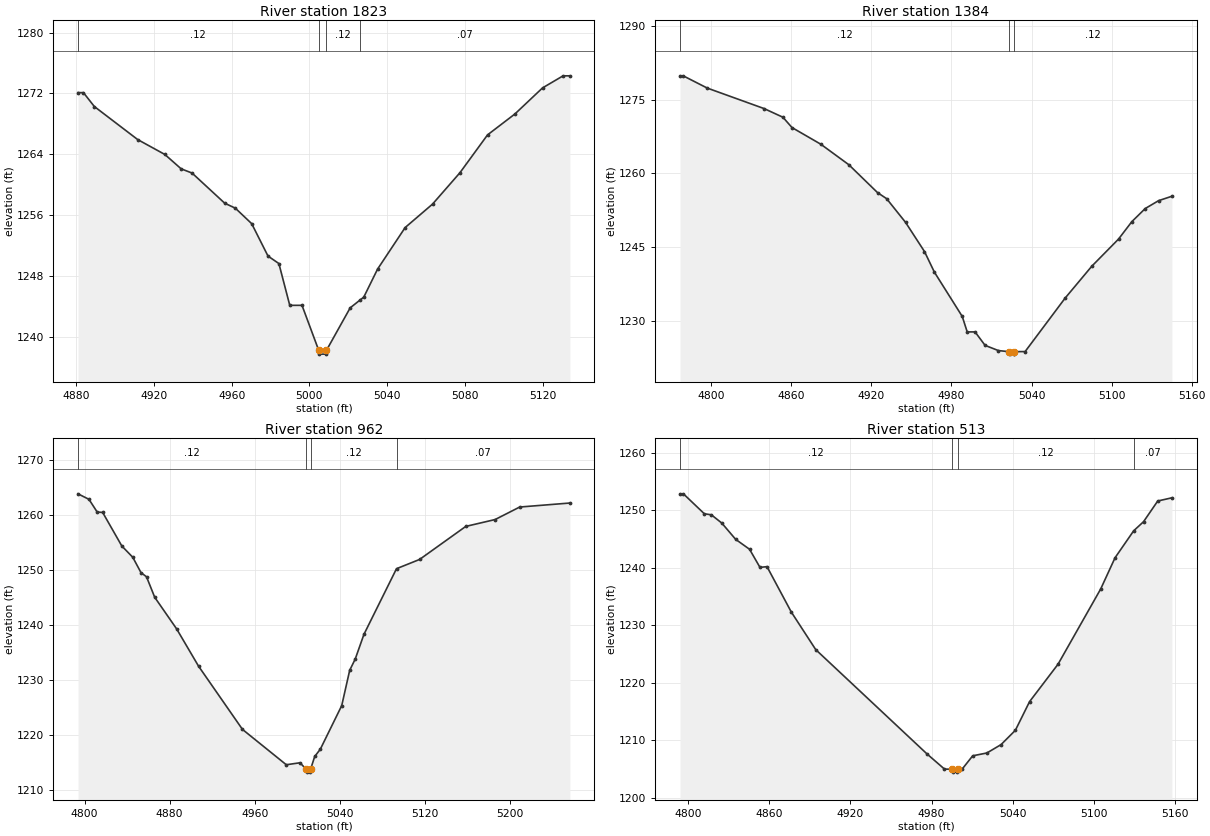
Type RM Length L Ch R = 1,1823,439,439,439
BEGIN DESCRIPTION:
Stream0003_DS 4.0
END DESCRIPTION:
XS GIS Cut Line= 3
      2077574.99     13887825.01      2077475.00     13887875.00
      2077375.01     13887974.99
#Sta/Elev= 30
  4880.9 1272.10  4883.7 1272.10  4889.3 1270.28  4911.6 1265.94  4925.6 1263.98
  4934.0 1262.09  4939.6 1261.54  4956.4 1257.58  4961.9 1256.92  4970.3 1254.89
  4978.7 1250.63  4984.3 1249.65  4989.9 1244.16  4996.2 1244.16  5004.8 1238.25
  5005.1 1237.75  5008.6 1237.75  5008.8 1238.25  5021.0 1243.83  5026.0 1244.84
  5028.0 1245.24  5035.1 1248.92  5049.3 1254.38  5063.4 1257.46  5077.5 1261.58
  5091.7 1266.55  5105.8 1269.30  5120.0 1272.72  5130.6 1274.31  5134.1 1274.31
#Mann=4,-1,0
  4880.9    0.12       0  5004.8    0.05       0  5008.8    0.12       0
  5026.0    0.07       0
Bank Sta=5004.8,5008.8
Exp/Cntr=0.3,0.1

Type RM Length L Ch R = 1,1384,422,422,422
BEGIN DESCRIPTION:
Stream0003_DS 3.0
END DESCRIPTION:
XS GIS Cut Line= 3
      2077273.26     13887464.33      2077125.00     13887625.00
      2077125.00     13887774.98
#Sta/Elev= 30
  4776.6 1279.82  4779.0 1279.82  4797.0 1277.33  4839.6 1273.16  4853.7 1271.40
  4860.5 1269.30  4882.1 1265.91  4903.1 1261.74  4924.6 1256.07  4931.4 1254.84
  4945.6 1250.02  4959.8 1244.08  4967.2 1239.90  4988.1 1230.88  4991.8 1227.74
  4997.7 1227.74  5005.2 1225.00  5015.2 1223.94  5023.2 1223.72  5023.5 1223.22
  5027.0 1223.22  5027.2 1223.72  5035.2 1223.74  5065.2 1234.62  5085.2 1241.11
  5105.2 1246.62  5115.2 1250.17  5125.2 1252.83  5135.2 1254.43  5145.2 1255.33
#Mann=3,-1,0
  4776.6    0.12       0  5023.2    0.05       0  5027.2    0.12       0
Bank Sta=5023.2,5027.2
Exp/Cntr=0.3,0.1

Type RM Length L Ch R = 1,962,449,449,449
BEGIN DESCRIPTION:
Stream0003_DS 2.0
END DESCRIPTION:
XS GIS Cut Line= 3
      2076824.99     13887225.04      2076775.00     13887425.00
      2076700.44     13887670.20
#Sta/Elev= 30
  4793.9 1263.78  4804.2 1262.78  4811.9 1260.48  4817.1 1260.39  4835.1 1254.30
  4845.4 1252.25  4853.1 1249.47  4858.3 1248.71  4866.0 1244.99  4886.6 1239.25
  4907.2 1232.48  4948.5 1220.99  4989.7 1214.57  5002.6 1214.93  5008.5 1213.73
  5008.7 1213.23  5012.2 1213.23  5012.5 1213.73  5016.4 1216.07  5021.7 1217.40
  5041.8 1225.31  5049.3 1231.73  5054.5 1233.77  5062.7 1238.26  5093.3 1250.18
  5115.0 1251.86  5158.4 1257.86  5186.0 1259.11  5209.1 1261.38  5256.3 1262.11
#Mann=4,-1,0
  4793.9    0.12       0  5008.5    0.05       0  5012.5    0.12       0
  5093.3    0.07       0
Bank Sta=5008.5,5012.5
Exp/Cntr=0.3,0.1

Type RM Length L Ch R = 1,513,0,0,0
BEGIN DESCRIPTION:
Stream0003_DS 1.0
END DESCRIPTION:
XS GIS Cut Line= 3
      2076424.99     13887075.03      2076375.00     13887275.00
      2076325.01     13887424.97
#Sta/Elev= 30
  4793.8 1252.88  4796.3 1252.88  4811.8 1249.41  4817.0 1249.23  4824.7 1247.80
  4835.0 1244.96  4845.3 1243.23  4853.0 1240.08  4858.2 1240.21  4876.2 1232.31
  4894.3 1225.77  4976.7 1207.62  4989.6 1204.99  4995.3 1204.96  4995.6 1204.46
  4999.1 1204.46  4999.3 1204.96  5002.6 1204.96  5010.5 1207.30  5021.0 1207.79
  5031.5 1209.25  5042.1 1211.74  5052.6 1216.72  5073.7 1223.24  5105.3 1236.34
  5115.9 1241.76  5129.7 1246.45  5137.0 1248.03  5147.5 1251.63  5158.0 1252.19
#Mann=4,-1,0
  4793.8    0.12       0  4995.3    0.05       0  4999.3    0.12       0
  5129.7    0.07       0
Bank Sta=4995.3,4999.3
Exp/Cntr=0.3,0.1

Chan Stop Cuts=-1