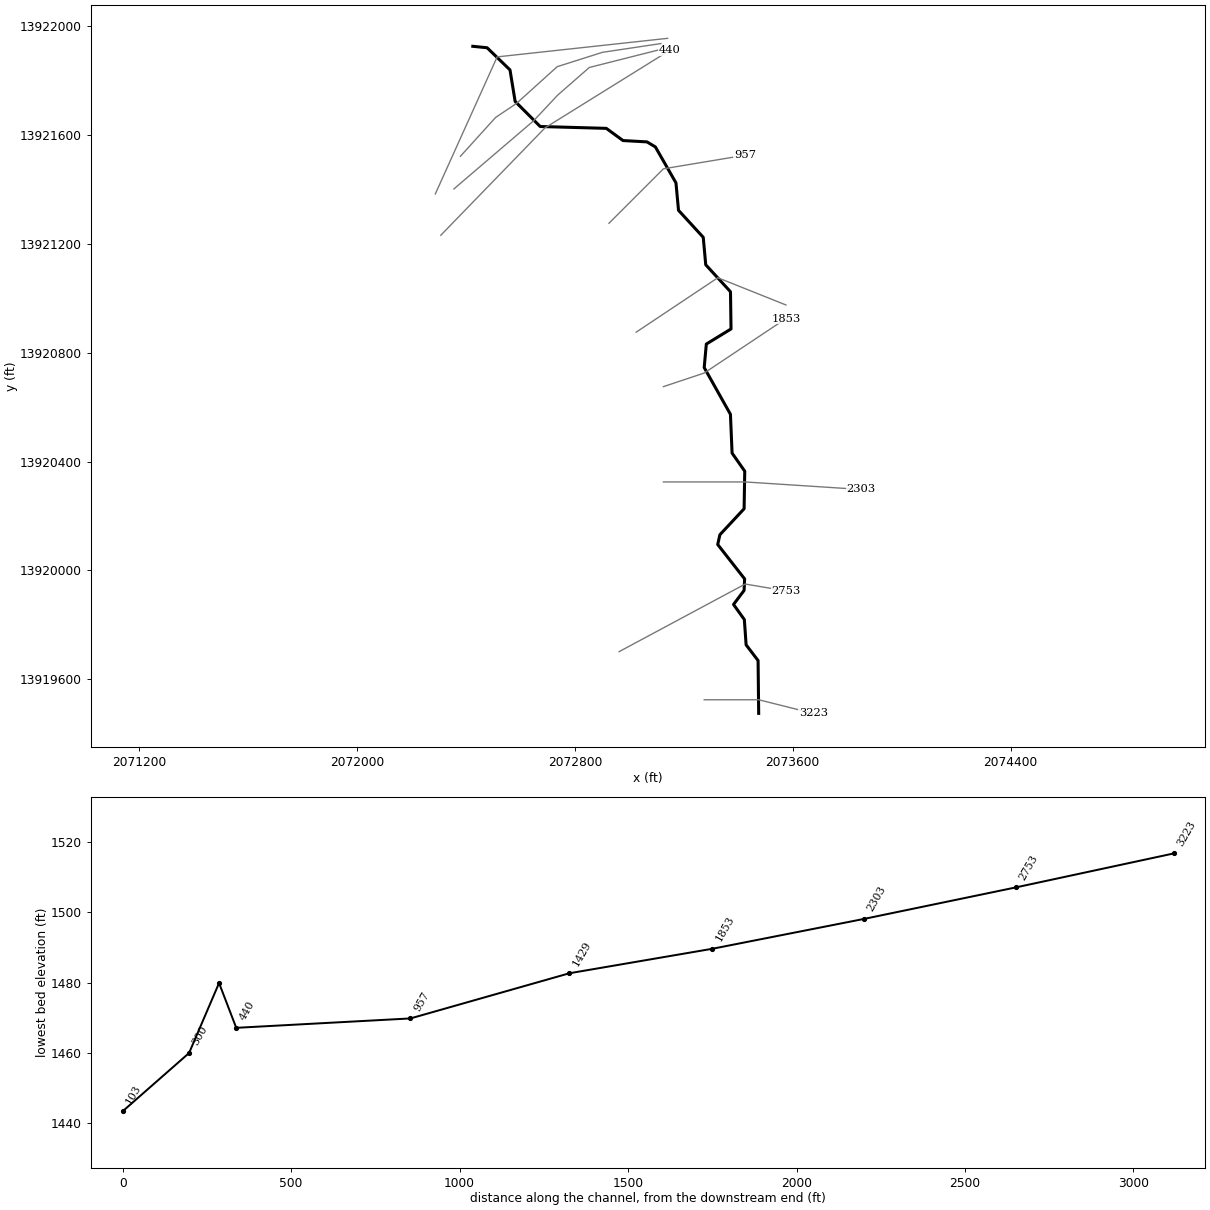
--- Stream0004_DS.prj (project) ---

Proj Title=Stream0004_DS Base Level Engineering
Current Plan=p01
Default Exp/Contr=0.3,0.1
English Units
Geom File=g01
Flow File=f01
Plan File=p01
BEGIN DESCRIPTION:
Stream0004_DS
END DESCRIPTION:

--- Stream0004_DS.p01 (plan) ---

Plan Title=Multiple Run
Short Identifier=Multiple
Geom File=g01
Flow File=f01
Subcritical Flow
K Sum by GR= 0
Std Step Tol= 0.01
Critical Tol= 0.01
Num of Std Step Trials= 20
Max Error Tol= 0.3
Flow Tol Ratio= 0.001
Split Flow NTrial= 30
Split Flow Tol= 0.02
Split Flow Ratio= 0.02
Log Output Level= 0
Friction Slope Method= 1
Unsteady Friction Slope Method= 2
Unsteady Bridges Friction Slope Method= 1
Parabolic Critical Depth
Global Vel Dist=  1 , 1 , 1
Global Log Level= 0
CheckData=True
Encroach Param= -1, 0, 0, 0
BEGIN DESCRIPTION:
Multiple Run
END DESCRIPTION:

--- Stream0004_DS.f01 (steady flow) ---

Flow Title=Multiple
Number of Profiles=7
Profile Names=10-year,25-year,50-year,1pct_min,100-year,1pct_plu,500-year
River Rch & RM= Stream0004_DS,Reach-1,3223
     420     686     932     619    1236    2466    2142
River Rch & RM= Stream0004_DS,Reach-1,2753
     648    1086    1501    1011    2017    4024    3600
Boundary for River Rch & Prof#=Stream0004_DS,Reach-1,1
Up Type=0
Dn Type=3
Dn Slope=0.005
Boundary for River Rch & Prof#=Stream0004_DS,Reach-1,2
Up Type=0
Dn Type=3
Dn Slope=0.005
Boundary for River Rch & Prof#=Stream0004_DS,Reach-1,3
Up Type=0
Dn Type=3
Dn Slope=0.005
Boundary for River Rch & Prof#=Stream0004_DS,Reach-1,4
Up Type=0
Dn Type=3
Dn Slope=0.005
Boundary for River Rch & Prof#=Stream0004_DS,Reach-1,5
Up Type=0
Dn Type=3
Dn Slope=0.005
Boundary for River Rch & Prof#=Stream0004_DS,Reach-1,6
Up Type=0
Dn Type=3
Dn Slope=0.005
Boundary for River Rch & Prof#=Stream0004_DS,Reach-1,7
Up Type=0
Dn Type=3
Dn Slope=0.005

--- Stream0004_DS.g01 (geometry) ---

Geom Title=Existing Conditions

River Reach=Stream0004_DS,Reach-1
Reach XY= 30
      2073475.00     13919475.00      2073472.75     13919669.07
      2073428.85     13919726.60      2073422.33     13919819.51
      2073382.59     13919875.01      2073421.42     13919926.65
      2073423.33     13919968.95      2073324.53     13920095.16
      2073332.48     13920131.04      2073421.46     13920226.47
      2073423.79     13920364.49      2073377.27     13920430.94
      2073371.24     13920573.44      2073274.88     13920745.10
      2073282.69     13920831.43      2073373.37     13920886.84
      2073371.46     13921023.52      2073280.54     13921122.58
      2073271.37     13921223.50      2073180.54     13921322.58
      2073171.17     13921423.42      2073095.54     13921555.54
      2073064.67     13921573.90      2072976.60     13921578.86
      2072915.34     13921623.62      2072672.53     13921630.45
      2072580.52     13921722.56      2072561.62     13921838.33
      2072477.54     13921919.70      2072425.00     13921925.00

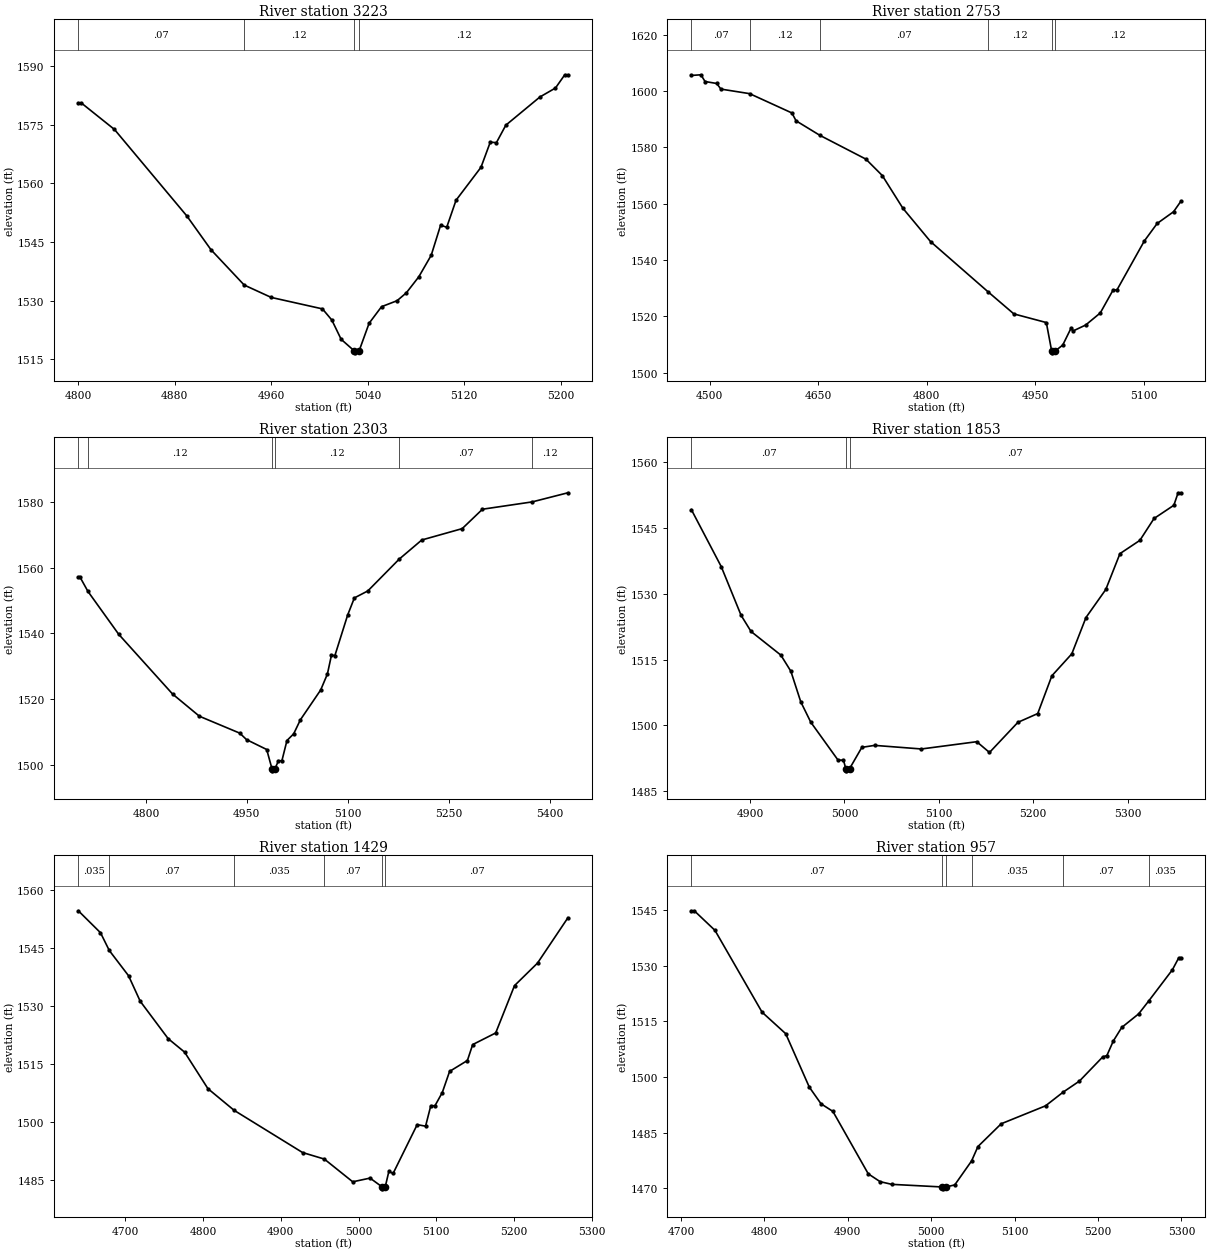
Type RM Length L Ch R = 1,3223,470,470,470
BEGIN DESCRIPTION:
Stream0004_DS 7.0
END DESCRIPTION:
XS GIS Cut Line= 3
      2073275.04     13919525.00      2073475.00     13919525.00
      2073674.98     13919475.00
#Sta/Elev= 30
  4800.0 1580.53  4802.5 1580.53  4830.0 1573.76  4890.0 1551.67  4910.0 1543.05
  4937.6 1534.01  4960.0 1530.85  5002.5 1527.92  5010.3 1525.06  5018.0 1520.15
  5028.9 1517.19  5029.1 1516.69  5032.9 1517.19  5041.2 1524.25  5051.5 1528.48
  5064.4 1530.01  5072.1 1532.03  5082.4 1536.11  5092.7 1541.61  5100.5 1549.29
  5105.6 1548.79  5113.3 1555.68  5134.0 1564.10  5141.7 1570.52  5146.8 1570.40
  5154.6 1574.86  5182.9 1582.07  5195.8 1584.36  5203.5 1587.74  5206.1 1587.74
#Mann=4,-1,0
  4800.0    0.07       0  4937.6    0.12       0  5028.9    0.05       0
  5032.9    0.12       0
Bank Sta=5028.9,5032.9
Exp/Cntr=0.3,0.1

Type RM Length L Ch R = 1,2753,450,450,450
BEGIN DESCRIPTION:
Stream0004_DS 6.0
END DESCRIPTION:
XS GIS Cut Line= 3
      2072962.29     13919701.65      2073425.40     13919950.00
      2073575.03     13919925.00
#Sta/Elev= 30
  4474.5 1605.48  4487.7 1605.72  4493.4 1603.33  4509.6 1602.63  4515.3 1600.64
  4555.1 1599.02  4613.6 1592.16  4619.3 1589.38  4652.2 1584.23  4715.9 1575.78
  4738.6 1569.95  4767.1 1558.33  4805.3 1546.52  4885.2 1528.61  4920.6 1520.83
  4965.5 1517.76  4973.0 1507.51  4973.3 1507.01  4977.0 1507.51  4988.2 1509.77
  5000.0 1515.93  5002.3 1514.75  5019.9 1516.88  5040.1 1521.16  5058.0 1529.38
  5063.1 1529.30  5101.0 1546.70  5118.8 1552.93  5141.5 1557.10  5151.7 1560.84
#Mann=6,-1,0
  4474.5    0.07       0  4555.1    0.12       0  4652.2    0.07       0
  4885.2    0.12       0  4973.0    0.05       0  4977.0    0.12       0
Bank Sta=4973,4977
Exp/Cntr=0.3,0.1

Type RM Length L Ch R = 1,2303,450,450,450
BEGIN DESCRIPTION:
Stream0004_DS 5.0
END DESCRIPTION:
XS GIS Cut Line= 3
      2073124.95     13920325.00      2073425.00     13920325.00
      2073851.76     13920297.37
#Sta/Elev= 30
  4699.5 1557.19  4702.0 1557.19  4713.8 1552.83  4759.5 1539.75  4839.5 1521.53
  4879.5 1514.73  4939.5 1509.57  4949.5 1507.60  4979.5 1504.58  4987.5 1498.57
  4987.8 1498.07  4991.5 1498.57  4997.0 1501.16  5002.1 1501.16  5009.6 1507.32
  5019.6 1509.37  5029.6 1513.66  5059.7 1522.74  5069.7 1527.61  5075.8 1533.43
  5080.8 1533.22  5099.8 1545.61  5109.8 1550.85  5129.8 1552.98  5176.4 1562.68
  5210.0 1568.53  5270.1 1572.00  5300.2 1577.92  5374.2 1580.16  5427.2 1582.94
#Mann=6,-1,0
  4699.5    0.07       0  4713.8    0.12       0  4987.5    0.05       0
  4991.5    0.12       0  5176.4    0.07       0  5374.2    0.12       0
Bank Sta=4987.5,4991.5
Exp/Cntr=0.3,0.1

Type RM Length L Ch R = 1,1853,424,424,424
BEGIN DESCRIPTION:
Stream0004_DS 4.0
END DESCRIPTION:
XS GIS Cut Line= 3
      2073125.03     13920675.01      2073275.00     13920725.00
      2073574.97     13920924.98
#Sta/Elev= 30
  4837.8 1549.20  4869.4 1536.22  4890.5 1525.07  4901.0 1521.40  4932.6 1516.00
  4943.2 1512.32  4953.7 1505.33  4964.3 1500.69  4993.2 1492.03  4998.9 1492.03
  5001.4 1490.09  5001.6 1489.59  5005.4 1490.09  5018.4 1494.95  5031.9 1495.40
  5081.5 1494.58  5140.1 1496.24  5153.6 1493.78  5183.7 1500.66  5204.7 1502.66
  5219.7 1511.29  5240.8 1516.29  5255.8 1524.58  5276.8 1530.98  5291.8 1539.16
  5312.9 1542.19  5327.9 1547.18  5348.9 1550.20  5353.4 1553.05  5356.4 1553.05
#Mann=3,-1,0
  4837.8    0.07       0  5001.4    0.05       0  5005.4    0.07       0
Bank Sta=5001.4,5005.4
Exp/Cntr=0.3,0.1

Type RM Length L Ch R = 1,1429,472,472,472
BEGIN DESCRIPTION:
Stream0004_DS 3.0
END DESCRIPTION:
XS GIS Cut Line= 3
      2073025.04     13920875.03      2073325.00     13921075.00
      2073575.03     13920974.99
#Sta/Elev= 30
  4639.5 1554.60  4668.0 1548.92  4679.3 1544.33  4704.1 1537.79  4719.1 1531.19
  4755.1 1521.50  4776.2 1518.02  4806.2 1508.57  4839.9 1502.96  4927.9 1492.04
  4956.0 1490.34  4992.5 1484.46  5014.8 1485.42  5030.3 1483.14  5030.6 1482.64
  5034.3 1483.14  5039.0 1487.18  5044.4 1486.61  5075.4 1499.25  5086.2 1498.86
  5092.9 1504.14  5098.3 1504.15  5107.7 1507.56  5117.1 1513.03  5140.0 1515.85
  5146.8 1519.97  5176.4 1522.98  5200.6 1535.23  5230.2 1541.06  5269.3 1552.79
#Mann=6,-1,0
  4639.5   0.035       0  4679.3    0.07       0  4839.9   0.035       0
  4956.0    0.07       0  5030.3    0.05       0  5034.3    0.07       0
Bank Sta=5030.3,5034.3
Exp/Cntr=0.3,0.1

Type RM Length L Ch R = 1,957,517,517,517
BEGIN DESCRIPTION:
Stream0004_DS 2.0
END DESCRIPTION:
XS GIS Cut Line= 3
      2072925.02     13921275.02      2073125.00     13921475.00
      2073425.04     13921525.01
#Sta/Elev= 30
  4712.4 1544.89  4715.9 1544.89  4740.7 1539.60  4797.2 1517.50  4825.5 1511.70
  4853.8 1497.27  4867.9 1492.76  4882.1 1490.71  4924.5 1473.85  4938.7 1471.74
  4952.8 1471.01  5013.5 1470.30  5013.7 1469.80  5017.5 1470.30  5028.2 1470.86
  5048.4 1477.34  5056.0 1481.22  5083.9 1487.37  5137.1 1492.22  5158.2 1495.92
  5177.7 1498.90  5205.6 1505.42  5210.6 1505.79  5218.3 1509.72  5228.4 1513.38
  5248.7 1517.05  5261.2 1520.66  5289.2 1528.97  5296.8 1532.20  5299.4 1532.20
#Mann=6,-1,0
  4712.4    0.07       0  5013.5    0.05       0  5017.5    0.07       0
  5048.4   0.035       0  5158.2    0.07       0  5261.2   0.035       0
Bank Sta=5013.5,5017.5
Exp/Cntr=0.3,0.1

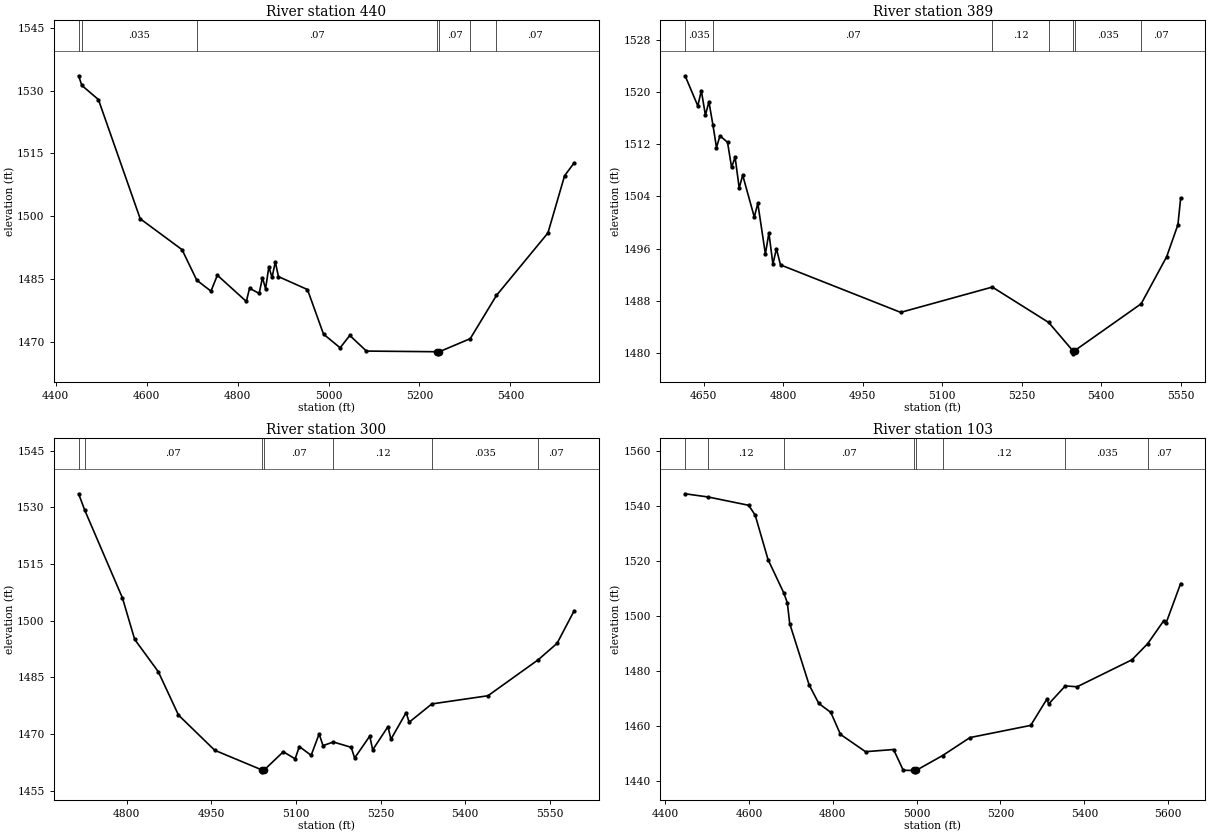
Type RM Length L Ch R = 1,440,51,51,51
BEGIN DESCRIPTION:
Stream0004_DS 1.0
END DESCRIPTION:
XS GIS Cut Line= 3
      2072307.47     13921231.03      2072690.15     13921625.38
      2073148.97     13921910.52
#Sta/Elev= 30
  4450.5 1533.56  4457.5 1531.26  4494.0 1527.88  4585.9 1499.40  4677.9 1492.02
  4710.3 1484.72  4741.5 1482.11  4755.6 1485.91  4819.2 1479.65  4826.4 1482.79
  4847.5 1481.56  4854.7 1485.33  4861.6 1482.68  4868.8 1487.91  4875.8 1485.37
  4883.0 1489.10  4889.9 1485.58  4953.7 1482.49  4989.0 1471.84  5025.5 1468.57
  5046.8 1471.52  5083.4 1467.79  5239.6 1467.63  5239.8 1467.13  5243.6 1467.63
  5311.7 1470.76  5369.2 1481.07  5482.5 1496.01  5519.1 1509.67  5540.2 1512.76
#Mann=7,-1,0
  4450.5    0.07       0  4457.5   0.035       0  4710.3    0.07       0
  5239.6    0.05       0  5243.6    0.07       0  5311.7   0.035       0
  5369.2    0.07       0
Bank Sta=5239.6,5243.6
Exp/Cntr=0.3,0.1

Type RM Length L Ch R = 1,389,89,89,89
BEGIN DESCRIPTION:
Stream0004_DS 0.2
END DESCRIPTION:
XS GIS Cut Line= 5
      2072355.55     13921401.12      2072648.06     13921651.14
      2072737.21     13921746.14      2072852.93     13921847.21
      2073110.49     13921912.38
#Sta/Elev= 30
  4615.2 1522.50  4639.2 1517.88  4645.8 1520.23  4653.5 1516.46  4660.1 1518.52
  4667.8 1514.90  4674.4 1511.49  4680.9 1513.30  4695.2 1512.30  4702.9 1508.45
  4709.5 1510.02  4717.2 1505.29  4723.8 1507.26  4745.7 1500.83  4752.3 1502.94
  4766.6 1495.16  4773.2 1498.40  4780.8 1493.62  4787.4 1495.97  4795.1 1493.50
  5021.7 1486.22  5194.5 1490.10  5300.8 1484.67  5346.0 1480.36  5346.2 1479.86
  5350.0 1480.36  5475.2 1487.54  5523.3 1494.76  5544.5 1499.67  5549.6 1503.73
#Mann=7,-1,0
  4615.2   0.035       0  4667.8    0.07       0  5194.5    0.12       0
  5300.8   0.035       0  5346.0    0.05       0  5350.0   0.035       0
  5475.2    0.07       0
Bank Sta=5346,5350
Exp/Cntr=0.3,0.1

Type RM Length L Ch R = 1,300,197,197,197
BEGIN DESCRIPTION:
Stream0004_DS 0.1
END DESCRIPTION:
XS GIS Cut Line= 6
      2072379.29     13921520.86      2072508.71     13921663.63
      2072585.51     13921715.19      2072735.02     13921850.16
      2072901.23     13921902.91      2073116.13     13921935.08
#Sta/Elev= 30
  4714.8 1533.57  4725.4 1529.31  4792.5 1505.98  4814.1 1495.04  4856.0 1486.47
  4891.8 1474.99  4956.0 1465.68  5039.7 1460.47  5040.0 1459.97  5043.7 1460.47
  5077.6 1465.28  5098.5 1463.41  5106.0 1466.66  5126.9 1464.34  5141.1 1470.00
  5147.9 1466.91  5166.2 1467.87  5197.9 1466.46  5204.0 1463.63  5230.8 1469.43
  5236.0 1465.79  5263.1 1471.94  5268.3 1468.58  5295.3 1475.66  5300.6 1473.10
  5340.9 1477.95  5440.3 1480.11  5529.4 1489.64  5562.7 1493.96  5593.1 1502.61
#Mann=7,-1,0
  4714.8    0.12       0  4725.4    0.07       0  5039.7    0.05       0
  5043.7    0.07       0  5166.2    0.12       0  5340.9   0.035       0
  5529.4    0.07       0
Bank Sta=5039.7,5043.7
Exp/Cntr=0.3,0.1

Type RM Length L Ch R = 1,103,0,0,0
BEGIN DESCRIPTION:
Stream0004_DS 0.0
END DESCRIPTION:
XS GIS Cut Line= 3
      2072287.33     13921382.70      2072514.46     13921886.14
      2073140.46     13921954.26
#Sta/Elev= 30
  4447.7 1544.30  4502.5 1543.14  4599.2 1540.13  4614.8 1536.59  4645.5 1520.45
  4683.4 1508.23  4691.6 1504.72  4697.2 1497.22  4743.5 1474.99  4766.6 1468.24
  4795.2 1465.00  4818.3 1457.01  4878.1 1450.74  4945.0 1451.53  4968.1 1443.99
  4994.6 1443.93  4994.9 1443.43  4998.6 1443.93  5061.7 1449.32  5127.2 1455.86
  5272.1 1460.28  5310.2 1469.70  5315.2 1468.10  5354.6 1474.60  5382.8 1474.29
  5513.6 1484.08  5551.3 1489.96  5589.7 1498.32  5594.7 1497.29  5629.7 1511.74
#Mann=8,-1,0
  4447.7   0.035       0  4502.5    0.12       0  4683.4    0.07       0
  4994.6    0.05       0  4998.6    0.07       0  5061.7    0.12       0
  5354.6   0.035       0  5551.3    0.07       0
Bank Sta=4994.6,4998.6
Exp/Cntr=0.3,0.1

Chan Stop Cuts=-1