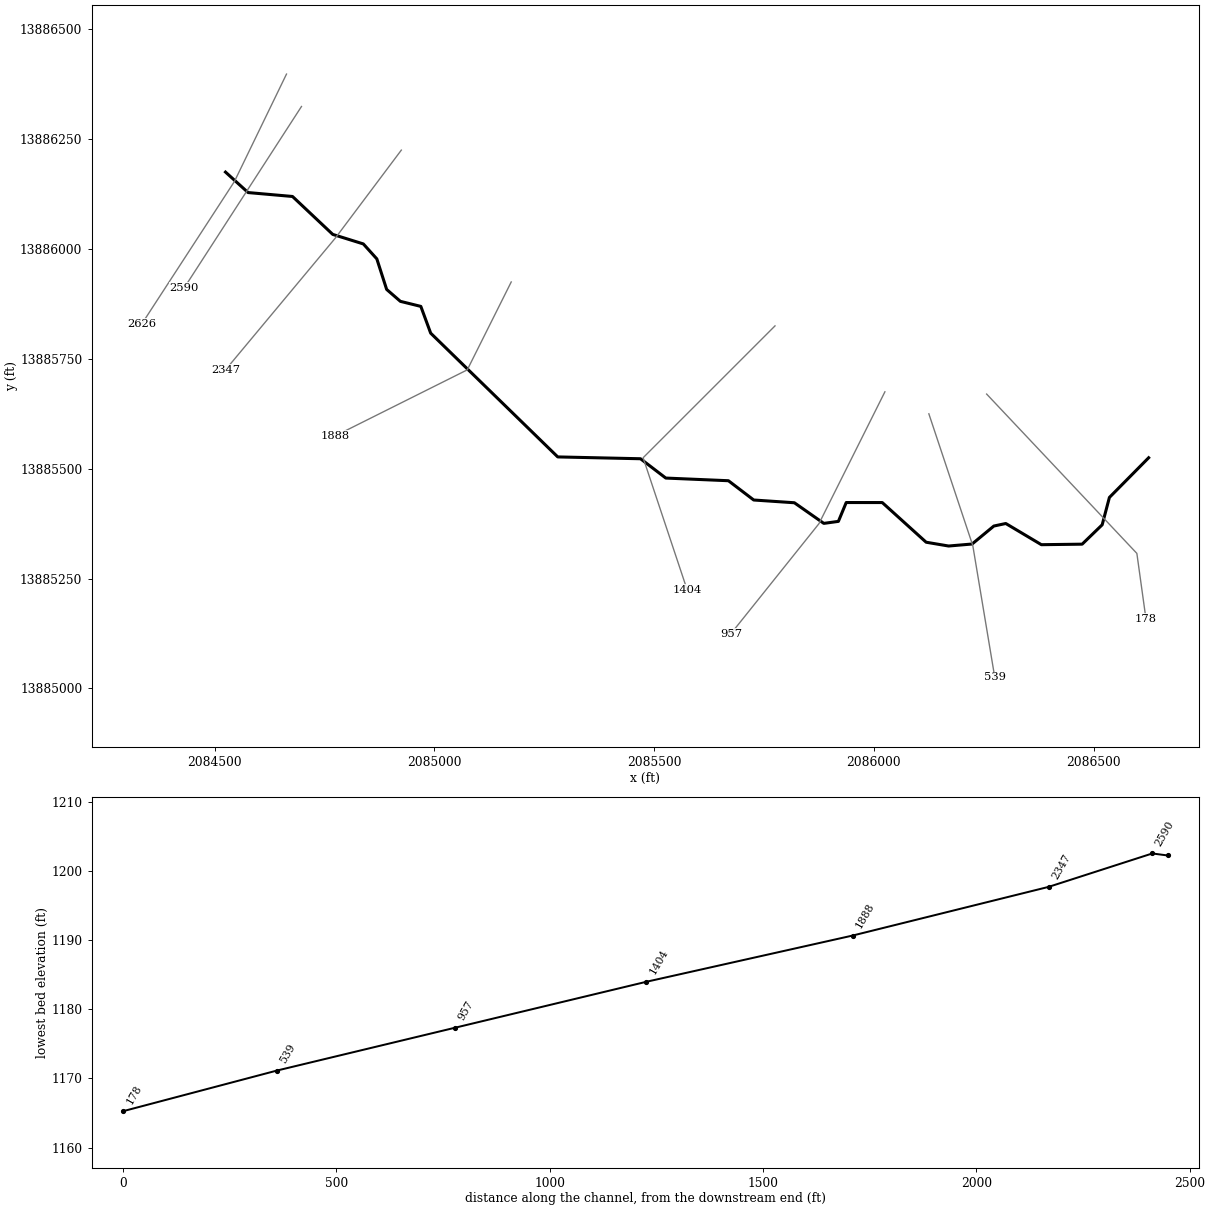
--- Stream0005_DS.prj (project) ---

Proj Title=Stream0005_DS Base Level Engineering
Current Plan=p01
Default Exp/Contr=0.3,0.1
English Units
Geom File=g01
Flow File=f01
Plan File=p01
BEGIN DESCRIPTION:
Stream0005_DS
END DESCRIPTION:

--- Stream0005_DS.p01 (plan) ---

Plan Title=Multiple Run
Short Identifier=Multiple
Geom File=g01
Flow File=f01
Subcritical Flow
K Sum by GR= 0
Std Step Tol= 0.01
Critical Tol= 0.01
Num of Std Step Trials= 20
Max Error Tol= 0.3
Flow Tol Ratio= 0.001
Split Flow NTrial= 30
Split Flow Tol= 0.02
Split Flow Ratio= 0.02
Log Output Level= 0
Friction Slope Method= 1
Unsteady Friction Slope Method= 2
Unsteady Bridges Friction Slope Method= 1
Parabolic Critical Depth
Global Vel Dist=  1 , 1 , 1
Global Log Level= 0
CheckData=True
Encroach Param= -1, 0, 0, 0
BEGIN DESCRIPTION:
Multiple Run
END DESCRIPTION:

--- Stream0005_DS.f01 (steady flow) ---

Flow Title=Multiple
Number of Profiles=7
Profile Names=10-year,25-year,50-year,1pct_min,100-year,1pct_plu,500-year
River Rch & RM= Stream0005_DS,Reach-1,2626
     768    1274    1746    1163    2320    4630    4045
River Rch & RM= Stream0005_DS,Reach-1,1404
    1023    1725    2392    1608    3208    6401    5705
Boundary for River Rch & Prof#=Stream0005_DS,Reach-1,1
Up Type=0
Dn Type=3
Dn Slope=0.005
Boundary for River Rch & Prof#=Stream0005_DS,Reach-1,2
Up Type=0
Dn Type=3
Dn Slope=0.005
Boundary for River Rch & Prof#=Stream0005_DS,Reach-1,3
Up Type=0
Dn Type=3
Dn Slope=0.005
Boundary for River Rch & Prof#=Stream0005_DS,Reach-1,4
Up Type=0
Dn Type=3
Dn Slope=0.005
Boundary for River Rch & Prof#=Stream0005_DS,Reach-1,5
Up Type=0
Dn Type=3
Dn Slope=0.005
Boundary for River Rch & Prof#=Stream0005_DS,Reach-1,6
Up Type=0
Dn Type=3
Dn Slope=0.005
Boundary for River Rch & Prof#=Stream0005_DS,Reach-1,7
Up Type=0
Dn Type=3
Dn Slope=0.005

--- Stream0005_DS.g01 (geometry) ---

Geom Title=Existing Conditions

River Reach=Stream0005_DS,Reach-1
Reach XY= 30
      2084525.00     13886175.00      2084576.41     13886128.39
      2084677.43     13886119.49      2084768.98     13886033.19
      2084838.56     13886011.51      2084869.24     13885977.51
      2084891.58     13885907.99      2084922.80     13885880.89
      2084969.35     13885869.37      2084991.73     13885808.52
      2085280.78     13885526.89      2085469.06     13885522.74
      2085526.57     13885478.79      2085669.06     13885472.73
      2085726.60     13885428.86      2085819.06     13885422.61
      2085886.04     13885375.68      2085919.21     13885380.22
      2085937.00     13885423.10      2086019.02     13885423.06
      2086118.84     13885332.78      2086169.96     13885324.16
      2086223.41     13885328.73      2086272.82     13885369.62
      2086300.00     13885375.40      2086380.97     13885327.19
      2086473.72     13885328.37      2086519.27     13885372.42
      2086535.72     13885434.69      2086625.00     13885525.00

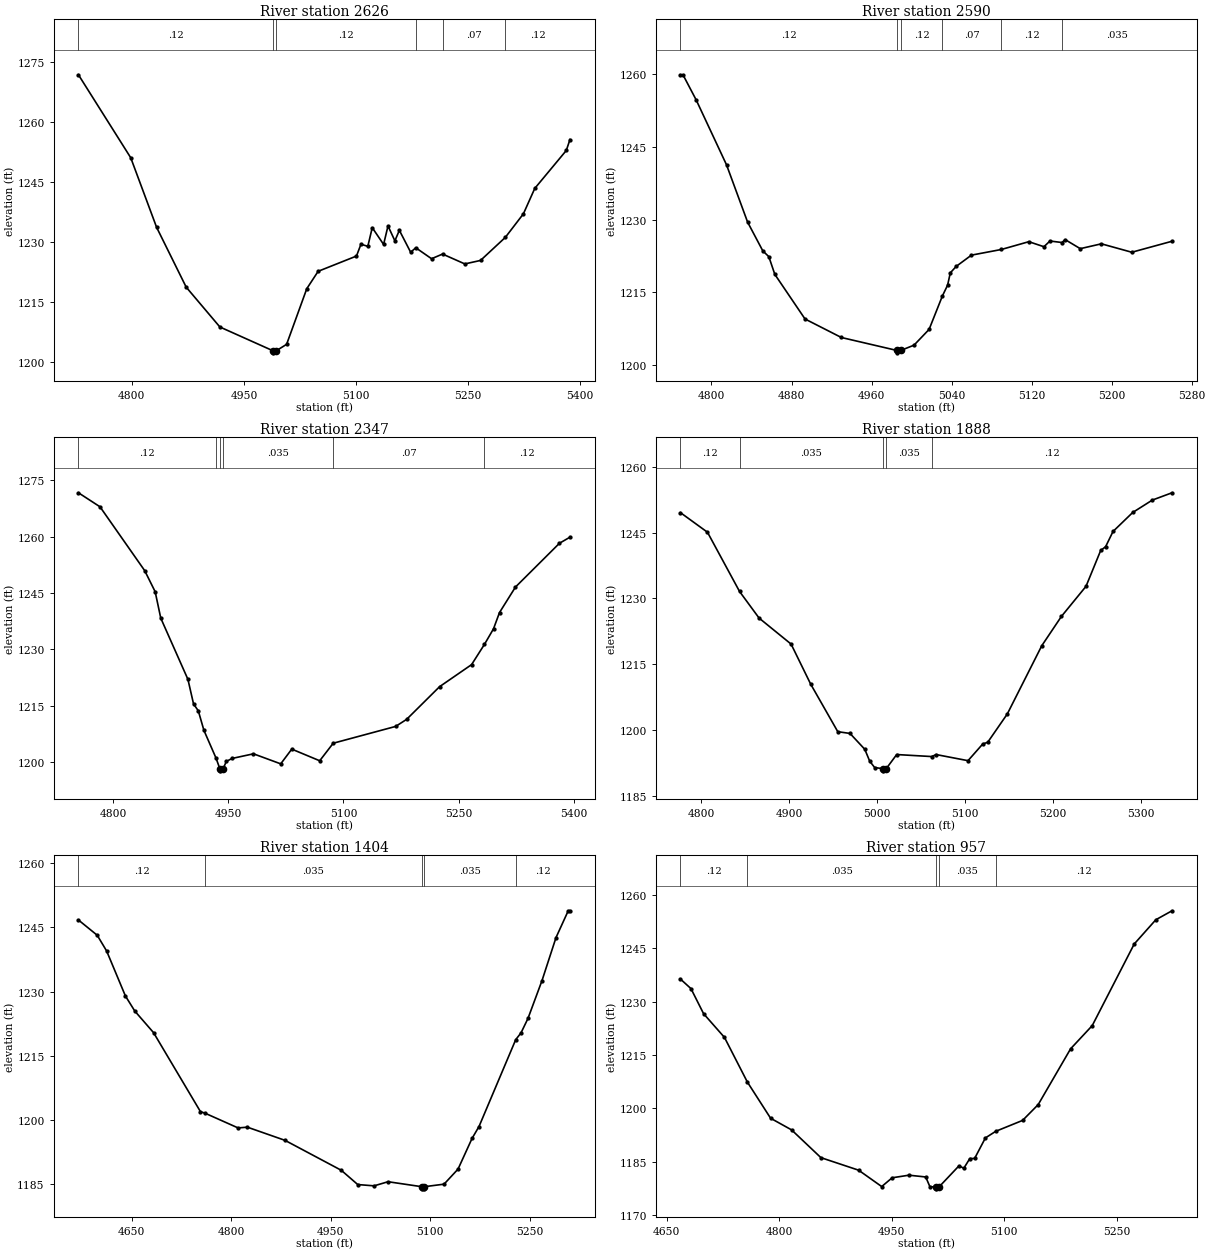
Type RM Length L Ch R = 1,2626,36,36,36
BEGIN DESCRIPTION:
Stream0005_DS 7.0
END DESCRIPTION:
XS GIS Cut Line= 3
      2084663.74     13886397.95      2084545.33     13886153.63
      2084334.78     13885829.75
#Sta/Elev= 30
  4728.5 1271.82  4798.5 1251.05  4833.1 1233.64  4872.7 1218.66  4917.8 1208.68
  4989.1 1202.71  4989.4 1202.21  4993.1 1202.71  5007.1 1204.34  5034.1 1218.27
  5049.3 1222.62  5100.6 1226.44  5106.6 1229.40  5115.8 1228.87  5121.7 1233.55
  5136.9 1229.35  5142.8 1233.98  5152.0 1230.25  5158.0 1232.88  5173.1 1227.40
  5180.0 1228.51  5201.1 1225.77  5215.8 1226.94  5245.6 1224.47  5266.6 1225.34
  5299.8 1231.11  5324.0 1237.01  5339.2 1243.37  5381.4 1252.87  5386.3 1255.60
#Mann=6,-1,0
  4728.5    0.12       0  4989.1    0.05       0  4993.1    0.12       0
  5180.0   0.035       0  5215.8    0.07       0  5299.8    0.12       0
Bank Sta=4989.1,4993.1
Exp/Cntr=0.3,0.1

Type RM Length L Ch R = 1,2590,243,243,243
BEGIN DESCRIPTION:
Stream0005_DS 6.0
END DESCRIPTION:
XS GIS Cut Line= 2
      2084697.84     13886324.23      2084431.11     13885911.64
#Sta/Elev= 30
  4769.0 1259.94  4771.5 1259.94  4784.7 1254.74  4815.0 1241.35  4836.1 1229.50
  4851.3 1223.56  4857.3 1222.37  4863.3 1218.71  4893.5 1209.49  4929.8 1205.67
  4985.2 1203.00  4985.5 1202.50  4989.2 1203.00  5002.4 1204.08  5017.5 1207.34
  5030.8 1214.25  5036.0 1216.48  5038.7 1219.02  5044.6 1220.36  5059.8 1222.68
  5089.7 1223.85  5117.2 1225.46  5132.3 1224.42  5138.3 1225.60  5150.3 1225.29
  5153.5 1225.89  5168.6 1224.02  5189.7 1225.02  5220.1 1223.28  5260.3 1225.55
#Mann=6,-1,0
  4769.0    0.12       0  4985.2    0.05       0  4989.2    0.12       0
  5030.8    0.07       0  5089.7    0.12       0  5150.3   0.035       0
Bank Sta=4985.2,4989.2
Exp/Cntr=0.3,0.1

Type RM Length L Ch R = 1,2347,459,459,459
BEGIN DESCRIPTION:
Stream0005_DS 5.0
END DESCRIPTION:
XS GIS Cut Line= 3
      2084924.98     13886224.97      2084775.00     13886025.00
      2084524.99     13885724.98
#Sta/Elev= 30
  4754.6 1271.68  4782.7 1267.95  4841.0 1250.94  4854.6 1245.34  4861.9 1238.31
  4897.3 1222.01  4904.6 1215.47  4910.8 1213.65  4918.1 1208.46  4933.8 1201.11
  4939.0 1198.17  4939.3 1197.67  4943.0 1198.17  4947.3 1200.16  4954.6 1200.96
  4982.7 1202.20  5018.2 1199.53  5032.6 1203.45  5069.0 1200.35  5086.6 1205.02
  5167.9 1209.49  5182.2 1211.36  5225.2 1220.07  5266.9 1225.94  5283.7 1231.34
  5295.5 1235.48  5303.3 1239.80  5324.1 1246.59  5381.4 1258.24  5395.1 1259.86
#Mann=6,-1,0
  4754.6    0.12       0  4933.8   0.035       0  4939.0   0.035       0
  4943.0   0.035       0  5086.6    0.07       0  5283.7    0.12       0
Bank Sta=4939,4943
Exp/Cntr=0.3,0.1

Type RM Length L Ch R = 1,1888,484,484,484
BEGIN DESCRIPTION:
Stream0005_DS 4.0
END DESCRIPTION:
XS GIS Cut Line= 3
      2085174.99     13885924.98      2085075.00     13885725.00
      2084774.99     13885575.00
#Sta/Elev= 30
  4776.4 1249.59  4807.1 1245.12  4843.6 1231.59  4865.8 1225.52  4902.2 1219.58
  4924.5 1210.43  4955.3 1199.58  4969.2 1199.18  4986.0 1195.56  4991.6 1192.85
  4997.2 1191.40  5006.4 1191.14  5006.6 1190.64  5010.4 1191.14  5022.3 1194.36
  5062.2 1193.90  5067.1 1194.36  5103.4 1192.96  5120.2 1196.78  5125.8 1197.16
  5148.1 1203.63  5187.3 1219.21  5209.6 1225.89  5237.6 1232.77  5254.3 1240.96
  5259.9 1241.82  5268.3 1245.29  5290.7 1249.63  5313.0 1252.46  5335.4 1254.13
#Mann=5,-1,0
  4776.4    0.12       0  4843.6   0.035       0  5006.4   0.035       0
  5010.4   0.035       0  5062.2    0.12       0
Bank Sta=5006.4,5010.4
Exp/Cntr=0.3,0.1

Type RM Length L Ch R = 1,1404,447,447,447
BEGIN DESCRIPTION:
Stream0005_DS 3.0
END DESCRIPTION:
XS GIS Cut Line= 3
      2085775.03     13885825.03      2085475.00     13885525.00
      2085574.99     13885225.04
#Sta/Elev= 30
  4569.9 1246.70  4598.2 1243.14  4612.4 1239.46  4640.7 1228.96  4654.8 1225.45
  4683.1 1220.40  4753.8 1201.95  4760.3 1201.63  4810.4 1198.17  4824.5 1198.34
  4881.1 1195.27  4965.9 1188.28  4990.7 1184.95  5015.3 1184.65  5036.4 1185.61
  5087.1 1184.45  5087.3 1183.95  5090.8 1183.95  5091.1 1184.45  5120.7 1185.04
  5141.8 1188.56  5162.9 1195.72  5173.4 1198.50  5228.7 1218.77  5236.7 1220.36
  5247.2 1223.74  5268.3 1232.56  5289.4 1242.60  5307.8 1248.85  5310.4 1248.85
#Mann=5,-1,0
  4569.9    0.12       0  4760.3   0.035       0  5087.1   0.035       0
  5091.1   0.035       0  5228.7    0.12       0
Bank Sta=5087.1,5091.1
Exp/Cntr=0.3,0.1

Type RM Length L Ch R = 1,957,418,418,418
BEGIN DESCRIPTION:
Stream0005_DS 2.0
END DESCRIPTION:
XS GIS Cut Line= 3
      2086025.02     13885675.04      2085875.00     13885375.00
      2085675.01     13885125.01
#Sta/Elev= 30
  4668.4 1236.36  4682.4 1233.68  4699.2 1226.63  4727.1 1219.94  4757.6 1207.39
  4788.6 1197.20  4816.6 1193.92  4855.7 1186.11  4906.0 1182.58  4936.8 1177.97
  4950.7 1180.44  4973.1 1181.17  4995.5 1180.67  5001.1 1177.93  5009.1 1177.83
  5009.3 1177.33  5013.1 1177.83  5039.9 1183.81  5046.3 1183.12  5054.3 1185.85
  5060.7 1185.87  5075.1 1191.66  5088.9 1193.52  5124.7 1196.59  5145.5 1201.03
  5188.7 1216.73  5217.6 1223.27  5273.6 1246.24  5302.4 1253.06  5324.0 1255.59
#Mann=5,-1,0
  4668.4    0.12       0  4757.6   0.035       0  5009.1   0.035       0
  5013.1   0.035       0  5088.9    0.12       0
Bank Sta=5009.1,5013.1
Exp/Cntr=0.3,0.1

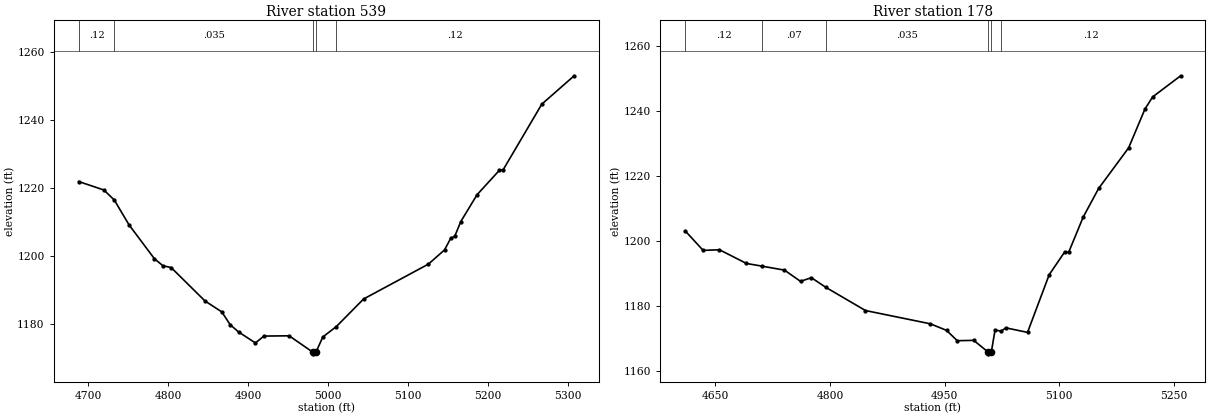
Type RM Length L Ch R = 1,539,361,361,361
BEGIN DESCRIPTION:
Stream0005_DS 1.0
END DESCRIPTION:
XS GIS Cut Line= 3
      2086125.01     13885624.97      2086225.00     13885325.00
      2086275.00     13885025.03
#Sta/Elev= 30
  4687.9 1221.87  4719.5 1219.37  4732.6 1216.40  4751.1 1209.07  4782.7 1199.15
  4793.3 1197.09  4803.8 1196.52  4846.0 1186.71  4867.1 1183.48  4877.6 1179.71
  4888.1 1177.57  4909.2 1174.34  4919.8 1176.36  4951.4 1176.44  4981.0 1171.63
  4981.3 1171.13  4985.0 1171.63  4993.6 1176.11  5010.4 1179.14  5044.6 1187.28
  5125.7 1197.54  5146.0 1201.75  5153.6 1205.13  5158.7 1205.74  5166.3 1210.08
  5186.6 1217.97  5214.5 1225.15  5219.5 1225.40  5267.7 1244.65  5308.2 1253.00
#Mann=5,-1,0
  4687.9    0.12       0  4732.6   0.035       0  4981.0   0.035       0
  4985.0   0.035       0  5010.4    0.12       0
Bank Sta=4981,4985
Exp/Cntr=0.3,0.1

Type RM Length L Ch R = 1,178,0,0,0
BEGIN DESCRIPTION:
Stream0005_DS 0.0
END DESCRIPTION:
XS GIS Cut Line= 3
      2086256.45     13885669.92      2086598.18     13885307.36
      2086618.82     13885158.71
#Sta/Elev= 30
  4610.4 1203.11  4634.0 1197.08  4655.4 1197.27  4690.6 1193.06  4711.4 1192.21
  4740.4 1191.01  4761.4 1187.55  4775.6 1188.68  4794.3 1185.74  4846.4 1178.57
  4931.3 1174.49  4952.4 1172.47  4966.5 1169.29  4988.0 1169.40  5007.0 1165.75
  5007.3 1165.25  5011.0 1165.75  5015.9 1172.59  5023.8 1172.22  5030.0 1173.25
  5058.4 1171.85  5086.7 1189.58  5106.8 1196.54  5112.3 1196.54  5131.2 1207.32
  5151.4 1216.12  5190.7 1228.65  5212.0 1240.56  5222.1 1244.30  5258.7 1250.80
#Mann=6,-1,0
  4610.4    0.12       0  4711.4    0.07       0  4794.3   0.035       0
  5007.0   0.035       0  5011.0   0.035       0  5023.8    0.12       0
Bank Sta=5007,5011
Exp/Cntr=0.3,0.1

Chan Stop Cuts=-1