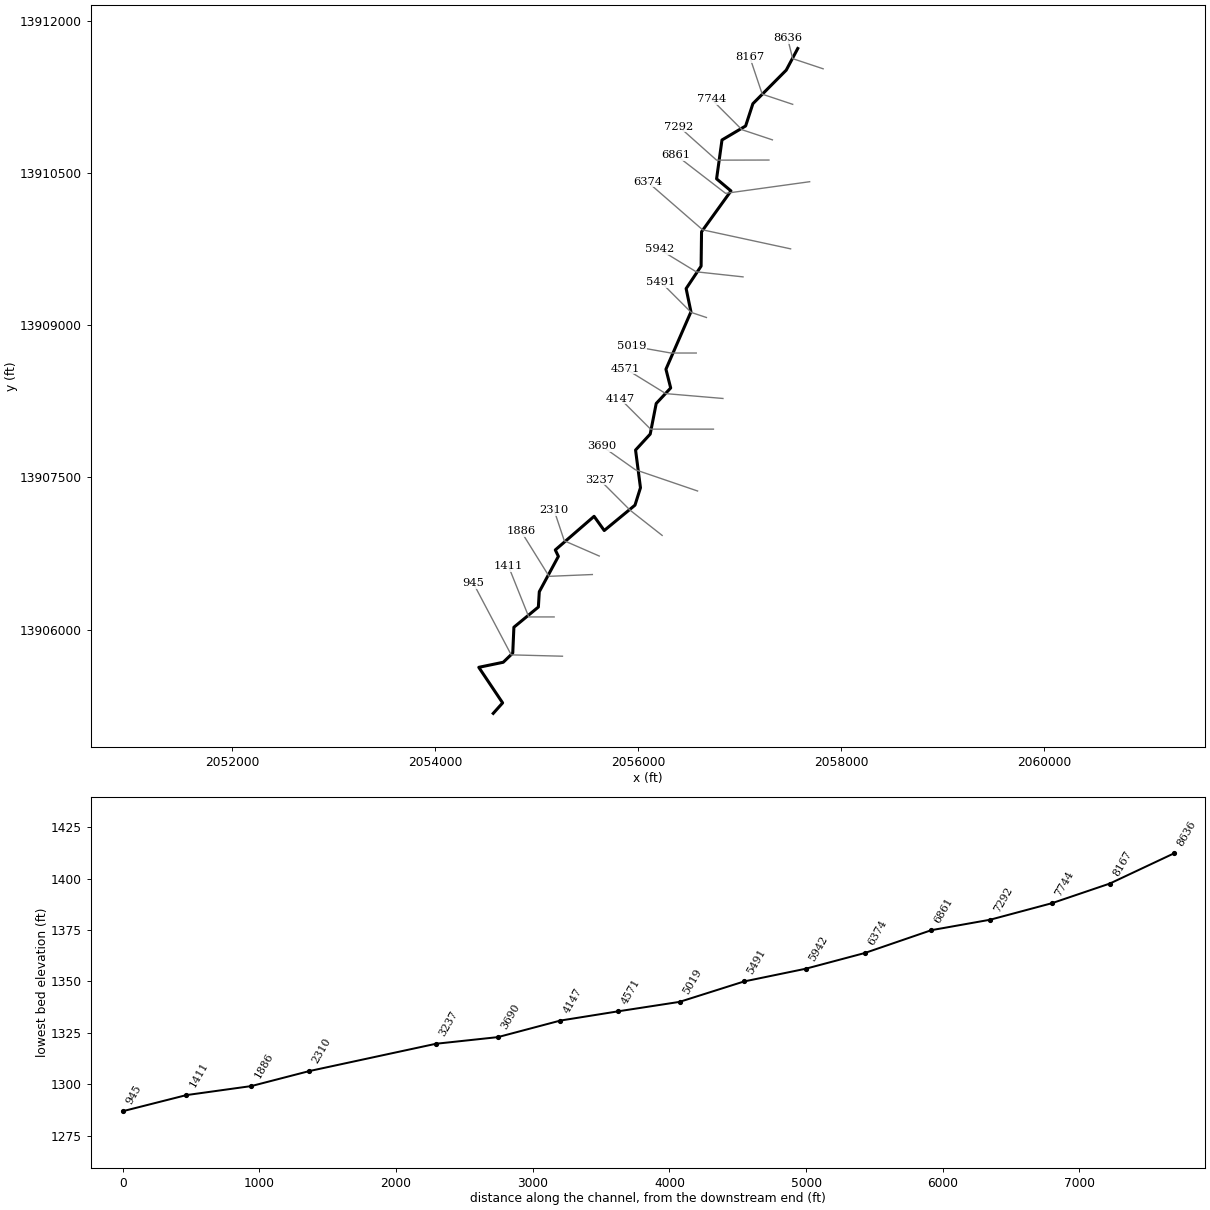
--- Stream0006_DS.prj (project) ---

Proj Title=Stream0006_DS Base Level Engineering
Current Plan=p01
Default Exp/Contr=0.3,0.1
English Units
Geom File=g01
Flow File=f01
Plan File=p01
BEGIN DESCRIPTION:
Stream0006_DS
END DESCRIPTION:

--- Stream0006_DS.p01 (plan) ---

Plan Title=Multiple Run
Short Identifier=Multiple
Geom File=g01
Flow File=f01
Subcritical Flow
K Sum by GR= 0
Std Step Tol= 0.01
Critical Tol= 0.01
Num of Std Step Trials= 20
Max Error Tol= 0.3
Flow Tol Ratio= 0.001
Split Flow NTrial= 30
Split Flow Tol= 0.02
Split Flow Ratio= 0.02
Log Output Level= 0
Friction Slope Method= 1
Unsteady Friction Slope Method= 2
Unsteady Bridges Friction Slope Method= 1
Parabolic Critical Depth
Global Vel Dist=  1 , 1 , 1
Global Log Level= 0
CheckData=True
Encroach Param= -1, 0, 0, 0
BEGIN DESCRIPTION:
Multiple Run
END DESCRIPTION:

--- Stream0006_DS.f01 (steady flow) ---

Flow Title=Multiple
Number of Profiles=7
Profile Names=10-year,25-year,50-year,1pct_min,100-year,1pct_plu,500-year
River Rch & RM= Stream0006_DS,Reach-1,8636
     242     374     490     313     625    1248    1004
River Rch & RM= Stream0006_DS,Reach-1,7744
    1144    1940    2699    1820    3631    7245    6499
Boundary for River Rch & Prof#=Stream0006_DS,Reach-1,1
Up Type=0
Dn Type=3
Dn Slope=0.005
Boundary for River Rch & Prof#=Stream0006_DS,Reach-1,2
Up Type=0
Dn Type=3
Dn Slope=0.005
Boundary for River Rch & Prof#=Stream0006_DS,Reach-1,3
Up Type=0
Dn Type=3
Dn Slope=0.005
Boundary for River Rch & Prof#=Stream0006_DS,Reach-1,4
Up Type=0
Dn Type=3
Dn Slope=0.005
Boundary for River Rch & Prof#=Stream0006_DS,Reach-1,5
Up Type=0
Dn Type=3
Dn Slope=0.005
Boundary for River Rch & Prof#=Stream0006_DS,Reach-1,6
Up Type=0
Dn Type=3
Dn Slope=0.005
Boundary for River Rch & Prof#=Stream0006_DS,Reach-1,7
Up Type=0
Dn Type=3
Dn Slope=0.005

--- Stream0006_DS.g01 (geometry) ---

Geom Title=Existing Conditions

River Reach=Stream0006_DS,Reach-1
Reach XY= 30
      2057575.00     13911725.00      2057461.37     13911511.79
      2057132.86     13911181.17      2057061.39     13910961.76
      2056828.44     13910823.77      2056775.29     13910441.04
      2056917.17     13910321.78      2056627.06     13909919.15
      2056622.76     13909580.93      2056475.25     13909359.78
      2056522.74     13909130.56      2056276.27     13908565.29
      2056323.09     13908380.68      2056180.46     13908227.66
      2056121.46     13907926.47      2055977.06     13907769.15
      2056025.38     13907397.81      2055971.48     13907226.28
      2055668.48     13906976.38      2055568.51     13907116.10
      2055186.24     13906785.00      2055216.75     13906721.77
      2055028.76     13906373.44      2055019.54     13906222.54
      2054778.53     13906023.55      2054767.20     13905768.79
      2054673.55     13905678.53      2054432.65     13905628.70
      2054667.48     13905278.33      2054575.00     13905175.00

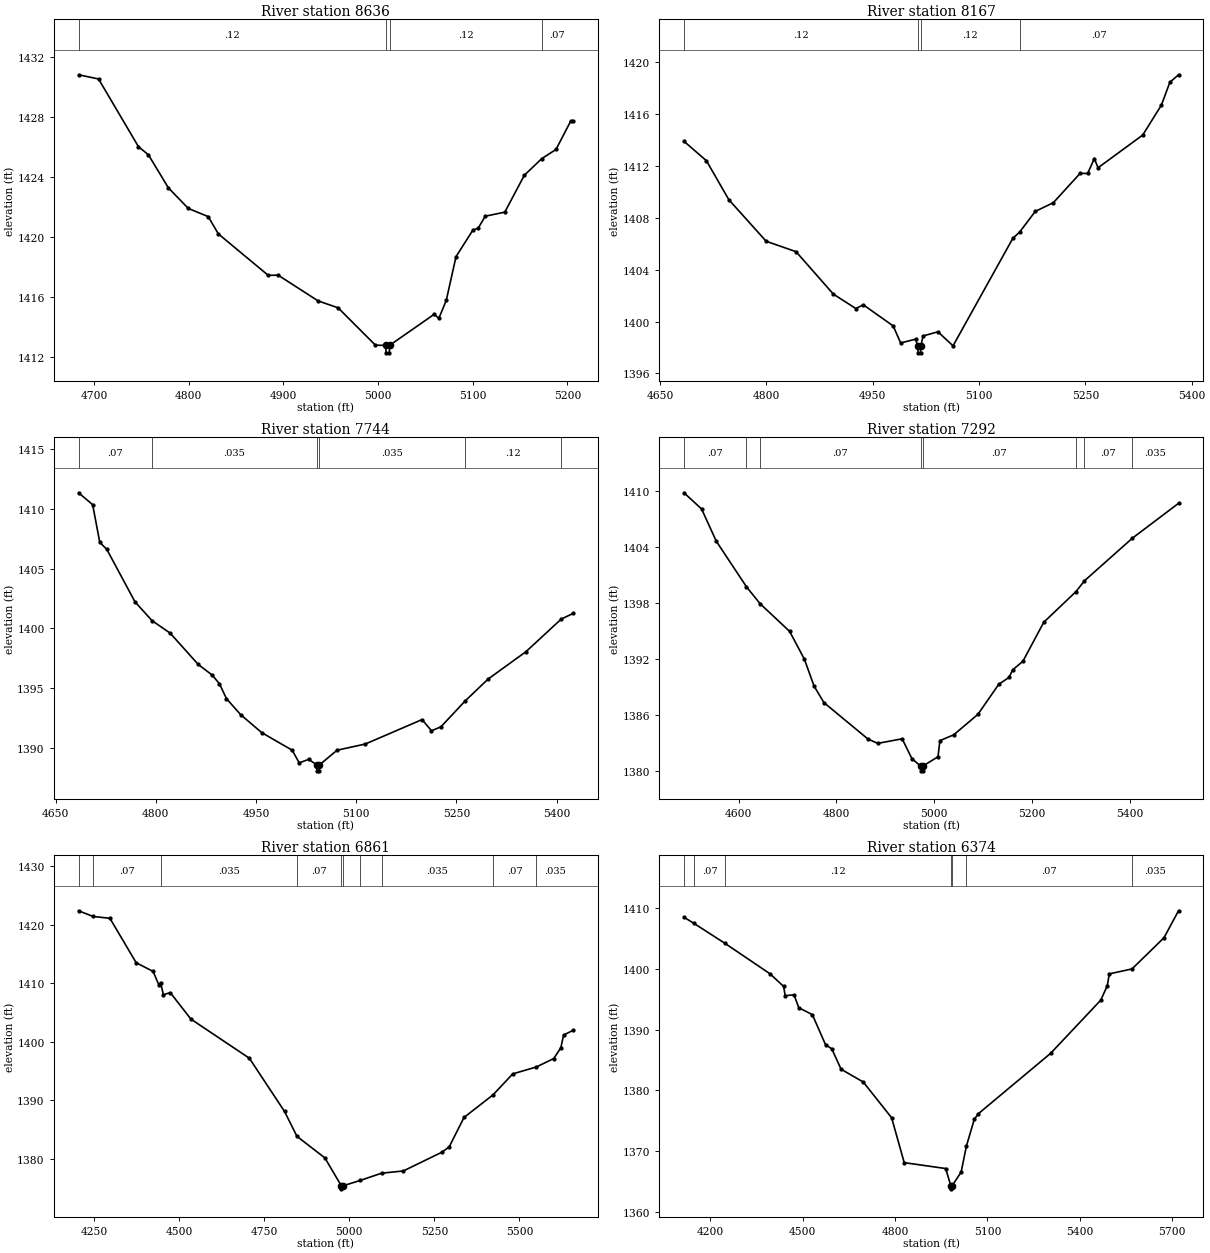
Type RM Length L Ch R = 1,8636,469,469,469
BEGIN DESCRIPTION:
Stream0006_DS 16.0
END DESCRIPTION:
XS GIS Cut Line= 3
      2057824.99     13911525.00      2057525.00     13911625.00
      2057474.99     13911825.03
#Sta/Elev= 30
  4683.7 1430.84  4704.8 1430.56  4746.9 1426.04  4757.5 1425.49  4778.6 1423.28
  4799.6 1421.91  4820.7 1421.36  4831.3 1420.21  4884.0 1417.44  4894.5 1417.45
  4936.7 1415.73  4957.8 1415.27  4997.3 1412.77  5008.2 1412.76  5008.5 1412.26
  5012.0 1412.26  5012.2 1412.76  5059.2 1414.83  5064.3 1414.57  5072.1 1415.77
  5082.4 1418.69  5100.4 1420.48  5105.6 1420.57  5113.3 1421.39  5133.9 1421.66
  5154.5 1424.12  5172.8 1425.23  5188.0 1425.85  5203.5 1427.74  5206.1 1427.74
#Mann=4,-1,0
  4683.7    0.12       0  5008.2    0.05       0  5012.2    0.12       0
  5172.8    0.07       0
Bank Sta=5008.2,5012.2
Exp/Cntr=0.3,0.1

Type RM Length L Ch R = 1,8167,423,423,423
BEGIN DESCRIPTION:
Stream0006_DS 15.0
END DESCRIPTION:
XS GIS Cut Line= 3
      2057525.03     13911174.99      2057225.00     13911275.00
      2057103.48     13911636.57
#Sta/Elev= 30
  4683.7 1413.88  4715.4 1412.38  4747.0 1409.38  4799.7 1406.18  4841.8 1405.38
  4894.5 1402.11  4926.2 1401.00  4936.7 1401.29  4978.9 1399.66  4989.4 1398.35
  5010.4 1398.64  5013.7 1398.09  5014.0 1397.59  5017.5 1397.59  5017.7 1398.09
  5021.1 1398.89  5042.0 1399.21  5063.3 1398.13  5147.7 1406.41  5157.3 1406.89
  5179.3 1408.48  5204.8 1409.15  5242.6 1411.41  5253.2 1411.40  5262.6 1412.55
  5267.9 1411.84  5330.9 1414.36  5357.2 1416.66  5369.2 1418.42  5381.4 1419.00
#Mann=4,-1,0
  4683.7    0.12       0  5013.7    0.05       0  5017.7    0.12       0
  5157.3    0.07       0
Bank Sta=5013.7,5017.7
Exp/Cntr=0.3,0.1

Type RM Length L Ch R = 1,7744,452,452,452
BEGIN DESCRIPTION:
Stream0006_DS 14.0
END DESCRIPTION:
XS GIS Cut Line= 3
      2057325.03     13910824.99      2057025.00     13910925.00
      2056725.02     13911224.98
#Sta/Elev= 30
  4684.3 1411.37  4705.4 1410.37  4716.0 1407.21  4726.5 1406.63  4768.7 1402.23
  4794.2 1400.65  4821.4 1399.60  4863.5 1396.97  4884.6 1396.07  4895.2 1395.35
  4905.7 1394.11  4926.8 1392.77  4958.4 1391.26  5004.1 1389.78  5014.7 1388.72
  5028.8 1389.01  5041.0 1388.55  5041.2 1388.05  5044.7 1388.05  5045.0 1388.55
  5071.3 1389.78  5113.7 1390.30  5198.6 1392.35  5212.7 1391.41  5226.8 1391.74
  5263.1 1393.91  5297.5 1395.75  5354.1 1398.04  5407.0 1400.78  5424.8 1401.25
#Mann=6,-1,0
  4684.3    0.07       0  4794.2   0.035       0  5041.0   0.035       0
  5045.0   0.035       0  5263.1    0.12       0  5407.0   0.035       0
Bank Sta=5041,5045
Exp/Cntr=0.3,0.1

Type RM Length L Ch R = 1,7292,431,431,431
BEGIN DESCRIPTION:
Stream0006_DS 13.0
END DESCRIPTION:
XS GIS Cut Line= 3
      2057291.00     13910626.16      2056775.00     13910625.00
      2056405.55     13910954.30
#Sta/Elev= 30
  4488.3 1409.78  4524.3 1408.05  4554.3 1404.60  4616.0 1399.72  4643.8 1397.91
  4704.3 1394.94  4734.3 1391.98  4754.3 1389.08  4774.3 1387.32  4864.3 1383.42
  4884.3 1382.95  4934.3 1383.44  4954.3 1381.31  4972.3 1380.51  4972.5 1380.01
  4976.0 1380.01  4976.3 1380.51  5007.6 1381.52  5011.4 1383.24  5039.8 1383.87
  5089.2 1386.06  5131.8 1389.28  5152.7 1390.01  5160.2 1390.82  5181.1 1391.74
  5223.8 1395.92  5289.8 1399.21  5306.8 1400.35  5404.9 1404.92  5499.2 1408.65
#Mann=8,-1,0
  4488.3    0.07       0  4616.0   0.035       0  4643.8    0.07       0
  4972.3    0.05       0  4976.3    0.07       0  5289.8   0.035       0
  5306.8    0.07       0  5404.9   0.035       0
Bank Sta=4972.3,4976.3
Exp/Cntr=0.3,0.1

Type RM Length L Ch R = 1,6861,487,487,487
BEGIN DESCRIPTION:
Stream0006_DS 12.0
END DESCRIPTION:
XS GIS Cut Line= 3
      2057691.98     13910412.61      2056863.90     13910298.03
      2056375.02     13910674.98
#Sta/Elev= 30
  4204.4 1422.37  4247.0 1421.40  4296.4 1421.09  4373.7 1413.50  4423.4 1412.02
  4440.5 1409.69  4445.2 1410.12  4453.7 1408.04  4473.9 1408.40  4534.5 1403.88
  4706.1 1397.21  4809.6 1388.12  4846.1 1383.87  4928.2 1380.19  4976.7 1375.41
  4976.9 1374.91  4980.7 1375.41  5032.8 1376.36  5094.7 1377.58  5158.6 1377.96
  5272.7 1381.18  5293.5 1382.07  5337.1 1387.10  5422.1 1390.94  5480.2 1394.53
  5549.6 1395.71  5600.7 1397.15  5621.5 1398.98  5629.7 1401.17  5657.7 1401.96
#Mann=10,-1,0
  4204.4    0.12       0  4247.0    0.07       0  4445.2   0.035       0
  4846.1    0.07       0  4976.7    0.05       0  4980.7    0.07       0
  5032.8    0.12       0  5094.7   0.035       0  5422.1    0.07       0
  5549.6   0.035       0
Bank Sta=4976.7,4980.7
Exp/Cntr=0.3,0.1

Type RM Length L Ch R = 1,6374,432,432,432
BEGIN DESCRIPTION:
Stream0006_DS 11.0
END DESCRIPTION:
XS GIS Cut Line= 3
      2057504.48     13909751.17      2056638.37     13909938.32
      2056094.59     13910411.29
#Sta/Elev= 30
  4113.9 1408.48  4146.3 1407.47  4247.8 1404.16  4393.6 1399.17  4437.7 1397.10
  4442.8 1395.57  4471.4 1395.72  4487.0 1393.60  4531.1 1392.45  4573.8 1387.52
  4594.2 1386.83  4624.5 1383.47  4696.5 1381.37  4788.6 1375.49  4829.5 1368.11
  4964.1 1367.14  4981.0 1364.30  4981.2 1363.80  4985.0 1364.30  5014.4 1366.55
  5031.7 1370.87  5057.2 1375.24  5070.7 1376.17  5305.0 1386.08  5468.3 1394.85
  5489.2 1397.21  5495.8 1399.16  5569.8 1399.98  5673.4 1405.10  5720.7 1409.54
#Mann=7,-1,0
  4113.9   0.035       0  4146.3    0.07       0  4247.8    0.12       0
  4981.0    0.05       0  4985.0    0.12       0  5031.7    0.07       0
  5569.8   0.035       0
Bank Sta=4981,4985
Exp/Cntr=0.3,0.1

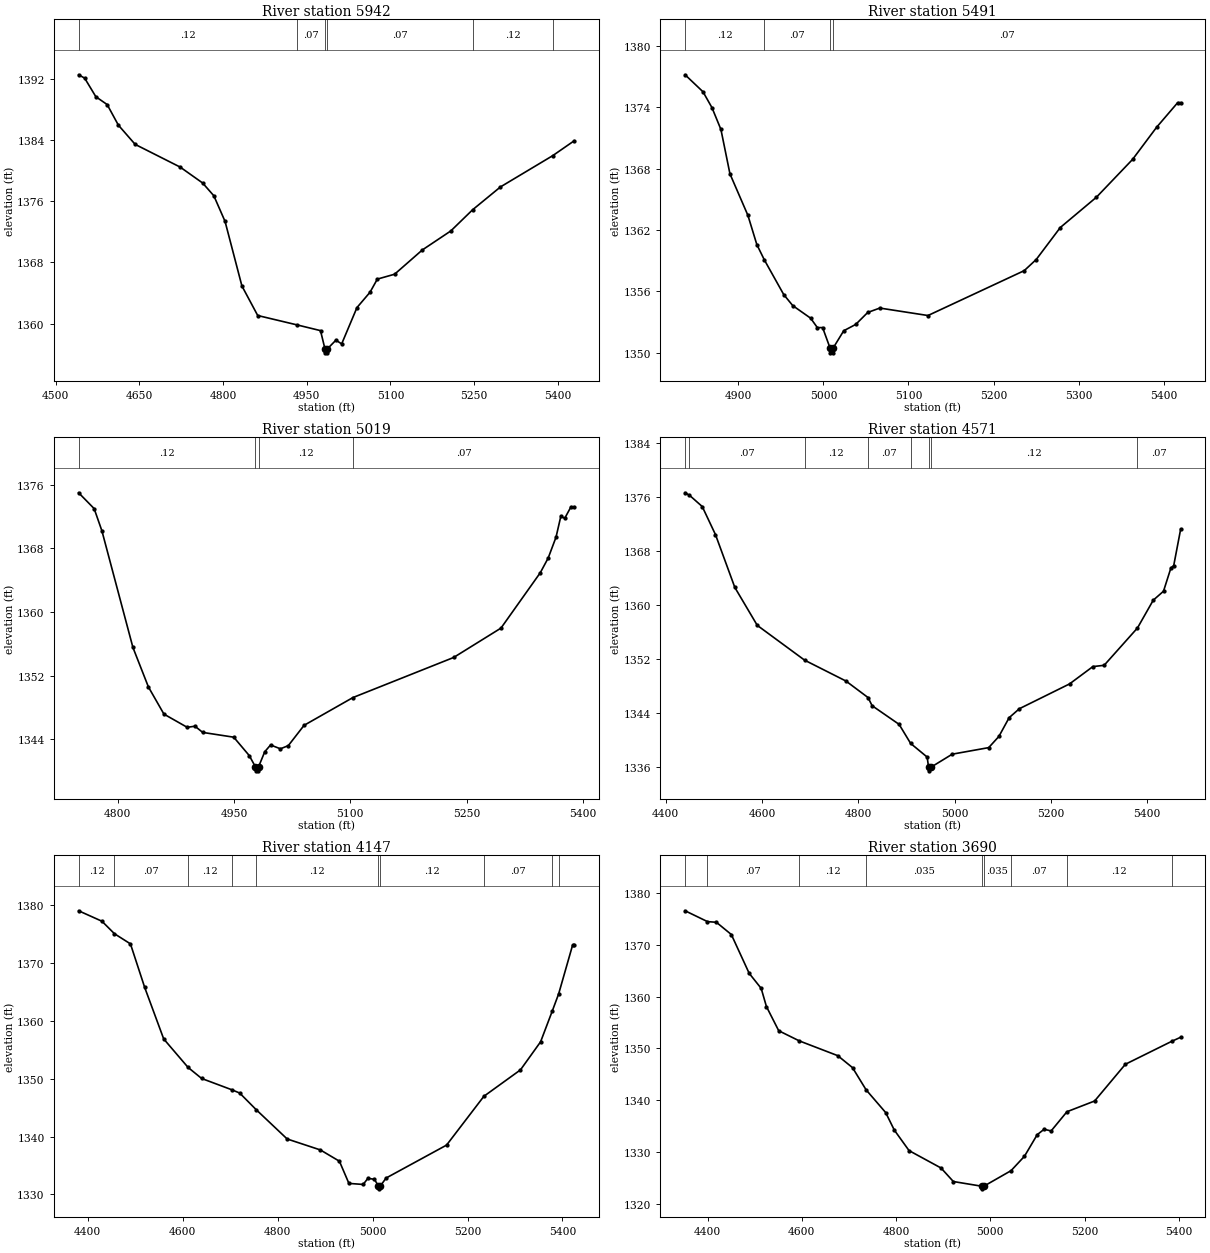
Type RM Length L Ch R = 1,5942,451,451,451
BEGIN DESCRIPTION:
Stream0006_DS 10.0
END DESCRIPTION:
XS GIS Cut Line= 3
      2057035.76     13909475.12      2056575.00     13909525.00
      2056212.84     13909745.96
#Sta/Elev= 30
  4541.4 1392.59  4552.2 1392.15  4572.3 1389.71  4592.5 1388.69  4612.6 1385.99
  4642.7 1383.47  4723.2 1380.50  4763.4 1378.42  4783.6 1376.74  4803.7 1373.38
  4833.9 1364.92  4862.2 1361.05  4932.7 1359.82  4974.7 1359.07  4982.7 1356.66
  4983.0 1356.16  4986.5 1356.16  4986.7 1356.66  5002.3 1357.82  5012.6 1357.33
  5040.0 1362.09  5063.4 1364.10  5076.5 1365.82  5107.4 1366.46  5157.1 1369.64
  5208.1 1372.13  5247.1 1374.90  5297.1 1377.90  5390.6 1381.99  5429.1 1383.94
#Mann=6,-1,0
  4541.4    0.12       0  4932.7    0.07       0  4982.7    0.05       0
  4986.7    0.07       0  5247.1    0.12       0  5390.6    0.07       0
Bank Sta=4982.7,4986.7
Exp/Cntr=0.3,0.1

Type RM Length L Ch R = 1,5491,472,472,472
BEGIN DESCRIPTION:
Stream0006_DS 9.0
END DESCRIPTION:
XS GIS Cut Line= 3
      2056674.97     13909075.01      2056525.00     13909125.00
      2056225.03     13909424.97
#Sta/Elev= 30
  4837.5 1377.17  4858.5 1375.51  4869.1 1373.95  4879.6 1371.82  4890.2 1367.48
  4911.3 1363.42  4921.8 1360.56  4930.7 1359.05  4953.4 1355.67  4964.0 1354.59
  4985.0 1353.36  4992.9 1352.44  4999.1 1352.44  5007.7 1350.47  5008.0 1349.97
  5011.5 1349.97  5011.7 1350.47  5023.9 1352.13  5038.0 1352.75  5052.1 1353.92
  5066.3 1354.35  5122.9 1353.62  5236.0 1358.01  5250.1 1359.10  5278.4 1362.23
  5320.8 1365.19  5363.3 1368.89  5391.6 1372.04  5416.3 1374.44  5419.8 1374.44
#Mann=4,-1,0
  4837.5    0.12       0  4930.7    0.07       0  5007.7    0.05       0
  5011.7    0.07       0
Bank Sta=5007.7,5011.7
Exp/Cntr=0.3,0.1

Type RM Length L Ch R = 1,5019,448,448,448
BEGIN DESCRIPTION:
Stream0006_DS 8.0
END DESCRIPTION:
XS GIS Cut Line= 3
      2056575.05     13908725.00      2056325.00     13908725.00
      2055942.01     13908792.83
#Sta/Elev= 30
  4749.6 1374.99  4769.6 1373.00  4779.6 1370.21  4819.6 1355.55  4839.6 1350.58
  4859.6 1347.17  4889.6 1345.51  4899.6 1345.65  4909.6 1344.87  4949.6 1344.27
  4969.6 1341.96  4977.6 1340.54  4977.9 1340.04  4981.4 1340.04  4981.6 1340.54
  4989.6 1342.44  4997.1 1343.29  5009.8 1342.81  5020.0 1343.21  5040.3 1345.76
  5103.3 1349.25  5233.2 1354.29  5294.2 1357.98  5344.9 1364.94  5355.1 1366.79
  5365.2 1369.41  5371.4 1372.04  5376.4 1371.78  5384.5 1373.23  5388.6 1373.23
#Mann=4,-1,0
  4749.6    0.12       0  4977.6    0.05       0  4981.6    0.12       0
  5103.3    0.07       0
Bank Sta=4977.6,4981.6
Exp/Cntr=0.3,0.1

Type RM Length L Ch R = 1,4571,424,424,424
BEGIN DESCRIPTION:
Stream0006_DS 7.0
END DESCRIPTION:
XS GIS Cut Line= 3
      2056837.89     13908277.20      2056275.00     13908325.00
      2055879.73     13908568.74
#Sta/Elev= 30
  4440.3 1376.67  4449.4 1376.30  4475.9 1374.63  4503.4 1370.47  4543.6 1362.64
  4590.2 1357.02  4688.6 1351.86  4774.4 1348.77  4820.3 1346.32  4828.8 1345.11
  4884.8 1342.35  4908.8 1339.52  4943.1 1337.50  4946.1 1335.96  4946.3 1335.46
  4950.1 1335.96  4995.2 1337.93  5070.9 1338.90  5092.1 1340.56  5113.4 1343.34
  5134.7 1344.67  5238.8 1348.34  5287.3 1350.91  5310.7 1351.10  5379.9 1356.63
  5412.7 1360.75  5434.0 1362.08  5449.4 1365.53  5455.2 1365.87  5469.6 1371.26
#Mann=8,-1,0
  4440.3    0.12       0  4449.4    0.07       0  4688.6    0.12       0
  4820.3    0.07       0  4908.8    0.12       0  4946.1    0.05       0
  4950.1    0.12       0  5379.9    0.07       0
Bank Sta=4946.1,4950.1
Exp/Cntr=0.3,0.1

Type RM Length L Ch R = 1,4147,457,457,457
BEGIN DESCRIPTION:
Stream0006_DS 6.0
END DESCRIPTION:
XS GIS Cut Line= 3
      2056744.15     13907975.12      2056125.00     13907975.00
      2055825.01     13908274.99
#Sta/Elev= 30
  4381.2 1379.08  4430.3 1377.27  4456.6 1375.11  4490.3 1373.35  4520.3 1365.81
  4560.3 1356.90  4611.7 1351.96  4640.3 1350.05  4704.3 1348.08  4720.3 1347.53
  4755.2 1344.64  4820.3 1339.58  4890.3 1337.68  4930.3 1335.73  4950.3 1331.89
  4980.3 1331.71  4990.3 1332.77  5003.9 1332.60  5012.5 1331.45  5012.7 1330.95
  5016.5 1331.45  5028.6 1332.82  5155.9 1338.52  5234.5 1346.97  5311.5 1351.54
  5353.9 1356.40  5378.5 1361.73  5391.9 1364.69  5421.1 1373.08  5424.6 1373.08
#Mann=10,-1,0
  4381.2    0.12       0  4456.6    0.07       0  4611.7    0.12       0
  4704.3    0.07       0  4755.2    0.12       0  5012.5    0.05       0
  5016.5    0.12       0  5234.5    0.07       0  5378.5    0.12       0
  5391.9    0.07       0
Bank Sta=5012.5,5016.5
Exp/Cntr=0.3,0.1

Type RM Length L Ch R = 1,3690,453,453,453
BEGIN DESCRIPTION:
Stream0006_DS 5.0
END DESCRIPTION:
XS GIS Cut Line= 3
      2056587.85     13907365.74      2055975.00     13907575.00
      2055645.15     13907808.45
#Sta/Elev= 30
  4352.3 1376.56  4399.8 1374.47  4418.7 1374.34  4450.4 1371.98  4488.3 1364.49
  4513.8 1361.58  4524.9 1358.08  4551.0 1353.41  4594.7 1351.45  4676.3 1348.60
  4707.6 1346.29  4736.5 1342.00  4778.0 1337.62  4796.3 1334.24  4827.6 1330.28
  4895.5 1326.92  4921.6 1324.31  4982.2 1323.40  4982.5 1322.90  4986.2 1323.40
  5044.1 1326.41  5072.5 1329.18  5099.6 1333.35  5114.3 1334.40  5129.1 1334.07
  5162.7 1337.78  5221.4 1339.85  5286.7 1346.94  5384.7 1351.35  5404.0 1352.15
#Mann=9,-1,0
  4352.3    0.12       0  4399.8    0.07       0  4594.7    0.12       0
  4736.5   0.035       0  4982.2   0.035       0  4986.2   0.035       0
  5044.1    0.07       0  5162.7    0.12       0  5384.7   0.035       0
Bank Sta=4982.2,4986.2
Exp/Cntr=0.3,0.1

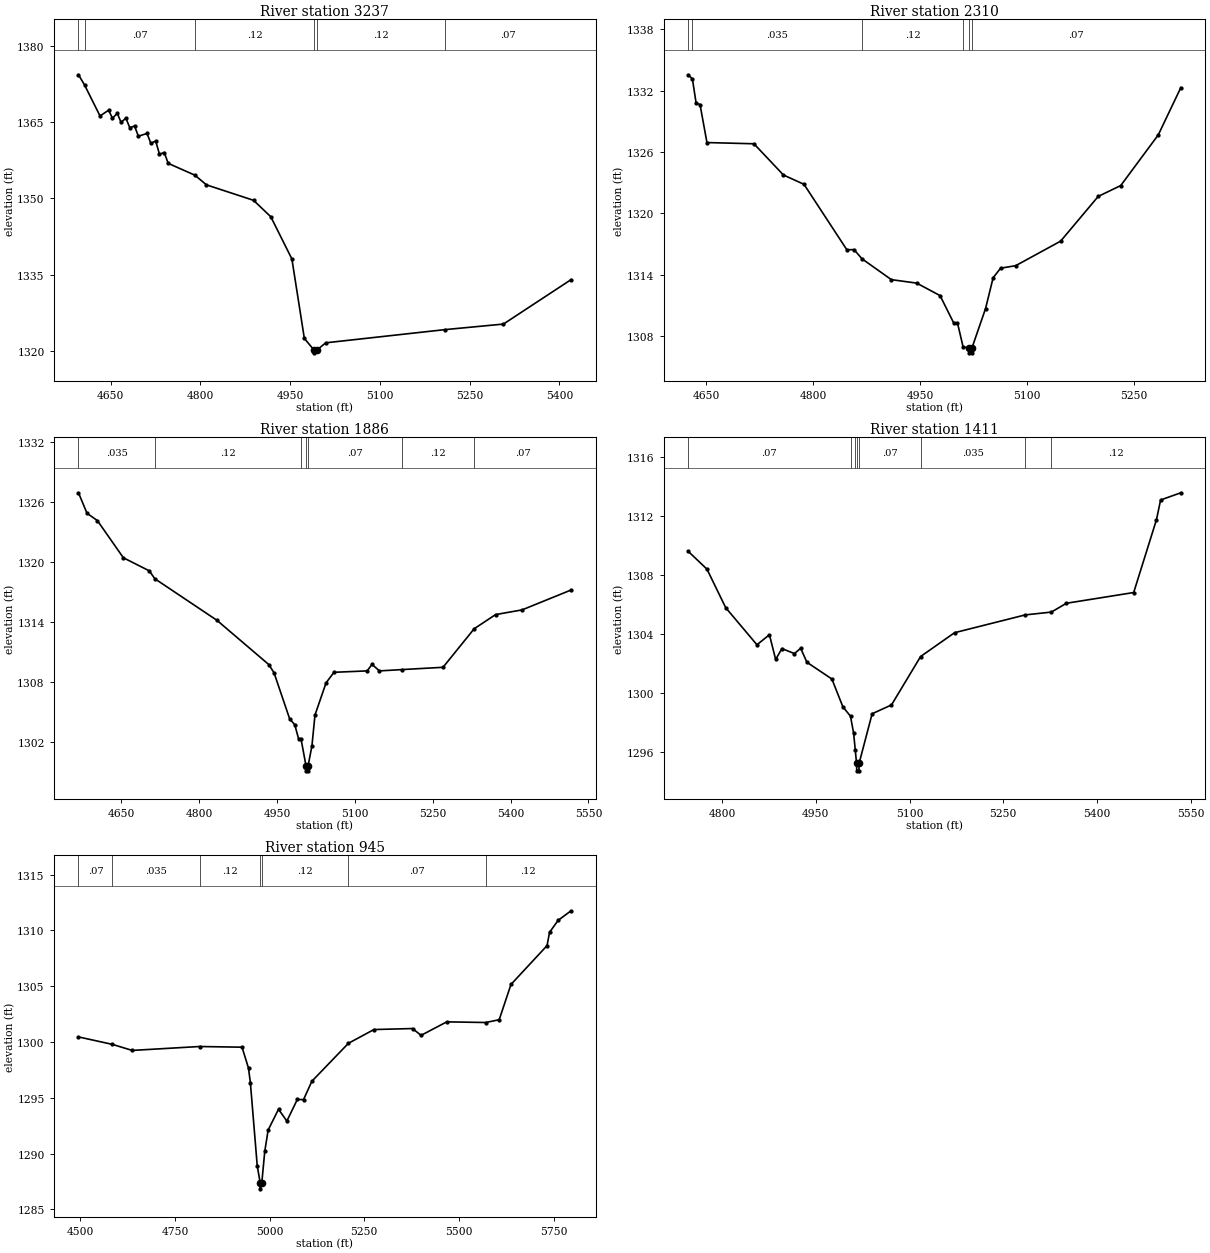
Type RM Length L Ch R = 1,3237,927,927,927
BEGIN DESCRIPTION:
Stream0006_DS 4.0
END DESCRIPTION:
XS GIS Cut Line= 3
      2056238.90     13906928.24      2055925.00     13907175.00
      2055625.03     13907474.97
#Sta/Elev= 30
  4596.1 1374.30  4606.2 1372.31  4632.1 1366.21  4646.5 1367.34  4652.9 1365.76
  4661.0 1366.73  4667.3 1364.95  4675.4 1365.78  4681.8 1363.91  4689.9 1364.23
  4696.2 1362.23  4710.7 1362.77  4717.1 1360.82  4725.1 1361.29  4731.5 1358.71
  4739.6 1359.03  4746.0 1356.90  4790.6 1354.58  4810.1 1352.67  4888.7 1349.64
  4917.6 1346.41  4952.9 1338.11  4973.7 1322.51  4990.2 1320.17  4990.5 1319.67
  4994.2 1320.17  5009.5 1321.64  5208.7 1324.23  5306.5 1325.32  5419.6 1334.05
#Mann=6,-1,0
  4596.1    0.12       0  4606.2    0.07       0  4790.6    0.12       0
  4990.2    0.05       0  4994.2    0.12       0  5208.7    0.07       0
Bank Sta=4990.2,4994.2
Exp/Cntr=0.3,0.1

Type RM Length L Ch R = 1,2310,424,424,424
BEGIN DESCRIPTION:
Stream0006_DS 3.0
END DESCRIPTION:
XS GIS Cut Line= 3
      2055619.15     13906725.10      2055275.00     13906875.00
      2055175.00     13907175.00
#Sta/Elev= 30
  4624.6 1333.54  4630.5 1333.13  4635.7 1330.77  4641.2 1330.63  4650.9 1326.92
  4716.9 1326.80  4758.3 1323.75  4787.2 1322.84  4847.3 1316.45  4857.5 1316.46
  4868.5 1315.57  4909.8 1313.53  4945.4 1313.19  4978.2 1311.97  4997.2 1309.32
  5002.6 1309.32  5010.6 1306.94  5019.1 1306.88  5019.3 1306.38  5022.8 1306.38
  5023.1 1306.88  5042.1 1310.71  5052.7 1313.71  5063.2 1314.65  5084.3 1314.89
  5147.5 1317.29  5200.3 1321.66  5231.9 1322.72  5284.6 1327.67  5316.2 1332.28
#Mann=6,-1,0
  4624.6    0.07       0  4630.5   0.035       0  4868.5    0.12       0
  5010.6    0.07       0  5019.1    0.05       0  5023.1    0.07       0
Bank Sta=5019.1,5023.1
Exp/Cntr=0.3,0.1

Type RM Length L Ch R = 1,1886,475,475,475
BEGIN DESCRIPTION:
Stream0006_DS 2.0
END DESCRIPTION:
XS GIS Cut Line= 3
      2055551.43     13906542.83      2055125.00     13906525.00
      2054849.15     13906968.51
#Sta/Elev= 30
  4567.4 1326.94  4583.8 1324.89  4603.9 1324.15  4653.9 1320.43  4703.9 1319.12
  4714.5 1318.33  4834.1 1314.17  4934.2 1309.73  4944.2 1308.91  4974.2 1304.31
  4984.2 1303.70  4991.7 1302.26  4996.3 1302.26  5005.8 1299.59  5006.0 1299.09
  5009.5 1299.09  5009.8 1299.59  5017.2 1301.58  5023.1 1304.68  5044.4 1307.90
  5059.7 1308.96  5123.7 1309.10  5132.9 1309.75  5147.3 1309.10  5190.3 1309.23
  5269.8 1309.46  5329.8 1313.32  5371.1 1314.74  5422.1 1315.21  5516.5 1317.20
#Mann=7,-1,0
  4567.4   0.035       0  4714.5    0.12       0  4996.3    0.07       0
  5005.8    0.05       0  5009.8    0.07       0  5190.3    0.12       0
  5329.8    0.07       0
Bank Sta=5005.8,5009.8
Exp/Cntr=0.3,0.1

Type RM Length L Ch R = 1,1411,466,466,466
BEGIN DESCRIPTION:
Stream0006_DS 1.0
END DESCRIPTION:
XS GIS Cut Line= 3
      2055175.00     13906125.00      2054925.00     13906125.00
      2054725.01     13906624.98
#Sta/Elev= 30
  4745.7 1309.62  4775.7 1308.41  4805.7 1305.79  4855.7 1303.27  4875.7 1303.95
  4885.7 1302.27  4895.7 1303.01  4915.7 1302.67  4925.7 1303.03  4935.7 1302.08
  4975.7 1300.94  4993.2 1299.06  5005.5 1298.41  5010.5 1297.25  5013.1 1296.12
  5015.2 1295.20  5015.5 1294.70  5019.0 1294.70  5019.2 1295.20  5040.1 1298.58
  5071.1 1299.18  5117.7 1302.47  5172.1 1304.09  5285.3 1305.30  5327.0 1305.49
  5351.1 1306.09  5458.8 1306.82  5495.2 1311.76  5501.9 1313.11  5534.2 1313.60
#Mann=8,-1,0
  4745.7    0.07       0  5005.5   0.035       0  5013.1    0.07       0
  5015.2    0.05       0  5019.2    0.07       0  5117.7   0.035       0
  5285.3    0.07       0  5327.0    0.12       0
Bank Sta=5015.2,5019.2
Exp/Cntr=0.3,0.1

Type RM Length L Ch R = 1,945,0,0,0
BEGIN DESCRIPTION:
Stream0006_DS 0.0
END DESCRIPTION:
XS GIS Cut Line= 3
      2055256.89     13905738.13      2054752.16     13905751.41
      2054379.95     13906455.25
#Sta/Elev= 30
  4495.1 1300.46  4584.9 1299.79  4637.0 1299.25  4814.8 1299.60  4927.1 1299.54
  4944.2 1297.66  4949.2 1296.34  4967.2 1288.94  4975.2 1287.35  4975.4 1286.85
  4979.2 1287.35  4987.2 1290.22  4996.1 1292.12  5023.5 1293.98  5045.5 1292.92
  5073.2 1294.86  5089.5 1294.84  5111.6 1296.49  5208.2 1299.89  5275.5 1301.12
  5377.4 1301.21  5400.0 1300.60  5467.9 1301.81  5570.8 1301.75  5606.4 1302.00
  5637.5 1305.16  5732.8 1308.64  5739.4 1309.83  5762.0 1310.90  5796.2 1311.76
#Mann=7,-1,0
  4495.1    0.07       0  4584.9   0.035       0  4814.8    0.12       0
  4975.2    0.05       0  4979.2    0.12       0  5208.2    0.07       0
  5570.8    0.12       0
Bank Sta=4975.2,4979.2
Exp/Cntr=0.3,0.1

Chan Stop Cuts=-1