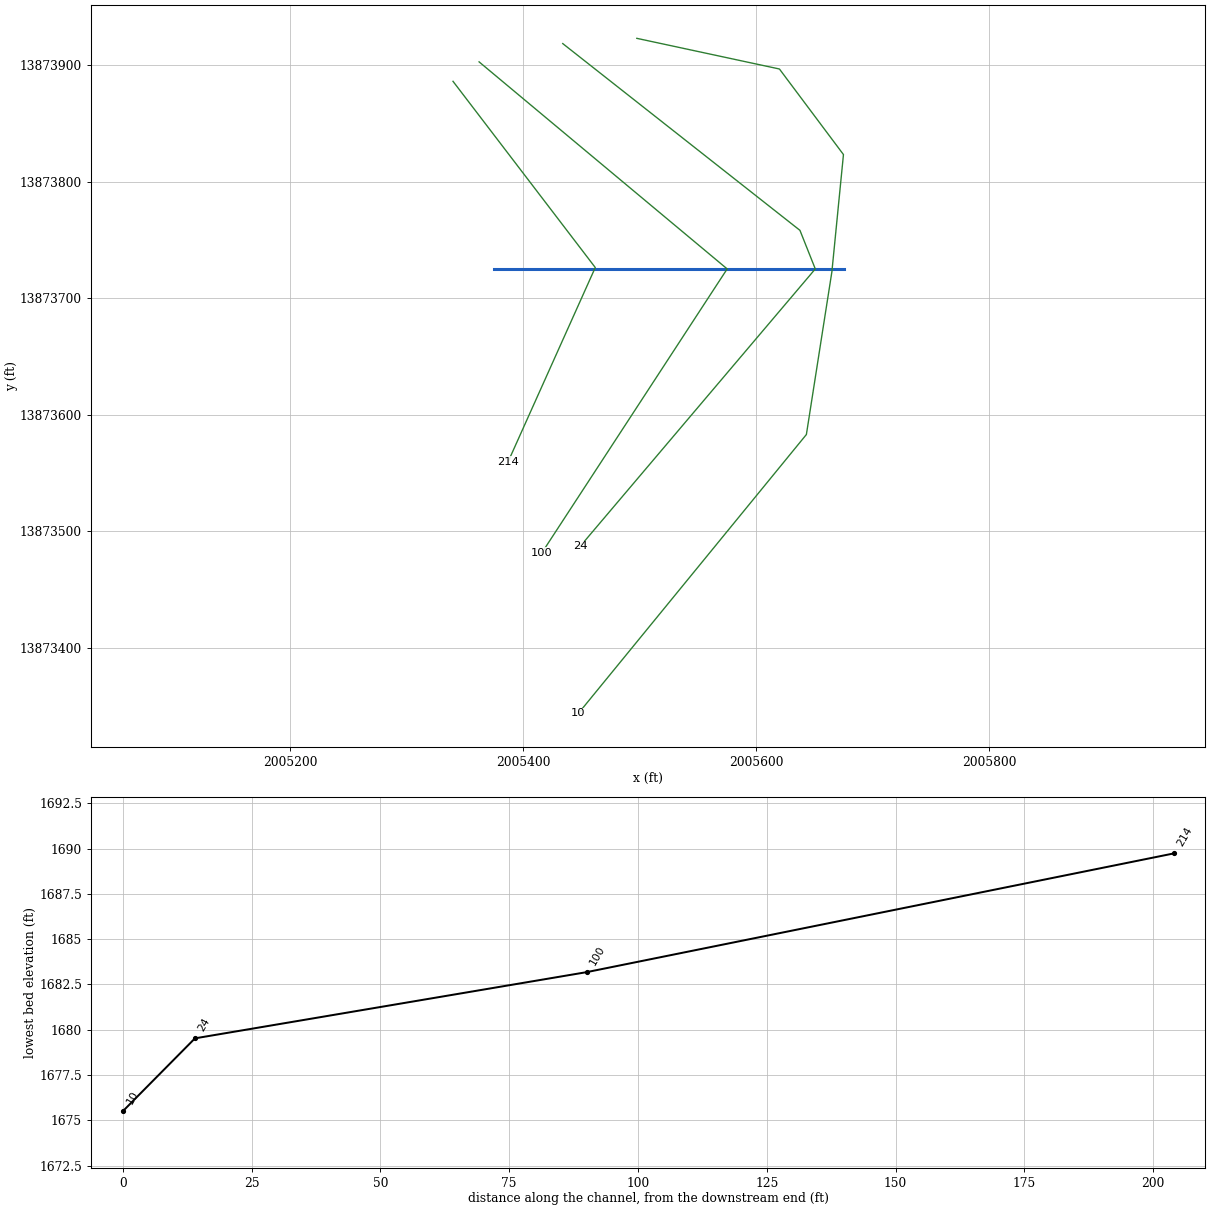
--- Stream0007_DS.prj (project) ---

Proj Title=Stream0007_DS Base Level Engineering
Current Plan=p01
Default Exp/Contr=0.3,0.1
English Units
Geom File=g01
Flow File=f01
Plan File=p01
BEGIN DESCRIPTION:
Stream0007_DS
END DESCRIPTION:

--- Stream0007_DS.p01 (plan) ---

Plan Title=Multiple Run
Short Identifier=Multiple
Geom File=g01
Flow File=f01
Subcritical Flow
K Sum by GR= 0
Std Step Tol= 0.01
Critical Tol= 0.01
Num of Std Step Trials= 20
Max Error Tol= 0.3
Flow Tol Ratio= 0.001
Split Flow NTrial= 30
Split Flow Tol= 0.02
Split Flow Ratio= 0.02
Log Output Level= 0
Friction Slope Method= 1
Unsteady Friction Slope Method= 2
Unsteady Bridges Friction Slope Method= 1
Parabolic Critical Depth
Global Vel Dist=  1 , 1 , 1
Global Log Level= 0
CheckData=True
Encroach Param= -1, 0, 0, 0
BEGIN DESCRIPTION:
Multiple Run
END DESCRIPTION:

--- Stream0007_DS.f01 (steady flow) ---

Flow Title=Multiple
Number of Profiles=7
Profile Names=10-year,25-year,50-year,1pct_min,100-year,1pct_plu,500-year
River Rch & RM= Stream0007_DS,Reach-1,214
     184     278     359     227     453     904     707
River Rch & RM= Stream0007_DS,Reach-1,24
     836    1410    1955    1316    2626    5240    4686
Boundary for River Rch & Prof#=Stream0007_DS,Reach-1,1
Up Type=0
Dn Type=3
Dn Slope=0.005
Boundary for River Rch & Prof#=Stream0007_DS,Reach-1,2
Up Type=0
Dn Type=3
Dn Slope=0.005
Boundary for River Rch & Prof#=Stream0007_DS,Reach-1,3
Up Type=0
Dn Type=3
Dn Slope=0.005
Boundary for River Rch & Prof#=Stream0007_DS,Reach-1,4
Up Type=0
Dn Type=3
Dn Slope=0.005
Boundary for River Rch & Prof#=Stream0007_DS,Reach-1,5
Up Type=0
Dn Type=3
Dn Slope=0.005
Boundary for River Rch & Prof#=Stream0007_DS,Reach-1,6
Up Type=0
Dn Type=3
Dn Slope=0.005
Boundary for River Rch & Prof#=Stream0007_DS,Reach-1,7
Up Type=0
Dn Type=3
Dn Slope=0.005

--- Stream0007_DS.g01 (geometry) ---

Geom Title=Existing Conditions

River Reach=Stream0007_DS,Reach-1
Reach XY= 10
      2005375.00     13873725.00      2005425.00     13873725.00
      2005450.00     13873725.00      2005497.73     13873725.00
      2005502.27     13873725.00      2005560.00     13873725.00
      2005580.00     13873725.00      2005610.00     13873725.00
      2005635.44     13873725.00      2005675.00     13873725.00

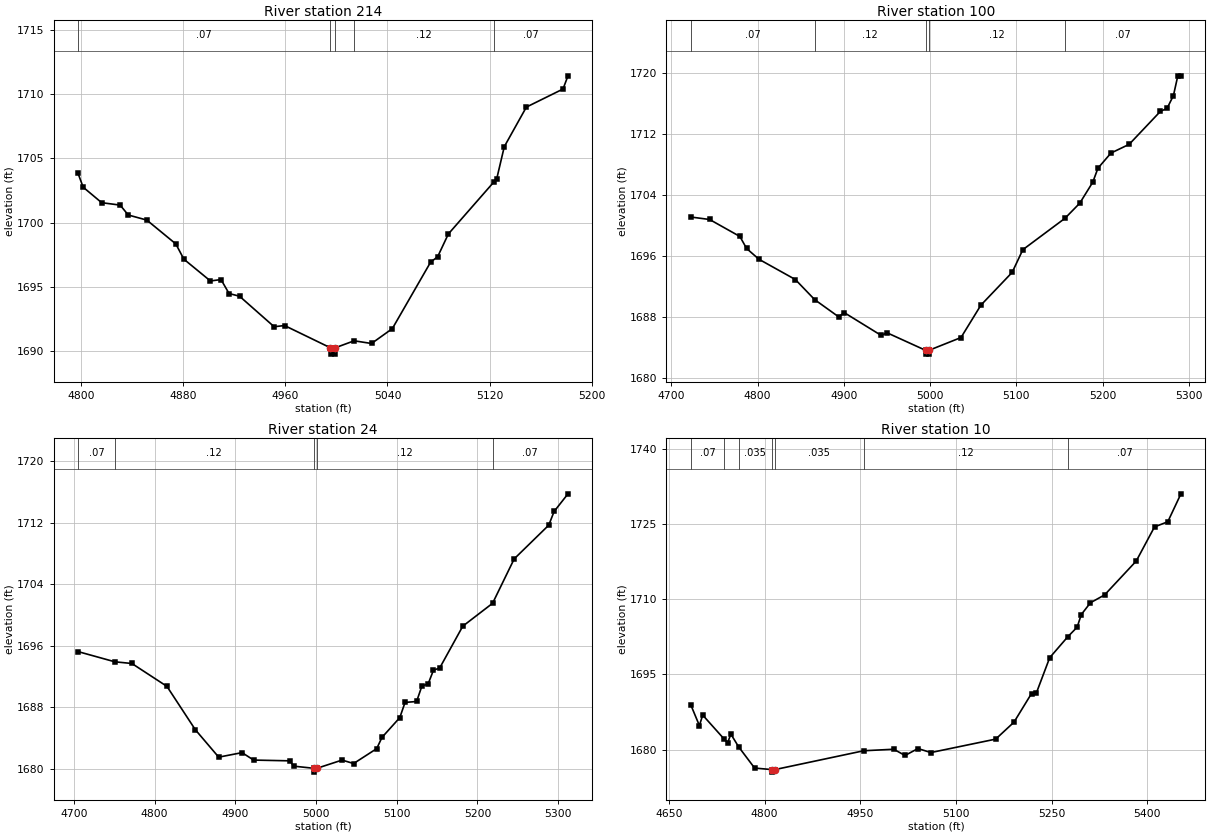
Type RM Length L Ch R = 1,214,114,114,114
BEGIN DESCRIPTION:
Stream0007_DS 1.0
END DESCRIPTION:
XS GIS Cut Line= 3
      2005339.73     13873885.98      2005461.82     13873726.19
      2005387.00     13873559.51
#Sta/Elev= 30
  4797.6 1703.84  4801.6 1702.76  4816.1 1701.55  4830.6 1701.36  4836.9 1700.59
  4851.5 1700.19  4874.2 1698.33  4880.5 1697.14  4901.3 1695.44  4909.6 1695.55
  4915.9 1694.46  4924.1 1694.25  4951.2 1691.87  4959.4 1691.96  4995.2 1690.23
  4995.4 1689.73  4998.9 1689.73  4999.2 1690.23  5013.9 1690.77  5027.5 1690.56
  5043.8 1691.72  5073.8 1696.91  5079.3 1697.33  5087.7 1699.11  5123.3 1703.16
  5125.6 1703.42  5131.5 1705.92  5148.8 1709.01  5177.5 1710.42  5181.4 1711.45
#Mann=5,-1,0
  4797.6    0.07       0  4995.2    0.05       0  4999.2    0.07       0
  5013.9    0.12       0  5123.3    0.07       0
Bank Sta=4995.2,4999.2
Exp/Cntr=0.3,0.1

Type RM Length L Ch R = 1,100,76,76,76
BEGIN DESCRIPTION:
Stream0007_DS 0.2
END DESCRIPTION:
XS GIS Cut Line= 3
      2005362.11     13873902.68      2005575.00     13873725.00
      2005416.04     13873481.49
#Sta/Elev= 30
  4722.7 1701.11  4744.3 1700.79  4779.4 1698.57  4787.2 1697.00  4801.5 1695.59
  4843.7 1692.94  4866.1 1690.31  4893.9 1688.06  4900.4 1688.61  4943.4 1685.62
  4949.9 1685.98  4994.7 1683.68  4995.0 1683.18  4998.5 1683.18  4998.7 1683.68
  5035.8 1685.35  5058.9 1689.59  5095.1 1693.87  5107.5 1696.84  5156.3 1700.94
  5173.5 1702.92  5188.6 1705.67  5194.6 1707.50  5209.7 1709.48  5230.8 1710.62
  5267.0 1714.93  5274.7 1715.32  5282.1 1716.99  5287.2 1719.58  5290.8 1719.58
#Mann=5,-1,0
  4722.7    0.07       0  4866.1    0.12       0  4994.7    0.05       0
  4998.7    0.12       0  5156.3    0.07       0
Bank Sta=4994.7,4998.7
Exp/Cntr=0.3,0.1

Type RM Length L Ch R = 1,24,14,14,14
BEGIN DESCRIPTION:
Stream0007_DS 0.1
END DESCRIPTION:
XS GIS Cut Line= 4
      2005433.90     13873918.37      2005637.46     13873758.10
      2005650.62     13873725.00      2005448.82     13873486.92
#Sta/Elev= 30
  4705.3 1695.23  4750.9 1693.90  4772.0 1693.68  4815.4 1690.70  4850.6 1685.05
  4879.5 1681.48  4908.4 1682.07  4922.8 1681.10  4967.8 1681.00  4972.2 1680.31
  4997.2 1680.03  4997.4 1679.53  5001.2 1680.03  5032.3 1681.10  5046.6 1680.65
  5075.2 1682.59  5081.7 1684.05  5103.8 1686.63  5110.3 1688.61  5124.6 1688.73
  5131.2 1690.75  5138.9 1691.02  5145.5 1692.81  5153.2 1693.09  5181.8 1698.54
  5218.7 1701.52  5245.5 1707.31  5288.3 1711.70  5294.9 1713.48  5312.1 1715.78
#Mann=5,-1,0
  4705.3    0.07       0  4750.9    0.12       0  4997.2    0.05       0
  5001.2    0.12       0  5218.7    0.07       0
Bank Sta=4997.2,5001.2
Exp/Cntr=0.3,0.1

Type RM Length L Ch R = 1,10,0,0,0
BEGIN DESCRIPTION:
Stream0007_DS 0.0
END DESCRIPTION:
XS GIS Cut Line= 6
      2005497.46     13873922.87      2005619.84     13873896.56
      2005674.79     13873823.14      2005664.86     13873722.55
      2005642.97     13873582.89      2005447.32     13873343.62
#Sta/Elev= 30
  4684.5 1688.83  4697.7 1684.79  4702.9 1686.88  4736.2 1682.15  4742.0 1681.38
  4747.1 1683.08  4759.2 1680.56  4784.3 1676.32  4811.9 1676.01  4812.2 1675.51
  4815.9 1676.01  4955.4 1679.77  5002.5 1680.07  5020.2 1678.83  5040.5 1680.21
  5060.7 1679.41  5162.4 1682.09  5191.1 1685.47  5218.6 1691.18  5226.3 1691.32
  5247.1 1698.32  5275.4 1702.48  5290.2 1704.41  5296.6 1706.91  5311.0 1709.27
  5333.2 1710.83  5382.8 1717.58  5411.5 1724.39  5432.3 1725.41  5452.9 1730.98
#Mann=7,-1,0
  4684.5    0.07       0  4736.2    0.12       0  4759.2   0.035       0
  4811.9    0.05       0  4815.9   0.035       0  4955.4    0.12       0
  5275.4    0.07       0
Bank Sta=4811.9,4815.9
Exp/Cntr=0.3,0.1

Chan Stop Cuts=-1