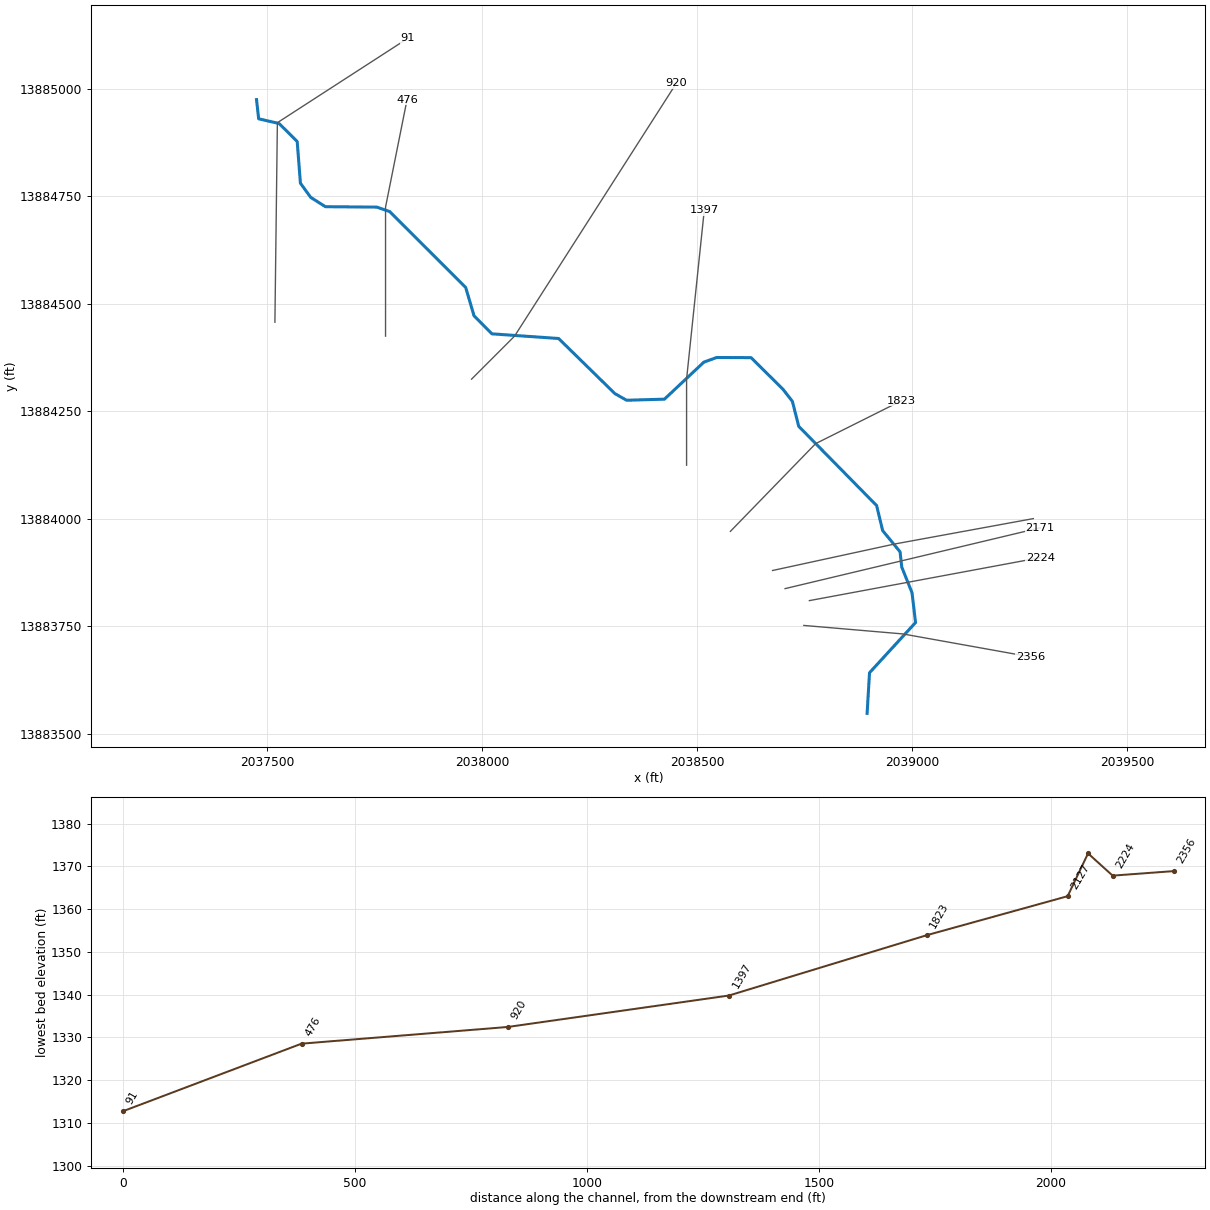
--- Stream0008_DS.prj (project) ---

Proj Title=Stream0008_DS Base Level Engineering
Current Plan=p01
Default Exp/Contr=0.3,0.1
English Units
Geom File=g01
Flow File=f01
Plan File=p01
BEGIN DESCRIPTION:
Stream0008_DS
END DESCRIPTION:

--- Stream0008_DS.p01 (plan) ---

Plan Title=Multiple Run
Short Identifier=Multiple
Geom File=g01
Flow File=f01
Subcritical Flow
K Sum by GR= 0
Std Step Tol= 0.01
Critical Tol= 0.01
Num of Std Step Trials= 20
Max Error Tol= 0.3
Flow Tol Ratio= 0.001
Split Flow NTrial= 30
Split Flow Tol= 0.02
Split Flow Ratio= 0.02
Log Output Level= 0
Friction Slope Method= 1
Unsteady Friction Slope Method= 2
Unsteady Bridges Friction Slope Method= 1
Parabolic Critical Depth
Global Vel Dist=  1 , 1 , 1
Global Log Level= 0
CheckData=True
Encroach Param= -1, 0, 0, 0
BEGIN DESCRIPTION:
Multiple Run
END DESCRIPTION:

--- Stream0008_DS.f01 (steady flow) ---

Flow Title=Multiple
Number of Profiles=7
Profile Names=10-year,25-year,50-year,1pct_min,100-year,1pct_plu,500-year
River Rch & RM= Stream0008_DS,Reach-1,2356
     508     823    1113     732    1461    2916    2484
River Rch & RM= Stream0008_DS,Reach-1,1397
    1016    1721    2393    1615    3223    6431    5777
Boundary for River Rch & Prof#=Stream0008_DS,Reach-1,1
Up Type=0
Dn Type=3
Dn Slope=0.005
Boundary for River Rch & Prof#=Stream0008_DS,Reach-1,2
Up Type=0
Dn Type=3
Dn Slope=0.005
Boundary for River Rch & Prof#=Stream0008_DS,Reach-1,3
Up Type=0
Dn Type=3
Dn Slope=0.005
Boundary for River Rch & Prof#=Stream0008_DS,Reach-1,4
Up Type=0
Dn Type=3
Dn Slope=0.005
Boundary for River Rch & Prof#=Stream0008_DS,Reach-1,5
Up Type=0
Dn Type=3
Dn Slope=0.005
Boundary for River Rch & Prof#=Stream0008_DS,Reach-1,6
Up Type=0
Dn Type=3
Dn Slope=0.005
Boundary for River Rch & Prof#=Stream0008_DS,Reach-1,7
Up Type=0
Dn Type=3
Dn Slope=0.005

--- Stream0008_DS.g01 (geometry) ---

Geom Title=Existing Conditions

River Reach=Stream0008_DS,Reach-1
Reach XY= 30
      2038894.77     13883547.83      2038900.41     13883642.34
      2039007.37     13883758.98      2038999.25     13883828.29
      2038975.38     13883887.96      2038971.40     13883923.51
      2038930.97     13883972.76      2038916.87     13884031.06
      2038735.77     13884215.32      2038721.05     13884273.36
      2038698.80     13884301.86      2038625.00     13884375.00
      2038544.87     13884375.32      2038515.19     13884364.54
      2038423.50     13884278.47      2038335.48     13884275.93
      2038308.25     13884291.40      2038177.45     13884419.53
      2038022.30     13884430.36      2037980.74     13884472.43
      2037961.36     13884538.20      2037784.80     13884714.52
      2037755.01     13884725.02      2037635.27     13884725.99
      2037600.98     13884747.66      2037577.07     13884780.69
      2037569.57     13884877.67      2037527.46     13884919.42
      2037479.96     13884930.35      2037475.00     13884975.00

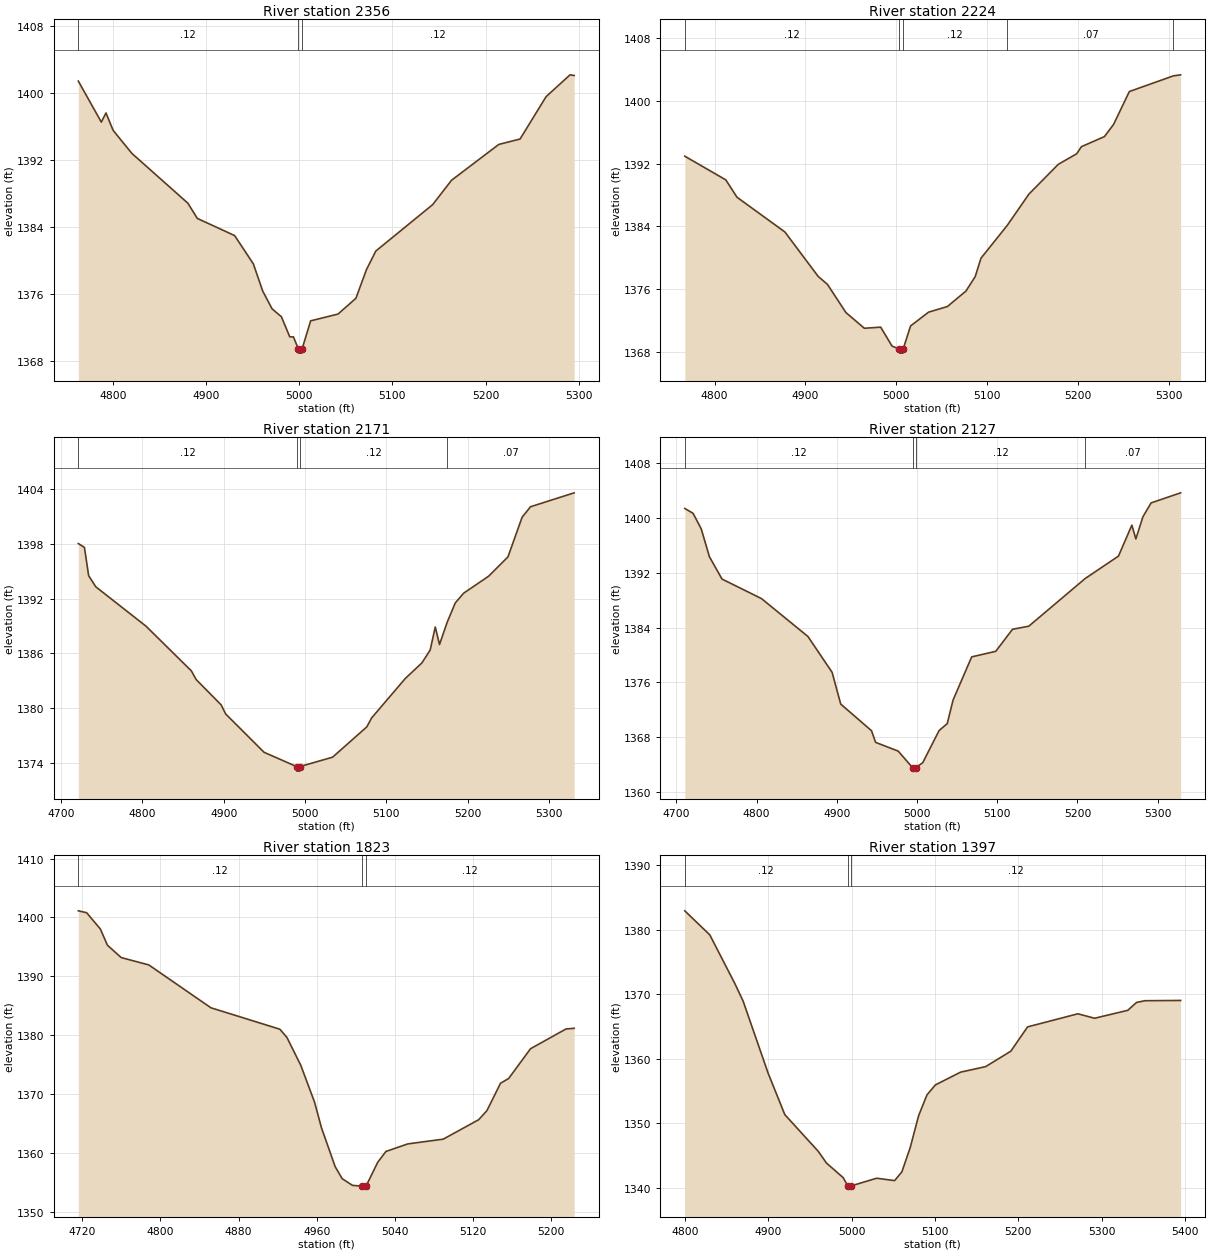
Type RM Length L Ch R = 1,2356,132,132,132
BEGIN DESCRIPTION:
Stream0008_DS 8.0
END DESCRIPTION:
XS GIS Cut Line= 3
      2038747.71     13883752.31      2038977.91     13883732.56
      2039274.62     13883679.29
#Sta/Elev= 30
  4762.7 1401.37  4787.4 1396.48  4792.4 1397.57  4800.1 1395.49  4820.2 1392.75
  4880.4 1386.80  4890.5 1384.99  4930.6 1382.94  4950.7 1379.56  4960.7 1376.33
  4970.8 1374.20  4980.8 1373.26  4989.8 1370.86  4993.7 1370.86  4999.0 1369.42
  4999.2 1368.92  5002.7 1368.92  5003.0 1369.42  5012.2 1372.77  5041.6 1373.58
  5060.8 1375.46  5072.1 1378.87  5082.2 1381.10  5143.2 1386.63  5163.5 1389.54
  5214.3 1393.82  5237.1 1394.46  5265.1 1399.52  5290.8 1402.12  5295.2 1402.04
#Mann=3,-1,0
  4762.7    0.12       0  4999.0    0.05       0  5003.0    0.12       0
Bank Sta=4999,5003
Exp/Cntr=0.3,0.1

Type RM Length L Ch R = 1,2224,53,53,53
BEGIN DESCRIPTION:
Stream0008_DS 7.0
END DESCRIPTION:
XS GIS Cut Line= 2
      2038760.54     13883810.02      2039297.52     13883909.98
#Sta/Elev= 30
  4767.1 1392.96  4812.3 1389.94  4824.6 1387.73  4877.4 1383.30  4914.0 1377.64
  4924.2 1376.63  4944.6 1373.03  4964.9 1371.03  4982.9 1371.17  4995.4 1368.76
  5003.6 1368.36  5003.8 1367.86  5007.3 1367.86  5007.6 1368.36  5015.8 1371.32
  5035.6 1373.08  5056.4 1373.80  5076.8 1375.77  5087.0 1377.61  5093.4 1379.96
  5122.5 1384.17  5146.2 1388.13  5178.5 1391.92  5198.8 1393.27  5204.0 1394.17
  5229.4 1395.46  5239.5 1397.02  5256.8 1401.20  5305.4 1403.20  5313.3 1403.33
#Mann=5,-1,0
  4767.1    0.12       0  5003.6    0.05       0  5007.6    0.12       0
  5122.5    0.07       0  5305.4    0.12       0
Bank Sta=5003.6,5007.6
Exp/Cntr=0.3,0.1

Type RM Length L Ch R = 1,2171,44,44,44
BEGIN DESCRIPTION:
Stream0008_DS 6.0
END DESCRIPTION:
XS GIS Cut Line= 2
      2038704.05     13883837.93      2039297.23     13883979.33
#Sta/Elev= 30
  4721.3 1398.05  4728.8 1397.63  4734.0 1394.52  4742.8 1393.30  4804.5 1388.98
  4860.3 1384.07  4866.2 1383.12  4897.0 1380.33  4902.5 1379.34  4949.7 1375.13
  4989.8 1373.56  4990.1 1373.06  4993.6 1373.06  4993.8 1373.56  5034.0 1374.59
  5076.1 1377.92  5082.1 1378.91  5123.4 1383.23  5143.8 1384.94  5154.0 1386.35
  5160.3 1388.89  5165.5 1386.96  5174.9 1389.40  5184.9 1391.53  5195.2 1392.60
  5226.0 1394.47  5249.7 1396.59  5267.1 1400.94  5277.4 1402.09  5331.1 1403.62
#Mann=4,-1,0
  4721.3    0.12       0  4989.8    0.05       0  4993.8    0.12       0
  5174.9    0.07       0
Bank Sta=4989.8,4993.8
Exp/Cntr=0.3,0.1

Type RM Length L Ch R = 1,2127,304,304,304
BEGIN DESCRIPTION:
Stream0008_DS 5.0
END DESCRIPTION:
XS GIS Cut Line= 3
      2038674.98     13883880.07      2038957.89     13883941.48
      2039281.21     13884000.72
#Sta/Elev= 30
  4710.5 1401.40  4720.8 1400.69  4731.0 1398.42  4741.2 1394.35  4756.9 1391.09
  4806.1 1388.24  4864.0 1382.71  4894.2 1377.47  4904.9 1372.84  4943.3 1368.95
  4948.4 1367.25  4976.6 1365.97  4994.5 1363.55  4994.8 1363.05  4998.5 1363.55
  5007.2 1364.29  5027.6 1368.98  5037.7 1369.98  5045.0 1373.43  5068.2 1379.73
  5098.2 1380.54  5119.1 1383.76  5139.4 1384.21  5209.6 1391.16  5251.2 1394.44
  5267.9 1398.96  5272.9 1396.95  5281.7 1400.19  5291.9 1402.21  5328.7 1403.68
#Mann=4,-1,0
  4710.5    0.12       0  4994.5    0.05       0  4998.5    0.12       0
  5209.6    0.07       0
Bank Sta=4994.5,4998.5
Exp/Cntr=0.3,0.1

Type RM Length L Ch R = 1,1823,426,426,426
BEGIN DESCRIPTION:
Stream0008_DS 4.0
END DESCRIPTION:
XS GIS Cut Line= 3
      2038576.88     13883971.07      2038775.00     13884175.00
      2038974.97     13884274.99
#Sta/Elev= 30
  4715.9 1401.13  4724.4 1400.81  4738.5 1398.04  4745.7 1395.30  4759.8 1393.20
  4788.1 1391.95  4851.7 1384.68  4922.4 1381.04  4929.6 1379.64  4943.7 1374.95
  4957.9 1368.66  4964.9 1364.35  4979.0 1357.72  4986.2 1355.68  4996.7 1354.55
  5006.6 1354.41  5006.9 1353.91  5010.4 1353.91  5010.6 1354.41  5022.6 1358.47
  5031.0 1360.30  5053.3 1361.58  5089.7 1362.39  5126.0 1365.69  5134.4 1367.22
  5148.4 1371.88  5156.7 1372.68  5179.1 1377.73  5215.4 1381.08  5223.8 1381.20
#Mann=3,-1,0
  4715.9    0.12       0  5006.6    0.05       0  5010.6    0.12       0
Bank Sta=5006.6,5010.6
Exp/Cntr=0.3,0.1

Type RM Length L Ch R = 1,1397,477,477,477
BEGIN DESCRIPTION:
Stream0008_DS 3.0
END DESCRIPTION:
XS GIS Cut Line= 3
      2038475.00     13884124.96      2038475.00     13884325.00
      2038516.12     13884717.61
#Sta/Elev= 30
  4800.0 1382.97  4830.0 1379.24  4860.0 1371.70  4870.0 1368.96  4900.0 1357.78
  4920.0 1351.36  4960.0 1345.69  4970.0 1343.85  4990.0 1341.59  4995.5 1340.31
  4995.8 1339.81  4999.3 1339.81  4999.5 1340.31  5030.2 1341.50  5051.7 1341.13
  5060.4 1342.49  5070.4 1346.25  5080.5 1351.20  5090.5 1354.42  5100.6 1355.97
  5130.8 1357.95  5160.9 1358.81  5191.1 1361.20  5211.2 1364.97  5271.5 1367.00
  5291.6 1366.31  5331.4 1367.54  5341.9 1368.76  5352.0 1369.03  5394.8 1369.07
#Mann=3,-1,0
  4800.0    0.12       0  4995.5    0.05       0  4999.5    0.12       0
Bank Sta=4995.5,4999.5
Exp/Cntr=0.3,0.1

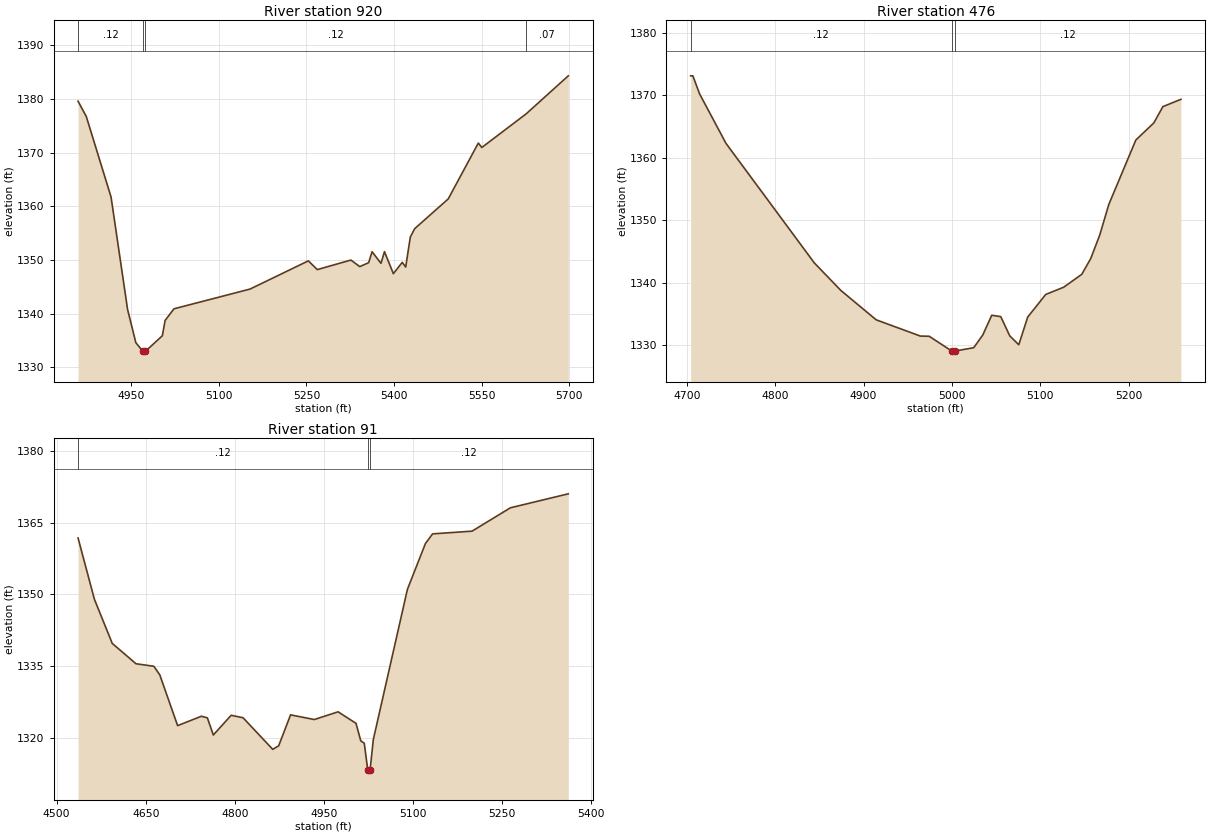
Type RM Length L Ch R = 1,920,444,444,444
BEGIN DESCRIPTION:
Stream0008_DS 2.0
END DESCRIPTION:
XS GIS Cut Line= 3
      2037975.03     13884325.03      2038075.00     13884425.00
      2038451.01     13885012.74
#Sta/Elev= 30
  4859.1 1379.61  4873.2 1376.76  4915.6 1361.74  4943.9 1340.77  4958.0 1334.59
  4970.2 1332.95  4970.4 1332.45  4974.2 1332.95  5003.4 1335.88  5008.1 1338.73
  5023.3 1340.90  5153.5 1344.58  5253.3 1349.84  5268.6 1348.21  5326.1 1349.99
  5341.3 1348.77  5356.5 1349.50  5362.4 1351.54  5377.6 1349.38  5383.6 1351.56
  5398.8 1347.45  5414.0 1349.56  5419.9 1348.68  5427.8 1354.27  5435.2 1355.83
  5492.7 1361.39  5544.2 1371.80  5550.2 1370.98  5626.0 1377.24  5698.2 1384.34
#Mann=4,-1,0
  4859.1    0.12       0  4970.2    0.05       0  4974.2    0.12       0
  5626.0    0.07       0
Bank Sta=4970.2,4974.2
Exp/Cntr=0.3,0.1

Type RM Length L Ch R = 1,476,385,385,385
BEGIN DESCRIPTION:
Stream0008_DS 1.0
END DESCRIPTION:
XS GIS Cut Line= 3
      2037775.00     13884425.04      2037775.00     13884725.00
      2037825.00     13884974.99
#Sta/Elev= 30
  4704.3 1373.08  4706.8 1373.08  4714.3 1370.22  4744.3 1362.27  4844.3 1343.14
  4874.3 1338.74  4914.3 1334.04  4964.3 1331.44  4974.3 1331.41  4999.8 1329.05
  5000.0 1328.55  5003.5 1328.55  5003.8 1329.05  5024.7 1329.58  5034.9 1331.60
  5045.1 1334.77  5055.3 1334.55  5065.5 1331.47  5075.7 1330.05  5085.8 1334.48
  5106.2 1338.10  5126.6 1339.26  5147.0 1341.32  5157.2 1343.86  5167.4 1347.63
  5177.6 1352.50  5208.2 1362.81  5228.6 1365.55  5238.8 1368.15  5259.2 1369.32
#Mann=3,-1,0
  4704.3    0.12       0  4999.8    0.05       0  5003.8    0.12       0
Bank Sta=4999.8,5003.8
Exp/Cntr=0.3,0.1

Type RM Length L Ch R = 1,91,0,0,0
BEGIN DESCRIPTION:
Stream0008_DS 0.0
END DESCRIPTION:
XS GIS Cut Line= 3
      2037517.75     13884457.37      2037523.48     13884921.33
      2037826.77     13885117.50
#Sta/Elev= 30
  4536.0 1361.85  4563.6 1348.97  4593.6 1339.73  4633.6 1335.47  4663.6 1334.94
  4673.6 1333.14  4703.6 1322.49  4743.6 1324.46  4753.7 1324.12  4763.7 1320.53
  4793.7 1324.66  4813.7 1324.15  4863.7 1317.52  4873.7 1318.26  4893.7 1324.75
  4933.7 1323.77  4973.7 1325.39  5003.9 1322.97  5011.9 1319.30  5017.8 1318.80
  5023.6 1313.24  5023.9 1312.74  5027.6 1313.24  5033.0 1319.57  5090.4 1351.07
  5120.7 1360.68  5132.8 1362.71  5199.2 1363.28  5263.8 1368.18  5361.2 1371.11
#Mann=3,-1,0
  4536.0    0.12       0  5023.6    0.05       0  5027.6    0.12       0
Bank Sta=5023.6,5027.6
Exp/Cntr=0.3,0.1

Chan Stop Cuts=-1