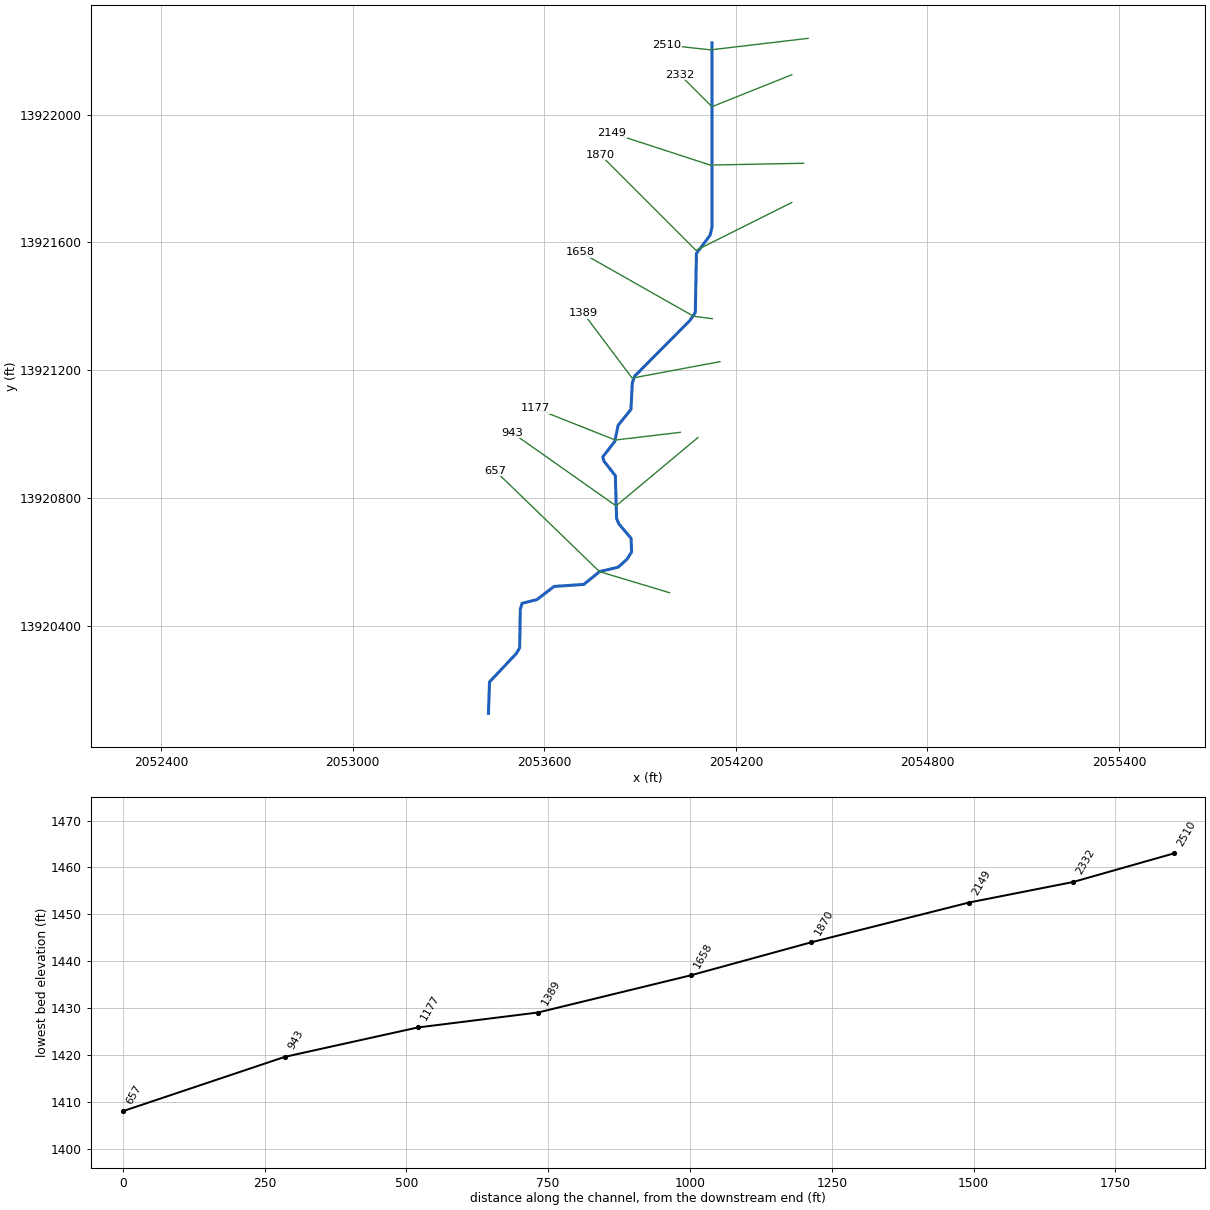
--- Stream0009_DS.prj (project) ---

Proj Title=Stream0009_DS Base Level Engineering
Current Plan=p01
Default Exp/Contr=0.3,0.1
English Units
Geom File=g01
Flow File=f01
Plan File=p01
BEGIN DESCRIPTION:
Stream0009_DS
END DESCRIPTION:

--- Stream0009_DS.p01 (plan) ---

Plan Title=Multiple Run
Short Identifier=Multiple
Geom File=g01
Flow File=f01
Subcritical Flow
K Sum by GR= 0
Std Step Tol= 0.01
Critical Tol= 0.01
Num of Std Step Trials= 20
Max Error Tol= 0.3
Flow Tol Ratio= 0.001
Split Flow NTrial= 30
Split Flow Tol= 0.02
Split Flow Ratio= 0.02
Log Output Level= 0
Friction Slope Method= 1
Unsteady Friction Slope Method= 2
Unsteady Bridges Friction Slope Method= 1
Parabolic Critical Depth
Global Vel Dist=  1 , 1 , 1
Global Log Level= 0
CheckData=True
Encroach Param= -1, 0, 0, 0
BEGIN DESCRIPTION:
Multiple Run
END DESCRIPTION:

--- Stream0009_DS.f01 (steady flow) ---

Flow Title=Multiple
Number of Profiles=7
Profile Names=10-year,25-year,50-year,1pct_min,100-year,1pct_plu,500-year
River Rch & RM= Stream0009_DS,Reach-1,2510
     234     360     470     300     599    1195     958
Boundary for River Rch & Prof#=Stream0009_DS,Reach-1,1
Up Type=0
Dn Type=3
Dn Slope=0.005
Boundary for River Rch & Prof#=Stream0009_DS,Reach-1,2
Up Type=0
Dn Type=3
Dn Slope=0.005
Boundary for River Rch & Prof#=Stream0009_DS,Reach-1,3
Up Type=0
Dn Type=3
Dn Slope=0.005
Boundary for River Rch & Prof#=Stream0009_DS,Reach-1,4
Up Type=0
Dn Type=3
Dn Slope=0.005
Boundary for River Rch & Prof#=Stream0009_DS,Reach-1,5
Up Type=0
Dn Type=3
Dn Slope=0.005
Boundary for River Rch & Prof#=Stream0009_DS,Reach-1,6
Up Type=0
Dn Type=3
Dn Slope=0.005
Boundary for River Rch & Prof#=Stream0009_DS,Reach-1,7
Up Type=0
Dn Type=3
Dn Slope=0.005

--- Stream0009_DS.g01 (geometry) ---

Geom Title=Existing Conditions

River Reach=Stream0009_DS,Reach-1
Reach XY= 30
      2054125.00     13922225.00      2054125.09     13921647.69
      2054119.25     13921622.67      2054076.38     13921565.34
      2054072.83     13921380.44      2054055.40     13921354.84
      2053882.86     13921181.17      2053875.52     13921159.78
      2053871.17     13921076.59      2053831.09     13921027.17
      2053820.58     13920976.64      2053783.04     13920928.32
      2053786.46     13920915.10      2053822.41     13920869.55
      2053826.25     13920735.50      2053833.20     13920718.92
      2053871.67     13920673.22      2053873.34     13920630.44
      2053858.94     13920607.94      2053831.43     13920583.02
      2053772.86     13920568.85      2053723.42     13920528.82
      2053630.53     13920522.57      2053576.78     13920481.30
      2053530.18     13920469.59      2053524.69     13920450.21
      2053522.81     13920330.46      2053511.60     13920311.70
      2053428.39     13920223.59      2053425.00     13920125.00

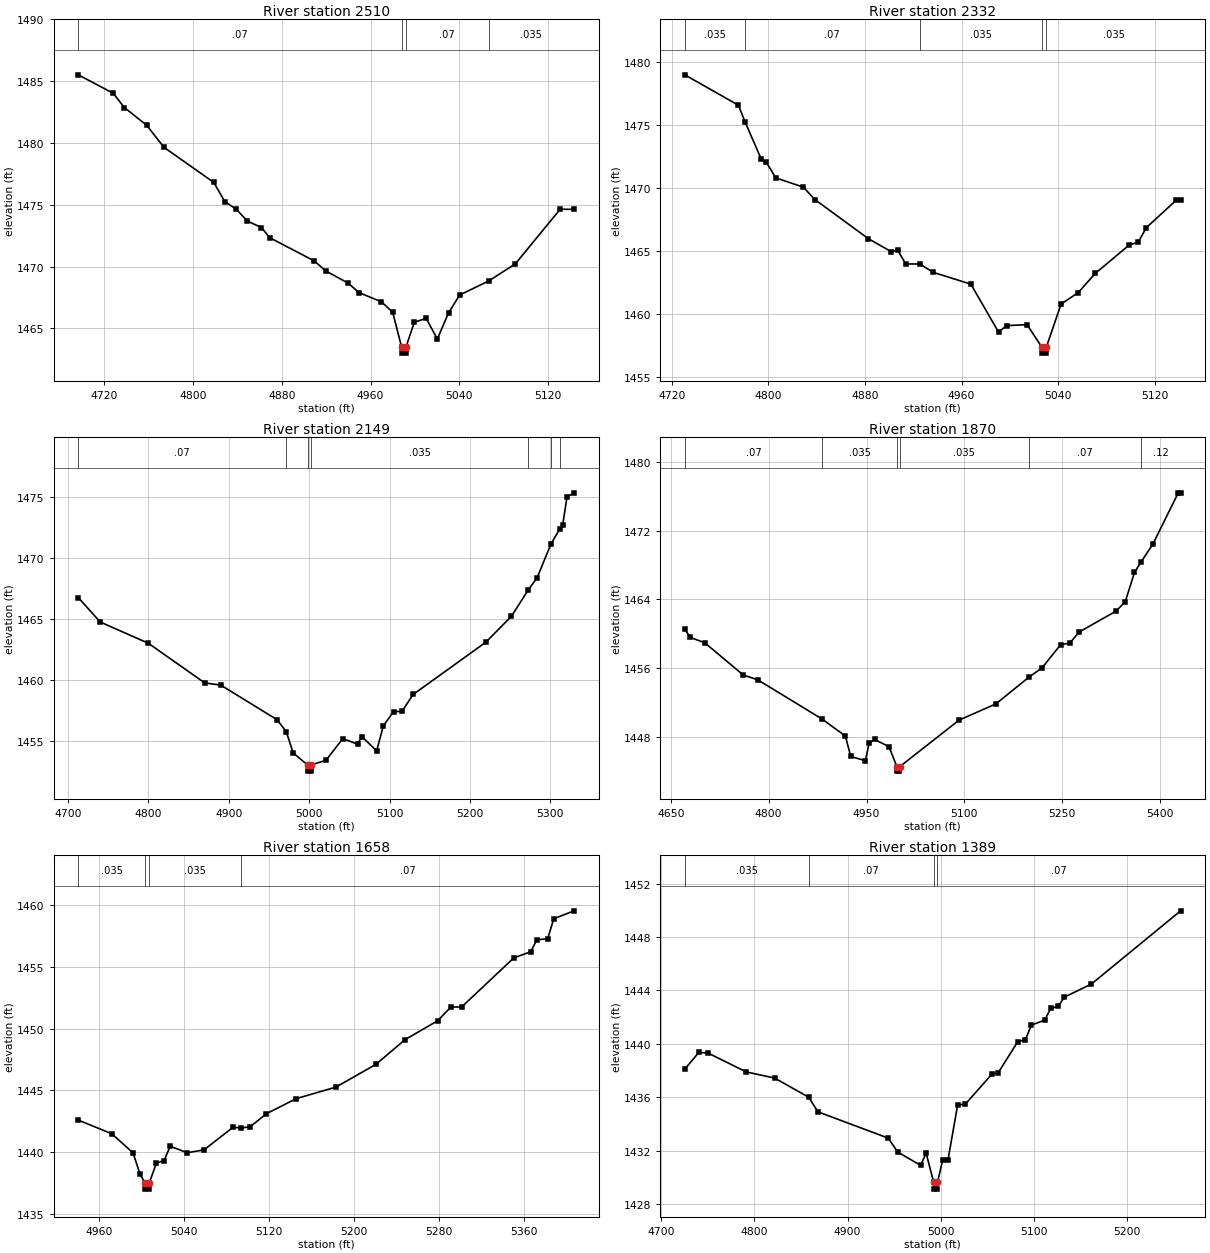
Type RM Length L Ch R = 1,2510,178,178,178
BEGIN DESCRIPTION:
Stream0009_DS 5.0
END DESCRIPTION:
XS GIS Cut Line= 3
      2054426.20     13922239.10      2054121.18     13922203.05
      2053982.43     13922218.02
#Sta/Elev= 30
  4696.7 1485.51  4728.1 1484.02  4738.2 1482.86  4758.3 1481.43  4773.8 1479.65
  4818.7 1476.81  4828.8 1475.24  4838.9 1474.65  4849.0 1473.68  4861.7 1473.16
  4869.1 1472.34  4909.4 1470.45  4919.4 1469.66  4939.6 1468.67  4949.7 1467.89
  4969.8 1467.15  4979.9 1466.31  4987.9 1463.50  4988.2 1463.00  4991.7 1463.00
  4991.9 1463.50  4999.4 1465.50  5010.1 1465.81  5020.1 1464.14  5030.2 1466.25
  5040.2 1467.70  5066.3 1468.83  5090.5 1470.23  5130.8 1474.64  5143.4 1474.63
#Mann=4,-1,0
  4696.7    0.07       0  4987.9    0.05       0  4991.9    0.07       0
  5066.3   0.035       0
Bank Sta=4987.9,4991.9
Exp/Cntr=0.3,0.1

Type RM Length L Ch R = 1,2332,183,183,183
BEGIN DESCRIPTION:
Stream0009_DS 4.0
END DESCRIPTION:
XS GIS Cut Line= 3
      2054374.95     13922124.98      2054125.00     13922025.00
      2054025.02     13922124.98
#Sta/Elev= 30
  4730.8 1478.97  4775.2 1476.56  4780.6 1475.26  4794.0 1472.31  4798.1 1472.07
  4806.1 1470.80  4829.0 1470.06  4838.5 1469.08  4882.9 1465.97  4901.7 1464.95
  4907.1 1465.06  4913.8 1463.97  4925.3 1463.97  4936.7 1463.30  4967.7 1462.37
  4990.6 1458.57  4997.3 1459.08  5014.2 1459.16  5026.3 1457.40  5026.5 1456.90
  5030.0 1456.90  5030.3 1457.40  5042.4 1460.79  5056.6 1461.70  5070.7 1463.22
  5099.0 1465.49  5106.1 1465.68  5113.1 1466.86  5137.9 1469.04  5141.4 1469.04
#Mann=5,-1,0
  4730.8   0.035       0  4780.6    0.07       0  4925.3   0.035       0
  5026.3   0.035       0  5030.3   0.035       0
Bank Sta=5026.3,5030.3
Exp/Cntr=0.3,0.1

Type RM Length L Ch R = 1,2149,279,279,279
BEGIN DESCRIPTION:
Stream0009_DS 3.5
END DESCRIPTION:
XS GIS Cut Line= 3
      2054412.16     13921847.88      2054119.56     13921842.23
      2053811.38     13921942.69
#Sta/Elev= 30
  4712.8 1466.78  4740.0 1464.78  4800.0 1463.03  4870.0 1459.78  4890.0 1459.60
  4960.0 1456.76  4971.4 1455.79  4980.0 1454.04  4998.0 1453.04  4998.3 1452.54
  5001.8 1452.54  5002.0 1453.04  5020.8 1453.43  5041.8 1455.21  5060.2 1454.75
  5065.4 1455.38  5083.9 1454.20  5092.1 1456.23  5104.9 1457.43  5115.4 1457.44
  5129.3 1458.83  5219.7 1463.12  5251.6 1465.25  5272.8 1467.44  5283.6 1468.42
  5300.6 1471.16  5311.5 1472.39  5315.3 1472.73  5320.7 1475.04  5329.6 1475.38
#Mann=7,-1,0
  4712.8    0.07       0  4971.4   0.035       0  4998.0   0.035       0
  5002.0   0.035       0  5272.8    0.07       0  5300.6    0.12       0
  5311.5    0.07       0
Bank Sta=4998,5002
Exp/Cntr=0.3,0.1

Type RM Length L Ch R = 1,1870,212,212,212
BEGIN DESCRIPTION:
Stream0009_DS 3.0
END DESCRIPTION:
XS GIS Cut Line= 3
      2054374.99     13921724.99      2054075.00     13921575.00
      2053774.97     13921875.03
#Sta/Elev= 30
  4671.6 1460.52  4680.0 1459.58  4702.3 1458.95  4761.0 1455.22  4783.4 1454.65
  4882.0 1450.09  4917.6 1448.12  4925.9 1445.74  4948.3 1445.25  4953.9 1447.27
  4962.3 1447.73  4984.6 1446.87  4996.6 1444.54  4996.9 1444.04  5000.4 1444.04
  5000.6 1444.54  5091.9 1449.97  5148.4 1451.86  5198.4 1454.93  5219.1 1456.05
  5247.4 1458.73  5261.6 1458.92  5275.7 1460.20  5332.3 1462.63  5346.4 1463.71
  5360.6 1467.13  5370.2 1468.29  5388.8 1470.42  5427.7 1476.38  5431.3 1476.38
#Mann=6,-1,0
  4671.6    0.07       0  4882.0   0.035       0  4996.6   0.035       0
  5000.6   0.035       0  5198.4    0.07       0  5370.2    0.12       0
Bank Sta=4996.6,5000.6
Exp/Cntr=0.3,0.1

Type RM Length L Ch R = 1,1658,269,269,269
BEGIN DESCRIPTION:
Stream0009_DS 2.5
END DESCRIPTION:
XS GIS Cut Line= 3
      2054126.09     13921361.11      2054067.19     13921368.81
      2053713.33     13921569.48
#Sta/Elev= 30
  4940.6 1442.60  4972.0 1441.50  4992.1 1439.95  4998.6 1438.23  5003.3 1437.52
  5003.6 1437.02  5007.1 1437.02  5007.3 1437.52  5014.0 1439.12  5021.2 1439.33
  5027.0 1440.49  5042.9 1439.96  5058.7 1440.19  5086.1 1442.02  5093.5 1441.97
  5102.0 1442.05  5117.5 1443.12  5145.3 1444.33  5182.8 1445.27  5220.3 1447.10
  5247.7 1449.10  5278.4 1450.63  5290.9 1451.74  5301.1 1451.75  5350.1 1455.72
  5366.0 1456.21  5371.7 1457.18  5381.9 1457.26  5387.6 1458.88  5406.8 1459.52
#Mann=4,-1,0
  4940.6   0.035       0  5003.3   0.035       0  5007.3   0.035       0
  5093.5    0.07       0
Bank Sta=5003.3,5007.3
Exp/Cntr=0.3,0.1

Type RM Length L Ch R = 1,1389,212,212,212
BEGIN DESCRIPTION:
Stream0009_DS 2.0
END DESCRIPTION:
XS GIS Cut Line= 3
      2054149.98     13921226.50      2053875.00     13921175.00
      2053722.95     13921377.51
#Sta/Elev= 30
  4725.1 1438.10  4740.3 1439.36  4750.5 1439.29  4791.2 1437.89  4821.7 1437.43
  4858.2 1436.00  4868.3 1434.90  4943.8 1432.93  4954.0 1431.89  4978.6 1430.89
  4984.5 1431.81  4992.7 1429.61  4992.9 1429.11  4996.4 1429.11  4996.7 1429.61
  5002.3 1431.28  5008.0 1431.28  5018.4 1435.42  5026.7 1435.48  5054.9 1437.70
  5062.1 1437.84  5083.0 1440.15  5091.3 1440.31  5097.6 1441.39  5112.1 1441.78
  5118.4 1442.65  5126.7 1442.81  5133.0 1443.49  5162.1 1444.47  5258.1 1449.96
#Mann=4,-1,0
  4725.1   0.035       0  4858.2    0.07       0  4992.7    0.05       0
  4996.7    0.07       0
Bank Sta=4992.7,4996.7
Exp/Cntr=0.3,0.1

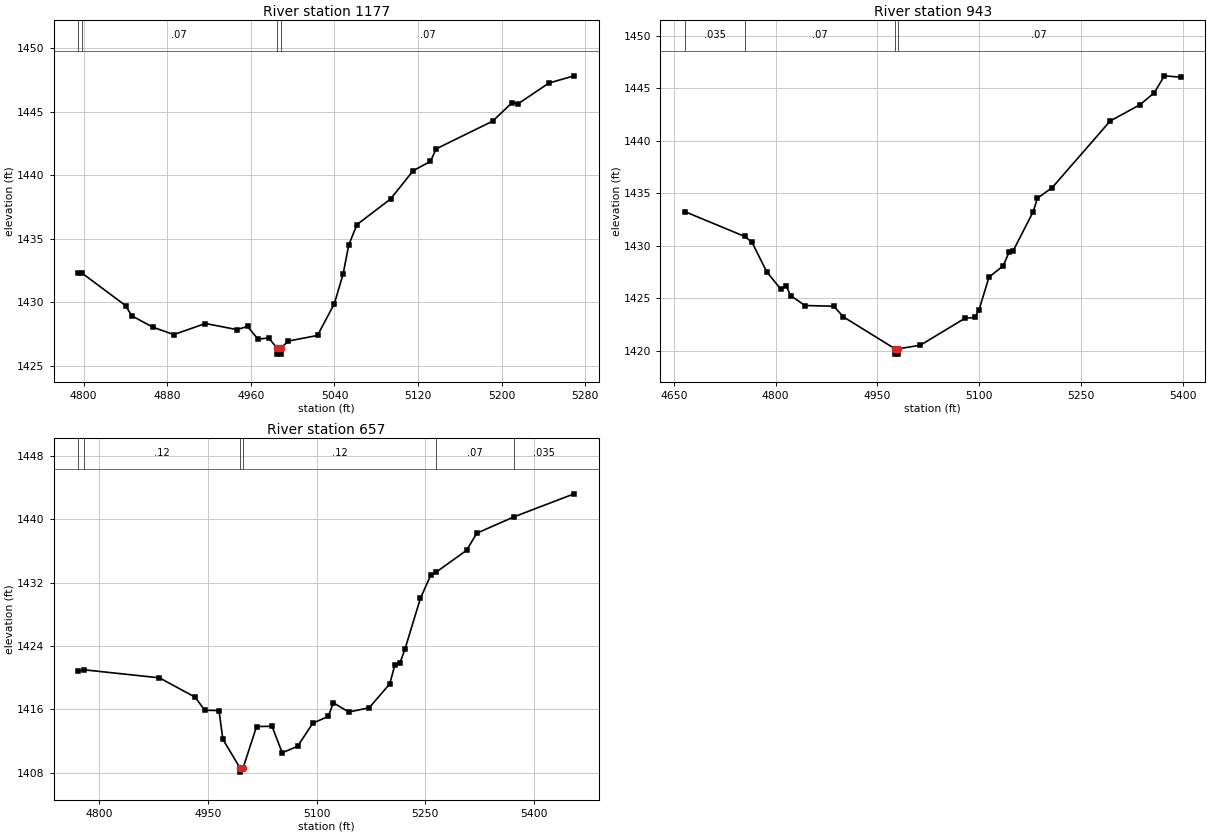
Type RM Length L Ch R = 1,1177,234,234,234
BEGIN DESCRIPTION:
Stream0009_DS 1.5
END DESCRIPTION:
XS GIS Cut Line= 3
      2054025.77     13921005.21      2053822.10     13920981.04
      2053571.78     13921080.61
#Sta/Elev= 30
  4794.9 1432.33  4798.0 1432.32  4840.1 1429.74  4846.0 1428.94  4866.2 1428.04
  4886.3 1427.46  4916.5 1428.33  4946.7 1427.85  4956.8 1428.10  4966.9 1427.10
  4976.9 1427.19  4985.0 1426.42  4985.3 1425.92  4988.8 1425.92  4989.0 1426.42
  4996.0 1426.95  5023.8 1427.39  5039.9 1429.89  5048.3 1432.23  5053.7 1434.51
  5061.5 1436.11  5093.7 1438.13  5115.3 1440.35  5131.9 1441.09  5137.3 1442.07
  5191.3 1444.25  5210.2 1445.72  5215.6 1445.61  5245.2 1447.25  5269.4 1447.82
#Mann=4,-1,0
  4794.9   0.035       0  4798.0    0.07       0  4985.0    0.05       0
  4989.0    0.07       0
Bank Sta=4985,4989
Exp/Cntr=0.3,0.1

Type RM Length L Ch R = 1,943,286,286,286
BEGIN DESCRIPTION:
Stream0009_DS 1.0
END DESCRIPTION:
XS GIS Cut Line= 3
      2054080.95     13920988.74      2053824.67     13920774.86
      2053500.10     13921003.47
#Sta/Elev= 30
  4666.2 1433.24  4754.3 1430.88  4765.1 1430.33  4786.9 1427.52  4807.7 1425.85
  4815.5 1426.19  4822.0 1425.25  4843.3 1424.30  4885.8 1424.23  4900.1 1423.21
  4976.2 1420.17  4976.5 1419.67  4980.0 1419.67  4980.2 1420.17  5013.4 1420.52
  5078.7 1423.07  5093.5 1423.17  5099.7 1423.84  5114.5 1427.00  5135.4 1428.07
  5144.1 1429.37  5150.2 1429.51  5179.8 1433.25  5185.9 1434.52  5207.5 1435.51
  5293.2 1441.87  5337.4 1443.43  5358.3 1444.57  5373.1 1446.17  5397.0 1446.04
#Mann=4,-1,0
  4666.2   0.035       0  4754.3    0.07       0  4976.2    0.05       0
  4980.2    0.07       0
Bank Sta=4976.2,4980.2
Exp/Cntr=0.3,0.1

Type RM Length L Ch R = 1,657,0,0,0
BEGIN DESCRIPTION:
Stream0145_DS 9.0
END DESCRIPTION:
XS GIS Cut Line= 3
      2053992.15     13920502.88      2053772.86     13920568.85
      2053445.52     13920885.46
#Sta/Elev= 30
  4771.0 1420.85  4779.3 1420.99  4882.9 1419.98  4932.2 1417.54  4945.5 1415.89
  4965.2 1415.85  4970.5 1412.23  4994.3 1408.58  4994.5 1408.08  4998.3 1408.58
  5017.0 1413.83  5038.3 1413.87  5052.4 1410.53  5073.6 1411.33  5094.7 1414.26
  5116.0 1415.11  5123.0 1416.83  5144.3 1415.66  5172.6 1416.21  5200.9 1419.22
  5207.8 1421.58  5215.0 1421.88  5222.0 1423.64  5243.3 1430.05  5257.5 1432.93
  5265.2 1433.34  5306.9 1436.07  5321.0 1438.23  5372.7 1440.31  5455.4 1443.20
#Mann=6,-1,0
  4771.0   0.035       0  4779.3    0.12       0  4994.3    0.05       0
  4998.3    0.12       0  5265.2    0.07       0  5372.7   0.035       0
Bank Sta=4994.3,4998.3
Exp/Cntr=0.3,0.1

Chan Stop Cuts=-1