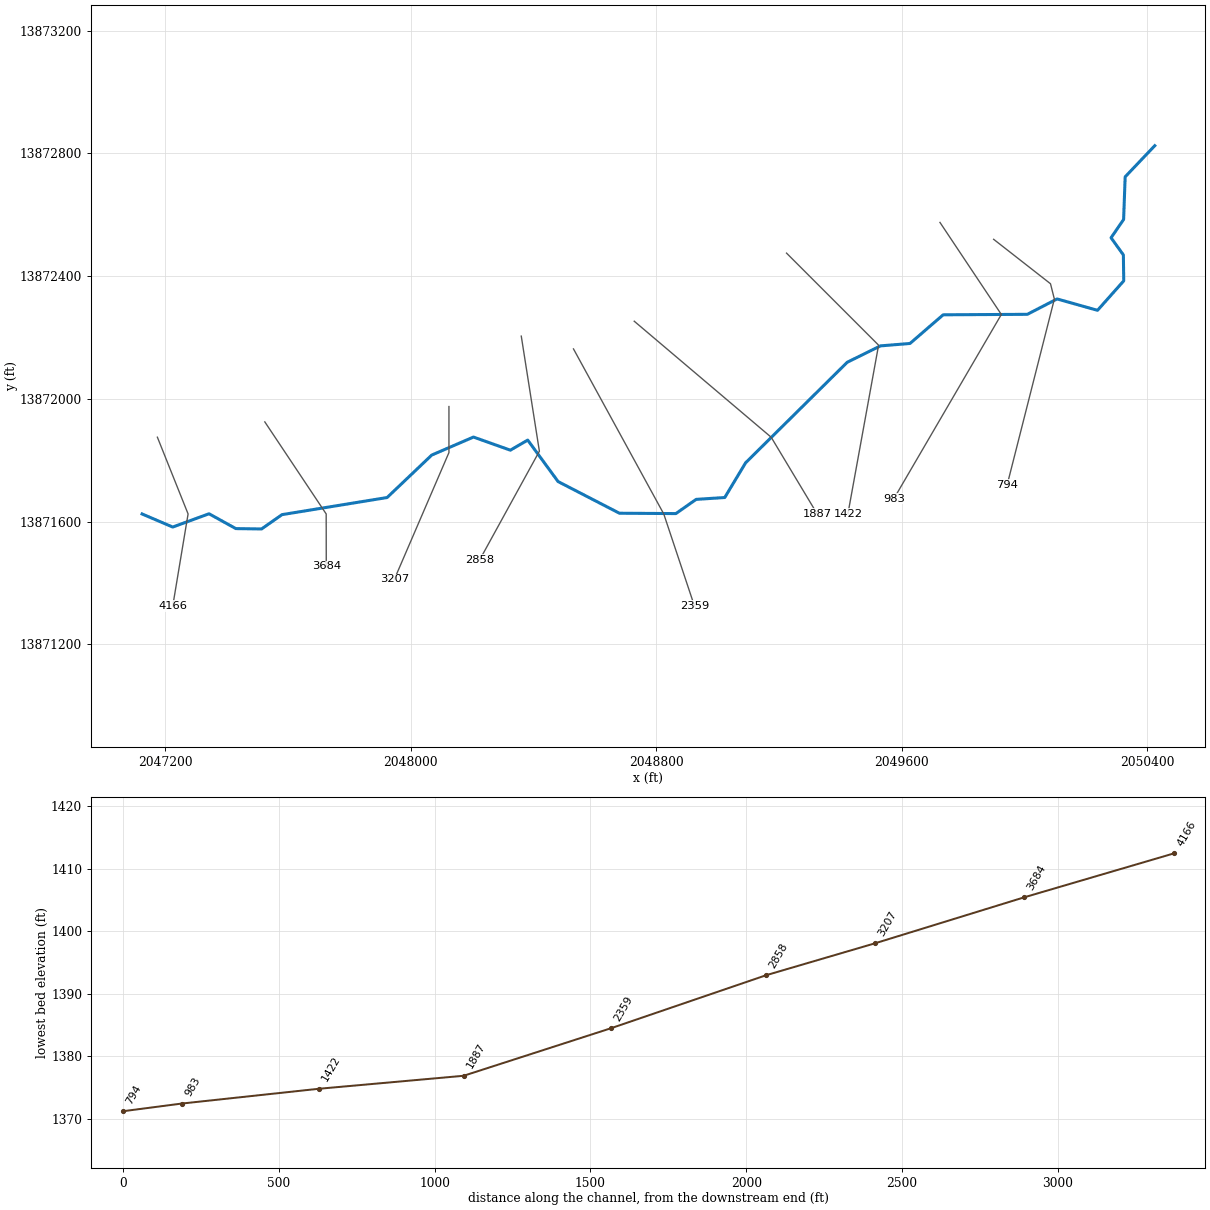
--- Stream0010_DS.prj (project) ---

Proj Title=Stream0010_DS Base Level Engineering
Current Plan=p01
Default Exp/Contr=0.3,0.1
English Units
Geom File=g01
Flow File=f01
Plan File=p01
BEGIN DESCRIPTION:
Stream0010_DS
END DESCRIPTION:

--- Stream0010_DS.p01 (plan) ---

Plan Title=Multiple Run
Short Identifier=Multiple
Geom File=g01
Flow File=f01
Subcritical Flow
K Sum by GR= 0
Std Step Tol= 0.01
Critical Tol= 0.01
Num of Std Step Trials= 20
Max Error Tol= 0.3
Flow Tol Ratio= 0.001
Split Flow NTrial= 30
Split Flow Tol= 0.02
Split Flow Ratio= 0.02
Log Output Level= 0
Friction Slope Method= 1
Unsteady Friction Slope Method= 2
Unsteady Bridges Friction Slope Method= 1
Parabolic Critical Depth
Global Vel Dist=  1 , 1 , 1
Global Log Level= 0
CheckData=True
Encroach Param= -1, 0, 0, 0
BEGIN DESCRIPTION:
Multiple Run
END DESCRIPTION:

--- Stream0010_DS.f01 (steady flow) ---

Flow Title=Multiple
Number of Profiles=7
Profile Names=10-year,25-year,50-year,1pct_min,100-year,1pct_plu,500-year
River Rch & RM= Stream0010_DS,Reach-1,4166
     873    1460    2013    1349    2691    5369    4745
River Rch & RM= Stream0010_DS,Reach-1,3684
    1176    1995    2778    1875    3741    7465    6708
Boundary for River Rch & Prof#=Stream0010_DS,Reach-1,1
Up Type=0
Dn Type=3
Dn Slope=0.005
Boundary for River Rch & Prof#=Stream0010_DS,Reach-1,2
Up Type=0
Dn Type=3
Dn Slope=0.005
Boundary for River Rch & Prof#=Stream0010_DS,Reach-1,3
Up Type=0
Dn Type=3
Dn Slope=0.005
Boundary for River Rch & Prof#=Stream0010_DS,Reach-1,4
Up Type=0
Dn Type=3
Dn Slope=0.005
Boundary for River Rch & Prof#=Stream0010_DS,Reach-1,5
Up Type=0
Dn Type=3
Dn Slope=0.005
Boundary for River Rch & Prof#=Stream0010_DS,Reach-1,6
Up Type=0
Dn Type=3
Dn Slope=0.005
Boundary for River Rch & Prof#=Stream0010_DS,Reach-1,7
Up Type=0
Dn Type=3
Dn Slope=0.005

--- Stream0010_DS.g01 (geometry) ---

Geom Title=Existing Conditions

River Reach=Stream0010_DS,Reach-1
Reach XY= 30
      2047125.00     13871625.00      2047224.96     13871582.32
      2047343.23     13871625.63      2047430.57     13871577.29
      2047514.45     13871576.10      2047580.94     13871622.73
      2047923.53     13871678.54      2048068.94     13871816.86
      2048204.95     13871875.59      2048325.10     13871832.81
      2048381.69     13871865.71      2048480.61     13871730.60
      2048680.52     13871627.35      2048864.50     13871626.22
      2048930.57     13871672.53      2049023.72     13871678.52
      2049091.66     13871791.66      2049422.70     13872119.17
      2049530.97     13872172.67      2049627.42     13872180.54
      2049735.44     13872273.94      2050009.78     13872275.52
      2050106.77     13872325.63      2050238.41     13872288.52
      2050323.90     13872384.62      2050322.64     13872469.10
      2050282.56     13872525.00      2050323.44     13872584.60
      2050328.49     13872723.55      2050425.00     13872825.00

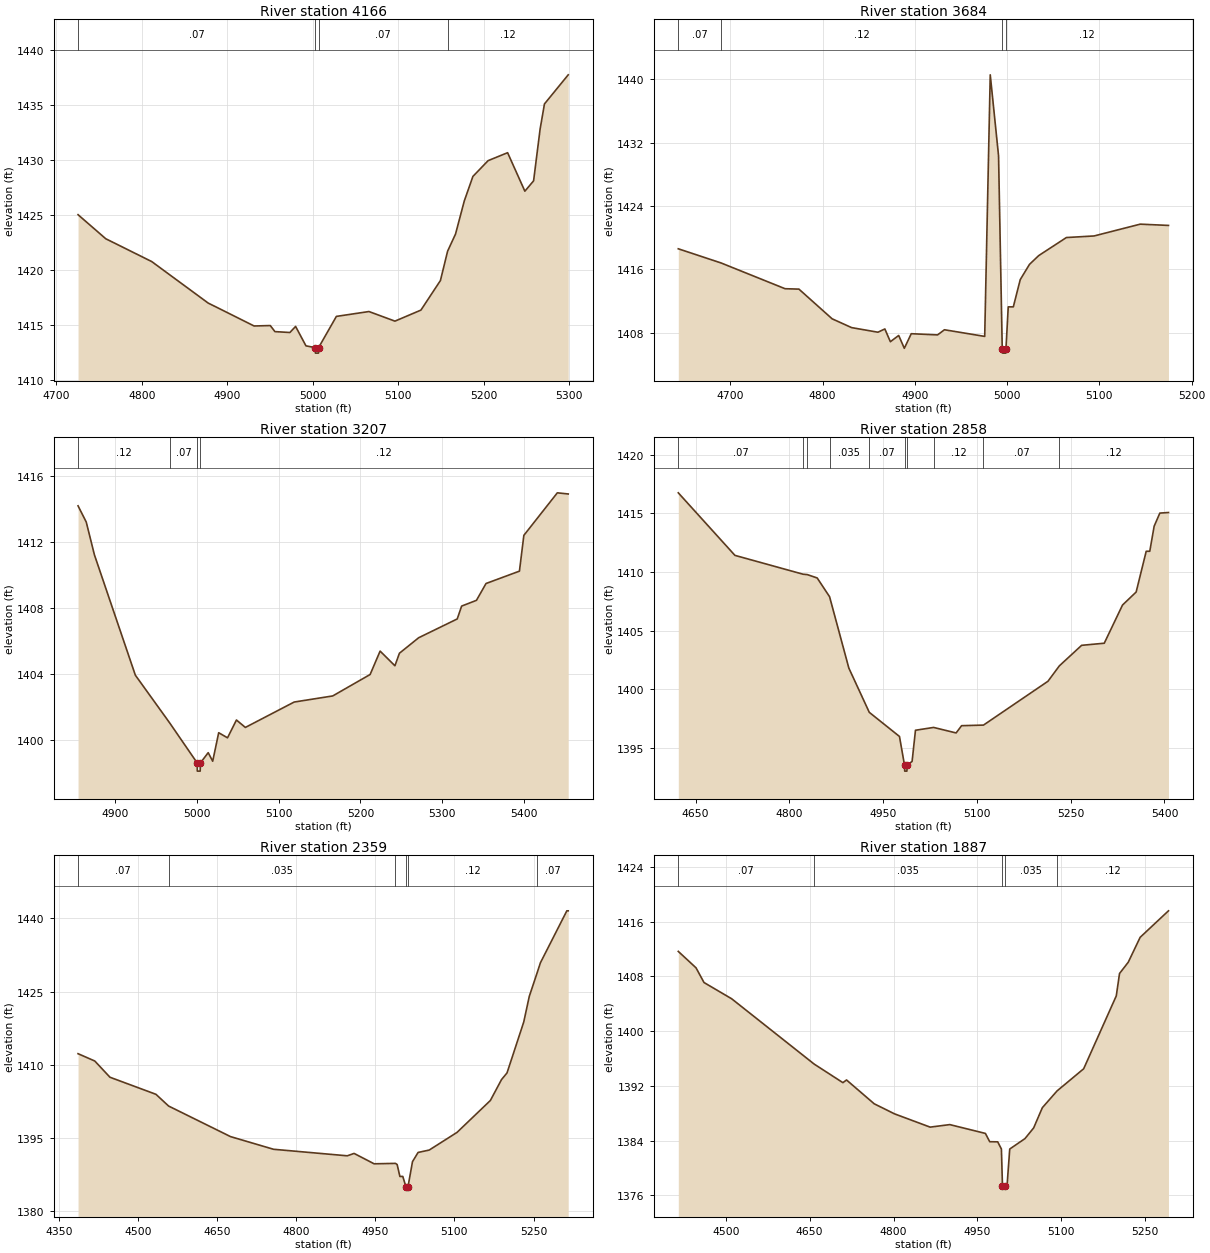
Type RM Length L Ch R = 1,4166,482,482,482
BEGIN DESCRIPTION:
Stream0010_DS 8.0
END DESCRIPTION:
XS GIS Cut Line= 3
      2047174.98     13871875.04      2047275.00     13871625.00
      2047225.01     13871325.04
#Sta/Elev= 30
  4725.5 1425.03  4757.9 1422.85  4811.7 1420.78  4877.7 1417.02  4931.5 1414.94
  4950.4 1414.98  4955.8 1414.43  4973.3 1414.35  4980.0 1414.90  4992.1 1413.14
  5002.9 1412.98  5003.2 1412.48  5006.7 1412.48  5006.9 1412.98  5027.7 1415.81
  5065.8 1416.25  5096.2 1415.38  5126.6 1416.38  5149.4 1419.06  5157.8 1421.72
  5167.1 1423.28  5177.3 1426.27  5187.4 1428.50  5205.2 1429.93  5228.0 1430.65
  5248.2 1427.16  5258.4 1428.10  5266.0 1432.78  5271.1 1435.07  5298.9 1437.71
#Mann=4,-1,0
  4725.5    0.07       0  5002.9    0.05       0  5006.9    0.07       0
  5157.8    0.12       0
Bank Sta=5002.9,5006.9
Exp/Cntr=0.3,0.1

Type RM Length L Ch R = 1,3684,477,477,477
BEGIN DESCRIPTION:
Stream0010_DS 7.0
END DESCRIPTION:
XS GIS Cut Line= 3
      2047525.01     13871924.98      2047725.00     13871625.00
      2047725.27     13871454.43
#Sta/Elev= 30
  4643.7 1418.60  4690.1 1416.81  4759.4 1413.56  4774.4 1413.51  4810.4 1409.76
  4831.5 1408.65  4860.0 1408.07  4867.5 1408.48  4873.5 1406.87  4882.5 1407.66
  4888.6 1406.04  4896.1 1407.88  4924.6 1407.73  4932.1 1408.38  4975.7 1407.54
  4981.7 1440.56  4990.7 1430.33  4994.7 1405.93  4995.0 1405.43  4998.5 1405.43
  4998.7 1405.93  5001.2 1411.27  5006.7 1411.27  5014.2 1414.71  5024.2 1416.63
  5034.2 1417.74  5064.2 1420.02  5094.2 1420.22  5144.2 1421.71  5174.8 1421.55
#Mann=4,-1,0
  4643.7    0.07       0  4690.1    0.12       0  4994.7    0.05       0
  4998.7    0.12       0
Bank Sta=4994.7,4998.7
Exp/Cntr=0.3,0.1

Type RM Length L Ch R = 1,3207,349,349,349
BEGIN DESCRIPTION:
Stream0010_DS 6.0
END DESCRIPTION:
XS GIS Cut Line= 3
      2048125.00     13871974.98      2048125.00     13871825.00
      2047947.48     13871412.78
#Sta/Elev= 30
  4855.1 1414.19  4865.1 1413.21  4875.1 1411.22  4925.1 1403.92  4967.1 1401.02
  5000.6 1398.60  5000.8 1398.10  5004.3 1398.10  5004.6 1398.60  5014.1 1399.22
  5019.6 1398.70  5026.9 1400.43  5037.7 1400.12  5048.6 1401.20  5059.5 1400.75
  5119.1 1402.29  5166.2 1402.66  5211.9 1403.96  5224.1 1405.38  5242.2 1404.49
  5247.7 1405.25  5271.2 1406.19  5318.3 1407.33  5323.7 1408.11  5341.8 1408.46
  5353.5 1409.48  5394.3 1410.23  5399.7 1412.40  5440.6 1414.98  5453.9 1414.91
#Mann=4,-1,0
  4855.1    0.12       0  4967.1    0.07       0  5000.6    0.05       0
  5004.6    0.12       0
Bank Sta=5000.6,5004.6
Exp/Cntr=0.3,0.1

Type RM Length L Ch R = 1,2858,499,499,499
BEGIN DESCRIPTION:
Stream0010_DS 5.0
END DESCRIPTION:
XS GIS Cut Line= 3
      2048360.68     13872204.48      2048419.71     13871829.47
      2048224.98     13871474.97
#Sta/Elev= 30
  4622.3 1416.76  4712.9 1411.42  4822.0 1409.81  4828.6 1409.78  4844.5 1409.49
  4864.3 1407.89  4895.1 1401.80  4927.8 1398.02  4976.1 1395.96  4984.2 1393.50
  4984.5 1393.00  4988.0 1393.00  4988.2 1393.50  4996.3 1393.83  5001.7 1396.49
  5030.7 1396.73  5066.7 1396.26  5075.5 1396.88  5110.5 1396.93  5213.6 1400.67
  5231.9 1401.99  5267.5 1403.74  5303.7 1403.92  5332.9 1407.18  5354.7 1408.29
  5370.8 1411.77  5376.5 1411.77  5383.5 1413.91  5392.6 1415.03  5406.4 1415.08
#Mann=10,-1,0
  4622.3    0.07       0  4822.0    0.12       0  4828.6    0.07       0
  4864.3   0.035       0  4927.8    0.07       0  4984.2    0.05       0
  4988.2    0.07       0  5030.7    0.12       0  5110.5    0.07       0
  5231.9    0.12       0
Bank Sta=4984.2,4988.2
Exp/Cntr=0.3,0.1

Type RM Length L Ch R = 1,2359,472,472,472
BEGIN DESCRIPTION:
Stream0010_DS 4.0
END DESCRIPTION:
XS GIS Cut Line= 3
      2048530.84     13872162.77      2048825.00     13871625.00
      2048925.00     13871325.00
#Sta/Elev= 30
  4386.6 1412.27  4418.3 1410.77  4447.1 1407.44  4534.3 1403.94  4558.2 1401.54
  4675.6 1395.27  4757.2 1392.67  4897.0 1391.33  4909.9 1391.82  4947.9 1389.69
  4988.3 1389.78  4991.5 1389.55  4996.7 1387.10  5002.2 1387.10  5008.1 1385.00
  5008.4 1384.50  5012.1 1385.00  5020.6 1390.13  5031.2 1392.02  5052.3 1392.51
  5105.0 1396.13  5168.2 1402.67  5189.3 1406.95  5199.8 1408.33  5231.5 1418.77
  5242.0 1424.03  5256.2 1428.63  5263.1 1430.91  5313.2 1441.56  5315.8 1441.56
#Mann=6,-1,0
  4386.6    0.07       0  4558.2   0.035       0  4988.3    0.12       0
  5008.1    0.05       0  5012.1    0.12       0  5256.2    0.07       0
Bank Sta=5008.1,5012.1
Exp/Cntr=0.3,0.1

Type RM Length L Ch R = 1,1887,465,465,465
BEGIN DESCRIPTION:
Stream0010_DS 3.0
END DESCRIPTION:
XS GIS Cut Line= 3
      2048728.78     13872253.05      2049175.00     13871875.00
      2049325.01     13871624.99
#Sta/Elev= 30
  4415.2 1411.65  4446.9 1409.25  4461.2 1407.10  4510.6 1404.73  4658.2 1395.18
  4709.5 1392.47  4716.0 1392.86  4765.5 1389.38  4801.8 1387.91  4865.5 1385.97
  4900.6 1386.34  4964.3 1385.05  4972.0 1383.84  4986.3 1383.82  4992.9 1382.77
  4994.8 1377.41  4995.0 1376.91  4998.8 1377.41  5003.0 1377.41  5007.8 1382.77
  5035.0 1384.29  5050.6 1385.86  5066.1 1388.81  5092.4 1391.26  5140.0 1394.50
  5198.3 1405.15  5204.1 1408.42  5219.7 1410.07  5241.0 1413.71  5291.6 1417.58
#Mann=5,-1,0
  4415.2    0.07       0  4658.2   0.035       0  4994.8   0.035       0
  4998.8   0.035       0  5092.4    0.12       0
Bank Sta=4994.8,4998.8
Exp/Cntr=0.3,0.1

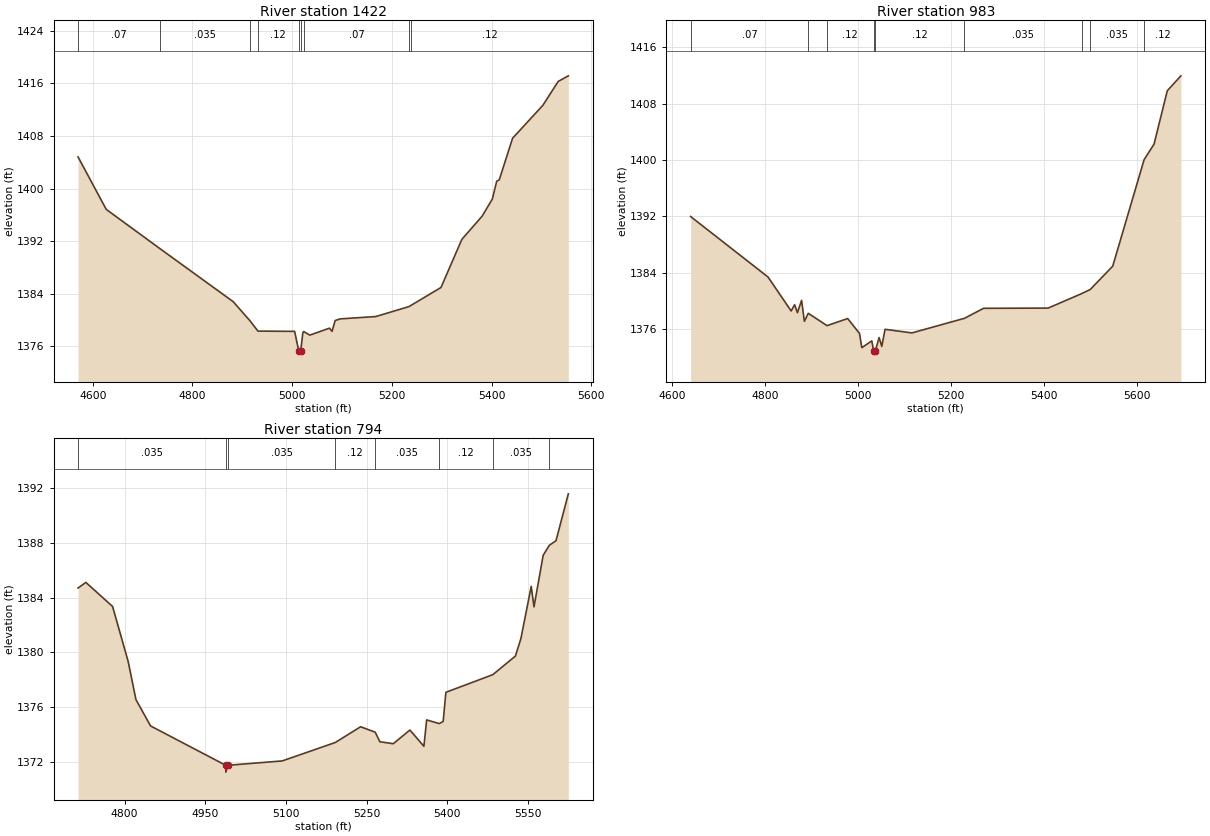
Type RM Length L Ch R = 1,1422,439,439,439
BEGIN DESCRIPTION:
Stream0010_DS 2.0
END DESCRIPTION:
XS GIS Cut Line= 3
      2049225.02     13872474.98      2049525.00     13872175.00
      2049424.99     13871624.96
#Sta/Elev= 30
  4570.6 1404.81  4627.1 1396.84  4734.1 1390.91  4881.7 1382.81  4915.0 1379.94
  4931.4 1378.33  5005.0 1378.29  5013.2 1375.33  5013.4 1374.83  5017.2 1375.33
  5021.5 1378.12  5023.2 1378.26  5035.5 1377.72  5074.9 1378.78  5080.0 1378.30
  5086.3 1379.94  5096.5 1380.19  5167.6 1380.54  5234.8 1382.07  5237.7 1382.21
  5298.5 1384.96  5340.4 1392.28  5381.1 1395.81  5401.4 1398.40  5410.3 1401.12
  5415.4 1401.33  5442.1 1407.65  5503.0 1412.67  5533.5 1416.28  5553.9 1417.14
#Mann=9,-1,0
  4570.6    0.07       0  4734.1   0.035       0  4915.0    0.07       0
  4931.4    0.12       0  5013.2    0.05       0  5017.2    0.12       0
  5023.2    0.07       0  5234.8   0.035       0  5237.7    0.12       0
Bank Sta=5013.2,5017.2
Exp/Cntr=0.3,0.1

Type RM Length L Ch R = 1,983,189,189,189
BEGIN DESCRIPTION:
Stream0010_DS 1.0
END DESCRIPTION:
XS GIS Cut Line= 3
      2049725.02     13872574.96      2049925.00     13872275.00
      2049575.02     13871675.03
#Sta/Elev= 30
  4639.4 1391.99  4806.1 1383.40  4855.7 1378.59  4863.2 1379.48  4869.2 1378.35
  4878.2 1380.10  4884.2 1377.12  4892.6 1378.26  4933.0 1376.51  4977.4 1377.52
  5002.8 1375.41  5007.8 1373.39  5029.3 1374.35  5033.1 1372.97  5033.3 1372.47
  5037.1 1372.97  5045.0 1374.82  5050.8 1373.57  5057.8 1375.99  5115.7 1375.48
  5228.7 1377.55  5269.9 1378.97  5408.8 1379.00  5480.8 1381.05  5499.3 1381.63
  5547.8 1384.95  5615.3 1400.05  5636.7 1402.26  5665.2 1409.83  5694.5 1411.95
#Mann=9,-1,0
  4639.4    0.07       0  4892.6   0.035       0  4933.0    0.12       0
  5033.1    0.05       0  5037.1    0.12       0  5228.7   0.035       0
  5480.8    0.07       0  5499.3   0.035       0  5615.3    0.12       0
Bank Sta=5033.1,5037.1
Exp/Cntr=0.3,0.1

Type RM Length L Ch R = 1,794,0,0,0
BEGIN DESCRIPTION:
Stream0010_DS 0.0
END DESCRIPTION:
XS GIS Cut Line= 4
      2049899.92     13872519.96      2050085.19     13872375.17
      2050097.77     13872325.27      2049943.92     13871719.61
#Sta/Elev= 30
  4713.4 1384.71  4727.9 1385.12  4777.6 1383.36  4806.6 1379.33  4821.0 1376.55
  4848.2 1374.62  4988.0 1371.74  4988.2 1371.24  4992.0 1371.74  5093.1 1372.06
  5191.8 1373.41  5238.7 1374.56  5265.9 1374.16  5274.5 1373.46  5299.5 1373.32
  5330.4 1374.32  5356.4 1373.13  5361.5 1375.06  5384.9 1374.79  5392.2 1374.95
  5397.3 1377.08  5484.5 1378.37  5526.5 1379.73  5536.8 1381.02  5555.9 1384.83
  5561.1 1383.33  5578.1 1387.10  5589.5 1387.83  5602.0 1388.17  5624.9 1391.60
#Mann=8,-1,0
  4713.4   0.035       0  4988.0   0.035       0  4992.0   0.035       0
  5191.8    0.12       0  5265.9   0.035       0  5384.9    0.12       0
  5484.5   0.035       0  5589.5    0.12       0
Bank Sta=4988,4992
Exp/Cntr=0.3,0.1

Chan Stop Cuts=-1