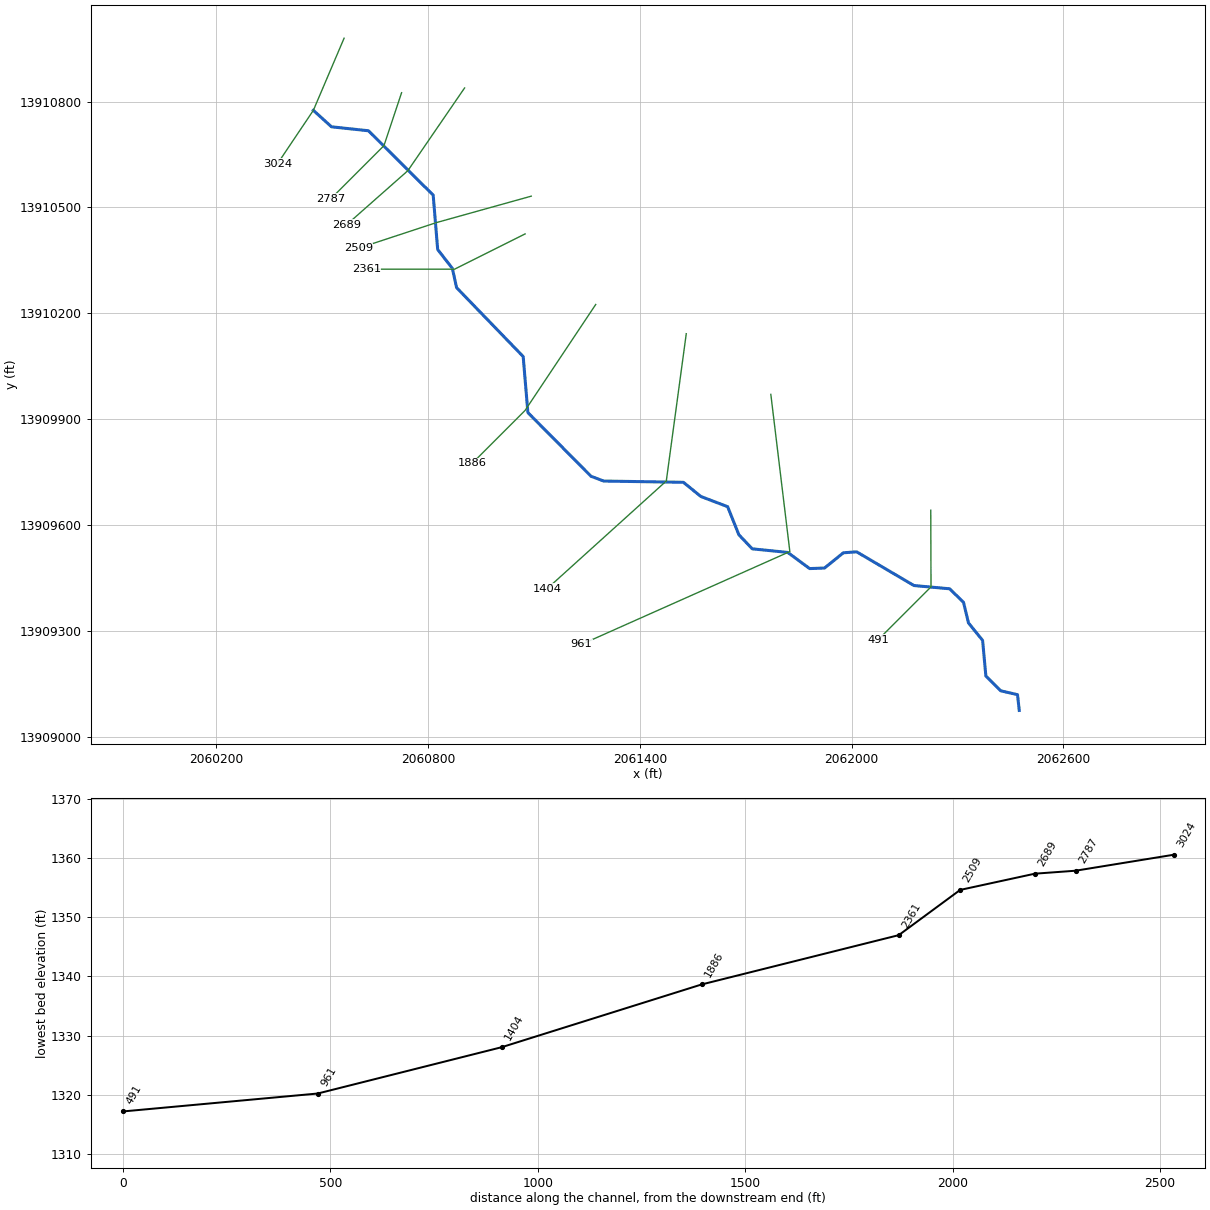
--- Stream0011_DS.prj (project) ---

Proj Title=Stream0011_DS Base Level Engineering
Current Plan=p01
Default Exp/Contr=0.3,0.1
English Units
Geom File=g01
Flow File=f01
Plan File=p01
Y Axis Title=Elevation
X Axis Title(PF)=Main Channel Distance
X Axis Title(XS)=Station
BEGIN DESCRIPTION:
Stream0011_DS
END DESCRIPTION:
DSS Export Rating Curves= 0
DSS Export Rating Curve Sorted= 0
DSS Export Volume Flow Curves= 0
DXF OffsetX= 0
DXF OffsetY= 0
DXF ScaleX= 1
DXF ScaleY= 10

--- Stream0011_DS.p01 (plan) ---

Plan Title=Multiple Run
Short Identifier=Multiple
Geom File=g01
Flow File=f01
Subcritical Flow
K Sum by GR= 0
Std Step Tol= 0.01
Critical Tol= 0.01
Num of Std Step Trials= 20
Max Error Tol= 0.3
Flow Tol Ratio= 0.001
Split Flow NTrial= 30
Split Flow Tol= 0.02
Split Flow Ratio= 0.02
Log Output Level= 0
Friction Slope Method= 1
Unsteady Friction Slope Method= 2
Unsteady Bridges Friction Slope Method= 1
Parabolic Critical Depth
Global Vel Dist=  1 , 1 , 1
Global Log Level= 0
CheckData=True
Encroach Param= -1, 0, 0, 0
BEGIN DESCRIPTION:
Multiple Run
END DESCRIPTION:

--- Stream0011_DS.f01 (steady flow) ---

Flow Title=Multiple
Number of Profiles=7
Profile Names=10-year,25-year,50-year,1pct_min,100-year,1pct_plu,500-year
River Rch & RM= Stream0011_DS,Reach-1,3024
     341     541     720     468     933    1861    1546
River Rch & RM= Stream0011_DS,Reach-1,2689
     528     854    1152     756    1508    3008    2549
Boundary for River Rch & Prof#=Stream0011_DS,Reach-1,1
Up Type=0
Dn Type=3
Dn Slope=0.005
Boundary for River Rch & Prof#=Stream0011_DS,Reach-1,2
Up Type=0
Dn Type=3
Dn Slope=0.005
Boundary for River Rch & Prof#=Stream0011_DS,Reach-1,3
Up Type=0
Dn Type=3
Dn Slope=0.005
Boundary for River Rch & Prof#=Stream0011_DS,Reach-1,4
Up Type=0
Dn Type=3
Dn Slope=0.005
Boundary for River Rch & Prof#=Stream0011_DS,Reach-1,5
Up Type=0
Dn Type=3
Dn Slope=0.005
Boundary for River Rch & Prof#=Stream0011_DS,Reach-1,6
Up Type=0
Dn Type=3
Dn Slope=0.005
Boundary for River Rch & Prof#=Stream0011_DS,Reach-1,7
Up Type=0
Dn Type=3
Dn Slope=0.005

--- Stream0011_DS.g01 (geometry) ---

Geom Title=Existing Conditions
Program Version=4.10

River Reach=Stream0011_DS   ,Reach-1
Reach XY= 30
        2060475.       13910775.      2060526.41     13910728.39
      2060631.18     13910717.16      2060814.52      13910534.8
      2060827.25     13910380.93      2060868.86     13910327.17
      2060880.83      13910272.7      2061069.53     13910077.45
      2061082.82     13909918.81      2061261.68     13909738.37
      2061297.65      13909724.8      2061523.45     13909721.25
      2061572.85     13909681.15      2061648.84     13909652.14
      2061680.75     13909572.45      2061718.55     13909532.75
      2061819.03     13909522.62      2061881.12     13909476.82
      2061923.28      13909478.4      2061976.72      13909521.6
      2062014.31     13909524.25      2062176.59     13909428.83
      2062277.68     13909419.58        2062317.     13909381.38
      2062331.15     13909322.85      2062371.17     13909273.41
      2062380.42     13909172.33      2062422.54     13909130.58
      2062470.04     13909119.65        2062475.       13909075.

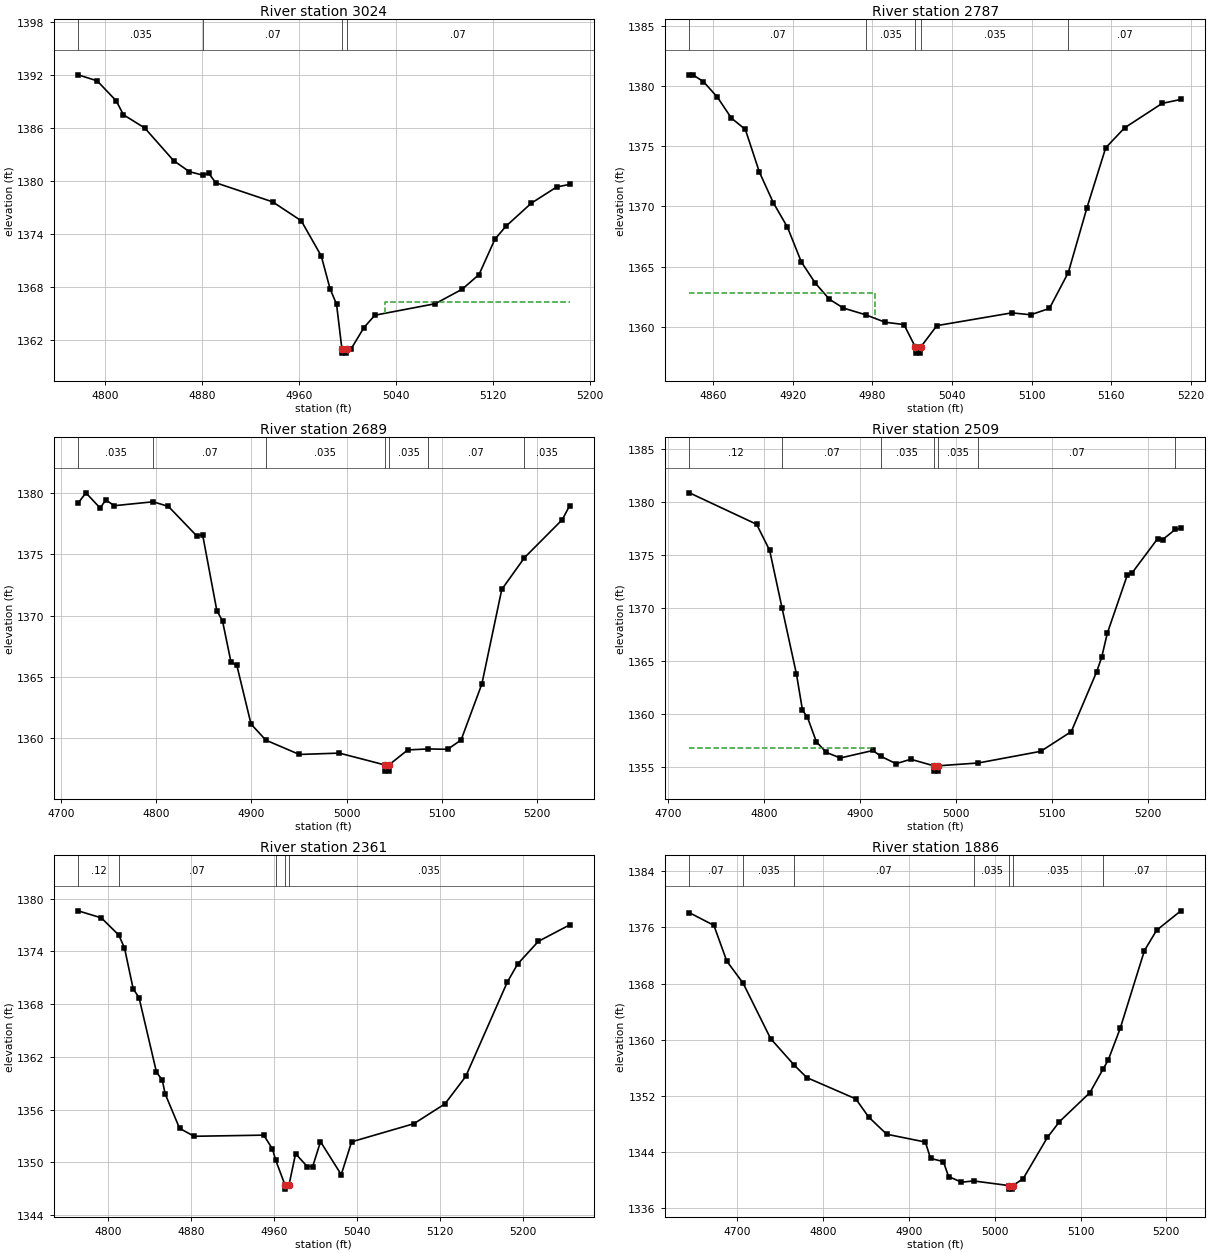
Type RM Length L Ch R = 1 ,3024    ,237,237,237
BEGIN DESCRIPTION:
Stream0011_DS 7.0
END DESCRIPTION:
XS GIS Cut Line= 3
      2060562.08     13910979.43        2060475.       13910775.
      2060372.94     13910623.11
#Sta/Elev= 30
  4777.8 1392.01  4793.5 1391.33  4809.2 1389.07  4815.2 1387.49  4832.8 1385.99
  4856.5 1382.31  4869.6 1381.05  4880.8 1380.66  4885.5 1380.87  4891.3  1379.8
  4938.2 1377.64  4961.8  1375.5  4978.3 1371.52  4985.5 1367.83  4990.9 1366.06
  4995.3 1361.03  4995.5 1360.53    4999 1360.53  4999.3 1361.03    5003 1361.03
  5013.5 1363.42  5022.5 1364.82  5072.3 1366.12  5094.5 1367.76  5108.4 1369.42
  5121.5 1373.42  5130.5 1374.87  5151.5 1377.49  5172.5 1379.33    5183 1379.61
#Mann= 4 ,-1 , 0
  4777.8    .035       0  4880.8     .07       0  4995.3     .05       0
  4999.3     .07       0
#XS Ineff= 2 , 0
       0                  5031.1       0 1366.27
Permanent Ineff=
       F       F
Bank Sta=4995.3,4999.3
XS Rating Curve= 0 ,0
Exp/Cntr=0.3,0.1

Type RM Length L Ch R = 1 ,2787    ,98,98,98
BEGIN DESCRIPTION:
Stream0011_DS 6.0
END DESCRIPTION:
XS GIS Cut Line= 3
      2060724.99     13910824.97        2060675.       13910675.
      2060525.01     13910525.01
#Sta/Elev= 30
  4842.2 1380.91  4844.8 1380.91  4852.7 1380.35  4863.3 1379.05  4873.8 1377.32
  4884.3 1376.38  4894.9 1372.84  4905.4  1370.3    4916 1368.28  4926.5 1365.39
    4937 1363.64  4947.6  1362.3  4958.1 1361.57  4974.9 1361.01  4989.7 1360.39
  5003.8  1360.2  5012.4 1358.33  5012.7 1357.83  5016.2 1357.83  5016.4 1358.33
  5028.6 1360.11  5085.1 1361.17  5099.3 1361.01  5113.4 1361.54  5127.6 1364.51
  5141.7  1369.9  5155.8 1374.86    5170 1376.51  5198.3 1378.54  5212.4 1378.87
#Mann= 5 ,-1 , 0
  4842.2     .07       0  4974.9    .035       0  5012.4    .035       0
  5016.4    .035       0  5127.6     .07       0
#XS Ineff= 2 , 0
       0 4981.72 1362.82               0
Permanent Ineff=
       F       F
Bank Sta=5012.4,5016.4
XS Rating Curve= 0 ,0
Exp/Cntr=0.3,0.1

Type RM Length L Ch R = 1 ,2689    ,180,180,180
BEGIN DESCRIPTION:
Stream0011_DS 5.2
END DESCRIPTION:
XS GIS Cut Line= 3
      2060903.46     13910838.42      2060742.87     13910604.22
      2060569.09     13910450.78
#Sta/Elev= 30
  4718.2 1379.19  4726.4 1380.03  4741.3 1378.79  4747.3 1379.45  4756.2 1378.98
  4796.9  1379.3    4813 1378.92  4842.8 1376.51  4848.9 1376.61  4863.8 1370.43
  4869.8 1369.57  4878.7 1366.21  4884.8 1365.96  4899.7 1361.17  4915.2 1359.86
  4950.4 1358.69  4992.4  1358.8  5040.4 1357.83  5040.6 1357.33  5044.1 1357.33
  5044.4 1357.83  5064.2 1359.06  5085.5 1359.14  5106.1 1359.11  5120.2 1359.87
    5142 1364.44  5162.9 1372.15  5186.7 1374.74  5226.4 1377.84    5234 1378.96
#Mann= 7 ,-1 , 0
  4718.2    .035       0  4796.9     .07       0  4915.2    .035       0
  5040.4    .035       0  5044.4    .035       0  5085.5     .07       0
  5186.7    .035       0
Bank Sta=5040.4,5044.4
XS Rating Curve= 0 ,0
Exp/Cntr=0.3,0.1

Type RM Length L Ch R = 1 ,2509    ,148,148,148
BEGIN DESCRIPTION:
Stream0011_DS 5.1
END DESCRIPTION:
XS GIS Cut Line= 3
      2061092.39     13910531.93      2060823.35      13910456.9
      2060602.14     13910384.06
#Sta/Elev= 30
  4722.5 1380.86  4792.5 1377.89  4806.1 1375.43    4819    1370    4834 1363.77
  4840.3 1360.35  4845.5 1359.67  4854.8 1357.36  4865.1 1356.36  4879.7 1355.83
  4913.8 1356.54  4921.8    1356  4937.8 1355.29  4953.2 1355.71  4977.3 1355.09
  4977.6 1354.59  4981.1 1354.59  4981.3 1355.09  5023.6 1355.36  5088.7 1356.46
  5120.5 1358.32    5147 1363.98  5152.2 1365.34    5158 1367.59  5178.8 1373.07
  5183.7 1373.28  5210.5 1376.53  5215.8 1376.45    5229 1377.41  5234.7 1377.51
#Mann= 7 ,-1 , 0
  4722.5     .12       0    4819     .07       0  4921.8    .035       0
  4977.3    .035       0  4981.3    .035       0  5023.6     .07       0
    5229    .035       0
#XS Ineff= 2 , 0
       0 4914.16  1356.8               0
Permanent Ineff=
       F       F
Bank Sta=4977.3,4981.3
XS Rating Curve= 0 ,0
Exp/Cntr=0.3,0.1

Type RM Length L Ch R = 1 ,2361    ,475,475,475
BEGIN DESCRIPTION:
Stream0011_DS 5.0
END DESCRIPTION:
XS GIS Cut Line= 3
      2061075.01     13910425.01        2060875.       13910325.
      2060625.02       13910325.
#Sta/Elev= 30
  4771.3 1378.61  4793.7 1377.81  4810.5 1375.85    4816 1374.39  4824.4 1369.72
    4830 1368.75  4846.8 1360.27  4852.4 1359.36  4855.2 1357.79  4869.1 1353.87
  4883.1 1352.97  4950.2  1353.1  4958.6 1351.53  4961.7 1350.26  4970.6 1347.46
  4970.8 1346.96  4974.6 1347.46  4980.9 1350.99  4992.1 1349.53  4997.4 1349.53
  5004.9 1352.36  5024.9 1348.61  5034.9 1352.34  5094.9  1354.4  5124.9 1356.66
  5144.9 1359.78  5184.9 1370.49  5194.9 1372.56  5214.9 1375.14  5244.9    1377
#Mann= 5 ,-1 , 0
  4771.3     .12       0  4810.5     .07       0  4961.7    .035       0
  4970.6    .035       0  4974.6    .035       0
Bank Sta=4970.6,4974.6
XS Rating Curve= 0 ,0
Exp/Cntr=0.3,0.1

Type RM Length L Ch R = 1 ,1886    ,482,482,482
BEGIN DESCRIPTION:
Stream0011_DS 4.0
END DESCRIPTION:
XS GIS Cut Line= 3
      2061274.98     13910224.97        2061075.       13909925.
      2060925.04     13909775.04
#Sta/Elev= 30
  4644.3 1378.11  4672.8  1376.3  4687.8  1371.2  4706.8 1368.05  4738.9 1360.13
  4766.6 1356.32    4781 1354.57  4838.1 1351.53  4853.1 1348.94  4874.1 1346.48
  4919.2 1345.36  4925.2 1343.03  4940.2 1342.57  4946.2 1340.44  4961.3 1339.63
  4975.5 1339.81    5017 1339.14  5017.2 1338.64  5020.7 1338.64    5021 1339.14
  5033.1 1340.12  5061.4 1346.02  5075.5 1348.28  5110.9 1352.41  5126.3 1355.79
  5132.1 1357.02  5146.2 1361.58  5174.5 1372.71  5188.7 1375.61  5216.9 1378.38
#Mann= 7 ,-1 , 0
  4644.3     .07       0  4706.8    .035       0  4766.6     .07       0
  4975.5    .035       0    5017    .035       0    5021    .035       0
  5126.3     .07       0
Bank Sta=5017,5021
XS Rating Curve= 0 ,0
Exp/Cntr=0.3,0.1

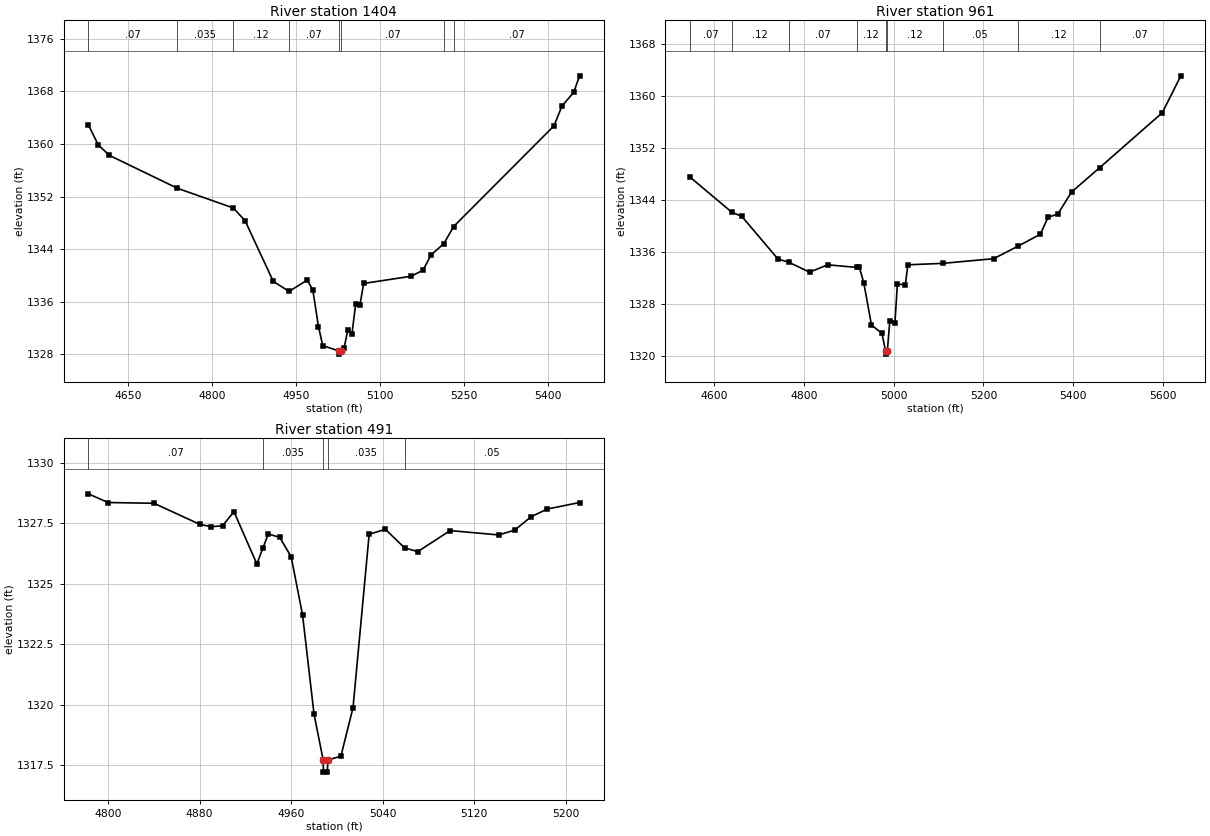
Type RM Length L Ch R = 1 ,1404    ,443,443,443
BEGIN DESCRIPTION:
Stream0011_DS 3.0
END DESCRIPTION:
XS GIS Cut Line= 3
      2061531.56     13910142.29        2061475.       13909725.
      2061136.64     13909419.17
#Sta/Elev= 30
  4579.3 1362.94  4596.8  1359.9  4616.9 1358.28  4738.5 1353.27  4838.2 1350.28
  4859.1 1348.36  4909.6 1339.11  4937.8 1337.59  4970.1 1339.31  4980.2 1337.81
  4990.3 1332.24  4997.9 1329.34  5026.4 1328.55  5026.7 1328.05  5030.4 1328.55
  5035.9 1328.93  5042.6 1331.67  5050.1 1331.13  5056.8 1335.72  5064.3 1335.51
    5071  1338.8  5156.2  1339.9  5177.1 1340.83  5191.3 1343.13  5214.3 1344.87
  5231.7 1347.46    5411 1362.78  5425.2  1365.8  5446.2 1367.87  5456.5 1370.38
#Mann= 8 ,-1 , 0
  4579.3     .07       0  4738.5    .035       0  4838.2     .12       0
  4937.8     .07       0  5026.4     .05       0  5030.4     .07       0
  5214.3     .12       0  5231.7     .07       0
Bank Sta=5026.4,5030.4
XS Rating Curve= 0 ,0
Exp/Cntr=0.3,0.1

Type RM Length L Ch R = 1 ,961     ,470,470,470
BEGIN DESCRIPTION:
Stream0011_DS 2.0
END DESCRIPTION:
XS GIS Cut Line= 3
      2061771.15      13909970.4        2061825.       13909525.
      2061234.65     13909262.07
#Sta/Elev= 30
  4545.2 1347.51  4639.2 1342.06  4661.4 1341.43    4742 1334.87  4765.9 1334.38
  4812.5 1332.85  4852.8 1333.98  4917.7 1333.58  4923.3 1333.63  4933.4 1331.18
  4950.4 1324.71  4973.7 1323.45  4981.8 1320.74    4982 1320.24  4985.8 1320.74
  4991.3 1325.36  5002.7 1325.04  5008.2 1331.03    5026 1330.89  5031.4 1333.98
  5108.8  1334.2  5222.8 1334.92    5276 1336.81  5326.7 1338.67  5344.1 1341.29
    5366  1341.8  5396.4 1345.17  5458.8  1348.9  5598.7 1357.37  5640.1 1363.05
#Mann= 9 ,-1 , 0
  4545.2     .07       0  4639.2     .12       0  4765.9     .07       0
  4917.7     .12       0  4981.8     .05       0  4985.8     .12       0
  5108.8     .05       0    5276     .12       0  5458.8     .07       0
Bank Sta=4981.8,4985.8
XS Rating Curve= 0 ,0
Exp/Cntr=0.3,0.1

Type RM Length L Ch R = 1 ,491     ,0,0,0
BEGIN DESCRIPTION:
Stream0011_DS 1.0
END DESCRIPTION:
XS GIS Cut Line= 3
      2062224.27     13909642.25        2062225.       13909425.
      2062074.99     13909274.99
#Sta/Elev= 30
  4782.8 1328.72  4800.1 1328.36  4840.1 1328.33  4880.1 1327.46  4890.1 1327.36
  4900.1  1327.4  4910.1 1327.98  4930.1 1325.82  4935.6  1326.5  4940.1 1327.06
  4950.1 1326.92  4960.1 1326.12  4970.1  1323.7  4980.1 1319.61  4988.1 1317.71
  4988.3 1317.21  4991.8 1317.21  4992.1 1317.71  5003.6 1317.87  5014.2 1319.88
  5028.3 1327.05  5042.5 1327.25  5059.4 1326.48  5070.8 1326.33  5099.1  1327.2
  5141.5 1327.02  5155.6 1327.22  5169.8 1327.77  5183.9 1328.09  5212.2 1328.36
#Mann= 5 ,-1 , 0
  4782.8     .07       0  4935.6    .035       0  4988.1    .035       0
  4992.1    .035       0  5059.4     .05       0
Bank Sta=4988.1,4992.1
XS Rating Curve= 0 ,0
Exp/Cntr=0.3,0.1

Chan Stop Cuts=-1
Use User Specified Reach Order=0
Composite Channel Slope=5