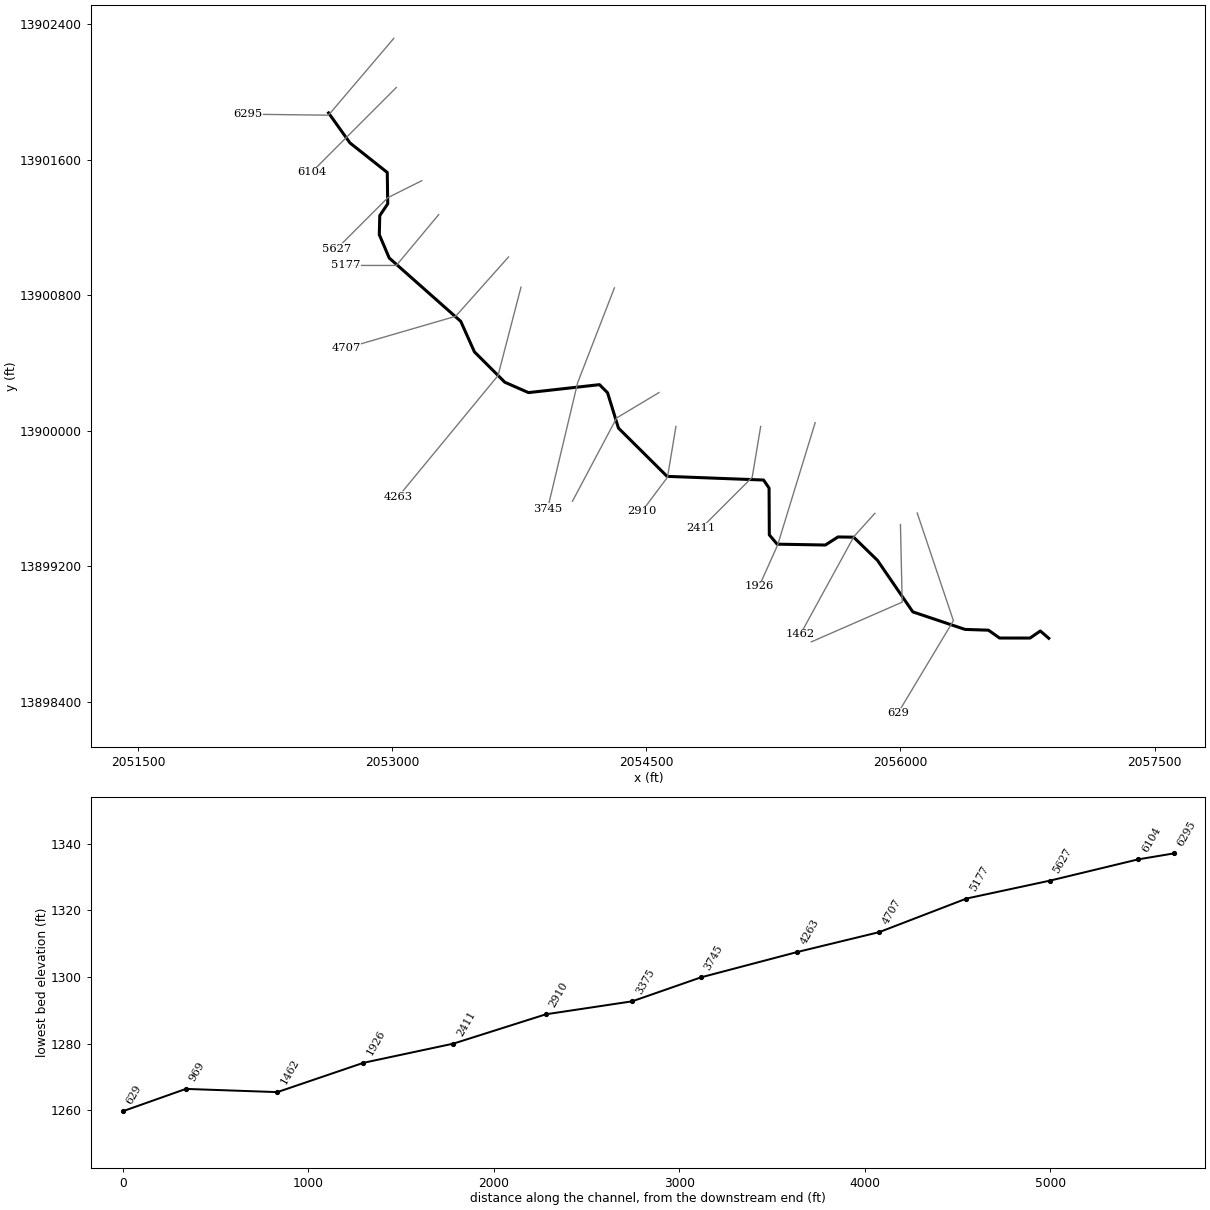
--- Stream0012_DS.prj (project) ---

Proj Title=Stream0012_DS Base Level Engineering
Current Plan=p01
Default Exp/Contr=0.3,0.1
English Units
Geom File=g01
Flow File=f01
Plan File=p01
BEGIN DESCRIPTION:
Stream0012_DS
END DESCRIPTION:

--- Stream0012_DS.p01 (plan) ---

Plan Title=Multiple Run
Short Identifier=Multiple
Geom File=g01
Flow File=f01
Subcritical Flow
K Sum by GR= 0
Std Step Tol= 0.01
Critical Tol= 0.01
Num of Std Step Trials= 20
Max Error Tol= 0.3
Flow Tol Ratio= 0.001
Split Flow NTrial= 30
Split Flow Tol= 0.02
Split Flow Ratio= 0.02
Log Output Level= 0
Friction Slope Method= 1
Unsteady Friction Slope Method= 2
Unsteady Bridges Friction Slope Method= 1
Parabolic Critical Depth
Global Vel Dist=  1 , 1 , 1
Global Log Level= 0
CheckData=True
Encroach Param= -1, 0, 0, 0
BEGIN DESCRIPTION:
Multiple Run
END DESCRIPTION:

--- Stream0012_DS.f01 (steady flow) ---

Flow Title=Multiple
Number of Profiles=7
Profile Names=10-year,25-year,50-year,1pct_min,100-year,1pct_plu,500-year
River Rch & RM= Stream0012_DS,Reach-1,6295
     525     846    1136     742    1480    2954    2480
River Rch & RM= Stream0012_DS,Reach-1,6104
     937    1563    2148    1432    2857    5700    4994
Boundary for River Rch & Prof#=Stream0012_DS,Reach-1,1
Up Type=0
Dn Type=3
Dn Slope=0.005
Boundary for River Rch & Prof#=Stream0012_DS,Reach-1,2
Up Type=0
Dn Type=3
Dn Slope=0.005
Boundary for River Rch & Prof#=Stream0012_DS,Reach-1,3
Up Type=0
Dn Type=3
Dn Slope=0.005
Boundary for River Rch & Prof#=Stream0012_DS,Reach-1,4
Up Type=0
Dn Type=3
Dn Slope=0.005
Boundary for River Rch & Prof#=Stream0012_DS,Reach-1,5
Up Type=0
Dn Type=3
Dn Slope=0.005
Boundary for River Rch & Prof#=Stream0012_DS,Reach-1,6
Up Type=0
Dn Type=3
Dn Slope=0.005
Boundary for River Rch & Prof#=Stream0012_DS,Reach-1,7
Up Type=0
Dn Type=3
Dn Slope=0.005

--- Stream0012_DS.g01 (geometry) ---

Geom Title=Existing Conditions

River Reach=Stream0012_DS,Reach-1
Reach XY= 30
      2052625.00     13901875.00      2052751.30     13901698.18
      2052971.55     13901523.75      2052974.32     13901338.92
      2052927.25     13901269.06      2052924.57     13901156.67
      2052983.13     13901018.93      2053405.22     13900645.09
      2053485.76     13900465.32      2053665.32     13900285.76
      2053804.85     13900224.64      2054223.77     13900271.57
      2054271.49     13900223.75      2054335.76     13900015.32
      2054622.55     13899730.46      2055192.23     13899708.76
      2055224.53     13899661.29      2055225.98     13899385.26
      2055272.26     13899330.34      2055556.73     13899325.21
      2055630.98     13899372.84      2055723.50     13899371.54
      2055864.22     13899234.68      2056072.69     13898930.82
      2056380.94     13898827.27      2056519.06     13898822.73
      2056584.66     13898776.38      2056764.58     13898776.31
      2056825.14     13898818.09      2056875.00     13898775.00

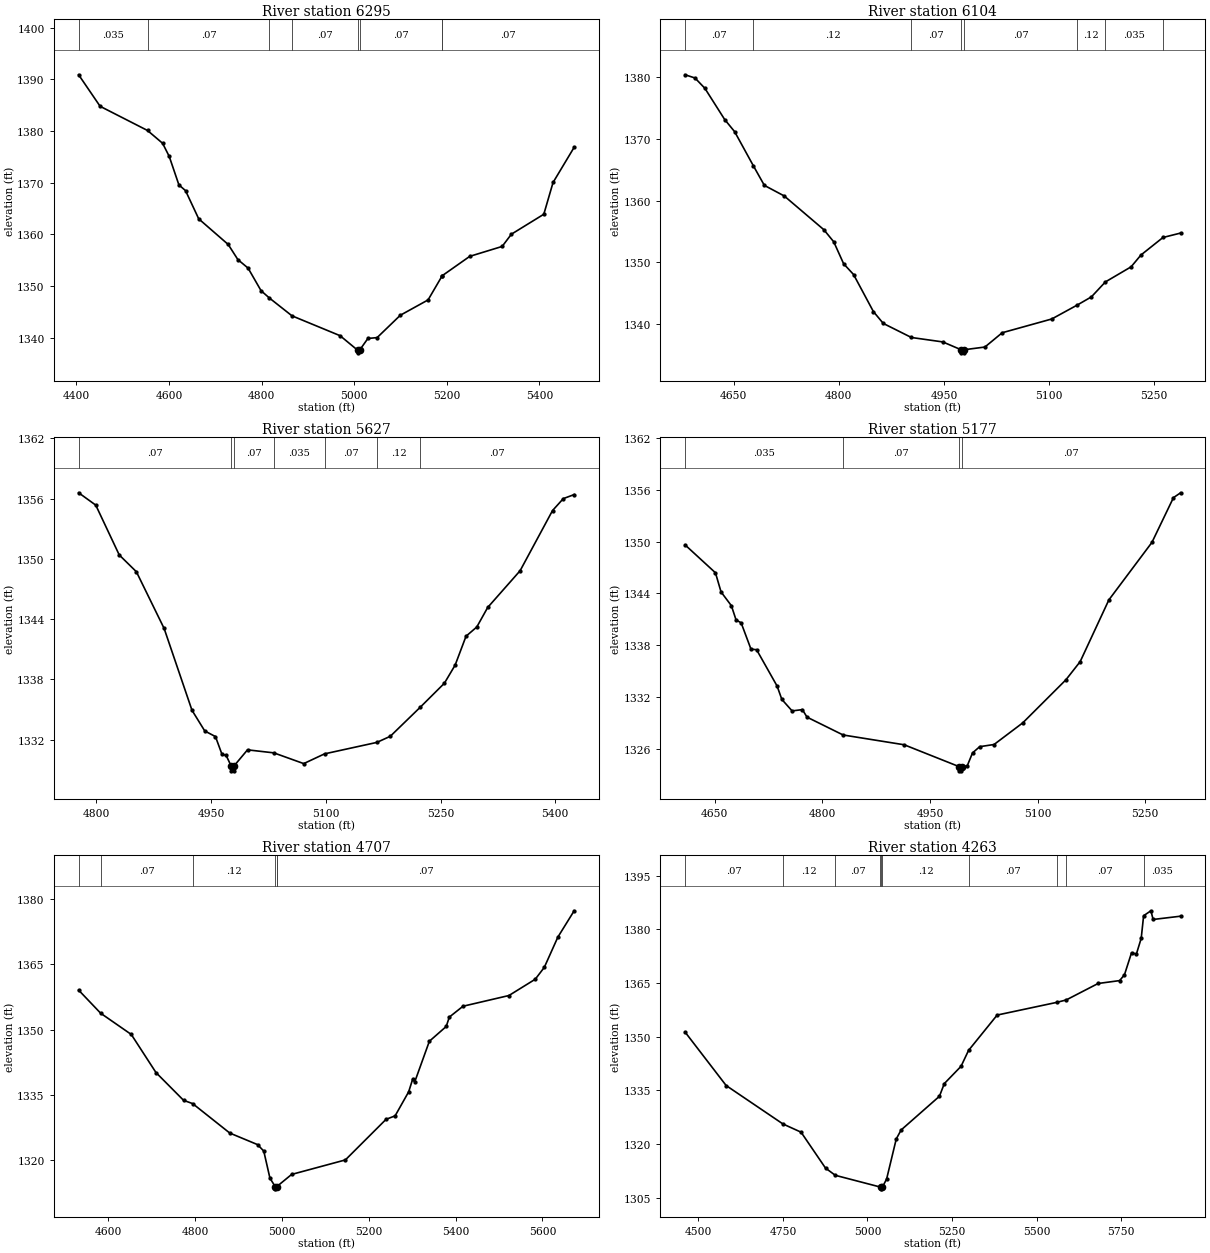
Type RM Length L Ch R = 1,6295,191,191,191
BEGIN DESCRIPTION:
Stream0012_DS 14.0
END DESCRIPTION:
XS GIS Cut Line= 3
      2053010.16     13902315.16      2052624.45     13901861.72
      2052149.39     13901867.43
#Sta/Elev= 30
  4404.7 1390.88  4451.1 1384.78  4553.5 1380.10  4586.1 1377.62  4600.4 1375.08
  4621.3 1369.57  4635.6 1368.46  4664.1 1363.00  4727.8 1358.04  4748.7 1355.11
  4770.7 1353.47  4798.8 1349.09  4816.9 1347.67  4865.6 1344.23  4969.4 1340.39
  5007.5 1337.57  5007.7 1337.07  5011.5 1337.57  5029.5 1339.85  5049.5 1340.02
  5099.5 1344.34  5159.5 1347.31  5190.0 1351.98  5190.3 1352.01  5249.5 1355.74
  5319.5 1357.66  5339.5 1360.03  5409.5 1363.89  5429.5 1370.04  5475.1 1376.85
#Mann=8,-1,0
  4404.7   0.035       0  4553.5    0.07       0  4816.9    0.12       0
  4865.6    0.07       0  5007.5    0.05       0  5011.5    0.07       0
  5190.0   0.035       0  5190.3    0.07       0
Bank Sta=5007.5,5011.5
Exp/Cntr=0.3,0.1

Type RM Length L Ch R = 1,6104,477,477,477
BEGIN DESCRIPTION:
Stream0012_DS 13.0
END DESCRIPTION:
XS GIS Cut Line= 3
      2053024.97     13902024.97      2052725.00     13901725.00
      2052524.98     13901524.98
#Sta/Elev= 30
  4580.6 1380.40  4594.7 1379.88  4608.8 1378.21  4637.1 1373.14  4651.3 1371.17
  4678.2 1365.60  4693.7 1362.46  4722.0 1360.75  4778.6 1355.27  4792.7 1353.31
  4806.8 1349.75  4821.0 1348.00  4849.3 1341.99  4863.4 1340.07  4903.5 1337.79
  4948.3 1337.07  4974.5 1335.80  4974.8 1335.30  4978.3 1335.30  4978.5 1335.80
  5008.4 1336.24  5033.1 1338.56  5103.8 1340.79  5140.3 1343.06  5160.4 1344.38
  5180.3 1346.80  5217.0 1349.25  5231.1 1351.17  5262.5 1354.01  5287.7 1354.73
#Mann=8,-1,0
  4580.6    0.07       0  4678.2    0.12       0  4903.5    0.07       0
  4974.5    0.05       0  4978.5    0.07       0  5140.3    0.12       0
  5180.3   0.035       0  5262.5    0.12       0
Bank Sta=4974.5,4978.5
Exp/Cntr=0.3,0.1

Type RM Length L Ch R = 1,5627,450,450,450
BEGIN DESCRIPTION:
Stream0012_DS 12.0
END DESCRIPTION:
XS GIS Cut Line= 3
      2053175.02     13901475.01      2052975.00     13901375.00
      2052674.99     13901074.99
#Sta/Elev= 30
  4776.8 1356.58  4799.2 1355.35  4829.9 1350.39  4852.3 1348.72  4888.6 1343.07
  4925.0 1334.93  4941.7 1332.87  4955.7 1332.31  4964.1 1330.57  4969.7 1330.43
  4976.1 1329.40  4976.3 1328.90  4979.8 1328.90  4980.1 1329.40  4997.6 1330.99
  5032.0 1330.69  5071.1 1329.62  5098.3 1330.59  5166.7 1331.73  5184.3 1332.34
  5223.7 1335.25  5255.0 1337.62  5269.1 1339.43  5283.3 1342.30  5297.4 1343.22
  5311.6 1345.16  5354.0 1348.82  5396.4 1354.81  5410.5 1356.00  5424.7 1356.40
#Mann=7,-1,0
  4776.8    0.07       0  4976.1    0.05       0  4980.1    0.07       0
  5032.0   0.035       0  5098.3    0.07       0  5166.7    0.12       0
  5223.7    0.07       0
Bank Sta=4976.1,4980.1
Exp/Cntr=0.3,0.1

Type RM Length L Ch R = 1,5177,470,470,470
BEGIN DESCRIPTION:
Stream0012_DS 11.0
END DESCRIPTION:
XS GIS Cut Line= 3
      2053275.02     13901275.02      2053025.00     13900975.00
      2052725.04     13900975.00
#Sta/Elev= 30
  4608.8 1349.61  4651.1 1346.39  4658.9 1344.18  4673.3 1342.59  4679.8 1340.95
  4686.9 1340.61  4700.6 1337.57  4708.4 1337.51  4737.0 1333.31  4743.6 1331.77
  4757.9 1330.44  4772.2 1330.59  4778.7 1329.72  4829.0 1327.66  4914.1 1326.53
  4990.2 1324.02  4990.4 1323.52  4993.9 1323.52  4994.2 1324.02  5001.8 1324.07
  5009.3 1325.59  5019.3 1326.31  5039.3 1326.56  5079.3 1329.06  5139.3 1334.02
  5159.3 1336.13  5199.3 1343.26  5259.3 1349.90  5289.3 1355.07  5299.3 1355.63
#Mann=4,-1,0
  4608.8   0.035       0  4829.0    0.07       0  4990.2    0.05       0
  4994.2    0.07       0
Bank Sta=4990.2,4994.2
Exp/Cntr=0.3,0.1

Type RM Length L Ch R = 1,4707,444,444,444
BEGIN DESCRIPTION:
Stream0012_DS 10.0
END DESCRIPTION:
XS GIS Cut Line= 3
      2053686.88     13901024.90      2053375.00     13900675.00
      2052728.89     13900487.08
#Sta/Elev= 30
  4531.5 1359.08  4582.3 1353.77  4652.8 1348.90  4709.7 1340.15  4773.2 1333.78
  4794.2 1333.02  4879.7 1326.26  4943.8 1323.60  4958.0 1322.12  4972.2 1315.91
  4984.4 1313.95  4984.7 1313.45  4988.4 1313.95  4988.8 1314.03  5022.2 1316.76
  5146.0 1320.09  5239.7 1329.41  5260.6 1330.21  5291.8 1335.73  5300.8 1338.56
  5306.0 1338.06  5339.5 1347.34  5378.3 1350.73  5385.5 1352.89  5417.0 1355.38
  5522.8 1357.84  5583.4 1361.58  5604.2 1364.29  5635.5 1371.25  5673.1 1377.30
#Mann=6,-1,0
  4531.5    0.12       0  4582.3    0.07       0  4794.2    0.12       0
  4984.4    0.05       0  4988.4    0.12       0  4988.8    0.07       0
Bank Sta=4984.4,4988.4
Exp/Cntr=0.3,0.1

Type RM Length L Ch R = 1,4263,518,518,518
BEGIN DESCRIPTION:
Stream0012_DS 9.0
END DESCRIPTION:
XS GIS Cut Line= 3
      2053760.68     13900846.94      2053625.00     13900325.00
      2053035.89     13899610.03
#Sta/Elev= 30
  4460.5 1351.25  4581.9 1336.32  4749.9 1325.58  4803.5 1323.28  4875.8 1313.25
  4904.8 1311.23  5036.3 1307.99  5040.1 1307.95  5040.4 1307.45  5044.1 1307.95
  5056.5 1310.17  5085.1 1321.40  5099.5 1323.90  5212.8 1333.32  5227.2 1336.86
  5276.7 1341.69  5298.9 1346.13  5383.5 1356.01  5559.5 1359.55  5587.7 1360.23
  5682.0 1364.83  5745.8 1365.64  5760.1 1367.28  5781.0 1373.43  5795.3 1373.06
  5809.6 1377.46  5816.7 1383.77  5838.3 1385.15  5844.8 1382.72  5926.2 1383.64
#Mann=10,-1,0
  4460.5    0.07       0  4749.9    0.12       0  4904.8    0.07       0
  5036.3    0.12       0  5040.1    0.05       0  5044.1    0.12       0
  5298.9    0.07       0  5559.5   0.035       0  5587.7    0.07       0
  5816.7   0.035       0
Bank Sta=5040.1,5044.1
Exp/Cntr=0.3,0.1

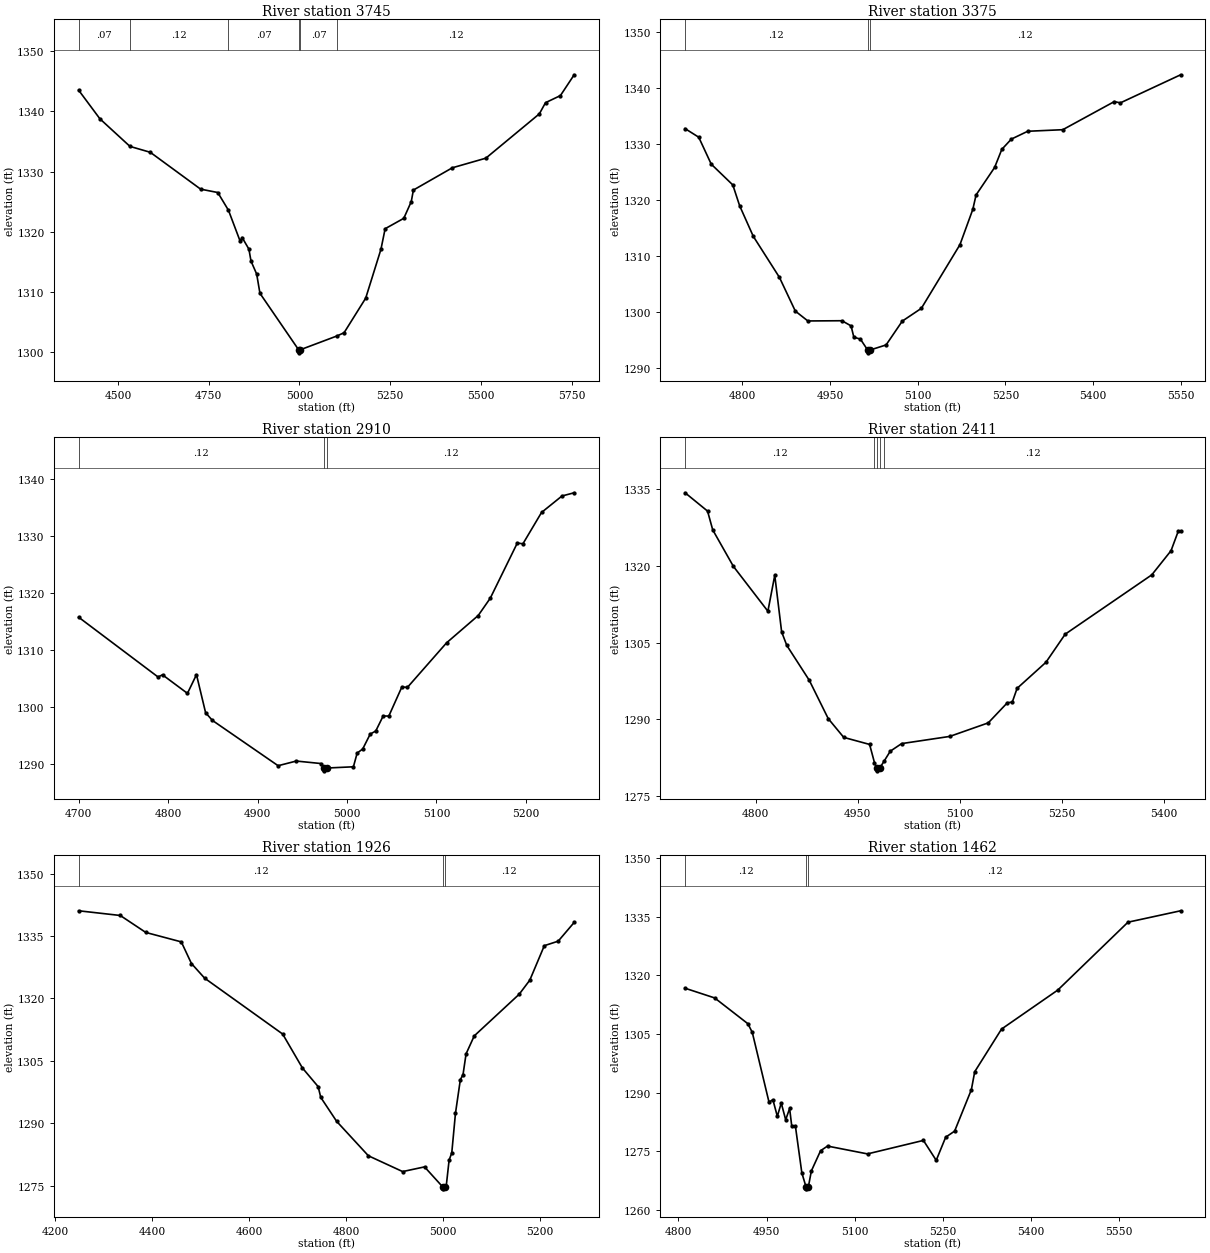
Type RM Length L Ch R = 1,3745,370,370,370
BEGIN DESCRIPTION:
Stream0012_DS 8.0
END DESCRIPTION:
XS GIS Cut Line= 3
      2054311.92     13900842.66      2054094.90     13900282.74
      2053917.40     13899538.12
#Sta/Elev= 30
  4391.3 1343.54  4449.9 1338.78  4532.8 1334.19  4588.8 1333.21  4727.6 1327.08
  4774.9 1326.52  4804.4 1323.56  4836.6 1318.41  4842.0 1319.04  4860.7 1317.10
  4866.5 1315.11  4882.1 1312.96  4891.1 1309.76  4997.8 1300.36  4998.0 1299.86
  5001.8 1300.36  5104.0 1302.68  5123.1 1303.21  5182.6 1308.95  5224.7 1317.09
  5236.2 1320.50  5287.6 1322.23  5308.2 1325.00  5314.1 1326.93  5421.3 1330.63
  5513.8 1332.23  5661.3 1339.60  5678.3 1341.46  5719.4 1342.64  5757.3 1346.10
#Mann=6,-1,0
  4391.3    0.07       0  4532.8    0.12       0  4804.4    0.07       0
  4997.8    0.05       0  5001.8    0.07       0  5104.0    0.12       0
Bank Sta=4997.8,5001.8
Exp/Cntr=0.3,0.1

Type RM Length L Ch R = 1,3375,465,465,465
BEGIN DESCRIPTION:
Stream0012_DS 7.0
END DESCRIPTION:
XS GIS Cut Line= 3
      2054575.01     13900225.01      2054325.00     13900075.00
      2054064.52     13899583.97
#Sta/Elev= 30
  4702.2 1332.69  4725.5 1331.16  4746.9 1326.35  4783.8 1322.64  4795.5 1318.92
  4818.8 1313.47  4863.5 1306.15  4890.7 1300.13  4912.1 1298.37  4970.4 1298.41
  4986.0 1297.49  4990.8 1295.46  5001.9 1295.14  5014.4 1293.18  5014.6 1292.68
  5018.4 1293.18  5045.9 1294.09  5073.6 1298.34  5106.2 1300.62  5172.2 1311.98
  5194.2 1318.28  5199.8 1320.86  5231.5 1325.76  5243.8 1328.99  5260.1 1330.82
  5288.1 1332.22  5348.1 1332.50  5436.1 1337.51  5446.6 1337.29  5549.6 1342.30
#Mann=3,-1,0
  4702.2    0.12       0  5014.4    0.05       0  5018.4    0.12       0
Bank Sta=5014.4,5018.4
Exp/Cntr=0.3,0.1

Type RM Length L Ch R = 1,2910,499,499,499
BEGIN DESCRIPTION:
Stream0012_DS 6.0
END DESCRIPTION:
XS GIS Cut Line= 3
      2054675.01     13900025.05      2054625.00     13899725.00
      2054474.99     13899524.99
#Sta/Elev= 30
  4699.8 1315.78  4788.6 1305.28  4793.6 1305.66  4821.5 1302.40  4831.6 1305.69
  4841.8 1299.00  4849.4 1297.65  4922.9 1289.69  4943.2 1290.51  4971.0 1290.07
  4974.1 1289.29  4974.4 1288.79  4978.1 1289.29  5007.1 1289.50  5011.3 1291.91
  5017.5 1292.63  5025.9 1295.25  5032.1 1295.79  5040.4 1298.43  5046.7 1298.41
  5061.3 1303.53  5067.5 1303.45  5111.3 1311.28  5146.7 1316.08  5160.2 1319.13
  5190.4 1328.81  5196.7 1328.68  5217.5 1334.18  5240.4 1337.08  5254.0 1337.64
#Mann=3,-1,0
  4699.8    0.12       0  4974.1    0.05       0  4978.1    0.12       0
Bank Sta=4974.1,4978.1
Exp/Cntr=0.3,0.1

Type RM Length L Ch R = 1,2411,485,485,485
BEGIN DESCRIPTION:
Stream0012_DS 5.0
END DESCRIPTION:
XS GIS Cut Line= 3
      2055175.00     13900025.01      2055125.00     13899725.00
      2054825.01     13899425.01
#Sta/Elev= 30
  4696.3 1334.19  4729.3 1330.62  4736.9 1326.96  4767.3 1319.84  4818.0 1311.10
  4828.1 1318.10  4838.2 1307.07  4845.8 1304.43  4878.8 1297.64  4906.7 1290.16
  4929.5 1286.50  4967.5 1285.13  4974.7 1281.56  4978.2 1280.48  4978.4 1279.98
  4982.2 1280.48  4989.1 1281.93  4997.9 1283.81  5014.6 1285.29  5085.3 1286.69
  5141.9 1289.33  5170.1 1293.27  5177.2 1293.37  5184.3 1296.06  5226.7 1301.14
  5255.0 1306.62  5382.3 1318.19  5410.6 1322.90  5421.2 1326.70  5424.7 1326.70
#Mann=5,-1,0
  4696.3    0.12       0  4974.7    0.07       0  4978.2    0.05       0
  4982.2    0.07       0  4989.1    0.12       0
Bank Sta=4978.2,4982.2
Exp/Cntr=0.3,0.1

Type RM Length L Ch R = 1,1926,464,464,464
BEGIN DESCRIPTION:
Stream0012_DS 4.0
END DESCRIPTION:
XS GIS Cut Line= 3
      2055496.60     13900047.55      2055275.00     13899325.00
      2055165.87     13899081.39
#Sta/Elev= 30
  4247.9 1341.08  4333.8 1339.95  4386.5 1335.87  4459.8 1333.60  4480.7 1328.40
  4508.0 1324.87  4669.0 1311.44  4709.7 1303.29  4742.2 1298.80  4747.6 1296.21
  4780.4 1290.45  4845.9 1282.17  4916.6 1278.37  4961.8 1279.50  4999.0 1274.72
  4999.3 1274.22  5003.0 1274.72  5006.4 1274.72  5012.5 1281.13  5018.0 1282.87
  5025.6 1292.37  5035.7 1300.48  5041.2 1301.67  5047.5 1306.68  5064.4 1311.00
  5157.1 1321.01  5179.0 1324.39  5209.0 1332.69  5237.6 1333.77  5270.6 1338.28
#Mann=3,-1,0
  4247.9    0.12       0  4999.0    0.05       0  5003.0    0.12       0
Bank Sta=4999,5003
Exp/Cntr=0.3,0.1

Type RM Length L Ch R = 1,1462,493,493,493
BEGIN DESCRIPTION:
Stream0012_DS 3.0
END DESCRIPTION:
XS GIS Cut Line= 3
      2055848.79     13899512.32      2055725.00     13899375.00
      2055409.07     13898797.68
#Sta/Elev= 30
  4811.3 1316.71  4861.6 1314.23  4918.1 1307.64  4925.6 1305.42  4954.0 1287.62
  4960.7 1288.19  4968.2 1283.96  4974.9 1287.36  4982.4 1283.08  4989.1 1285.97
  4992.8 1281.40  4999.0 1281.40  5009.9 1269.51  5017.0 1265.93  5017.2 1265.43
  5021.0 1265.93  5026.1 1270.01  5041.8 1275.18  5053.6 1276.36  5121.6 1274.36
  5216.7 1277.81  5238.5 1272.72  5254.6 1278.63  5269.8 1280.18  5298.3 1290.78
  5304.0 1295.37  5349.6 1306.27  5445.3 1316.24  5564.7 1333.59  5654.3 1336.51
#Mann=3,-1,0
  4811.3    0.12       0  5017.0    0.05       0  5021.0    0.12       0
Bank Sta=5017,5021
Exp/Cntr=0.3,0.1

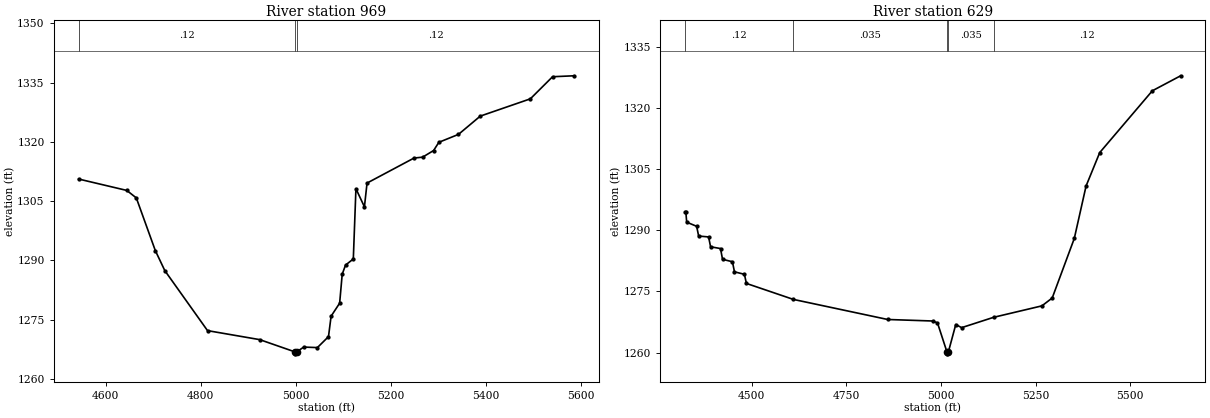
Type RM Length L Ch R = 1,969,340,340,340
BEGIN DESCRIPTION:
Stream0012_DS 2.0
END DESCRIPTION:
XS GIS Cut Line= 3
      2055999.71     13899446.42      2056010.13     13898988.13
      2055473.71     13898753.77
#Sta/Elev= 30
  4542.7 1310.59  4644.1 1307.71  4664.2 1305.82  4704.2 1292.51  4724.2 1287.44
  4814.2 1272.26  4924.2 1269.98  4998.2 1266.89  4998.4 1266.39  5002.2 1266.89
  5016.8 1268.10  5045.6 1267.97  5069.0 1270.74  5074.5 1275.91  5092.5 1279.20
  5097.9 1286.53  5104.9 1288.83  5121.3 1290.38  5126.8 1308.15  5144.7 1303.56
  5150.2 1309.57  5249.2 1315.90  5267.2 1316.12  5290.4 1317.80  5301.5 1319.88
  5342.8 1321.88  5388.7 1326.50  5494.2 1330.87  5541.0 1336.46  5586.5 1336.70
#Mann=3,-1,0
  4542.7    0.12       0  4998.2    0.05       0  5002.2    0.12       0
Bank Sta=4998.2,5002.2
Exp/Cntr=0.3,0.1

Type RM Length L Ch R = 1,629,0,0,0
BEGIN DESCRIPTION:
Stream0012_DS 1.0
END DESCRIPTION:
XS GIS Cut Line= 3
      2056098.69     13899514.12      2056312.21     13898878.75
      2055984.06     13898331.83
#Sta/Elev= 30
  4324.7 1294.41  4326.7 1294.41  4328.9 1291.97  4355.2 1290.95  4360.5 1288.56
  4386.7 1288.35  4392.0 1285.93  4418.2 1285.50  4423.5 1282.86  4449.7 1282.26
  4455.0 1279.79  4481.3 1279.19  4486.5 1276.95  4610.6 1273.03  4859.5 1268.11
  4977.8 1267.74  4990.9 1267.29  5015.8 1260.19  5016.0 1259.69  5019.8 1260.19
  5039.2 1266.88  5054.7 1266.11  5139.0 1268.64  5266.6 1271.45  5293.8 1273.38
  5352.1 1287.98  5383.2 1300.84  5419.2 1309.02  5558.1 1324.17  5632.8 1327.85
#Mann=5,-1,0
  4324.7    0.12       0  4610.6   0.035       0  5015.8   0.035       0
  5019.8   0.035       0  5139.0    0.12       0
Bank Sta=5015.8,5019.8
Exp/Cntr=0.3,0.1

Chan Stop Cuts=-1