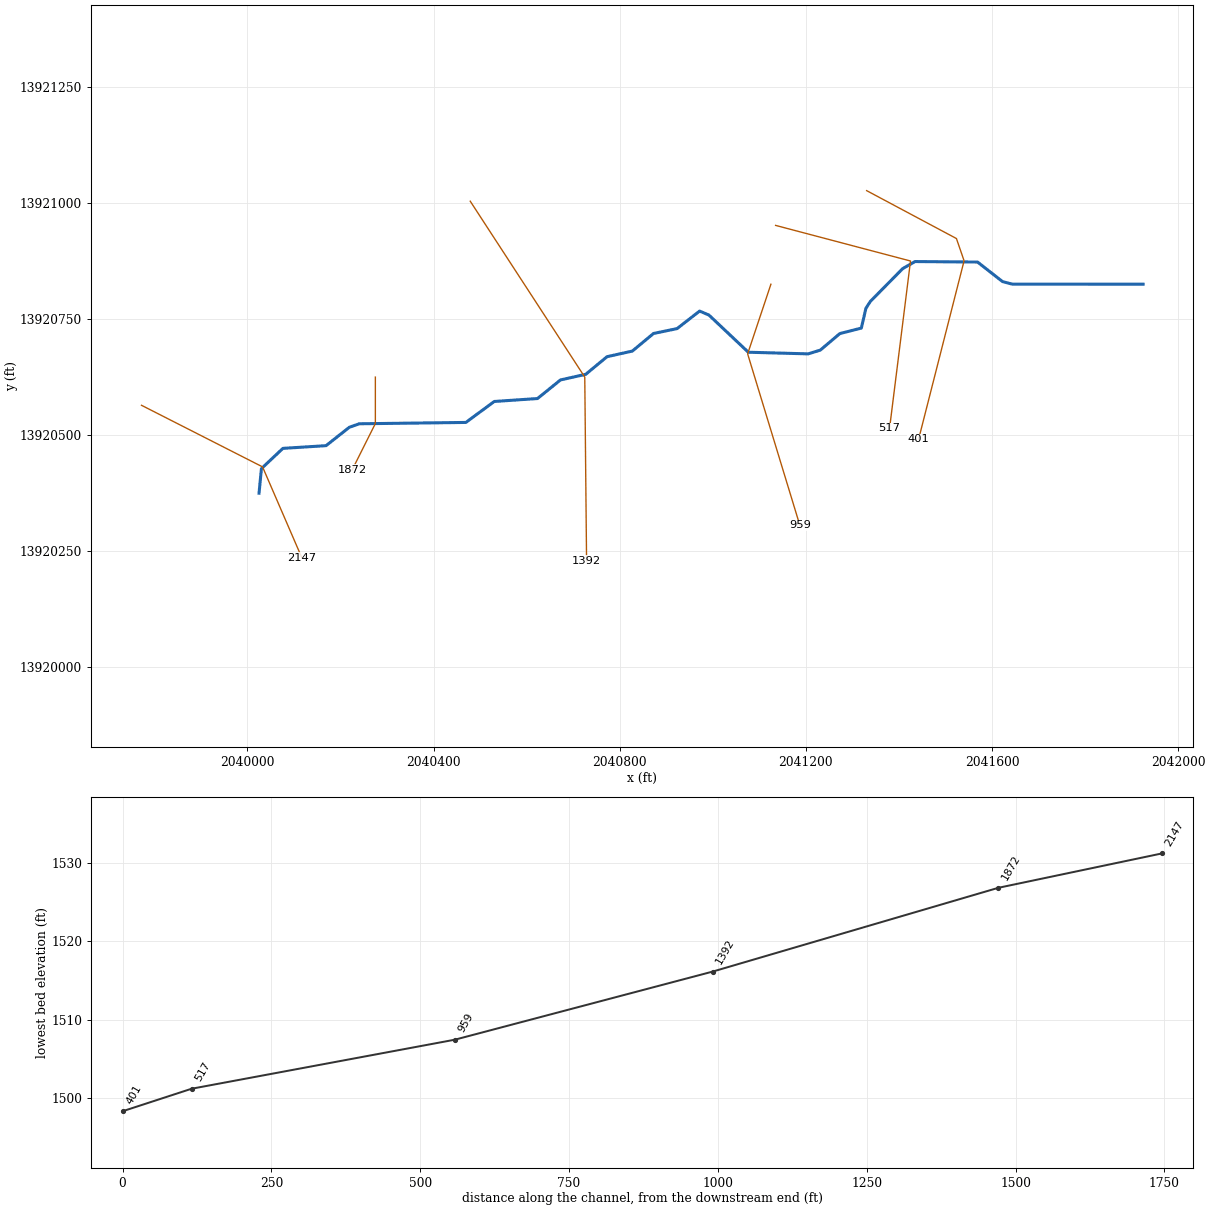
--- Stream0013_DS.prj (project) ---

Proj Title=Stream0013_DS Base Level Engineering
Current Plan=p01
Default Exp/Contr=0.3,0.1
English Units
Geom File=g01
Flow File=f01
Plan File=p01
BEGIN DESCRIPTION:
Stream0013_DS
END DESCRIPTION:

--- Stream0013_DS.p01 (plan) ---

Plan Title=Multiple Run
Short Identifier=Multiple
Geom File=g01
Flow File=f01
Subcritical Flow
K Sum by GR= 0
Std Step Tol= 0.01
Critical Tol= 0.01
Num of Std Step Trials= 20
Max Error Tol= 0.3
Flow Tol Ratio= 0.001
Split Flow NTrial= 30
Split Flow Tol= 0.02
Split Flow Ratio= 0.02
Log Output Level= 0
Friction Slope Method= 1
Unsteady Friction Slope Method= 2
Unsteady Bridges Friction Slope Method= 1
Parabolic Critical Depth
Global Vel Dist=  1 , 1 , 1
Global Log Level= 0
CheckData=True
Encroach Param= -1, 0, 0, 0
BEGIN DESCRIPTION:
Multiple Run
END DESCRIPTION:

--- Stream0013_DS.f01 (steady flow) ---

Flow Title=Multiple
Number of Profiles=7
Profile Names=10-year,25-year,50-year,1pct_min,100-year,1pct_plu,500-year
River Rch & RM= Stream0013_DS,Reach-1,2147
     622    1040    1437     967    1929    3850    3440
River Rch & RM= Stream0013_DS,Reach-1,1872
     719    1212    1681    1135    2266    4520    4070
Boundary for River Rch & Prof#=Stream0013_DS,Reach-1,1
Up Type=0
Dn Type=3
Dn Slope=0.005
Boundary for River Rch & Prof#=Stream0013_DS,Reach-1,2
Up Type=0
Dn Type=3
Dn Slope=0.005
Boundary for River Rch & Prof#=Stream0013_DS,Reach-1,3
Up Type=0
Dn Type=3
Dn Slope=0.005
Boundary for River Rch & Prof#=Stream0013_DS,Reach-1,4
Up Type=0
Dn Type=3
Dn Slope=0.005
Boundary for River Rch & Prof#=Stream0013_DS,Reach-1,5
Up Type=0
Dn Type=3
Dn Slope=0.005
Boundary for River Rch & Prof#=Stream0013_DS,Reach-1,6
Up Type=0
Dn Type=3
Dn Slope=0.005
Boundary for River Rch & Prof#=Stream0013_DS,Reach-1,7
Up Type=0
Dn Type=3
Dn Slope=0.005

--- Stream0013_DS.g01 (geometry) ---

Geom Title=Existing Conditions

River Reach=Stream0013_DS,Reach-1
Reach XY= 30
      2040025.00     13920375.00      2040030.13     13920427.94
      2040076.30     13920471.54      2040169.02     13920477.36
      2040218.94     13920516.86      2040240.22     13920524.48
      2040469.47     13920527.38      2040530.57     13920572.53
      2040623.42     13920578.83      2040672.82     13920618.88
      2040727.20     13920631.08      2040772.80     13920668.92
      2040827.20     13920681.08      2040872.81     13920718.95
      2040923.37     13920729.44      2040971.77     13920767.16
      2040991.69     13920758.68      2041076.47     13920678.55
      2041204.98     13920675.04      2041231.12     13920683.07
      2041273.16     13920718.72      2041319.39     13920730.59
      2041329.12     13920773.00      2041338.71     13920788.01
      2041408.20     13920858.58      2041434.59     13920873.81
      2041569.06     13920872.75      2041622.67     13920830.75
      2041643.27     13920825.21      2041925.00     13920825.00

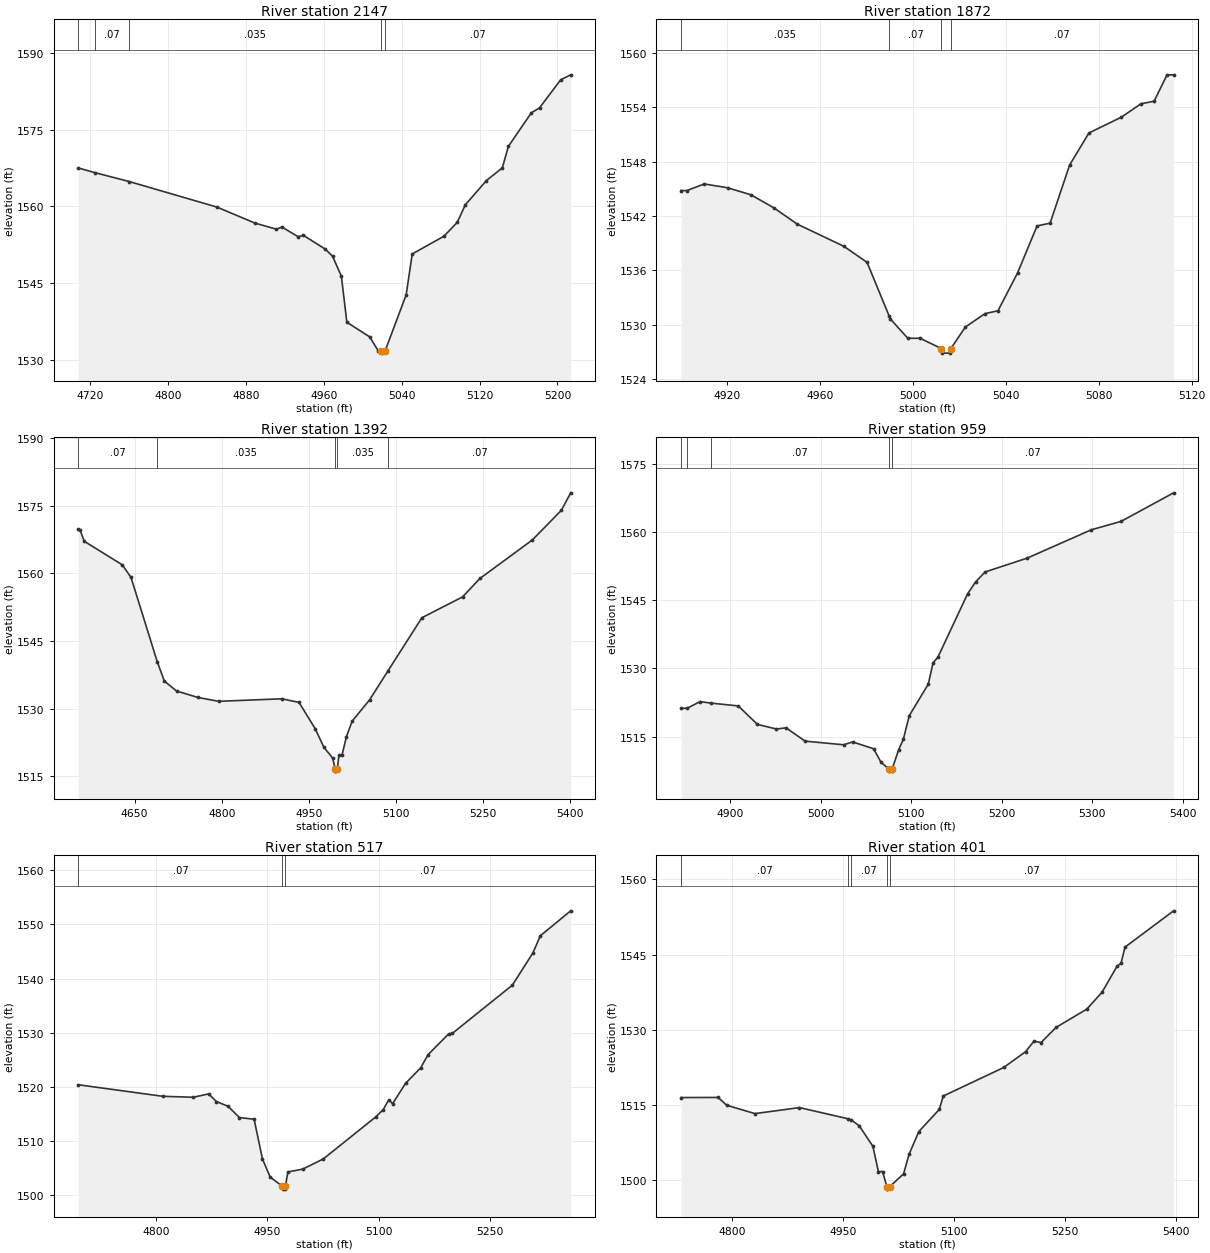
Type RM Length L Ch R = 1,2147,275,275,275
BEGIN DESCRIPTION:
Stream0013_DS 5.0
END DESCRIPTION:
XS GIS Cut Line= 3
      2039772.42     13920564.31      2040032.56     13920431.69
      2040117.19     13920235.57
#Sta/Elev= 30
  4708.0 1567.55  4724.9 1566.64  4760.6 1564.87  4850.4 1559.88  4889.3 1556.75
  4911.5 1555.54  4917.1 1555.97  4933.7 1554.08  4939.3 1554.33  4961.6 1551.64
  4969.1 1550.26  4978.2 1546.32  4983.8 1537.31  5007.3 1534.44  5015.8 1531.77
  5019.2 1531.76  5019.4 1531.26  5023.2 1531.76  5044.7 1542.68  5050.9 1550.69
  5083.5 1554.17  5097.2 1556.90  5105.3 1560.29  5127.1 1565.08  5143.4 1567.56
  5149.6 1571.77  5173.2 1578.35  5181.6 1579.32  5203.3 1584.82  5213.6 1585.79
#Mann=5,-1,0
  4708.0   0.035       0  4724.9    0.07       0  4760.6   0.035       0
  5019.2   0.035       0  5023.2    0.07       0
Bank Sta=5019.2,5023.2
Exp/Cntr=0.3,0.1

Type RM Length L Ch R = 1,1872,480,480,480
BEGIN DESCRIPTION:
Stream0013_DS 4.0
END DESCRIPTION:
XS GIS Cut Line= 3
      2040275.00     13920624.98      2040275.00     13920525.00
      2040224.99     13920424.99
#Sta/Elev= 30
  4900.4 1544.81  4902.9 1544.81  4910.4 1545.54  4920.4 1545.12  4930.4 1544.35
  4940.4 1542.89  4950.4 1541.10  4970.4 1538.66  4980.4 1536.88  4989.9 1530.95
  4990.4 1530.64  4997.9 1528.50  5003.2 1528.50  5012.4 1527.36  5012.6 1526.86
  5016.1 1526.86  5016.4 1527.36  5022.7 1529.75  5031.1 1531.22  5036.7 1531.54
  5045.1 1535.71  5053.5 1540.91  5059.1 1541.21  5067.5 1547.63  5075.8 1551.17
  5089.8 1552.92  5098.2 1554.40  5103.8 1554.67  5109.4 1557.59  5112.2 1557.59
#Mann=4,-1,0
  4900.4   0.035       0  4989.9    0.07       0  5012.4    0.05       0
  5016.4    0.07       0
Bank Sta=5012.4,5016.4
Exp/Cntr=0.3,0.1

Type RM Length L Ch R = 1,1392,433,433,433
BEGIN DESCRIPTION:
Stream0013_DS 3.0
END DESCRIPTION:
XS GIS Cut Line= 3
      2040478.86     13921003.79      2040725.00     13920625.00
      2040728.87     13920228.85
#Sta/Elev= 30
  4552.9 1569.76  4556.2 1569.55  4563.4 1567.07  4628.7 1561.87  4643.8 1559.08
  4689.0 1540.41  4701.2 1536.10  4722.3 1533.90  4758.5 1532.48  4794.8 1531.61
  4903.5 1532.17  4933.1 1531.37  4960.8 1525.56  4976.0 1521.41  4991.1 1519.02
  4995.1 1516.64  4995.3 1516.14  4999.1 1516.64  5001.7 1519.67  5007.1 1519.67
  5014.6 1523.75  5024.6 1527.22  5054.6 1531.94  5086.2 1538.35  5144.6 1550.13
  5214.6 1554.75  5244.6 1558.84  5334.7 1567.36  5384.7 1573.94  5400.8 1577.81
#Mann=5,-1,0
  4552.9    0.07       0  4689.0   0.035       0  4995.1   0.035       0
  4999.1   0.035       0  5086.2    0.07       0
Bank Sta=4995.1,4999.1
Exp/Cntr=0.3,0.1

Type RM Length L Ch R = 1,959,442,442,442
BEGIN DESCRIPTION:
Stream0013_DS 2.0
END DESCRIPTION:
XS GIS Cut Line= 3
      2041124.99     13920824.96      2041075.00     13920675.00
      2041187.21     13920305.85
#Sta/Elev= 30
  4845.8 1521.21  4852.8 1521.27  4866.8 1522.71  4878.4 1522.39  4909.0 1521.76
  4930.1 1517.71  4951.2 1516.68  4961.7 1516.95  4982.8 1514.02  5025.5 1513.22
  5035.2 1513.85  5058.4 1512.35  5066.6 1509.40  5075.0 1507.93  5075.3 1507.43
  5078.8 1507.43  5079.0 1507.93  5086.0 1512.07  5091.3 1514.44  5097.9 1519.65
  5118.8 1526.53  5124.1 1531.23  5129.4 1532.45  5162.2 1546.38  5171.1 1549.02
  5181.6 1551.20  5228.0 1554.24  5298.9 1560.47  5331.8 1562.32  5389.7 1568.59
#Mann=5,-1,0
  4845.8    0.07       0  4852.8   0.035       0  4878.4    0.07       0
  5075.0    0.05       0  5079.0    0.07       0
Bank Sta=5075,5079
Exp/Cntr=0.3,0.1

Type RM Length L Ch R = 1,517,116,116,116
BEGIN DESCRIPTION:
Stream0013_DS 1.0
END DESCRIPTION:
XS GIS Cut Line= 3
      2041135.12     13920951.67      2041425.00     13920875.00
      2041379.96     13920514.45
#Sta/Elev= 30
  4695.6 1520.41  4809.3 1518.28  4850.6 1518.10  4871.3 1518.72  4881.7 1517.31
  4897.4 1516.44  4912.7 1514.36  4932.5 1514.05  4943.7 1506.74  4954.1 1503.39
  4970.7 1501.66  4971.0 1501.16  4974.5 1501.16  4974.7 1501.66  4977.9 1504.33
  4998.0 1504.85  5025.7 1506.73  5096.2 1514.47  5106.3 1515.82  5113.9 1517.65
  5118.9 1516.91  5136.5 1520.68  5156.7 1523.52  5166.8 1525.97  5194.5 1529.79
  5199.6 1529.90  5280.2 1538.77  5307.9 1544.72  5317.9 1547.88  5358.8 1552.48
#Mann=3,-1,0
  4695.6    0.07       0  4970.7    0.05       0  4974.7    0.07       0
Bank Sta=4970.7,4974.7
Exp/Cntr=0.3,0.1

Type RM Length L Ch R = 1,401,0,0,0
BEGIN DESCRIPTION:
Stream0013_DS 0.0
END DESCRIPTION:
XS GIS Cut Line= 4
      2041330.79     13921026.52      2041523.69     13920923.38
      2041540.16     13920875.47      2041442.43     13920491.31
#Sta/Elev= 30
  4730.6 1516.53  4780.7 1516.55  4792.3 1515.00  4830.5 1513.33  4890.7 1514.53
  4956.7 1512.29  4960.1 1512.12  4971.4 1510.92  4989.9 1506.83  4997.4 1501.78
  5003.1 1501.78  5008.8 1498.78  5009.1 1498.28  5012.8 1498.78  5031.4 1501.33
  5038.9 1505.25  5052.1 1509.76  5079.8 1514.18  5085.0 1516.83  5166.8 1522.52
  5196.5 1525.69  5207.7 1527.78  5217.2 1527.49  5237.8 1530.53  5279.1 1534.15
  5299.7 1537.52  5320.2 1542.75  5325.3 1543.25  5330.7 1546.50  5396.4 1553.74
#Mann=5,-1,0
  4730.6    0.07       0  4956.7   0.035       0  4960.1    0.07       0
  5008.8    0.05       0  5012.8    0.07       0
Bank Sta=5008.8,5012.8
Exp/Cntr=0.3,0.1

Chan Stop Cuts=-1