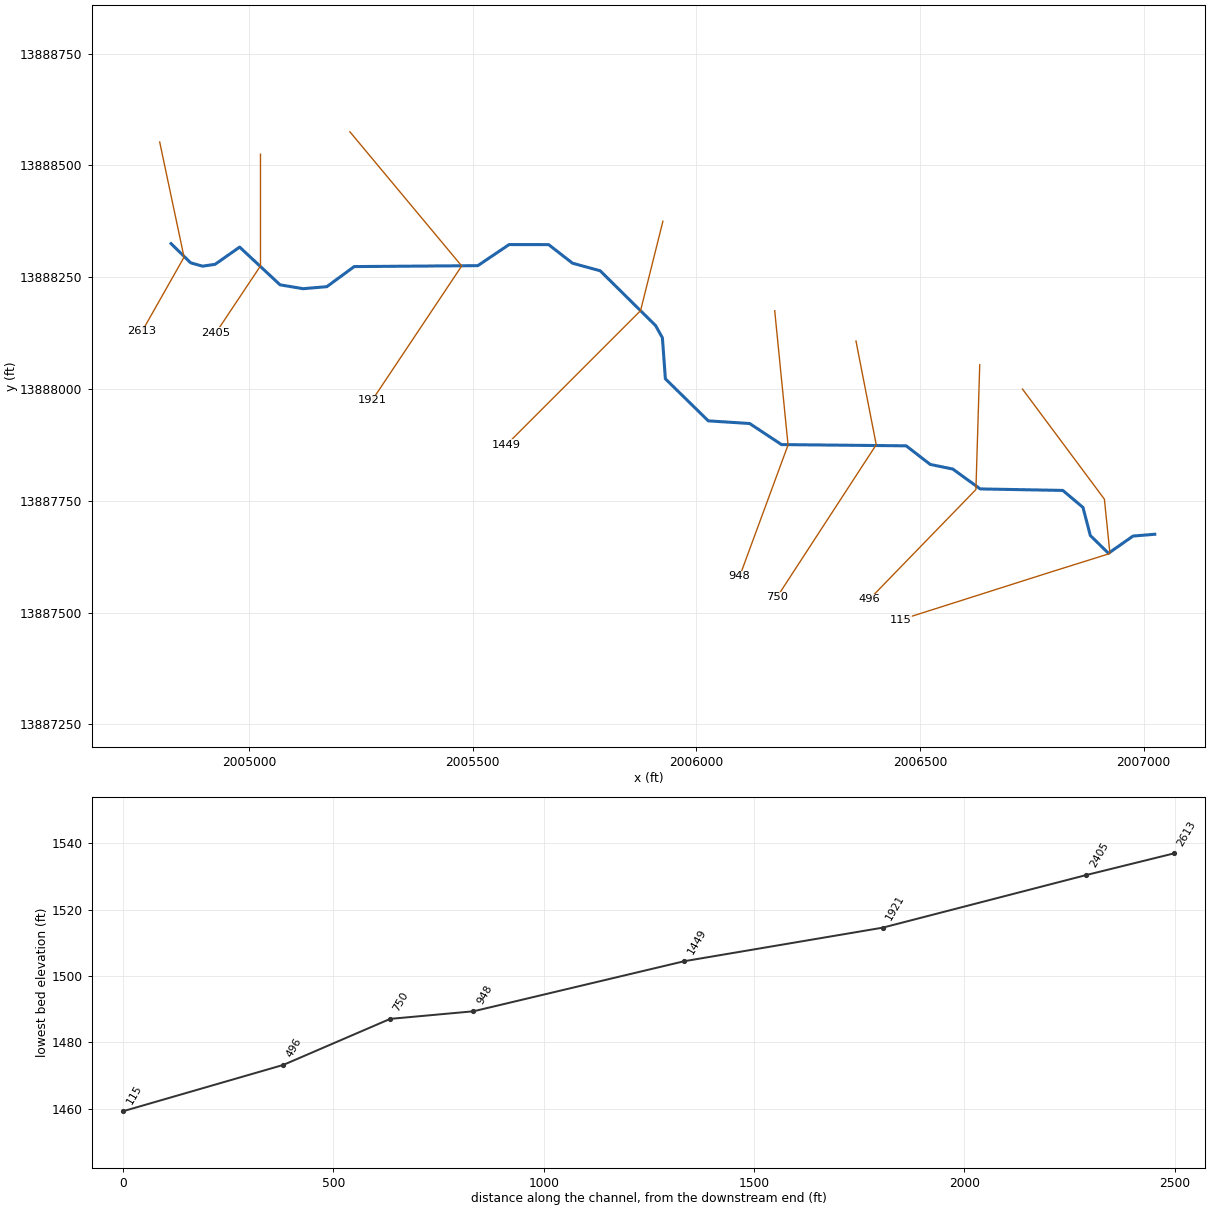
--- Stream0014_DS.prj (project) ---

Proj Title=Stream0014_DS Base Level Engineering
Current Plan=p01
Default Exp/Contr=0.3,0.1
English Units
Geom File=g01
Flow File=f01
Plan File=p01
BEGIN DESCRIPTION:
Stream0014_DS
END DESCRIPTION:

--- Stream0014_DS.p01 (plan) ---

Plan Title=Multiple Run
Short Identifier=Multiple
Geom File=g01
Flow File=f01
Subcritical Flow
K Sum by GR= 0
Std Step Tol= 0.01
Critical Tol= 0.01
Num of Std Step Trials= 20
Max Error Tol= 0.3
Flow Tol Ratio= 0.001
Split Flow NTrial= 30
Split Flow Tol= 0.02
Split Flow Ratio= 0.02
Log Output Level= 0
Friction Slope Method= 1
Unsteady Friction Slope Method= 2
Unsteady Bridges Friction Slope Method= 1
Parabolic Critical Depth
Global Vel Dist=  1 , 1 , 1
Global Log Level= 0
CheckData=True
Encroach Param= -1, 0, 0, 0
BEGIN DESCRIPTION:
Multiple Run
END DESCRIPTION:

--- Stream0014_DS.f01 (steady flow) ---

Flow Title=Multiple
Number of Profiles=7
Profile Names=10-year,25-year,50-year,1pct_min,100-year,1pct_plu,500-year
River Rch & RM= Stream0014_DS,Reach-1,2613
     333     528     702     456     909    1814    1501
Boundary for River Rch & Prof#=Stream0014_DS,Reach-1,1
Up Type=0
Dn Type=3
Dn Slope=0.005
Boundary for River Rch & Prof#=Stream0014_DS,Reach-1,2
Up Type=0
Dn Type=3
Dn Slope=0.005
Boundary for River Rch & Prof#=Stream0014_DS,Reach-1,3
Up Type=0
Dn Type=3
Dn Slope=0.005
Boundary for River Rch & Prof#=Stream0014_DS,Reach-1,4
Up Type=0
Dn Type=3
Dn Slope=0.005
Boundary for River Rch & Prof#=Stream0014_DS,Reach-1,5
Up Type=0
Dn Type=3
Dn Slope=0.005
Boundary for River Rch & Prof#=Stream0014_DS,Reach-1,6
Up Type=0
Dn Type=3
Dn Slope=0.005
Boundary for River Rch & Prof#=Stream0014_DS,Reach-1,7
Up Type=0
Dn Type=3
Dn Slope=0.005

--- Stream0014_DS.g01 (geometry) ---

Geom Title=Existing Conditions

River Reach=Stream0014_DS,Reach-1
Reach XY= 30
      2004825.00     13888325.00      2004868.86     13888281.98
      2004895.25     13888274.54      2004923.42     13888278.61
      2004978.40     13888317.19      2005068.83     13888232.80
      2005120.41     13888224.16      2005173.40     13888228.70
      2005234.66     13888273.62      2005511.08     13888275.69
      2005580.98     13888322.83      2005669.44     13888322.74
      2005722.83     13888281.15      2005784.68     13888264.24
      2005908.54     13888141.75      2005923.83     13888114.52
      2005930.52     13888022.56      2006026.48     13887928.61
      2006119.02     13887922.64      2006190.22     13887875.52
      2006469.07     13887872.76      2006522.82     13887831.12
      2006573.26     13887820.81      2006634.65     13887776.36
      2006819.33     13887773.02      2006864.38     13887735.02
      2006880.85     13887672.18      2006921.34     13887632.48
      2006976.34     13887670.97      2007025.00     13887675.00

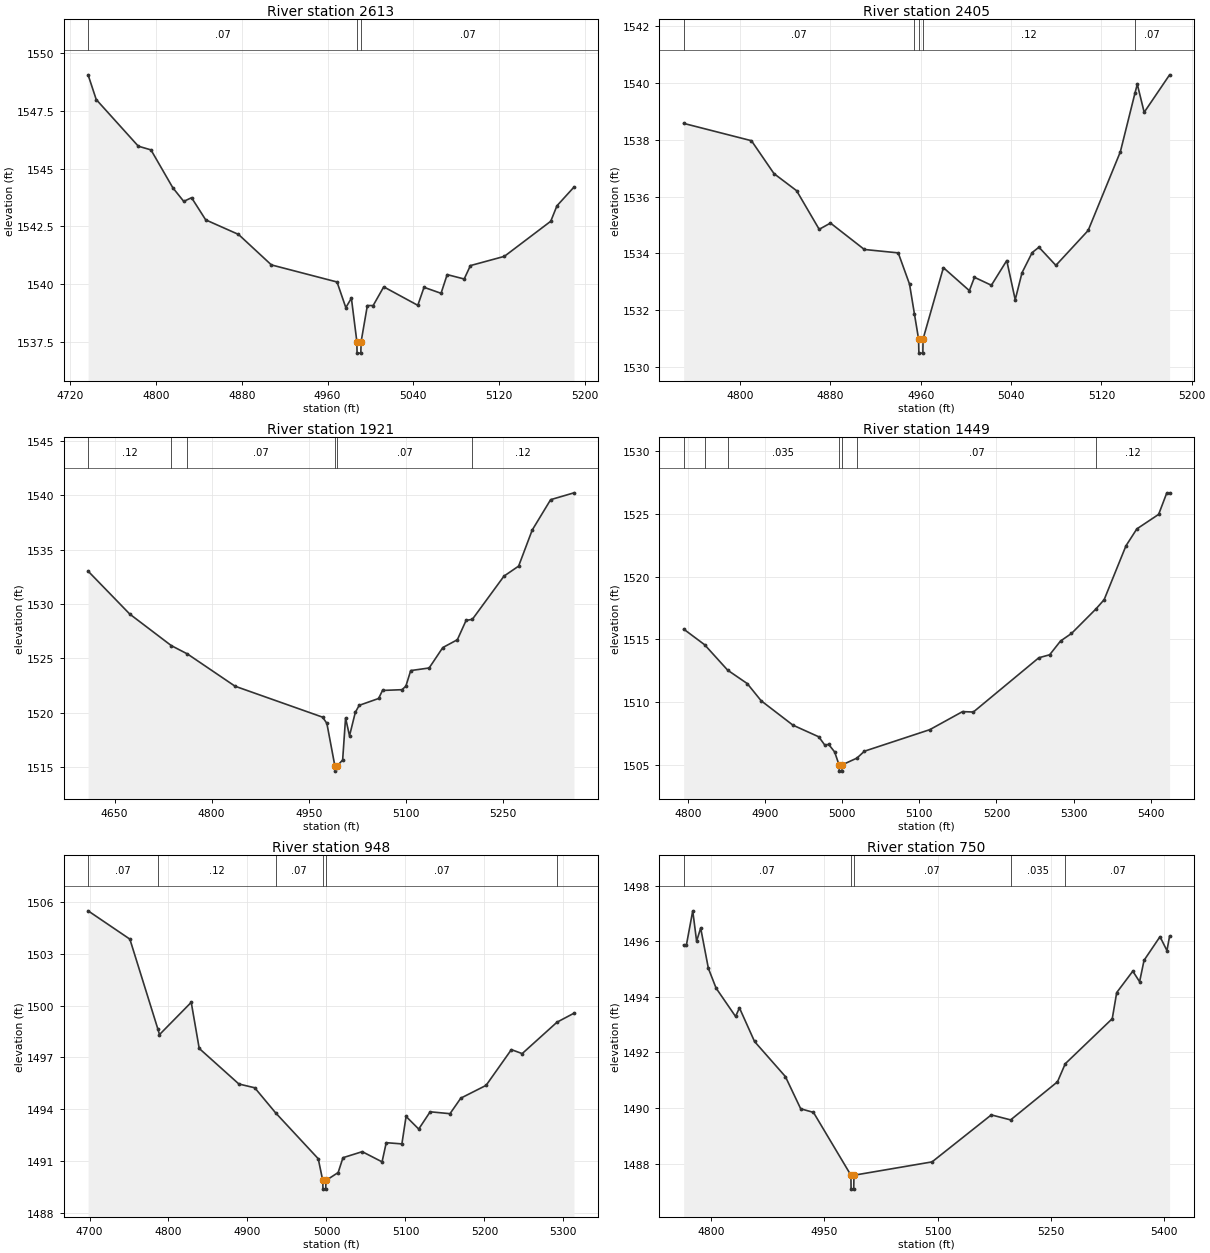
Type RM Length L Ch R = 1,2613,208,208,208
BEGIN DESCRIPTION:
Stream0014_DS 6.0
END DESCRIPTION:
XS GIS Cut Line= 3
      2004799.57     13888552.41      2004854.09     13888294.61
      2004760.43     13888129.18
#Sta/Elev= 30
  4736.5 1549.06  4744.1 1547.99  4783.4 1545.97  4795.2 1545.81  4815.6 1544.17
  4825.8 1543.58  4833.1 1543.74  4846.3 1542.78  4876.9 1542.15  4907.6 1540.83
  4968.9 1540.09  4977.1 1538.98  4982.3 1539.39  4987.4 1537.51  4987.6 1537.01
  4991.1 1537.01  4991.4 1537.51  4997.2 1539.07  5002.6 1539.07  5012.5 1539.88
  5044.3 1539.08  5050.1 1539.86  5066.0 1539.60  5071.7 1540.41  5087.6 1540.22
  5093.4 1540.80  5125.1 1541.20  5168.4 1542.72  5174.2 1543.39  5190.1 1544.20
#Mann=3,-1,0
  4736.5    0.07       0  4987.4    0.05       0  4991.4    0.07       0
Bank Sta=4987.4,4991.4
Exp/Cntr=0.3,0.1

Type RM Length L Ch R = 1,2405,484,484,484
BEGIN DESCRIPTION:
Stream0014_DS 5.0
END DESCRIPTION:
XS GIS Cut Line= 3
      2005025.00     13888525.01      2005025.00     13888275.00
      2004924.99     13888124.99
#Sta/Elev= 30
  4750.1 1538.58  4810.1 1537.97  4830.1 1536.81  4850.1 1536.21  4870.1 1534.85
  4880.1 1535.07  4910.1 1534.14  4940.1 1534.02  4950.1 1532.92  4954.4 1531.88
  4958.1 1530.99  4958.4 1530.49  4961.9 1530.49  4962.1 1530.99  4980.1 1533.50
  5003.1 1532.69  5007.6 1533.16  5022.6 1532.88  5036.2 1533.75  5043.7 1532.37
  5049.7 1533.32  5058.7 1534.03  5064.7 1534.22  5079.7 1533.58  5108.3 1534.81
  5136.8 1537.58  5149.7 1539.64  5151.8 1539.96  5157.9 1538.97  5180.4 1540.29
#Mann=5,-1,0
  4750.1    0.07       0  4954.4    0.12       0  4958.1    0.05       0
  4962.1    0.12       0  5149.7    0.07       0
Bank Sta=4958.1,4962.1
Exp/Cntr=0.3,0.1

Type RM Length L Ch R = 1,1921,472,472,472
BEGIN DESCRIPTION:
Stream0014_DS 4.0
END DESCRIPTION:
XS GIS Cut Line= 3
      2005224.99     13888575.02      2005475.00     13888275.00
      2005274.99     13887974.99
#Sta/Elev= 30
  4609.0 1533.03  4673.5 1529.07  4737.6 1526.17  4762.6 1525.40  4836.2 1522.43
  4971.5 1519.58  4978.1 1519.01  4990.4 1515.11  4990.6 1514.61  4994.4 1515.11
  5002.5 1515.64  5007.0 1519.51  5013.1 1517.86  5022.1 1520.03  5028.1 1520.67
  5058.1 1521.30  5064.1 1522.04  5094.2 1522.11  5100.2 1522.43  5107.7 1523.87
  5136.2 1524.11  5157.3 1525.99  5179.8 1526.71  5193.3 1528.49  5203.0 1528.59
  5251.9 1532.57  5274.5 1533.49  5295.5 1536.81  5324.0 1539.61  5360.1 1540.24
#Mann=6,-1,0
  4609.0    0.12       0  4737.6   0.035       0  4762.6    0.07       0
  4990.4    0.05       0  4994.4    0.07       0  5203.0    0.12       0
Bank Sta=4990.4,4994.4
Exp/Cntr=0.3,0.1

Type RM Length L Ch R = 1,1449,501,501,501
BEGIN DESCRIPTION:
Stream0014_DS 3.0
END DESCRIPTION:
XS GIS Cut Line= 3
      2005925.01     13888375.04      2005875.00     13888175.00
      2005574.97     13887874.97
#Sta/Elev= 30
  4794.1 1515.82  4821.3 1514.57  4851.2 1512.54  4876.6 1511.47  4894.6 1510.10
  4935.9 1508.15  4969.4 1507.22  4977.1 1506.57  4982.3 1506.61  4990.0 1506.01
  4995.7 1504.98  4996.0 1504.48  4999.5 1504.48  4999.7 1504.98  5018.9 1505.52
  5028.6 1506.07  5113.4 1507.79  5155.9 1509.23  5170.0 1509.20  5254.9 1513.53
  5269.0 1513.77  5283.1 1514.87  5297.3 1515.47  5328.9 1517.42  5339.7 1518.17
  5368.0 1522.47  5382.1 1523.82  5410.4 1524.98  5421.0 1526.70  5424.6 1526.70
#Mann=7,-1,0
  4794.1   0.035       0  4821.3    0.07       0  4851.2   0.035       0
  4995.7   0.035       0  4999.7   0.035       0  5018.9    0.07       0
  5328.9    0.12       0
Bank Sta=4995.7,4999.7
Exp/Cntr=0.3,0.1

Type RM Length L Ch R = 1,948,198,198,198
BEGIN DESCRIPTION:
Stream0014_DS 2.0
END DESCRIPTION:
XS GIS Cut Line= 3
      2006175.00     13888174.96      2006204.85     13887874.64
      2006096.53     13887580.56
#Sta/Elev= 30
  4698.2 1505.49  4751.1 1503.85  4786.5 1498.65  4788.6 1498.32  4828.8 1500.19
  4838.9 1497.52  4889.1 1495.46  4909.2 1495.24  4935.6 1493.79  4989.6 1491.13
  4995.3 1489.87  4995.6 1489.37  4999.1 1489.37  4999.3 1489.87  5014.8 1490.33
  5020.9 1491.19  5045.3 1491.54  5070.4 1490.95  5075.7 1492.06  5095.5 1491.99
  5100.8 1493.58  5116.8 1492.85  5131.3 1493.85  5156.4 1493.74  5170.1 1494.64
  5202.1 1495.38  5234.1 1497.45  5247.8 1497.22  5291.9 1499.04  5313.4 1499.56
#Mann=6,-1,0
  4698.2    0.07       0  4786.5    0.12       0  4935.6    0.07       0
  4995.3    0.05       0  4999.3    0.07       0  5291.9    0.12       0
Bank Sta=4995.3,4999.3
Exp/Cntr=0.3,0.1

Type RM Length L Ch R = 1,750,254,254,254
BEGIN DESCRIPTION:
Stream0014_DS 1.5
END DESCRIPTION:
XS GIS Cut Line= 3
      2006356.77     13888107.07      2006402.05     13887875.26
      2006179.98     13887534.18
#Sta/Elev= 30
  4763.8 1495.86  4767.4 1495.86  4775.8 1497.09  4780.9 1496.00  4786.3 1496.47
  4796.5 1495.02  4806.7 1494.31  4832.5 1493.29  4837.6 1493.60  4857.6 1492.39
  4898.4 1491.13  4918.7 1489.97  4935.6 1489.84  4985.2 1487.58  4985.4 1487.08
  4988.9 1487.08  4989.2 1487.58  5092.6 1488.06  5171.0 1489.75  5196.6 1489.57
  5258.6 1490.94  5268.9 1491.59  5331.1 1493.21  5337.0 1494.15  5358.3 1494.92
  5367.3 1494.54  5373.2 1495.31  5394.3 1496.16  5403.5 1495.66  5407.0 1496.18
#Mann=5,-1,0
  4763.8    0.07       0  4985.2    0.05       0  4989.2    0.07       0
  5196.6   0.035       0  5268.9    0.07       0
Bank Sta=4985.2,4989.2
Exp/Cntr=0.3,0.1

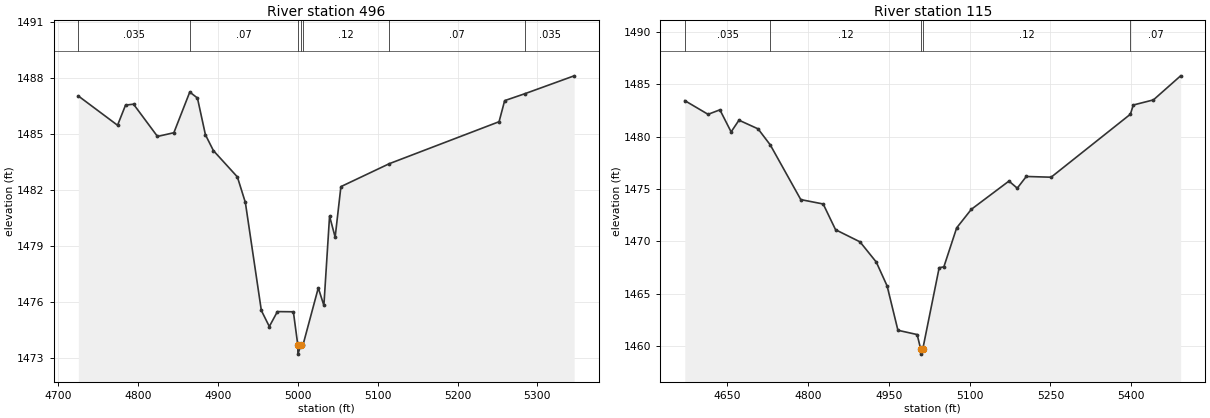
Type RM Length L Ch R = 1,496,381,381,381
BEGIN DESCRIPTION:
Stream0014_DS 1.0
END DESCRIPTION:
XS GIS Cut Line= 3
      2006633.51     13888054.03      2006625.00     13887775.00
      2006387.13     13887529.92
#Sta/Elev= 30
  4725.3 1487.03  4774.4 1485.46  4784.4 1486.54  4794.4 1486.59  4824.4 1484.86
  4844.9 1485.06  4864.8 1487.24  4874.4 1486.92  4884.4 1484.95  4894.4 1484.10
  4924.4 1482.69  4934.4 1481.32  4954.4 1475.53  4964.4 1474.67  4974.5 1475.47
  4994.5 1475.46  5000.0 1473.69  5000.2 1473.19  5004.0 1473.69  5006.6 1473.69
  5025.7 1476.74  5032.7 1475.80  5039.8 1480.59  5046.8 1479.46  5054.0 1482.17
  5114.6 1483.40  5252.0 1485.65  5259.0 1486.78  5284.2 1487.15  5346.0 1488.11
#Mann=7,-1,0
  4725.3   0.035       0  4864.8    0.07       0  5000.0    0.05       0
  5004.0    0.07       0  5006.6    0.12       0  5114.6    0.07       0
  5284.2   0.035       0
Bank Sta=5000,5004
Exp/Cntr=0.3,0.1

Type RM Length L Ch R = 1,115,0,0,0
BEGIN DESCRIPTION:
Stream0014_DS 0.0
END DESCRIPTION:
XS GIS Cut Line= 5
      2006729.12     13887999.65      2006912.31     13887753.42
      2006924.70     13887631.95      2006796.04     13887591.65
      2006455.86     13887483.45
#Sta/Elev= 30
  4571.0 1483.44  4614.2 1482.13  4636.2 1482.56  4657.0 1480.45  4671.6 1481.57
  4707.1 1480.74  4729.7 1479.21  4786.4 1473.98  4828.0 1473.56  4851.0 1471.10
  4896.4 1469.94  4926.6 1468.01  4946.7 1465.73  4966.8 1461.49  5002.5 1461.08
  5009.0 1459.71  5009.2 1459.21  5013.0 1459.71  5043.4 1467.47  5052.1 1467.55
  5075.9 1471.28  5103.1 1473.05  5173.0 1475.75  5188.4 1475.07  5205.2 1476.19
  5251.3 1476.12  5398.5 1482.14  5403.9 1483.02  5441.3 1483.51  5491.8 1485.81
#Mann=5,-1,0
  4571.0   0.035       0  4729.7    0.12       0  5009.0    0.05       0
  5013.0    0.12       0  5398.5    0.07       0
Bank Sta=5009,5013
Exp/Cntr=0.3,0.1

Chan Stop Cuts=-1