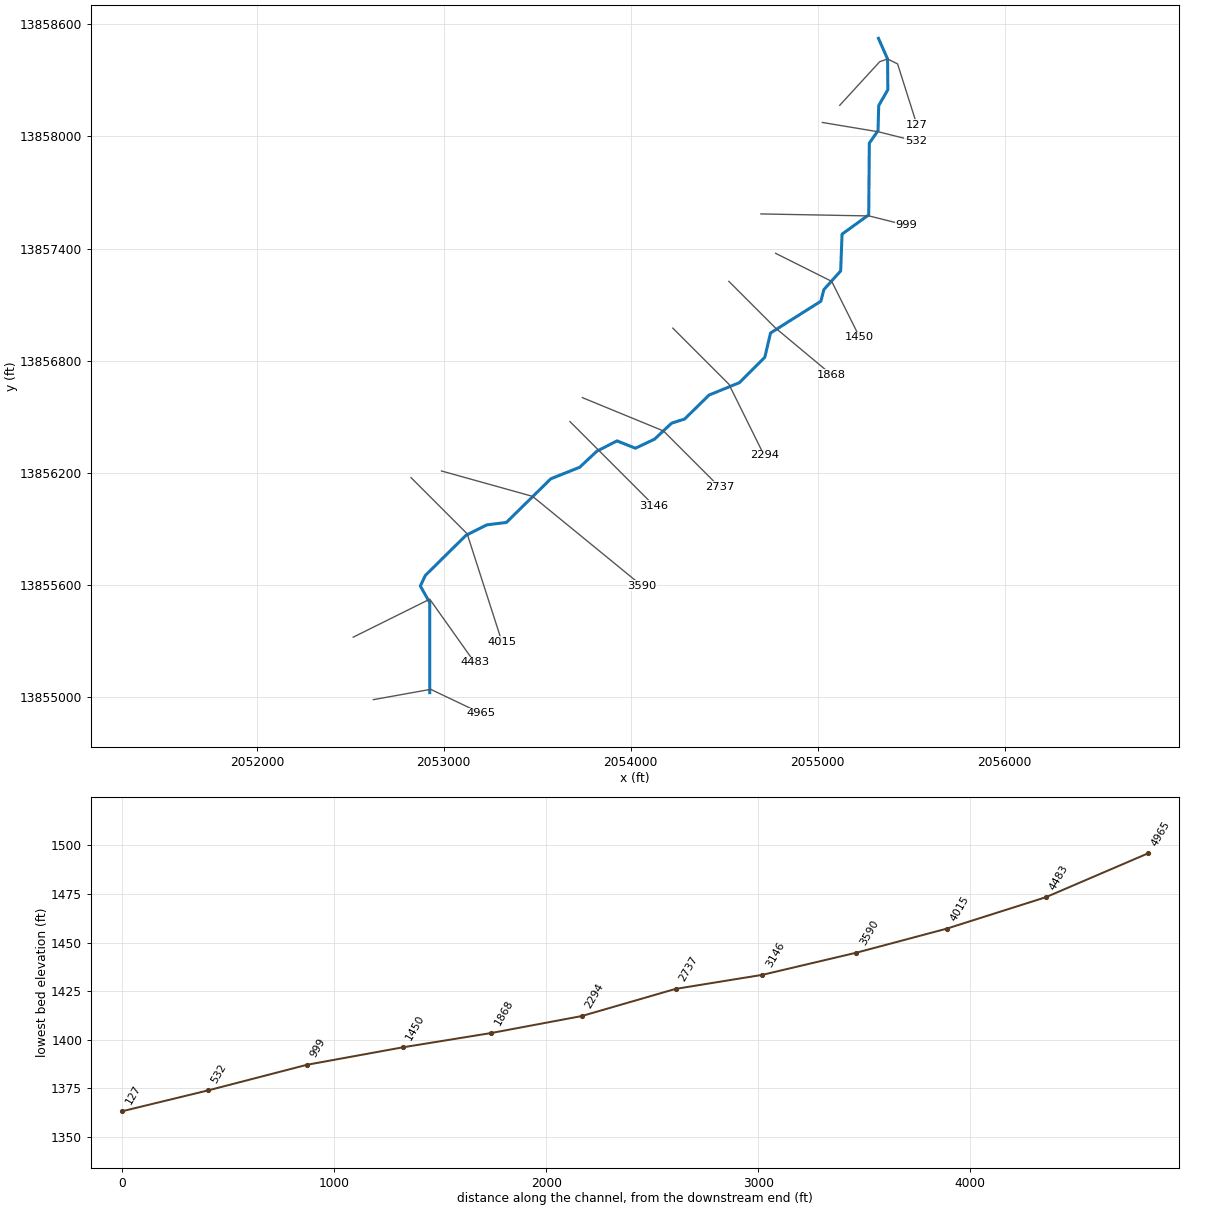
--- Stream0015_DS.prj (project) ---

Proj Title=Stream0015_DS Base Level Engineering
Current Plan=p01
Default Exp/Contr=0.3,0.1
English Units
Geom File=g01
Flow File=f01
Plan File=p01
BEGIN DESCRIPTION:
Stream0015_DS
END DESCRIPTION:

--- Stream0015_DS.p01 (plan) ---

Plan Title=Multiple Run
Short Identifier=Multiple
Geom File=g01
Flow File=f01
Subcritical Flow
K Sum by GR= 0
Std Step Tol= 0.01
Critical Tol= 0.01
Num of Std Step Trials= 20
Max Error Tol= 0.3
Flow Tol Ratio= 0.001
Split Flow NTrial= 30
Split Flow Tol= 0.02
Split Flow Ratio= 0.02
Log Output Level= 0
Friction Slope Method= 1
Unsteady Friction Slope Method= 2
Unsteady Bridges Friction Slope Method= 1
Parabolic Critical Depth
Global Vel Dist=  1 , 1 , 1
Global Log Level= 0
CheckData=True
Encroach Param= -1, 0, 0, 0
BEGIN DESCRIPTION:
Multiple Run
END DESCRIPTION:

--- Stream0015_DS.f01 (steady flow) ---

Flow Title=Multiple
Number of Profiles=7
Profile Names=10-year,25-year,50-year,1pct_min,100-year,1pct_plu,500-year
River Rch & RM= Stream0015_DS,Reach-1,4965
     309     479     629     403     804    1603    1290
River Rch & RM= Stream0015_DS,Reach-1,3146
     463     739     988     643    1282    2558    2128
Boundary for River Rch & Prof#=Stream0015_DS,Reach-1,1
Up Type=0
Dn Type=3
Dn Slope=0.005
Boundary for River Rch & Prof#=Stream0015_DS,Reach-1,2
Up Type=0
Dn Type=3
Dn Slope=0.005
Boundary for River Rch & Prof#=Stream0015_DS,Reach-1,3
Up Type=0
Dn Type=3
Dn Slope=0.005
Boundary for River Rch & Prof#=Stream0015_DS,Reach-1,4
Up Type=0
Dn Type=3
Dn Slope=0.005
Boundary for River Rch & Prof#=Stream0015_DS,Reach-1,5
Up Type=0
Dn Type=3
Dn Slope=0.005
Boundary for River Rch & Prof#=Stream0015_DS,Reach-1,6
Up Type=0
Dn Type=3
Dn Slope=0.005
Boundary for River Rch & Prof#=Stream0015_DS,Reach-1,7
Up Type=0
Dn Type=3
Dn Slope=0.005

--- Stream0015_DS.g01 (geometry) ---

Geom Title=Existing Conditions

River Reach=Stream0015_DS,Reach-1
Reach XY= 30
      2052925.00     13855025.00      2052924.77     13855506.74
      2052874.64     13855595.21      2052901.04     13855651.82
      2053118.94     13855866.86      2053230.56     13855922.55
      2053334.79     13855935.52      2053572.70     13856169.17
      2053727.29     13856230.85      2053818.95     13856316.85
      2053926.73     13856371.63      2054025.00     13856332.56
      2054127.28     13856380.82      2054218.96     13856466.82
      2054288.21     13856488.63      2054418.94     13856616.86
      2054581.06     13856683.14      2054717.14     13856818.83
      2054747.72     13856948.89      2055016.96     13857118.67
      2055033.19     13857181.02      2055122.93     13857280.86
      2055130.36     13857477.70      2055273.02     13857580.67
      2055276.22     13857964.50      2055322.73     13858030.94
      2055326.39     13858165.33      2055375.20     13858249.92
      2055373.88     13858414.54      2055325.00     13858525.00

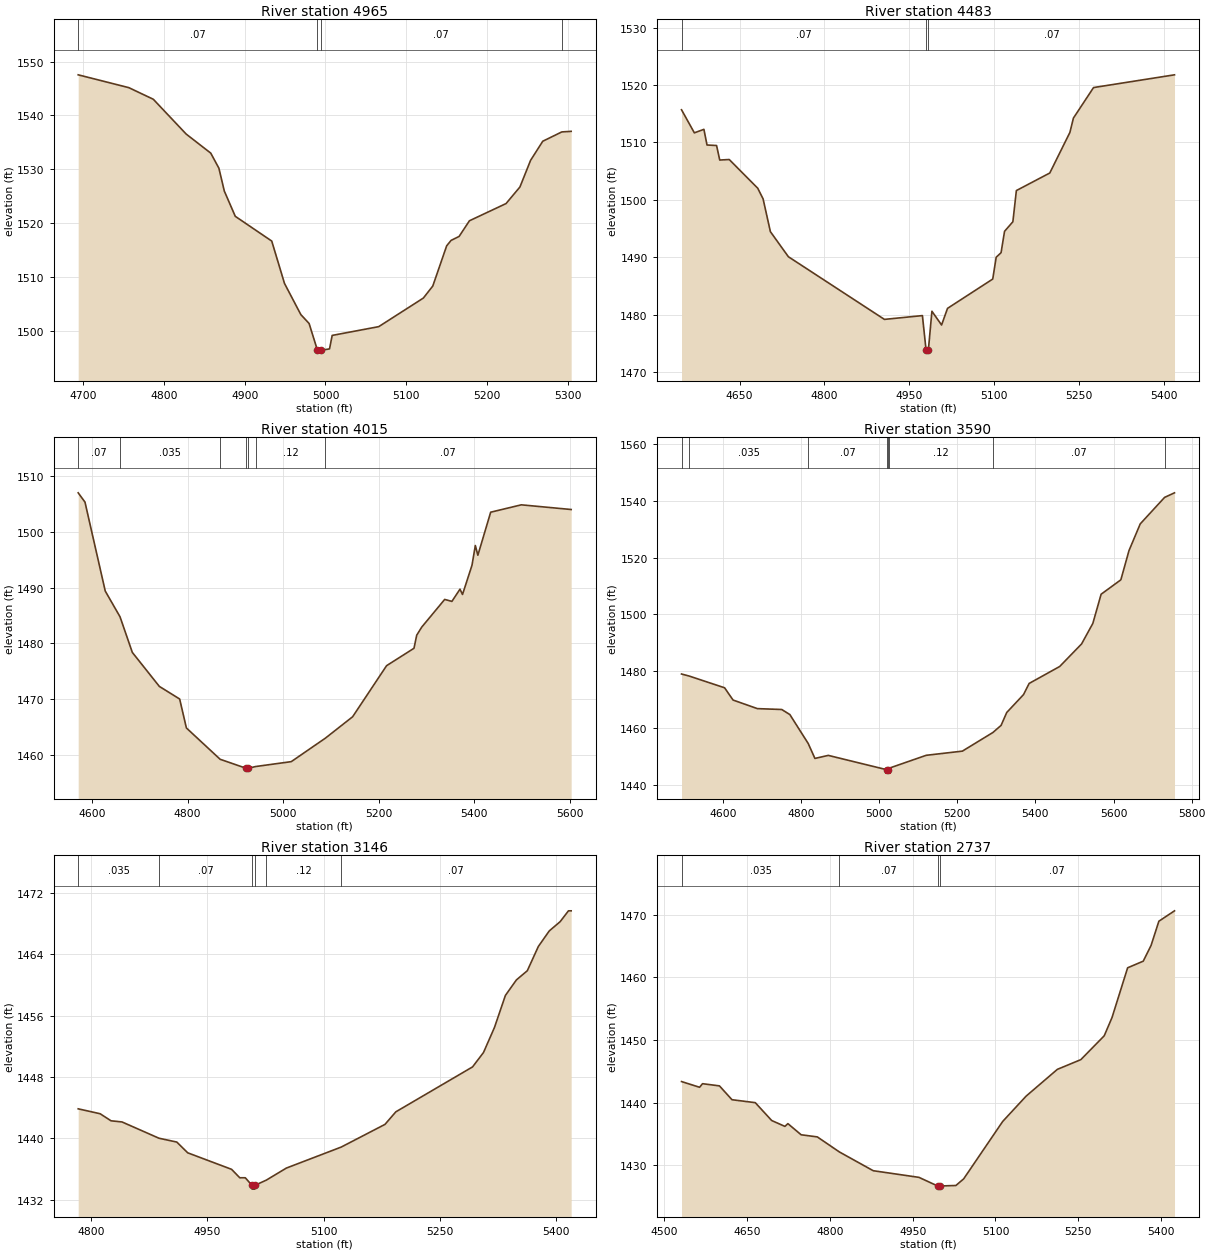
Type RM Length L Ch R = 1,4965,482,482,482
BEGIN DESCRIPTION:
Stream0015_DS 11.0
END DESCRIPTION:
XS GIS Cut Line= 3
      2052623.34     13854987.66      2052929.94     13855042.78
      2053200.43     13854914.23
#Sta/Elev= 30
  4693.5 1547.54  4756.2 1545.16  4786.6 1543.00  4827.3 1536.54  4857.8 1532.99
  4867.9 1530.19  4874.6 1525.95  4888.2 1521.25  4933.4 1516.65  4949.2 1508.78
  4969.5 1502.98  4979.7 1501.34  4990.1 1496.33  4990.4 1495.83  4994.1 1496.33
  5005.0 1496.62  5008.3 1499.12  5066.0 1500.75  5121.3 1506.06  5133.0 1508.30
  5150.2 1515.77  5155.7 1516.78  5165.6 1517.51  5178.4 1520.42  5223.8 1523.62
  5241.0 1526.70  5254.2 1531.65  5269.3 1535.20  5292.9 1536.93  5304.5 1537.04
#Mann=4,-1,0
  4693.5    0.07       0  4990.1    0.05       0  4994.1    0.07       0
  5292.9    0.12       0
Bank Sta=4990.1,4994.1
Exp/Cntr=0.3,0.1

Type RM Length L Ch R = 1,4483,468,468,468
BEGIN DESCRIPTION:
Stream0015_DS 10.0
END DESCRIPTION:
XS GIS Cut Line= 3
      2052515.70     13855321.85      2052925.00     13855525.00
      2053165.05     13855186.40
#Sta/Elev= 30
  4547.2 1515.70  4569.9 1511.68  4586.8 1512.29  4592.3 1509.56  4609.2 1509.47
  4614.8 1506.94  4631.6 1507.03  4682.0 1502.03  4691.5 1500.17  4704.4 1494.46
  4736.2 1490.09  4906.1 1479.17  4973.3 1479.83  4979.8 1473.79  4980.1 1473.29
  4983.8 1473.79  4990.1 1480.59  5007.2 1478.19  5017.7 1481.09  5097.7 1486.20
  5103.8 1490.00  5112.4 1490.79  5118.6 1494.52  5133.3 1496.18  5139.5 1501.62
  5198.6 1504.68  5234.2 1511.76  5240.4 1514.25  5276.0 1519.57  5419.2 1521.79
#Mann=3,-1,0
  4547.2    0.07       0  4979.8    0.05       0  4983.8    0.07       0
Bank Sta=4979.8,4983.8
Exp/Cntr=0.3,0.1

Type RM Length L Ch R = 1,4015,425,425,425
BEGIN DESCRIPTION:
Stream0015_DS 9.0
END DESCRIPTION:
XS GIS Cut Line= 3
      2052824.98     13856175.02      2053125.00     13855875.00
      2053310.85     13855297.57
#Sta/Elev= 30
  4571.4 1506.97  4585.6 1505.31  4628.0 1489.37  4658.9 1484.76  4684.6 1478.38
  4741.1 1472.29  4783.6 1470.03  4797.7 1464.84  4868.3 1459.23  4923.0 1457.61
  4923.2 1457.11  4927.0 1457.61  4942.2 1457.93  5017.0 1458.81  5088.4 1463.02
  5145.3 1466.85  5216.3 1476.00  5273.6 1479.12  5279.3 1481.46  5289.8 1482.91
  5337.8 1487.87  5352.9 1487.52  5369.8 1489.71  5375.1 1488.76  5394.9 1493.99
  5401.9 1497.53  5407.2 1495.79  5434.0 1503.50  5498.1 1504.82  5602.3 1503.98
#Mann=7,-1,0
  4571.4    0.07       0  4658.9   0.035       0  4868.3    0.07       0
  4923.0    0.05       0  4927.0    0.07       0  4942.2    0.12       0
  5088.4    0.07       0
Bank Sta=4923,4927
Exp/Cntr=0.3,0.1

Type RM Length L Ch R = 1,3590,444,444,444
BEGIN DESCRIPTION:
Stream0015_DS 8.0
END DESCRIPTION:
XS GIS Cut Line= 3
      2052987.94     13856210.75      2053475.00     13856075.00
      2054060.41     13855596.52
#Sta/Elev= 30
  4494.4 1478.99  4514.0 1478.27  4604.6 1474.14  4626.3 1469.82  4688.6 1466.80
  4750.9 1466.49  4771.6 1464.72  4818.6 1454.53  4835.8 1449.26  4870.0 1450.33
  5019.6 1445.29  5019.8 1444.79  5023.6 1445.29  5025.9 1445.83  5120.6 1450.36
  5213.2 1451.83  5291.3 1458.39  5312.3 1460.90  5326.7 1465.43  5369.7 1471.74
  5384.1 1475.67  5462.3 1481.64  5518.3 1489.58  5547.1 1496.81  5568.3 1507.08
  5618.8 1512.16  5639.7 1522.47  5668.4 1531.85  5730.8 1541.19  5756.1 1542.79
#Mann=8,-1,0
  4494.4    0.12       0  4514.0   0.035       0  4818.6    0.07       0
  5019.6    0.05       0  5023.6    0.07       0  5025.9    0.12       0
  5291.3    0.07       0  5730.8    0.12       0
Bank Sta=5019.6,5023.6
Exp/Cntr=0.3,0.1

Type RM Length L Ch R = 1,3146,409,409,409
BEGIN DESCRIPTION:
Stream0015_DS 7.0
END DESCRIPTION:
XS GIS Cut Line= 3
      2053675.01     13856474.99      2053825.00     13856325.00
      2054125.01     13856024.99
#Sta/Elev= 30
  4783.1 1443.85  4811.4 1443.21  4825.5 1442.29  4839.7 1442.14  4887.4 1440.02
  4910.4 1439.52  4924.5 1438.12  4981.1 1435.97  4991.7 1434.87  4998.8 1434.87
  5007.4 1433.89  5007.6 1433.39  5011.1 1433.39  5011.4 1433.89  5026.1 1434.57
  5051.8 1436.13  5122.7 1438.87  5179.1 1441.82  5193.2 1443.46  5292.2 1449.31
  5306.3 1451.18  5320.5 1454.45  5334.6 1458.62  5348.8 1460.64  5362.9 1461.84
  5377.1 1464.99  5391.2 1467.02  5405.3 1468.23  5416.0 1469.64  5419.5 1469.64
#Mann=6,-1,0
  4783.1   0.035       0  4887.4    0.07       0  5007.4    0.05       0
  5011.4    0.07       0  5026.1    0.12       0  5122.7    0.07       0
Bank Sta=5007.4,5011.4
Exp/Cntr=0.3,0.1

Type RM Length L Ch R = 1,2737,443,443,443
BEGIN DESCRIPTION:
Stream0015_DS 6.0
END DESCRIPTION:
XS GIS Cut Line= 3
      2053741.44     13856603.09      2054175.00     13856425.00
      2054475.02     13856124.98
#Sta/Elev= 30
  4531.3 1443.35  4564.0 1442.44  4569.4 1443.01  4600.0 1442.66  4622.7 1440.45
  4664.9 1439.98  4694.6 1437.13  4718.6 1436.19  4724.0 1436.63  4748.0 1434.85
  4777.3 1434.51  4817.4 1432.10  4878.6 1429.11  4961.4 1428.05  4995.3 1426.67
  4995.6 1426.17  4999.3 1426.67  5028.3 1426.75  5042.4 1427.81  5113.1 1436.98
  5155.6 1441.03  5212.1 1445.30  5254.6 1446.85  5297.0 1450.66  5311.1 1453.57
  5339.4 1461.52  5367.7 1462.58  5381.8 1465.08  5396.0 1468.96  5424.3 1470.62
#Mann=4,-1,0
  4531.3   0.035       0  4817.4    0.07       0  4995.3    0.05       0
  4999.3    0.07       0
Bank Sta=4995.3,4999.3
Exp/Cntr=0.3,0.1

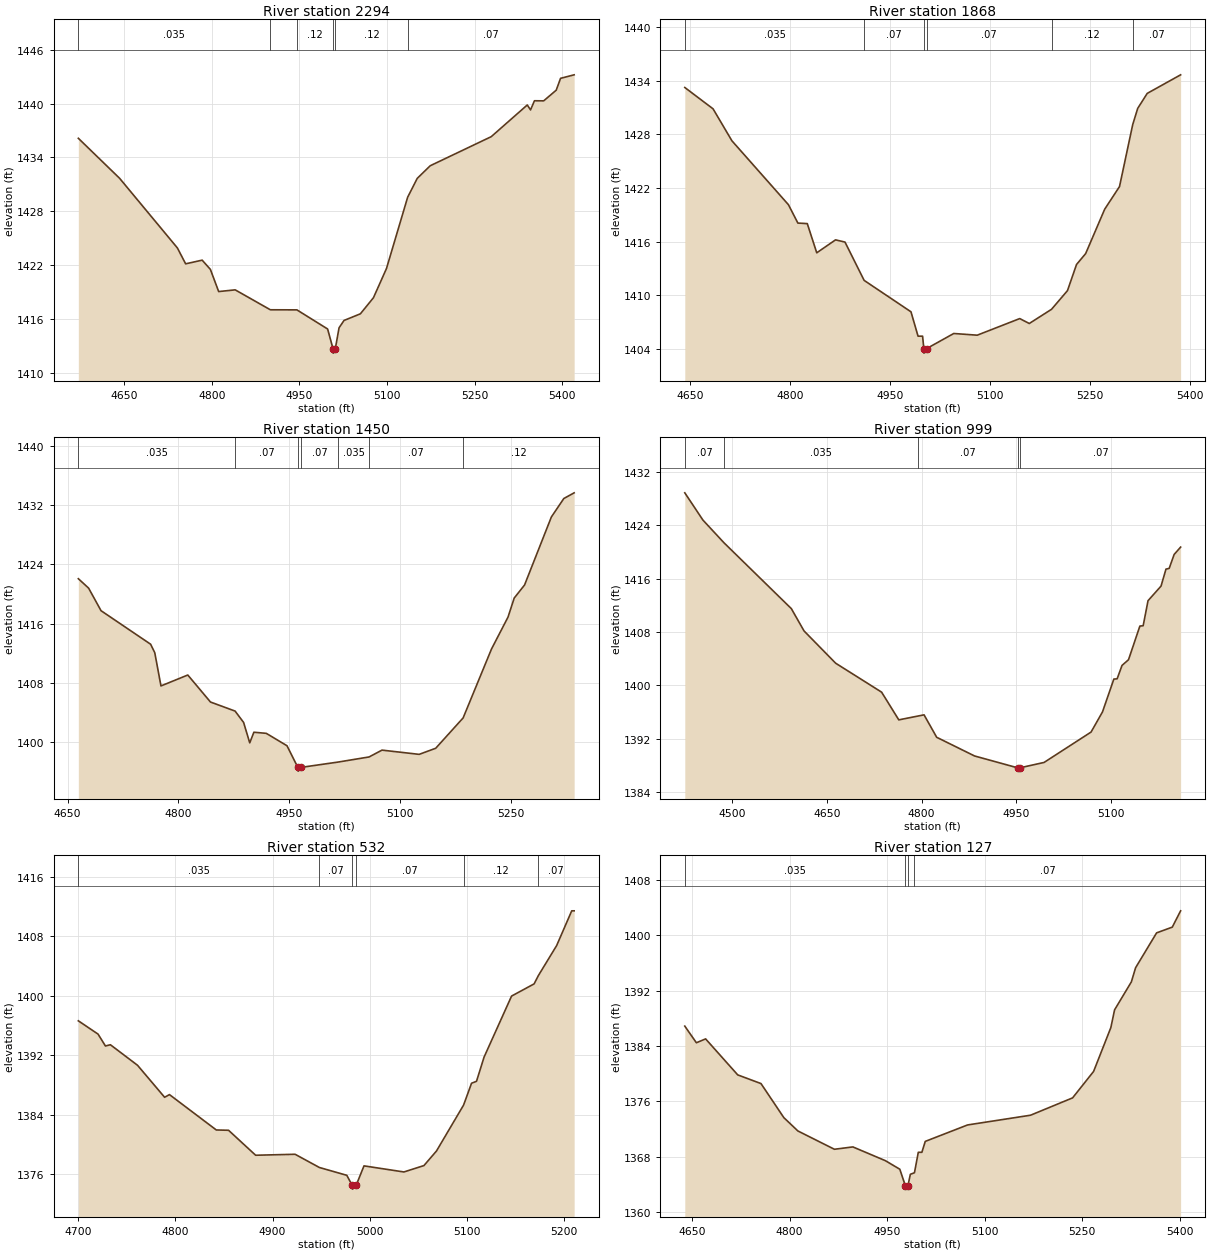
Type RM Length L Ch R = 1,2294,426,426,426
BEGIN DESCRIPTION:
Stream0015_DS 5.0
END DESCRIPTION:
XS GIS Cut Line= 3
      2054225.02     13856974.98      2054525.00     13856675.00
      2054713.63     13856294.08
#Sta/Elev= 30
  4571.2 1436.14  4641.9 1431.68  4740.9 1423.92  4755.0 1422.15  4783.3 1422.56
  4797.4 1421.53  4811.6 1419.06  4839.9 1419.25  4900.1 1417.03  4945.6 1417.02
  4998.2 1414.89  5007.4 1412.70  5007.7 1412.20  5011.4 1412.70  5017.8 1415.02
  5026.3 1415.84  5054.3 1416.58  5076.7 1418.37  5099.1 1421.64  5135.3 1429.57
  5151.7 1431.67  5174.0 1433.08  5278.5 1436.32  5340.2 1439.85  5345.8 1439.30
  5352.5 1440.32  5368.3 1440.31  5389.8 1441.50  5397.2 1442.82  5420.5 1443.21
#Mann=6,-1,0
  4571.2   0.035       0  4900.1    0.07       0  4945.6    0.12       0
  5007.4    0.05       0  5011.4    0.12       0  5135.3    0.07       0
Bank Sta=5007.4,5011.4
Exp/Cntr=0.3,0.1

Type RM Length L Ch R = 1,1868,418,418,418
BEGIN DESCRIPTION:
Stream0015_DS 4.0
END DESCRIPTION:
XS GIS Cut Line= 3
      2054525.02     13857224.98      2054775.00     13856975.00
      2055074.97     13856725.02
#Sta/Elev= 30
  4641.6 1433.26  4684.0 1430.87  4712.3 1427.29  4797.1 1420.13  4811.3 1418.07
  4825.4 1418.01  4839.6 1414.74  4867.8 1416.19  4882.0 1415.94  4910.7 1411.65
  4981.0 1408.13  4991.6 1405.40  4998.4 1405.40  5000.3 1404.00  5000.5 1403.50
  5004.3 1404.00  5045.2 1405.70  5080.4 1405.51  5144.2 1407.37  5158.5 1406.82
  5191.9 1408.41  5215.8 1410.50  5229.4 1413.43  5243.1 1414.65  5271.7 1419.63
  5293.9 1422.16  5313.7 1429.10  5321.2 1430.92  5335.5 1432.60  5385.6 1434.68
#Mann=6,-1,0
  4641.6   0.035       0  4910.7    0.07       0  5000.3    0.05       0
  5004.3    0.07       0  5191.9    0.12       0  5313.7    0.07       0
Bank Sta=5000.3,5004.3
Exp/Cntr=0.3,0.1

Type RM Length L Ch R = 1,1450,451,451,451
BEGIN DESCRIPTION:
Stream0015_DS 3.0
END DESCRIPTION:
XS GIS Cut Line= 3
      2054775.04     13857374.98      2055075.00     13857225.00
      2055225.01     13856924.98
#Sta/Elev= 30
  4664.6 1422.06  4678.5 1420.79  4695.3 1417.75  4762.4 1413.23  4768.0 1412.09
  4776.4 1407.61  4812.7 1409.08  4843.4 1405.44  4876.7 1404.22  4888.2 1402.69
  4896.5 1399.94  4902.1 1401.37  4918.9 1401.22  4946.9 1399.55  4961.6 1396.63
  4961.9 1396.13  4965.6 1396.63  5016.0 1397.35  5058.0 1398.04  5075.4 1398.96
  5125.7 1398.39  5148.1 1399.21  5185.2 1403.30  5223.6 1412.59  5245.9 1416.88
  5254.3 1419.45  5268.3 1421.21  5304.6 1430.38  5321.4 1432.86  5335.4 1433.63
#Mann=7,-1,0
  4664.6   0.035       0  4876.7    0.07       0  4961.6    0.05       0
  4965.6    0.07       0  5016.0   0.035       0  5058.0    0.07       0
  5185.2    0.12       0
Bank Sta=4961.6,4965.6
Exp/Cntr=0.3,0.1

Type RM Length L Ch R = 1,999,467,467,467
BEGIN DESCRIPTION:
Stream0015_DS 2.0
END DESCRIPTION:
XS GIS Cut Line= 3
      2054696.28     13857585.74      2055275.00     13857575.00
      2055475.03     13857524.99
#Sta/Elev= 30
  4425.2 1428.86  4453.9 1424.78  4487.1 1421.39  4593.9 1411.51  4614.0 1408.17
  4664.0 1403.34  4736.8 1399.00  4764.0 1394.85  4794.8 1395.43  4804.0 1395.60
  4824.0 1392.24  4884.0 1389.44  4952.0 1387.67  4952.3 1387.17  4956.0 1387.67
  4994.0 1388.47  5068.4 1393.02  5086.5 1396.04  5104.5 1400.96  5109.7 1401.00
  5117.4 1403.00  5127.7 1403.86  5145.7 1408.90  5150.9 1408.95  5158.6 1412.70
  5179.2 1414.89  5187.0 1417.43  5192.1 1417.54  5199.9 1419.62  5210.2 1420.73
#Mann=5,-1,0
  4425.2    0.07       0  4487.1   0.035       0  4794.8    0.07       0
  4952.0    0.05       0  4956.0    0.07       0
Bank Sta=4952,4956
Exp/Cntr=0.3,0.1

Type RM Length L Ch R = 1,532,405,405,405
BEGIN DESCRIPTION:
Stream0015_DS 1.0
END DESCRIPTION:
XS GIS Cut Line= 3
      2055024.96     13858075.01      2055325.00     13858025.00
      2055524.96     13857975.01
#Sta/Elev= 30
  4700.1 1396.64  4720.4 1394.85  4728.0 1393.25  4733.1 1393.42  4761.0 1390.66
  4788.9 1386.35  4793.9 1386.71  4842.1 1381.95  4854.7 1381.91  4882.6 1378.55
  4923.2 1378.68  4948.2 1376.90  4976.4 1375.85  4982.0 1374.49  4982.3 1373.99
  4986.0 1374.49  4994.1 1377.12  5035.2 1376.30  5055.8 1377.16  5068.7 1379.12
  5096.6 1385.30  5104.8 1388.24  5109.9 1388.50  5117.7 1391.76  5146.0 1399.97
  5169.2 1401.61  5173.5 1402.71  5192.4 1406.77  5207.9 1411.44  5210.4 1411.44
#Mann=6,-1,0
  4700.1   0.035       0  4948.2    0.07       0  4982.0    0.05       0
  4986.0    0.07       0  5096.6    0.12       0  5173.5    0.07       0
Bank Sta=4982,4986
Exp/Cntr=0.3,0.1

Type RM Length L Ch R = 1,127,0,0,0
BEGIN DESCRIPTION:
Stream0015_DS 0.0
END DESCRIPTION:
XS GIS Cut Line= 5
      2055117.98     13858166.83      2055331.89     13858400.08
      2055373.88     13858414.54      2055427.29     13858388.38
      2055530.52     13858062.82
#Sta/Elev= 30
  4639.1 1386.88  4656.9 1384.47  4671.1 1385.03  4720.4 1379.82  4756.2 1378.56
  4791.3 1373.63  4812.9 1371.70  4869.0 1369.05  4897.4 1369.39  4947.3 1367.40
  4969.5 1366.16  4978.0 1363.78  4978.3 1363.28  4982.0 1363.78  4985.7 1365.43
  4992.0 1365.65  4997.9 1368.61  5003.4 1368.61  5008.6 1370.19  5073.6 1372.57
  5170.4 1373.98  5235.0 1376.49  5267.3 1380.32  5293.8 1386.67  5299.5 1389.23
  5325.3 1393.28  5331.8 1395.33  5364.1 1400.38  5388.2 1401.21  5401.0 1403.57
#Mann=4,-1,0
  4639.1   0.035       0  4978.0    0.05       0  4982.0   0.035       0
  4992.0    0.07       0
Bank Sta=4978,4982
Exp/Cntr=0.3,0.1

Chan Stop Cuts=-1