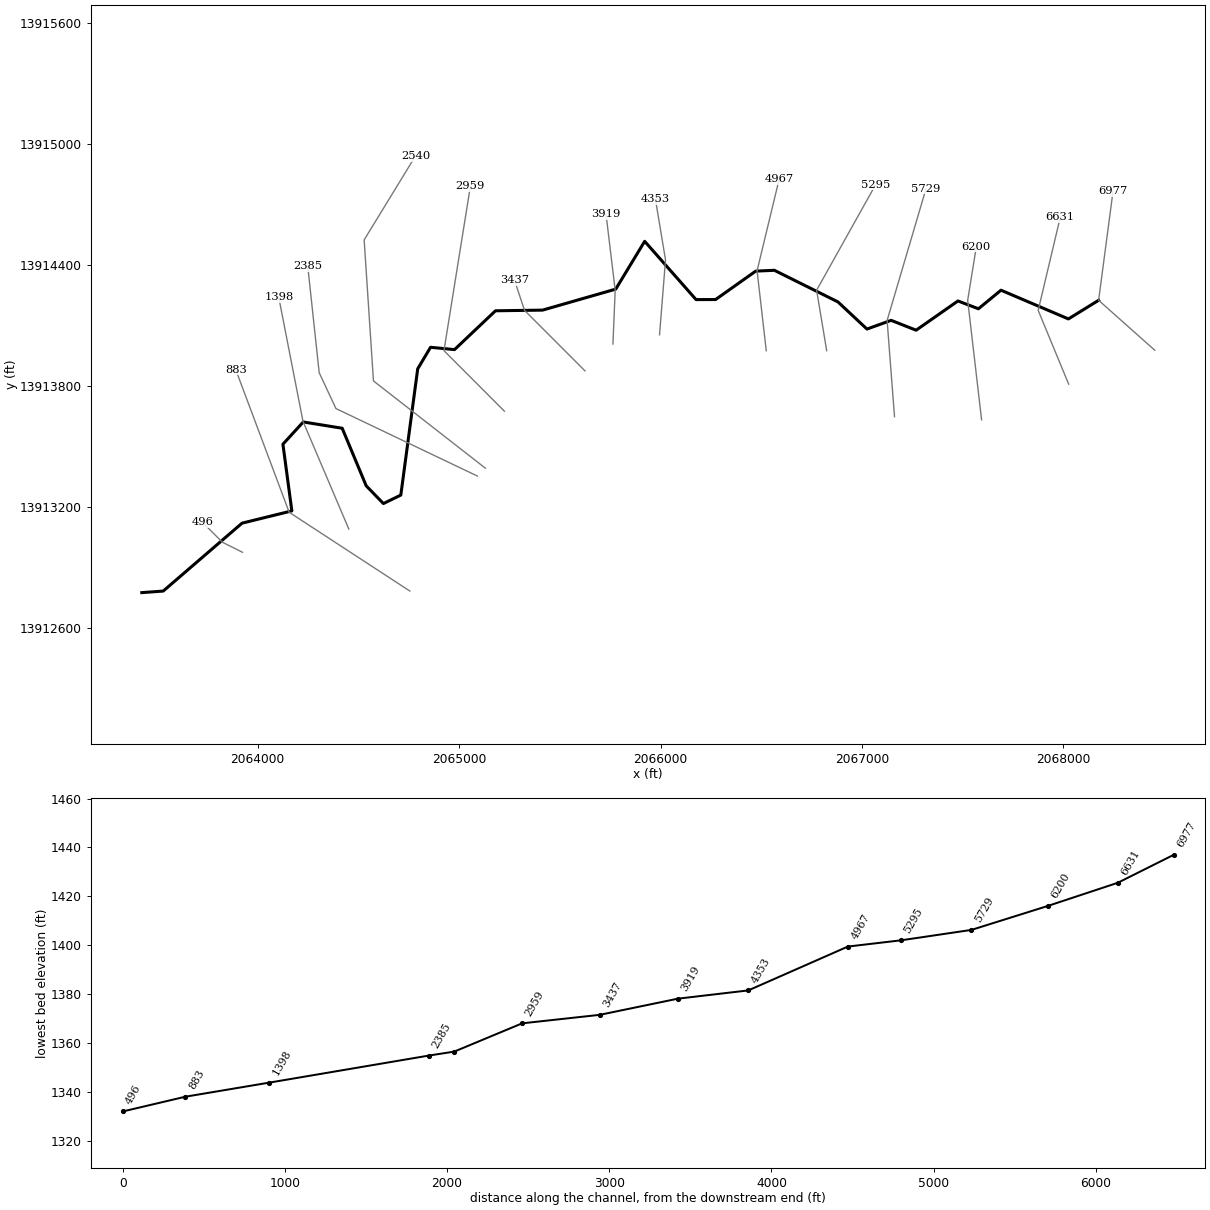
--- Stream0018_DS.prj (project) ---

Proj Title=Stream0018_DS Base Level Engineering
Current Plan=p01
Default Exp/Contr=0.3,0.1
English Units
Geom File=g01
Flow File=f01
Plan File=p01
BEGIN DESCRIPTION:
Stream0018_DS
END DESCRIPTION:

--- Stream0018_DS.p01 (plan) ---

Plan Title=Multiple Run
Short Identifier=Multiple
Geom File=g01
Flow File=f01
Subcritical Flow
K Sum by GR= 0
Std Step Tol= 0.01
Critical Tol= 0.01
Num of Std Step Trials= 20
Max Error Tol= 0.3
Flow Tol Ratio= 0.001
Split Flow NTrial= 30
Split Flow Tol= 0.02
Split Flow Ratio= 0.02
Log Output Level= 0
Friction Slope Method= 1
Unsteady Friction Slope Method= 2
Unsteady Bridges Friction Slope Method= 1
Parabolic Critical Depth
Global Vel Dist=  1 , 1 , 1
Global Log Level= 0
CheckData=True
Encroach Param= -1, 0, 0, 0
BEGIN DESCRIPTION:
Multiple Run
END DESCRIPTION:

--- Stream0018_DS.f01 (steady flow) ---

Flow Title=Multiple
Number of Profiles=7
Profile Names=10-year,25-year,50-year,1pct_min,100-year,1pct_plu,500-year
River Rch & RM= Stream0018_DS,Reach-1,6977
     429     690     928     608    1212    2419    2046
River Rch & RM= Stream0018_DS,Reach-1,6631
     790    1316    1808    1207    2408    4804    4228
Boundary for River Rch & Prof#=Stream0018_DS,Reach-1,1
Up Type=0
Dn Type=3
Dn Slope=0.005
Boundary for River Rch & Prof#=Stream0018_DS,Reach-1,2
Up Type=0
Dn Type=3
Dn Slope=0.005
Boundary for River Rch & Prof#=Stream0018_DS,Reach-1,3
Up Type=0
Dn Type=3
Dn Slope=0.005
Boundary for River Rch & Prof#=Stream0018_DS,Reach-1,4
Up Type=0
Dn Type=3
Dn Slope=0.005
Boundary for River Rch & Prof#=Stream0018_DS,Reach-1,5
Up Type=0
Dn Type=3
Dn Slope=0.005
Boundary for River Rch & Prof#=Stream0018_DS,Reach-1,6
Up Type=0
Dn Type=3
Dn Slope=0.005
Boundary for River Rch & Prof#=Stream0018_DS,Reach-1,7
Up Type=0
Dn Type=3
Dn Slope=0.005

--- Stream0018_DS.g01 (geometry) ---

Geom Title=Existing Conditions

River Reach=Stream0018_DS,Reach-1
Reach XY= 30
      2068175.00     13914225.00      2068025.01     13914132.51
      2067690.34     13914275.04      2067578.40     13914182.84
      2067476.74     13914221.63      2067268.96     13914076.63
      2067145.05     13914125.57      2067024.90     13914082.32
      2066881.06     13914216.86      2066565.30     13914373.76
      2066472.58     13914369.59      2066273.41     13914228.67
      2066176.48     13914228.45      2065921.42     13914517.52
      2065777.70     13914280.36      2065414.50     13914176.22
      2065180.85     13914172.94      2064977.43     13913980.40
      2064858.43     13913991.87      2064794.67     13913885.05
      2064710.78     13913258.77      2064624.27     13913216.77
      2064538.92     13913304.82      2064419.75     13913590.37
      2064226.46     13913621.46      2064125.52     13913511.14
      2064169.84     13913180.41      2063922.56     13913119.52
      2063531.22     13912782.74      2063425.00     13912775.00

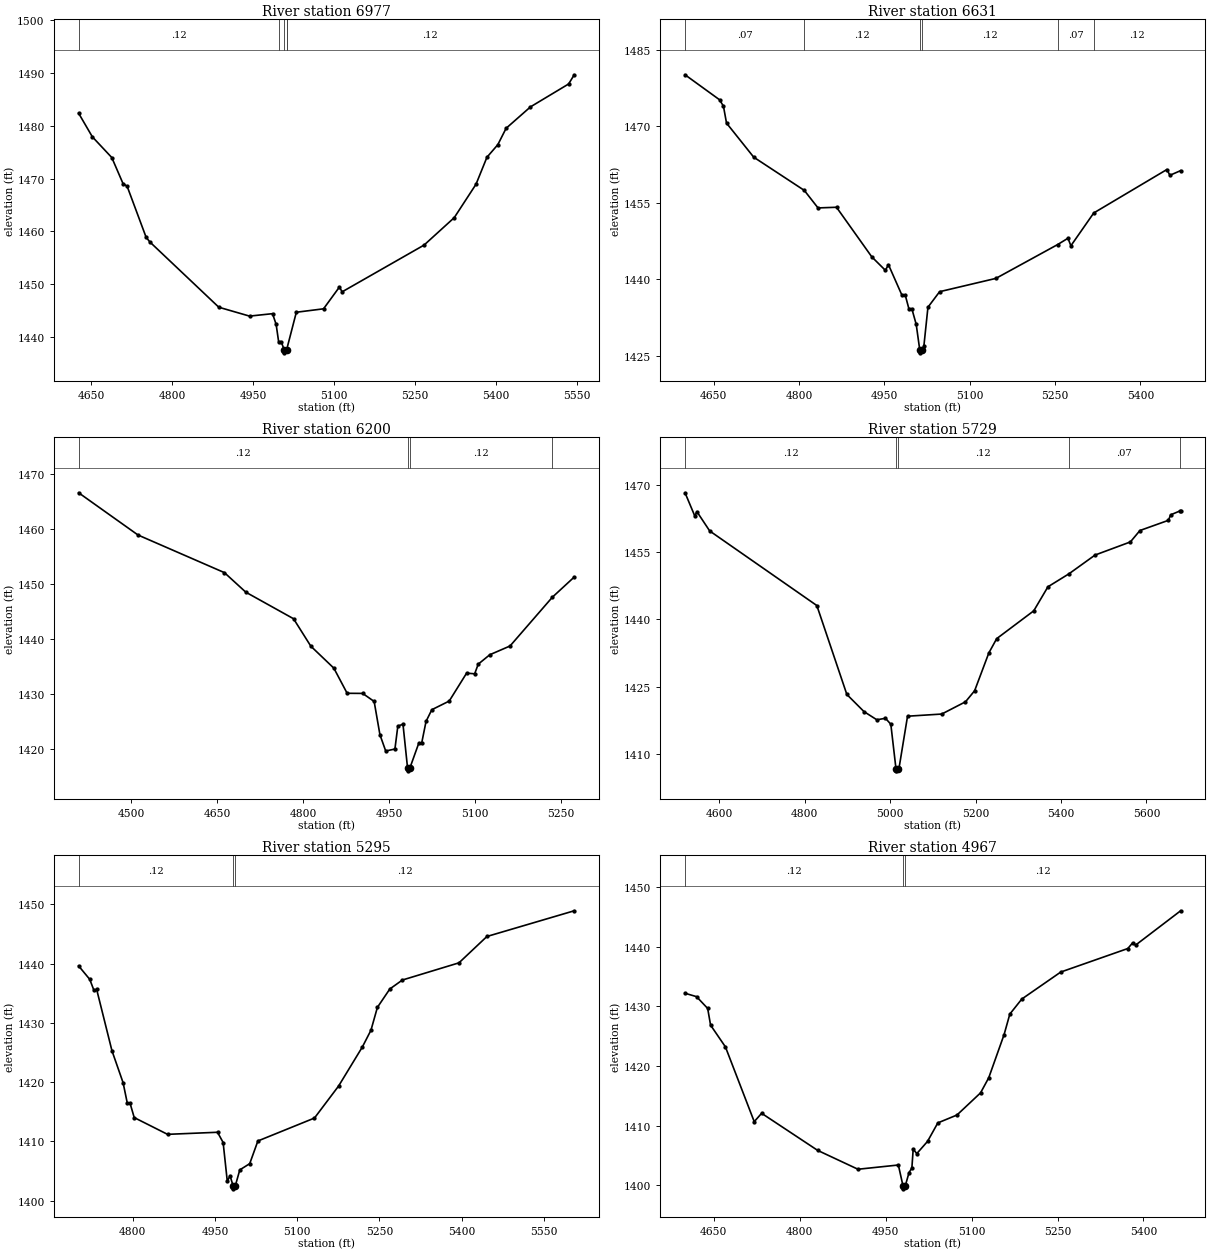
Type RM Length L Ch R = 1,6977,346,346,346
BEGIN DESCRIPTION:
Stream0018_DS 14.0
END DESCRIPTION:
XS GIS Cut Line= 3
      2068453.76     13913977.32      2068175.00     13914225.00
      2068246.55     13914765.28
#Sta/Elev= 30
  4627.1 1482.35  4652.5 1477.89  4688.5 1473.97  4709.4 1469.02  4716.9 1468.54
  4752.1 1458.88  4759.2 1457.98  4886.7 1445.65  4943.6 1443.97  4986.2 1444.43
  4992.9 1442.41  4997.6 1439.06  5002.5 1439.06  5008.1 1437.52  5008.3 1437.02
  5012.1 1437.52  5012.2 1437.55  5030.3 1444.70  5080.7 1445.35  5110.1 1449.47
  5115.1 1448.56  5266.9 1457.41  5322.8 1462.60  5363.1 1468.92  5383.3 1474.02
  5403.5 1476.41  5418.8 1479.50  5464.0 1483.56  5534.6 1487.89  5545.0 1489.63
#Mann=5,-1,0
  4627.1    0.12       0  4997.6    0.07       0  5008.1    0.05       0
  5012.1    0.07       0  5012.2    0.12       0
Bank Sta=5008.1,5012.1
Exp/Cntr=0.3,0.1

Type RM Length L Ch R = 1,6631,431,431,431
BEGIN DESCRIPTION:
Stream0018_DS 13.0
END DESCRIPTION:
XS GIS Cut Line= 3
      2068026.34     13913809.00      2067875.00     13914175.00
      2067984.69     13914637.10
#Sta/Elev= 30
  4599.7 1480.10  4660.3 1475.20  4667.2 1473.94  4672.6 1470.62  4720.4 1463.93
  4809.3 1457.41  4833.4 1453.97  4865.9 1454.10  4927.9 1444.37  4951.8 1441.72
  4957.2 1442.83  4981.1 1436.79  4986.5 1436.95  4993.1 1434.19  4998.3 1434.19
  5006.0 1431.11  5012.3 1426.03  5012.5 1425.53  5016.3 1426.03  5019.4 1426.80
  5026.6 1434.48  5047.1 1437.53  5146.0 1440.14  5254.4 1446.77  5272.7 1448.02
  5277.8 1446.54  5318.0 1452.98  5446.6 1461.51  5451.8 1460.37  5470.7 1461.29
#Mann=6,-1,0
  4599.7    0.07       0  4809.3    0.12       0  5012.3    0.05       0
  5016.3    0.12       0  5254.4    0.07       0  5318.0    0.12       0
Bank Sta=5012.3,5016.3
Exp/Cntr=0.3,0.1

Type RM Length L Ch R = 1,6200,471,471,471
BEGIN DESCRIPTION:
Stream0018_DS 12.0
END DESCRIPTION:
XS GIS Cut Line= 3
      2067594.06     13913631.92      2067525.00     13914225.00
      2067567.93     13914490.67
#Sta/Elev= 30
  4407.7 1466.55  4511.5 1458.88  4662.5 1452.05  4699.9 1448.50  4783.3 1443.68
  4813.5 1438.70  4853.8 1434.70  4877.0 1430.14  4904.1 1430.12  4924.2 1428.66
  4934.3 1422.62  4944.4 1419.66  4960.5 1420.02  4965.6 1424.19  4974.6 1424.52
  4982.6 1416.56  4982.9 1416.06  4986.6 1416.56  5002.3 1421.11  5007.3 1421.11
  5014.9 1425.04  5025.0 1427.16  5055.4 1428.73  5085.8 1433.80  5099.9 1433.68
  5106.1 1435.43  5126.3 1437.14  5161.7 1438.73  5235.7 1447.59  5273.9 1451.25
#Mann=4,-1,0
  4407.7    0.12       0  4982.6    0.05       0  4986.6    0.12       0
  5235.7    0.07       0
Bank Sta=4982.6,4986.6
Exp/Cntr=0.3,0.1

Type RM Length L Ch R = 1,5729,434,434,434
BEGIN DESCRIPTION:
Stream0018_DS 11.0
END DESCRIPTION:
XS GIS Cut Line= 3
      2067161.77     13913647.51      2067125.00     13914125.00
      2067318.03     13914777.75
#Sta/Elev= 30
  4520.3 1468.24  4543.1 1463.07  4548.1 1464.03  4578.0 1459.73  4828.7 1443.10
  4898.9 1423.28  4939.1 1419.45  4969.1 1417.63  4989.2 1417.97  5001.8 1416.64
  5013.8 1406.75  5014.1 1406.25  5017.8 1406.75  5021.1 1406.91  5040.9 1418.43
  5120.9 1418.91  5176.5 1421.64  5197.9 1424.11  5231.1 1432.53  5249.5 1435.72
  5336.2 1441.92  5369.4 1447.28  5418.7 1450.18  5479.7 1454.36  5562.3 1457.28
  5584.7 1459.83  5651.3 1462.10  5656.5 1463.32  5678.0 1464.18  5679.9 1464.18
#Mann=5,-1,0
  4520.3    0.12       0  5013.8    0.05       0  5017.8    0.12       0
  5418.7    0.07       0  5678.0    0.12       0
Bank Sta=5013.8,5017.8
Exp/Cntr=0.3,0.1

Type RM Length L Ch R = 1,5295,328,328,328
BEGIN DESCRIPTION:
Stream0018_DS 10.0
END DESCRIPTION:
XS GIS Cut Line= 3
      2066825.00     13913975.01      2066775.00     13914275.00
      2067068.02     13914798.55
#Sta/Elev= 30
  4701.4 1439.62  4721.7 1437.35  4729.3 1435.50  4734.3 1435.65  4762.2 1425.30
  4782.5 1419.91  4790.1 1416.49  4795.2 1416.44  4802.8 1414.02  4863.6 1411.19
  4954.8 1411.54  4965.0 1409.81  4972.6 1403.25  4977.6 1404.21  4983.2 1402.49
  4983.5 1401.99  4987.2 1402.49  4995.4 1405.19  5013.5 1406.24  5028.4 1410.07
  5131.6 1413.94  5175.6 1419.34  5219.0 1425.94  5234.7 1428.77  5246.4 1432.62
  5269.1 1435.73  5292.0 1437.24  5395.2 1440.14  5446.2 1444.59  5605.5 1448.93
#Mann=3,-1,0
  4701.4    0.12       0  4983.2    0.05       0  4987.2    0.12       0
Bank Sta=4983.2,4987.2
Exp/Cntr=0.3,0.1

Type RM Length L Ch R = 1,4967,614,614,614
BEGIN DESCRIPTION:
Stream0018_DS 9.0
END DESCRIPTION:
XS GIS Cut Line= 3
      2066525.00     13913975.00      2066479.48     13914371.46
      2066588.85     13914824.59
#Sta/Elev= 30
  4599.7 1432.18  4619.8 1431.61  4639.2 1429.64  4644.3 1426.84  4670.2 1423.20
  4720.5 1410.68  4733.4 1412.08  4831.2 1405.87  4901.6 1402.71  4972.1 1403.42
  4980.2 1399.93  4980.4 1399.43  4984.2 1399.93  4990.7 1402.14  4995.7 1402.91
  4998.0 1406.08  5004.3 1405.33  5023.0 1407.37  5041.0 1410.47  5074.4 1411.79
  5115.6 1415.50  5129.9 1418.03  5156.7 1425.26  5166.7 1428.69  5187.6 1431.21
  5255.6 1435.73  5372.7 1439.67  5381.2 1440.63  5386.4 1440.25  5464.9 1445.99
#Mann=3,-1,0
  4599.7    0.12       0  4980.2    0.05       0  4984.2    0.12       0
Bank Sta=4980.2,4984.2
Exp/Cntr=0.3,0.1

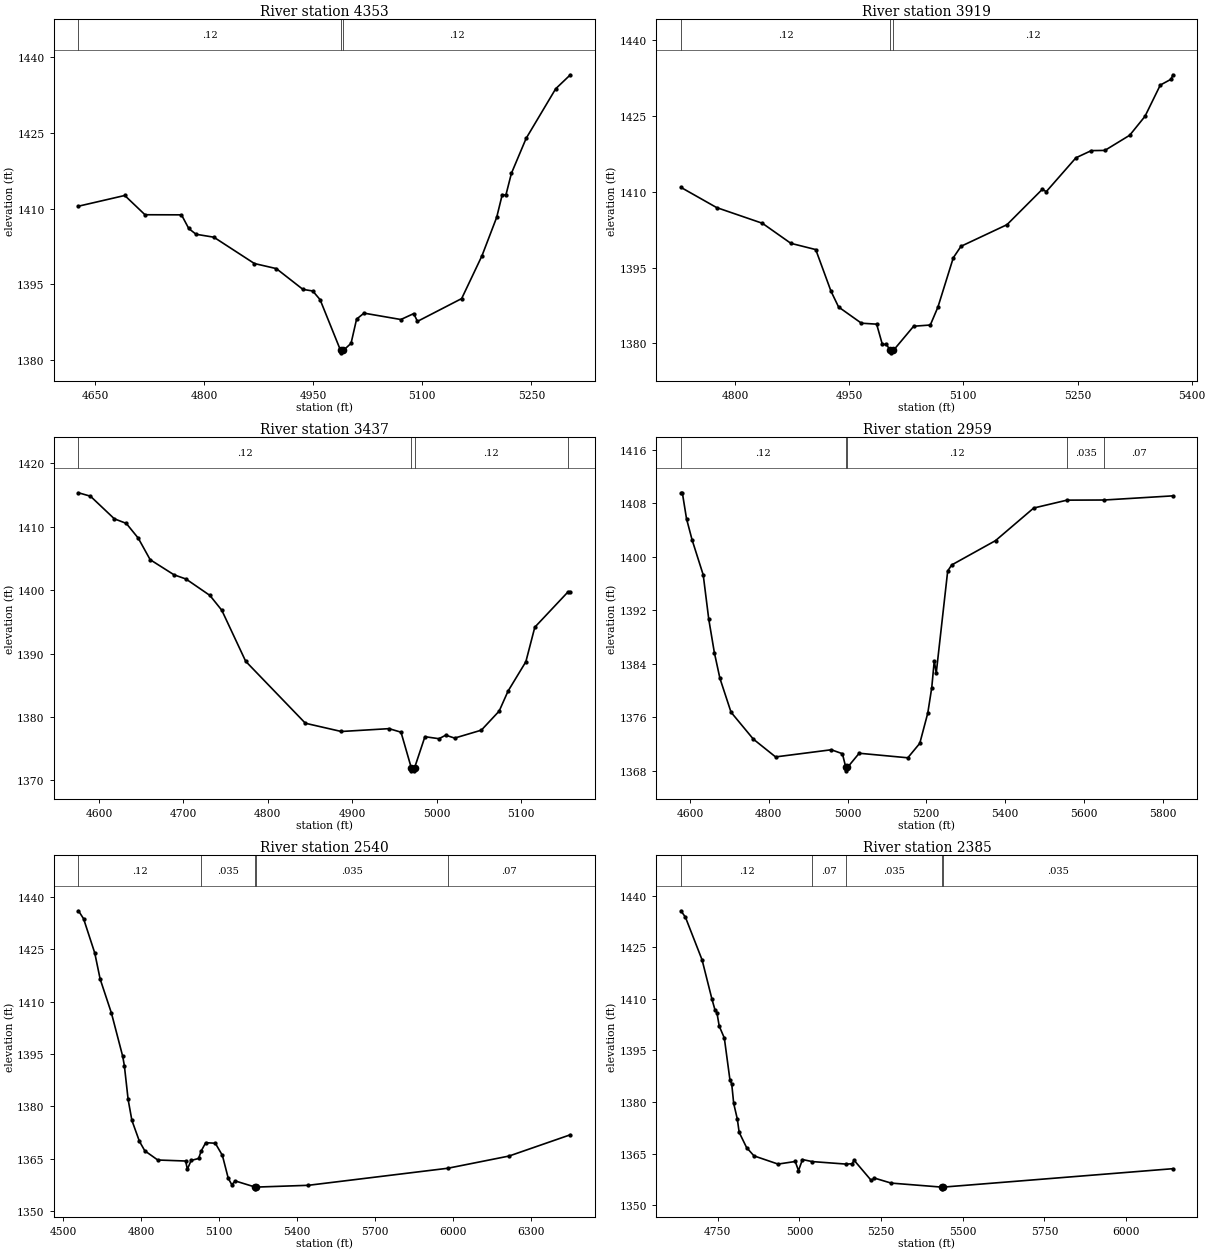
Type RM Length L Ch R = 1,4353,434,434,434
BEGIN DESCRIPTION:
Stream0018_DS 8.0
END DESCRIPTION:
XS GIS Cut Line= 3
      2065995.11     13914053.80      2066025.00     13914425.00
      2065975.01     13914724.96
#Sta/Elev= 30
  4627.2 1410.48  4690.9 1412.60  4718.7 1408.79  4768.9 1408.77  4778.9 1406.07
  4788.9 1404.93  4813.4 1404.35  4869.2 1399.14  4899.3 1398.14  4935.9 1394.03
  4949.4 1393.71  4959.5 1392.00  4987.6 1381.98  4987.8 1381.48  4991.6 1381.98
  5002.1 1383.36  5009.7 1388.15  5019.9 1389.33  5070.6 1388.07  5088.3 1389.24
  5093.4 1387.70  5154.2 1392.21  5182.1 1400.66  5202.4 1408.29  5210.0 1412.76
  5215.0 1412.66  5222.6 1416.97  5242.9 1423.90  5283.5 1433.70  5303.7 1436.47
#Mann=3,-1,0
  4627.2    0.12       0  4987.6    0.05       0  4991.6    0.12       0
Bank Sta=4987.6,4991.6
Exp/Cntr=0.3,0.1

Type RM Length L Ch R = 1,3919,482,482,482
BEGIN DESCRIPTION:
Stream0018_DS 7.0
END DESCRIPTION:
XS GIS Cut Line= 3
      2065763.90     13914008.10      2065775.00     13914275.00
      2065729.64     13914651.34
#Sta/Elev= 30
  4729.0 1410.87  4775.9 1406.87  4836.0 1403.76  4873.4 1399.79  4906.1 1398.55
  4926.1 1390.32  4936.1 1387.18  4966.1 1383.97  4986.1 1383.78  4993.6 1379.77
  4998.7 1379.77  5004.2 1378.60  5004.5 1378.10  5008.2 1378.60  5034.7 1383.37
  5056.6 1383.61  5066.6 1387.16  5086.8 1396.93  5096.9 1399.20  5157.3 1403.48
  5203.8 1410.50  5208.9 1410.02  5247.9 1416.73  5268.1 1418.15  5285.9 1418.19
  5318.5 1421.19  5338.6 1424.94  5358.7 1431.13  5373.0 1432.30  5375.2 1433.17
#Mann=3,-1,0
  4729.0    0.12       0  5004.2    0.05       0  5008.2    0.12       0
Bank Sta=5004.2,5008.2
Exp/Cntr=0.3,0.1

Type RM Length L Ch R = 1,3437,478,478,478
BEGIN DESCRIPTION:
Stream0018_DS 6.0
END DESCRIPTION:
XS GIS Cut Line= 3
      2065625.03     13913874.97      2065325.00     13914175.00
      2065275.01     13914324.98
#Sta/Elev= 30
  4575.8 1415.37  4590.0 1414.83  4618.3 1411.26  4632.4 1410.54  4646.6 1408.21
  4660.7 1404.81  4689.0 1402.42  4703.1 1401.76  4731.4 1399.17  4745.5 1396.83
  4773.8 1388.77  4844.5 1378.99  4887.0 1377.69  4943.5 1378.14  4957.7 1377.58
  4969.8 1371.98  4970.1 1371.48  4973.6 1371.48  4973.8 1371.98  4986.0 1376.87
  5002.7 1376.55  5010.6 1377.11  5021.2 1376.65  5052.8 1377.90  5073.9 1380.91
  5084.4 1384.06  5105.5 1388.70  5116.1 1394.15  5155.6 1399.75  5158.2 1399.75
#Mann=4,-1,0
  4575.8    0.12       0  4969.8    0.05       0  4973.8    0.12       0
  5155.6    0.07       0
Bank Sta=4969.8,4973.8
Exp/Cntr=0.3,0.1

Type RM Length L Ch R = 1,2959,419,419,419
BEGIN DESCRIPTION:
Stream0018_DS 5.0
END DESCRIPTION:
XS GIS Cut Line= 3
      2065225.02     13913674.98      2064925.00     13913975.00
      2065056.02     13914789.54
#Sta/Elev= 30
  4576.9 1409.57  4580.5 1409.57  4591.1 1405.69  4605.2 1402.54  4633.5 1397.30
  4647.6 1390.67  4661.8 1385.68  4675.9 1381.84  4704.2 1376.77  4760.8 1372.75
  4817.3 1370.09  4958.8 1371.16  4987.0 1370.57  4995.7 1368.51  4995.9 1368.01
  4999.7 1368.51  5029.6 1370.64  5153.1 1369.96  5183.5 1372.12  5203.8 1376.64
  5213.9 1380.44  5220.3 1384.46  5225.3 1382.63  5254.4 1397.88  5264.5 1398.78
  5375.9 1402.42  5472.8 1407.29  5557.5 1408.47  5652.3 1408.49  5826.2 1409.11
#Mann=5,-1,0
  4576.9    0.12       0  4995.7    0.05       0  4999.7    0.12       0
  5557.5   0.035       0  5652.3    0.07       0
Bank Sta=4995.7,4999.7
Exp/Cntr=0.3,0.1

Type RM Length L Ch R = 1,2540,155,155,155
BEGIN DESCRIPTION:
Stream0018_DS 4.0
END DESCRIPTION:
XS GIS Cut Line= 4
      2065130.54     13913392.29      2064575.00     13913825.00
      2064528.76     13914524.53      2064783.62     13914940.77
#Sta/Elev= 30
  4558.9 1435.98  4578.6 1433.71  4621.6 1423.92  4642.4 1416.45  4685.9 1406.70
  4729.3 1394.32  4735.6 1391.67  4750.1 1381.99  4764.6 1376.01  4793.5 1370.04
  4814.3 1367.31  4864.1 1364.68  4971.5 1364.39  4978.1 1362.02  4992.6 1364.55
  5021.5 1365.12  5031.2 1367.24  5048.7 1369.63  5085.6 1369.48  5112.9 1366.00
  5135.5 1359.43  5149.0 1357.63  5162.7 1358.68  5239.4 1356.93  5239.6 1356.43
  5243.4 1356.93  5443.5 1357.44  5980.6 1362.32  6216.1 1365.81  6452.2 1371.90
#Mann=5,-1,0
  4558.9    0.12       0  5031.2   0.035       0  5239.4    0.05       0
  5243.4   0.035       0  5980.6    0.07       0
Bank Sta=5239.4,5243.4
Exp/Cntr=0.3,0.1

Type RM Length L Ch R = 1,2385,987,987,987
BEGIN DESCRIPTION:
Stream0018_DS 3.5
END DESCRIPTION:
XS GIS Cut Line= 4
      2065090.79     13913353.30      2064388.73     13913687.98
      2064305.59     13913865.83      2064248.76     13914394.11
#Sta/Elev= 30
  4637.5 1435.57  4651.3 1433.70  4702.2 1421.32  4732.5 1409.89  4742.0 1406.70
  4747.6 1406.02  4754.7 1402.08  4770.3 1398.63  4787.4 1386.53  4793.0 1385.24
  4799.0 1379.62  4810.1 1375.09  4815.7 1371.24  4838.4 1366.82  4861.1 1364.40
  4934.7 1362.02  4987.3 1362.77  4997.3 1360.12  5009.5 1363.34  5038.8 1362.75
  5143.6 1362.01  5161.7 1362.12  5167.2 1363.16  5220.0 1357.26  5229.8 1357.95
  5280.7 1356.50  5435.7 1355.33  5436.0 1354.83  5439.7 1355.33  6142.9 1360.68
#Mann=5,-1,0
  4637.5    0.12       0  5038.8    0.07       0  5143.6   0.035       0
  5435.7    0.05       0  5439.7   0.035       0
Bank Sta=5435.7,5439.7
Exp/Cntr=0.3,0.1

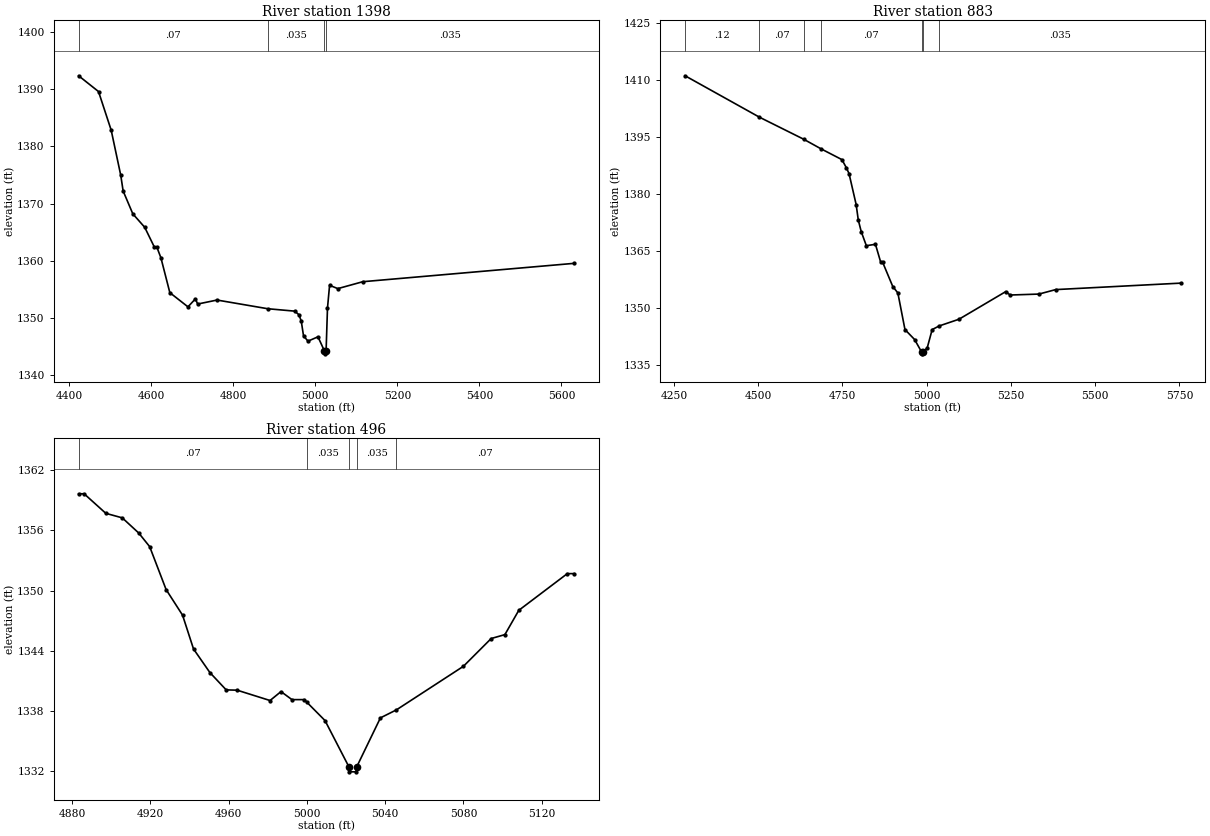
Type RM Length L Ch R = 1,1398,515,515,515
BEGIN DESCRIPTION:
Stream0018_DS 3.0
END DESCRIPTION:
XS GIS Cut Line= 3
      2064452.61     13913090.40      2064225.00     13913625.00
      2064104.61     13914240.60
#Sta/Elev= 30
  4422.8 1392.36  4471.3 1389.60  4502.2 1382.84  4525.6 1374.92  4531.3 1372.21
  4554.9 1368.21  4584.0 1365.85  4607.6 1362.37  4613.1 1362.46  4623.4 1360.53
  4645.2 1354.42  4689.4 1351.94  4707.6 1353.34  4713.0 1352.43  4760.3 1353.13
  4884.0 1351.61  4949.5 1351.19  4960.2 1350.55  4965.7 1349.42  4971.2 1346.85
  4982.1 1345.94  5006.4 1346.70  5022.2 1344.22  5022.5 1343.72  5026.2 1344.22
  5029.6 1351.73  5034.7 1355.71  5054.8 1355.13  5115.9 1356.34  5631.1 1359.55
#Mann=4,-1,0
  4422.8    0.07       0  4884.0   0.035       0  5022.2   0.035       0
  5026.2   0.035       0
Bank Sta=5022.2,5026.2
Exp/Cntr=0.3,0.1

Type RM Length L Ch R = 1,883,387,387,387
BEGIN DESCRIPTION:
Stream0018_DS 2.0
END DESCRIPTION:
XS GIS Cut Line= 3
      2064755.52     13912782.92      2064156.56     13913173.55
      2063891.28     13913880.97
#Sta/Elev= 30
  4282.9 1411.21  4503.4 1400.31  4634.6 1394.51  4686.3 1391.97  4748.3 1389.13
  4761.1 1387.05  4769.4 1385.46  4790.5 1377.31  4796.9 1373.21  4805.6 1370.16
  4820.8 1366.46  4847.8 1366.83  4862.9 1362.26  4868.9 1362.15  4899.2 1355.71
  4914.3 1354.02  4935.4 1344.37  4964.0 1341.75  4984.7 1338.48  4985.0 1337.98
  4988.7 1338.48  5001.4 1339.53  5016.1 1344.37  5037.4 1345.34  5095.6 1347.09
  5234.5 1354.37  5247.5 1353.47  5332.9 1353.72  5382.8 1354.90  5753.5 1356.60
#Mann=7,-1,0
  4282.9    0.12       0  4503.4    0.07       0  4634.6    0.12       0
  4686.3    0.07       0  4984.7    0.05       0  4988.7    0.07       0
  5037.4   0.035       0
Bank Sta=4984.7,4988.7
Exp/Cntr=0.3,0.1

Type RM Length L Ch R = 1,496,0,0,0
BEGIN DESCRIPTION:
Stream0018_DS 1.0
END DESCRIPTION:
XS GIS Cut Line= 3
      2063924.98     13912975.01      2063825.00     13913025.00
      2063725.00     13913125.00
#Sta/Elev= 30
  4883.4 1359.65  4886.2 1359.65  4897.3 1357.70  4905.7 1357.25  4914.1 1355.74
  4919.7 1354.38  4928.1 1350.10  4936.5 1347.55  4942.1 1344.18  4950.5 1341.82
  4958.8 1340.10  4964.4 1340.07  4981.2 1339.04  4986.8 1339.93  4992.4 1339.13
  4998.7 1339.13  4999.9 1338.89  5009.3 1337.04  5021.5 1332.43  5021.7 1331.93
  5025.2 1331.93  5025.5 1332.43  5037.6 1337.31  5045.8 1338.11  5080.0 1342.45
  5094.2 1345.22  5101.2 1345.61  5108.3 1348.03  5133.1 1351.69  5136.6 1351.69
#Mann=5,-1,0
  4883.4    0.07       0  4999.9   0.035       0  5021.5   0.035       0
  5025.5   0.035       0  5045.8    0.07       0
Bank Sta=5021.5,5025.5
Exp/Cntr=0.3,0.1

Chan Stop Cuts=-1