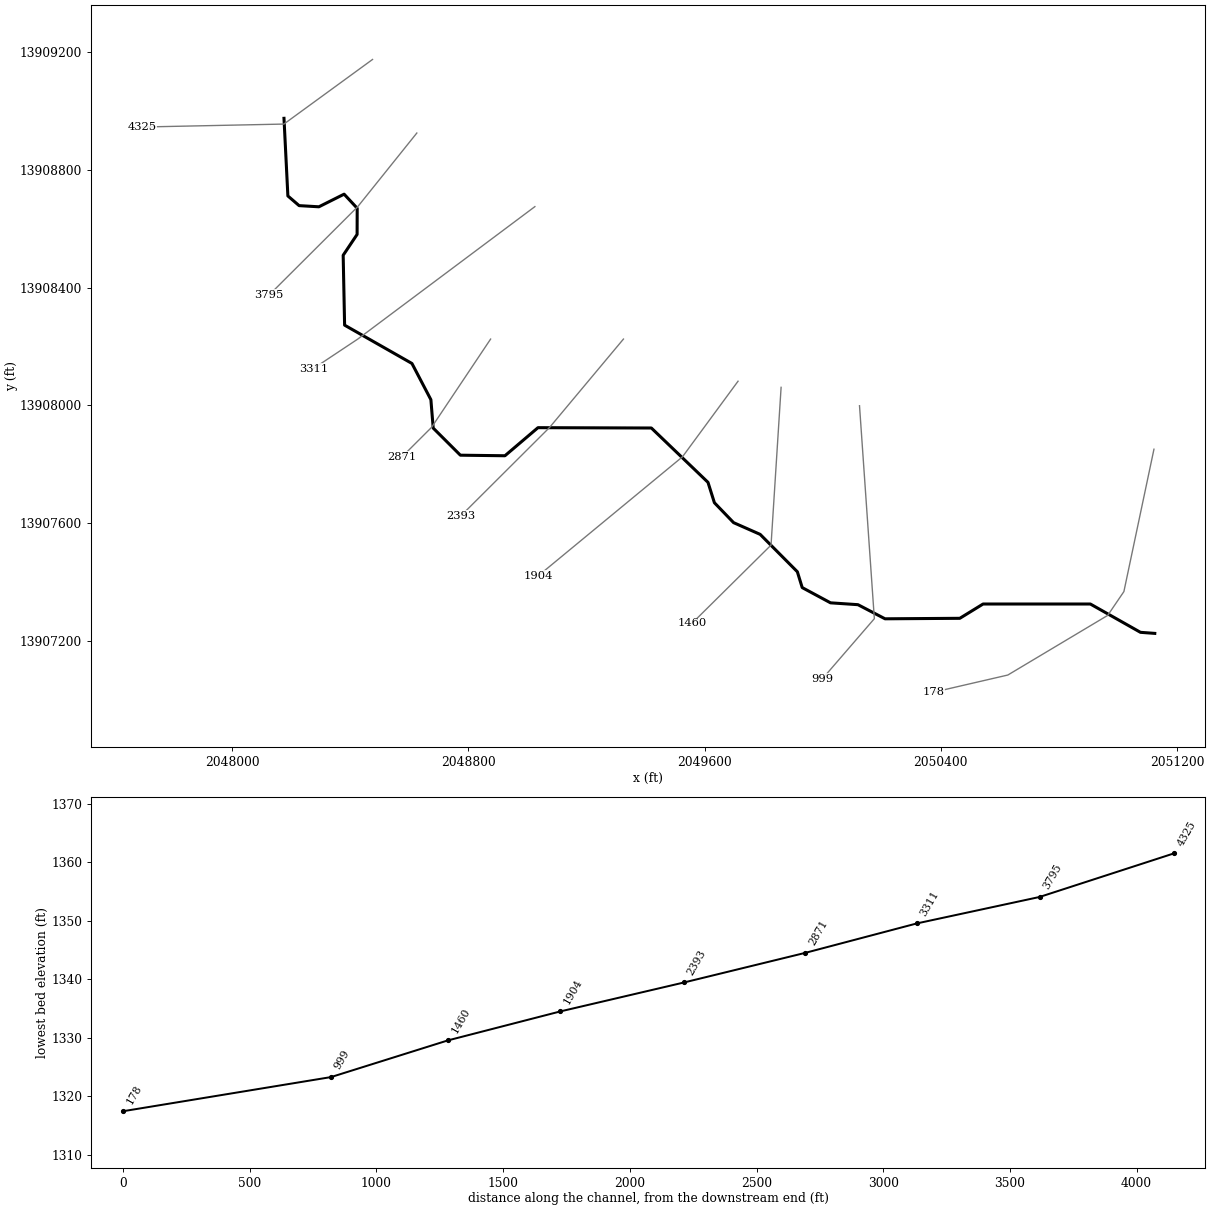
--- Stream0019_DS.prj (project) ---

Proj Title=Stream0019_DS Base Level Engineering
Current Plan=p01
Default Exp/Contr=0.3,0.1
English Units
Geom File=g01
Flow File=f01
Plan File=p01
BEGIN DESCRIPTION:
Stream0019_DS
END DESCRIPTION:

--- Stream0019_DS.p01 (plan) ---

Plan Title=Multiple Run
Short Identifier=Multiple
Geom File=g01
Flow File=f01
Subcritical Flow
K Sum by GR= 0
Std Step Tol= 0.01
Critical Tol= 0.01
Num of Std Step Trials= 20
Max Error Tol= 0.3
Flow Tol Ratio= 0.001
Split Flow NTrial= 30
Split Flow Tol= 0.02
Split Flow Ratio= 0.02
Log Output Level= 0
Friction Slope Method= 1
Unsteady Friction Slope Method= 2
Unsteady Bridges Friction Slope Method= 1
Parabolic Critical Depth
Global Vel Dist=  1 , 1 , 1
Global Log Level= 0
CheckData=True
Encroach Param= -1, 0, 0, 0
BEGIN DESCRIPTION:
Multiple Run
END DESCRIPTION:

--- Stream0019_DS.f01 (steady flow) ---

Flow Title=Multiple
Number of Profiles=7
Profile Names=10-year,25-year,50-year,1pct_min,100-year,1pct_plu,500-year
River Rch & RM= Stream0019_DS,Reach-1,4325
     811    1356    1869    1252    2498    4983    4414
River Rch & RM= Stream0019_DS,Reach-1,3795
    1122    1896    2630    1768    3528    7039    6277
Boundary for River Rch & Prof#=Stream0019_DS,Reach-1,1
Up Type=0
Dn Type=3
Dn Slope=0.005
Boundary for River Rch & Prof#=Stream0019_DS,Reach-1,2
Up Type=0
Dn Type=3
Dn Slope=0.005
Boundary for River Rch & Prof#=Stream0019_DS,Reach-1,3
Up Type=0
Dn Type=3
Dn Slope=0.005
Boundary for River Rch & Prof#=Stream0019_DS,Reach-1,4
Up Type=0
Dn Type=3
Dn Slope=0.005
Boundary for River Rch & Prof#=Stream0019_DS,Reach-1,5
Up Type=0
Dn Type=3
Dn Slope=0.005
Boundary for River Rch & Prof#=Stream0019_DS,Reach-1,6
Up Type=0
Dn Type=3
Dn Slope=0.005
Boundary for River Rch & Prof#=Stream0019_DS,Reach-1,7
Up Type=0
Dn Type=3
Dn Slope=0.005

--- Stream0019_DS.g01 (geometry) ---

Geom Title=Existing Conditions

River Reach=Stream0019_DS,Reach-1
Reach XY= 30
      2048175.00     13908975.00      2048188.20     13908711.25
      2048226.25     13908678.36      2048293.25     13908674.41
      2048378.71     13908717.32      2048423.04     13908669.51
      2048422.72     13908580.58      2048375.52     13908509.78
      2048380.36     13908272.30      2048608.52     13908142.06
      2048672.67     13908019.03      2048680.52     13907922.56
      2048772.54     13907830.45      2048923.53     13907828.54
      2049035.44     13907923.94      2049419.56     13907922.83
      2049611.37     13907738.21      2049633.15     13907668.93
      2049698.12     13907601.27      2049788.21     13907561.37
      2049914.11     13907434.42      2049930.61     13907380.59
      2050026.56     13907328.81      2050119.43     13907322.53
      2050211.18     13907274.56      2050464.50     13907276.22
      2050543.27     13907324.79      2050906.74     13907324.80
      2051076.49     13907228.60      2051125.00     13907225.00

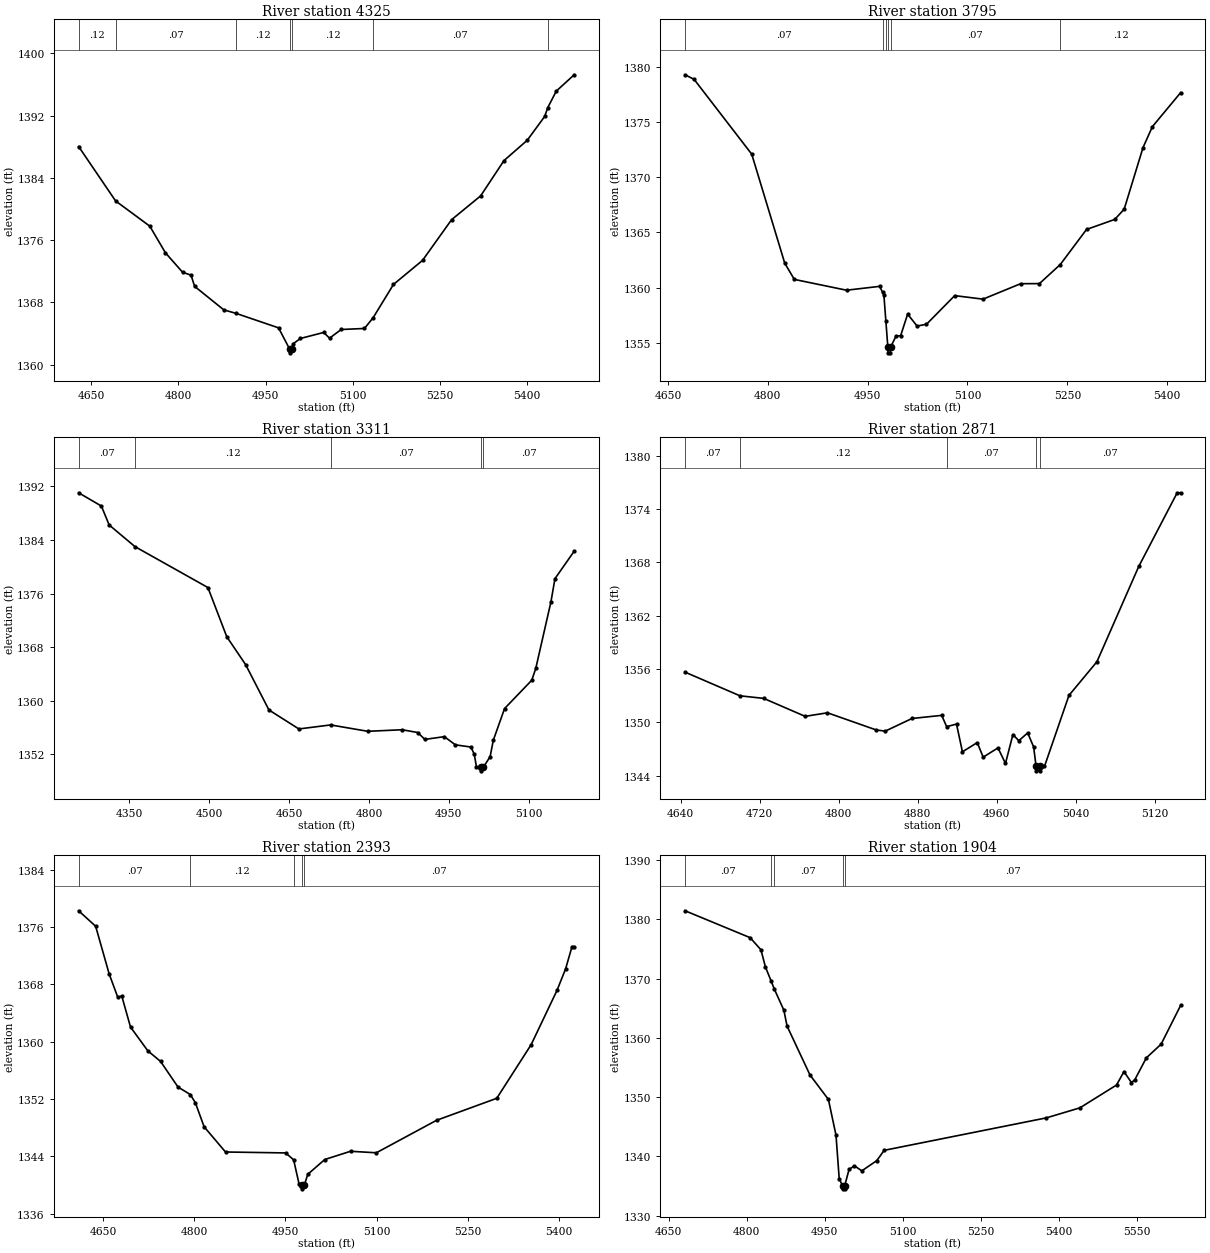
Type RM Length L Ch R = 1,4325,530,530,530
BEGIN DESCRIPTION:
Stream0019_DS 9.0
END DESCRIPTION:
XS GIS Cut Line= 3
      2048475.00     13909175.00      2048174.65     13908955.48
      2047694.18     13908945.44
#Sta/Elev= 30
  4628.4 1388.04  4692.0 1381.05  4750.8 1377.81  4777.8 1374.38  4807.2 1371.89
  4821.8 1371.51  4828.0 1370.07  4878.2 1367.05  4898.9 1366.61  4972.4 1364.74
  4991.3 1362.03  4991.5 1361.53  4995.3 1362.03  4997.1 1362.67  5010.1 1363.38
  5050.1 1364.15  5060.1 1363.41  5080.1 1364.53  5120.1 1364.66  5135.0 1366.03
  5170.1 1370.32  5220.1 1373.41  5270.1 1378.64  5320.1 1381.70  5360.2 1386.23
  5400.2 1388.84  5430.2 1391.90  5435.6 1393.04  5450.2 1395.16  5481.0 1397.26
#Mann=7,-1,0
  4628.4    0.12       0  4692.0    0.07       0  4898.9    0.12       0
  4991.3    0.05       0  4995.3    0.12       0  5135.0    0.07       0
  5435.6    0.12       0
Bank Sta=4991.3,4995.3
Exp/Cntr=0.3,0.1

Type RM Length L Ch R = 1,3795,484,484,484
BEGIN DESCRIPTION:
Stream0019_DS 8.0
END DESCRIPTION:
XS GIS Cut Line= 3
      2048625.01     13908925.02      2048425.00     13908675.00
      2048125.03     13908375.03
#Sta/Elev= 30
  4675.8 1379.30  4689.4 1378.88  4775.9 1372.10  4825.5 1362.21  4839.9 1360.74
  4918.3 1359.76  4968.0 1360.11  4972.5 1359.57  4974.4 1359.34  4977.4 1356.96
  4980.4 1354.58  4980.6 1354.08  4984.1 1354.08  4984.4 1354.58  4992.8 1355.62
  4999.5 1355.62  5010.1 1357.59  5024.3 1356.51  5038.4 1356.67  5080.8 1359.27
  5123.3 1358.95  5179.8 1360.35  5208.1 1360.36  5239.4 1362.09  5278.8 1365.27
  5321.2 1366.18  5335.4 1367.11  5363.7 1372.70  5377.8 1374.60  5420.2 1377.68
#Mann=6,-1,0
  4675.8    0.07       0  4972.5    0.12       0  4977.4    0.07       0
  4980.4    0.05       0  4984.4    0.07       0  5239.4    0.12       0
Bank Sta=4980.4,4984.4
Exp/Cntr=0.3,0.1

Type RM Length L Ch R = 1,3311,440,440,440
BEGIN DESCRIPTION:
Stream0019_DS 7.0
END DESCRIPTION:
XS GIS Cut Line= 3
      2049025.00     13908675.00      2048425.00     13908225.00
      2048274.98     13908124.99
#Sta/Elev= 30
  4255.0 1391.05  4297.7 1389.07  4312.3 1386.25  4360.7 1383.02  4497.7 1376.91
  4533.1 1369.57  4568.5 1365.41  4612.3 1358.64  4668.5 1355.81  4728.1 1356.41
  4797.7 1355.46  4862.3 1355.69  4891.5 1355.28  4905.0 1354.25  4941.5 1354.66
  4962.3 1353.44  4991.5 1353.11  4997.7 1352.04  5001.9 1350.13  5010.5 1350.06
  5010.8 1349.56  5014.5 1350.06  5027.5 1351.67  5033.5 1354.13  5054.6 1358.85
  5105.7 1363.08  5113.2 1364.84  5141.7 1374.78  5149.2 1378.23  5185.3 1382.33
#Mann=5,-1,0
  4255.0    0.07       0  4360.7    0.12       0  4728.1    0.07       0
  5010.5    0.05       0  5014.5    0.07       0
Bank Sta=5010.5,5014.5
Exp/Cntr=0.3,0.1

Type RM Length L Ch R = 1,2871,478,478,478
BEGIN DESCRIPTION:
Stream0019_DS 6.0
END DESCRIPTION:
XS GIS Cut Line= 3
      2048874.98     13908224.97      2048675.00     13907925.00
      2048575.02     13907825.02
#Sta/Elev= 30
  4644.4 1355.63  4700.0 1352.97  4724.0 1352.68  4766.0 1350.66  4788.6 1351.06
  4838.2 1349.12  4847.2 1349.00  4874.2 1350.42  4904.3 1350.77  4909.3 1349.50
  4919.3 1349.79  4925.3 1346.67  4940.3 1347.71  4946.3 1346.07  4961.3 1347.11
  4968.9 1345.36  4976.4 1348.61  4982.4 1347.92  4991.4 1348.80  4997.4 1347.22
  4999.9 1345.03  5000.2 1344.53  5003.7 1344.53  5003.9 1345.03  5008.4 1345.03
  5033.2 1353.02  5061.5 1356.80  5103.9 1367.53  5142.8 1375.81  5146.3 1375.81
#Mann=5,-1,0
  4644.4    0.07       0  4700.0    0.12       0  4909.3    0.07       0
  4999.9    0.05       0  5003.9    0.07       0
Bank Sta=4999.9,5003.9
Exp/Cntr=0.3,0.1

Type RM Length L Ch R = 1,2393,489,489,489
BEGIN DESCRIPTION:
Stream0019_DS 5.0
END DESCRIPTION:
XS GIS Cut Line= 3
      2049325.00     13908225.00      2049075.00     13907925.00
      2048774.98     13907624.98
#Sta/Elev= 30
  4610.0 1378.26  4638.0 1376.10  4660.1 1369.48  4674.4 1366.18  4680.9 1366.38
  4695.3 1362.04  4723.9 1358.71  4744.7 1357.25  4773.4 1353.67  4793.6 1352.63
  4802.0 1351.47  4816.3 1348.13  4851.5 1344.61  4950.4 1344.48  4963.5 1343.52
  4972.5 1340.13  4977.0 1339.97  4977.3 1339.47  4981.0 1339.97  4986.8 1341.50
  5014.7 1343.56  5057.1 1344.71  5099.5 1344.50  5198.5 1349.03  5297.5 1352.10
  5354.1 1359.59  5396.5 1367.14  5410.6 1370.13  5421.2 1373.25  5424.8 1373.25
#Mann=5,-1,0
  4610.0    0.07       0  4793.6    0.12       0  4963.5    0.07       0
  4977.0    0.05       0  4981.0    0.07       0
Bank Sta=4977,4981
Exp/Cntr=0.3,0.1

Type RM Length L Ch R = 1,1904,444,444,444
BEGIN DESCRIPTION:
Stream0019_DS 4.0
END DESCRIPTION:
XS GIS Cut Line= 3
      2049713.23     13908081.84      2049525.00     13907825.00
      2049036.14     13907420.39
#Sta/Elev= 30
  4681.6 1381.44  4806.7 1376.90  4827.5 1374.85  4836.0 1371.98  4847.3 1369.53
  4853.1 1368.24  4871.5 1364.67  4877.7 1361.98  4921.7 1353.74  4957.2 1349.60
  4971.8 1343.57  4978.0 1336.20  4984.5 1335.01  4984.7 1334.51  4988.2 1334.51
  4988.5 1335.01  4996.9 1337.78  5007.2 1338.39  5021.5 1337.55  5050.2 1339.27
  5064.5 1341.01  5376.5 1346.49  5440.9 1348.18  5511.3 1352.03  5525.6 1354.30
  5539.9 1352.45  5546.4 1352.91  5568.6 1356.61  5597.1 1358.93  5634.6 1365.47
#Mann=5,-1,0
  4681.6    0.07       0  4847.3   0.035       0  4853.1    0.07       0
  4984.5    0.05       0  4988.5    0.07       0
Bank Sta=4984.5,4988.5
Exp/Cntr=0.3,0.1

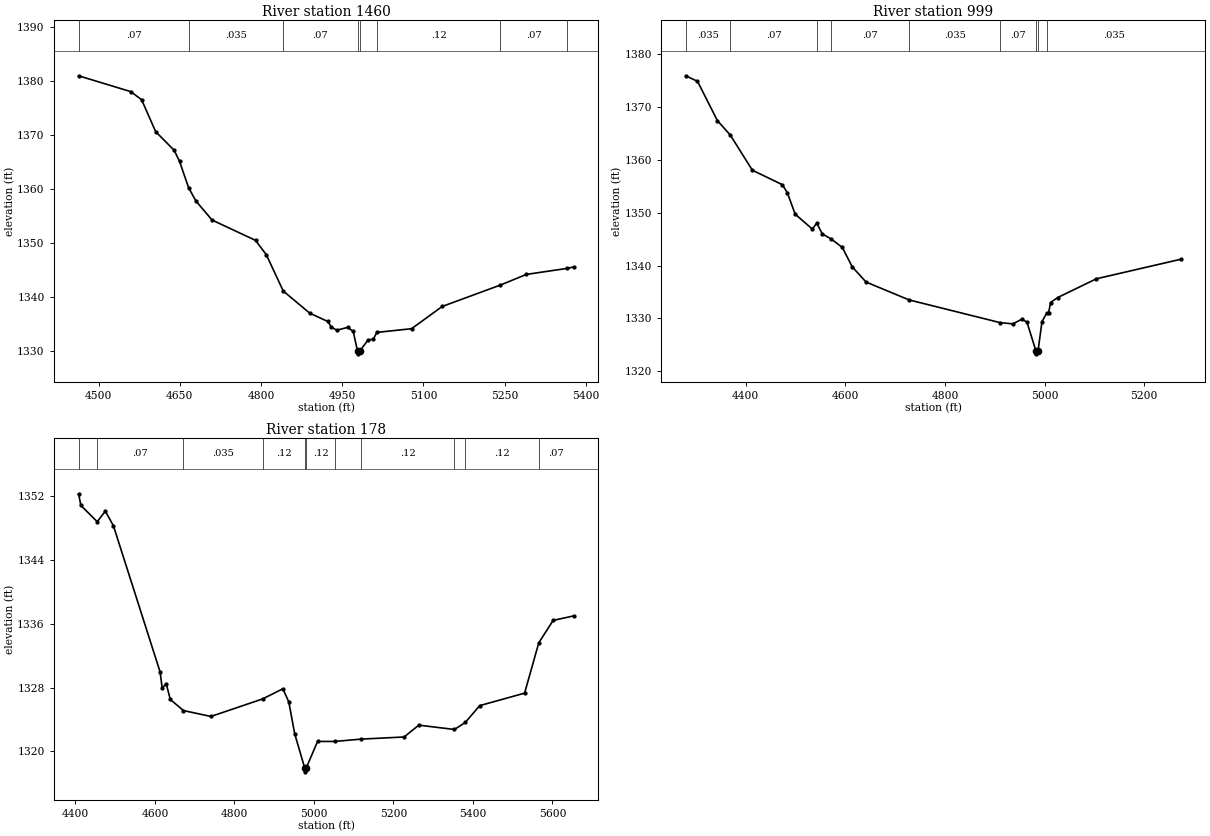
Type RM Length L Ch R = 1,1460,461,461,461
BEGIN DESCRIPTION:
Stream0019_DS 3.0
END DESCRIPTION:
XS GIS Cut Line= 3
      2049859.09     13908061.04      2049825.00     13907525.00
      2049557.53     13907259.48
#Sta/Elev= 30
  4463.2 1381.01  4559.4 1378.08  4579.5 1376.59  4605.5 1370.67  4639.6 1367.23
  4649.6 1365.18  4666.3 1360.30  4679.7 1357.86  4709.7 1354.31  4789.9 1350.55
  4809.9 1347.89  4841.1 1341.18  4890.1 1337.07  4923.4 1335.54  4930.2 1334.46
  4940.2 1333.93  4960.2 1334.45  4970.3 1333.71  4978.3 1330.05  4978.5 1329.55
  4982.3 1330.05  4997.8 1332.12  5007.4 1332.26  5014.0 1333.52  5078.1 1334.20
  5134.7 1338.32  5241.6 1342.26  5290.2 1344.25  5365.1 1345.36  5377.2 1345.62
#Mann=8,-1,0
  4463.2    0.07       0  4666.3   0.035       0  4841.1    0.07       0
  4978.3    0.05       0  4982.3    0.07       0  5014.0    0.12       0
  5241.6    0.07       0  5365.1   0.035       0
Bank Sta=4978.3,4982.3
Exp/Cntr=0.3,0.1

Type RM Length L Ch R = 1,999,821,821,821
BEGIN DESCRIPTION:
Stream0019_DS 2.0
END DESCRIPTION:
XS GIS Cut Line= 3
      2050124.72     13907998.50      2050175.00     13907275.00
      2049999.88     13907071.66
#Sta/Elev= 30
  4279.5 1375.95  4303.1 1374.90  4343.2 1367.44  4368.9 1364.73  4413.3 1358.06
  4473.5 1355.32  4483.5 1353.79  4499.2 1349.74  4533.6 1346.92  4542.6 1348.03
  4553.7 1345.98  4571.3 1345.05  4593.8 1343.44  4613.8 1339.76  4641.5 1336.88
  4727.7 1333.50  4910.6 1329.19  4936.1 1328.96  4954.6 1329.85  4964.6 1329.26
  4982.7 1323.78  4982.9 1323.28  4986.7 1323.78  4994.7 1329.38  5004.5 1331.05
  5008.0 1331.05  5011.9 1333.00  5026.1 1333.94  5104.0 1337.50  5273.1 1341.19
#Mann=9,-1,0
  4279.5   0.035       0  4368.9    0.07       0  4542.6   0.035       0
  4571.3    0.07       0  4727.7   0.035       0  4910.6    0.07       0
  4982.7    0.05       0  4986.7    0.07       0  5004.5   0.035       0
Bank Sta=4982.7,4986.7
Exp/Cntr=0.3,0.1

Type RM Length L Ch R = 1,178,0,0,0
BEGIN DESCRIPTION:
Stream0019_DS 1.0
END DESCRIPTION:
XS GIS Cut Line= 5
      2051122.21     13907850.77      2051020.37     13907367.04
      2050965.47     13907286.14      2050627.21     13907083.53
      2050375.01     13907025.00
#Sta/Elev= 30
  4407.9 1352.29  4413.6 1350.83  4454.8 1348.79  4475.1 1350.11  4495.5 1348.28
  4612.9 1329.97  4618.2 1327.94  4628.4 1328.48  4638.6 1326.51  4671.8 1325.12
  4740.8 1324.38  4871.0 1326.58  4921.8 1327.85  4936.7 1326.21  4951.7 1322.19
  4976.7 1317.94  4976.9 1317.44  4980.7 1317.94  5009.2 1321.25  5052.3 1321.25
  5118.6 1321.54  5226.9 1321.81  5263.9 1323.29  5353.6 1322.75  5380.8 1323.63
  5417.1 1325.74  5530.0 1327.30  5565.8 1333.62  5601.9 1336.42  5653.2 1336.98
#Mann=11,-1,0
  4407.9   0.035       0  4454.8    0.07       0  4671.8   0.035       0
  4871.0    0.12       0  4976.7    0.05       0  4980.7    0.12       0
  5052.3    0.07       0  5118.6    0.12       0  5353.6    0.07       0
  5380.8    0.12       0  5565.8    0.07       0
Bank Sta=4976.7,4980.7
Exp/Cntr=0.3,0.1

Chan Stop Cuts=-1