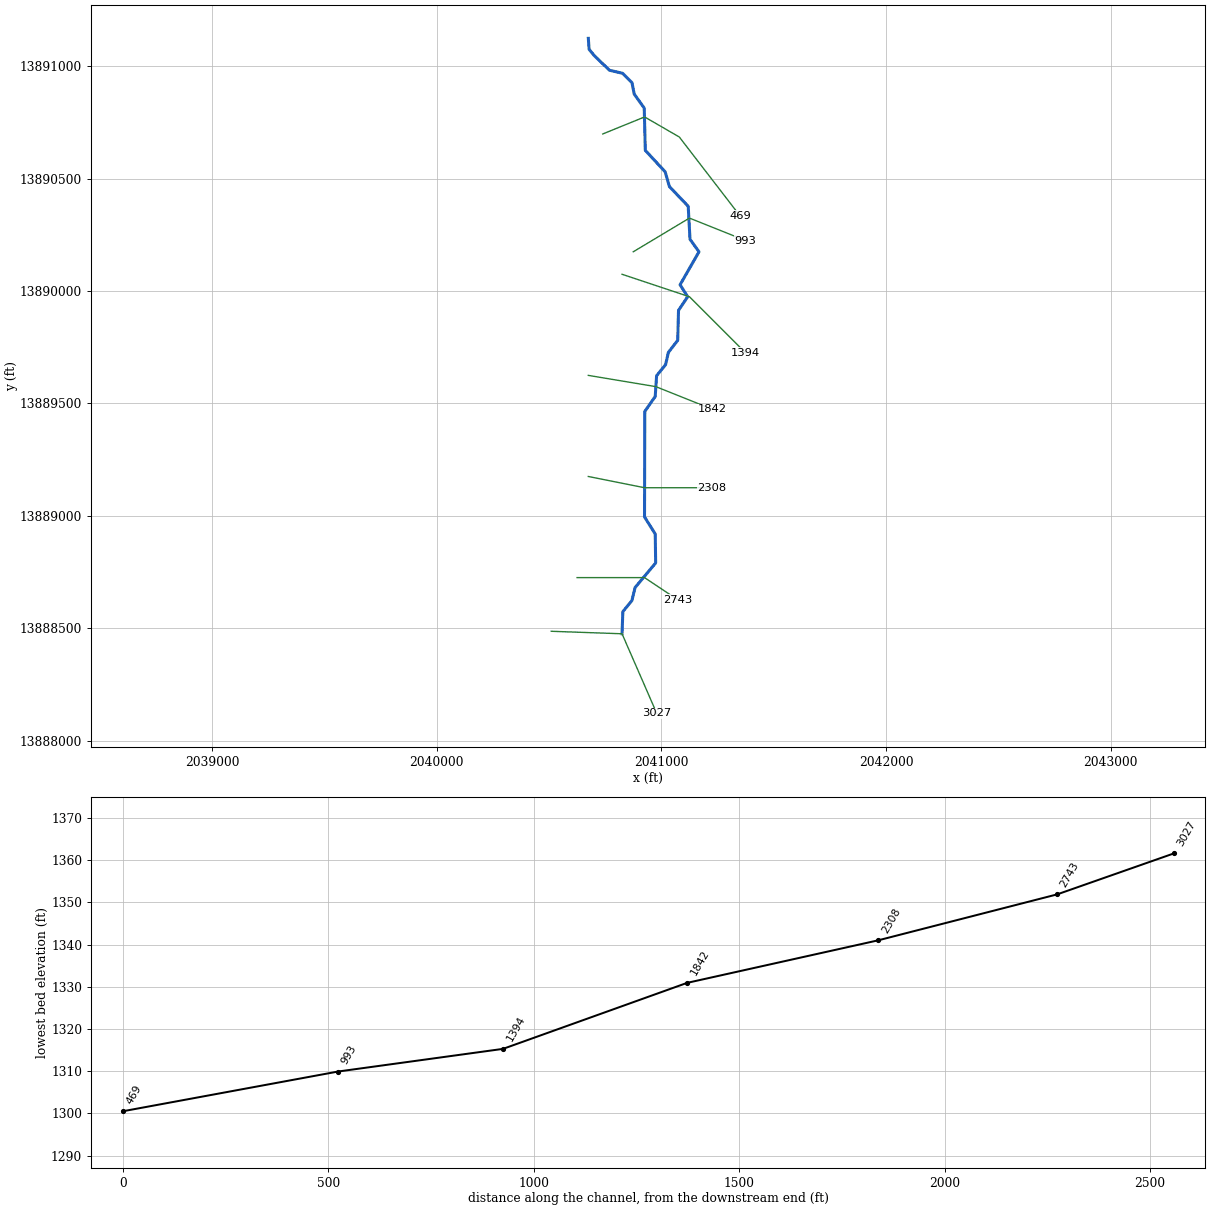
--- Stream0020_DS.prj (project) ---

Proj Title=Stream0020_DS Base Level Engineering
Current Plan=p01
Default Exp/Contr=0.3,0.1
English Units
Geom File=g01
Flow File=f01
Plan File=p01
BEGIN DESCRIPTION:
Stream0020_DS
END DESCRIPTION:

--- Stream0020_DS.p01 (plan) ---

Plan Title=Multiple Run
Short Identifier=Multiple
Geom File=g01
Flow File=f01
Subcritical Flow
K Sum by GR= 0
Std Step Tol= 0.01
Critical Tol= 0.01
Num of Std Step Trials= 20
Max Error Tol= 0.3
Flow Tol Ratio= 0.001
Split Flow NTrial= 30
Split Flow Tol= 0.02
Split Flow Ratio= 0.02
Log Output Level= 0
Friction Slope Method= 1
Unsteady Friction Slope Method= 2
Unsteady Bridges Friction Slope Method= 1
Parabolic Critical Depth
Global Vel Dist=  1 , 1 , 1
Global Log Level= 0
CheckData=True
Encroach Param= -1, 0, 0, 0
BEGIN DESCRIPTION:
Multiple Run
END DESCRIPTION:

--- Stream0020_DS.f01 (steady flow) ---

Flow Title=Multiple
Number of Profiles=7
Profile Names=10-year,25-year,50-year,1pct_min,100-year,1pct_plu,500-year
River Rch & RM= Stream0020_DS,Reach-1,3027
     284     441     579     371     739    1475    1188
River Rch & RM= Stream0020_DS,Reach-1,2308
     419     668     892     580    1158    2310    1921
Boundary for River Rch & Prof#=Stream0020_DS,Reach-1,1
Up Type=0
Dn Type=3
Dn Slope=0.005
Boundary for River Rch & Prof#=Stream0020_DS,Reach-1,2
Up Type=0
Dn Type=3
Dn Slope=0.005
Boundary for River Rch & Prof#=Stream0020_DS,Reach-1,3
Up Type=0
Dn Type=3
Dn Slope=0.005
Boundary for River Rch & Prof#=Stream0020_DS,Reach-1,4
Up Type=0
Dn Type=3
Dn Slope=0.005
Boundary for River Rch & Prof#=Stream0020_DS,Reach-1,5
Up Type=0
Dn Type=3
Dn Slope=0.005
Boundary for River Rch & Prof#=Stream0020_DS,Reach-1,6
Up Type=0
Dn Type=3
Dn Slope=0.005
Boundary for River Rch & Prof#=Stream0020_DS,Reach-1,7
Up Type=0
Dn Type=3
Dn Slope=0.005

--- Stream0020_DS.g01 (geometry) ---

Geom Title=Existing Conditions

River Reach=Stream0020_DS,Reach-1
Reach XY= 30
      2040825.00     13888475.00      2040828.63     13888573.50
      2040868.89     13888622.82      2040883.16     13888681.05
      2040974.63     13888790.17      2040972.75     13888919.06
      2040925.07     13888995.03      2040926.22     13889464.50
      2040972.64     13889530.98      2040978.83     13889623.42
      2041018.89     13889672.82      2041031.12     13889727.18
      2041072.75     13889780.93      2041076.39     13889914.56
      2041117.20     13889975.10      2041083.24     13890028.23
      2041167.47     13890174.99      2041127.47     13890230.86
      2041119.52     13890377.44      2041035.80     13890465.33
      2041016.82     13890531.04      2040928.55     13890626.47
      2040923.80     13890814.50      2040879.23     13890876.78
      2040869.27     13890927.55      2040827.54     13890969.25
      2040768.95     13890983.15      2040701.32     13891048.13
      2040678.27     13891076.34      2040675.00     13891125.00

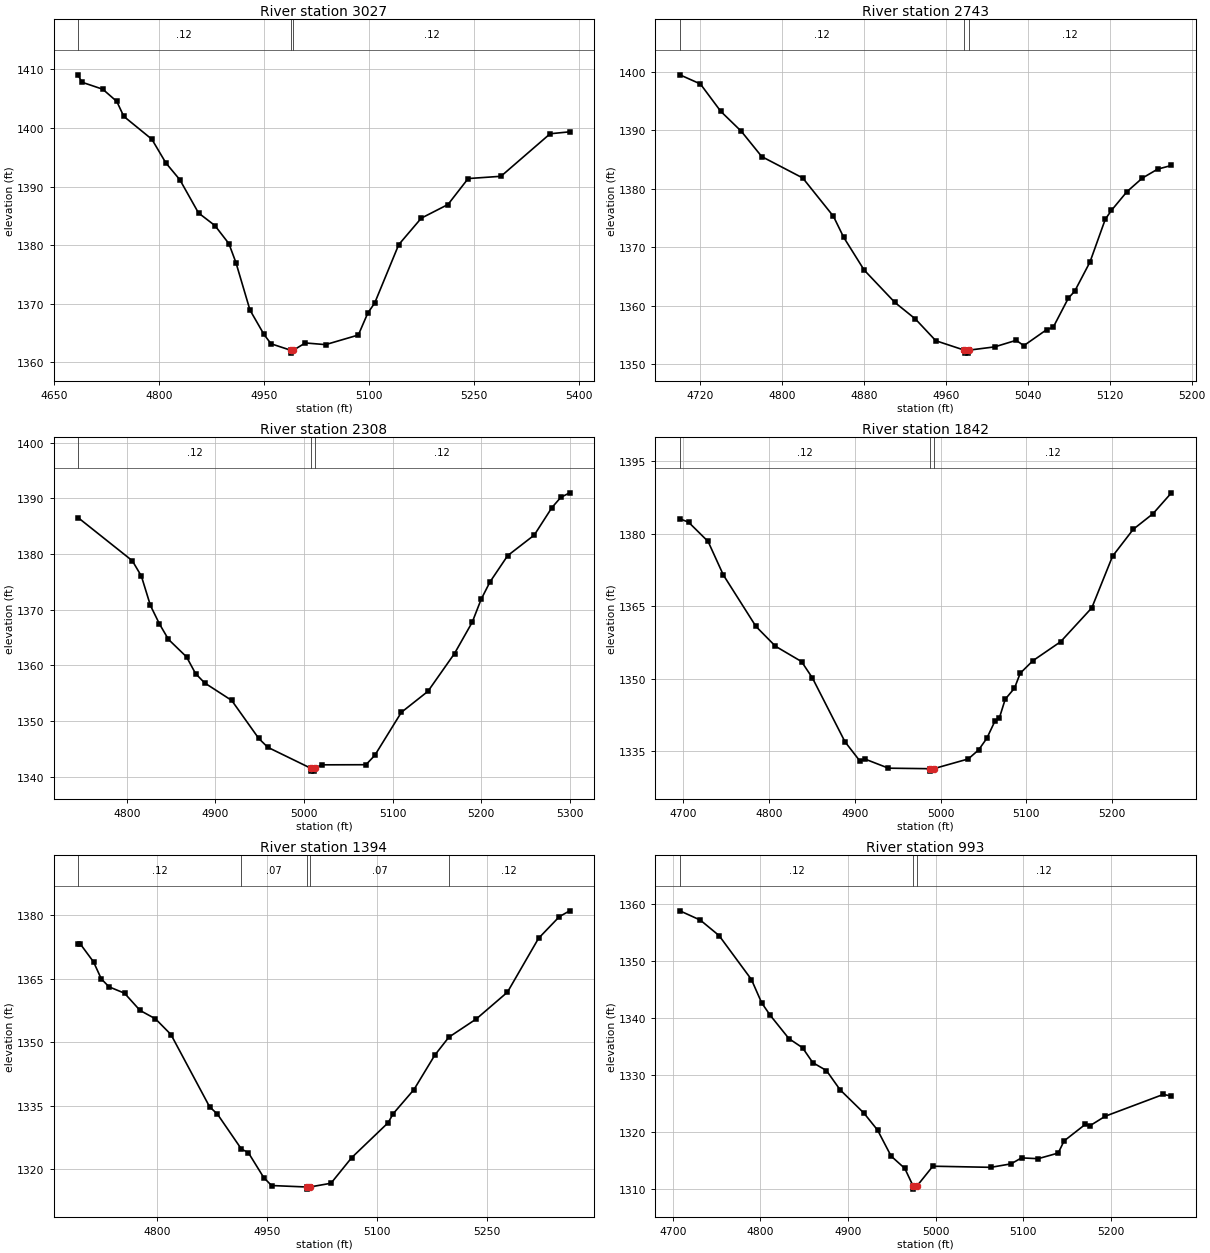
Type RM Length L Ch R = 1,3027,284,284,284
BEGIN DESCRIPTION:
Stream0020_DS 6.0
END DESCRIPTION:
XS GIS Cut Line= 3
      2040509.80     13888486.11      2040825.00     13888475.00
      2040979.54     13888120.74
#Sta/Elev= 30
  4684.6 1409.09  4689.8 1407.84  4719.8 1406.63  4739.8 1404.55  4749.8 1402.00
  4789.9 1398.09  4809.9 1394.05  4829.9 1391.17  4856.5 1385.51  4879.9 1383.36
  4899.9 1380.27  4909.9 1377.05  4930.0 1368.93  4950.0 1364.77  4960.0 1363.18
  4988.0 1362.08  4988.2 1361.58  4992.0 1362.08  5009.0 1363.32  5037.9 1363.03
  5084.7 1364.67  5098.2 1368.41  5108.1 1370.14  5142.4 1380.10  5174.6 1384.62
  5212.7 1386.95  5241.5 1391.38  5288.4 1391.77  5358.6 1399.03  5386.5 1399.36
#Mann=3,-1,0
  4684.6    0.12       0  4988.0    0.05       0  4992.0    0.12       0
Bank Sta=4988,4992
Exp/Cntr=0.3,0.1

Type RM Length L Ch R = 1,2743,435,435,435
BEGIN DESCRIPTION:
Stream0020_DS 5.0
END DESCRIPTION:
XS GIS Cut Line= 3
      2040625.04     13888725.00      2040925.00     13888725.00
      2041074.97     13888625.02
#Sta/Elev= 30
  4700.0 1399.48  4720.0 1397.92  4740.0 1393.22  4760.0 1389.82  4780.0 1385.49
  4820.0 1381.84  4850.0 1375.28  4860.0 1371.69  4880.0 1366.09  4910.0 1360.55
  4930.0 1357.73  4950.0 1354.00  4978.0 1352.38  4978.2 1351.88  4981.7 1351.88
  4982.0 1352.38  5007.5 1352.95  5028.5 1354.07  5036.0 1353.16  5058.5 1355.92
  5064.6 1356.27  5079.6 1361.32  5085.6 1362.44  5100.6 1367.46  5115.6 1374.79
  5121.6 1376.30  5136.7 1379.49  5151.7 1381.81  5166.7 1383.35  5180.2 1383.98
#Mann=3,-1,0
  4700.0    0.12       0  4978.0    0.05       0  4982.0    0.12       0
Bank Sta=4978,4982
Exp/Cntr=0.3,0.1

Type RM Length L Ch R = 1,2308,466,466,466
BEGIN DESCRIPTION:
Stream0020_DS 4.0
END DESCRIPTION:
XS GIS Cut Line= 3
      2040675.01     13889175.00      2040925.00     13889125.00
      2041224.96     13889125.00
#Sta/Elev= 30
  4745.1 1386.52  4806.3 1378.78  4816.5 1376.03  4826.7 1370.76  4836.9 1367.44
  4847.1 1364.66  4867.5 1361.52  4877.7 1358.52  4887.9 1356.85  4918.5 1353.70
  4949.0 1346.88  4959.2 1345.29  5008.0 1341.51  5008.3 1341.01  5011.8 1341.01
  5012.0 1341.51  5020.0 1342.14  5070.0 1342.16  5080.0 1343.84  5110.0 1351.57
  5140.0 1355.34  5170.0 1362.13  5190.0 1367.75  5200.0 1371.84  5210.0 1374.97
  5230.0 1379.70  5260.0 1383.39  5280.0 1388.34  5290.0 1390.17  5300.0 1390.98
#Mann=3,-1,0
  4745.1    0.12       0  5008.0    0.05       0  5012.0    0.12       0
Bank Sta=5008,5012
Exp/Cntr=0.3,0.1

Type RM Length L Ch R = 1,1842,448,448,448
BEGIN DESCRIPTION:
Stream0020_DS 3.0
END DESCRIPTION:
XS GIS Cut Line= 3
      2040675.03     13889624.99      2040975.00     13889575.00
      2041225.04     13889474.99
#Sta/Elev= 30
  4695.9 1383.08  4706.0 1382.38  4728.8 1378.39  4746.6 1371.46  4784.6 1360.83
  4807.4 1356.73  4837.8 1353.56  4850.5 1350.17  4888.5 1336.97  4906.2 1332.93
  4911.3 1333.44  4939.2 1331.52  4987.9 1331.41  4988.1 1330.91  4991.9 1331.41
  5032.3 1333.43  5044.4 1335.30  5053.9 1337.69  5063.3 1341.21  5068.7 1341.98
  5075.4 1345.78  5086.2 1348.06  5092.9 1351.15  5107.7 1353.74  5140.0 1357.66
  5176.4 1364.67  5200.6 1375.35  5224.8 1380.92  5247.7 1384.12  5269.3 1388.45
#Mann=3,-1,0
  4695.9    0.12       0  4987.9    0.05       0  4991.9    0.12       0
Bank Sta=4987.9,4991.9
Exp/Cntr=0.3,0.1

Type RM Length L Ch R = 1,1394,401,401,401
BEGIN DESCRIPTION:
Stream0020_DS 2.0
END DESCRIPTION:
XS GIS Cut Line= 3
      2040825.04     13890074.99      2041125.00     13889975.00
      2041374.97     13889725.03
#Sta/Elev= 30
  4692.5 1373.26  4695.1 1373.26  4713.5 1368.94  4724.1 1364.92  4734.6 1363.05
  4755.7 1361.55  4776.8 1357.49  4797.9 1355.49  4819.0 1351.78  4871.7 1334.70
  4882.2 1333.02  4915.0 1324.73  4924.4 1323.90  4945.4 1318.01  4956.0 1316.13
  5004.1 1315.78  5004.3 1315.28  5008.1 1315.78  5037.0 1316.67  5065.3 1322.73
  5114.8 1330.95  5121.8 1333.10  5150.1 1338.80  5178.4 1346.91  5197.6 1351.16
  5235.0 1355.47  5277.4 1361.79  5319.8 1374.51  5348.1 1379.62  5362.2 1381.00
#Mann=5,-1,0
  4692.5    0.12       0  4915.0    0.07       0  5004.1    0.05       0
  5008.1    0.07       0  5197.6    0.12       0
Bank Sta=5004.1,5008.1
Exp/Cntr=0.3,0.1

Type RM Length L Ch R = 1,993,524,524,524
BEGIN DESCRIPTION:
Stream0020_DS 1.0
END DESCRIPTION:
XS GIS Cut Line= 3
      2040875.00     13890175.00      2041125.00     13890325.00
      2041374.99     13890225.00
#Sta/Elev= 30
  4708.1 1358.83  4731.4 1357.20  4752.8 1354.48  4789.7 1346.76  4801.4 1342.66
  4811.1 1340.48  4832.5 1336.37  4848.0 1334.77  4859.7 1332.15  4875.3 1330.76
  4890.8 1327.39  4918.0 1323.29  4933.6 1320.30  4949.1 1315.72  4964.7 1313.56
  4974.3 1310.42  4974.6 1309.92  4978.3 1310.42  4996.7 1313.95  5062.9 1313.75
  5085.8 1314.36  5097.9 1315.41  5116.8 1315.27  5139.7 1316.26  5146.4 1318.39
  5170.6 1321.30  5176.0 1321.07  5193.5 1322.74  5259.5 1326.56  5268.9 1326.28
#Mann=3,-1,0
  4708.1    0.12       0  4974.3    0.05       0  4978.3    0.12       0
Bank Sta=4974.3,4978.3
Exp/Cntr=0.3,0.1

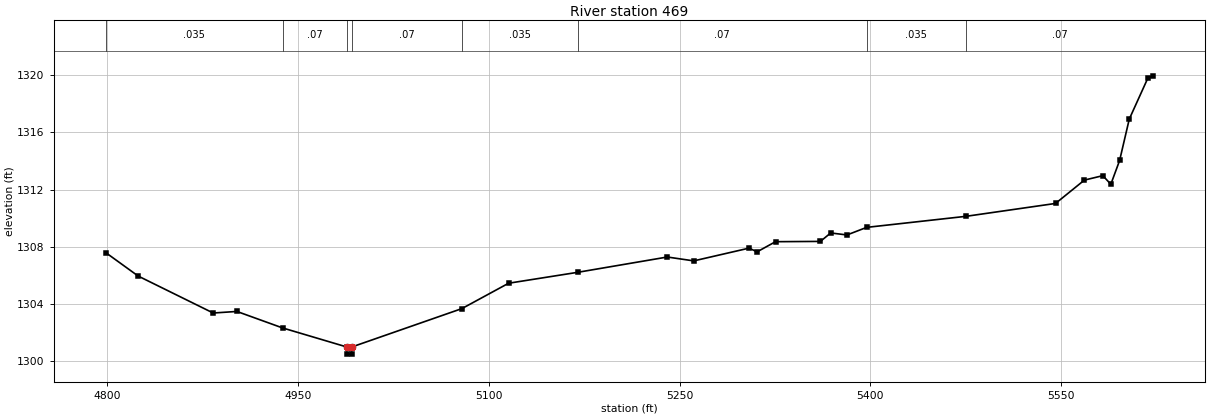
Type RM Length L Ch R = 1,469,0,0,0
BEGIN DESCRIPTION:
Stream0020_DS 0.0
END DESCRIPTION:
XS GIS Cut Line= 4
      2040739.03     13890699.36      2040925.40     13890775.17
      2041079.92     13890685.85      2041350.63     13890334.14
#Sta/Elev= 30
  4798.8 1307.59  4824.2 1305.96  4883.2 1303.38  4901.8 1303.49  4937.7 1302.34
  4988.2 1301.01  4988.5 1300.51  4992.0 1300.51  4992.2 1301.01  5078.8 1303.69
  5115.5 1305.46  5169.7 1306.22  5240.3 1307.29  5261.1 1307.02  5304.6 1307.91
  5310.9 1307.65  5325.4 1308.36  5360.7 1308.38  5368.8 1308.97  5381.6 1308.83
  5397.1 1309.36  5475.1 1310.13  5545.6 1311.03  5568.3 1312.66  5582.8 1312.97
  5589.1 1312.37  5596.0 1314.03  5603.6 1316.92  5618.1 1319.76  5622.3 1319.94
#Mann=8,-1,0
  4798.8   0.035       0  4937.7    0.07       0  4988.2    0.05       0
  4992.2    0.07       0  5078.8   0.035       0  5169.7    0.07       0
  5397.1   0.035       0  5475.1    0.07       0
Bank Sta=4988.2,4992.2
Exp/Cntr=0.3,0.1

Chan Stop Cuts=-1