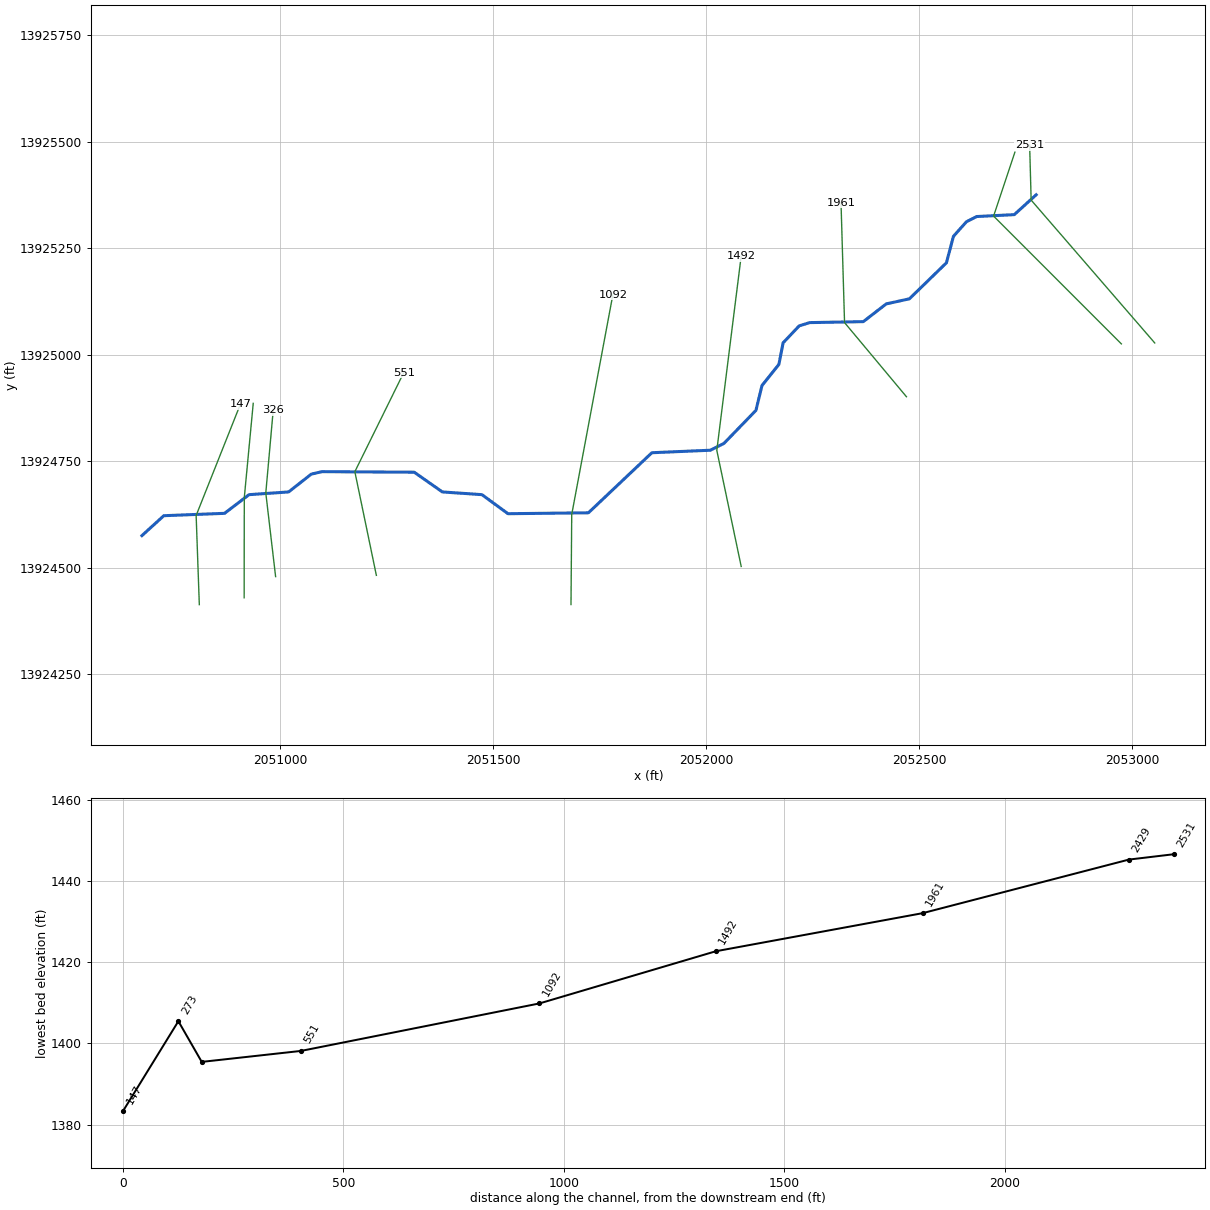
--- Stream0021_DS.prj (project) ---

Proj Title=Stream0021_DS Base Level Engineering
Current Plan=p01
Default Exp/Contr=0.3,0.1
English Units
Geom File=g01
Flow File=f01
Plan File=p01
BEGIN DESCRIPTION:
Stream0021_DS
END DESCRIPTION:

--- Stream0021_DS.p01 (plan) ---

Plan Title=Multiple Run
Short Identifier=Multiple
Geom File=g01
Flow File=f01
Subcritical Flow
K Sum by GR= 0
Std Step Tol= 0.01
Critical Tol= 0.01
Num of Std Step Trials= 20
Max Error Tol= 0.3
Flow Tol Ratio= 0.001
Split Flow NTrial= 30
Split Flow Tol= 0.02
Split Flow Ratio= 0.02
Log Output Level= 0
Friction Slope Method= 1
Unsteady Friction Slope Method= 2
Unsteady Bridges Friction Slope Method= 1
Parabolic Critical Depth
Global Vel Dist=  1 , 1 , 1
Global Log Level= 0
CheckData=True
Encroach Param= -1, 0, 0, 0
BEGIN DESCRIPTION:
Multiple Run
END DESCRIPTION:

--- Stream0021_DS.f01 (steady flow) ---

Flow Title=Multiple
Number of Profiles=7
Profile Names=10-year,25-year,50-year,1pct_min,100-year,1pct_plu,500-year
River Rch & RM= Stream0021_DS,Reach-1,2531
     603     998    1368     913    1822    3636    3195
Boundary for River Rch & Prof#=Stream0021_DS,Reach-1,1
Up Type=0
Dn Type=3
Dn Slope=0.005
Boundary for River Rch & Prof#=Stream0021_DS,Reach-1,2
Up Type=0
Dn Type=3
Dn Slope=0.005
Boundary for River Rch & Prof#=Stream0021_DS,Reach-1,3
Up Type=0
Dn Type=3
Dn Slope=0.005
Boundary for River Rch & Prof#=Stream0021_DS,Reach-1,4
Up Type=0
Dn Type=3
Dn Slope=0.005
Boundary for River Rch & Prof#=Stream0021_DS,Reach-1,5
Up Type=0
Dn Type=3
Dn Slope=0.005
Boundary for River Rch & Prof#=Stream0021_DS,Reach-1,6
Up Type=0
Dn Type=3
Dn Slope=0.005
Boundary for River Rch & Prof#=Stream0021_DS,Reach-1,7
Up Type=0
Dn Type=3
Dn Slope=0.005

--- Stream0021_DS.g01 (geometry) ---

Geom Title=Existing Conditions

River Reach=Stream0021_DS,Reach-1
Reach XY= 30
      2052775.00     13925375.00      2052723.59     13925328.39
      2052635.31     13925323.94      2052611.34     13925311.75
      2052580.74     13925277.57      2052564.22     13925215.32
      2052477.31     13925130.82      2052422.83     13925118.86
      2052369.07     13925077.25      2052243.11     13925074.94
      2052218.52     13925067.30      2052180.71     13925027.58
      2052170.80     13924976.77      2052131.10     13924927.19
      2052116.87     13924868.93      2052041.80     13924791.42
      2052009.84     13924775.40      2051872.55     13924769.53
      2051723.54     13924628.54      2051534.66     13924626.38
      2051473.40     13924671.14      2051380.57     13924677.47
      2051314.50     13924723.78      2051097.69     13924725.10
      2051072.66     13924719.26      2051019.43     13924677.47
      2050926.60     13924671.14      2050869.06     13924627.27
      2050726.37     13924621.70      2050675.00     13924575.00

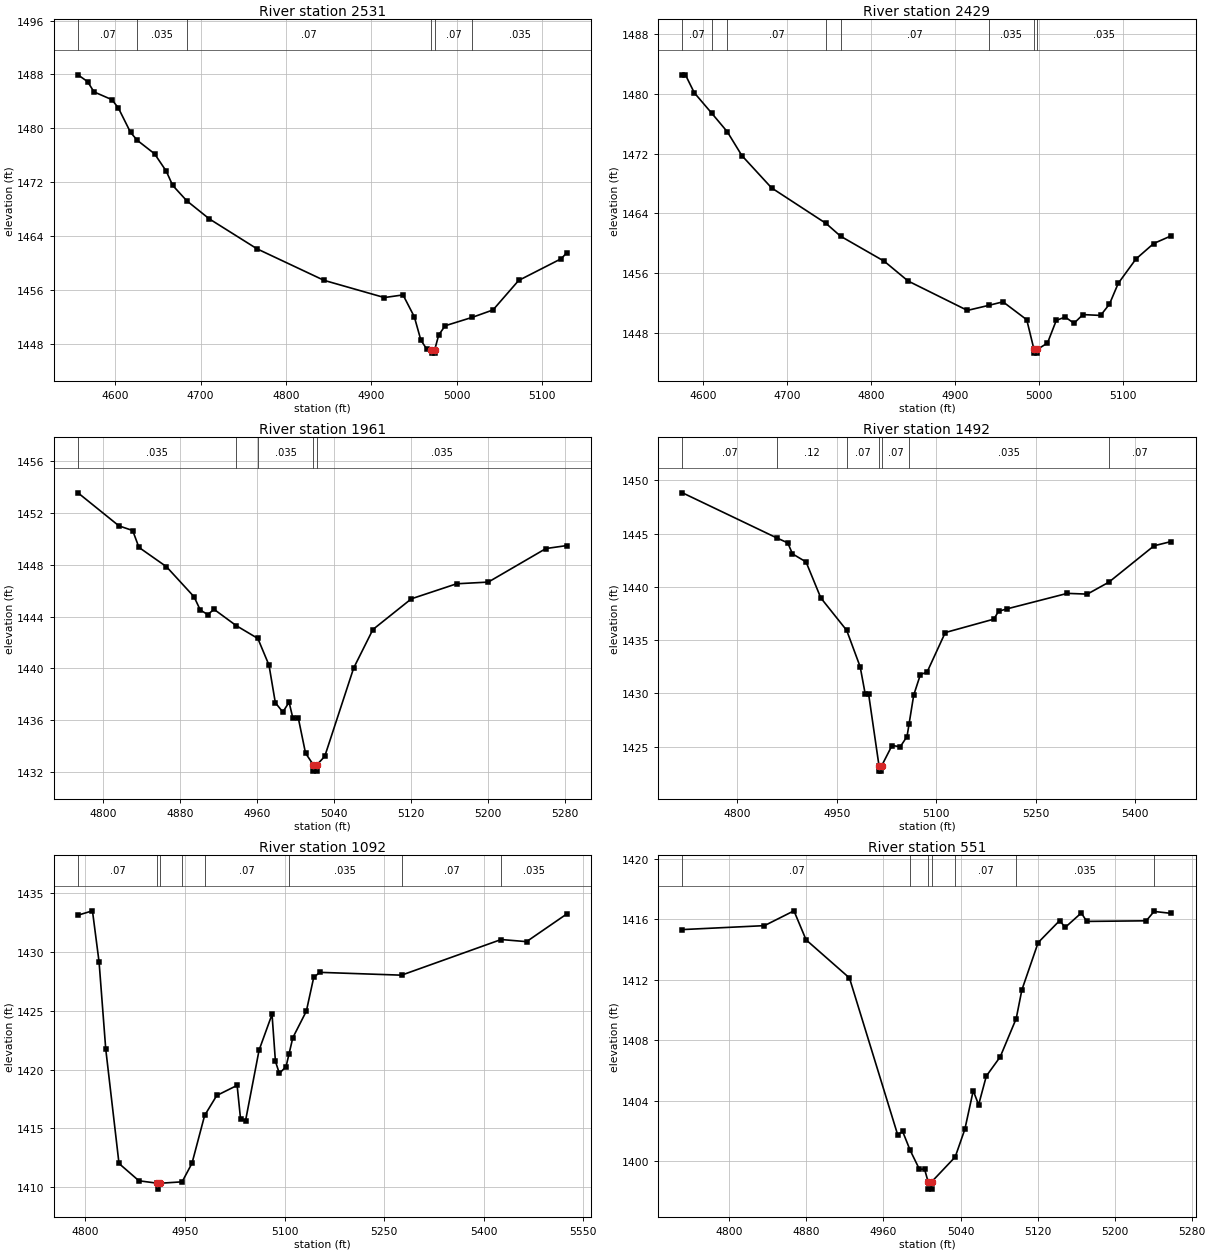
Type RM Length L Ch R = 1,2531,102,102,102
BEGIN DESCRIPTION:
Stream0021_DS 6.0
END DESCRIPTION:
XS GIS Cut Line= 3
      2053053.50     13925027.14      2052763.18     13925362.54
      2052759.65     13925491.49
#Sta/Elev= 30
  4556.4 1487.95  4567.6 1486.94  4575.2 1485.41  4596.1 1484.26  4603.7 1483.02
  4618.0 1479.38  4626.1 1478.19  4646.1 1476.21  4659.7 1473.65  4667.3 1471.52
  4683.8 1469.23  4710.1 1466.55  4766.1 1462.09  4844.5 1457.41  4915.2 1454.85
  4937.1 1455.24  4950.3 1451.99  4958.0 1448.51  4964.6 1447.24  4970.2 1447.09
  4970.5 1446.59  4974.0 1446.59  4974.2 1447.09  4978.9 1449.30  4986.5 1450.66
  5018.2 1451.91  5042.5 1453.01  5072.5 1457.39  5122.5 1460.63  5129.0 1461.54
#Mann=6,-1,0
  4556.4    0.07       0  4626.1   0.035       0  4683.8    0.07       0
  4970.2    0.05       0  4974.2    0.07       0  5018.2   0.035       0
Bank Sta=4970.2,4974.2
Exp/Cntr=0.3,0.1

Type RM Length L Ch R = 1,2429,468,468,468
BEGIN DESCRIPTION:
Stream0021_DS 5.0
END DESCRIPTION:
XS GIS Cut Line= 3
      2052975.00     13925025.00      2052675.00     13925325.00
      2052725.01     13925475.02
#Sta/Elev= 30
  4575.6 1482.54  4579.1 1482.54  4589.7 1480.13  4610.5 1477.39  4629.0 1474.91
  4646.3 1471.73  4681.7 1467.40  4746.6 1462.64  4763.9 1460.93  4816.0 1457.57
  4844.3 1454.93  4915.0 1450.99  4940.2 1451.66  4957.4 1452.14  4985.7 1449.74
  4994.3 1445.77  4994.6 1445.27  4998.1 1445.27  4998.3 1445.77  5010.4 1446.62
  5020.9 1449.66  5031.5 1450.10  5042.0 1449.27  5052.6 1450.43  5073.7 1450.32
  5084.2 1451.83  5094.7 1454.62  5115.8 1457.88  5136.9 1459.95  5158.0 1460.99
#Mann=8,-1,0
  4575.6    0.07       0  4610.5   0.035       0  4629.0    0.07       0
  4746.6   0.035       0  4763.9    0.07       0  4940.2   0.035       0
  4994.3   0.035       0  4998.3   0.035       0
Bank Sta=4994.3,4998.3
Exp/Cntr=0.3,0.1

Type RM Length L Ch R = 1,1961,469,469,469
BEGIN DESCRIPTION:
Stream0021_DS 4.0
END DESCRIPTION:
XS GIS Cut Line= 3
      2052470.33     13924900.97      2052325.00     13925075.00
      2052316.67     13925356.74
#Sta/Elev= 30
  4773.7 1453.55  4816.3 1451.00  4830.6 1450.64  4837.1 1449.34  4865.7 1447.85
  4894.4 1445.53  4900.9 1444.51  4908.7 1444.15  4915.2 1444.56  4938.3 1443.30
  4960.8 1442.31  4972.4 1440.25  4979.0 1437.35  4986.8 1436.63  4993.3 1437.39
  4997.2 1436.17  5002.9 1436.17  5010.4 1433.46  5018.4 1432.57  5018.7 1432.07
  5022.2 1432.07  5022.4 1432.57  5030.4 1433.21  5060.5 1440.03  5080.5 1443.00
  5120.5 1445.37  5167.6 1446.53  5200.5 1446.66  5260.5 1449.25  5282.3 1449.48
#Mann=5,-1,0
  4773.7   0.035       0  4938.3    0.12       0  4960.8   0.035       0
  5018.4   0.035       0  5022.4   0.035       0
Bank Sta=5018.4,5022.4
Exp/Cntr=0.3,0.1

Type RM Length L Ch R = 1,1492,400,400,400
BEGIN DESCRIPTION:
Stream0021_DS 3.0
END DESCRIPTION:
XS GIS Cut Line= 3
      2052082.30     13924502.53      2052025.00     13924775.00
      2052082.20     13925230.89
#Sta/Elev= 30
  4717.0 1448.82  4859.5 1444.58  4875.9 1444.12  4883.0 1443.09  4903.5 1442.33
  4925.8 1438.95  4964.8 1435.91  4985.2 1432.48  4992.9 1429.89  4998.0 1429.89
  5013.6 1423.19  5013.8 1422.69  5017.3 1422.69  5017.6 1423.19  5033.2 1425.09
  5045.8 1424.99  5055.9 1425.94  5059.0 1427.13  5066.0 1429.83  5076.1 1431.76
  5086.1 1431.98  5113.6 1435.70  5186.9 1436.96  5194.1 1437.70  5207.1 1437.93
  5297.8 1439.38  5328.0 1439.31  5360.5 1440.43  5428.8 1443.85  5454.9 1444.25
#Mann=7,-1,0
  4717.0    0.07       0  4859.5    0.12       0  4964.8    0.07       0
  5013.6    0.05       0  5017.6    0.07       0  5059.0   0.035       0
  5360.5    0.07       0
Bank Sta=5013.6,5017.6
Exp/Cntr=0.3,0.1

Type RM Length L Ch R = 1,1092,541,541,541
BEGIN DESCRIPTION:
Stream0021_DS 2.0
END DESCRIPTION:
XS GIS Cut Line= 3
      2051682.58     13924413.20      2051684.30     13924624.50
      2051780.99     13925140.92
#Sta/Elev= 30
  4788.7 1433.13  4810.5 1433.50  4820.5 1429.14  4830.5 1421.76  4850.5 1412.02
  4880.5 1410.55  4908.5 1410.34  4908.8 1409.84  4912.5 1410.34  4945.6 1410.46
  4960.5 1412.04  4979.5 1416.10  4997.8 1417.80  5028.5 1418.66  5033.6 1415.84
  5041.2 1415.66  5061.6 1421.66  5081.1 1424.70  5086.2 1420.71  5092.1 1419.68
  5102.2 1420.25  5106.8 1421.36  5112.4 1422.71  5132.8 1424.97  5143.9 1427.84
  5153.1 1428.27  5276.2 1428.03  5426.3 1431.06  5464.6 1430.88  5525.4 1433.24
#Mann=8,-1,0
  4788.7    0.07       0  4908.5    0.05       0  4912.5    0.07       0
  4945.6   0.035       0  4979.5    0.07       0  5106.8   0.035       0
  5276.2    0.07       0  5426.3   0.035       0
Bank Sta=4908.5,4912.5
Exp/Cntr=0.3,0.1

Type RM Length L Ch R = 1,551,225,225,225
BEGIN DESCRIPTION:
Stream0021_DS 1.0
END DESCRIPTION:
XS GIS Cut Line= 3
      2051225.53     13924481.71      2051175.00     13924725.00
      2051289.66     13924957.26
#Sta/Elev= 30
  4751.4 1415.31  4836.5 1415.57  4867.1 1416.55  4879.7 1414.63  4924.7 1412.11
  4974.8 1401.73  4979.9 1401.96  4987.8 1400.70  4997.3 1399.46  5002.7 1399.46
  5006.3 1398.64  5006.6 1398.14  5010.1 1398.14  5010.3 1398.64  5034.5 1400.27
  5044.5 1402.10  5053.2 1404.65  5058.8 1403.72  5066.8 1405.62  5081.2 1406.89
  5097.8 1409.42  5103.7 1411.32  5120.6 1414.45  5143.0 1415.91  5148.6 1415.45
  5165.4 1416.41  5171.0 1415.85  5232.8 1415.89  5240.9 1416.51  5258.9 1416.38
#Mann=7,-1,0
  4751.4    0.07       0  4987.8   0.035       0  5006.3   0.035       0
  5010.3   0.035       0  5034.5    0.07       0  5097.8   0.035       0
  5240.9    0.07       0
Bank Sta=5006.3,5010.3
Exp/Cntr=0.3,0.1

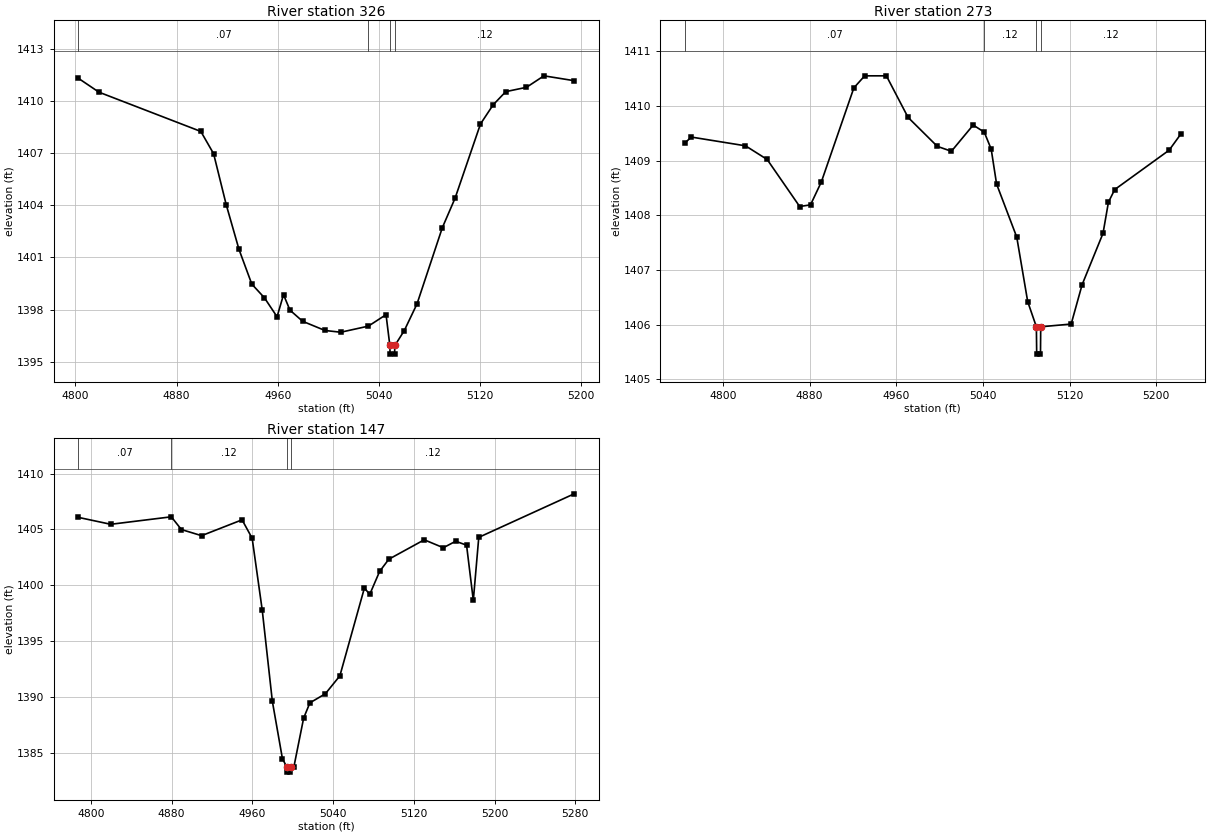
Type RM Length L Ch R = 1,326,53,53,53
BEGIN DESCRIPTION:
Stream0021_DS 0.2
END DESCRIPTION:
XS GIS Cut Line= 3
      2050988.91     13924478.77      2050965.86     13924675.12
      2050983.26     13924868.84
#Sta/Elev= 30
  4802.3 1411.31  4818.6 1410.51  4899.2 1408.25  4909.3 1406.97  4919.3 1404.03
  4929.4 1401.46  4939.5 1399.47  4949.5 1398.68  4959.5 1397.59  4964.6 1398.86
  4969.7 1397.97  4979.7 1397.33  4997.4 1396.80  5009.9 1396.70  5031.7 1397.05
  5045.7 1397.71  5048.7 1395.94  5048.9 1395.44  5052.4 1395.44  5052.7 1395.94
  5060.1 1396.79  5070.2 1398.33  5090.2 1402.71  5100.3 1404.41  5120.4 1408.68
  5130.4 1409.78  5140.4 1410.54  5156.8 1410.79  5170.6 1411.45  5194.5 1411.17
#Mann=4,-1,0
  4802.3    0.07       0  5031.7    0.12       0  5048.7    0.05       0
  5052.7    0.12       0
Bank Sta=5048.7,5052.7
Exp/Cntr=0.3,0.1

Type RM Length L Ch R = 1,273,126,126,126
BEGIN DESCRIPTION:
Stream0021_DS 0.1
END DESCRIPTION:
XS GIS Cut Line= 3
      2050915.02     13924429.01      2050915.37     13924664.11
      2050936.37     13924885.51
#Sta/Elev= 30
  4764.9 1409.32  4770.9 1409.43  4820.9 1409.27  4840.9 1409.02  4870.9 1408.16
  4880.9 1408.19  4890.9 1408.61  4920.9 1410.33  4930.9 1410.55  4950.9 1410.55
  4970.9 1409.79  4997.9 1409.26  5010.9 1409.17  5031.0 1409.65  5041.2 1409.52
  5047.6 1409.21  5052.6 1408.57  5071.2 1407.60  5081.3 1406.42  5089.3 1405.96
  5089.6 1405.46  5093.1 1405.46  5093.3 1405.96  5121.4 1406.01  5131.5 1406.73
  5150.8 1407.67  5155.8 1408.24  5161.6 1408.47  5211.8 1409.19  5222.4 1409.48
#Mann=4,-1,0
  4764.9    0.07       0  5041.2    0.12       0  5089.3    0.05       0
  5093.3    0.12       0
Bank Sta=5089.3,5093.3
Exp/Cntr=0.3,0.1

Type RM Length L Ch R = 1,147,0,0,0
BEGIN DESCRIPTION:
Stream0021_DS 0.0
END DESCRIPTION:
XS GIS Cut Line= 3
      2050809.76     13924412.94      2050802.31     13924622.25
      2050906.45     13924884.06
#Sta/Elev= 30
  4787.7 1406.08  4819.8 1405.46  4879.8 1406.13  4889.8 1404.99  4909.8 1404.44
  4949.9 1405.86  4959.9 1404.21  4969.9 1397.76  4979.9 1389.60  4989.9 1384.45
  4994.0 1383.75  4994.3 1383.25  4997.8 1383.25  4998.0 1383.75  5001.3 1383.75
  5010.9 1388.09  5017.1 1389.46  5032.4 1390.27  5046.8 1391.88  5071.1 1399.75
  5076.4 1399.18  5086.2 1401.24  5095.3 1402.33  5130.4 1404.07  5149.3 1403.36
  5161.5 1403.94  5172.3 1403.59  5179.0 1398.64  5184.4 1404.29  5278.9 1408.19
#Mann=4,-1,0
  4787.7    0.07       0  4879.8    0.12       0  4994.0    0.05       0
  4998.0    0.12       0
Bank Sta=4994,4998
Exp/Cntr=0.3,0.1

Chan Stop Cuts=-1