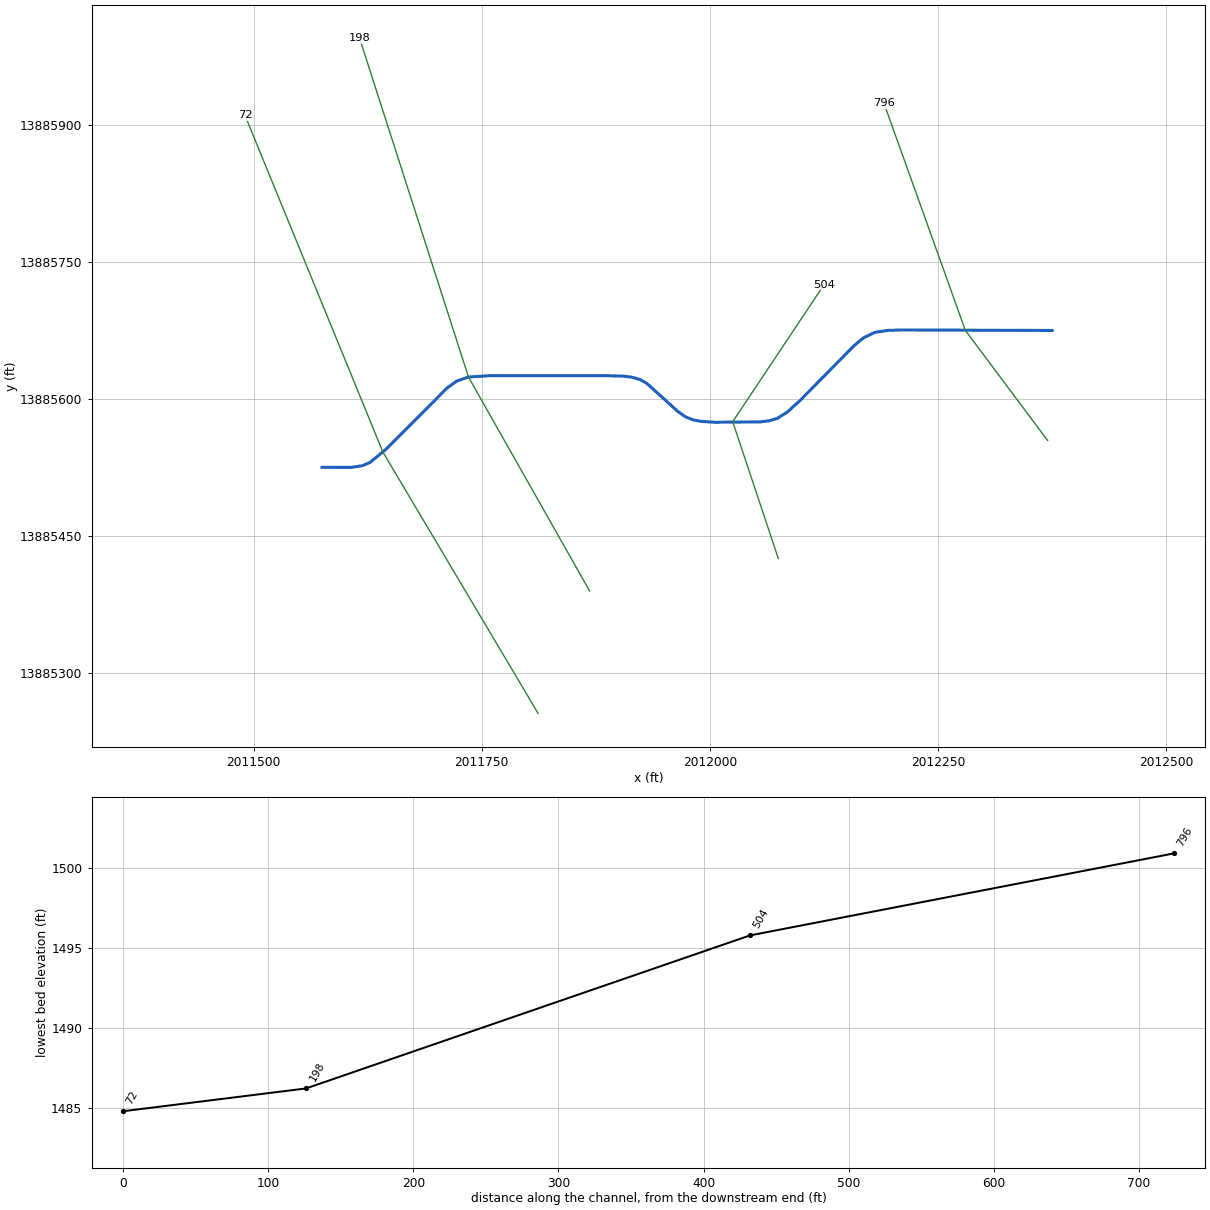
--- Stream0022_DS.prj (project) ---

Proj Title=Stream0022_DS Base Level Engineering
Current Plan=p01
Default Exp/Contr=0.3,0.1
English Units
Geom File=g01
Flow File=f01
Plan File=p01
BEGIN DESCRIPTION:
Stream0022_DS
END DESCRIPTION:

--- Stream0022_DS.p01 (plan) ---

Plan Title=Multiple Run
Short Identifier=Multiple
Geom File=g01
Flow File=f01
Subcritical Flow
K Sum by GR= 0
Std Step Tol= 0.01
Critical Tol= 0.01
Num of Std Step Trials= 20
Max Error Tol= 0.3
Flow Tol Ratio= 0.001
Split Flow NTrial= 30
Split Flow Tol= 0.02
Split Flow Ratio= 0.02
Log Output Level= 0
Friction Slope Method= 1
Unsteady Friction Slope Method= 2
Unsteady Bridges Friction Slope Method= 1
Parabolic Critical Depth
Global Vel Dist=  1 , 1 , 1
Global Log Level= 0
CheckData=True
Encroach Param= -1, 0, 0, 0
BEGIN DESCRIPTION:
Multiple Run
END DESCRIPTION:

--- Stream0022_DS.f01 (steady flow) ---

Flow Title=Multiple
Number of Profiles=7
Profile Names=10-year,25-year,50-year,1pct_min,100-year,1pct_plu,500-year
River Rch & RM= Stream0022_DS,Reach-1,796
     682    1143    1579    1062    2119    4227    3765
Boundary for River Rch & Prof#=Stream0022_DS,Reach-1,1
Up Type=0
Dn Type=3
Dn Slope=0.005
Boundary for River Rch & Prof#=Stream0022_DS,Reach-1,2
Up Type=0
Dn Type=3
Dn Slope=0.005
Boundary for River Rch & Prof#=Stream0022_DS,Reach-1,3
Up Type=0
Dn Type=3
Dn Slope=0.005
Boundary for River Rch & Prof#=Stream0022_DS,Reach-1,4
Up Type=0
Dn Type=3
Dn Slope=0.005
Boundary for River Rch & Prof#=Stream0022_DS,Reach-1,5
Up Type=0
Dn Type=3
Dn Slope=0.005
Boundary for River Rch & Prof#=Stream0022_DS,Reach-1,6
Up Type=0
Dn Type=3
Dn Slope=0.005
Boundary for River Rch & Prof#=Stream0022_DS,Reach-1,7
Up Type=0
Dn Type=3
Dn Slope=0.005

--- Stream0022_DS.g01 (geometry) ---

Geom Title=Existing Conditions

River Reach=Stream0022_DS,Reach-1
Reach XY= 30
      2012375.00     13885675.00      2012209.79     13885675.51
      2012194.98     13885675.05      2012180.85     13885672.94
      2012168.81     13885667.17      2012158.25     13885658.54
      2012098.50     13885597.90      2012084.78     13885585.46
      2012073.50     13885578.47      2012064.52     13885575.94
      2012054.95     13885574.79      2012004.96     13885574.39
      2011990.28     13885575.38      2011980.98     13885577.16
      2011972.69     13885580.68      2011965.37     13885585.81
      2011931.06     13885616.85      2011923.43     13885621.22
      2011914.50     13885623.78      2011904.97     13885624.93
      2011885.18     13885625.46      2011759.80     13885625.49
      2011735.43     13885623.95      2011722.55     13885619.54
      2011711.68     13885611.63      2011645.07     13885544.84
      2011627.51     13885530.33      2011618.85     13885526.69
      2011606.88     13885524.93      2011575.00     13885525.00

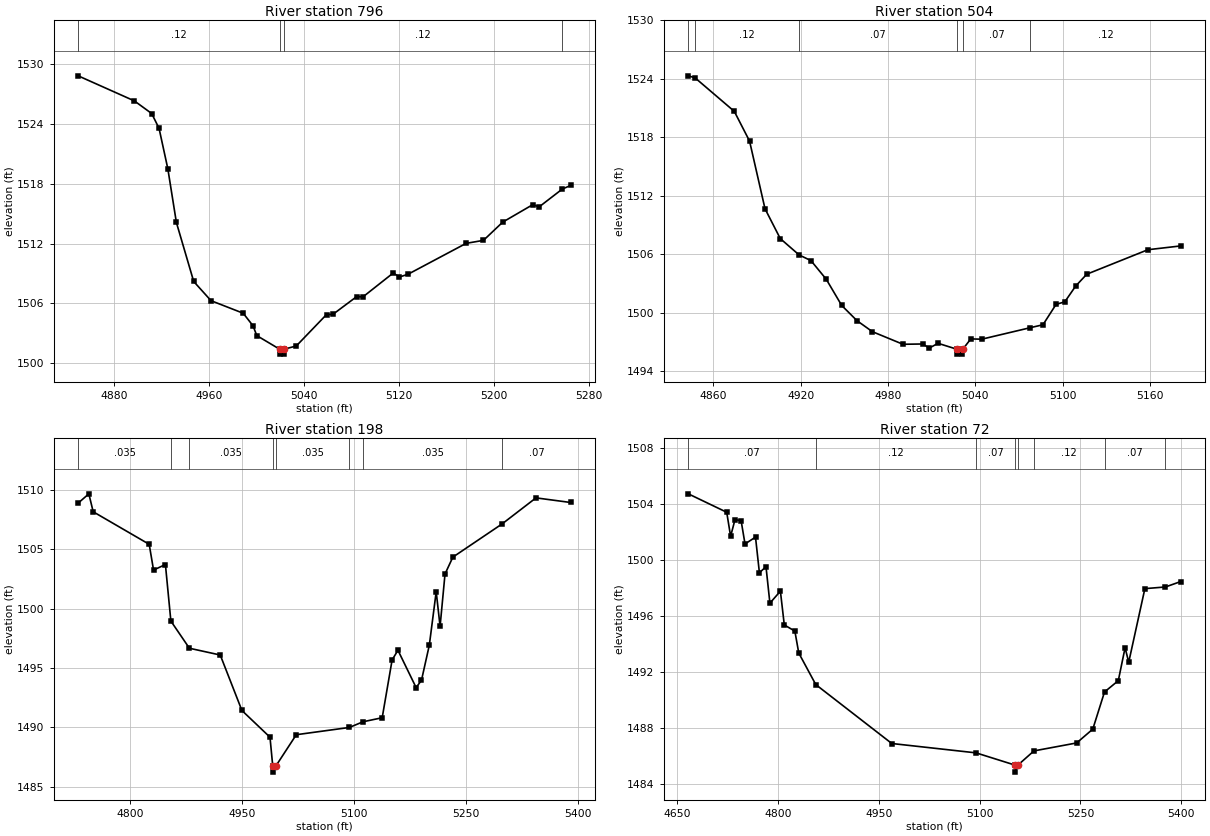
Type RM Length L Ch R = 1,796,292,292,292
BEGIN DESCRIPTION:
Stream0022_DS 2.0
END DESCRIPTION:
XS GIS Cut Line= 3
      2012370.12     13885554.44      2012279.97     13885675.08
      2012190.73     13885924.17
#Sta/Elev= 30
  4849.4 1528.85  4896.8 1526.33  4911.4 1525.06  4917.6 1523.57  4925.0 1519.51
  4932.2 1514.12  4946.8 1508.19  4961.4 1506.26  4988.5 1505.00  4996.8 1503.74
  5000.0 1502.75  5019.2 1501.39  5019.4 1500.89  5022.9 1500.89  5023.2 1501.39
  5033.3 1501.71  5058.8 1504.87  5064.1 1504.88  5084.2 1506.67  5089.5 1506.64
  5115.0 1509.04  5120.3 1508.64  5127.4 1508.91  5176.5 1512.02  5191.1 1512.32
  5207.3 1514.15  5232.7 1515.91  5238.0 1515.68  5257.5 1517.47  5264.6 1517.84
#Mann=4,-1,0
  4849.4    0.12       0  5019.2    0.05       0  5023.2    0.12       0
  5257.5   0.035       0
Bank Sta=5019.2,5023.2
Exp/Cntr=0.3,0.1

Type RM Length L Ch R = 1,504,306,306,306
BEGIN DESCRIPTION:
Stream0022_DS 1.0
END DESCRIPTION:
XS GIS Cut Line= 3
      2012074.99     13885425.04      2012025.00     13885575.00
      2012125.03     13885725.04
#Sta/Elev= 30
  4842.8 1524.30  4847.4 1524.10  4874.4 1520.66  4884.9 1517.61  4895.5 1510.68
  4906.0 1507.62  4918.9 1505.95  4927.1 1505.36  4937.6 1503.45  4948.2 1500.77
  4958.7 1499.21  4969.3 1498.08  4990.3 1496.79  5003.9 1496.82  5008.4 1496.40
  5014.4 1496.89  5027.4 1496.28  5027.7 1495.78  5031.2 1495.78  5031.4 1496.28
  5036.9 1497.34  5044.4 1497.31  5077.8 1498.49  5086.5 1498.79  5095.5 1500.88
  5101.5 1501.14  5109.0 1502.76  5116.6 1503.97  5158.6 1506.48  5181.2 1506.87
#Mann=6,-1,0
  4842.8    0.07       0  4847.4    0.12       0  4918.9    0.07       0
  5027.4    0.05       0  5031.4    0.07       0  5077.8    0.12       0
Bank Sta=5027.4,5031.4
Exp/Cntr=0.3,0.1

Type RM Length L Ch R = 1,198,126,126,126
BEGIN DESCRIPTION:
Stream0022_DS 0.1
END DESCRIPTION:
XS GIS Cut Line= 3
      2011868.17     13885389.52      2011735.43     13885623.95
      2011616.14     13885995.15
#Sta/Elev= 30
  4730.6 1508.89  4744.9 1509.67  4750.7 1508.16  4825.7 1505.42  4831.5 1503.25
  4847.4 1503.72  4854.7 1498.96  4879.5 1496.67  4920.8 1496.10  4949.8 1491.43
  4987.4 1489.18  4991.1 1486.74  4991.3 1486.24  4995.1 1486.74  5022.6 1489.39
  5093.6 1490.00  5112.0 1490.48  5137.6 1490.82  5150.9 1495.69  5158.7 1496.50
  5183.0 1493.36  5190.2 1493.97  5200.7 1496.93  5209.9 1501.43  5215.1 1498.51
  5221.7 1502.92  5232.2 1504.34  5298.2 1507.14  5343.5 1509.33  5389.9 1508.94
#Mann=8,-1,0
  4730.6   0.035       0  4854.7    0.12       0  4879.5   0.035       0
  4991.1   0.035       0  4995.1   0.035       0  5093.6    0.07       0
  5112.0   0.035       0  5298.2    0.07       0
Bank Sta=4991.1,4995.1
Exp/Cntr=0.3,0.1

Type RM Length L Ch R = 1,72,0,0,0
BEGIN DESCRIPTION:
Stream0022_DS 0.0
END DESCRIPTION:
XS GIS Cut Line= 3
      2011811.75     13885255.33      2011641.68     13885541.63
      2011490.41     13885910.94
#Sta/Elev= 30
  4667.0 1504.75  4724.1 1503.43  4729.9 1501.71  4736.4 1502.90  4745.5 1502.83
  4751.3 1501.16  4766.9 1501.65  4772.7 1499.10  4782.5 1499.53  4788.3 1496.92
  4803.9 1497.78  4809.7 1495.36  4825.4 1494.92  4831.2 1493.35  4856.5 1491.09
  4969.5 1486.87  5094.7 1486.20  5152.9 1485.32  5153.2 1484.82  5156.9 1485.32
  5180.8 1486.34  5244.3 1486.91  5268.3 1487.90  5285.7 1490.56  5306.2 1491.37
  5316.3 1493.73  5321.7 1492.69  5345.7 1497.96  5376.3 1498.08  5399.1 1498.47
#Mann=8,-1,0
  4667.0    0.07       0  4856.5    0.12       0  5094.7    0.07       0
  5152.9    0.05       0  5156.9    0.07       0  5180.8    0.12       0
  5285.7    0.07       0  5376.3    0.12       0
Bank Sta=5152.9,5156.9
Exp/Cntr=0.3,0.1

Chan Stop Cuts=-1