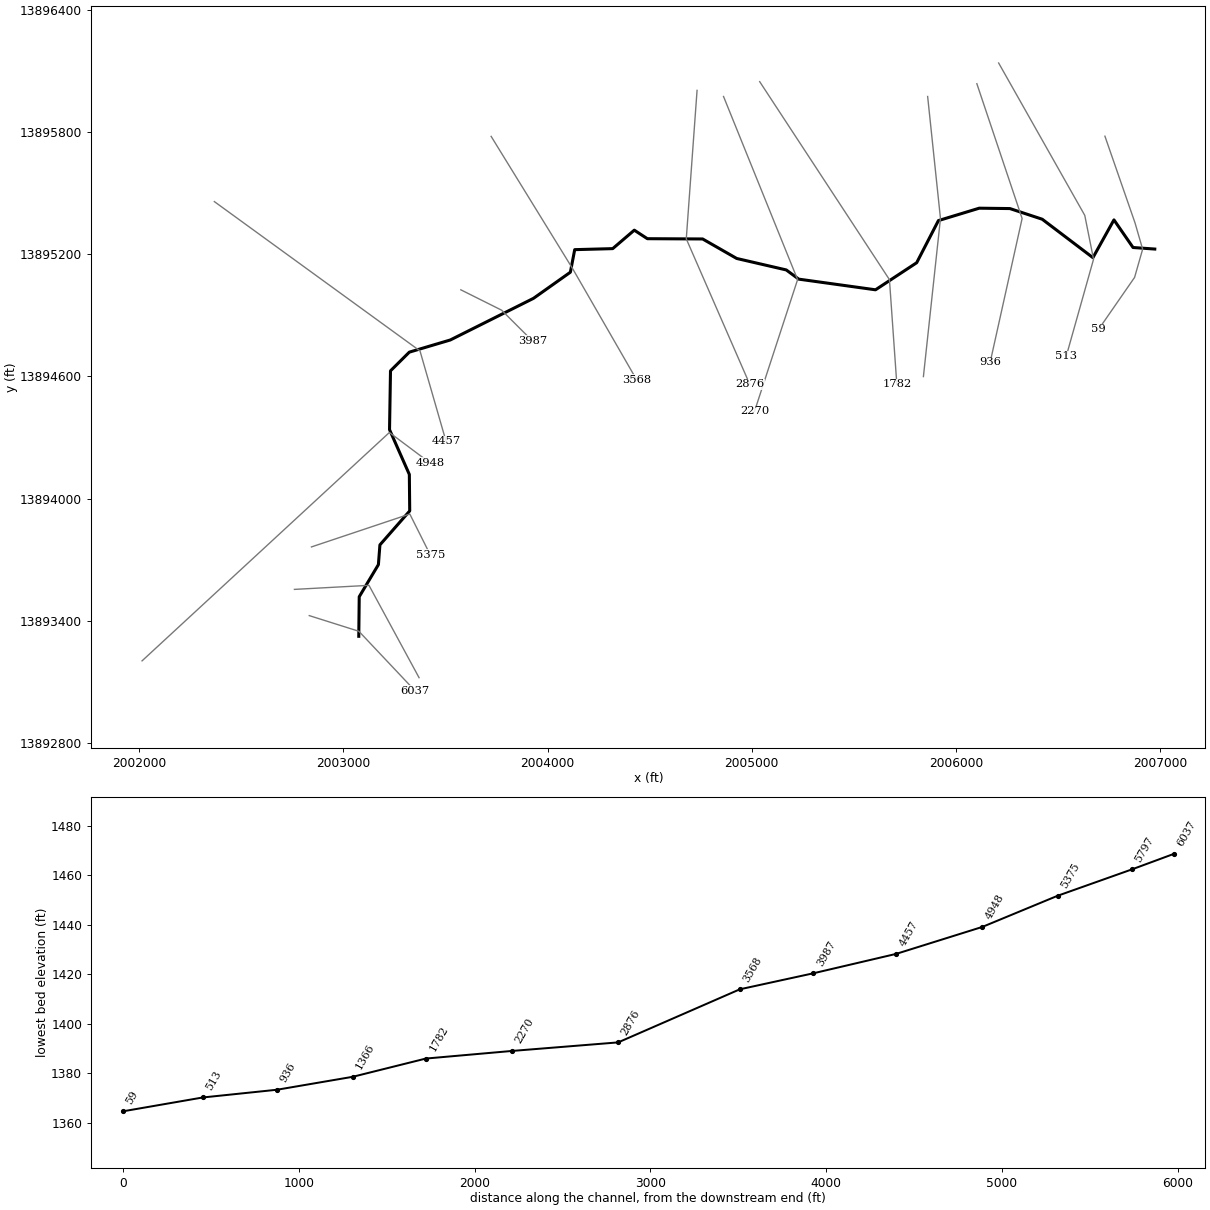
--- Stream0023_DS.prj (project) ---

Proj Title=Stream0023_DS Base Level Engineering
Current Plan=p01
Default Exp/Contr=0.3,0.1
English Units
Geom File=g01
Flow File=f01
Plan File=p01
BEGIN DESCRIPTION:
Stream0023_DS
END DESCRIPTION:

--- Stream0023_DS.p01 (plan) ---

Plan Title=Multiple Run
Short Identifier=Multiple
Geom File=g01
Flow File=f01
Subcritical Flow
K Sum by GR= 0
Std Step Tol= 0.01
Critical Tol= 0.01
Num of Std Step Trials= 20
Max Error Tol= 0.3
Flow Tol Ratio= 0.001
Split Flow NTrial= 30
Split Flow Tol= 0.02
Split Flow Ratio= 0.02
Log Output Level= 0
Friction Slope Method= 1
Unsteady Friction Slope Method= 2
Unsteady Bridges Friction Slope Method= 1
Parabolic Critical Depth
Global Vel Dist=  1 , 1 , 1
Global Log Level= 0
CheckData=True
Encroach Param= -1, 0, 0, 0
BEGIN DESCRIPTION:
Multiple Run
END DESCRIPTION:

--- Stream0023_DS.f01 (steady flow) ---

Flow Title=Multiple
Number of Profiles=7
Profile Names=10-year,25-year,50-year,1pct_min,100-year,1pct_plu,500-year
River Rch & RM= Stream0023_DS,Reach-1,6037
     488     800    1090     723    1443    2879    2496
River Rch & RM= Stream0023_DS,Reach-1,5797
    1231    2133    3010    2061    4113    8206    7595
Boundary for River Rch & Prof#=Stream0023_DS,Reach-1,1
Up Type=0
Dn Type=3
Dn Slope=0.005
Boundary for River Rch & Prof#=Stream0023_DS,Reach-1,2
Up Type=0
Dn Type=3
Dn Slope=0.005
Boundary for River Rch & Prof#=Stream0023_DS,Reach-1,3
Up Type=0
Dn Type=3
Dn Slope=0.005
Boundary for River Rch & Prof#=Stream0023_DS,Reach-1,4
Up Type=0
Dn Type=3
Dn Slope=0.005
Boundary for River Rch & Prof#=Stream0023_DS,Reach-1,5
Up Type=0
Dn Type=3
Dn Slope=0.005
Boundary for River Rch & Prof#=Stream0023_DS,Reach-1,6
Up Type=0
Dn Type=3
Dn Slope=0.005
Boundary for River Rch & Prof#=Stream0023_DS,Reach-1,7
Up Type=0
Dn Type=3
Dn Slope=0.005

--- Stream0023_DS.g01 (geometry) ---

Geom Title=Existing Conditions

River Reach=Stream0023_DS,Reach-1
Reach XY= 30
      2003075.00     13893325.00      2003077.23     13893519.08
      2003171.17     13893676.59      2003178.61     13893773.50
      2003324.62     13893940.16      2003322.74     13894119.06
      2003225.68     13894338.92      2003230.45     13894627.47
      2003322.69     13894719.18      2003523.42     13894778.83
      2003931.05     13894983.16      2004111.73     13895111.38
      2004132.97     13895222.06      2004319.15     13895227.08
      2004424.90     13895317.67      2004488.86     13895275.83
      2004759.79     13895274.49      2004926.58     13895178.83
      2005169.43     13895122.53      2005230.53     13895077.38
      2005606.77     13895025.07      2005808.51     13895157.95
      2005914.89     13895364.62      2006114.82     13895425.46
      2006265.34     13895423.62      2006423.50     13895371.39
      2006671.97     13895182.75      2006774.97     13895368.12
      2006868.45     13895232.61      2006975.00     13895225.00

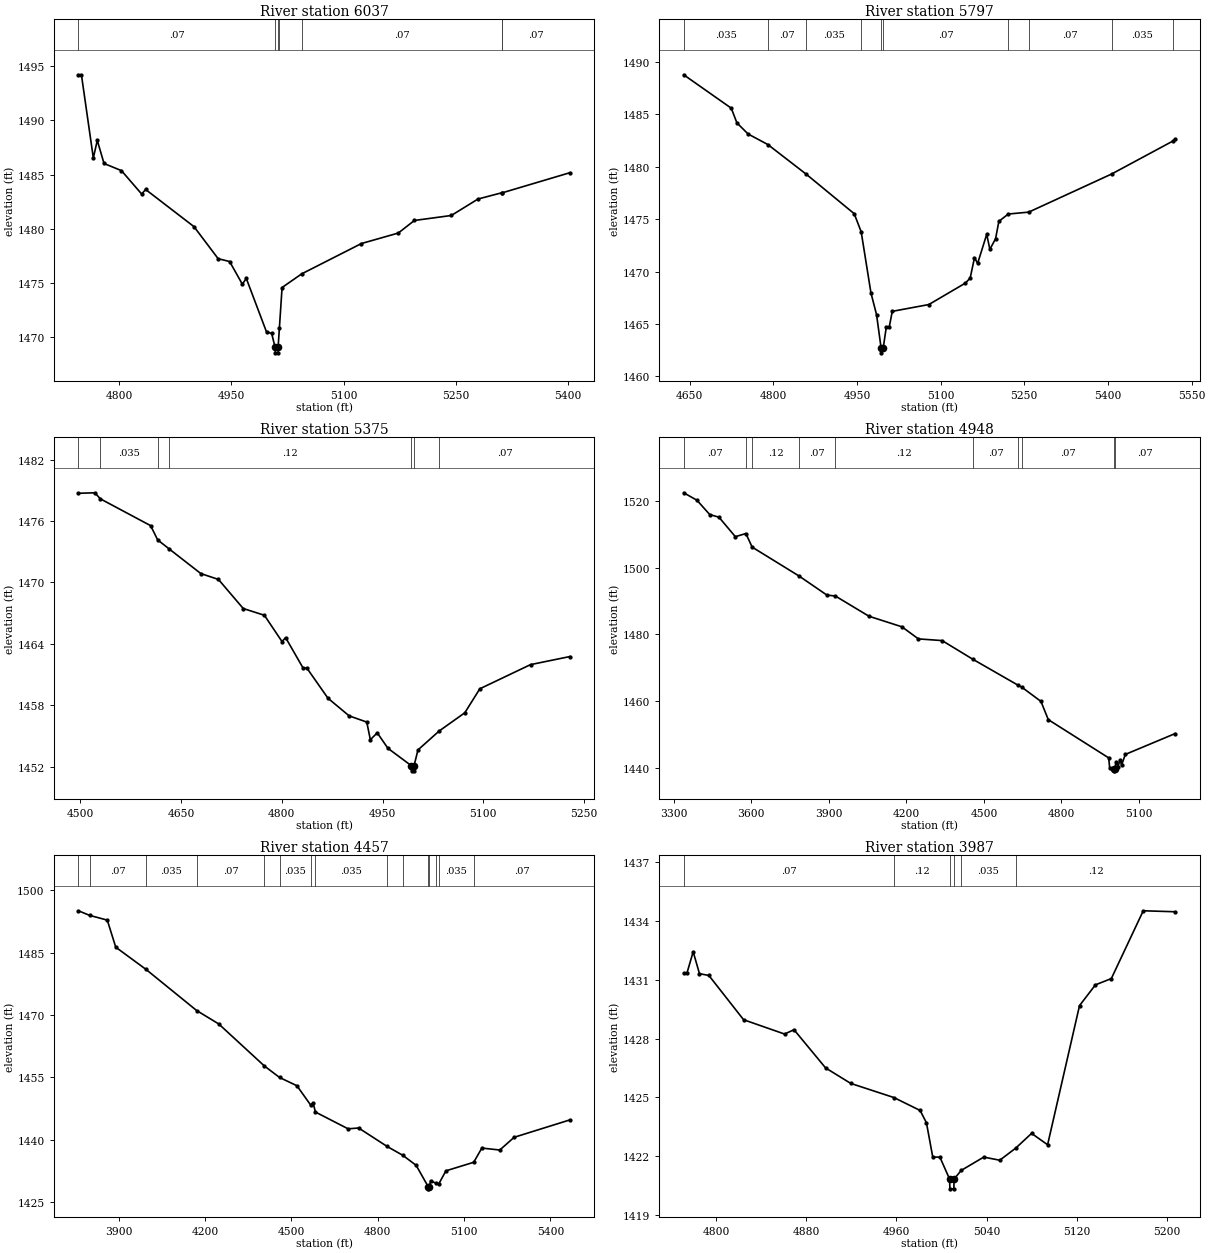
Type RM Length L Ch R = 1,6037,240,240,240
BEGIN DESCRIPTION:
Stream0023_DS 14.0
END DESCRIPTION:
XS GIS Cut Line= 3
      2002832.43     13893426.45      2003075.54     13893349.55
      2003351.08     13893057.23
#Sta/Elev= 30
  4745.6 1494.22  4749.6 1494.22  4765.5 1486.54  4770.8 1488.16  4779.8 1486.03
  4803.1 1485.37  4830.1 1483.21  4835.4 1483.63  4900.0 1480.20  4932.3 1477.24
  4947.6 1476.98  4964.6 1474.89  4969.9 1475.42  4996.9 1470.48  5003.8 1470.34
  5008.4 1469.05  5008.7 1468.55  5012.2 1468.55  5012.4 1469.05  5014.1 1470.82
  5017.7 1474.58  5043.9 1475.84  5123.7 1478.64  5173.0 1479.61  5194.5 1480.77
  5243.8 1481.23  5279.5 1482.75  5311.4 1483.33  5312.2 1483.33  5402.3 1485.18
#Mann=7,-1,0
  4745.6    0.07       0  5008.4    0.05       0  5012.4    0.07       0
  5014.1   0.035       0  5043.9    0.07       0  5311.4   0.035       0
  5312.2    0.07       0
Bank Sta=5008.4,5012.4
Exp/Cntr=0.3,0.1

Type RM Length L Ch R = 1,5797,422,422,422
BEGIN DESCRIPTION:
Stream0023_DS 13.0
END DESCRIPTION:
XS GIS Cut Line= 3
      2002759.75     13893555.09      2003125.00     13893575.00
      2003370.40     13893121.87
#Sta/Elev= 30
  4639.4 1488.79  4724.7 1485.60  4734.8 1484.20  4754.8 1483.14  4790.3 1482.13
  4859.1 1479.30  4945.1 1475.53  4957.6 1473.80  4975.1 1467.97  4985.2 1465.88
  4993.2 1462.75  4993.4 1462.25  4997.2 1462.75  5002.7 1464.74  5008.0 1464.74
  5013.3 1466.21  5078.9 1466.86  5144.5 1468.91  5153.0 1469.39  5160.7 1471.33
  5166.4 1470.79  5182.6 1473.56  5188.3 1472.13  5198.5 1473.14  5204.4 1474.80
  5221.3 1475.50  5257.9 1475.68  5406.6 1479.32  5516.6 1482.47  5520.5 1482.67
#Mann=10,-1,0
  4639.4   0.035       0  4790.3    0.07       0  4859.1   0.035       0
  4957.6    0.07       0  4993.2    0.05       0  4997.2    0.07       0
  5221.3   0.035       0  5257.9    0.07       0  5406.6   0.035       0
  5516.6    0.07       0
Bank Sta=4993.2,4997.2
Exp/Cntr=0.3,0.1

Type RM Length L Ch R = 1,5375,427,427,427
BEGIN DESCRIPTION:
Stream0023_DS 12.0
END DESCRIPTION:
XS GIS Cut Line= 3
      2002843.09     13893763.44      2003325.00     13893925.00
      2003425.01     13893724.98
#Sta/Elev= 30
  4497.1 1478.71  4521.6 1478.76  4529.7 1478.17  4604.6 1475.55  4615.1 1474.16
  4632.6 1473.26  4679.4 1470.87  4705.6 1470.30  4742.5 1467.46  4774.0 1466.80
  4800.3 1464.23  4805.6 1464.62  4831.8 1461.63  4837.1 1461.66  4868.7 1458.70
  4900.2 1456.98  4926.5 1456.37  4931.8 1454.65  4942.1 1455.32  4958.0 1453.81
  4992.9 1452.11  4993.1 1451.61  4996.6 1451.61  4996.9 1452.11  5002.7 1453.65
  5034.3 1455.50  5072.5 1457.28  5094.8 1459.62  5170.3 1461.98  5229.0 1462.77
#Mann=7,-1,0
  4497.1    0.12       0  4529.7   0.035       0  4615.1    0.07       0
  4632.6    0.12       0  4992.9    0.05       0  4996.9    0.12       0
  5034.3    0.07       0
Bank Sta=4992.9,4996.9
Exp/Cntr=0.3,0.1

Type RM Length L Ch R = 1,4948,491,491,491
BEGIN DESCRIPTION:
Stream0023_DS 11.0
END DESCRIPTION:
XS GIS Cut Line= 3
      2002013.19     13893204.39      2003225.00     13894325.00
      2003424.98     13894175.02
#Sta/Elev= 30
  3339.2 1522.53  3390.5 1520.29  3439.8 1516.00  3475.5 1515.20  3539.0 1509.35
  3579.7 1510.30  3603.9 1506.22  3785.4 1497.54  3892.9 1491.82  3925.6 1491.54
  4055.6 1485.47  4183.2 1482.29  4246.7 1478.67  4338.5 1478.16  4456.9 1472.57
  4632.7 1464.74  4646.0 1464.21  4720.7 1459.90  4749.0 1454.43  4982.6 1442.95
  4986.3 1440.01  5001.3 1439.56  5001.5 1439.06  5005.3 1439.56  5011.6 1441.82
  5017.9 1440.08  5026.2 1442.35  5032.4 1440.78  5047.0 1443.99  5239.7 1450.25
#Mann=10,-1,0
  3339.2    0.07       0  3579.7   0.035       0  3603.9    0.12       0
  3785.4    0.07       0  3925.6    0.12       0  4456.9    0.07       0
  4632.7    0.12       0  4646.0    0.07       0  5001.3    0.05       0
  5005.3    0.07       0
Bank Sta=5001.3,5005.3
Exp/Cntr=0.3,0.1

Type RM Length L Ch R = 1,4457,470,470,470
BEGIN DESCRIPTION:
Stream0023_DS 10.0
END DESCRIPTION:
XS GIS Cut Line= 3
      2002367.35     13895457.88      2003375.00     13894725.00
      2003502.78     13894280.80
#Sta/Elev= 30
  3759.6 1495.05  3798.3 1493.95  3859.9 1492.80  3889.3 1486.29  3994.0 1480.97
  4170.5 1471.05  4247.1 1467.83  4405.9 1457.71  4458.5 1454.95  4519.1 1452.95
  4566.3 1448.35  4575.5 1448.76  4583.2 1446.63  4696.9 1442.59  4733.5 1442.79
  4832.7 1438.34  4886.9 1436.22  4933.3 1433.81  4975.4 1428.65  4975.6 1428.15
  4979.4 1428.65  4983.6 1430.07  5002.3 1429.50  5012.2 1429.36  5036.8 1432.48
  5133.4 1434.54  5161.7 1437.96  5224.1 1437.49  5273.9 1440.55  5467.8 1444.74
#Mann=15,-1,0
  3759.6    0.12       0  3798.3    0.07       0  3994.0   0.035       0
  4170.5    0.07       0  4405.9    0.12       0  4458.5   0.035       0
  4566.3    0.07       0  4583.2   0.035       0  4832.7    0.12       0
  4886.9   0.035       0  4975.4   0.035       0  4979.4   0.035       0
  5002.3    0.07       0  5012.2   0.035       0  5133.4    0.07       0
Bank Sta=4975.4,4979.4
Exp/Cntr=0.3,0.1

Type RM Length L Ch R = 1,3987,419,419,419
BEGIN DESCRIPTION:
Stream0023_DS 9.0
END DESCRIPTION:
XS GIS Cut Line= 3
      2003575.02     13895024.99      2003775.00     13894925.00
      2003924.99     13894775.01
#Sta/Elev= 30
  4771.4 1431.32  4774.2 1431.32  4779.8 1432.43  4785.4 1431.31  4793.7 1431.22
  4824.5 1428.96  4860.8 1428.23  4869.2 1428.45  4897.2 1426.50  4919.5 1425.71
  4957.7 1424.99  4981.0 1424.33  4986.6 1423.70  4992.2 1421.95  4998.5 1421.95
  5007.1 1420.83  5007.4 1420.33  5010.9 1420.33  5011.1 1420.83  5017.4 1421.27
  5037.4 1421.95  5051.6 1421.79  5065.8 1422.41  5079.8 1423.16  5094.0 1422.58
  5122.3 1429.68  5136.4 1430.74  5150.5 1431.06  5178.8 1434.52  5207.1 1434.47
#Mann=6,-1,0
  4771.4    0.07       0  4957.7    0.12       0  5007.1    0.05       0
  5011.1    0.12       0  5017.4   0.035       0  5065.8    0.12       0
Bank Sta=5007.1,5011.1
Exp/Cntr=0.3,0.1

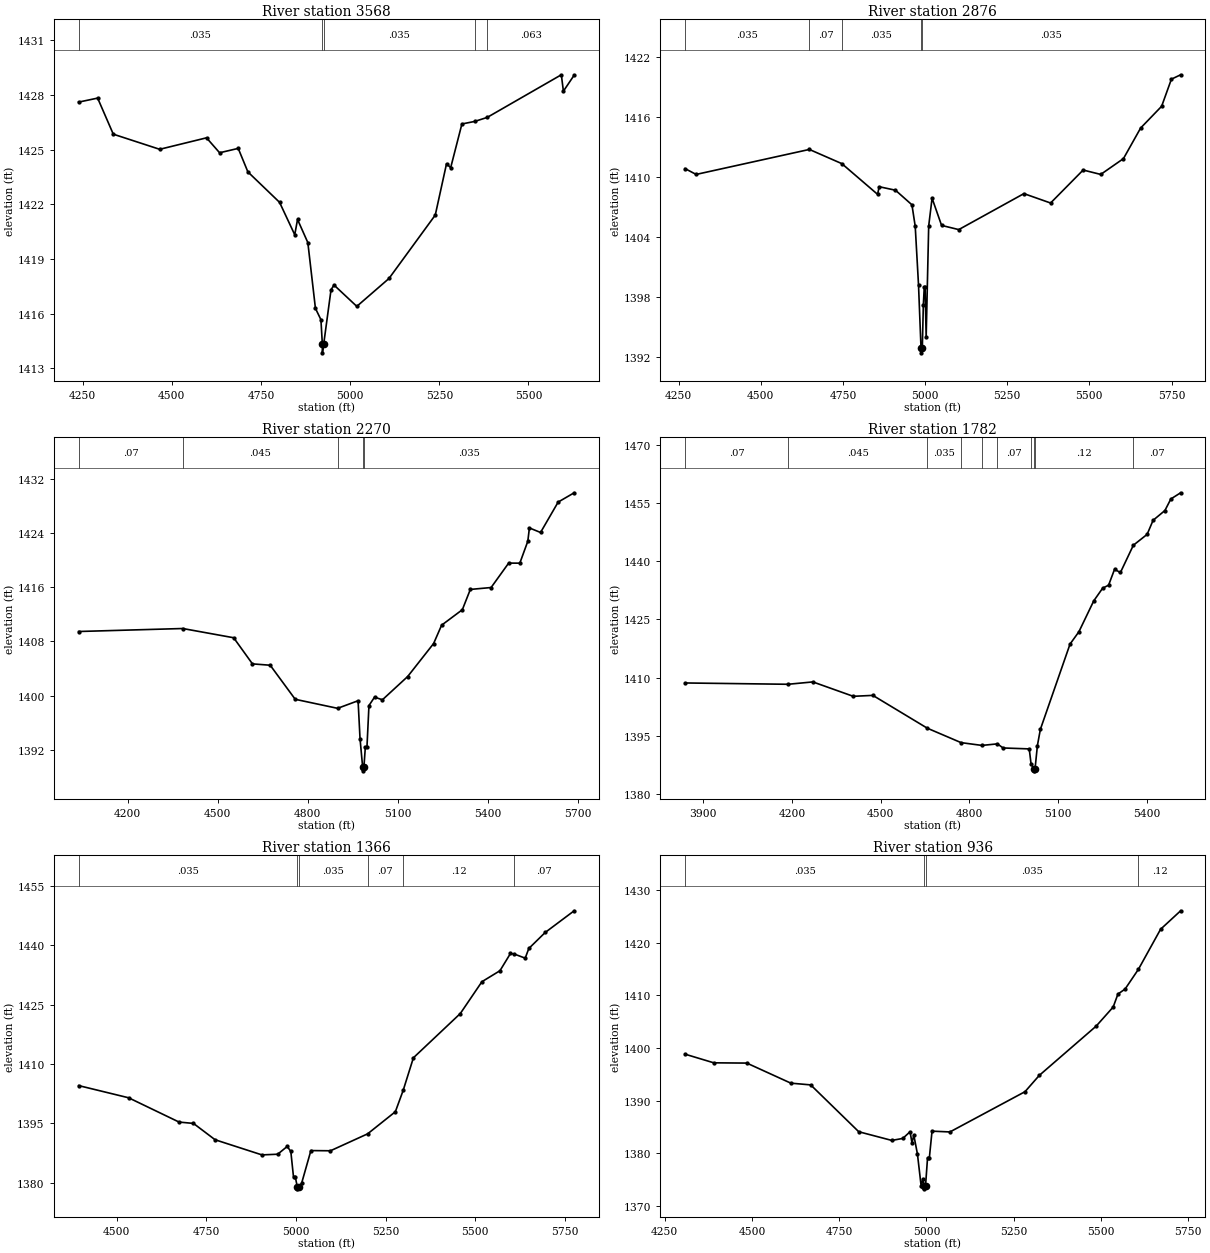
Type RM Length L Ch R = 1,3568,692,692,692
BEGIN DESCRIPTION:
Stream0023_DS 8.0
END DESCRIPTION:
XS GIS Cut Line= 3
      2003723.56     13895777.83      2004125.00     13895125.00
      2004435.63     13894584.83
#Sta/Elev= 30
  4238.6 1427.61  4291.9 1427.83  4335.8 1425.85  4465.9 1425.02  4597.2 1425.65
  4633.9 1424.83  4686.1 1425.07  4713.2 1423.78  4802.0 1422.11  4844.6 1420.33
  4852.4 1421.17  4881.3 1419.90  4902.6 1416.29  4918.0 1415.67  4921.9 1414.35
  4922.1 1413.85  4925.9 1414.35  4946.3 1417.31  4954.7 1417.57  5018.6 1416.40
  5108.8 1417.93  5238.6 1421.41  5270.2 1424.23  5281.8 1424.01  5313.3 1426.41
  5349.2 1426.55  5384.2 1426.77  5592.1 1429.11  5597.9 1428.21  5628.1 1429.09
#Mann=5,-1,0
  4238.6   0.035       0  4921.9   0.035       0  4925.9   0.035       0
  5349.2    0.07       0  5384.2   0.063       0
Bank Sta=4921.9,4925.9
Exp/Cntr=0.3,0.1

Type RM Length L Ch R = 1,2876,606,606,606
BEGIN DESCRIPTION:
Stream0023_DS 6.0
END DESCRIPTION:
XS GIS Cut Line= 3
      2004732.43     13896003.58      2004679.58     13895275.09
      2004990.25     13894562.03
#Sta/Elev= 30
  4269.6 1410.84  4303.2 1410.26  4647.8 1412.76  4746.6 1411.34  4855.4 1408.27
  4860.4 1409.03  4909.9 1408.68  4960.0 1407.22  4970.0 1405.07  4980.0 1399.22
  4987.6 1392.91  4987.9 1392.41  4991.6 1392.91  4994.7 1397.19  4997.5 1398.98
  5000.0 1398.98  5003.3 1393.99  5011.0 1405.11  5021.3 1407.88  5050.2 1405.16
  5102.5 1404.74  5300.8 1408.34  5382.0 1407.40  5481.1 1410.70  5534.6 1410.26
  5603.7 1411.84  5656.0 1414.90  5720.0 1417.08  5749.7 1419.79  5777.8 1420.23
#Mann=5,-1,0
  4269.6   0.035       0  4647.8    0.07       0  4746.6   0.035       0
  4987.6   0.035       0  4991.6   0.035       0
Bank Sta=4987.6,4991.6
Exp/Cntr=0.3,0.1

Type RM Length L Ch R = 1,2270,488,488,488
BEGIN DESCRIPTION:
Stream0023_DS 5.0
END DESCRIPTION:
XS GIS Cut Line= 3
      2004862.16     13895973.49      2005225.00     13895075.00
      2005013.75     13894428.31
#Sta/Elev= 30
  4037.2 1409.47  4383.7 1409.91  4553.2 1408.55  4615.7 1404.70  4674.8 1404.50
  4758.1 1399.48  4899.1 1398.15  4967.3 1399.27  4973.8 1393.67  4982.6 1389.44
  4982.9 1388.94  4986.6 1389.44  4991.4 1392.40  4996.8 1392.41  5003.5 1398.56
  5022.1 1399.80  5048.3 1399.41  5132.4 1402.84  5218.7 1407.70  5245.3 1410.40
  5314.3 1412.68  5340.9 1415.67  5410.0 1415.95  5468.5 1419.55  5505.6 1419.54
  5532.2 1422.77  5537.5 1424.73  5574.6 1424.06  5633.2 1428.54  5686.5 1429.91
#Mann=5,-1,0
  4037.2    0.07       0  4383.7   0.045       0  4899.1   0.035       0
  4982.6   0.035       0  4986.6   0.035       0
Bank Sta=4982.6,4986.6
Exp/Cntr=0.3,0.1

Type RM Length L Ch R = 1,1782,416,416,416
BEGIN DESCRIPTION:
Stream0023_DS 4.0
END DESCRIPTION:
XS GIS Cut Line= 3
      2005039.25     13896046.40      2005675.00     13895075.00
      2005711.12     13894562.01
#Sta/Elev= 30
  3839.0 1408.59  4187.0 1408.25  4270.9 1408.86  4407.4 1405.14  4473.8 1405.38
  4657.8 1396.90  4771.9 1393.17  4842.4 1392.45  4894.7 1392.85  4914.0 1391.79
  5002.4 1391.55  5008.4 1387.76  5018.0 1386.38  5018.2 1385.88  5022.0 1386.38
  5030.0 1392.42  5040.0 1396.60  5140.3 1418.64  5170.4 1421.84  5220.5 1429.81
  5250.6 1433.09  5270.6 1433.86  5290.7 1437.94  5310.7 1437.14  5354.3 1444.18
  5400.9 1446.99  5421.0 1450.62  5461.1 1453.16  5481.1 1456.14  5514.2 1457.74
#Mann=10,-1,0
  3839.0    0.07       0  4187.0   0.045       0  4657.8   0.035       0
  4771.9   0.045       0  4842.4   0.035       0  4894.7    0.07       0
  5008.4    0.12       0  5018.0    0.05       0  5022.0    0.12       0
  5354.3    0.07       0
Bank Sta=5018,5022
Exp/Cntr=0.3,0.1

Type RM Length L Ch R = 1,1366,430,430,430
BEGIN DESCRIPTION:
Stream0023_DS 3.0
END DESCRIPTION:
XS GIS Cut Line= 3
      2005862.16     13895973.52      2005925.00     13895375.00
      2005841.40     13894599.20
#Sta/Elev= 30
  4393.8 1404.55  4533.1 1401.48  4673.9 1395.35  4714.1 1395.01  4774.4 1390.89
  4905.1 1387.07  4949.0 1387.24  4975.5 1389.20  4985.6 1387.94  4993.1 1381.49
  4998.1 1381.49  5003.7 1379.01  5003.9 1378.51  5007.7 1379.01  5015.7 1379.91
  5041.6 1388.16  5096.2 1388.11  5199.8 1392.38  5277.2 1397.96  5299.0 1403.35
  5327.5 1411.56  5458.3 1422.72  5518.6 1430.75  5568.9 1433.52  5598.2 1437.87
  5608.2 1437.75  5639.3 1436.69  5649.4 1439.13  5695.1 1443.17  5775.9 1448.64
#Mann=6,-1,0
  4393.8   0.035       0  5003.7   0.035       0  5007.7   0.035       0
  5199.8    0.07       0  5299.0    0.12       0  5608.2    0.07       0
Bank Sta=5003.7,5007.7
Exp/Cntr=0.3,0.1

Type RM Length L Ch R = 1,936,423,423,423
BEGIN DESCRIPTION:
Stream0023_DS 2.0
END DESCRIPTION:
XS GIS Cut Line= 3
      2006103.31     13896036.23      2006325.00     13895375.00
      2006168.52     13894669.55
#Sta/Elev= 30
  4308.5 1398.85  4390.7 1397.21  4485.3 1397.16  4611.5 1393.35  4668.4 1393.02
  4806.1 1384.13  4900.8 1382.48  4932.3 1382.86  4953.2 1384.13  4958.6 1382.03
  4963.9 1383.47  4974.3 1379.90  4984.8 1373.88  4990.1 1375.20  4993.4 1373.79
  4993.7 1373.29  4997.4 1373.79  5003.3 1379.22  5008.5 1379.22  5016.1 1384.24
  5067.4 1384.09  5282.5 1391.73  5323.4 1394.82  5486.5 1404.18  5535.2 1407.80
  5548.8 1410.26  5569.3 1411.21  5607.5 1414.96  5671.0 1422.56  5728.5 1426.07
#Mann=4,-1,0
  4308.5   0.035       0  4993.4   0.035       0  4997.4   0.035       0
  5607.5    0.12       0
Bank Sta=4993.4,4997.4
Exp/Cntr=0.3,0.1

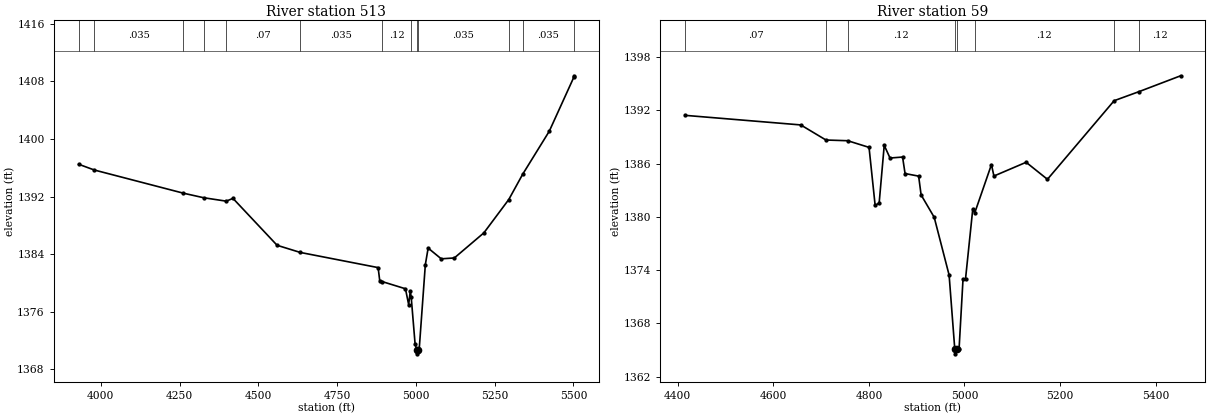
Type RM Length L Ch R = 1,513,454,454,454
BEGIN DESCRIPTION:
Stream0023_DS 1.0
END DESCRIPTION:
XS GIS Cut Line= 4
      2006210.07     13896137.83      2006631.95     13895390.42
      2006675.00     13895175.00      2006541.14     13894698.90
#Sta/Elev= 30
  3929.7 1396.50  3979.4 1395.70  4262.0 1392.48  4326.1 1391.85  4398.3 1391.37
  4419.4 1391.76  4559.5 1385.24  4632.8 1384.25  4880.1 1382.14  4885.3 1380.28
  4893.5 1380.19  4966.8 1379.20  4977.0 1377.00  4982.1 1378.89  4985.1 1378.01
  4997.4 1371.52  5003.1 1370.66  5003.3 1370.16  5007.1 1370.66  5010.2 1370.66
  5029.9 1382.55  5038.8 1384.85  5080.4 1383.36  5121.9 1383.48  5215.7 1386.97
  5294.7 1391.60  5338.8 1395.11  5423.1 1401.08  5500.9 1408.57  5502.2 1408.79
#Mann=13,-1,0
  3929.7   0.045       0  3979.4   0.035       0  4262.0    0.07       0
  4326.1   0.035       0  4398.3    0.07       0  4632.8   0.035       0
  4893.5    0.12       0  4985.1   0.035       0  5003.1   0.035       0
  5007.1   0.035       0  5294.7    0.07       0  5338.8   0.035       0
  5500.9    0.12       0
Bank Sta=5003.1,5007.1
Exp/Cntr=0.3,0.1

Type RM Length L Ch R = 1,59,0,0,0
BEGIN DESCRIPTION:
Stream0023_DS 0.0
END DESCRIPTION:
XS GIS Cut Line= 5
      2006730.73     13895778.76      2006878.34     13895352.96
      2006915.52     13895224.18      2006876.11     13895085.95
      2006700.46     13894832.03
#Sta/Elev= 30
  4415.3 1391.45  4657.4 1390.37  4710.1 1388.67  4755.7 1388.59  4800.3 1387.84
  4813.1 1381.29  4821.5 1381.58  4832.1 1388.07  4844.2 1386.64  4870.5 1386.75
  4875.7 1384.89  4904.1 1384.60  4909.3 1382.48  4936.7 1379.96  4967.9 1373.45
  4979.8 1365.07  4980.1 1364.57  4983.8 1365.07  4988.7 1365.09  4997.0 1372.98
  5002.2 1372.98  5017.4 1380.88  5021.5 1380.45  5056.5 1385.90  5061.7 1384.61
  5129.1 1386.16  5173.7 1384.24  5313.3 1393.10  5365.7 1394.13  5452.5 1395.91
#Mann=8,-1,0
  4415.3    0.07       0  4710.1   0.035       0  4755.7    0.12       0
  4979.8    0.05       0  4983.8    0.12       0  5021.5    0.12       0
  5313.3    0.07       0  5365.7    0.12       0
Bank Sta=4979.8,4983.8
Exp/Cntr=0.3,0.1

Chan Stop Cuts=-1