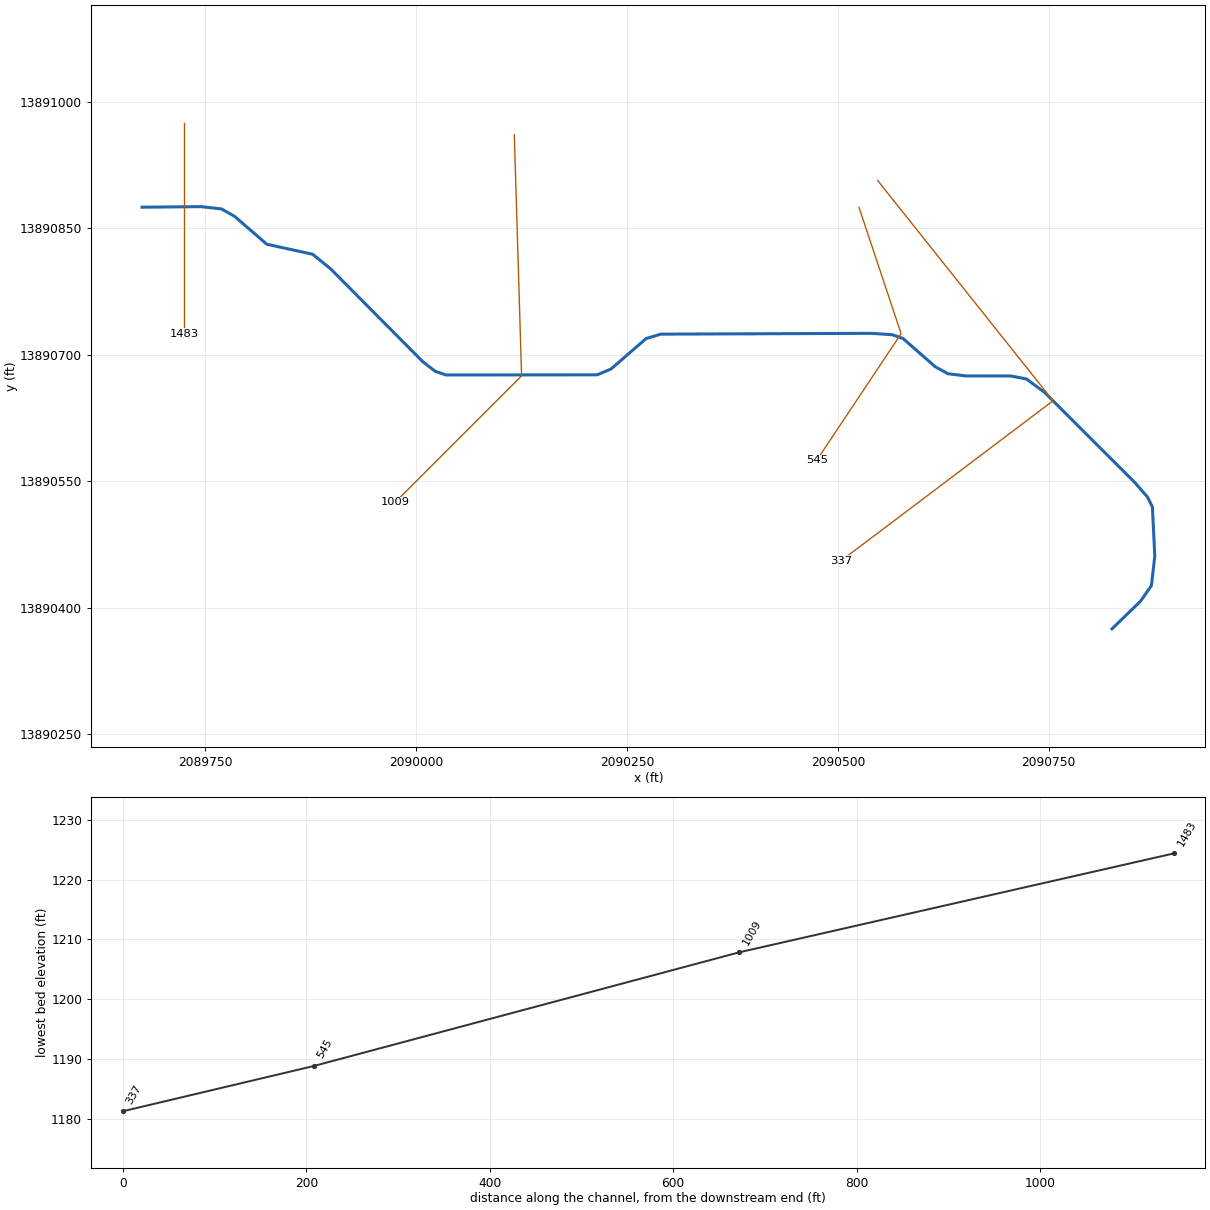
--- Stream0024_DS.prj (project) ---

Proj Title=Stream0024_DS Base Level Engineering
Current Plan=p01
Default Exp/Contr=0.3,0.1
English Units
Geom File=g01
Flow File=f01
Plan File=p01
BEGIN DESCRIPTION:
Stream0024_DS
END DESCRIPTION:

--- Stream0024_DS.p01 (plan) ---

Plan Title=Multiple Run
Short Identifier=Multiple
Geom File=g01
Flow File=f01
Subcritical Flow
K Sum by GR= 0
Std Step Tol= 0.01
Critical Tol= 0.01
Num of Std Step Trials= 20
Max Error Tol= 0.3
Flow Tol Ratio= 0.001
Split Flow NTrial= 30
Split Flow Tol= 0.02
Split Flow Ratio= 0.02
Log Output Level= 0
Friction Slope Method= 1
Unsteady Friction Slope Method= 2
Unsteady Bridges Friction Slope Method= 1
Parabolic Critical Depth
Global Vel Dist=  1 , 1 , 1
Global Log Level= 0
CheckData=True
Encroach Param= -1, 0, 0, 0
BEGIN DESCRIPTION:
Multiple Run
END DESCRIPTION:

--- Stream0024_DS.f01 (steady flow) ---

Flow Title=Multiple
Number of Profiles=7
Profile Names=10-year,25-year,50-year,1pct_min,100-year,1pct_plu,500-year
River Rch & RM= Stream0024_DS,Reach-1,1483
     324     508     672     434     865    1726    1412
Boundary for River Rch & Prof#=Stream0024_DS,Reach-1,1
Up Type=0
Dn Type=3
Dn Slope=0.005
Boundary for River Rch & Prof#=Stream0024_DS,Reach-1,2
Up Type=0
Dn Type=3
Dn Slope=0.005
Boundary for River Rch & Prof#=Stream0024_DS,Reach-1,3
Up Type=0
Dn Type=3
Dn Slope=0.005
Boundary for River Rch & Prof#=Stream0024_DS,Reach-1,4
Up Type=0
Dn Type=3
Dn Slope=0.005
Boundary for River Rch & Prof#=Stream0024_DS,Reach-1,5
Up Type=0
Dn Type=3
Dn Slope=0.005
Boundary for River Rch & Prof#=Stream0024_DS,Reach-1,6
Up Type=0
Dn Type=3
Dn Slope=0.005
Boundary for River Rch & Prof#=Stream0024_DS,Reach-1,7
Up Type=0
Dn Type=3
Dn Slope=0.005

--- Stream0024_DS.g01 (geometry) ---

Geom Title=Existing Conditions

River Reach=Stream0024_DS,Reach-1
Reach XY= 30
      2089675.00     13890875.00      2089745.27     13890875.64
      2089769.14     13890872.93      2089784.67     13890864.21
      2089822.82     13890831.11      2089877.30     13890819.17
      2089898.47     13890801.99      2090008.24     13890691.43
      2090022.55     13890680.46      2090035.43     13890676.05
      2090214.49     13890676.22      2090231.06     13890683.14
      2090272.67     13890719.25      2090290.22     13890724.48
      2090540.18     13890725.43      2090564.50     13890723.78
      2090577.34     13890719.26      2090615.37     13890685.90
      2090630.57     13890677.47      2090652.25     13890674.94
      2090704.95     13890674.87      2090723.50     13890671.39
      2090745.16     13890655.37      2090852.16     13890548.53
      2090867.24     13890531.18      2090872.94     13890519.53
      2090875.77     13890461.34      2090871.82     13890426.41
      2090858.96     13890407.95      2090825.00     13890375.00

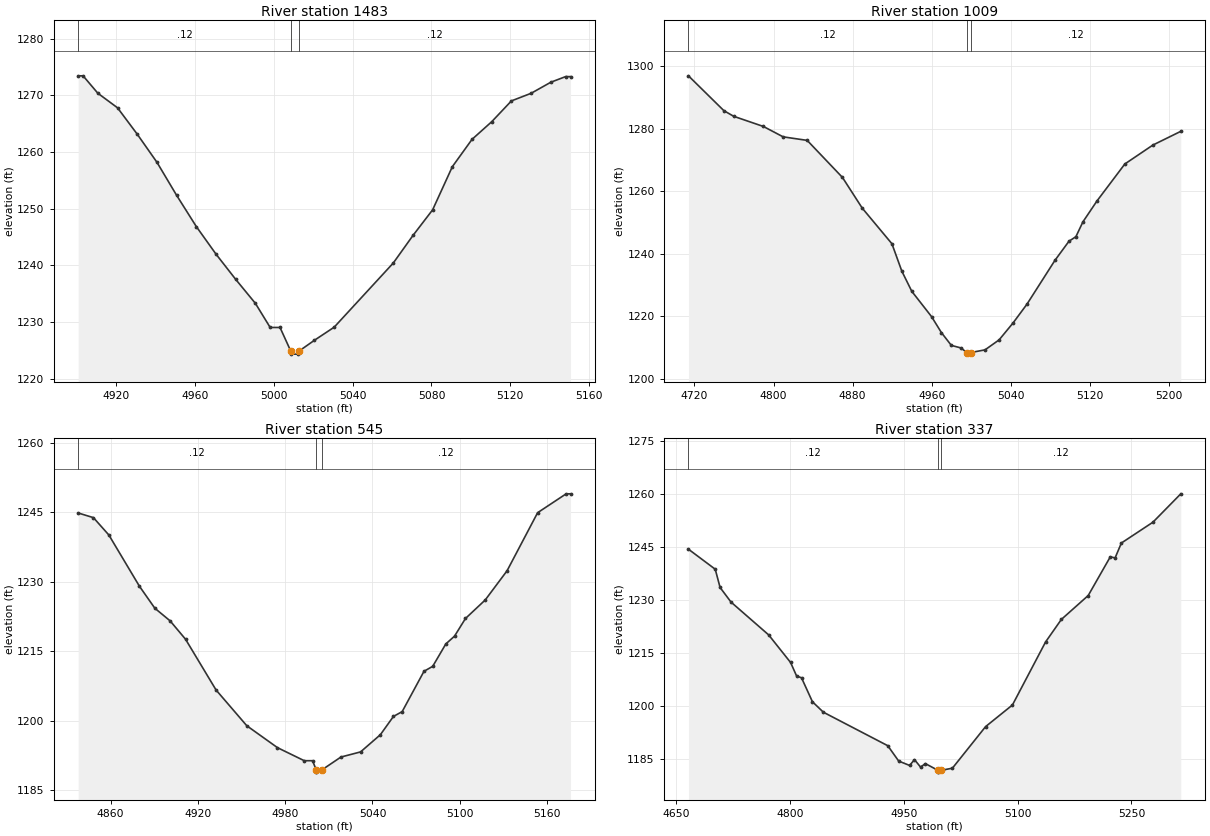
Type RM Length L Ch R = 1,1483,474,474,474
BEGIN DESCRIPTION:
Stream0024_DS 3.0
END DESCRIPTION:
XS GIS Cut Line= 3
      2089725.00     13890975.03      2089725.00     13890875.00
      2089725.00     13890725.03
#Sta/Elev= 30
  4900.6 1273.43  4903.1 1273.43  4910.6 1270.36  4920.6 1267.79  4930.6 1263.14
  4940.6 1258.19  4950.6 1252.36  4960.6 1246.85  4970.6 1241.99  4980.6 1237.54
  4990.6 1233.31  4998.1 1229.06  5003.1 1229.06  5008.6 1224.86  5008.9 1224.36
  5012.4 1224.36  5012.6 1224.86  5020.6 1226.81  5030.6 1229.11  5060.6 1240.42
  5070.6 1245.28  5080.6 1249.81  5090.6 1257.41  5100.6 1262.23  5110.6 1265.34
  5120.6 1269.01  5130.6 1270.35  5140.6 1272.30  5148.1 1273.29  5150.6 1273.29
#Mann=3,-1,0
  4900.6    0.12       0  5008.6    0.05       0  5012.6    0.12       0
Bank Sta=5008.6,5012.6
Exp/Cntr=0.3,0.1

Type RM Length L Ch R = 1,1009,464,464,464
BEGIN DESCRIPTION:
Stream0024_DS 2.0
END DESCRIPTION:
XS GIS Cut Line= 3
      2090116.41     13890960.75      2090125.00     13890675.00
      2089975.01     13890525.01
#Sta/Elev= 30
  4713.9 1296.99  4749.7 1285.84  4759.7 1284.02  4789.7 1280.77  4809.7 1277.44
  4834.0 1276.31  4869.7 1264.43  4889.7 1254.60  4919.7 1243.20  4929.7 1234.44
  4939.8 1227.96  4959.8 1219.85  4969.8 1214.72  4979.8 1210.64  4989.8 1209.80
  4995.3 1208.34  4995.5 1207.84  4999.3 1208.34  5013.9 1209.21  5028.1 1212.40
  5042.2 1217.81  5056.3 1223.84  5084.6 1237.88  5098.8 1244.01  5105.8 1245.46
  5112.9 1250.21  5127.1 1256.90  5155.3 1268.75  5183.6 1274.80  5211.9 1279.21
#Mann=3,-1,0
  4713.9    0.12       0  4995.3    0.05       0  4999.3    0.12       0
Bank Sta=4995.3,4999.3
Exp/Cntr=0.3,0.1

Type RM Length L Ch R = 1,545,208,208,208
BEGIN DESCRIPTION:
Stream0024_DS 1.0
END DESCRIPTION:
XS GIS Cut Line= 3
      2090525.01     13890874.97      2090575.00     13890725.00
      2090474.98     13890574.97
#Sta/Elev= 30
  4837.7 1244.87  4848.2 1243.86  4858.8 1240.11  4879.8 1229.04  4890.4 1224.28
  4900.9 1221.55  4911.5 1217.58  4932.5 1206.60  4953.6 1198.88  4974.7 1194.14
  4993.1 1191.32  4998.8 1191.32  5001.3 1189.35  5001.5 1188.85  5005.3 1189.35
  5018.3 1192.11  5031.8 1193.22  5045.4 1196.93  5054.4 1200.89  5060.4 1201.93
  5075.4 1210.65  5081.4 1211.72  5090.4 1216.56  5096.4 1218.25  5103.9 1222.06
  5117.5 1226.07  5132.5 1232.38  5153.5 1244.93  5173.1 1249.01  5176.1 1249.01
#Mann=3,-1,0
  4837.7    0.12       0  5001.3    0.05       0  5005.3    0.12       0
Bank Sta=5001.3,5005.3
Exp/Cntr=0.3,0.1

Type RM Length L Ch R = 1,337,0,0,0
BEGIN DESCRIPTION:
Stream0024_DS 0.0
END DESCRIPTION:
XS GIS Cut Line= 3
      2090547.23     13890906.58      2090755.20     13890645.48
      2090503.69     13890455.66
#Sta/Elev= 30
  4666.2 1244.42  4701.5 1238.75  4707.9 1233.58  4722.3 1229.45  4771.9 1220.16
  4800.8 1212.35  4808.8 1208.49  4815.2 1208.02  4829.6 1201.23  4844.0 1198.27
  4928.9 1188.78  4943.3 1184.43  4957.7 1183.19  4964.1 1184.84  4972.1 1182.73
  4978.5 1183.71  4995.1 1181.80  4995.4 1181.30  4999.1 1181.80  5014.1 1182.42
  5057.8 1194.18  5093.2 1200.31  5136.9 1218.16  5157.7 1224.54  5193.1 1231.31
  5222.2 1242.27  5228.5 1241.95  5236.8 1246.17  5278.4 1252.07  5315.1 1260.10
#Mann=3,-1,0
  4666.2    0.12       0  4995.1    0.05       0  4999.1    0.12       0
Bank Sta=4995.1,4999.1
Exp/Cntr=0.3,0.1

Chan Stop Cuts=-1