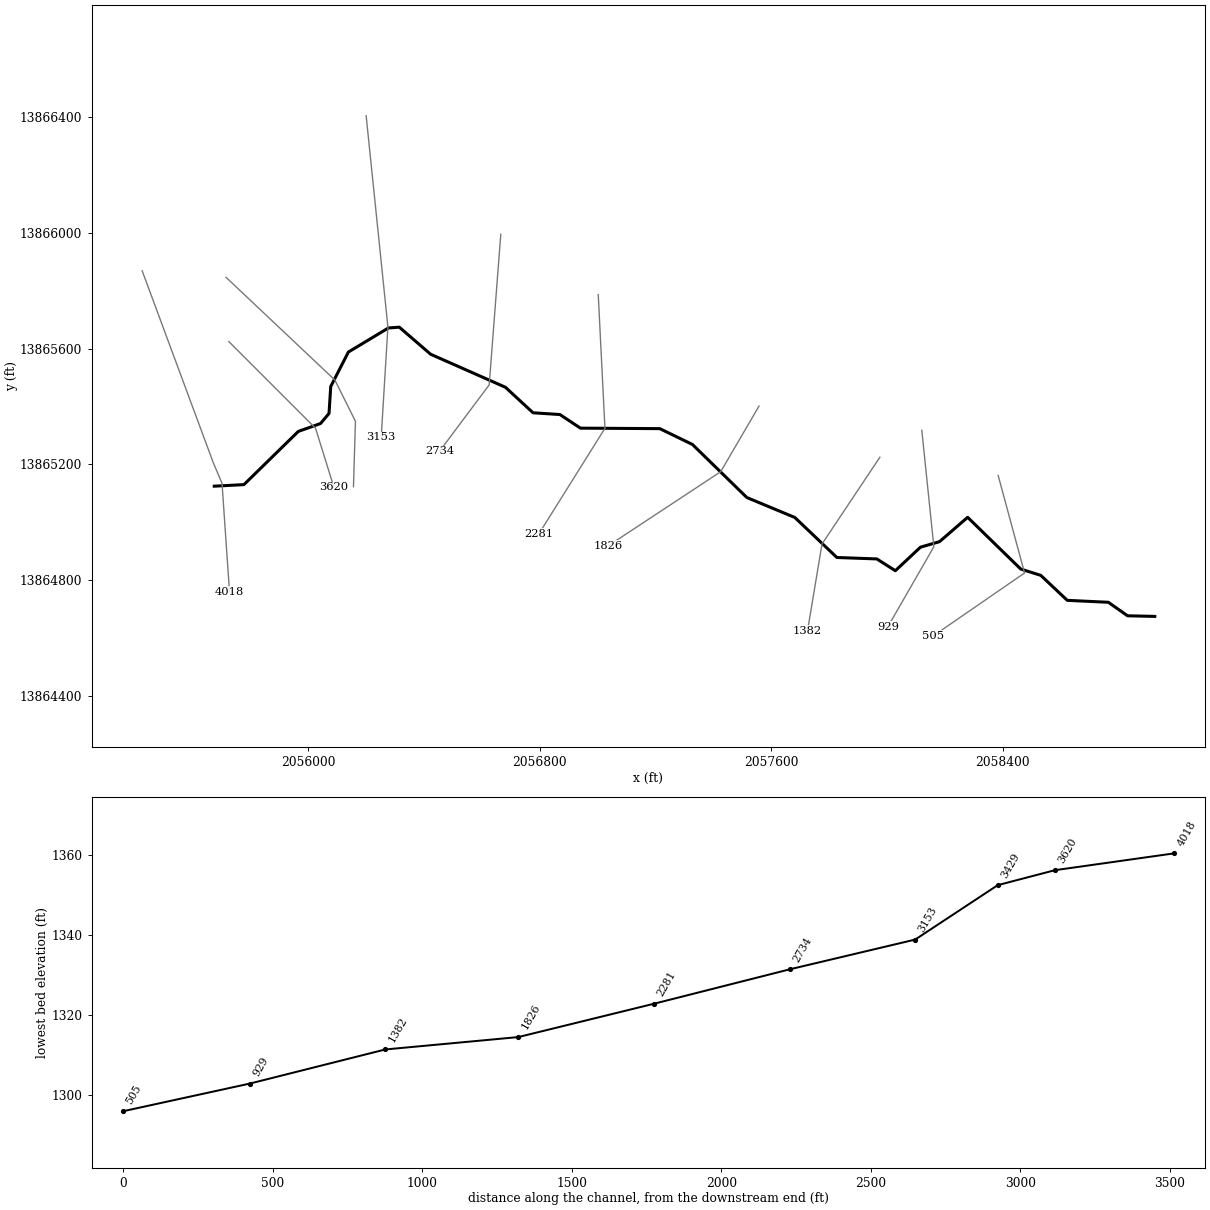
--- Stream0025_DS.prj (project) ---

Proj Title=Stream0025_DS Base Level Engineering
Current Plan=p01
Default Exp/Contr=0.3,0.1
English Units
Geom File=g01
Flow File=f01
Plan File=p01
Y Axis Title=Elevation
X Axis Title(PF)=Main Channel Distance
X Axis Title(XS)=Station
BEGIN DESCRIPTION:
Stream0025_DS
END DESCRIPTION:
DSS Export Rating Curves= 0
DSS Export Rating Curve Sorted= 0
DSS Export Volume Flow Curves= 0
DXF OffsetX= 0
DXF OffsetY= 0
DXF ScaleX= 1
DXF ScaleY= 10

--- Stream0025_DS.p01 (plan) ---

Plan Title=Multiple Run
Short Identifier=Multiple
Geom File=g01
Flow File=f01
Subcritical Flow
K Sum by GR= 0
Std Step Tol= 0.01
Critical Tol= 0.01
Num of Std Step Trials= 20
Max Error Tol= 0.3
Flow Tol Ratio= 0.001
Split Flow NTrial= 30
Split Flow Tol= 0.02
Split Flow Ratio= 0.02
Log Output Level= 0
Friction Slope Method= 1
Unsteady Friction Slope Method= 2
Unsteady Bridges Friction Slope Method= 1
Parabolic Critical Depth
Global Vel Dist=  1 , 1 , 1
Global Log Level= 0
CheckData=True
Encroach Param= -1, 0, 0, 0
BEGIN DESCRIPTION:
Multiple Run
END DESCRIPTION:

--- Stream0025_DS.f01 (steady flow) ---

Flow Title=Multiple
Number of Profiles=7
Profile Names=10-year,25-year,50-year,1pct_min,100-year,1pct_plu,500-year
River Rch & RM= Stream0025_DS,Reach-1,4018
     786    1299    1778    1182    2358    4704    4092
River Rch & RM= Stream0025_DS,Reach-1,3620
    1186    2009    2793    1882    3755    7493    6712
Boundary for River Rch & Prof#=Stream0025_DS,Reach-1,1
Up Type=0
Dn Type=3
Dn Slope=0.005
Boundary for River Rch & Prof#=Stream0025_DS,Reach-1,2
Up Type=0
Dn Type=3
Dn Slope=0.005
Boundary for River Rch & Prof#=Stream0025_DS,Reach-1,3
Up Type=0
Dn Type=3
Dn Slope=0.005
Boundary for River Rch & Prof#=Stream0025_DS,Reach-1,4
Up Type=0
Dn Type=3
Dn Slope=0.005
Boundary for River Rch & Prof#=Stream0025_DS,Reach-1,5
Up Type=0
Dn Type=3
Dn Slope=0.005
Boundary for River Rch & Prof#=Stream0025_DS,Reach-1,6
Up Type=0
Dn Type=3
Dn Slope=0.005
Boundary for River Rch & Prof#=Stream0025_DS,Reach-1,7
Up Type=0
Dn Type=3
Dn Slope=0.005

--- Stream0025_DS.g01 (geometry) ---

Geom Title=Existing Conditions
Program Version=4.10

River Reach=Stream0025_DS   ,Reach-1
Reach XY= 30
        2055675.       13865125.       2055777.5     13865130.35
      2055965.34     13865314.21      2056042.13     13865341.46
      2056071.48     13865376.28      2056077.45     13865469.44
      2056138.47     13865588.57      2056276.73     13865671.69
      2056314.37      13865674.4      2056422.71     13865580.85
      2056681.05     13865466.84       2056776.5     13865378.62
      2056869.43     13865372.53      2056940.22     13865325.52
       2057214.5      13865323.8       2057327.3     13865269.17
      2057515.32     13865085.76      2057681.06     13865016.86
      2057826.47     13864878.54      2057964.56      13864873.6
      2058028.41     13864832.81      2058115.32     13864914.18
      2058181.05      13864933.2      2058278.34      13865017.4
      2058461.79     13864838.63      2058531.04     13864816.82
      2058622.56     13864730.48       2058764.5     13864723.79
      2058830.87      13864677.1        2058925.       13864675.

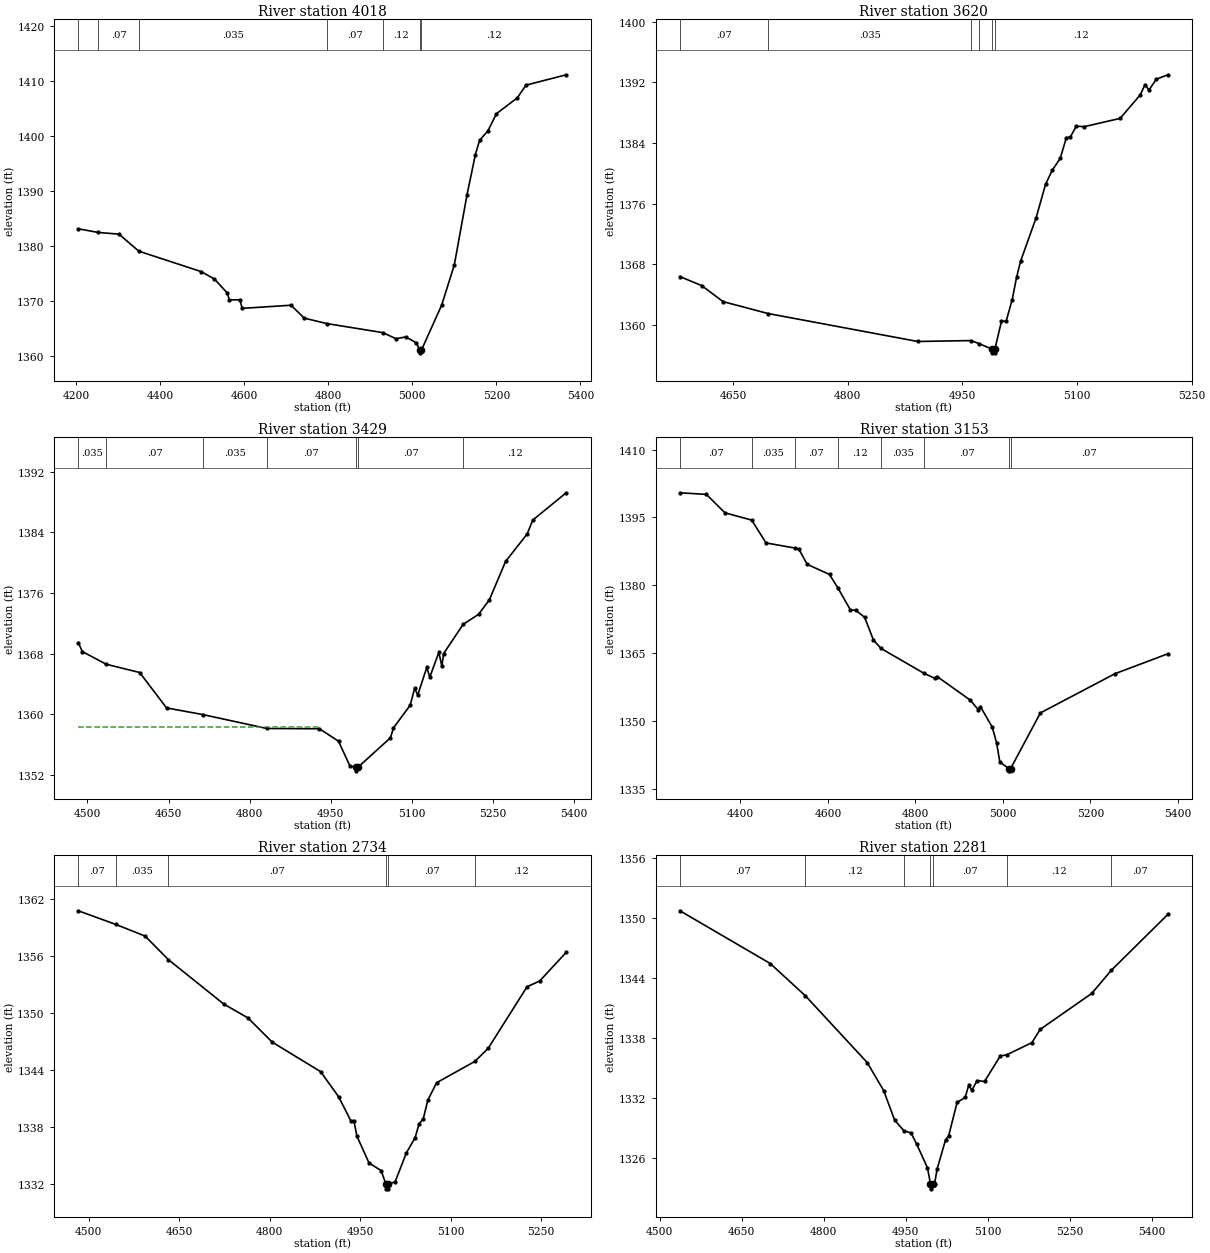
Type RM Length L Ch R = 1 ,4018    ,398,398,398
BEGIN DESCRIPTION:
Stream0025_DS 9.0
END DESCRIPTION:
XS GIS Cut Line= 4
      2055425.83     13865869.24      2055671.52     13865206.16
      2055701.75     13865134.87      2055727.67     13864759.43
#Sta/Elev= 30
  4205.2 1383.05    4253 1382.38    4302 1382.08  4349.3 1378.98  4497.7 1375.26
  4529.1 1373.92  4559.4  1371.4  4564.8 1370.13  4589.8 1370.12  4595.2 1368.58
  4711.4 1369.15  4742.9  1366.8  4796.7 1365.81  4929.6 1364.17  4961.1 1363.06
  4984.7 1363.39  5009.7 1362.29  5017.7 1360.99    5018 1360.49  5021.7 1360.99
  5069.8 1369.16  5099.9 1376.48    5130 1389.18    5150 1396.55    5160 1399.13
  5180.1  1400.9  5200.1 1403.98    5250 1406.88  5270.3 1409.17  5366.1 1411.06
#Mann= 7 ,-1 , 0
  4205.2     .12       0    4253     .07       0  4349.3    .035       0
  4796.7     .07       0  4929.6     .12       0  5017.7     .05       0
  5021.7     .12       0
Bank Sta=5017.7,5021.7
XS Rating Curve= 0 ,0
Exp/Cntr=0.3,0.1

Type RM Length L Ch R = 1 ,3620    ,191,191,191
BEGIN DESCRIPTION:
Stream0025_DS 8.0
END DESCRIPTION:
XS GIS Cut Line= 3
      2055725.02     13865624.98        2056025.       13865325.
      2056088.63      13865120.5
#Sta/Elev= 30
  4580.4 1366.36  4608.7 1365.18  4636.9 1363.05  4695.8 1361.48  4891.5 1357.79
  4961.3 1357.91  4971.9  1357.5  4988.5 1356.79  4988.7 1356.29  4992.2 1356.29
  4992.5 1356.79  5001.1 1360.47  5007.2 1360.47  5015.1 1363.31  5020.9 1366.29
  5026.1 1368.39  5046.5 1374.15  5058.7 1378.53  5067.5 1380.41  5077.9 1381.96
    5086 1384.71  5091.2 1384.79  5098.9 1386.22  5109.4 1386.16  5156.3 1387.25
  5182.7 1390.36  5188.8  1391.7  5194.1 1390.99  5203.6 1392.42  5218.8 1393.01
#Mann= 6 ,-1 , 0
  4580.4     .07       0  4695.8    .035       0  4961.3     .07       0
  4971.9     .12       0  4988.5     .05       0  4992.5     .12       0
Bank Sta=4988.5,4992.5
XS Rating Curve= 0 ,0
Exp/Cntr=0.3,0.1

Type RM Length L Ch R = 1 ,3429    ,276,276,276
BEGIN DESCRIPTION:
Stream0025_DS 7.5
END DESCRIPTION:
XS GIS Cut Line= 4
      2055715.89      13865846.5      2056091.83      13865491.6
      2056162.76     13865349.26      2056155.97       13865123.
#Sta/Elev= 30
    4483 1369.46  4490.6 1368.28  4534.8 1366.61  4596.6 1365.52  4646.3 1360.85
  4713.5 1359.97  4831.6 1358.14  4929.1  1358.1  4964.3 1356.46  4985.7 1353.15
  4996.7 1353.05    4997 1352.55  5000.7 1353.05  5060.4 1356.91    5066 1358.22
  5096.8  1361.2  5105.2 1363.46  5110.8 1362.54  5127.6 1366.19  5133.1  1364.9
  5149.9 1368.18  5155.5 1366.33  5158.6 1368.01  5194.8 1371.87  5223.3 1373.19
  5243.3 1375.11  5273.3 1380.17  5313.4 1383.81  5323.4 1385.62  5385.4 1389.23
#Mann= 7 ,-1 , 0
    4483    .035       0  4534.8     .07       0  4713.5    .035       0
  4831.6     .07       0  4996.7     .05       0  5000.7     .07       0
  5194.8     .12       0
#XS Ineff= 2 , 0
       0 4928.68 1358.37               0
Permanent Ineff=
       F       F
Bank Sta=4996.7,5000.7
XS Rating Curve= 0 ,0
Exp/Cntr=0.3,0.1

Type RM Length L Ch R = 1 ,3153    ,419,419,419
BEGIN DESCRIPTION:
Stream0025_DS 7.0
END DESCRIPTION:
XS GIS Cut Line= 3
      2056199.75      13866405.2        2056275.       13865675.
      2056251.83     13865294.07
#Sta/Elev= 30
  4261.6 1400.43  4322.1 1400.07  4364.5    1396  4425.7 1394.39  4458.5 1389.34
  4524.3 1388.21  4533.2 1388.02  4552.5 1384.62  4603.6 1382.36  4622.9 1379.37
  4651.5 1374.51  4663.9 1374.45    4684 1372.87  4704.1 1367.85  4721.5    1366
  4820.1 1360.48  4844.6 1359.39  4849.6  1359.8  4925.3 1354.59  4943.6 1352.49
  4948.7 1353.14  4975.6 1348.62  4985.6 1345.15  4993.1 1340.87  5013.7 1339.44
  5013.9 1338.94  5017.7 1339.44  5085.8 1351.75  5256.1 1360.41  5377.3 1364.83
#Mann= 8 ,-1 , 0
  4261.6     .07       0  4425.7    .035       0  4524.3     .07       0
  4622.9     .12       0  4721.5    .035       0  4820.1     .07       0
  5013.7     .05       0  5017.7     .07       0
Bank Sta=5013.7,5017.7
XS Rating Curve= 0 ,0
Exp/Cntr=0.3,0.1

Type RM Length L Ch R = 1 ,2734    ,453,453,453
BEGIN DESCRIPTION:
Stream0025_DS 6.0
END DESCRIPTION:
XS GIS Cut Line= 3
      2056665.02     13865995.43        2056625.       13865475.
       2056453.2     13865245.44
#Sta/Elev= 30
  4482.9 1360.73  4545.4 1359.29  4593.7 1358.07  4632.2  1355.6    4724 1350.93
  4764.2 1349.47  4804.3 1346.93  4884.5 1343.83  4914.6 1341.17  4934.7 1338.65
  4939.7 1338.68  4944.7 1337.05  4964.8 1334.23  4984.8 1333.43  4992.8 1332.01
  4993.1 1331.51  4996.6 1331.51  4996.8 1332.01    5008 1332.24  5026.8  1335.3
  5041.3  1336.9  5047.6 1338.31  5054.8 1338.89  5062.2 1340.82  5076.8 1342.66
  5140.2  1344.9  5162.2 1346.27  5226.8 1352.75  5247.6 1353.35  5291.6 1356.36
#Mann= 6 ,-1 , 0
  4482.9     .07       0  4545.4    .035       0  4632.2     .07       0
  4992.8     .05       0  4996.8     .07       0  5140.2     .12       0
Bank Sta=4992.8,4996.8
XS Rating Curve= 0 ,0
Exp/Cntr=0.3,0.1

Type RM Length L Ch R = 1 ,2281    ,455,455,455
BEGIN DESCRIPTION:
Stream0025_DS 5.0
END DESCRIPTION:
XS GIS Cut Line= 3
      2057001.83     13865787.12        2057025.       13865325.
      2056796.99     13864960.78
#Sta/Elev= 30
  4537.2 1350.76  4702.4 1345.48  4766.8 1342.24  4879.8 1335.56  4909.8 1332.76
  4929.8 1329.81  4946.8 1328.74  4959.9 1328.51  4969.9 1327.43  4989.9 1325.03
  4995.4 1323.42  4995.6 1322.92  4999.4 1323.42  5002.9 1323.42  5007.6 1324.91
  5022.9 1327.81  5028.8 1328.26  5044.1 1331.57  5058.9 1332.08  5065.3 1333.28
  5071.2 1332.79  5080.6 1333.76  5094.3 1333.67  5123.1 1336.23  5134.6 1336.33
  5180.9 1337.56  5196.2 1338.89  5290.5 1342.49  5325.9 1344.79  5429.6  1350.4
#Mann= 7 ,-1 , 0
  4537.2     .07       0  4766.8     .12       0  4946.8     .07       0
  4995.4     .05       0  4999.4     .07       0  5134.6     .12       0
  5325.9     .07       0
Bank Sta=4995.4,4999.4
XS Rating Curve= 0 ,0
Exp/Cntr=0.3,0.1

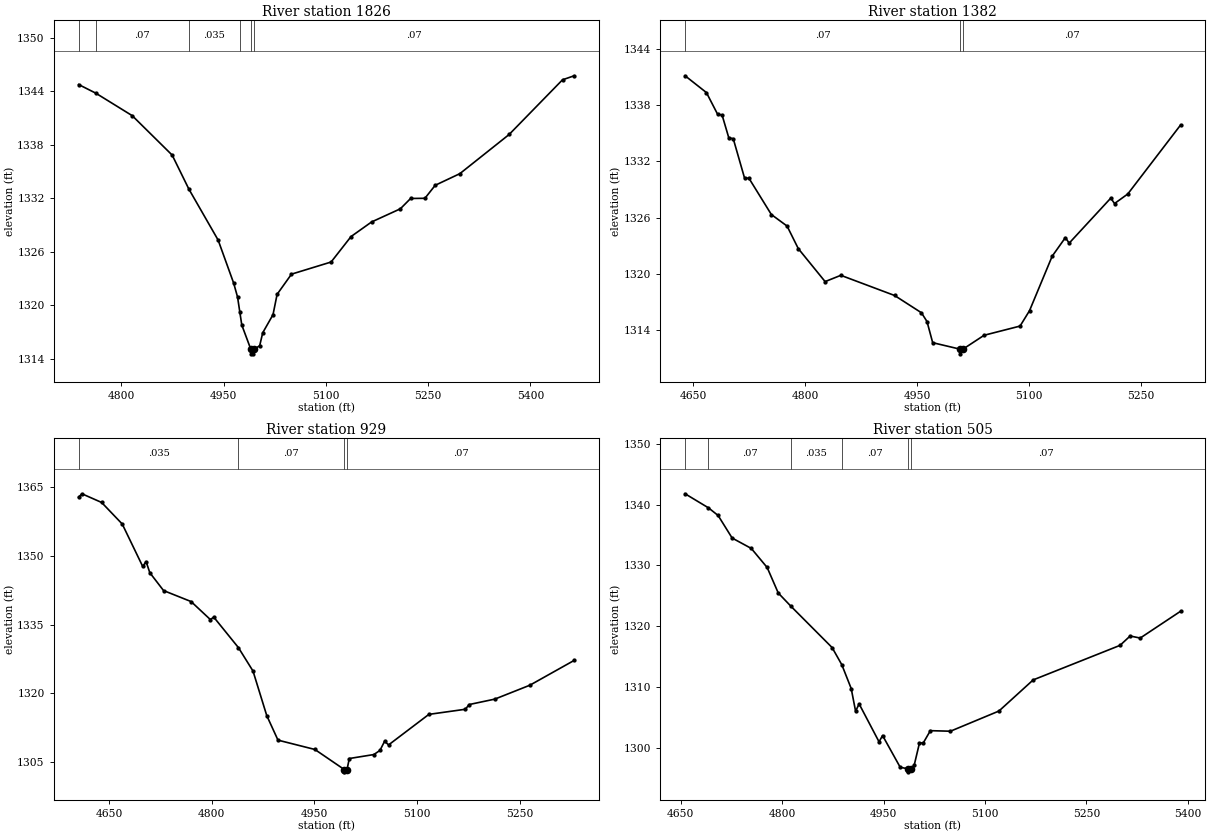
Type RM Length L Ch R = 1 ,1826    ,444,444,444
BEGIN DESCRIPTION:
Stream0025_DS 4.0
END DESCRIPTION:
XS GIS Cut Line= 3
      2057557.37     13865401.68        2057425.       13865175.
      2057037.28     13864919.56
#Sta/Elev= 30
  4737.5 1344.74  4762.7 1343.77  4816.1 1341.25  4874.7 1336.83  4899.2 1333.02
  4942.1 1327.31  4964.9 1322.48  4970.6 1320.92  4973.8  1319.3  4976.8 1317.79
  4990.1 1315.06  4990.4 1314.56  4993.9 1314.56  4994.1 1315.06    5003 1315.46
  5007.5 1316.92  5022.6 1318.95  5028.6 1321.23  5049.7 1323.49  5107.8 1324.85
    5137  1327.7  5167.2 1329.34  5209.3 1330.81  5224.4 1331.97  5245.4 1331.99
  5260.5 1333.45  5296.6 1334.75  5368.9 1339.14  5447.2 1345.27  5464.3 1345.72
#Mann= 6 ,-1 , 0
  4737.5    .035       0  4762.7     .07       0  4899.2    .035       0
  4973.8     .07       0  4990.1     .05       0  4994.1     .07       0
Bank Sta=4990.1,4994.1
XS Rating Curve= 0 ,0
Exp/Cntr=0.3,0.1

Type RM Length L Ch R = 1 ,1382    ,453,453,453
BEGIN DESCRIPTION:
Stream0025_DS 3.0
END DESCRIPTION:
XS GIS Cut Line= 3
      2057975.02     13865225.03        2057775.       13864925.
      2057725.01     13864625.03
#Sta/Elev= 30
  4639.1 1341.11  4667.7 1339.32  4682.7 1337.01  4688.7 1336.93  4697.7  1334.5
  4703.7  1334.4  4718.8 1330.22  4724.8 1330.18  4754.8 1326.32  4775.9 1325.09
  4790.9 1322.69  4826.9 1319.17    4848 1319.84  4920.1 1317.69  4956.1 1315.85
  4963.6 1314.91  4971.2 1312.66  5007.8 1311.97  5008.1 1311.47  5011.8 1311.97
  5040.2 1313.45  5088.4 1314.43  5101.1 1316.07  5131.5 1321.88  5149.2 1323.86
  5154.3 1323.27  5210.1 1328.07  5215.1 1327.49  5232.9 1328.51  5303.8 1335.87
#Mann= 3 ,-1 , 0
  4639.1     .07       0  5007.8     .05       0  5011.8     .07       0
Bank Sta=5007.8,5011.8
XS Rating Curve= 0 ,0
Exp/Cntr=0.3,0.1

Type RM Length L Ch R = 1 ,929     ,424,424,424
BEGIN DESCRIPTION:
Stream0025_DS 2.0
END DESCRIPTION:
XS GIS Cut Line= 3
      2058119.88     13865318.41      2058161.55     13864915.61
      2058002.47     13864638.93
#Sta/Elev= 30
  4605.5 1362.73  4610.3 1363.47  4639.1 1361.58  4669.2 1356.89  4699.1 1347.66
  4704.1  1348.7  4709.5 1346.29  4729.6  1342.4  4769.8 1340.01  4797.9  1336.1
    4803 1336.61    4839 1329.98  4860.3 1324.88  4880.4 1315.18  4896.8 1309.84
  4950.7 1307.81  4993.7 1303.44  4993.9 1302.94  4997.7 1303.44    5001 1305.84
  5036.8  1306.7  5045.8  1307.6  5052.6  1309.6  5058.4  1308.8  5117.3 1315.45
  5170.5 1316.56  5176.2 1317.59  5213.6 1318.77  5264.9  1321.8  5329.6  1327.2
#Mann= 4 ,-1 , 0
  4605.5    .035       0    4839     .07       0  4993.7     .05       0
  4997.7     .07       0
Bank Sta=4993.7,4997.7
XS Rating Curve= 0 ,0
Exp/Cntr=0.3,0.1

Type RM Length L Ch R = 1 ,505     ,0,0,0
BEGIN DESCRIPTION:
Stream0025_DS 1.0
END DESCRIPTION:
XS GIS Cut Line= 3
      2058383.77     13865162.14        2058475.       13864825.
      2058159.04     13864607.24
#Sta/Elev= 30
  4656.4 1341.81    4691 1339.49  4705.2 1338.24    4726 1334.52  4754.3 1332.81
  4777.8 1329.67  4794.2 1325.47  4812.4 1323.35  4873.9 1316.48  4888.2 1313.66
  4902.1 1309.74  4908.6    1306  4913.8 1307.21  4943.3 1300.96  4948.5    1302
  4974.6 1296.77  4986.3 1296.52  4986.6 1296.02  4990.3 1296.52  4995.3 1297.12
  5003.1 1300.78  5008.7 1300.78  5019.2  1302.8  5048.9 1302.71  5120.6 1306.03
  5171.3 1311.16  5299.8 1316.85  5314.7 1318.39  5329.6 1318.05  5389.4 1322.47
#Mann= 6 ,-1 , 0
  4656.4    .035       0    4691     .07       0  4812.4    .035       0
  4888.2     .07       0  4986.3     .05       0  4990.3     .07       0
Bank Sta=4986.3,4990.3
XS Rating Curve= 0 ,0
Exp/Cntr=0.3,0.1

Chan Stop Cuts=-1
Use User Specified Reach Order=0
Composite Channel Slope=5