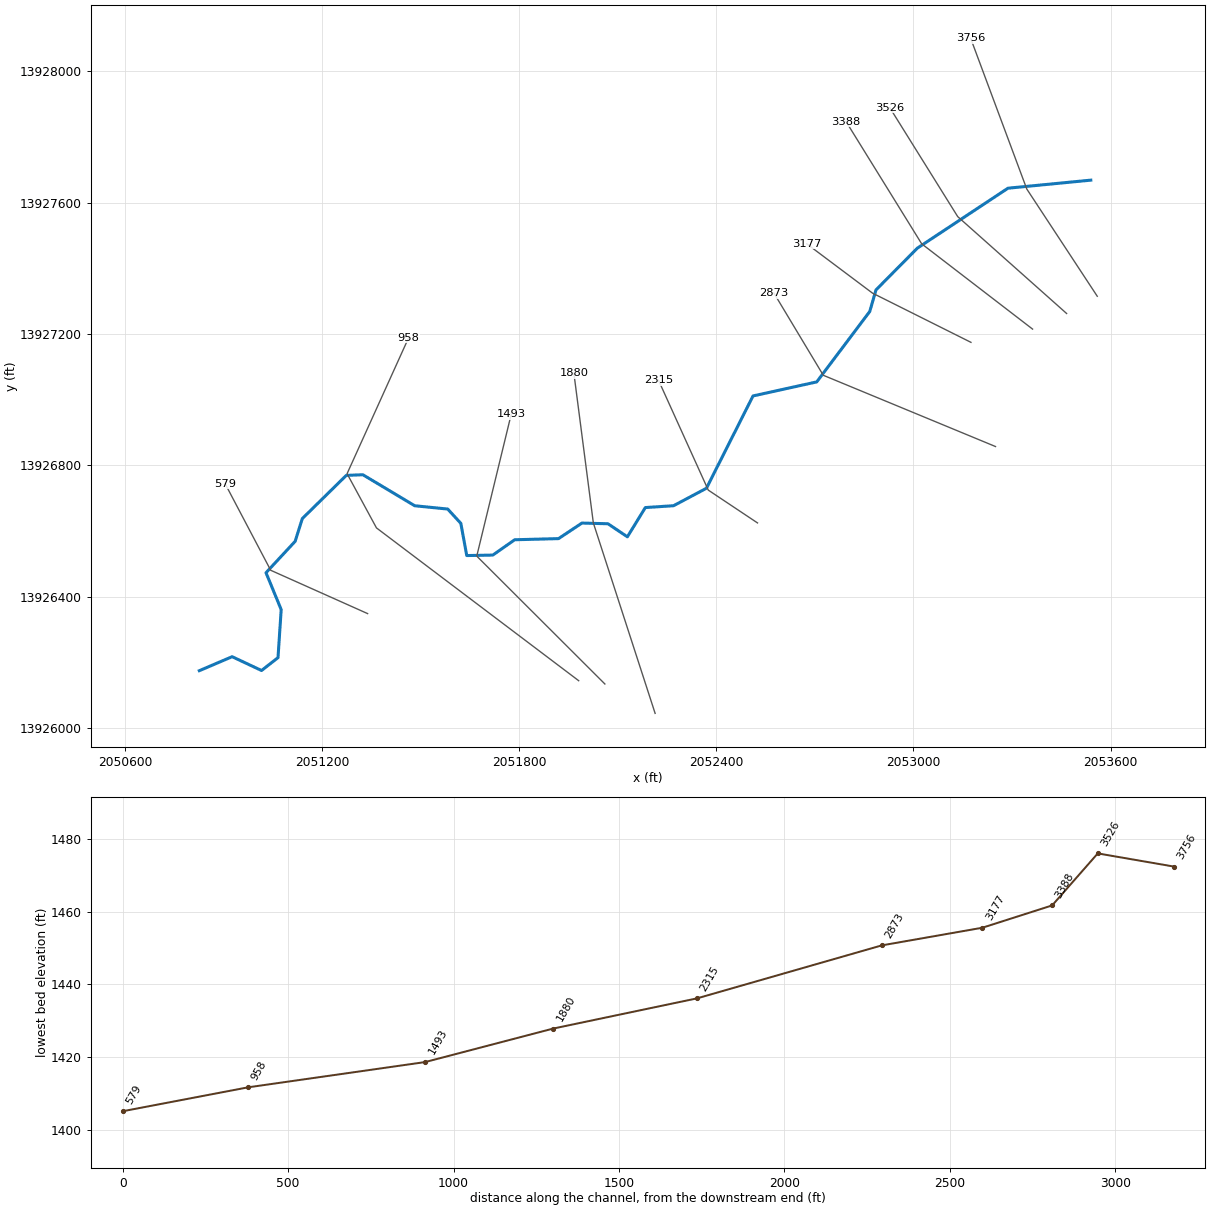
--- Stream0026_DS.prj (project) ---

Proj Title=Stream0026_DS Base Level Engineering
Current Plan=p01
Default Exp/Contr=0.3,0.1
English Units
Geom File=g01
Flow File=f01
Plan File=p01
BEGIN DESCRIPTION:
Stream0026_DS
END DESCRIPTION:

--- Stream0026_DS.p01 (plan) ---

Plan Title=Multiple Run
Short Identifier=Multiple
Geom File=g01
Flow File=f01
Subcritical Flow
K Sum by GR= 0
Std Step Tol= 0.01
Critical Tol= 0.01
Num of Std Step Trials= 20
Max Error Tol= 0.3
Flow Tol Ratio= 0.001
Split Flow NTrial= 30
Split Flow Tol= 0.02
Split Flow Ratio= 0.02
Log Output Level= 0
Friction Slope Method= 1
Unsteady Friction Slope Method= 2
Unsteady Bridges Friction Slope Method= 1
Parabolic Critical Depth
Global Vel Dist=  1 , 1 , 1
Global Log Level= 0
CheckData=True
Encroach Param= -1, 0, 0, 0
BEGIN DESCRIPTION:
Multiple Run
END DESCRIPTION:

--- Stream0026_DS.f01 (steady flow) ---

Flow Title=Multiple
Number of Profiles=7
Profile Names=10-year,25-year,50-year,1pct_min,100-year,1pct_plu,500-year
River Rch & RM= Stream0026_DS,Reach-1,3756
     697    1164    1604    1075    2145    4280    3798
River Rch & RM= Stream0026_DS,Reach-1,3177
     770    1290    1782    1196    2386    4762    4238
Boundary for River Rch & Prof#=Stream0026_DS,Reach-1,1
Up Type=0
Dn Type=3
Dn Slope=0.005
Boundary for River Rch & Prof#=Stream0026_DS,Reach-1,2
Up Type=0
Dn Type=3
Dn Slope=0.005
Boundary for River Rch & Prof#=Stream0026_DS,Reach-1,3
Up Type=0
Dn Type=3
Dn Slope=0.005
Boundary for River Rch & Prof#=Stream0026_DS,Reach-1,4
Up Type=0
Dn Type=3
Dn Slope=0.005
Boundary for River Rch & Prof#=Stream0026_DS,Reach-1,5
Up Type=0
Dn Type=3
Dn Slope=0.005
Boundary for River Rch & Prof#=Stream0026_DS,Reach-1,6
Up Type=0
Dn Type=3
Dn Slope=0.005
Boundary for River Rch & Prof#=Stream0026_DS,Reach-1,7
Up Type=0
Dn Type=3
Dn Slope=0.005

--- Stream0026_DS.g01 (geometry) ---

Geom Title=Existing Conditions

River Reach=Stream0026_DS,Reach-1
Reach XY= 30
      2053539.91     13927668.96      2053287.74     13927644.41
      2053011.99     13927462.00      2052885.77     13927334.68
      2052866.82     13927268.96      2052705.28     13927054.48
      2052511.33     13927011.77      2052369.42     13926730.58
      2052269.38     13926677.47      2052183.34     13926671.79
      2052128.65     13926582.73      2052069.53     13926622.50
      2051990.28     13926624.61      2051919.06     13926577.27
      2051785.51     13926573.77      2051718.93     13926527.12
      2051639.49     13926525.64      2051621.45     13926623.67
      2051581.50     13926667.27      2051480.97     13926677.34
      2051323.26     13926771.69      2051272.70     13926769.91
      2051138.63     13926638.21      2051116.82     13926568.96
      2051028.14     13926473.36      2051074.31     13926361.08
      2051064.66     13926214.77      2051014.53     13926175.57
      2050924.97     13926217.65      2050825.00     13926175.00

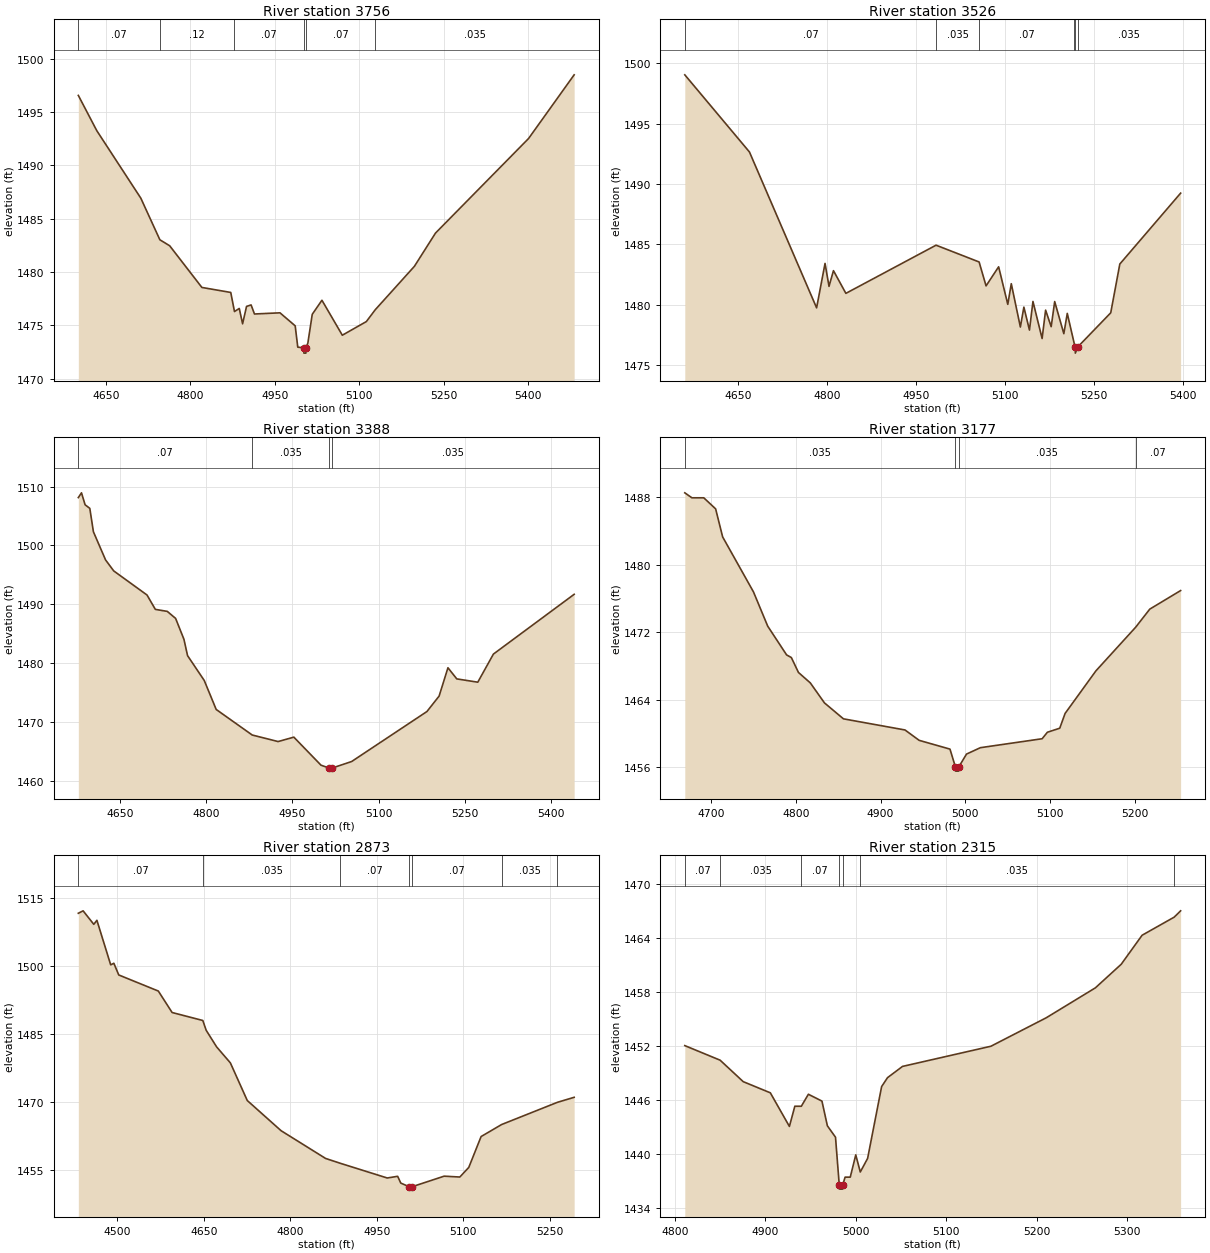
Type RM Length L Ch R = 1,3756,230,230,230
BEGIN DESCRIPTION:
Stream0026_DS 10.0
END DESCRIPTION:
XS GIS Cut Line= 3
      2053559.69     13927315.36      2053344.97     13927642.07
      2053174.15     13928100.85
#Sta/Elev= 30
  4600.9 1496.55  4633.6 1493.25  4711.9 1486.91  4745.7 1483.01  4763.1 1482.45
  4820.3 1478.54  4871.6 1478.07  4878.2 1476.28  4886.7 1476.57  4892.6 1475.13
  4899.6 1476.76  4907.7 1476.90  4913.7 1476.05  4959.0 1476.16  4986.0 1474.94
  4990.6 1472.94  5001.2 1472.88  5001.5 1472.38  5005.0 1472.38  5005.2 1472.88
  5008.5 1473.32  5016.3 1476.02  5033.5 1477.34  5069.7 1474.06  5112.4 1475.34
  5128.2 1476.45  5197.7 1480.52  5235.2 1483.64  5400.5 1492.51  5481.4 1498.48
#Mann=6,-1,0
  4600.9    0.07       0  4745.7    0.12       0  4878.2    0.07       0
  5001.2    0.05       0  5005.2    0.07       0  5128.2   0.035       0
Bank Sta=5001.2,5005.2
Exp/Cntr=0.3,0.1

Type RM Length L Ch R = 1,3526,138,138,138
BEGIN DESCRIPTION:
Stream0026_DS 9.0
END DESCRIPTION:
XS GIS Cut Line= 3
      2053466.35     13927262.86      2053134.68     13927557.90
      2052927.73     13927889.87
#Sta/Elev= 30
  4560.7 1499.05  4669.6 1492.66  4782.7 1479.75  4796.9 1483.43  4803.6 1481.53
  4811.1 1482.83  4832.0 1480.95  4983.9 1484.94  5056.4 1483.55  5068.1 1481.57
  5089.3 1483.15  5104.7 1480.04  5110.6 1481.75  5125.9 1478.16  5131.8 1479.81
  5141.2 1477.91  5147.1 1480.28  5162.5 1477.21  5168.4 1479.56  5177.8 1478.19
  5183.7 1480.27  5199.1 1477.61  5204.9 1479.29  5216.4 1476.84  5218.3 1476.50
  5218.5 1476.00  5222.3 1476.50  5278.1 1479.34  5293.4 1483.38  5395.8 1489.25
#Mann=6,-1,0
  4560.7    0.07       0  4983.9   0.035       0  5056.4    0.07       0
  5216.4   0.035       0  5218.3   0.035       0  5222.3   0.035       0
Bank Sta=5218.3,5222.3
Exp/Cntr=0.3,0.1

Type RM Length L Ch R = 1,3388,211,211,211
BEGIN DESCRIPTION:
Stream0026_DS 8.0
END DESCRIPTION:
XS GIS Cut Line= 3
      2053362.68     13927215.34      2053025.00     13927475.00
      2052794.57     13927847.41
#Sta/Elev= 30
  4576.9 1508.12  4582.4 1508.93  4588.7 1506.90  4596.9 1506.29  4603.2 1502.31
  4624.4 1497.53  4638.6 1495.67  4696.6 1491.58  4711.1 1489.14  4731.9 1488.80
  4746.4 1487.61  4760.9 1484.07  4767.2 1481.29  4796.3 1477.07  4817.1 1472.15
  4879.9 1467.81  4925.0 1466.70  4952.4 1467.45  4999.7 1462.69  5014.4 1462.18
  5014.7 1461.68  5018.4 1462.18  5053.1 1463.31  5184.3 1471.80  5205.5 1474.42
  5220.9 1479.23  5236.3 1477.34  5272.9 1476.78  5300.1 1481.55  5440.8 1491.70
#Mann=4,-1,0
  4576.9    0.07       0  4879.9   0.035       0  5014.4   0.035       0
  5018.4   0.035       0
Bank Sta=5014.4,5018.4
Exp/Cntr=0.3,0.1

Type RM Length L Ch R = 1,3177,304,304,304
BEGIN DESCRIPTION:
Stream0026_DS 7.0
END DESCRIPTION:
XS GIS Cut Line= 3
      2053175.02     13927174.99      2052875.00     13927325.00
      2052675.03     13927474.98
#Sta/Elev= 30
  4668.9 1488.54  4677.3 1487.95  4691.3 1487.95  4705.3 1486.64  4713.6 1483.31
  4750.0 1476.79  4766.8 1472.73  4789.1 1469.32  4794.7 1469.01  4803.1 1467.24
  4817.1 1466.00  4833.8 1463.63  4856.2 1461.74  4928.9 1460.42  4945.6 1459.19
  4982.0 1458.15  4988.4 1456.04  4988.6 1455.54  4992.1 1455.54  4992.4 1456.04
  5001.5 1457.56  5017.9 1458.32  5090.8 1459.38  5097.0 1460.15  5111.6 1460.63
  5117.9 1462.38  5154.3 1467.43  5201.1 1472.59  5217.9 1474.75  5254.3 1476.95
#Mann=4,-1,0
  4668.9   0.035       0  4988.4   0.035       0  4992.4   0.035       0
  5201.1    0.07       0
Bank Sta=4988.4,4992.4
Exp/Cntr=0.3,0.1

Type RM Length L Ch R = 1,2873,558,558,558
BEGIN DESCRIPTION:
Stream0026_DS 6.0
END DESCRIPTION:
XS GIS Cut Line= 3
      2053249.80     13926857.68      2052725.32     13927074.67
      2052575.00     13927325.00
#Sta/Elev= 30
  4432.4 1511.58  4440.7 1512.12  4459.2 1509.14  4464.6 1510.03  4488.5 1500.20
  4494.0 1500.54  4502.5 1497.96  4571.1 1494.41  4595.0 1489.67  4648.2 1487.91
  4654.0 1485.76  4672.1 1482.09  4696.0 1478.55  4725.3 1470.24  4783.9 1463.58
  4861.0 1457.46  4886.2 1456.40  4967.9 1453.14  4986.0 1453.51  4991.4 1452.02
  5006.3 1451.18  5006.5 1450.68  5010.3 1451.18  5066.6 1453.54  5093.8 1453.35
  5109.3 1455.47  5130.7 1462.29  5166.4 1464.95  5263.1 1469.85  5292.0 1470.95
#Mann=7,-1,0
  4432.4    0.07       0  4648.2   0.035       0  4886.2    0.07       0
  5006.3    0.05       0  5010.3    0.07       0  5166.4   0.035       0
  5263.1    0.12       0
Bank Sta=5006.3,5010.3
Exp/Cntr=0.3,0.1

Type RM Length L Ch R = 1,2315,435,435,435
BEGIN DESCRIPTION:
Stream0026_DS 5.0
END DESCRIPTION:
XS GIS Cut Line= 3
      2052524.99     13926625.00      2052375.00     13926725.00
      2052223.10     13927060.33
#Sta/Elev= 30
  4810.8 1452.04  4849.9 1450.42  4875.4 1448.04  4905.4 1446.80  4926.5 1443.07
  4932.5 1445.31  4939.7 1445.31  4947.5 1446.64  4962.5 1445.88  4968.5 1443.14
  4977.5 1441.87  4981.6 1436.61  4981.8 1436.11  4985.3 1436.11  4985.6 1436.61
  4988.1 1437.44  4993.8 1437.44  4999.9 1439.91  5004.9 1438.01  5013.0 1439.52
  5028.5 1447.49  5035.0 1448.48  5051.6 1449.73  5149.4 1451.97  5210.6 1455.13
  5264.9 1458.45  5293.5 1461.07  5316.6 1464.29  5352.1 1466.30  5359.2 1467.00
#Mann=7,-1,0
  4810.8    0.07       0  4849.9   0.035       0  4939.7    0.07       0
  4981.6    0.05       0  4985.6    0.07       0  5004.9   0.035       0
  5352.1    0.07       0
Bank Sta=4981.6,4985.6
Exp/Cntr=0.3,0.1

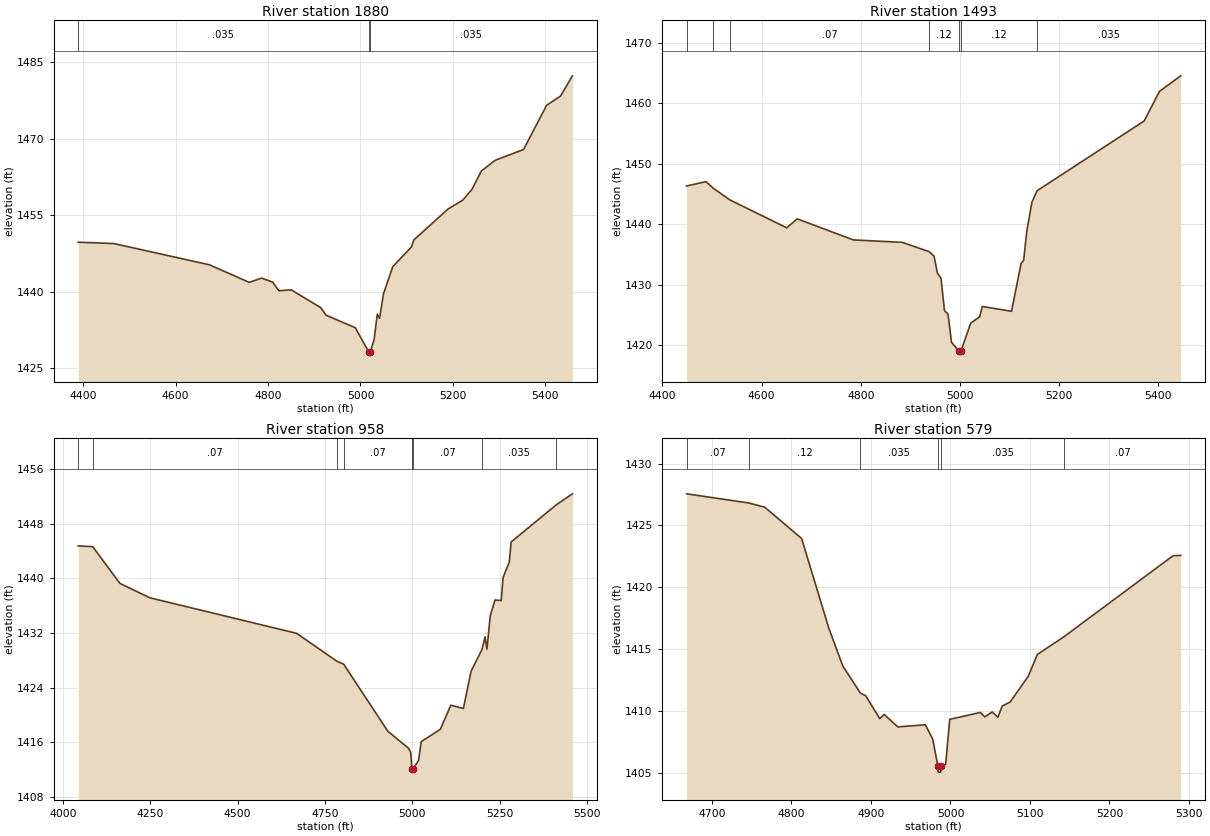
Type RM Length L Ch R = 1,1880,387,387,387
BEGIN DESCRIPTION:
Stream0026_DS 4.0
END DESCRIPTION:
XS GIS Cut Line= 3
      2052213.16     13926045.02      2052025.00     13926625.00
      2051965.81     13927080.33
#Sta/Elev= 30
  4389.5 1449.72  4466.4 1449.46  4673.3 1445.29  4759.5 1441.85  4786.2 1442.69
  4810.0 1441.90  4823.4 1440.20  4850.1 1440.39  4914.1 1436.89  4925.7 1435.42
  4988.7 1432.97  5017.4 1428.29  5017.7 1427.79  5021.4 1428.29  5029.5 1430.67
  5036.3 1435.60  5041.3 1434.81  5049.7 1439.59  5069.8 1444.92  5110.2 1448.79
  5115.4 1450.16  5189.5 1456.23  5221.1 1457.95  5241.3 1460.10  5261.4 1463.67
  5291.7 1465.78  5352.8 1467.89  5402.6 1476.54  5432.9 1478.37  5458.4 1482.32
#Mann=3,-1,0
  4389.5   0.035       0  5017.4   0.035       0  5021.4   0.035       0
Bank Sta=5017.4,5021.4
Exp/Cntr=0.3,0.1

Type RM Length L Ch R = 1,1493,535,535,535
BEGIN DESCRIPTION:
Stream0026_DS 3.0
END DESCRIPTION:
XS GIS Cut Line= 3
      2052060.15     13926134.51      2051669.95     13926523.96
      2051775.02     13926956.58
#Sta/Elev= 30
  4448.7 1446.33  4488.0 1447.05  4502.9 1445.94  4536.6 1444.01  4650.7 1439.43
  4671.9 1440.90  4785.0 1437.43  4884.0 1437.02  4937.8 1435.49  4947.7 1434.76
  4954.7 1431.93  4961.8 1431.10  4968.9 1425.75  4976.0 1425.17  4983.0 1420.53
  4998.0 1419.07  4998.2 1418.57  5002.0 1419.07  5021.7 1423.69  5039.8 1424.74
  5045.0 1426.44  5104.0 1425.64  5123.4 1433.56  5128.5 1434.05  5134.8 1438.86
  5145.1 1443.64  5155.6 1445.55  5371.5 1457.06  5402.4 1461.95  5445.2 1464.52
#Mann=7,-1,0
  4448.7    0.07       0  4502.9   0.035       0  4536.6    0.07       0
  4937.8    0.12       0  4998.0    0.05       0  5002.0    0.12       0
  5155.6   0.035       0
Bank Sta=4998,5002
Exp/Cntr=0.3,0.1

Type RM Length L Ch R = 1,958,379,379,379
BEGIN DESCRIPTION:
Stream0026_DS 2.0
END DESCRIPTION:
XS GIS Cut Line= 4
      2051980.37     13926144.52      2051364.49     13926609.89
      2051275.00     13926775.00      2051462.52     13927189.20
#Sta/Elev= 30
  4043.8 1444.77  4085.3 1444.66  4163.0 1439.28  4248.4 1437.17  4668.8 1431.96
  4784.4 1427.86  4803.6 1427.43  4929.8 1417.62  4989.8 1415.09  4995.4 1414.54
  4998.7 1412.12  4998.9 1411.62  5002.7 1412.12  5017.8 1413.32  5025.5 1416.08
  5080.4 1417.91  5110.2 1421.43  5146.2 1420.94  5168.2 1426.40  5199.5 1429.60
  5208.1 1431.44  5213.6 1429.66  5223.1 1434.53  5236.7 1436.85  5254.3 1436.76
  5259.8 1440.14  5277.4 1442.38  5282.9 1445.35  5412.0 1450.79  5458.2 1452.40
#Mann=8,-1,0
  4043.8   0.035       0  4085.3    0.07       0  4784.4   0.035       0
  4803.6    0.07       0  4998.7    0.05       0  5002.7    0.07       0
  5199.5   0.035       0  5412.0    0.07       0
Bank Sta=4998.7,5002.7
Exp/Cntr=0.3,0.1

Type RM Length L Ch R = 1,579,0,0,0
BEGIN DESCRIPTION:
Stream0026_DS 1.0
END DESCRIPTION:
XS GIS Cut Line= 3
      2051337.53     13926348.89      2051042.37     13926480.85
      2050903.49     13926744.72
#Sta/Elev= 30
  4668.1 1427.56  4746.4 1426.82  4766.4 1426.48  4812.8 1423.95  4847.0 1416.70
  4864.7 1413.62  4886.7 1411.44  4893.4 1411.22  4911.1 1409.37  4916.6 1409.71
  4933.8 1408.70  4968.5 1408.87  4977.6 1407.73  4984.2 1405.54  4984.4 1405.04
  4987.9 1405.04  4988.2 1405.54  4994.0 1405.67  4999.1 1409.31  5037.5 1409.87
  5043.2 1409.51  5052.6 1409.91  5059.6 1409.48  5065.2 1410.39  5075.2 1410.72
  5097.8 1412.79  5109.3 1414.56  5142.9 1416.00  5279.9 1422.55  5289.6 1422.58
#Mann=6,-1,0
  4668.1    0.07       0  4746.4    0.12       0  4886.7   0.035       0
  4984.2   0.035       0  4988.2   0.035       0  5142.9    0.07       0
Bank Sta=4984.2,4988.2
Exp/Cntr=0.3,0.1

Chan Stop Cuts=-1