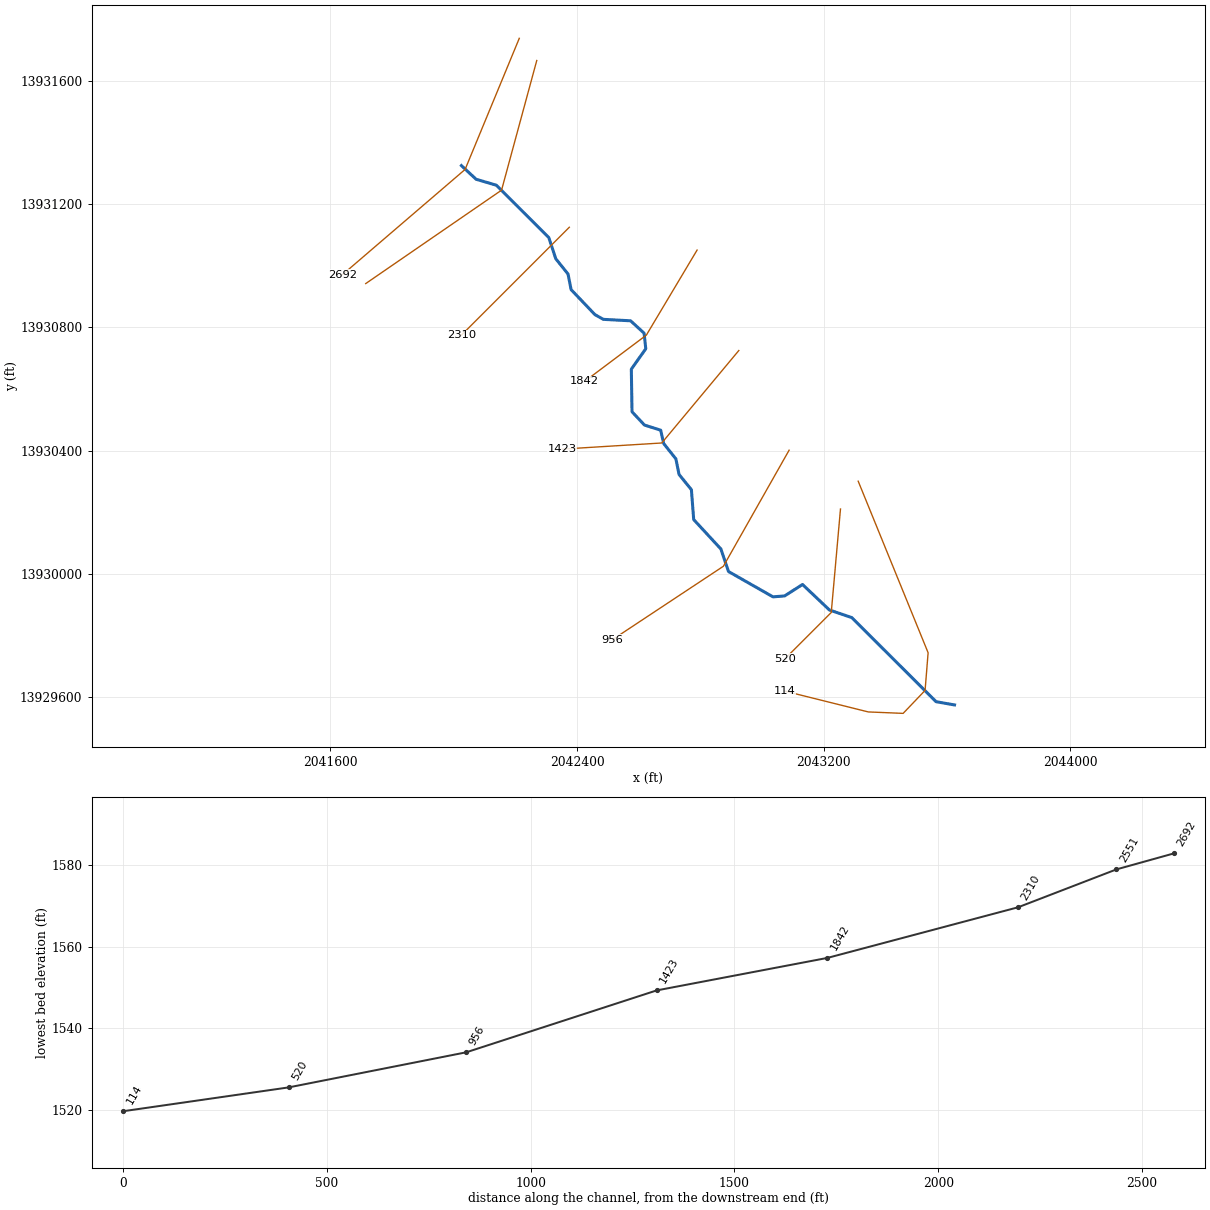
--- Stream0028_DS.prj (project) ---

Proj Title=Stream0028_DS Base Level Engineering
Current Plan=p01
Default Exp/Contr=0.3,0.1
English Units
Geom File=g01
Flow File=f01
Plan File=p01
BEGIN DESCRIPTION:
Stream0028_DS
END DESCRIPTION:

--- Stream0028_DS.p01 (plan) ---

Plan Title=Multiple Run
Short Identifier=Multiple
Geom File=g01
Flow File=f01
Subcritical Flow
K Sum by GR= 0
Std Step Tol= 0.01
Critical Tol= 0.01
Num of Std Step Trials= 20
Max Error Tol= 0.3
Flow Tol Ratio= 0.001
Split Flow NTrial= 30
Split Flow Tol= 0.02
Split Flow Ratio= 0.02
Log Output Level= 0
Friction Slope Method= 1
Unsteady Friction Slope Method= 2
Unsteady Bridges Friction Slope Method= 1
Parabolic Critical Depth
Global Vel Dist=  1 , 1 , 1
Global Log Level= 0
CheckData=True
Encroach Param= -1, 0, 0, 0
BEGIN DESCRIPTION:
Multiple Run
END DESCRIPTION:

--- Stream0028_DS.f01 (steady flow) ---

Flow Title=Multiple
Number of Profiles=7
Profile Names=10-year,25-year,50-year,1pct_min,100-year,1pct_plu,500-year
River Rch & RM= Stream0028_DS,Reach-1,2692
     549     914    1258     844    1685    3362    2986
River Rch & RM= Stream0028_DS,Reach-1,2310
     655    1100    1523    1026    2048    4086    3665
Boundary for River Rch & Prof#=Stream0028_DS,Reach-1,1
Up Type=0
Dn Type=3
Dn Slope=0.005
Boundary for River Rch & Prof#=Stream0028_DS,Reach-1,2
Up Type=0
Dn Type=3
Dn Slope=0.005
Boundary for River Rch & Prof#=Stream0028_DS,Reach-1,3
Up Type=0
Dn Type=3
Dn Slope=0.005
Boundary for River Rch & Prof#=Stream0028_DS,Reach-1,4
Up Type=0
Dn Type=3
Dn Slope=0.005
Boundary for River Rch & Prof#=Stream0028_DS,Reach-1,5
Up Type=0
Dn Type=3
Dn Slope=0.005
Boundary for River Rch & Prof#=Stream0028_DS,Reach-1,6
Up Type=0
Dn Type=3
Dn Slope=0.005
Boundary for River Rch & Prof#=Stream0028_DS,Reach-1,7
Up Type=0
Dn Type=3
Dn Slope=0.005

--- Stream0028_DS.g01 (geometry) ---

Geom Title=Existing Conditions

River Reach=Stream0028_DS,Reach-1
Reach XY= 30
      2042025.00     13931325.00      2042072.65     13931280.71
      2042138.23     13931261.43      2042308.36     13931091.68
      2042331.10     13931022.81      2042370.81     13930973.26
      2042380.83     13930922.69      2042458.21     13930841.44
      2042485.48     13930826.17      2042573.78     13930821.47
      2042617.65     13930781.38      2042623.11     13930730.77
      2042576.23     13930664.50      2042578.47     13930526.27
      2042618.92     13930483.15      2042671.46     13930466.51
      2042681.24     13930423.15      2042720.85     13930373.31
      2042731.12     13930322.82      2042771.17     13930273.41
      2042778.62     13930176.50      2042866.81     13930081.02
      2042891.49     13930007.95      2043035.70     13929925.80
      2043073.36     13929928.61      2043131.72     13929965.83
      2043218.95     13929883.20      2043291.67     13929858.35
      2043565.21     13929585.51      2043625.00     13929575.00

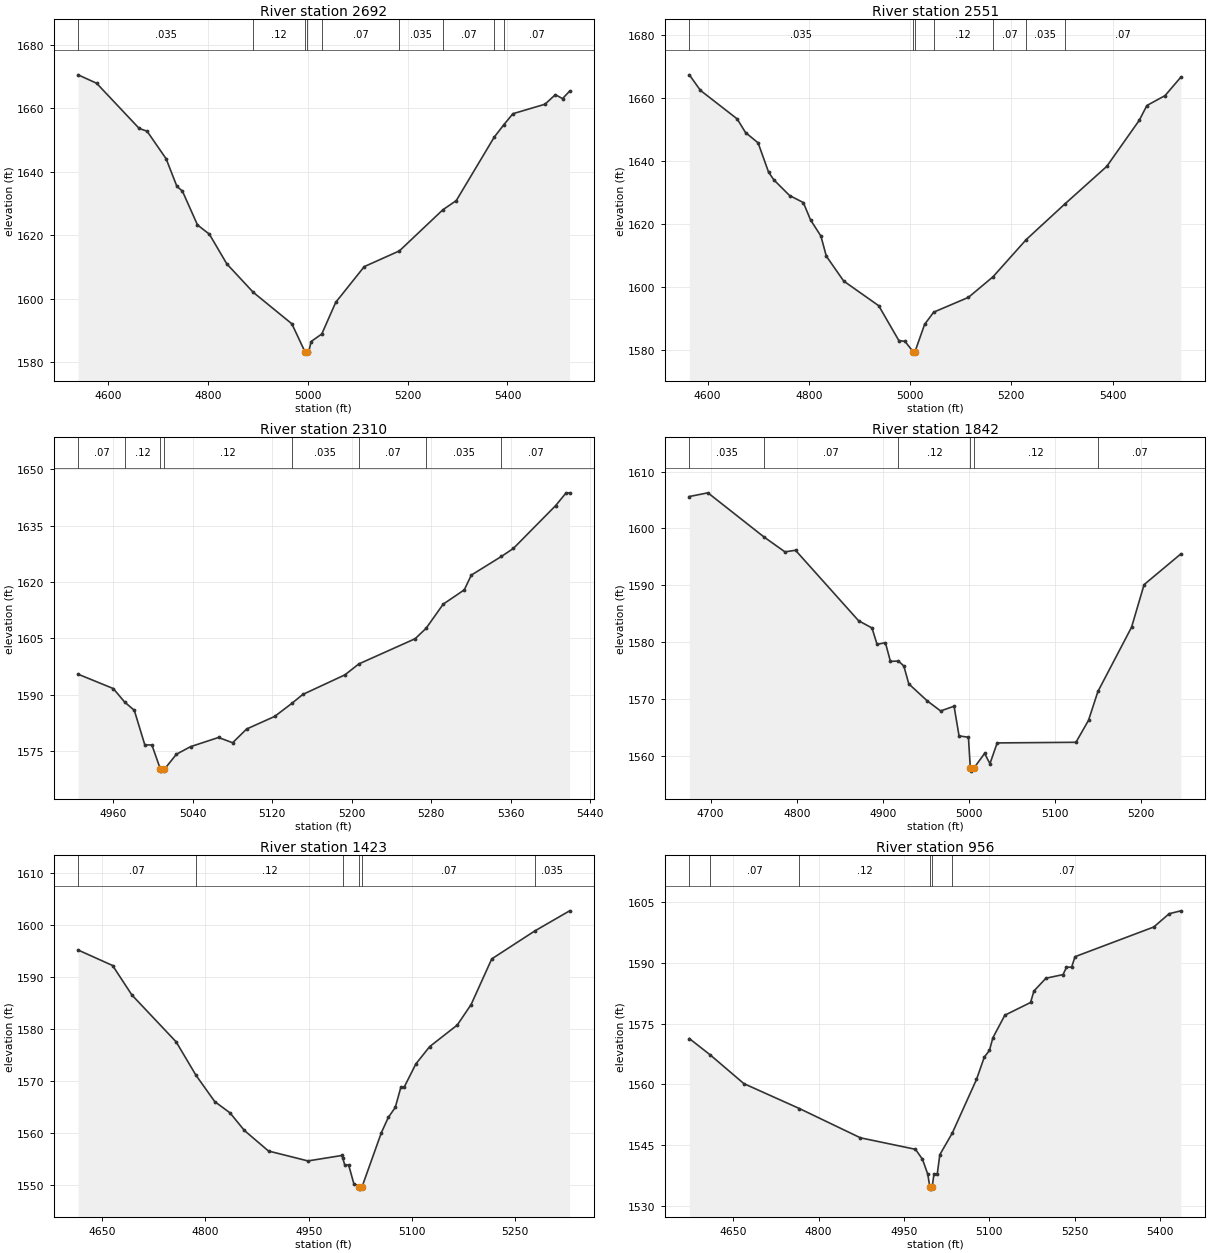
Type RM Length L Ch R = 1,2692,141,141,141
BEGIN DESCRIPTION:
Stream0028_DS 7.0
END DESCRIPTION:
XS GIS Cut Line= 3
      2042212.65     13931738.02      2042036.85     13931312.61
      2041638.79     13930971.08
#Sta/Elev= 30
  4539.7 1670.61  4576.8 1667.95  4662.0 1653.72  4677.9 1652.83  4716.1 1644.13
  4737.7 1635.42  4748.6 1633.98  4778.9 1623.28  4802.7 1620.37  4837.6 1611.02
  4890.5 1602.06  4968.0 1592.11  4994.0 1583.37  4994.3 1582.87  4998.0 1583.37
  5002.0 1583.37  5006.5 1586.52  5027.9 1588.90  5055.9 1598.89  5113.0 1610.14
  5183.4 1615.10  5270.5 1628.06  5297.4 1630.96  5373.3 1650.93  5392.2 1654.78
  5410.9 1658.35  5475.1 1661.34  5496.0 1664.35  5510.3 1663.11  5524.5 1665.47
#Mann=9,-1,0
  4539.7   0.035       0  4890.5    0.12       0  4994.0    0.05       0
  4998.0    0.12       0  5027.9    0.07       0  5183.4   0.035       0
  5270.5    0.07       0  5373.3   0.035       0  5392.2    0.07       0
Bank Sta=4994,4998
Exp/Cntr=0.3,0.1

Type RM Length L Ch R = 1,2551,241,241,241
BEGIN DESCRIPTION:
Stream0028_DS 6.0
END DESCRIPTION:
XS GIS Cut Line= 3
      2042269.37     13931666.07      2042155.16     13931245.39
      2041714.35     13930942.22
#Sta/Elev= 30
  4564.1 1667.37  4585.9 1662.44  4658.5 1653.38  4675.1 1649.03  4699.9 1645.76
  4720.6 1636.45  4731.0 1634.01  4762.1 1629.02  4789.3 1626.79  4803.5 1621.28
  4824.0 1616.14  4834.6 1609.79  4869.0 1601.85  4938.2 1594.01  4978.0 1582.93
  4990.0 1582.70  5005.9 1579.45  5006.1 1578.95  5009.9 1579.45  5028.9 1588.10
  5046.8 1591.97  5115.4 1596.67  5164.0 1603.21  5229.6 1615.03  5305.4 1626.27
  5388.6 1638.27  5453.0 1652.96  5467.9 1657.62  5503.8 1660.77  5535.0 1666.63
#Mann=7,-1,0
  4564.1   0.035       0  5005.9   0.035       0  5009.9   0.035       0
  5046.8    0.12       0  5164.0    0.07       0  5229.6   0.035       0
  5305.4    0.07       0
Bank Sta=5005.9,5009.9
Exp/Cntr=0.3,0.1

Type RM Length L Ch R = 1,2310,468,468,468
BEGIN DESCRIPTION:
Stream0028_DS 5.0
END DESCRIPTION:
XS GIS Cut Line= 3
      2042375.02     13931125.02      2042325.00     13931075.00
      2042025.00     13930775.00
#Sta/Elev= 30
  4924.5 1595.48  4959.9 1591.66  4971.3 1588.08  4981.1 1585.85  4991.7 1576.64
  4998.8 1576.64  5007.4 1570.17  5007.6 1569.67  5011.1 1569.67  5011.4 1570.17
  5023.5 1574.17  5037.7 1576.18  5065.9 1578.63  5080.1 1577.23  5094.2 1580.88
  5122.5 1584.24  5139.7 1587.70  5150.8 1590.09  5193.2 1595.30  5207.2 1598.21
  5263.9 1604.92  5274.9 1607.68  5292.2 1614.13  5313.4 1617.93  5320.5 1621.86
  5350.8 1626.83  5362.9 1628.97  5405.4 1640.36  5416.0 1643.77  5419.5 1643.77
#Mann=8,-1,0
  4924.5    0.07       0  4971.3    0.12       0  5007.4    0.05       0
  5011.4    0.12       0  5139.7   0.035       0  5207.2    0.07       0
  5274.9   0.035       0  5350.8    0.07       0
Bank Sta=5007.4,5011.4
Exp/Cntr=0.3,0.1

Type RM Length L Ch R = 1,1842,419,419,419
BEGIN DESCRIPTION:
Stream0028_DS 4.0
END DESCRIPTION:
XS GIS Cut Line= 3
      2042789.62     13931050.94      2042625.00     13930775.00
      2042425.01     13930625.01
#Sta/Elev= 30
  4675.2 1605.63  4696.8 1606.28  4761.9 1598.51  4786.3 1595.88  4798.6 1596.16
  4871.9 1583.75  4887.5 1582.47  4893.4 1579.59  4903.1 1579.88  4908.9 1576.59
  4918.3 1576.64  4924.5 1575.77  4930.3 1572.62  4951.7 1569.63  4967.3 1567.85
  4982.9 1568.69  4988.7 1563.46  4999.6 1563.22  5001.8 1557.75  5002.1 1557.25
  5005.8 1557.75  5018.4 1560.37  5024.6 1558.56  5033.0 1562.22  5124.6 1562.33
  5139.2 1566.21  5150.1 1571.28  5189.2 1582.60  5203.8 1590.11  5246.5 1595.52
#Mann=6,-1,0
  4675.2   0.035       0  4761.9    0.07       0  4918.3    0.12       0
  5001.8    0.05       0  5005.8    0.12       0  5150.1    0.07       0
Bank Sta=5001.8,5005.8
Exp/Cntr=0.3,0.1

Type RM Length L Ch R = 1,1423,467,467,467
BEGIN DESCRIPTION:
Stream0028_DS 3.0
END DESCRIPTION:
XS GIS Cut Line= 3
      2042925.00     13930725.01      2042675.00     13930425.00
      2042352.13     13930405.14
#Sta/Elev= 30
  4615.1 1595.15  4665.2 1592.18  4693.2 1586.53  4757.6 1577.52  4786.3 1571.13
  4813.6 1566.07  4835.7 1563.92  4856.6 1560.54  4891.7 1556.59  4949.0 1554.69
  4998.5 1555.74  4999.6 1555.23  5002.4 1553.92  5008.1 1553.92  5015.6 1550.35
  5023.7 1549.78  5023.9 1549.28  5027.7 1549.78  5055.7 1560.13  5065.7 1563.03
  5075.8 1564.95  5083.9 1568.79  5088.9 1568.88  5105.8 1573.31  5125.8 1576.62
  5165.9 1580.76  5186.0 1584.69  5216.0 1593.45  5278.4 1598.80  5329.1 1602.67
#Mann=6,-1,0
  4615.1    0.07       0  4786.3    0.12       0  4999.6    0.07       0
  5023.7    0.05       0  5027.7    0.07       0  5278.4   0.035       0
Bank Sta=5023.7,5027.7
Exp/Cntr=0.3,0.1

Type RM Length L Ch R = 1,956,436,436,436
BEGIN DESCRIPTION:
Stream0028_DS 2.0
END DESCRIPTION:
XS GIS Cut Line= 3
      2043088.24     13930401.65      2042875.00     13930025.00
      2042515.30     13929787.06
#Sta/Elev= 30
  4572.8 1571.35  4609.4 1567.32  4668.7 1560.20  4766.3 1554.04  4873.6 1546.80
  4970.3 1543.96  4982.6 1541.52  4991.9 1537.83  4995.7 1534.61  4995.9 1534.11
  4999.7 1534.61  5002.8 1537.80  5008.6 1537.80  5013.2 1542.64  5034.9 1547.93
  5077.6 1561.23  5091.4 1566.78  5100.4 1568.41  5106.4 1571.53  5127.5 1577.13
  5172.7 1580.27  5178.6 1583.11  5199.7 1586.27  5229.8 1587.17  5235.8 1588.98
  5244.9 1589.03  5250.9 1591.60  5389.3 1598.94  5416.4 1602.23  5436.9 1602.94
#Mann=6,-1,0
  4572.8   0.035       0  4609.4    0.07       0  4766.3    0.12       0
  4995.7    0.05       0  4999.7    0.12       0  5034.9    0.07       0
Bank Sta=4995.7,4999.7
Exp/Cntr=0.3,0.1

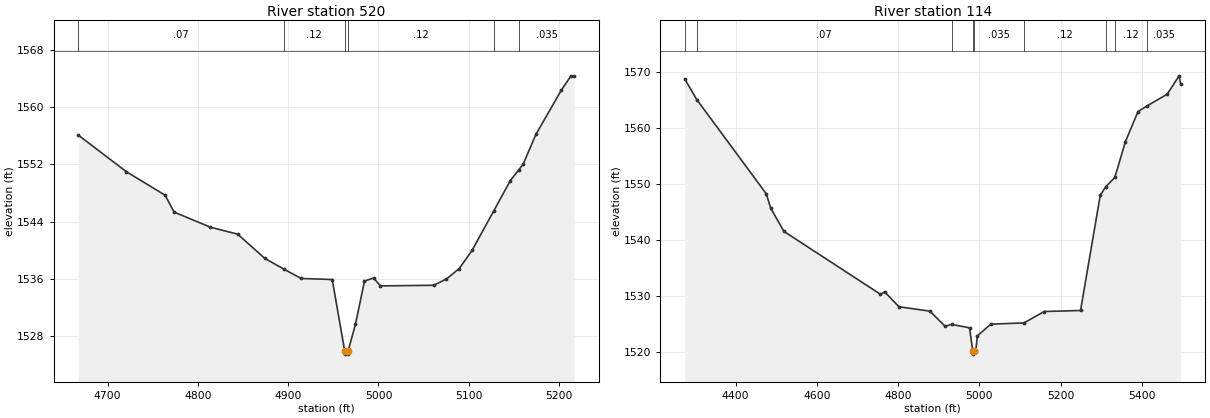
Type RM Length L Ch R = 1,520,406,406,406
BEGIN DESCRIPTION:
Stream0028_DS 1.0
END DESCRIPTION:
XS GIS Cut Line= 3
      2043254.92     13930210.68      2043225.00     13929875.00
      2043075.03     13929725.03
#Sta/Elev= 30
  4667.6 1556.06  4720.7 1550.97  4763.7 1547.68  4773.7 1545.32  4813.9 1543.21
  4844.0 1542.25  4874.1 1538.86  4895.2 1537.37  4914.3 1536.06  4948.8 1535.91
  4962.5 1526.00  4962.7 1525.50  4966.2 1525.50  4966.5 1526.00  4974.5 1529.66
  4984.5 1535.69  4994.6 1536.13  5002.1 1535.02  5061.2 1535.11  5075.3 1535.99
  5089.5 1537.45  5103.6 1539.97  5127.7 1545.50  5146.0 1549.71  5155.6 1551.26
  5160.2 1552.00  5174.3 1556.16  5202.6 1562.36  5213.2 1564.34  5216.7 1564.34
#Mann=6,-1,0
  4667.6    0.07       0  4895.2    0.12       0  4962.5    0.05       0
  4966.5    0.12       0  5127.7    0.07       0  5155.6   0.035       0
Bank Sta=4962.5,4966.5
Exp/Cntr=0.3,0.1

Type RM Length L Ch R = 1,114,0,0,0
BEGIN DESCRIPTION:
Stream0028_DS 0.0
END DESCRIPTION:
XS GIS Cut Line= 6
      2043312.42     13930300.96      2043539.27     13929744.36
      2043529.42     13929622.07      2043458.23     13929547.62
      2043345.08     13929552.31      2043073.09     13929620.10
#Sta/Elev= 30
  4275.0 1568.70  4304.4 1565.05  4475.5 1548.25  4486.6 1545.66  4519.0 1541.54
  4756.6 1530.33  4767.0 1530.77  4801.8 1528.11  4878.2 1527.32  4915.5 1524.64
  4931.8 1524.96  4975.7 1524.35  4983.8 1520.16  4984.0 1519.66  4987.8 1520.16
  4991.1 1520.26  4995.1 1522.91  5028.1 1525.01  5109.7 1525.22  5159.6 1527.26
  5249.0 1527.44  5297.5 1547.98  5310.7 1549.47  5333.4 1551.16  5359.4 1557.54
  5390.3 1562.89  5413.0 1563.93  5462.4 1566.01  5491.5 1569.28  5495.3 1567.88
#Mann=9,-1,0
  4275.0   0.035       0  4304.4    0.07       0  4931.8   0.035       0
  4983.8   0.035       0  4987.8   0.035       0  5109.7    0.12       0
  5310.7    0.07       0  5333.4    0.12       0  5413.0   0.035       0
Bank Sta=4983.8,4987.8
Exp/Cntr=0.3,0.1

Chan Stop Cuts=-1