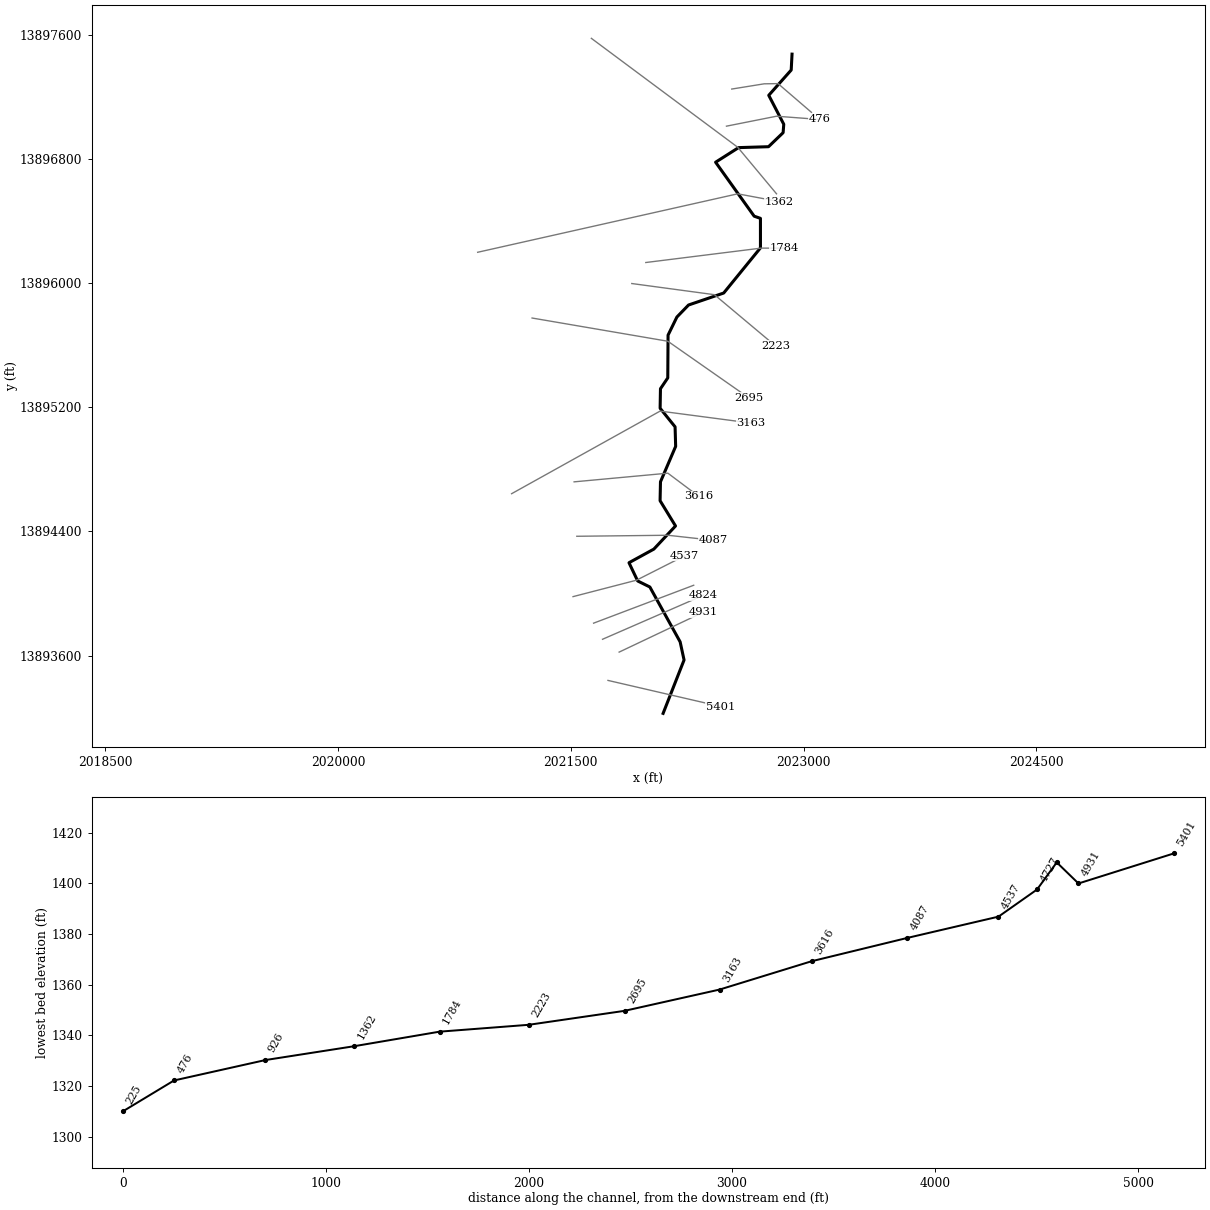
--- Stream0029_DS.prj (project) ---

Proj Title=Stream0029_DS Base Level Engineering
Current Plan=p01
Default Exp/Contr=0.3,0.1
English Units
Geom File=g01
Flow File=f01
Plan File=p01
BEGIN DESCRIPTION:
Stream0029_DS
END DESCRIPTION:

--- Stream0029_DS.p01 (plan) ---

Plan Title=Multiple Run
Short Identifier=Multiple
Geom File=g01
Flow File=f01
Subcritical Flow
K Sum by GR= 0
Std Step Tol= 0.01
Critical Tol= 0.01
Num of Std Step Trials= 20
Max Error Tol= 0.3
Flow Tol Ratio= 0.001
Split Flow NTrial= 30
Split Flow Tol= 0.02
Split Flow Ratio= 0.02
Log Output Level= 0
Friction Slope Method= 1
Unsteady Friction Slope Method= 2
Unsteady Bridges Friction Slope Method= 1
Parabolic Critical Depth
Global Vel Dist=  1 , 1 , 1
Global Log Level= 0
CheckData=True
Encroach Param= -1, 0, 0, 0
BEGIN DESCRIPTION:
Multiple Run
END DESCRIPTION:

--- Stream0029_DS.f01 (steady flow) ---

Flow Title=Multiple
Number of Profiles=7
Profile Names=10-year,25-year,50-year,1pct_min,100-year,1pct_plu,500-year
River Rch & RM= Stream0029_DS,Reach-1,5401
     645    1062    1448     960    1915    3820    3305
River Rch & RM= Stream0029_DS,Reach-1,4087
    1143    1948    2719    1839    3670    7323    6614
Boundary for River Rch & Prof#=Stream0029_DS,Reach-1,1
Up Type=0
Dn Type=3
Dn Slope=0.005
Boundary for River Rch & Prof#=Stream0029_DS,Reach-1,2
Up Type=0
Dn Type=3
Dn Slope=0.005
Boundary for River Rch & Prof#=Stream0029_DS,Reach-1,3
Up Type=0
Dn Type=3
Dn Slope=0.005
Boundary for River Rch & Prof#=Stream0029_DS,Reach-1,4
Up Type=0
Dn Type=3
Dn Slope=0.005
Boundary for River Rch & Prof#=Stream0029_DS,Reach-1,5
Up Type=0
Dn Type=3
Dn Slope=0.005
Boundary for River Rch & Prof#=Stream0029_DS,Reach-1,6
Up Type=0
Dn Type=3
Dn Slope=0.005
Boundary for River Rch & Prof#=Stream0029_DS,Reach-1,7
Up Type=0
Dn Type=3
Dn Slope=0.005

--- Stream0029_DS.g01 (geometry) ---

Geom Title=Existing Conditions

River Reach=Stream0029_DS,Reach-1
Reach XY= 30
      2022094.35     13893227.32      2022229.30     13893571.21
      2022204.05     13893688.12      2022008.87     13894041.68
      2021930.47     13894080.43      2021874.44     13894198.01
      2022034.68     13894285.76      2022174.29     13894434.79
      2022074.78     13894597.66      2022077.37     13894719.47
      2022175.12     13894947.70      2022171.46     13895073.53
      2022075.07     13895193.23      2022077.25     13895319.06
      2022124.32     13895388.92      2022126.20     13895664.50
      2022183.13     13895781.08      2022258.21     13895858.56
      2022484.71     13895935.75      2022721.47     13896226.47
      2022721.44     13896416.85      2022681.06     13896430.80
      2022432.49     13896778.59      2022580.52     13896872.65
      2022773.55     13896878.53      2022867.53     13896968.93
      2022871.69     13897023.26      2022774.95     13897209.66
      2022919.65     13897372.50      2022925.00     13897475.00

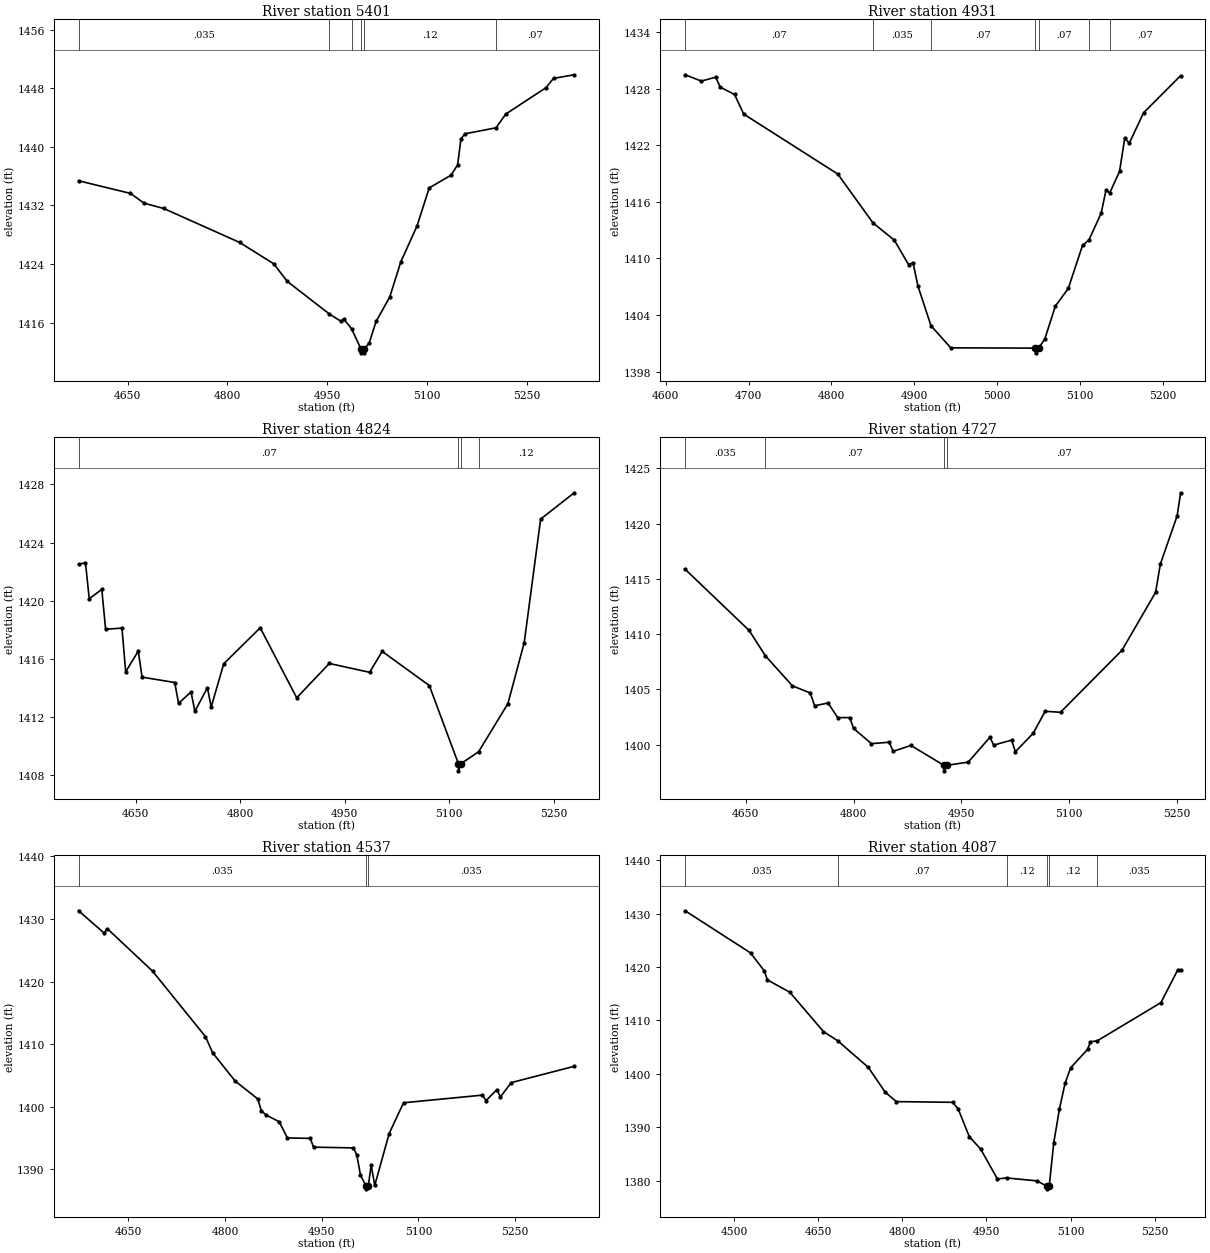
Type RM Length L Ch R = 1,5401,470,470,470
BEGIN DESCRIPTION:
Stream0029_DS 14.0
END DESCRIPTION:
XS GIS Cut Line= 2
      2021739.07     13893439.71      2022465.33     13893271.42
#Sta/Elev= 30
  4576.1 1435.37  4654.0 1433.65  4674.6 1432.31  4704.0 1431.59  4818.3 1426.95
  4869.6 1424.03  4890.1 1421.62  4953.4 1417.17  4970.3 1416.21  4975.4 1416.44
  4986.7 1415.16  5001.0 1412.37  5001.3 1411.87  5004.8 1411.87  5005.0 1412.37
  5013.0 1413.15  5023.6 1416.16  5044.1 1419.48  5060.8 1424.30  5085.2 1429.20
  5103.5 1434.40  5136.5 1436.14  5146.2 1437.54  5151.3 1441.10  5157.0 1441.78
  5204.1 1442.61  5218.6 1444.48  5279.3 1448.09  5290.5 1449.36  5321.6 1449.85
#Mann=6,-1,0
  4576.1   0.035       0  4953.4    0.07       0  4986.7    0.12       0
  5001.0    0.05       0  5005.0    0.12       0  5204.1    0.07       0
Bank Sta=5001,5005
Exp/Cntr=0.3,0.1

Type RM Length L Ch R = 1,4931,107,107,107
BEGIN DESCRIPTION:
Stream0029_DS 13.0
END DESCRIPTION:
XS GIS Cut Line= 2
      2021811.03     13893622.09      2022351.65     13893878.62
#Sta/Elev= 30
  4623.3 1429.47  4643.0 1428.80  4660.2 1429.22  4665.8 1428.16  4683.0 1427.38
  4694.1 1425.30  4807.7 1418.95  4850.2 1413.77  4875.9 1411.95  4893.1 1409.36
  4898.6 1409.54  4904.4 1407.10  4920.2 1402.88  4944.1 1400.53  5046.3 1400.50
  5046.6 1400.00  5050.3 1400.50  5057.7 1401.47  5070.4 1404.95  5086.0 1406.82
  5103.2 1411.38  5111.0 1411.97  5125.8 1414.81  5131.5 1417.23  5136.1 1416.95
  5147.9 1419.22  5154.2 1422.75  5159.7 1422.22  5176.9 1425.44  5221.7 1429.38
#Mann=7,-1,0
  4623.3    0.07       0  4850.2   0.035       0  4920.2    0.07       0
  5046.3    0.05       0  5050.3    0.07       0  5111.0    0.12       0
  5136.1    0.07       0
Bank Sta=5046.3,5050.3
Exp/Cntr=0.3,0.1

Type RM Length L Ch R = 1,4824,97,97,97
BEGIN DESCRIPTION:
Stream0029_DS 12.0
END DESCRIPTION:
XS GIS Cut Line= 2
      2021704.00     13893704.80      2022355.44     13893988.66
#Sta/Elev= 30
  4568.4 1422.51  4578.2 1422.63  4583.6 1420.15  4601.6 1420.79  4607.1 1418.05
  4630.5 1418.13  4635.9 1415.13  4653.9 1416.55  4659.4 1414.76  4706.2 1414.39
  4711.7 1412.96  4729.6 1413.74  4735.1 1412.41  4753.1 1414.03  4758.5 1412.71
  4776.5 1415.68  4828.8 1418.15  4881.1 1413.34  4927.9 1415.70  4985.7 1415.09
  5003.7 1416.53  5071.3 1414.18  5112.9 1408.82  5113.1 1408.32  5116.9 1408.82
  5141.9 1409.63  5184.0 1412.94  5207.4 1417.14  5230.9 1425.62  5279.0 1427.43
#Mann=4,-1,0
  4568.4    0.07       0  5112.9    0.05       0  5116.9    0.07       0
  5141.9    0.12       0
Bank Sta=5112.9,5116.9
Exp/Cntr=0.3,0.1

Type RM Length L Ch R = 1,4727,190,190,190
BEGIN DESCRIPTION:
Stream0029_DS 11.0
END DESCRIPTION:
XS GIS Cut Line= 2
      2021646.37     13893808.58      2022291.36     13894052.87
#Sta/Elev= 30
  4565.6 1415.87  4654.7 1410.33  4677.4 1408.03  4715.0 1405.31  4739.8 1404.67
  4745.9 1403.51  4764.6 1403.76  4778.0 1402.44  4794.8 1402.44  4800.1 1401.46
  4824.9 1400.08  4849.7 1400.21  4855.1 1399.38  4879.9 1399.92  4925.7 1398.12
  4926.0 1397.62  4929.7 1398.12  4959.7 1398.41  4989.8 1400.65  4995.2 1399.95
  5020.0 1400.40  5025.3 1399.35  5050.1 1401.02  5066.7 1403.01  5088.1 1402.92
  5173.6 1408.53  5220.4 1413.77  5227.1 1416.34  5250.5 1420.71  5255.3 1422.79
#Mann=4,-1,0
  4565.6   0.035       0  4677.4    0.07       0  4925.7    0.05       0
  4929.7    0.07       0
Bank Sta=4925.7,4929.7
Exp/Cntr=0.3,0.1

Type RM Length L Ch R = 1,4537,450,450,450
BEGIN DESCRIPTION:
Stream0029_DS 10.0
END DESCRIPTION:
XS GIS Cut Line= 3
      2021513.98     13893979.54      2021922.55     13894085.37
      2022231.54     13894241.84
#Sta/Elev= 30
  4573.1 1431.32  4612.6 1427.76  4617.7 1428.45  4687.8 1421.67  4769.8 1411.21
  4780.8 1408.65  4815.6 1404.14  4851.0 1401.25  4856.2 1399.41  4863.4 1398.72
  4884.1 1397.62  4896.8 1395.04  4932.2 1394.96  4937.4 1393.56  4999.3 1393.44
  5004.5 1392.28  5010.1 1389.12  5018.3 1387.40  5018.6 1386.90  5022.3 1387.40
  5026.7 1390.68  5032.3 1387.45  5054.6 1395.73  5076.9 1400.65  5199.3 1401.87
  5204.9 1400.99  5221.6 1402.75  5227.2 1401.59  5243.9 1403.87  5341.5 1406.47
#Mann=3,-1,0
  4573.1   0.035       0  5018.3   0.035       0  5022.3   0.035       0
Bank Sta=5018.3,5022.3
Exp/Cntr=0.3,0.1

Type RM Length L Ch R = 1,4087,471,471,471
BEGIN DESCRIPTION:
Stream0029_DS 9.0
END DESCRIPTION:
XS GIS Cut Line= 3
      2021538.30     13894368.43      2022125.00     13894375.00
      2022419.85     13894342.27
#Sta/Elev= 30
  4412.9 1430.54  4529.6 1422.65  4554.0 1419.30  4559.6 1417.60  4599.6 1415.29
  4659.6 1407.92  4685.1 1406.19  4739.6 1401.21  4769.6 1396.58  4789.6 1394.81
  4889.6 1394.68  4899.6 1393.48  4919.6 1388.22  4939.6 1385.96  4969.6 1380.34
  4986.3 1380.52  5039.9 1379.97  5058.0 1378.98  5058.3 1378.48  5062.0 1378.98
  5070.1 1387.09  5080.1 1393.36  5090.2 1398.22  5100.3 1401.16  5130.4 1404.59
  5135.5 1406.01  5147.8 1406.20  5261.2 1413.35  5291.3 1419.50  5296.3 1419.50
#Mann=6,-1,0
  4412.9   0.035       0  4685.1    0.07       0  4986.3    0.12       0
  5058.0    0.05       0  5062.0    0.12       0  5147.8   0.035       0
Bank Sta=5058,5062
Exp/Cntr=0.3,0.1

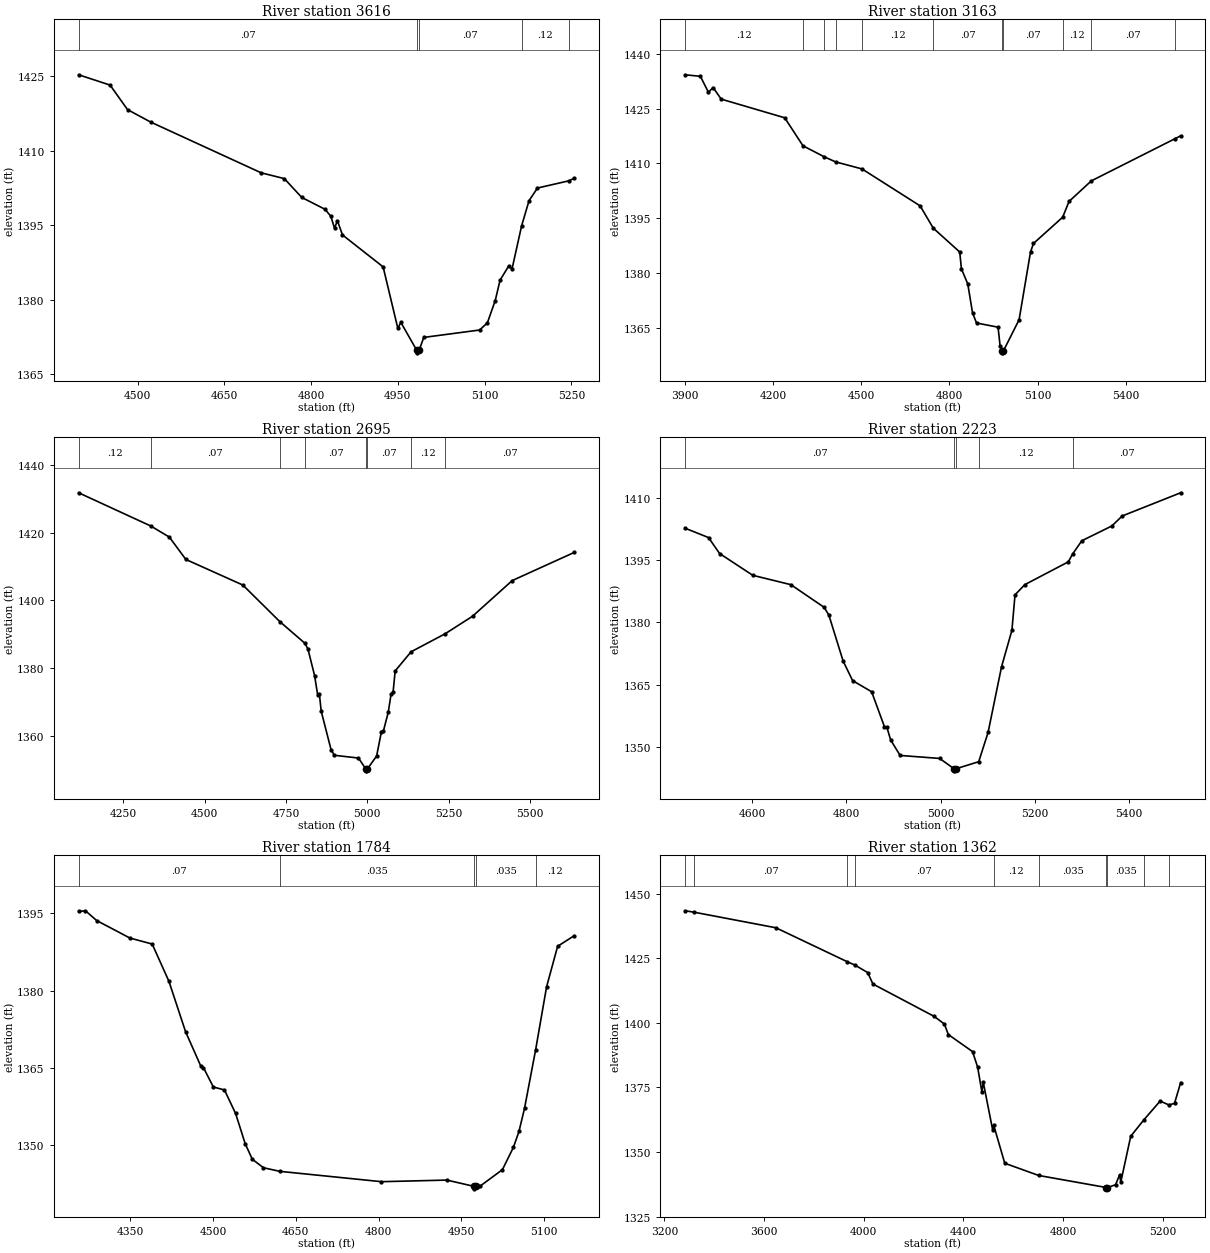
Type RM Length L Ch R = 1,3616,453,453,453
BEGIN DESCRIPTION:
Stream0029_DS 8.0
END DESCRIPTION:
XS GIS Cut Line= 3
      2021520.88     13894719.12      2022125.00     13894775.00
      2022325.00     13894625.00
#Sta/Elev= 30
  4398.2 1425.33  4452.6 1423.25  4482.7 1418.31  4522.9 1415.79  4713.7 1405.57
  4753.8 1404.40  4784.0 1400.60  4824.1 1398.22  4834.2 1396.82  4840.6 1394.39
  4845.6 1395.92  4854.3 1393.05  4924.6 1386.61  4950.1 1374.19  4955.2 1375.43
  4982.8 1369.78  4983.1 1369.28  4986.8 1369.78  4994.9 1372.39  5091.4 1373.88
  5104.9 1375.34  5118.4 1379.81  5126.8 1383.93  5141.4 1386.73  5147.6 1386.25
  5164.0 1394.87  5176.8 1399.93  5191.4 1402.50  5246.3 1403.97  5254.9 1404.48
#Mann=5,-1,0
  4398.2    0.07       0  4982.8    0.05       0  4986.8    0.07       0
  5164.0    0.12       0  5246.3    0.07       0
Bank Sta=4982.8,4986.8
Exp/Cntr=0.3,0.1

Type RM Length L Ch R = 1,3163,468,468,468
BEGIN DESCRIPTION:
Stream0029_DS 7.0
END DESCRIPTION:
XS GIS Cut Line= 3
      2021118.18     13894642.75      2022075.00     13895175.00
      2022661.64     13895097.81
#Sta/Elev= 30
  3900.5 1434.27  3952.5 1433.85  3979.9 1429.48  3995.9 1430.78  4023.4 1427.60
  4239.5 1422.49  4301.7 1414.82  4374.8 1411.77  4412.6 1410.41  4502.6 1408.48
  4700.4 1398.36  4745.1 1392.26  4835.2 1385.72  4841.0 1381.12  4862.7 1376.94
  4878.8 1369.05  4892.4 1366.27  4965.7 1365.13  4972.5 1360.09  4979.7 1358.60
  4979.9 1358.10  4983.7 1358.60  5037.3 1367.17  5076.1 1385.71  5086.2 1388.06
  5185.7 1395.26  5207.2 1399.57  5283.0 1405.20  5568.6 1416.79  5587.1 1417.53
#Mann=11,-1,0
  3900.5    0.12       0  4301.7    0.07       0  4374.8    0.12       0
  4412.6    0.07       0  4502.6    0.12       0  4745.1    0.07       0
  4979.7    0.05       0  4983.7    0.07       0  5185.7    0.12       0
  5283.0    0.07       0  5568.6    0.12       0
Bank Sta=4979.7,4983.7
Exp/Cntr=0.3,0.1

Type RM Length L Ch R = 1,2695,472,472,472
BEGIN DESCRIPTION:
Stream0029_DS 6.0
END DESCRIPTION:
XS GIS Cut Line= 3
      2021250.10     13895774.68      2022125.00     13895625.00
      2022645.90     13895260.81
#Sta/Elev= 30
  4112.8 1431.80  4334.6 1421.99  4391.7 1418.71  4442.4 1412.11  4617.5 1404.56
  4731.0 1393.78  4808.6 1387.34  4817.8 1385.61  4838.1 1377.82  4847.7 1372.03
  4852.7 1372.45  4858.4 1367.32  4888.8 1355.92  4899.0 1354.29  4972.9 1353.48
  4995.9 1350.20  4996.1 1349.70  4999.9 1350.20  5028.8 1354.08  5043.6 1361.31
  5049.7 1361.48  5064.5 1366.99  5073.2 1372.34  5079.3 1372.84  5085.8 1379.20
  5134.7 1384.85  5239.4 1390.17  5323.5 1395.34  5445.6 1405.88  5636.0 1414.18
#Mann=8,-1,0
  4112.8    0.12       0  4334.6    0.07       0  4731.0   0.035       0
  4808.6    0.07       0  4995.9    0.05       0  4999.9    0.07       0
  5134.7    0.12       0  5239.4    0.07       0
Bank Sta=4995.9,4999.9
Exp/Cntr=0.3,0.1

Type RM Length L Ch R = 1,2223,439,439,439
BEGIN DESCRIPTION:
Stream0029_DS 5.0
END DESCRIPTION:
XS GIS Cut Line= 3
      2021892.47     13895996.90      2022425.00     13895925.00
      2022819.55     13895594.11
#Sta/Elev= 30
  4457.3 1402.68  4507.1 1400.42  4530.5 1396.58  4601.1 1391.32  4681.9 1389.07
  4752.5 1383.61  4762.6 1381.73  4792.8 1370.68  4813.0 1365.94  4853.4 1363.26
  4880.6 1354.83  4885.6 1354.76  4893.8 1351.64  4913.9 1347.90  4997.9 1347.18
  5028.4 1344.69  5028.7 1344.19  5032.4 1344.69  5080.8 1346.39  5100.7 1353.45
  5129.3 1369.29  5151.3 1378.06  5157.9 1386.62  5178.8 1389.08  5271.1 1394.57
  5280.0 1396.42  5299.7 1399.65  5363.5 1403.22  5385.6 1405.63  5509.6 1411.22
#Mann=5,-1,0
  4457.3    0.07       0  5028.4    0.05       0  5032.4    0.07       0
  5080.8    0.12       0  5280.0    0.07       0
Bank Sta=5028.4,5032.4
Exp/Cntr=0.3,0.1

Type RM Length L Ch R = 1,1784,422,422,422
BEGIN DESCRIPTION:
Stream0029_DS 4.0
END DESCRIPTION:
XS GIS Cut Line= 3
      2021982.70     13896132.31      2022725.00     13896225.00
      2022875.03     13896225.00
#Sta/Elev= 30
  4256.5 1395.36  4268.9 1395.50  4289.1 1393.61  4349.5 1390.20  4389.8 1389.04
  4420.1 1381.81  4450.3 1372.01  4477.7 1365.38  4482.8 1365.01  4500.7 1361.26
  4520.8 1360.69  4541.0 1356.12  4558.4 1350.24  4571.2 1347.24  4591.4 1345.58
  4621.0 1344.88  4805.4 1342.87  4923.9 1343.18  4972.3 1341.98  4972.6 1341.48
  4976.3 1341.98  4984.4 1342.03  5024.6 1345.21  5044.6 1349.57  5054.6 1352.65
  5064.6 1357.11  5084.8 1368.53  5104.6 1380.73  5124.6 1388.60  5154.6 1390.65
#Mann=5,-1,0
  4256.5    0.07       0  4621.0   0.035       0  4972.3   0.035       0
  4976.3   0.035       0  5084.8    0.12       0
Bank Sta=4972.3,4976.3
Exp/Cntr=0.3,0.1

Type RM Length L Ch R = 1,1362,436,436,436
BEGIN DESCRIPTION:
Stream0029_DS 3.0
END DESCRIPTION:
XS GIS Cut Line= 3
      2020899.45     13896198.30      2022575.00     13896575.00
      2022841.89     13896525.04
#Sta/Elev= 30
  3282.9 1443.42  3317.5 1442.90  3647.3 1436.84  3933.4 1423.70  3963.4 1422.44
  4015.6 1419.50  4036.8 1415.05  4282.8 1402.50  4323.8 1399.53  4339.2 1395.49
  4436.5 1388.89  4457.0 1382.88  4474.2 1373.20  4479.3 1377.16  4517.5 1358.47
  4521.3 1360.42  4565.9 1345.63  4702.0 1340.90  4974.1 1336.22  4974.3 1335.72
  4978.1 1336.22  5010.5 1337.30  5026.6 1341.06  5031.7 1338.39  5071.5 1356.09
  5123.8 1362.40  5189.5 1369.71  5224.7 1368.22  5247.2 1368.82  5271.8 1376.85
#Mann=10,-1,0
  3282.9    0.12       0  3317.5    0.07       0  3933.4    0.12       0
  3963.4    0.07       0  4521.3    0.12       0  4702.0   0.035       0
  4974.1   0.035       0  4978.1   0.035       0  5123.8    0.12       0
  5224.7    0.07       0
Bank Sta=4974.1,4978.1
Exp/Cntr=0.3,0.1

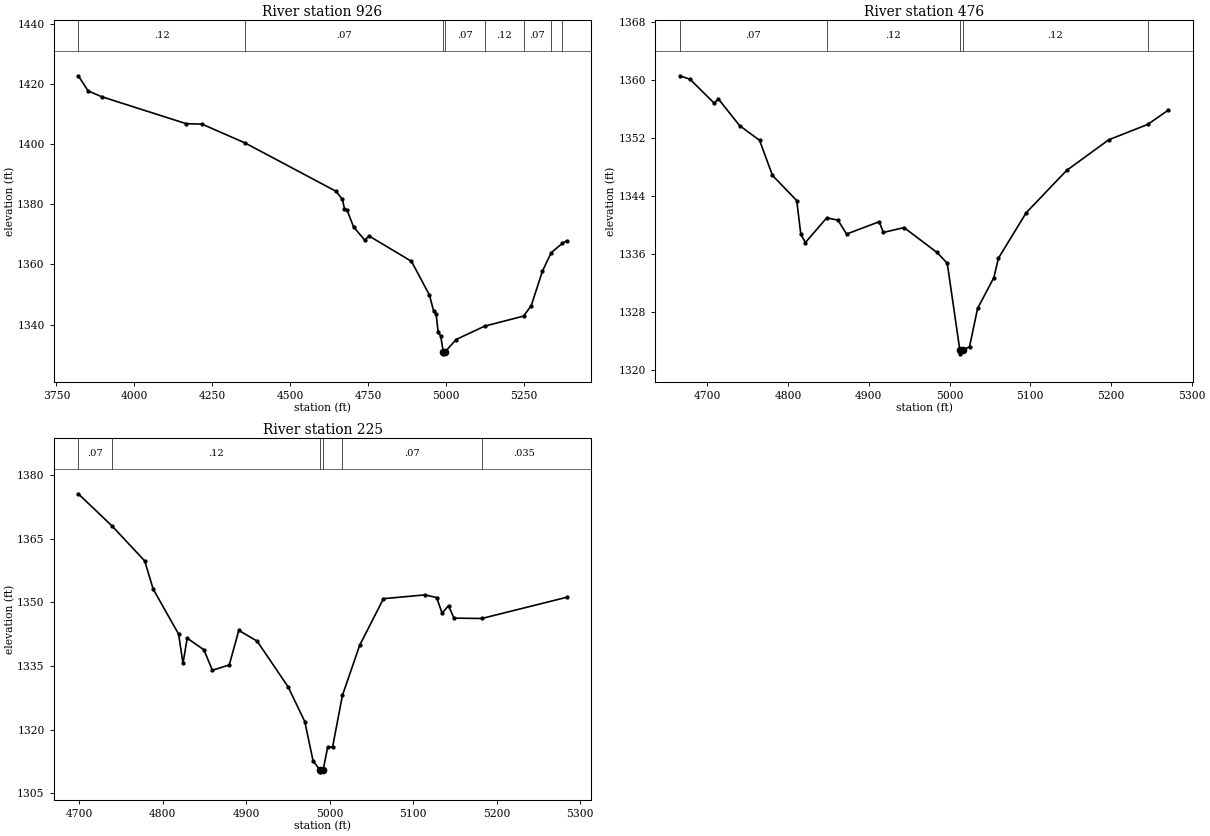
Type RM Length L Ch R = 1,926,450,450,450
BEGIN DESCRIPTION:
Stream0029_DS 2.0
END DESCRIPTION:
XS GIS Cut Line= 3
      2021632.00     13897576.78      2022575.00     13896875.00
      2022825.01     13896574.99
#Sta/Elev= 30
  3820.2 1422.77  3851.7 1417.75  3895.5 1415.80  4166.6 1406.82  4216.7 1406.70
  4355.0 1400.42  4646.4 1384.35  4667.2 1381.64  4673.4 1378.61  4681.8 1378.09
  4702.6 1372.52  4738.1 1368.14  4752.7 1369.46  4888.3 1361.05  4945.8 1349.87
  4959.2 1344.62  4967.5 1343.44  4973.8 1337.62  4982.1 1336.16  4990.6 1330.77
  4990.8 1330.27  4994.6 1330.77  5031.5 1335.04  5122.8 1339.48  5247.6 1342.82
  5272.3 1346.28  5308.1 1357.75  5336.4 1363.92  5372.4 1367.07  5386.2 1367.88
#Mann=8,-1,0
  3820.2    0.12       0  4355.0    0.07       0  4990.6    0.05       0
  4994.6    0.07       0  5122.8    0.12       0  5247.6    0.07       0
  5336.4    0.12       0  5372.4    0.07       0
Bank Sta=4990.6,4994.6
Exp/Cntr=0.3,0.1

Type RM Length L Ch R = 1,476,251,251,251
BEGIN DESCRIPTION:
Stream0029_DS 1.0
END DESCRIPTION:
XS GIS Cut Line= 3
      2022502.50     13897010.86      2022825.00     13897075.00
      2023100.60     13897054.24
#Sta/Elev= 30
  4665.9 1360.58  4678.6 1360.09  4708.5 1356.79  4713.5 1357.41  4739.8 1353.71
  4764.7 1351.67  4780.6 1346.84  4810.7 1343.36  4815.8 1338.68  4821.4 1337.57
  4847.9 1340.98  4861.8 1340.66  4872.4 1338.74  4912.9 1340.44  4918.0 1338.96
  4943.7 1339.63  4984.5 1336.20  4997.2 1334.71  5012.8 1322.71  5013.0 1322.21
  5016.8 1322.71  5024.8 1323.20  5034.8 1328.49  5054.9 1332.72  5060.6 1335.41
  5095.0 1341.68  5145.1 1347.52  5197.3 1351.75  5245.4 1353.86  5271.1 1355.84
#Mann=5,-1,0
  4665.9    0.07       0  4847.9    0.12       0  5012.8    0.05       0
  5016.8    0.12       0  5245.4   0.035       0
Bank Sta=5012.8,5016.8
Exp/Cntr=0.3,0.1

Type RM Length L Ch R = 1,225,0,0,0
BEGIN DESCRIPTION:
Stream0029_DS 0.0
END DESCRIPTION:
XS GIS Cut Line= 4
      2022536.47     13897250.00      2022745.67     13897283.73
      2022834.86     13897285.04      2023050.02     13897099.98
#Sta/Elev= 30
  4698.9 1375.64  4738.8 1368.15  4778.4 1359.82  4788.6 1353.15  4819.0 1342.56
  4824.3 1335.65  4829.3 1341.59  4849.3 1338.85  4859.5 1334.02  4879.7 1335.27
  4891.1 1343.42  4913.0 1340.90  4950.1 1330.12  4970.1 1321.92  4980.1 1312.59
  4988.1 1310.56  4988.4 1310.06  4992.1 1310.56  4997.6 1315.92  5003.4 1315.92
  5015.2 1328.10  5035.8 1339.88  5064.3 1350.90  5113.7 1351.79  5128.0 1351.17
  5134.5 1347.50  5142.2 1349.24  5148.8 1346.31  5182.1 1346.23  5283.8 1351.23
#Mann=6,-1,0
  4698.9    0.07       0  4738.8    0.12       0  4988.1    0.05       0
  4992.1    0.12       0  5015.2    0.07       0  5182.1   0.035       0
Bank Sta=4988.1,4992.1
Exp/Cntr=0.3,0.1

Chan Stop Cuts=-1