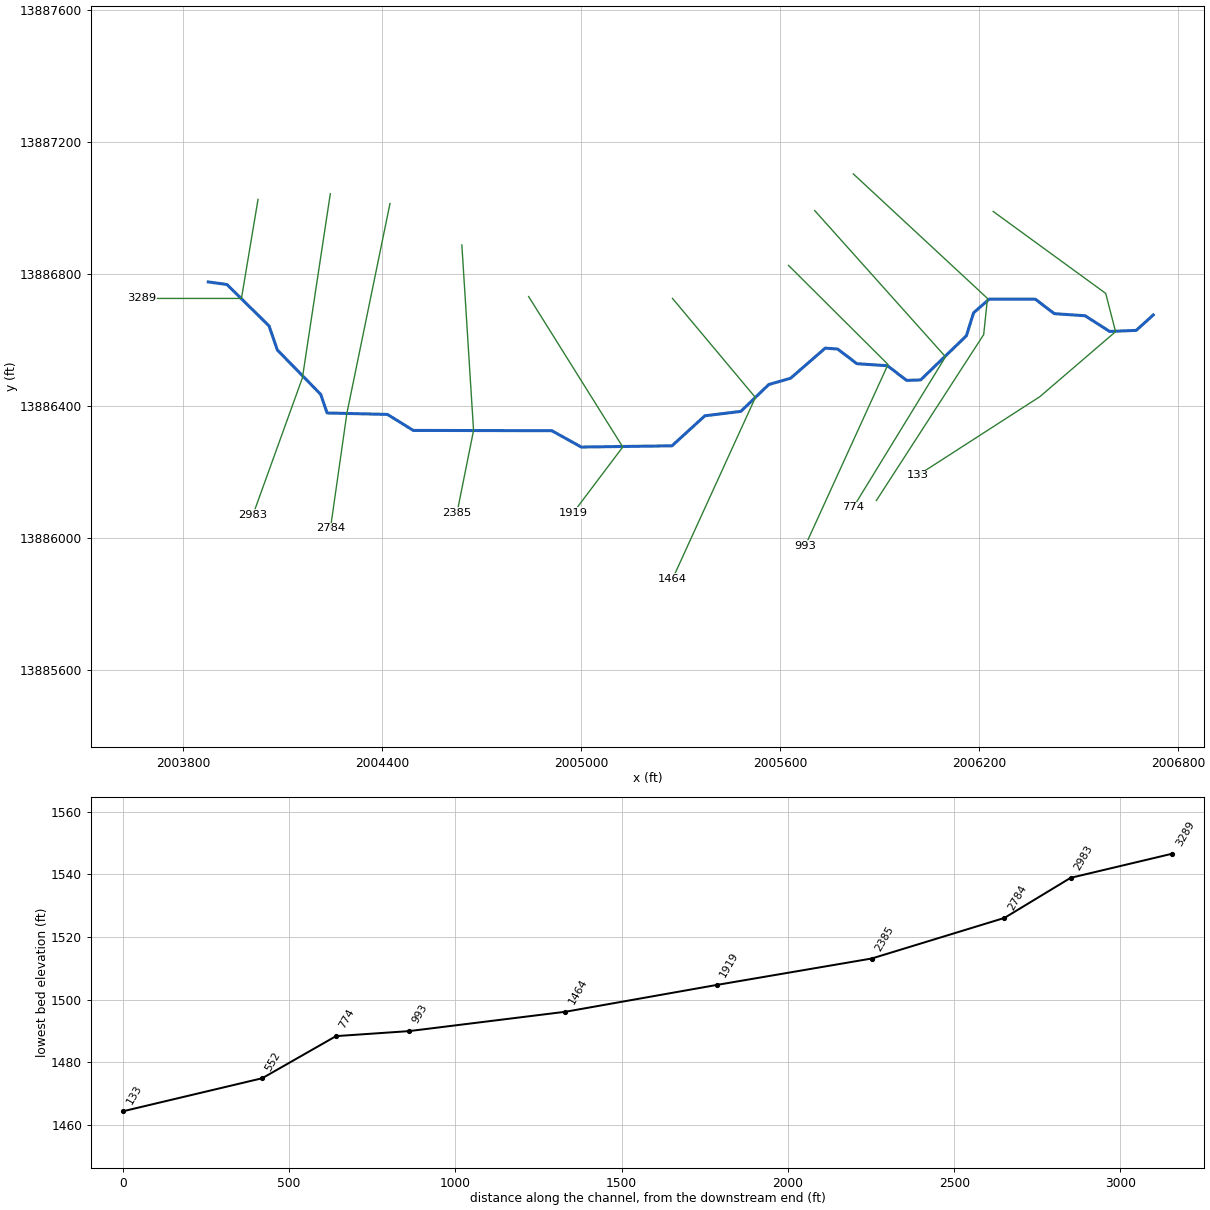
--- Stream0030_DS.prj (project) ---

Proj Title=Stream0030_DS Base Level Engineering
Current Plan=p01
Default Exp/Contr=0.3,0.1
English Units
Geom File=g01
Flow File=f01
Plan File=p01
BEGIN DESCRIPTION:
Stream0030_DS
END DESCRIPTION:

--- Stream0030_DS.p01 (plan) ---

Plan Title=Multiple Run
Short Identifier=Multiple
Geom File=g01
Flow File=f01
Subcritical Flow
K Sum by GR= 0
Std Step Tol= 0.01
Critical Tol= 0.01
Num of Std Step Trials= 20
Max Error Tol= 0.3
Flow Tol Ratio= 0.001
Split Flow NTrial= 30
Split Flow Tol= 0.02
Split Flow Ratio= 0.02
Log Output Level= 0
Friction Slope Method= 1
Unsteady Friction Slope Method= 2
Unsteady Bridges Friction Slope Method= 1
Parabolic Critical Depth
Global Vel Dist=  1 , 1 , 1
Global Log Level= 0
CheckData=True
Encroach Param= -1, 0, 0, 0
BEGIN DESCRIPTION:
Multiple Run
END DESCRIPTION:

--- Stream0030_DS.f01 (steady flow) ---

Flow Title=Multiple
Number of Profiles=7
Profile Names=10-year,25-year,50-year,1pct_min,100-year,1pct_plu,500-year
River Rch & RM= Stream0030_DS,Reach-1,3289
     655    1092    1504    1007    2010    4010    3546
Boundary for River Rch & Prof#=Stream0030_DS,Reach-1,1
Up Type=0
Dn Type=3
Dn Slope=0.005
Boundary for River Rch & Prof#=Stream0030_DS,Reach-1,2
Up Type=0
Dn Type=3
Dn Slope=0.005
Boundary for River Rch & Prof#=Stream0030_DS,Reach-1,3
Up Type=0
Dn Type=3
Dn Slope=0.005
Boundary for River Rch & Prof#=Stream0030_DS,Reach-1,4
Up Type=0
Dn Type=3
Dn Slope=0.005
Boundary for River Rch & Prof#=Stream0030_DS,Reach-1,5
Up Type=0
Dn Type=3
Dn Slope=0.005
Boundary for River Rch & Prof#=Stream0030_DS,Reach-1,6
Up Type=0
Dn Type=3
Dn Slope=0.005
Boundary for River Rch & Prof#=Stream0030_DS,Reach-1,7
Up Type=0
Dn Type=3
Dn Slope=0.005

--- Stream0030_DS.g01 (geometry) ---

Geom Title=Existing Conditions

River Reach=Stream0030_DS,Reach-1
Reach XY= 30
      2003875.00     13886775.00      2003931.21     13886767.24
      2004058.35     13886641.67      2004083.16     13886568.95
      2004214.09     13886434.37      2004233.30     13886378.07
      2004415.34     13886373.62      2004493.27     13886325.21
      2004911.08     13886324.32      2004999.92     13886274.80
      2005273.53     13886278.55      2005372.58     13886369.46
      2005481.16     13886382.88      2005565.33     13886464.20
      2005631.04     13886483.18      2005735.62     13886574.40
      2005773.25     13886571.66      2005830.97     13886527.38
      2005923.42     13886521.11      2005981.13     13886476.78
      2006023.37     13886478.13      2006161.36     13886611.80
      2006183.02     13886681.38      2006230.26     13886722.92
      2006369.47     13886722.63      2006426.60     13886678.86
      2006519.43     13886672.53      2006593.31     13886625.04
      2006673.60     13886628.19      2006725.00     13886675.00

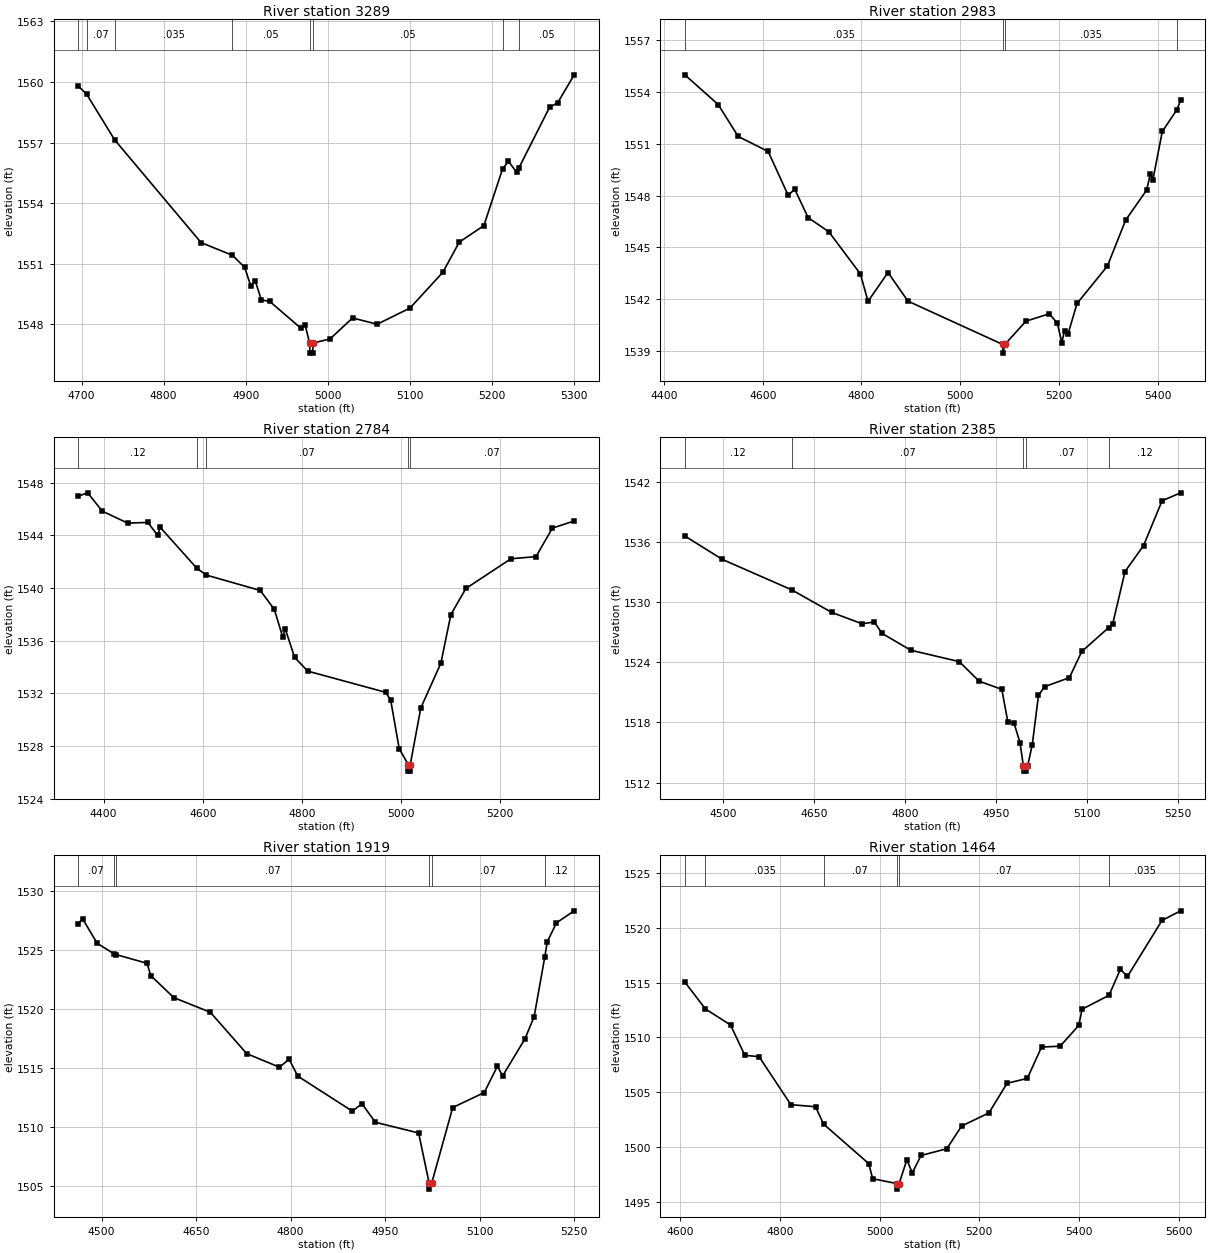
Type RM Length L Ch R = 1,3289,306,306,306
BEGIN DESCRIPTION:
Stream0030_DS 7.0
END DESCRIPTION:
XS GIS Cut Line= 3
      2004025.00     13887024.99      2003975.00     13886725.00
      2003675.02     13886725.00
#Sta/Elev= 30
  4696.1 1559.79  4706.1 1559.40  4740.4 1557.13  4845.6 1552.05  4883.9 1551.42
  4898.8 1550.82  4906.4 1549.88  4911.5 1550.17  4919.1 1549.21  4929.3 1549.14
  4967.3 1547.81  4972.3 1547.99  4977.9 1547.08  4978.2 1546.58  4981.7 1546.58
  4981.9 1547.08  5002.7 1547.28  5030.2 1548.32  5060.2 1548.01  5100.2 1548.81
  5140.2 1550.58  5160.2 1552.07  5190.2 1552.89  5213.0 1555.70  5220.2 1556.07
  5230.2 1555.52  5232.7 1555.73  5270.2 1558.74  5280.2 1558.97  5300.2 1560.35
#Mann=8,-1,0
  4696.1   0.035       0  4706.1    0.07       0  4740.4   0.035       0
  4883.9    0.05       0  4977.9    0.05       0  4981.9    0.05       0
  5213.0   0.035       0  5232.7    0.05       0
Bank Sta=4977.9,4981.9
Exp/Cntr=0.3,0.1

Type RM Length L Ch R = 1,2983,199,199,199
BEGIN DESCRIPTION:
Stream0030_DS 6.5
END DESCRIPTION:
XS GIS Cut Line= 3
      2004242.97     13887041.88      2004158.87     13886484.50
      2004009.98     13886070.13
#Sta/Elev= 30
  4442.2 1554.99  4509.8 1553.27  4550.3 1551.42  4611.0 1550.55  4651.4 1548.02
  4664.9 1548.36  4691.9 1546.72  4733.8 1545.90  4797.7 1543.46  4813.2 1541.87
  4853.7 1543.54  4894.1 1541.88  5086.2 1539.37  5086.4 1538.87  5090.2 1539.37
  5132.9 1540.72  5180.3 1541.15  5196.6 1540.60  5205.7 1539.48  5211.1 1540.18
  5217.9 1539.95  5236.5 1541.75  5297.9 1543.91  5334.8 1546.57  5377.3 1548.31
  5384.8 1549.24  5390.1 1548.92  5409.1 1551.71  5438.5 1552.96  5446.2 1553.52
#Mann=4,-1,0
  4442.2   0.035       0  5086.2   0.035       0  5090.2   0.035       0
  5438.5    0.07       0
Bank Sta=5086.2,5090.2
Exp/Cntr=0.3,0.1

Type RM Length L Ch R = 1,2784,399,399,399
BEGIN DESCRIPTION:
Stream0030_DS 6.0
END DESCRIPTION:
XS GIS Cut Line= 3
      2004422.97     13887012.35      2004292.87     13886376.34
      2004243.51     13886028.81
#Sta/Elev= 30
  4349.1 1546.99  4367.9 1547.24  4397.4 1545.85  4448.5 1544.94  4489.3 1544.99
  4509.1 1544.01  4514.2 1544.62  4588.1 1541.51  4607.2 1540.99  4716.1 1539.82
  4744.5 1538.38  4761.4 1536.28  4766.6 1536.89  4785.3 1534.74  4811.9 1533.69
  4969.0 1532.08  4979.2 1531.49  4996.4 1527.79  5014.7 1526.59  5015.0 1526.09
  5018.5 1526.09  5018.7 1526.59  5040.0 1530.90  5080.4 1534.29  5100.6 1537.99
  5130.9 1539.97  5221.8 1542.23  5272.3 1542.39  5305.4 1544.56  5349.3 1545.10
#Mann=5,-1,0
  4349.1    0.12       0  4588.1   0.035       0  4607.2    0.07       0
  5014.7    0.05       0  5018.7    0.07       0
Bank Sta=5014.7,5018.7
Exp/Cntr=0.3,0.1

Type RM Length L Ch R = 1,2385,466,466,466
BEGIN DESCRIPTION:
Stream0030_DS 5.0
END DESCRIPTION:
XS GIS Cut Line= 3
      2004639.76     13886886.98      2004675.00     13886325.00
      2004625.01     13886075.03
#Sta/Elev= 30
  4436.9 1536.58  4499.0 1534.24  4613.4 1531.21  4679.4 1528.96  4729.5 1527.83
  4749.5 1528.01  4762.4 1526.87  4809.6 1525.20  4889.8 1524.06  4922.5 1522.11
  4959.9 1521.30  4969.9 1518.03  4979.9 1517.97  4990.0 1515.97  4995.5 1513.65
  4995.7 1513.15  4999.2 1513.15  4999.5 1513.65  5002.5 1513.65  5010.2 1515.80
  5020.4 1520.70  5030.6 1521.57  5071.4 1522.46  5091.8 1525.07  5136.2 1527.45
  5142.8 1527.81  5163.2 1533.04  5193.7 1535.62  5224.3 1540.09  5254.9 1540.88
#Mann=5,-1,0
  4436.9    0.12       0  4613.4    0.07       0  4995.5    0.05       0
  4999.5    0.07       0  5136.2    0.12       0
Bank Sta=4995.5,4999.5
Exp/Cntr=0.3,0.1

Type RM Length L Ch R = 1,1919,455,455,455
BEGIN DESCRIPTION:
Stream0030_DS 4.0
END DESCRIPTION:
XS GIS Cut Line= 3
      2004841.17     13886730.68      2005125.00     13886275.00
      2004975.03     13886075.04
#Sta/Elev= 30
  4463.1 1527.24  4469.8 1527.65  4493.1 1525.56  4519.2 1524.69  4523.0 1524.61
  4572.2 1523.87  4578.0 1522.83  4614.6 1520.96  4672.5 1519.72  4730.3 1516.21
  4782.2 1515.06  4797.6 1515.73  4811.4 1514.30  4897.9 1511.33  4913.2 1511.96
  4934.4 1510.39  5003.1 1509.48  5019.8 1505.22  5020.1 1504.72  5023.8 1505.22
  5057.2 1511.64  5107.2 1512.91  5128.1 1515.14  5136.4 1514.32  5171.8 1517.46
  5186.4 1519.35  5203.3 1524.41  5207.2 1525.69  5221.8 1527.30  5249.9 1528.32
#Mann=6,-1,0
  4463.1    0.07       0  4519.2    0.12       0  4523.0    0.07       0
  5019.8    0.05       0  5023.8    0.07       0  5203.3    0.12       0
Bank Sta=5019.8,5023.8
Exp/Cntr=0.3,0.1

Type RM Length L Ch R = 1,1464,471,471,471
BEGIN DESCRIPTION:
Stream0030_DS 3.0
END DESCRIPTION:
XS GIS Cut Line= 3
      2005274.99     13886725.01      2005525.00     13886425.00
      2005274.99     13885874.98
#Sta/Elev= 30
  4609.4 1515.05  4650.7 1512.60  4701.2 1511.13  4729.8 1508.37  4758.5 1508.24
  4822.2 1503.87  4871.7 1503.68  4887.7 1502.10  4978.4 1498.50  4986.3 1497.12
  5035.3 1496.67  5035.5 1496.17  5039.3 1496.67  5054.9 1498.84  5065.8 1497.65
  5083.4 1499.24  5135.0 1499.85  5164.7 1501.92  5219.6 1503.12  5255.9 1505.82
  5296.5 1506.26  5325.1 1509.12  5362.4 1509.20  5399.8 1511.09  5406.4 1512.57
  5460.5 1513.84  5483.2 1516.21  5497.5 1515.56  5566.7 1520.66  5604.1 1521.54
#Mann=6,-1,0
  4609.4    0.07       0  4650.7   0.035       0  4887.7    0.07       0
  5035.3    0.05       0  5039.3    0.07       0  5460.5   0.035       0
Bank Sta=5035.3,5039.3
Exp/Cntr=0.3,0.1

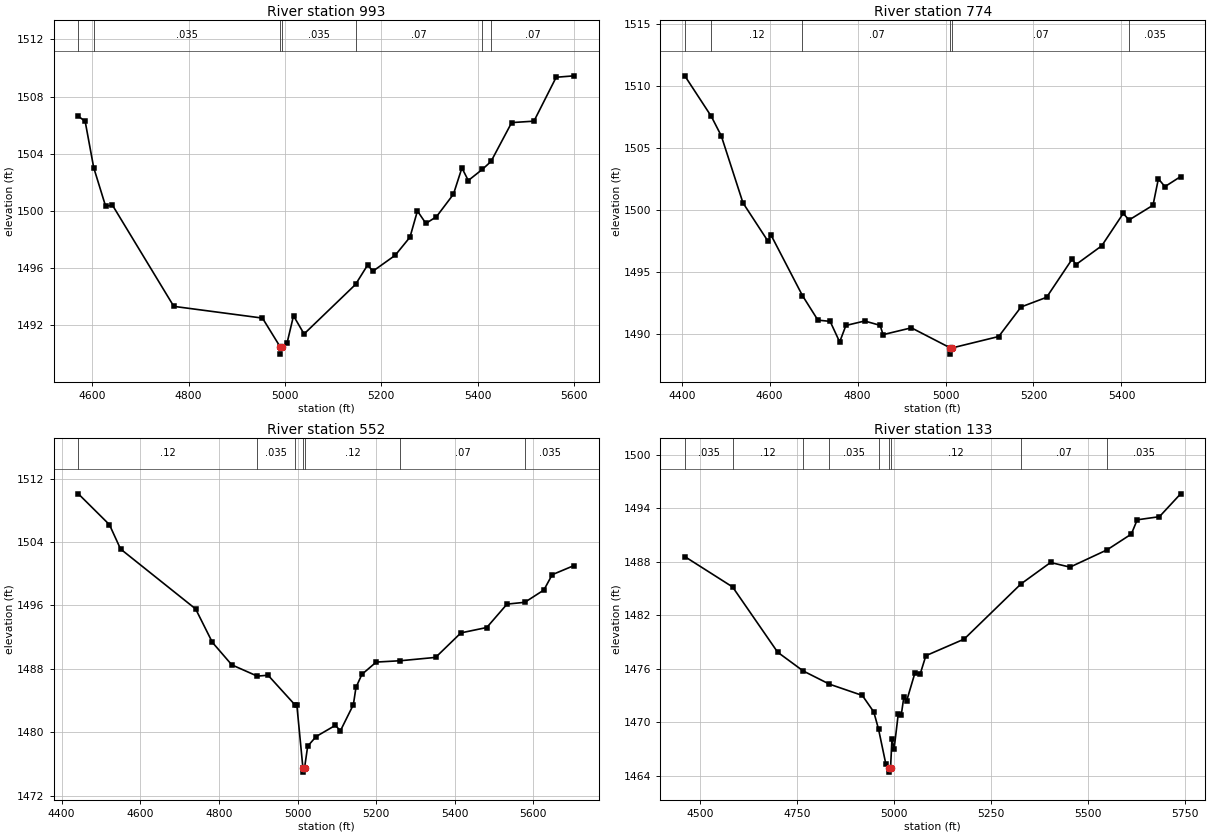
Type RM Length L Ch R = 1,993,219,219,219
BEGIN DESCRIPTION:
Stream0030_DS 2.0
END DESCRIPTION:
XS GIS Cut Line= 3
      2005624.98     13886825.02      2005925.00     13886525.00
      2005675.02     13885975.04
#Sta/Elev= 30
  4571.5 1506.63  4585.7 1506.26  4603.4 1503.03  4628.1 1500.33  4642.2 1500.41
  4769.5 1493.33  4953.4 1492.51  4990.3 1490.49  4990.5 1489.99  4994.3 1490.49
  5004.6 1490.79  5017.8 1492.67  5039.7 1491.40  5146.4 1494.86  5171.5 1496.22
  5182.5 1495.79  5228.7 1496.90  5259.4 1498.17  5274.8 1500.00  5292.4 1499.13
  5314.3 1499.60  5349.5 1501.17  5367.1 1503.01  5380.3 1502.13  5409.5 1502.91
  5427.4 1503.46  5470.3 1506.18  5516.5 1506.28  5562.6 1509.35  5599.9 1509.45
#Mann=7,-1,0
  4571.5    0.07       0  4603.4   0.035       0  4990.3   0.035       0
  4994.3   0.035       0  5146.4    0.07       0  5409.5   0.035       0
  5427.4    0.07       0
Bank Sta=4990.3,4994.3
Exp/Cntr=0.3,0.1

Type RM Length L Ch R = 1,774,222,222,222
BEGIN DESCRIPTION:
Stream0030_DS 1.5
END DESCRIPTION:
XS GIS Cut Line= 3
      2005704.01     13886991.07      2006098.41     13886548.24
      2005820.02     13886091.84
#Sta/Elev= 30
  4407.0 1510.83  4467.3 1507.56  4490.0 1505.99  4539.3 1500.59  4596.2 1497.50
  4602.9 1498.01  4674.5 1493.12  4709.7 1491.14  4737.5 1491.04  4759.2 1489.38
  4773.4 1490.71  4816.1 1491.07  4851.2 1490.72  4857.9 1489.97  4922.3 1490.52
  5010.9 1488.90  5011.1 1488.40  5014.9 1488.90  5120.9 1489.82  5171.7 1492.20
  5229.8 1492.98  5287.9 1496.06  5296.6 1495.62  5355.2 1497.13  5404.1 1499.74
  5417.3 1499.21  5471.8 1500.40  5484.0 1502.53  5498.9 1501.90  5534.6 1502.71
#Mann=6,-1,0
  4407.0    0.07       0  4467.3    0.12       0  4674.5    0.07       0
  5010.9    0.05       0  5014.9    0.07       0  5417.3   0.035       0
Bank Sta=5010.9,5014.9
Exp/Cntr=0.3,0.1

Type RM Length L Ch R = 1,552,419,419,419
BEGIN DESCRIPTION:
Stream0030_DS 1.0
END DESCRIPTION:
XS GIS Cut Line= 4
      2005820.33     13887102.22      2006225.00     13886725.00
      2006213.53     13886615.51      2005889.86     13886112.80
#Sta/Elev= 30
  4442.5 1510.07  4521.6 1506.18  4549.9 1503.11  4740.9 1495.55  4783.4 1491.34
  4832.8 1488.50  4897.6 1487.08  4925.1 1487.19  4992.9 1483.49  4998.2 1483.49
  5013.8 1475.47  5014.1 1474.97  5017.8 1475.47  5025.9 1478.24  5047.4 1479.46
  5096.3 1480.87  5109.1 1480.18  5142.1 1483.48  5148.7 1485.65  5163.8 1487.30
  5200.2 1488.85  5261.9 1489.02  5351.3 1489.44  5415.6 1492.53  5481.4 1493.21
  5532.9 1496.16  5578.2 1496.39  5626.7 1497.94  5647.8 1499.87  5703.7 1501.03
#Mann=7,-1,0
  4442.5    0.12       0  4897.6   0.035       0  4992.9    0.12       0
  5013.8    0.05       0  5017.8    0.12       0  5261.9    0.07       0
  5578.2   0.035       0
Bank Sta=5013.8,5017.8
Exp/Cntr=0.3,0.1

Type RM Length L Ch R = 1,133,0,0,0
BEGIN DESCRIPTION:
Stream0030_DS 0.0
END DESCRIPTION:
XS GIS Cut Line= 5
      2006242.35     13886988.35      2006581.55     13886740.29
      2006611.27     13886624.26      2006382.76     13886427.30
      2006015.41     13886189.47
#Sta/Elev= 30
  4460.0 1488.57  4583.3 1485.17  4699.6 1477.86  4765.5 1475.76  4833.3 1474.28
  4918.0 1473.02  4947.6 1471.17  4959.9 1469.24  4978.6 1465.36  4986.9 1464.93
  4987.2 1464.43  4990.9 1464.93  4994.5 1468.13  5000.0 1467.02  5010.7 1470.92
  5018.4 1470.81  5025.0 1472.79  5032.6 1472.44  5053.5 1475.50  5067.7 1475.47
  5082.0 1477.47  5180.8 1479.33  5327.4 1485.51  5403.7 1487.91  5453.9 1487.39
  5549.3 1489.32  5612.1 1491.09  5627.3 1492.69  5684.6 1493.04  5739.3 1495.60
#Mann=9,-1,0
  4460.0   0.035       0  4583.3    0.12       0  4765.5    0.07       0
  4833.3   0.035       0  4959.9    0.12       0  4986.9    0.05       0
  4990.9    0.12       0  5327.4    0.07       0  5549.3   0.035       0
Bank Sta=4986.9,4990.9
Exp/Cntr=0.3,0.1

Chan Stop Cuts=-1