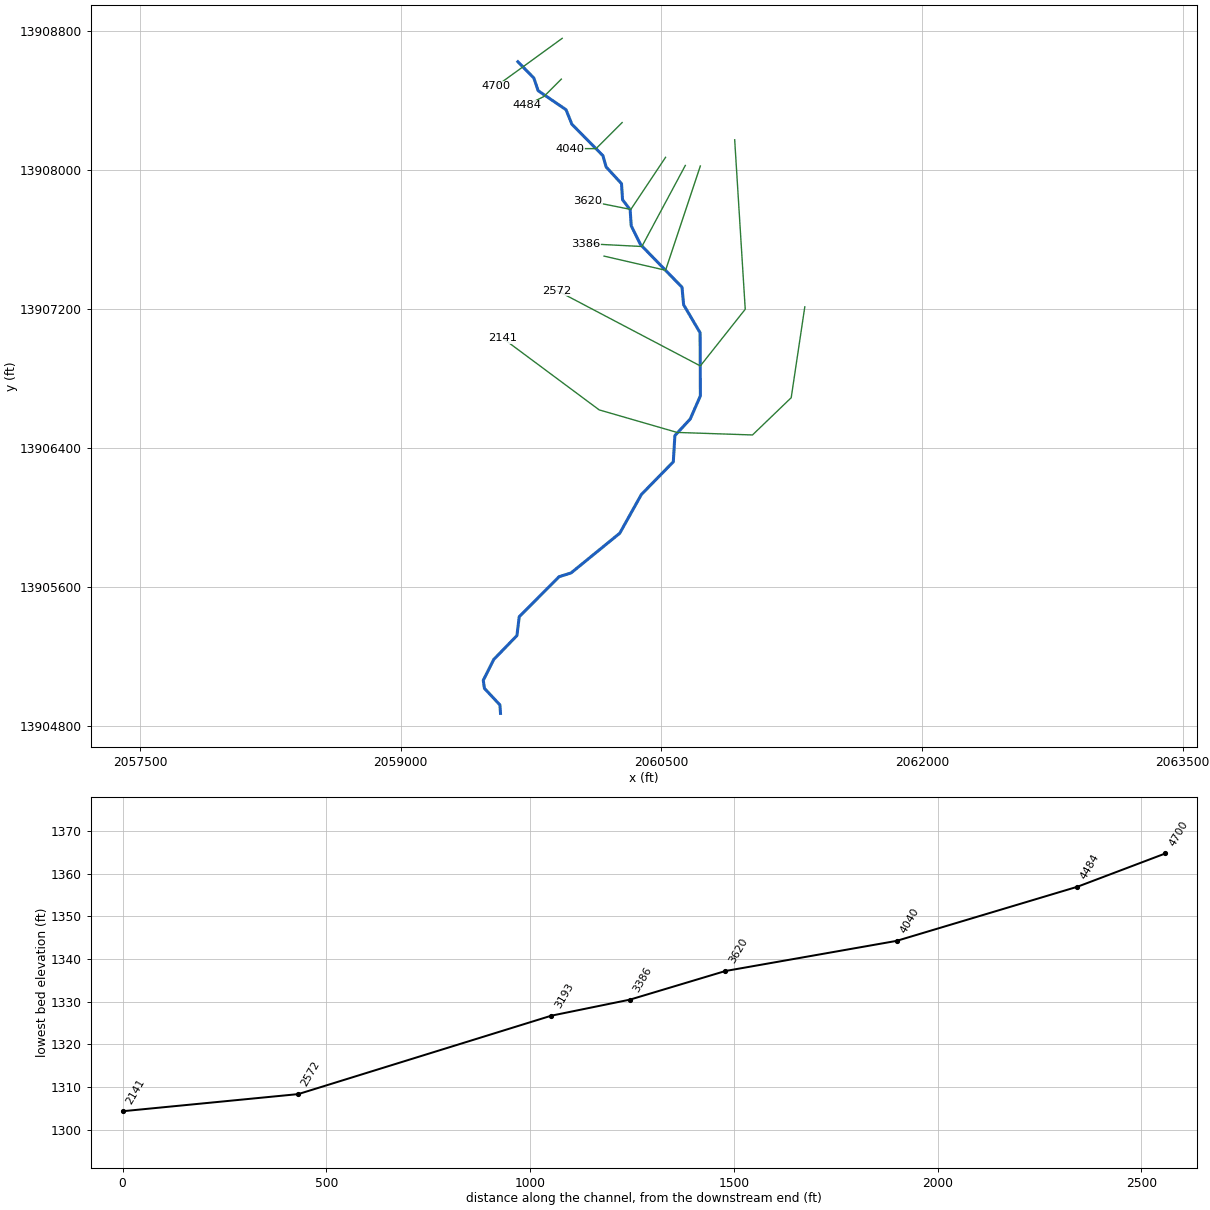
--- Stream0031_DS.prj (project) ---

Proj Title=Stream0031_DS Base Level Engineering
Current Plan=p01
Default Exp/Contr=0.3,0.1
English Units
Geom File=g01
Flow File=f01
Plan File=p01
BEGIN DESCRIPTION:
Stream0031_DS
END DESCRIPTION:

--- Stream0031_DS.p01 (plan) ---

Plan Title=Multiple Run
Short Identifier=Multiple
Geom File=g01
Flow File=f01
Subcritical Flow
K Sum by GR= 0
Std Step Tol= 0.01
Critical Tol= 0.01
Num of Std Step Trials= 20
Max Error Tol= 0.3
Flow Tol Ratio= 0.001
Split Flow NTrial= 30
Split Flow Tol= 0.02
Split Flow Ratio= 0.02
Log Output Level= 0
Friction Slope Method= 1
Unsteady Friction Slope Method= 2
Unsteady Bridges Friction Slope Method= 1
Parabolic Critical Depth
Global Vel Dist=  1 , 1 , 1
Global Log Level= 0
CheckData=True
Encroach Param= -1, 0, 0, 0
BEGIN DESCRIPTION:
Multiple Run
END DESCRIPTION:

--- Stream0031_DS.f01 (steady flow) ---

Flow Title=Multiple
Number of Profiles=7
Profile Names=10-year,25-year,50-year,1pct_min,100-year,1pct_plu,500-year
River Rch & RM= Stream0031_DS,Reach-1,4700
     227     344     444     280     558    1114     868
River Rch & RM= Stream0031_DS,Reach-1,4040
     703    1154    1570    1037    2069    4128    3549
Boundary for River Rch & Prof#=Stream0031_DS,Reach-1,1
Up Type=0
Dn Type=3
Dn Slope=0.005
Boundary for River Rch & Prof#=Stream0031_DS,Reach-1,2
Up Type=0
Dn Type=3
Dn Slope=0.005
Boundary for River Rch & Prof#=Stream0031_DS,Reach-1,3
Up Type=0
Dn Type=3
Dn Slope=0.005
Boundary for River Rch & Prof#=Stream0031_DS,Reach-1,4
Up Type=0
Dn Type=3
Dn Slope=0.005
Boundary for River Rch & Prof#=Stream0031_DS,Reach-1,5
Up Type=0
Dn Type=3
Dn Slope=0.005
Boundary for River Rch & Prof#=Stream0031_DS,Reach-1,6
Up Type=0
Dn Type=3
Dn Slope=0.005
Boundary for River Rch & Prof#=Stream0031_DS,Reach-1,7
Up Type=0
Dn Type=3
Dn Slope=0.005

--- Stream0031_DS.g01 (geometry) ---

Geom Title=Existing Conditions

River Reach=Stream0031_DS,Reach-1
Reach XY= 30
      2059675.00     13908625.00      2059766.89     13908531.07
      2059791.63     13908458.29      2059952.14     13908348.84
      2059985.79     13908265.34      2060164.22     13908084.68
      2060183.18     13908018.96      2060271.38     13907923.50
      2060277.47     13907830.57      2060321.15     13907773.40
      2060327.33     13907680.97      2060380.83     13907572.70
      2060619.48     13907327.43      2060628.83     13907226.59
      2060723.64     13907065.35      2060725.29     13906702.15
      2060666.84     13906568.95      2060578.55     13906473.53
      2060569.53     13906322.55      2060385.78     13906134.68
      2060261.38     13905911.76      2059981.05     13905683.16
      2059911.79     13905661.37      2059682.86     13905431.17
      2059669.48     13905322.57      2059535.76     13905184.68
      2059475.86     13905065.14      2059482.48     13905018.95
      2059571.71     13904923.64      2059575.00     13904875.00

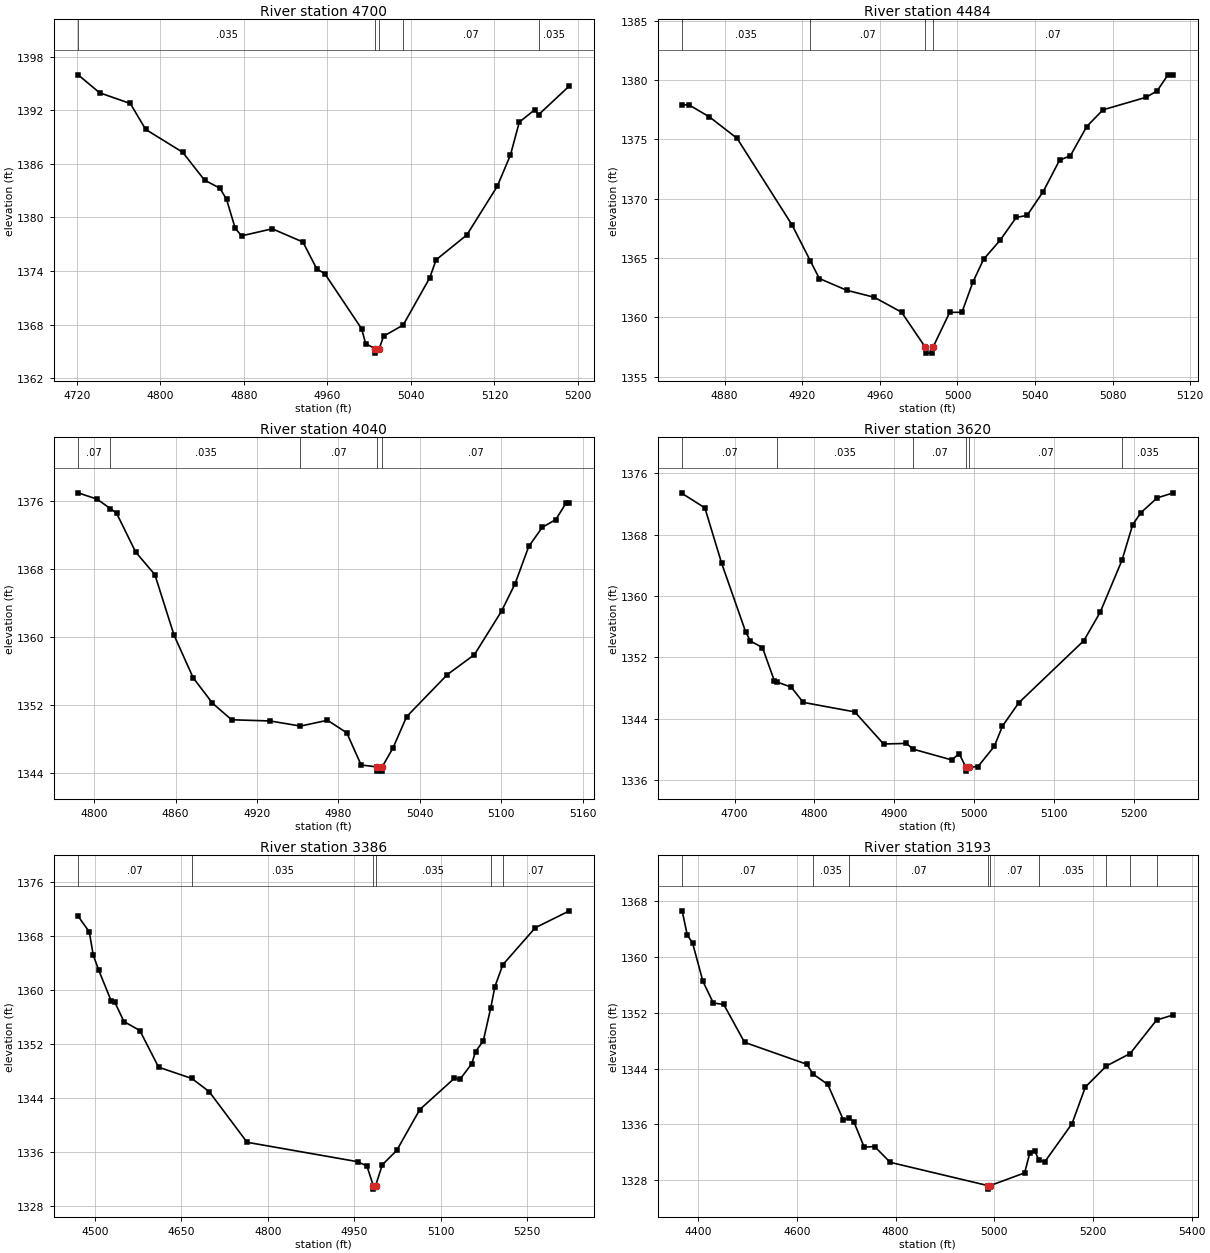
Type RM Length L Ch R = 1,4700,216,216,216
BEGIN DESCRIPTION:
Stream0031_DS 5.0
END DESCRIPTION:
XS GIS Cut Line= 3
      2059930.08     13908759.64      2059704.42     13908595.73
      2059548.88     13908483.52
#Sta/Elev= 30
  4721.1 1395.96  4741.7 1393.95  4771.1 1392.75  4785.8 1389.85  4821.3 1387.29
  4842.2 1384.17  4856.9 1383.27  4863.3 1382.02  4871.6 1378.78  4877.7 1377.93
  4907.1 1378.72  4936.5 1377.24  4949.8 1374.22  4957.4 1373.70  4992.7 1367.53
  4996.6 1365.86  5005.6 1365.30  5005.9 1364.80  5009.6 1365.30  5013.8 1366.70
  5032.5 1367.94  5057.9 1373.21  5064.1 1375.25  5093.5 1378.03  5122.6 1383.46
  5135.3 1386.98  5143.8 1390.67  5158.5 1392.04  5162.3 1391.50  5191.8 1394.72
#Mann=5,-1,0
  4721.1   0.035       0  5005.6   0.035       0  5009.6   0.035       0
  5032.5    0.07       0  5162.3   0.035       0
Bank Sta=5005.6,5009.6
Exp/Cntr=0.3,0.1

Type RM Length L Ch R = 1,4484,444,444,444
BEGIN DESCRIPTION:
Stream0031_DS 4.0
END DESCRIPTION:
XS GIS Cut Line= 3
      2059925.00     13908525.00      2059825.00     13908425.00
      2059725.02     13908375.01
#Sta/Elev= 30
  4858.1 1377.91  4861.6 1377.91  4872.2 1376.89  4886.4 1375.09  4914.7 1367.80
  4924.2 1364.75  4928.8 1363.27  4942.9 1362.28  4957.1 1361.69  4971.2 1360.43
  4983.4 1357.48  4983.6 1356.98  4987.1 1356.98  4987.4 1357.48  4996.0 1360.42
  5002.3 1360.42  5007.9 1362.95  5013.5 1364.90  5021.9 1366.48  5030.3 1368.42
  5035.9 1368.59  5044.2 1370.60  5052.6 1373.24  5058.2 1373.62  5066.6 1376.08
  5075.0 1377.49  5097.3 1378.55  5102.9 1379.09  5108.5 1380.44  5111.3 1380.44
#Mann=4,-1,0
  4858.1   0.035       0  4924.2    0.07       0  4983.4    0.05       0
  4987.4    0.07       0
Bank Sta=4983.4,4987.4
Exp/Cntr=0.3,0.1

Type RM Length L Ch R = 1,4040,420,420,420
BEGIN DESCRIPTION:
Stream0031_DS 3.0
END DESCRIPTION:
XS GIS Cut Line= 3
      2060274.99     13908274.99      2060125.00     13908125.00
      2059975.02     13908125.00
#Sta/Elev= 30
  4788.1 1377.00  4802.2 1376.25  4811.9 1375.14  4816.4 1374.62  4830.5 1370.04
  4844.7 1367.37  4858.8 1360.26  4872.9 1355.25  4887.1 1352.27  4901.2 1350.31
  4929.5 1350.17  4952.0 1349.57  4971.9 1350.25  4986.1 1348.78  4996.7 1344.99
  5008.2 1344.77  5008.5 1344.27  5012.0 1344.27  5012.2 1344.77  5020.2 1347.00
  5030.2 1350.67  5060.2 1355.62  5080.2 1357.97  5100.2 1363.09  5110.2 1366.33
  5120.2 1370.69  5130.2 1372.94  5140.2 1373.86  5147.7 1375.79  5150.2 1375.79
#Mann=5,-1,0
  4788.1    0.07       0  4811.9   0.035       0  4952.0    0.07       0
  5008.2    0.05       0  5012.2    0.07       0
Bank Sta=5008.2,5012.2
Exp/Cntr=0.3,0.1

Type RM Length L Ch R = 1,3620,234,234,234
BEGIN DESCRIPTION:
Stream0031_DS 2.0
END DESCRIPTION:
XS GIS Cut Line= 3
      2060524.99     13908074.98      2060325.00     13907775.00
      2060074.98     13907825.00
#Sta/Elev= 30
  4634.2 1373.35  4662.7 1371.47  4683.8 1364.23  4713.8 1355.33  4719.8 1354.13
  4734.8 1353.29  4749.9 1348.92  4753.3 1348.80  4770.9 1348.13  4785.9 1346.15
  4850.5 1344.91  4886.6 1340.73  4915.1 1340.81  4923.6 1340.06  4972.2 1338.65
  4981.2 1339.49  4989.7 1337.70  4990.0 1337.20  4993.7 1337.70  5004.9 1337.80
  5025.3 1340.43  5035.5 1343.06  5055.9 1346.09  5137.5 1354.19  5157.9 1357.88
  5185.2 1364.64  5198.7 1369.30  5208.9 1370.84  5229.3 1372.77  5249.7 1373.43
#Mann=6,-1,0
  4634.2    0.07       0  4753.3   0.035       0  4923.6    0.07       0
  4989.7    0.05       0  4993.7    0.07       0  5185.2   0.035       0
Bank Sta=4989.7,4993.7
Exp/Cntr=0.3,0.1

Type RM Length L Ch R = 1,3386,193,193,193
BEGIN DESCRIPTION:
Stream0031_DS 1.5
END DESCRIPTION:
XS GIS Cut Line= 3
      2060638.59     13908028.11      2060388.62     13907561.78
      2060065.83     13907578.19
#Sta/Elev= 30
  4470.9 1370.97  4490.3 1368.65  4497.1 1365.22  4506.5 1363.00  4528.5 1358.36
  4534.1 1358.30  4550.4 1355.35  4578.0 1354.01  4610.5 1348.58  4668.2 1346.90
  4698.2 1344.96  4764.0 1337.44  4955.7 1334.56  4971.9 1333.92  4983.0 1330.99
  4983.3 1330.49  4987.0 1330.99  4998.5 1334.09  5023.6 1336.23  5063.7 1342.30
  5123.8 1346.94  5133.8 1346.82  5153.8 1349.09  5160.3 1350.89  5173.8 1352.48
  5186.7 1357.36  5193.9 1360.51  5207.7 1363.78  5264.0 1369.26  5323.2 1371.77
#Mann=6,-1,0
  4470.9    0.07       0  4668.2   0.035       0  4983.0   0.035       0
  4987.0   0.035       0  5186.7    0.12       0  5207.7    0.07       0
Bank Sta=4983,4987
Exp/Cntr=0.3,0.1

Type RM Length L Ch R = 1,3193,621,621,621
BEGIN DESCRIPTION:
Stream0031_DS 1.0
END DESCRIPTION:
XS GIS Cut Line= 3
      2060725.00     13908024.99      2060525.00     13907425.00
      2060171.18     13907506.37
#Sta/Elev= 30
  4367.6 1366.61  4378.1 1363.13  4388.7 1362.01  4409.7 1356.51  4430.8 1353.40
  4451.9 1353.19  4494.1 1347.76  4620.6 1344.61  4632.4 1343.24  4662.7 1341.73
  4694.4 1336.62  4705.1 1336.91  4715.4 1336.41  4736.5 1332.73  4757.6 1332.83
  4789.2 1330.56  4987.5 1327.22  4987.8 1326.72  4991.5 1327.22  5061.6 1329.05
  5072.0 1331.89  5082.1 1332.19  5090.8 1330.84  5102.7 1330.66  5157.6 1336.10
  5184.7 1341.36  5227.2 1344.37  5275.5 1346.16  5329.0 1350.96  5363.1 1351.69
#Mann=9,-1,0
  4367.6    0.07       0  4632.4   0.035       0  4705.1    0.07       0
  4987.5    0.05       0  4991.5    0.07       0  5090.8   0.035       0
  5227.2    0.07       0  5275.5   0.035       0  5329.0    0.12       0
Bank Sta=4987.5,4991.5
Exp/Cntr=0.3,0.1

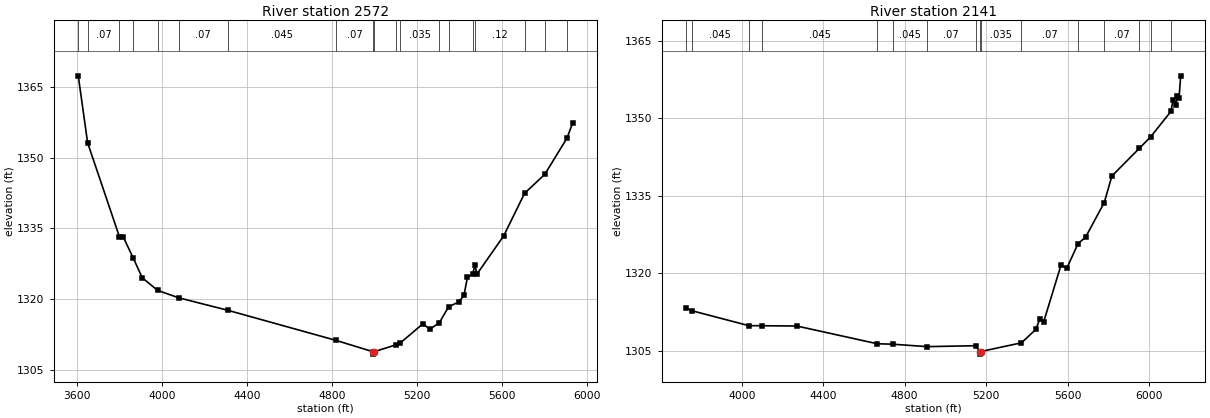
Type RM Length L Ch R = 1,2572,431,431,431
BEGIN DESCRIPTION:
Stream0031_DS 0.1
END DESCRIPTION:
XS GIS Cut Line= 4
      2060922.68     13908175.73      2060983.40     13907200.75
      2060725.03     13906874.54      2059899.61     13907308.42
#Sta/Elev= 30
  3607.0 1367.35  3651.0 1353.16  3800.4 1333.25  3818.1 1333.24  3865.9 1328.67
  3908.3 1324.51  3980.3 1321.84  4078.7 1320.28  4311.4 1317.61  4819.3 1311.24
  4994.5 1308.82  4994.8 1308.32  4998.5 1308.82  5100.9 1310.28  5122.9 1310.71
  5229.1 1314.78  5259.9 1313.60  5304.6 1314.88  5349.3 1318.35  5399.8 1319.46
  5421.9 1320.87  5438.3 1324.65  5462.5 1325.27  5473.4 1327.21  5482.4 1325.27
  5609.0 1333.43  5707.0 1342.44  5802.1 1346.46  5905.9 1354.10  5932.5 1357.25
#Mann=19,-1,0
  3607.0    0.12       0  3651.0    0.07       0  3800.4   0.035       0
  3865.9    0.07       0  3980.3   0.035       0  4078.7    0.07       0
  4311.4   0.045       0  4819.3    0.07       0  4994.5    0.05       0
  4998.5    0.07       0  5100.9   0.045       0  5122.9   0.035       0
  5304.6   0.045       0  5349.3   0.035       0  5462.5    0.07       0
  5473.4    0.12       0  5707.0    0.07       0  5802.1    0.12       0
  5905.9    0.07       0
Bank Sta=4994.5,4998.5
Exp/Cntr=0.3,0.1

Type RM Length L Ch R = 1,2141,0,0,0
BEGIN DESCRIPTION:
Stream0031_DS 0.0
END DESCRIPTION:
XS GIS Cut Line= 6
      2061326.19     13907214.50      2061247.91     13906691.45
      2061025.21     13906477.20      2060591.46     13906491.75
      2060142.94     13906621.48      2059589.90     13907032.40
#Sta/Elev= 30
  3728.1 1313.24  3755.2 1312.70  4034.8 1309.81  4100.1 1309.80  4270.7 1309.74
  4665.3 1306.31  4742.3 1306.22  4909.7 1305.75  5148.1 1305.93  5168.9 1304.80
  5169.1 1304.30  5172.9 1304.80  5373.7 1306.49  5443.9 1309.07  5464.2 1311.11
  5482.1 1310.46  5567.6 1321.49  5596.9 1320.97  5651.9 1325.72  5688.6 1326.94
  5780.4 1333.65  5818.0 1338.80  5953.3 1344.17  6009.0 1346.41  6108.0 1351.30
  6118.4 1353.56  6133.0 1352.60  6139.2 1354.25  6147.6 1353.83  6155.9 1358.19
#Mann=16,-1,0
  3728.1    0.07       0  3755.2   0.045       0  4034.8   0.035       0
  4100.1   0.045       0  4665.3   0.035       0  4742.3   0.045       0
  4909.7    0.07       0  5148.1   0.035       0  5168.9    0.05       0
  5172.9   0.035       0  5373.7    0.07       0  5651.9    0.12       0
  5780.4    0.07       0  5953.3    0.12       0  6009.0    0.07       0
  6108.0    0.12       0
Bank Sta=5168.9,5172.9
Exp/Cntr=0.3,0.1

Chan Stop Cuts=-1