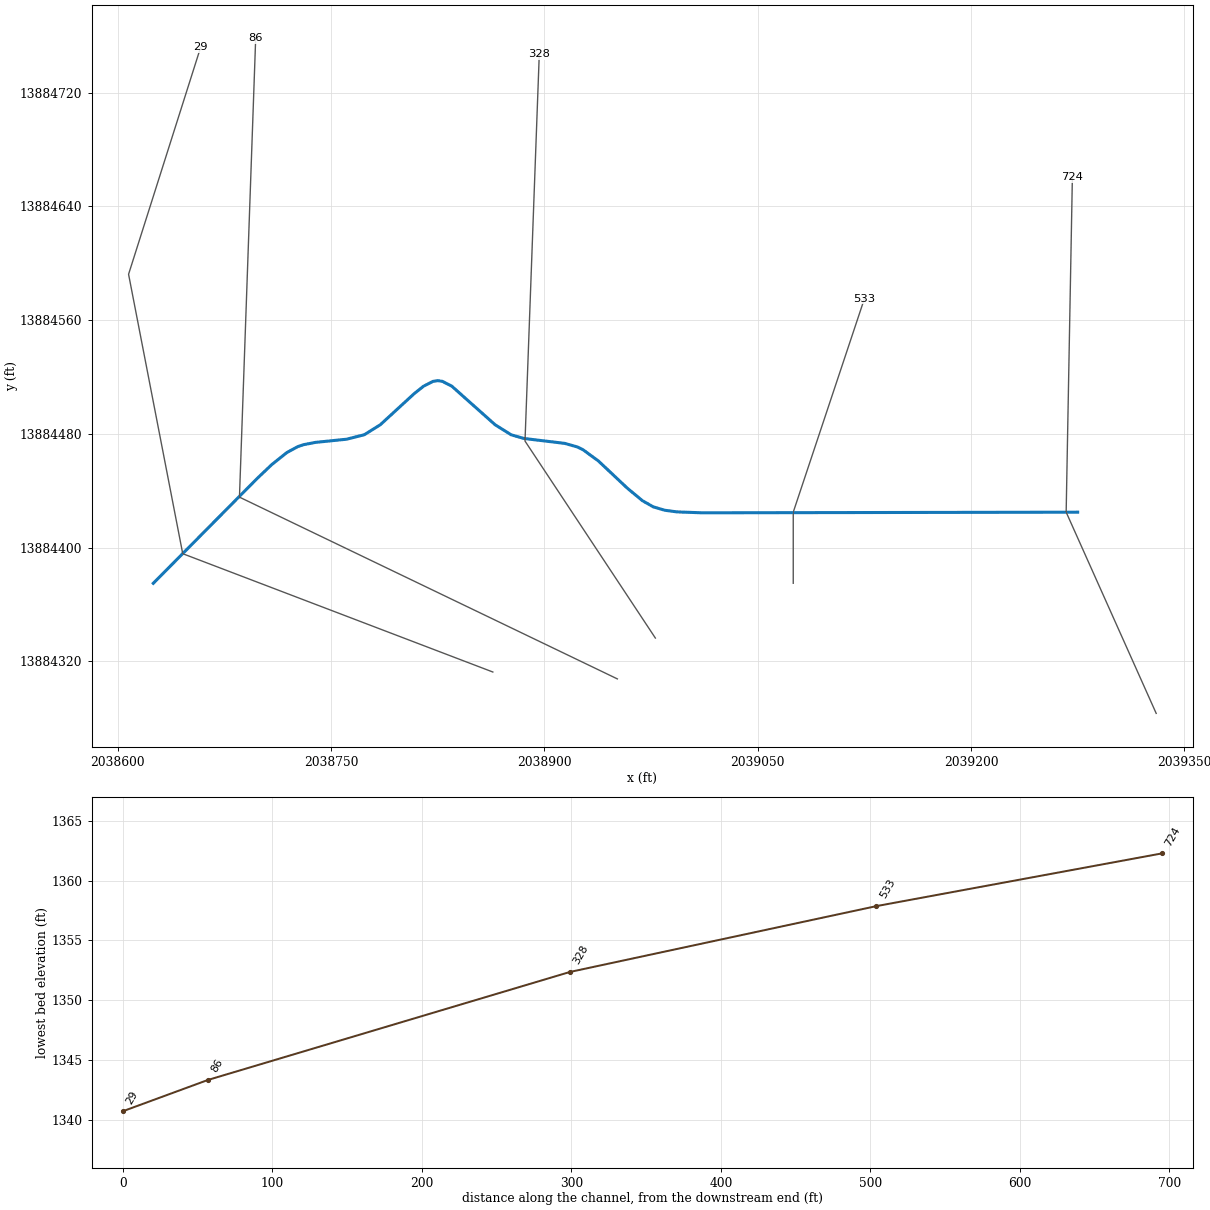
--- Stream0032_DS.prj (project) ---

Proj Title=Stream0032_DS Base Level Engineering
Current Plan=p01
Default Exp/Contr=0.3,0.1
English Units
Geom File=g01
Flow File=f01
Plan File=p01
BEGIN DESCRIPTION:
Stream0032_DS
END DESCRIPTION:

--- Stream0032_DS.p01 (plan) ---

Plan Title=Multiple Run
Short Identifier=Multiple
Geom File=g01
Flow File=f01
Subcritical Flow
K Sum by GR= 0
Std Step Tol= 0.01
Critical Tol= 0.01
Num of Std Step Trials= 20
Max Error Tol= 0.3
Flow Tol Ratio= 0.001
Split Flow NTrial= 30
Split Flow Tol= 0.02
Split Flow Ratio= 0.02
Log Output Level= 0
Friction Slope Method= 1
Unsteady Friction Slope Method= 2
Unsteady Bridges Friction Slope Method= 1
Parabolic Critical Depth
Global Vel Dist=  1 , 1 , 1
Global Log Level= 0
CheckData=True
Encroach Param= -1, 0, 0, 0
BEGIN DESCRIPTION:
Multiple Run
END DESCRIPTION:

--- Stream0032_DS.f01 (steady flow) ---

Flow Title=Multiple
Number of Profiles=7
Profile Names=10-year,25-year,50-year,1pct_min,100-year,1pct_plu,500-year
River Rch & RM= Stream0032_DS,Reach-1,724
     585     956    1298     858    1711    3414    2933
River Rch & RM= Stream0032_DS,Reach-1,86
    1016    1721    2393    1615    3223    6431    5777
Boundary for River Rch & Prof#=Stream0032_DS,Reach-1,1
Up Type=0
Dn Type=3
Dn Slope=0.005
Boundary for River Rch & Prof#=Stream0032_DS,Reach-1,2
Up Type=0
Dn Type=3
Dn Slope=0.005
Boundary for River Rch & Prof#=Stream0032_DS,Reach-1,3
Up Type=0
Dn Type=3
Dn Slope=0.005
Boundary for River Rch & Prof#=Stream0032_DS,Reach-1,4
Up Type=0
Dn Type=3
Dn Slope=0.005
Boundary for River Rch & Prof#=Stream0032_DS,Reach-1,5
Up Type=0
Dn Type=3
Dn Slope=0.005
Boundary for River Rch & Prof#=Stream0032_DS,Reach-1,6
Up Type=0
Dn Type=3
Dn Slope=0.005
Boundary for River Rch & Prof#=Stream0032_DS,Reach-1,7
Up Type=0
Dn Type=3
Dn Slope=0.005

--- Stream0032_DS.g01 (geometry) ---

Geom Title=Existing Conditions

River Reach=Stream0032_DS,Reach-1
Reach XY= 30
      2039275.00     13884425.00      2039011.18     13884424.55
      2038993.26     13884425.20      2038984.65     13884426.36
      2038976.55     13884428.75      2038968.92     13884433.10
      2038958.39     13884441.81      2038938.03     13884460.97
      2038927.17     13884468.91      2038923.25     13884470.84
      2038914.29     13884473.38      2038885.62     13884476.83
      2038876.64     13884479.42      2038865.32     13884486.50
      2038834.92     13884513.60      2038828.31     13884516.98
      2038825.00     13884517.50      2038821.69     13884516.98
      2038815.08     13884513.60      2038808.45     13884508.35
      2038784.67     13884486.51      2038773.35     13884479.45
      2038760.94     13884476.31      2038739.07     13884474.08
      2038730.63     13884472.45      2038726.63     13884471.12
      2038718.93     13884466.94      2038708.29     13884458.45
      2038698.14     13884448.81      2038625.00     13884375.00

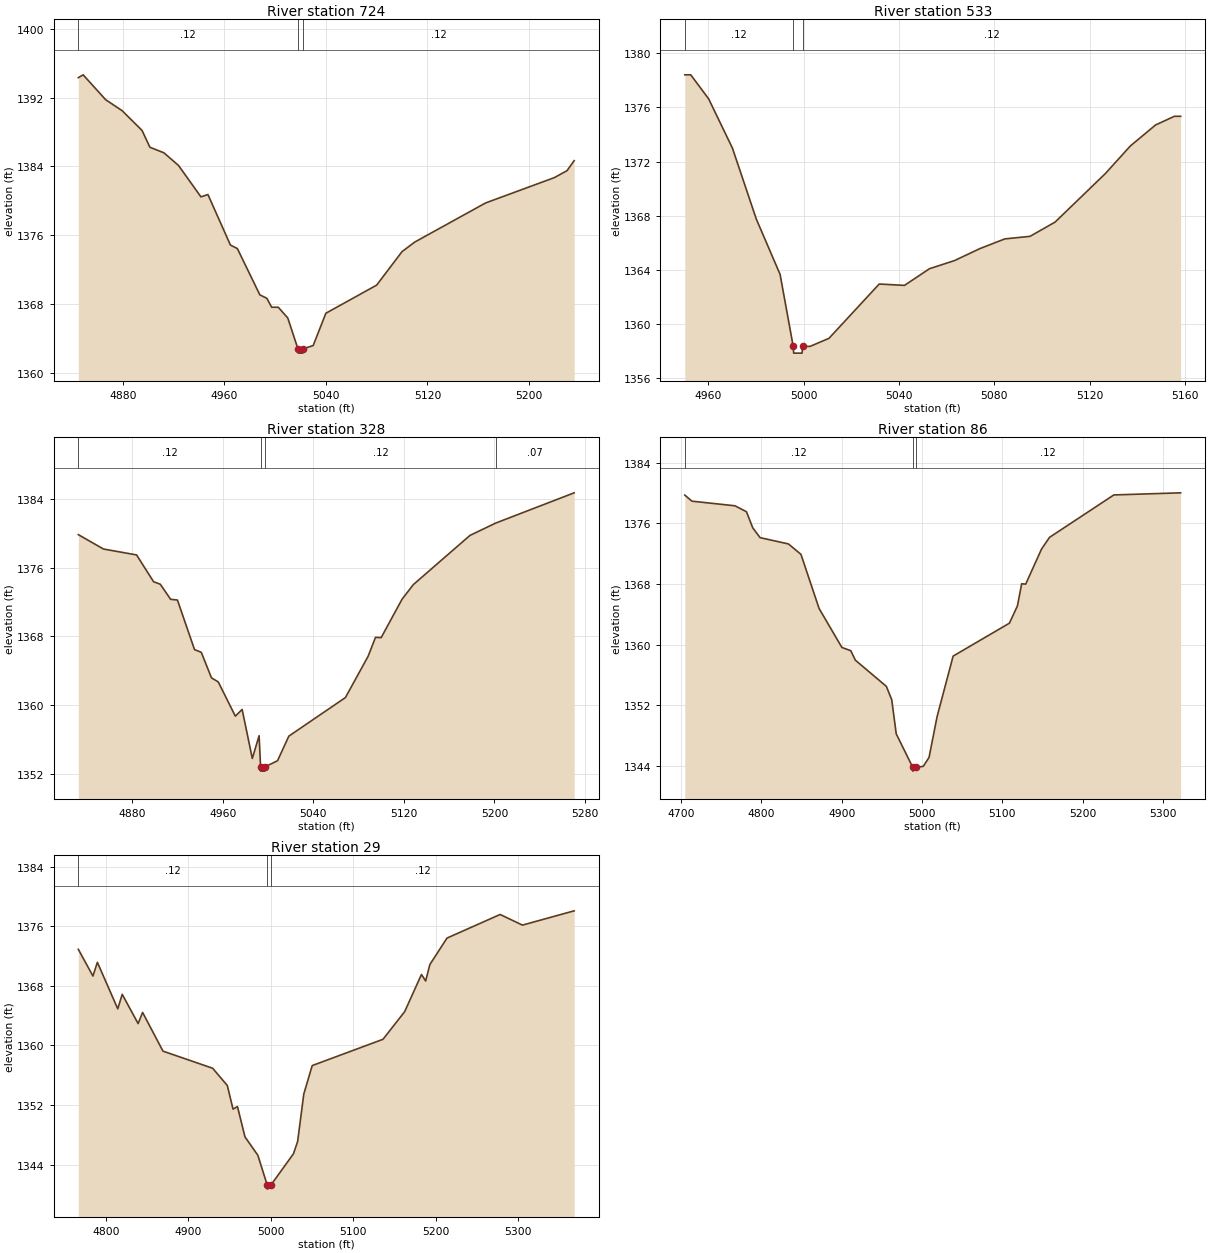
Type RM Length L Ch R = 1,724,191,191,191
BEGIN DESCRIPTION:
Stream0032_DS 5.0
END DESCRIPTION:
XS GIS Cut Line= 3
      2039330.22     13884283.52      2039266.91     13884425.00
      2039271.28     13884660.56
#Sta/Elev= 30
  4845.0 1394.32  4848.8 1394.65  4866.5 1391.76  4879.5 1390.48  4895.2 1388.18
  4901.4 1386.22  4912.4 1385.58  4923.9 1384.11  4941.6 1380.45  4947.1 1380.72
  4964.8 1374.85  4970.3 1374.43  4988.0 1369.05  4993.5 1368.65  4997.3 1367.61
  5002.5 1367.61  5010.0 1366.36  5018.0 1362.77  5018.3 1362.27  5021.8 1362.27
  5022.0 1362.77  5030.0 1363.15  5040.0 1366.91  5080.0 1370.18  5100.0 1374.08
  5110.0 1375.19  5165.8 1379.74  5220.0 1382.69  5230.0 1383.50  5235.6 1384.66
#Mann=3,-1,0
  4845.0    0.12       0  5018.0    0.05       0  5022.0    0.12       0
Bank Sta=5018,5022
Exp/Cntr=0.3,0.1

Type RM Length L Ch R = 1,533,205,205,205
BEGIN DESCRIPTION:
Stream0032_DS 4.0
END DESCRIPTION:
XS GIS Cut Line= 3
      2039075.00     13884375.01      2039075.00     13884425.00
      2039125.00     13884575.00
#Sta/Elev= 26
  4950.1 1378.40  4952.6 1378.40  4960.1 1376.63  4970.1 1372.99  4980.1 1367.76
  4990.1 1363.67  4995.6 1358.36  4995.8 1357.86  4999.3 1357.86  4999.6 1358.36
  5000.1 1358.36  5002.7 1358.36  5010.6 1358.95  5031.7 1362.96  5042.3 1362.86
  5052.8 1364.09  5063.3 1364.69  5073.9 1365.57  5084.4 1366.29  5095.0 1366.48
  5105.5 1367.53  5126.6 1371.11  5137.1 1373.15  5147.7 1374.70  5155.6 1375.34
  5158.2 1375.34
#Mann=3,-1,0
  4950.1    0.12       0  4995.6    0.05       0  4999.6    0.12       0
Bank Sta=4995.6,4999.6
Exp/Cntr=0.3,0.1

Type RM Length L Ch R = 1,328,242,242,242
BEGIN DESCRIPTION:
Stream0032_DS 3.0
END DESCRIPTION:
XS GIS Cut Line= 3
      2038978.04     13884336.49      2038886.38     13884475.00
      2038896.41     13884747.02
#Sta/Elev= 30
  4832.2 1379.84  4854.4 1378.17  4883.7 1377.48  4898.7 1374.37  4904.7 1374.07
  4913.8 1372.32  4919.8 1372.24  4934.9 1366.48  4940.9 1366.16  4949.9 1363.19
  4955.9 1362.72  4971.0 1358.74  4977.0 1359.52  4986.0 1353.82  4992.0 1356.47
  4993.3 1352.85  4993.5 1352.35  4997.0 1352.35  4997.3 1352.85  5008.3 1353.56
  5018.3 1356.42  5068.3 1360.90  5088.4 1365.71  5094.9 1367.90  5099.9 1367.87
  5118.4 1372.34  5128.4 1374.04  5178.4 1379.75  5201.1 1381.18  5270.5 1384.70
#Mann=4,-1,0
  4832.2    0.12       0  4993.3    0.05       0  4997.3    0.12       0
  5201.1    0.07       0
Bank Sta=4993.3,4997.3
Exp/Cntr=0.3,0.1

Type RM Length L Ch R = 1,86,57,57,57
BEGIN DESCRIPTION:
Stream0032_DS 2.0
END DESCRIPTION:
XS GIS Cut Line= 3
      2038951.32     13884307.76      2038685.58     13884435.58
      2038696.99     13884758.20
#Sta/Elev= 30
  4704.5 1379.72  4713.4 1378.92  4767.0 1378.31  4781.3 1377.53  4789.2 1375.40
  4798.3 1374.11  4833.6 1373.28  4849.2 1371.91  4871.8 1364.77  4900.2 1359.63
  4911.3 1359.20  4917.0 1357.95  4955.6 1354.50  4962.3 1352.74  4967.9 1348.24
  4988.5 1343.82  4988.7 1343.32  4992.5 1343.82  5001.6 1343.95  5008.8 1345.13
  5018.8 1350.51  5038.8 1358.49  5108.9 1362.83  5118.9 1365.11  5124.2 1368.03
  5129.2 1367.98  5148.9 1372.60  5158.9 1374.15  5239.0 1379.74  5322.2 1380.02
#Mann=3,-1,0
  4704.5    0.12       0  4988.5    0.05       0  4992.5    0.12       0
Bank Sta=4988.5,4992.5
Exp/Cntr=0.3,0.1

Type RM Length L Ch R = 1,29,0,0,0
BEGIN DESCRIPTION:
Stream0032_DS 1.0
END DESCRIPTION:
XS GIS Cut Line= 4
      2038863.75     13884312.61      2038645.69     13884395.81
      2038607.61     13884592.30      2038658.29     13884751.90
#Sta/Elev= 30
  4766.6 1372.92  4784.3 1369.33  4789.7 1371.17  4814.4 1364.92  4819.8 1366.87
  4839.1 1362.94  4844.5 1364.44  4869.2 1359.24  4929.4 1356.94  4947.2 1354.62
  4954.1 1351.45  4959.5 1351.79  4968.6 1347.72  4984.2 1345.25  4995.7 1341.20
  4995.9 1340.70  4999.7 1341.20  5027.3 1345.44  5032.4 1347.09  5039.9 1353.48
  5050.1 1357.30  5135.9 1360.83  5162.2 1364.55  5182.5 1369.54  5187.6 1368.66
  5192.7 1370.87  5213.5 1374.43  5277.9 1377.60  5304.9 1376.17  5367.6 1378.09
#Mann=3,-1,0
  4766.6    0.12       0  4995.7    0.05       0  4999.7    0.12       0
Bank Sta=4995.7,4999.7
Exp/Cntr=0.3,0.1

Chan Stop Cuts=-1