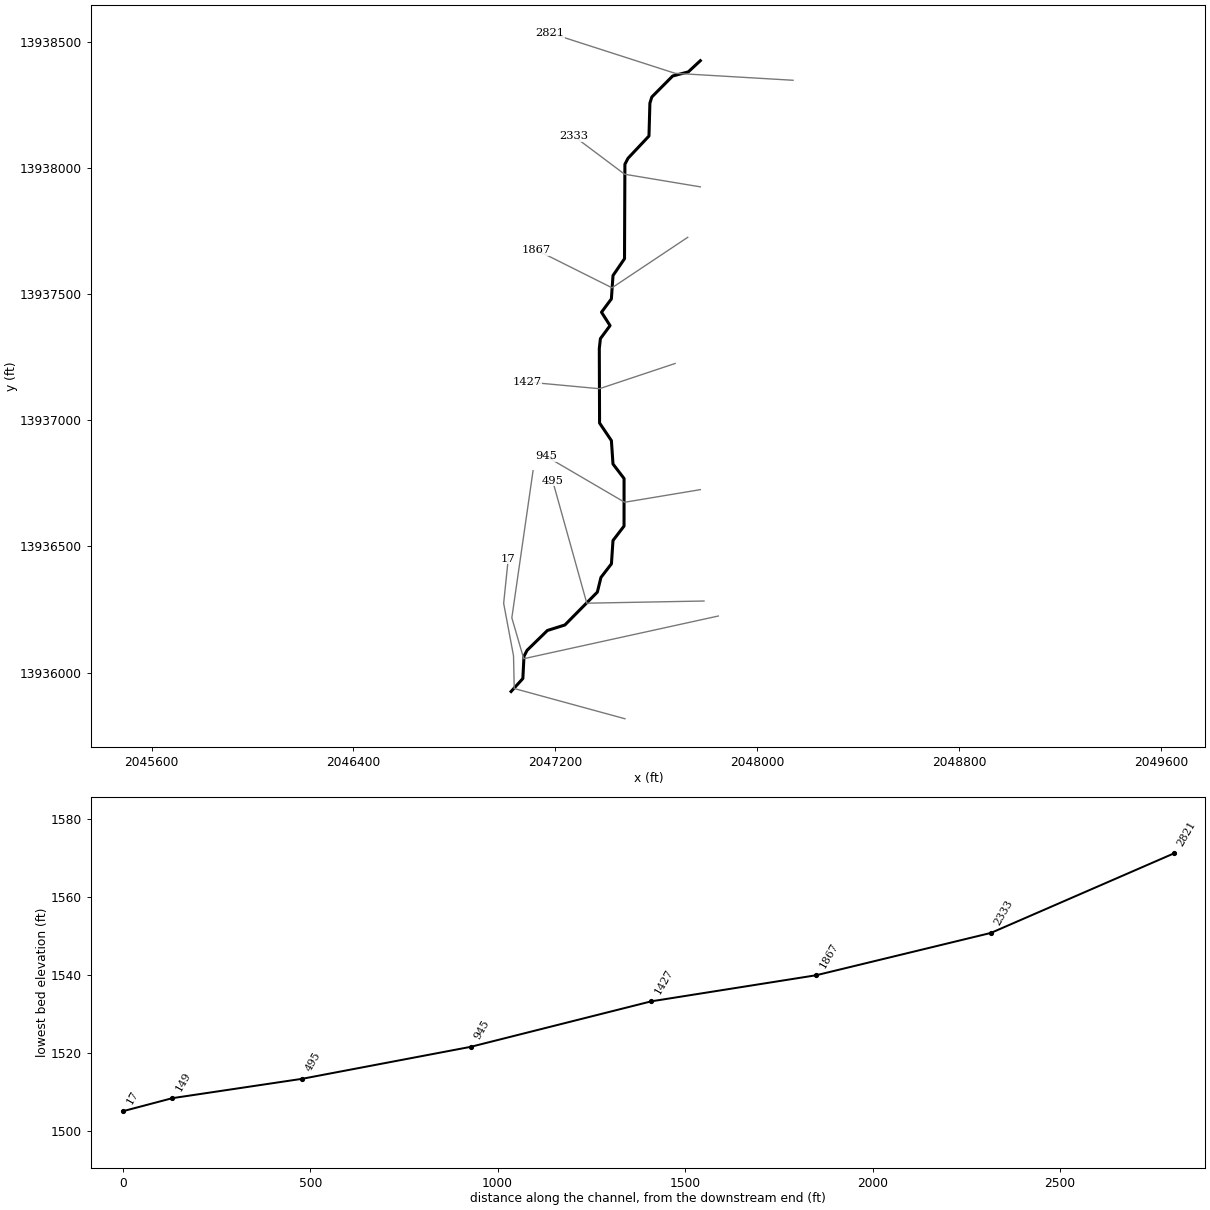
--- Stream0033_DS.prj (project) ---

Proj Title=Stream0033_DS Base Level Engineering
Current Plan=p01
Default Exp/Contr=0.3,0.1
English Units
Geom File=g01
Flow File=f01
Plan File=p01
BEGIN DESCRIPTION:
Stream0033_DS
END DESCRIPTION:

--- Stream0033_DS.p01 (plan) ---

Plan Title=Multiple Run
Short Identifier=Multiple
Geom File=g01
Flow File=f01
Subcritical Flow
K Sum by GR= 0
Std Step Tol= 0.01
Critical Tol= 0.01
Num of Std Step Trials= 20
Max Error Tol= 0.3
Flow Tol Ratio= 0.001
Split Flow NTrial= 30
Split Flow Tol= 0.02
Split Flow Ratio= 0.02
Log Output Level= 0
Friction Slope Method= 1
Unsteady Friction Slope Method= 2
Unsteady Bridges Friction Slope Method= 1
Parabolic Critical Depth
Global Vel Dist=  1 , 1 , 1
Global Log Level= 0
CheckData=True
Encroach Param= -1, 0, 0, 0
BEGIN DESCRIPTION:
Multiple Run
END DESCRIPTION:

--- Stream0033_DS.f01 (steady flow) ---

Flow Title=Multiple
Number of Profiles=7
Profile Names=10-year,25-year,50-year,1pct_min,100-year,1pct_plu,500-year
River Rch & RM= Stream0033_DS,Reach-1,2821
     336     539     724     475     948    1891    1603
River Rch & RM= Stream0033_DS,Reach-1,2333
     437     712     966     638    1274    2542    2192
River Rch & RM= Stream0033_DS,Reach-1,17
    3063    5524    8006    5608   11189   22325   21701
Boundary for River Rch & Prof#=Stream0033_DS,Reach-1,1
Up Type=0
Dn Type=3
Dn Slope=0.005
Boundary for River Rch & Prof#=Stream0033_DS,Reach-1,2
Up Type=0
Dn Type=3
Dn Slope=0.005
Boundary for River Rch & Prof#=Stream0033_DS,Reach-1,3
Up Type=0
Dn Type=3
Dn Slope=0.005
Boundary for River Rch & Prof#=Stream0033_DS,Reach-1,4
Up Type=0
Dn Type=3
Dn Slope=0.005
Boundary for River Rch & Prof#=Stream0033_DS,Reach-1,5
Up Type=0
Dn Type=3
Dn Slope=0.005
Boundary for River Rch & Prof#=Stream0033_DS,Reach-1,6
Up Type=0
Dn Type=3
Dn Slope=0.005
Boundary for River Rch & Prof#=Stream0033_DS,Reach-1,7
Up Type=0
Dn Type=3
Dn Slope=0.005

--- Stream0033_DS.g01 (geometry) ---

Geom Title=Existing Conditions

River Reach=Stream0033_DS,Reach-1
Reach XY= 30
      2047775.00     13938425.00      2047727.35     13938380.71
      2047665.27     13938364.31      2047582.81     13938281.21
      2047575.11     13938256.78      2047571.44     13938126.47
      2047488.40     13938038.31      2047476.06     13938014.56
      2047474.48     13937640.22      2047428.85     13937573.40
      2047422.46     13937480.89      2047383.28     13937428.22
      2047417.21     13937375.10      2047379.00     13937323.54
      2047374.59     13937284.30      2047375.68     13936988.92
      2047422.53     13936919.43      2047428.86     13936826.60
      2047472.74     13936769.06      2047472.63     13936580.53
      2047428.86     13936523.40      2047422.67     13936430.97
      2047381.14     13936377.17      2047366.86     13936318.94
      2047238.21     13936188.63      2047168.93     13936166.85
      2047088.38     13936088.33      2047076.12     13936064.54
      2047071.61     13935976.41      2047025.00     13935925.00

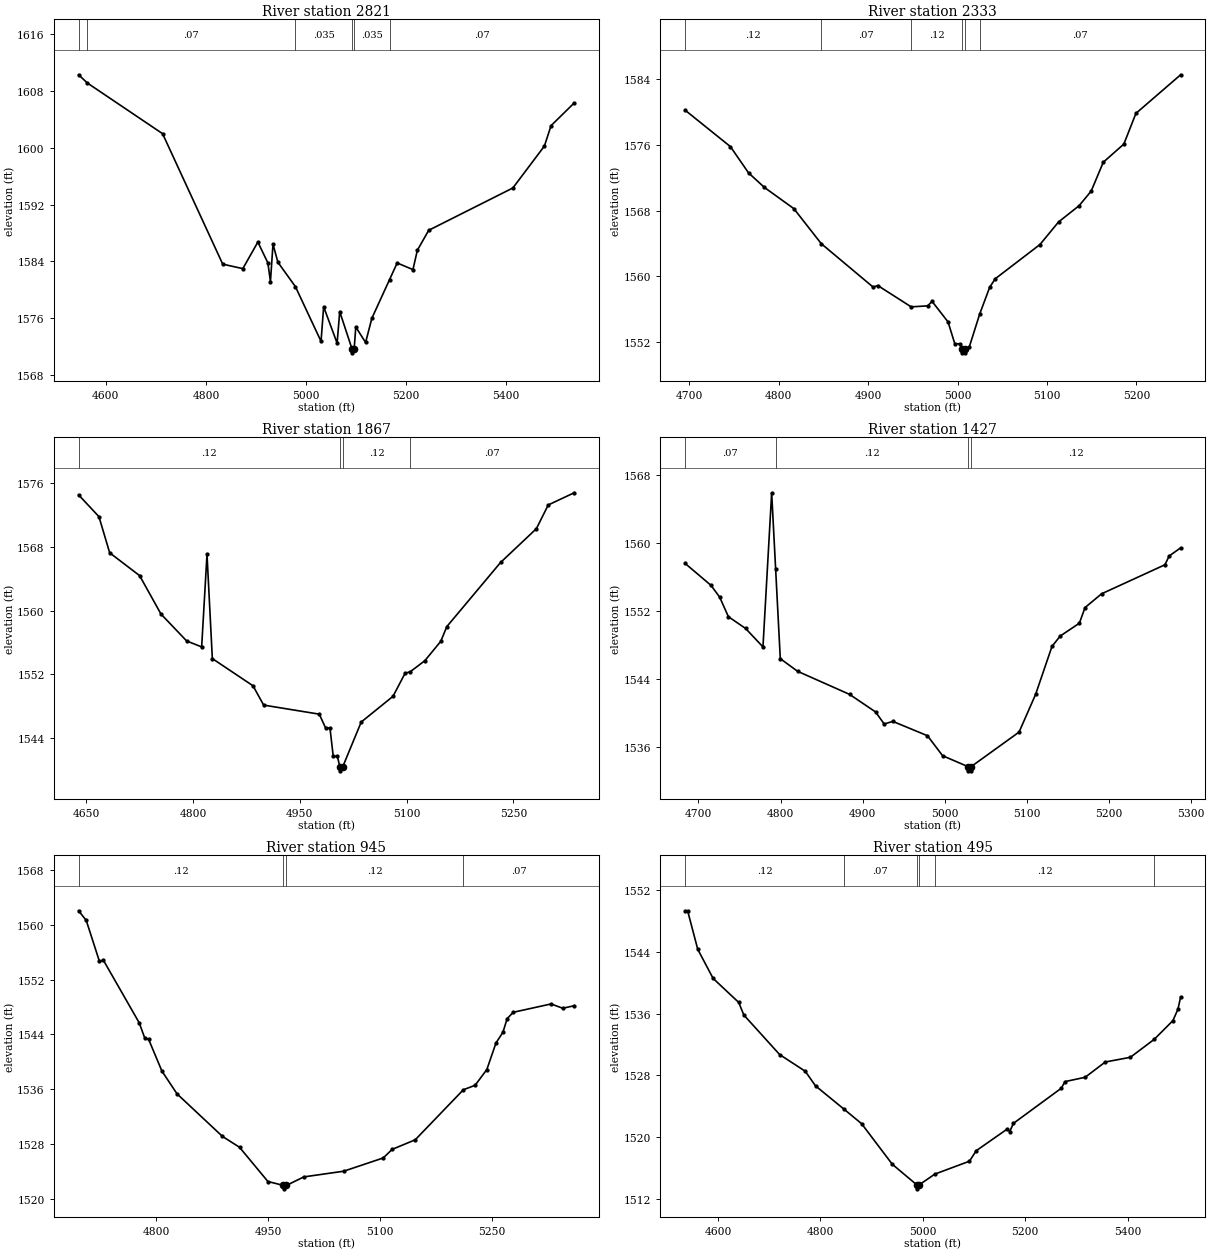
Type RM Length L Ch R = 1,2821,488,488,488
BEGIN DESCRIPTION:
Stream0033_DS 6.0
END DESCRIPTION:
XS GIS Cut Line= 3
      2048142.45     13938347.42      2047675.00     13938375.00
      2047178.37     13938534.91
#Sta/Elev= 30
  4545.7 1610.31  4563.1 1609.15  4713.4 1602.00  4833.6 1583.59  4873.7 1582.96
  4903.8 1586.71  4923.8 1583.76  4928.9 1581.14  4934.0 1586.41  4943.8 1583.86
  4978.7 1580.43  5030.0 1572.70  5035.2 1577.58  5062.1 1572.45  5067.3 1576.90
  5092.1 1571.58  5092.4 1571.08  5096.1 1571.58  5099.4 1574.73  5119.0 1572.54
  5131.5 1575.95  5166.9 1581.42  5182.1 1583.76  5213.6 1582.82  5222.4 1585.55
  5245.1 1588.37  5413.2 1594.34  5476.2 1600.25  5489.5 1603.13  5535.7 1606.33
#Mann=6,-1,0
  4545.7    0.12       0  4563.1    0.07       0  4978.7   0.035       0
  5092.1   0.035       0  5096.1   0.035       0  5166.9    0.07       0
Bank Sta=5092.1,5096.1
Exp/Cntr=0.3,0.1

Type RM Length L Ch R = 1,2333,466,466,466
BEGIN DESCRIPTION:
Stream0033_DS 5.0
END DESCRIPTION:
XS GIS Cut Line= 3
      2047774.96     13937925.01      2047475.00     13937975.00
      2047275.00     13938125.00
#Sta/Elev= 30
  4695.4 1580.25  4746.1 1575.81  4766.3 1572.62  4784.1 1570.84  4817.0 1568.26
  4847.7 1563.99  4905.7 1558.70  4910.8 1558.90  4948.2 1556.30  4966.6 1556.42
  4971.6 1556.96  4989.4 1554.47  4997.0 1551.80  5002.6 1551.80  5004.8 1551.20
  5005.0 1550.70  5008.5 1550.70  5008.8 1551.20  5013.0 1551.36  5024.9 1555.45
  5036.0 1558.69  5042.2 1559.72  5092.2 1563.89  5113.0 1566.64  5136.0 1568.62
  5149.5 1570.40  5163.0 1573.91  5186.0 1576.12  5199.5 1579.86  5249.5 1584.56
#Mann=6,-1,0
  4695.4    0.12       0  4847.7    0.07       0  4948.2    0.12       0
  5004.8    0.05       0  5008.8    0.12       0  5024.9    0.07       0
Bank Sta=5004.8,5008.8
Exp/Cntr=0.3,0.1

Type RM Length L Ch R = 1,1867,440,440,440
BEGIN DESCRIPTION:
Stream0033_DS 4.0
END DESCRIPTION:
XS GIS Cut Line= 3
      2047725.00     13937725.00      2047425.00     13937525.00
      2047124.97     13937675.01
#Sta/Elev= 30
  4639.4 1574.56  4667.9 1571.83  4683.0 1567.28  4725.0 1564.41  4755.1 1559.57
  4791.1 1556.19  4812.2 1555.44  4819.7 1567.08  4827.2 1553.97  4884.3 1550.55
  4899.3 1548.12  4977.4 1546.98  4986.4 1545.22  4992.4 1545.25  4997.0 1541.68
  5002.8 1541.68  5006.3 1540.35  5006.6 1539.85  5010.3 1540.35  5036.3 1545.99
  5081.0 1549.23  5097.8 1552.11  5105.4 1552.33  5125.7 1553.71  5148.1 1556.15
  5156.5 1557.99  5232.0 1566.06  5282.3 1570.31  5299.0 1573.30  5335.4 1574.83
#Mann=4,-1,0
  4639.4    0.12       0  5006.3    0.05       0  5010.3    0.12       0
  5105.4    0.07       0
Bank Sta=5006.3,5010.3
Exp/Cntr=0.3,0.1

Type RM Length L Ch R = 1,1427,482,482,482
BEGIN DESCRIPTION:
Stream0033_DS 3.0
END DESCRIPTION:
XS GIS Cut Line= 3
      2047674.95     13937224.98      2047375.00     13937125.00
      2047089.11     13937151.59
#Sta/Elev= 30
  4683.8 1557.57  4715.4 1554.98  4725.9 1553.60  4736.5 1551.30  4757.5 1549.91
  4778.6 1547.74  4789.2 1565.88  4794.0 1556.96  4799.7 1546.36  4820.8 1544.87
  4884.0 1542.16  4915.7 1540.09  4926.2 1538.67  4936.7 1538.98  4978.9 1537.29
  4997.3 1534.94  5028.1 1533.66  5028.4 1533.16  5031.9 1533.16  5032.1 1533.66
  5090.4 1537.72  5110.5 1542.15  5130.5 1547.81  5140.6 1549.03  5163.8 1550.53
  5170.7 1552.37  5190.8 1553.99  5268.0 1557.41  5273.1 1558.44  5287.1 1559.40
#Mann=4,-1,0
  4683.8    0.07       0  4794.0    0.12       0  5028.1    0.05       0
  5032.1    0.12       0
Bank Sta=5028.1,5032.1
Exp/Cntr=0.3,0.1

Type RM Length L Ch R = 1,945,450,450,450
BEGIN DESCRIPTION:
Stream0033_DS 2.0
END DESCRIPTION:
XS GIS Cut Line= 3
      2047775.03     13936725.00      2047475.00     13936675.00
      2047164.65     13936856.52
#Sta/Elev= 30
  4696.0 1562.04  4706.2 1560.63  4723.9 1554.65  4729.0 1554.86  4777.1 1545.71
  4784.7 1543.44  4789.8 1543.28  4807.5 1538.67  4827.8 1535.34  4888.6 1529.14
  4911.5 1527.55  4949.5 1522.56  4970.3 1521.99  4970.5 1521.49  4974.3 1521.99
  4997.6 1523.23  5051.0 1524.06  5103.9 1525.99  5116.0 1527.25  5146.8 1528.64
  5211.3 1535.94  5227.0 1536.59  5242.7 1538.88  5255.0 1542.77  5264.2 1544.31
  5270.0 1546.32  5278.2 1547.24  5328.7 1548.45  5344.4 1547.83  5359.7 1548.19
#Mann=4,-1,0
  4696.0    0.12       0  4970.3    0.05       0  4974.3    0.12       0
  5211.3    0.07       0
Bank Sta=4970.3,4974.3
Exp/Cntr=0.3,0.1

Type RM Length L Ch R = 1,495,346,346,346
BEGIN DESCRIPTION:
Stream0033_DS 1.0
END DESCRIPTION:
XS GIS Cut Line= 3
      2047789.67     13936283.61      2047325.00     13936275.00
      2047189.85     13936759.55
#Sta/Elev= 30
  4535.6 1549.31  4540.5 1549.31  4560.3 1544.32  4590.3 1540.55  4640.3 1537.44
  4650.3 1535.81  4720.3 1530.68  4770.3 1528.52  4790.3 1526.63  4845.6 1523.63
  4880.3 1521.73  4940.3 1516.47  4988.4 1513.79  4988.6 1513.29  4992.4 1513.79
  5023.4 1515.20  5091.0 1516.87  5104.2 1518.23  5164.6 1521.03  5169.7 1520.71
  5176.8 1521.77  5270.3 1526.32  5277.5 1527.18  5316.9 1527.74  5356.2 1529.72
  5405.2 1530.33  5451.9 1532.66  5488.3 1535.08  5498.2 1536.57  5503.4 1538.15
#Mann=6,-1,0
  4535.6    0.12       0  4845.6    0.07       0  4988.4    0.05       0
  4992.4    0.07       0  5023.4    0.12       0  5451.9    0.07       0
Bank Sta=4988.4,4992.4
Exp/Cntr=0.3,0.1

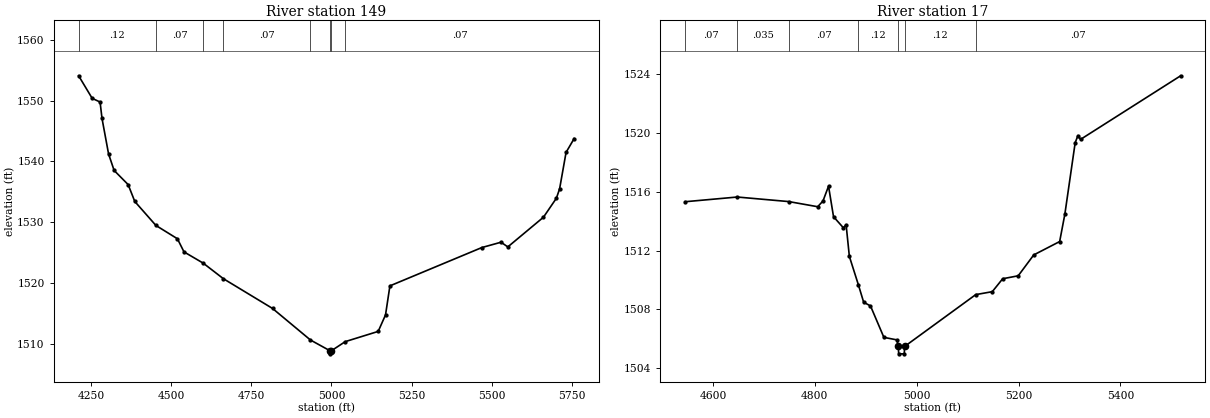
Type RM Length L Ch R = 1,149,132,132,132
BEGIN DESCRIPTION:
Stream0033_DS 0.1
END DESCRIPTION:
XS GIS Cut Line= 4
      2047846.32     13936224.17      2047075.07     13936054.98
      2047027.96     13936217.01      2047112.03     13936800.04
#Sta/Elev= 30
  4210.4 1554.07  4252.7 1550.36  4277.4 1549.75  4283.4 1547.05  4303.9 1541.21
  4321.2 1538.50  4365.0 1536.17  4385.8 1533.39  4451.7 1529.45  4518.9 1527.26
  4539.4 1525.10  4599.4 1523.25  4662.4 1520.69  4815.8 1515.80  4934.2 1510.61
  4995.5 1508.83  4995.7 1508.33  4999.5 1508.83  5043.0 1510.34  5145.8 1512.02
  5168.7 1514.73  5182.4 1519.51  5469.8 1525.82  5529.4 1526.69  5550.6 1525.92
  5661.8 1530.80  5702.2 1533.92  5712.3 1535.47  5732.5 1541.47  5757.8 1543.75
#Mann=8,-1,0
  4210.4    0.12       0  4451.7    0.07       0  4599.4    0.12       0
  4662.4    0.07       0  4934.2    0.12       0  4995.5    0.05       0
  4999.5    0.12       0  5043.0    0.07       0
Bank Sta=4995.5,4999.5
Exp/Cntr=0.3,0.1

Type RM Length L Ch R = 1,17,0,0,0
BEGIN DESCRIPTION:
Stream0033_DS 0.0
END DESCRIPTION:
XS GIS Cut Line= 5
      2047476.19     13935817.02      2047037.46     13935936.82
      2047034.62     13936066.45      2046995.54     13936274.34
      2047013.74     13936450.61
#Sta/Elev= 30
  4545.2 1515.33  4647.7 1515.65  4748.9 1515.34  4805.6 1514.99  4816.0 1515.38
  4826.9 1516.39  4836.7 1514.31  4856.2 1513.55  4861.4 1513.77  4867.8 1511.61
  4885.4 1509.69  4895.9 1508.49  4909.3 1508.24  4935.6 1506.10  4961.1 1505.93
  4964.1 1505.48  4964.6 1504.98  4975.7 1504.98  4976.2 1505.48  5116.0 1509.01
  5148.5 1509.21  5168.9 1510.09  5199.4 1510.29  5229.9 1511.71  5280.8 1512.62
  5291.0 1514.48  5311.3 1519.35  5316.7 1519.83  5321.8 1519.57  5518.4 1523.90
#Mann=7,-1,0
  4545.2    0.07       0  4647.7   0.035       0  4748.9    0.07       0
  4885.4    0.12       0  4964.1    0.05       0  4976.2    0.12       0
  5116.0    0.07       0
Bank Sta=4964.1,4976.2
Exp/Cntr=0.3,0.1

Chan Stop Cuts=-1