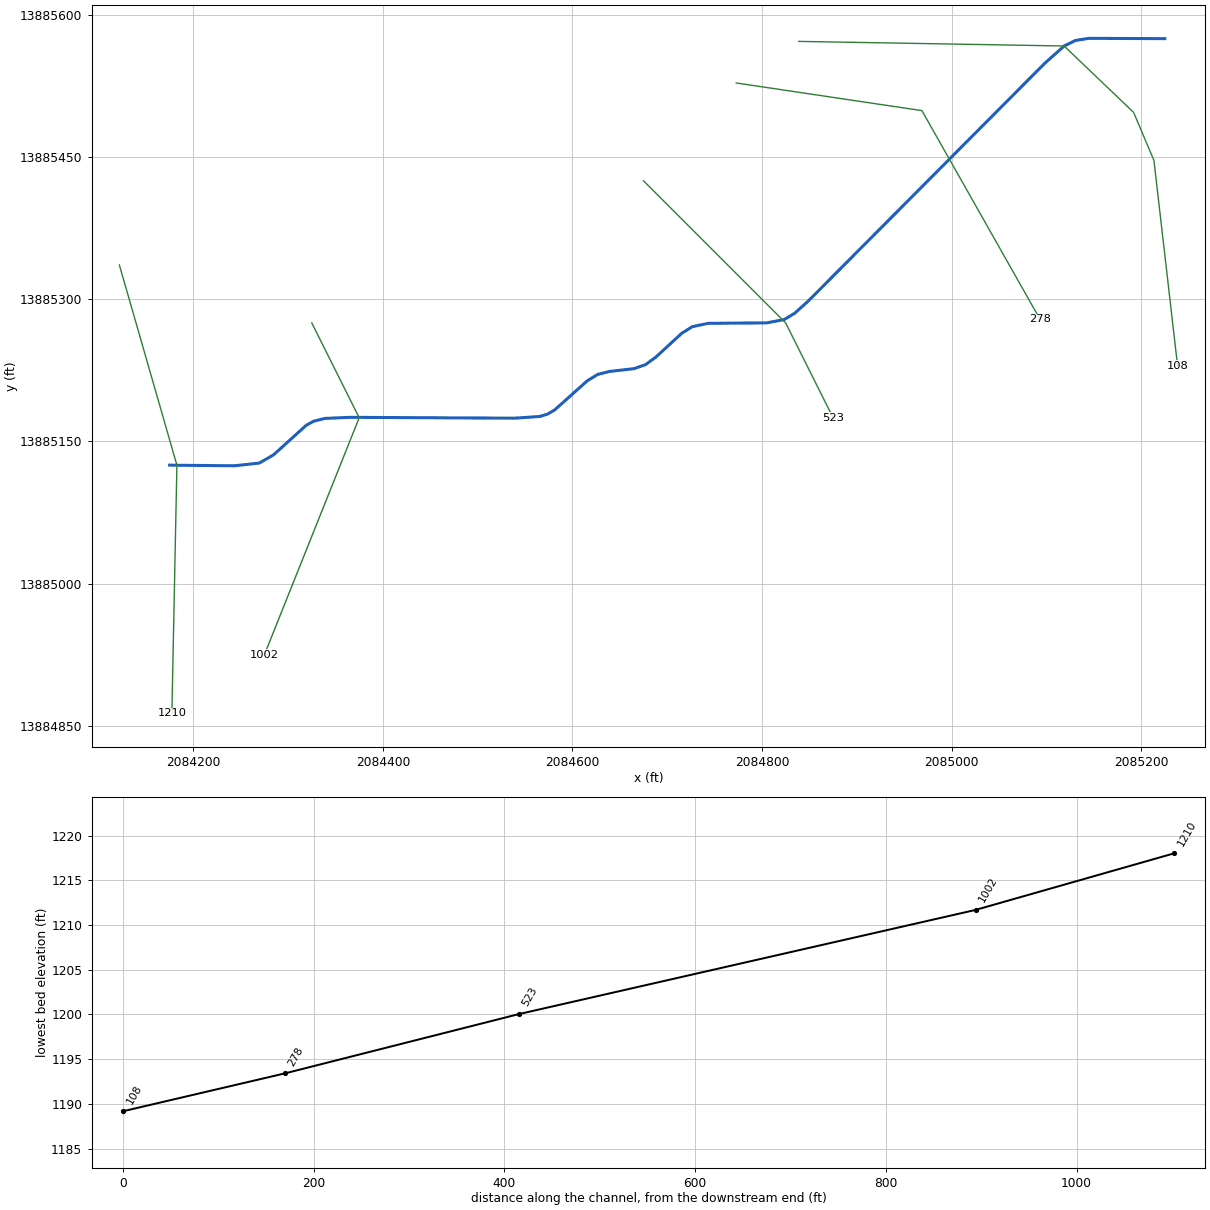
--- Stream0034_DS.prj (project) ---

Proj Title=Stream0034_DS Base Level Engineering
Current Plan=p01
Default Exp/Contr=0.3,0.1
English Units
Geom File=g01
Flow File=f01
Plan File=p01
BEGIN DESCRIPTION:
Stream0034_DS
END DESCRIPTION:

--- Stream0034_DS.p01 (plan) ---

Plan Title=Multiple Run
Short Identifier=Multiple
Geom File=g01
Flow File=f01
Subcritical Flow
K Sum by GR= 0
Std Step Tol= 0.01
Critical Tol= 0.01
Num of Std Step Trials= 20
Max Error Tol= 0.3
Flow Tol Ratio= 0.001
Split Flow NTrial= 30
Split Flow Tol= 0.02
Split Flow Ratio= 0.02
Log Output Level= 0
Friction Slope Method= 1
Unsteady Friction Slope Method= 2
Unsteady Bridges Friction Slope Method= 1
Parabolic Critical Depth
Global Vel Dist=  1 , 1 , 1
Global Log Level= 0
CheckData=True
Encroach Param= -1, 0, 0, 0
BEGIN DESCRIPTION:
Multiple Run
END DESCRIPTION:

--- Stream0034_DS.f01 (steady flow) ---

Flow Title=Multiple
Number of Profiles=7
Profile Names=10-year,25-year,50-year,1pct_min,100-year,1pct_plu,500-year
River Rch & RM= Stream0034_DS,Reach-1,1210
     354     559     742     480     958    1911    1571
Boundary for River Rch & Prof#=Stream0034_DS,Reach-1,1
Up Type=0
Dn Type=3
Dn Slope=0.005
Boundary for River Rch & Prof#=Stream0034_DS,Reach-1,2
Up Type=0
Dn Type=3
Dn Slope=0.005
Boundary for River Rch & Prof#=Stream0034_DS,Reach-1,3
Up Type=0
Dn Type=3
Dn Slope=0.005
Boundary for River Rch & Prof#=Stream0034_DS,Reach-1,4
Up Type=0
Dn Type=3
Dn Slope=0.005
Boundary for River Rch & Prof#=Stream0034_DS,Reach-1,5
Up Type=0
Dn Type=3
Dn Slope=0.005
Boundary for River Rch & Prof#=Stream0034_DS,Reach-1,6
Up Type=0
Dn Type=3
Dn Slope=0.005
Boundary for River Rch & Prof#=Stream0034_DS,Reach-1,7
Up Type=0
Dn Type=3
Dn Slope=0.005

--- Stream0034_DS.g01 (geometry) ---

Geom Title=Existing Conditions

River Reach=Stream0034_DS,Reach-1
Reach XY= 30
      2084175.00     13885125.00      2084243.46     13885124.33
      2084269.53     13885127.22      2084284.64     13885135.86
      2084318.93     13885166.90      2084326.55     13885171.25
      2084338.91     13885174.33      2084365.72     13885175.45
      2084538.82     13885174.56      2084565.35     13885176.36
      2084573.45     13885178.75      2084581.08     13885183.09
      2084615.47     13885213.86      2084626.74     13885220.81
      2084639.10     13885223.88      2084665.15     13885226.83
      2084677.18     13885231.11      2084688.04     13885239.03
      2084715.35     13885264.16      2084726.59     13885271.17
      2084743.33     13885274.64      2084804.95     13885275.13
      2084823.50     13885278.61      2084834.79     13885285.52
      2084848.52     13885297.88      2085098.14     13885548.81
      2085118.78     13885567.26      2085130.77     13885573.14
      2085144.86     13885575.33      2085225.00     13885575.00

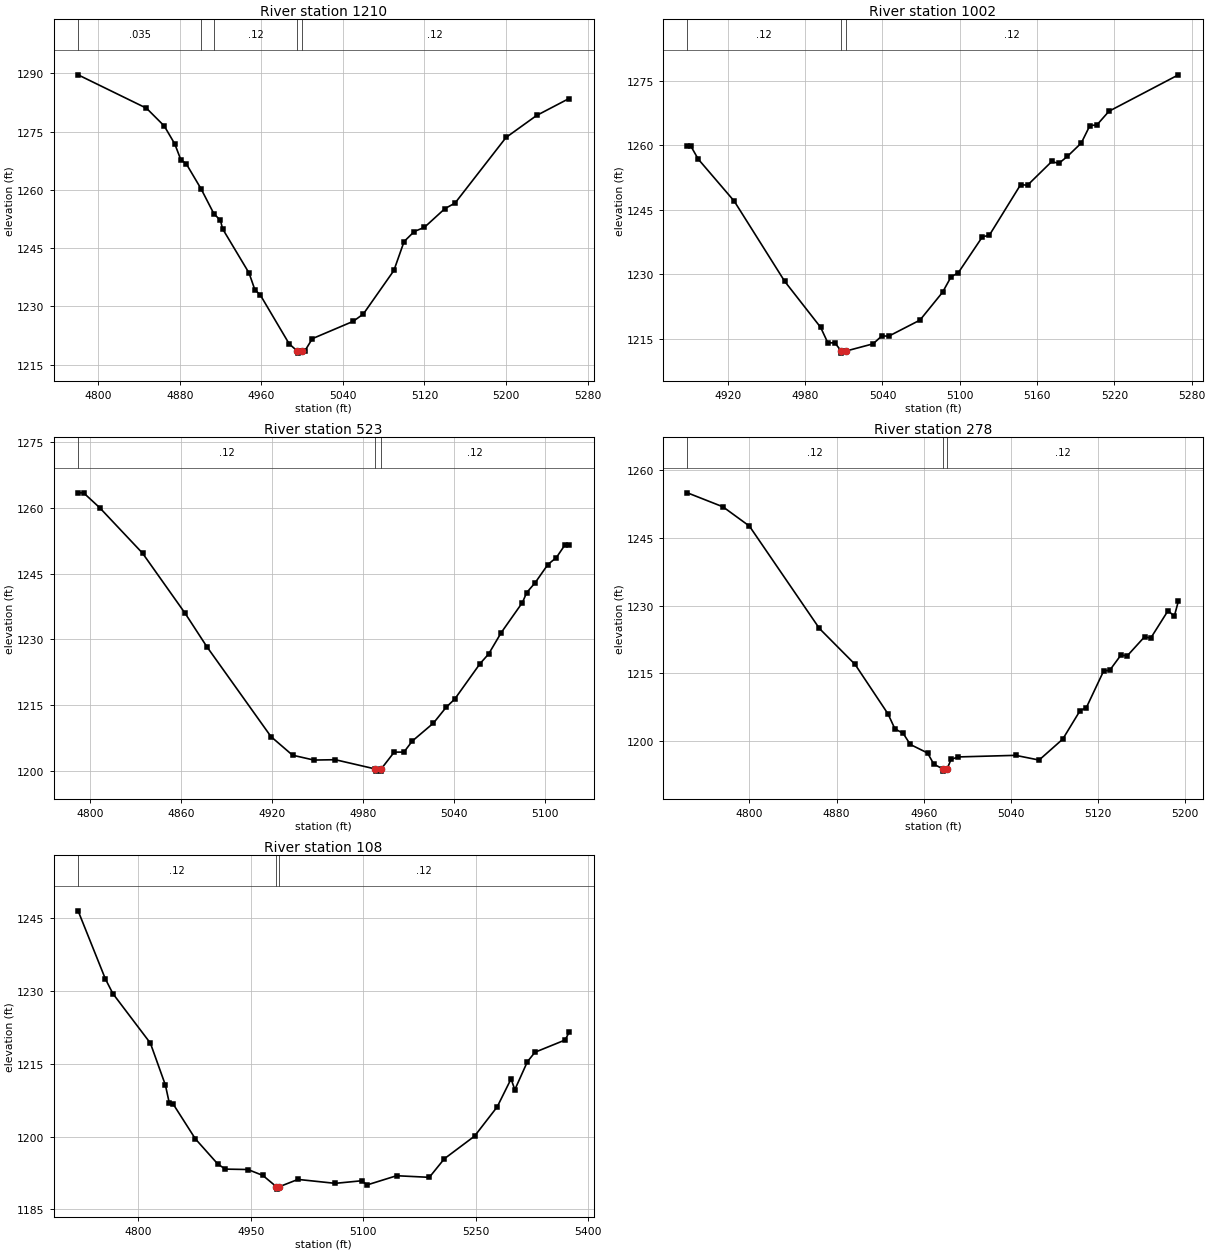
Type RM Length L Ch R = 1,1210,208,208,208
BEGIN DESCRIPTION:
Stream0034_DS 3.0
END DESCRIPTION:
XS GIS Cut Line= 3
      2084121.97     13885336.21      2084182.67     13885124.96
      2084177.36     13884863.11
#Sta/Elev= 30
  4780.2 1289.59  4847.3 1281.00  4864.7 1276.44  4875.1 1271.79  4881.0 1267.72
  4886.2 1266.75  4901.0 1260.19  4913.3 1253.91  4919.9 1252.12  4921.9 1250.00
  4947.9 1238.61  4953.6 1234.31  4958.8 1233.02  4987.3 1220.38  4995.4 1218.50
  4995.6 1218.00  4999.4 1218.50  5002.5 1218.50  5010.0 1221.72  5050.0 1226.17
  5060.0 1228.05  5090.0 1239.26  5100.0 1246.70  5110.0 1249.28  5120.0 1250.37
  5140.0 1255.16  5150.0 1256.60  5200.0 1273.47  5230.0 1279.13  5261.9 1283.50
#Mann=5,-1,0
  4780.2   0.035       0  4901.0    0.07       0  4913.3    0.12       0
  4995.4    0.05       0  4999.4    0.12       0
Bank Sta=4995.4,4999.4
Exp/Cntr=0.3,0.1

Type RM Length L Ch R = 1,1002,479,479,479
BEGIN DESCRIPTION:
Stream0034_DS 2.0
END DESCRIPTION:
XS GIS Cut Line= 3
      2084324.99     13885275.03      2084375.00     13885175.00
      2084275.00     13884924.99
#Sta/Elev= 30
  4888.6 1259.75  4891.4 1259.75  4897.0 1256.80  4925.0 1247.00  4964.1 1228.38
  4992.0 1217.68  4997.6 1214.07  5003.1 1214.07  5007.9 1212.18  5008.1 1211.68
  5011.9 1212.18  5032.7 1213.84  5039.5 1215.68  5044.9 1215.63  5069.1 1219.36
  5086.6 1225.82  5093.3 1229.45  5098.7 1230.31  5117.6 1238.75  5122.9 1239.07
  5147.2 1250.85  5152.6 1250.73  5171.4 1256.25  5176.8 1255.79  5183.5 1257.42
  5194.3 1260.54  5201.0 1264.61  5206.4 1264.74  5215.8 1267.93  5269.7 1276.40
#Mann=3,-1,0
  4888.6    0.12       0  5007.9    0.05       0  5011.9    0.12       0
Bank Sta=5007.9,5011.9
Exp/Cntr=0.3,0.1

Type RM Length L Ch R = 1,523,245,245,245
BEGIN DESCRIPTION:
Stream0034_DS 1.0
END DESCRIPTION:
XS GIS Cut Line= 3
      2084674.98     13885425.02      2084825.00     13885275.00
      2084875.02     13885174.97
#Sta/Elev= 30
  4792.2 1263.39  4795.8 1263.39  4806.4 1260.02  4834.7 1249.66  4862.9 1235.92
  4877.1 1228.39  4919.5 1207.88  4933.7 1203.66  4947.8 1202.55  4961.9 1202.63
  4988.2 1200.53  4988.5 1200.03  4992.0 1200.03  4992.2 1200.53  5000.8 1204.36
  5007.2 1204.36  5012.7 1206.87  5026.7 1210.97  5035.1 1214.58  5040.7 1216.42
  5057.5 1224.53  5063.1 1226.70  5071.4 1231.56  5085.4 1238.42  5088.2 1240.67
  5093.8 1242.92  5102.2 1247.07  5107.8 1248.65  5113.4 1251.50  5116.2 1251.50
#Mann=3,-1,0
  4792.2    0.12       0  4988.2    0.05       0  4992.2    0.12       0
Bank Sta=4988.2,4992.2
Exp/Cntr=0.3,0.1

Type RM Length L Ch R = 1,278,170,170,170
BEGIN DESCRIPTION:
Stream0034_DS 0.5
END DESCRIPTION:
XS GIS Cut Line= 3
      2084772.80     13885528.24      2084968.71     13885499.06
      2085093.20     13885279.12
#Sta/Elev= 30
  4743.0 1254.95  4775.6 1251.86  4799.9 1247.60  4864.2 1224.95  4896.9 1217.02
  4927.2 1206.05  4933.5 1202.76  4941.1 1201.76  4947.6 1199.31  4963.5 1197.42
  4969.2 1194.96  4977.4 1193.91  4977.6 1193.41  4981.4 1193.91  4985.1 1196.01
  4991.7 1196.55  5044.3 1196.90  5065.9 1195.86  5087.6 1200.49  5103.5 1206.78
  5109.2 1207.42  5125.1 1215.53  5130.9 1215.76  5141.0 1219.07  5146.8 1218.90
  5162.7 1223.11  5168.4 1222.83  5184.3 1228.90  5190.0 1227.65  5193.8 1231.03
#Mann=3,-1,0
  4743.0    0.12       0  4977.4    0.05       0  4981.4    0.12       0
Bank Sta=4977.4,4981.4
Exp/Cntr=0.3,0.1

Type RM Length L Ch R = 1,108,0,0,0
BEGIN DESCRIPTION:
Stream0034_DS 0.0
END DESCRIPTION:
XS GIS Cut Line= 5
      2084838.62     13885572.11      2085118.78     13885567.26
      2085192.06     13885497.21      2085213.52     13885446.51
      2085238.47     13885229.78
#Sta/Elev= 30
  4719.8 1246.48  4756.2 1232.45  4766.2 1229.43  4816.2 1219.23  4836.2 1210.61
  4841.5 1206.85  4846.5 1206.71  4876.2 1199.52  4906.2 1194.32  4916.2 1193.29
  4946.2 1193.21  4966.2 1191.99  4984.2 1189.67  4984.5 1189.17  4988.2 1189.67
  5013.0 1191.17  5062.7 1190.36  5097.9 1190.89  5105.3 1190.04  5144.6 1191.93
  5188.2 1191.60  5208.2 1195.42  5248.5 1200.08  5278.7 1206.11  5297.2 1211.87
  5302.2 1209.64  5319.0 1215.42  5329.1 1217.36  5369.3 1219.88  5374.6 1221.48
#Mann=3,-1,0
  4719.8    0.12       0  4984.2    0.05       0  4988.2    0.12       0
Bank Sta=4984.2,4988.2
Exp/Cntr=0.3,0.1

Chan Stop Cuts=-1