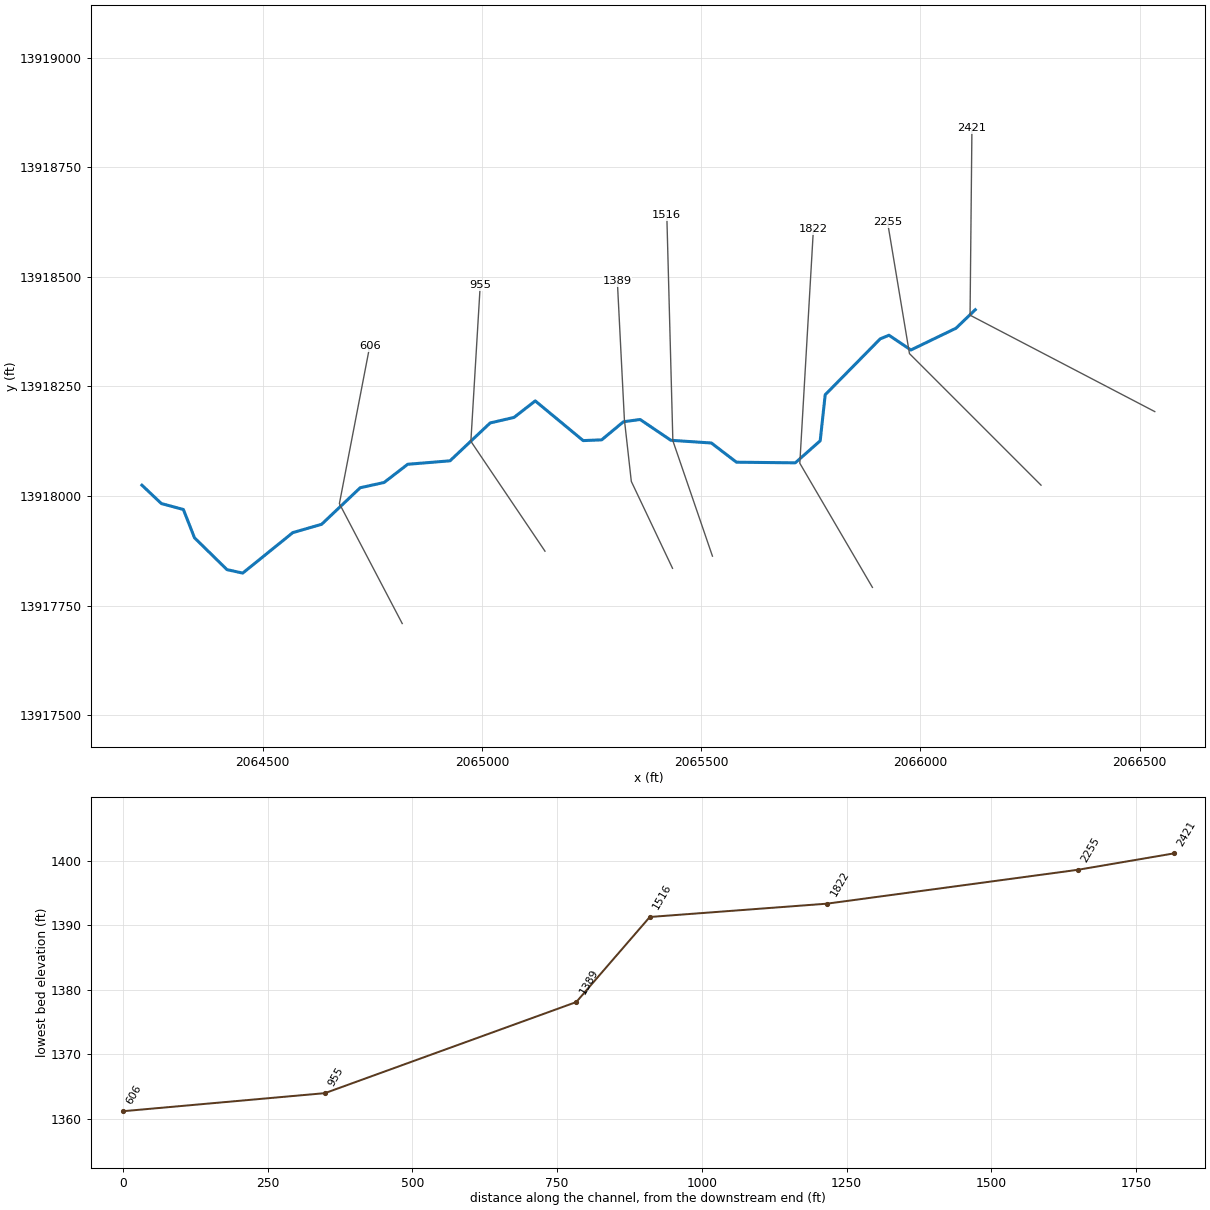
--- Stream0035_DS.prj (project) ---

Proj Title=Stream0035_DS Base Level Engineering
Current Plan=p01
Default Exp/Contr=0.3,0.1
English Units
Geom File=g01
Flow File=f01
Plan File=p01
BEGIN DESCRIPTION:
Stream0035_DS
END DESCRIPTION:

--- Stream0035_DS.p01 (plan) ---

Plan Title=Multiple Run
Short Identifier=Multiple
Geom File=g01
Flow File=f01
Subcritical Flow
K Sum by GR= 0
Std Step Tol= 0.01
Critical Tol= 0.01
Num of Std Step Trials= 20
Max Error Tol= 0.3
Flow Tol Ratio= 0.001
Split Flow NTrial= 30
Split Flow Tol= 0.02
Split Flow Ratio= 0.02
Log Output Level= 0
Friction Slope Method= 1
Unsteady Friction Slope Method= 2
Unsteady Bridges Friction Slope Method= 1
Parabolic Critical Depth
Global Vel Dist=  1 , 1 , 1
Global Log Level= 0
CheckData=True
Encroach Param= -1, 0, 0, 0
BEGIN DESCRIPTION:
Multiple Run
END DESCRIPTION:

--- Stream0035_DS.f01 (steady flow) ---

Flow Title=Multiple
Number of Profiles=7
Profile Names=10-year,25-year,50-year,1pct_min,100-year,1pct_plu,500-year
River Rch & RM= Stream0035_DS,Reach-1,2421
    1038    1785    2508    1712    3417    6817    6281
River Rch & RM= Stream0035_DS,Reach-1,2255
    1097    1889    2656    1814    3619    7220    6656
Boundary for River Rch & Prof#=Stream0035_DS,Reach-1,1
Up Type=0
Dn Type=3
Dn Slope=0.005
Boundary for River Rch & Prof#=Stream0035_DS,Reach-1,2
Up Type=0
Dn Type=3
Dn Slope=0.005
Boundary for River Rch & Prof#=Stream0035_DS,Reach-1,3
Up Type=0
Dn Type=3
Dn Slope=0.005
Boundary for River Rch & Prof#=Stream0035_DS,Reach-1,4
Up Type=0
Dn Type=3
Dn Slope=0.005
Boundary for River Rch & Prof#=Stream0035_DS,Reach-1,5
Up Type=0
Dn Type=3
Dn Slope=0.005
Boundary for River Rch & Prof#=Stream0035_DS,Reach-1,6
Up Type=0
Dn Type=3
Dn Slope=0.005
Boundary for River Rch & Prof#=Stream0035_DS,Reach-1,7
Up Type=0
Dn Type=3
Dn Slope=0.005

--- Stream0035_DS.g01 (geometry) ---

Geom Title=Existing Conditions

River Reach=Stream0035_DS,Reach-1
Reach XY= 30
      2066125.00     13918425.00      2066081.14     13918382.88
      2065978.23     13918333.23      2065928.33     13918366.86
      2065908.33     13918358.61      2065782.86     13918231.17
      2065771.49     13918126.25      2065714.73     13918075.97
      2065580.53     13918077.37      2065523.40     13918121.14
      2065430.97     13918127.38      2065360.90     13918174.75
      2065322.80     13918169.58      2065273.26     13918128.37
      2065231.04     13918126.64      2065121.77     13918217.16
      2065073.35     13918179.46      2065018.96     13918166.86
      2064927.42     13918080.54      2064830.97     13918072.67
      2064777.17     13918031.14      2064722.71     13918019.16
      2064634.67     13917935.80      2064568.96     13917916.82
      2064454.83     13917824.53      2064418.93     13917832.46
      2064344.84     13917905.03      2064319.49     13917969.56
      2064269.30     13917983.12      2064225.00     13918025.00

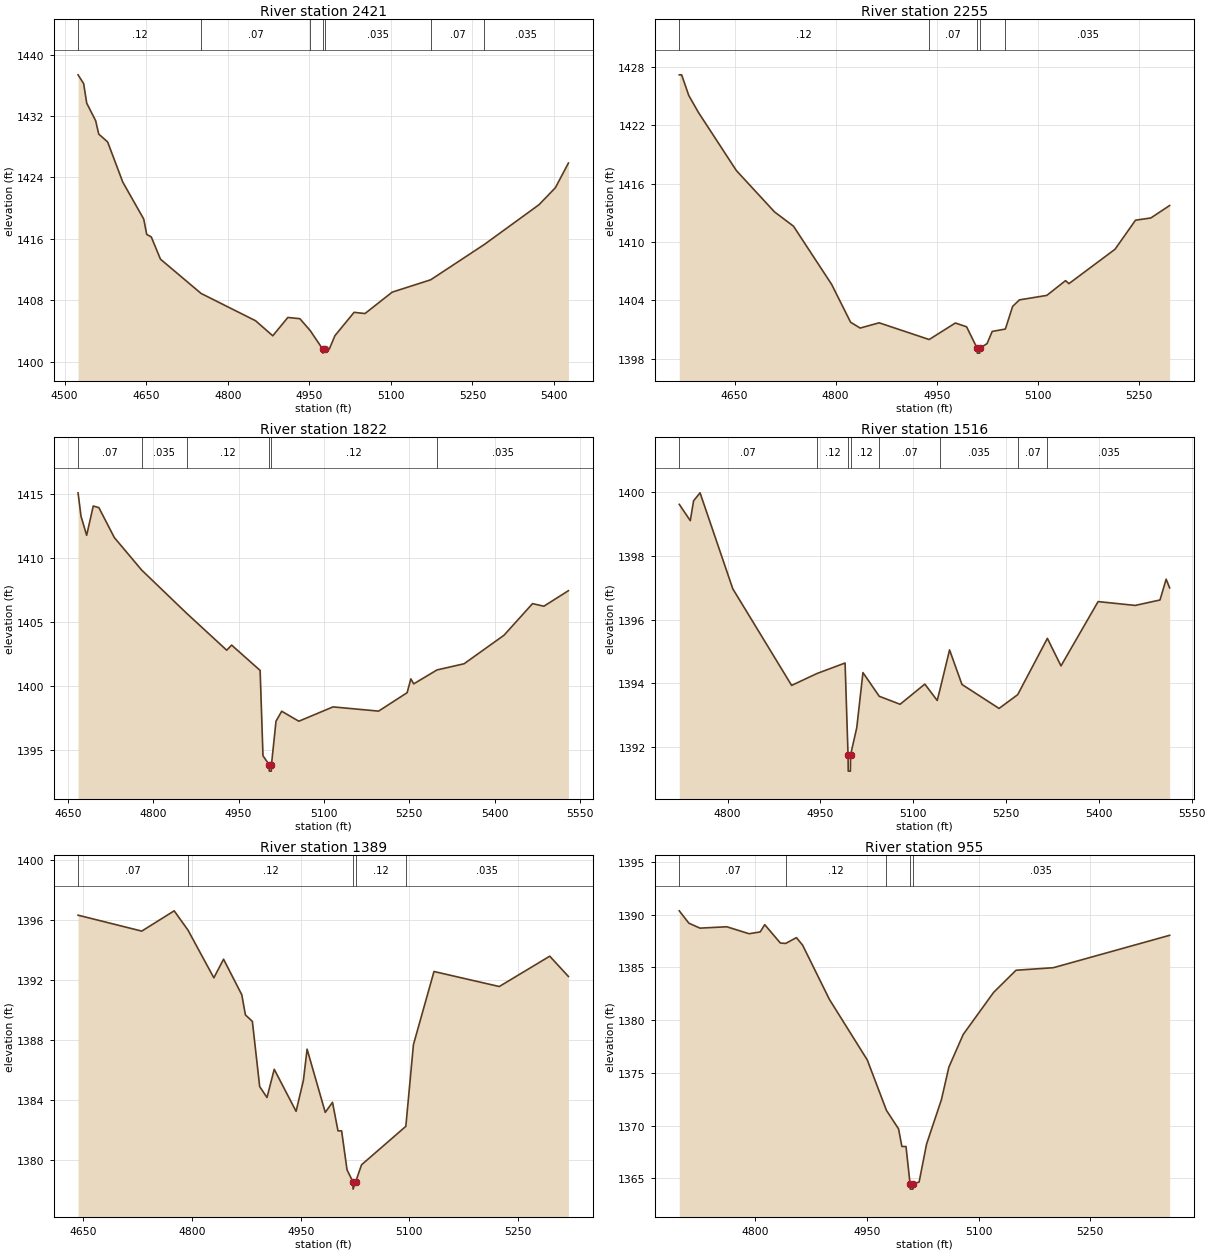
Type RM Length L Ch R = 1,2421,166,166,166
BEGIN DESCRIPTION:
Stream0035_DS 6.0
END DESCRIPTION:
XS GIS Cut Line= 3
      2066534.32     13918192.77      2066113.15     13918412.61
      2066117.45     13918838.99
#Sta/Elev= 30
  4524.9 1437.38  4535.2 1436.23  4540.8 1433.69  4557.2 1431.41  4562.9 1429.66
  4579.3 1428.63  4607.1 1423.40  4645.6 1418.58  4651.2 1416.57  4659.5 1416.25
  4676.4 1413.35  4751.1 1408.88  4851.3 1405.32  4882.9 1403.36  4910.6 1405.75
  4932.7 1405.59  4951.8 1404.03  4974.9 1401.60  4975.1 1401.10  4978.9 1401.60
  4986.6 1401.60  4997.2 1403.38  5032.4 1406.42  5052.4 1406.26  5102.4 1409.05
  5173.2 1410.66  5271.5 1415.25  5372.4 1420.45  5402.4 1422.66  5426.4 1425.88
#Mann=7,-1,0
  4524.9    0.12       0  4751.1    0.07       0  4951.8   0.035       0
  4974.9   0.035       0  4978.9   0.035       0  5173.2    0.07       0
  5271.5   0.035       0
Bank Sta=4974.9,4978.9
Exp/Cntr=0.3,0.1

Type RM Length L Ch R = 1,2255,433,433,433
BEGIN DESCRIPTION:
Stream0035_DS 5.0
END DESCRIPTION:
XS GIS Cut Line= 3
      2066274.97     13918025.03      2065975.00     13918325.00
      2065924.99     13918625.04
#Sta/Elev= 30
  4567.7 1427.20  4571.2 1427.20  4581.8 1425.08  4595.9 1423.36  4652.5 1417.35
  4709.1 1413.10  4737.4 1411.62  4793.9 1405.65  4822.2 1401.74  4836.4 1401.14
  4864.6 1401.68  4938.9 1399.96  4977.8 1401.66  4994.5 1401.27  5010.2 1399.06
  5010.4 1398.56  5013.9 1398.56  5014.2 1399.06  5024.9 1399.54  5032.5 1400.79
  5052.1 1401.04  5062.9 1403.37  5073.0 1404.04  5113.6 1404.50  5141.5 1406.02
  5146.5 1405.71  5215.0 1409.25  5245.4 1412.24  5268.2 1412.47  5296.1 1413.75
#Mann=5,-1,0
  4567.7    0.12       0  4938.9    0.07       0  5010.2    0.05       0
  5014.2    0.07       0  5052.1   0.035       0
Bank Sta=5010.2,5014.2
Exp/Cntr=0.3,0.1

Type RM Length L Ch R = 1,1822,306,306,306
BEGIN DESCRIPTION:
Stream0035_DS 4.0
END DESCRIPTION:
XS GIS Cut Line= 3
      2065890.53     13917791.99      2065725.00     13918075.00
      2065755.96     13918608.04
#Sta/Elev= 30
  4668.0 1415.07  4673.2 1413.24  4683.1 1411.75  4694.7 1414.04  4704.6 1413.91
  4731.8 1411.57  4779.9 1409.03  4859.2 1405.64  4929.3 1402.77  4937.9 1403.17
  4988.0 1401.19  4993.0 1394.52  5003.9 1393.82  5004.1 1393.32  5007.6 1393.32
  5007.9 1393.82  5015.9 1397.22  5025.9 1398.00  5056.0 1397.22  5116.1 1398.34
  5196.2 1398.01  5246.3 1399.45  5252.9 1400.53  5257.9 1400.14  5298.9 1401.23
  5346.4 1401.71  5416.6 1403.94  5466.7 1406.41  5486.7 1406.21  5529.8 1407.42
#Mann=6,-1,0
  4668.0    0.07       0  4779.9   0.035       0  4859.2    0.12       0
  5003.9    0.05       0  5007.9    0.12       0  5298.9   0.035       0
Bank Sta=5003.9,5007.9
Exp/Cntr=0.3,0.1

Type RM Length L Ch R = 1,1516,127,127,127
BEGIN DESCRIPTION:
Stream0035_DS 3.5
END DESCRIPTION:
XS GIS Cut Line= 3
      2065525.79     13917863.20      2065435.54     13918126.35
      2065421.74     13918640.57
#Sta/Elev= 30
  4721.8 1399.60  4739.6 1399.09  4744.9 1399.71  4755.4 1399.96  4808.3 1396.96
  4903.4 1393.94  4944.2 1394.31  4989.8 1394.64  4994.6 1391.76  4994.9 1391.26
  4998.4 1391.26  4998.6 1391.76  5008.7 1392.62  5018.7 1394.34  5045.0 1393.60
  5078.7 1393.35  5118.7 1393.98  5138.7 1393.47  5143.3 1393.82  5158.7 1395.05
  5178.7 1393.97  5238.7 1393.22  5268.8 1393.65  5316.8 1395.41  5338.8 1394.55
  5398.8 1396.56  5458.8 1396.44  5498.8 1396.61  5508.8 1397.26  5514.4 1396.99
#Mann=8,-1,0
  4721.8    0.07       0  4944.2    0.12       0  4994.6    0.05       0
  4998.6    0.12       0  5045.0    0.07       0  5143.3   0.035       0
  5268.8    0.07       0  5316.8   0.035       0
Bank Sta=4994.6,4998.6
Exp/Cntr=0.3,0.1

Type RM Length L Ch R = 1,1389,434,434,434
BEGIN DESCRIPTION:
Stream0035_DS 3.0
END DESCRIPTION:
XS GIS Cut Line= 4
      2065434.77     13917835.45      2065340.81     13918033.59
      2065325.00     13918175.00      2065308.93     13918490.41
#Sta/Elev= 30
  4642.5 1396.33  4730.5 1395.27  4775.3 1396.62  4794.3 1395.34  4830.1 1392.16
  4843.5 1393.40  4868.7 1391.03  4873.7 1389.69  4883.3 1389.26  4893.4 1384.92
  4903.5 1384.19  4913.5 1386.07  4943.7 1383.27  4953.8 1385.33  4958.9 1387.41
  4984.0 1383.20  4994.0 1383.87  5001.6 1381.97  5006.6 1381.97  5014.1 1379.37
  5022.1 1378.59  5022.4 1378.09  5026.1 1378.59  5034.1 1379.71  5095.3 1382.27
  5105.8 1387.71  5134.2 1392.58  5224.4 1391.58  5294.1 1393.60  5319.9 1392.25
#Mann=5,-1,0
  4642.5    0.07       0  4794.3    0.12       0  5022.1    0.05       0
  5026.1    0.12       0  5095.3   0.035       0
Bank Sta=5022.1,5026.1
Exp/Cntr=0.3,0.1

Type RM Length L Ch R = 1,955,349,349,349
BEGIN DESCRIPTION:
Stream0035_DS 2.0
END DESCRIPTION:
XS GIS Cut Line= 3
      2065143.95     13917874.53      2064975.00     13918125.00
      2064996.34     13918481.04
#Sta/Elev= 30
  4697.9 1390.36  4710.8 1389.19  4725.7 1388.72  4761.7 1388.85  4791.7 1388.19
  4806.6 1388.36  4812.7 1389.05  4833.7 1387.31  4840.8 1387.27  4855.3 1387.82
  4863.6 1387.11  4899.6 1381.97  4950.5 1376.23  4976.2 1371.46  4992.5 1369.70
  4997.0 1368.03  5002.5 1368.03  5008.0 1364.49  5008.3 1363.99  5011.8 1363.99
  5012.0 1364.49  5020.1 1364.66  5030.1 1368.25  5050.1 1372.47  5060.1 1375.55
  5079.4 1378.65  5120.2 1382.63  5150.3 1384.73  5200.4 1384.97  5356.7 1388.04
#Mann=5,-1,0
  4697.9    0.07       0  4840.8    0.12       0  4976.2   0.035       0
  5008.0   0.035       0  5012.0   0.035       0
Bank Sta=5008,5012
Exp/Cntr=0.3,0.1

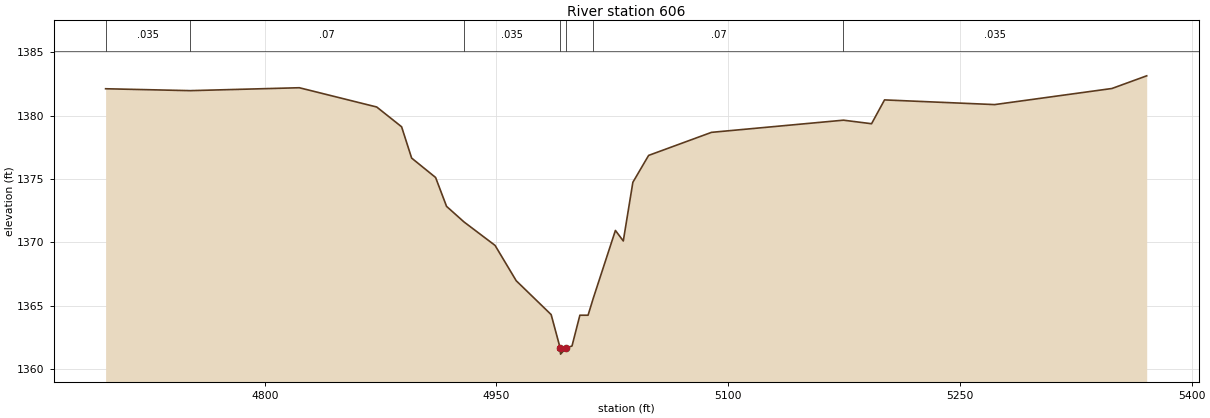
Type RM Length L Ch R = 1,606,0,0,0
BEGIN DESCRIPTION:
Stream0035_DS 1.0
END DESCRIPTION:
XS GIS Cut Line= 3
      2064818.47     13917709.54      2064675.23     13917983.01
      2064744.35     13918341.59
#Sta/Elev= 30
  4697.0 1382.13  4751.8 1381.98  4822.4 1382.21  4872.5 1380.69  4888.6 1379.13
  4895.1 1376.66  4910.6 1375.13  4917.7 1372.85  4929.0 1371.62  4949.1 1369.77
  4962.8 1366.98  4985.4 1364.31  4991.2 1361.69  4991.5 1361.19  4995.2 1361.69
  4998.9 1361.83  5004.0 1364.26  5009.3 1364.26  5012.7 1365.61  5027.0 1370.95
  5032.1 1370.12  5038.3 1374.75  5048.5 1376.87  5089.2 1378.69  5174.6 1379.65
  5192.8 1379.37  5201.2 1381.25  5272.5 1380.88  5348.4 1382.15  5370.9 1383.15
#Mann=7,-1,0
  4697.0   0.035       0  4751.8    0.07       0  4929.0   0.035       0
  4991.2   0.035       0  4995.2   0.035       0  5012.7    0.07       0
  5174.6   0.035       0
Bank Sta=4991.2,4995.2
Exp/Cntr=0.3,0.1

Chan Stop Cuts=-1