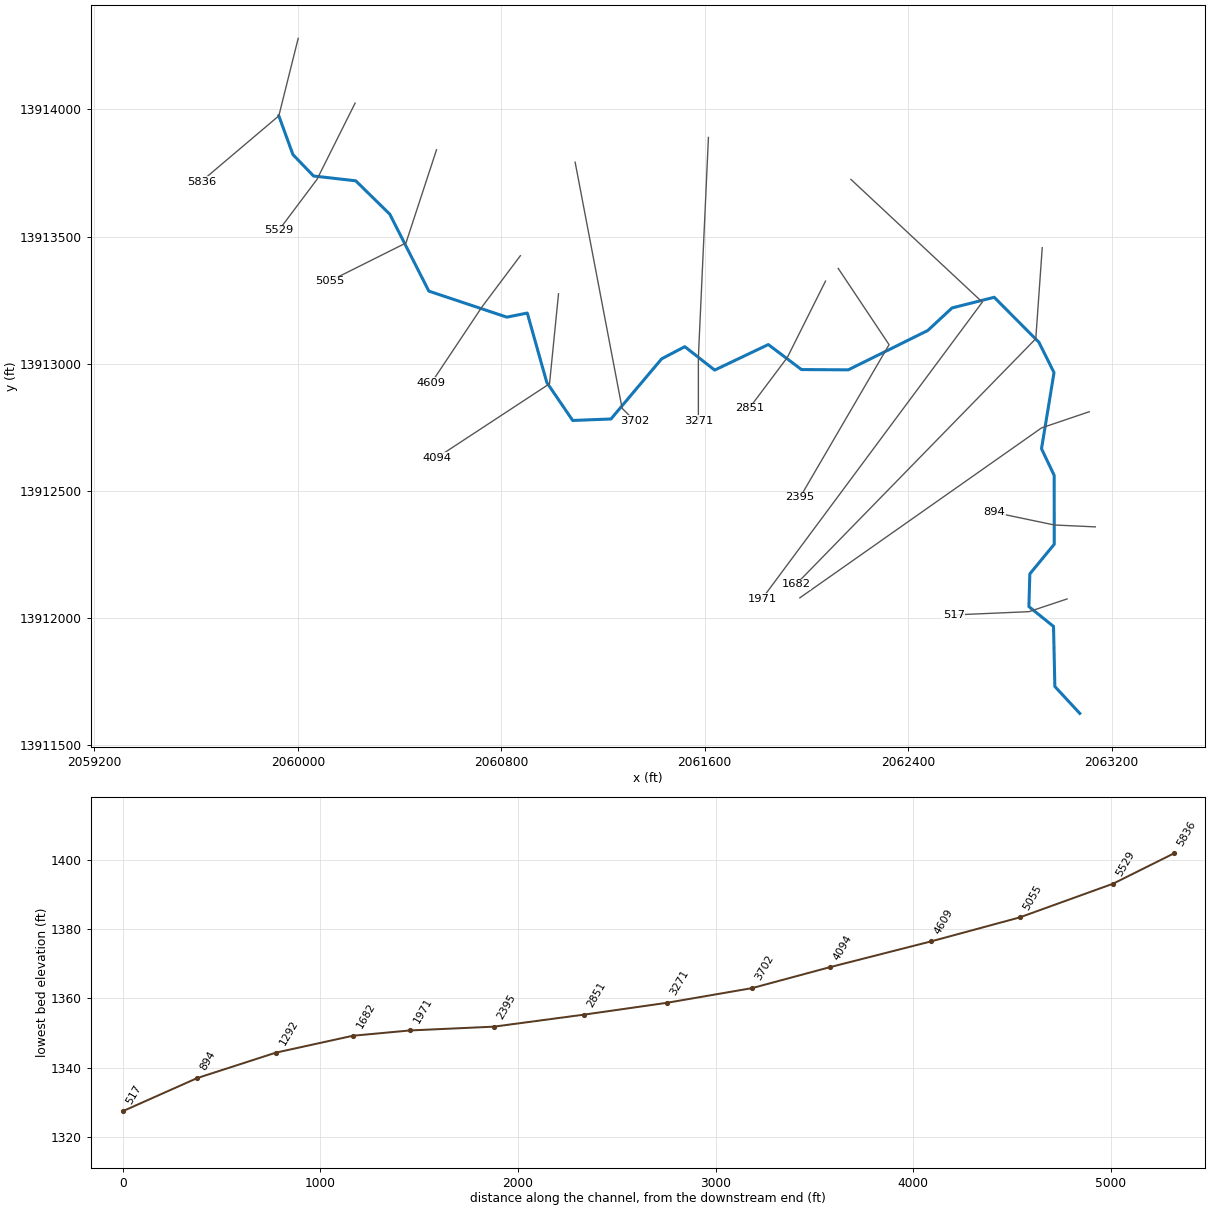
--- Stream0036_DS.prj (project) ---

Proj Title=Stream0036_DS Base Level Engineering
Current Plan=p01
Default Exp/Contr=0.3,0.1
English Units
Geom File=g01
Flow File=f01
Plan File=p01
BEGIN DESCRIPTION:
Stream0036_DS
END DESCRIPTION:

--- Stream0036_DS.p01 (plan) ---

Plan Title=Multiple Run
Short Identifier=Multiple
Geom File=g01
Flow File=f01
Subcritical Flow
K Sum by GR= 0
Std Step Tol= 0.01
Critical Tol= 0.01
Num of Std Step Trials= 20
Max Error Tol= 0.3
Flow Tol Ratio= 0.001
Split Flow NTrial= 30
Split Flow Tol= 0.02
Split Flow Ratio= 0.02
Log Output Level= 0
Friction Slope Method= 1
Unsteady Friction Slope Method= 2
Unsteady Bridges Friction Slope Method= 1
Parabolic Critical Depth
Global Vel Dist=  1 , 1 , 1
Global Log Level= 0
CheckData=True
Encroach Param= -1, 0, 0, 0
BEGIN DESCRIPTION:
Multiple Run
END DESCRIPTION:

--- Stream0036_DS.f01 (steady flow) ---

Flow Title=Multiple
Number of Profiles=7
Profile Names=10-year,25-year,50-year,1pct_min,100-year,1pct_plu,500-year
River Rch & RM= Stream0036_DS,Reach-1,5836
     449     724     975     639    1276    2545    2158
River Rch & RM= Stream0036_DS,Reach-1,5529
     695    1148    1570    1043    2081    4153    3622
Boundary for River Rch & Prof#=Stream0036_DS,Reach-1,1
Up Type=0
Dn Type=3
Dn Slope=0.005
Boundary for River Rch & Prof#=Stream0036_DS,Reach-1,2
Up Type=0
Dn Type=3
Dn Slope=0.005
Boundary for River Rch & Prof#=Stream0036_DS,Reach-1,3
Up Type=0
Dn Type=3
Dn Slope=0.005
Boundary for River Rch & Prof#=Stream0036_DS,Reach-1,4
Up Type=0
Dn Type=3
Dn Slope=0.005
Boundary for River Rch & Prof#=Stream0036_DS,Reach-1,5
Up Type=0
Dn Type=3
Dn Slope=0.005
Boundary for River Rch & Prof#=Stream0036_DS,Reach-1,6
Up Type=0
Dn Type=3
Dn Slope=0.005
Boundary for River Rch & Prof#=Stream0036_DS,Reach-1,7
Up Type=0
Dn Type=3
Dn Slope=0.005

--- Stream0036_DS.g01 (geometry) ---

Geom Title=Existing Conditions

River Reach=Stream0036_DS,Reach-1
Reach XY= 30
      2059925.00     13913975.00      2059980.49     13913822.55
      2060061.65     13913738.36      2060227.45     13913719.53
      2060361.38     13913588.22      2060515.00     13913285.63
      2060821.79     13913183.29      2060902.13     13913199.42
      2060978.82     13912926.58      2061080.67     13912776.97
      2061231.19     13912782.81      2061430.62     13913019.44
      2061521.73     13913067.17      2061639.04     13912975.10
      2061850.03     13913075.50      2061980.45     13912977.18
      2062164.56     13912976.05      2062477.29     13913130.85
      2062572.58     13913219.47      2062738.38     13913261.47
      2062914.24     13913084.68      2062973.75     13912965.30
      2062924.54     13912665.72      2062974.32     13912561.08
      2062974.61     13912290.16      2062878.54     13912173.53
      2062874.91     13912044.89      2062971.74     13911966.98
      2062976.99     13911730.68      2063075.00     13911625.00

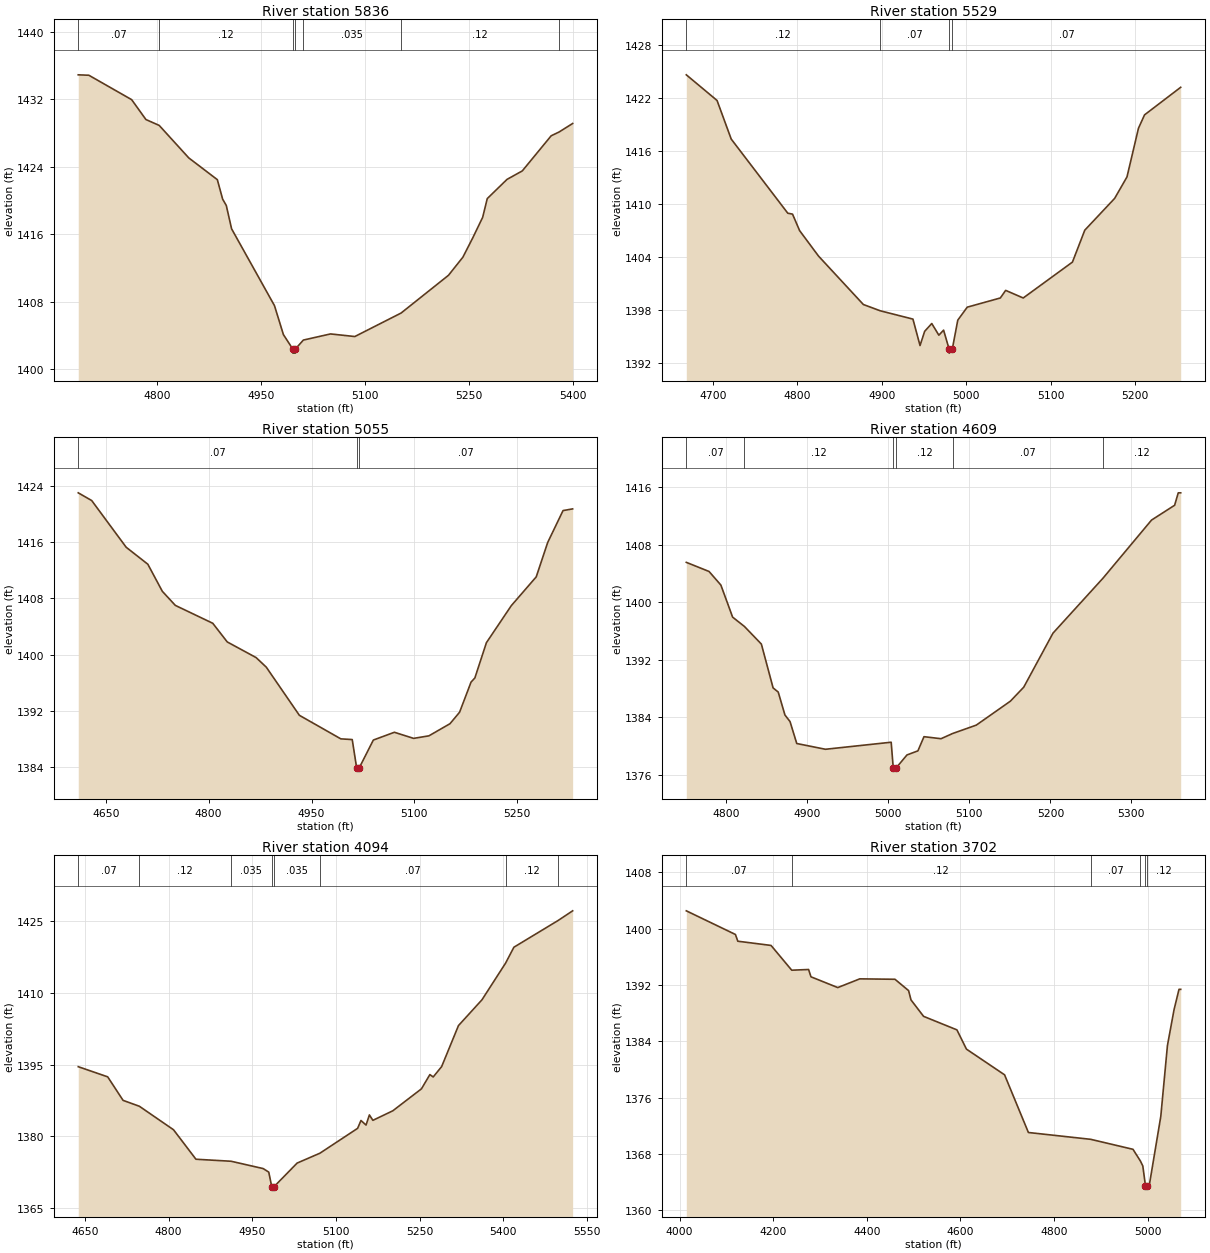
Type RM Length L Ch R = 1,5836,307,307,307
BEGIN DESCRIPTION:
Stream0036_DS 11.0
END DESCRIPTION:
XS GIS Cut Line= 3
      2060001.14     13914279.83      2059925.00     13913975.00
      2059620.05     13913716.77
#Sta/Elev= 30
  4685.8 1434.92  4701.1 1434.87  4762.9 1431.97  4783.5 1429.61  4802.7 1428.91
  4845.4 1425.05  4886.6 1422.47  4894.3 1420.15  4899.5 1419.41  4907.2 1416.63
  4969.1 1407.51  4982.0 1404.07  4995.4 1402.37  4995.7 1401.87  4999.2 1401.87
  4999.4 1402.37  5010.8 1403.42  5050.0 1404.15  5085.1 1403.84  5151.9 1406.63
  5220.3 1411.11  5241.1 1413.26  5255.4 1415.56  5269.7 1418.00  5276.3 1420.22
  5304.8 1422.50  5326.9 1423.51  5368.6 1427.68  5380.0 1428.13  5399.6 1429.14
#Mann=7,-1,0
  4685.8    0.07       0  4802.7    0.12       0  4995.4    0.05       0
  4999.4    0.12       0  5010.8   0.035       0  5151.9    0.12       0
  5380.0    0.07       0
Bank Sta=4995.4,4999.4
Exp/Cntr=0.3,0.1

Type RM Length L Ch R = 1,5529,474,474,474
BEGIN DESCRIPTION:
Stream0036_DS 10.0
END DESCRIPTION:
XS GIS Cut Line= 3
      2060225.02     13914025.04      2060075.00     13913725.00
      2059924.97     13913524.96
#Sta/Elev= 30
  4668.4 1424.63  4704.8 1421.73  4721.6 1417.36  4788.6 1408.97  4794.2 1408.87
  4802.6 1407.00  4825.0 1404.12  4878.1 1398.64  4898.1 1397.93  4936.8 1396.99
  4945.2 1394.00  4950.7 1395.61  4959.1 1396.49  4967.5 1395.17  4973.1 1395.74
  4979.5 1393.64  4979.7 1393.14  4983.5 1393.64  4989.9 1396.87  5001.1 1398.34
  5040.3 1399.38  5046.6 1400.24  5067.4 1399.38  5125.7 1403.44  5140.3 1407.05
  5175.7 1410.65  5190.3 1413.08  5203.9 1418.59  5211.1 1420.10  5253.9 1423.22
#Mann=4,-1,0
  4668.4    0.12       0  4898.1    0.07       0  4979.5    0.05       0
  4983.5    0.07       0
Bank Sta=4979.5,4983.5
Exp/Cntr=0.3,0.1

Type RM Length L Ch R = 1,5055,446,446,446
BEGIN DESCRIPTION:
Stream0036_DS 9.0
END DESCRIPTION:
XS GIS Cut Line= 3
      2060545.16     13913841.47      2060425.00     13913475.00
      2060124.98     13913324.99
#Sta/Elev= 30
  4609.8 1423.06  4629.4 1421.96  4679.7 1415.30  4711.3 1412.88  4732.4 1409.02
  4751.4 1407.01  4806.0 1404.46  4827.1 1401.80  4869.2 1399.57  4884.0 1398.21
  4932.3 1391.34  4992.8 1387.98  5009.4 1387.88  5015.8 1383.88  5016.1 1383.38
  5019.8 1383.88  5040.2 1387.81  5070.9 1388.92  5098.9 1388.05  5121.2 1388.41
  5152.0 1390.14  5166.0 1391.78  5182.7 1396.07  5188.3 1396.67  5205.1 1401.69
  5241.4 1406.97  5277.8 1411.08  5294.5 1415.98  5316.9 1420.53  5330.9 1420.77
#Mann=3,-1,0
  4609.8    0.07       0  5015.8    0.05       0  5019.8    0.07       0
Bank Sta=5015.8,5019.8
Exp/Cntr=0.3,0.1

Type RM Length L Ch R = 1,4609,515,515,515
BEGIN DESCRIPTION:
Stream0036_DS 8.0
END DESCRIPTION:
XS GIS Cut Line= 3
      2060874.97     13913424.96      2060725.00     13913225.00
      2060525.01     13912925.01
#Sta/Elev= 30
  4750.4 1405.54  4778.5 1404.27  4793.1 1402.38  4807.6 1397.92  4822.2 1396.62
  4843.1 1394.17  4857.6 1388.07  4863.9 1387.50  4872.2 1384.31  4878.5 1383.39
  4886.8 1380.34  4922.2 1379.54  5003.4 1380.52  5005.9 1377.00  5006.1 1376.50
  5009.9 1377.00  5022.9 1378.75  5036.4 1379.32  5043.9 1381.29  5065.0 1381.01
  5079.2 1381.73  5108.5 1382.90  5150.6 1386.23  5167.1 1388.18  5203.2 1395.69
  5264.9 1403.33  5324.9 1411.42  5353.4 1413.48  5357.9 1415.21  5360.9 1415.21
#Mann=6,-1,0
  4750.4    0.07       0  4822.2    0.12       0  5005.9    0.05       0
  5009.9    0.12       0  5079.2    0.07       0  5264.9    0.12       0
Bank Sta=5005.9,5009.9
Exp/Cntr=0.3,0.1

Type RM Length L Ch R = 1,4094,392,392,392
BEGIN DESCRIPTION:
Stream0036_DS 7.0
END DESCRIPTION:
XS GIS Cut Line= 3
      2061025.00     13913275.04      2060989.59     13912921.30
      2060545.41     13912629.80
#Sta/Elev= 30
  4637.9 1394.57  4690.7 1392.45  4718.3 1387.54  4747.5 1386.31  4808.8 1381.40
  4849.0 1375.25  4912.0 1374.83  4969.6 1373.30  4979.6 1372.56  4985.0 1369.51
  4985.2 1369.01  4989.0 1369.51  5030.5 1374.45  5071.4 1376.51  5139.0 1381.70
  5145.0 1383.34  5154.1 1382.38  5160.1 1384.50  5166.4 1383.37  5202.2 1385.37
  5253.5 1389.95  5268.6 1392.92  5274.6 1392.43  5289.7 1394.59  5319.9 1403.15
  5362.0 1408.53  5404.3 1416.17  5419.3 1419.51  5498.6 1425.09  5524.7 1427.11
#Mann=8,-1,0
  4637.9    0.07       0  4747.5    0.12       0  4912.0   0.035       0
  4985.0   0.035       0  4989.0   0.035       0  5071.4    0.07       0
  5404.3    0.12       0  5498.6    0.07       0
Bank Sta=4985,4989
Exp/Cntr=0.3,0.1

Type RM Length L Ch R = 1,3702,431,431,431
BEGIN DESCRIPTION:
Stream0036_DS 6.0
END DESCRIPTION:
XS GIS Cut Line= 3
      2061090.30     13913792.78      2061275.00     13912825.00
      2061325.03     13912774.97
#Sta/Elev= 30
  4014.5 1402.55  4119.4 1399.19  4124.5 1398.23  4195.5 1397.63  4239.7 1394.11
  4275.7 1394.21  4280.8 1393.17  4338.0 1391.64  4385.1 1392.88  4460.2 1392.82
  4489.3 1391.21  4494.4 1389.89  4521.3 1387.55  4592.5 1385.63  4612.9 1382.89
  4694.3 1379.24  4745.2 1371.04  4878.3 1370.07  4968.6 1368.65  4984.6 1366.97
  4989.6 1366.28  4995.2 1363.49  4995.5 1362.99  4999.2 1363.49  5003.3 1363.49
  5028.0 1373.33  5042.2 1383.41  5056.3 1388.50  5066.9 1391.39  5070.5 1391.39
#Mann=6,-1,0
  4014.5    0.07       0  4239.7    0.12       0  4878.3    0.07       0
  4984.6    0.12       0  4995.2    0.05       0  4999.2    0.12       0
Bank Sta=4995.2,4999.2
Exp/Cntr=0.3,0.1

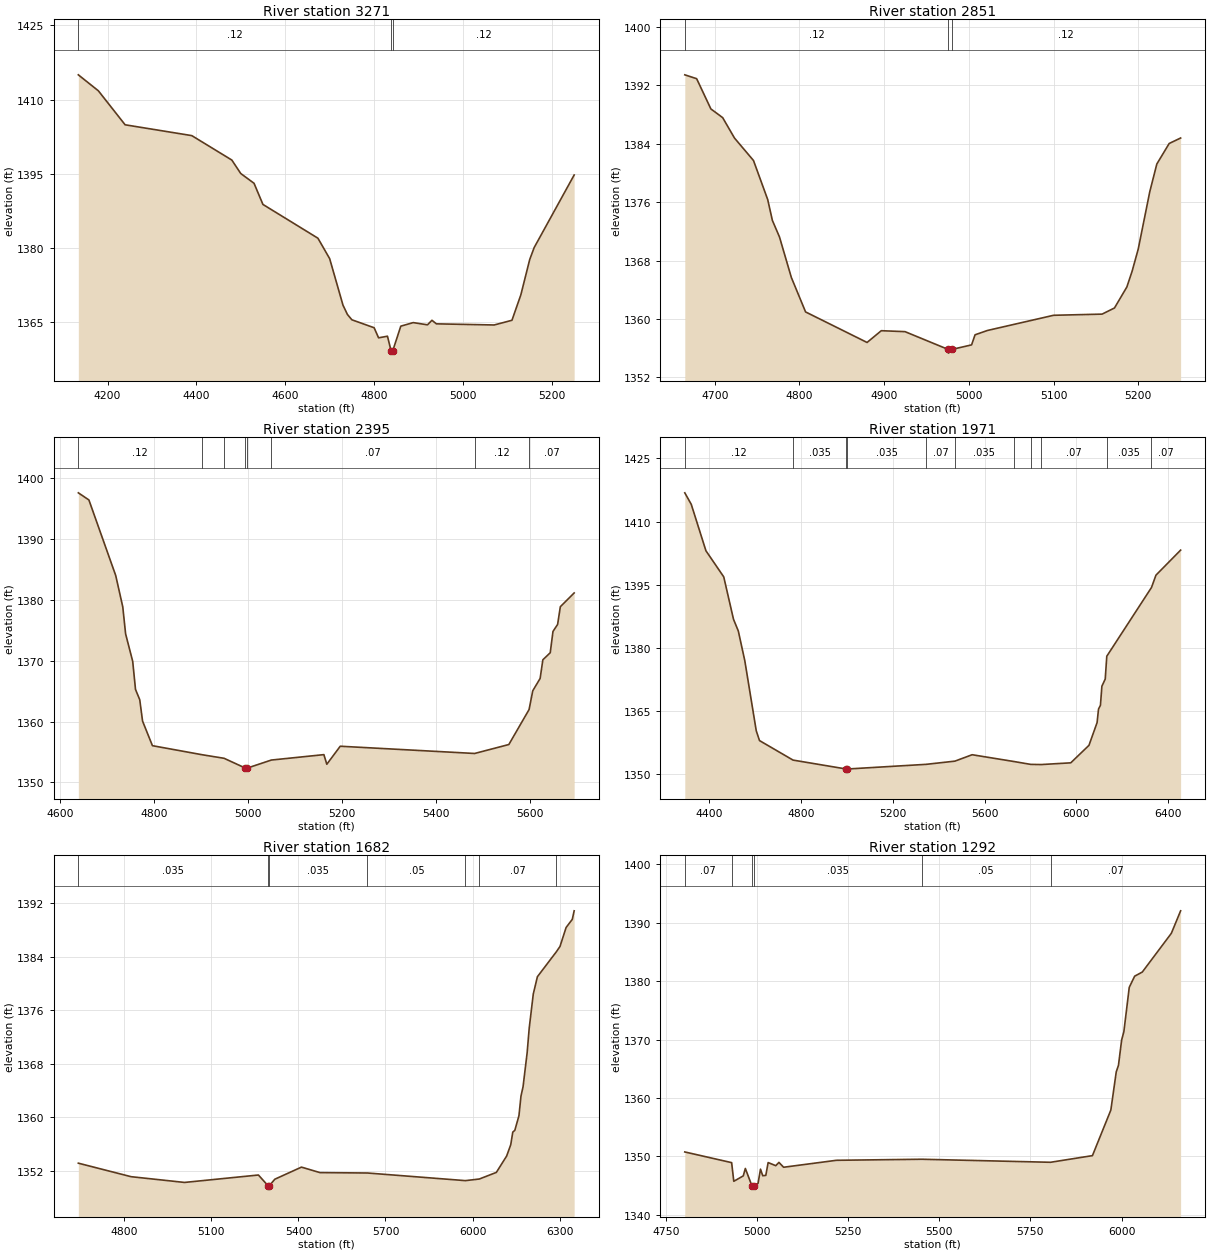
Type RM Length L Ch R = 1,3271,420,420,420
BEGIN DESCRIPTION:
Stream0036_DS 5.0
END DESCRIPTION:
XS GIS Cut Line= 3
      2061614.59     13913890.09      2061575.00     13913025.00
      2061575.00     13912775.00
#Sta/Elev= 30
  4134.1 1415.01  4179.2 1411.78  4239.4 1404.91  4389.5 1402.72  4479.6 1397.78
  4499.6 1395.07  4529.6 1393.08  4549.6 1388.81  4673.4 1381.98  4699.8 1377.85
  4729.8 1368.44  4739.8 1366.56  4749.8 1365.49  4799.9 1363.88  4809.9 1361.84
  4829.9 1362.17  4837.9 1359.25  4838.2 1358.75  4841.9 1359.25  4859.9 1364.20
  4887.9 1364.92  4920.0 1364.47  4930.0 1365.39  4940.0 1364.67  5070.1 1364.44
  5110.1 1365.39  5130.1 1370.53  5150.1 1377.68  5160.1 1380.09  5250.1 1394.76
#Mann=3,-1,0
  4134.1    0.12       0  4837.9    0.05       0  4841.9    0.12       0
Bank Sta=4837.9,4841.9
Exp/Cntr=0.3,0.1

Type RM Length L Ch R = 1,2851,456,456,456
BEGIN DESCRIPTION:
Stream0036_DS 4.0
END DESCRIPTION:
XS GIS Cut Line= 3
      2062075.01     13913325.02      2061925.00     13913025.00
      2061775.02     13912825.03
#Sta/Elev= 30
  4664.6 1393.43  4678.6 1392.90  4695.4 1388.76  4709.3 1387.57  4723.3 1384.77
  4745.7 1381.70  4762.5 1376.35  4768.0 1373.50  4776.4 1371.23  4790.4 1365.69
  4807.2 1360.97  4879.8 1356.79  4896.6 1358.40  4924.6 1358.27  4975.7 1355.83
  4975.9 1355.33  4979.7 1355.83  5003.2 1356.46  5007.3 1357.84  5021.9 1358.43
  5100.0 1360.51  5157.3 1360.67  5171.9 1361.51  5186.5 1364.38  5192.7 1366.53
  5200.0 1369.60  5213.6 1377.44  5221.9 1381.22  5236.5 1384.03  5250.0 1384.78
#Mann=3,-1,0
  4664.6    0.12       0  4975.7    0.05       0  4979.7    0.12       0
Bank Sta=4975.7,4979.7
Exp/Cntr=0.3,0.1

Type RM Length L Ch R = 1,2395,424,424,424
BEGIN DESCRIPTION:
Stream0036_DS 3.0
END DESCRIPTION:
XS GIS Cut Line= 3
      2062125.01     13913374.99      2062325.00     13913075.00
      2061974.98     13912474.97
#Sta/Elev= 30
  4639.5 1397.58  4662.0 1396.41  4719.1 1383.99  4734.1 1378.84  4740.1 1374.41
  4755.2 1369.90  4761.2 1365.28  4770.2 1363.59  4776.2 1360.08  4797.2 1356.04
  4903.2 1354.55  4949.6 1353.97  4995.0 1352.36  4995.3 1351.86  4999.0 1352.36
  5050.3 1353.68  5162.1 1354.57  5168.3 1352.99  5196.9 1355.95  5482.9 1354.76
  5555.7 1356.23  5598.8 1361.98  5606.6 1365.06  5622.3 1367.09  5628.1 1370.15
  5643.8 1371.31  5649.6 1374.80  5659.5 1375.96  5665.3 1378.87  5694.7 1381.13
#Mann=8,-1,0
  4639.5    0.12       0  4903.2    0.07       0  4949.6   0.035       0
  4995.0   0.035       0  4999.0   0.035       0  5050.3    0.07       0
  5482.9    0.12       0  5598.8    0.07       0
Bank Sta=4995,4999
Exp/Cntr=0.3,0.1

Type RM Length L Ch R = 1,1971,289,289,289
BEGIN DESCRIPTION:
Stream0036_DS 2.0
END DESCRIPTION:
XS GIS Cut Line= 3
      2062174.98     13913725.02      2062691.75     13913242.38
      2061824.99     13912074.98
#Sta/Elev= 30
  4292.9 1416.82  4321.0 1414.10  4385.0 1403.07  4462.7 1396.87  4505.2 1386.81
  4526.2 1384.02  4554.5 1376.96  4604.4 1360.33  4618.5 1358.02  4764.6 1353.39
  4996.8 1351.27  4997.1 1350.77  5000.8 1351.27  5344.8 1352.38  5470.2 1353.14
  5545.4 1354.66  5727.5 1353.05  5800.6 1352.37  5846.4 1352.33  5975.2 1352.74
  6054.5 1356.89  6089.9 1362.29  6096.2 1365.51  6104.5 1366.39  6110.8 1370.92
  6125.4 1372.62  6132.2 1378.04  6327.0 1394.35  6346.5 1397.28  6454.0 1403.22
#Mann=11,-1,0
  4292.9    0.12       0  4764.6   0.035       0  4996.8   0.035       0
  5000.8   0.035       0  5344.8    0.07       0  5470.2   0.035       0
  5727.5    0.05       0  5800.6   0.035       0  5846.4    0.07       0
  6132.2   0.035       0  6327.0    0.07       0
Bank Sta=4996.8,5000.8
Exp/Cntr=0.3,0.1

Type RM Length L Ch R = 1,1682,390,390,390
BEGIN DESCRIPTION:
Stream0036_DS 1.3
END DESCRIPTION:
XS GIS Cut Line= 3
      2062927.40     13913456.37      2062901.99     13913098.47
      2061958.74     13912132.11
#Sta/Elev= 30
  4641.2 1353.12  4823.0 1351.10  5007.3 1350.24  5262.0 1351.35  5295.4 1349.74
  5295.7 1349.24  5299.4 1349.74  5318.5 1350.72  5410.4 1352.53  5474.1 1351.71
  5637.9 1351.65  5975.4 1350.51  6023.4 1350.75  6082.2 1351.74  6117.7 1354.19
  6131.8 1355.88  6138.8 1357.76  6145.9 1358.03  6160.1 1360.22  6167.1 1363.15
  6174.2 1364.53  6188.4 1369.65  6195.4 1373.27  6209.5 1378.41  6223.7 1380.99
  6289.4 1384.74  6301.5 1385.51  6322.7 1388.35  6344.0 1389.57  6350.4 1390.84
#Mann=7,-1,0
  4641.2   0.035       0  5295.4   0.035       0  5299.4   0.035       0
  5637.9    0.05       0  5975.4   0.035       0  6023.4    0.07       0
  6289.4   0.035       0
Bank Sta=5295.4,5299.4
Exp/Cntr=0.3,0.1

Type RM Length L Ch R = 1,1292,398,398,398
BEGIN DESCRIPTION:
Stream0036_DS 1.2
END DESCRIPTION:
XS GIS Cut Line= 3
      2063112.32     13912811.31      2062924.79     13912747.79
      2061974.12     13912079.43
#Sta/Elev= 30
  4802.0 1350.73  4930.5 1348.90  4936.4 1345.70  4962.4 1346.63  4968.1 1347.90
  4986.5 1344.86  4986.8 1344.36  4990.5 1344.86  5002.9 1345.34  5009.7 1347.78
  5015.8 1346.66  5024.2 1346.71  5030.6 1348.91  5051.5 1348.38  5060.2 1348.94
  5073.1 1348.11  5217.9 1349.30  5452.3 1349.48  5805.2 1348.96  5920.2 1350.10
  5970.7 1357.91  5985.5 1364.45  5991.6 1365.58  6000.3 1369.92  6006.4 1371.33
  6021.2 1378.94  6036.0 1380.85  6057.0 1381.56  6136.6 1388.19  6162.1 1392.05
#Mann=6,-1,0
  4802.0    0.07       0  4930.5   0.035       0  4986.5   0.035       0
  4990.5   0.035       0  5452.3    0.05       0  5805.2    0.07       0
Bank Sta=4986.5,4990.5
Exp/Cntr=0.3,0.1

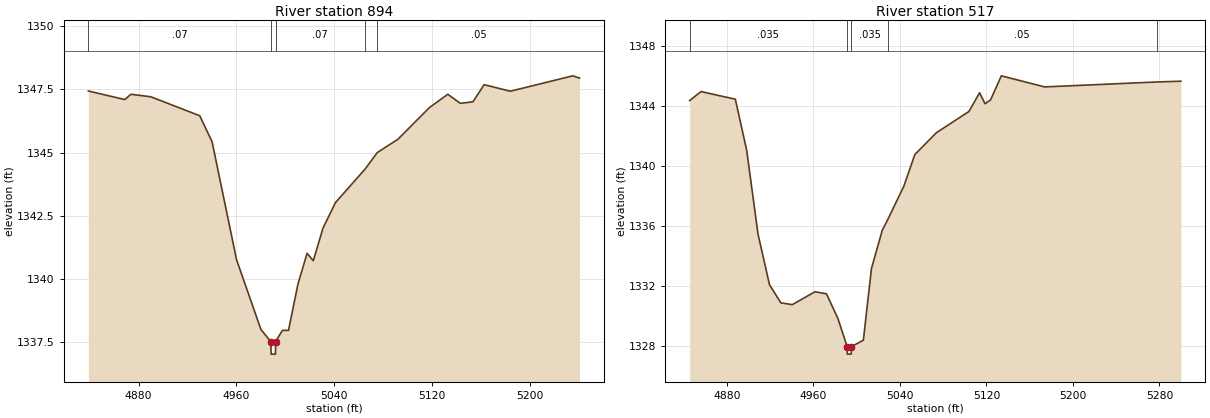
Type RM Length L Ch R = 1,894,377,377,377
BEGIN DESCRIPTION:
Stream0036_DS 1.1
END DESCRIPTION:
XS GIS Cut Line= 3
      2063136.04     13912358.46      2062975.12     13912365.86
      2062739.61     13912415.11
#Sta/Elev= 30
  4838.9 1347.44  4868.7 1347.10  4873.7 1347.31  4890.0 1347.21  4930.0 1346.46
  4940.1 1345.43  4960.1 1340.76  4980.1 1337.99  4988.1 1337.52  4988.4 1337.02
  4991.9 1337.02  4992.1 1337.52  4997.6 1337.96  5002.6 1337.96  5010.3 1339.79
  5017.8 1341.01  5022.9 1340.72  5030.8 1342.01  5041.0 1343.02  5065.1 1344.34
  5075.2 1345.00  5092.1 1345.53  5117.8 1346.78  5132.9 1347.31  5143.1 1346.95
  5153.4 1347.01  5162.6 1347.69  5184.0 1347.43  5235.1 1348.04  5240.6 1347.95
#Mann=5,-1,0
  4838.9    0.07       0  4988.1    0.05       0  4992.1    0.07       0
  5065.1   0.035       0  5075.2    0.05       0
Bank Sta=4988.1,4992.1
Exp/Cntr=0.3,0.1

Type RM Length L Ch R = 1,517,0,0,0
BEGIN DESCRIPTION:
Stream0036_DS 1.0
END DESCRIPTION:
XS GIS Cut Line= 3
      2063024.99     13912075.00      2062875.00     13912025.00
      2062579.19     13912012.12
#Sta/Elev= 30
  4845.6 1344.36  4856.1 1344.96  4887.8 1344.45  4898.3 1341.05  4908.8 1335.45
  4919.4 1332.08  4929.9 1330.87  4940.5 1330.75  4961.5 1331.61  4972.1 1331.47
  4982.6 1329.84  4991.2 1327.95  4991.4 1327.45  4994.9 1327.45  4995.2 1327.95
  5006.2 1328.38  5013.7 1333.16  5023.7 1335.71  5028.8 1336.43  5043.7 1338.66
  5053.8 1340.76  5073.8 1342.22  5103.8 1343.63  5113.7 1344.88  5118.7 1344.15
  5123.8 1344.40  5133.8 1346.01  5173.9 1345.27  5277.4 1345.60  5299.8 1345.65
#Mann=5,-1,0
  4845.6   0.035       0  4991.2   0.035       0  4995.2   0.035       0
  5028.8    0.05       0  5277.4   0.035       0
Bank Sta=4991.2,4995.2
Exp/Cntr=0.3,0.1

Chan Stop Cuts=-1