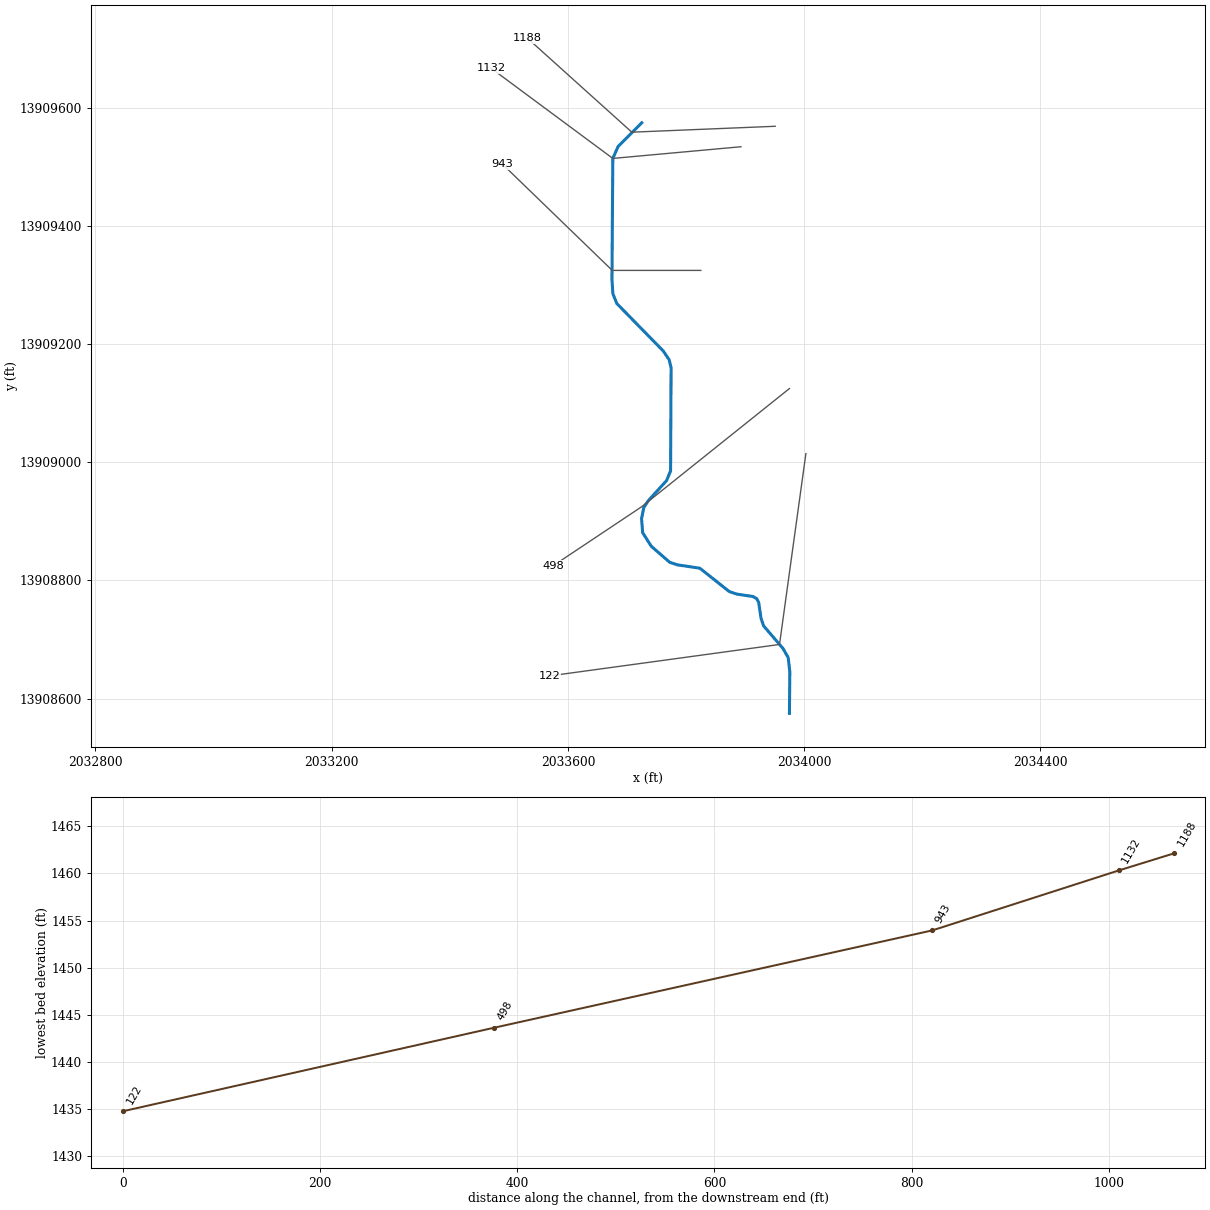
--- Stream0037_DS.prj (project) ---

Proj Title=Stream0037_DS Base Level Engineering
Current Plan=p01
Default Exp/Contr=0.3,0.1
English Units
Geom File=g01
Flow File=f01
Plan File=p01
BEGIN DESCRIPTION:
Stream0037_DS
END DESCRIPTION:

--- Stream0037_DS.p01 (plan) ---

Plan Title=Multiple Run
Short Identifier=Multiple
Geom File=g01
Flow File=f01
Subcritical Flow
K Sum by GR= 0
Std Step Tol= 0.01
Critical Tol= 0.01
Num of Std Step Trials= 20
Max Error Tol= 0.3
Flow Tol Ratio= 0.001
Split Flow NTrial= 30
Split Flow Tol= 0.02
Split Flow Ratio= 0.02
Log Output Level= 0
Friction Slope Method= 1
Unsteady Friction Slope Method= 2
Unsteady Bridges Friction Slope Method= 1
Parabolic Critical Depth
Global Vel Dist=  1 , 1 , 1
Global Log Level= 0
CheckData=True
Encroach Param= -1, 0, 0, 0
BEGIN DESCRIPTION:
Multiple Run
END DESCRIPTION:

--- Stream0037_DS.f01 (steady flow) ---

Flow Title=Multiple
Number of Profiles=7
Profile Names=10-year,25-year,50-year,1pct_min,100-year,1pct_plu,500-year
River Rch & RM= Stream0037_DS,Reach-1,1188
     459     744    1004     661    1319    2631    2240
Boundary for River Rch & Prof#=Stream0037_DS,Reach-1,1
Up Type=0
Dn Type=3
Dn Slope=0.005
Boundary for River Rch & Prof#=Stream0037_DS,Reach-1,2
Up Type=0
Dn Type=3
Dn Slope=0.005
Boundary for River Rch & Prof#=Stream0037_DS,Reach-1,3
Up Type=0
Dn Type=3
Dn Slope=0.005
Boundary for River Rch & Prof#=Stream0037_DS,Reach-1,4
Up Type=0
Dn Type=3
Dn Slope=0.005
Boundary for River Rch & Prof#=Stream0037_DS,Reach-1,5
Up Type=0
Dn Type=3
Dn Slope=0.005
Boundary for River Rch & Prof#=Stream0037_DS,Reach-1,6
Up Type=0
Dn Type=3
Dn Slope=0.005
Boundary for River Rch & Prof#=Stream0037_DS,Reach-1,7
Up Type=0
Dn Type=3
Dn Slope=0.005

--- Stream0037_DS.g01 (geometry) ---

Geom Title=Existing Conditions

River Reach=Stream0037_DS,Reach-1
Reach XY= 30
      2033725.00     13909575.00      2033685.05     13909534.98
      2033675.96     13909514.60      2033674.51     13909309.80
      2033676.06     13909285.44      2033682.83     13909268.81
      2033761.60     13909188.31      2033771.45     13909173.53
      2033774.61     13909159.84      2033773.76     13908985.50
      2033766.81     13908968.92      2033735.54     13908934.51
      2033728.33     13908923.22      2033724.61     13908904.72
      2033726.54     13908880.85      2033741.06     13908857.94
      2033772.38     13908830.73      2033785.44     13908826.44
      2033823.26     13908820.81      2033873.15     13908781.24
      2033886.09     13908776.86      2033913.01     13908772.93
      2033919.42     13908769.42      2033922.94     13908763.01
      2033926.87     13908736.10      2033931.25     13908723.16
      2033964.23     13908684.73      2033972.94     13908669.17
      2033975.65     13908645.28      2033975.00     13908575.00

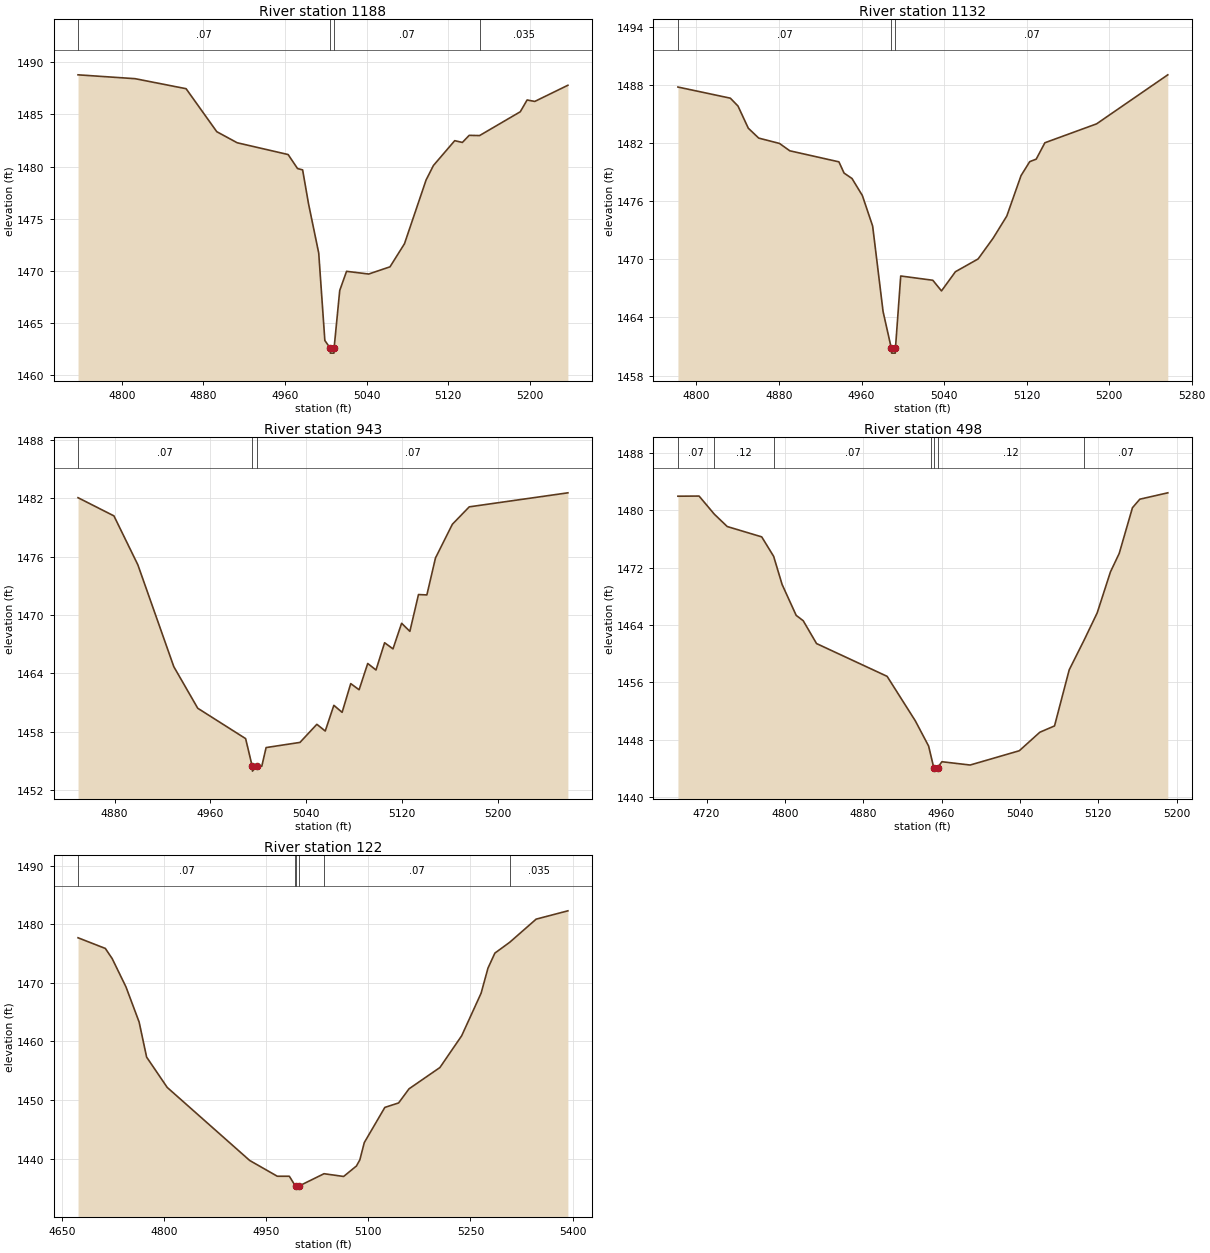
Type RM Length L Ch R = 1,1188,56,56,56
BEGIN DESCRIPTION:
Stream0037_DS 4.0
END DESCRIPTION:
XS GIS Cut Line= 3
      2033950.95     13909569.03      2033708.15     13909559.03
      2033531.64     13909717.93
#Sta/Elev= 30
  4757.0 1488.79  4813.0 1488.42  4863.0 1487.46  4893.1 1483.34  4913.1 1482.28
  4963.1 1481.15  4972.3 1479.81  4977.3 1479.68  4983.1 1476.43  4993.1 1471.71
  4999.1 1463.33  5004.2 1462.62  5004.5 1462.12  5008.0 1462.12  5008.2 1462.62
  5013.7 1468.12  5020.4 1469.96  5042.1 1469.70  5063.0 1470.39  5077.2 1472.60
  5098.4 1478.71  5105.6 1480.10  5126.5 1482.48  5134.0 1482.31  5140.7 1482.99
  5150.9 1482.97  5190.8 1485.25  5197.5 1486.38  5205.0 1486.24  5237.5 1487.79
#Mann=4,-1,0
  4757.0    0.07       0  5004.2    0.05       0  5008.2    0.07       0
  5150.9   0.035       0
Bank Sta=5004.2,5008.2
Exp/Cntr=0.3,0.1

Type RM Length L Ch R = 1,1132,189,189,189
BEGIN DESCRIPTION:
Stream0037_DS 3.0
END DESCRIPTION:
XS GIS Cut Line= 3
      2033892.96     13909534.39      2033675.96     13909514.60
      2033469.63     13909667.48
#Sta/Elev= 30
  4782.1 1487.77  4832.9 1486.62  4840.3 1485.81  4850.3 1483.52  4860.4 1482.50
  4880.5 1481.95  4890.5 1481.19  4938.1 1480.05  4943.1 1478.89  4950.8 1478.33
  4960.8 1476.58  4970.8 1473.42  4980.9 1464.60  4988.9 1460.81  4989.2 1460.31
  4992.7 1460.31  4992.9 1460.81  4998.0 1468.27  5029.1 1467.83  5037.5 1466.73
  5051.0 1468.71  5073.0 1470.03  5087.6 1472.18  5100.8 1474.46  5114.6 1478.63
  5123.0 1480.07  5129.3 1480.33  5137.7 1482.02  5187.8 1483.97  5256.8 1489.03
#Mann=3,-1,0
  4782.1    0.07       0  4988.9    0.05       0  4992.9    0.07       0
Bank Sta=4988.9,4992.9
Exp/Cntr=0.3,0.1

Type RM Length L Ch R = 1,943,445,445,445
BEGIN DESCRIPTION:
Stream0037_DS 2.0
END DESCRIPTION:
XS GIS Cut Line= 3
      2033825.00     13909325.00      2033675.00     13909325.00
      2033488.72     13909505.24
#Sta/Elev= 30
  4849.4 1482.05  4879.4 1480.18  4899.4 1475.15  4929.4 1464.69  4949.4 1460.42
  4989.4 1457.30  4994.9 1454.46  4995.1 1453.96  4998.9 1454.46  5002.9 1454.46
  5006.5 1456.38  5034.8 1456.91  5048.9 1458.77  5055.9 1458.08  5063.1 1460.72
  5070.0 1460.00  5077.2 1462.95  5084.2 1462.32  5091.4 1465.02  5098.3 1464.35
  5105.5 1467.15  5112.5 1466.52  5119.7 1469.15  5126.6 1468.32  5133.8 1472.10
  5140.8 1472.06  5148.0 1475.86  5162.1 1479.32  5176.2 1481.11  5258.6 1482.55
#Mann=3,-1,0
  4849.4    0.07       0  4994.9    0.05       0  4998.9    0.07       0
Bank Sta=4994.9,4998.9
Exp/Cntr=0.3,0.1

Type RM Length L Ch R = 1,498,376,376,376
BEGIN DESCRIPTION:
Stream0037_DS 1.0
END DESCRIPTION:
XS GIS Cut Line= 3
      2033974.97     13909124.97      2033725.00     13908925.00
      2033574.99     13908824.99
#Sta/Elev= 30
  4690.7 1481.95  4712.3 1481.97  4727.9 1479.44  4741.1 1477.72  4776.3 1476.28
  4788.5 1473.56  4797.1 1469.65  4811.5 1465.34  4818.7 1464.59  4832.3 1461.41
  4904.4 1456.84  4933.2 1450.64  4946.8 1447.12  4949.2 1445.74  4952.0 1444.13
  4952.2 1443.63  4956.0 1444.13  4960.4 1444.94  4989.2 1444.48  5039.4 1446.47
  5060.4 1449.05  5075.4 1449.93  5090.4 1457.75  5105.3 1461.80  5119.0 1465.69
  5132.5 1471.39  5141.5 1473.98  5155.0 1480.34  5162.5 1481.53  5191.1 1482.42
#Mann=7,-1,0
  4690.7    0.07       0  4727.9    0.12       0  4788.5    0.07       0
  4949.2    0.12       0  4952.0    0.05       0  4956.0    0.12       0
  5105.3    0.07       0
Bank Sta=4952,4956
Exp/Cntr=0.3,0.1

Type RM Length L Ch R = 1,122,0,0,0
BEGIN DESCRIPTION:
Stream0037_DS 0.0
END DESCRIPTION:
XS GIS Cut Line= 3
      2034002.84     13909014.71      2033958.19     13908691.68
      2033568.82     13908638.43
#Sta/Elev= 30
  4673.9 1477.69  4714.0 1475.87  4724.1 1474.12  4744.3 1469.30  4763.6 1463.30
  4774.6 1457.32  4804.8 1452.15  4926.0 1439.67  4966.4 1436.99  4984.1 1436.99
  4992.6 1435.39  4993.8 1435.29  4994.0 1434.79  4997.8 1435.29  5035.0 1437.42
  5063.8 1436.95  5082.6 1438.74  5087.6 1439.79  5094.1 1442.73  5124.3 1448.74
  5144.5 1449.50  5159.8 1451.91  5205.1 1455.54  5237.1 1460.97  5265.6 1468.23
  5275.7 1472.51  5285.8 1475.07  5307.7 1476.93  5346.4 1480.87  5393.0 1482.29
#Mann=6,-1,0
  4673.9    0.07       0  4992.6    0.12       0  4993.8    0.05       0
  4997.8    0.12       0  5035.0    0.07       0  5307.7   0.035       0
Bank Sta=4993.8,4997.8
Exp/Cntr=0.3,0.1

Chan Stop Cuts=-1