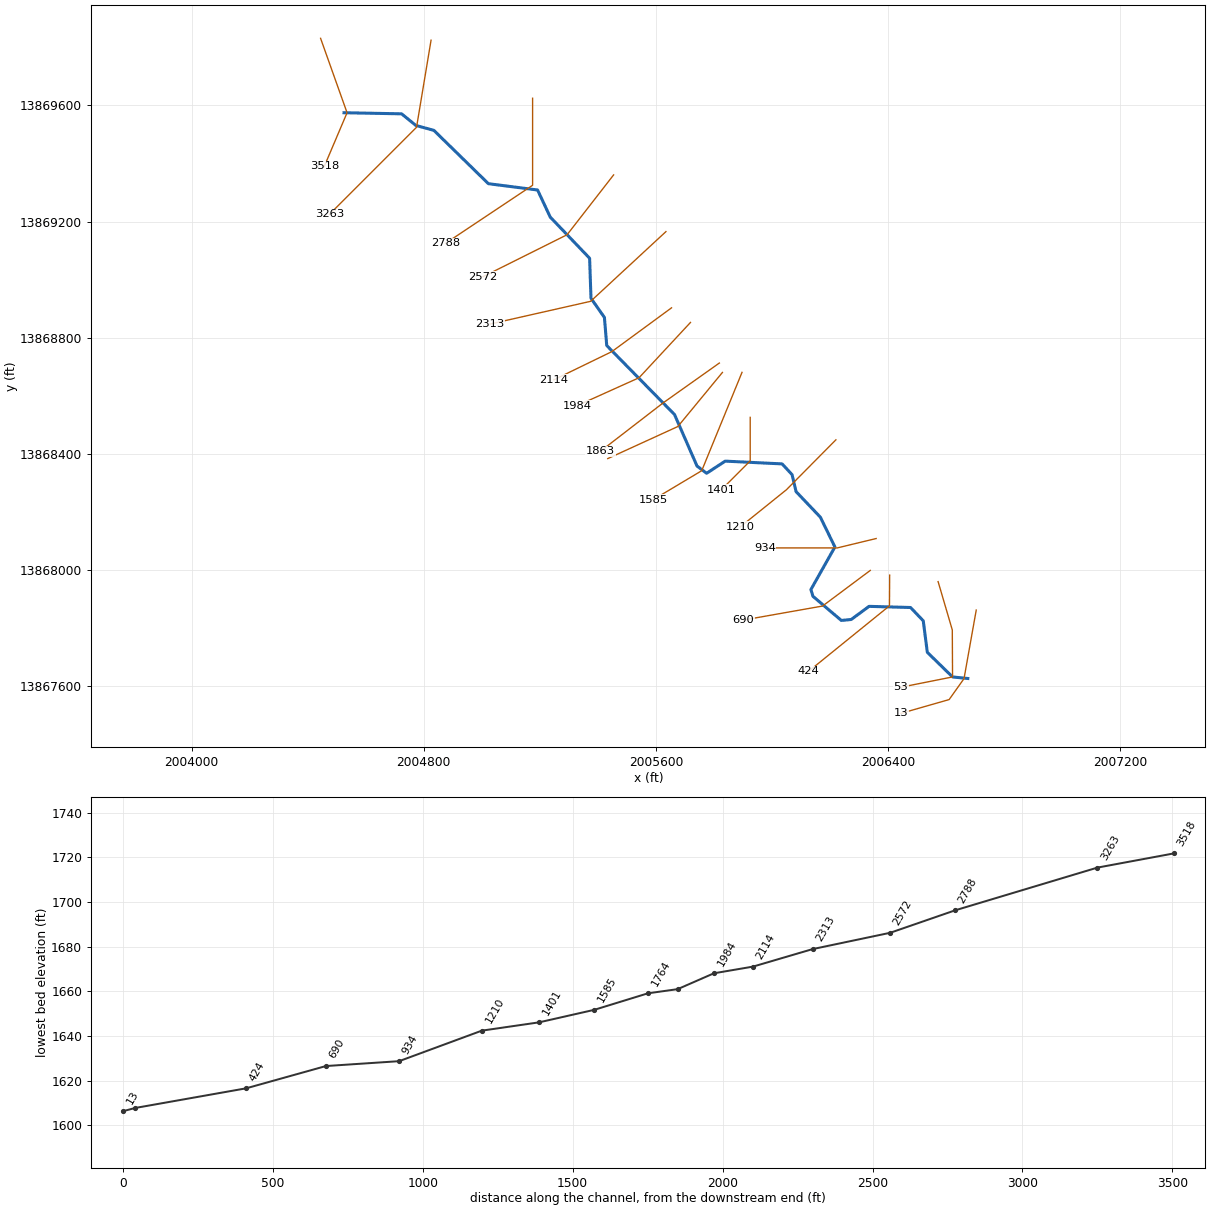
--- Stream0038_DS.prj (project) ---

Proj Title=Stream0038_DS Base Level Engineering
Current Plan=p01
Default Exp/Contr=0.3,0.1
English Units
Geom File=g01
Flow File=f01
Plan File=p01
BEGIN DESCRIPTION:
Stream0038_DS
END DESCRIPTION:

--- Stream0038_DS.p01 (plan) ---

Plan Title=Multiple Run
Short Identifier=Multiple
Geom File=g01
Flow File=f01
Subcritical Flow
K Sum by GR= 0
Std Step Tol= 0.01
Critical Tol= 0.01
Num of Std Step Trials= 20
Max Error Tol= 0.3
Flow Tol Ratio= 0.001
Split Flow NTrial= 30
Split Flow Tol= 0.02
Split Flow Ratio= 0.02
Log Output Level= 0
Friction Slope Method= 1
Unsteady Friction Slope Method= 2
Unsteady Bridges Friction Slope Method= 1
Parabolic Critical Depth
Global Vel Dist=  1 , 1 , 1
Global Log Level= 0
CheckData=True
Encroach Param= -1, 0, 0, 0
BEGIN DESCRIPTION:
Multiple Run
END DESCRIPTION:

--- Stream0038_DS.f01 (steady flow) ---

Flow Title=Multiple
Number of Profiles=7
Profile Names=10-year,25-year,50-year,1pct_min,100-year,1pct_plu,500-year
River Rch & RM= Stream0038_DS,Reach-1,3518
     374     598     801     523    1044    2083    1748
River Rch & RM= Stream0038_DS,Reach-1,2788
     518     846    1148     759    1514    3021    2597
River Rch & RM= Stream0038_DS,Reach-1,53
    4022    7225   10439    7272   14509   28950   27773
River Rch & RM= Stream0038_DS,Reach-1,13
    4122    7411   10713    7466   14898   29724   28544
Boundary for River Rch & Prof#=Stream0038_DS,Reach-1,1
Up Type=0
Dn Type=3
Dn Slope=0.005
Boundary for River Rch & Prof#=Stream0038_DS,Reach-1,2
Up Type=0
Dn Type=3
Dn Slope=0.005
Boundary for River Rch & Prof#=Stream0038_DS,Reach-1,3
Up Type=0
Dn Type=3
Dn Slope=0.005
Boundary for River Rch & Prof#=Stream0038_DS,Reach-1,4
Up Type=0
Dn Type=3
Dn Slope=0.005
Boundary for River Rch & Prof#=Stream0038_DS,Reach-1,5
Up Type=0
Dn Type=3
Dn Slope=0.005
Boundary for River Rch & Prof#=Stream0038_DS,Reach-1,6
Up Type=0
Dn Type=3
Dn Slope=0.005
Boundary for River Rch & Prof#=Stream0038_DS,Reach-1,7
Up Type=0
Dn Type=3
Dn Slope=0.005

--- Stream0038_DS.g01 (geometry) ---

Geom Title=Existing Conditions

River Reach=Stream0038_DS,Reach-1
Reach XY= 30
      2004525.00     13869575.00      2004723.45     13869571.26
      2004772.83     13869531.14      2004834.68     13869514.24
      2005022.55     13869330.47      2005192.14     13869308.72
      2005235.79     13869215.34      2005371.46     13869073.53
      2005376.23     13868935.51      2005422.53     13868869.43
      2005430.52     13868772.57      2005664.24     13868534.68
      2005741.63     13868357.43      2005774.68     13868332.23
      2005838.85     13868374.17      2006035.12     13868364.66
      2006069.26     13868327.58      2006083.19     13868268.98
      2006166.86     13868181.04      2006216.98     13868078.31
      2006134.24     13867931.54      2006141.27     13867908.26
      2006239.03     13867825.10      2006273.25     13867828.34
      2006334.66     13867873.61      2006477.73     13867869.66
      2006521.49     13867823.75      2006535.50     13867715.19
      2006622.46     13867630.30      2006675.00     13867625.00

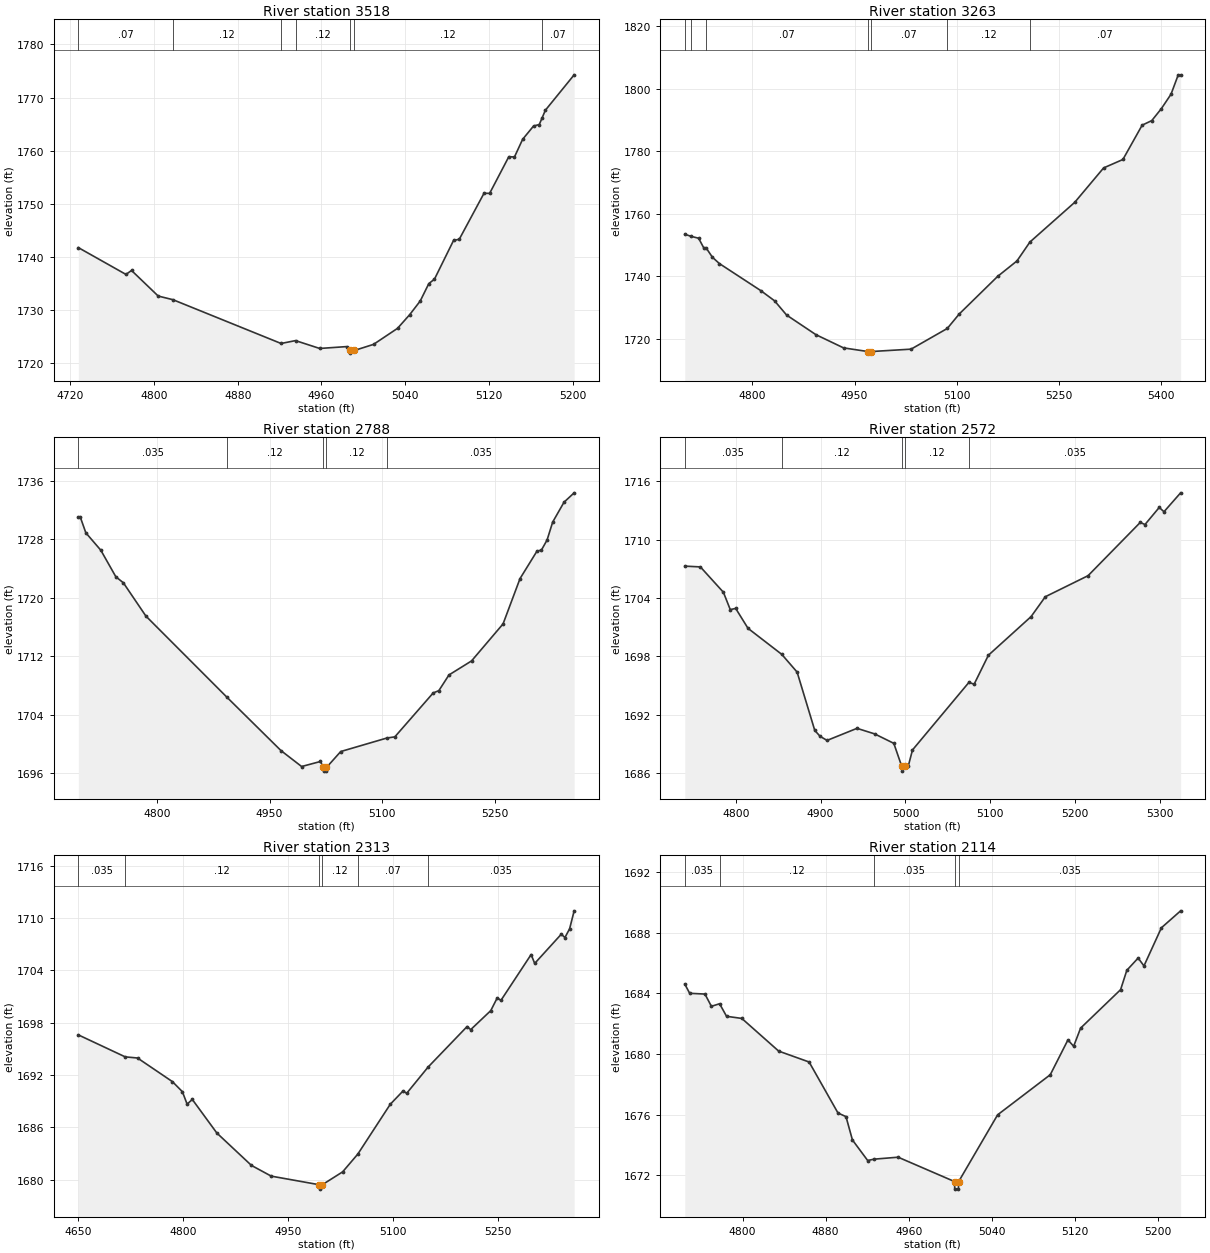
Type RM Length L Ch R = 1,3518,255,255,255
BEGIN DESCRIPTION:
Stream0038_DS 16.0
END DESCRIPTION:
XS GIS Cut Line= 3
      2004444.25     13869831.46      2004535.48     13869575.01
      2004456.79     13869389.72
#Sta/Elev= 30
  4727.8 1741.70  4773.3 1736.64  4778.6 1737.39  4804.1 1732.56  4818.1 1731.88
  4921.4 1723.62  4935.2 1724.16  4958.3 1722.68  4983.9 1723.03  4987.4 1722.30
  4987.6 1721.80  4991.4 1722.30  5009.7 1723.45  5032.6 1726.47  5044.2 1729.04
  5054.3 1731.63  5062.5 1734.91  5067.9 1735.75  5086.1 1743.04  5091.6 1743.28
  5115.2 1751.94  5120.6 1751.93  5138.9 1758.84  5144.3 1758.79  5152.1 1762.12
  5162.5 1764.62  5168.0 1764.91  5170.7 1766.16  5173.8 1767.60  5201.3 1774.28
#Mann=7,-1,0
  4727.8    0.07       0  4818.1    0.12       0  4921.4    0.07       0
  4935.2    0.12       0  4987.4    0.05       0  4991.4    0.12       0
  5170.7    0.07       0
Bank Sta=4987.4,4991.4
Exp/Cntr=0.3,0.1

Type RM Length L Ch R = 1,3263,475,475,475
BEGIN DESCRIPTION:
Stream0038_DS 15.0
END DESCRIPTION:
XS GIS Cut Line= 3
      2004825.00     13869825.02      2004775.00     13869525.00
      2004475.02     13869225.02
#Sta/Elev= 30
  4700.6 1753.47  4710.3 1752.78  4720.9 1752.20  4728.5 1749.09  4731.8 1749.14
  4741.2 1746.11  4751.3 1744.11  4812.1 1735.46  4832.4 1732.19  4850.2 1727.61
  4893.2 1721.35  4933.8 1717.12  4969.8 1715.94  4970.1 1715.44  4973.8 1715.94
  5033.0 1716.71  5086.2 1723.33  5103.8 1727.97  5160.3 1740.01  5188.6 1744.94
  5207.6 1750.98  5273.5 1763.70  5315.9 1774.70  5344.2 1777.39  5372.5 1788.38
  5386.6 1789.83  5400.7 1793.66  5414.9 1798.28  5425.5 1804.48  5429.0 1804.48
#Mann=7,-1,0
  4700.6    0.07       0  4710.3   0.035       0  4731.8    0.07       0
  4969.8    0.05       0  4973.8    0.07       0  5086.2    0.12       0
  5207.6    0.07       0
Bank Sta=4969.8,4973.8
Exp/Cntr=0.3,0.1

Type RM Length L Ch R = 1,2788,216,216,216
BEGIN DESCRIPTION:
Stream0038_DS 14.0
END DESCRIPTION:
XS GIS Cut Line= 3
      2005175.00     13869625.04      2005175.00     13869325.00
      2004874.99     13869125.00
#Sta/Elev= 30
  4695.3 1731.07  4697.8 1731.07  4705.3 1728.89  4725.3 1726.50  4745.3 1722.87
  4755.3 1722.05  4785.3 1717.50  4893.4 1706.38  4965.3 1699.09  4992.8 1696.91
  5017.9 1697.60  5021.9 1696.78  5022.1 1696.28  5025.6 1696.28  5025.9 1696.78
  5044.9 1698.96  5106.4 1700.81  5117.0 1700.97  5168.1 1706.98  5175.6 1707.29
  5189.1 1709.44  5219.2 1711.36  5261.2 1716.43  5283.8 1722.63  5306.3 1726.37
  5312.3 1726.53  5319.8 1727.90  5327.3 1730.36  5342.4 1733.08  5355.9 1734.36
#Mann=5,-1,0
  4695.3   0.035       0  4893.4    0.12       0  5021.9    0.05       0
  5025.9    0.12       0  5106.4   0.035       0
Bank Sta=5021.9,5025.9
Exp/Cntr=0.3,0.1

Type RM Length L Ch R = 1,2572,259,259,259
BEGIN DESCRIPTION:
Stream0038_DS 13.0
END DESCRIPTION:
XS GIS Cut Line= 3
      2005454.19     13869360.73      2005293.91     13869154.53
      2005004.60     13869010.14
#Sta/Elev= 30
  4739.9 1707.27  4758.3 1707.19  4785.4 1704.59  4793.5 1702.81  4799.9 1702.93
  4814.4 1700.89  4854.2 1698.22  4872.3 1696.40  4893.1 1690.42  4899.4 1689.81
  4907.6 1689.39  4942.9 1690.63  4963.7 1690.06  4986.3 1689.09  4995.6 1686.74
  4995.9 1686.24  4999.6 1686.74  5003.3 1686.74  5008.3 1688.41  5074.8 1695.34
  5081.0 1695.16  5097.8 1698.13  5148.1 1702.09  5164.9 1704.13  5215.3 1706.29
  5276.8 1711.75  5282.4 1711.54  5299.2 1713.29  5304.8 1712.85  5324.4 1714.79
#Mann=5,-1,0
  4739.9   0.035       0  4854.2    0.12       0  4995.6    0.05       0
  4999.6    0.12       0  5074.8   0.035       0
Bank Sta=4995.6,4999.6
Exp/Cntr=0.3,0.1

Type RM Length L Ch R = 1,2313,199,199,199
BEGIN DESCRIPTION:
Stream0038_DS 12.0
END DESCRIPTION:
XS GIS Cut Line= 3
      2005634.54     13869165.24      2005375.00     13868925.00
      2005028.70     13868846.72
#Sta/Elev= 30
  4650.8 1696.60  4717.8 1694.08  4735.4 1693.95  4785.3 1691.24  4799.5 1690.09
  4806.3 1688.66  4813.7 1689.20  4848.8 1685.35  4898.2 1681.64  4926.5 1680.41
  4995.4 1679.42  4995.6 1678.92  4999.4 1679.42  5028.6 1680.90  5050.3 1682.94
  5096.7 1688.65  5115.0 1690.18  5120.1 1689.90  5150.6 1692.90  5206.5 1697.56
  5211.6 1697.20  5240.3 1699.38  5249.6 1700.85  5254.8 1700.55  5298.0 1705.81
  5303.1 1704.79  5341.1 1708.14  5346.3 1707.76  5353.0 1708.76  5359.5 1710.82
#Mann=6,-1,0
  4650.8   0.035       0  4717.8    0.12       0  4995.4    0.05       0
  4999.4    0.12       0  5050.3    0.07       0  5150.6   0.035       0
Bank Sta=4995.4,4999.4
Exp/Cntr=0.3,0.1

Type RM Length L Ch R = 1,2114,130,130,130
BEGIN DESCRIPTION:
Stream0038_DS 11.0
END DESCRIPTION:
XS GIS Cut Line= 3
      2005653.96     13868902.68      2005447.88     13868751.48
      2005248.40     13868654.50
#Sta/Elev= 30
  4744.4 1684.62  4749.1 1684.01  4763.8 1683.96  4770.0 1683.15  4777.9 1683.32
  4784.6 1682.49  4799.3 1682.35  4834.8 1680.19  4864.1 1679.47  4891.9 1676.10
  4899.6 1675.86  4905.8 1674.32  4920.5 1672.96  4926.6 1673.05  4949.8 1673.18
  5004.1 1671.57  5004.3 1671.07  5007.8 1671.07  5008.1 1671.57  5045.6 1675.98
  5096.3 1678.63  5113.3 1680.93  5118.8 1680.51  5125.5 1681.71  5164.0 1684.25
  5170.0 1685.53  5180.9 1686.34  5186.5 1685.82  5203.3 1688.34  5221.8 1689.46
#Mann=5,-1,0
  4744.4   0.035       0  4777.9    0.12       0  4926.6   0.035       0
  5004.1   0.035       0  5008.1   0.035       0
Bank Sta=5004.1,5008.1
Exp/Cntr=0.3,0.1

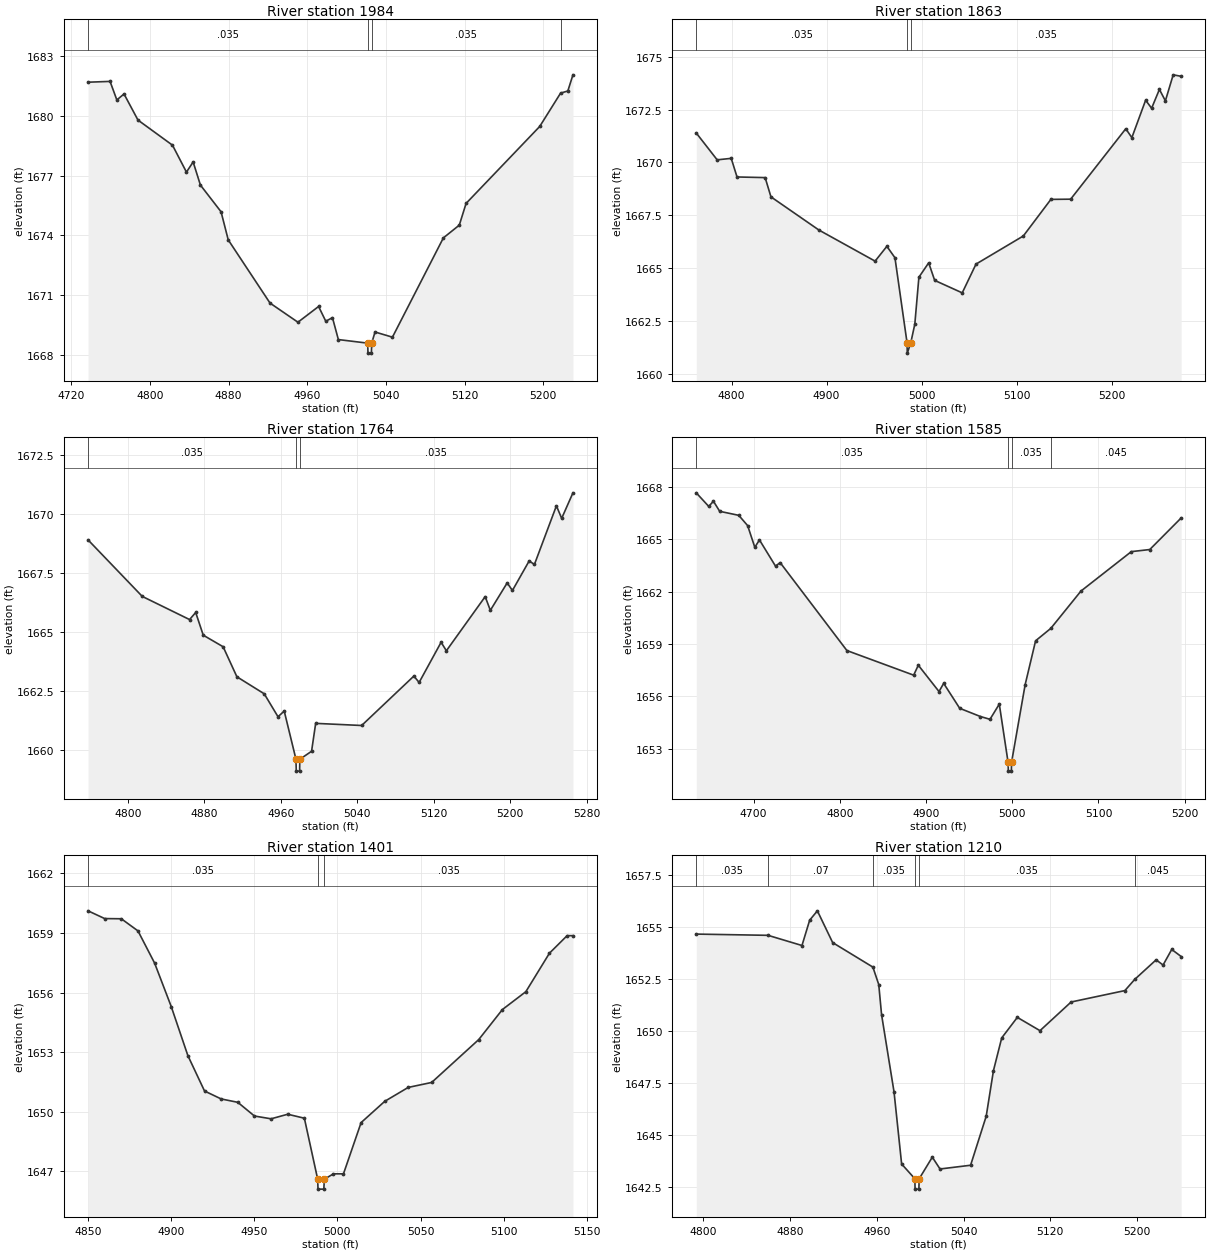
Type RM Length L Ch R = 1,1984,121,121,121
BEGIN DESCRIPTION:
Stream0038_DS 10.0
END DESCRIPTION:
XS GIS Cut Line= 3
      2005719.17     13868852.25      2005541.93     13868661.61
      2005329.61     13868565.91
#Sta/Elev= 30
  4737.0 1681.68  4759.4 1681.72  4766.3 1680.79  4773.6 1681.09  4787.8 1679.78
  4822.9 1678.52  4837.1 1677.17  4843.9 1677.68  4851.3 1676.52  4872.3 1675.18
  4879.6 1673.77  4922.1 1670.60  4950.5 1669.64  4971.5 1670.43  4978.8 1669.69
  4985.6 1669.87  4991.6 1668.77  5021.5 1668.59  5021.7 1668.09  5025.2 1668.09
  5025.5 1668.59  5028.9 1669.15  5046.6 1668.89  5098.4 1673.87  5114.6 1674.51
  5121.5 1675.60  5196.4 1679.46  5217.6 1681.13  5225.0 1681.24  5230.2 1682.05
#Mann=4,-1,0
  4737.0   0.035       0  5021.5   0.035       0  5025.5   0.035       0
  5217.6    0.07       0
Bank Sta=5021.5,5025.5
Exp/Cntr=0.3,0.1

Type RM Length L Ch R = 1,1863,99,99,99
BEGIN DESCRIPTION:
Stream0038_DS 9.0
END DESCRIPTION:
XS GIS Cut Line= 3
      2005818.62     13868712.28      2005625.00     13868575.00
      2005408.91     13868408.23
#Sta/Elev= 30
  4762.9 1671.39  4784.9 1670.12  4799.7 1670.19  4805.8 1669.31  4835.4 1669.28
  4841.5 1668.37  4892.0 1666.80  4951.1 1665.33  4963.5 1666.03  4972.0 1665.49
  4984.7 1661.48  4985.0 1660.98  4988.7 1661.48  4992.9 1662.35  4997.2 1664.57
  5007.5 1665.25  5013.8 1664.42  5042.8 1663.83  5057.3 1665.19  5107.1 1666.52
  5136.1 1668.25  5156.9 1668.26  5214.9 1671.59  5221.3 1671.17  5235.8 1672.94
  5242.1 1672.56  5250.3 1673.45  5256.6 1672.91  5264.8 1674.14  5273.2 1674.07
#Mann=3,-1,0
  4762.9   0.035       0  4984.7   0.035       0  4988.7   0.035       0
Bank Sta=4984.7,4988.7
Exp/Cntr=0.3,0.1

Type RM Length L Ch R = 1,1764,179,179,179
BEGIN DESCRIPTION:
Stream0038_DS 8.0
END DESCRIPTION:
XS GIS Cut Line= 3
      2005829.20     13868679.86      2005675.66     13868493.45
      2005434.06     13868382.89
#Sta/Elev= 30
  4758.5 1668.90  4815.2 1666.51  4864.7 1665.53  4871.1 1665.83  4879.0 1664.87
  4899.8 1664.38  4914.2 1663.11  4942.8 1662.39  4957.2 1661.42  4963.7 1661.66
  4976.0 1659.62  4976.3 1659.12  4979.8 1659.12  4980.0 1659.62  4992.3 1659.96
  4996.6 1661.14  5044.7 1661.05  5099.3 1663.14  5104.8 1662.87  5127.8 1664.57
  5133.3 1664.21  5173.9 1666.50  5179.3 1665.92  5196.9 1667.08  5202.4 1666.76
  5219.9 1668.01  5225.4 1667.86  5248.4 1670.34  5253.9 1669.81  5265.7 1670.89
#Mann=3,-1,0
  4758.5   0.035       0  4976.0   0.035       0  4980.0   0.035       0
Bank Sta=4976,4980
Exp/Cntr=0.3,0.1

Type RM Length L Ch R = 1,1585,184,184,184
BEGIN DESCRIPTION:
Stream0038_DS 7.0
END DESCRIPTION:
XS GIS Cut Line= 3
      2005896.81     13868680.19      2005757.91     13868341.14
      2005589.69     13868240.74
#Sta/Elev= 30
  4633.6 1667.67  4648.1 1666.89  4653.5 1667.19  4660.8 1666.61  4682.9 1666.38
  4693.2 1665.79  4701.5 1664.55  4706.9 1664.97  4725.5 1663.47  4730.9 1663.67
  4808.3 1658.63  4885.7 1657.22  4891.1 1657.79  4915.1 1656.28  4920.5 1656.75
  4939.1 1655.32  4963.1 1654.85  4974.2 1654.69  4985.0 1655.56  4995.2 1652.22
  4995.5 1651.72  4999.0 1651.72  4999.2 1652.22  5015.0 1656.68  5027.1 1659.19
  5044.7 1659.90  5079.7 1662.04  5138.1 1664.30  5159.5 1664.42  5195.9 1666.23
#Mann=4,-1,0
  4633.6   0.035       0  4995.2   0.035       0  4999.2   0.035       0
  5044.7   0.045       0
Bank Sta=4995.2,4999.2
Exp/Cntr=0.3,0.1

Type RM Length L Ch R = 1,1401,191,191,191
BEGIN DESCRIPTION:
Stream0038_DS 6.0
END DESCRIPTION:
XS GIS Cut Line= 3
      2005925.00     13868524.97      2005925.00     13868375.00
      2005825.00     13868275.00
#Sta/Elev= 30
  4850.2 1660.12  4860.2 1659.73  4870.2 1659.72  4880.2 1659.11  4890.2 1657.49
  4900.2 1655.30  4910.2 1652.83  4920.2 1651.05  4930.2 1650.65  4940.2 1650.48
  4950.2 1649.79  4960.2 1649.65  4970.2 1649.88  4980.2 1649.68  4988.2 1646.61
  4988.4 1646.11  4991.9 1646.11  4992.2 1646.61  4997.7 1646.88  5003.7 1646.88
  5014.3 1649.46  5028.5 1650.53  5042.6 1651.23  5056.7 1651.48  5085.0 1653.64
  5099.2 1655.15  5113.3 1656.05  5127.5 1657.99  5138.1 1658.87  5141.6 1658.87
#Mann=3,-1,0
  4850.2   0.035       0  4988.2   0.035       0  4992.2   0.035       0
Bank Sta=4988.2,4992.2
Exp/Cntr=0.3,0.1

Type RM Length L Ch R = 1,1210,276,276,276
BEGIN DESCRIPTION:
Stream0038_DS 5.0
END DESCRIPTION:
XS GIS Cut Line= 3
      2006220.32     13868447.62      2006049.93     13868275.64
      2005890.15     13868147.03
#Sta/Elev= 30
  4793.5 1654.67  4859.7 1654.61  4891.0 1654.12  4898.1 1655.34  4905.2 1655.79
  4919.3 1654.26  4956.4 1653.08  4961.8 1652.24  4964.4 1650.79  4975.9 1647.07
  4982.9 1643.60  4995.1 1642.89  4995.3 1642.39  4998.8 1642.39  4999.1 1642.89
  5011.2 1643.93  5018.3 1643.36  5046.5 1643.54  5060.9 1645.90  5067.6 1648.10
  5075.2 1649.67  5089.6 1650.66  5110.5 1650.02  5139.2 1651.40  5188.8 1651.95
  5197.9 1652.49  5217.6 1653.43  5224.0 1653.18  5232.0 1653.93  5240.7 1653.59
#Mann=6,-1,0
  4793.5   0.035       0  4859.7    0.07       0  4956.4   0.035       0
  4995.1   0.035       0  4999.1   0.035       0  5197.9   0.045       0
Bank Sta=4995.1,4999.1
Exp/Cntr=0.3,0.1

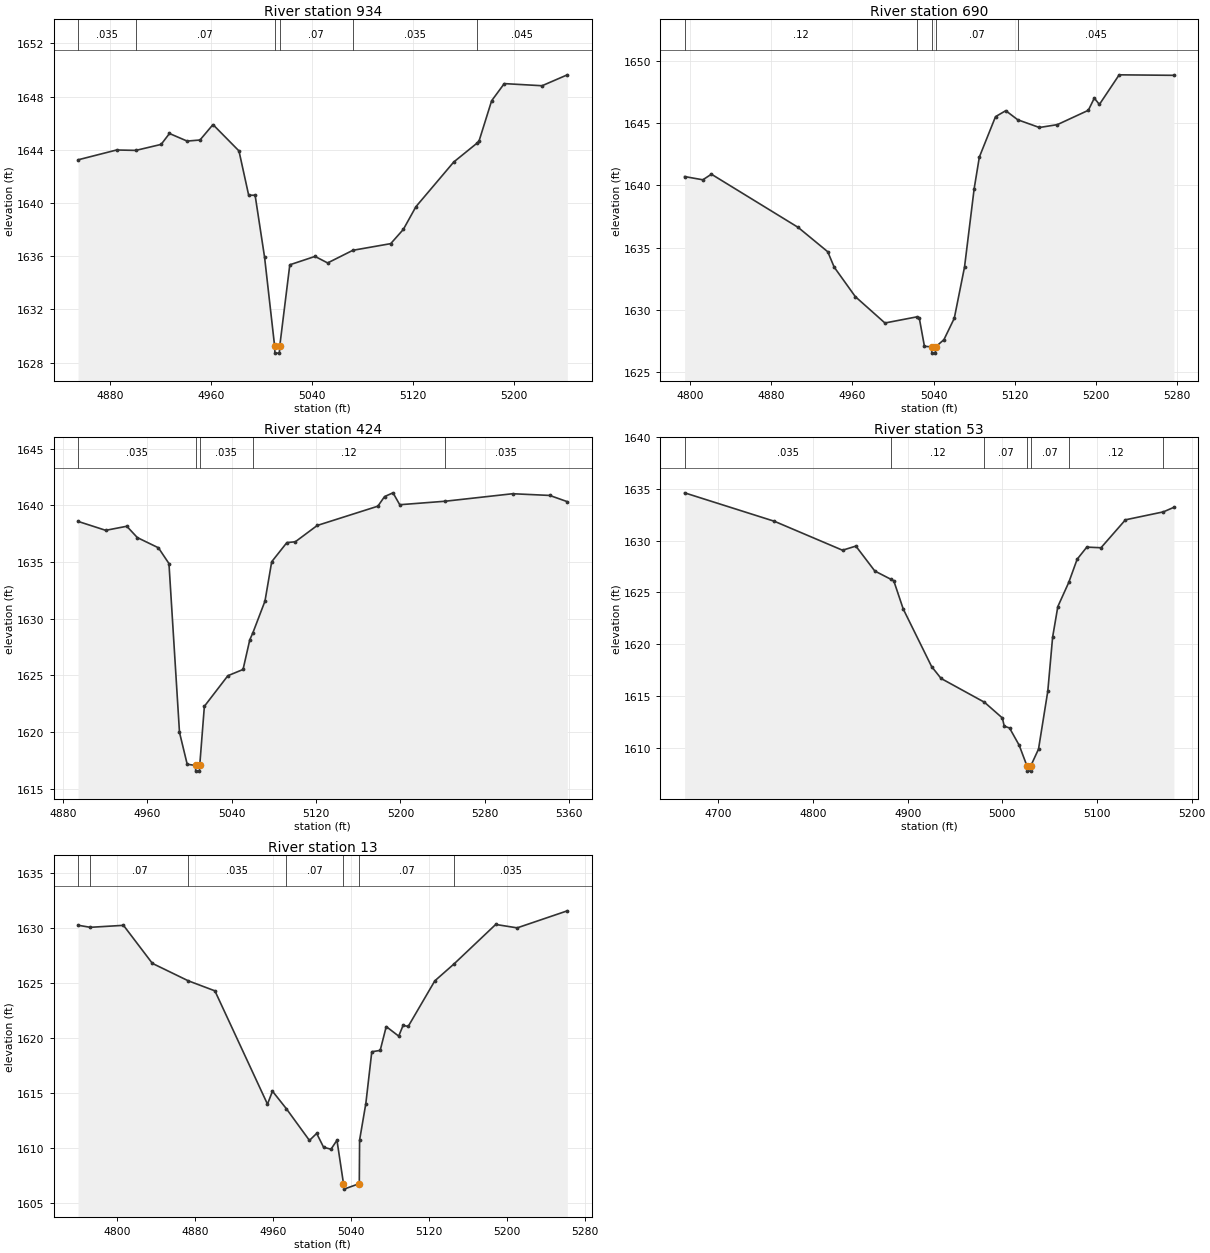
Type RM Length L Ch R = 1,934,244,244,244
BEGIN DESCRIPTION:
Stream0038_DS 4.0
END DESCRIPTION:
XS GIS Cut Line= 3
      2006359.05     13868107.37      2006225.00     13868075.00
      2005975.00     13868075.00
#Sta/Elev= 30
  4854.6 1643.24  4885.2 1643.98  4900.5 1643.95  4920.5 1644.40  4927.1 1645.22
  4941.1 1644.65  4951.3 1644.73  4961.6 1645.89  4982.2 1643.91  4989.9 1640.58
  4995.0 1640.58  5002.5 1635.92  5010.5 1629.21  5010.7 1628.71  5014.2 1628.71
  5014.5 1629.21  5022.5 1635.35  5042.5 1635.98  5052.5 1635.49  5072.5 1636.44
  5102.5 1636.94  5112.5 1638.01  5122.5 1639.72  5152.5 1643.08  5171.0 1644.50
  5172.5 1644.65  5182.5 1647.68  5192.5 1648.97  5222.5 1648.81  5242.5 1649.63
#Mann=6,-1,0
  4854.6   0.035       0  4900.5    0.07       0  5010.5    0.05       0
  5014.5    0.07       0  5072.5   0.035       0  5171.0   0.045       0
Bank Sta=5010.5,5014.5
Exp/Cntr=0.3,0.1

Type RM Length L Ch R = 1,690,266,266,266
BEGIN DESCRIPTION:
Stream0038_DS 3.0
END DESCRIPTION:
XS GIS Cut Line= 3
      2006338.86     13867997.48      2006174.43     13867874.72
      2005901.97     13867826.46
#Sta/Elev= 30
  4794.8 1640.71  4812.8 1640.45  4821.2 1640.90  4906.6 1636.63  4935.8 1634.67
  4942.1 1633.44  4962.9 1631.07  4992.1 1628.95  5023.4 1629.44  5025.9 1629.36
  5031.0 1627.08  5038.0 1627.03  5038.3 1626.53  5041.8 1626.53  5042.0 1627.03
  5050.2 1627.61  5060.4 1629.33  5070.5 1633.45  5080.0 1639.75  5085.1 1642.28
  5101.0 1645.52  5111.1 1646.00  5122.9 1645.27  5144.2 1644.65  5161.9 1644.88
  5192.4 1646.03  5198.3 1647.01  5203.3 1646.50  5222.8 1648.88  5276.7 1648.84
#Mann=5,-1,0
  4794.8    0.12       0  5023.4    0.07       0  5038.0    0.05       0
  5042.0    0.07       0  5122.9   0.045       0
Bank Sta=5038,5042
Exp/Cntr=0.3,0.1

Type RM Length L Ch R = 1,424,371,371,371
BEGIN DESCRIPTION:
Stream0038_DS 2.0
END DESCRIPTION:
XS GIS Cut Line= 3
      2006405.71     13867981.32      2006405.05     13867875.42
      2006126.51     13867649.88
#Sta/Elev= 30
  4894.1 1638.59  4920.4 1637.80  4940.4 1638.16  4950.4 1637.16  4970.4 1636.26
  4980.4 1634.87  4990.4 1619.97  4997.7 1617.16  5005.6 1617.05  5005.8 1616.55
  5009.3 1616.55  5009.6 1617.05  5014.0 1622.27  5036.3 1624.97  5050.7 1625.52
  5057.1 1628.14  5060.0 1628.75  5071.5 1631.55  5077.9 1635.03  5092.3 1636.72
  5100.3 1636.79  5121.1 1638.23  5178.6 1639.93  5185.0 1640.78  5193.0 1641.11
  5199.4 1640.06  5242.7 1640.37  5306.5 1641.03  5341.7 1640.88  5358.4 1640.33
#Mann=5,-1,0
  4894.1   0.035       0  5005.6   0.035       0  5009.6   0.035       0
  5060.0    0.12       0  5242.7   0.035       0
Bank Sta=5005.6,5009.6
Exp/Cntr=0.3,0.1

Type RM Length L Ch R = 1,53,40,40,40
BEGIN DESCRIPTION:
Stream0038_DS 1.0
END DESCRIPTION:
XS GIS Cut Line= 4
      2006572.70     13867958.87      2006621.58     13867792.27
      2006622.46     13867630.30      2006444.75     13867594.94
#Sta/Elev= 30
  4664.4 1634.63  4759.2 1631.88  4831.2 1629.08  4845.3 1629.48  4865.3 1627.07
  4882.7 1626.25  4885.3 1626.13  4895.3 1623.40  4925.3 1617.83  4935.3 1616.68
  4981.1 1614.38  5000.0 1612.86  5002.0 1612.07  5007.6 1611.89  5017.8 1610.22
  5026.0 1608.22  5026.3 1607.72  5029.8 1607.72  5030.0 1608.22  5038.2 1609.85
  5048.0 1615.45  5053.1 1620.68  5058.6 1623.63  5070.2 1625.98  5079.0 1628.21
  5089.2 1629.38  5104.2 1629.32  5130.0 1632.02  5170.1 1632.79  5181.2 1633.23
#Mann=7,-1,0
  4664.4   0.035       0  4882.7    0.12       0  4981.1    0.07       0
  5026.0    0.05       0  5030.0    0.07       0  5070.2    0.12       0
  5170.1   0.035       0
Bank Sta=5026,5030
Exp/Cntr=0.3,0.1

Type RM Length L Ch R = 1,13,0,0,0
BEGIN DESCRIPTION:
Stream0038_DS 0.0
END DESCRIPTION:
XS GIS Cut Line= 4
      2006704.11     13867860.85      2006662.02     13867624.57
      2006610.64     13867552.31      2006444.48     13867504.75
#Sta/Elev= 30
  4760.0 1630.29  4772.6 1630.10  4806.6 1630.28  4836.2 1626.82  4873.1 1625.23
  4900.3 1624.32  4954.2 1614.01  4959.3 1615.19  4973.6 1613.59  4997.2 1610.71
  5004.6 1611.35  5011.7 1610.09  5019.3 1609.91  5025.4 1610.73  5032.1 1606.78
  5032.6 1606.28  5048.3 1606.78  5048.6 1610.74  5055.0 1614.07  5061.1 1618.78
  5069.7 1618.90  5075.9 1621.07  5088.7 1620.20  5093.2 1621.18  5098.4 1621.08
  5125.7 1625.23  5145.4 1626.77  5188.1 1630.36  5210.1 1630.05  5261.5 1631.60
#Mann=7,-1,0
  4760.0   0.035       0  4772.6    0.07       0  4873.1   0.035       0
  4973.6    0.07       0  5032.1    0.05       0  5048.3    0.07       0
  5145.4   0.035       0
Bank Sta=5032.1,5048.3
Exp/Cntr=0.3,0.1

Chan Stop Cuts=-1