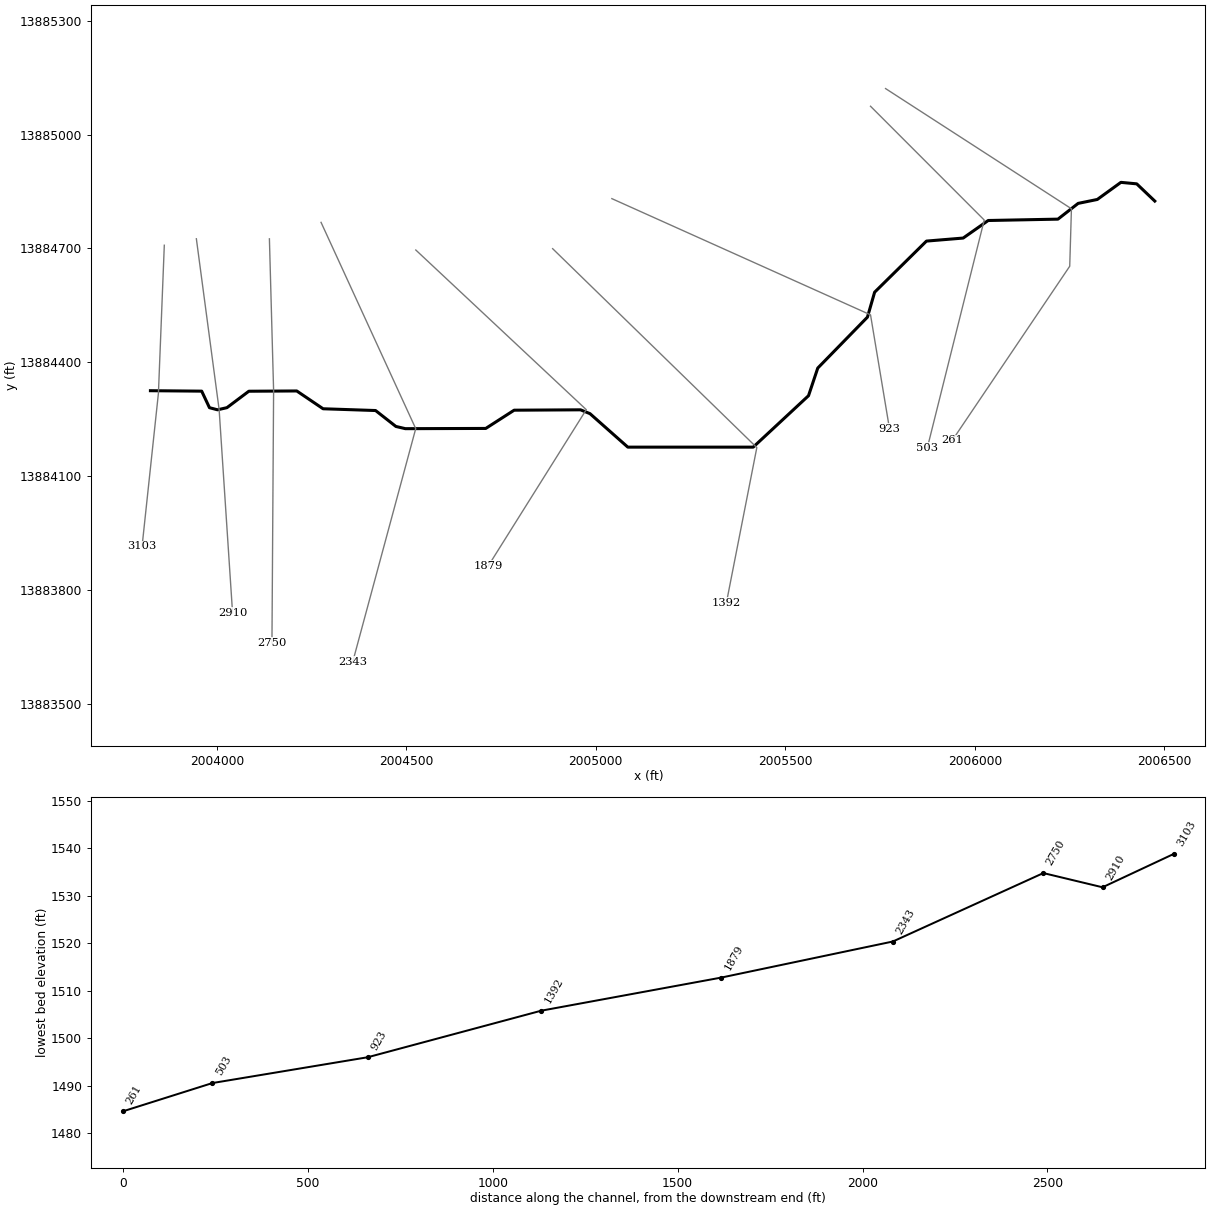
--- Stream0040_DS.prj (project) ---

Proj Title=Stream0040_DS Base Level Engineering
Current Plan=p01
Default Exp/Contr=0.3,0.1
English Units
Geom File=g01
Flow File=f01
Plan File=p01
BEGIN DESCRIPTION:
Stream0040_DS
END DESCRIPTION:

--- Stream0040_DS.p01 (plan) ---

Plan Title=Multiple Run
Short Identifier=Multiple
Geom File=g01
Flow File=f01
Subcritical Flow
K Sum by GR= 0
Std Step Tol= 0.01
Critical Tol= 0.01
Num of Std Step Trials= 20
Max Error Tol= 0.3
Flow Tol Ratio= 0.001
Split Flow NTrial= 30
Split Flow Tol= 0.02
Split Flow Ratio= 0.02
Log Output Level= 0
Friction Slope Method= 1
Unsteady Friction Slope Method= 2
Unsteady Bridges Friction Slope Method= 1
Parabolic Critical Depth
Global Vel Dist=  1 , 1 , 1
Global Log Level= 0
CheckData=True
Encroach Param= -1, 0, 0, 0
BEGIN DESCRIPTION:
Multiple Run
END DESCRIPTION:

--- Stream0040_DS.f01 (steady flow) ---

Flow Title=Multiple
Number of Profiles=7
Profile Names=10-year,25-year,50-year,1pct_min,100-year,1pct_plu,500-year
River Rch & RM= Stream0040_DS,Reach-1,3103
     362     579     774     505    1007    2010    1682
River Rch & RM= Stream0040_DS,Reach-1,2910
     697    1161    1597    1068    2131    4251    3745
Boundary for River Rch & Prof#=Stream0040_DS,Reach-1,1
Up Type=0
Dn Type=3
Dn Slope=0.005
Boundary for River Rch & Prof#=Stream0040_DS,Reach-1,2
Up Type=0
Dn Type=3
Dn Slope=0.005
Boundary for River Rch & Prof#=Stream0040_DS,Reach-1,3
Up Type=0
Dn Type=3
Dn Slope=0.005
Boundary for River Rch & Prof#=Stream0040_DS,Reach-1,4
Up Type=0
Dn Type=3
Dn Slope=0.005
Boundary for River Rch & Prof#=Stream0040_DS,Reach-1,5
Up Type=0
Dn Type=3
Dn Slope=0.005
Boundary for River Rch & Prof#=Stream0040_DS,Reach-1,6
Up Type=0
Dn Type=3
Dn Slope=0.005
Boundary for River Rch & Prof#=Stream0040_DS,Reach-1,7
Up Type=0
Dn Type=3
Dn Slope=0.005

--- Stream0040_DS.g01 (geometry) ---

Geom Title=Existing Conditions

River Reach=Stream0040_DS,Reach-1
Reach XY= 30
      2003825.00     13884325.00      2003960.26     13884323.83
      2003980.78     13884280.20      2004002.06     13884274.65
      2004026.87     13884280.28      2004084.64     13884323.61
      2004211.07     13884324.33      2004280.53     13884277.39
      2004419.06     13884272.73      2004472.67     13884230.75
      2004497.69     13884224.91      2004709.78     13884225.52
      2004784.66     13884273.62      2004959.84     13884274.61
      2004984.79     13884264.50      2005084.59     13884176.21
      2005415.41     13884176.20      2005561.37     13884311.79
      2005585.78     13884384.68      2005716.84     13884518.95
      2005735.78     13884584.68      2005872.57     13884719.48
      2005969.43     13884727.47      2006035.50     13884773.78
      2006219.48     13884777.35      2006272.82     13884818.89
      2006323.28     13884829.21      2006385.62     13884874.34
      2006427.36     13884870.40      2006475.00     13884825.00

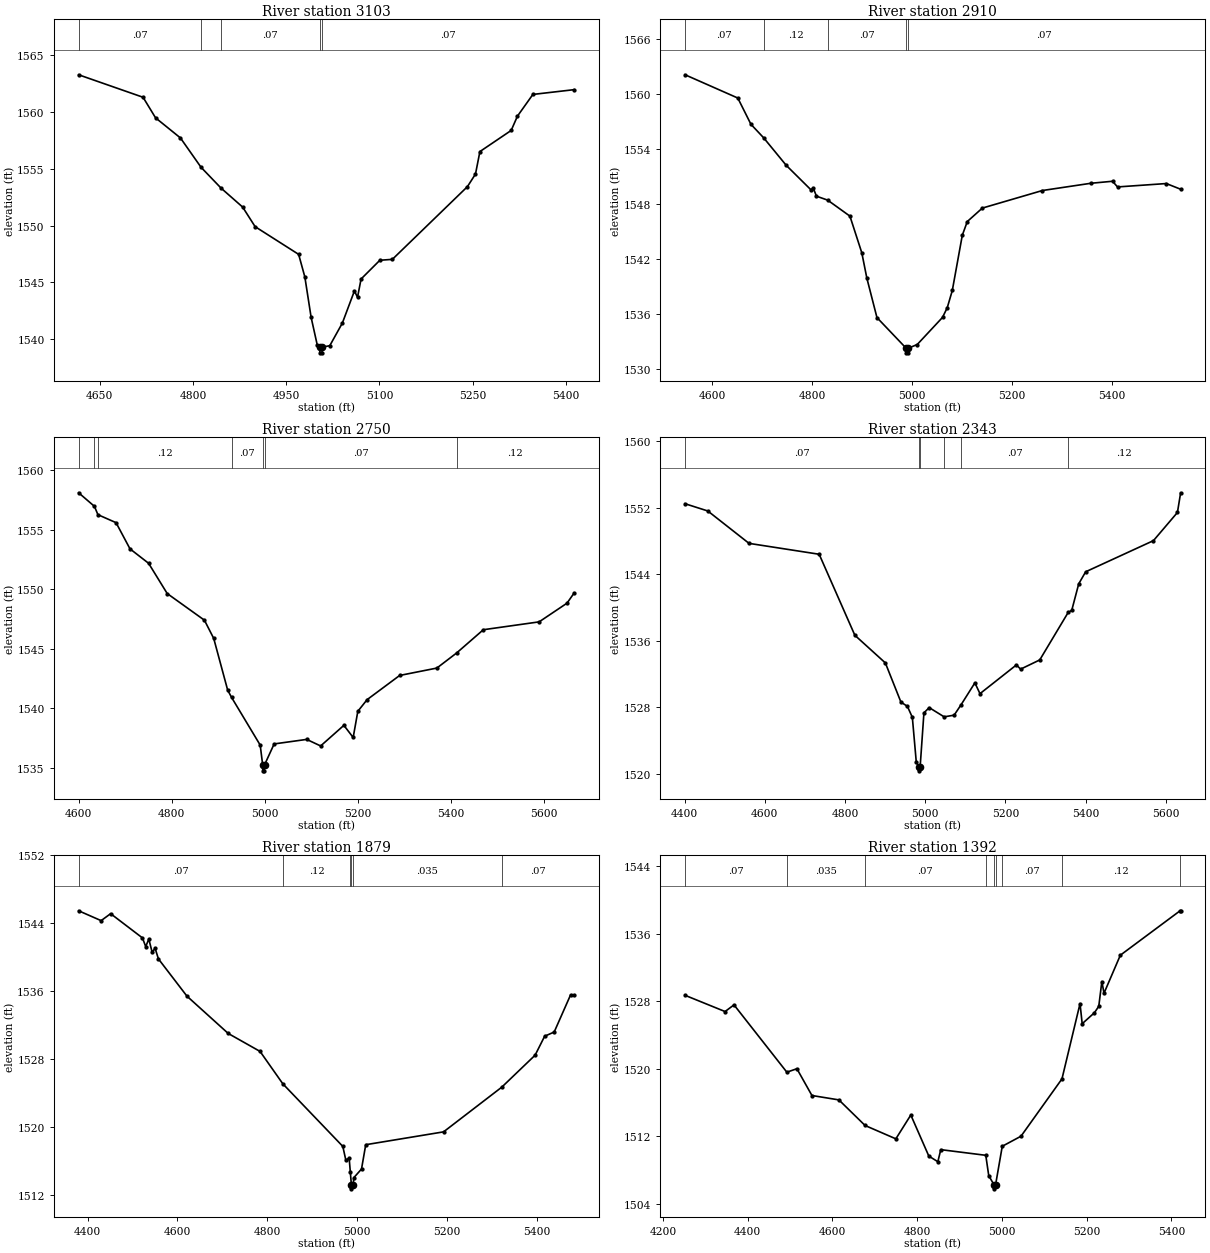
Type RM Length L Ch R = 1,3103,193,193,193
BEGIN DESCRIPTION:
Stream0040_DS 7.0
END DESCRIPTION:
XS GIS Cut Line= 3
      2003861.62     13884708.56      2003846.10     13884318.44
      2003802.90     13883914.27
#Sta/Elev= 30
  4616.2 1563.27  4719.8 1561.29  4739.9 1559.48  4779.9 1557.71  4813.0 1555.13
  4845.1 1553.30  4880.0 1551.62  4900.0 1549.90  4970.0 1547.46  4980.0 1545.47
  4990.1 1541.91  5000.1 1539.44  5003.8 1539.29  5004.1 1538.79  5007.6 1538.79
  5007.8 1539.29  5020.1 1539.42  5040.3 1541.41  5059.7 1544.24  5064.7 1543.68
  5070.4 1545.29  5100.6 1546.94  5120.7 1547.02  5241.4 1553.42  5254.4 1554.53
  5261.5 1556.51  5311.8 1558.37  5321.9 1559.63  5346.7 1561.54  5413.1 1561.96
#Mann=5,-1,0
  4616.2    0.07       0  4813.0    0.12       0  4845.1    0.07       0
  5003.8    0.05       0  5007.8    0.07       0
Bank Sta=5003.8,5007.8
Exp/Cntr=0.3,0.1

Type RM Length L Ch R = 1,2910,160,160,160
BEGIN DESCRIPTION:
Stream0040_DS 6.0
END DESCRIPTION:
XS GIS Cut Line= 3
      2003946.20     13884725.60      2004006.31     13884274.79
      2004041.73     13883738.96
#Sta/Elev= 30
  4545.2 1562.13  4650.7 1559.59  4677.0 1556.72  4702.5 1555.24  4747.6 1552.24
  4797.0 1549.57  4802.0 1549.72  4808.1 1548.87  4830.5 1548.44  4875.1 1546.69
  4898.9 1542.68  4909.0 1539.91  4929.2 1535.61  4987.7 1532.26  4987.9 1531.76
  4991.4 1531.76  4991.7 1532.26  5009.8 1532.67  5060.4 1535.63  5069.9 1536.69
  5080.0 1538.57  5100.0 1544.60  5110.0 1546.10  5140.1 1547.57  5260.4 1549.49
  5357.3 1550.28  5400.7 1550.50  5410.7 1549.88  5508.3 1550.25  5537.0 1549.63
#Mann=5,-1,0
  4545.2    0.07       0  4702.5    0.12       0  4830.5    0.07       0
  4987.7    0.05       0  4991.7    0.07       0
Bank Sta=4987.7,4991.7
Exp/Cntr=0.3,0.1

Type RM Length L Ch R = 1,2750,407,407,407
BEGIN DESCRIPTION:
Stream0040_DS 5.5
END DESCRIPTION:
XS GIS Cut Line= 3
      2004138.93     13884725.45      2004150.00     13884325.40
      2004145.63     13883659.62
#Sta/Elev= 30
  4599.8 1558.10  4633.8 1556.96  4641.3 1556.26  4680.3 1555.59  4710.3 1553.39
  4750.3 1552.18  4790.3 1549.64  4870.4 1547.40  4890.4 1545.87  4920.4 1541.53
  4928.9 1540.91  4990.4 1536.91  4995.7 1535.25  4995.9 1534.75  4999.4 1534.75
  4999.7 1535.25  5020.4 1537.01  5090.4 1537.39  5120.4 1536.84  5170.4 1538.57
  5190.4 1537.55  5200.4 1539.75  5220.4 1540.73  5290.4 1542.76  5370.4 1543.38
  5412.7 1544.64  5470.4 1546.60  5590.4 1547.26  5650.4 1548.83  5665.8 1549.69
#Mann=7,-1,0
  4599.8   0.035       0  4633.8    0.07       0  4641.3    0.12       0
  4928.9    0.07       0  4995.7    0.05       0  4999.7    0.07       0
  5412.7    0.12       0
Bank Sta=4995.7,4999.7
Exp/Cntr=0.3,0.1

Type RM Length L Ch R = 1,2343,464,464,464
BEGIN DESCRIPTION:
Stream0040_DS 5.0
END DESCRIPTION:
XS GIS Cut Line= 3
      2004275.19     13884768.87      2004525.00     13884225.00
      2004358.63     13883609.59
#Sta/Elev= 30
  4401.1 1552.50  4457.7 1551.63  4560.6 1547.73  4735.5 1546.42  4824.5 1536.67
  4900.6 1533.34  4939.4 1528.63  4955.6 1528.11  4967.9 1526.79  4977.6 1521.47
  4983.4 1520.85  4983.6 1520.35  4987.4 1520.85  4996.8 1527.33  5010.0 1527.96
  5047.2 1526.85  5072.1 1527.05  5089.4 1528.30  5123.9 1530.94  5136.6 1529.64
  5227.5 1533.10  5237.9 1532.59  5285.7 1533.70  5356.5 1539.41  5365.5 1539.67
  5382.9 1542.86  5400.2 1544.31  5569.3 1548.06  5629.1 1551.45  5637.1 1553.82
#Mann=6,-1,0
  4401.1    0.07       0  4983.4    0.05       0  4987.4    0.07       0
  5047.2   0.035       0  5089.4    0.07       0  5356.5    0.12       0
Bank Sta=4983.4,4987.4
Exp/Cntr=0.3,0.1

Type RM Length L Ch R = 1,1879,487,487,487
BEGIN DESCRIPTION:
Stream0040_DS 4.0
END DESCRIPTION:
XS GIS Cut Line= 3
      2004525.20     13884695.96      2004975.00     13884275.00
      2004716.17     13883862.67
#Sta/Elev= 30
  4380.0 1545.46  4430.1 1544.30  4451.2 1545.12  4522.0 1542.27  4529.3 1541.25
  4536.2 1542.13  4543.5 1540.61  4550.3 1541.03  4557.6 1539.80  4621.1 1535.42
  4713.0 1531.03  4783.8 1528.92  4834.5 1525.11  4968.0 1517.75  4974.8 1516.11
  4982.1 1516.38  4984.6 1514.79  4987.0 1513.26  4987.2 1512.76  4991.0 1513.26
  4992.6 1514.08  5009.6 1515.09  5019.0 1517.95  5192.2 1519.46  5321.6 1524.71
  5396.0 1528.48  5417.2 1530.71  5438.4 1531.20  5475.0 1535.58  5482.9 1535.52
#Mann=6,-1,0
  4380.0    0.07       0  4834.5    0.12       0  4984.6   0.035       0
  4987.0   0.035       0  4991.0   0.035       0  5321.6    0.07       0
Bank Sta=4987,4991
Exp/Cntr=0.3,0.1

Type RM Length L Ch R = 1,1392,469,469,469
BEGIN DESCRIPTION:
Stream0040_DS 3.0
END DESCRIPTION:
XS GIS Cut Line= 3
      2004886.26     13884699.48      2005425.00     13884175.00
      2005344.62     13883765.39
#Sta/Elev= 30
  4252.4 1528.70  4346.7 1526.78  4367.8 1527.57  4492.5 1519.60  4516.2 1520.01
  4551.7 1516.84  4615.3 1516.32  4677.1 1513.29  4749.7 1511.71  4785.0 1514.53
  4827.5 1509.67  4848.8 1509.00  4855.7 1510.43  4961.9 1509.76  4968.9 1507.35
  4981.1 1506.29  4981.3 1505.79  4985.1 1506.29  5000.8 1510.83  5045.0 1512.02
  5141.7 1518.81  5184.3 1527.72  5189.4 1525.34  5218.3 1526.64  5228.5 1527.40
  5235.8 1530.33  5240.9 1528.95  5279.4 1533.45  5420.4 1538.71  5421.7 1538.71
#Mann=9,-1,0
  4252.4    0.07       0  4492.5   0.035       0  4677.1    0.07       0
  4961.9   0.035       0  4981.1   0.035       0  4985.1   0.035       0
  5000.8    0.07       0  5141.7    0.12       0  5420.4    0.07       0
Bank Sta=4981.1,4985.1
Exp/Cntr=0.3,0.1

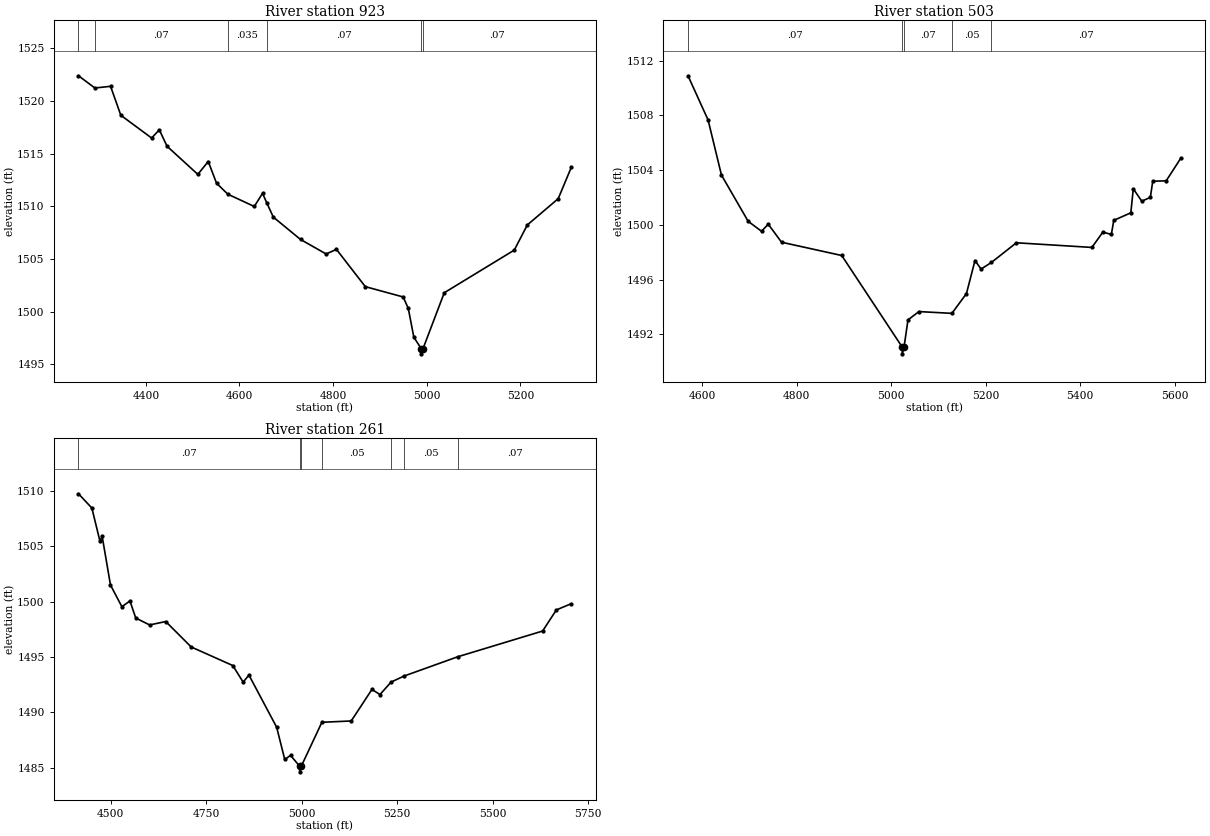
Type RM Length L Ch R = 1,923,420,420,420
BEGIN DESCRIPTION:
Stream0040_DS 2.0
END DESCRIPTION:
XS GIS Cut Line= 3
      2005042.51     13884831.41      2005725.00     13884525.00
      2005775.01     13884224.95
#Sta/Elev= 30
  4256.2 1522.40  4291.2 1521.24  4324.7 1521.40  4346.6 1518.65  4412.4 1516.49
  4428.8 1517.27  4445.3 1515.71  4511.0 1513.04  4533.3 1514.26  4551.0 1512.20
  4575.0 1511.16  4631.6 1509.99  4649.2 1511.24  4658.4 1510.32  4672.3 1508.98
  4730.3 1506.86  4785.1 1505.48  4807.0 1505.92  4868.7 1502.38  4949.5 1501.40
  4960.5 1500.31  4972.3 1497.58  4988.0 1496.50  4988.2 1496.00  4992.0 1496.50
  5037.3 1501.80  5186.8 1505.85  5214.7 1508.24  5280.6 1510.73  5308.5 1513.70
#Mann=6,-1,0
  4256.2   0.035       0  4291.2    0.07       0  4575.0   0.035       0
  4658.4    0.07       0  4988.0    0.05       0  4992.0    0.07       0
Bank Sta=4988,4992
Exp/Cntr=0.3,0.1

Type RM Length L Ch R = 1,503,242,242,242
BEGIN DESCRIPTION:
Stream0040_DS 1.0
END DESCRIPTION:
XS GIS Cut Line= 3
      2005724.96     13885075.04      2006025.00     13884775.00
      2005875.00     13884174.98
#Sta/Elev= 30
  4570.3 1510.90  4612.8 1507.67  4641.1 1503.64  4697.6 1500.26  4725.9 1499.53
  4740.1 1500.05  4768.3 1498.73  4895.6 1497.76  5023.5 1491.07  5023.8 1490.57
  5027.5 1491.07  5035.8 1493.05  5059.0 1493.66  5128.7 1493.53  5159.5 1494.97
  5177.6 1497.39  5190.5 1496.77  5212.3 1497.25  5265.2 1498.69  5425.0 1498.35
  5448.2 1499.47  5466.2 1499.30  5471.3 1500.33  5507.4 1500.88  5512.6 1502.64
  5530.6 1501.73  5548.7 1502.01  5553.8 1503.19  5582.2 1503.22  5613.1 1504.87
#Mann=5,-1,0
  4570.3    0.07       0  5023.5    0.05       0  5027.5    0.07       0
  5128.7    0.05       0  5212.3    0.07       0
Bank Sta=5023.5,5027.5
Exp/Cntr=0.3,0.1

Type RM Length L Ch R = 1,261,0,0,0
BEGIN DESCRIPTION:
Stream0040_DS 0.0
END DESCRIPTION:
XS GIS Cut Line= 4
      2005764.67     13885121.60      2006255.11     13884804.73
      2006250.57     13884653.14      2005940.64     13884194.01
#Sta/Elev= 30
  4416.1 1509.76  4451.1 1508.47  4472.2 1505.48  4478.1 1505.90  4499.8 1501.51
  4529.6 1499.55  4550.7 1500.07  4565.9 1498.53  4602.2 1497.90  4644.4 1498.21
  4711.0 1495.91  4819.9 1494.23  4847.0 1492.73  4862.1 1493.37  4934.7 1488.65
  4955.8 1485.74  4971.0 1486.11  4995.0 1485.12  4995.2 1484.62  4999.0 1485.12
  5053.0 1489.10  5129.8 1489.22  5184.0 1492.07  5205.0 1491.61  5234.3 1492.74
  5268.0 1493.28  5408.2 1495.02  5630.6 1497.35  5666.6 1499.26  5705.6 1499.82
#Mann=7,-1,0
  4416.1    0.07       0  4995.0    0.05       0  4999.0    0.07       0
  5053.0    0.05       0  5234.3    0.07       0  5268.0    0.05       0
  5408.2    0.07       0
Bank Sta=4995,4999
Exp/Cntr=0.3,0.1

Chan Stop Cuts=-1