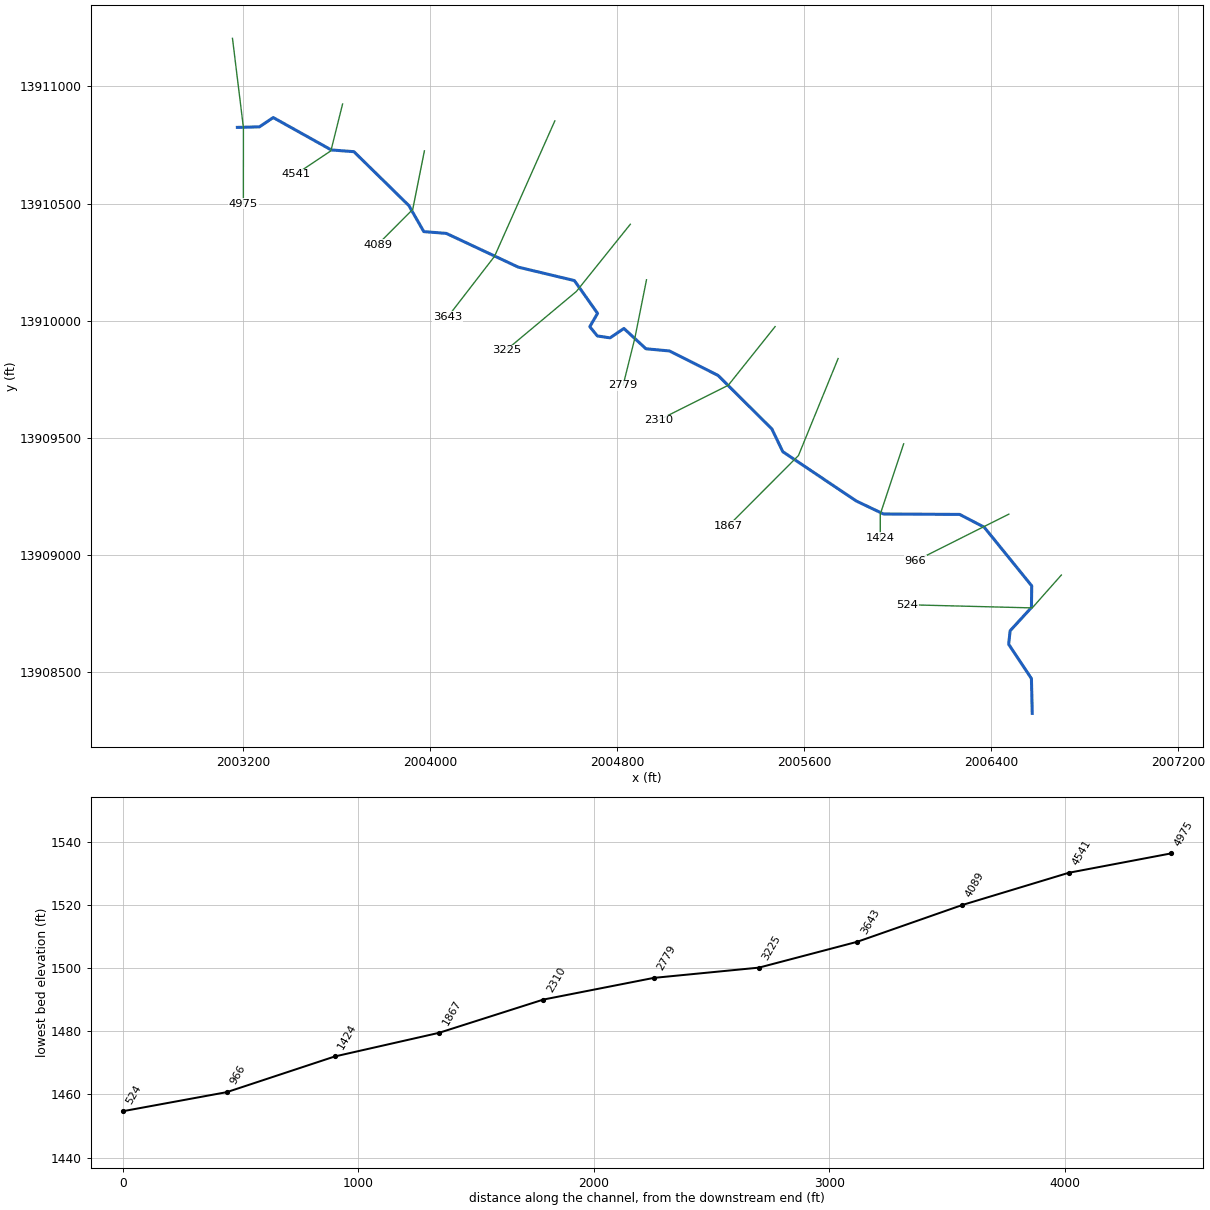
--- Stream0041_DS.prj (project) ---

Proj Title=Stream0041_DS Base Level Engineering
Current Plan=p01
Default Exp/Contr=0.3,0.1
English Units
Geom File=g01
Flow File=f01
Plan File=p01
BEGIN DESCRIPTION:
Stream0041_DS
END DESCRIPTION:

--- Stream0041_DS.p01 (plan) ---

Plan Title=Multiple Run
Short Identifier=Multiple
Geom File=g01
Flow File=f01
Subcritical Flow
K Sum by GR= 0
Std Step Tol= 0.01
Critical Tol= 0.01
Num of Std Step Trials= 20
Max Error Tol= 0.3
Flow Tol Ratio= 0.001
Split Flow NTrial= 30
Split Flow Tol= 0.02
Split Flow Ratio= 0.02
Log Output Level= 0
Friction Slope Method= 1
Unsteady Friction Slope Method= 2
Unsteady Bridges Friction Slope Method= 1
Parabolic Critical Depth
Global Vel Dist=  1 , 1 , 1
Global Log Level= 0
CheckData=True
Encroach Param= -1, 0, 0, 0
BEGIN DESCRIPTION:
Multiple Run
END DESCRIPTION:

--- Stream0041_DS.f01 (steady flow) ---

Flow Title=Multiple
Number of Profiles=7
Profile Names=10-year,25-year,50-year,1pct_min,100-year,1pct_plu,500-year
River Rch & RM= Stream0041_DS,Reach-1,4975
     330     527     704     460     917    1830    1535
River Rch & RM= Stream0041_DS,Reach-1,4541
     904    1531    2126    1433    2859    5705    5115
Boundary for River Rch & Prof#=Stream0041_DS,Reach-1,1
Up Type=0
Dn Type=3
Dn Slope=0.005
Boundary for River Rch & Prof#=Stream0041_DS,Reach-1,2
Up Type=0
Dn Type=3
Dn Slope=0.005
Boundary for River Rch & Prof#=Stream0041_DS,Reach-1,3
Up Type=0
Dn Type=3
Dn Slope=0.005
Boundary for River Rch & Prof#=Stream0041_DS,Reach-1,4
Up Type=0
Dn Type=3
Dn Slope=0.005
Boundary for River Rch & Prof#=Stream0041_DS,Reach-1,5
Up Type=0
Dn Type=3
Dn Slope=0.005
Boundary for River Rch & Prof#=Stream0041_DS,Reach-1,6
Up Type=0
Dn Type=3
Dn Slope=0.005
Boundary for River Rch & Prof#=Stream0041_DS,Reach-1,7
Up Type=0
Dn Type=3
Dn Slope=0.005

--- Stream0041_DS.g01 (geometry) ---

Geom Title=Existing Conditions

River Reach=Stream0041_DS,Reach-1
Reach XY= 30
      2003175.00     13910825.00      2003269.23     13910827.34
      2003328.31     13910866.99      2003576.59     13910728.83
      2003673.50     13910721.39      2003908.34     13910491.66
      2003972.33     13910380.42      2004069.02     13910372.64
      2004376.56     13910228.76      2004616.52     13910171.49
      2004715.68     13910031.65      2004682.47     13909974.72
      2004714.61     13909935.20      2004769.28     13909927.11
      2004828.40     13909967.16      2004922.57     13909880.55
      2005023.41     13909871.17      2005231.06     13909766.86
      2005461.36     13909538.20      2005507.95     13909441.50
      2005822.71     13909230.84      2005938.91     13909175.67
      2006264.52     13909173.81      2006369.39     13909119.41
      2006572.87     13908869.06      2006571.53     13908776.50
      2006480.41     13908677.42      2006474.13     13908619.96
      2006571.49     13908473.55      2006575.00     13908325.00

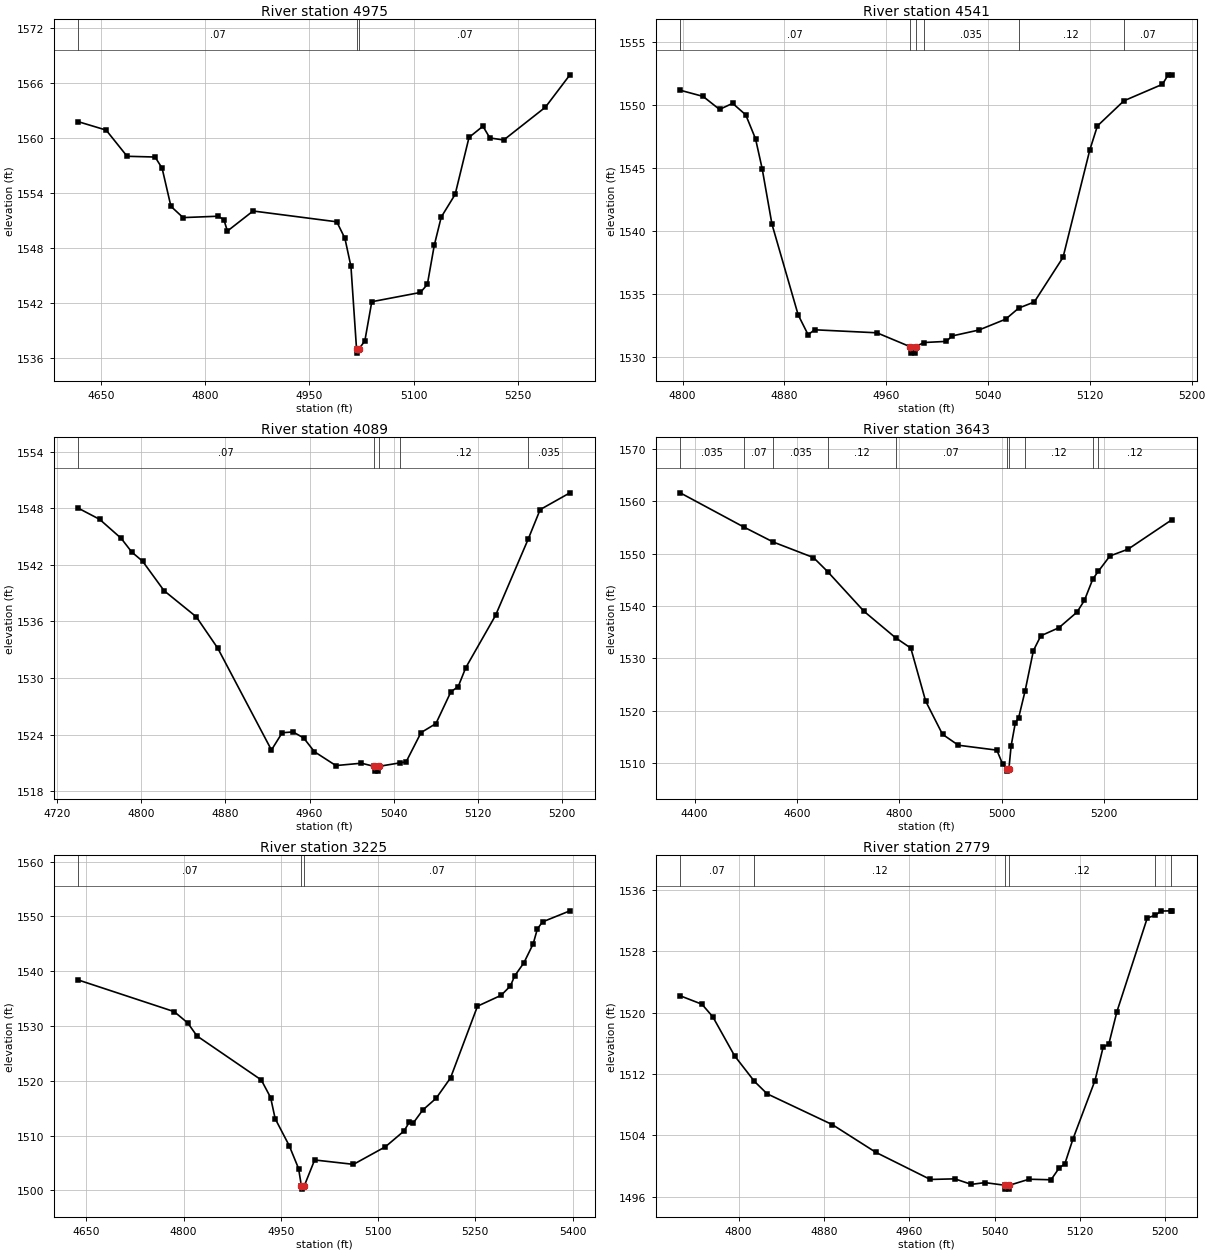
Type RM Length L Ch R = 1,4975,434,434,434
BEGIN DESCRIPTION:
Stream0041_DS 11.0
END DESCRIPTION:
XS GIS Cut Line= 3
      2003154.00     13911204.97      2003200.85     13910823.77
      2003200.62     13910499.74
#Sta/Elev= 30
  4616.9 1561.74  4657.2 1560.82  4687.4 1557.96  4727.7 1557.88  4737.8 1556.66
  4750.5 1552.50  4768.0 1551.27  4818.4 1551.42  4826.7 1551.05  4831.8 1549.80
  4868.8 1551.99  4989.3 1550.81  5001.0 1549.01  5009.7 1545.94  5017.7 1536.98
  5018.0 1536.48  5021.7 1536.98  5029.7 1537.82  5039.7 1542.09  5109.7 1543.10
  5119.7 1543.98  5129.7 1548.26  5139.7 1551.33  5159.7 1553.80  5179.7 1560.02
  5199.7 1561.24  5209.7 1559.96  5229.7 1559.74  5289.7 1563.32  5325.0 1566.85
#Mann=3,-1,0
  4616.9    0.07       0  5017.7    0.05       0  5021.7    0.07       0
Bank Sta=5017.7,5021.7
Exp/Cntr=0.3,0.1

Type RM Length L Ch R = 1,4541,452,452,452
BEGIN DESCRIPTION:
Stream0041_DS 10.0
END DESCRIPTION:
XS GIS Cut Line= 3
      2003624.99     13910924.98      2003575.00     13910725.00
      2003425.01     13910625.01
#Sta/Elev= 30
  4798.1 1551.17  4816.1 1550.68  4829.0 1549.65  4839.3 1550.13  4849.6 1549.22
  4857.3 1547.32  4862.5 1544.96  4870.2 1540.56  4890.8 1533.37  4898.6 1531.80
  4903.7 1532.19  4952.7 1531.95  4979.0 1530.84  4979.3 1530.34  4982.8 1530.34
  4983.0 1530.84  4989.5 1531.18  5007.2 1531.27  5011.7 1531.70  5032.8 1532.17
  5053.8 1533.03  5064.1 1533.91  5076.3 1534.39  5098.9 1537.93  5119.9 1546.43
  5125.9 1548.34  5146.7 1550.33  5177.0 1551.64  5181.5 1552.39  5184.5 1552.39
#Mann=6,-1,0
  4798.1    0.07       0  4979.0   0.035       0  4983.0    0.07       0
  4989.5   0.035       0  5064.1    0.12       0  5146.7    0.07       0
Bank Sta=4979,4983
Exp/Cntr=0.3,0.1

Type RM Length L Ch R = 1,4089,446,446,446
BEGIN DESCRIPTION:
Stream0041_DS 9.0
END DESCRIPTION:
XS GIS Cut Line= 3
      2003975.00     13910725.02      2003925.00     13910475.00
      2003775.00     13910325.00
#Sta/Elev= 30
  4740.2 1548.02  4760.6 1546.83  4781.0 1544.82  4791.2 1543.35  4801.4 1542.39
  4821.8 1539.26  4852.4 1536.49  4872.8 1533.16  4923.8 1522.36  4934.0 1524.19
  4944.2 1524.28  4954.4 1523.64  4964.6 1522.18  4985.0 1520.71  5009.3 1520.96
  5021.5 1520.62  5021.7 1520.12  5025.2 1520.12  5025.5 1520.62  5045.5 1520.99
  5051.7 1521.10  5065.9 1524.21  5080.0 1525.16  5094.2 1528.53  5101.2 1529.09
  5108.3 1531.08  5136.6 1536.63  5167.8 1544.77  5179.0 1547.86  5207.3 1549.64
#Mann=5,-1,0
  4740.2    0.07       0  5021.5    0.05       0  5025.5    0.07       0
  5045.5    0.12       0  5167.8   0.035       0
Bank Sta=5021.5,5025.5
Exp/Cntr=0.3,0.1

Type RM Length L Ch R = 1,3643,418,418,418
BEGIN DESCRIPTION:
Stream0041_DS 8.0
END DESCRIPTION:
XS GIS Cut Line= 3
      2004532.83     13910852.72      2004275.00     13910275.00
      2004074.47     13910015.87
#Sta/Elev= 30
  4371.9 1561.65  4495.6 1555.14  4553.9 1552.23  4632.2 1549.27  4659.7 1546.60
  4730.8 1539.00  4792.4 1533.95  4822.2 1531.97  4851.2 1521.83  4884.1 1515.49
  4915.1 1513.40  4990.2 1512.46  5001.8 1509.72  5009.8 1508.95  5010.0 1508.45
  5013.8 1508.95  5018.1 1513.28  5026.3 1517.70  5032.6 1518.59  5045.3 1523.75
  5061.6 1531.49  5076.1 1534.32  5111.4 1535.86  5146.7 1538.84  5161.2 1541.09
  5177.6 1545.17  5188.2 1546.63  5211.0 1549.58  5246.3 1550.87  5332.2 1556.52
#Mann=10,-1,0
  4371.9   0.035       0  4495.6    0.07       0  4553.9   0.035       0
  4659.7    0.12       0  4792.4    0.07       0  5009.8    0.05       0
  5013.8    0.07       0  5045.3    0.12       0  5177.6    0.07       0
  5188.2    0.12       0
Bank Sta=5009.8,5013.8
Exp/Cntr=0.3,0.1

Type RM Length L Ch R = 1,3225,446,446,446
BEGIN DESCRIPTION:
Stream0041_DS 7.0
END DESCRIPTION:
XS GIS Cut Line= 3
      2004855.74     13910411.73      2004625.00     13910125.00
      2004324.97     13909874.97
#Sta/Elev= 30
  4637.4 1538.41  4785.5 1532.63  4806.3 1530.58  4820.7 1528.19  4919.9 1520.16
  4934.3 1516.95  4941.3 1513.10  4963.0 1508.17  4977.4 1504.00  4981.9 1500.74
  4982.1 1500.24  4985.9 1500.74  5002.2 1505.56  5062.1 1504.76  5111.5 1507.98
  5140.2 1510.86  5148.0 1512.42  5154.5 1512.33  5168.8 1514.65  5189.6 1516.82
  5211.8 1520.53  5253.4 1533.62  5289.9 1535.61  5304.2 1537.32  5310.7 1539.13
  5325.0 1541.54  5339.3 1545.00  5345.8 1547.73  5353.7 1549.00  5396.0 1551.02
#Mann=3,-1,0
  4637.4    0.07       0  4981.9    0.05       0  4985.9    0.07       0
Bank Sta=4981.9,4985.9
Exp/Cntr=0.3,0.1

Type RM Length L Ch R = 1,2779,469,469,469
BEGIN DESCRIPTION:
Stream0041_DS 6.0
END DESCRIPTION:
XS GIS Cut Line= 3
      2004924.99     13910174.96      2004875.00     13909925.00
      2004824.99     13909724.97
#Sta/Elev= 30
  4745.2 1522.18  4765.6 1521.08  4775.8 1519.44  4796.2 1514.36  4814.8 1511.03
  4826.7 1509.41  4887.9 1505.39  4928.7 1501.78  4979.7 1498.25  5002.7 1498.33
  5018.2 1497.61  5031.0 1497.84  5049.7 1497.49  5049.9 1496.99  5053.4 1496.99
  5053.7 1497.49  5072.3 1498.28  5092.9 1498.21  5100.6 1499.76  5105.8 1500.27
  5113.5 1503.54  5134.1 1511.14  5141.8 1515.52  5147.0 1515.86  5154.7 1520.13
  5183.1 1532.31  5190.8 1532.69  5196.0 1533.22  5205.7 1533.25  5206.3 1533.25
#Mann=6,-1,0
  4745.2    0.07       0  4814.8    0.12       0  5049.7    0.05       0
  5053.7    0.12       0  5190.8    0.12       0  5205.7    0.07       0
Bank Sta=5049.7,5053.7
Exp/Cntr=0.3,0.1

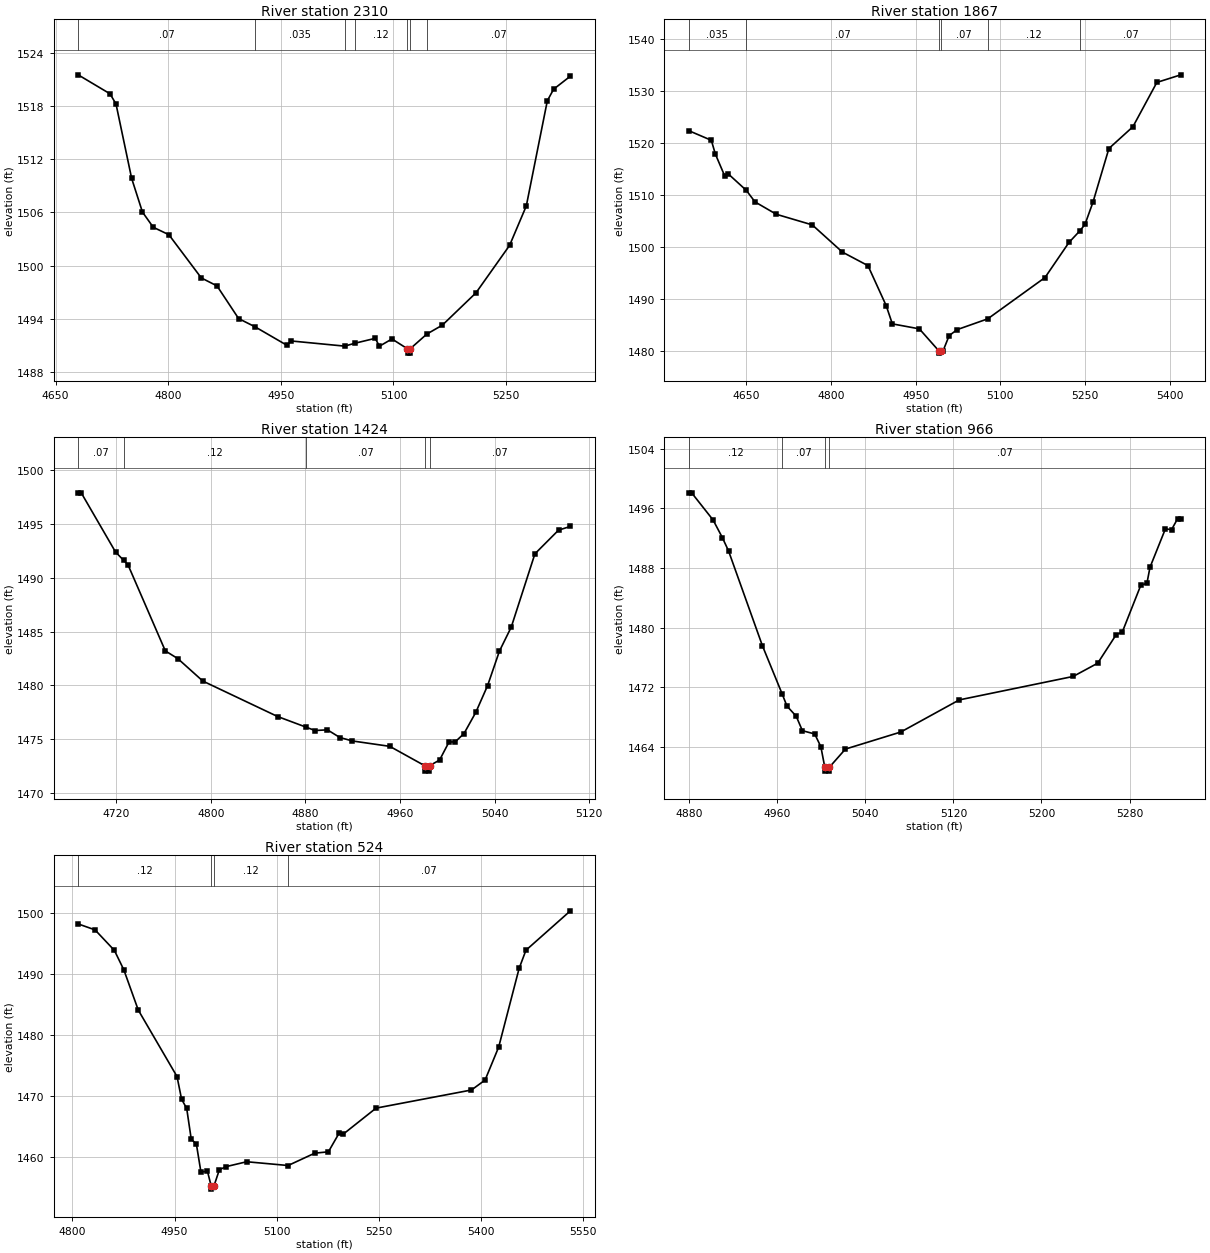
Type RM Length L Ch R = 1,2310,443,443,443
BEGIN DESCRIPTION:
Stream0041_DS 5.0
END DESCRIPTION:
XS GIS Cut Line= 3
      2005474.98     13909974.97      2005275.00     13909725.00
      2004975.03     13909575.01
#Sta/Elev= 30
  4680.1 1521.53  4722.5 1519.39  4730.5 1518.24  4751.3 1509.85  4765.7 1506.04
  4780.1 1504.32  4800.9 1503.48  4844.1 1498.60  4865.0 1497.70  4893.8 1494.01
  4915.7 1493.08  4957.8 1491.01  4964.2 1491.48  5035.0 1490.90  5048.3 1491.22
  5075.7 1491.78  5081.3 1490.89  5098.0 1491.71  5118.4 1490.61  5118.7 1490.11
  5122.2 1490.11  5122.4 1490.61  5144.4 1492.26  5165.1 1493.27  5209.9 1496.92
  5254.6 1502.27  5276.9 1506.73  5304.9 1518.61  5313.3 1519.91  5335.6 1521.38
#Mann=7,-1,0
  4680.1    0.07       0  4915.7   0.035       0  5035.0    0.07       0
  5048.3    0.12       0  5118.4   0.035       0  5122.4    0.12       0
  5144.4    0.07       0
Bank Sta=5118.4,5122.4
Exp/Cntr=0.3,0.1

Type RM Length L Ch R = 1,1867,443,443,443
BEGIN DESCRIPTION:
Stream0041_DS 4.0
END DESCRIPTION:
XS GIS Cut Line= 3
      2005744.64     13909838.83      2005575.00     13909425.00
      2005275.01     13909125.01
#Sta/Elev= 30
  4547.9 1522.39  4588.2 1520.52  4595.3 1517.88  4612.2 1513.58  4617.6 1514.11
  4650.0 1510.90  4665.6 1508.66  4703.3 1506.28  4766.9 1504.24  4820.3 1499.00
  4865.5 1496.40  4897.7 1488.72  4908.7 1485.19  4956.5 1484.23  4990.5 1480.06
  4990.7 1479.56  4994.5 1480.06  4998.7 1480.06  5009.3 1482.93  5023.4 1484.08
  5077.6 1486.16  5179.0 1494.11  5221.4 1500.86  5240.8 1503.11  5249.7 1504.32
  5263.9 1508.61  5292.1 1518.94  5334.6 1523.13  5377.0 1531.66  5419.4 1533.12
#Mann=6,-1,0
  4547.9   0.035       0  4650.0    0.07       0  4990.5    0.05       0
  4994.5    0.07       0  5077.6    0.12       0  5240.8    0.07       0
Bank Sta=4990.5,4994.5
Exp/Cntr=0.3,0.1

Type RM Length L Ch R = 1,1424,458,458,458
BEGIN DESCRIPTION:
Stream0041_DS 3.0
END DESCRIPTION:
XS GIS Cut Line= 3
      2006024.99     13909474.96      2005925.00     13909175.00
      2005925.00     13909074.99
#Sta/Elev= 30
  4687.9 1497.88  4690.5 1497.88  4719.5 1492.39  4726.4 1491.61  4730.0 1491.21
  4761.6 1483.21  4772.2 1482.49  4793.3 1480.41  4856.5 1477.12  4880.4 1476.14
  4888.1 1475.82  4898.7 1475.88  4909.2 1475.17  4919.8 1474.85  4951.4 1474.35
  4981.0 1472.55  4981.3 1472.05  4984.8 1472.05  4985.0 1472.55  4993.5 1473.08
  5001.5 1474.76  5006.6 1474.76  5014.1 1475.53  5024.1 1477.50  5034.1 1479.99
  5044.1 1483.19  5054.1 1485.42  5074.1 1492.22  5094.1 1494.42  5104.1 1494.76
#Mann=5,-1,0
  4687.9    0.07       0  4726.4    0.12       0  4880.4    0.07       0
  4981.0    0.05       0  4985.0    0.07       0
Bank Sta=4981,4985
Exp/Cntr=0.3,0.1

Type RM Length L Ch R = 1,966,442,442,442
BEGIN DESCRIPTION:
Stream0041_DS 2.0
END DESCRIPTION:
XS GIS Cut Line= 3
      2006474.98     13909174.99      2006375.00     13909125.00
      2006074.99     13908975.00
#Sta/Elev= 30
  4879.4 1498.10  4882.2 1498.10  4901.7 1494.45  4910.1 1492.09  4915.7 1490.31
  4946.5 1477.57  4964.6 1471.04  4968.8 1469.47  4977.2 1468.11  4982.8 1466.17
  4994.0 1465.73  4999.6 1464.01  5003.2 1461.24  5003.4 1460.74  5006.9 1460.74
  5007.2 1461.24  5021.9 1463.70  5072.2 1465.99  5125.3 1470.30  5228.8 1473.45
  5251.1 1475.23  5267.9 1479.06  5273.5 1479.43  5290.3 1485.71  5295.8 1485.94
  5298.6 1488.10  5312.6 1493.26  5318.2 1493.16  5323.8 1494.65  5326.6 1494.65
#Mann=4,-1,0
  4879.4    0.12       0  4964.6    0.07       0  5003.2    0.05       0
  5007.2    0.07       0
Bank Sta=5003.2,5007.2
Exp/Cntr=0.3,0.1

Type RM Length L Ch R = 1,524,0,0,0
BEGIN DESCRIPTION:
Stream0041_DS 1.0
END DESCRIPTION:
XS GIS Cut Line= 3
      2006699.45     13908915.16      2006575.00     13908775.00
      2006039.71     13908788.55
#Sta/Elev= 30
  4808.4 1498.26  4833.2 1497.28  4861.6 1493.91  4875.5 1490.71  4896.7 1484.10
  4953.6 1473.18  4960.3 1469.45  4967.8 1467.95  4974.5 1462.87  4982.0 1462.10
  4988.7 1457.50  4998.3 1457.61  5003.8 1455.18  5004.1 1454.68  5007.8 1455.18
  5015.8 1457.87  5025.8 1458.38  5055.9 1459.18  5116.7 1458.56  5155.9 1460.59
  5175.9 1460.81  5192.1 1463.97  5197.1 1463.66  5245.9 1467.99  5386.0 1470.97
  5406.0 1472.60  5426.0 1478.03  5456.0 1490.95  5466.0 1493.93  5531.3 1500.41
#Mann=4,-1,0
  4808.4    0.12       0  5003.8    0.05       0  5007.8    0.12       0
  5116.7    0.07       0
Bank Sta=5003.8,5007.8
Exp/Cntr=0.3,0.1

Chan Stop Cuts=-1