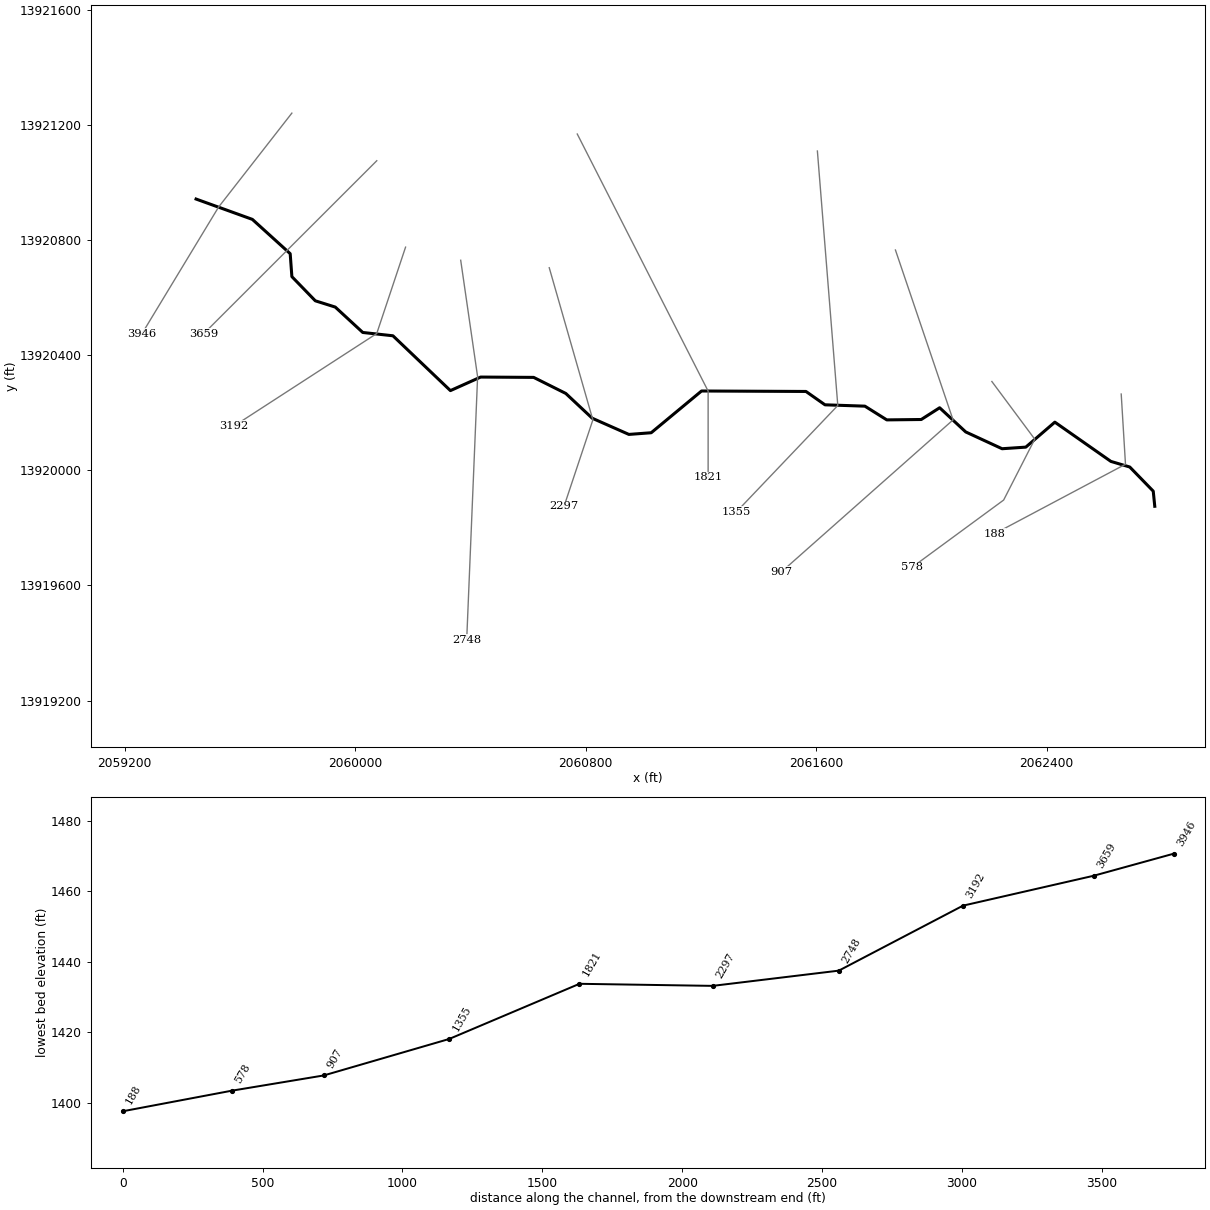
--- Stream0042_DS.prj (project) ---

Proj Title=Stream0042_DS Base Level Engineering
Current Plan=p01
Default Exp/Contr=0.3,0.1
English Units
Geom File=g01
Flow File=f01
Plan File=p01
BEGIN DESCRIPTION:
Stream0042_DS
END DESCRIPTION:

--- Stream0042_DS.p01 (plan) ---

Plan Title=Multiple Run
Short Identifier=Multiple
Geom File=g01
Flow File=f01
Subcritical Flow
K Sum by GR= 0
Std Step Tol= 0.01
Critical Tol= 0.01
Num of Std Step Trials= 20
Max Error Tol= 0.3
Flow Tol Ratio= 0.001
Split Flow NTrial= 30
Split Flow Tol= 0.02
Split Flow Ratio= 0.02
Log Output Level= 0
Friction Slope Method= 1
Unsteady Friction Slope Method= 2
Unsteady Bridges Friction Slope Method= 1
Parabolic Critical Depth
Global Vel Dist=  1 , 1 , 1
Global Log Level= 0
CheckData=True
Encroach Param= -1, 0, 0, 0
BEGIN DESCRIPTION:
Multiple Run
END DESCRIPTION:

--- Stream0042_DS.f01 (steady flow) ---

Flow Title=Multiple
Number of Profiles=7
Profile Names=10-year,25-year,50-year,1pct_min,100-year,1pct_plu,500-year
River Rch & RM= Stream0042_DS,Reach-1,3946
     461     837    1216     858    1711    3414    3337
River Rch & RM= Stream0042_DS,Reach-1,3659
     945    1626    2287    1565    3123    6232    5764
Boundary for River Rch & Prof#=Stream0042_DS,Reach-1,1
Up Type=0
Dn Type=3
Dn Slope=0.005
Boundary for River Rch & Prof#=Stream0042_DS,Reach-1,2
Up Type=0
Dn Type=3
Dn Slope=0.005
Boundary for River Rch & Prof#=Stream0042_DS,Reach-1,3
Up Type=0
Dn Type=3
Dn Slope=0.005
Boundary for River Rch & Prof#=Stream0042_DS,Reach-1,4
Up Type=0
Dn Type=3
Dn Slope=0.005
Boundary for River Rch & Prof#=Stream0042_DS,Reach-1,5
Up Type=0
Dn Type=3
Dn Slope=0.005
Boundary for River Rch & Prof#=Stream0042_DS,Reach-1,6
Up Type=0
Dn Type=3
Dn Slope=0.005
Boundary for River Rch & Prof#=Stream0042_DS,Reach-1,7
Up Type=0
Dn Type=3
Dn Slope=0.005

--- Stream0042_DS.g01 (geometry) ---

Geom Title=Existing Conditions

River Reach=Stream0042_DS,Reach-1
Reach XY= 30
      2059447.97     13920942.02      2059643.35     13920871.37
      2059774.61     13920752.27      2059780.45     13920672.54
      2059861.76     13920588.62      2059931.04     13920566.82
      2060026.50     13920478.63      2060131.17     13920467.14
      2060330.62     13920276.73      2060435.50     13920323.76
      2060619.48     13920322.65      2060731.05     13920266.84
      2060822.71     13920180.84      2060950.00     13920124.58
      2061027.43     13920130.40      2061202.12     13920275.37
      2061564.50     13920273.78      2061630.53     13920227.39
      2061769.06     13920222.73      2061845.04     13920175.05
      2061964.56     13920176.38      2062028.41     13920217.19
      2062118.94     13920133.18      2062245.10     13920074.89
      2062327.43     13920080.43      2062428.23     13920167.16
      2062622.72     13920030.87      2062688.24     13920011.39
      2062769.70     13919927.54      2062775.00     13919875.00

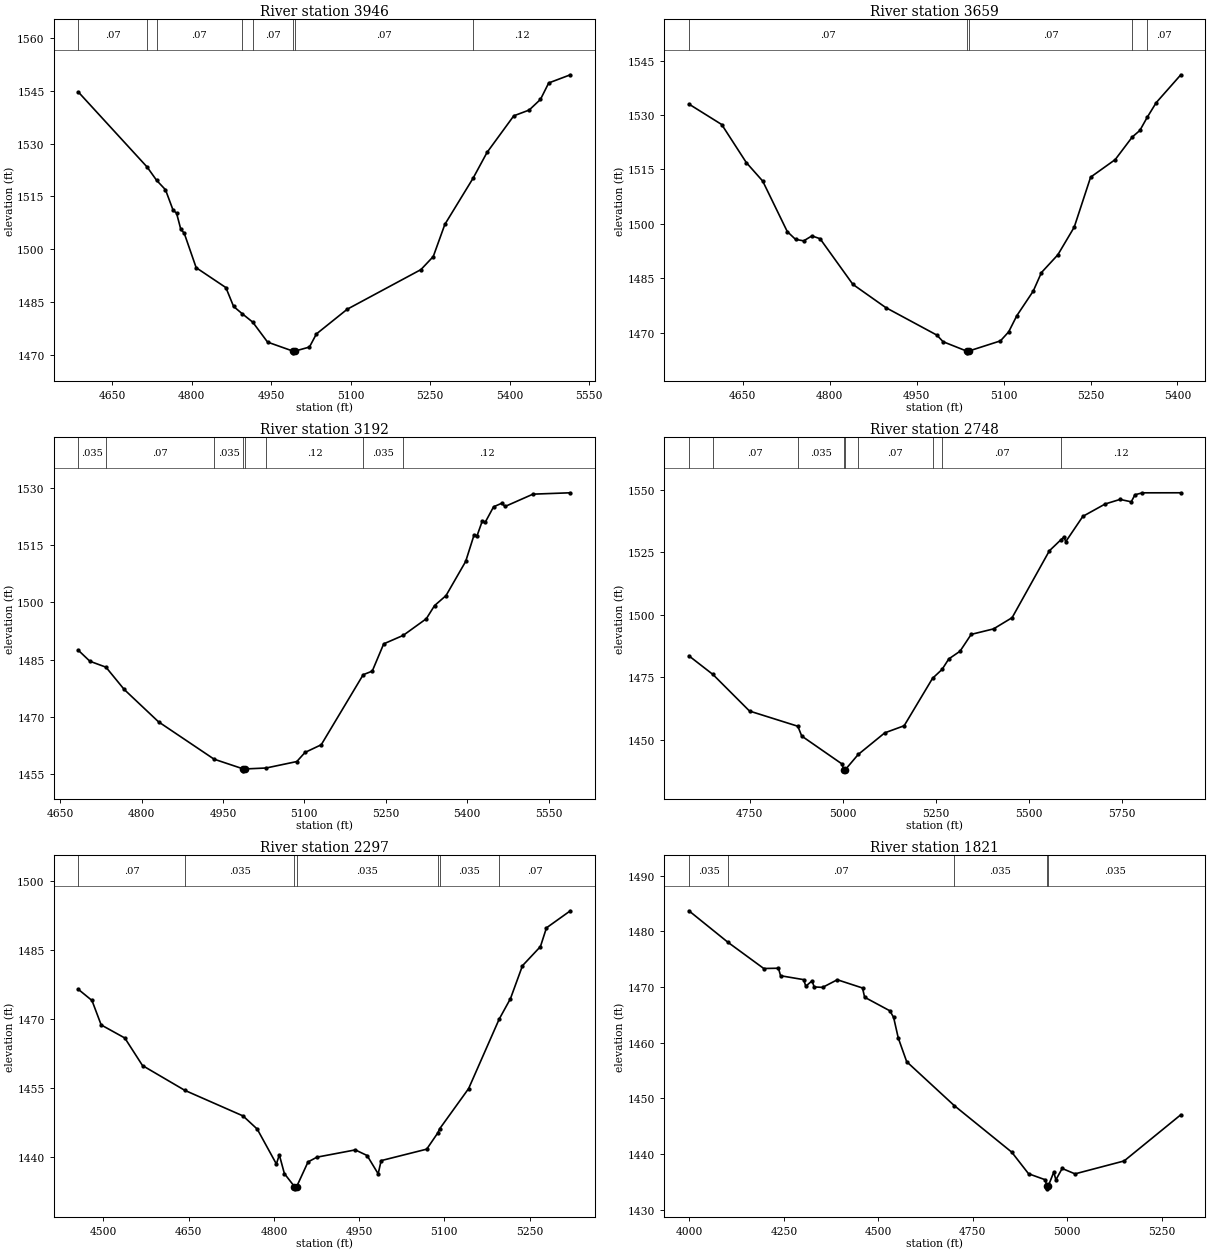
Type RM Length L Ch R = 1,3946,287,287,287
BEGIN DESCRIPTION:
Stream0042_DS 8.0
END DESCRIPTION:
XS GIS Cut Line= 3
      2059780.37     13921240.39      2059526.12     13920914.19
      2059259.68     13920473.57
#Sta/Elev= 30
  4586.0 1544.56  4715.7 1523.32  4733.5 1519.57  4750.3 1516.89  4764.8 1511.03
  4771.1 1510.31  4779.2 1505.67  4785.6 1504.60  4808.2 1494.80  4864.3 1489.16
  4878.8 1483.82  4895.0 1481.77  4914.9 1479.38  4943.0 1473.71  4990.7 1471.17
  4991.0 1470.67  4994.7 1471.17  5022.0 1472.31  5035.1 1476.02  5093.3 1483.03
  5232.4 1494.26  5255.7 1497.96  5277.6 1507.08  5331.0 1520.20  5357.2 1527.47
  5407.7 1537.85  5436.7 1539.48  5458.1 1542.51  5473.6 1547.16  5514.5 1549.48
#Mann=8,-1,0
  4586.0    0.07       0  4715.7    0.12       0  4733.5    0.07       0
  4895.0    0.12       0  4914.9    0.07       0  4990.7    0.05       0
  4994.7    0.07       0  5331.0    0.12       0
Bank Sta=4990.7,4994.7
Exp/Cntr=0.3,0.1

Type RM Length L Ch R = 1,3659,467,467,467
BEGIN DESCRIPTION:
Stream0042_DS 7.0
END DESCRIPTION:
XS GIS Cut Line= 3
      2060075.03     13921075.03      2059775.00     13920775.00
      2059474.98     13920474.98
#Sta/Elev= 30
  4557.2 1533.04  4613.8 1527.39  4656.2 1516.90  4684.5 1511.79  4726.9 1497.85
  4741.1 1495.71  4755.2 1495.29  4769.4 1496.66  4783.5 1495.88  4840.1 1483.28
  4896.7 1476.89  4985.0 1469.28  4995.7 1467.46  5036.1 1464.89  5036.3 1464.39
  5040.1 1464.89  5094.6 1467.69  5108.8 1470.17  5122.9 1474.64  5151.2 1481.43
  5165.4 1486.55  5193.6 1491.43  5221.9 1499.07  5250.2 1512.87  5292.6 1517.71
  5322.1 1523.96  5335.1 1525.75  5347.9 1529.40  5363.3 1533.42  5405.8 1541.12
#Mann=5,-1,0
  4557.2    0.07       0  5036.1    0.05       0  5040.1    0.07       0
  5322.1    0.12       0  5347.9    0.07       0
Bank Sta=5036.1,5040.1
Exp/Cntr=0.3,0.1

Type RM Length L Ch R = 1,3192,444,444,444
BEGIN DESCRIPTION:
Stream0042_DS 6.0
END DESCRIPTION:
XS GIS Cut Line= 3
      2060175.00     13920774.99      2060075.00     13920475.00
      2059579.90     13920153.96
#Sta/Elev= 30
  4683.8 1487.41  4704.9 1484.57  4734.5 1483.02  4768.1 1477.19  4831.4 1468.72
  4933.7 1458.96  4987.5 1456.41  4987.7 1455.91  4991.5 1456.41  5029.5 1456.65
  5086.1 1458.34  5101.2 1460.72  5131.1 1462.73  5208.4 1481.05  5225.1 1481.99
  5246.2 1489.12  5282.2 1491.34  5324.7 1495.69  5339.9 1499.13  5361.0 1501.74
  5397.2 1510.67  5412.4 1517.48  5418.3 1517.44  5427.5 1521.12  5433.5 1520.99
  5448.6 1524.96  5463.8 1525.90  5469.8 1525.05  5521.2 1528.27  5590.1 1528.63
#Mann=8,-1,0
  4683.8   0.035       0  4734.5    0.07       0  4933.7   0.035       0
  4987.5   0.035       0  4991.5   0.035       0  5029.5    0.12       0
  5208.4   0.035       0  5282.2    0.12       0
Bank Sta=4987.5,4991.5
Exp/Cntr=0.3,0.1

Type RM Length L Ch R = 1,2748,451,451,451
BEGIN DESCRIPTION:
Stream0042_DS 5.0
END DESCRIPTION:
XS GIS Cut Line= 3
      2060366.33     13920729.47      2060425.00     13920325.00
      2060387.16     13919411.78
#Sta/Elev= 30
  4586.6 1483.56  4651.2 1476.09  4749.6 1461.43  4879.5 1455.34  4890.0 1451.41
  4997.8 1440.27  5003.3 1437.97  5003.6 1437.47  5007.3 1437.97  5041.8 1444.02
  5113.2 1452.69  5165.4 1455.54  5241.7 1474.54  5267.3 1478.11  5285.5 1482.33
  5315.6 1485.40  5345.6 1492.15  5405.7 1494.35  5455.7 1498.86  5555.8 1525.64
  5587.4 1530.15  5595.0 1531.12  5600.0 1529.33  5645.9 1539.45  5705.9 1544.41
  5745.9 1546.24  5776.0 1545.28  5786.0 1548.11  5806.0 1548.88  5909.3 1548.90
#Mann=9,-1,0
  4586.6   0.035       0  4651.2    0.07       0  4879.5   0.035       0
  5003.3   0.035       0  5007.3   0.035       0  5041.8    0.07       0
  5241.7   0.035       0  5267.3    0.07       0  5587.4    0.12       0
Bank Sta=5003.3,5007.3
Exp/Cntr=0.3,0.1

Type RM Length L Ch R = 1,2297,476,476,476
BEGIN DESCRIPTION:
Stream0042_DS 4.0
END DESCRIPTION:
XS GIS Cut Line= 3
      2060673.61     13920703.46      2060825.00     13920175.00
      2060725.02     13919875.05
#Sta/Elev= 30
  4456.0 1476.47  4479.8 1474.07  4496.0 1468.76  4537.6 1465.92  4568.8 1459.93
  4643.2 1454.55  4745.7 1448.99  4770.7 1446.13  4804.4 1438.55  4809.6 1440.53
  4818.5 1436.46  4836.2 1433.65  4836.5 1433.15  4840.2 1433.65  4860.1 1438.99
  4875.7 1440.03  4943.3 1441.61  4964.1 1440.39  4983.6 1436.41  4988.8 1439.28
  5069.0 1441.77  5088.7 1445.33  5091.8 1446.19  5142.8 1454.93  5196.5 1470.00
  5216.5 1474.49  5237.6 1481.63  5269.2 1485.78  5279.8 1489.85  5321.9 1493.56
#Mann=7,-1,0
  4456.0    0.07       0  4643.2   0.035       0  4836.2   0.035       0
  4840.2   0.035       0  5088.7    0.07       0  5091.8   0.035       0
  5196.5    0.07       0
Bank Sta=4836.2,4840.2
Exp/Cntr=0.3,0.1

Type RM Length L Ch R = 1,1821,466,466,466
BEGIN DESCRIPTION:
Stream0042_DS 3.0
END DESCRIPTION:
XS GIS Cut Line= 3
      2060770.85     13921167.81      2061225.00     13920275.00
      2061225.00     13919974.98
#Sta/Elev= 30
  3998.8 1483.69  4102.7 1478.00  4196.9 1473.32  4235.7 1473.37  4241.4 1472.02
  4302.5 1471.32  4308.1 1470.14  4324.7 1471.10  4330.3 1470.01  4352.6 1469.93
  4391.5 1471.30  4458.2 1469.82  4463.8 1468.16  4530.6 1465.72  4540.5 1464.54
  4552.8 1460.84  4575.1 1456.58  4700.9 1448.70  4853.1 1440.33  4897.6 1436.45
  4942.1 1435.36  4945.7 1434.24  4945.9 1433.74  4949.7 1434.24  4964.3 1436.74
  4969.9 1435.36  4986.5 1437.40  5020.5 1436.43  5150.5 1438.75  5300.5 1447.05
#Mann=5,-1,0
  3998.8   0.035       0  4102.7    0.07       0  4700.9   0.035       0
  4945.7   0.035       0  4949.7   0.035       0
Bank Sta=4945.7,4949.7
Exp/Cntr=0.3,0.1

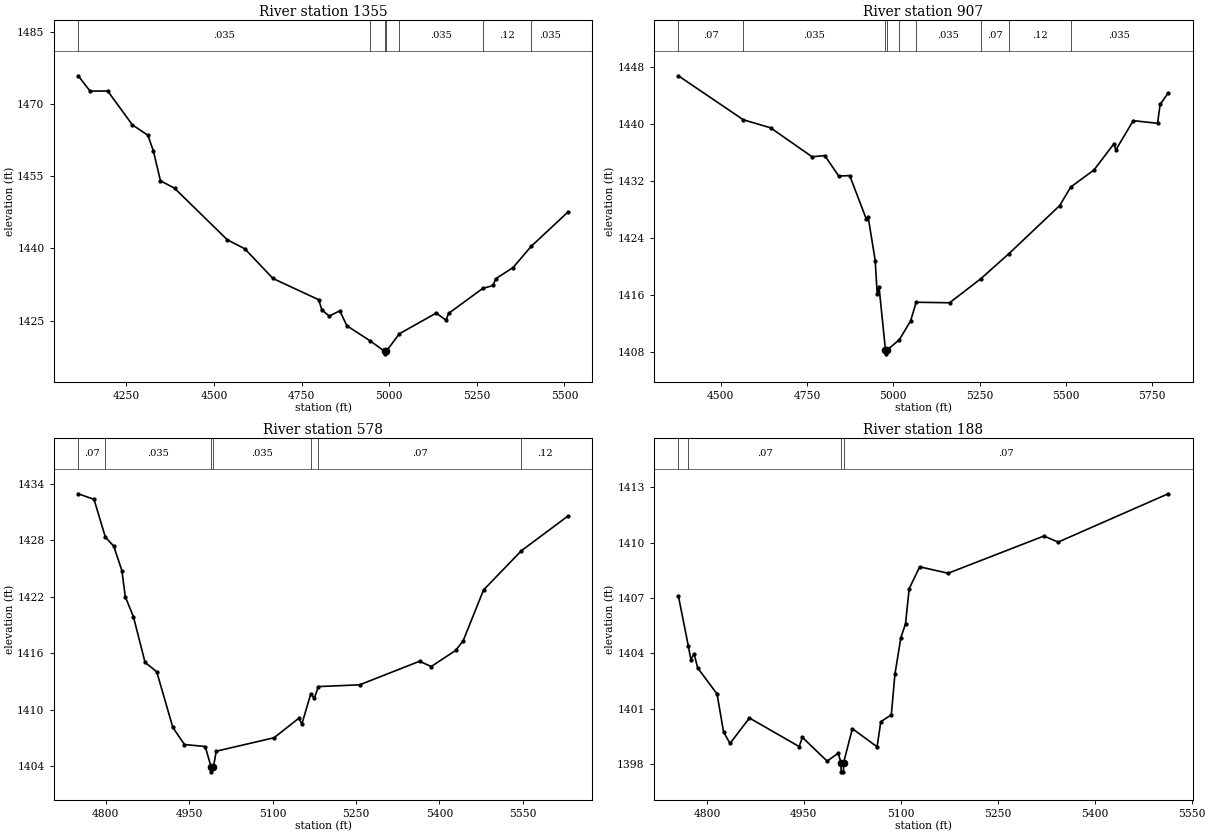
Type RM Length L Ch R = 1,1355,448,448,448
BEGIN DESCRIPTION:
Stream0042_DS 2.0
END DESCRIPTION:
XS GIS Cut Line= 3
      2061604.17     13921108.83      2061675.00     13920225.00
      2061322.90     13919855.30
#Sta/Elev= 30
  4112.9 1475.84  4146.8 1472.65  4197.0 1472.68  4267.2 1465.66  4311.7 1463.47
  4327.4 1460.21  4347.5 1454.02  4387.6 1452.49  4538.1 1441.78  4588.2 1439.90
  4668.5 1433.73  4798.9 1429.32  4807.9 1427.22  4829.0 1425.92  4859.1 1427.02
  4879.2 1423.92  4946.1 1420.76  4987.5 1418.58  4987.8 1418.08  4991.5 1418.58
  5028.8 1422.24  5134.0 1426.54  5162.3 1425.08  5169.2 1426.47  5266.7 1431.66
  5296.6 1432.28  5303.5 1433.66  5353.3 1436.00  5405.1 1440.41  5510.1 1447.55
#Mann=7,-1,0
  4112.9   0.035       0  4946.1    0.12       0  4987.5    0.05       0
  4991.5    0.12       0  5028.8   0.035       0  5266.7    0.12       0
  5405.1   0.035       0
Bank Sta=4987.5,4991.5
Exp/Cntr=0.3,0.1

Type RM Length L Ch R = 1,907,329,329,329
BEGIN DESCRIPTION:
Stream0042_DS 1.0
END DESCRIPTION:
XS GIS Cut Line= 3
      2061875.02     13920765.03      2062075.00     13920175.00
      2061479.56     13919647.33
#Sta/Elev= 30
  4377.3 1446.77  4565.6 1440.59  4644.3 1439.47  4764.7 1435.40  4801.4 1435.57
  4841.9 1432.69  4873.6 1432.76  4921.8 1426.64  4927.0 1426.97  4947.5 1420.82
  4953.2 1416.10  4958.5 1417.17  4977.2 1408.24  4977.4 1407.74  4981.2 1408.24
  5017.3 1409.72  5050.1 1412.38  5066.1 1414.98  5163.0 1414.91  5253.0 1418.27
  5335.0 1421.81  5481.6 1428.54  5514.0 1431.16  5581.2 1433.55  5638.0 1437.17
  5644.7 1436.39  5694.9 1440.47  5765.2 1440.10  5772.7 1442.74  5795.9 1444.36
#Mann=9,-1,0
  4377.3    0.07       0  4565.6   0.035       0  4977.2   0.035       0
  4981.2   0.035       0  5017.3    0.12       0  5066.1   0.035       0
  5253.0    0.07       0  5335.0    0.12       0  5514.0   0.035       0
Bank Sta=4977.2,4981.2
Exp/Cntr=0.3,0.1

Type RM Length L Ch R = 1,578,390,390,390
BEGIN DESCRIPTION:
Stream0042_DS 0.5
END DESCRIPTION:
XS GIS Cut Line= 4
      2062209.70     13920308.31      2062358.52     13920108.06
      2062250.57     13919896.67      2061933.03     13919663.35
#Sta/Elev= 30
  4750.5 1432.93  4778.9 1432.34  4799.3 1428.33  4814.4 1427.37  4829.0 1424.78
  4835.2 1421.99  4849.8 1419.88  4870.7 1415.03  4891.7 1414.04  4920.7 1408.12
  4941.6 1406.31  4978.9 1406.10  4989.6 1403.91  4989.9 1403.41  4993.6 1403.91
  4998.8 1405.60  5102.8 1407.03  5147.2 1409.10  5152.8 1408.49  5168.9 1411.72
  5175.1 1411.21  5182.4 1412.46  5256.7 1412.65  5364.5 1415.15  5385.4 1414.59
  5429.3 1416.30  5442.8 1417.32  5479.5 1422.72  5547.5 1426.88  5631.4 1430.57
#Mann=7,-1,0
  4750.5    0.07       0  4799.3   0.035       0  4989.6   0.035       0
  4993.6   0.035       0  5168.9    0.12       0  5182.4    0.07       0
  5547.5    0.12       0
Bank Sta=4989.6,4993.6
Exp/Cntr=0.3,0.1

Type RM Length L Ch R = 1,188,0,0,0
BEGIN DESCRIPTION:
Stream0042_DS 0.0
END DESCRIPTION:
XS GIS Cut Line= 3
      2062658.55     13920264.78      2062673.36     13920021.03
      2062219.77     13919780.12
#Sta/Elev= 30
  4755.8 1407.12  4771.3 1404.38  4775.2 1403.66  4780.2 1403.97  4785.6 1403.21
  4815.7 1401.79  4825.7 1399.74  4835.7 1399.11  4865.8 1400.49  4942.7 1398.94
  4947.7 1399.44  4986.0 1398.15  5003.0 1398.58  5007.5 1398.07  5007.7 1397.57
  5011.2 1397.57  5011.5 1398.07  5025.0 1399.91  5063.3 1398.93  5069.0 1400.29
  5085.3 1400.66  5090.9 1402.87  5100.1 1404.85  5107.3 1405.60  5112.9 1407.50
  5129.2 1408.69  5173.2 1408.34  5321.4 1410.36  5343.4 1410.03  5513.6 1412.65
#Mann=4,-1,0
  4755.8    0.12       0  4771.3    0.07       0  5007.5    0.05       0
  5011.5    0.07       0
Bank Sta=5007.5,5011.5
Exp/Cntr=0.3,0.1

Chan Stop Cuts=-1