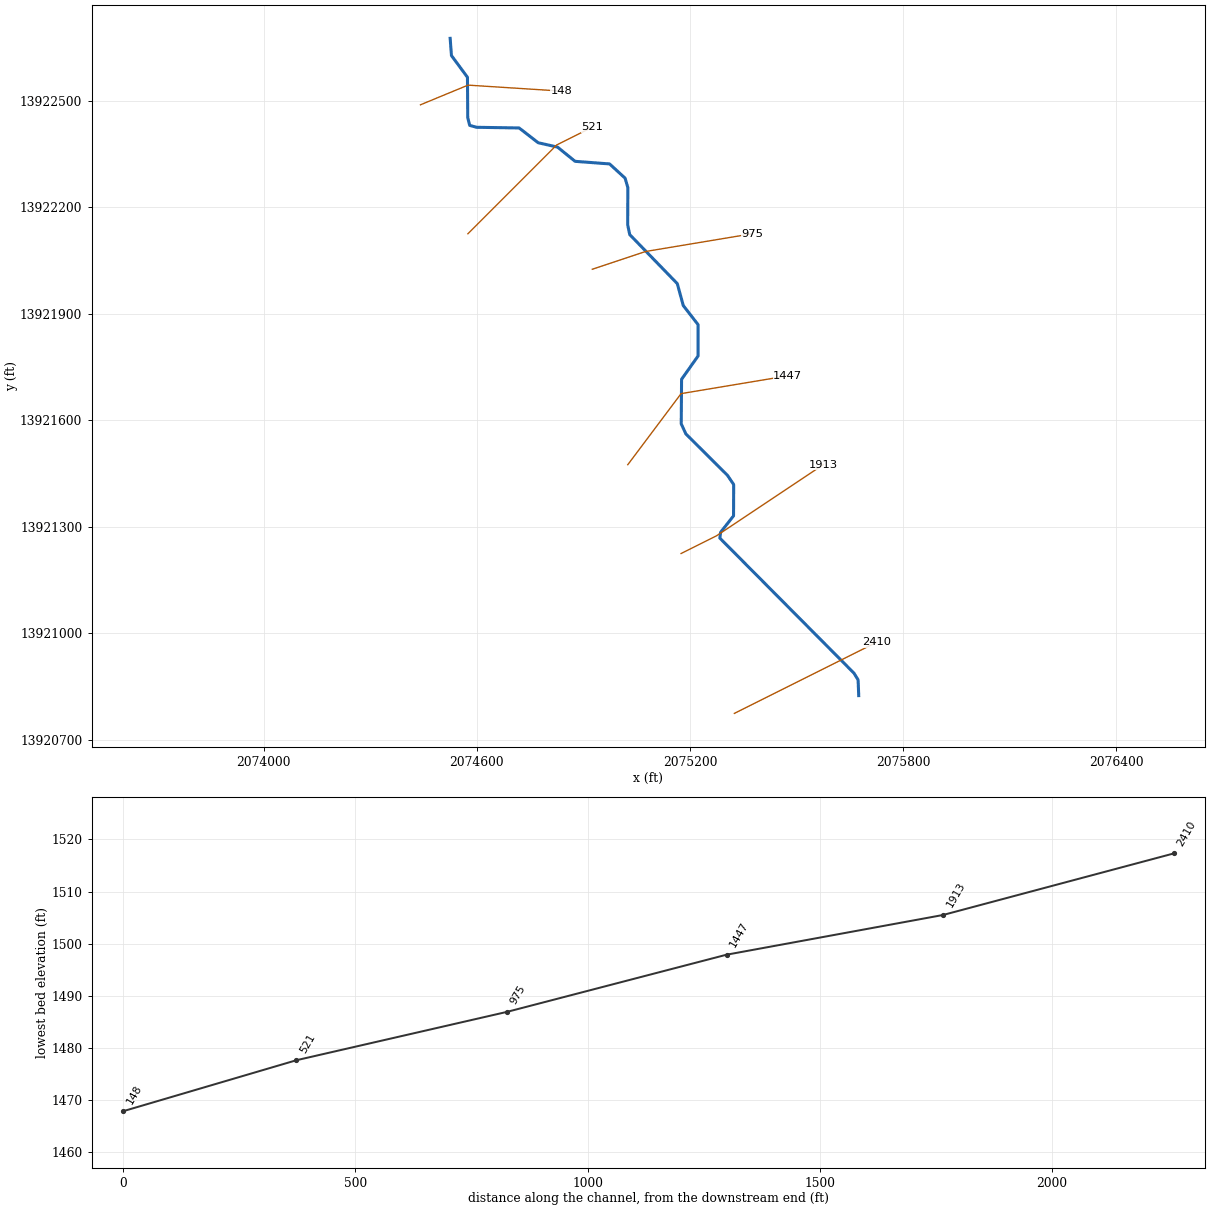
--- Stream0043_DS.prj (project) ---

Proj Title=Stream0043_DS Base Level Engineering
Current Plan=p01
Default Exp/Contr=0.3,0.1
English Units
Geom File=g01
Flow File=f01
Plan File=p01
Y Axis Title=Elevation
X Axis Title(PF)=Main Channel Distance
X Axis Title(XS)=Station
BEGIN DESCRIPTION:
Stream0043_DS
END DESCRIPTION:
DSS Export Rating Curves= 0
DSS Export Rating Curve Sorted= 0
DSS Export Volume Flow Curves= 0
DXF OffsetX= 0
DXF OffsetY= 0
DXF ScaleX= 1
DXF ScaleY= 10

--- Stream0043_DS.p01 (plan) ---

Plan Title=Multiple Run
Short Identifier=Multiple
Geom File=g01
Flow File=f01
Subcritical Flow
K Sum by GR= 0
Std Step Tol= 0.01
Critical Tol= 0.01
Num of Std Step Trials= 20
Max Error Tol= 0.3
Flow Tol Ratio= 0.001
Split Flow NTrial= 30
Split Flow Tol= 0.02
Split Flow Ratio= 0.02
Log Output Level= 0
Friction Slope Method= 1
Unsteady Friction Slope Method= 2
Unsteady Bridges Friction Slope Method= 1
Parabolic Critical Depth
Global Vel Dist=  1 , 1 , 1
Global Log Level= 0
CheckData=True
Encroach Param= -1, 0, 0, 0
BEGIN DESCRIPTION:
Multiple Run
END DESCRIPTION:

--- Stream0043_DS.f01 (steady flow) ---

Flow Title=Multiple
Number of Profiles=7
Profile Names=10-year,25-year,50-year,1pct_min,100-year,1pct_plu,500-year
River Rch & RM= Stream0043_DS,Reach-1,2410
     791    1340    1866    1264    2522    5033    4562
Boundary for River Rch & Prof#=Stream0043_DS,Reach-1,1
Up Type=0
Dn Type=3
Dn Slope=0.005
Boundary for River Rch & Prof#=Stream0043_DS,Reach-1,2
Up Type=0
Dn Type=3
Dn Slope=0.005
Boundary for River Rch & Prof#=Stream0043_DS,Reach-1,3
Up Type=0
Dn Type=3
Dn Slope=0.005
Boundary for River Rch & Prof#=Stream0043_DS,Reach-1,4
Up Type=0
Dn Type=3
Dn Slope=0.005
Boundary for River Rch & Prof#=Stream0043_DS,Reach-1,5
Up Type=0
Dn Type=3
Dn Slope=0.005
Boundary for River Rch & Prof#=Stream0043_DS,Reach-1,6
Up Type=0
Dn Type=3
Dn Slope=0.005
Boundary for River Rch & Prof#=Stream0043_DS,Reach-1,7
Up Type=0
Dn Type=3
Dn Slope=0.005

--- Stream0043_DS.g01 (geometry) ---

Geom Title=Existing Conditions
Program Version=4.10

River Reach=Stream0043_DS   ,Reach-1
Reach XY= 30
        2075675.       13920825.       2075673.2     13920869.33
      2075661.53     13920888.27      2075284.13     13921268.26
      2075286.33     13921284.85      2075322.63     13921330.89
      2075323.03     13921419.11      2075305.42     13921445.15
      2075188.37     13921561.68      2075175.37     13921590.16
      2075176.37     13921715.33      2075222.83     13921780.98
      2075222.86     13921869.03      2075181.15     13921922.83
      2075164.24     13921984.68      2075030.47     13922122.55
      2075024.73     13922149.89      2075025.07     13922255.12
      2075017.32     13922281.52      2074973.75     13922321.49
      2074876.59     13922328.83      2074827.18     13922368.89
      2074772.82     13922381.12      2074719.06     13922422.75
      2074599.59     13922424.61      2074580.01     13922430.01
       2074574.5     13922451.76      2074573.71     13922565.36
      2074528.65     13922626.51        2074525.       13922675.

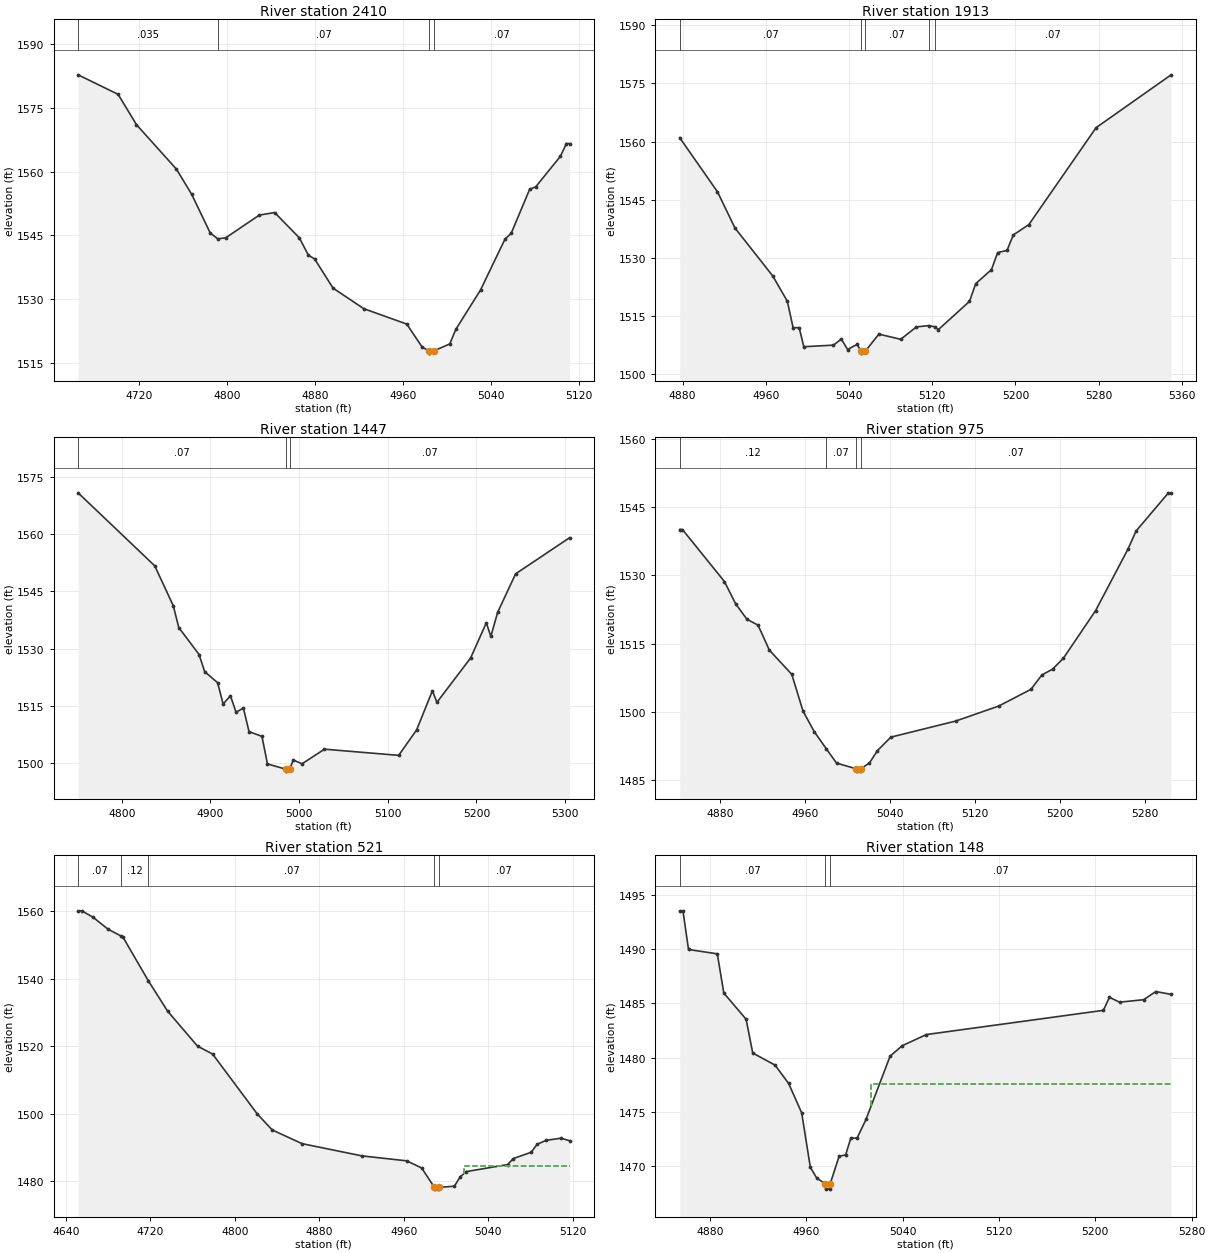
Type RM Length L Ch R = 1 ,2410    ,497,497,497
BEGIN DESCRIPTION:
Stream0043_DS 5.0
END DESCRIPTION:
XS GIS Cut Line= 3
      2075324.98     13920774.99        2075625.       13920925.
      2075724.97     13920974.99
#Sta/Elev= 30
  4664.4 1582.82  4700.8 1578.23  4717.5 1571.09  4753.9 1560.61  4767.8 1554.67
  4784.6  1545.6  4791.4 1544.22  4798.6 1544.43  4829.3  1549.8  4843.3  1550.4
  4865.7 1544.45    4874 1540.35  4879.6 1539.49  4896.4 1532.61  4924.4 1527.76
  4963.5 1524.14  4977.5 1518.72  4983.9  1517.8  4984.1  1517.3  4987.9  1517.8
  5002.6 1519.46  5008.2 1522.93  5030.6 1532.16  5052.9 1544.15  5058.5 1545.49
  5075.3 1555.86  5080.9 1556.47  5103.2  1563.6  5108.8 1566.64  5111.6 1566.64
#Mann= 4 ,-1 , 0
  4664.4    .035       0  4791.4     .07       0  4983.9     .05       0
  4987.9     .07       0
Bank Sta=4983.9,4987.9
XS Rating Curve= 0 ,0
Exp/Cntr=0.3,0.1

Type RM Length L Ch R = 1 ,1913    ,466,466,466
BEGIN DESCRIPTION:
Stream0043_DS 4.0
END DESCRIPTION:
XS GIS Cut Line= 3
      2075175.02     13921225.01        2075275.       13921275.
      2075574.97     13921474.98
#Sta/Elev= 30
  4877.3 1561.02  4913.6 1547.08  4930.4 1537.75  4966.7  1525.4  4980.7 1518.89
  4986.3 1512.06  4992.1 1512.06  4996.6 1507.15  5025.1 1507.56  5032.6 1509.13
  5038.7 1506.43  5047.7 1507.75  5051.7    1506  5051.9  1505.5  5055.7    1506
  5068.7  1510.4  5089.7 1509.06  5104.8 1512.26  5116.8  1512.6  5122.8 1512.27
  5125.8 1511.54  5155.8 1518.83  5161.8  1523.4  5176.9 1527.01  5182.9 1531.42
  5191.9 1531.97  5197.9 1535.96  5212.9 1538.64  5277.5 1563.61  5349.6 1577.23
#Mann= 5 ,-1 , 0
  4877.3     .07       0  5051.7     .05       0  5055.7     .07       0
  5116.8    .035       0  5122.8     .07       0
Bank Sta=5051.7,5055.7
XS Rating Curve= 0 ,0
Exp/Cntr=0.3,0.1

Type RM Length L Ch R = 1 ,1447    ,472,472,472
BEGIN DESCRIPTION:
Stream0043_DS 3.0
END DESCRIPTION:
XS GIS Cut Line= 3
      2075025.02     13921475.03        2075175.       13921675.
        2075475.       13921725.
#Sta/Elev= 30
  4750.8 1570.79  4837.2 1551.67  4858.1 1541.22  4864.3 1535.51  4887.2 1528.44
  4893.5 1523.95  4908.1 1521.06  4914.3 1515.48  4922.6 1517.62  4928.9 1513.32
  4937.2 1514.41  4943.5 1508.25  4958.1 1506.99  4964.3 1499.77  4985.2 1498.39
  4985.5 1497.89  4989.2 1498.39  4993.5  1500.8  5003.3 1499.81  5028.6 1503.64
  5112.3 1502.02  5132.6 1508.73  5150.3 1518.94  5155.4 1515.91  5193.4 1527.53
  5211.1 1536.75  5216.2 1533.17  5223.8 1539.45  5244.1 1549.56  5304.9 1559.02
#Mann= 3 ,-1 , 0
  4750.8     .07       0  4985.2     .05       0  4989.2     .07       0
Bank Sta=4985.2,4989.2
XS Rating Curve= 0 ,0
Exp/Cntr=0.3,0.1

Type RM Length L Ch R = 1 ,975     ,454,454,454
BEGIN DESCRIPTION:
Stream0043_DS 2.0
END DESCRIPTION:
XS GIS Cut Line= 3
      2074925.04     13922025.01        2075075.       13922075.
      2075374.99       13922125.
#Sta/Elev= 30
  4842.2 1540.05  4844.8 1540.05  4884.3 1528.61  4894.9 1523.69  4905.4 1520.34
  4915.9 1519.03  4926.5 1513.55  4947.6 1508.23  4958.1  1500.2  4968.7 1495.64
  4979.9 1491.92  4989.7 1488.72  5008.4 1487.45  5008.7 1486.95  5012.2 1486.95
  5012.4 1487.45  5020.6 1488.72  5028.2 1491.46  5040.8 1494.42  5101.7 1497.95
  5142.2 1501.25  5172.6 1504.93  5182.8 1508.08  5192.9 1509.36    5203 1511.74
  5233.4 1522.24  5263.9 1535.79  5271.5 1539.74  5301.9 1548.12  5304.4 1548.12
#Mann= 4 ,-1 , 0
  4842.2     .12       0  4979.9     .07       0  5008.4     .05       0
  5012.4     .07       0
Bank Sta=5008.4,5012.4
XS Rating Curve= 0 ,0
Exp/Cntr=0.3,0.1

Type RM Length L Ch R = 1 ,521     ,373,373,373
BEGIN DESCRIPTION:
Stream0043_DS 1.0
END DESCRIPTION:
XS GIS Cut Line= 3
      2074575.01     13922125.01        2074825.       13922375.
      2074924.96     13922424.98
#Sta/Elev= 30
  4651.5 1560.11    4655 1560.11  4665.6 1558.22  4679.8 1554.68  4691.9 1552.69
  4693.9 1552.36    4718 1539.38  4736.3 1530.37  4764.6 1520.02  4778.8  1517.7
  4821.2 1499.92  4835.3  1495.2  4863.6 1491.14  4920.2 1487.52  4962.6 1486.05
  4976.8 1483.94  4988.9 1478.17  4989.1 1477.67  4992.6 1477.67  4992.9 1478.17
  5007.8 1478.55  5013.4 1481.36    5019 1482.86  5058.1 1484.94  5063.7 1486.74
  5080.5 1488.59  5086.1 1490.95  5094.5  1492.1  5108.5 1492.76  5116.8 1492.04
#Mann= 5 ,-1 , 0
  4651.5     .07       0  4691.9     .12       0    4718     .07       0
  4988.9     .05       0  4992.9     .07       0
#XS Ineff= 2 , 0
       0                 5016.84       0 1484.58
Permanent Ineff=
       F       F
Bank Sta=4988.9,4992.9
XS Rating Curve= 0 ,0
Exp/Cntr=0.3,0.1

Type RM Length L Ch R = 1 ,148     ,0,0,0
BEGIN DESCRIPTION:
Stream0043_DS 0.0
END DESCRIPTION:
XS GIS Cut Line= 3
      2074441.45     13922487.93      2074575.36      13922543.3
      2074837.72     13922526.52
#Sta/Elev= 30
  4855.1 1493.52  4857.8 1493.52  4862.4 1489.96  4886.3 1489.56  4891.7 1485.95
  4910.2 1483.54  4915.7 1480.43  4934.2 1479.32  4945.5 1477.63  4956.3 1474.93
  4963.5 1469.91  4968.9  1468.9    4976  1468.4  4976.2  1467.9  4979.7  1467.9
    4980  1468.4  4987.4 1470.93  4992.8 1471.05  4997.1  1472.6  5002.3  1472.6
  5009.7 1474.32  5029.7 1480.14  5039.7  1481.1  5059.8 1482.13  5206.7 1484.36
  5211.7 1485.56  5220.1 1485.11  5240.1 1485.34  5250.2 1486.09  5262.9 1485.83
#Mann= 3 ,-1 , 0
  4855.1     .07       0    4976     .05       0    4980     .07       0
#XS Ineff= 2 , 0
       0                    5014       0 1477.56
Permanent Ineff=
       F       F
Bank Sta=4976,4980
XS Rating Curve= 0 ,0
Exp/Cntr=0.3,0.1

Chan Stop Cuts=-1
Use User Specified Reach Order=0
Composite Channel Slope=5