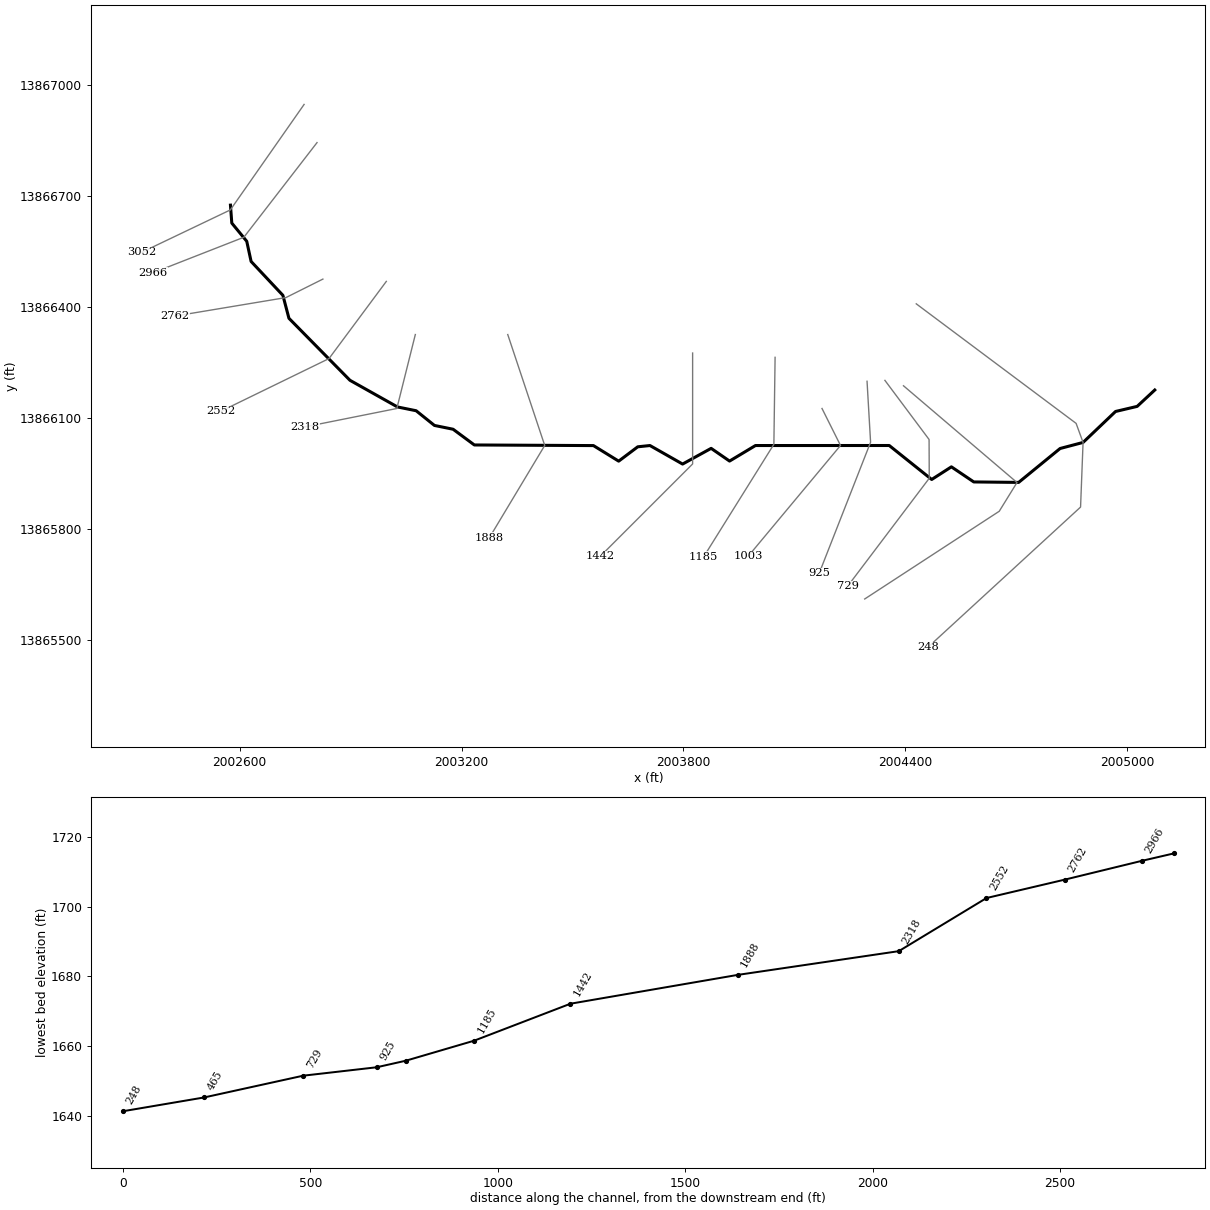
--- Stream0044_DS.prj (project) ---

Proj Title=Stream0044_DS Base Level Engineering
Current Plan=p01
Default Exp/Contr=0.3,0.1
English Units
Geom File=g01
Flow File=f01
Plan File=p01
BEGIN DESCRIPTION:
Stream0044_DS
END DESCRIPTION:

--- Stream0044_DS.p01 (plan) ---

Plan Title=Multiple Run
Short Identifier=Multiple
Geom File=g01
Flow File=f01
Subcritical Flow
K Sum by GR= 0
Std Step Tol= 0.01
Critical Tol= 0.01
Num of Std Step Trials= 20
Max Error Tol= 0.3
Flow Tol Ratio= 0.001
Split Flow NTrial= 30
Split Flow Tol= 0.02
Split Flow Ratio= 0.02
Log Output Level= 0
Friction Slope Method= 1
Unsteady Friction Slope Method= 2
Unsteady Bridges Friction Slope Method= 1
Parabolic Critical Depth
Global Vel Dist=  1 , 1 , 1
Global Log Level= 0
CheckData=True
Encroach Param= -1, 0, 0, 0
BEGIN DESCRIPTION:
Multiple Run
END DESCRIPTION:

--- Stream0044_DS.f01 (steady flow) ---

Flow Title=Multiple
Number of Profiles=7
Profile Names=10-year,25-year,50-year,1pct_min,100-year,1pct_plu,500-year
River Rch & RM= Stream0044_DS,Reach-1,3052
     513     841    1145     760    1516    3024    2619
River Rch & RM= Stream0044_DS,Reach-1,2966
     860    1455    2023    1367    2728    5443    4899
Boundary for River Rch & Prof#=Stream0044_DS,Reach-1,1
Up Type=0
Dn Type=3
Dn Slope=0.005
Boundary for River Rch & Prof#=Stream0044_DS,Reach-1,2
Up Type=0
Dn Type=3
Dn Slope=0.005
Boundary for River Rch & Prof#=Stream0044_DS,Reach-1,3
Up Type=0
Dn Type=3
Dn Slope=0.005
Boundary for River Rch & Prof#=Stream0044_DS,Reach-1,4
Up Type=0
Dn Type=3
Dn Slope=0.005
Boundary for River Rch & Prof#=Stream0044_DS,Reach-1,5
Up Type=0
Dn Type=3
Dn Slope=0.005
Boundary for River Rch & Prof#=Stream0044_DS,Reach-1,6
Up Type=0
Dn Type=3
Dn Slope=0.005
Boundary for River Rch & Prof#=Stream0044_DS,Reach-1,7
Up Type=0
Dn Type=3
Dn Slope=0.005

--- Stream0044_DS.g01 (geometry) ---

Geom Title=Existing Conditions

River Reach=Stream0044_DS,Reach-1
Reach XY= 30
      2002575.00     13866675.00      2002578.60     13866626.49
      2002619.03     13866577.24      2002630.83     13866522.70
      2002716.82     13866431.04      2002733.16     13866368.95
      2002898.18     13866201.29      2003026.72     13866129.16
      2003077.20     13866118.92      2003126.72     13866079.16
      2003177.18     13866068.88      2003234.65     13866026.36
      2003556.78     13866024.67      2003625.01     13865982.59
      2003676.64     13866021.39      2003709.59     13866024.83
      2003797.84     13865974.71      2003875.08     13866017.17
      2003924.90     13865982.79      2003994.98     13866024.82
      2004356.78     13866024.90      2004471.67     13865933.01
      2004524.90     13865967.19      2004585.44     13865926.36
      2004706.77     13865925.08      2004818.96     13866016.82
      2004881.04     13866033.18      2004968.92     13866116.93
      2005027.35     13866130.70      2005075.00     13866175.00

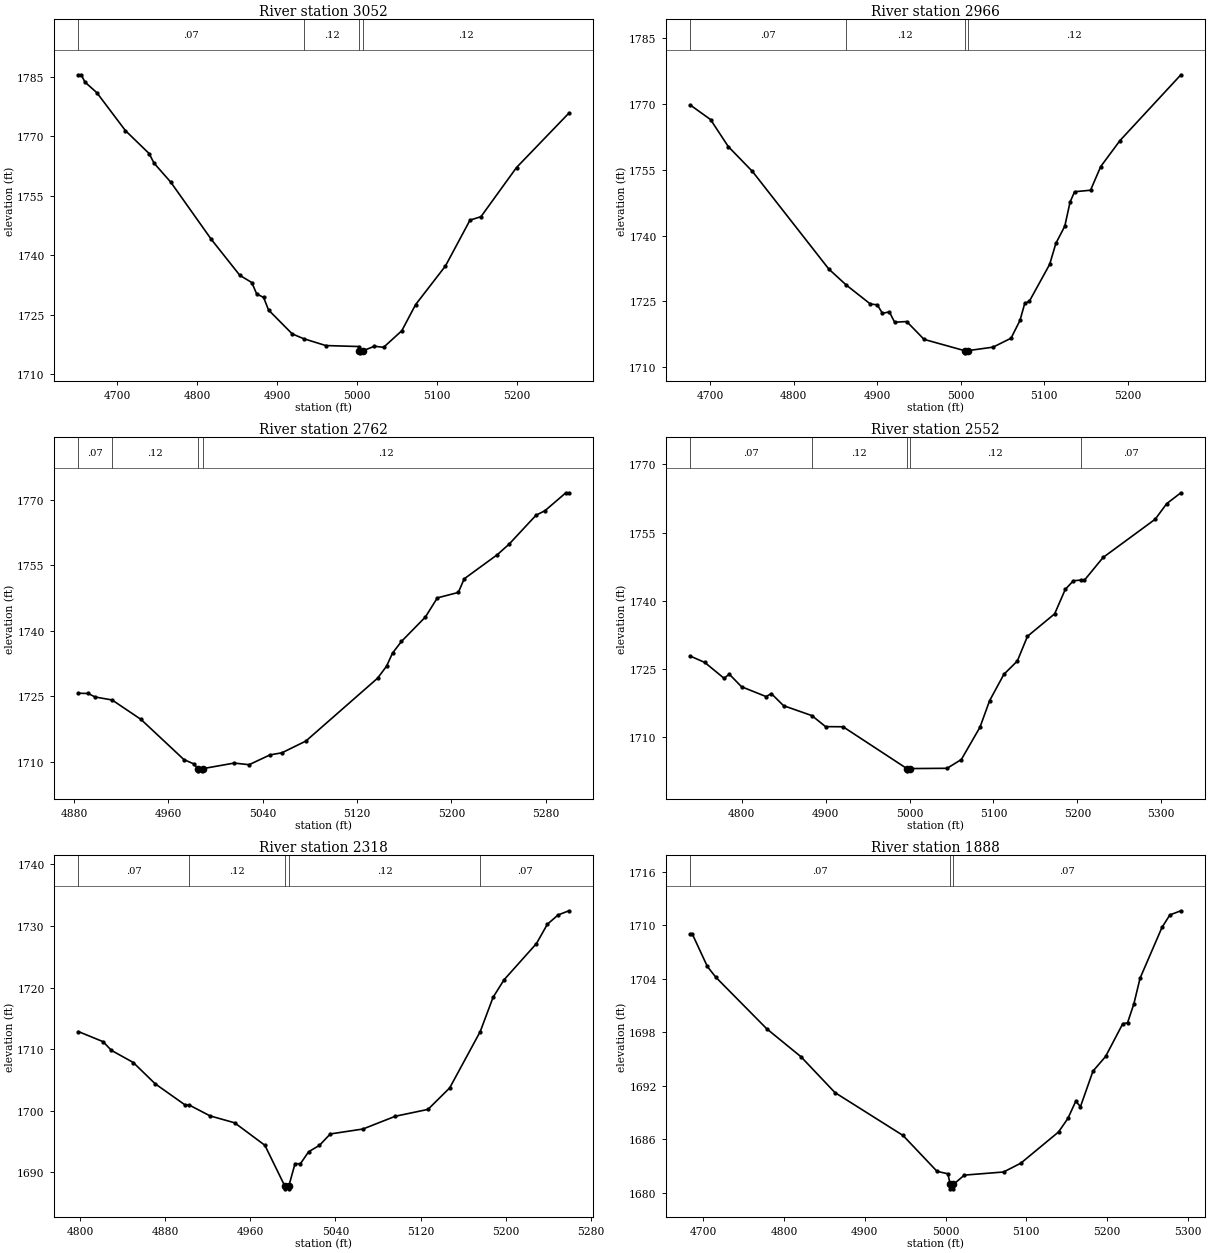
Type RM Length L Ch R = 1,3052,86,86,86
BEGIN DESCRIPTION:
Stream0044_DS 7.0
END DESCRIPTION:
XS GIS Cut Line= 3
      2002774.17     13866947.39      2002574.62     13866662.04
      2002335.88     13866547.94
#Sta/Elev= 30
  4651.8 1785.53  4655.4 1785.53  4659.9 1783.70  4674.8 1781.03  4710.5 1771.46
  4740.1 1765.67  4746.3 1763.24  4767.2 1758.44  4817.8 1744.02  4853.5 1734.93
  4868.4 1733.12  4874.5 1730.26  4883.2 1729.35  4889.3 1726.20  4918.9 1720.16
  4933.2 1718.95  4960.8 1717.22  5002.4 1716.97  5002.9 1715.88  5003.2 1715.38
  5006.9 1715.88  5021.7 1717.04  5033.1 1716.78  5055.8 1720.95  5073.0 1727.53
  5110.4 1737.31  5141.0 1748.86  5154.7 1749.73  5199.1 1762.13  5264.6 1775.87
#Mann=4,-1,0
  4651.8    0.07       0  4933.2    0.12       0  5002.9    0.05       0
  5006.9    0.12       0
Bank Sta=5002.9,5006.9
Exp/Cntr=0.3,0.1

Type RM Length L Ch R = 1,2966,204,204,204
BEGIN DESCRIPTION:
Stream0044_DS 6.0
END DESCRIPTION:
XS GIS Cut Line= 3
      2002809.14     13866844.17      2002611.22     13866588.15
      2002365.57     13866491.99
#Sta/Elev= 30
  4676.4 1769.79  4700.6 1766.48  4721.8 1760.32  4750.8 1754.63  4842.2 1732.36
  4862.9 1728.74  4892.0 1724.37  4900.2 1724.20  4906.5 1722.24  4914.7 1722.59
  4921.0 1720.22  4935.5 1720.37  4956.3 1716.30  5004.7 1713.73  5004.9 1713.23
  5008.7 1713.73  5038.9 1714.53  5060.4 1716.57  5071.1 1720.62  5076.9 1724.56
  5082.2 1724.95  5106.7 1733.44  5114.1 1738.22  5124.8 1742.15  5131.1 1747.65
  5136.5 1750.00  5155.6 1750.35  5167.8 1755.75  5190.8 1761.67  5263.8 1776.70
#Mann=4,-1,0
  4676.4    0.07       0  4862.9    0.12       0  5004.7    0.05       0
  5008.7    0.12       0
Bank Sta=5004.7,5008.7
Exp/Cntr=0.3,0.1

Type RM Length L Ch R = 1,2762,210,210,210
BEGIN DESCRIPTION:
Stream0044_DS 5.0
END DESCRIPTION:
XS GIS Cut Line= 3
      2002825.01     13866475.01      2002725.00     13866425.00
      2002424.95     13866374.99
#Sta/Elev= 30
  4883.7 1725.68  4892.1 1725.62  4897.7 1724.83  4912.3 1724.13  4936.8 1719.67
  4973.2 1710.45  4981.5 1709.47  4985.1 1708.37  4985.4 1707.87  4988.9 1707.87
  4989.1 1708.37  5015.8 1709.65  5028.5 1709.28  5046.2 1711.53  5056.3 1712.01
  5076.6 1714.70  5137.4 1729.12  5145.0 1731.87  5150.1 1734.89  5157.7 1737.57
  5178.0 1743.18  5188.1 1747.56  5205.9 1748.81  5210.9 1751.94  5238.8 1757.44
  5249.0 1759.90  5271.8 1766.53  5279.4 1767.57  5297.1 1771.68  5299.7 1771.68
#Mann=4,-1,0
  4883.7    0.07       0  4912.3    0.12       0  4985.1    0.05       0
  4989.1    0.12       0
Bank Sta=4985.1,4989.1
Exp/Cntr=0.3,0.1

Type RM Length L Ch R = 1,2552,234,234,234
BEGIN DESCRIPTION:
Stream0044_DS 4.5
END DESCRIPTION:
XS GIS Cut Line= 3
      2002996.55     13866468.73      2002841.52     13866260.01
      2002549.80     13866117.88
#Sta/Elev= 30
  4738.8 1727.80  4756.0 1726.41  4779.0 1722.92  4785.2 1723.83  4799.8 1721.06
  4829.0 1718.90  4835.3 1719.55  4849.9 1716.89  4883.7 1714.70  4899.9 1712.28
  4920.8 1712.25  4996.8 1703.05  4997.1 1702.55  5000.8 1703.05  5044.7 1703.11
  5061.7 1705.04  5083.9 1712.15  5095.4 1718.00  5112.4 1723.79  5128.4 1726.72
  5140.5 1732.16  5172.9 1737.11  5185.5 1742.47  5195.2 1744.39  5203.8 1744.53
  5208.1 1744.45  5230.6 1749.51  5292.7 1757.93  5306.4 1761.36  5323.3 1763.75
#Mann=5,-1,0
  4738.8    0.07       0  4883.7    0.12       0  4996.8    0.05       0
  5000.8    0.12       0  5203.8    0.07       0
Bank Sta=4996.8,5000.8
Exp/Cntr=0.3,0.1

Type RM Length L Ch R = 1,2318,430,430,430
BEGIN DESCRIPTION:
Stream0044_DS 4.0
END DESCRIPTION:
XS GIS Cut Line= 3
      2003075.01     13866325.04      2003025.00     13866125.00
      2002775.05     13866075.01
#Sta/Elev= 30
  4798.4 1712.84  4821.6 1711.20  4829.4 1709.79  4850.0 1707.81  4870.6 1704.35
  4898.9 1700.89  4902.7 1700.89  4922.1 1699.14  4945.3 1698.01  4973.7 1694.36
  4992.3 1687.78  4992.5 1687.28  4996.0 1687.28  4996.3 1687.78  5002.0 1691.36
  5007.1 1691.36  5014.8 1693.30  5025.0 1694.35  5035.2 1696.20  5065.8 1697.00
  5096.4 1699.08  5127.0 1700.19  5147.4 1703.68  5176.1 1712.83  5188.2 1718.41
  5198.4 1721.23  5229.0 1727.15  5239.2 1730.28  5249.3 1731.79  5259.5 1732.47
#Mann=5,-1,0
  4798.4    0.07       0  4902.7    0.12       0  4992.3    0.05       0
  4996.3    0.12       0  5176.1    0.07       0
Bank Sta=4992.3,4996.3
Exp/Cntr=0.3,0.1

Type RM Length L Ch R = 1,1888,446,446,446
BEGIN DESCRIPTION:
Stream0044_DS 3.0
END DESCRIPTION:
XS GIS Cut Line= 3
      2003325.00     13866324.99      2003425.00     13866025.00
      2003274.98     13865774.97
#Sta/Elev= 30
  4683.8 1709.01  4686.4 1709.01  4704.9 1705.40  4715.4 1704.19  4778.7 1698.39
  4820.8 1695.28  4863.0 1691.25  4947.3 1686.44  4989.5 1682.41  5002.9 1682.14
  5005.8 1680.95  5006.0 1680.45  5009.5 1680.45  5009.8 1680.95  5023.3 1681.99
  5071.9 1682.34  5093.3 1683.33  5140.0 1686.83  5151.6 1688.35  5161.3 1690.27
  5167.2 1689.68  5182.7 1693.66  5198.3 1695.30  5219.6 1698.98  5225.5 1699.08
  5233.3 1701.19  5241.0 1704.08  5268.2 1709.79  5278.0 1711.19  5291.6 1711.65
#Mann=3,-1,0
  4683.8    0.07       0  5005.8    0.05       0  5009.8    0.07       0
Bank Sta=5005.8,5009.8
Exp/Cntr=0.3,0.1

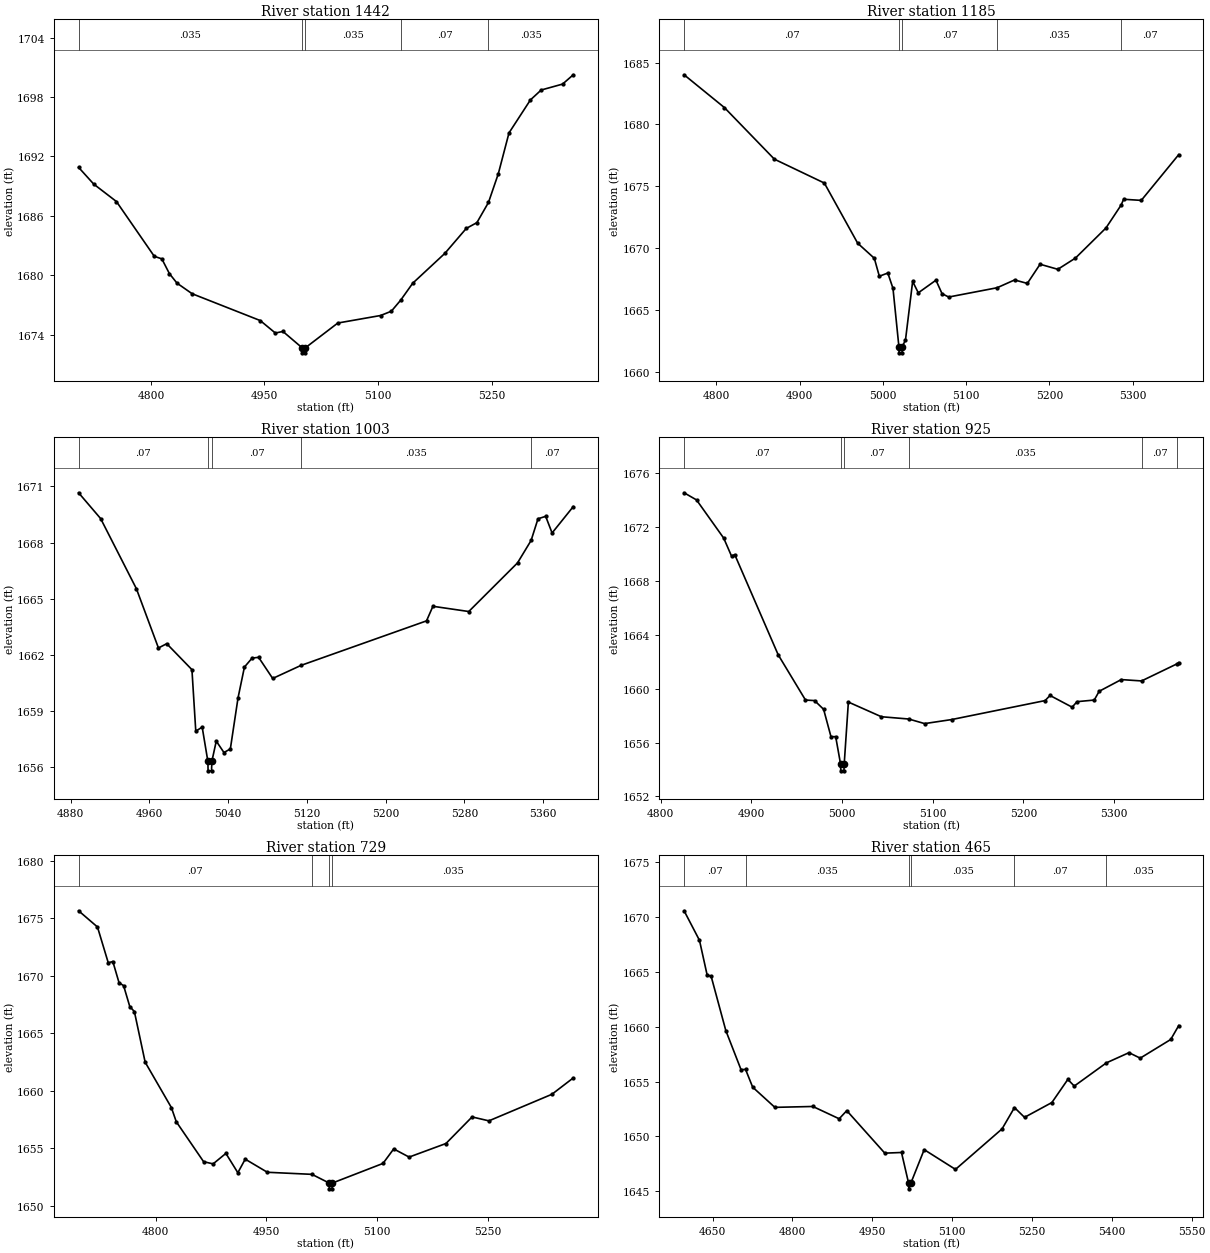
Type RM Length L Ch R = 1,1442,257,257,257
BEGIN DESCRIPTION:
Stream0044_DS 2.0
END DESCRIPTION:
XS GIS Cut Line= 3
      2003825.00     13866275.04      2003825.00     13865975.00
      2003575.00     13865725.00
#Sta/Elev= 30
  4704.4 1690.90  4724.4 1689.21  4754.4 1687.45  4804.4 1681.92  4814.4 1681.66
  4824.4 1680.17  4834.4 1679.21  4854.4 1678.14  4944.4 1675.43  4964.4 1674.17
  4974.4 1674.33  4999.9 1672.67  5000.2 1672.17  5003.7 1672.17  5003.9 1672.67
  5046.9 1675.18  5103.4 1675.94  5117.6 1676.37  5129.9 1677.48  5145.9 1679.20
  5188.3 1682.21  5216.6 1684.73  5230.7 1685.32  5246.0 1687.36  5259.0 1690.26
  5273.1 1694.38  5301.4 1697.71  5315.6 1698.71  5343.9 1699.31  5358.0 1700.25
#Mann=5,-1,0
  4704.4   0.035       0  4999.9   0.035       0  5003.9   0.035       0
  5129.9    0.07       0  5246.0   0.035       0
Bank Sta=4999.9,5003.9
Exp/Cntr=0.3,0.1

Type RM Length L Ch R = 1,1185,182,182,182
BEGIN DESCRIPTION:
Stream0044_DS 1.5
END DESCRIPTION:
XS GIS Cut Line= 3
      2004048.07     13866263.42      2004044.77     13866028.18
      2003854.92     13865723.92
#Sta/Elev= 30
  4761.3 1684.01  4809.7 1681.36  4869.7 1677.19  4929.7 1675.26  4969.7 1670.40
  4989.7 1669.18  4995.7 1667.73  5005.9 1667.99  5012.1 1666.75  5019.2 1662.04
  5019.5 1661.54  5023.0 1661.54  5023.2 1662.04  5027.1 1662.57  5035.7 1667.31
  5042.5 1666.39  5063.7 1667.41  5071.0 1666.32  5079.0 1666.05  5137.1 1666.80
  5158.1 1667.43  5173.4 1667.15  5188.7 1668.70  5210.0 1668.29  5231.2 1669.20
  5267.8 1671.63  5286.0 1673.48  5289.0 1673.95  5310.2 1673.86  5355.2 1677.56
#Mann=5,-1,0
  4761.3    0.07       0  5019.2    0.05       0  5023.2    0.07       0
  5137.1   0.035       0  5286.0    0.07       0
Bank Sta=5019.2,5023.2
Exp/Cntr=0.3,0.1

Type RM Length L Ch R = 1,1003,78,78,78
BEGIN DESCRIPTION:
Stream0044_DS 1.0
END DESCRIPTION:
XS GIS Cut Line= 3
      2004174.99     13866125.01      2004225.00     13866025.00
      2003975.02     13865725.02
#Sta/Elev= 30
  4888.2 1670.66  4910.6 1669.28  4946.9 1665.53  4969.3 1662.36  4977.7 1662.59
  5003.3 1661.20  5007.2 1657.91  5013.7 1658.13  5019.5 1656.29  5019.7 1655.79
  5023.2 1655.79  5023.5 1656.29  5028.0 1657.38  5035.8 1656.77  5042.3 1656.96
  5050.1 1659.69  5056.6 1661.34  5064.4 1661.82  5071.0 1661.86  5085.3 1660.73
  5114.1 1661.43  5241.5 1663.81  5248.0 1664.59  5284.4 1664.31  5333.9 1666.91
  5347.7 1668.11  5354.7 1669.27  5362.5 1669.40  5369.0 1668.51  5390.5 1669.92
#Mann=5,-1,0
  4888.2    0.07       0  5019.5    0.05       0  5023.5    0.07       0
  5114.1   0.035       0  5347.7    0.07       0
Bank Sta=5019.5,5023.5
Exp/Cntr=0.3,0.1

Type RM Length L Ch R = 1,925,196,196,196
BEGIN DESCRIPTION:
Stream0044_DS 0.2
END DESCRIPTION:
XS GIS Cut Line= 3
      2004296.76     13866198.66      2004306.33     13866033.80
      2004167.43     13865679.59
#Sta/Elev= 30
  4825.7 1674.56  4839.4 1674.03  4869.4 1671.19  4878.0 1669.86  4881.6 1669.96
  4929.5 1662.52  4959.6 1659.16  4969.6 1659.12  4979.6 1658.47  4987.7 1656.44
  4992.9 1656.44  4998.3 1654.40  4998.5 1653.90  5002.0 1653.90  5002.3 1654.40
  5006.9 1659.01  5043.3 1657.92  5073.5 1657.75  5091.0 1657.41  5120.8 1657.71
  5223.9 1659.12  5229.3 1659.50  5253.7 1658.63  5259.1 1659.04  5278.1 1659.16
  5283.5 1659.81  5307.9 1660.68  5330.3 1660.58  5369.7 1661.86  5371.3 1661.94
#Mann=6,-1,0
  4825.7    0.07       0  4998.3    0.05       0  5002.3    0.07       0
  5073.5   0.035       0  5330.3    0.07       0  5369.7   0.035       0
Bank Sta=4998.3,5002.3
Exp/Cntr=0.3,0.1

Type RM Length L Ch R = 1,729,264,264,264
BEGIN DESCRIPTION:
Stream0044_DS 0.1
END DESCRIPTION:
XS GIS Cut Line= 4
      2004345.09     13866201.07      2004464.56     13866041.13
      2004465.01     13865936.26      2004244.41     13865644.46
#Sta/Elev= 30
  4695.5 1675.65  4721.1 1674.24  4735.7 1671.13  4741.9 1671.24  4750.3 1669.40
  4756.5 1669.14  4764.9 1667.32  4771.1 1666.89  4785.7 1662.49  4821.2 1658.55
  4827.9 1657.31  4864.9 1653.84  4877.8 1653.65  4895.1 1654.56  4911.3 1652.88
  4921.3 1654.06  4951.3 1652.92  5011.7 1652.74  5035.2 1651.98  5035.4 1651.48
  5038.9 1651.48  5039.2 1651.98  5108.0 1653.69  5122.5 1654.95  5143.4 1654.24
  5193.3 1655.42  5228.7 1657.73  5251.5 1657.39  5336.9 1659.70  5365.8 1661.12
#Mann=4,-1,0
  4695.5    0.07       0  5011.7   0.035       0  5035.2    0.05       0
  5039.2   0.035       0
Bank Sta=5035.2,5039.2
Exp/Cntr=0.3,0.1

Type RM Length L Ch R = 1,465,217,217,217
BEGIN DESCRIPTION:
Stream0044_DS 0.01
END DESCRIPTION:
XS GIS Cut Line= 4
      2004395.33     13866186.45      2004702.34     13865924.78
      2004654.32     13865847.03      2004290.43     13865609.77
#Sta/Elev= 30
  4596.6 1670.55  4625.5 1667.86  4639.8 1664.72  4647.5 1664.57  4675.0 1659.64
  4703.5 1656.09  4712.1 1656.10  4725.4 1654.49  4767.1 1652.65  4838.5 1652.73
  4887.9 1651.61  4902.2 1652.35  4973.6 1648.48  5005.0 1648.54  5018.4 1645.73
  5018.7 1645.23  5022.4 1645.73  5047.6 1648.80  5106.4 1647.00  5193.9 1650.69
  5217.2 1652.63  5236.1 1651.74  5287.5 1653.09  5317.4 1655.19  5329.6 1654.59
  5389.8 1656.70  5432.3 1657.63  5453.4 1657.13  5510.7 1658.83  5525.8 1660.10
#Mann=6,-1,0
  4596.6    0.07       0  4712.1   0.035       0  5018.4   0.035       0
  5022.4   0.035       0  5217.2    0.07       0  5389.8   0.035       0
Bank Sta=5018.4,5022.4
Exp/Cntr=0.3,0.1

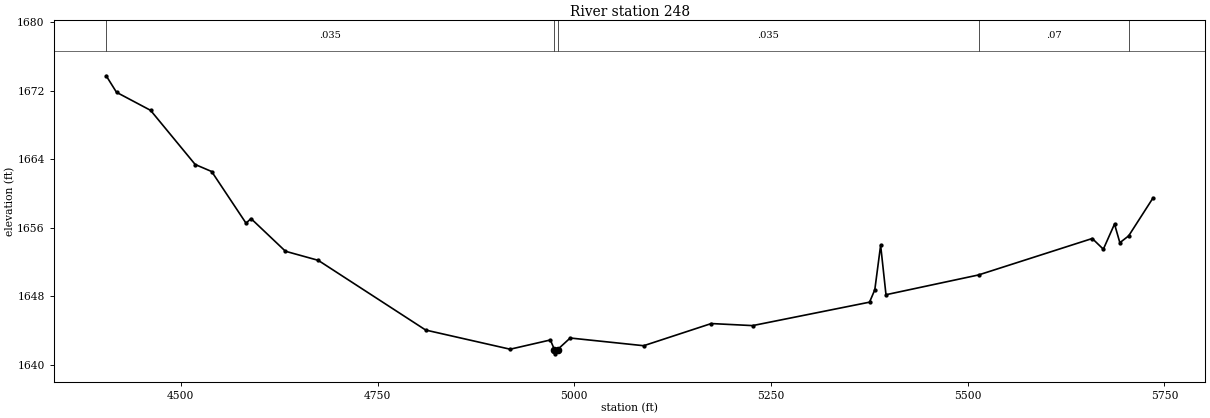
Type RM Length L Ch R = 1,248,0,0,0
BEGIN DESCRIPTION:
Stream0044_DS 0.0
END DESCRIPTION:
XS GIS Cut Line= 5
      2004429.85     13866408.08      2004862.22     13866084.74
      2004881.04     13866033.18      2004874.27     13865858.39
      2004461.43     13865479.16
#Sta/Elev= 30
  4405.2 1673.76  4418.3 1671.83  4461.6 1669.72  4518.3 1663.39  4539.2 1662.57
  4582.9 1656.53  4589.2 1657.07  4633.0 1653.25  4674.6 1652.19  4811.2 1644.04
  4918.5 1641.80  4969.6 1642.88  4974.8 1641.76  4975.0 1641.26  4978.8 1641.76
  4994.8 1643.11  5088.2 1642.21  5174.1 1644.80  5226.6 1644.56  5375.2 1647.30
  5381.9 1648.75  5389.3 1653.95  5396.1 1648.17  5513.7 1650.48  5658.2 1654.74
  5672.3 1653.49  5686.5 1656.43  5693.3 1654.25  5704.5 1655.05  5735.5 1659.49
#Mann=5,-1,0
  4405.2   0.035       0  4974.8   0.035       0  4978.8   0.035       0
  5513.7    0.07       0  5704.5    0.12       0
Bank Sta=4974.8,4978.8
Exp/Cntr=0.3,0.1

Chan Stop Cuts=-1