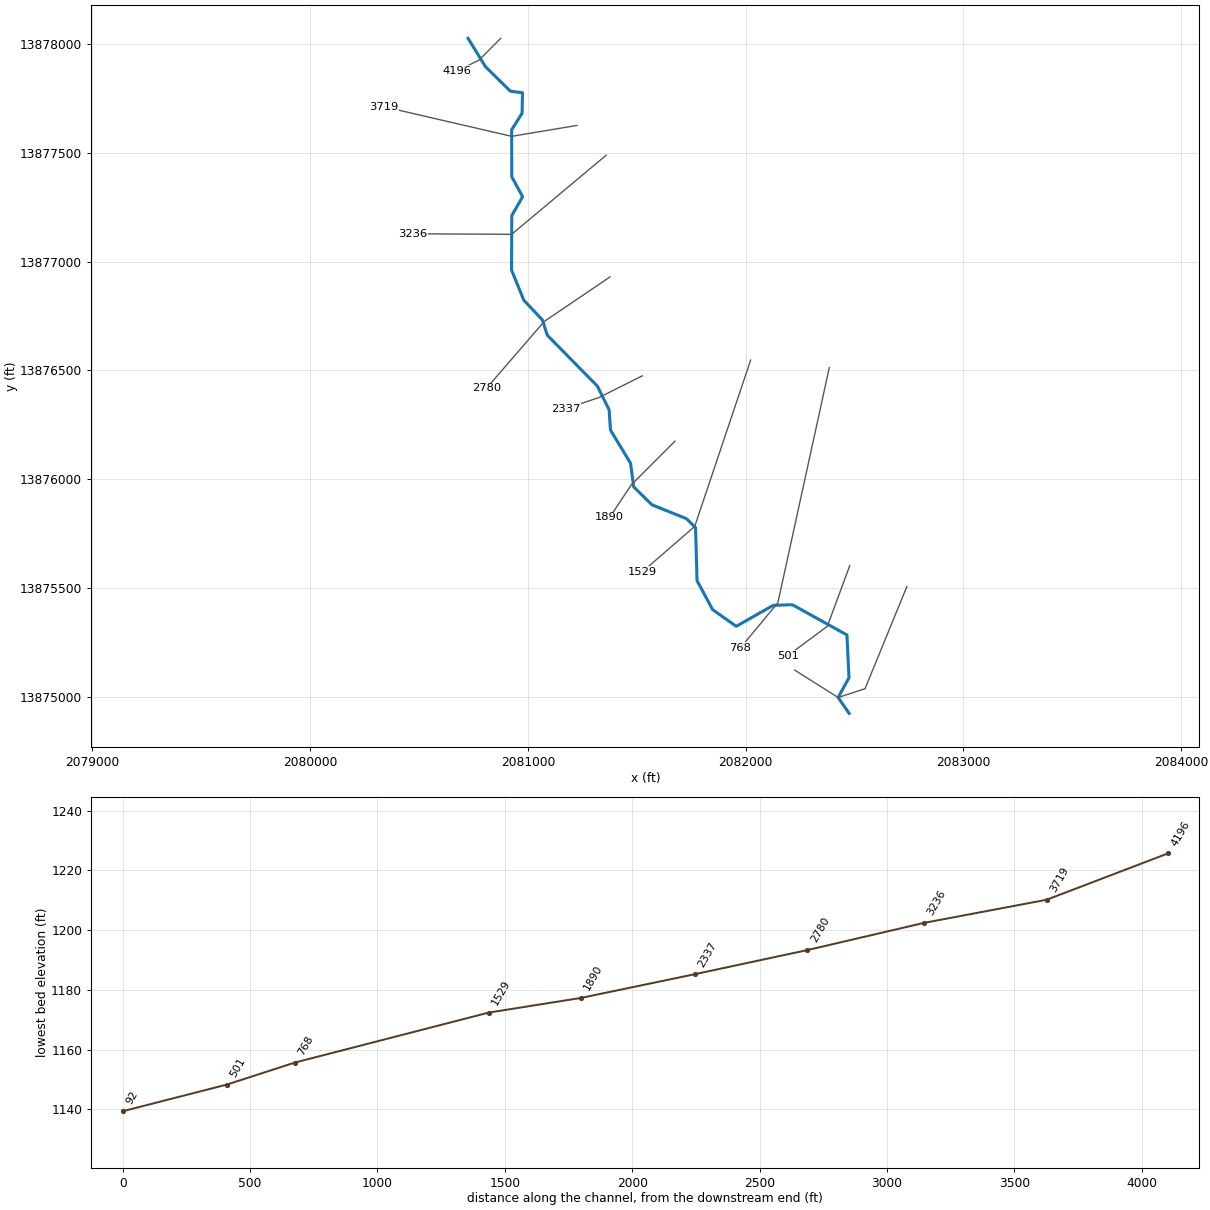
--- Stream0045DS.prj (project) ---

Proj Title=Stream0045DS Base Level Engineering
Current Plan=p01
Default Exp/Contr=0.3,0.1
English Units
Geom File=g01
Flow File=f01
Plan File=p01
BEGIN DESCRIPTION:
Stream0045DS
END DESCRIPTION:

--- Stream0045DS.p01 (plan) ---

Plan Title=Multiple Run
Short Identifier=Multiple
Geom File=g01
Flow File=f01
Subcritical Flow
K Sum by GR= 0
Std Step Tol= 0.01
Critical Tol= 0.01
Num of Std Step Trials= 20
Max Error Tol= 0.3
Flow Tol Ratio= 0.001
Split Flow NTrial= 30
Split Flow Tol= 0.02
Split Flow Ratio= 0.02
Log Output Level= 0
Friction Slope Method= 1
Unsteady Friction Slope Method= 2
Unsteady Bridges Friction Slope Method= 1
Parabolic Critical Depth
Global Vel Dist=  1 , 1 , 1
Global Log Level= 0
CheckData=True
Encroach Param= -1, 0, 0, 0
BEGIN DESCRIPTION:
Multiple Run
END DESCRIPTION:

--- Stream0045DS.f01 (steady flow) ---

Flow Title=Multiple
Number of Profiles=7
Profile Names=10-year,25-year,50-year,1pct_min,100-year,1pct_plu,500-year
River Rch & RM= Stream0045DS,Reach-1,4196
     237     360     467     296     591    1180     929
River Rch & RM= Stream0045DS,Reach-1,3719
     617    1010    1374     910    1815    3621    3123
River Rch & RM= Stream0045DS,Reach-1,2337
     758    1254    1718    1143    2281    4552    3970
Boundary for River Rch & Prof#=Stream0045DS,Reach-1,1
Up Type=0
Dn Type=3
Dn Slope=0.005
Boundary for River Rch & Prof#=Stream0045DS,Reach-1,2
Up Type=0
Dn Type=3
Dn Slope=0.005
Boundary for River Rch & Prof#=Stream0045DS,Reach-1,3
Up Type=0
Dn Type=3
Dn Slope=0.005
Boundary for River Rch & Prof#=Stream0045DS,Reach-1,4
Up Type=0
Dn Type=3
Dn Slope=0.005
Boundary for River Rch & Prof#=Stream0045DS,Reach-1,5
Up Type=0
Dn Type=3
Dn Slope=0.005
Boundary for River Rch & Prof#=Stream0045DS,Reach-1,6
Up Type=0
Dn Type=3
Dn Slope=0.005
Boundary for River Rch & Prof#=Stream0045DS,Reach-1,7
Up Type=0
Dn Type=3
Dn Slope=0.005

--- Stream0045DS.g01 (geometry) ---

Geom Title=Existing Conditions

River Reach=Stream0045DS,Reach-1
Reach XY= 30
      2080725.00     13878025.00      2080804.61     13877894.83
      2080918.79     13877782.76      2080975.00     13877775.00
      2080972.78     13877680.47      2080925.06     13877604.97
      2080925.70     13877388.91      2080975.38     13877297.81
      2080925.70     13877211.09      2080924.55     13876961.18
      2080980.84     13876822.71      2081066.82     13876731.04
      2081088.63     13876661.79      2081319.17     13876427.30
      2081372.67     13876319.03      2081378.83     13876226.58
      2081471.17     13876073.41      2081485.51     13875965.19
      2081568.93     13875883.13      2081727.58     13875819.29
      2081769.64     13875777.70      2081776.36     13875534.65
      2081847.99     13875401.47      2081956.54     13875324.74
      2082126.58     13875421.33      2082214.46     13875423.92
      2082464.66     13875285.12      2082474.31     13875088.91
      2082424.39     13874997.85      2082475.00     13874925.00

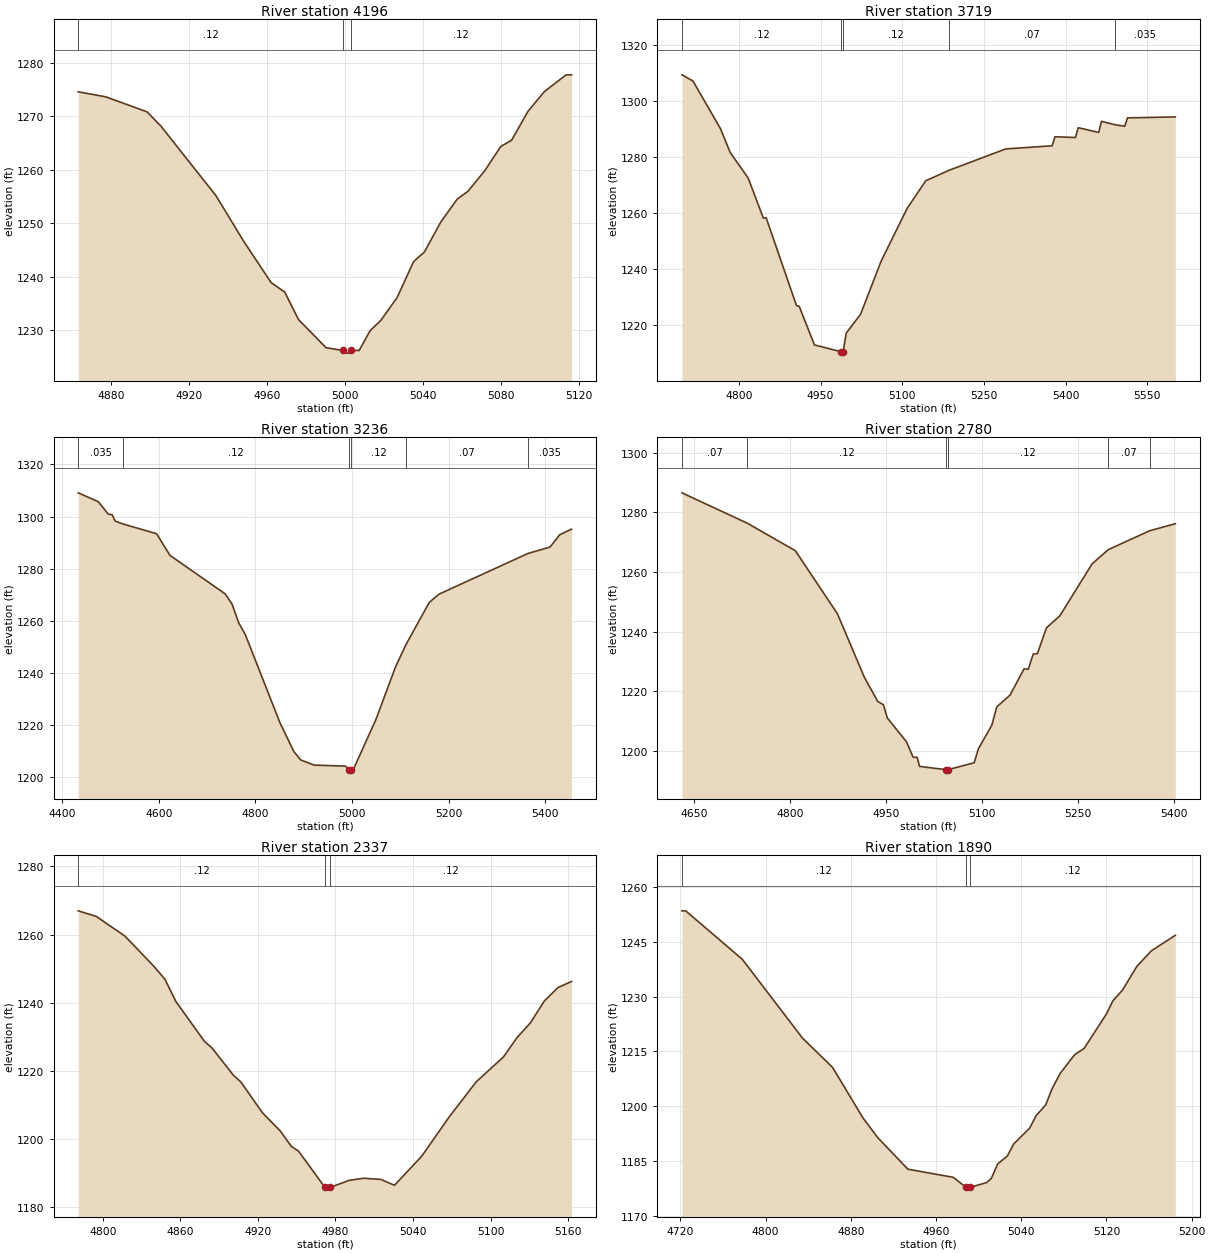
Type RM Length L Ch R = 1,4196,477,477,477
BEGIN DESCRIPTION:
Stream0045DS 9.0
END DESCRIPTION:
XS GIS Cut Line= 3
      2080874.97     13878024.97      2080775.00     13877925.00
      2080674.99     13877874.99
#Sta/Elev= 30
  4863.2 1274.62  4877.3 1273.68  4898.5 1270.87  4905.6 1268.21  4933.9 1255.15
  4948.0 1246.68  4962.2 1238.87  4969.2 1237.08  4976.3 1231.91  4990.4 1226.66
  4999.0 1226.14  4999.3 1225.64  5002.8 1225.64  5003.0 1226.14  5007.4 1226.14
  5013.0 1229.83  5018.6 1231.82  5026.9 1236.07  5035.3 1242.78  5040.9 1244.61
  5049.3 1250.22  5057.7 1254.50  5063.3 1256.00  5071.7 1259.75  5080.1 1264.38
  5085.6 1265.53  5094.0 1270.94  5102.4 1274.64  5113.6 1277.80  5116.4 1277.80
#Mann=3,-1,0
  4863.2    0.12       0  4999.0    0.05       0  5003.0    0.12       0
Bank Sta=4999,5003
Exp/Cntr=0.3,0.1

Type RM Length L Ch R = 1,3719,483,483,483
BEGIN DESCRIPTION:
Stream0045DS 8.0
END DESCRIPTION:
XS GIS Cut Line= 3
      2081224.97     13877624.99      2080925.00     13877575.00
      2080338.61     13877710.75
#Sta/Elev= 30
  4695.5 1309.26  4715.7 1307.06  4766.4 1290.02  4784.2 1281.55  4817.1 1272.50
  4845.0 1258.20  4850.1 1258.36  4905.8 1227.06  4910.9 1226.76  4938.8 1213.05
  4987.5 1210.62  4987.7 1210.12  4991.5 1210.62  4997.1 1217.24  5023.5 1223.95
  5061.1 1242.81  5108.9 1261.65  5143.3 1271.53  5185.4 1275.21  5290.0 1282.86
  5375.4 1283.99  5380.5 1287.21  5418.1 1286.93  5423.2 1290.43  5460.8 1288.74
  5465.9 1292.70  5491.1 1291.47  5508.6 1290.95  5513.7 1293.92  5601.5 1294.27
#Mann=5,-1,0
  4695.5    0.12       0  4987.5    0.05       0  4991.5    0.12       0
  5185.4    0.07       0  5491.1   0.035       0
Bank Sta=4987.5,4991.5
Exp/Cntr=0.3,0.1

Type RM Length L Ch R = 1,3236,456,456,456
BEGIN DESCRIPTION:
Stream0045DS 7.0
END DESCRIPTION:
XS GIS Cut Line= 3
      2081359.49     13877488.54      2080925.00     13877125.00
      2080470.62     13877127.41
#Sta/Elev= 30
  4433.4 1309.12  4474.9 1305.73  4495.7 1300.93  4503.5 1300.74  4510.0 1298.27
  4526.4 1297.15  4595.7 1293.42  4623.2 1285.14  4737.7 1270.34  4752.0 1266.31
  4765.2 1259.40  4779.4 1254.63  4850.9 1220.91  4879.5 1209.90  4893.9 1206.63
  4921.7 1204.66  4986.2 1204.28  4994.7 1202.85  4994.9 1202.35  4998.7 1202.85
  5002.4 1202.85  5049.9 1222.34  5089.9 1242.28  5111.6 1250.88  5159.9 1267.09
  5179.9 1270.23  5364.1 1285.86  5409.9 1288.33  5429.9 1293.06  5454.3 1295.18
#Mann=6,-1,0
  4433.4   0.035       0  4526.4    0.12       0  4994.7    0.05       0
  4998.7    0.12       0  5111.6    0.07       0  5364.1   0.035       0
Bank Sta=4994.7,4998.7
Exp/Cntr=0.3,0.1

Type RM Length L Ch R = 1,2780,443,443,443
BEGIN DESCRIPTION:
Stream0045DS 6.0
END DESCRIPTION:
XS GIS Cut Line= 3
      2081376.84     13876929.50      2081075.00     13876725.00
      2080808.68     13876417.09
#Sta/Elev= 30
  4630.4 1286.56  4732.5 1276.39  4807.8 1267.15  4873.6 1246.02  4915.6 1224.79
  4936.6 1216.64  4945.5 1215.53  4951.6 1211.11  4981.5 1203.14  4992.0 1197.93
  4998.3 1197.93  5002.1 1194.87  5042.9 1193.78  5043.1 1193.28  5046.9 1193.78
  5087.5 1196.09  5094.3 1200.87  5115.1 1208.66  5122.8 1214.81  5143.6 1218.77
  5165.5 1227.57  5172.1 1227.44  5179.8 1232.49  5186.4 1232.68  5200.6 1241.30
  5221.5 1245.33  5271.9 1262.74  5297.4 1267.54  5362.1 1273.85  5402.1 1276.21
#Mann=6,-1,0
  4630.4    0.07       0  4732.5    0.12       0  5042.9    0.05       0
  5046.9    0.12       0  5297.4    0.07       0  5362.1   0.035       0
Bank Sta=5042.9,5046.9
Exp/Cntr=0.3,0.1

Type RM Length L Ch R = 1,2337,447,447,447
BEGIN DESCRIPTION:
Stream0045DS 5.0
END DESCRIPTION:
XS GIS Cut Line= 3
      2081524.99     13876475.00      2081325.00     13876375.00
      2081175.01     13876325.00
#Sta/Elev= 30
  4781.0 1266.96  4795.0 1265.32  4817.3 1259.49  4839.7 1250.60  4848.1 1246.85
  4856.5 1240.36  4878.8 1228.54  4884.4 1226.71  4901.2 1218.60  4906.8 1216.70
  4923.5 1207.65  4937.5 1202.21  4945.9 1197.74  4951.5 1196.34  4971.9 1185.69
  4972.1 1185.19  4975.9 1185.69  4990.6 1187.77  5001.8 1188.39  5015.1 1188.05
  5025.7 1186.32  5046.8 1194.87  5067.8 1206.29  5088.9 1216.70  5110.0 1224.03
  5120.5 1229.69  5131.1 1234.16  5141.6 1240.46  5152.2 1244.41  5162.7 1246.21
#Mann=3,-1,0
  4781.0    0.12       0  4971.9    0.05       0  4975.9    0.12       0
Bank Sta=4971.9,4975.9
Exp/Cntr=0.3,0.1

Type RM Length L Ch R = 1,1890,361,361,361
BEGIN DESCRIPTION:
Stream0045DS 4.0
END DESCRIPTION:
XS GIS Cut Line= 3
      2081675.00     13876175.00      2081475.00     13875975.00
      2081375.01     13875825.02
#Sta/Elev= 30
  4721.5 1253.56  4725.0 1253.56  4778.1 1240.29  4834.6 1218.68  4862.9 1210.62
  4891.2 1196.87  4905.3 1191.36  4933.6 1182.72  4976.1 1180.49  4988.2 1177.75
  4988.5 1177.25  4992.2 1177.75  5007.3 1179.02  5011.9 1180.18  5017.9 1184.16
  5026.9 1186.31  5032.9 1189.64  5047.9 1193.98  5053.9 1197.38  5062.9 1200.32
  5068.9 1204.76  5076.5 1208.97  5090.0 1214.09  5099.0 1215.83  5120.0 1225.30
  5126.0 1228.88  5135.0 1231.81  5148.6 1238.36  5162.1 1242.59  5184.6 1246.85
#Mann=3,-1,0
  4721.5    0.12       0  4988.2    0.05       0  4992.2    0.12       0
Bank Sta=4988.2,4992.2
Exp/Cntr=0.3,0.1

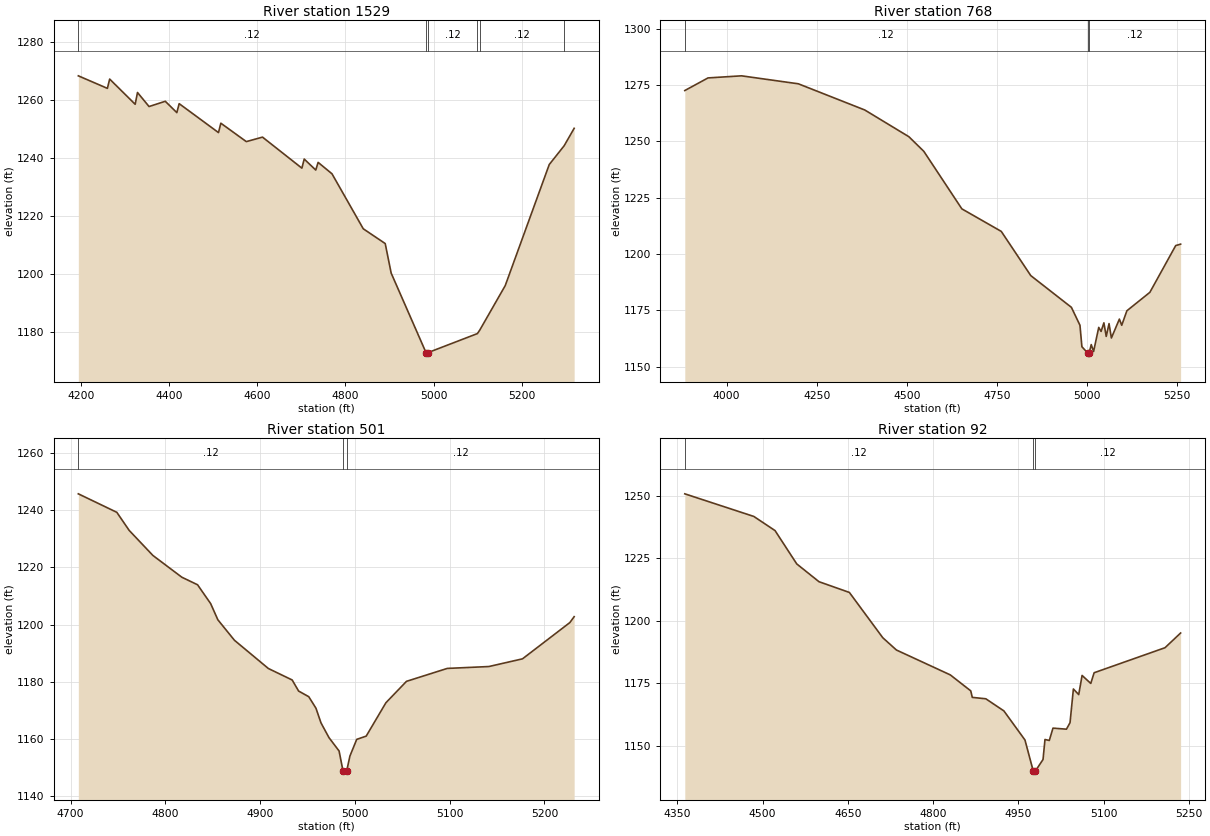
Type RM Length L Ch R = 1,1529,761,761,761
BEGIN DESCRIPTION:
Stream0045DS 3.0
END DESCRIPTION:
XS GIS Cut Line= 3
      2082022.65     13876547.51      2081765.72     13875783.66
      2081524.98     13875574.98
#Sta/Elev= 30
  4194.1 1268.25  4260.0 1263.93  4265.2 1267.13  4323.0 1258.45  4328.3 1262.50
  4354.5 1257.67  4391.3 1259.48  4417.5 1255.57  4422.8 1258.66  4512.0 1248.69
  4517.3 1251.93  4575.1 1245.58  4611.8 1247.13  4701.1 1236.44  4706.4 1239.57
  4732.6 1235.78  4737.9 1238.43  4769.4 1234.49  4840.3 1215.55  4890.1 1210.46
  4903.6 1200.28  4982.7 1172.86  4982.9 1172.36  4986.7 1172.86  5099.2 1179.44
  5104.7 1180.68  5162.3 1195.97  5262.1 1237.68  5295.9 1244.15  5318.6 1250.16
#Mann=6,-1,0
  4194.1    0.12       0  4982.7    0.05       0  4986.7    0.12       0
  5099.2    0.07       0  5104.7    0.12       0  5295.9    0.07       0
Bank Sta=4982.7,4986.7
Exp/Cntr=0.3,0.1

Type RM Length L Ch R = 1,768,267,267,267
BEGIN DESCRIPTION:
Stream0045DS 2.0
END DESCRIPTION:
XS GIS Cut Line= 3
      2082383.79     13876512.87      2082147.66     13875432.97
      2081975.01     13875225.01
#Sta/Elev= 30
  3883.8 1272.58  3948.2 1278.18  4041.1 1279.11  4198.9 1275.57  4383.2 1263.95
  4505.5 1252.10  4547.0 1245.61  4652.5 1220.09  4761.9 1210.09  4843.8 1190.47
  4956.4 1176.41  4980.2 1168.45  4985.6 1158.92  5001.6 1156.14  5001.9 1155.64
  5005.6 1156.14  5011.5 1159.87  5018.0 1156.79  5032.3 1167.49  5038.8 1165.71
  5046.6 1169.52  5053.1 1163.50  5060.9 1169.18  5067.4 1162.80  5089.6 1171.18
  5096.1 1168.44  5110.4 1174.87  5174.2 1183.06  5245.9 1203.81  5259.5 1204.43
#Mann=3,-1,0
  3883.8    0.12       0  5001.6    0.05       0  5005.6    0.12       0
Bank Sta=5001.6,5005.6
Exp/Cntr=0.3,0.1

Type RM Length L Ch R = 1,501,409,409,409
BEGIN DESCRIPTION:
Stream0045DS 1.0
END DESCRIPTION:
XS GIS Cut Line= 3
      2082477.52     13875603.08      2082375.00     13875325.00
      2082192.88     13875189.96
#Sta/Elev= 30
  4708.2 1245.82  4748.8 1239.34  4761.8 1233.02  4786.9 1224.21  4817.4 1216.59
  4834.0 1213.94  4847.8 1207.34  4855.4 1201.67  4872.9 1194.49  4908.7 1184.59
  4933.8 1180.57  4940.6 1176.69  4951.3 1174.71  4958.9 1170.68  4964.2 1165.54
  4972.6 1160.38  4983.3 1155.68  4987.4 1148.77  4987.6 1148.27  4991.4 1148.77
  4994.7 1153.88  5001.9 1159.75  5011.9 1160.89  5032.7 1172.59  5054.4 1180.09
  5097.4 1184.62  5141.3 1185.28  5176.8 1187.98  5226.8 1200.70  5231.3 1202.76
#Mann=3,-1,0
  4708.2    0.12       0  4987.4    0.05       0  4991.4    0.12       0
Bank Sta=4987.4,4991.4
Exp/Cntr=0.3,0.1

Type RM Length L Ch R = 1,92,0,0,0
BEGIN DESCRIPTION:
Stream0045DS 0.0
END DESCRIPTION:
XS GIS Cut Line= 4
      2082740.04     13875507.34      2082547.93     13875038.37
      2082424.39     13874997.85      2082225.07     13875123.65
#Sta/Elev= 30
  4363.2 1250.79  4484.6 1241.74  4522.0 1236.07  4560.2 1222.72  4599.4 1215.59
  4652.8 1211.30  4711.6 1193.16  4735.6 1188.24  4830.4 1178.28  4866.4 1171.88
  4869.1 1169.27  4892.9 1168.71  4924.7 1163.86  4961.8 1152.21  4976.3 1139.84
  4976.6 1139.34  4980.3 1139.84  4993.6 1144.41  4997.0 1152.40  5004.6 1152.02
  5011.1 1156.96  5034.8 1156.54  5041.1 1159.14  5047.0 1172.63  5056.4 1170.39
  5062.3 1178.06  5077.6 1174.86  5083.5 1179.14  5208.2 1189.16  5235.7 1195.05
#Mann=3,-1,0
  4363.2    0.12       0  4976.3    0.05       0  4980.3    0.12       0
Bank Sta=4976.3,4980.3
Exp/Cntr=0.3,0.1

Chan Stop Cuts=-1