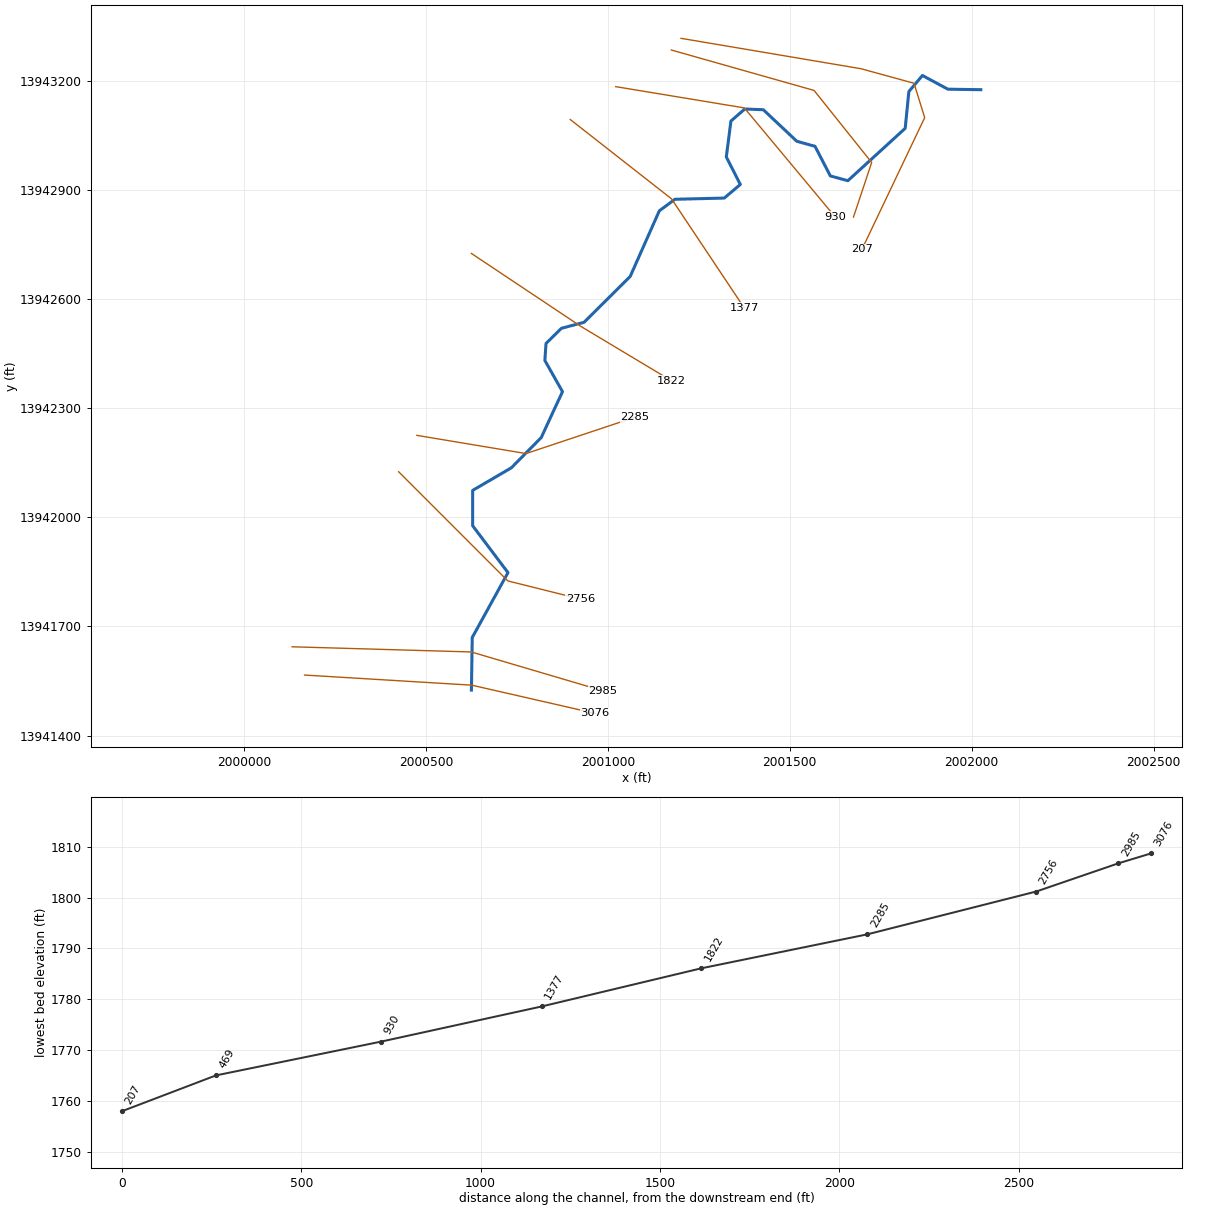
--- Stream0046_DS.prj (project) ---

Proj Title=Stream0046_DS Base Level Engineering
Current Plan=p01
Default Exp/Contr=0.3,0.1
English Units
Geom File=g01
Flow File=f01
Plan File=p01
BEGIN DESCRIPTION:
Stream0046_DS
END DESCRIPTION:

--- Stream0046_DS.p01 (plan) ---

Plan Title=Multiple Run
Short Identifier=Multiple
Geom File=g01
Flow File=f01
Subcritical Flow
K Sum by GR= 0
Std Step Tol= 0.01
Critical Tol= 0.01
Num of Std Step Trials= 20
Max Error Tol= 0.3
Flow Tol Ratio= 0.001
Split Flow NTrial= 30
Split Flow Tol= 0.02
Split Flow Ratio= 0.02
Log Output Level= 0
Friction Slope Method= 1
Unsteady Friction Slope Method= 2
Unsteady Bridges Friction Slope Method= 1
Parabolic Critical Depth
Global Vel Dist=  1 , 1 , 1
Global Log Level= 0
CheckData=True
Encroach Param= -1, 0, 0, 0
BEGIN DESCRIPTION:
Multiple Run
END DESCRIPTION:

--- Stream0046_DS.f01 (steady flow) ---

Flow Title=Multiple
Number of Profiles=7
Profile Names=10-year,25-year,50-year,1pct_min,100-year,1pct_plu,500-year
River Rch & RM= Stream0046_DS,Reach-1,3076
     607    1017    1403     942    1880    3752    3343
River Rch & RM= Stream0046_DS,Reach-1,2985
     744    1257    1746    1178    2350    4689    4222
Boundary for River Rch & Prof#=Stream0046_DS,Reach-1,1
Up Type=0
Dn Type=3
Dn Slope=0.005
Boundary for River Rch & Prof#=Stream0046_DS,Reach-1,2
Up Type=0
Dn Type=3
Dn Slope=0.005
Boundary for River Rch & Prof#=Stream0046_DS,Reach-1,3
Up Type=0
Dn Type=3
Dn Slope=0.005
Boundary for River Rch & Prof#=Stream0046_DS,Reach-1,4
Up Type=0
Dn Type=3
Dn Slope=0.005
Boundary for River Rch & Prof#=Stream0046_DS,Reach-1,5
Up Type=0
Dn Type=3
Dn Slope=0.005
Boundary for River Rch & Prof#=Stream0046_DS,Reach-1,6
Up Type=0
Dn Type=3
Dn Slope=0.005
Boundary for River Rch & Prof#=Stream0046_DS,Reach-1,7
Up Type=0
Dn Type=3
Dn Slope=0.005

--- Stream0046_DS.g01 (geometry) ---

Geom Title=Existing Conditions

River Reach=Stream0046_DS,Reach-1
Reach XY= 30
      2000625.00     13941525.00      2000627.31     13941669.50
      2000725.47     13941847.84      2000628.47     13941976.50
      2000628.37     13942073.72      2000734.68     13942135.78
      2000816.87     13942218.93      2000875.29     13942345.18
      2000826.91     13942430.75      2000829.99     13942477.55
      2000872.39     13942519.25      2000934.66     13942535.79
      2001061.38     13942661.78      2001141.45     13942842.14
      2001184.44     13942873.85      2001319.96     13942877.17
      2001364.06     13942914.56      2001325.52     13942990.22
      2001338.19     13943088.80      2001376.40     13943122.00
      2001427.26     13943119.93      2001519.26     13943033.30
      2001569.37     13943019.34      2001611.47     13942938.03
      2001659.59     13942924.87      2001817.14     13943068.83
      2001827.26     13943169.93      2001864.57     13943214.08
      2001934.49     13943176.41      2002025.00     13943175.00

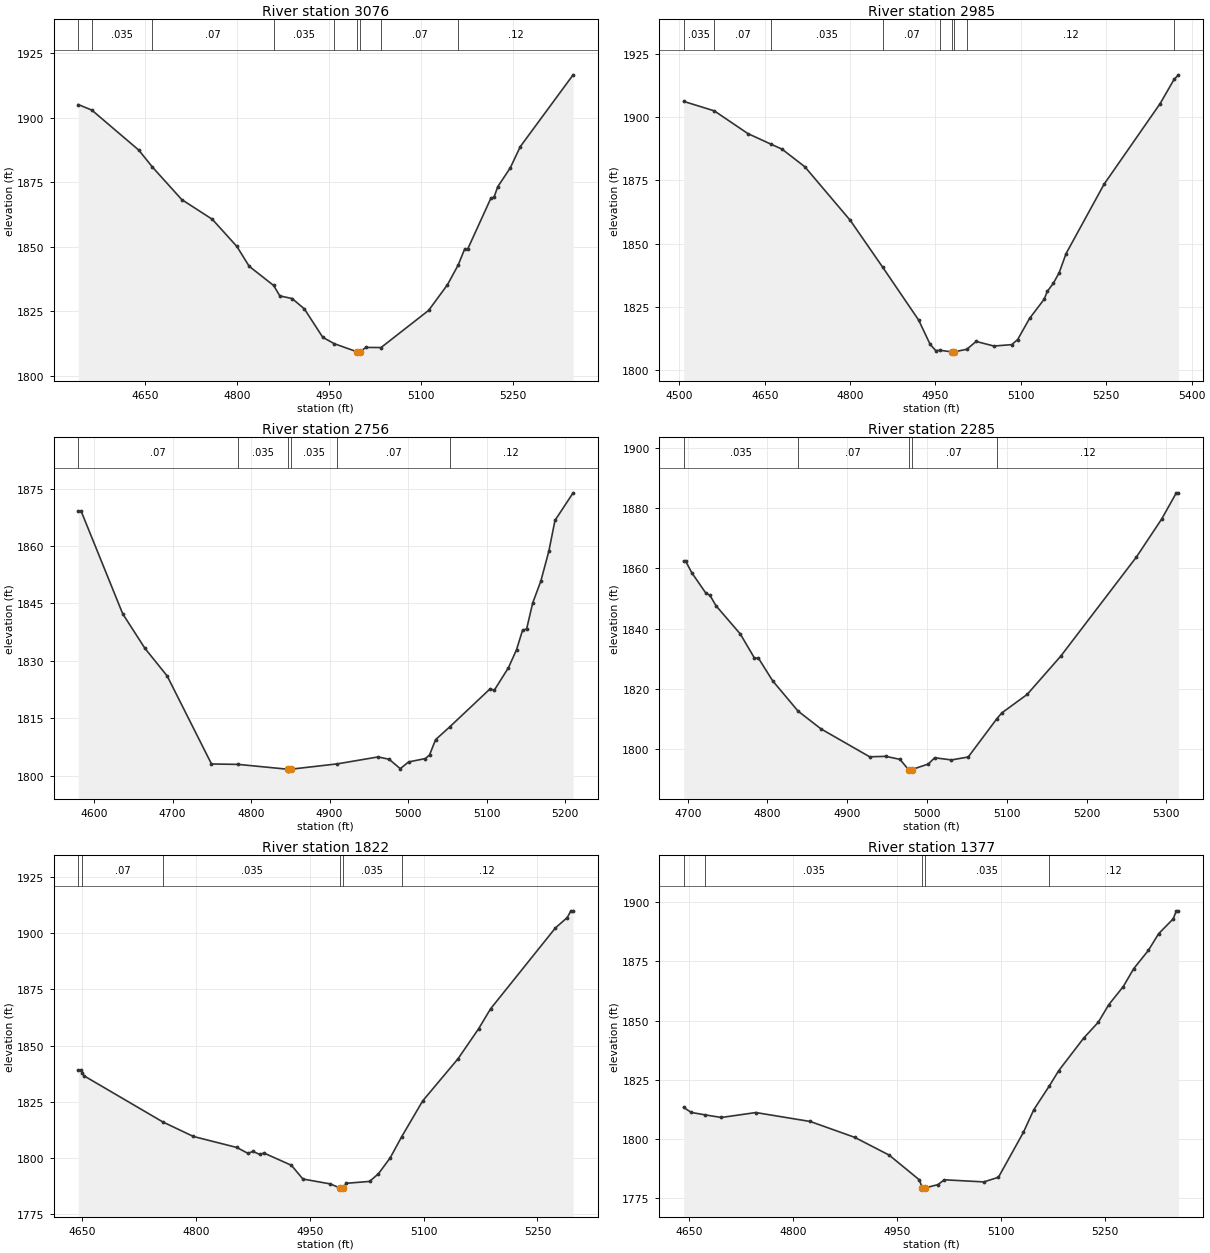
Type RM Length L Ch R = 1,3076,91,91,91
BEGIN DESCRIPTION:
Stream0046_DS 8.0
END DESCRIPTION:
XS GIS Cut Line= 3
      2000166.41     13941566.31      2000626.14     13941538.46
      2000965.02     13941460.96
#Sta/Elev= 30
  4540.6 1905.16  4562.8 1903.00  4639.4 1887.49  4661.7 1880.91  4709.5 1868.30
  4759.6 1860.62  4799.7 1850.08  4819.7 1842.41  4859.7 1834.95  4869.8 1830.90
  4889.8 1829.89  4909.9 1825.86  4939.9 1814.85  4958.6 1812.37  4996.1 1809.20
  4996.4 1808.70  5000.1 1809.20  5010.3 1810.91  5035.1 1810.87  5112.8 1825.28
  5143.6 1835.25  5161.1 1842.90  5171.5 1849.01  5176.6 1849.07  5214.4 1868.78
  5219.6 1869.19  5225.7 1873.28  5246.2 1880.61  5262.5 1888.83  5348.8 1916.70
#Mann=9,-1,0
  4540.6    0.07       0  4562.8   0.035       0  4661.7    0.07       0
  4859.7   0.035       0  4958.6    0.12       0  4996.1    0.05       0
  5000.1    0.12       0  5035.1    0.07       0  5161.1    0.12       0
Bank Sta=4996.1,5000.1
Exp/Cntr=0.3,0.1

Type RM Length L Ch R = 1,2985,229,229,229
BEGIN DESCRIPTION:
Stream0046_DS 7.0
END DESCRIPTION:
XS GIS Cut Line= 3
      2000132.28     13941643.96      2000624.48     13941629.76
      2000985.97     13941523.09
#Sta/Elev= 30
  4507.6 1906.17  4561.4 1902.43  4620.4 1893.46  4660.2 1889.36  4680.4 1887.31
  4720.4 1880.37  4800.4 1859.15  4857.6 1840.57  4920.5 1819.78  4940.5 1810.26
  4950.5 1807.74  4958.0 1807.88  4978.5 1807.25  4978.8 1806.75  4982.5 1807.25
  5005.1 1808.27  5021.4 1811.37  5052.7 1809.55  5084.0 1810.11  5094.4 1812.13
  5115.2 1820.43  5140.9 1828.04  5146.5 1831.16  5156.9 1834.29  5167.4 1838.56
  5179.4 1846.06  5246.0 1873.40  5344.6 1905.29  5369.1 1914.84  5376.9 1916.66
#Mann=9,-1,0
  4507.6   0.035       0  4561.4    0.07       0  4660.2   0.035       0
  4857.6    0.07       0  4958.0   0.035       0  4978.5   0.035       0
  4982.5   0.035       0  5005.1    0.12       0  5369.1    0.07       0
Bank Sta=4978.5,4982.5
Exp/Cntr=0.3,0.1

Type RM Length L Ch R = 1,2756,471,471,471
BEGIN DESCRIPTION:
Stream0046_DS 6.0
END DESCRIPTION:
XS GIS Cut Line= 3
      2000424.98     13942125.02      2000725.00     13941825.00
      2000924.95     13941775.01
#Sta/Elev= 30
  4579.8 1869.15  4583.4 1869.15  4636.4 1842.31  4664.7 1833.28  4693.0 1826.08
  4749.5 1803.07  4783.5 1802.96  4846.5 1801.70  4846.8 1801.20  4850.5 1801.70
  4909.9 1803.10  4961.7 1804.91  4975.8 1804.30  4990.0 1801.84  5000.6 1803.60
  5022.1 1804.49  5027.3 1805.43  5035.0 1809.43  5052.8 1812.72  5104.6 1822.73
  5109.7 1822.31  5127.8 1828.22  5138.1 1832.91  5145.8 1838.02  5151.0 1838.35
  5158.7 1845.14  5169.0 1850.80  5179.3 1858.68  5187.1 1866.70  5210.2 1873.91
#Mann=6,-1,0
  4579.8    0.07       0  4783.5   0.035       0  4846.5    0.05       0
  4850.5   0.035       0  4909.9    0.07       0  5052.8    0.12       0
Bank Sta=4846.5,4850.5
Exp/Cntr=0.3,0.1

Type RM Length L Ch R = 1,2285,463,463,463
BEGIN DESCRIPTION:
Stream0046_DS 5.0
END DESCRIPTION:
XS GIS Cut Line= 3
      2000475.00     13942225.00      2000775.00     13942175.00
      2001075.03     13942275.01
#Sta/Elev= 30
  4694.9 1862.36  4697.4 1862.36  4705.0 1858.56  4722.8 1851.73  4727.8 1851.06
  4735.4 1847.60  4765.9 1838.23  4783.6 1830.27  4788.7 1830.20  4806.4 1822.73
  4838.4 1812.65  4867.2 1806.75  4928.1 1797.52  4948.3 1797.67  4966.1 1796.67
  4976.8 1793.27  4977.0 1792.77  4980.8 1793.27  5001.7 1795.14  5009.6 1797.20
  5030.7 1796.48  5051.7 1797.46  5087.2 1810.01  5093.9 1812.09  5125.5 1818.17
  5167.7 1830.88  5262.6 1863.75  5294.2 1876.31  5312.6 1885.00  5315.3 1885.00
#Mann=5,-1,0
  4694.9   0.035       0  4838.4    0.07       0  4976.8    0.05       0
  4980.8    0.07       0  5087.2    0.12       0
Bank Sta=4976.8,4980.8
Exp/Cntr=0.3,0.1

Type RM Length L Ch R = 1,1822,445,445,445
BEGIN DESCRIPTION:
Stream0046_DS 4.0
END DESCRIPTION:
XS GIS Cut Line= 3
      2000624.99     13942725.01      2000925.00     13942525.00
      2001174.98     13942375.01
#Sta/Elev= 30
  4644.9 1839.12  4647.9 1839.12  4650.3 1837.75  4652.4 1836.55  4756.3 1816.00
  4796.6 1809.53  4853.7 1804.64  4868.8 1801.96  4874.8 1802.92  4883.8 1801.55
  4889.8 1802.12  4925.8 1796.69  4940.9 1790.58  4976.9 1788.41  4989.9 1786.58
  4990.2 1786.08  4993.9 1786.58  4998.0 1788.67  5028.8 1789.52  5040.5 1792.94
  5056.0 1800.05  5070.9 1809.32  5098.8 1825.39  5145.4 1844.17  5172.6 1857.57
  5188.2 1866.37  5273.7 1902.40  5289.2 1907.00  5294.1 1910.01  5297.0 1910.01
#Mann=6,-1,0
  4644.9   0.035       0  4650.3    0.07       0  4756.3   0.035       0
  4989.9   0.035       0  4993.9   0.035       0  5070.9    0.12       0
Bank Sta=4989.9,4993.9
Exp/Cntr=0.3,0.1

Type RM Length L Ch R = 1,1377,447,447,447
BEGIN DESCRIPTION:
Stream0046_DS 3.0
END DESCRIPTION:
XS GIS Cut Line= 3
      2000896.57     13943093.12      2001175.00     13942875.00
      2001375.03     13942574.96
#Sta/Elev= 30
  4642.5 1813.18  4653.6 1811.05  4674.0 1810.00  4696.9 1808.92  4746.7 1811.01
  4825.3 1807.22  4889.5 1800.50  4939.2 1792.97  4982.6 1782.53  4987.0 1779.07
  4987.2 1778.57  4991.0 1779.07  5009.7 1780.50  5018.7 1782.53  5075.8 1781.63
  5096.9 1783.60  5132.9 1802.61  5147.9 1812.19  5170.2 1822.22  5184.0 1828.79
  5220.0 1842.57  5241.1 1849.29  5256.1 1856.68  5277.1 1864.39  5292.2 1871.98
  5313.2 1879.66  5328.2 1886.79  5349.2 1893.07  5353.7 1896.46  5356.8 1896.46
#Mann=5,-1,0
  4642.5    0.07       0  4674.0   0.035       0  4987.0   0.035       0
  4991.0   0.035       0  5170.2    0.12       0
Bank Sta=4987,4991
Exp/Cntr=0.3,0.1

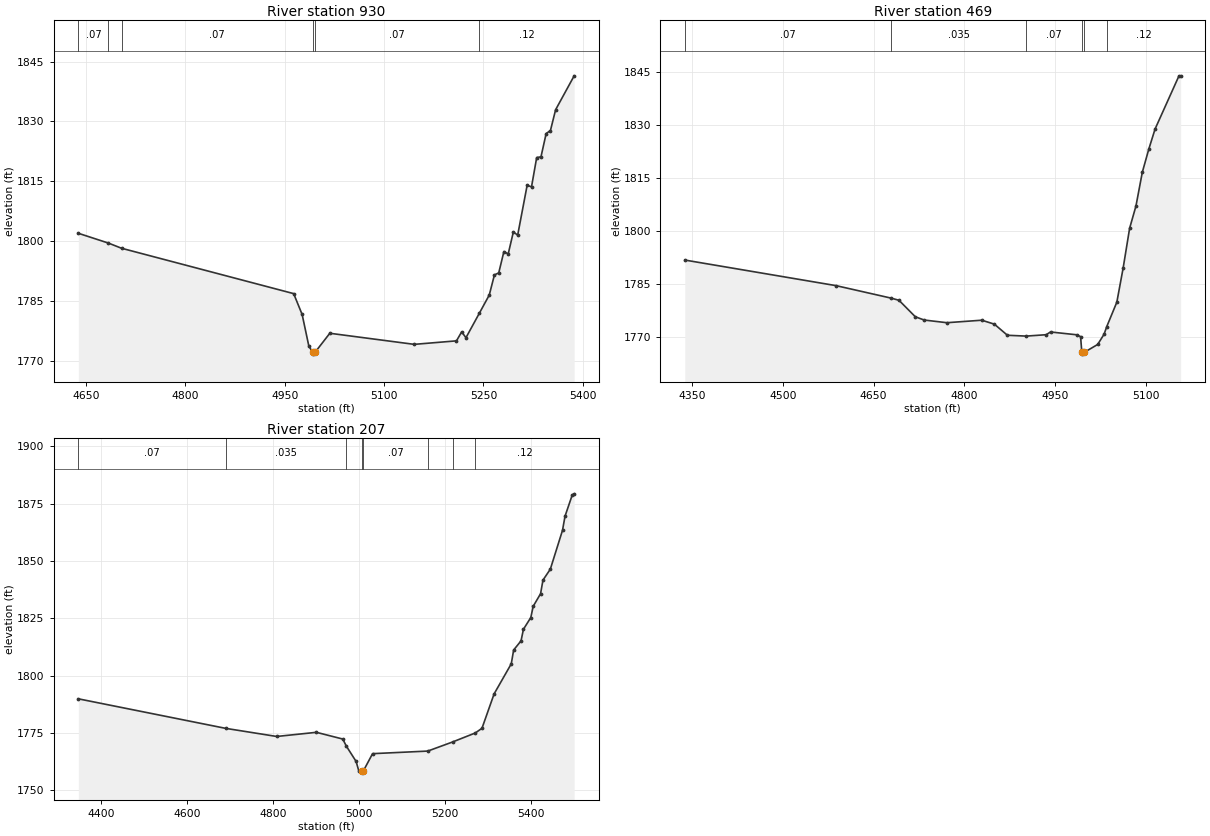
Type RM Length L Ch R = 1,930,461,461,461
BEGIN DESCRIPTION:
Stream0046_DS 2.0
END DESCRIPTION:
XS GIS Cut Line= 3
      2001021.52     13943183.42      2001375.00     13943125.00
      2001625.01     13942824.99
#Sta/Elev= 30
  4638.2 1801.96  4683.7 1799.50  4703.4 1798.21  4963.4 1786.83  4976.2 1781.60
  4986.3 1773.69  4991.9 1772.16  4992.2 1771.66  4995.9 1772.16  5018.0 1776.89
  5145.5 1774.11  5209.3 1774.99  5217.1 1777.24  5223.6 1775.78  5243.7 1781.88
  5258.8 1786.48  5266.6 1791.53  5273.1 1792.03  5280.9 1797.38  5287.4 1796.78
  5295.2 1802.31  5301.7 1801.49  5316.0 1813.99  5322.6 1813.60  5330.4 1820.94
  5336.9 1821.13  5344.7 1826.96  5351.2 1827.73  5359.0 1832.94  5387.0 1841.44
#Mann=6,-1,0
  4638.2    0.07       0  4683.7   0.035       0  4703.4    0.07       0
  4991.9    0.05       0  4995.9    0.07       0  5243.7    0.12       0
Bank Sta=4991.9,4995.9
Exp/Cntr=0.3,0.1

Type RM Length L Ch R = 1,469,262,262,262
BEGIN DESCRIPTION:
Stream0046_DS 1.0
END DESCRIPTION:
XS GIS Cut Line= 4
      2001174.36     13943284.10      2001566.67     13943173.00
      2001725.00     13942975.00      2001674.99     13942824.98
#Sta/Elev= 30
  4338.1 1791.71  4588.2 1784.44  4679.6 1780.88  4692.1 1780.28  4719.1 1775.60
  4733.7 1774.68  4771.2 1773.92  4828.9 1774.63  4849.7 1773.51  4871.3 1770.35
  4902.4 1770.12  4935.3 1770.51  4942.5 1771.29  4985.8 1770.49  4992.2 1769.96
  4994.2 1765.50  4994.4 1765.00  4998.2 1765.50  5020.4 1767.74  5031.0 1770.65
  5035.5 1772.84  5052.1 1779.76  5062.6 1789.52  5073.2 1800.72  5083.7 1807.06
  5094.2 1816.64  5104.8 1823.14  5115.3 1828.92  5154.8 1844.01  5157.5 1844.01
#Mann=6,-1,0
  4338.1    0.07       0  4679.6   0.035       0  4902.4    0.07       0
  4994.2    0.05       0  4998.2    0.07       0  5035.5    0.12       0
Bank Sta=4994.2,4998.2
Exp/Cntr=0.3,0.1

Type RM Length L Ch R = 1,207,0,0,0
BEGIN DESCRIPTION:
Stream0046_DS 0.0
END DESCRIPTION:
XS GIS Cut Line= 5
      2001201.24     13943316.17      2001695.83     13943232.63
      2001841.44     13943192.65      2001870.72     13943098.20
      2001698.16     13942735.88
#Sta/Elev= 30
  4347.4 1789.92  4690.2 1777.03  4808.7 1773.50  4900.9 1775.31  4962.2 1772.38
  4970.7 1769.24  4993.3 1762.59  4999.3 1758.59  5006.0 1758.45  5006.3 1757.95
  5010.0 1758.45  5031.5 1766.00  5159.8 1767.13  5217.4 1771.09  5270.4 1775.03
  5285.9 1777.08  5314.1 1792.08  5354.0 1805.19  5359.5 1811.21  5376.7 1815.20
  5382.3 1820.26  5399.4 1825.37  5405.0 1830.28  5422.1 1835.75  5427.7 1841.69
  5444.8 1846.47  5473.1 1863.40  5479.0 1869.57  5495.8 1878.84  5500.2 1879.32
#Mann=8,-1,0
  4347.4    0.07       0  4690.2   0.035       0  4970.7    0.07       0
  5006.0    0.05       0  5010.0    0.07       0  5159.8   0.035       0
  5217.4    0.07       0  5270.4    0.12       0
Bank Sta=5006,5010
Exp/Cntr=0.3,0.1

Chan Stop Cuts=-1