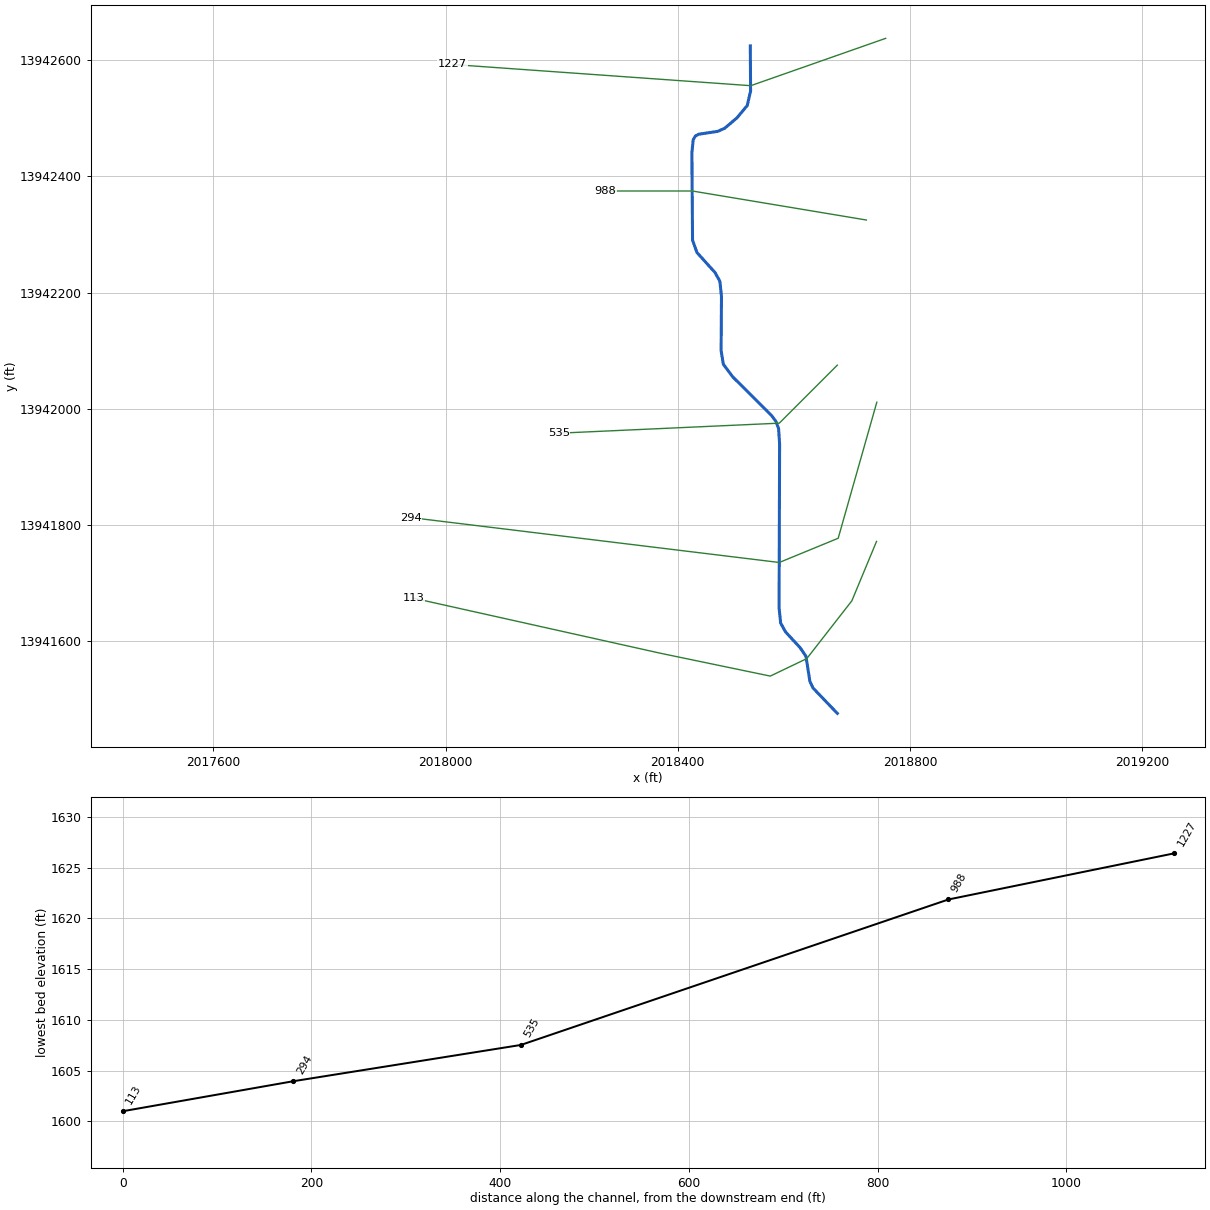
--- Stream0047_DS.prj (project) ---

Proj Title=Stream0047_DS Base Level Engineering
Current Plan=p01
Default Exp/Contr=0.3,0.1
English Units
Geom File=g01
Flow File=f01
Plan File=p01
BEGIN DESCRIPTION:
Stream0047_DS
END DESCRIPTION:

--- Stream0047_DS.p01 (plan) ---

Plan Title=Multiple Run
Short Identifier=Multiple
Geom File=g01
Flow File=f01
Subcritical Flow
K Sum by GR= 0
Std Step Tol= 0.01
Critical Tol= 0.01
Num of Std Step Trials= 20
Max Error Tol= 0.3
Flow Tol Ratio= 0.001
Split Flow NTrial= 30
Split Flow Tol= 0.02
Split Flow Ratio= 0.02
Log Output Level= 0
Friction Slope Method= 1
Unsteady Friction Slope Method= 2
Unsteady Bridges Friction Slope Method= 1
Parabolic Critical Depth
Global Vel Dist=  1 , 1 , 1
Global Log Level= 0
CheckData=True
Encroach Param= -1, 0, 0, 0
BEGIN DESCRIPTION:
Multiple Run
END DESCRIPTION:

--- Stream0047_DS.f01 (steady flow) ---

Flow Title=Multiple
Number of Profiles=7
Profile Names=10-year,25-year,50-year,1pct_min,100-year,1pct_plu,500-year
River Rch & RM= Stream0047_DS,Reach-1,1227
     856    1461    2041    1386    2765    5517    5030
Boundary for River Rch & Prof#=Stream0047_DS,Reach-1,1
Up Type=0
Dn Type=3
Dn Slope=0.005
Boundary for River Rch & Prof#=Stream0047_DS,Reach-1,2
Up Type=0
Dn Type=3
Dn Slope=0.005
Boundary for River Rch & Prof#=Stream0047_DS,Reach-1,3
Up Type=0
Dn Type=3
Dn Slope=0.005
Boundary for River Rch & Prof#=Stream0047_DS,Reach-1,4
Up Type=0
Dn Type=3
Dn Slope=0.005
Boundary for River Rch & Prof#=Stream0047_DS,Reach-1,5
Up Type=0
Dn Type=3
Dn Slope=0.005
Boundary for River Rch & Prof#=Stream0047_DS,Reach-1,6
Up Type=0
Dn Type=3
Dn Slope=0.005
Boundary for River Rch & Prof#=Stream0047_DS,Reach-1,7
Up Type=0
Dn Type=3
Dn Slope=0.005

--- Stream0047_DS.g01 (geometry) ---

Geom Title=Existing Conditions

River Reach=Stream0047_DS,Reach-1
Reach XY= 30
      2018525.00     13942625.00      2018525.53     13942547.41
      2018519.73     13942522.23      2018502.15     13942501.13
      2018481.01     13942483.16      2018469.08     13942477.76
      2018436.04     13942472.79      2018430.21     13942469.55
      2018426.64     13942463.17      2018424.37     13942440.55
      2018425.52     13942290.22      2018433.14     13942268.94
      2018464.14     13942234.64      2018472.61     13942219.47
      2018475.35     13942193.33      2018474.73     13942099.89
      2018478.56     13942076.47      2018494.65     13942054.86
      2018561.60     13941988.31      2018569.52     13941977.45
      2018573.79     13941965.41      2018575.50     13941938.84
      2018574.60     13941656.65      2018577.34     13941630.52
      2018585.78     13941615.32      2018610.98     13941588.05
      2018620.92     13941573.31      2018627.61     13941530.63
      2018632.91     13941518.85      2018675.00     13941475.00

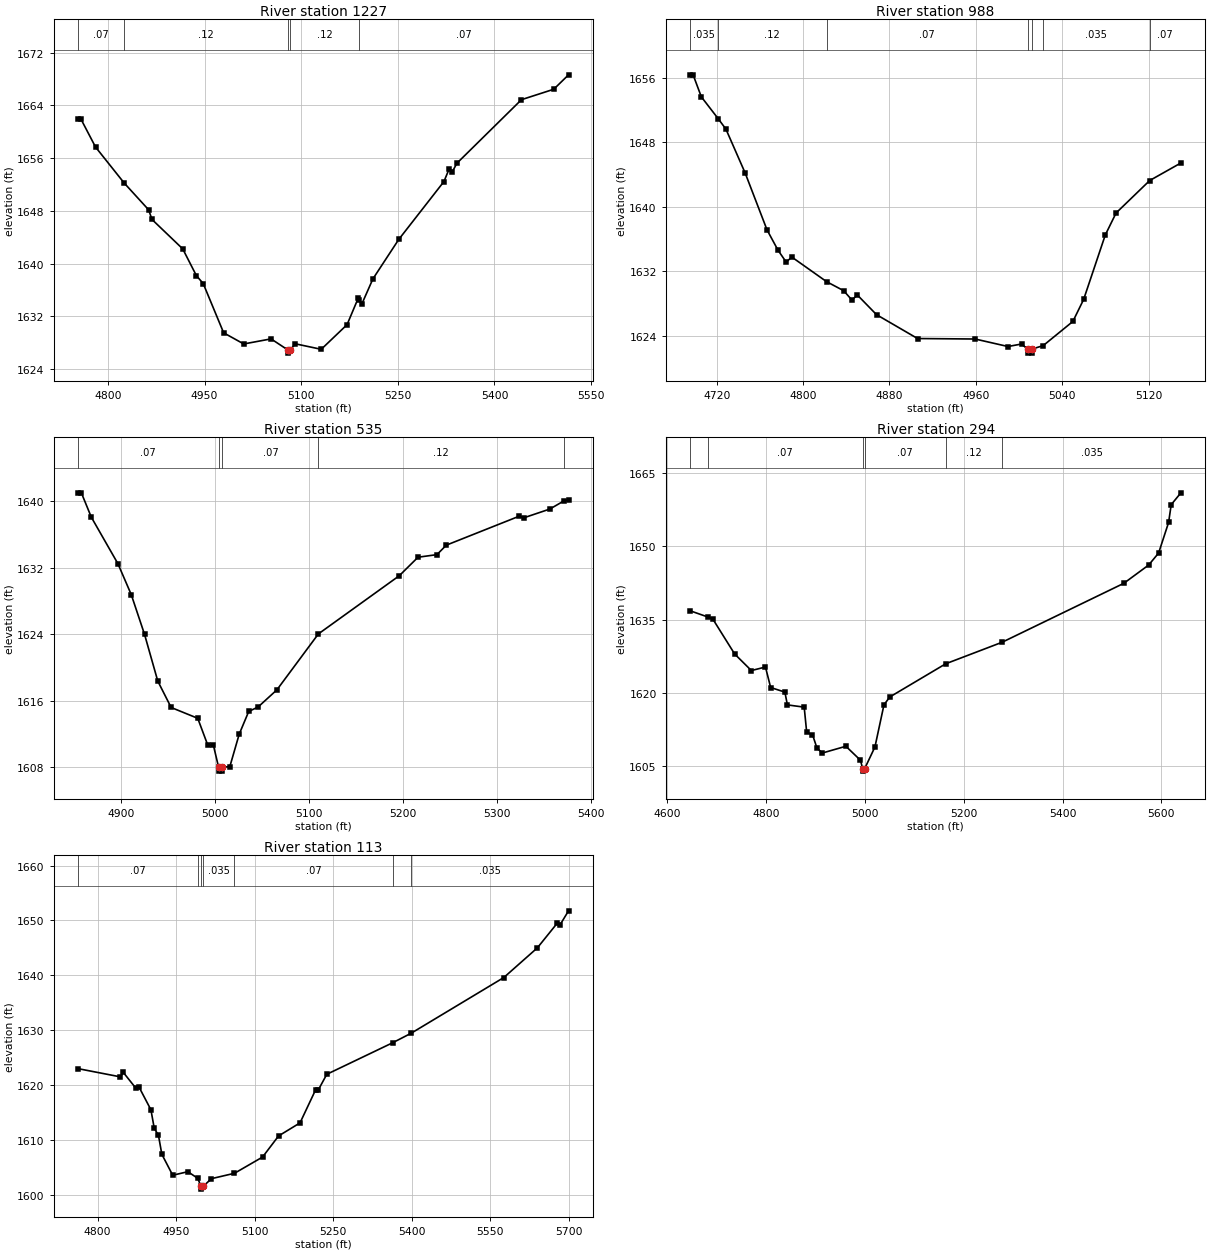
Type RM Length L Ch R = 1,1227,239,239,239
BEGIN DESCRIPTION:
Stream0047_DS 4.0
END DESCRIPTION:
XS GIS Cut Line= 3
      2018758.29     13942638.01      2018525.79     13942556.42
      2018012.09     13942592.96
#Sta/Elev= 30
  4753.6 1661.92  4758.0 1661.92  4780.7 1657.67  4825.1 1652.22  4863.1 1648.15
  4868.4 1646.68  4916.1 1642.22  4937.3 1638.16  4947.9 1636.96  4979.6 1629.49
  5010.8 1627.80  5053.2 1628.57  5079.0 1626.91  5079.2 1626.41  5083.0 1626.91
  5091.0 1627.82  5131.1 1626.99  5171.2 1630.73  5188.8 1634.82  5190.3 1634.52
  5193.9 1633.81  5211.3 1637.67  5251.4 1643.65  5321.6 1652.44  5329.5 1654.31
  5334.5 1653.90  5341.7 1655.21  5441.9 1664.85  5492.0 1666.43  5515.0 1668.62
#Mann=5,-1,0
  4753.6    0.07       0  4825.1    0.12       0  5079.0    0.05       0
  5083.0    0.12       0  5190.3    0.07       0
Bank Sta=5079,5083
Exp/Cntr=0.3,0.1

Type RM Length L Ch R = 1,988,453,453,453
BEGIN DESCRIPTION:
Stream0047_DS 2.0
END DESCRIPTION:
XS GIS Cut Line= 3
      2018724.98     13942325.00      2018425.00     13942375.00
      2018275.02     13942375.00
#Sta/Elev= 30
  4695.7 1656.38  4698.2 1656.38  4705.8 1653.65  4721.3 1650.96  4728.6 1649.64
  4746.4 1644.20  4766.6 1637.16  4776.8 1634.63  4784.4 1633.15  4789.5 1633.79
  4821.8 1630.73  4837.6 1629.61  4845.2 1628.46  4850.3 1629.07  4868.0 1626.64
  4906.0 1623.68  4959.3 1623.62  4989.7 1622.69  5002.3 1623.00  5007.8 1622.37
  5008.1 1621.87  5011.6 1621.87  5011.8 1622.37  5022.3 1622.80  5049.8 1625.80
  5059.8 1628.54  5079.8 1636.52  5089.8 1639.25  5120.9 1643.27  5149.8 1645.45
#Mann=7,-1,0
  4695.7   0.035       0  4721.3    0.12       0  4821.8    0.07       0
  5007.8    0.05       0  5011.8    0.07       0  5022.3   0.035       0
  5120.9    0.07       0
Bank Sta=5007.8,5011.8
Exp/Cntr=0.3,0.1

Type RM Length L Ch R = 1,535,241,241,241
BEGIN DESCRIPTION:
Stream0047_DS 1.0
END DESCRIPTION:
XS GIS Cut Line= 3
      2018675.00     13942075.00      2018575.00     13941975.00
      2018195.11     13941957.73
#Sta/Elev= 30
  4854.4 1640.99  4857.9 1640.99  4868.5 1638.06  4896.8 1632.47  4911.0 1628.75
  4925.1 1623.98  4939.2 1618.36  4953.4 1615.19  4981.7 1613.89  4992.3 1610.68
  4998.3 1610.68  5003.8 1608.04  5004.1 1607.54  5007.6 1607.54  5007.8 1608.04
  5015.8 1608.07  5025.8 1611.98  5035.9 1614.71  5045.9 1615.25  5065.9 1617.31
  5110.0 1624.03  5196.0 1631.02  5216.0 1633.25  5236.1 1633.56  5246.1 1634.70
  5323.6 1638.18  5328.6 1637.99  5356.2 1639.04  5371.2 1640.02  5376.1 1640.14
#Mann=5,-1,0
  4854.4    0.07       0  5003.8    0.05       0  5007.8    0.07       0
  5110.0    0.12       0  5371.2   0.035       0
Bank Sta=5003.8,5007.8
Exp/Cntr=0.3,0.1

Type RM Length L Ch R = 1,294,181,181,181
BEGIN DESCRIPTION:
Stream0047_DS 0.1
END DESCRIPTION:
XS GIS Cut Line= 4
      2018742.99     13942011.11      2018676.45     13941776.72
      2018574.95     13941734.98      2017940.25     13941812.34
#Sta/Elev= 30
  4646.6 1636.78  4681.2 1635.55  4691.8 1635.13  4736.1 1627.96  4770.0 1624.56
  4798.5 1625.29  4809.0 1621.09  4837.8 1620.15  4842.9 1617.53  4876.9 1617.07
  4882.0 1611.88  4893.7 1611.45  4902.6 1608.73  4913.4 1607.67  4961.3 1609.06
  4990.7 1606.21  4995.3 1604.47  4995.5 1603.97  4999.3 1604.47  5020.1 1608.92
  5038.4 1617.56  5050.3 1619.16  5163.4 1625.95  5277.6 1630.36  5523.8 1642.42
  5574.2 1646.17  5594.3 1648.62  5614.5 1654.88  5619.8 1658.53  5639.4 1660.95
#Mann=6,-1,0
  4646.6   0.035       0  4681.2    0.07       0  4995.3    0.05       0
  4999.3    0.07       0  5163.4    0.12       0  5277.6   0.035       0
Bank Sta=4995.3,4999.3
Exp/Cntr=0.3,0.1

Type RM Length L Ch R = 1,113,0,0,0
BEGIN DESCRIPTION:
Stream0047_DS 0.0
END DESCRIPTION:
XS GIS Cut Line= 6
      2018742.51     13941771.26      2018699.97     13941668.93
      2018622.32     13941569.34      2018559.43     13941539.24
      2018369.71     13941578.69      2017944.46     13941673.52
#Sta/Elev= 30
  4762.9 1622.98  4843.8 1621.48  4849.2 1622.30  4873.1 1619.43  4879.4 1619.60
  4902.0 1615.47  4908.3 1612.12  4916.4 1610.80  4922.8 1607.37  4943.6 1603.54
  4972.5 1604.19  4991.4 1602.98  4997.6 1601.51  4997.8 1601.01  5001.6 1601.51
  5017.6 1602.92  5061.5 1603.90  5115.1 1606.86  5145.7 1610.71  5186.6 1613.09
  5216.5 1619.15  5221.6 1619.12  5237.7 1621.95  5363.4 1627.70  5398.8 1629.44
  5575.7 1639.60  5639.7 1645.01  5678.0 1649.55  5683.2 1649.24  5699.2 1651.76
#Mann=7,-1,0
  4762.9    0.07       0  4991.4   0.035       0  4997.6   0.035       0
  5001.6   0.035       0  5061.5    0.07       0  5363.4    0.12       0
  5398.8   0.035       0
Bank Sta=4997.6,5001.6
Exp/Cntr=0.3,0.1

Chan Stop Cuts=-1