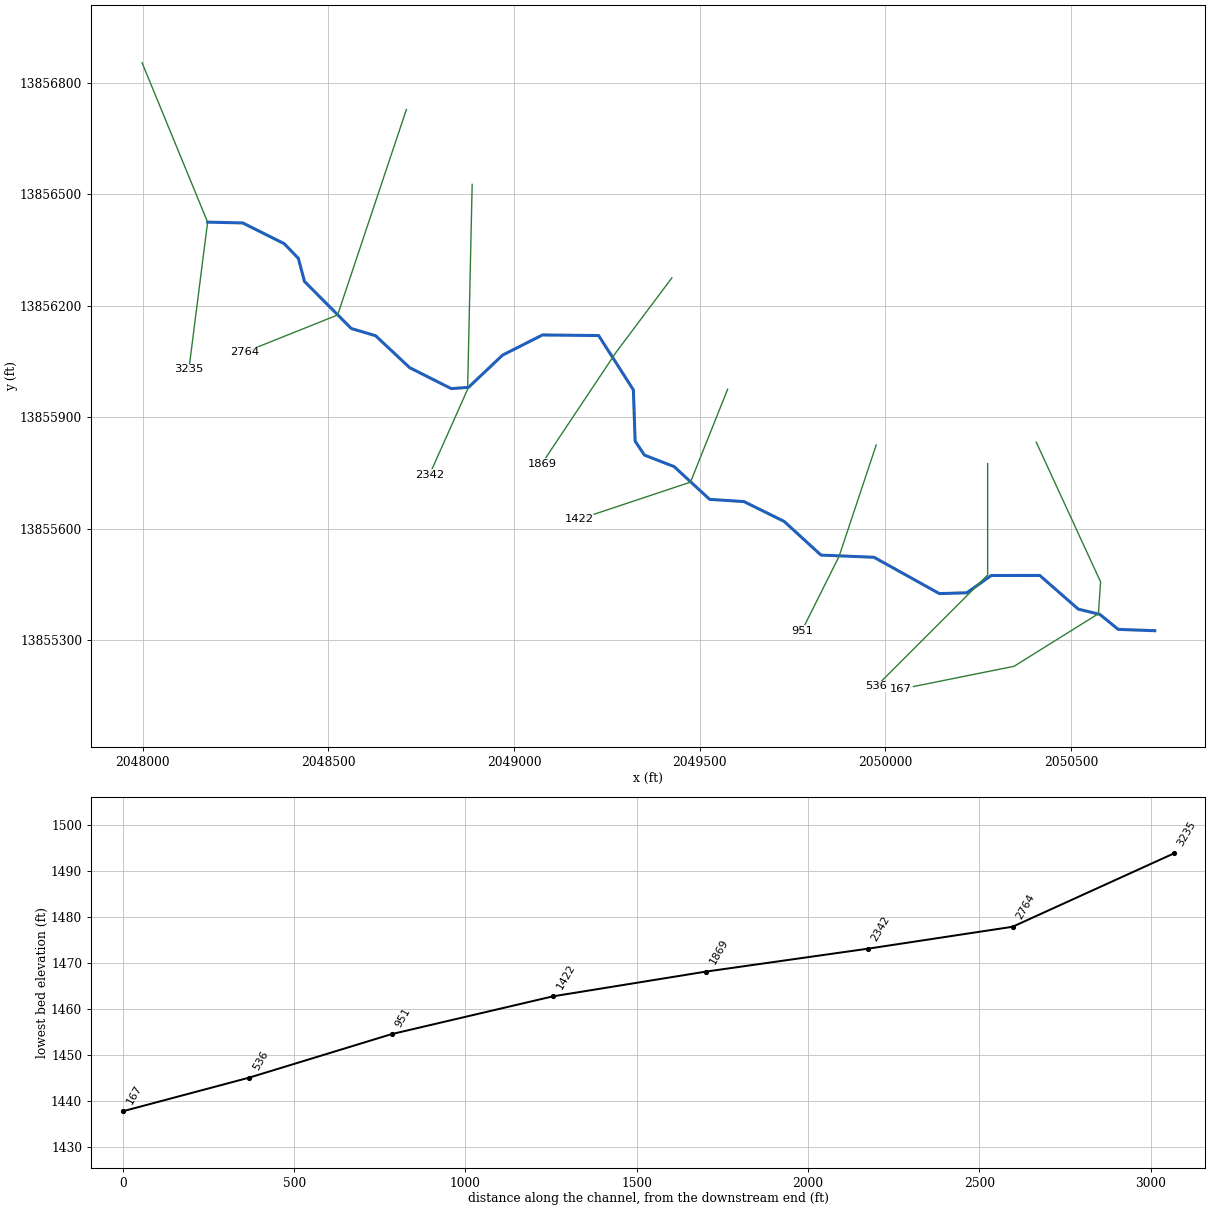
--- Stream0048_DS.prj (project) ---

Proj Title=Stream0048_DS Base Level Engineering
Current Plan=p01
Default Exp/Contr=0.3,0.1
English Units
Geom File=g01
Flow File=f01
Plan File=p01
BEGIN DESCRIPTION:
Stream0048_DS
END DESCRIPTION:

--- Stream0048_DS.p01 (plan) ---

Plan Title=Multiple Run
Short Identifier=Multiple
Geom File=g01
Flow File=f01
Subcritical Flow
K Sum by GR= 0
Std Step Tol= 0.01
Critical Tol= 0.01
Num of Std Step Trials= 20
Max Error Tol= 0.3
Flow Tol Ratio= 0.001
Split Flow NTrial= 30
Split Flow Tol= 0.02
Split Flow Ratio= 0.02
Log Output Level= 0
Friction Slope Method= 1
Unsteady Friction Slope Method= 2
Unsteady Bridges Friction Slope Method= 1
Parabolic Critical Depth
Global Vel Dist=  1 , 1 , 1
Global Log Level= 0
CheckData=True
Encroach Param= -1, 0, 0, 0
BEGIN DESCRIPTION:
Multiple Run
END DESCRIPTION:

--- Stream0048_DS.f01 (steady flow) ---

Flow Title=Multiple
Number of Profiles=7
Profile Names=10-year,25-year,50-year,1pct_min,100-year,1pct_plu,500-year
River Rch & RM= Stream0048_DS,Reach-1,3235
     959    1623    2255    1524    3041    6067    5454
River Rch & RM= Stream0048_DS,Reach-1,2764
    1442    2493    3516    2405    4798    9573    8831
Boundary for River Rch & Prof#=Stream0048_DS,Reach-1,1
Up Type=0
Dn Type=3
Dn Slope=0.005
Boundary for River Rch & Prof#=Stream0048_DS,Reach-1,2
Up Type=0
Dn Type=3
Dn Slope=0.005
Boundary for River Rch & Prof#=Stream0048_DS,Reach-1,3
Up Type=0
Dn Type=3
Dn Slope=0.005
Boundary for River Rch & Prof#=Stream0048_DS,Reach-1,4
Up Type=0
Dn Type=3
Dn Slope=0.005
Boundary for River Rch & Prof#=Stream0048_DS,Reach-1,5
Up Type=0
Dn Type=3
Dn Slope=0.005
Boundary for River Rch & Prof#=Stream0048_DS,Reach-1,6
Up Type=0
Dn Type=3
Dn Slope=0.005
Boundary for River Rch & Prof#=Stream0048_DS,Reach-1,7
Up Type=0
Dn Type=3
Dn Slope=0.005

--- Stream0048_DS.g01 (geometry) ---

Geom Title=Existing Conditions

River Reach=Stream0048_DS,Reach-1
Reach XY= 30
      2048175.00     13856425.00      2048269.55     13856422.81
      2048381.34     13856366.98      2048419.25     13856327.54
      2048435.79     13856265.34      2048561.79     13856138.63
      2048627.28     13856119.13      2048718.95     13856033.15
      2048830.72     13855976.88      2048877.29     13855980.10
      2048968.95     13856066.84      2049076.56     13856121.26
      2049227.70     13856119.65      2049321.24     13855973.44
      2049326.00     13855835.29      2049351.03     13855797.81
      2049431.02     13855766.81      2049526.50     13855678.62
      2049619.03     13855672.67      2049727.29     13855619.15
      2049826.47     13855528.55      2049969.07     13855522.75
      2050145.09     13855424.89      2050219.02     13855427.17
      2050284.67     13855473.63      2050415.40     13855473.80
      2050518.95     13855383.16      2050577.18     13855368.89
      2050626.50     13855328.63      2050725.00     13855325.00

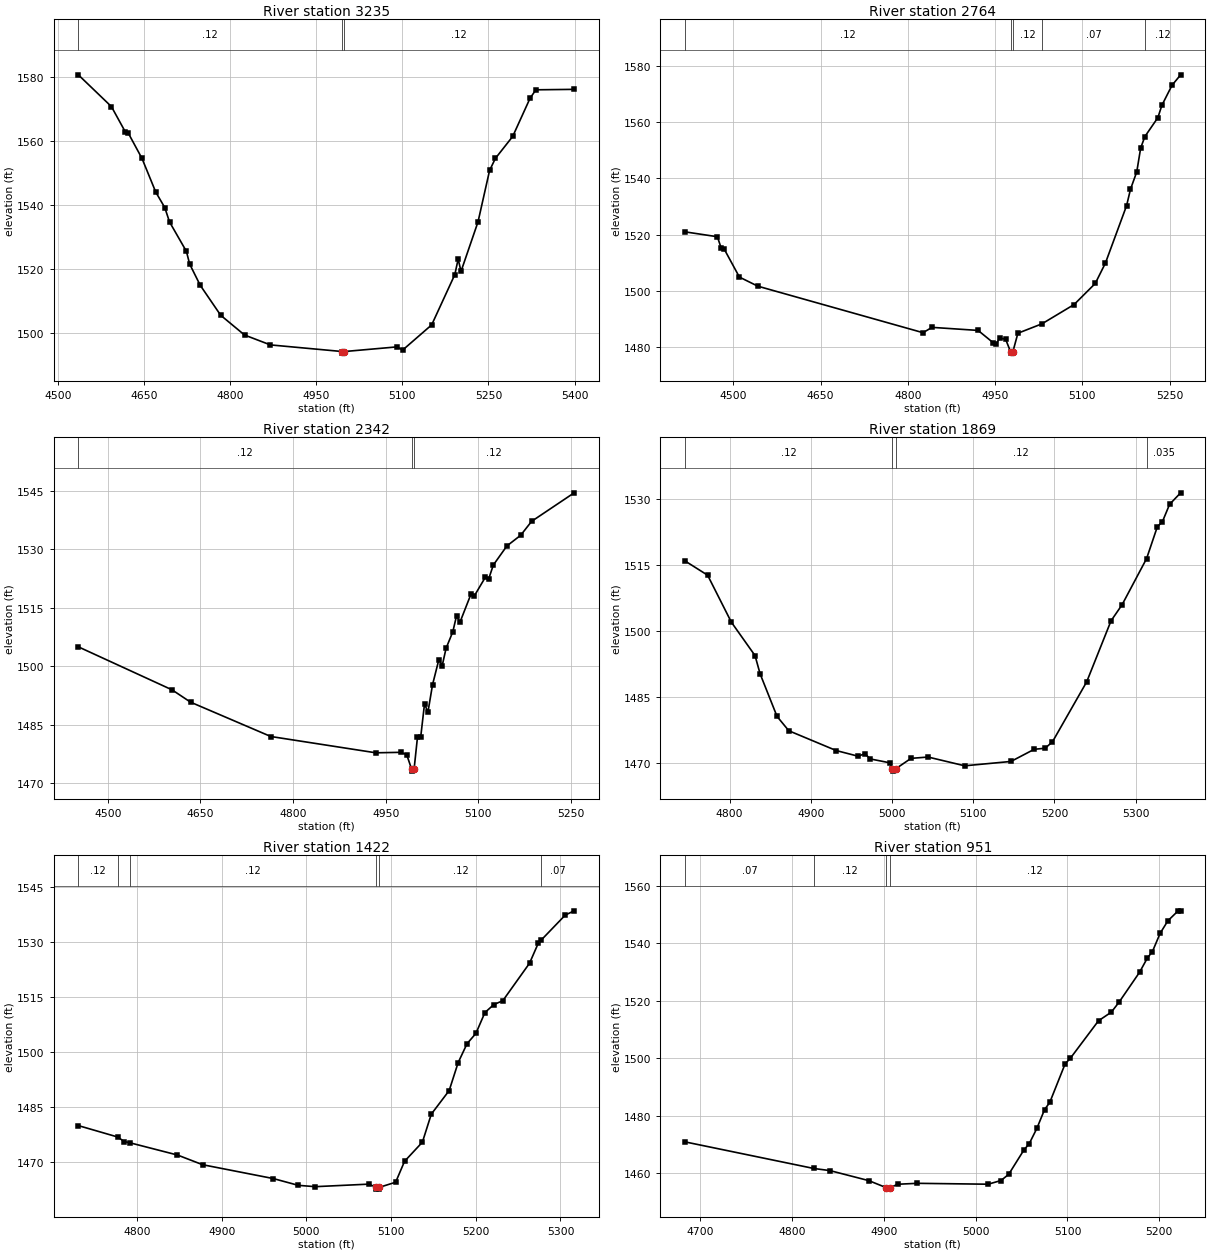
Type RM Length L Ch R = 1,3235,471,471,471
BEGIN DESCRIPTION:
Stream0048_DS 7.0
END DESCRIPTION:
XS GIS Cut Line= 3
      2047998.50     13856854.23      2048175.00     13856425.00
      2048124.59     13856028.90
#Sta/Elev= 30
  4535.9 1580.74  4593.5 1570.82  4617.4 1563.02  4622.8 1562.56  4646.8 1554.60
  4670.8 1544.07  4686.4 1539.28  4694.7 1534.78  4724.1 1525.58  4729.7 1521.64
  4748.1 1515.00  4783.8 1505.62  4825.3 1499.45  4870.3 1496.36  4995.3 1494.29
  4995.5 1493.79  4999.3 1494.29  5090.7 1495.74  5100.8 1494.77  5151.2 1502.62
  5191.5 1518.33  5197.3 1523.17  5202.3 1519.33  5231.9 1534.81  5252.0 1550.85
  5262.1 1554.62  5292.3 1561.50  5322.6 1573.46  5332.7 1576.06  5399.3 1576.20
#Mann=3,-1,0
  4535.9    0.12       0  4995.3    0.05       0  4999.3    0.12       0
Bank Sta=4995.3,4999.3
Exp/Cntr=0.3,0.1

Type RM Length L Ch R = 1,2764,422,422,422
BEGIN DESCRIPTION:
Stream0048_DS 6.0
END DESCRIPTION:
XS GIS Cut Line= 3
      2048710.15     13856728.06      2048525.00     13856175.00
      2048274.99     13856075.00
#Sta/Elev= 30
  4416.5 1521.02  4472.5 1519.27  4478.8 1515.40  4484.1 1514.93  4510.4 1504.91
  4542.0 1501.68  4826.1 1485.12  4841.5 1487.02  4920.8 1485.93  4947.0 1481.51
  4952.4 1481.18  4957.6 1483.21  4968.1 1482.79  4976.6 1478.35  4976.9 1477.85
  4980.6 1478.35  4989.2 1484.93  5030.7 1488.29  5085.9 1495.15  5122.2 1502.64
  5139.7 1509.90  5176.1 1530.34  5182.8 1536.16  5193.6 1542.38  5200.3 1550.84
  5207.6 1554.94  5229.9 1561.66  5236.7 1566.01  5254.2 1573.17  5269.0 1576.89
#Mann=5,-1,0
  4416.5    0.12       0  4976.6    0.05       0  4980.6    0.12       0
  5030.7    0.07       0  5207.6    0.12       0
Bank Sta=4976.6,4980.6
Exp/Cntr=0.3,0.1

Type RM Length L Ch R = 1,2342,473,473,473
BEGIN DESCRIPTION:
Stream0048_DS 5.0
END DESCRIPTION:
XS GIS Cut Line= 3
      2048887.25     13856526.76      2048875.00     13855975.00
      2048772.67     13855745.48
#Sta/Elev= 30
  4452.1 1504.97  4603.9 1493.94  4633.9 1490.78  4763.9 1481.97  4934.0 1477.79
  4974.0 1477.91  4984.0 1477.33  4992.0 1473.59  4992.2 1473.09  4996.0 1473.59
  5001.5 1481.82  5006.7 1481.82  5012.9 1490.35  5018.4 1488.20  5025.9 1495.27
  5036.1 1501.67  5041.6 1500.18  5047.8 1504.59  5058.7 1508.82  5064.8 1512.94
  5070.3 1511.27  5088.0 1518.43  5093.5 1518.01  5111.3 1522.78  5116.7 1522.33
  5124.4 1525.96  5146.3 1530.84  5168.7 1533.59  5186.4 1537.16  5255.3 1544.47
#Mann=3,-1,0
  4452.1    0.12       0  4992.0    0.05       0  4996.0    0.12       0
Bank Sta=4992,4996
Exp/Cntr=0.3,0.1

Type RM Length L Ch R = 1,1869,447,447,447
BEGIN DESCRIPTION:
Stream0048_DS 4.0
END DESCRIPTION:
XS GIS Cut Line= 3
      2049425.01     13856275.01      2049275.00     13856075.00
      2049074.98     13855774.97
#Sta/Elev= 30
  4744.8 1515.88  4772.9 1512.61  4802.1 1501.95  4831.3 1494.35  4837.5 1490.23
  4858.4 1480.53  4872.9 1477.28  4931.3 1472.78  4958.4 1471.49  4966.7 1472.10
  4972.9 1470.89  4997.8 1469.98  5000.3 1468.61  5000.6 1468.11  5004.3 1468.61
  5023.4 1471.01  5044.4 1471.31  5089.5 1469.32  5146.5 1470.31  5175.1 1473.07
  5188.6 1473.31  5197.6 1474.78  5239.7 1488.38  5269.7 1502.25  5283.3 1505.90
  5313.5 1516.39  5326.8 1523.66  5332.8 1524.69  5341.8 1528.70  5355.4 1531.32
#Mann=4,-1,0
  4744.8    0.12       0  5000.3    0.05       0  5004.3    0.12       0
  5313.5   0.035       0
Bank Sta=5000.3,5004.3
Exp/Cntr=0.3,0.1

Type RM Length L Ch R = 1,1422,471,471,471
BEGIN DESCRIPTION:
Stream0048_DS 3.0
END DESCRIPTION:
XS GIS Cut Line= 3
      2049575.00     13855975.01      2049475.00     13855725.00
      2049175.00     13855625.00
#Sta/Elev= 30
  4730.7 1480.04  4777.6 1476.90  4784.6 1475.70  4792.2 1475.32  4847.8 1472.02
  4877.5 1469.38  4960.9 1465.61  4990.5 1463.76  5010.5 1463.40  5073.8 1464.09
  5082.3 1463.23  5082.5 1462.73  5086.0 1462.73  5086.3 1463.23  5105.4 1464.61
  5115.9 1470.30  5137.0 1475.53  5147.5 1483.16  5168.6 1489.58  5179.2 1497.19
  5189.7 1502.35  5200.2 1505.16  5210.8 1510.83  5221.3 1513.01  5231.9 1514.05
  5263.5 1524.27  5274.0 1529.82  5277.4 1530.61  5305.7 1537.39  5316.2 1538.55
#Mann=6,-1,0
  4730.7    0.12       0  4777.6    0.07       0  4792.2    0.12       0
  5082.3    0.05       0  5086.3    0.12       0  5277.4    0.07       0
Bank Sta=5082.3,5086.3
Exp/Cntr=0.3,0.1

Type RM Length L Ch R = 1,951,415,415,415
BEGIN DESCRIPTION:
Stream0048_DS 2.0
END DESCRIPTION:
XS GIS Cut Line= 3
      2049975.00     13855825.01      2049875.00     13855525.00
      2049775.02     13855325.04
#Sta/Elev= 30
  4683.4 1470.97  4823.9 1461.70  4841.5 1460.96  4883.7 1457.48  4902.8 1455.02
  4903.0 1454.52  4906.5 1454.52  4906.8 1455.02  4915.3 1456.22  4936.4 1456.54
  5013.6 1456.23  5027.6 1457.51  5036.0 1459.66  5052.7 1468.20  5058.3 1470.28
  5066.7 1475.66  5075.1 1482.21  5080.7 1484.66  5097.5 1498.13  5103.1 1500.02
  5133.8 1513.09  5147.8 1516.09  5156.2 1519.57  5178.5 1529.96  5186.9 1534.86
  5192.5 1537.17  5200.9 1543.51  5209.3 1547.85  5220.5 1551.33  5223.2 1551.33
#Mann=4,-1,0
  4683.4    0.07       0  4823.9    0.12       0  4902.8    0.05       0
  4906.8    0.12       0
Bank Sta=4902.8,4906.8
Exp/Cntr=0.3,0.1

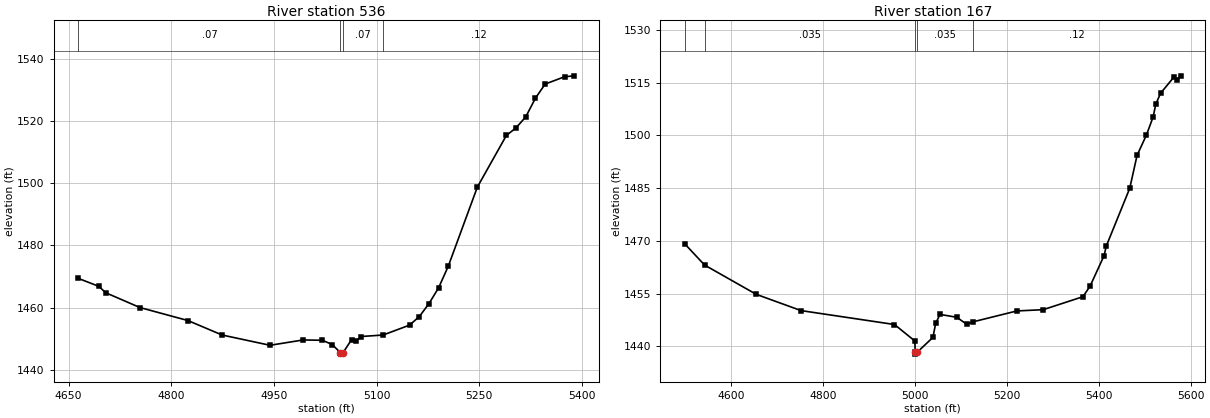
Type RM Length L Ch R = 1,536,369,369,369
BEGIN DESCRIPTION:
Stream0048_DS 1.0
END DESCRIPTION:
XS GIS Cut Line= 3
      2050275.00     13855774.97      2050275.00     13855475.00
      2049975.02     13855175.02
#Sta/Elev= 30
  4664.3 1469.40  4694.3 1466.84  4704.3 1464.79  4754.3 1460.04  4824.3 1455.87
  4874.3 1451.22  4944.3 1447.92  4992.6 1449.63  5020.8 1449.53  5035.0 1448.17
  5047.1 1445.58  5047.4 1445.08  5051.1 1445.58  5063.3 1449.71  5070.3 1449.37
  5077.4 1450.74  5109.4 1451.21  5148.1 1454.40  5162.3 1457.13  5176.4 1461.29
  5190.5 1466.37  5204.7 1473.35  5247.1 1498.72  5289.5 1515.30  5303.7 1517.77
  5317.8 1521.28  5332.0 1527.29  5346.1 1531.80  5374.4 1534.15  5388.5 1534.45
#Mann=4,-1,0
  4664.3    0.07       0  5047.1    0.05       0  5051.1    0.07       0
  5109.4    0.12       0
Bank Sta=5047.1,5051.1
Exp/Cntr=0.3,0.1

Type RM Length L Ch R = 1,167,0,0,0
BEGIN DESCRIPTION:
Stream0048_DS 0.0
END DESCRIPTION:
XS GIS Cut Line= 5
      2050405.80     13855832.71      2050579.09     13855456.50
      2050573.26     13855370.80      2050346.09     13855229.22
      2050042.16     13855168.05
#Sta/Elev= 30
  4499.9 1469.11  4542.9 1463.10  4655.2 1454.77  4752.5 1450.15  4955.7 1446.19
  5000.0 1441.50  5000.7 1438.27  5000.9 1437.77  5004.7 1438.27  5039.3 1442.53
  5045.2 1446.49  5054.6 1449.07  5091.2 1448.24  5112.4 1446.29  5126.0 1446.94
  5221.8 1450.05  5279.0 1450.41  5365.4 1454.10  5381.0 1457.13  5411.1 1465.72
  5416.2 1468.53  5467.1 1484.93  5483.0 1494.28  5503.4 1500.08  5517.9 1505.20
  5523.8 1508.86  5534.0 1511.92  5563.7 1516.64  5568.8 1515.71  5577.7 1516.90
#Mann=5,-1,0
  4499.9    0.07       0  4542.9   0.035       0  5000.7   0.035       0
  5004.7   0.035       0  5126.0    0.12       0
Bank Sta=5000.7,5004.7
Exp/Cntr=0.3,0.1

Chan Stop Cuts=-1