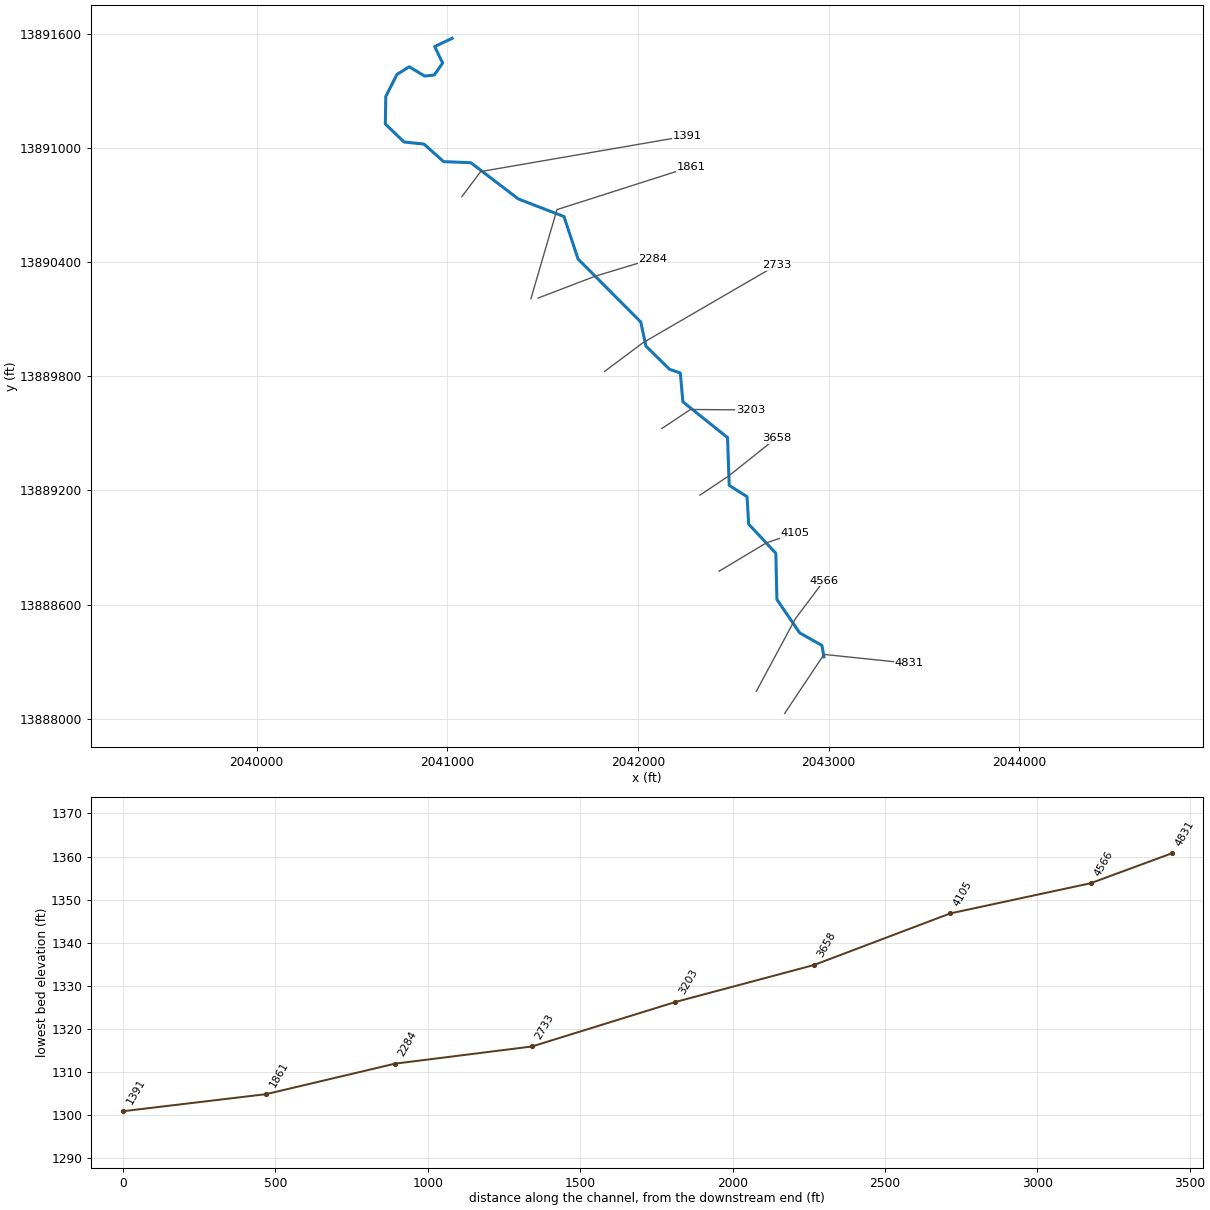
--- Stream0049_DS.prj (project) ---

Proj Title=Stream0049_DS Base Level Engineering
Current Plan=p01
Default Exp/Contr=0.3,0.1
English Units
Geom File=g01
Flow File=f01
Plan File=p01
BEGIN DESCRIPTION:
Stream0049_DS
END DESCRIPTION:

--- Stream0049_DS.p01 (plan) ---

Plan Title=Multiple Run
Short Identifier=Multiple
Geom File=g01
Flow File=f01
Subcritical Flow
K Sum by GR= 0
Std Step Tol= 0.01
Critical Tol= 0.01
Num of Std Step Trials= 20
Max Error Tol= 0.3
Flow Tol Ratio= 0.001
Split Flow NTrial= 30
Split Flow Tol= 0.02
Split Flow Ratio= 0.02
Log Output Level= 0
Friction Slope Method= 1
Unsteady Friction Slope Method= 2
Unsteady Bridges Friction Slope Method= 1
Parabolic Critical Depth
Global Vel Dist=  1 , 1 , 1
Global Log Level= 0
CheckData=True
Encroach Param= -1, 0, 0, 0
BEGIN DESCRIPTION:
Multiple Run
END DESCRIPTION:

--- Stream0049_DS.f01 (steady flow) ---

Flow Title=Multiple
Number of Profiles=7
Profile Names=10-year,25-year,50-year,1pct_min,100-year,1pct_plu,500-year
River Rch & RM= Stream0049_DS,Reach-1,4831
     386     611     814     528    1053    2100    1736
River Rch & RM= Stream0049_DS,Reach-1,3658
     591     963    1304     858    1713    3418    2917
Boundary for River Rch & Prof#=Stream0049_DS,Reach-1,1
Up Type=0
Dn Type=3
Dn Slope=0.005
Boundary for River Rch & Prof#=Stream0049_DS,Reach-1,2
Up Type=0
Dn Type=3
Dn Slope=0.005
Boundary for River Rch & Prof#=Stream0049_DS,Reach-1,3
Up Type=0
Dn Type=3
Dn Slope=0.005
Boundary for River Rch & Prof#=Stream0049_DS,Reach-1,4
Up Type=0
Dn Type=3
Dn Slope=0.005
Boundary for River Rch & Prof#=Stream0049_DS,Reach-1,5
Up Type=0
Dn Type=3
Dn Slope=0.005
Boundary for River Rch & Prof#=Stream0049_DS,Reach-1,6
Up Type=0
Dn Type=3
Dn Slope=0.005
Boundary for River Rch & Prof#=Stream0049_DS,Reach-1,7
Up Type=0
Dn Type=3
Dn Slope=0.005

--- Stream0049_DS.g01 (geometry) ---

Geom Title=Existing Conditions

River Reach=Stream0049_DS,Reach-1
Reach XY= 30
      2042975.00     13888325.00      2042964.67     13888385.25
      2042847.86     13888451.16      2042728.55     13888626.47
      2042722.83     13888869.56      2042580.47     13889022.56
      2042571.89     13889166.68      2042478.48     13889226.26
      2042469.55     13889477.47      2042235.47     13889665.18
      2042221.92     13889816.69      2042165.63     13889835.91
      2042041.46     13889958.25      2042014.48     13890084.79
      2041685.76     13890415.32      2041611.77     13890638.72
      2041372.71     13890730.84      2041123.53     13890921.45
      2040980.45     13890927.19      2040877.42     13891019.46
      2040772.55     13891030.46      2040675.00     13891125.00
      2040677.19     13891269.09      2040735.63     13891385.12
      2040799.88     13891425.52      2040881.17     13891376.79
      2040931.43     13891382.37      2040975.37     13891445.03
      2040933.81     13891531.96      2041025.00     13891575.00

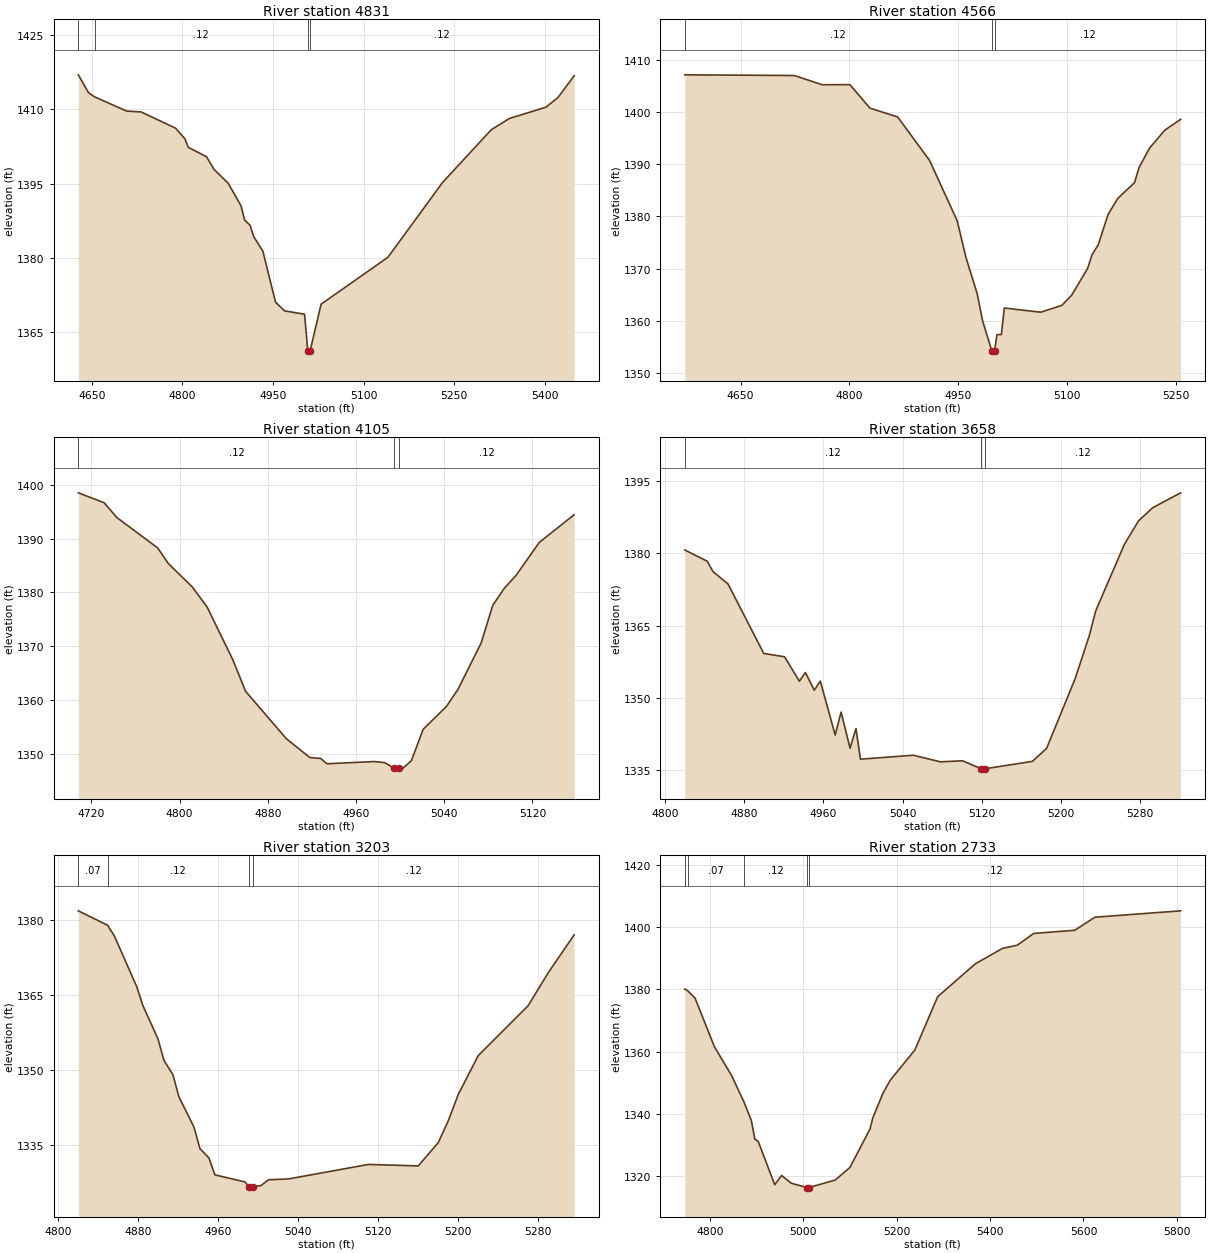
Type RM Length L Ch R = 1,4831,265,265,265
BEGIN DESCRIPTION:
Stream0049_DS 11.0
END DESCRIPTION:
XS GIS Cut Line= 3
      2042769.12     13888028.24      2042975.44     13888338.02
      2043421.62     13888291.46
#Sta/Elev= 30
  4627.8 1416.97  4644.7 1413.36  4654.7 1412.52  4708.0 1409.64  4731.8 1409.47
  4788.9 1406.18  4804.0 1404.07  4810.0 1402.30  4840.0 1400.43  4852.2 1397.90
  4876.1 1395.03  4897.1 1390.50  4903.1 1387.61  4912.1 1386.58  4918.1 1384.26
  4933.2 1381.37  4954.2 1371.04  4969.2 1369.27  5002.3 1368.59  5007.6 1361.23
  5007.9 1360.73  5011.6 1361.23  5029.7 1370.62  5140.3 1380.10  5230.8 1395.22
  5311.2 1405.85  5341.4 1408.15  5401.7 1410.42  5421.8 1412.38  5448.6 1416.79
#Mann=4,-1,0
  4627.8    0.07       0  4654.7    0.12       0  5007.6    0.05       0
  5011.6    0.12       0
Bank Sta=5007.6,5011.6
Exp/Cntr=0.3,0.1

Type RM Length L Ch R = 1,4566,461,461,461
BEGIN DESCRIPTION:
Stream0049_DS 10.0
END DESCRIPTION:
XS GIS Cut Line= 3
      2042620.30     13888143.84      2042825.00     13888525.00
      2042974.97     13888724.96
#Sta/Elev= 30
  4573.3 1407.14  4724.2 1407.01  4762.4 1405.24  4800.6 1405.26  4828.2 1400.76
  4866.3 1399.07  4910.2 1390.76  4948.3 1379.18  4960.5 1372.08  4975.9 1365.18
  4983.2 1360.04  4995.8 1354.31  4996.1 1353.81  4999.8 1354.31  5003.1 1357.36
  5009.1 1357.36  5013.2 1362.46  5063.2 1361.65  5092.4 1362.96  5105.9 1364.91
  5127.8 1370.03  5134.1 1372.70  5142.4 1374.54  5155.9 1380.34  5169.5 1383.48
  5192.4 1386.47  5198.7 1389.38  5213.2 1393.11  5234.1 1396.53  5255.9 1398.61
#Mann=3,-1,0
  4573.3    0.12       0  4995.8    0.05       0  4999.8    0.12       0
Bank Sta=4995.8,4999.8
Exp/Cntr=0.3,0.1

Type RM Length L Ch R = 1,4105,447,447,447
BEGIN DESCRIPTION:
Stream0049_DS 9.0
END DESCRIPTION:
XS GIS Cut Line= 3
      2042424.96     13888774.97      2042675.00     13888925.00
      2042824.99     13888975.00
#Sta/Elev= 30
  4708.1 1398.51  4731.5 1396.67  4743.1 1393.91  4780.1 1388.27  4789.8 1385.35
  4811.2 1381.08  4824.8 1377.33  4848.1 1367.54  4859.8 1361.62  4896.7 1352.83
  4918.1 1349.31  4927.8 1349.15  4933.6 1348.16  4976.4 1348.57  4986.1 1348.37
  4994.8 1347.29  4995.0 1346.79  4998.5 1346.79  4998.8 1347.29  5002.3 1347.29
  5010.2 1348.74  5020.8 1354.55  5041.9 1358.80  5052.4 1361.97  5073.5 1370.64
  5084.0 1377.61  5094.6 1380.81  5105.1 1383.16  5126.2 1389.30  5157.8 1394.44
#Mann=3,-1,0
  4708.1    0.12       0  4994.8    0.05       0  4998.8    0.12       0
Bank Sta=4994.8,4998.8
Exp/Cntr=0.3,0.1

Type RM Length L Ch R = 1,3658,455,455,455
BEGIN DESCRIPTION:
Stream0049_DS 8.0
END DESCRIPTION:
XS GIS Cut Line= 3
      2042324.96     13889174.98      2042475.00     13889275.00
      2042725.02     13889475.01
#Sta/Elev= 30
  4820.2 1380.73  4842.8 1378.39  4848.8 1376.21  4863.8 1373.68  4899.9 1359.24
  4920.9 1358.55  4935.9 1353.47  4941.9 1355.29  4950.9 1351.62  4957.0 1353.50
  4972.0 1342.31  4978.0 1347.07  4987.0 1339.57  4993.0 1343.65  4997.5 1337.29
  5050.9 1338.11  5078.2 1336.74  5100.6 1336.96  5119.4 1335.31  5119.6 1334.81
  5123.4 1335.31  5171.0 1336.83  5185.4 1339.53  5214.2 1353.99  5228.6 1362.99
  5235.0 1368.09  5263.9 1381.88  5278.3 1386.80  5292.7 1389.52  5320.7 1392.59
#Mann=3,-1,0
  4820.2    0.12       0  5119.4    0.05       0  5123.4    0.12       0
Bank Sta=5119.4,5123.4
Exp/Cntr=0.3,0.1

Type RM Length L Ch R = 1,3203,470,470,470
BEGIN DESCRIPTION:
Stream0049_DS 7.0
END DESCRIPTION:
XS GIS Cut Line= 3
      2042124.97     13889524.98      2042275.00     13889625.00
      2042590.97     13889622.46
#Sta/Elev= 30
  4820.2 1381.92  4849.5 1379.03  4856.3 1376.88  4878.8 1366.67  4884.8 1362.97
  4899.9 1356.30  4905.9 1351.99  4914.9 1349.10  4920.9 1344.67  4935.9 1338.65
  4941.9 1334.33  4950.9 1332.46  4956.9 1329.07  4987.0 1327.65  4991.0 1326.71
  4991.3 1326.21  4994.8 1326.21  4995.0 1326.71  5003.0 1326.92  5010.5 1328.08
  5030.5 1328.25  5110.5 1331.15  5160.5 1330.86  5180.5 1335.52  5190.5 1339.89
  5200.5 1345.17  5220.5 1352.94  5270.5 1362.94  5290.5 1369.52  5316.5 1377.11
#Mann=4,-1,0
  4820.2    0.07       0  4849.5    0.12       0  4991.0    0.05       0
  4995.0    0.12       0
Bank Sta=4991,4995
Exp/Cntr=0.3,0.1

Type RM Length L Ch R = 1,2733,449,449,449
BEGIN DESCRIPTION:
Stream0049_DS 6.0
END DESCRIPTION:
XS GIS Cut Line= 3
      2041824.99     13889824.99      2042025.00     13889975.00
      2042727.04     13890383.39
#Sta/Elev= 30
  4746.0 1380.14  4752.4 1379.58  4767.9 1377.26  4809.6 1361.57  4846.0 1352.45
  4872.7 1343.89  4888.7 1337.88  4896.0 1331.95  4903.3 1331.19  4938.7 1317.30
  4953.3 1320.28  4974.1 1317.78  5007.7 1316.39  5007.9 1315.89  5011.7 1316.39
  5068.4 1318.82  5099.9 1322.87  5142.9 1335.25  5148.7 1338.72  5170.2 1346.57
  5185.9 1350.82  5238.9 1360.58  5287.7 1377.67  5368.0 1388.21  5426.7 1393.20
  5458.2 1394.22  5493.5 1398.00  5581.5 1399.01  5624.5 1403.21  5808.2 1405.26
#Mann=5,-1,0
  4746.0    0.12       0  4752.4    0.07       0  4872.7    0.12       0
  5007.7    0.05       0  5011.7    0.12       0
Bank Sta=5007.7,5011.7
Exp/Cntr=0.3,0.1

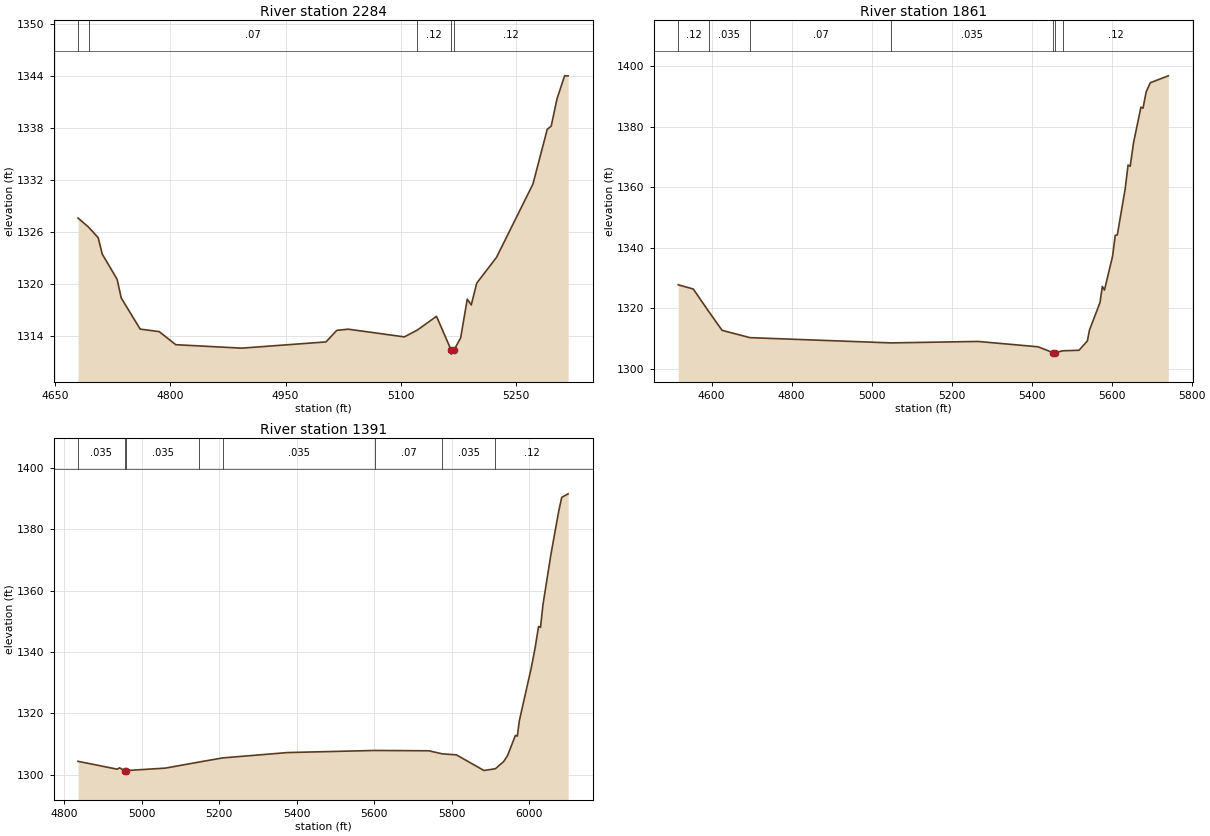
Type RM Length L Ch R = 1,2284,423,423,423
BEGIN DESCRIPTION:
Stream0049_DS 5.0
END DESCRIPTION:
XS GIS Cut Line= 3
      2041476.33     13890210.33      2041775.00     13890325.00
      2042078.84     13890417.05
#Sta/Elev= 30
  4680.1 1327.61  4693.8 1326.56  4706.3 1325.34  4711.6 1323.45  4730.9 1320.54
  4736.3 1318.38  4760.9 1314.79  4785.6 1314.50  4807.2 1312.99  4892.9 1312.59
  5002.6 1313.31  5016.5 1314.64  5031.4 1314.78  5104.5 1313.89  5121.4 1314.68
  5146.3 1316.27  5165.2 1312.40  5165.5 1311.90  5169.2 1312.40  5177.7 1313.77
  5186.3 1318.25  5191.5 1317.58  5198.6 1320.09  5224.4 1323.08  5271.7 1331.53
  5290.3 1337.85  5295.5 1338.23  5303.0 1341.37  5312.9 1344.03  5317.5 1344.03
#Mann=5,-1,0
  4680.1    0.12       0  4693.8    0.07       0  5121.4    0.12       0
  5165.2    0.05       0  5169.2    0.12       0
Bank Sta=5165.2,5169.2
Exp/Cntr=0.3,0.1

Type RM Length L Ch R = 1,1861,470,470,470
BEGIN DESCRIPTION:
Stream0049_DS 4.0
END DESCRIPTION:
XS GIS Cut Line= 3
      2041438.47     13890207.16      2041575.00     13890675.00
      2042277.68     13890900.07
#Sta/Elev= 30
  4516.4 1327.73  4554.1 1326.34  4592.3 1318.98  4626.2 1312.67  4695.7 1310.27
  5048.3 1308.53  5266.3 1309.01  5416.0 1307.24  5453.3 1305.32  5453.5 1304.82
  5457.3 1305.32  5478.1 1305.92  5518.3 1306.10  5539.3 1309.17  5544.6 1312.81
  5570.8 1321.83  5576.7 1327.20  5582.0 1325.99  5602.3 1337.19  5608.9 1344.06
  5614.1 1344.20  5633.8 1359.43  5641.0 1367.29  5646.3 1366.88  5654.8 1374.73
  5673.2 1386.43  5678.4 1386.08  5686.3 1391.50  5696.8 1394.50  5741.6 1396.77
#Mann=7,-1,0
  4516.4    0.12       0  4592.3   0.035       0  4695.7    0.07       0
  5048.3   0.035       0  5453.3    0.05       0  5457.3   0.035       0
  5478.1    0.12       0
Bank Sta=5453.3,5457.3
Exp/Cntr=0.3,0.1

Type RM Length L Ch R = 1,1391,0,0,0
BEGIN DESCRIPTION:
Stream0049_DS 3.0
END DESCRIPTION:
XS GIS Cut Line= 3
      2041076.26     13890743.35      2041175.00     13890875.00
      2042259.06     13891062.36
#Sta/Elev= 30
  4835.4 1304.37  4936.4 1301.81  4942.7 1302.25  4955.3 1301.35  4955.5 1300.85
  4959.3 1301.35  5060.9 1302.16  5148.5 1304.15  5208.5 1305.48  5375.4 1307.22
  5602.2 1307.91  5740.8 1307.80  5775.0 1306.81  5811.8 1306.47  5882.9 1301.39
  5912.3 1301.95  5933.6 1304.28  5943.8 1306.23  5963.9 1312.80  5969.0 1312.59
  5974.2 1317.62  6004.6 1334.62  6014.8 1341.22  6023.7 1348.29  6028.8 1347.98
  6035.1 1355.33  6055.4 1371.55  6075.7 1385.78  6083.5 1390.34  6100.1 1391.50
#Mann=8,-1,0
  4835.4   0.035       0  4955.3   0.035       0  4959.3   0.035       0
  5148.5    0.07       0  5208.5   0.035       0  5602.2    0.07       0
  5775.0   0.035       0  5912.3    0.12       0
Bank Sta=4955.3,4959.3
Exp/Cntr=0.3,0.1

Chan Stop Cuts=-1