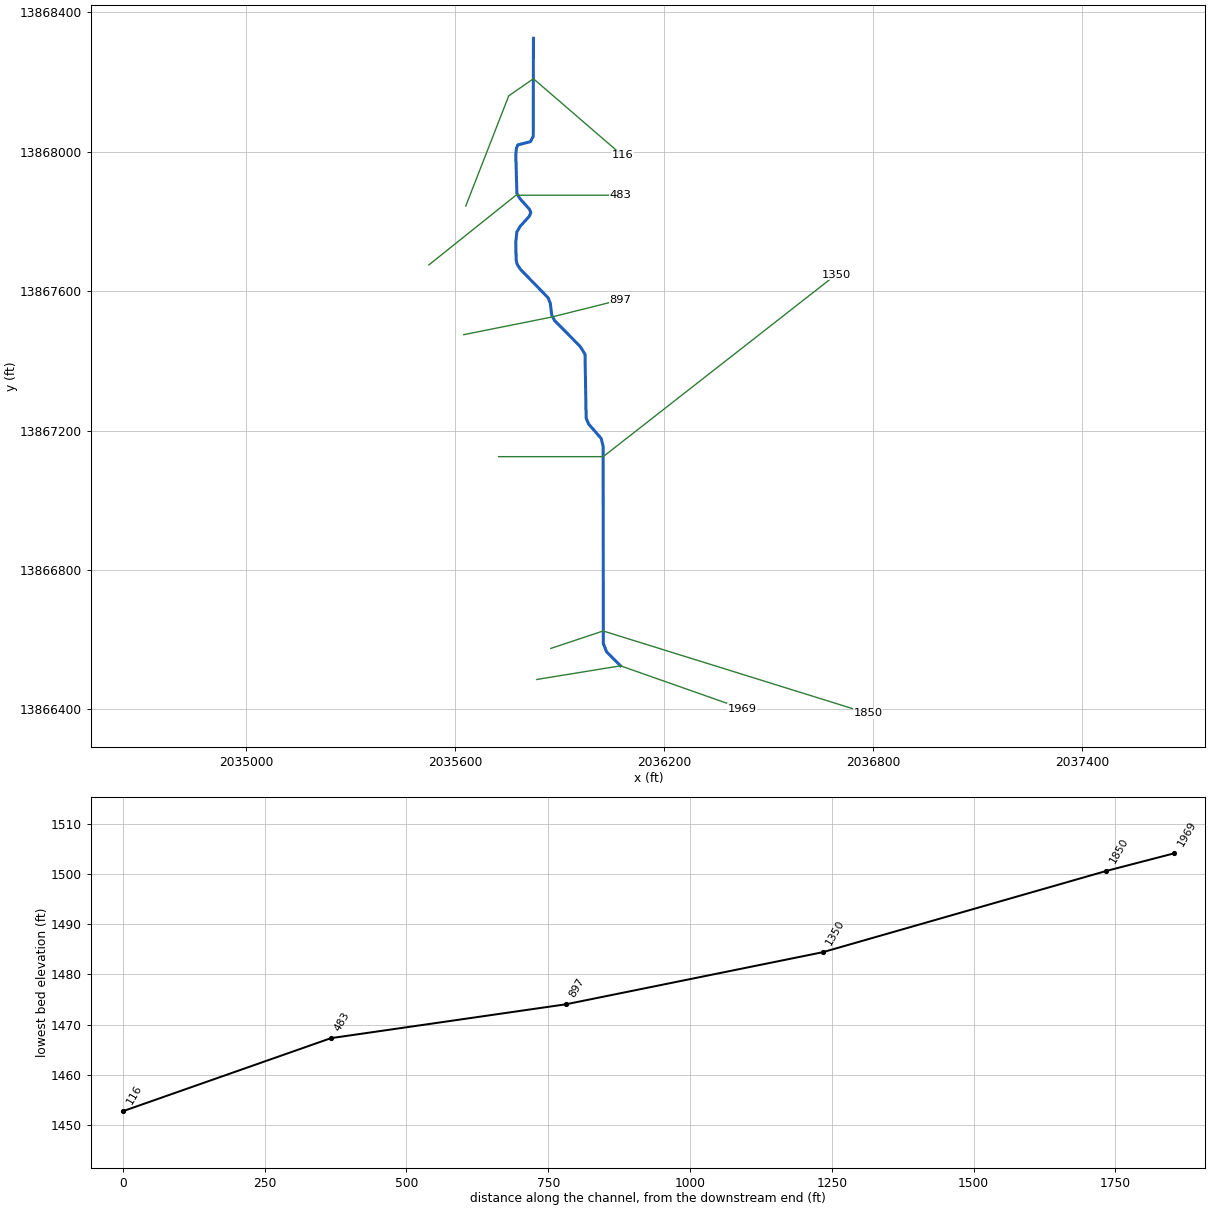
--- Stream0050_DS.prj (project) ---

Proj Title=Stream0050_DS Base Level Engineering
Current Plan=p01
Default Exp/Contr=0.3,0.1
English Units
Geom File=g01
Flow File=f01
Plan File=p01
BEGIN DESCRIPTION:
Stream0050_DS
END DESCRIPTION:

--- Stream0050_DS.p01 (plan) ---

Plan Title=Multiple Run
Short Identifier=Multiple
Geom File=g01
Flow File=f01
Subcritical Flow
K Sum by GR= 0
Std Step Tol= 0.01
Critical Tol= 0.01
Num of Std Step Trials= 20
Max Error Tol= 0.3
Flow Tol Ratio= 0.001
Split Flow NTrial= 30
Split Flow Tol= 0.02
Split Flow Ratio= 0.02
Log Output Level= 0
Friction Slope Method= 1
Unsteady Friction Slope Method= 2
Unsteady Bridges Friction Slope Method= 1
Parabolic Critical Depth
Global Vel Dist=  1 , 1 , 1
Global Log Level= 0
CheckData=True
Encroach Param= -1, 0, 0, 0
BEGIN DESCRIPTION:
Multiple Run
END DESCRIPTION:

--- Stream0050_DS.f01 (steady flow) ---

Flow Title=Multiple
Number of Profiles=7
Profile Names=10-year,25-year,50-year,1pct_min,100-year,1pct_plu,500-year
River Rch & RM= Stream0050_DS,Reach-1,1969
     337     530     702     454     906    1808    1483
River Rch & RM= Stream0050_DS,Reach-1,1350
     621    1020    1391     923    1841    3674    3183
Boundary for River Rch & Prof#=Stream0050_DS,Reach-1,1
Up Type=0
Dn Type=3
Dn Slope=0.005
Boundary for River Rch & Prof#=Stream0050_DS,Reach-1,2
Up Type=0
Dn Type=3
Dn Slope=0.005
Boundary for River Rch & Prof#=Stream0050_DS,Reach-1,3
Up Type=0
Dn Type=3
Dn Slope=0.005
Boundary for River Rch & Prof#=Stream0050_DS,Reach-1,4
Up Type=0
Dn Type=3
Dn Slope=0.005
Boundary for River Rch & Prof#=Stream0050_DS,Reach-1,5
Up Type=0
Dn Type=3
Dn Slope=0.005
Boundary for River Rch & Prof#=Stream0050_DS,Reach-1,6
Up Type=0
Dn Type=3
Dn Slope=0.005
Boundary for River Rch & Prof#=Stream0050_DS,Reach-1,7
Up Type=0
Dn Type=3
Dn Slope=0.005

--- Stream0050_DS.g01 (geometry) ---

Geom Title=Existing Conditions

River Reach=Stream0050_DS,Reach-1
Reach XY= 30
      2036075.00     13866525.00      2036035.05     13866565.02
      2036025.50     13866588.84      2036024.93     13867154.97
      2036019.25     13867177.33      2035983.14     13867218.94
      2035976.22     13867235.51      2035972.93     13867419.14
      2035958.54     13867441.75      2035885.80     13867515.33
      2035877.65     13867530.64      2035873.29     13867565.20
      2035866.82     13867581.04      2035788.36     13867661.71
      2035778.47     13867676.50      2035775.41     13867688.92
      2035774.33     13867740.08      2035777.36     13867769.10
      2035786.16     13867784.78      2035813.52     13867815.09
      2035817.44     13867825.00      2035813.52     13867834.90
      2035786.20     13867865.21      2035777.56     13867880.46
      2035774.45     13867989.13      2035776.18     13868010.16
      2035780.61     13868019.37      2035816.41     13868028.58
      2035824.50     13868043.68      2035825.00     13868325.00

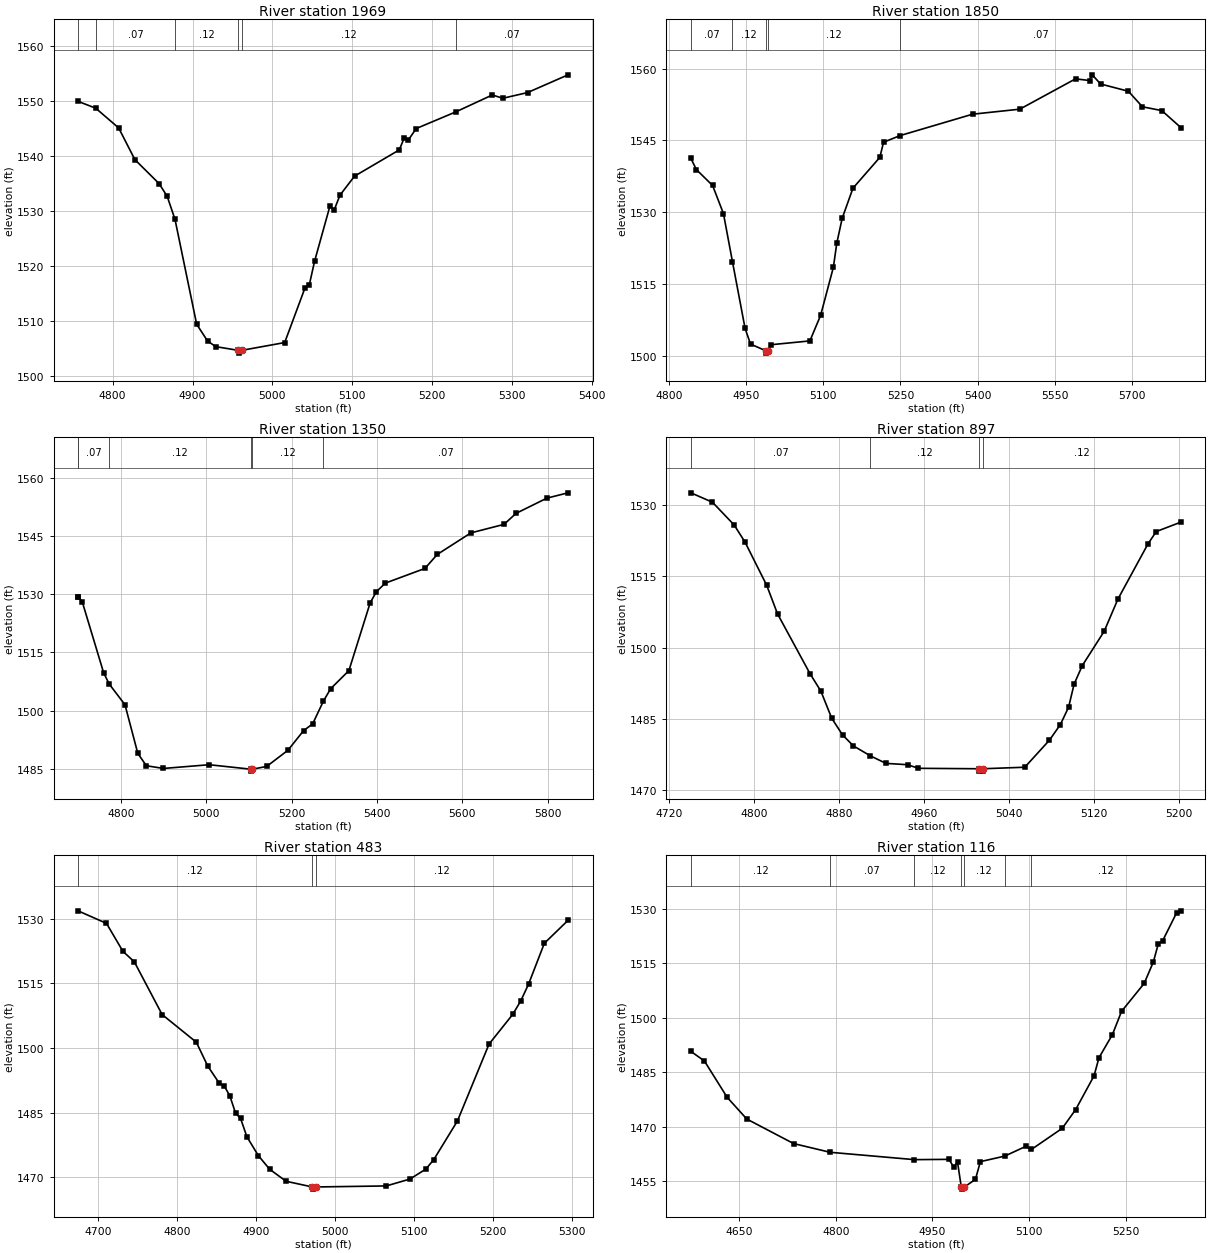
Type RM Length L Ch R = 1,1969,119,119,119
BEGIN DESCRIPTION:
Stream0050_DS 5.0
END DESCRIPTION:
XS GIS Cut Line= 3
      2035834.72     13866485.92      2036075.00     13866525.00
      2036424.51     13866401.93
#Sta/Elev= 30
  4756.6 1549.86  4778.7 1548.62  4807.5 1545.03  4827.8 1539.27  4858.2 1534.90
  4868.3 1532.59  4878.1 1528.39  4905.2 1509.35  4918.9 1506.30  4929.1 1505.28
  4957.5 1504.60  4957.7 1504.10  4961.5 1504.60  5015.5 1506.02  5041.1 1516.02
  5046.4 1516.55  5053.0 1520.84  5072.1 1530.79  5077.4 1530.08  5084.8 1532.82
  5103.0 1536.26  5159.0 1541.03  5165.0 1543.11  5170.3 1542.81  5180.2 1544.91
  5229.8 1547.94  5275.6 1551.02  5288.8 1550.42  5319.7 1551.45  5370.5 1554.68
#Mann=6,-1,0
  4756.6   0.035       0  4778.7    0.07       0  4878.1    0.12       0
  4957.5    0.05       0  4961.5    0.12       0  5229.8    0.07       0
Bank Sta=4957.5,4961.5
Exp/Cntr=0.3,0.1

Type RM Length L Ch R = 1,1850,500,500,500
BEGIN DESCRIPTION:
Stream0050_DS 4.0
END DESCRIPTION:
XS GIS Cut Line= 3
      2035874.96     13866574.99      2036025.00     13866625.00
      2036784.31     13866388.62
#Sta/Elev= 30
  4842.2 1541.25  4852.8 1538.93  4884.4 1535.60  4905.5 1529.74  4923.1 1519.67
  4947.6 1505.77  4958.2 1502.50  4987.8 1501.11  4988.1 1500.61  4991.8 1501.11
  4997.7 1502.36  5073.7 1503.16  5094.6 1508.50  5119.4 1518.53  5126.0 1523.54
  5136.5 1528.74  5157.5 1535.04  5209.8 1541.47  5217.0 1544.63  5249.3 1546.02
  5390.2 1550.48  5482.1 1551.53  5590.6 1557.86  5617.9 1557.51  5623.1 1558.70
  5639.2 1556.79  5693.4 1555.27  5720.7 1552.03  5758.5 1551.23  5795.6 1547.68
#Mann=5,-1,0
  4842.2    0.07       0  4923.1    0.12       0  4987.8    0.05       0
  4991.8    0.12       0  5249.3    0.07       0
Bank Sta=4987.8,4991.8
Exp/Cntr=0.3,0.1

Type RM Length L Ch R = 1,1350,453,453,453
BEGIN DESCRIPTION:
Stream0050_DS 3.0
END DESCRIPTION:
XS GIS Cut Line= 3
      2035724.99     13867125.00      2036025.00     13867125.00
      2036693.19     13867647.28
#Sta/Elev= 30
  4699.5 1529.31  4700.5 1529.31  4709.5 1528.02  4759.5 1509.76  4772.6 1506.86
  4809.5 1501.53  4839.5 1489.00  4859.5 1485.81  4899.5 1485.11  5006.7 1486.07
  5104.2 1484.92  5104.5 1484.42  5108.2 1484.92  5141.5 1485.63  5191.2 1489.79
  5228.0 1494.86  5249.1 1496.58  5274.4 1502.47  5291.4 1505.67  5334.1 1510.32
  5383.9 1527.79  5398.3 1530.62  5419.1 1532.87  5512.3 1536.67  5541.2 1540.28
  5619.9 1545.83  5697.6 1548.03  5725.7 1550.86  5798.0 1554.79  5847.6 1556.16
#Mann=6,-1,0
  4699.5    0.12       0  4700.5    0.07       0  4772.6    0.12       0
  5104.2    0.05       0  5108.2    0.12       0  5274.4    0.07       0
Bank Sta=5104.2,5108.2
Exp/Cntr=0.3,0.1

Type RM Length L Ch R = 1,897,414,414,414
BEGIN DESCRIPTION:
Stream0050_DS 2.0
END DESCRIPTION:
XS GIS Cut Line= 3
      2035625.05     13867475.01      2035875.00     13867525.00
      2036075.04     13867575.01
#Sta/Elev= 30
  4740.7 1532.55  4761.0 1530.57  4781.4 1525.79  4791.6 1522.20  4812.0 1513.12
  4822.2 1507.11  4852.8 1494.52  4863.0 1490.86  4873.2 1485.16  4883.4 1481.65
  4893.6 1479.35  4909.6 1477.25  4924.2 1475.67  4944.6 1475.39  4954.8 1474.63
  5011.6 1474.54  5011.9 1474.04  5015.4 1474.04  5015.6 1474.54  5054.9 1474.86
  5078.1 1480.55  5088.4 1483.84  5096.1 1487.48  5101.3 1492.34  5109.0 1496.23
  5129.6 1503.44  5142.5 1510.20  5170.8 1521.81  5178.6 1524.41  5201.8 1526.39
#Mann=4,-1,0
  4740.7    0.07       0  4909.6    0.12       0  5011.6    0.05       0
  5015.6    0.12       0
Bank Sta=5011.6,5015.6
Exp/Cntr=0.3,0.1

Type RM Length L Ch R = 1,483,367,367,367
BEGIN DESCRIPTION:
Stream0050_DS 1.0
END DESCRIPTION:
XS GIS Cut Line= 3
      2035525.01     13867675.01      2035775.00     13867875.00
      2036074.96     13867875.00
#Sta/Elev= 30
  4675.1 1531.80  4711.1 1528.89  4731.9 1522.41  4746.3 1519.99  4781.5 1507.76
  4824.8 1501.35  4839.2 1495.84  4853.6 1491.90  4860.0 1491.25  4867.2 1488.91
  4874.4 1484.93  4880.8 1483.67  4888.8 1479.43  4903.2 1475.08  4917.6 1471.90
  4938.4 1469.12  4971.6 1467.80  4971.9 1467.30  4975.6 1467.80  5065.2 1468.04
  5095.2 1469.64  5115.2 1471.94  5125.2 1474.12  5155.2 1483.09  5195.2 1500.91
  5225.2 1507.80  5235.2 1510.87  5245.2 1514.79  5265.2 1524.28  5295.2 1529.60
#Mann=3,-1,0
  4675.1    0.12       0  4971.6    0.05       0  4975.6    0.12       0
Bank Sta=4971.6,4975.6
Exp/Cntr=0.3,0.1

Type RM Length L Ch R = 1,116,0,0,0
BEGIN DESCRIPTION:
Stream0050_DS 0.0
END DESCRIPTION:
XS GIS Cut Line= 4
      2035630.90     13867844.10      2035754.28     13868160.19
      2035825.03     13868209.06      2036079.55     13867989.55
#Sta/Elev= 30
  4574.7 1490.72  4595.7 1488.07  4631.0 1478.06  4661.5 1472.07  4734.3 1465.30
  4790.9 1462.90  4922.1 1460.87  4975.7 1460.95  4982.9 1458.84  4989.0 1460.17
  4994.9 1453.24  4995.2 1452.74  4998.9 1453.24  5016.8 1455.43  5024.5 1460.32
  5062.4 1461.85  5094.7 1464.50  5103.8 1463.68  5151.7 1469.51  5172.6 1474.69
  5201.1 1483.98  5208.8 1488.99  5229.6 1495.33  5243.9 1501.77  5279.0 1509.46
  5293.3 1515.39  5300.9 1520.36  5307.5 1521.15  5329.5 1528.97  5336.1 1529.48
#Mann=7,-1,0
  4574.7    0.12       0  4790.9    0.07       0  4922.1    0.12       0
  4994.9    0.05       0  4998.9    0.12       0  5062.4    0.07       0
  5103.8    0.12       0
Bank Sta=4994.9,4998.9
Exp/Cntr=0.3,0.1

Chan Stop Cuts=-1