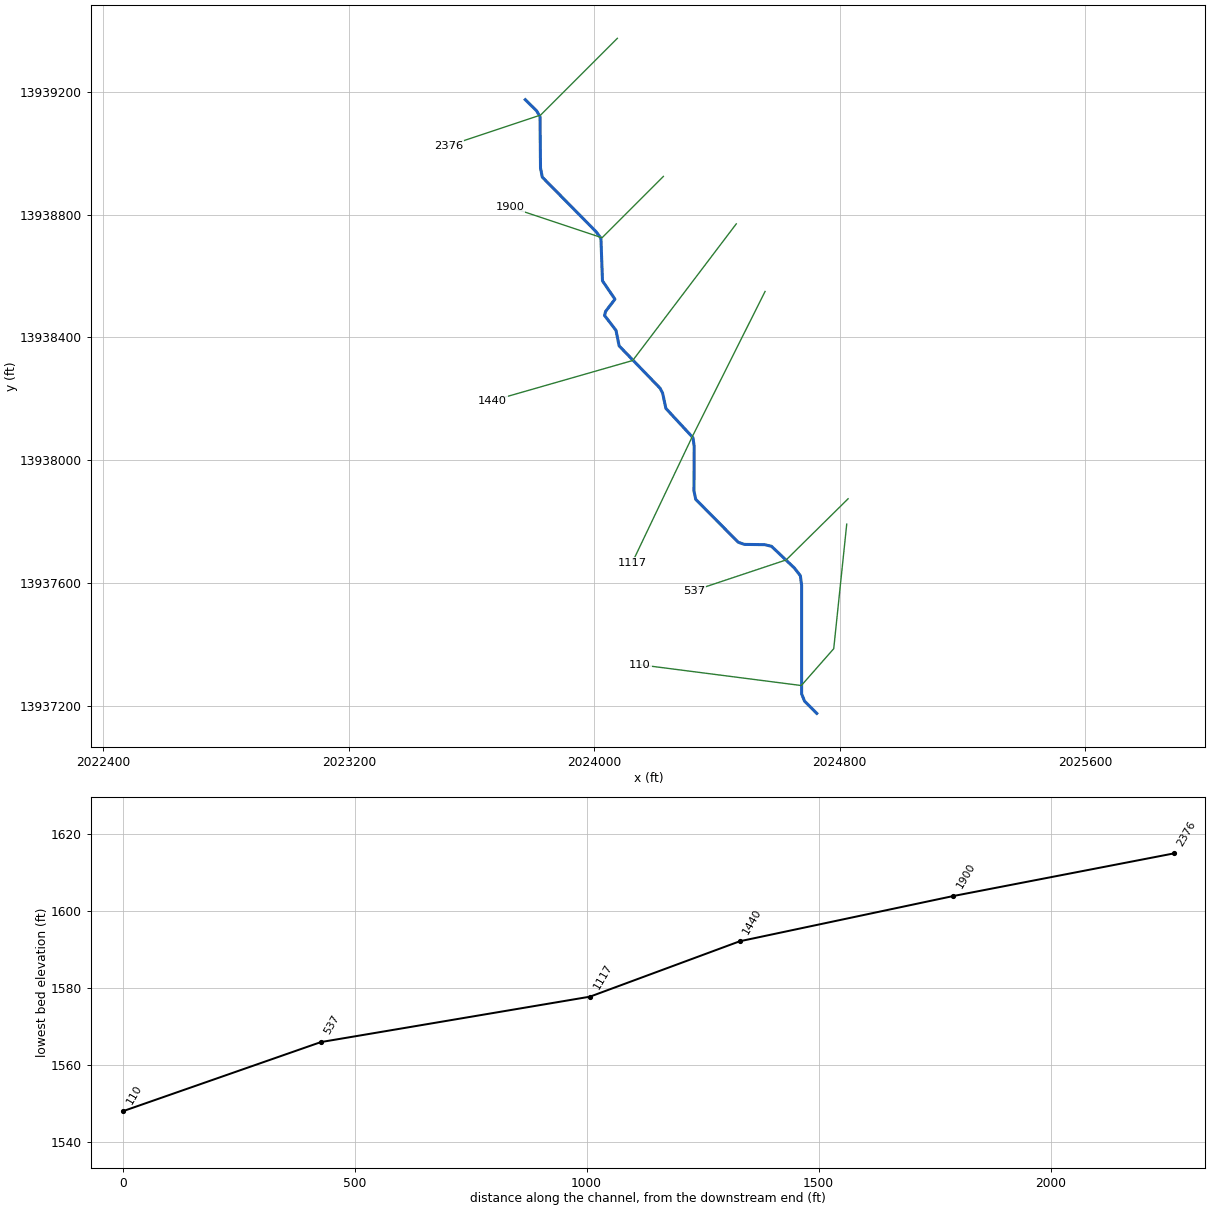
--- Stream0051_DS.prj (project) ---

Proj Title=Stream0051_DS Base Level Engineering
Current Plan=p01
Default Exp/Contr=0.3,0.1
English Units
Geom File=g01
Flow File=f01
Plan File=p01
BEGIN DESCRIPTION:
Stream0051_DS
END DESCRIPTION:

--- Stream0051_DS.p01 (plan) ---

Plan Title=Multiple Run
Short Identifier=Multiple
Geom File=g01
Flow File=f01
Subcritical Flow
K Sum by GR= 0
Std Step Tol= 0.01
Critical Tol= 0.01
Num of Std Step Trials= 20
Max Error Tol= 0.3
Flow Tol Ratio= 0.001
Split Flow NTrial= 30
Split Flow Tol= 0.02
Split Flow Ratio= 0.02
Log Output Level= 0
Friction Slope Method= 1
Unsteady Friction Slope Method= 2
Unsteady Bridges Friction Slope Method= 1
Parabolic Critical Depth
Global Vel Dist=  1 , 1 , 1
Global Log Level= 0
CheckData=True
Encroach Param= -1, 0, 0, 0
BEGIN DESCRIPTION:
Multiple Run
END DESCRIPTION:

--- Stream0051_DS.f01 (steady flow) ---

Flow Title=Multiple
Number of Profiles=7
Profile Names=10-year,25-year,50-year,1pct_min,100-year,1pct_plu,500-year
River Rch & RM= Stream0051_DS,Reach-1,2376
     598     998    1375     922    1839    3670    3259
River Rch & RM= Stream0051_DS,Reach-1,1900
     714    1205    1672    1128    2250    4490    4038
Boundary for River Rch & Prof#=Stream0051_DS,Reach-1,1
Up Type=0
Dn Type=3
Dn Slope=0.005
Boundary for River Rch & Prof#=Stream0051_DS,Reach-1,2
Up Type=0
Dn Type=3
Dn Slope=0.005
Boundary for River Rch & Prof#=Stream0051_DS,Reach-1,3
Up Type=0
Dn Type=3
Dn Slope=0.005
Boundary for River Rch & Prof#=Stream0051_DS,Reach-1,4
Up Type=0
Dn Type=3
Dn Slope=0.005
Boundary for River Rch & Prof#=Stream0051_DS,Reach-1,5
Up Type=0
Dn Type=3
Dn Slope=0.005
Boundary for River Rch & Prof#=Stream0051_DS,Reach-1,6
Up Type=0
Dn Type=3
Dn Slope=0.005
Boundary for River Rch & Prof#=Stream0051_DS,Reach-1,7
Up Type=0
Dn Type=3
Dn Slope=0.005

--- Stream0051_DS.g01 (geometry) ---

Geom Title=Existing Conditions

River Reach=Stream0051_DS,Reach-1
Reach XY= 30
      2023775.00     13939175.00      2023812.08     13939138.50
      2023823.00     13939119.63      2023824.63     13938952.12
      2023830.46     13938922.55      2024005.39     13938745.16
      2024021.46     13938723.53      2024026.55     13938584.59
      2024067.20     13938524.90      2024036.81     13938485.04
      2024033.24     13938471.77      2024070.56     13938423.35
      2024080.81     13938372.71      2024214.22     13938234.68
      2024222.47     13938218.95      2024233.18     13938168.96
      2024321.45     13938073.53      2024325.43     13938045.18
      2024324.71     13937899.88      2024330.46     13937872.55
      2024468.83     13937732.86      2024488.91     13937725.67
      2024554.95     13937724.87      2024577.44     13937719.48
      2024652.16     13937648.58      2024671.47     13937623.55
      2024675.46     13937593.38      2024675.50     13937238.84
      2024685.05     13937215.02      2024725.00     13937175.00

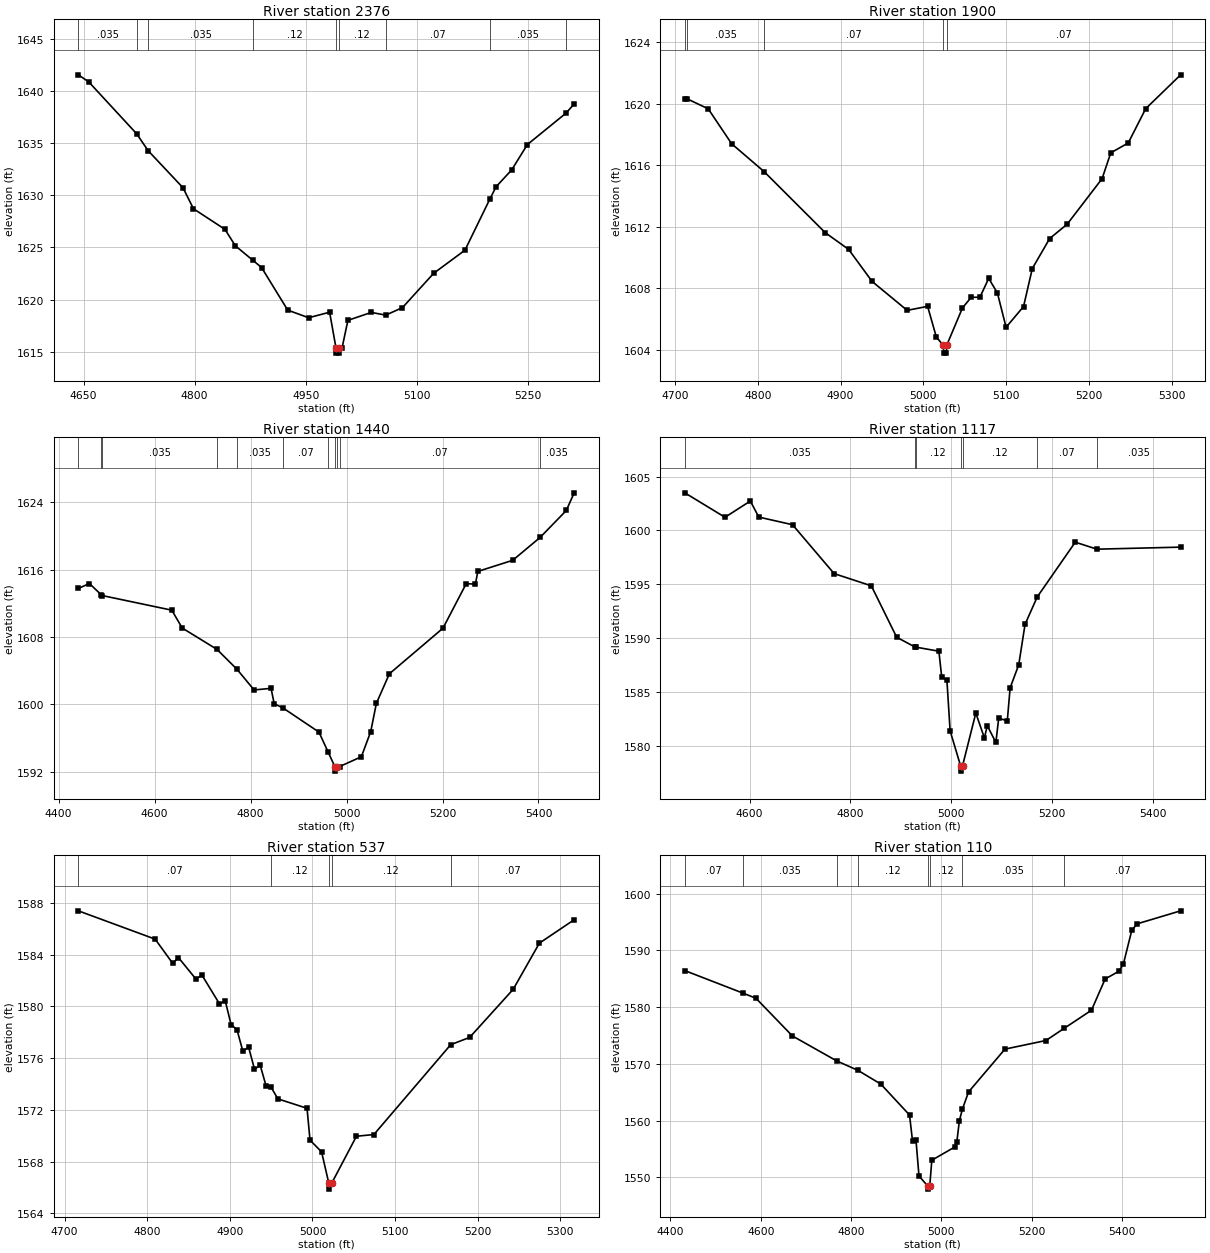
Type RM Length L Ch R = 1,2376,476,476,476
BEGIN DESCRIPTION:
Stream0051_DS 5.0
END DESCRIPTION:
XS GIS Cut Line= 3
      2024074.98     13939374.98      2023825.00     13939125.00
      2023525.05     13939025.02
#Sta/Elev= 30
  4642.9 1641.53  4657.0 1640.85  4721.7 1635.88  4737.2 1634.26  4784.3 1630.71
  4798.4 1628.70  4840.9 1626.73  4855.0 1625.15  4878.7 1623.76  4890.4 1623.07
  4925.7 1618.99  4954.0 1618.26  4982.3 1618.79  4990.9 1615.37  4991.1 1614.87
  4994.6 1614.87  4994.9 1615.37  4999.1 1615.37  5007.0 1618.01  5038.6 1618.77
  5058.1 1618.51  5080.7 1619.23  5122.9 1622.52  5165.1 1624.73  5198.8 1629.64
  5207.2 1630.81  5228.3 1632.43  5249.4 1634.85  5301.6 1637.86  5312.6 1638.74
#Mann=9,-1,0
  4642.9   0.035       0  4721.7    0.12       0  4737.2   0.035       0
  4878.7    0.12       0  4990.9   0.035       0  4994.9    0.12       0
  5058.1    0.07       0  5198.8   0.035       0  5301.6    0.07       0
Bank Sta=4990.9,4994.9
Exp/Cntr=0.3,0.1

Type RM Length L Ch R = 1,1900,460,460,460
BEGIN DESCRIPTION:
Stream0051_DS 4.0
END DESCRIPTION:
XS GIS Cut Line= 3
      2024224.99     13938924.99      2024025.00     13938725.00
      2023724.96     13938825.01
#Sta/Elev= 30
  4711.8 1620.32  4714.6 1620.32  4740.1 1619.67  4768.4 1617.40  4807.6 1615.59
  4881.5 1611.62  4909.8 1610.53  4938.1 1608.45  4980.5 1606.57  5005.2 1606.83
  5015.7 1604.84  5024.2 1604.29  5024.5 1603.79  5028.0 1603.79  5028.2 1604.29
  5047.3 1606.73  5057.9 1607.42  5068.4 1607.42  5079.0 1608.65  5089.5 1607.70
  5100.0 1605.47  5121.1 1606.82  5131.7 1609.29  5152.7 1611.24  5173.8 1612.17
  5216.0 1615.13  5226.5 1616.81  5247.6 1617.45  5268.7 1619.68  5310.9 1621.88
#Mann=5,-1,0
  4711.8    0.12       0  4714.6   0.035       0  4807.6    0.07       0
  5024.2    0.05       0  5028.2    0.07       0
Bank Sta=5024.2,5028.2
Exp/Cntr=0.3,0.1

Type RM Length L Ch R = 1,1440,323,323,323
BEGIN DESCRIPTION:
Stream0051_DS 3.0
END DESCRIPTION:
XS GIS Cut Line= 3
      2024462.53     13938770.26      2024125.00     13938325.00
      2023668.71     13938194.22
#Sta/Elev= 30
  4441.0 1613.76  4464.1 1614.35  4488.8 1613.01  4490.8 1612.92  4635.8 1611.18
  4657.5 1609.06  4730.0 1606.52  4771.6 1604.16  4807.3 1601.70  4842.7 1601.89
  4849.2 1600.06  4867.0 1599.58  4942.5 1596.69  4961.6 1594.32  4975.9 1592.55
  4976.2 1592.05  4979.9 1592.55  4985.8 1592.60  5030.9 1593.76  5050.4 1596.75
  5062.2 1600.11  5089.3 1603.62  5201.0 1609.04  5249.4 1614.33  5268.5 1614.28
  5273.7 1615.79  5346.4 1617.11  5403.3 1619.82  5458.0 1623.03  5474.4 1625.13
#Mann=11,-1,0
  4441.0   0.035       0  4488.8    0.07       0  4490.8   0.035       0
  4730.0    0.07       0  4771.6   0.035       0  4867.0    0.07       0
  4961.6   0.035       0  4975.9    0.05       0  4979.9   0.035       0
  4985.8    0.07       0  5403.3   0.035       0
Bank Sta=4975.9,4979.9
Exp/Cntr=0.3,0.1

Type RM Length L Ch R = 1,1117,580,580,580
BEGIN DESCRIPTION:
Stream0051_DS 2.0
END DESCRIPTION:
XS GIS Cut Line= 3
      2024556.42     13938549.99      2024319.53     13938077.45
      2024123.51     13937666.28
#Sta/Elev= 30
  4471.4 1603.49  4551.2 1601.22  4601.5 1602.73  4618.2 1601.24  4685.2 1600.53
  4767.8 1595.99  4841.6 1594.86  4891.9 1590.09  4927.8 1589.19  4929.8 1589.17
  4975.7 1588.79  4981.3 1586.39  4991.6 1586.11  4998.0 1581.40  5018.7 1578.16
  5019.0 1577.66  5022.7 1578.16  5049.0 1583.05  5066.1 1580.73  5071.7 1581.88
  5088.8 1580.32  5094.4 1582.56  5111.5 1582.34  5117.1 1585.39  5134.2 1587.53
  5146.7 1591.28  5170.8 1593.82  5246.4 1598.91  5289.3 1598.26  5455.5 1598.45
#Mann=7,-1,0
  4471.4   0.035       0  4927.8    0.07       0  4929.8    0.12       0
  5018.7    0.05       0  5022.7    0.12       0  5170.8    0.07       0
  5289.3   0.035       0
Bank Sta=5018.7,5022.7
Exp/Cntr=0.3,0.1

Type RM Length L Ch R = 1,537,427,427,427
BEGIN DESCRIPTION:
Stream0051_DS 1.0
END DESCRIPTION:
XS GIS Cut Line= 3
      2024827.08     13937874.39      2024625.00     13937675.00
      2024325.01     13937575.00
#Sta/Elev= 30
  4716.6 1587.39  4809.6 1585.20  4830.8 1583.33  4837.8 1583.77  4859.1 1582.10
  4866.1 1582.43  4887.4 1580.20  4894.4 1580.43  4901.5 1578.59  4908.6 1578.20
  4915.7 1576.54  4922.7 1576.84  4929.8 1575.15  4936.8 1575.43  4944.0 1573.81
  4949.7 1573.77  4958.1 1572.85  4993.4 1572.12  4997.0 1569.66  5011.0 1568.75
  5019.6 1566.37  5019.8 1565.87  5023.6 1566.37  5053.2 1569.96  5074.3 1570.09
  5167.3 1577.04  5190.2 1577.60  5242.9 1581.32  5274.6 1584.89  5316.7 1586.70
#Mann=5,-1,0
  4716.6    0.07       0  4949.7    0.12       0  5019.6    0.05       0
  5023.6    0.12       0  5167.3    0.07       0
Bank Sta=5019.6,5023.6
Exp/Cntr=0.3,0.1

Type RM Length L Ch R = 1,110,0,0,0
BEGIN DESCRIPTION:
Stream0051_DS 0.0
END DESCRIPTION:
XS GIS Cut Line= 4
      2024822.58     13937791.77      2024780.22     13937385.78
      2024674.58     13937265.74      2024149.22     13937333.37
#Sta/Elev= 30
  4431.9 1586.42  4561.6 1582.42  4589.5 1581.54  4670.0 1574.91  4768.3 1570.50
  4815.0 1568.85  4865.9 1566.42  4929.5 1560.97  4936.1 1556.38  4943.7 1556.63
  4950.4 1550.23  4970.2 1548.41  4970.4 1547.91  4974.2 1548.41  4978.8 1553.00
  5029.1 1555.31  5034.1 1556.15  5039.9 1560.00  5046.5 1561.99  5060.1 1565.03
  5140.7 1572.58  5231.5 1574.10  5272.0 1576.25  5332.3 1579.43  5362.6 1584.94
  5392.8 1586.29  5402.9 1587.56  5421.5 1593.49  5433.1 1594.65  5529.7 1596.95
#Mann=8,-1,0
  4431.9    0.07       0  4561.6   0.035       0  4768.3    0.07       0
  4815.0    0.12       0  4970.2    0.05       0  4974.2    0.12       0
  5046.5   0.035       0  5272.0    0.07       0
Bank Sta=4970.2,4974.2
Exp/Cntr=0.3,0.1

Chan Stop Cuts=-1