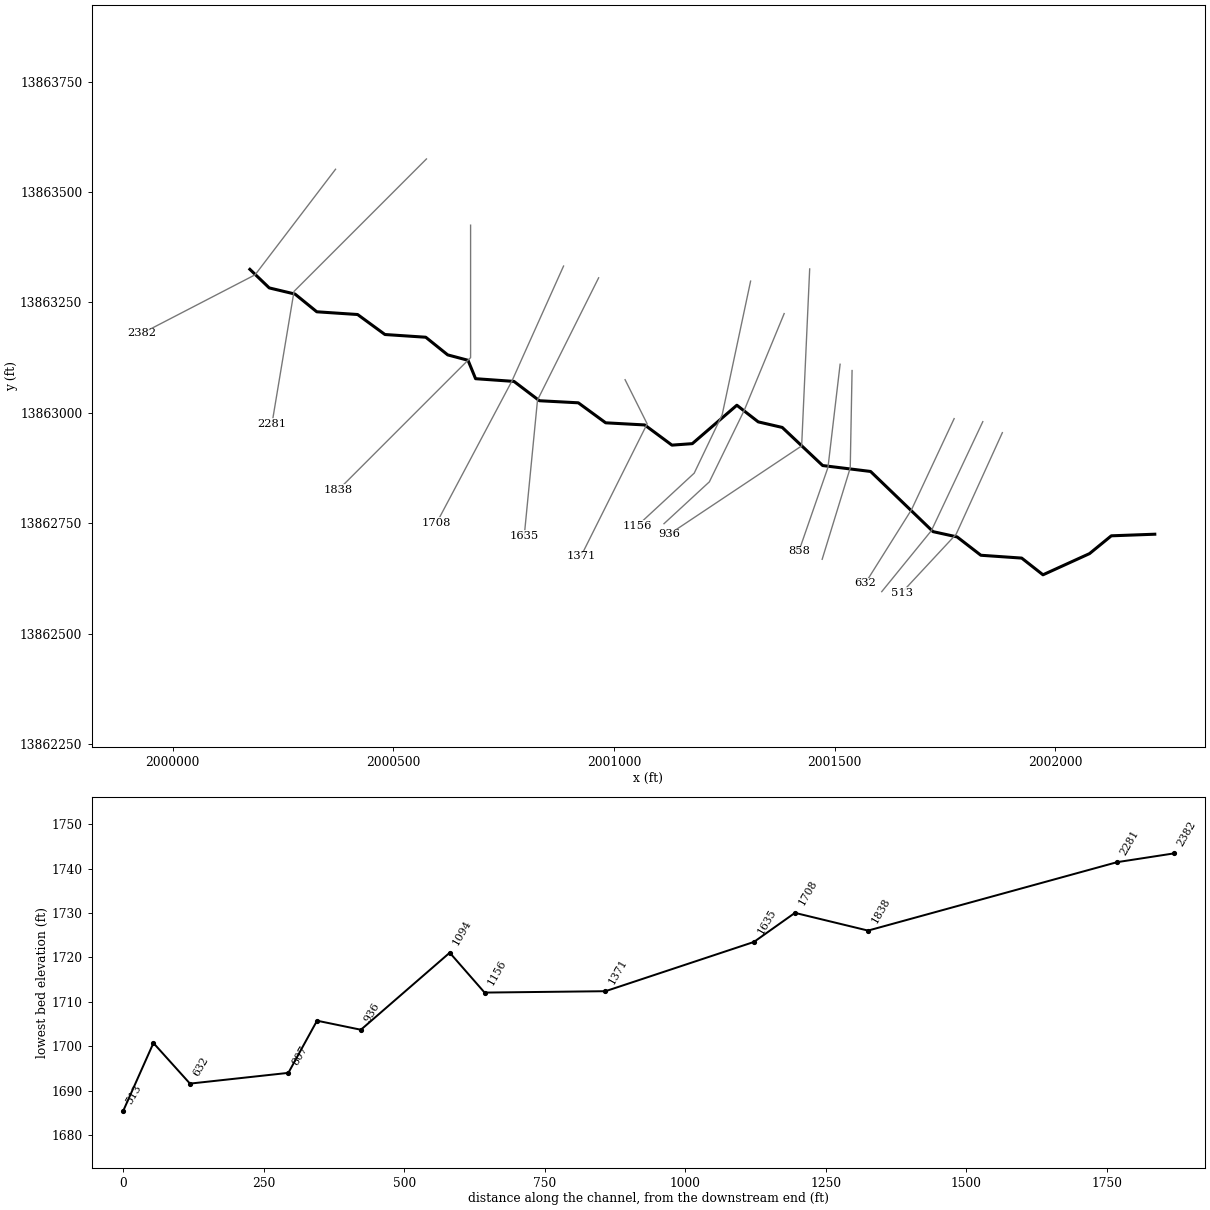
--- Stream0052_DS.prj (project) ---

Proj Title=Stream0052_DS Base Level Engineering
Current Plan=p01
Default Exp/Contr=0.3,0.1
English Units
Geom File=g01
Flow File=f01
Plan File=p01
Y Axis Title=Elevation
X Axis Title(PF)=Main Channel Distance
X Axis Title(XS)=Station
BEGIN DESCRIPTION:
Stream0052_DS
END DESCRIPTION:
DSS Export Rating Curves= 0
DSS Export Rating Curve Sorted= 0
DSS Export Volume Flow Curves= 0
DXF OffsetX= 0
DXF OffsetY= 0
DXF ScaleX= 1
DXF ScaleY= 10

--- Stream0052_DS.p01 (plan) ---

Plan Title=Multiple Run
Short Identifier=Multiple
Geom File=g01
Flow File=f01
Subcritical Flow
K Sum by GR= 0
Std Step Tol= 0.01
Critical Tol= 0.01
Num of Std Step Trials= 20
Max Error Tol= 0.3
Flow Tol Ratio= 0.001
Split Flow NTrial= 30
Split Flow Tol= 0.02
Split Flow Ratio= 0.02
Log Output Level= 0
Friction Slope Method= 1
Unsteady Friction Slope Method= 2
Unsteady Bridges Friction Slope Method= 1
Parabolic Critical Depth
Global Vel Dist=  1 , 1 , 1
Global Log Level= 0
CheckData=True
Encroach Param= -1, 0, 0, 0
BEGIN DESCRIPTION:
Multiple Run
END DESCRIPTION:

--- Stream0052_DS.f01 (steady flow) ---

Flow Title=Multiple
Number of Profiles=7
Profile Names=10-year,25-year,50-year,1pct_min,100-year,1pct_plu,500-year
River Rch & RM= Stream0052_DS,Reach-1,2382
     482     783    1061     700    1396    2786    2386
Boundary for River Rch & Prof#=Stream0052_DS,Reach-1,1
Up Type=0
Dn Type=3
Dn Slope=0.005
Boundary for River Rch & Prof#=Stream0052_DS,Reach-1,2
Up Type=0
Dn Type=3
Dn Slope=0.005
Boundary for River Rch & Prof#=Stream0052_DS,Reach-1,3
Up Type=0
Dn Type=3
Dn Slope=0.005
Boundary for River Rch & Prof#=Stream0052_DS,Reach-1,4
Up Type=0
Dn Type=3
Dn Slope=0.005
Boundary for River Rch & Prof#=Stream0052_DS,Reach-1,5
Up Type=0
Dn Type=3
Dn Slope=0.005
Boundary for River Rch & Prof#=Stream0052_DS,Reach-1,6
Up Type=0
Dn Type=3
Dn Slope=0.005
Boundary for River Rch & Prof#=Stream0052_DS,Reach-1,7
Up Type=0
Dn Type=3
Dn Slope=0.005

--- Stream0052_DS.g01 (geometry) ---

Geom Title=Existing Conditions
Program Version=4.10

River Reach=Stream0052_DS   ,Reach-1
Reach XY= 30
        2000175.       13863325.      2000218.85     13863282.91
      2000277.22     13863268.97      2000326.58     13863228.82
      2000419.03     13863222.65      2000480.98     13863177.35
      2000573.44     13863171.18      2000623.13     13863131.21
      2000669.21     13863118.98      2000686.31     13863077.26
      2000773.33     13863071.12      2000830.97     13863027.35
      2000919.03     13863022.65      2000980.97     13862977.35
      2001069.44      13862972.5      2001131.13     13862926.78
       2001177.3     13862930.12      2001278.23     13863017.16
      2001326.65     13862979.46      2001381.04     13862966.86
      2001472.58     13862880.54      2001581.17     13862867.14
       2001722.7     13862730.83      2001777.17     13862718.86
      2001830.97     13862677.33       2001923.5     13862670.91
      2001971.71     13862633.05      2002077.18     13862681.06
       2002126.5     13862721.37        2002225.       13862725.

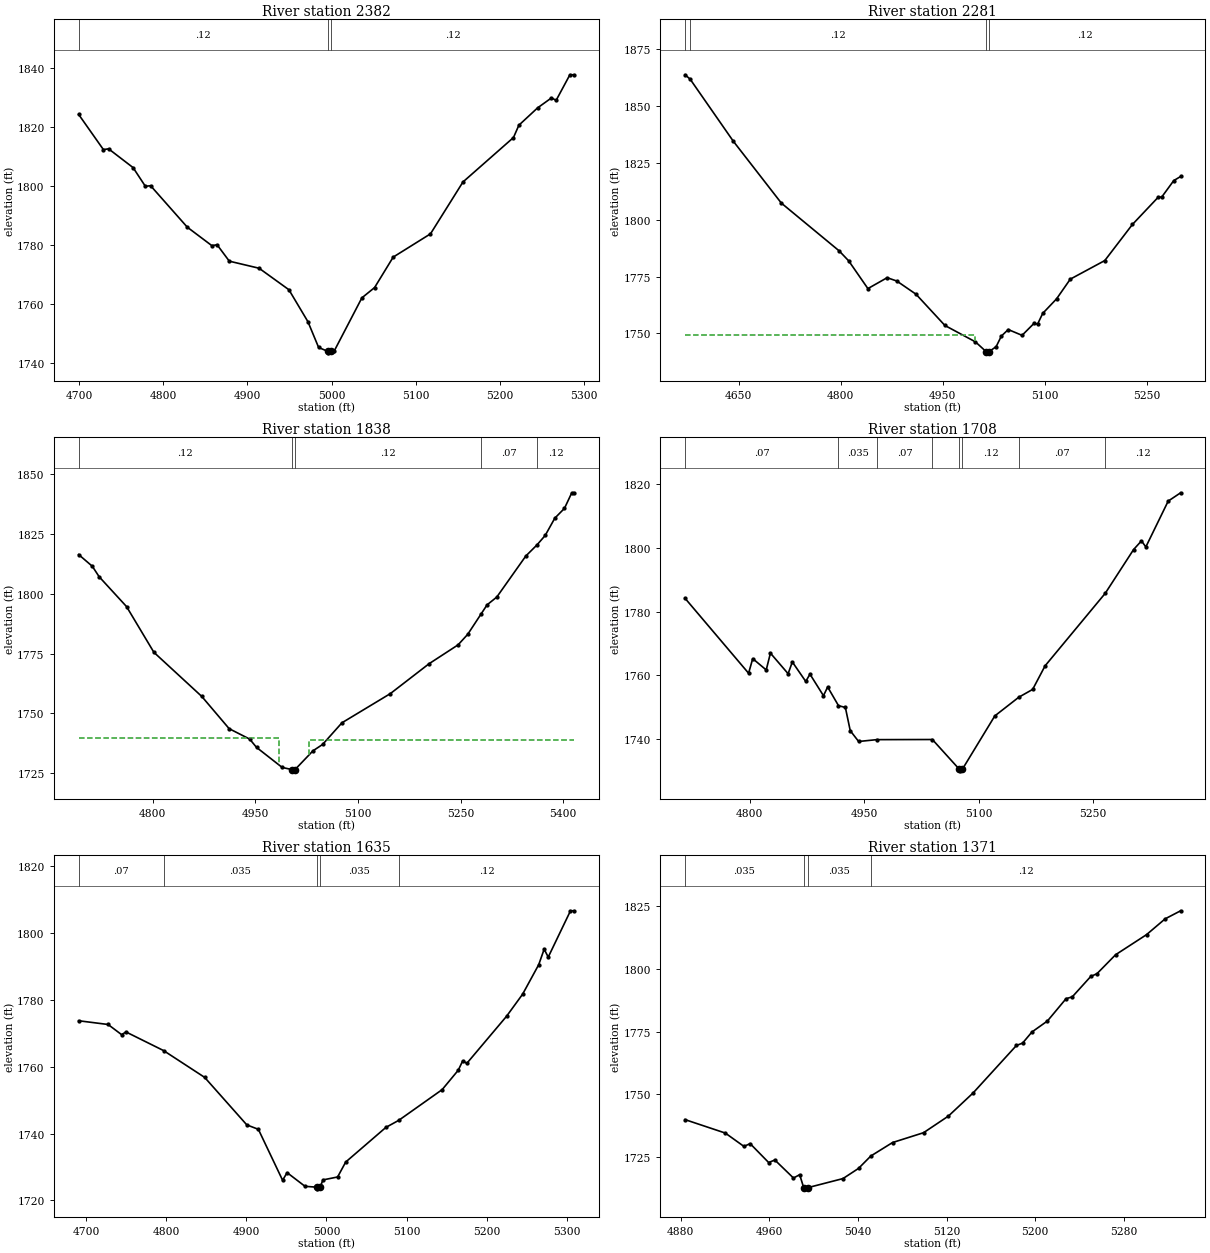
Type RM Length L Ch R = 1 ,2382    ,101,101,101
BEGIN DESCRIPTION:
Stream0052_DS 14.0
END DESCRIPTION:
XS GIS Cut Line= 3
      2000369.07     13863551.69      2000186.85     13863312.61
      1999931.01     13863180.15
#Sta/Elev= 30
  4699.4  1824.4  4728.8 1812.46    4735 1812.71  4764.1 1806.33  4778.7 1799.98
  4784.9 1800.19  4828.5  1786.1  4857.6 1779.85  4863.9 1780.13  4878.4 1774.56
  4913.8 1772.16  4949.2 1764.86  4971.8 1754.01  4984.5 1745.26  4995.4 1743.93
  4995.7 1743.43  4999.4 1743.93  5002.8 1743.93  5035.9  1762.1    5051  1765.6
  5073.1 1775.94  5117.4 1783.84    5156 1801.46    5216 1816.55  5222.4 1820.73
  5244.6 1826.61  5261.1    1830  5266.7 1829.19    5283 1837.86  5288.1 1837.86
#Mann= 3 ,-1 , 0
  4699.4     .12       0  4995.4     .05       0  4999.4     .12       0
Bank Sta=4995.4,4999.4
XS Rating Curve= 0 ,0
Exp/Cntr=0.3,0.1

Type RM Length L Ch R = 1 ,2281    ,443,443,443
BEGIN DESCRIPTION:
Stream0052_DS 13.0
END DESCRIPTION:
XS GIS Cut Line= 3
      2000575.02     13863575.02        2000275.       13863275.
      2000225.01     13862975.04
#Sta/Elev= 30
  4571.1 1863.68  4578.5 1861.76  4641.8 1834.54  4712.6 1807.27  4797.4 1786.32
  4811.6 1781.88  4839.8  1769.7  4868.1 1774.49  4882.3 1773.02  4910.5 1767.23
    4953 1753.49  4997.9 1746.28  5013.7 1741.96  5013.9 1741.46  5017.7 1741.96
  5028.3 1744.17    5036 1748.83  5046.1  1751.7  5066.4 1749.15  5084.1 1754.45
  5089.2 1754.08  5096.8 1758.81  5117.1 1765.18  5137.3 1773.85    5188 1782.02
  5228.6 1797.88  5266.6 1809.89  5271.7 1809.94  5289.4 1817.18  5299.5 1818.97
#Mann= 4 ,-1 , 0
  4571.1     .07       0  4578.5     .12       0  5013.7     .05       0
  5017.7     .12       0
#XS Ineff= 2 , 0
       0 4996.84  1749.3               0
Permanent Ineff=
       F       F
Bank Sta=5013.7,5017.7
XS Rating Curve= 0 ,0
Exp/Cntr=0.3,0.1

Type RM Length L Ch R = 1 ,1838    ,130,130,130
BEGIN DESCRIPTION:
Stream0052_DS 12.0
END DESCRIPTION:
XS GIS Cut Line= 3
        2000675.     13863425.03        2000675.       13863125.
      2000374.99     13862824.99
#Sta/Elev= 30
  4691.6 1816.38  4711.6 1811.49  4721.6 1807.11  4761.6 1794.66  4801.6 1775.55
  4871.6 1757.12  4911.6 1743.66  4941.6 1739.31  4951.6 1735.85  4989.1 1727.47
  5003.8 1726.55    5004 1726.05  5007.8 1726.55  5034.1 1734.41  5048.2 1737.07
  5076.5 1746.12  5147.2  1758.3  5203.8 1770.78  5246.2 1778.66  5260.3 1783.06
  5279.7  1791.5  5288.6 1795.37  5302.8 1798.63  5345.2 1815.76  5361.5 1820.39
  5373.5 1824.34  5387.6 1831.57  5401.7 1835.67  5412.4 1842.18  5415.9 1842.18
#Mann= 5 ,-1 , 0
  4691.6     .12       0  5003.8     .05       0  5007.8     .12       0
  5279.7     .07       0  5361.5     .12       0
#XS Ineff= 2 , 0
       0 4984.12 1739.82 5028.04       0 1738.77
Permanent Ineff=
       F       F
Bank Sta=5003.8,5007.8
XS Rating Curve= 0 ,0
Exp/Cntr=0.3,0.1

Type RM Length L Ch R = 1 ,1708    ,73,73,73
BEGIN DESCRIPTION:
Stream0052_DS 11.0
END DESCRIPTION:
XS GIS Cut Line= 3
      2000885.62     13863332.42      2000768.94     13863072.62
      2000598.11     13862750.63
#Sta/Elev= 30
  4715.2 1784.22  4798.4  1760.7  4803.8 1765.29  4821.5 1761.73    4827 1767.02
  4850.2 1760.55  4855.7 1764.25  4873.3 1758.12  4878.8 1760.41  4896.5 1753.64
    4902 1756.38  4916.2 1750.51  4925.2 1749.95  4931.6 1742.65  4942.6 1739.26
  4966.4 1739.84  5039.2 1739.88  5074.5 1730.54  5074.8 1730.04  5078.5 1730.54
    5121 1747.29  5152.4 1753.16  5170.6 1755.62  5186.9 1763.03  5265.7 1785.81
  5302.9 1799.57  5313.2 1802.29  5318.9 1800.37  5348.2 1814.78  5364.5 1817.39
#Mann= 8 ,-1 , 0
  4715.2     .07       0  4916.2    .035       0  4966.4     .07       0
  5039.2     .12       0  5074.5     .05       0  5078.5     .12       0
  5152.4     .07       0  5265.7     .12       0
Bank Sta=5074.5,5078.5
XS Rating Curve= 0 ,0
Exp/Cntr=0.3,0.1

Type RM Length L Ch R = 1 ,1635    ,264,264,264
BEGIN DESCRIPTION:
Stream0052_DS 10.0
END DESCRIPTION:
XS GIS Cut Line= 3
      2000965.07     13863305.76      2000826.59     13863028.85
      2000796.54     13862720.92
#Sta/Elev= 30
  4690.4 1773.81  4727.2 1772.69    4744 1769.66  4749.6 1770.45  4796.5 1764.88
  4847.8 1756.86  4900.5 1742.63  4914.9 1741.31  4945.2 1726.05  4950.8 1728.34
  4973.2 1724.24    4988 1723.99  4988.2 1723.49    4992 1723.99  4995.6 1726.16
  5013.9 1727.04    5024 1731.51  5074.2 1741.88  5090.3    1744  5144.5 1753.19
  5164.6    1759  5170.2 1761.82  5175.3 1761.05  5224.9 1775.14    5245 1781.76
  5265.1 1790.59  5271.9 1795.23    5277 1792.86  5304.8 1806.73  5309.4 1806.73
#Mann= 5 ,-1 , 0
  4690.4     .07       0  4796.5    .035       0    4988    .035       0
    4992    .035       0  5090.3     .12       0
Bank Sta=4988,4992
XS Rating Curve= 0 ,0
Exp/Cntr=0.3,0.1

Type RM Length L Ch R = 1 ,1371    ,215,215,215
BEGIN DESCRIPTION:
Stream0052_DS 9.0
END DESCRIPTION:
XS GIS Cut Line= 3
      2001025.01     13863074.97        2001075.       13862975.
      2000924.99     13862674.98
#Sta/Elev= 30
    4884 1739.98  4920.3 1734.63  4937.1 1729.31  4942.7 1730.42  4959.4 1722.89
    4965 1723.89  4981.8 1716.71  4987.4 1718.04    4991  1712.9  4991.2  1712.4
    4995  1712.9  5026.5 1716.49  5040.5 1720.54  5051.6 1725.48  5071.2 1730.85
  5099.2 1734.77  5121.6 1741.39  5143.9 1750.61    5183 1769.53  5188.6  1770.5
    5197 1774.91    5211  1779.3  5227.8 1788.19  5233.4 1788.91  5250.1 1797.05
  5255.7 1798.15  5272.5  1805.7  5300.4  1813.7  5317.2    1820  5331.2 1823.22
#Mann= 4 ,-1 , 0
    4884    .035       0    4991    .035       0    4995    .035       0
  5051.6     .12       0
Bank Sta=4991,4995
XS Rating Curve= 0 ,0
Exp/Cntr=0.3,0.1

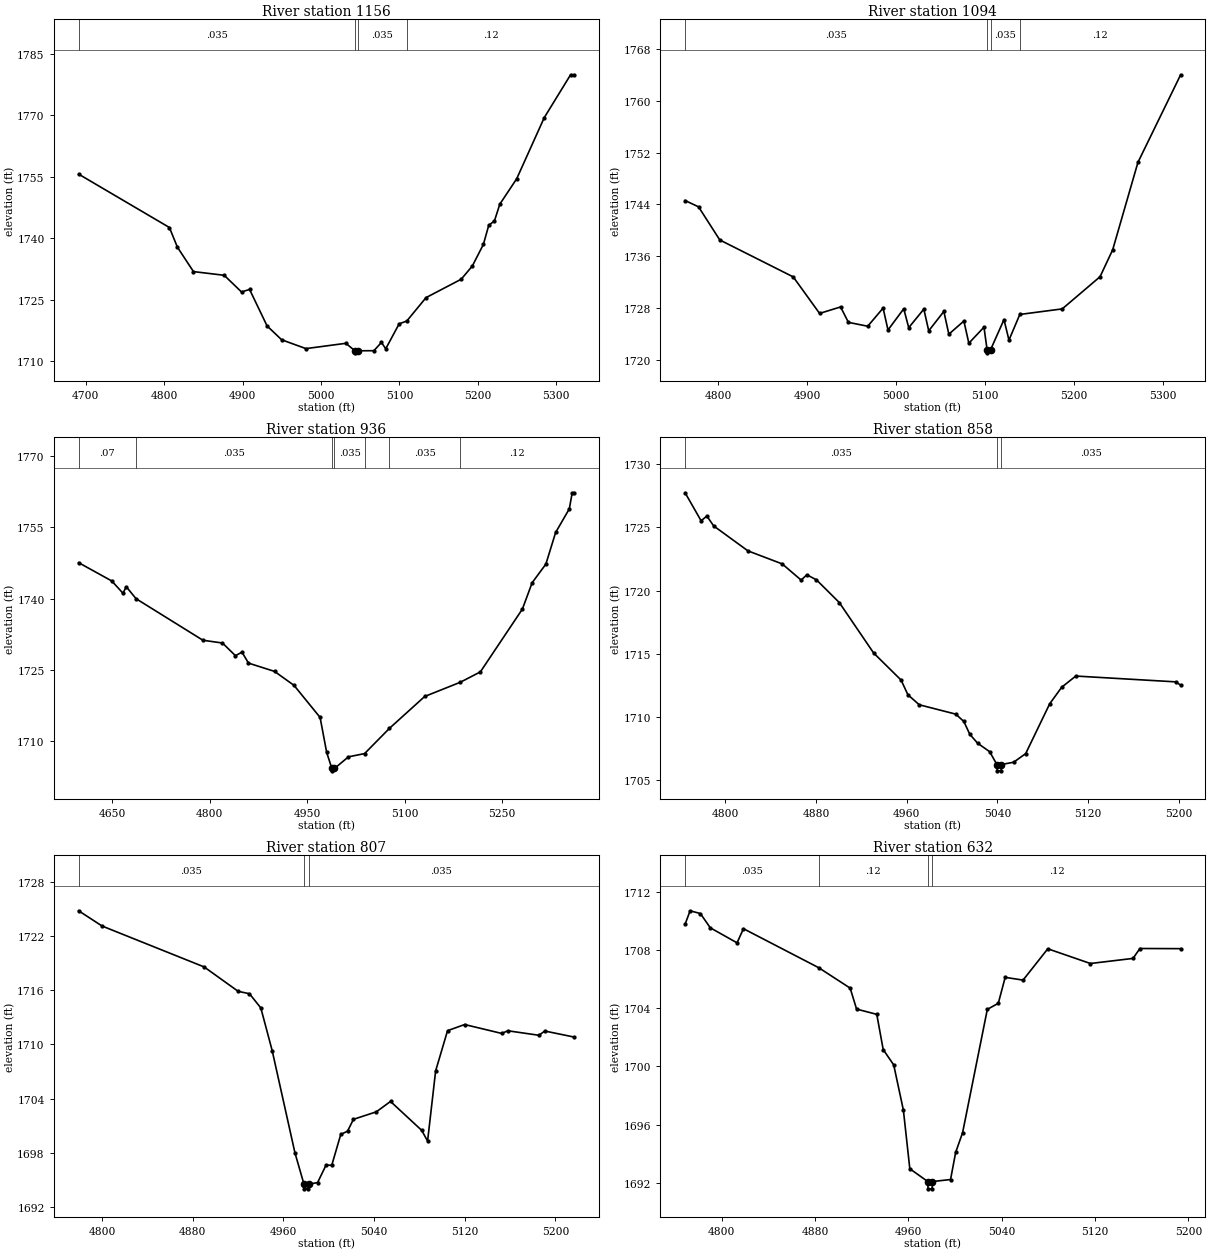
Type RM Length L Ch R = 1 ,1156    ,62,62,62
BEGIN DESCRIPTION:
Stream0052_DS 8.0
END DESCRIPTION:
XS GIS Cut Line= 4
      2001309.36     13863298.29      2001245.01     13862995.85
      2001181.61     13862863.32      2001052.37     13862743.73
#Sta/Elev= 30
  4690.8 1755.62  4806.6 1742.62  4816.8 1737.83  4837.3 1731.88  4876.5 1730.98
  4898.6 1726.92  4908.9 1727.53  4931.2 1718.65  4949.8 1715.27  4980.8 1713.12
  5031.7 1714.41  5043.3 1712.59  5043.5 1712.09  5047.3 1712.59  5067.5 1712.61
  5077.1 1714.62  5082.6 1713.08  5099.7 1719.15  5109.5 1719.85    5134 1725.54
  5178.8 1730.01    5193 1733.22  5207.2 1738.51    5214 1743.15  5221.3 1744.23
  5228.1 1748.29  5249.7  1754.5  5284.8 1769.37  5318.4 1779.82    5323 1779.82
#Mann= 4 ,-1 , 0
  4690.8    .035       0  5043.3    .035       0  5047.3    .035       0
  5109.5     .12       0
Bank Sta=5043.3,5047.3
XS Rating Curve= 0 ,0
Exp/Cntr=0.3,0.1

Type RM Length L Ch R = 1 ,1094    ,158,158,158
BEGIN DESCRIPTION:
Stream0052_DS 7.0
END DESCRIPTION:
XS GIS Cut Line= 4
       2001385.4     13863224.74      2001294.84      13863005.4
      2001215.95     13862843.65      2001113.16     13862748.84
#Sta/Elev= 30
  4762.7  1744.6  4777.8 1743.63  4801.7 1738.51  4884.3  1732.8  4913.9 1727.16
  4937.5 1728.16  4946.3 1725.78    4968 1725.18  4985.3 1727.98  4990.8  1724.6
  5008.5 1727.88  5014.1 1724.96  5031.1 1727.82  5036.6 1724.47  5053.6 1727.47
  5059.2 1723.95  5076.1 1725.98  5081.7 1722.56  5098.7 1725.03  5102.2 1721.57
  5102.5 1721.07  5106.2 1721.57  5121.2  1726.2  5126.8 1723.04    5139    1727
  5186.7 1727.86  5229.2 1732.83  5243.4 1736.99  5271.8  1750.5  5319.8 1764.03
#Mann= 4 ,-1 , 0
  4762.7    .035       0  5102.2    .035       0  5106.2    .035       0
    5139     .12       0
Bank Sta=5102.2,5106.2
XS Rating Curve= 0 ,0
Exp/Cntr=0.3,0.1

Type RM Length L Ch R = 1 ,936     ,78,78,78
BEGIN DESCRIPTION:
Stream0052_DS 6.0
END DESCRIPTION:
XS GIS Cut Line= 3
       2001443.2     13863325.86        2001425.       13862925.
      2001125.03     13862725.02
#Sta/Elev= 30
  4598.7 1747.56  4649.6 1743.71  4666.9 1741.12  4671.9  1742.5    4687 1739.97
  4789.8 1731.22  4819.8 1730.64  4839.8 1727.97  4849.8 1728.72  4859.8 1726.41
  4899.9 1724.66  4929.9 1721.71  4969.9 1714.97    4980 1707.61    4988 1704.22
  4988.2 1703.72    4992 1704.22  5013.5 1706.67  5038.3 1707.35  5076.6 1712.68
  5130.7 1719.38  5185.5 1722.38  5216.3 1724.56  5280.9 1737.79  5295.9 1743.34
    5317 1747.26    5332 1753.92    5353 1758.89  5357.5 1762.28  5360.5 1762.28
#Mann= 7 ,-1 , 0
  4598.7     .07       0    4687    .035       0    4988    .035       0
    4992    .035       0  5038.3     .12       0  5076.6    .035       0
  5185.5     .12       0
Bank Sta=4988,4992
XS Rating Curve= 0 ,0
Exp/Cntr=0.3,0.1

Type RM Length L Ch R = 1 ,858     ,51,51,51
BEGIN DESCRIPTION:
Stream0052_DS 5.0
END DESCRIPTION:
XS GIS Cut Line= 3
      2001512.13     13863110.01      2001484.64     13862876.32
      2001418.56     13862685.97
#Sta/Elev= 30
  4764.7 1727.73  4778.8 1725.52  4783.9 1725.89  4789.9 1725.11  4820.1 1723.14
  4850.3 1722.11    4867 1720.83    4872 1721.25  4880.5 1720.85  4900.6 1719.06
  4930.9 1715.07  4955.1 1712.93  4961.1 1711.77  4971.1 1710.98  5003.3 1710.24
  5010.4 1709.66  5015.7 1708.64  5022.6 1707.94  5033.2 1707.27  5039.5 1706.26
  5039.8 1705.76  5043.3 1705.76  5043.5 1706.26  5054.3 1706.44  5064.9 1707.12
  5086.1 1711.06  5096.7 1712.37  5109.1 1713.25  5197.2 1712.79  5201.5 1712.53
#Mann= 3 ,-1 , 0
  4764.7    .035       0  5039.5    .035       0  5043.5    .035       0
Bank Sta=5039.5,5043.5
XS Rating Curve= 0 ,0
Exp/Cntr=0.3,0.1

Type RM Length L Ch R = 1 ,807     ,175,175,175
BEGIN DESCRIPTION:
Stream0052_DS 4.0
END DESCRIPTION:
XS GIS Cut Line= 3
      2001539.23     13863095.72      2001535.07     13862875.16
      2001471.49      13862668.2
#Sta/Elev= 30
  4779.4 1724.81  4800.1 1723.12  4890.1 1718.59  4920.1 1715.89  4930.1 1715.62
  4940.1 1714.05  4950.1 1709.33  4970.2    1698  4978.2 1694.51  4978.4 1694.01
  4981.9 1694.01  4982.2 1694.51  4990.2 1694.71  4997.6 1696.63  5002.7 1696.63
  5010.6 1700.03  5016.6  1700.4  5021.8 1701.71    5042 1702.54  5054.5 1703.69
    5082 1700.49  5087.2  1699.3  5094.3 1707.07  5104.8 1711.53  5119.9 1712.21
  5152.7 1711.22  5157.9 1711.52  5185.4 1711.02  5190.6 1711.49  5216.5 1710.82
#Mann= 3 ,-1 , 0
  4779.4    .035       0  4978.2    .035       0  4982.2    .035       0
Bank Sta=4978.2,4982.2
XS Rating Curve= 0 ,0
Exp/Cntr=0.3,0.1

Type RM Length L Ch R = 1 ,632     ,65,65,65
BEGIN DESCRIPTION:
Stream0052_DS 3.0
END DESCRIPTION:
XS GIS Cut Line= 3
      2001770.47     13862986.85      2001674.08      13862780.9
      2001569.27     13862613.97
#Sta/Elev= 30
  4768.8 1709.76  4773.1 1710.68  4781.9 1710.49  4790.4 1709.51  4813.3 1708.48
  4818.8 1709.45  4883.3 1706.77  4910.2 1705.37  4915.7 1703.93    4933 1703.57
  4938.5 1701.15  4947.5  1700.1  4955.8 1696.99  4961.3 1692.97  4976.7 1692.09
  4976.9 1691.59  4980.4 1691.59  4980.7 1692.09  4996.2 1692.23  5000.6  1694.1
  5006.5 1695.44  5027.7 1703.91  5037.1 1704.33    5043 1706.11  5058.3 1705.92
  5079.5 1708.07    5116 1707.06  5152.5 1707.41  5158.4 1708.09  5193.3 1708.08
#Mann= 4 ,-1 , 0
  4768.8    .035       0  4883.3     .12       0  4976.7     .05       0
  4980.7     .12       0
Bank Sta=4976.7,4980.7
XS Rating Curve= 0 ,0
Exp/Cntr=0.3,0.1

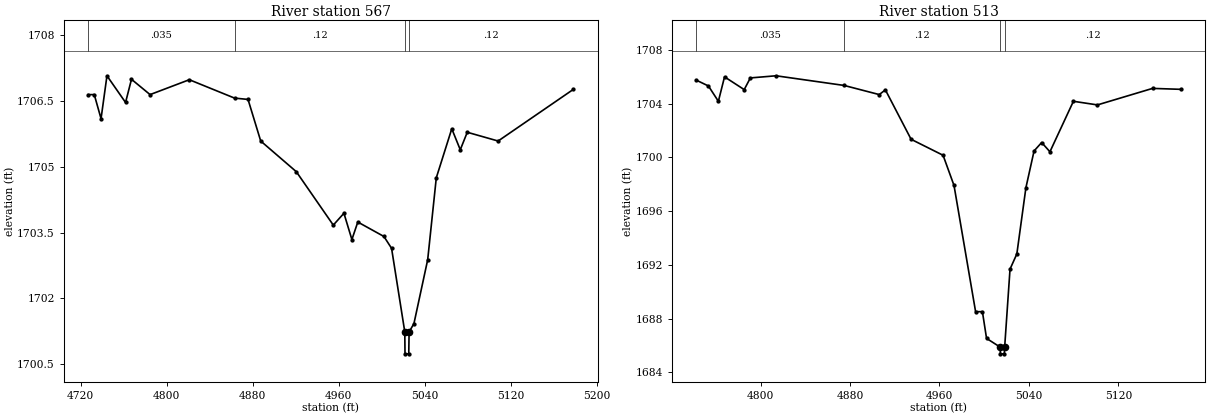
Type RM Length L Ch R = 1 ,567     ,54,54,54
BEGIN DESCRIPTION:
Stream0052_DS 2.0
END DESCRIPTION:
XS GIS Cut Line= 3
      2001835.39     13862979.95      2001718.94     13862733.14
      2001606.46     13862594.93
#Sta/Elev= 30
  4727.1 1706.65  4732.6 1706.65  4738.9  1706.1  4744.4 1707.08  4761.7 1706.47
  4767.2    1707  4784.5 1706.65    4821 1706.99  4863.1 1706.57  4875.6 1706.54
  4887.4 1705.59  4920.5 1704.89  4954.9 1703.67  4964.8 1703.94  4972.2 1703.34
  4977.7 1703.74    5002 1703.41  5009.1 1703.14  5021.4 1701.23  5021.6 1700.73
  5025.1 1700.73  5025.4 1701.23  5029.9 1701.42  5042.7 1702.88  5050.7 1704.75
  5065.1 1705.87    5073 1705.39  5079.5 1705.79  5108.2 1705.59  5178.2 1706.77
#Mann= 4 ,-1 , 0
  4727.1    .035       0  4863.1     .12       0  5021.4     .05       0
  5025.4     .12       0
Bank Sta=5021.4,5025.4
XS Rating Curve= 0 ,0
Exp/Cntr=0.3,0.1

Type RM Length L Ch R = 1 ,513     ,0,0,0
BEGIN DESCRIPTION:
Stream0052_DS 1.0
END DESCRIPTION:
XS GIS Cut Line= 3
      2001879.68       13862955.        2001775.       13862725.
      2001651.53     13862592.38
#Sta/Elev= 30
  4742.3 1705.76  4753.3 1705.32  4762.2 1704.18  4767.7    1706  4785.3 1705.05
  4790.8 1705.92  4813.8 1706.08  4874.7 1705.36  4906.1 1704.68  4911.6 1705.03
  4934.6 1701.35  4963.2 1700.16    4973 1697.91  4992.3 1688.51  4998.4 1688.51
  5002.1 1686.52  5014.3 1685.87  5014.5 1685.37    5018 1685.37  5018.3 1685.87
  5023.1 1691.68  5029.2 1692.81  5037.3 1697.74  5044.6 1700.48  5051.4 1701.11
  5058.8 1700.42  5079.8 1704.18  5101.3 1703.91  5150.6 1705.14  5176.2 1705.07
#Mann= 4 ,-1 , 0
  4742.3    .035       0  4874.7     .12       0  5014.3     .05       0
  5018.3     .12       0
Bank Sta=5014.3,5018.3
XS Rating Curve= 0 ,0
Exp/Cntr=0.3,0.1

Chan Stop Cuts=-1
Use User Specified Reach Order=0
Composite Channel Slope=5