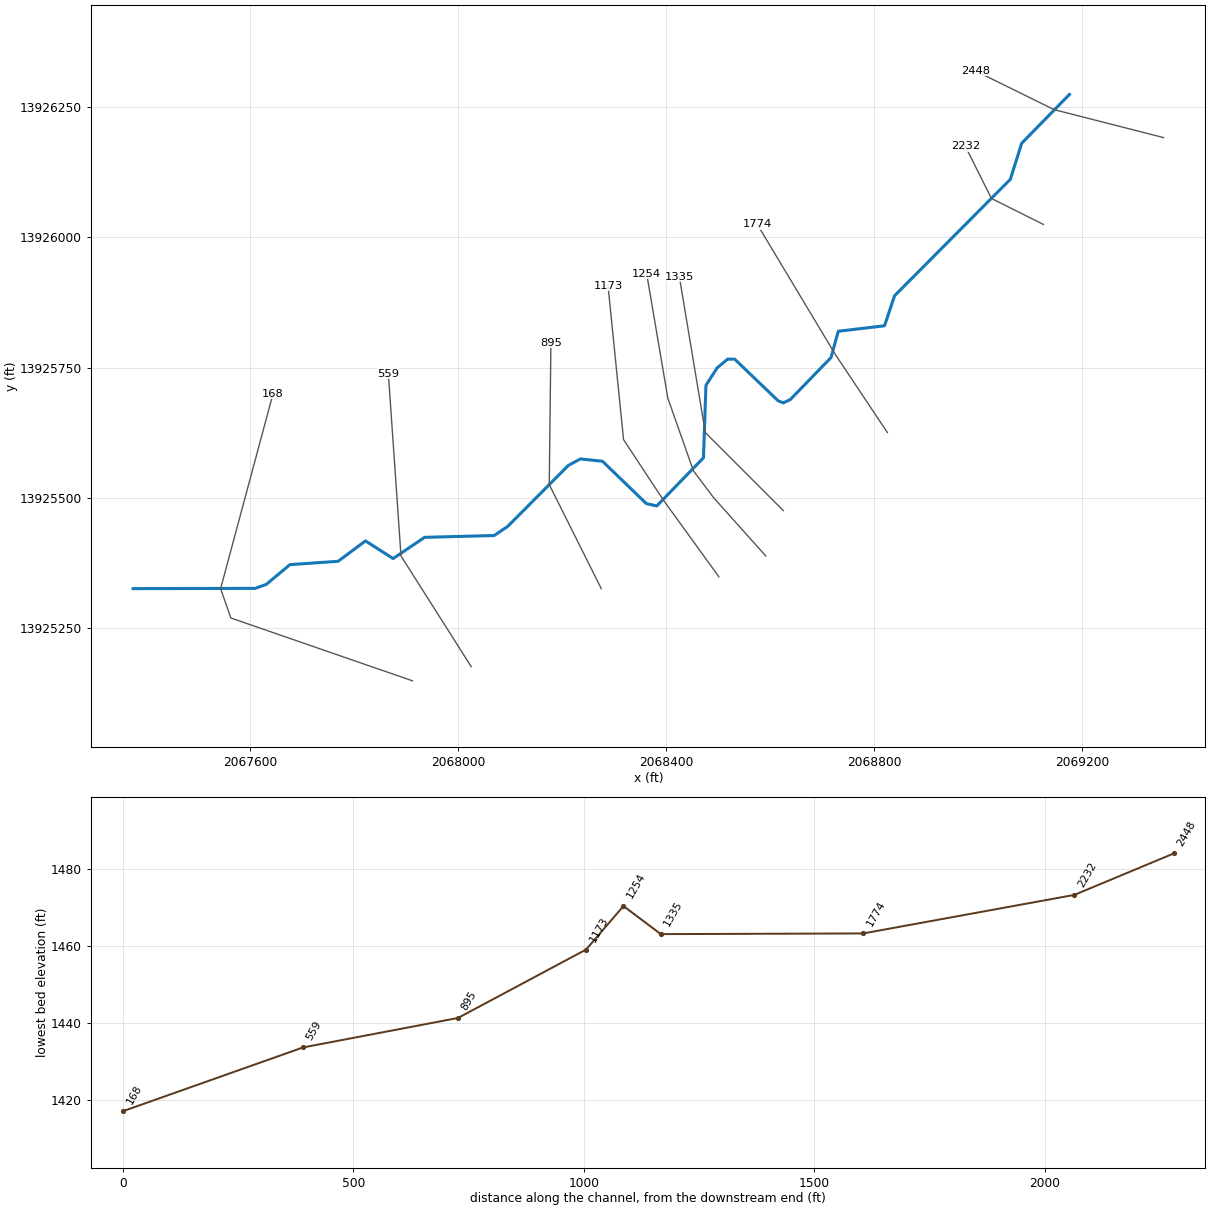
--- Stream0053_DS.prj (project) ---

Proj Title=Stream0053_DS Base Level Engineering
Current Plan=p01
Default Exp/Contr=0.3,0.1
English Units
Geom File=g01
Flow File=f01
Plan File=p01
BEGIN DESCRIPTION:
Stream0053_DS
END DESCRIPTION:

--- Stream0053_DS.p01 (plan) ---

Plan Title=Multiple Run
Short Identifier=Multiple
Geom File=g01
Flow File=f01
Subcritical Flow
K Sum by GR= 0
Std Step Tol= 0.01
Critical Tol= 0.01
Num of Std Step Trials= 20
Max Error Tol= 0.3
Flow Tol Ratio= 0.001
Split Flow NTrial= 30
Split Flow Tol= 0.02
Split Flow Ratio= 0.02
Log Output Level= 0
Friction Slope Method= 1
Unsteady Friction Slope Method= 2
Unsteady Bridges Friction Slope Method= 1
Parabolic Critical Depth
Global Vel Dist=  1 , 1 , 1
Global Log Level= 0
CheckData=True
Encroach Param= -1, 0, 0, 0
BEGIN DESCRIPTION:
Multiple Run
END DESCRIPTION:

--- Stream0053_DS.f01 (steady flow) ---

Flow Title=Multiple
Number of Profiles=7
Profile Names=10-year,25-year,50-year,1pct_min,100-year,1pct_plu,500-year
River Rch & RM= Stream0053_DS,Reach-1,2448
     361     578     774     507    1011    2017    1701
River Rch & RM= Stream0053_DS,Reach-1,2232
     464     755    1023     676    1349    2691    2315
Boundary for River Rch & Prof#=Stream0053_DS,Reach-1,1
Up Type=0
Dn Type=3
Dn Slope=0.005
Boundary for River Rch & Prof#=Stream0053_DS,Reach-1,2
Up Type=0
Dn Type=3
Dn Slope=0.005
Boundary for River Rch & Prof#=Stream0053_DS,Reach-1,3
Up Type=0
Dn Type=3
Dn Slope=0.005
Boundary for River Rch & Prof#=Stream0053_DS,Reach-1,4
Up Type=0
Dn Type=3
Dn Slope=0.005
Boundary for River Rch & Prof#=Stream0053_DS,Reach-1,5
Up Type=0
Dn Type=3
Dn Slope=0.005
Boundary for River Rch & Prof#=Stream0053_DS,Reach-1,6
Up Type=0
Dn Type=3
Dn Slope=0.005
Boundary for River Rch & Prof#=Stream0053_DS,Reach-1,7
Up Type=0
Dn Type=3
Dn Slope=0.005

--- Stream0053_DS.g01 (geometry) ---

Geom Title=Existing Conditions

River Reach=Stream0053_DS,Reach-1
Reach XY= 30
      2069175.00     13926275.00      2069083.11     13926181.07
      2069061.37     13926111.79      2068838.74     13925887.95
      2068819.46     13925830.29      2068730.54     13925819.71
      2068716.70     13925769.26      2068638.36     13925688.41
      2068625.01     13925682.09      2068615.00     13925686.00
      2068531.49     13925766.08      2068518.00     13925766.17
      2068497.86     13925749.53      2068476.21     13925715.76
      2068471.46     13925576.44      2068381.69     13925483.95
      2068361.68     13925488.44      2068277.29     13925569.91
      2068234.80     13925574.29      2068211.79     13925561.89
      2068095.16     13925444.61      2068069.14     13925427.07
      2067935.44     13925423.61      2067874.90     13925382.79
      2067821.78     13925416.72      2067769.11     13925377.54
      2067676.60     13925371.15      2067631.06     13925333.14
      2067609.78     13925325.52      2067375.00     13925325.00

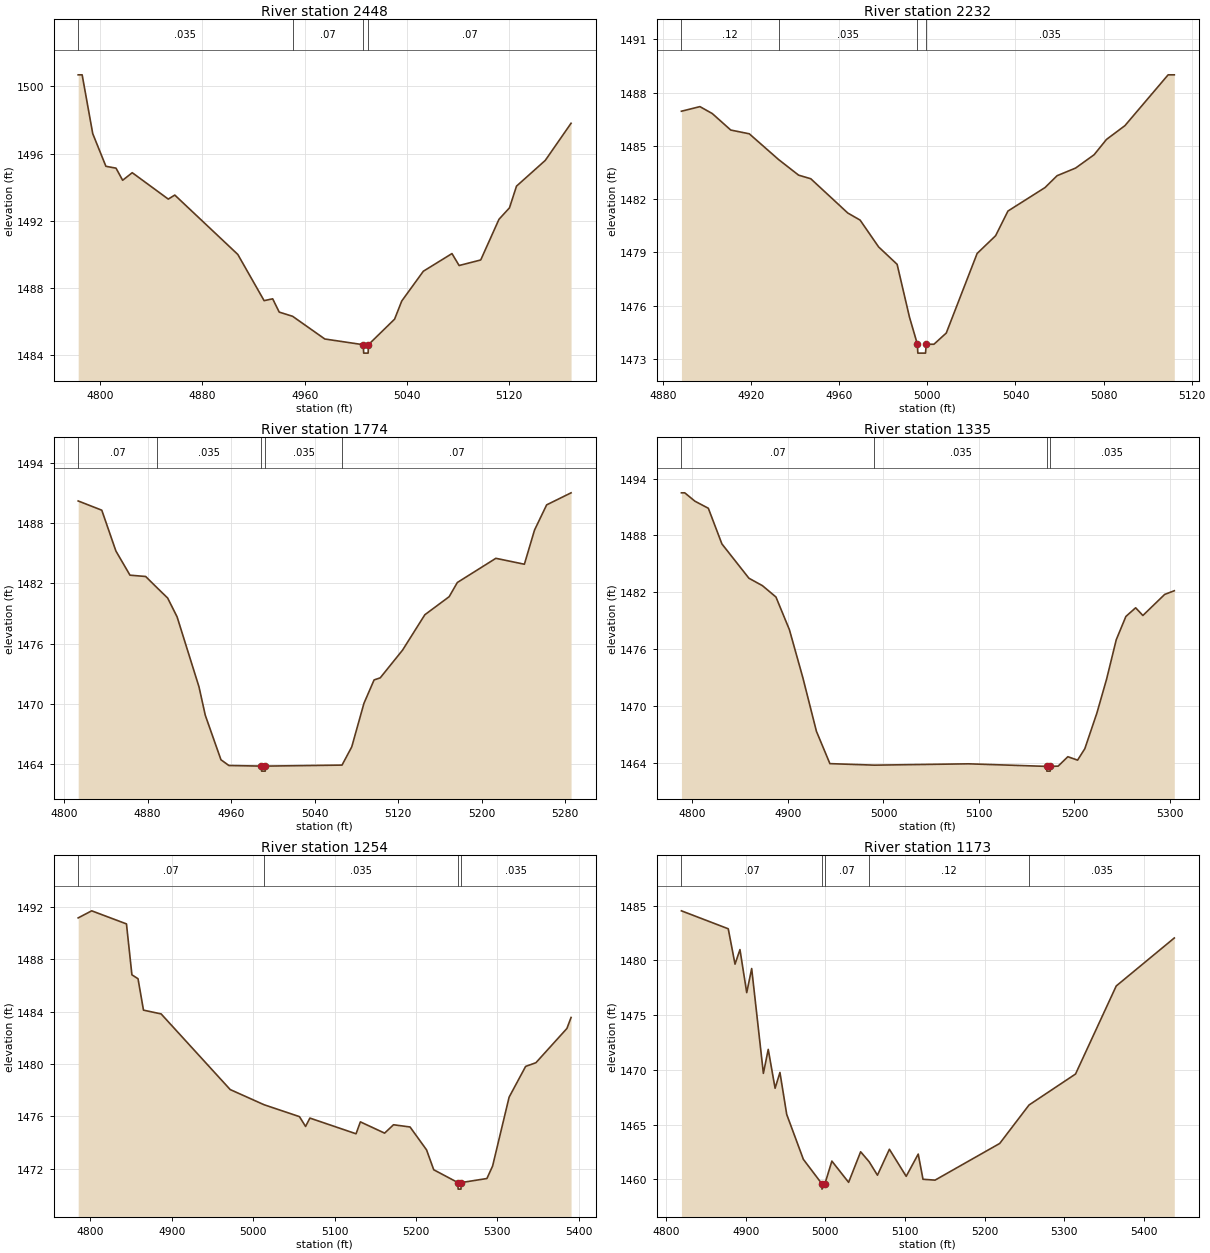
Type RM Length L Ch R = 1,2448,216,216,216
BEGIN DESCRIPTION:
Stream0053_DS 6.0
END DESCRIPTION:
XS GIS Cut Line= 3
      2069356.02     13926191.98      2069145.58     13926245.73
      2068994.42     13926320.18
#Sta/Elev= 30
  4782.8 1500.68  4785.9 1500.68  4794.2 1497.18  4804.5 1495.24  4812.4 1495.13
  4817.6 1494.41  4825.1 1494.86  4853.3 1493.29  4858.4 1493.53  4907.7 1490.00
  4928.3 1487.25  4935.0 1487.36  4940.1 1486.57  4950.6 1486.32  4975.8 1484.97
  5005.9 1484.63  5006.2 1484.13  5009.7 1484.13  5009.9 1484.63  5030.4 1486.15
  5036.0 1487.23  5052.9 1489.00  5075.3 1490.05  5080.9 1489.34  5097.8 1489.67
  5112.1 1492.09  5120.3 1492.77  5125.8 1494.06  5148.3 1495.59  5168.5 1497.80
#Mann=4,-1,0
  4782.8   0.035       0  4950.6    0.07       0  5005.9    0.05       0
  5009.9    0.07       0
Bank Sta=5005.9,5009.9
Exp/Cntr=0.3,0.1

Type RM Length L Ch R = 1,2232,458,458,458
BEGIN DESCRIPTION:
Stream0053_DS 5.0
END DESCRIPTION:
XS GIS Cut Line= 3
      2069125.04     13926024.98      2069025.00     13926075.00
      2068974.98     13926175.04
#Sta/Elev= 30
  4888.4 1486.95  4896.8 1487.21  4902.4 1486.82  4910.8 1485.89  4919.2 1485.68
  4932.5 1484.23  4941.6 1483.35  4947.1 1483.15  4963.9 1481.22  4969.5 1480.82
  4977.9 1479.31  4986.3 1478.33  4991.9 1475.36  4995.5 1473.83  4995.7 1473.33
  4999.2 1473.33  4999.5 1473.83  5003.0 1473.83  5008.6 1474.46  5022.6 1478.94
  5031.0 1479.94  5036.6 1481.33  5053.4 1482.65  5058.9 1483.32  5067.3 1483.75
  5075.7 1484.50  5081.3 1485.36  5089.7 1486.14  5109.3 1489.00  5112.1 1489.00
#Mann=4,-1,0
  4888.4    0.12       0  4932.5   0.035       0  4995.5   0.035       0
  4999.5   0.035       0
Bank Sta=4995.5,4999.5
Exp/Cntr=0.3,0.1

Type RM Length L Ch R = 1,1774,439,439,439
BEGIN DESCRIPTION:
Stream0053_DS 4.0
END DESCRIPTION:
XS GIS Cut Line= 3
      2068825.02     13925624.97      2068725.00     13925775.00
      2068574.98     13926025.03
#Sta/Elev= 30
  4813.6 1490.21  4836.2 1489.29  4849.7 1485.23  4863.2 1482.82  4878.2 1482.69
  4889.1 1481.57  4899.3 1480.54  4908.3 1478.67  4929.3 1471.69  4935.3 1468.87
  4950.3 1464.44  4957.9 1463.87  4988.9 1463.81  4989.2 1463.31  4992.7 1463.31
  4992.9 1463.81  5066.2 1463.91  5075.5 1465.72  5087.2 1470.06  5096.9 1472.39
  5102.8 1472.60  5124.1 1475.35  5145.5 1478.88  5168.8 1480.68  5176.6 1482.09
  5213.5 1484.50  5240.8 1483.91  5250.5 1487.31  5262.1 1489.82  5285.5 1491.02
#Mann=5,-1,0
  4813.6    0.07       0  4889.1   0.035       0  4988.9   0.035       0
  4992.9   0.035       0  5066.2    0.07       0
Bank Sta=4988.9,4992.9
Exp/Cntr=0.3,0.1

Type RM Length L Ch R = 1,1335,81,81,81
BEGIN DESCRIPTION:
Stream0053_DS 3.0
END DESCRIPTION:
XS GIS Cut Line= 3
      2068624.97     13925475.03      2068475.00     13925625.00
      2068425.00     13925924.97
#Sta/Elev= 30
  4788.4 1492.49  4791.9 1492.49  4802.5 1491.61  4816.6 1490.86  4830.8 1487.10
  4859.1 1483.48  4873.2 1482.70  4887.4 1481.50  4901.5 1478.05  4915.6 1472.98
  4929.8 1467.33  4943.9 1463.92  4990.6 1463.76  5089.2 1463.90  5170.8 1463.63
  5171.1 1463.13  5174.6 1463.13  5174.8 1463.63  5183.0 1463.66  5193.1 1464.65
  5203.3 1464.29  5210.9 1465.50  5223.5 1469.25  5233.7 1472.84  5243.8 1476.99
  5253.9 1479.45  5264.1 1480.36  5271.7 1479.55  5294.5 1481.77  5304.6 1482.16
#Mann=4,-1,0
  4788.4    0.07       0  4990.6   0.035       0  5170.8   0.035       0
  5174.8   0.035       0
Bank Sta=5170.8,5174.8
Exp/Cntr=0.3,0.1

Type RM Length L Ch R = 1,1254,81,81,81
BEGIN DESCRIPTION:
Stream0053_DS 2.1
END DESCRIPTION:
XS GIS Cut Line= 5
      2068591.25     13925387.77      2068490.96     13925499.79
      2068452.14     13925551.36      2068402.99     13925691.05
      2068362.33     13925930.03
#Sta/Elev= 30
  4785.1 1491.16  4801.7 1491.70  4844.4 1490.70  4851.1 1486.81  4858.6 1486.51
  4865.3 1484.11  4887.0 1483.82  4971.8 1478.04  5013.4 1476.88  5056.9 1475.97
  5064.4 1475.22  5069.7 1475.86  5126.4 1474.66  5131.7 1475.57  5161.5 1474.71
  5172.4 1475.35  5192.7 1475.18  5213.0 1473.43  5221.8 1471.91  5251.5 1470.93
  5251.8 1470.43  5255.3 1470.43  5255.5 1470.93  5287.1 1471.24  5294.1 1472.19
  5314.4 1477.46  5334.7 1479.81  5347.3 1480.09  5385.4 1482.71  5390.5 1483.55
#Mann=4,-1,0
  4785.1    0.07       0  5013.4   0.035       0  5251.5    0.05       0
  5255.5   0.035       0
Bank Sta=5251.5,5255.5
Exp/Cntr=0.3,0.1

Type RM Length L Ch R = 1,1173,278,278,278
BEGIN DESCRIPTION:
Stream0053_DS 2.2
END DESCRIPTION:
XS GIS Cut Line= 4
      2068501.13     13925347.79      2068395.05     13925494.19
      2068317.81     13925611.48      2068287.98     13925907.55
#Sta/Elev= 30
  4819.2 1484.53  4878.0 1482.89  4886.5 1479.66  4892.7 1480.99  4901.2 1477.06
  4907.4 1479.26  4922.1 1469.69  4928.2 1471.88  4936.8 1468.33  4942.9 1469.77
  4951.4 1465.94  4972.3 1461.84  4995.4 1459.62  4995.7 1459.12  4999.4 1459.62
  5008.1 1461.68  5029.1 1459.74  5044.2 1462.53  5054.9 1461.62  5065.3 1460.39
  5080.3 1462.76  5101.4 1460.29  5116.5 1462.32  5122.5 1460.02  5137.6 1459.94
  5218.8 1463.29  5255.6 1466.80  5314.0 1469.63  5365.1 1477.67  5438.0 1482.05
#Mann=5,-1,0
  4819.2    0.07       0  4995.4    0.05       0  4999.4    0.07       0
  5054.9    0.12       0  5255.6   0.035       0
Bank Sta=4995.4,4999.4
Exp/Cntr=0.3,0.1

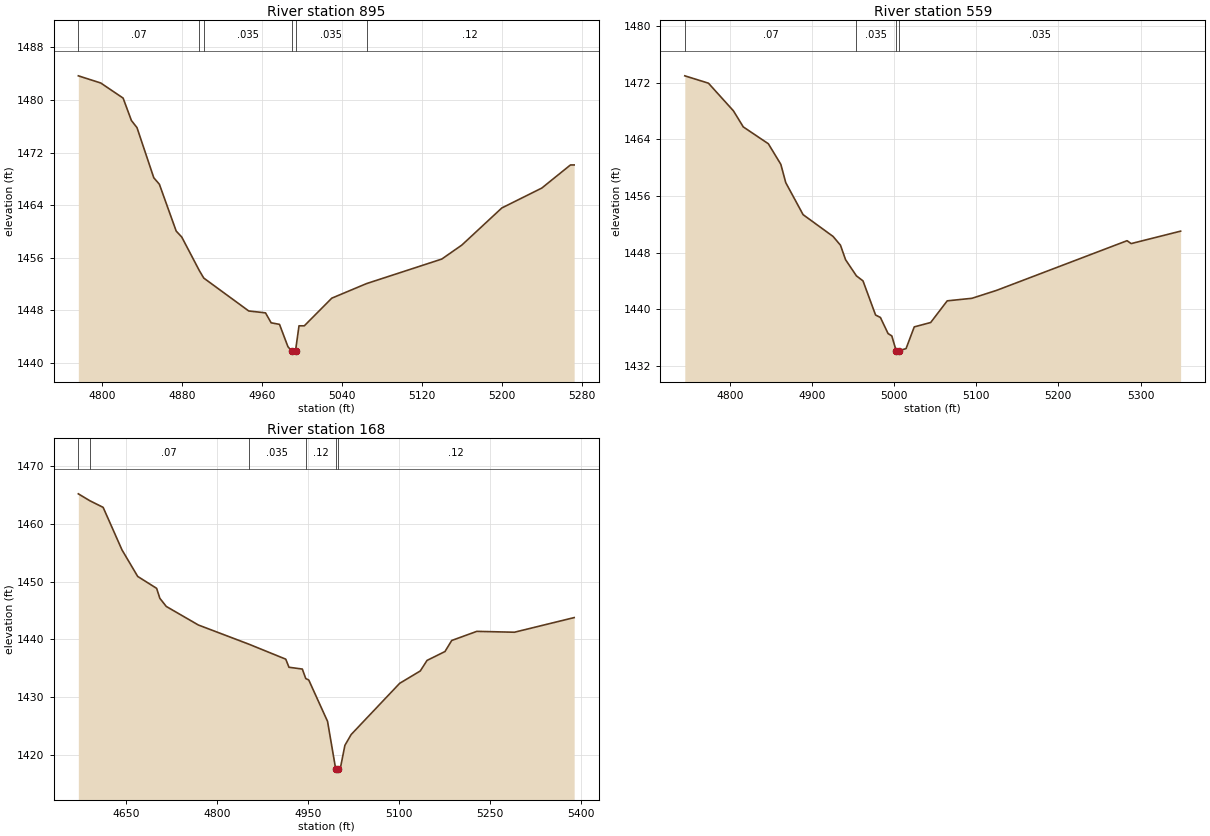
Type RM Length L Ch R = 1,895,336,336,336
BEGIN DESCRIPTION:
Stream0053_DS 2.0
END DESCRIPTION:
XS GIS Cut Line= 3
      2068275.01     13925324.97      2068175.00     13925525.00
      2068178.22     13925797.44
#Sta/Elev= 30
  4776.0 1483.68  4798.4 1482.59  4820.8 1480.29  4829.1 1476.88  4834.7 1475.79
  4851.5 1468.16  4857.1 1467.17  4873.9 1460.05  4879.5 1459.13  4897.2 1453.99
  4901.5 1452.89  4946.5 1447.88  4963.3 1447.59  4968.9 1446.08  4977.3 1445.84
  4985.7 1442.45  4989.3 1441.81  4989.5 1441.31  4993.0 1441.31  4993.3 1441.81
  4996.8 1445.62  5002.1 1445.62  5029.6 1449.83  5064.4 1452.05  5139.6 1455.78
  5159.7 1457.91  5199.7 1463.56  5239.7 1466.59  5268.4 1470.11  5272.1 1470.11
#Mann=6,-1,0
  4776.0    0.07       0  4897.2    0.12       0  4901.5   0.035       0
  4989.3   0.035       0  4993.3   0.035       0  5064.4    0.12       0
Bank Sta=4989.3,4993.3
Exp/Cntr=0.3,0.1

Type RM Length L Ch R = 1,559,391,391,391
BEGIN DESCRIPTION:
Stream0053_DS 1.0
END DESCRIPTION:
XS GIS Cut Line= 3
      2068025.01     13925174.99      2067890.03     13925387.76
      2067865.72     13925738.44
#Sta/Elev= 30
  4745.3 1472.98  4774.1 1471.94  4804.5 1468.03  4816.5 1465.76  4847.0 1463.38
  4862.2 1460.47  4868.2 1457.88  4889.3 1453.36  4925.8 1450.28  4934.8 1449.04
  4941.0 1446.99  4954.2 1444.71  4962.2 1444.00  4977.5 1439.18  4983.4 1438.83
  4992.7 1436.56  4997.3 1436.22  5002.5 1434.15  5002.8 1433.65  5006.3 1433.65
  5006.5 1434.15  5014.6 1434.43  5024.6 1437.50  5044.6 1438.12  5064.7 1441.18
  5094.8 1441.54  5124.8 1442.66  5283.6 1449.68  5288.6 1449.27  5348.8 1451.03
#Mann=4,-1,0
  4745.3    0.07       0  4954.2   0.035       0  5002.5   0.035       0
  5006.5   0.035       0
Bank Sta=5002.5,5006.5
Exp/Cntr=0.3,0.1

Type RM Length L Ch R = 1,168,0,0,0
BEGIN DESCRIPTION:
Stream0053_DS 0.0
END DESCRIPTION:
XS GIS Cut Line= 4
      2067912.02     13925147.82      2067563.00     13925268.50
      2067543.25     13925324.84      2067644.14     13925700.01
#Sta/Elev= 30
  4571.0 1465.19  4589.9 1464.00  4611.9 1462.85  4643.0 1455.49  4668.9 1450.90
  4700.1 1448.84  4705.4 1447.12  4716.0 1445.71  4768.9 1442.50  4852.0 1439.19
  4913.0 1436.59  4918.3 1435.19  4940.3 1434.88  4946.0 1433.23  4950.9 1432.99
  4981.9 1425.83  4995.4 1417.55  4995.7 1417.05  4999.4 1417.55  5002.7 1417.55
  5010.5 1421.68  5020.8 1423.55  5100.8 1432.41  5134.8 1434.55  5145.9 1436.37
  5175.5 1437.91  5186.6 1439.82  5228.0 1441.40  5290.1 1441.25  5388.5 1443.78
#Mann=6,-1,0
  4571.0   0.035       0  4589.9    0.07       0  4852.0   0.035       0
  4946.0    0.12       0  4995.4    0.05       0  4999.4    0.12       0
Bank Sta=4995.4,4999.4
Exp/Cntr=0.3,0.1

Chan Stop Cuts=-1