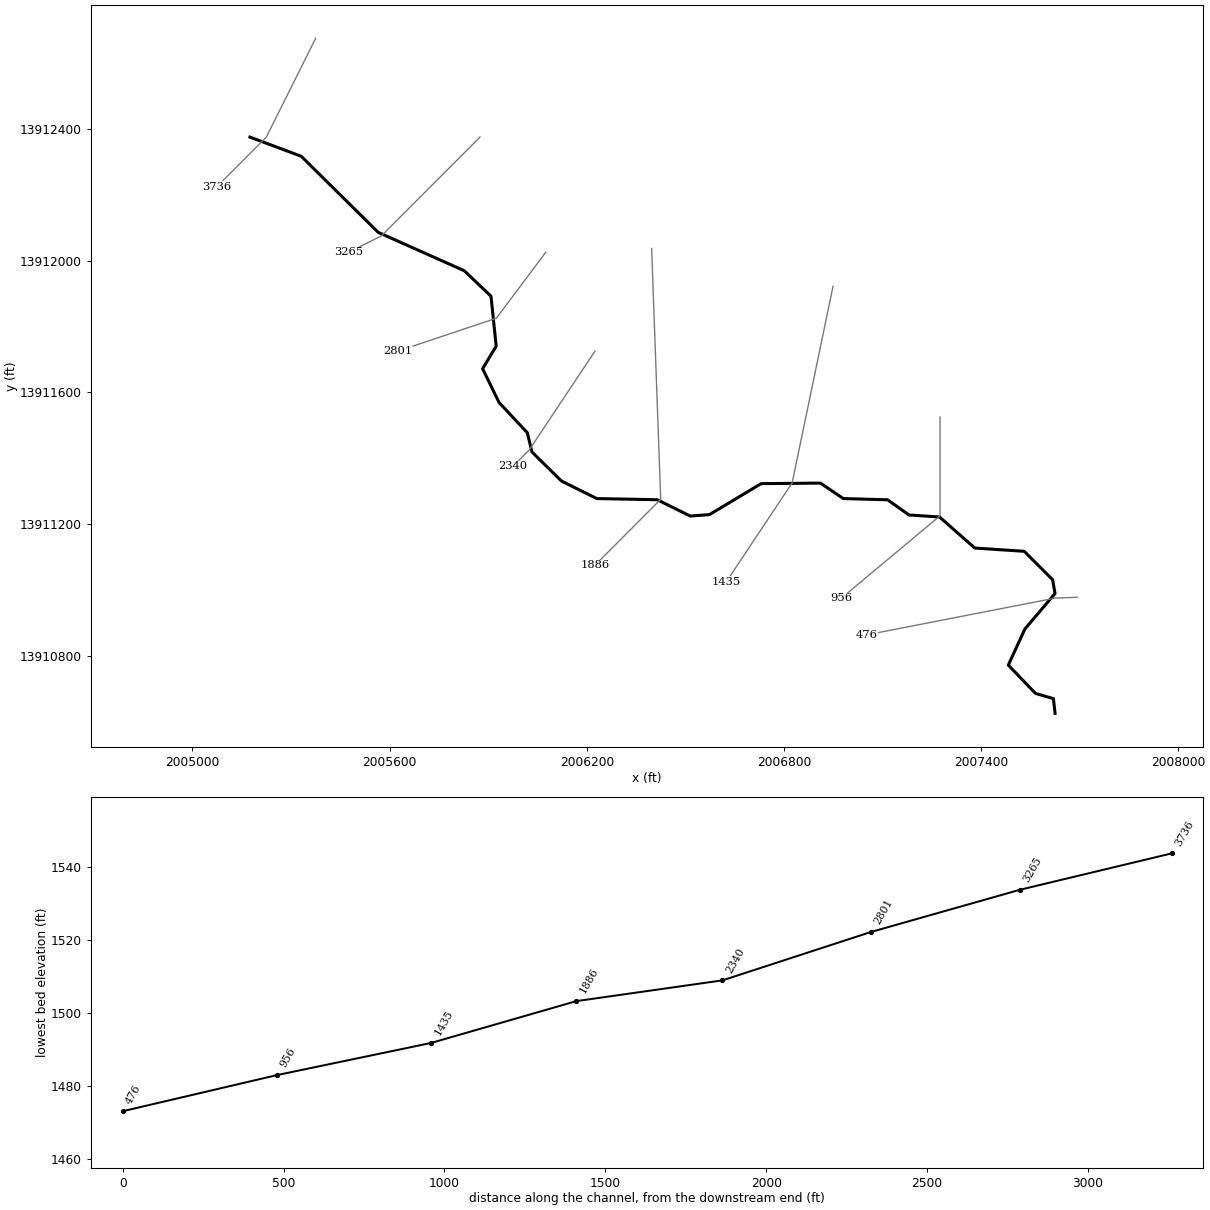
--- Stream0054_DS.prj (project) ---

Proj Title=Stream0054_DS Base Level Engineering
Current Plan=p01
Default Exp/Contr=0.3,0.1
English Units
Geom File=g01
Flow File=f01
Plan File=p01
BEGIN DESCRIPTION:
Stream0054_DS
END DESCRIPTION:

--- Stream0054_DS.p01 (plan) ---

Plan Title=Multiple Run
Short Identifier=Multiple
Geom File=g01
Flow File=f01
Subcritical Flow
K Sum by GR= 0
Std Step Tol= 0.01
Critical Tol= 0.01
Num of Std Step Trials= 20
Max Error Tol= 0.3
Flow Tol Ratio= 0.001
Split Flow NTrial= 30
Split Flow Tol= 0.02
Split Flow Ratio= 0.02
Log Output Level= 0
Friction Slope Method= 1
Unsteady Friction Slope Method= 2
Unsteady Bridges Friction Slope Method= 1
Parabolic Critical Depth
Global Vel Dist=  1 , 1 , 1
Global Log Level= 0
CheckData=True
Encroach Param= -1, 0, 0, 0
BEGIN DESCRIPTION:
Multiple Run
END DESCRIPTION:

--- Stream0054_DS.f01 (steady flow) ---

Flow Title=Multiple
Number of Profiles=7
Profile Names=10-year,25-year,50-year,1pct_min,100-year,1pct_plu,500-year
River Rch & RM= Stream0054_DS,Reach-1,3736
     601    1000    1375     920    1836    3662    3238
River Rch & RM= Stream0054_DS,Reach-1,3265
     754    1270    1759    1184    2363    4714    4224
Boundary for River Rch & Prof#=Stream0054_DS,Reach-1,1
Up Type=0
Dn Type=3
Dn Slope=0.005
Boundary for River Rch & Prof#=Stream0054_DS,Reach-1,2
Up Type=0
Dn Type=3
Dn Slope=0.005
Boundary for River Rch & Prof#=Stream0054_DS,Reach-1,3
Up Type=0
Dn Type=3
Dn Slope=0.005
Boundary for River Rch & Prof#=Stream0054_DS,Reach-1,4
Up Type=0
Dn Type=3
Dn Slope=0.005
Boundary for River Rch & Prof#=Stream0054_DS,Reach-1,5
Up Type=0
Dn Type=3
Dn Slope=0.005
Boundary for River Rch & Prof#=Stream0054_DS,Reach-1,6
Up Type=0
Dn Type=3
Dn Slope=0.005
Boundary for River Rch & Prof#=Stream0054_DS,Reach-1,7
Up Type=0
Dn Type=3
Dn Slope=0.005

--- Stream0054_DS.g01 (geometry) ---

Geom Title=Existing Conditions

River Reach=Stream0054_DS,Reach-1
Reach XY= 30
      2005175.00     13912375.00      2005331.06     13912316.87
      2005565.32     13912085.76      2005827.31     13911969.17
      2005908.59     13911891.80      2005924.36     13911740.17
      2005883.04     13911671.68      2005933.14     13911568.96
      2006019.13     13911477.28      2006033.15     13911418.93
      2006122.69     13911330.82      2006230.52     13911277.35
      2006414.50     13911273.78      2006514.95     13911224.22
      2006573.42     13911228.67      2006730.52     13911322.65
      2006911.08     13911324.32      2006980.53     13911277.39
      2007115.33     13911273.61      2007180.57     13911227.47
      2007273.50     13911221.38      2007380.86     13911127.08
      2007531.21     13911117.19      2007617.55     13911031.07
      2007624.96     13910989.07      2007533.14     13910881.04
      2007482.76     13910771.58      2007565.41     13910685.72
      2007620.08     13910669.67      2007625.00     13910625.00

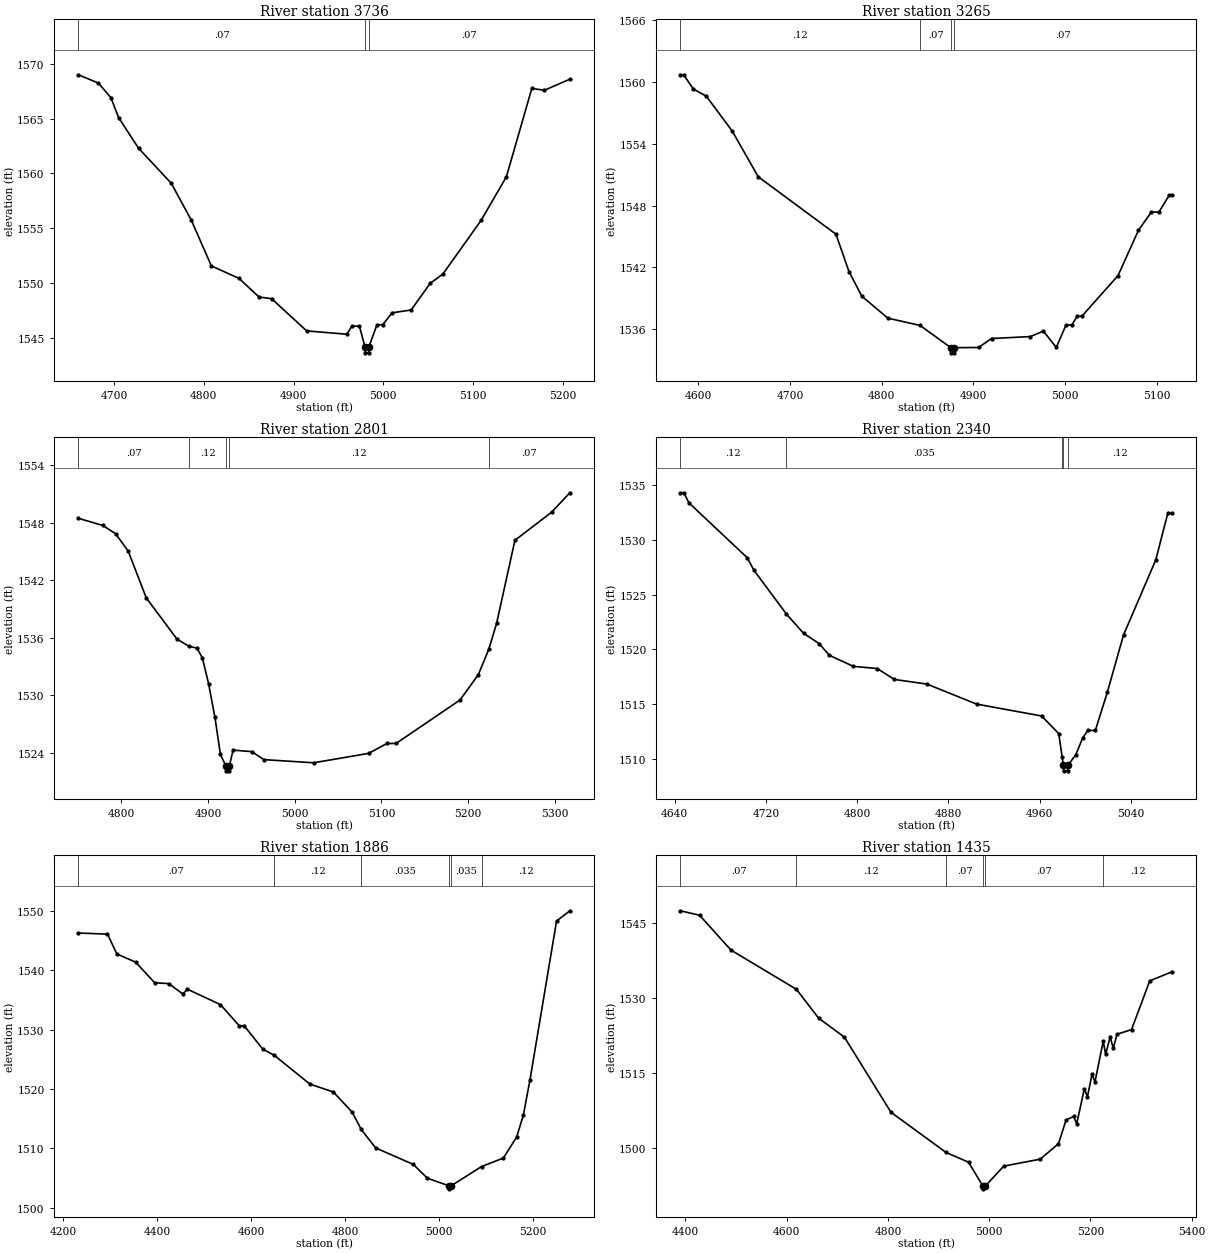
Type RM Length L Ch R = 1,3736,471,471,471
BEGIN DESCRIPTION:
Stream0054_DS 8.0
END DESCRIPTION:
XS GIS Cut Line= 3
      2005374.98     13912674.97      2005225.00     13912375.00
      2005075.01     13912225.01
#Sta/Elev= 30
  4660.3 1569.00  4682.6 1568.24  4696.6 1566.90  4705.0 1565.10  4727.3 1562.30
  4763.7 1559.11  4786.0 1555.75  4808.4 1551.57  4839.2 1550.43  4861.5 1548.73
  4875.5 1548.58  4914.6 1545.64  4959.3 1545.34  4964.9 1546.07  4973.3 1546.08
  4979.7 1544.14  4980.0 1543.64  4983.5 1543.64  4983.7 1544.14  4992.9 1546.20
  4999.2 1546.20  5009.8 1547.29  5031.0 1547.55  5052.2 1549.98  5066.4 1550.83
  5108.8 1555.71  5137.1 1559.70  5165.4 1567.75  5179.5 1567.59  5207.8 1568.60
#Mann=3,-1,0
  4660.3    0.07       0  4979.7    0.05       0  4983.7    0.07       0
Bank Sta=4979.7,4983.7
Exp/Cntr=0.3,0.1

Type RM Length L Ch R = 1,3265,464,464,464
BEGIN DESCRIPTION:
Stream0054_DS 7.0
END DESCRIPTION:
XS GIS Cut Line= 3
      2005875.01     13912375.01      2005575.00     13912075.00
      2005474.98     13912024.99
#Sta/Elev= 30
  4580.5 1560.70  4584.0 1560.70  4594.6 1559.32  4608.8 1558.62  4637.1 1555.23
  4665.4 1550.80  4750.2 1545.22  4764.4 1541.59  4778.5 1539.19  4806.8 1537.07
  4842.0 1536.36  4875.5 1534.20  4875.7 1533.70  4879.2 1533.70  4879.5 1534.20
  4905.8 1534.22  4919.9 1535.09  4962.3 1535.28  4976.5 1535.81  4990.6 1534.22
  5001.2 1536.41  5007.6 1536.41  5013.2 1537.23  5018.7 1537.28  5057.9 1541.20
  5080.2 1545.60  5094.2 1547.36  5102.6 1547.38  5113.8 1549.01  5116.6 1549.01
#Mann=4,-1,0
  4580.5    0.12       0  4842.0    0.07       0  4875.5    0.05       0
  4879.5    0.07       0
Bank Sta=4875.5,4879.5
Exp/Cntr=0.3,0.1

Type RM Length L Ch R = 1,2801,461,461,461
BEGIN DESCRIPTION:
Stream0054_DS 6.0
END DESCRIPTION:
XS GIS Cut Line= 3
      2006075.03     13912025.04      2005925.00     13911825.00
      2005624.98     13911724.99
#Sta/Elev= 30
  4750.8 1548.44  4779.0 1547.69  4793.6 1546.83  4808.1 1545.03  4829.0 1540.14
  4864.4 1535.85  4878.7 1535.08  4887.3 1534.92  4893.6 1533.89  4900.8 1531.20
  4908.1 1527.70  4914.4 1523.84  4920.7 1522.62  4921.0 1522.12  4924.5 1522.12
  4924.7 1522.62  4929.0 1524.28  4950.8 1524.12  4964.4 1523.29  5021.9 1522.96
  5085.2 1523.94  5106.3 1524.97  5116.8 1524.97  5190.6 1529.51  5211.7 1532.16
  5223.7 1534.80  5232.7 1537.50  5253.8 1546.15  5296.0 1549.07  5317.1 1551.10
#Mann=5,-1,0
  4750.8    0.07       0  4878.7    0.12       0  4920.7    0.05       0
  4924.7    0.12       0  5223.7    0.07       0
Bank Sta=4920.7,4924.7
Exp/Cntr=0.3,0.1

Type RM Length L Ch R = 1,2340,454,454,454
BEGIN DESCRIPTION:
Stream0054_DS 5.0
END DESCRIPTION:
XS GIS Cut Line= 3
      2006224.98     13911724.98      2006025.00     13911425.00
      2005975.03     13911375.03
#Sta/Elev= 30
  4644.9 1534.30  4647.9 1534.30  4652.4 1533.38  4703.5 1528.37  4709.5 1527.21
  4738.0 1523.21  4753.0 1521.46  4766.6 1520.52  4775.6 1519.45  4796.6 1518.44
  4817.6 1518.24  4832.7 1517.24  4861.2 1516.82  4904.8 1514.99  4961.9 1513.90
  4976.9 1512.29  4979.9 1510.12  4980.9 1509.39  4981.1 1508.89  4984.6 1508.89
  4984.9 1509.39  4991.9 1510.37  4997.9 1511.91  5002.4 1512.58  5009.0 1512.58
  5019.6 1516.10  5033.7 1521.30  5062.0 1528.16  5072.6 1532.44  5076.1 1532.44
#Mann=5,-1,0
  4644.9    0.12       0  4738.0   0.035       0  4979.9    0.12       0
  4980.9    0.05       0  4984.9    0.12       0
Bank Sta=4980.9,4984.9
Exp/Cntr=0.3,0.1

Type RM Length L Ch R = 1,1886,451,451,451
BEGIN DESCRIPTION:
Stream0054_DS 4.0
END DESCRIPTION:
XS GIS Cut Line= 3
      2006397.40     13912036.76      2006425.00     13911275.00
      2006225.00     13911075.00
#Sta/Elev= 30
  4233.2 1546.26  4295.0 1546.07  4315.0 1542.73  4355.0 1541.35  4395.1 1537.90
  4425.1 1537.74  4455.1 1536.01  4465.1 1536.80  4535.2 1534.21  4575.2 1530.65
  4585.7 1530.66  4625.2 1526.72  4650.0 1525.66  4725.3 1520.84  4775.3 1519.51
  4815.3 1516.12  4834.6 1513.21  4865.4 1510.09  4945.4 1507.32  4975.4 1504.99
  5021.7 1503.71  5022.0 1503.21  5025.7 1503.71  5090.4 1506.96  5136.9 1508.39
  5165.2 1511.94  5179.3 1515.60  5193.4 1521.51  5250.0 1548.27  5278.3 1550.00
#Mann=6,-1,0
  4233.2    0.07       0  4650.0    0.12       0  4834.6   0.035       0
  5021.7   0.035       0  5025.7   0.035       0  5090.4    0.12       0
Bank Sta=5021.7,5025.7
Exp/Cntr=0.3,0.1

Type RM Length L Ch R = 1,1435,479,479,479
BEGIN DESCRIPTION:
Stream0054_DS 3.0
END DESCRIPTION:
XS GIS Cut Line= 3
      2006949.48     13911922.12      2006825.00     13911325.00
      2006625.01     13911025.01
#Sta/Elev= 30
  4390.2 1547.35  4428.1 1546.46  4490.1 1539.49  4619.5 1531.64  4663.1 1525.90
  4714.1 1522.09  4806.1 1507.07  4914.9 1499.04  4959.3 1497.09  4987.9 1492.27
  4988.2 1491.77  4991.9 1492.27  5028.7 1496.31  5100.8 1497.70  5136.9 1500.79
  5151.9 1505.55  5166.9 1506.24  5172.9 1504.76  5187.9 1511.78  5194.0 1510.15
  5203.0 1514.63  5209.0 1513.21  5225.2 1521.25  5230.0 1518.67  5239.0 1522.16
  5245.0 1519.86  5252.5 1522.67  5281.1 1523.60  5317.1 1533.34  5360.7 1535.14
#Mann=6,-1,0
  4390.2    0.07       0  4619.5    0.12       0  4914.9    0.07       0
  4987.9    0.05       0  4991.9    0.07       0  5225.2    0.12       0
Bank Sta=4987.9,4991.9
Exp/Cntr=0.3,0.1

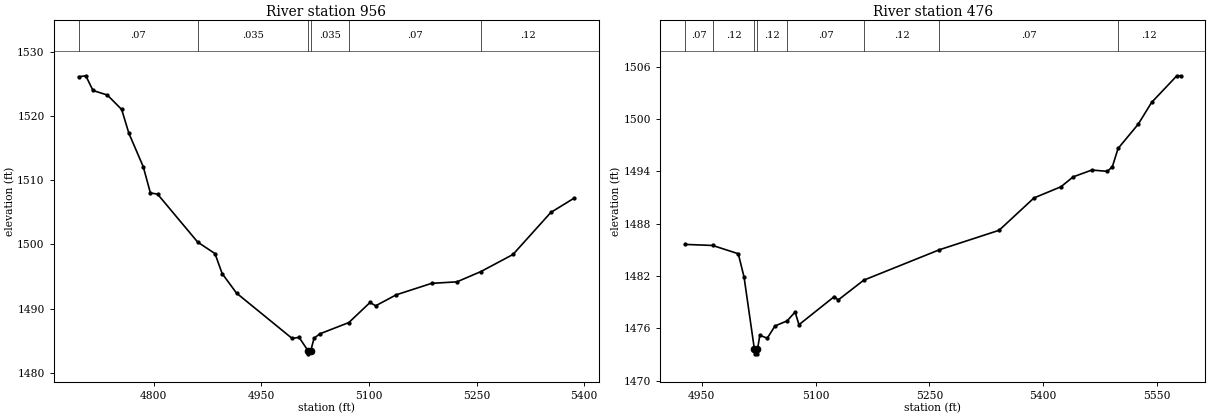
Type RM Length L Ch R = 1,956,480,480,480
BEGIN DESCRIPTION:
Stream0054_DS 2.0
END DESCRIPTION:
XS GIS Cut Line= 3
      2007275.00     13911525.00      2007275.00     13911225.00
      2006975.01     13910975.01
#Sta/Elev= 30
  4695.4 1526.12  4705.4 1526.27  4715.4 1523.98  4735.4 1523.27  4755.4 1521.02
  4765.4 1517.32  4785.4 1512.12  4795.4 1508.03  4805.4 1507.84  4861.3 1500.37
  4885.4 1498.58  4895.4 1495.47  4915.4 1492.43  4992.9 1485.37  5002.6 1485.54
  5014.9 1483.47  5015.1 1482.97  5018.9 1483.47  5023.4 1485.38  5031.2 1486.07
  5071.9 1487.84  5101.5 1490.97  5109.3 1490.45  5137.9 1492.16  5187.4 1493.95
  5222.5 1494.18  5255.9 1495.78  5300.6 1498.44  5353.4 1504.99  5385.9 1507.22
#Mann=6,-1,0
  4695.4    0.07       0  4861.3   0.035       0  5014.9   0.035       0
  5018.9   0.035       0  5071.9    0.07       0  5255.9    0.12       0
Bank Sta=5014.9,5018.9
Exp/Cntr=0.3,0.1

Type RM Length L Ch R = 1,476,0,0,0
BEGIN DESCRIPTION:
Stream0054_DS 1.0
END DESCRIPTION:
XS GIS Cut Line= 3
      2007692.51     13910977.69      2007625.00     13910975.00
      2007050.15     13910863.10
#Sta/Elev= 30
  4928.0 1485.62  4964.3 1485.50  4998.1 1484.55  5005.7 1481.88  5019.4 1473.57
  5019.6 1473.07  5023.1 1473.07  5023.4 1473.57  5026.5 1475.20  5036.3 1474.86
  5046.5 1476.27  5062.5 1476.85  5073.0 1477.87  5078.1 1476.41  5124.7 1479.64
  5129.7 1479.24  5163.5 1481.52  5263.3 1485.01  5341.9 1487.24  5387.9 1490.95
  5423.4 1492.23  5439.6 1493.37  5464.2 1494.15  5484.6 1494.00  5491.2 1494.53
  5498.7 1496.62  5525.3 1499.41  5542.9 1501.90  5576.2 1504.96  5581.2 1504.96
#Mann=8,-1,0
  4928.0    0.07       0  4964.3    0.12       0  5019.4    0.05       0
  5023.4    0.12       0  5062.5    0.07       0  5163.5    0.12       0
  5263.3    0.07       0  5498.7    0.12       0
Bank Sta=5019.4,5023.4
Exp/Cntr=0.3,0.1

Chan Stop Cuts=-1