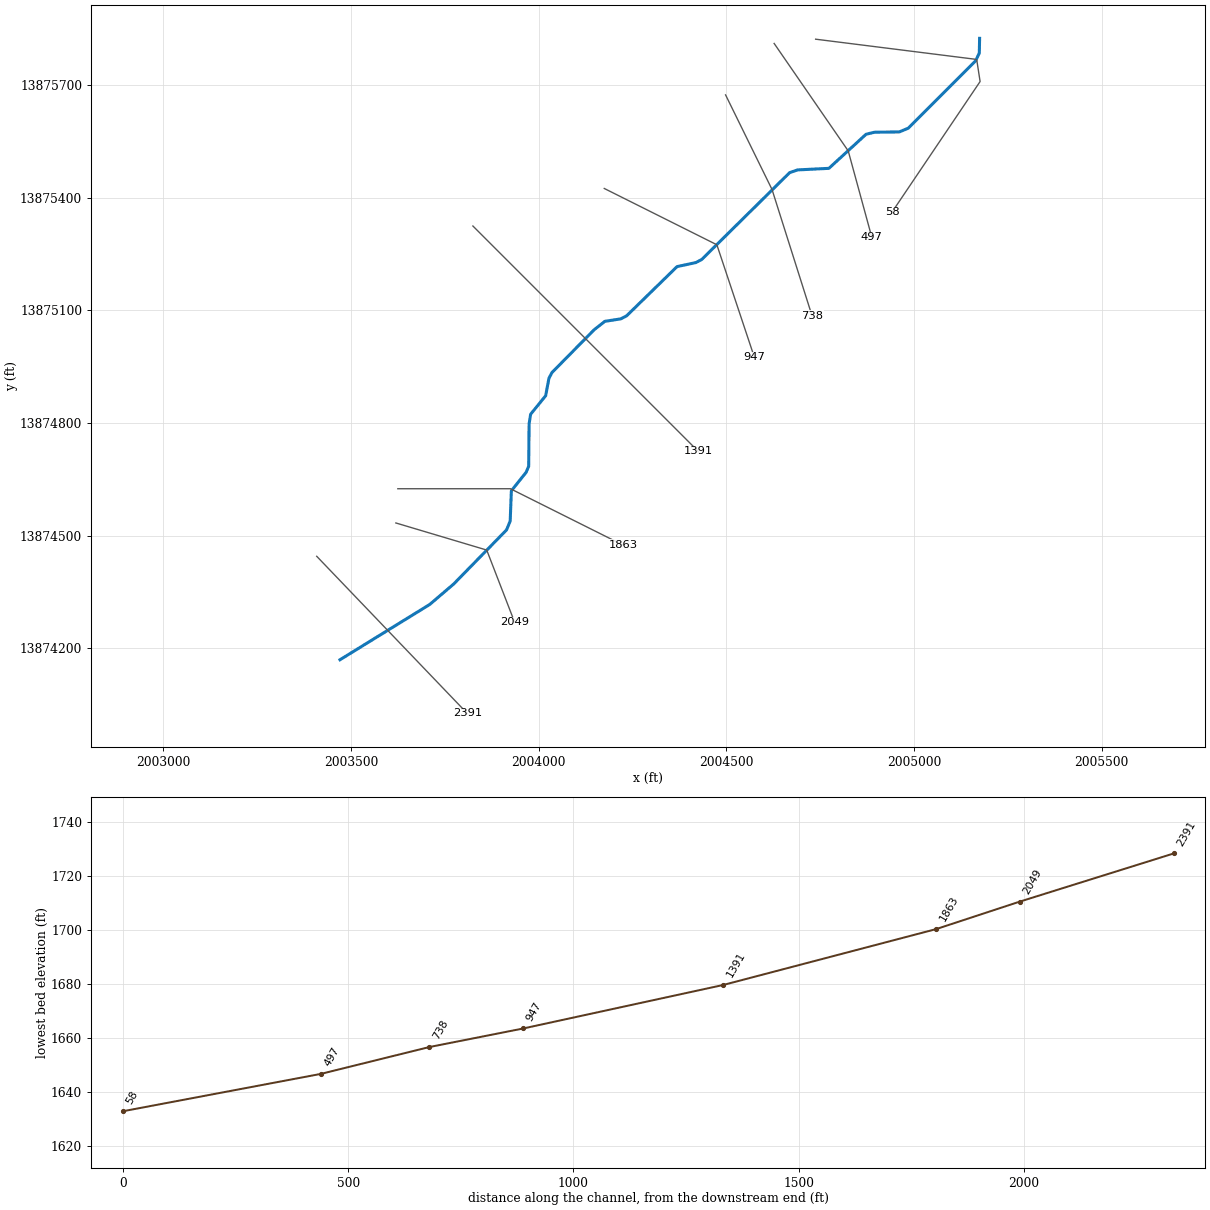
--- Stream0055_DS.prj (project) ---

Proj Title=Stream0055_DS Base Level Engineering
Current Plan=p01
Default Exp/Contr=0.3,0.1
English Units
Geom File=g01
Flow File=f01
Plan File=p01
BEGIN DESCRIPTION:
Stream0055_DS
END DESCRIPTION:

--- Stream0055_DS.p01 (plan) ---

Plan Title=Multiple Run
Short Identifier=Multiple
Geom File=g01
Flow File=f01
Subcritical Flow
K Sum by GR= 0
Std Step Tol= 0.01
Critical Tol= 0.01
Num of Std Step Trials= 20
Max Error Tol= 0.3
Flow Tol Ratio= 0.001
Split Flow NTrial= 30
Split Flow Tol= 0.02
Split Flow Ratio= 0.02
Log Output Level= 0
Friction Slope Method= 1
Unsteady Friction Slope Method= 2
Unsteady Bridges Friction Slope Method= 1
Parabolic Critical Depth
Global Vel Dist=  1 , 1 , 1
Global Log Level= 0
CheckData=True
Encroach Param= -1, 0, 0, 0
BEGIN DESCRIPTION:
Multiple Run
END DESCRIPTION:

--- Stream0055_DS.f01 (steady flow) ---

Flow Title=Multiple
Number of Profiles=7
Profile Names=10-year,25-year,50-year,1pct_min,100-year,1pct_plu,500-year
River Rch & RM= Stream0055_DS,Reach-1,2391
     370     593     794     519    1036    2067    1737
River Rch & RM= Stream0055_DS,Reach-1,58
    1249    2157    3035    2071    4132    8245    7579
Boundary for River Rch & Prof#=Stream0055_DS,Reach-1,1
Up Type=0
Dn Type=3
Dn Slope=0.005
Boundary for River Rch & Prof#=Stream0055_DS,Reach-1,2
Up Type=0
Dn Type=3
Dn Slope=0.005
Boundary for River Rch & Prof#=Stream0055_DS,Reach-1,3
Up Type=0
Dn Type=3
Dn Slope=0.005
Boundary for River Rch & Prof#=Stream0055_DS,Reach-1,4
Up Type=0
Dn Type=3
Dn Slope=0.005
Boundary for River Rch & Prof#=Stream0055_DS,Reach-1,5
Up Type=0
Dn Type=3
Dn Slope=0.005
Boundary for River Rch & Prof#=Stream0055_DS,Reach-1,6
Up Type=0
Dn Type=3
Dn Slope=0.005
Boundary for River Rch & Prof#=Stream0055_DS,Reach-1,7
Up Type=0
Dn Type=3
Dn Slope=0.005

--- Stream0055_DS.g01 (geometry) ---

Geom Title=Existing Conditions

River Reach=Stream0055_DS,Reach-1
Reach XY= 30
      2003470.95     13874169.41      2003710.02     13874316.67
      2003773.81     13874371.16      2003914.57     13874515.18
      2003924.35     13874538.91      2003927.47     13874619.43
      2003966.86     13874668.94      2003973.61     13874684.67
      2003974.74     13874797.84      2003978.76     13874823.44
      2004018.86     13874872.83      2004027.61     13874919.38
      2004035.76     13874934.68      2004148.18     13875048.70
      2004176.65     13875071.02      2004218.95     13875077.54
      2004234.68     13875085.78      2004368.95     13875216.84
      2004418.95     13875227.53      2004434.68     13875235.78
      2004668.83     13875467.14      2004690.22     13875474.47
      2004773.50     13875478.63      2004872.58     13875569.46
      2004895.06     13875574.86      2004961.09     13875575.67
      2004984.79     13875585.52      2005164.49     13875765.21
      2005174.25     13875785.76      2005175.00     13875825.00

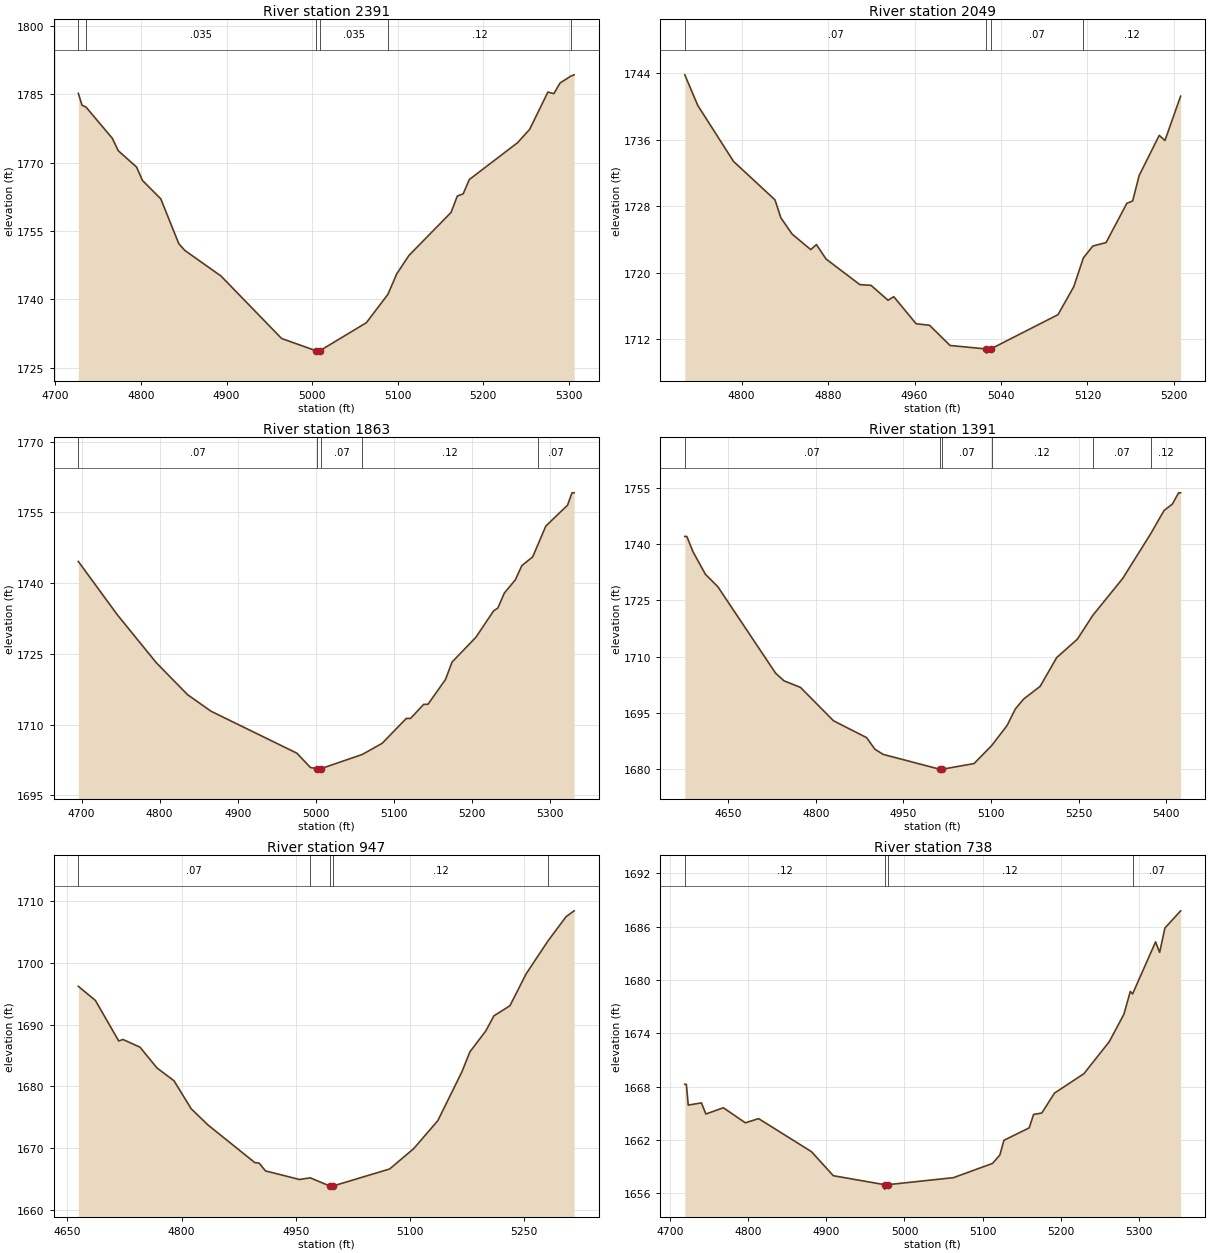
Type RM Length L Ch R = 1,2391,342,342,342
BEGIN DESCRIPTION:
Stream0055_DS 6.0
END DESCRIPTION:
XS GIS Cut Line= 2
      2003408.91     13874445.00      2003809.89     13874026.49
#Sta/Elev= 30
  4726.7 1785.17  4731.0 1782.56  4735.7 1782.15  4766.5 1775.29  4773.4 1772.58
  4794.8 1769.00  4801.7 1766.06  4823.1 1762.03  4844.2 1752.18  4851.3 1750.71
  4893.5 1745.11  4964.3 1731.42  5004.8 1728.71  5005.0 1728.21  5008.8 1728.71
  5063.4 1734.88  5088.6 1741.10  5098.9 1745.59  5113.1 1749.61  5162.4 1759.05
  5169.7 1762.64  5176.6 1763.14  5183.7 1766.26  5240.1 1774.33  5254.3 1777.28
  5275.6 1785.44  5282.6 1785.09  5289.8 1787.43  5302.6 1788.96  5306.3 1789.22
#Mann=6,-1,0
  4726.7    0.07       0  4735.7   0.035       0  5004.8   0.035       0
  5008.8   0.035       0  5088.6    0.12       0  5302.6    0.07       0
Bank Sta=5004.8,5008.8
Exp/Cntr=0.3,0.1

Type RM Length L Ch R = 1,2049,186,186,186
BEGIN DESCRIPTION:
Stream0055_DS 5.0
END DESCRIPTION:
XS GIS Cut Line= 3
      2003619.79     13874533.80      2003861.85     13874461.59
      2003936.24     13874269.17
#Sta/Elev= 30
  4747.4 1743.79  4759.4 1740.12  4792.5 1733.39  4830.9 1728.77  4836.3 1726.62
  4846.8 1724.65  4864.0 1722.79  4869.2 1723.40  4878.1 1721.67  4909.4 1718.59
  4919.8 1718.50  4935.5 1716.71  4940.8 1717.14  4961.5 1713.89  4973.9 1713.71
  4992.9 1711.28  5026.5 1710.86  5026.8 1710.36  5030.5 1710.86  5092.8 1714.98
  5107.4 1718.34  5116.3 1721.80  5125.0 1723.22  5137.3 1723.64  5156.5 1728.35
  5161.9 1728.64  5167.9 1731.69  5186.5 1736.52  5191.8 1735.90  5206.3 1741.23
#Mann=4,-1,0
  4747.4    0.07       0  5026.5    0.05       0  5030.5    0.07       0
  5116.3    0.12       0
Bank Sta=5026.5,5030.5
Exp/Cntr=0.3,0.1

Type RM Length L Ch R = 1,1863,472,472,472
BEGIN DESCRIPTION:
Stream0055_DS 4.0
END DESCRIPTION:
XS GIS Cut Line= 3
      2003625.00     13874625.00      2003925.00     13874625.00
      2004224.99     13874475.00
#Sta/Elev= 30
  4695.8 1744.60  4745.8 1733.29  4795.8 1723.12  4835.8 1716.36  4865.8 1712.86
  4975.8 1703.97  4993.3 1700.92  5002.2 1700.66  5002.4 1700.16  5006.2 1700.66
  5059.7 1703.69  5085.2 1706.06  5116.0 1711.32  5121.6 1711.34  5138.3 1714.30
  5143.9 1714.33  5166.3 1719.58  5174.7 1723.27  5205.4 1728.55  5227.8 1734.09
  5233.4 1734.73  5241.8 1737.92  5255.7 1740.67  5264.1 1743.70  5278.1 1745.58
  5285.1 1748.30  5294.9 1752.10  5322.8 1756.54  5328.4 1759.14  5331.2 1759.14
#Mann=5,-1,0
  4695.8    0.07       0  5002.2    0.05       0  5006.2    0.07       0
  5059.7    0.12       0  5285.1    0.07       0
Bank Sta=5002.2,5006.2
Exp/Cntr=0.3,0.1

Type RM Length L Ch R = 1,1391,444,444,444
BEGIN DESCRIPTION:
Stream0055_DS 3.0
END DESCRIPTION:
XS GIS Cut Line= 3
      2003825.02     13875324.98      2004125.00     13875025.00
      2004425.00     13874725.00
#Sta/Elev= 30
  4576.0 1741.99  4579.5 1741.99  4590.1 1737.91  4611.3 1731.92  4632.5 1728.62
  4731.5 1705.56  4745.7 1703.55  4774.0 1701.79  4830.5 1692.90  4887.1 1688.42
  4901.2 1685.35  4915.4 1683.95  5012.4 1679.99  5012.6 1679.49  5016.4 1679.99
  5071.0 1681.51  5100.9 1686.25  5127.5 1691.64  5141.7 1696.06  5155.8 1698.69
  5184.1 1702.07  5212.4 1709.73  5247.7 1714.62  5274.3 1721.00  5325.5 1730.84
  5373.4 1742.75  5396.2 1748.93  5410.4 1750.62  5421.0 1753.62  5424.5 1753.62
#Mann=6,-1,0
  4576.0    0.07       0  5012.4    0.05       0  5016.4    0.07       0
  5100.9    0.12       0  5274.3    0.07       0  5373.4    0.12       0
Bank Sta=5012.4,5016.4
Exp/Cntr=0.3,0.1

Type RM Length L Ch R = 1,947,209,209,209
BEGIN DESCRIPTION:
Stream0055_DS 2.0
END DESCRIPTION:
XS GIS Cut Line= 3
      2004174.98     13875425.01      2004475.00     13875275.00
      2004575.01     13874974.96
#Sta/Elev= 30
  4664.3 1696.18  4686.7 1693.90  4717.4 1687.34  4723.0 1687.58  4745.4 1686.33
  4767.7 1682.97  4790.1 1680.90  4812.5 1676.39  4834.8 1673.74  4896.3 1667.66
  4901.9 1667.59  4910.3 1666.32  4955.0 1664.93  4969.1 1665.20  4994.9 1663.87
  4995.2 1663.37  4998.7 1663.37  4998.9 1663.87  5073.5 1666.63  5105.1 1669.92
  5136.8 1674.45  5168.4 1682.33  5178.9 1685.56  5200.0 1688.99  5210.5 1691.40
  5231.6 1693.04  5252.7 1698.16  5281.6 1703.52  5305.4 1707.45  5316.0 1708.39
#Mann=5,-1,0
  4664.3    0.07       0  4969.1    0.12       0  4994.9    0.05       0
  4998.9    0.12       0  5281.6    0.07       0
Bank Sta=4994.9,4998.9
Exp/Cntr=0.3,0.1

Type RM Length L Ch R = 1,738,241,241,241
BEGIN DESCRIPTION:
Stream0055_DS 1.5
END DESCRIPTION:
XS GIS Cut Line= 3
      2004498.24     13875674.26      2004621.95     13875422.29
      2004728.52     13875085.86
#Sta/Elev= 30
  4719.3 1668.26  4721.3 1668.26  4723.7 1665.92  4740.6 1666.17  4746.2 1664.92
  4768.6 1665.62  4796.7 1663.93  4813.6 1664.40  4881.1 1660.69  4909.1 1657.98
  4974.6 1656.97  4974.8 1656.47  4978.6 1656.97  5062.6 1657.76  5112.5 1659.36
  5121.9 1660.31  5127.1 1661.96  5159.4 1663.36  5165.0 1664.87  5175.5 1665.03
  5191.7 1667.27  5229.3 1669.45  5261.6 1673.04  5280.4 1676.13  5288.6 1678.71
  5291.5 1678.42  5320.9 1684.28  5326.1 1683.09  5332.8 1685.83  5352.9 1687.77
#Mann=4,-1,0
  4719.3    0.12       0  4974.6    0.05       0  4978.6    0.12       0
  5291.5    0.07       0
Bank Sta=4974.6,4978.6
Exp/Cntr=0.3,0.1

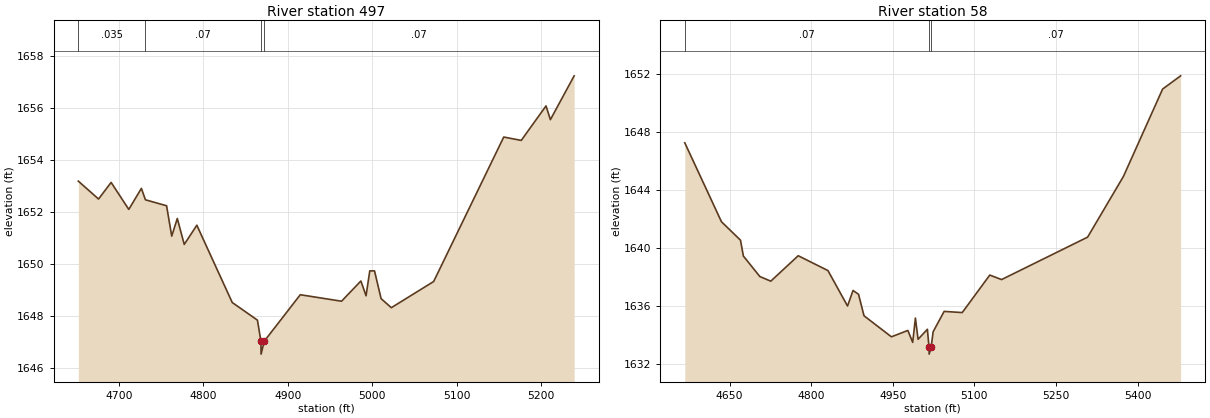
Type RM Length L Ch R = 1,497,439,439,439
BEGIN DESCRIPTION:
Stream0055_DS 1.0
END DESCRIPTION:
XS GIS Cut Line= 3
      2004627.62     13875811.38      2004825.00     13875525.00
      2004887.91     13875294.65
#Sta/Elev= 30
  4652.2 1653.19  4676.1 1652.50  4691.0 1653.14  4711.9 1652.10  4726.8 1652.91
  4731.6 1652.47  4756.6 1652.24  4762.7 1651.07  4769.3 1651.75  4777.5 1650.75
  4792.4 1651.49  4834.3 1648.51  4864.1 1647.83  4868.2 1647.02  4868.4 1646.52
  4872.2 1647.02  4914.8 1648.81  4963.6 1648.56  4986.5 1649.34  4992.6 1648.77
  4997.0 1649.73  5002.6 1649.73  5010.4 1648.66  5022.5 1648.31  5072.6 1649.32
  5155.5 1654.89  5176.2 1654.76  5205.5 1656.09  5210.7 1655.56  5238.8 1657.25
#Mann=4,-1,0
  4652.2   0.035       0  4731.6    0.07       0  4868.2    0.05       0
  4872.2    0.07       0
Bank Sta=4868.2,4872.2
Exp/Cntr=0.3,0.1

Type RM Length L Ch R = 1,58,0,0,0
BEGIN DESCRIPTION:
Stream0055_DS 0.0
END DESCRIPTION:
XS GIS Cut Line= 4
      2004738.11     13875822.73      2005167.24     13875768.79
      2005176.35     13875709.92      2004941.76     13875362.11
#Sta/Elev= 30
  4567.5 1647.24  4634.9 1641.81  4669.9 1640.54  4675.2 1639.45  4705.5 1638.04
  4725.6 1637.72  4776.0 1639.47  4830.7 1638.45  4866.7 1636.01  4876.8 1637.08
  4886.9 1636.82  4897.0 1635.34  4947.4 1633.89  4977.6 1634.33  4986.5 1633.51
  4991.5 1635.18  4996.4 1633.72  5013.5 1634.41  5016.5 1633.20  5016.8 1632.70
  5020.5 1633.20  5024.1 1634.24  5044.3 1635.64  5077.6 1635.56  5128.2 1638.14
  5149.9 1637.83  5308.1 1640.75  5374.0 1644.93  5446.0 1650.94  5479.1 1651.85
#Mann=3,-1,0
  4567.5    0.07       0  5016.5    0.05       0  5020.5    0.07       0
Bank Sta=5016.5,5020.5
Exp/Cntr=0.3,0.1

Chan Stop Cuts=-1