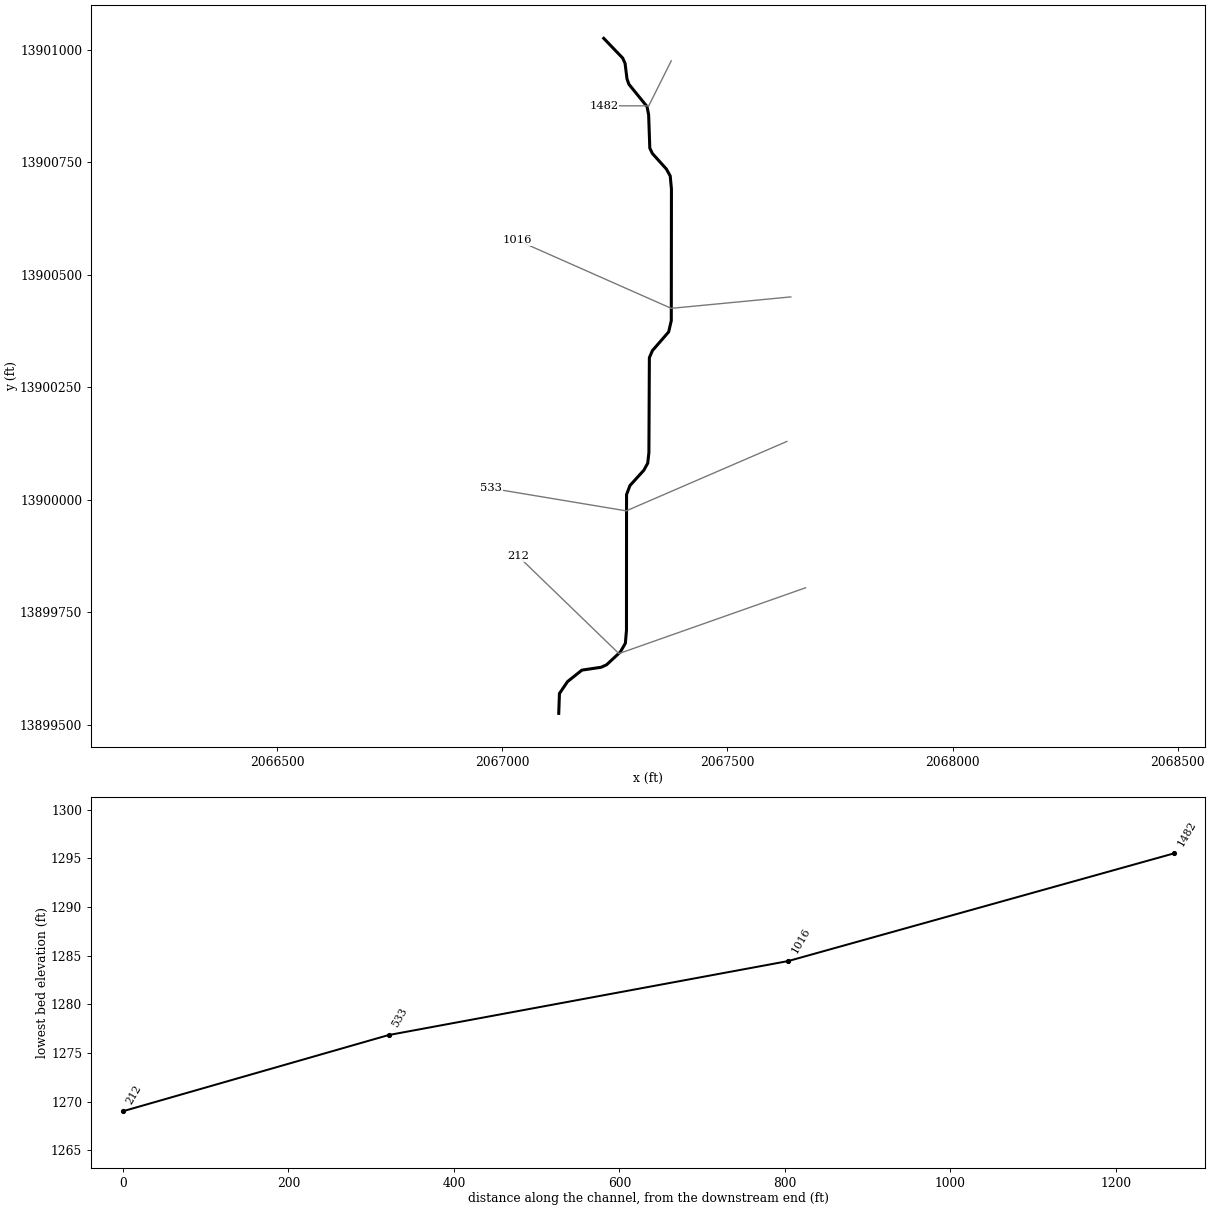
--- Stream0056_DS.prj (project) ---

Proj Title=Stream0056_DS Base Level Engineering
Current Plan=p01
Default Exp/Contr=0.3,0.1
English Units
Geom File=g01
Flow File=f01
Plan File=p01
BEGIN DESCRIPTION:
Stream0056_DS
END DESCRIPTION:

--- Stream0056_DS.p01 (plan) ---

Plan Title=Multiple Run
Short Identifier=Multiple
Geom File=g01
Flow File=f01
Subcritical Flow
K Sum by GR= 0
Std Step Tol= 0.01
Critical Tol= 0.01
Num of Std Step Trials= 20
Max Error Tol= 0.3
Flow Tol Ratio= 0.001
Split Flow NTrial= 30
Split Flow Tol= 0.02
Split Flow Ratio= 0.02
Log Output Level= 0
Friction Slope Method= 1
Unsteady Friction Slope Method= 2
Unsteady Bridges Friction Slope Method= 1
Parabolic Critical Depth
Global Vel Dist=  1 , 1 , 1
Global Log Level= 0
CheckData=True
Encroach Param= -1, 0, 0, 0
BEGIN DESCRIPTION:
Multiple Run
END DESCRIPTION:

--- Stream0056_DS.f01 (steady flow) ---

Flow Title=Multiple
Number of Profiles=7
Profile Names=10-year,25-year,50-year,1pct_min,100-year,1pct_plu,500-year
River Rch & RM= Stream0056_DS,Reach-1,1482
     627    1028    1398     925    1845    3682    3172
Boundary for River Rch & Prof#=Stream0056_DS,Reach-1,1
Up Type=0
Dn Type=3
Dn Slope=0.005
Boundary for River Rch & Prof#=Stream0056_DS,Reach-1,2
Up Type=0
Dn Type=3
Dn Slope=0.005
Boundary for River Rch & Prof#=Stream0056_DS,Reach-1,3
Up Type=0
Dn Type=3
Dn Slope=0.005
Boundary for River Rch & Prof#=Stream0056_DS,Reach-1,4
Up Type=0
Dn Type=3
Dn Slope=0.005
Boundary for River Rch & Prof#=Stream0056_DS,Reach-1,5
Up Type=0
Dn Type=3
Dn Slope=0.005
Boundary for River Rch & Prof#=Stream0056_DS,Reach-1,6
Up Type=0
Dn Type=3
Dn Slope=0.005
Boundary for River Rch & Prof#=Stream0056_DS,Reach-1,7
Up Type=0
Dn Type=3
Dn Slope=0.005

--- Stream0056_DS.g01 (geometry) ---

Geom Title=Existing Conditions

River Reach=Stream0056_DS,Reach-1
Reach XY= 30
      2067225.00     13901025.00      2067267.09     13900981.15
      2067272.39     13900969.37      2067276.68     13900934.79
      2067281.03     13900922.78      2067321.18     13900873.42
      2067324.77     13900854.91      2067327.36     13900780.98
      2067333.19     13900768.97      2067364.15     13900734.65
      2067372.74     13900719.06      2067375.43     13900690.18
      2067375.09     13900397.69      2067369.25     13900372.67
      2067333.14     13900331.06      2067326.38     13900315.34
      2067325.36     13900104.85      2067322.74     13900080.94
      2067314.15     13900065.35      2067283.14     13900031.06
      2067275.68     13900011.08      2067275.51     13899709.74
      2067273.02     13899680.67      2067261.78     13899661.33
      2067231.38     13899633.01      2067219.15     13899627.43
      2067176.50     13899621.12      2067144.56     13899595.63
      2067126.56     13899569.13      2067125.00     13899525.00

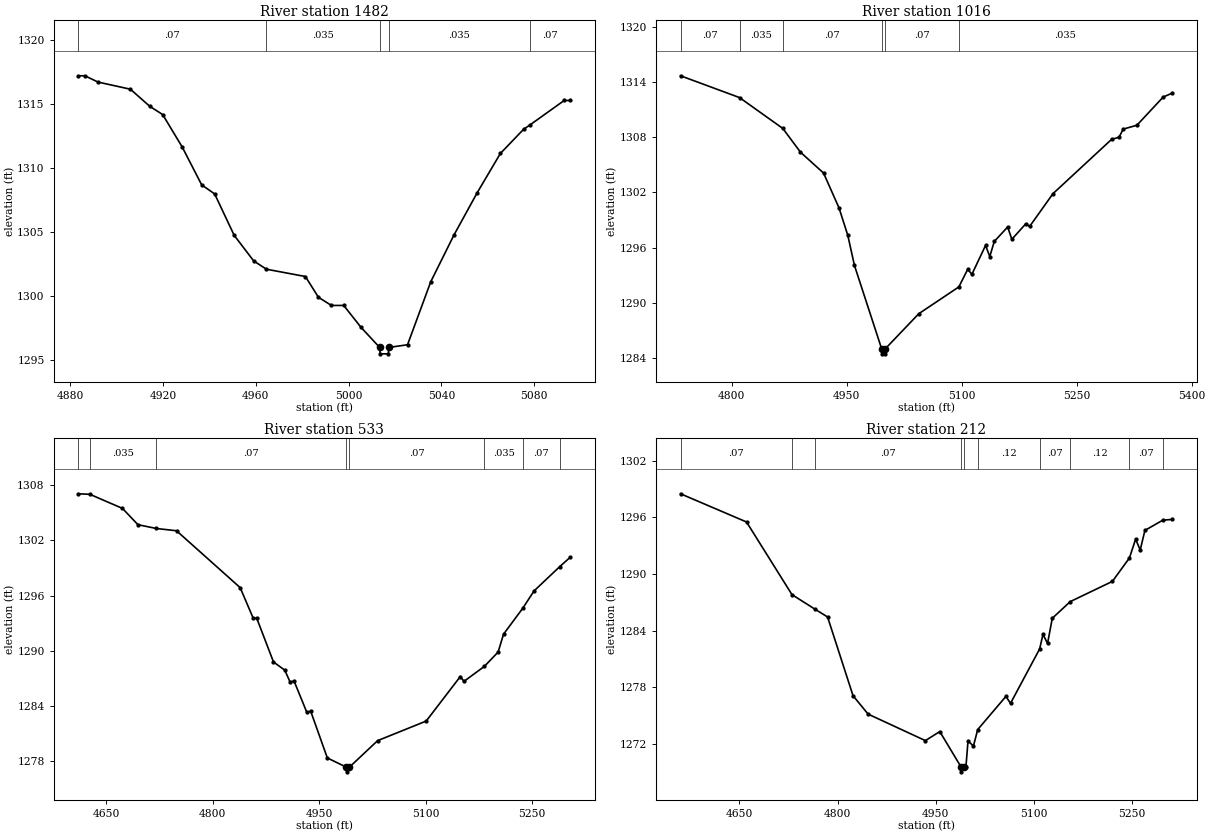
Type RM Length L Ch R = 1,1482,466,466,466
BEGIN DESCRIPTION:
Stream0056_DS 3.0
END DESCRIPTION:
XS GIS Cut Line= 3
      2067375.00     13900975.00      2067325.00     13900875.00
      2067225.00     13900875.00
#Sta/Elev= 30
  4883.6 1317.22  4886.4 1317.22  4892.0 1316.73  4906.0 1316.17  4914.3 1314.84
  4919.9 1314.19  4928.3 1311.66  4936.7 1308.70  4942.3 1307.99  4950.7 1304.76
  4959.1 1302.76  4964.6 1302.11  4981.4 1301.54  4987.0 1299.92  4992.6 1299.28
  4997.9 1299.28  5005.4 1297.56  5013.4 1296.00  5013.6 1295.50  5017.1 1295.50
  5017.4 1296.00  5025.4 1296.21  5035.4 1301.13  5045.4 1304.78  5055.4 1308.08
  5065.4 1311.15  5075.4 1313.04  5078.0 1313.36  5092.9 1315.29  5095.4 1315.29
#Mann=5,-1,0
  4883.6    0.07       0  4964.6   0.035       0  5013.4   0.035       0
  5017.4   0.035       0  5078.0    0.07       0
Bank Sta=5013.4,5017.4
Exp/Cntr=0.3,0.1

Type RM Length L Ch R = 1,1016,483,483,483
BEGIN DESCRIPTION:
Stream0056_DS 2.0
END DESCRIPTION:
XS GIS Cut Line= 3
      2067640.68     13900450.46      2067375.00     13900425.00
      2067032.98     13900576.34
#Sta/Elev= 30
  4733.5 1314.69  4810.4 1312.32  4866.9 1308.96  4889.9 1306.38  4920.0 1304.11
  4940.1 1300.33  4951.6 1297.34  4960.2 1294.08  4995.9 1284.95  4996.1 1284.45
  4999.6 1284.45  4999.9 1284.95  5044.1 1288.81  5096.4 1291.73  5107.9 1293.64
  5113.4 1293.10  5131.2 1296.24  5136.7 1295.03  5142.6 1296.68  5160.0 1298.24
  5165.5 1296.91  5183.3 1298.56  5188.8 1298.32  5219.1 1301.87  5295.6 1307.78
  5305.2 1308.00  5310.7 1308.89  5328.5 1309.31  5362.7 1312.37  5374.4 1312.80
#Mann=6,-1,0
  4733.5    0.07       0  4810.4   0.035       0  4866.9    0.07       0
  4995.9    0.05       0  4999.9    0.07       0  5096.4   0.035       0
Bank Sta=4995.9,4999.9
Exp/Cntr=0.3,0.1

Type RM Length L Ch R = 1,533,321,321,321
BEGIN DESCRIPTION:
Stream0056_DS 1.0
END DESCRIPTION:
XS GIS Cut Line= 3
      2067631.99     13900129.29      2067275.00     13899975.00
      2066975.04     13900024.99
#Sta/Elev= 30
  4610.7 1307.07  4626.9 1307.01  4672.8 1305.48  4694.6 1303.71  4720.4 1303.30
  4749.0 1303.05  4838.7 1296.87  4856.7 1293.62  4862.2 1293.52  4885.7 1288.79
  4901.6 1287.90  4909.2 1286.59  4914.6 1286.74  4932.7 1283.31  4938.1 1283.45
  4961.6 1278.36  4988.6 1277.35  4988.8 1276.85  4992.6 1277.35  5032.5 1280.24
  5101.0 1282.37  5149.1 1287.21  5154.2 1286.68  5183.0 1288.31  5202.4 1289.87
  5210.0 1291.81  5237.1 1294.63  5253.0 1296.51  5289.2 1299.15  5303.7 1300.15
#Mann=8,-1,0
  4610.7    0.07       0  4626.9   0.035       0  4720.4    0.07       0
  4988.6    0.05       0  4992.6    0.07       0  5183.0   0.035       0
  5237.1    0.07       0  5289.2   0.035       0
Bank Sta=4988.6,4992.6
Exp/Cntr=0.3,0.1

Type RM Length L Ch R = 1,212,0,0,0
BEGIN DESCRIPTION:
Stream0056_DS 0.0
END DESCRIPTION:
XS GIS Cut Line= 3
      2067673.50     13899804.10      2067258.73     13899657.86
      2067035.15     13899874.04
#Sta/Elev= 30
  4560.2 1298.51  4661.0 1295.52  4730.4 1287.82  4765.4 1286.28  4784.8 1285.45
  4823.7 1277.10  4846.7 1275.15  4934.2 1272.34  4956.2 1273.30  4988.8 1269.53
  4989.1 1269.03  4992.8 1269.53  4996.1 1269.54  4999.3 1272.30  5007.6 1271.77
  5014.1 1273.51  5057.2 1277.03  5064.2 1276.29  5108.7 1282.06  5113.8 1283.61
  5120.8 1282.64  5128.0 1285.31  5155.5 1287.08  5219.8 1289.22  5245.8 1291.70
  5255.3 1293.70  5262.3 1292.55  5269.5 1294.63  5296.8 1295.71  5311.0 1295.79
#Mann=10,-1,0
  4560.2    0.07       0  4730.4    0.12       0  4765.4    0.07       0
  4988.8    0.05       0  4992.8    0.07       0  5014.1    0.12       0
  5108.7    0.07       0  5155.5    0.12       0  5245.8    0.07       0
  5296.8    0.12       0
Bank Sta=4988.8,4992.8
Exp/Cntr=0.3,0.1

Chan Stop Cuts=-1