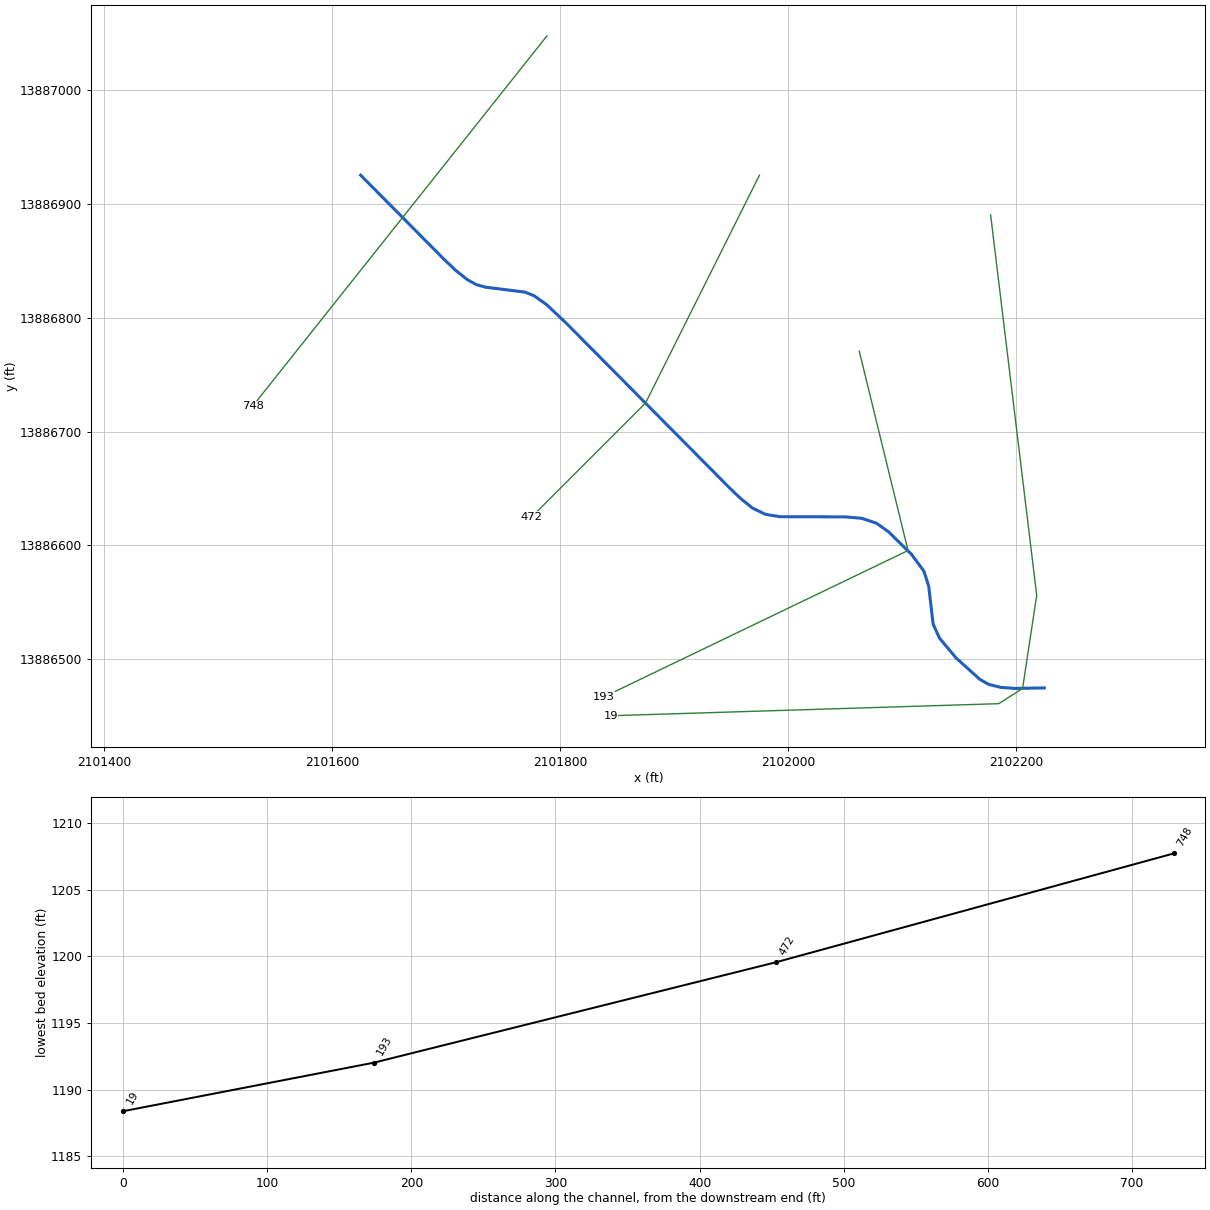
--- Stream0057_DS.prj (project) ---

Proj Title=Stream0057_DS Base Level Engineering
Current Plan=p01
Default Exp/Contr=0.3,0.1
English Units
Geom File=g01
Flow File=f01
Plan File=p01
BEGIN DESCRIPTION:
Stream0057_DS
END DESCRIPTION:

--- Stream0057_DS.p01 (plan) ---

Plan Title=Multiple Run
Short Identifier=Multiple
Geom File=g01
Flow File=f01
Subcritical Flow
K Sum by GR= 0
Std Step Tol= 0.01
Critical Tol= 0.01
Num of Std Step Trials= 20
Max Error Tol= 0.3
Flow Tol Ratio= 0.001
Split Flow NTrial= 30
Split Flow Tol= 0.02
Split Flow Ratio= 0.02
Log Output Level= 0
Friction Slope Method= 1
Unsteady Friction Slope Method= 2
Unsteady Bridges Friction Slope Method= 1
Parabolic Critical Depth
Global Vel Dist=  1 , 1 , 1
Global Log Level= 0
CheckData=True
Encroach Param= -1, 0, 0, 0
BEGIN DESCRIPTION:
Multiple Run
END DESCRIPTION:

--- Stream0057_DS.f01 (steady flow) ---

Flow Title=Multiple
Number of Profiles=7
Profile Names=10-year,25-year,50-year,1pct_min,100-year,1pct_plu,500-year
River Rch & RM= Stream0057_DS,Reach-1,748
     336     528     699     451     900    1797    1470
River Rch & RM= Stream0057_DS,Reach-1,19
    1069    1815    2527    1708    3408    6799    6124
Boundary for River Rch & Prof#=Stream0057_DS,Reach-1,1
Up Type=0
Dn Type=3
Dn Slope=0.005
Boundary for River Rch & Prof#=Stream0057_DS,Reach-1,2
Up Type=0
Dn Type=3
Dn Slope=0.005
Boundary for River Rch & Prof#=Stream0057_DS,Reach-1,3
Up Type=0
Dn Type=3
Dn Slope=0.005
Boundary for River Rch & Prof#=Stream0057_DS,Reach-1,4
Up Type=0
Dn Type=3
Dn Slope=0.005
Boundary for River Rch & Prof#=Stream0057_DS,Reach-1,5
Up Type=0
Dn Type=3
Dn Slope=0.005
Boundary for River Rch & Prof#=Stream0057_DS,Reach-1,6
Up Type=0
Dn Type=3
Dn Slope=0.005
Boundary for River Rch & Prof#=Stream0057_DS,Reach-1,7
Up Type=0
Dn Type=3
Dn Slope=0.005

--- Stream0057_DS.g01 (geometry) ---

Geom Title=Existing Conditions

River Reach=Stream0057_DS,Reach-1
Reach XY= 30
      2101625.00     13886925.00      2101698.14     13886851.20
      2101708.29     13886841.57      2101718.93     13886833.11
      2101726.64     13886828.95      2101734.79     13886826.70
      2101769.37     13886822.37      2101777.29     13886819.15
      2101788.21     13886811.37      2101805.16     13886795.39
      2101948.13     13886651.18      2101958.25     13886641.46
      2101968.83     13886632.86      2101980.49     13886627.27
      2101993.29     13886625.26      2102050.12     13886625.12
      2102064.67     13886623.90      2102077.67     13886619.58
      2102088.65     13886611.74      2102108.54     13886592.13
      2102119.28     13886577.57      2102123.55     13886564.51
      2102127.47     13886530.95      2102132.99     13886518.72
      2102147.73     13886501.16      2102168.37     13886482.59
      2102176.03     13886478.14      2102186.62     13886475.50
      2102199.51     13886474.54      2102225.00     13886475.00

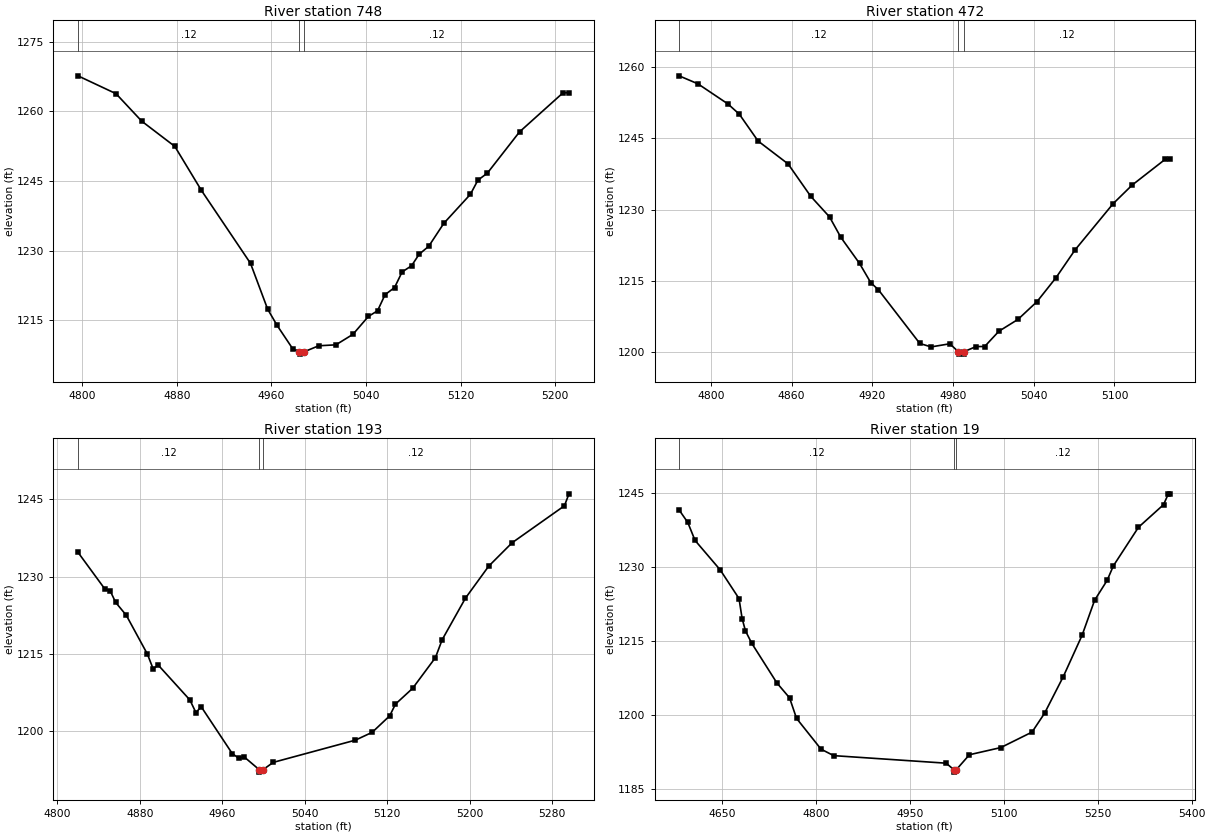
Type RM Length L Ch R = 1,748,276,276,276
BEGIN DESCRIPTION:
Stream0057_DS 2.0
END DESCRIPTION:
XS GIS Cut Line= 2
      2101788.44     13887047.23      2101530.09     13886722.20
#Sta/Elev= 30
  4796.5 1267.65  4828.7 1263.80  4850.4 1257.89  4878.4 1252.45  4900.8 1243.01
  4942.4 1227.27  4956.9 1217.40  4964.9 1213.90  4978.2 1208.83  4983.7 1208.22
  4984.0 1207.72  4987.7 1208.22  5000.1 1209.52  5014.6 1209.72  5029.0 1211.98
  5042.1 1215.84  5049.8 1217.05  5056.2 1220.53  5064.2 1222.05  5070.6 1225.42
  5078.6 1226.75  5085.0 1229.23  5093.1 1230.94  5105.9 1235.90  5128.3 1242.12
  5134.7 1245.18  5142.7 1246.70  5169.9 1255.58  5206.7 1264.00  5211.7 1264.00
#Mann=3,-1,0
  4796.5    0.12       0  4983.7    0.05       0  4987.7    0.12       0
Bank Sta=4983.7,4987.7
Exp/Cntr=0.3,0.1

Type RM Length L Ch R = 1,472,279,279,279
BEGIN DESCRIPTION:
Stream0057_DS 1.0
END DESCRIPTION:
XS GIS Cut Line= 3
      2101974.99     13886924.99      2101875.00     13886725.00
      2101775.01     13886625.01
#Sta/Elev= 30
  4776.4 1258.19  4790.4 1256.50  4812.7 1252.26  4821.1 1250.12  4835.1 1244.45
  4857.4 1239.63  4874.2 1232.82  4888.2 1228.47  4896.6 1224.17  4910.5 1218.67
  4918.9 1214.60  4924.5 1213.13  4955.3 1201.81  4963.7 1201.08  4977.6 1201.74
  4984.0 1200.06  4984.3 1199.56  4987.8 1199.56  4988.0 1200.06  4997.2 1201.16
  5003.5 1201.16  5014.1 1204.38  5028.3 1206.88  5042.4 1210.61  5056.6 1215.68
  5070.7 1221.51  5099.0 1231.25  5113.1 1235.16  5137.9 1240.64  5141.4 1240.64
#Mann=3,-1,0
  4776.4    0.12       0  4984.0    0.05       0  4988.0    0.12       0
Bank Sta=4984,4988
Exp/Cntr=0.3,0.1

Type RM Length L Ch R = 1,193,174,174,174
BEGIN DESCRIPTION:
Stream0057_DS 0.1
END DESCRIPTION:
XS GIS Cut Line= 3
      2102062.63     13886770.51      2102105.41     13886595.57
      2101838.22     13886467.03
#Sta/Elev= 30
  4819.9 1234.71  4846.0 1227.58  4851.1 1227.25  4856.5 1224.98  4866.8 1222.48
  4887.3 1214.94  4892.8 1212.11  4897.9 1212.79  4928.5 1206.05  4934.4 1203.59
  4939.5 1204.73  4969.7 1195.62  4976.0 1194.73  4981.2 1194.99  4995.7 1192.53
  4996.0 1192.03  4999.7 1192.53  5009.4 1193.92  5089.2 1198.24  5105.5 1199.76
  5122.5 1202.96  5128.1 1205.24  5144.7 1208.29  5166.9 1214.27  5173.4 1217.73
  5196.0 1225.80  5218.6 1232.02  5241.3 1236.56  5292.1 1243.74  5296.5 1246.06
#Mann=3,-1,0
  4819.9    0.12       0  4995.7    0.05       0  4999.7    0.12       0
Bank Sta=4995.7,4999.7
Exp/Cntr=0.3,0.1

Type RM Length L Ch R = 1,19,0,0,0
BEGIN DESCRIPTION:
Stream0057_DS 0.0
END DESCRIPTION:
XS GIS Cut Line= 5
      2102177.91     13886890.19      2102218.37     13886556.22
      2102205.96     13886474.47      2102184.98     13886461.15
      2101844.39     13886450.57
#Sta/Elev= 30
  4580.9 1241.48  4594.7 1238.96  4606.3 1235.32  4646.6 1229.34  4676.6 1223.54
  4681.6 1219.47  4686.9 1217.00  4696.9 1214.49  4737.2 1206.44  4757.4 1203.43
  4768.5 1199.28  4807.7 1193.04  4827.9 1191.73  5007.7 1190.20  5019.9 1188.89
  5020.1 1188.39  5023.9 1188.89  5044.8 1191.91  5094.9 1193.36  5144.9 1196.50
  5164.9 1200.31  5194.9 1207.75  5224.9 1216.11  5244.9 1223.20  5264.9 1227.22
  5274.9 1230.17  5315.0 1237.98  5355.0 1242.55  5362.8 1244.75  5365.6 1244.75
#Mann=3,-1,0
  4580.9    0.12       0  5019.9    0.05       0  5023.9    0.12       0
Bank Sta=5019.9,5023.9
Exp/Cntr=0.3,0.1

Chan Stop Cuts=-1