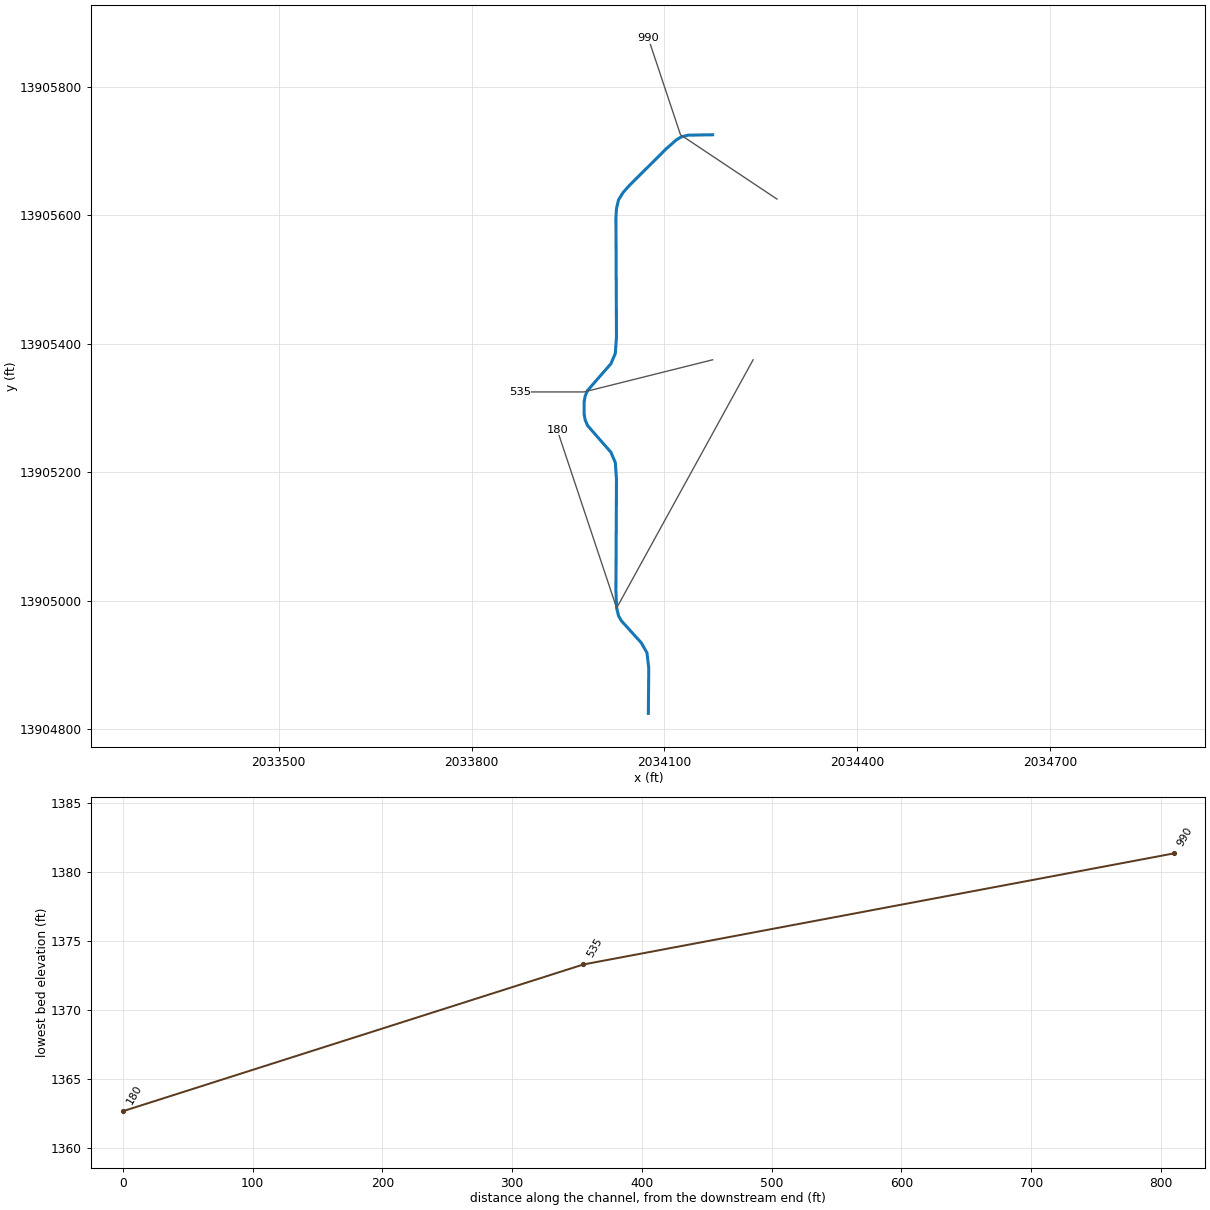
--- Stream0058_DS.prj (project) ---

Proj Title=Stream0058_DS Base Level Engineering
Current Plan=p01
Default Exp/Contr=0.3,0.1
English Units
Geom File=g01
Flow File=f01
Plan File=p01
BEGIN DESCRIPTION:
Stream0058_DS
END DESCRIPTION:

--- Stream0058_DS.p01 (plan) ---

Plan Title=Multiple Run
Short Identifier=Multiple
Geom File=g01
Flow File=f01
Subcritical Flow
K Sum by GR= 0
Std Step Tol= 0.01
Critical Tol= 0.01
Num of Std Step Trials= 20
Max Error Tol= 0.3
Flow Tol Ratio= 0.001
Split Flow NTrial= 30
Split Flow Tol= 0.02
Split Flow Ratio= 0.02
Log Output Level= 0
Friction Slope Method= 1
Unsteady Friction Slope Method= 2
Unsteady Bridges Friction Slope Method= 1
Parabolic Critical Depth
Global Vel Dist=  1 , 1 , 1
Global Log Level= 0
CheckData=True
Encroach Param= -1, 0, 0, 0
BEGIN DESCRIPTION:
Multiple Run
END DESCRIPTION:

--- Stream0058_DS.f01 (steady flow) ---

Flow Title=Multiple
Number of Profiles=7
Profile Names=10-year,25-year,50-year,1pct_min,100-year,1pct_plu,500-year
River Rch & RM= Stream0058_DS,Reach-1,990
     532     868    1178     778    1552    3097    2659
Boundary for River Rch & Prof#=Stream0058_DS,Reach-1,1
Up Type=0
Dn Type=3
Dn Slope=0.005
Boundary for River Rch & Prof#=Stream0058_DS,Reach-1,2
Up Type=0
Dn Type=3
Dn Slope=0.005
Boundary for River Rch & Prof#=Stream0058_DS,Reach-1,3
Up Type=0
Dn Type=3
Dn Slope=0.005
Boundary for River Rch & Prof#=Stream0058_DS,Reach-1,4
Up Type=0
Dn Type=3
Dn Slope=0.005
Boundary for River Rch & Prof#=Stream0058_DS,Reach-1,5
Up Type=0
Dn Type=3
Dn Slope=0.005
Boundary for River Rch & Prof#=Stream0058_DS,Reach-1,6
Up Type=0
Dn Type=3
Dn Slope=0.005
Boundary for River Rch & Prof#=Stream0058_DS,Reach-1,7
Up Type=0
Dn Type=3
Dn Slope=0.005

--- Stream0058_DS.g01 (geometry) ---

Geom Title=Existing Conditions

River Reach=Stream0058_DS,Reach-1
Reach XY= 30
      2034175.00     13905725.00      2034136.83     13905724.41
      2034126.34     13905721.74      2034118.76     13905717.25
      2034101.48     13905701.99      2034044.57     13905645.20
      2034035.45     13905634.83      2034028.52     13905623.55
      2034025.38     13905609.85      2034024.57     13905595.18
      2034025.43     13905411.18      2034023.60     13905384.65
      2034016.81     13905368.92      2033980.38     13905327.18
      2033976.82     13905318.88      2033975.09     13905309.61
      2033975.09     13905290.39      2033976.82     13905281.12
      2033980.38     13905272.82      2034016.81     13905231.08
      2034023.60     13905215.35      2034025.43     13905188.82
      2034024.55     13905015.72      2034025.67     13904988.91
      2034028.75     13904976.55      2034033.10     13904968.93
      2034064.14     13904934.64      2034072.90     13904919.13
      2034075.63     13904895.26      2034075.00     13904825.00

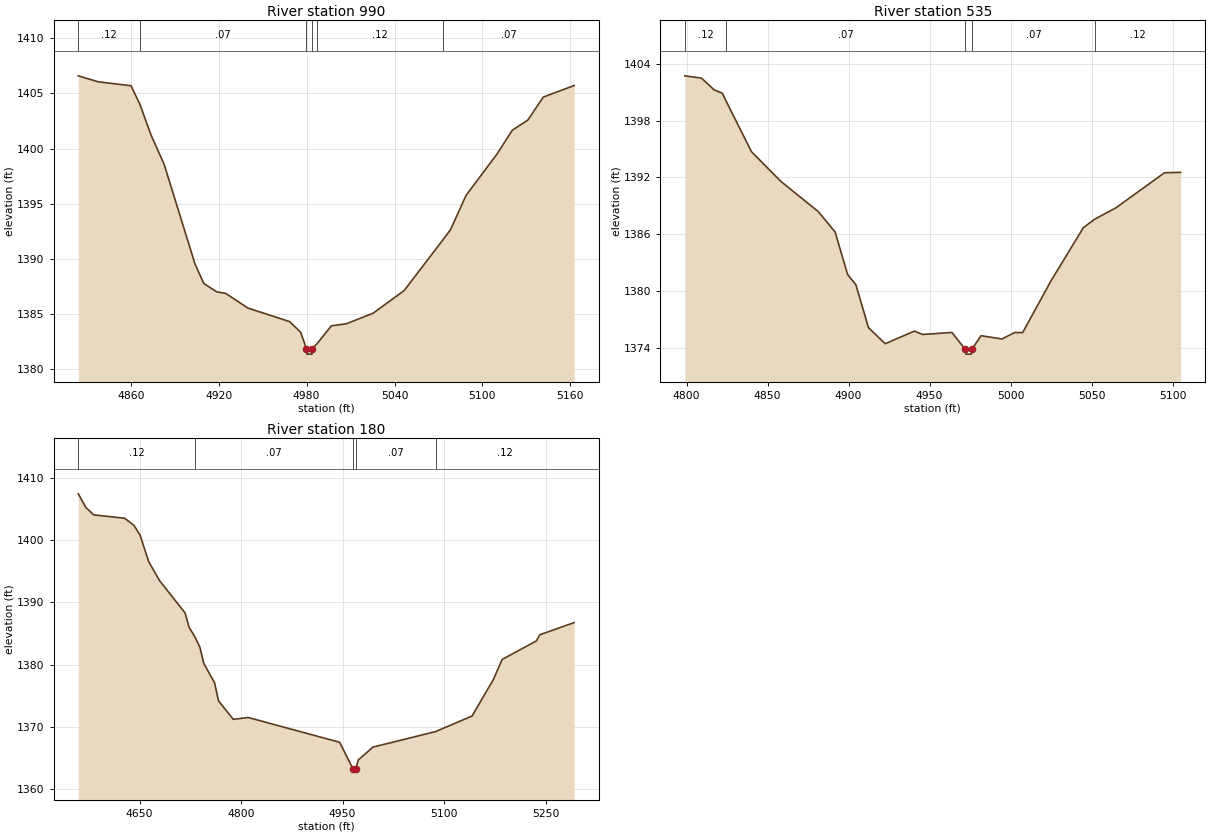
Type RM Length L Ch R = 1,990,455,455,455
BEGIN DESCRIPTION:
Stream0058_DS 2.0
END DESCRIPTION:
XS GIS Cut Line= 3
      2034274.99     13905625.01      2034125.00     13905725.00
      2034074.99     13905875.02
#Sta/Elev= 30
  4824.2 1406.60  4837.7 1406.06  4860.2 1405.70  4866.3 1403.99  4873.8 1401.24
  4882.8 1398.56  4903.8 1389.55  4909.8 1387.77  4918.8 1387.00  4924.8 1386.87
  4939.9 1385.54  4968.4 1384.31  4975.9 1383.35  4979.9 1381.86  4980.2 1381.36
  4983.7 1381.36  4983.9 1381.86  4987.3 1382.33  4996.9 1383.93  5007.1 1384.11
  5025.5 1385.08  5046.6 1387.13  5073.0 1391.72  5078.2 1392.64  5088.8 1395.75
  5109.9 1399.50  5120.4 1401.67  5131.0 1402.59  5141.5 1404.67  5162.6 1405.72
#Mann=6,-1,0
  4824.2    0.12       0  4866.3    0.07       0  4979.9    0.05       0
  4983.9    0.07       0  4987.3    0.12       0  5073.0    0.07       0
Bank Sta=4979.9,4983.9
Exp/Cntr=0.3,0.1

Type RM Length L Ch R = 1,535,355,355,355
BEGIN DESCRIPTION:
Stream0058_DS 1.0
END DESCRIPTION:
XS GIS Cut Line= 3
      2034174.98     13905375.00      2033975.00     13905325.00
      2033875.04     13905325.00
#Sta/Elev= 30
  4798.9 1402.73  4809.2 1402.49  4816.9 1401.26  4822.1 1400.89  4824.6 1399.99
  4840.1 1394.70  4858.2 1391.57  4881.3 1388.38  4891.7 1386.22  4899.4 1381.73
  4904.5 1380.65  4912.3 1376.11  4922.6 1374.41  4940.6 1375.74  4945.8 1375.39
  4963.8 1375.60  4972.1 1373.81  4972.4 1373.31  4975.9 1373.31  4976.1 1373.81
  4981.8 1375.26  4994.7 1374.91  5002.5 1375.59  5007.5 1375.59  5025.0 1381.06
  5045.0 1386.69  5052.1 1387.59  5065.0 1388.77  5095.0 1392.48  5105.0 1392.53
#Mann=5,-1,0
  4798.9    0.12       0  4824.6    0.07       0  4972.1    0.05       0
  4976.1    0.07       0  5052.1    0.12       0
Bank Sta=4972.1,4976.1
Exp/Cntr=0.3,0.1

Type RM Length L Ch R = 1,180,0,0,0
BEGIN DESCRIPTION:
Stream0058_DS 0.0
END DESCRIPTION:
XS GIS Cut Line= 3
      2034237.92     13905374.91      2034025.67     13904988.91
      2033933.25     13905266.01
#Sta/Elev= 30
  4559.5 1407.50  4570.5 1405.32  4582.2 1404.11  4627.9 1403.57  4641.6 1402.43
  4650.7 1400.86  4663.4 1396.60  4679.5 1393.52  4717.3 1388.30  4723.0 1386.05
  4732.4 1384.31  4739.1 1382.80  4744.8 1380.20  4760.9 1377.04  4766.6 1374.17
  4788.4 1371.17  4810.5 1371.47  4945.6 1367.48  4965.4 1363.17  4965.6 1362.67
  4969.4 1363.17  4973.1 1364.63  4994.9 1366.70  5087.3 1369.20  5141.3 1371.71
  5172.9 1377.62  5185.6 1380.82  5236.1 1383.79  5241.4 1384.80  5292.1 1386.76
#Mann=5,-1,0
  4559.5    0.12       0  4732.4    0.07       0  4965.4    0.05       0
  4969.4    0.07       0  5087.3    0.12       0
Bank Sta=4965.4,4969.4
Exp/Cntr=0.3,0.1

Chan Stop Cuts=-1