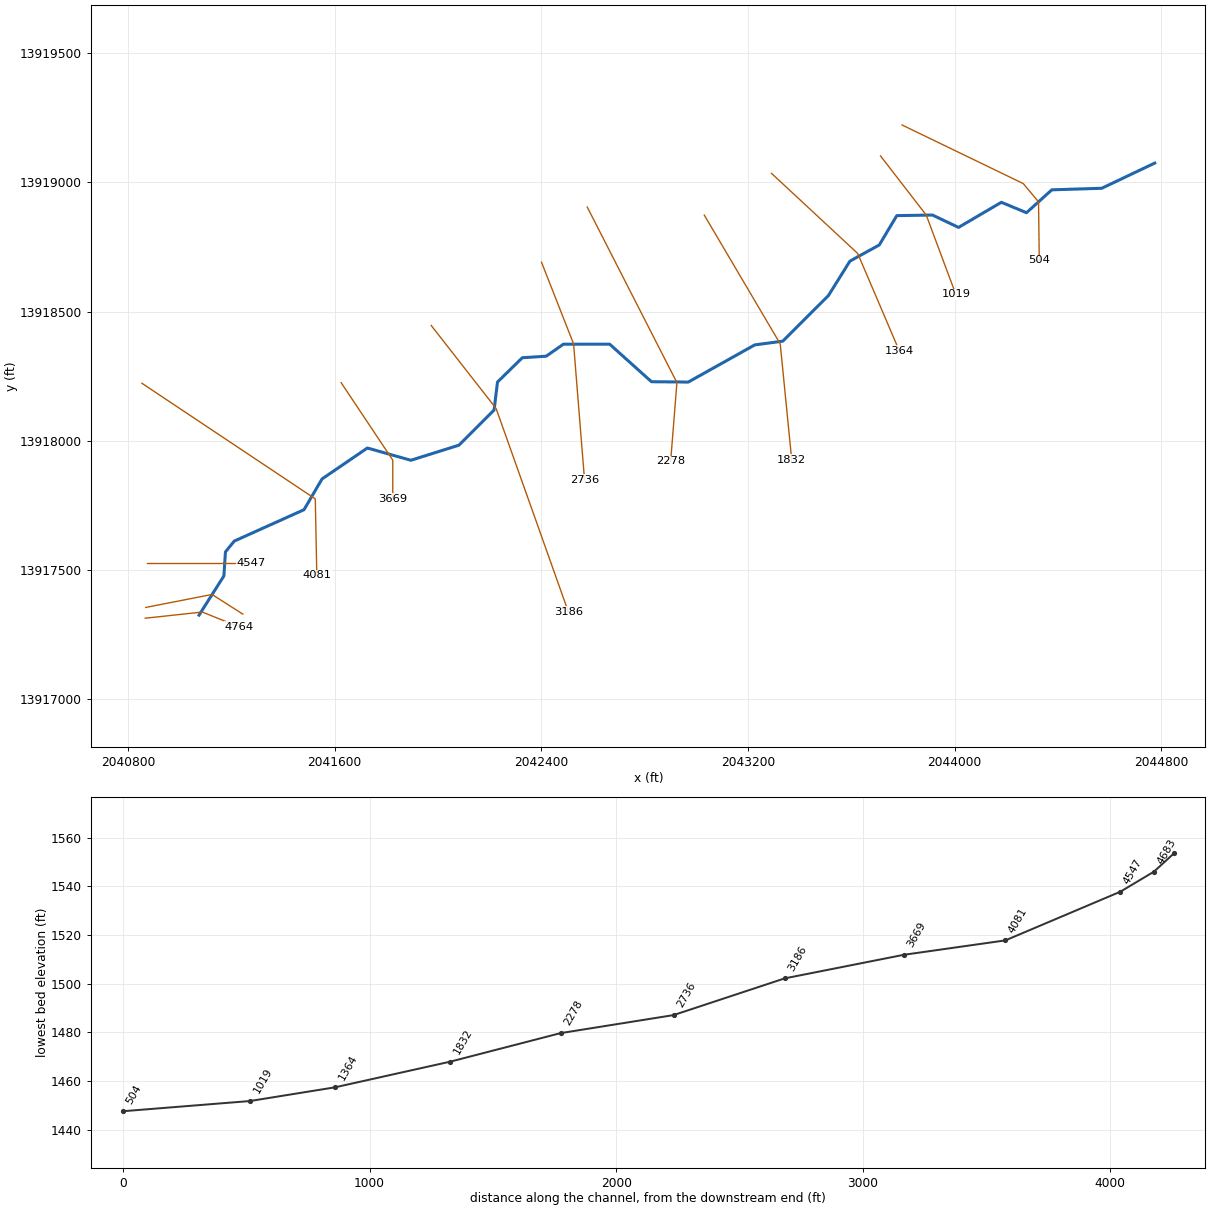
--- Stream0059_DS.prj (project) ---

Proj Title=Stream0059_DS Base Level Engineering
Current Plan=p01
Default Exp/Contr=0.3,0.1
English Units
Geom File=g01
Flow File=f01
Plan File=p01
Y Axis Title=Elevation
X Axis Title(PF)=Main Channel Distance
X Axis Title(XS)=Station
BEGIN DESCRIPTION:
Stream0059_DS
END DESCRIPTION:
DSS Export Rating Curves= 0
DSS Export Rating Curve Sorted= 0
DSS Export Volume Flow Curves= 0
DXF OffsetX= 0
DXF OffsetY= 0
DXF ScaleX= 1
DXF ScaleY= 10

--- Stream0059_DS.p01 (plan) ---

Plan Title=Multiple Run
Short Identifier=Multiple
Geom File=g01
Flow File=f01
Subcritical Flow
K Sum by GR= 0
Std Step Tol= 0.01
Critical Tol= 0.01
Num of Std Step Trials= 20
Max Error Tol= 0.3
Flow Tol Ratio= 0.001
Split Flow NTrial= 30
Split Flow Tol= 0.02
Split Flow Ratio= 0.02
Log Output Level= 0
Friction Slope Method= 1
Unsteady Friction Slope Method= 2
Unsteady Bridges Friction Slope Method= 1
Parabolic Critical Depth
Global Vel Dist=  1 , 1 , 1
Global Log Level= 0
CheckData=True
Encroach Param= -1, 0, 0, 0
BEGIN DESCRIPTION:
Multiple Run
END DESCRIPTION:

--- Stream0059_DS.f01 (steady flow) ---

Flow Title=Multiple
Number of Profiles=7
Profile Names=10-year,25-year,50-year,1pct_min,100-year,1pct_plu,500-year
River Rch & RM= Stream0059_DS,Reach-1,4764
     501     826    1129     752    1501    2995    2624
River Rch & RM= Stream0059_DS,Reach-1,4081
     701    1175    1623    1091    2177    4343    3874
Boundary for River Rch & Prof#=Stream0059_DS,Reach-1,1
Up Type=0
Dn Type=3
Dn Slope=0.005
Boundary for River Rch & Prof#=Stream0059_DS,Reach-1,2
Up Type=0
Dn Type=3
Dn Slope=0.005
Boundary for River Rch & Prof#=Stream0059_DS,Reach-1,3
Up Type=0
Dn Type=3
Dn Slope=0.005
Boundary for River Rch & Prof#=Stream0059_DS,Reach-1,4
Up Type=0
Dn Type=3
Dn Slope=0.005
Boundary for River Rch & Prof#=Stream0059_DS,Reach-1,5
Up Type=0
Dn Type=3
Dn Slope=0.005
Boundary for River Rch & Prof#=Stream0059_DS,Reach-1,6
Up Type=0
Dn Type=3
Dn Slope=0.005
Boundary for River Rch & Prof#=Stream0059_DS,Reach-1,7
Up Type=0
Dn Type=3
Dn Slope=0.005

--- Stream0059_DS.g01 (geometry) ---

Geom Title=Existing Conditions
Program Version=4.10

River Reach=Stream0059_DS   ,Reach-1
Reach XY= 30
        2041075.       13917325.      2041171.18     13917476.58
      2041177.18      13917569.7      2041211.37     13917611.55
      2041481.34     13917733.03      2041551.17     13917852.13
      2041726.64     13917971.86      2041895.05     13917924.41
      2042081.17     13917982.86      2042217.14     13918118.83
      2042230.52     13918227.44      2042326.48     13918321.39
      2042419.02     13918327.36       2042485.5     13918373.78
      2042664.57     13918373.95      2042826.47     13918228.53
      2042969.07     13918227.23      2043226.59     13918371.17
      2043334.79     13918385.52      2043511.37     13918561.79
      2043594.77     13918695.41       2043708.5     13918757.96
      2043776.25     13918871.56       2043914.5     13918873.77
      2044015.16     13918825.91      2044181.13     13918923.16
       2044278.4     13918882.83      2044376.46     13918971.44
      2044569.47     13918977.38        2044775.       13919075.

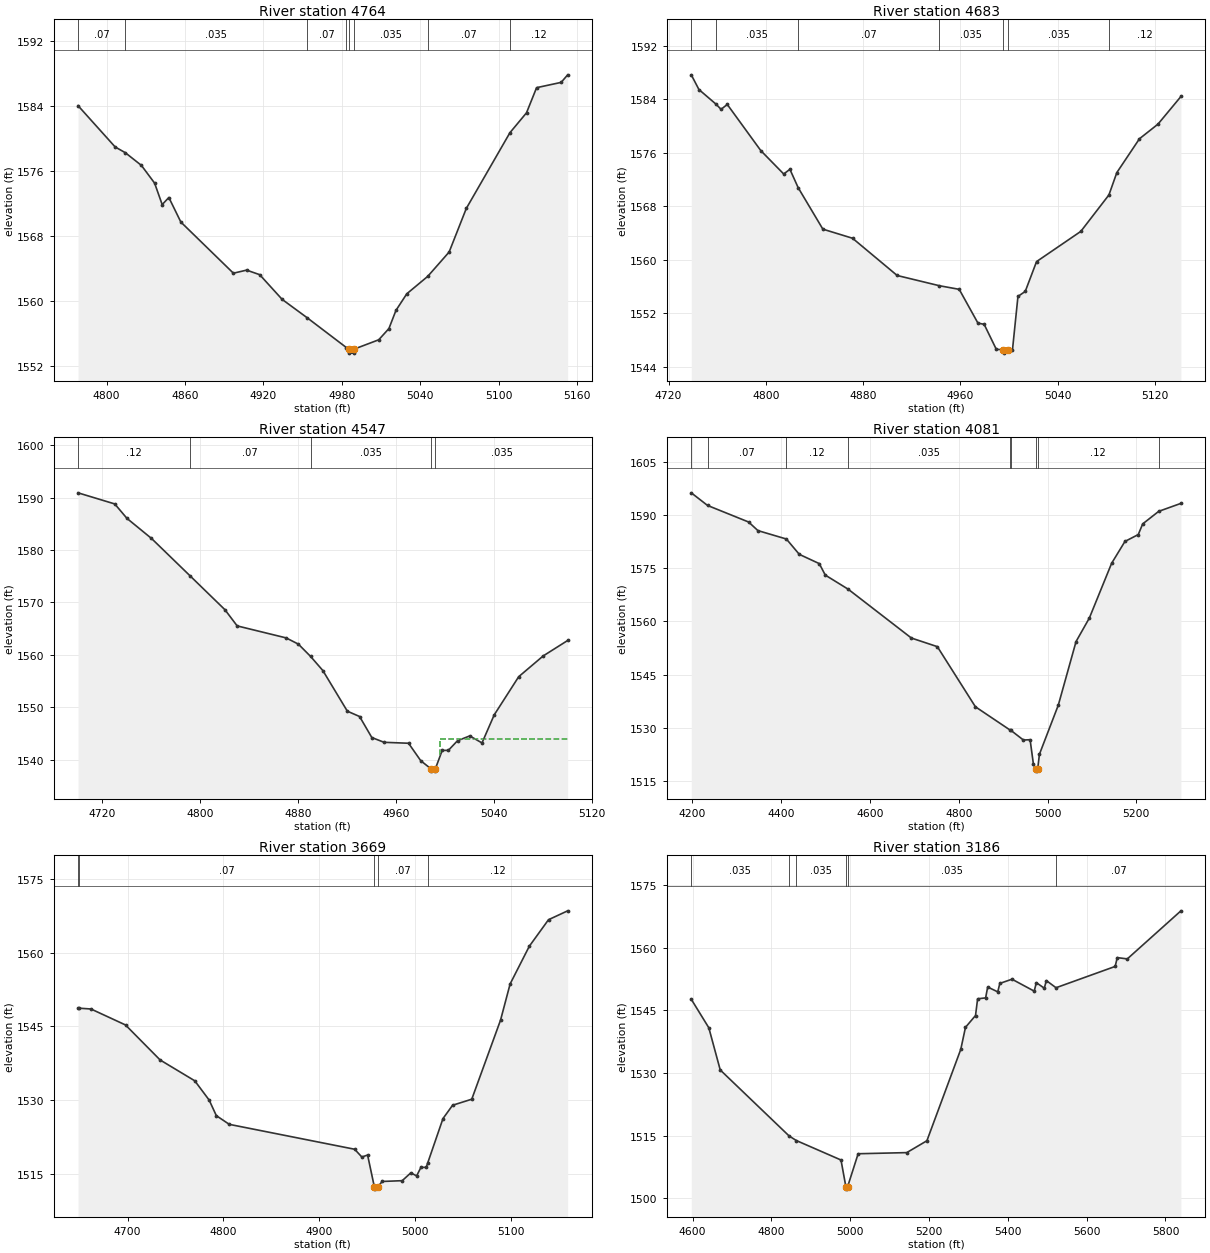
Type RM Length L Ch R = 1 ,4764    ,81,81,81
BEGIN DESCRIPTION:
Stream0059_DS 12.0
END DESCRIPTION:
XS GIS Cut Line= 3
      2040866.78     13917312.97      2041087.39     13917336.85
      2041229.21     13917279.98
#Sta/Elev= 30
  4778.1    1584  4806.5 1578.92  4814.3 1578.21  4826.6 1576.65  4836.7 1574.47
  4842.5 1571.83  4847.6  1572.7  4856.8 1569.68    4897 1563.39  4907.1 1563.77
  4917.1 1563.21  4934.3 1560.17  4953.7 1557.88  4983.4 1554.25  4985.5 1554.06
  4985.8 1553.56  4989.3 1553.56  4989.5 1554.06  5008.2  1555.2    5016 1556.58
  5021.4 1558.82  5029.7 1560.86  5045.7    1563  5062.1    1566  5075.2 1571.35
  5108.6 1580.67  5121.3 1583.12    5129 1586.21  5147.8 1586.86  5152.8 1587.79
#Mann= 8 ,-1 , 0
  4778.1     .07       0  4814.3    .035       0  4953.7     .07       0
  4983.4    .035       0  4985.5    .035       0  4989.5    .035       0
  5045.7     .07       0  5108.6     .12       0
Bank Sta=4985.5,4989.5
XS Rating Curve= 0 ,0
Exp/Cntr=0.3,0.1

Type RM Length L Ch R = 1 ,4683    ,136,136,136
BEGIN DESCRIPTION:
Stream0059_DS 11.0
END DESCRIPTION:
XS GIS Cut Line= 3
      2040868.83     13917354.74      2041125.28     13917404.89
      2041244.42     13917328.93
#Sta/Elev= 30
  4738.7 1587.66    4745 1585.46    4759 1583.28  4763.2  1582.5  4768.3 1583.23
  4795.9 1576.32  4814.7 1572.83  4819.8 1573.53  4826.6 1570.78  4846.9 1564.58
  4871.3 1563.22    4908 1557.65  4942.7 1556.12    4959 1555.58  4974.4 1550.53
  4979.5 1550.35  4989.5 1546.61  4995.3 1546.54  4995.6 1546.04  4999.3 1546.54
  5002.8 1546.54  5007.3 1554.52  5013.3 1555.27  5022.6 1559.73    5059 1564.25
  5082.1  1569.7  5088.6 1573.04  5107.2  1578.1  5122.4 1580.28  5141.3 1584.42
#Mann= 7 ,-1 , 0
  4738.7     .07       0    4759    .035       0  4826.6     .07       0
  4942.7    .035       0  4995.3    .035       0  4999.3    .035       0
  5082.1     .12       0
Bank Sta=4995.3,4999.3
XS Rating Curve= 0 ,0
Exp/Cntr=0.3,0.1

Type RM Length L Ch R = 1 ,4547    ,466,466,466
BEGIN DESCRIPTION:
Stream0059_DS 10.0
END DESCRIPTION:
XS GIS Cut Line= 3
      2040875.05       13917525.        2041175.       13917525.
      2041275.05       13917525.
#Sta/Elev= 30
  4700.1 1590.92  4730.1  1588.8  4740.1 1586.04  4760.1 1582.22  4791.5 1575.11
  4820.1 1568.62  4830.1 1565.53  4870.1 1563.24  4880.1 1562.05  4890.1  1559.7
  4900.1 1557.01  4920.1 1549.26  4930.1 1548.24  4940.1 1544.23  4950.1 1543.32
  4970.1 1543.14  4980.1  1539.8  4988.1 1538.32  4988.3 1537.82  4991.8 1537.82
  4992.1 1538.32  4997.6 1541.78  5002.6 1541.78  5010.1 1543.62  5020.1 1544.54
  5030.1  1543.2  5040.1 1548.56  5060.1 1555.84  5080.1  1559.8  5100.1 1562.75
#Mann= 5 ,-1 , 0
  4700.1     .12       0  4791.5     .07       0  4890.1    .035       0
  4988.1    .035       0  4992.1    .035       0
#XS Ineff= 2 , 0
       0                 4996.17       0 1543.92
Permanent Ineff=
       F       F
Bank Sta=4988.1,4992.1
XS Rating Curve= 0 ,0
Exp/Cntr=0.3,0.1

Type RM Length L Ch R = 1 ,4081    ,412,412,412
BEGIN DESCRIPTION:
Stream0059_DS 9.0
END DESCRIPTION:
XS GIS Cut Line= 3
      2040853.89     13918222.49        2041525.       13917775.
      2041530.94     13917478.88
#Sta/Elev= 30
  4197.7  1596.2  4234.3 1592.65  4326.8 1587.98  4347.8 1585.56  4411.9 1583.19
    4441 1578.87    4486 1576.26  4499.5 1573.03  4551.1 1569.05  4693.4  1555.3
  4751.9 1552.87  4837.6 1535.94  4915.1 1529.43  4917.6 1529.29  4945.7 1526.57
  4960.8 1526.66  4968.3 1519.76  4973.8 1518.31    4974 1517.81  4977.8 1518.31
  4981.8 1522.56  5024.3 1536.39  5064.3 1554.31  5094.3 1560.95  5144.4 1576.35
  5174.4 1582.51  5204.4 1584.44  5214.4 1587.45  5250.4 1590.98  5300.5 1593.23
#Mann= 9 ,-1 , 0
  4197.7    .035       0  4234.3     .07       0  4411.9     .12       0
  4551.1    .035       0  4915.1     .07       0  4917.6     .12       0
  4973.8     .05       0  4977.8     .12       0  5250.4     .07       0
Bank Sta=4973.8,4977.8
XS Rating Curve= 0 ,0
Exp/Cntr=0.3,0.1

Type RM Length L Ch R = 1 ,3669    ,483,483,483
BEGIN DESCRIPTION:
Stream0059_DS 8.0
END DESCRIPTION:
XS GIS Cut Line= 3
      2041625.02     13918224.97        2041825.       13917925.
        2041825.     13917775.02
#Sta/Elev= 30
  4648.4 1548.73    4649 1548.73  4661.9 1548.56  4697.9 1545.31    4734 1538.18
  4770.1 1533.94  4785.1 1530.02  4792.6 1526.84  4806.1 1525.07  4936.8    1520
  4944.3 1518.42  4950.3 1518.82  4957.3 1512.38  4957.6 1511.88  4961.3 1512.38
  4965.4 1513.44  4986.4  1513.6  4995.4  1515.2  5001.4 1514.57  5005.9 1516.31
  5011.4 1516.31  5012.9 1517.17  5028.9 1526.25  5038.9 1528.96  5058.9 1530.19
  5088.9 1546.29  5098.9 1553.67  5118.9 1561.34  5138.9 1566.74  5158.9 1568.55
#Mann= 5 ,-1 , 0
  4648.4    .035       0    4649     .07       0  4957.3     .05       0
  4961.3     .07       0  5012.9     .12       0
Bank Sta=4957.3,4961.3
XS Rating Curve= 0 ,0
Exp/Cntr=0.3,0.1

Type RM Length L Ch R = 1 ,3186    ,450,450,450
BEGIN DESCRIPTION:
Stream0059_DS 7.0
END DESCRIPTION:
XS GIS Cut Line= 3
      2041973.66     13918446.48        2042225.       13918125.
      2042504.41     13917338.53
#Sta/Elev= 30
  4596.6 1547.63  4641.1 1540.81  4670.1 1530.71  4845.1 1514.89  4863.3 1513.81
  4976.6 1509.15  4989.1 1502.68  4989.3 1502.18  4993.1 1502.68  5020.1 1510.65
  5143.5 1510.92  5194.6 1513.76  5280.6 1535.65  5292.5 1540.91    5318 1543.74
  5323.3 1547.74  5343.6 1547.96  5348.9 1550.56  5374.4  1549.4  5379.7 1551.43
  5410.6 1552.43    5467 1549.57  5472.3 1551.61  5492.5 1550.28  5497.8  1552.1
  5522.3 1550.39  5672.4 1555.49  5677.7  1557.6  5703.2 1557.29  5839.3  1568.8
#Mann= 6 ,-1 , 0
  4596.6    .035       0  4845.1     .12       0  4863.3    .035       0
  4989.1     .05       0  4993.1    .035       0  5522.3     .07       0
Bank Sta=4989.1,4993.1
XS Rating Curve= 0 ,0
Exp/Cntr=0.3,0.1

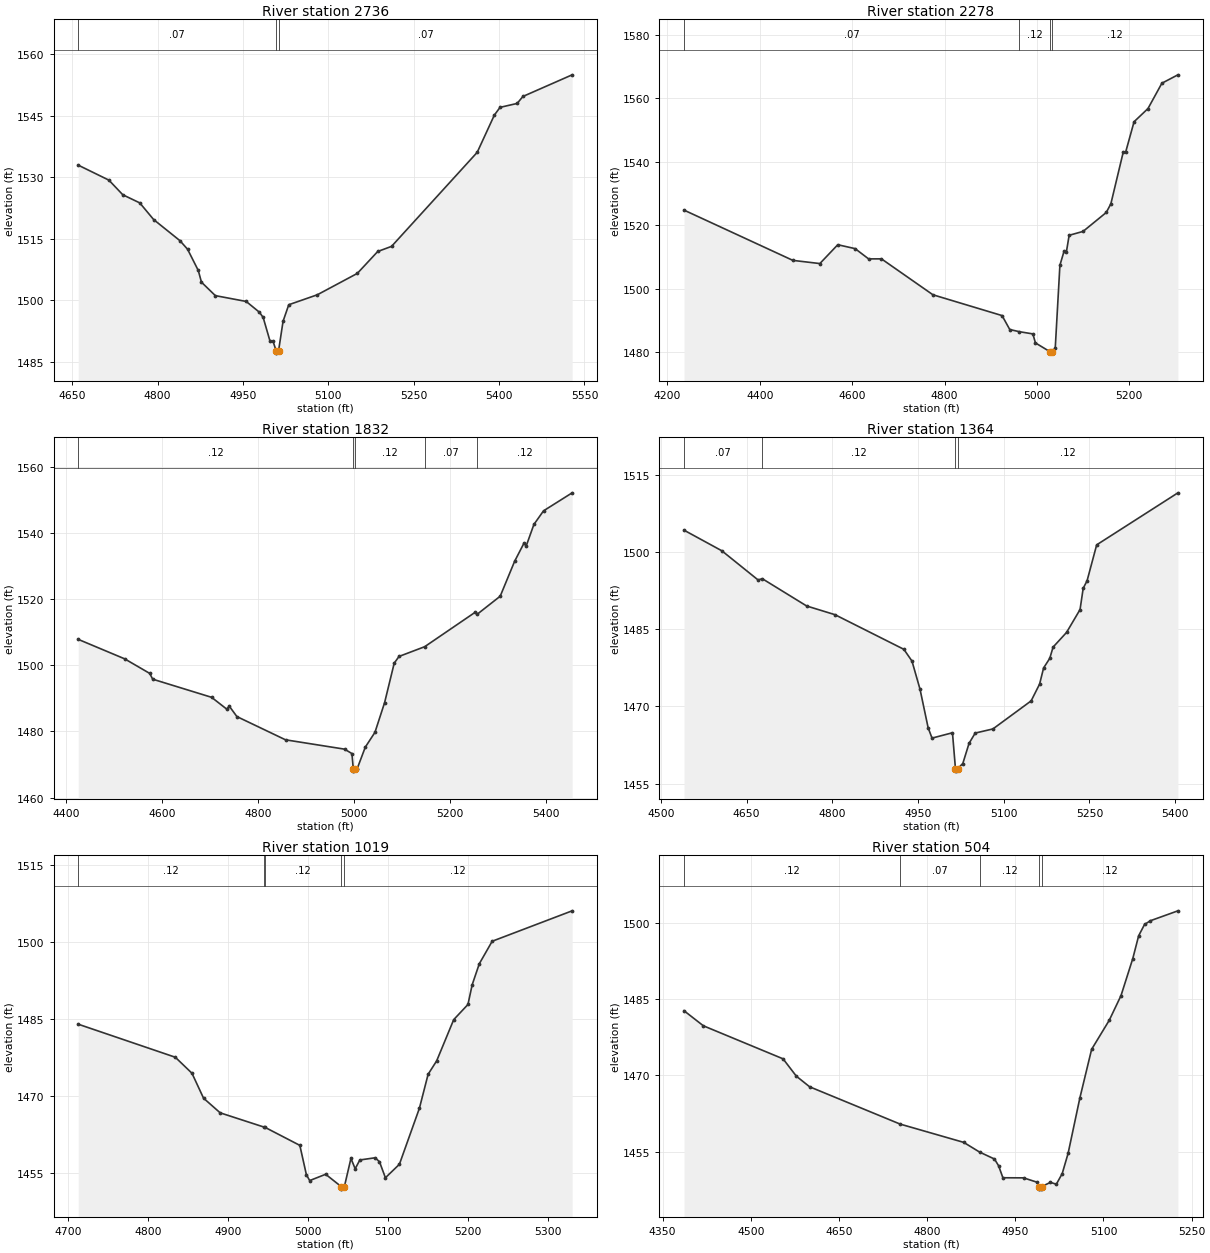
Type RM Length L Ch R = 1 ,2736    ,458,458,458
BEGIN DESCRIPTION:
Stream0059_DS 6.0
END DESCRIPTION:
XS GIS Cut Line= 3
      2042400.74     13918691.29        2042525.       13918375.
      2042567.32     13917848.72
#Sta/Elev= 30
  4660.6 1532.97  4714.5 1529.31  4738.9 1525.74  4768.7 1523.76  4793.1 1519.69
  4839.3 1514.54  4852.7 1512.45  4871.5 1507.27  4877.1 1504.41  4901.5 1501.13
  4955.7 1499.71  4978.9 1497.08  4985.5 1495.81  4997.7 1489.96  5002.9 1489.96
  5008.5  1487.6  5008.7  1487.1  5012.5  1487.6  5020.5 1494.89  5030.5 1498.91
  5080.7 1501.34  5150.9 1506.55  5186.8  1511.9  5211.1 1513.15  5361.6  1536.1
  5391.7 1545.18  5401.7 1547.07  5431.8 1548.03  5441.9 1549.73  5528.4 1555.01
#Mann= 3 ,-1 , 0
  4660.6     .07       0  5008.5     .05       0  5012.5     .07       0
Bank Sta=5008.5,5012.5
XS Rating Curve= 0 ,0
Exp/Cntr=0.3,0.1

Type RM Length L Ch R = 1 ,2278    ,446,446,446
BEGIN DESCRIPTION:
Stream0059_DS 5.0
END DESCRIPTION:
XS GIS Cut Line= 3
      2042577.83      13918904.8        2042925.       13918225.
      2042900.75     13917920.38
#Sta/Elev= 30
  4236.2 1524.72  4471.8 1508.89  4530.2 1507.89    4569 1513.82  4606.5 1512.59
  4635.7 1509.36  4663.5 1509.37  4774.9 1498.06  4924.5 1491.51  4941.2 1487.12
    4962 1486.44  4991.2 1485.74  4996.7 1482.91  5027.6 1480.19  5027.9 1479.69
  5031.6 1480.19  5039.6 1481.21  5049.7 1507.36  5058.6 1511.73  5063.6 1511.43
  5069.7 1516.79  5099.8 1518.01    5150 1523.97    5160 1526.71  5186.8    1543
  5191.8 1542.88  5210.2 1552.54  5240.3 1556.69  5270.4 1564.67  5305.1 1567.31
#Mann= 4 ,-1 , 0
  4236.2     .07       0    4962     .12       0  5027.6     .05       0
  5031.6     .12       0
Bank Sta=5027.6,5031.6
XS Rating Curve= 0 ,0
Exp/Cntr=0.3,0.1

Type RM Length L Ch R = 1 ,1832    ,468,468,468
BEGIN DESCRIPTION:
Stream0059_DS 4.0
END DESCRIPTION:
XS GIS Cut Line= 3
      2043030.97     13918873.54        2043325.       13918375.
      2043369.51     13917925.59
#Sta/Elev= 30
  4425.2 1507.87    4522 1501.98  4574.4 1497.56  4580.5 1495.82  4703.4 1490.33
  4734.7 1486.79  4740.5 1487.61  4756.2  1484.5  4857.6 1477.47  4980.8 1474.64
  4996.2  1473.3  4999.1 1468.49  4999.3 1467.99  5003.1 1468.49  5006.5 1468.49
  5024.1 1475.26  5044.2 1479.73  5064.3  1488.7  5084.4 1500.67  5094.4  1502.7
    5148 1505.65  5253.9 1516.13  5257.8  1515.5  5305.5 1520.93  5335.6  1531.5
  5354.9 1536.93  5359.9  1536.2  5375.8 1542.65  5395.9 1546.77  5455.6 1552.22
#Mann= 5 ,-1 , 0
  4425.2     .12       0  4999.1     .05       0  5003.1     .12       0
    5148     .07       0  5257.8     .12       0
Bank Sta=4999.1,5003.1
XS Rating Curve= 0 ,0
Exp/Cntr=0.3,0.1

Type RM Length L Ch R = 1 ,1364    ,345,345,345
BEGIN DESCRIPTION:
Stream0059_DS 3.0
END DESCRIPTION:
XS GIS Cut Line= 3
       2043291.4     13919034.98        2043625.       13918725.
      2043785.64     13918348.74
#Sta/Elev= 30
  4540.3  1504.2  4606.5  1500.2    4670 1494.53  4677.3 1494.78    4755 1489.48
  4804.6 1487.79  4925.1 1481.07  4939.3 1478.79  4953.4 1473.32  4967.6 1465.84
  4974.4 1463.83  5010.2 1464.87  5015.4 1457.92  5015.7 1457.42  5019.4 1457.92
  5028.3  1458.9  5039.2 1462.81    5050 1464.81    5081 1465.61  5147.9 1471.06
  5162.7 1474.32  5169.7 1477.45  5180.5 1479.32  5186.3  1481.5  5209.9 1484.35
  5233.5 1488.79    5239 1492.91  5245.8 1494.38  5262.6 1501.35  5404.8 1511.45
#Mann= 4 ,-1 , 0
  4540.3     .07       0  4677.3     .12       0  5015.4     .05       0
  5019.4     .12       0
Bank Sta=5015.4,5019.4
XS Rating Curve= 0 ,0
Exp/Cntr=0.3,0.1

Type RM Length L Ch R = 1 ,1019    ,515,515,515
BEGIN DESCRIPTION:
Stream0059_DS 2.0
END DESCRIPTION:
XS GIS Cut Line= 3
      2043713.25     13919102.72      2043890.34     13918873.54
      2044004.93     13918566.24
#Sta/Elev= 30
  4712.8 1483.97  4834.2 1477.52    4855  1474.4  4869.5 1469.53  4890.3 1466.67
  4944.9  1463.9  4946.1 1463.86  4989.9 1460.32  4998.1 1454.58  5002.2 1453.45
  5022.2 1454.68  5041.6 1452.28  5041.8 1451.78  5045.6 1452.28  5053.8 1457.78
  5059.1 1455.75  5064.9 1457.47  5084.1  1457.9  5089.5 1457.12  5096.9    1454
  5114.4 1456.63  5139.4 1467.56  5150.3  1474.2    5161 1476.82  5182.3 1484.86
  5200.1 1487.82  5205.4 1491.67  5214.3 1495.77  5230.4 1500.16  5330.4  1506.1
#Mann= 5 ,-1 , 0
  4712.8     .12       0  4944.9     .07       0  4946.1     .12       0
  5041.6     .05       0  5045.6     .12       0
Bank Sta=5041.6,5045.6
XS Rating Curve= 0 ,0
Exp/Cntr=0.3,0.1

Type RM Length L Ch R = 1 ,504     ,0,0,0
BEGIN DESCRIPTION:
Stream0059_DS 1.0
END DESCRIPTION:
XS GIS Cut Line= 4
       2043796.6     13919222.49      2044265.85     13918995.62
        2044325.       13918925.      2044327.82     13918698.25
#Sta/Elev= 30
  4386.5 1482.74  4419.4 1479.77    4555 1473.26  4577.6 1469.84  4600.2 1467.75
  4754.2  1460.4  4862.3  1456.8  4889.4 1454.88  4914.6 1453.52  4921.6 1452.19
  4928.9 1449.83  4964.1 1449.81  4986.2 1448.98  4990.7 1448.09  4990.9 1447.59
  4994.4 1447.59  4994.7 1448.09  5009.8 1448.92  5019.8 1448.56  5029.8 1450.65
  5039.8 1454.63  5059.8 1465.54  5079.8 1475.13  5109.8 1480.86  5129.8 1485.72
  5149.8    1493  5159.8  1497.5  5169.8 1499.73  5179.8 1500.47  5226.6 1502.42
#Mann= 5 ,-1 , 0
  4386.5     .12       0  4754.2     .07       0  4889.4     .12       0
  4990.7     .05       0  4994.7     .12       0
Bank Sta=4990.7,4994.7
XS Rating Curve= 0 ,0
Exp/Cntr=0.3,0.1

Chan Stop Cuts=-1
Use User Specified Reach Order=0
Composite Channel Slope=5