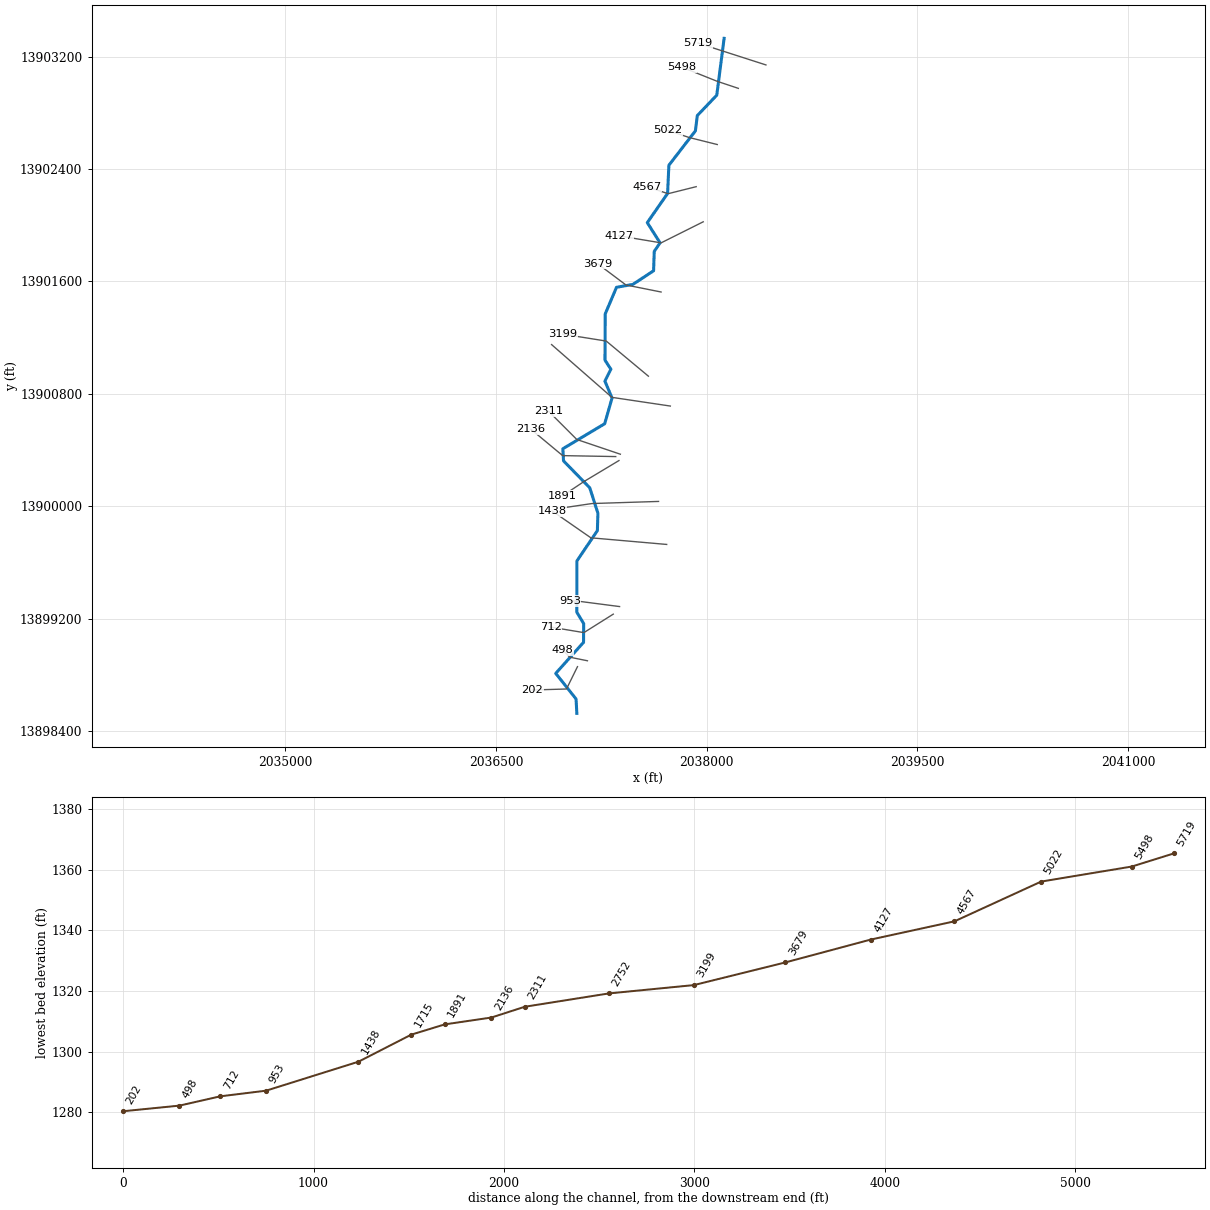
--- Stream0060_DS.prj (project) ---

Proj Title=Stream0060_DS Base Level Engineering
Current Plan=p01
Default Exp/Contr=0.3,0.1
English Units
Geom File=g01
Flow File=f01
Plan File=p01
Y Axis Title=Elevation
X Axis Title(PF)=Main Channel Distance
X Axis Title(XS)=Station
BEGIN DESCRIPTION:
Stream0060_DS
END DESCRIPTION:
DSS Export Rating Curves= 0
DSS Export Rating Curve Sorted= 0
DSS Export Volume Flow Curves= 0
DXF OffsetX= 0
DXF OffsetY= 0
DXF ScaleX= 1
DXF ScaleY= 10

--- Stream0060_DS.p01 (plan) ---

Plan Title=Multiple Run
Short Identifier=Multiple
Geom File=g01
Flow File=f01
Subcritical Flow
K Sum by GR= 0
Std Step Tol= 0.01
Critical Tol= 0.01
Num of Std Step Trials= 20
Max Error Tol= 0.3
Flow Tol Ratio= 0.001
Split Flow NTrial= 30
Split Flow Tol= 0.02
Split Flow Ratio= 0.02
Log Output Level= 0
Friction Slope Method= 1
Unsteady Friction Slope Method= 2
Unsteady Bridges Friction Slope Method= 1
Parabolic Critical Depth
Global Vel Dist=  1 , 1 , 1
Global Log Level= 0
CheckData=True
Encroach Param= -1, 0, 0, 0
BEGIN DESCRIPTION:
Multiple Run
END DESCRIPTION:

--- Stream0060_DS.f01 (steady flow) ---

Flow Title=Multiple
Number of Profiles=7
Profile Names=10-year,25-year,50-year,1pct_min,100-year,1pct_plu,500-year
River Rch & RM= Stream0060_DS,Reach-1,5719
     660    1093    1497     996    1988    3967    3464
River Rch & RM= Stream0060_DS,Reach-1,4127
    1128    1920    2677    1811    3613    7210    6505
Boundary for River Rch & Prof#=Stream0060_DS,Reach-1,1
Up Type=0
Dn Type=3
Dn Slope=0.005
Boundary for River Rch & Prof#=Stream0060_DS,Reach-1,2
Up Type=0
Dn Type=3
Dn Slope=0.005
Boundary for River Rch & Prof#=Stream0060_DS,Reach-1,3
Up Type=0
Dn Type=3
Dn Slope=0.005
Boundary for River Rch & Prof#=Stream0060_DS,Reach-1,4
Up Type=0
Dn Type=3
Dn Slope=0.005
Boundary for River Rch & Prof#=Stream0060_DS,Reach-1,5
Up Type=0
Dn Type=3
Dn Slope=0.005
Boundary for River Rch & Prof#=Stream0060_DS,Reach-1,6
Up Type=0
Dn Type=3
Dn Slope=0.005
Boundary for River Rch & Prof#=Stream0060_DS,Reach-1,7
Up Type=0
Dn Type=3
Dn Slope=0.005

--- Stream0060_DS.g01 (geometry) ---

Geom Title=Existing Conditions
Program Version=4.10

River Reach=Stream0060_DS   ,Reach-1
Reach XY= 30
      2038123.78     13903331.12       2038071.5     13902926.45
      2037932.86     13902781.17      2037919.46     13902672.58
      2037730.47     13902427.45      2037721.25     13902226.55
      2037576.69     13902018.85      2037667.78     13901875.11
       2037626.4     13901814.56      2037621.55     13901676.25
      2037473.41     13901578.83      2037357.79     13901558.73
      2037277.26     13901369.06      2037275.66     13901040.16
      2037317.41     13900974.99      2037275.15     13900890.42
      2037325.81     13900769.97      2037273.27     13900586.85
      2036975.52     13900409.11      2036980.37     13900322.63
      2037167.14     13900131.17      2037225.23     13899950.07
      2037221.46     13899826.47      2037075.51     13899609.79
      2037075.07     13899245.03      2037123.79     13899164.49
      2037122.95     13899030.86      2036924.89     13898809.64
      2037069.65      13898627.5        2037075.       13898525.

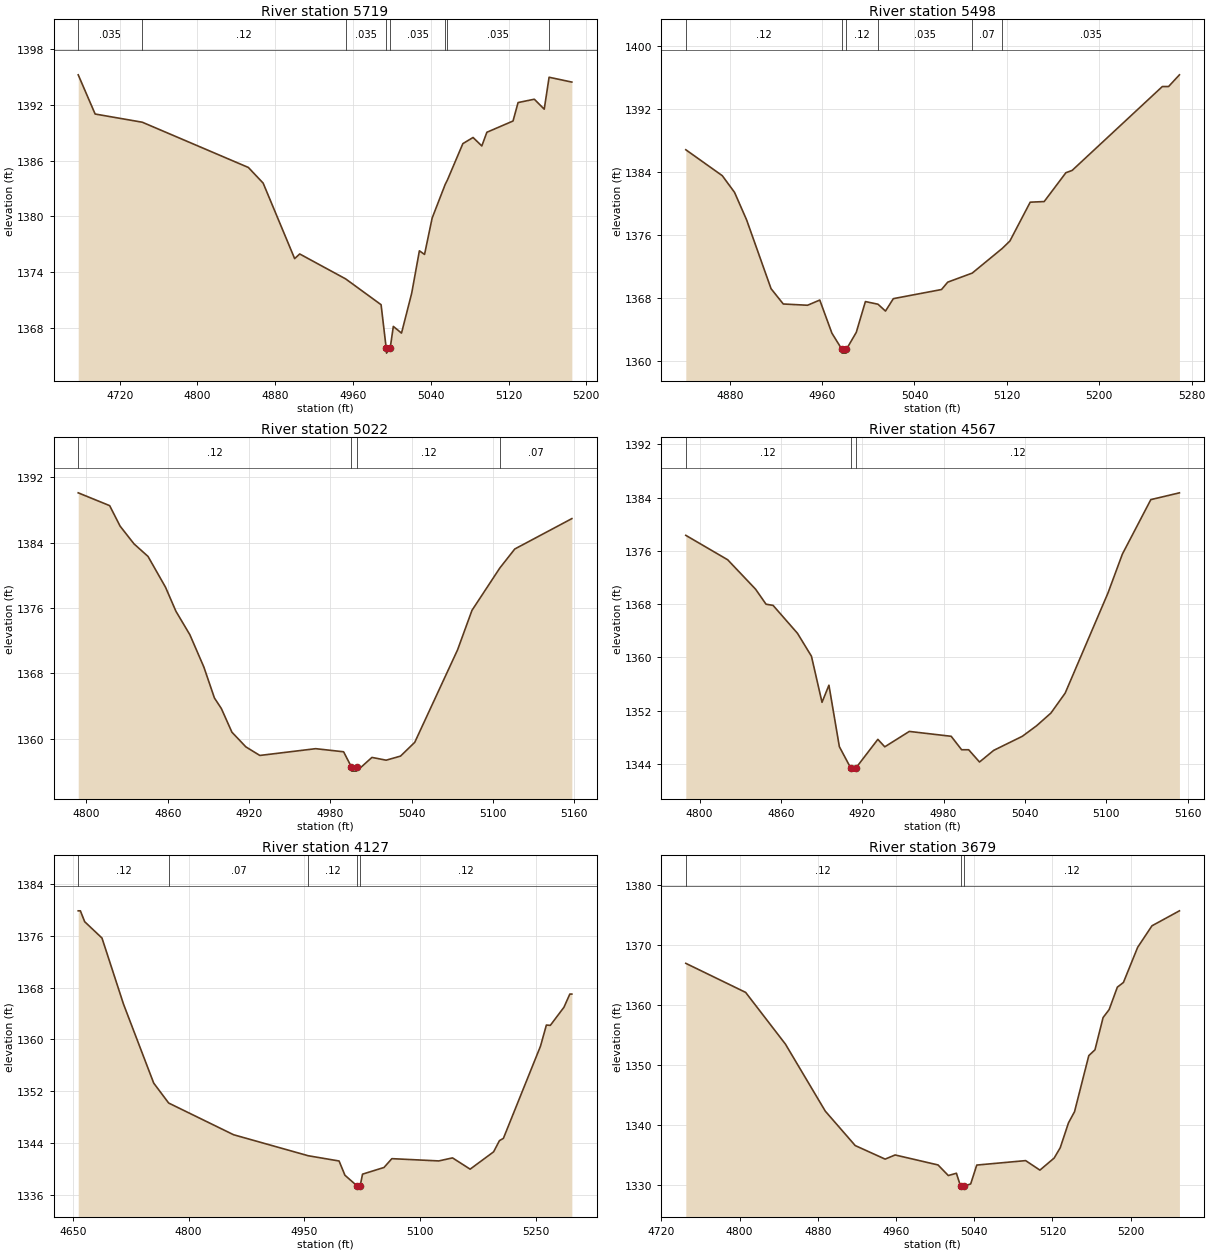
Type RM Length L Ch R = 1 ,5719    ,221,221,221
BEGIN DESCRIPTION:
Stream0060_DS 13.0
END DESCRIPTION:
XS GIS Cut Line= 2
      2038421.56     13903141.76      2037938.24     13903297.19
#Sta/Elev= 30
  4677.4 1395.21  4694.8    1391  4743.3 1390.12  4852.4 1385.26  4867.6 1383.58
    4900 1375.47  4905.2 1375.97  4952.5 1373.29  4988.9 1370.52  4994.2 1365.82
  4994.5 1365.32  4998.2 1365.82  5001.5 1368.19  5009.9 1367.47  5020.4 1371.76
  5028.3 1376.31  5033.6 1375.92  5041.4 1379.82  5054.8 1383.43  5057.1 1383.91
    5073 1387.82  5083.5 1388.48  5092.5 1387.57  5097.7 1389.04  5124.6 1390.25
  5129.8 1392.23  5146.5 1392.59  5156.7 1391.52  5161.7 1394.95  5185.1 1394.43
#Mann= 8 ,-1 , 0
  4677.4    .035       0  4743.3     .12       0  4952.5    .035       0
  4994.2    .035       0  4998.2    .035       0  5054.8     .07       0
  5057.1    .035       0  5161.7     .07       0
Bank Sta=4994.2,4998.2
XS Rating Curve= 0 ,0
Exp/Cntr=0.3,0.1

Type RM Length L Ch R = 1 ,5498    ,476,476,476
BEGIN DESCRIPTION:
Stream0060_DS 12.0
END DESCRIPTION:
XS GIS Cut Line= 3
      2038225.02     13902974.99        2038075.       13903025.
        2037825.       13903125.
#Sta/Elev= 30
    4842 1386.86  4873.6 1383.56  4884.2 1381.44  4894.7 1377.92  4915.8 1369.19
  4926.4 1367.24  4947.4 1367.08    4958 1367.74  4968.5 1363.53  4977.1 1361.49
  4977.3 1360.99  4980.8 1360.99  4981.1 1361.49  4989.6 1363.63  4997.5 1367.55
  5008.4 1367.21  5014.9 1366.34  5021.7 1367.92  5063.4 1369.08  5068.8 1370.02
    5090 1371.17    5116 1374.31  5122.6 1375.25  5140.2 1380.19  5152.3 1380.27
  5171.1 1383.94  5176.5 1384.23  5254.6  1394.9    5260  1394.9  5269.4 1396.39
#Mann= 6 ,-1 , 0
    4842     .12       0  4977.1     .05       0  4981.1     .12       0
  5008.4    .035       0    5090     .07       0    5116    .035       0
Bank Sta=4977.1,4981.1
XS Rating Curve= 0 ,0
Exp/Cntr=0.3,0.1

Type RM Length L Ch R = 1 ,5022    ,455,455,455
BEGIN DESCRIPTION:
Stream0060_DS 11.0
END DESCRIPTION:
XS GIS Cut Line= 3
      2038074.97     13902575.01        2037875.       13902625.
      2037725.04     13902674.99
#Sta/Elev= 30
  4793.9 1390.12  4817.1 1388.55  4824.8 1386.04  4835.1 1383.86  4845.4 1382.33
  4858.3 1378.56    4866 1375.61  4876.3 1372.73  4886.6 1368.78  4894.4 1364.99
  4899.5  1363.7  4907.3  1360.8  4917.6    1359  4927.9 1357.95  4969.1 1358.78
  4989.7  1358.4  4995.5 1356.53  4995.7 1356.03  4999.2 1356.03  4999.5 1356.53
  5002.7 1356.53  5010.6 1357.71  5021.1 1357.37  5031.7 1357.87  5042.2 1359.56
  5073.8 1370.89  5084.4 1375.72    5105 1380.92    5116 1383.24  5158.1 1386.96
#Mann= 4 ,-1 , 0
  4793.9     .12       0  4995.5     .05       0  4999.5     .12       0
    5105     .07       0
Bank Sta=4995.5,4999.5
XS Rating Curve= 0 ,0
Exp/Cntr=0.3,0.1

Type RM Length L Ch R = 1 ,4567    ,440,440,440
BEGIN DESCRIPTION:
Stream0060_DS 10.0
END DESCRIPTION:
XS GIS Cut Line= 3
      2037924.96     13902274.99        2037725.       13902225.
      2037575.02     13902274.99
#Sta/Elev= 30
  4789.8 1378.33  4820.7 1374.66  4841.3 1370.24    4849 1367.99  4854.2 1367.81
  4872.2 1363.62  4882.5 1360.18  4890.3 1353.26  4895.4 1355.83  4903.1  1346.6
  4911.4 1343.43  4911.7 1342.93  4915.2 1342.93  4915.4 1343.43  4931.5  1347.7
  4936.6 1346.58  4954.7 1348.89  4985.6 1348.16  4993.3 1346.14  4998.5 1346.14
  5006.5  1344.3    5017 1346.05  5038.1 1348.16  5048.6 1349.74  5059.2 1351.65
  5069.7 1354.64  5101.3 1369.68  5111.9 1375.51  5132.9 1383.69    5154 1384.71
#Mann= 3 ,-1 , 0
  4789.8     .12       0  4911.4     .05       0  4915.4     .12       0
Bank Sta=4911.4,4915.4
XS Rating Curve= 0 ,0
Exp/Cntr=0.3,0.1

Type RM Length L Ch R = 1 ,4127    ,448,448,448
BEGIN DESCRIPTION:
Stream0060_DS 9.0
END DESCRIPTION:
XS GIS Cut Line= 3
      2037975.01       13902025.        2037675.       13901875.
      2037374.96     13901925.01
#Sta/Elev= 30
  4657.1 1379.84  4659.9 1379.84  4665.5 1378.16  4687.9 1375.64  4715.8 1365.44
  4754.9 1353.27  4774.3 1350.19  4858.4  1345.3  4955.1 1342.06  4995.1 1341.25
  5002.7 1339.05  5018.4 1337.41  5018.6 1336.91  5022.1 1336.91  5022.4 1337.41
  5025.5 1339.22  5053.3 1340.25  5063.5 1341.61  5124.3 1341.26  5142.1 1341.73
  5164.9 1339.99  5195.3 1342.66  5202.9 1344.39    5208 1344.74  5256.1 1358.97
  5263.7 1362.22  5268.8 1362.17  5286.5 1364.97  5294.1    1367  5296.7    1367
#Mann= 5 ,-1 , 0
  4657.1     .12       0  4774.3     .07       0  4955.1     .12       0
  5018.4     .05       0  5022.4     .12       0
Bank Sta=5018.4,5022.4
XS Rating Curve= 0 ,0
Exp/Cntr=0.3,0.1

Type RM Length L Ch R = 1 ,3679    ,480,480,480
BEGIN DESCRIPTION:
Stream0060_DS 8.0
END DESCRIPTION:
XS GIS Cut Line= 3
      2037674.96     13901525.01        2037425.       13901575.
      2037225.01     13901724.99
#Sta/Elev= 30
    4745 1366.92  4806.2 1362.09  4846.9 1353.49  4887.7 1342.34  4918.3 1336.62
  4948.9 1334.37  4959.1 1335.06    5003  1333.4  5013.5 1331.64  5021.8 1332.02
    5026 1329.88  5026.3 1329.38    5030 1329.88  5036.4 1330.25  5042.6 1333.38
  5092.6 1334.12  5107.2 1332.54  5121.8 1334.55    5128 1336.27  5136.4 1340.39
  5142.6 1342.25  5157.2 1351.58  5163.5 1352.54  5171.8  1357.9    5178 1359.23
  5186.4 1362.96  5192.6 1363.74  5207.2 1369.59  5221.8 1373.16  5249.9 1375.65
#Mann= 3 ,-1 , 0
    4745     .12       0    5026     .05       0    5030     .12       0
Bank Sta=5026,5030
XS Rating Curve= 0 ,0
Exp/Cntr=0.3,0.1

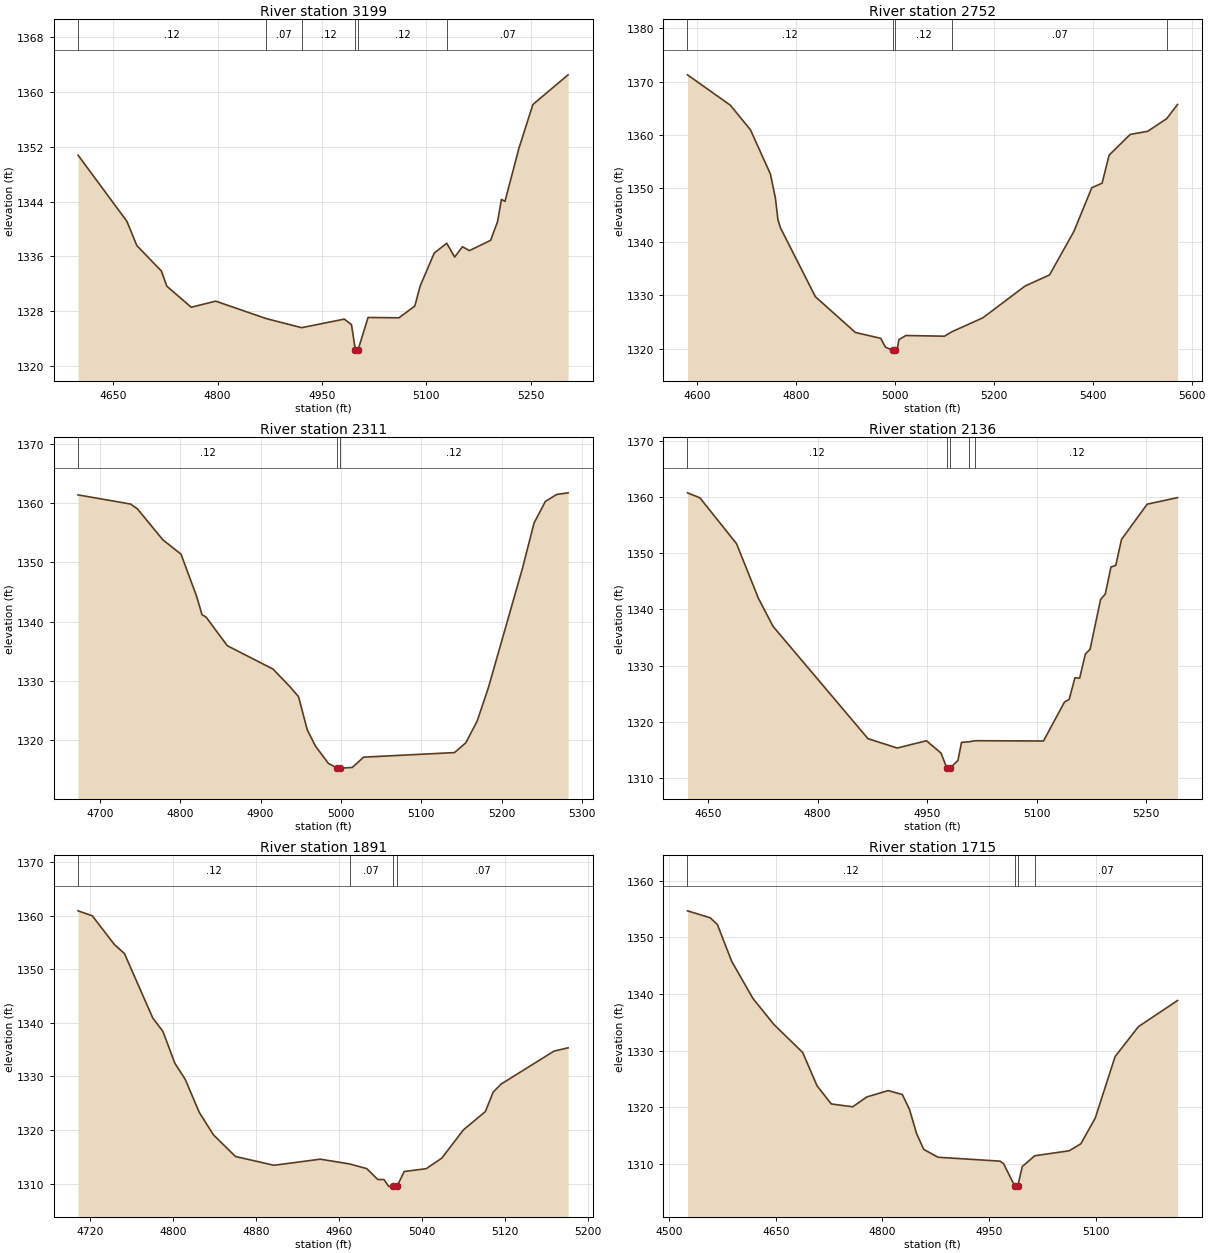
Type RM Length L Ch R = 1 ,3199    ,447,447,447
BEGIN DESCRIPTION:
Stream0060_DS 7.0
END DESCRIPTION:
XS GIS Cut Line= 3
      2037584.73     13900925.69      2037284.69     13901175.72
      2036975.04     13901224.99
#Sta/Elev= 30
  4599.6 1350.78  4669.8 1341.13  4684.1 1337.59  4719.3 1333.89  4727.1 1331.68
  4762.2  1328.6  4797.4 1329.49  4869.5 1326.96  4920.8 1325.62  4982.2 1326.87
  4992.5 1326.06    4998 1322.41  4998.2 1321.91    5002 1322.41  5016.3 1327.11
  5060.7 1327.06  5083.5 1328.78  5091.1 1331.68  5111.4 1336.51  5129.4 1337.93
  5140.7 1335.92  5151.9 1337.42    5162 1336.86  5192.4 1338.36  5202.5 1341.13
  5207.9 1344.33    5213 1344.03  5232.9 1351.72  5253.1 1358.16  5303.7 1362.49
#Mann= 6 ,-1 , 0
  4599.6     .12       0  4869.5     .07       0  4920.8     .12       0
    4998     .05       0    5002     .12       0  5129.4     .07       0
Bank Sta=4998,5002
XS Rating Curve= 0 ,0
Exp/Cntr=0.3,0.1

Type RM Length L Ch R = 1 ,2752    ,441,441,441
BEGIN DESCRIPTION:
Stream0060_DS 6.0
END DESCRIPTION:
XS GIS Cut Line= 3
       2037740.9     13900713.05        2037325.       13900775.
       2036895.4      13901150.7
#Sta/Elev= 30
  4580.3 1371.28  4667.1 1365.58  4707.6 1360.99    4748  1352.7  4758.1  1348.2
  4763.2 1344.17  4768.3 1342.63    4839 1329.72  4919.9 1323.03  4971.2 1321.93
  4980.6 1320.28  4996.3 1319.66  4996.5 1319.16  5000.3 1319.66  5004.1 1319.66
  5007.9 1321.69  5022.1 1322.46    5100 1322.33  5115.4 1323.18  5177.8 1325.78
  5263.2 1331.73  5312.6 1333.81  5361.9 1341.96    5398 1350.13  5418.9 1350.99
  5433.1 1356.24  5475.8 1360.12    5511  1360.7  5549.5 1363.06  5571.5 1365.73
#Mann= 5 ,-1 , 0
  4580.3     .12       0  4996.3     .05       0  5000.3     .12       0
  5115.4     .07       0  5549.5     .12       0
Bank Sta=4996.3,5000.3
XS Rating Curve= 0 ,0
Exp/Cntr=0.3,0.1

Type RM Length L Ch R = 1 ,2311    ,175,175,175
BEGIN DESCRIPTION:
Stream0060_DS 5.0
END DESCRIPTION:
XS GIS Cut Line= 3
      2037385.03     13900370.17        2037075.       13900475.
      2036875.01     13900674.99
#Sta/Elev= 30
  4672.7 1361.39    4738 1359.85  4746.6 1359.04  4778.3 1353.81  4800.9 1351.39
  4820.5 1344.21    4827 1341.18  4832.3 1340.74  4858.5 1335.94  4915.5 1331.99
  4936.6 1329.01  4947.2 1327.34  4958.1 1321.73  4968.3 1318.99  4984.3 1316.09
  4995.3 1315.27  4995.6 1314.77  4999.1 1314.77  4999.3 1315.27  5014.1 1315.39
  5028.3 1317.13  5141.4  1317.9  5155.5 1319.56  5169.7 1323.25  5183.8 1328.96
  5226.2  1349.1  5240.4 1356.63  5254.5 1360.29  5268.7 1361.47  5282.8 1361.74
#Mann= 3 ,-1 , 0
  4672.7     .12       0  4995.3     .05       0  4999.3     .12       0
Bank Sta=4995.3,4999.3
XS Rating Curve= 0 ,0
Exp/Cntr=0.3,0.1

Type RM Length L Ch R = 1 ,2136    ,245,245,245
BEGIN DESCRIPTION:
Stream0060_DS 4.5
END DESCRIPTION:
XS GIS Cut Line= 3
      2037352.05     13900353.34      2036974.11     13900360.17
      2036748.93     13900547.33
#Sta/Elev= 30
    4622 1360.72    4639 1359.83  4689.1 1351.68  4719.1 1341.95  4739.1 1336.97
  4869.1 1316.99  4909.1 1315.33  4949.1 1316.62  4969.1 1314.42  4977.1 1311.72
  4977.4 1311.22  4981.1 1311.72  4992.2 1313.12  4997.1 1316.33  5007.4 1316.44
  5016.2 1316.63  5109.3 1316.58    5138  1323.5  5144.5 1323.99  5152.3 1327.81
  5158.8 1327.76  5166.6 1332.05  5173.1 1332.89  5187.4 1341.73  5193.9 1342.73
  5201.7 1347.53  5208.2 1347.81  5216.1 1352.43  5251.2  1358.7  5292.8 1359.87
#Mann= 5 ,-1 , 0
    4622     .12       0  4977.1     .05       0  4981.1     .12       0
  5007.4     .07       0  5016.2     .12       0
Bank Sta=4977.1,4981.1
XS Rating Curve= 0 ,0
Exp/Cntr=0.3,0.1

Type RM Length L Ch R = 1 ,1891    ,176,176,176
BEGIN DESCRIPTION:
Stream0060_DS 4.0
END DESCRIPTION:
XS GIS Cut Line= 3
      2037375.04     13900325.02        2037125.       13900175.
      2036974.98     13900074.98
#Sta/Elev= 30
  4708.7 1360.89  4722.4 1359.97  4743.7  1354.6  4753.4 1352.92  4780.7 1340.87
  4790.4 1338.41    4802 1332.42  4811.8 1329.49  4825.4  1323.3    4839 1319.11
  4860.3 1315.05  4897.3 1313.41    4942 1314.55  4970.2 1313.66  4986.7 1312.79
  4997.4 1310.75  5003.3 1310.75  5007.8 1309.48  5011.8 1309.46  5012.1 1308.96
  5015.8 1309.46  5022.8 1312.25  5043.9 1312.77  5058.9 1314.73  5079.9 1320.04
  5100.9 1323.42  5108.5 1327.08    5116 1328.55    5167 1334.71  5180.6 1335.33
#Mann= 4 ,-1 , 0
  4708.7     .12       0  4970.2     .07       0  5011.8     .05       0
  5015.8     .07       0
Bank Sta=5011.8,5015.8
XS Rating Curve= 0 ,0
Exp/Cntr=0.3,0.1

Type RM Length L Ch R = 1 ,1715    ,277,277,277
BEGIN DESCRIPTION:
Stream0060_DS 3.5
END DESCRIPTION:
XS GIS Cut Line= 3
      2037656.96     13900033.99      2037183.19     13900018.97
      2036970.61     13899987.53
#Sta/Elev= 30
    4526  1354.7    4558 1353.47    4568 1352.28    4588 1345.82    4618 1339.23
  4647.4 1334.65    4688 1329.68    4708 1323.84  4728.1 1320.61  4758.1  1320.1
  4778.1 1321.84  4808.1 1322.97  4828.1 1322.26  4838.1 1319.63  4848.1 1315.36
  4858.1 1312.59  4878.1  1311.2  4965.3 1310.51  4970.3 1310.08  4986.2 1306.07
  4986.4 1305.57  4990.2 1306.07  4996.6 1309.55  5014.1 1311.46  5062.6 1312.34
    5079 1313.58  5099.3 1318.14  5127.1 1328.97  5159.9 1334.25  5214.9 1338.87
#Mann= 4 ,-1 , 0
    4526     .12       0  4986.2     .05       0  4990.2     .12       0
  5014.1     .07       0
Bank Sta=4986.2,4990.2
XS Rating Curve= 0 ,0
Exp/Cntr=0.3,0.1

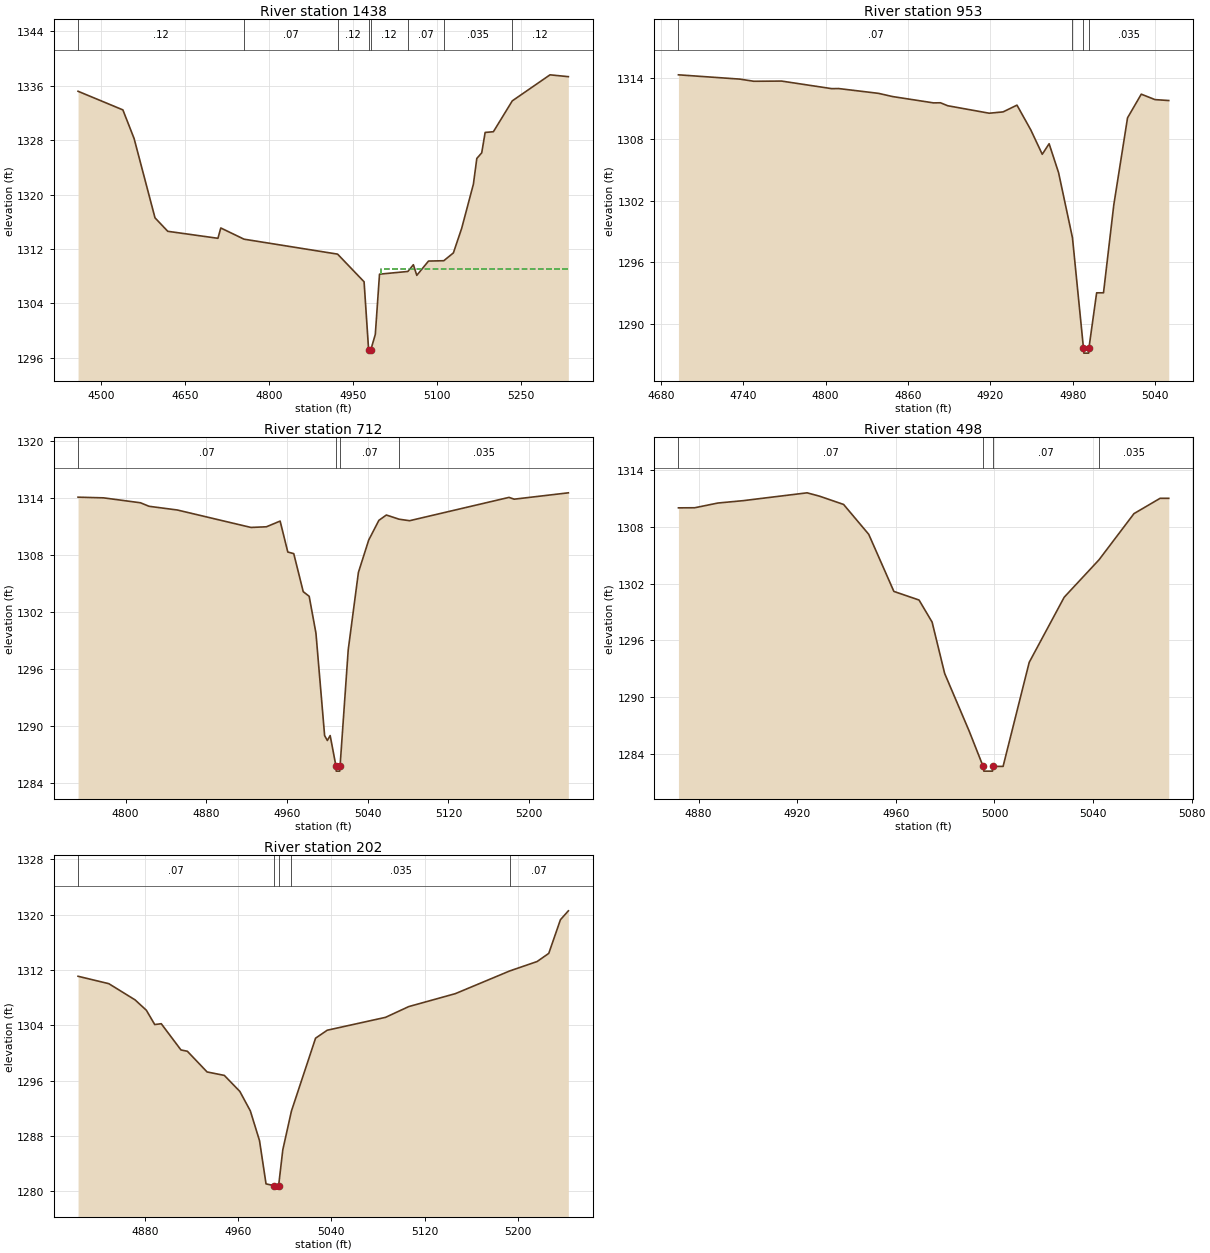
Type RM Length L Ch R = 1 ,1438    ,485,485,485
BEGIN DESCRIPTION:
Stream0060_DS 3.0
END DESCRIPTION:
XS GIS Cut Line= 3
      2037714.88      13899727.8        2037175.       13899775.
      2036899.45     13899966.15
#Sta/Elev= 30
  4458.1  1335.2  4538.3 1332.46  4558.4 1328.24  4595.8 1316.57  4618.6 1314.59
  4708.4 1313.56  4713.5 1315.08  4755.1 1313.43  4922.5 1311.23  4969.9 1307.16
    4978 1297.16  4978.2 1296.66    4982 1297.16    4990 1299.42  4997.5 1308.28
  5048.2 1308.68  5058.1 1309.67  5064.2 1308.11  5085.2 1310.21  5112.5 1310.26
  5129.7 1311.41  5144.6 1315.05  5165.5 1321.53  5171.6 1325.31  5180.4 1326.14
  5186.5 1329.14  5201.3 1329.25  5235.1 1333.79  5302.6 1337.62  5335.4 1337.35
#Mann= 8 ,-1 , 0
  4458.1     .12       0  4755.1     .07       0  4922.5     .12       0
    4978     .05       0    4982     .12       0  5048.2     .07       0
  5112.5    .035       0  5235.1     .12       0
#XS Ineff= 2 , 0
       0                    5000       0 1308.98
Permanent Ineff=
       F       F
Bank Sta=4978,4982
XS Rating Curve= 0 ,0
Exp/Cntr=0.3,0.1

Type RM Length L Ch R = 1 ,953     ,241,241,241
BEGIN DESCRIPTION:
Stream0060_DS 2.0
END DESCRIPTION:
XS GIS Cut Line= 3
      2037379.45     13899285.48        2037075.       13899325.
      2037025.01       13899325.
#Sta/Elev= 30
  4692.9 1314.29  4737.7 1313.87  4747.8 1313.66    4768 1313.68  4804.5 1312.94
  4809.5 1312.95  4838.6 1312.48  4848.7 1312.17  4878.6 1311.55  4883.7 1311.56
    4889 1311.27  4919.2 1310.54  4929.3 1310.67  4939.4 1311.33  4949.5  1308.9
  4957.8 1306.53  4962.8 1307.56  4969.7 1304.73  4979.8 1298.38  4987.8 1287.61
  4988.1 1287.11  4991.6 1287.11  4991.8 1287.61  4997.4    1293  5002.4    1293
  5009.9 1301.59  5019.9 1310.09  5029.9  1312.4  5039.9 1311.87  5049.9 1311.78
#Mann= 4 ,-1 , 0
  4692.9     .07       0  4979.8    .035       0  4987.8    .035       0
  4991.8    .035       0
Bank Sta=4987.8,4991.8
XS Rating Curve= 0 ,0
Exp/Cntr=0.3,0.1

Type RM Length L Ch R = 1 ,712     ,214,214,214
BEGIN DESCRIPTION:
Stream0060_DS 1.5
END DESCRIPTION:
XS GIS Cut Line= 3
      2037334.61     13899231.51      2037125.41       13899100.
      2036889.77      13899139.3
#Sta/Elev= 30
  4752.9 1314.12  4778.2 1314.05  4814.8 1313.53  4823.3 1313.16  4851.3 1312.77
  4924.3 1310.93  4939.6    1311  4953.2  1311.6  4960.8 1308.34  4966.7 1308.17
  4976.1 1304.16    4982 1303.67  4988.7 1299.79  4997.3 1288.99    5000 1288.47
  5002.8 1288.99  5008.6 1285.74  5008.8 1285.24  5012.3 1285.24  5012.6 1285.74
  5020.7 1298.03  5030.8 1306.19    5041  1309.6  5051.1 1311.68  5058.5 1312.24
  5071.1  1311.8  5081.5 1311.64  5180.1  1314.1  5185.2 1313.91  5238.9 1314.58
#Mann= 4 ,-1 , 0
  4752.9     .07       0  5008.6     .05       0  5012.6     .07       0
  5071.1    .035       0
Bank Sta=5008.6,5012.6
XS Rating Curve= 0 ,0
Exp/Cntr=0.3,0.1

Type RM Length L Ch R = 1 ,498     ,296,296,296
BEGIN DESCRIPTION:
Stream0060_DS 1.0
END DESCRIPTION:
XS GIS Cut Line= 3
      2037150.65     13898899.55        2037025.       13898925.
      2036975.01     13898974.99
#Sta/Elev= 25
  4871.8 1310.03  4878.4 1310.04  4887.8 1310.54    4898 1310.79    4924 1311.62
  4929.1 1311.26  4938.8 1310.39    4949 1307.23  4959.2 1301.19  4969.4 1300.28
  4974.7 1297.95  4979.8 1292.51  4989.8 1286.38  4995.4 1282.68  4995.7 1282.18
  4999.2 1282.18  4999.4 1282.68    5000 1282.68  5003.5 1282.68  5014.1 1293.69
  5028.3 1300.58  5042.4 1304.53  5056.6 1309.42  5067.2 1311.04  5070.7 1311.04
#Mann= 4 ,-1 , 0
  4871.8     .07       0  4995.4     .05       0  4999.4     .07       0
  5042.4    .035       0
Bank Sta=4995.4,4999.4
XS Rating Curve= 0 ,0
Exp/Cntr=0.3,0.1

Type RM Length L Ch R = 1 ,202     ,0,0,0
BEGIN DESCRIPTION:
Stream0060_DS 0.0
END DESCRIPTION:
XS GIS Cut Line= 3
      2037079.74     13898857.62      2037001.47     13898698.53
      2036758.18     13898691.49
#Sta/Elev= 30
  4822.7  1311.1  4849.1 1310.03  4871.6 1307.69  4881.3 1306.19  4888.5 1304.12
  4894.1 1304.24    4911 1300.45  4916.5 1300.26  4933.4 1297.27  4948.2 1296.77
  4961.5 1294.46  4970.5 1291.65  4978.4 1287.34    4984 1281.09  4990.8 1280.83
    4991 1280.33  4994.5 1280.33  4994.8 1280.83  4998.4 1286.03  5005.8 1291.62
  5026.5 1302.15  5036.5  1303.3  5086.5 1305.16  5106.5 1306.72  5146.5 1308.59
  5193.1 1311.87  5216.6 1313.23  5226.6 1314.41  5236.6 1319.27  5243.4 1320.56
#Mann= 5 ,-1 , 0
  4822.7     .07       0  4990.8     .05       0  4994.8     .07       0
  5005.8    .035       0  5193.1     .07       0
Bank Sta=4990.8,4994.8
XS Rating Curve= 0 ,0
Exp/Cntr=0.3,0.1

Chan Stop Cuts=-1
Use User Specified Reach Order=0
Composite Channel Slope=5