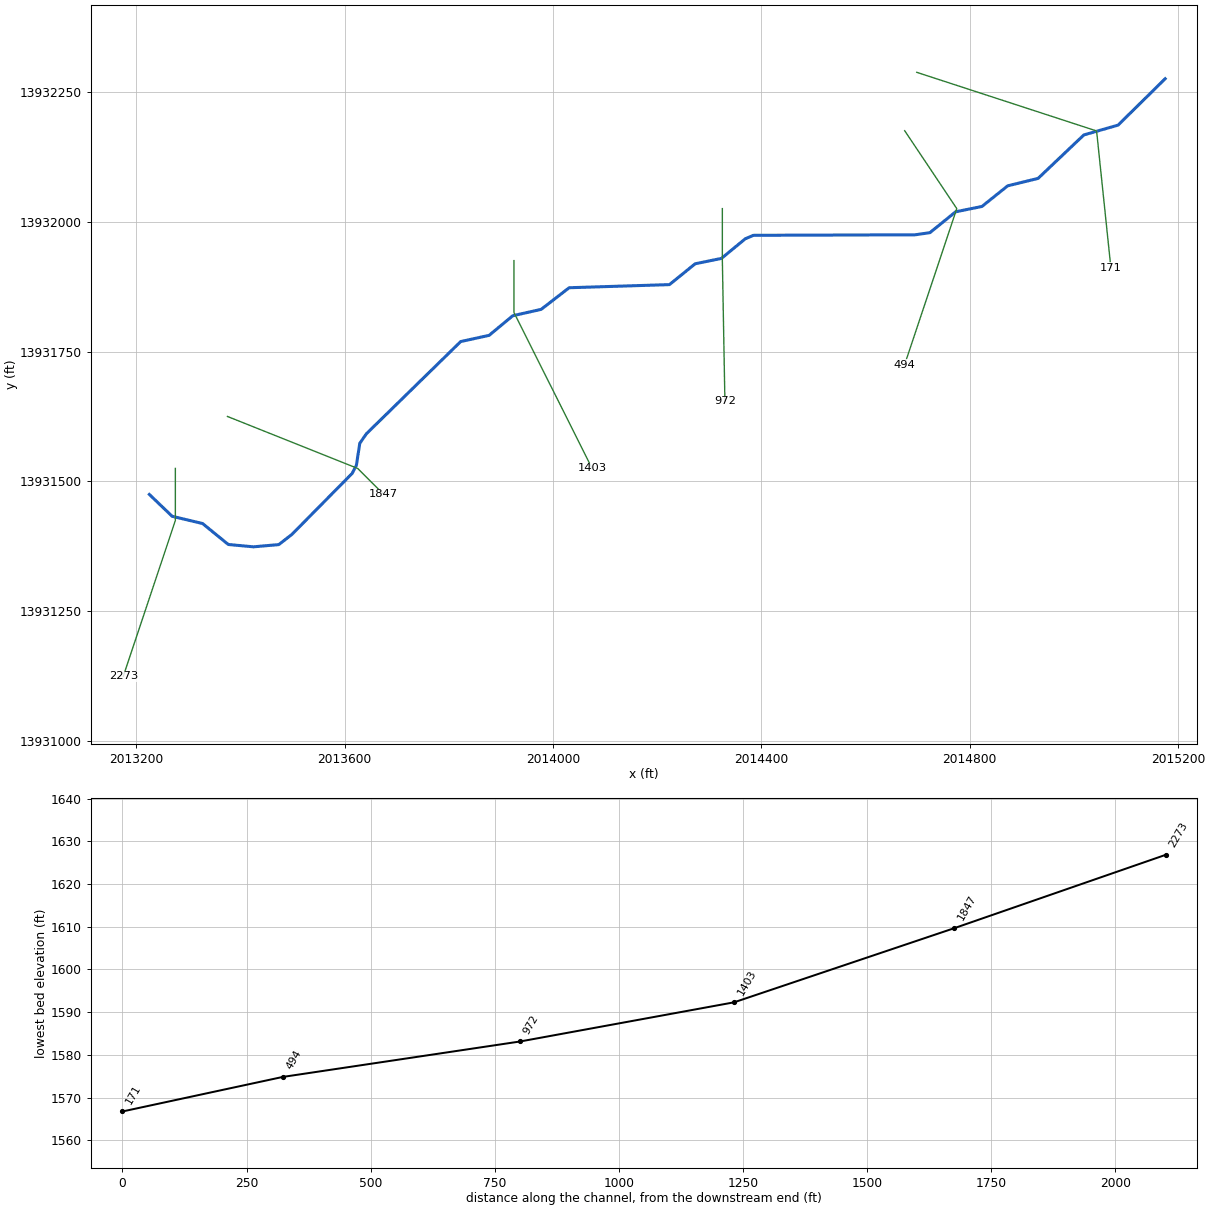
--- Stream0061_DS.prj (project) ---

Proj Title=Stream0061_DS Base Level Engineering
Current Plan=p01
Default Exp/Contr=0.3,0.1
English Units
Geom File=g01
Flow File=f01
Plan File=p01
BEGIN DESCRIPTION:
Stream0061_DS
END DESCRIPTION:

--- Stream0061_DS.p01 (plan) ---

Plan Title=Multiple Run
Short Identifier=Multiple
Geom File=g01
Flow File=f01
Subcritical Flow
K Sum by GR= 0
Std Step Tol= 0.01
Critical Tol= 0.01
Num of Std Step Trials= 20
Max Error Tol= 0.3
Flow Tol Ratio= 0.001
Split Flow NTrial= 30
Split Flow Tol= 0.02
Split Flow Ratio= 0.02
Log Output Level= 0
Friction Slope Method= 1
Unsteady Friction Slope Method= 2
Unsteady Bridges Friction Slope Method= 1
Parabolic Critical Depth
Global Vel Dist=  1 , 1 , 1
Global Log Level= 0
CheckData=True
Encroach Param= -1, 0, 0, 0
BEGIN DESCRIPTION:
Multiple Run
END DESCRIPTION:

--- Stream0061_DS.f01 (steady flow) ---

Flow Title=Multiple
Number of Profiles=7
Profile Names=10-year,25-year,50-year,1pct_min,100-year,1pct_plu,500-year
River Rch & RM= Stream0061_DS,Reach-1,2273
     643    1081    1496    1007    2009    4009    3591
River Rch & RM= Stream0061_DS,Reach-1,1847
    1055    1829    2582    1770    3532    7047    6555
Boundary for River Rch & Prof#=Stream0061_DS,Reach-1,1
Up Type=0
Dn Type=3
Dn Slope=0.005
Boundary for River Rch & Prof#=Stream0061_DS,Reach-1,2
Up Type=0
Dn Type=3
Dn Slope=0.005
Boundary for River Rch & Prof#=Stream0061_DS,Reach-1,3
Up Type=0
Dn Type=3
Dn Slope=0.005
Boundary for River Rch & Prof#=Stream0061_DS,Reach-1,4
Up Type=0
Dn Type=3
Dn Slope=0.005
Boundary for River Rch & Prof#=Stream0061_DS,Reach-1,5
Up Type=0
Dn Type=3
Dn Slope=0.005
Boundary for River Rch & Prof#=Stream0061_DS,Reach-1,6
Up Type=0
Dn Type=3
Dn Slope=0.005
Boundary for River Rch & Prof#=Stream0061_DS,Reach-1,7
Up Type=0
Dn Type=3
Dn Slope=0.005

--- Stream0061_DS.g01 (geometry) ---

Geom Title=Existing Conditions

River Reach=Stream0061_DS,Reach-1
Reach XY= 30
      2013225.00     13931475.00      2013268.85     13931432.91
      2013327.22     13931418.97      2013376.58     13931378.66
      2013425.01     13931374.15      2013473.50     13931378.46
      2013498.52     13931397.84      2013614.22     13931515.32
      2013622.47     13931531.05      2013628.98     13931573.35
      2013641.65     13931591.67      2013822.70     13931769.17
      2013877.19     13931781.10      2013922.80     13931818.92
      2013977.18     13931831.12      2014030.93     13931872.76
      2014223.45     13931878.75      2014272.82     13931918.88
      2014323.26     13931929.19      2014368.92     13931966.91
      2014384.65     13931973.64      2014695.15     13931974.64
      2014723.45     13931978.75      2014772.82     13932018.88
      2014823.28     13932029.16      2014872.81     13932068.90
      2014931.05     13932083.16      2015018.96     13932166.83
      2015084.70     13932185.72      2015175.00     13932275.00

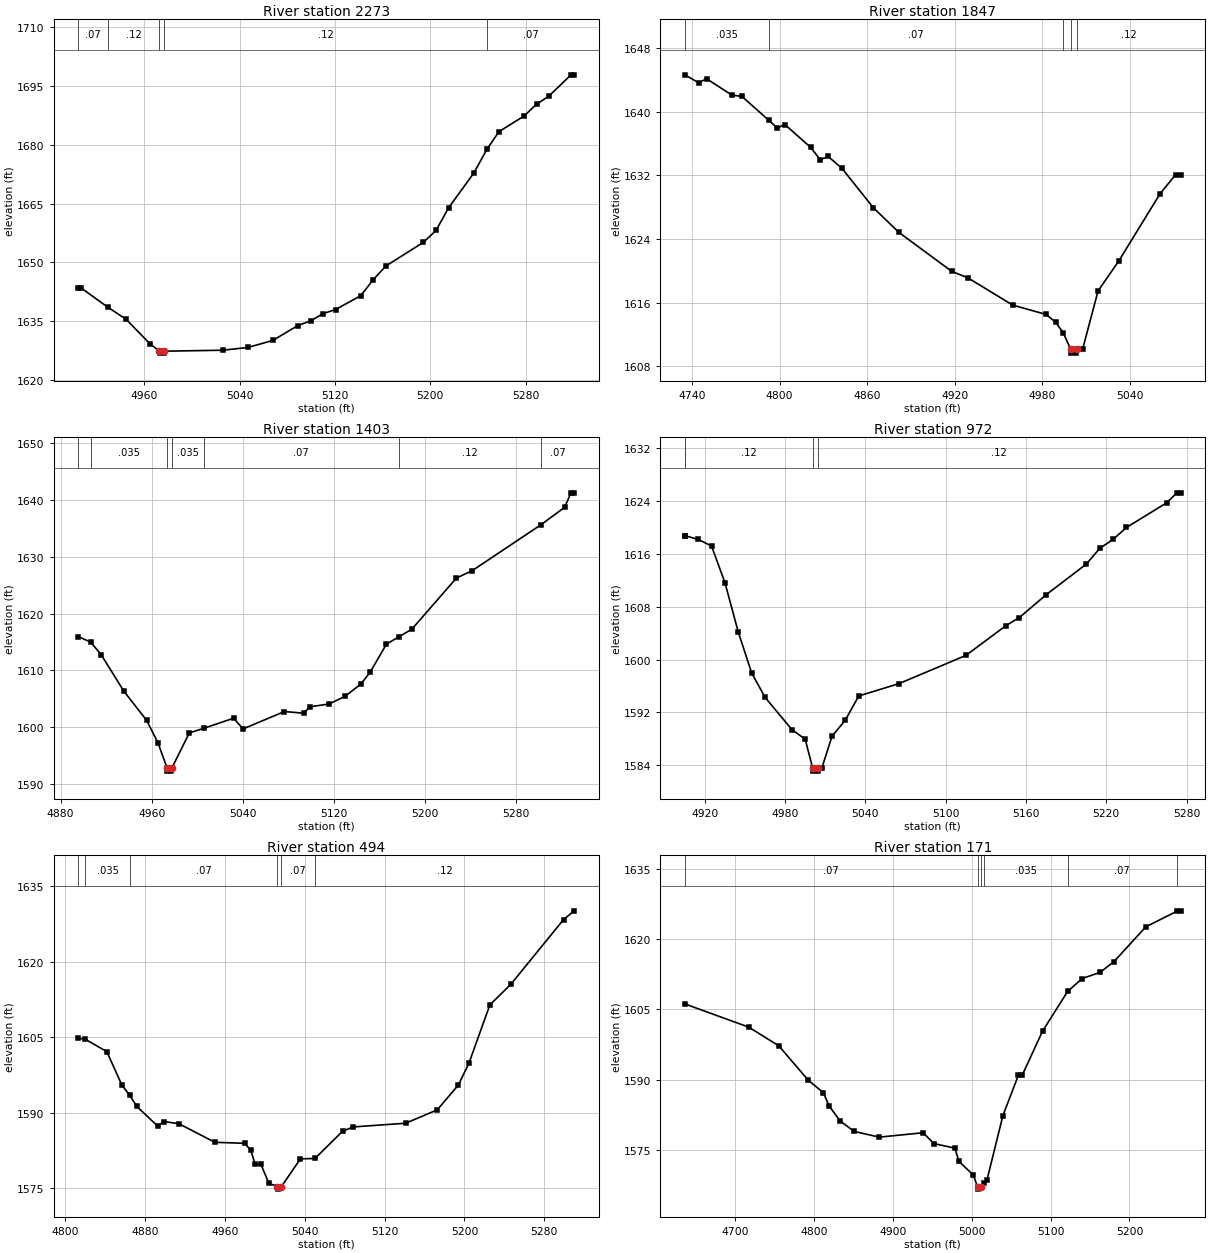
Type RM Length L Ch R = 1,2273,426,426,426
BEGIN DESCRIPTION:
Stream0061_DS 5.0
END DESCRIPTION:
XS GIS Cut Line= 3
      2013275.00     13931524.99      2013275.00     13931425.00
      2013175.01     13931125.02
#Sta/Elev= 30
  4904.6 1643.45  4907.1 1643.45  4929.1 1638.63  4944.6 1635.52  4964.6 1629.27
  4972.6 1627.35  4972.8 1626.85  4976.3 1626.85  4976.6 1627.35  5025.7 1627.59
  5046.8 1628.29  5067.8 1630.08  5088.9 1633.90  5099.5 1635.08  5110.0 1636.93
  5120.5 1637.98  5141.6 1641.49  5152.2 1645.62  5162.7 1649.09  5194.3 1655.15
  5204.9 1658.19  5215.4 1663.97  5236.5 1672.80  5247.5 1678.85  5257.6 1683.39
  5278.7 1687.38  5289.2 1690.39  5299.7 1692.52  5318.2 1697.91  5320.8 1697.91
#Mann=5,-1,0
  4904.6    0.07       0  4929.1    0.12       0  4972.6    0.05       0
  4976.6    0.12       0  5247.5    0.07       0
Bank Sta=4972.6,4976.6
Exp/Cntr=0.3,0.1

Type RM Length L Ch R = 1,1847,444,444,444
BEGIN DESCRIPTION:
Stream0061_DS 4.0
END DESCRIPTION:
XS GIS Cut Line= 3
      2013374.96     13931625.02      2013625.00     13931525.00
      2013674.99     13931475.01
#Sta/Elev= 30
  4735.0 1644.64  4744.5 1643.65  4749.9 1644.15  4767.4 1642.08  4774.1 1641.94
  4792.7 1638.91  4798.3 1637.97  4803.7 1638.38  4821.2 1635.54  4827.9 1633.98
  4833.3 1634.38  4842.8 1632.88  4864.3 1627.94  4881.8 1624.84  4918.1 1619.94
  4928.9 1619.15  4959.9 1615.70  4982.8 1614.53  4989.5 1613.52  4994.6 1612.18
  4999.6 1610.17  4999.9 1609.67  5003.4 1609.67  5003.6 1610.17  5007.8 1610.17
  5018.4 1617.49  5032.6 1621.25  5060.9 1629.70  5071.5 1632.08  5075.0 1632.08
#Mann=5,-1,0
  4735.0   0.035       0  4792.7    0.07       0  4994.6    0.12       0
  4999.6    0.05       0  5003.6    0.12       0
Bank Sta=4999.6,5003.6
Exp/Cntr=0.3,0.1

Type RM Length L Ch R = 1,1403,431,431,431
BEGIN DESCRIPTION:
Stream0061_DS 3.0
END DESCRIPTION:
XS GIS Cut Line= 3
      2013925.00     13931924.97      2013925.00     13931825.00
      2014075.01     13931524.98
#Sta/Elev= 30
  4895.5 1615.96  4906.3 1615.00  4915.5 1612.80  4935.5 1606.35  4955.5 1601.22
  4965.5 1597.24  4973.5 1592.79  4973.7 1592.29  4977.2 1592.29  4977.5 1592.79
  4993.0 1599.02  5005.6 1599.82  5031.8 1601.60  5040.2 1599.72  5076.5 1602.78
  5093.3 1602.48  5098.9 1603.61  5115.7 1604.10  5129.6 1605.45  5143.6 1607.60
  5152.0 1609.77  5166.0 1614.62  5176.9 1615.92  5188.3 1617.25  5227.5 1626.26
  5241.4 1627.57  5301.8 1635.65  5322.5 1638.70  5328.1 1641.26  5330.9 1641.26
#Mann=7,-1,0
  4895.5    0.07       0  4906.3   0.035       0  4973.5   0.035       0
  4977.5   0.035       0  5005.6    0.07       0  5176.9    0.12       0
  5301.8    0.07       0
Bank Sta=4973.5,4977.5
Exp/Cntr=0.3,0.1

Type RM Length L Ch R = 1,972,478,478,478
BEGIN DESCRIPTION:
Stream0061_DS 2.0
END DESCRIPTION:
XS GIS Cut Line= 3
      2014325.00     13932025.04      2014325.00     13931925.00
      2014329.90     13931654.49
#Sta/Elev= 30
  4905.0 1618.77  4905.1 1618.77  4915.0 1618.21  4925.0 1617.20  4935.0 1611.66
  4945.0 1604.15  4955.0 1597.98  4965.0 1594.29  4985.0 1589.42  4995.0 1587.95
  5000.5 1583.62  5000.8 1583.12  5004.3 1583.12  5004.5 1583.62  5007.5 1583.62
  5015.0 1588.38  5025.0 1590.85  5035.0 1594.50  5065.1 1596.37  5115.1 1600.64
  5145.1 1605.16  5155.1 1606.38  5175.1 1609.83  5205.1 1614.47  5215.1 1616.84
  5225.1 1618.21  5235.1 1620.01  5265.1 1623.74  5272.8 1625.26  5275.6 1625.26
#Mann=4,-1,0
  4905.0    0.07       0  4905.1    0.12       0  5000.5    0.05       0
  5004.5    0.12       0
Bank Sta=5000.5,5004.5
Exp/Cntr=0.3,0.1

Type RM Length L Ch R = 1,494,323,323,323
BEGIN DESCRIPTION:
Stream0061_DS 1.0
END DESCRIPTION:
XS GIS Cut Line= 3
      2014675.02     13932174.97      2014775.00     13932025.00
      2014674.99     13931724.97
#Sta/Elev= 30
  4813.4 1604.78  4820.4 1604.58  4841.9 1602.14  4856.9 1595.54  4864.9 1593.42
  4871.9 1591.26  4893.0 1587.31  4899.0 1588.24  4914.0 1587.83  4950.1 1584.12
  4980.1 1583.92  4986.1 1582.51  4990.6 1579.72  4996.3 1579.72  5004.2 1575.98
  5012.7 1575.32  5013.0 1574.82  5016.7 1575.32  5035.8 1580.83  5050.4 1580.91
  5078.0 1586.32  5088.5 1587.17  5141.2 1587.91  5172.8 1590.57  5193.9 1595.48
  5204.5 1599.81  5225.5 1611.42  5246.6 1615.53  5299.3 1628.37  5309.9 1630.10
#Mann=6,-1,0
  4813.4    0.07       0  4820.4   0.035       0  4864.9    0.07       0
  5012.7    0.05       0  5016.7    0.07       0  5050.4    0.12       0
Bank Sta=5012.7,5016.7
Exp/Cntr=0.3,0.1

Type RM Length L Ch R = 1,171,0,0,0
BEGIN DESCRIPTION:
Stream0061_DS 0.0
END DESCRIPTION:
XS GIS Cut Line= 3
      2014698.08     13932287.33      2015043.40     13932174.46
      2015070.83     13931911.09
#Sta/Elev= 30
  4636.7 1606.17  4717.6 1601.23  4755.7 1597.26  4792.8 1589.98  4812.3 1587.25
  4819.4 1584.48  4833.3 1581.26  4851.3 1579.01  4883.2 1577.80  4938.6 1578.74
  4952.2 1576.43  4978.8 1575.46  4984.0 1572.63  5002.2 1569.73  5007.5 1567.23
  5007.8 1566.73  5011.5 1567.23  5016.2 1568.12  5019.6 1568.76  5039.7 1582.40
  5059.2 1590.94  5064.2 1591.02  5089.9 1600.37  5121.6 1608.82  5140.2 1611.58
  5162.8 1612.88  5180.4 1615.18  5220.7 1622.58  5259.6 1625.86  5264.8 1625.99
#Mann=6,-1,0
  4636.7    0.07       0  5007.5    0.05       0  5011.5    0.07       0
  5016.2   0.035       0  5121.6    0.07       0  5259.6    0.12       0
Bank Sta=5007.5,5011.5
Exp/Cntr=0.3,0.1

Chan Stop Cuts=-1