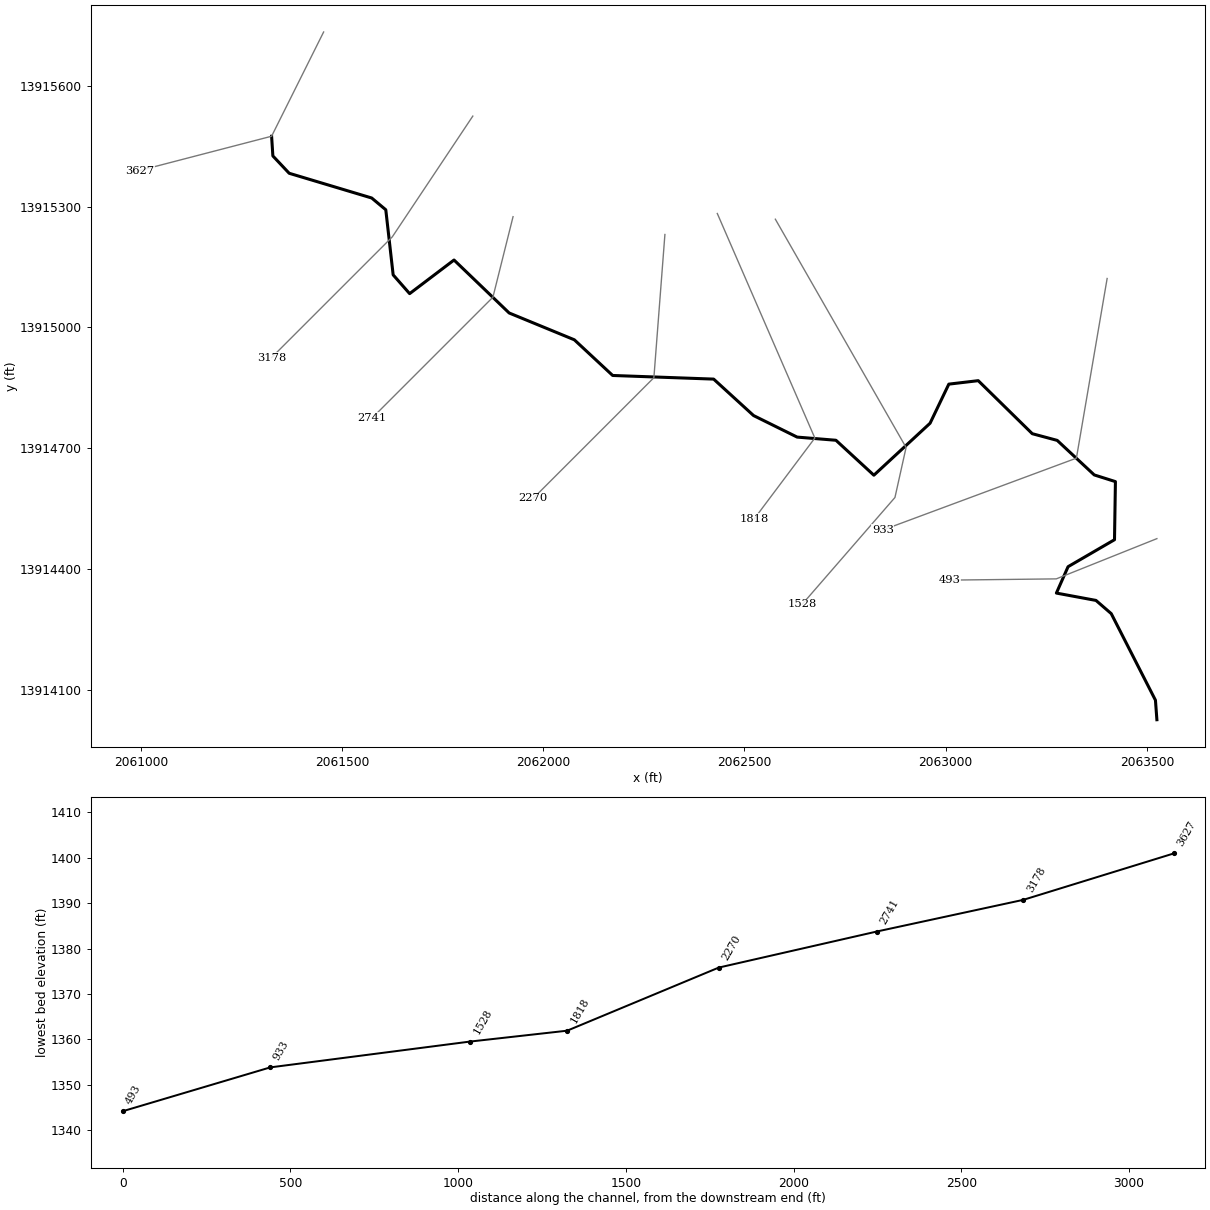
--- Stream0062_DS.prj (project) ---

Proj Title=Stream0062_DS Base Level Engineering
Current Plan=p01
Default Exp/Contr=0.3,0.1
English Units
Geom File=g01
Flow File=f01
Plan File=p01
BEGIN DESCRIPTION:
Stream0062_DS
END DESCRIPTION:

--- Stream0062_DS.p01 (plan) ---

Plan Title=Multiple Run
Short Identifier=Multiple
Geom File=g01
Flow File=f01
Subcritical Flow
K Sum by GR= 0
Std Step Tol= 0.01
Critical Tol= 0.01
Num of Std Step Trials= 20
Max Error Tol= 0.3
Flow Tol Ratio= 0.001
Split Flow NTrial= 30
Split Flow Tol= 0.02
Split Flow Ratio= 0.02
Log Output Level= 0
Friction Slope Method= 1
Unsteady Friction Slope Method= 2
Unsteady Bridges Friction Slope Method= 1
Parabolic Critical Depth
Global Vel Dist=  1 , 1 , 1
Global Log Level= 0
CheckData=True
Encroach Param= -1, 0, 0, 0
BEGIN DESCRIPTION:
Multiple Run
END DESCRIPTION:

--- Stream0062_DS.f01 (steady flow) ---

Flow Title=Multiple
Number of Profiles=7
Profile Names=10-year,25-year,50-year,1pct_min,100-year,1pct_plu,500-year
River Rch & RM= Stream0062_DS,Reach-1,3627
     362     577     771     503    1003    2001    1675
River Rch & RM= Stream0062_DS,Reach-1,3178
     470     758    1020     669    1334    2662    2256
Boundary for River Rch & Prof#=Stream0062_DS,Reach-1,1
Up Type=0
Dn Type=3
Dn Slope=0.005
Boundary for River Rch & Prof#=Stream0062_DS,Reach-1,2
Up Type=0
Dn Type=3
Dn Slope=0.005
Boundary for River Rch & Prof#=Stream0062_DS,Reach-1,3
Up Type=0
Dn Type=3
Dn Slope=0.005
Boundary for River Rch & Prof#=Stream0062_DS,Reach-1,4
Up Type=0
Dn Type=3
Dn Slope=0.005
Boundary for River Rch & Prof#=Stream0062_DS,Reach-1,5
Up Type=0
Dn Type=3
Dn Slope=0.005
Boundary for River Rch & Prof#=Stream0062_DS,Reach-1,6
Up Type=0
Dn Type=3
Dn Slope=0.005
Boundary for River Rch & Prof#=Stream0062_DS,Reach-1,7
Up Type=0
Dn Type=3
Dn Slope=0.005

--- Stream0062_DS.g01 (geometry) ---

Geom Title=Existing Conditions

River Reach=Stream0062_DS,Reach-1
Reach XY= 30
      2061325.00     13915475.00      2061328.14     13915426.03
      2061368.69     13915382.95      2061573.75     13915321.49
      2061608.76     13915292.22      2061627.07     13915130.45
      2061668.00     13915083.83      2061778.33     13915167.39
      2061915.32     13915035.77      2062077.29     13914969.15
      2062172.55     13914880.47      2062423.53     13914871.45
      2062522.71     13914780.85      2062630.97     13914727.33
      2062727.43     13914719.45      2062821.67     13914632.60
      2062961.36     13914761.80      2063007.95     13914858.95
      2063081.03     13914867.55      2063215.32     13914735.78
      2063277.28     13914719.13      2063369.31     13914633.32
      2063421.94     13914616.70      2063419.65     13914472.31
      2063304.28     13914405.26      2063275.26     13914339.70
      2063373.63     13914321.45      2063411.55     13914288.63
      2063521.40     13914073.51      2063525.00     13914025.00

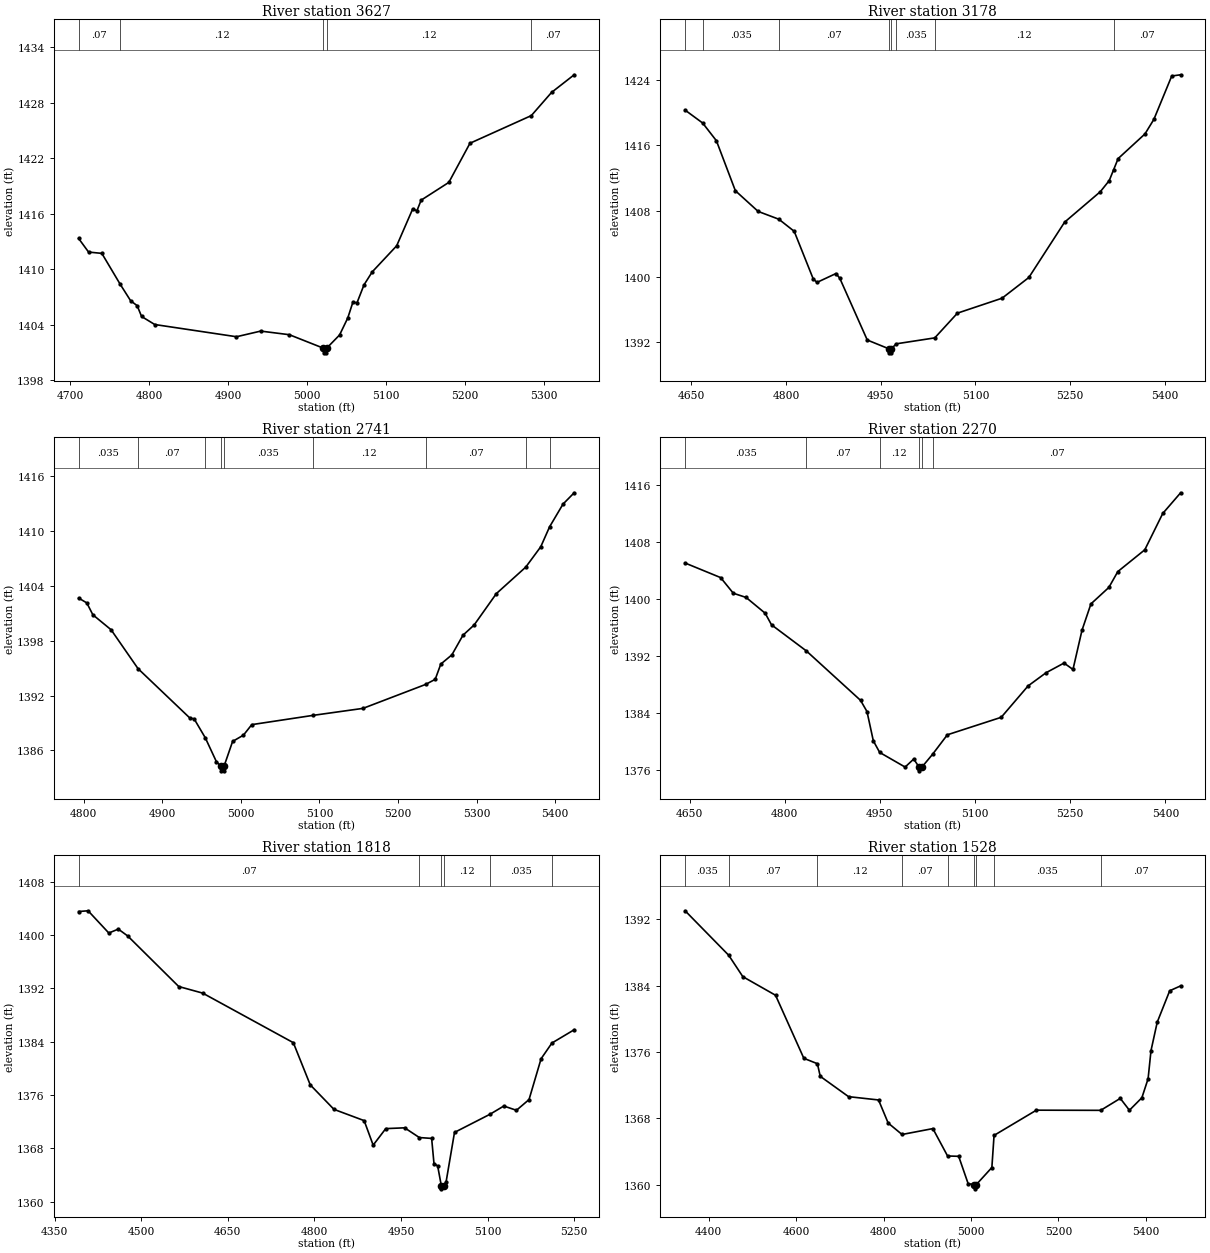
Type RM Length L Ch R = 1,3627,449,449,449
BEGIN DESCRIPTION:
Stream0062_DS 7.0
END DESCRIPTION:
XS GIS Cut Line= 3
      2061454.28     13915734.03      2061325.00     13915475.00
      2060997.19     13915389.79
#Sta/Elev= 30
  4710.5 1413.33  4723.1 1411.86  4739.9 1411.72  4763.2 1408.38  4776.5 1406.59
  4784.7 1406.07  4790.3 1404.90  4807.0 1404.03  4910.6 1402.71  4941.3 1403.32
  4977.6 1402.93  5020.9 1401.47  5021.1 1400.97  5024.6 1400.97  5024.9 1401.47
  5041.3 1402.90  5051.7 1404.74  5058.2 1406.45  5063.4 1406.38  5072.3 1408.32
  5082.7 1409.72  5113.7 1412.54  5134.1 1416.54  5139.3 1416.31  5144.7 1417.47
  5179.8 1419.39  5206.6 1423.62  5284.4 1426.61  5310.0 1429.11  5338.7 1431.02
#Mann=5,-1,0
  4710.5    0.07       0  4763.2    0.12       0  5020.9    0.05       0
  5024.9    0.12       0  5284.4    0.07       0
Bank Sta=5020.9,5024.9
Exp/Cntr=0.3,0.1

Type RM Length L Ch R = 1,3178,437,437,437
BEGIN DESCRIPTION:
Stream0062_DS 6.0
END DESCRIPTION:
XS GIS Cut Line= 3
      2061825.01     13915525.02      2061625.00     13915225.00
      2061325.03     13914925.03
#Sta/Elev= 30
  4640.1 1420.28  4667.9 1418.71  4689.7 1416.55  4719.7 1410.47  4755.8 1407.95
  4788.6 1407.00  4812.9 1405.53  4842.9 1399.76  4848.9 1399.31  4879.0 1400.39
  4885.0 1399.83  4928.6 1392.30  4962.6 1391.24  4962.9 1390.74  4966.4 1390.74
  4966.6 1391.24  4974.7 1391.84  5035.5 1392.56  5071.4 1395.57  5142.1 1397.39
  5184.5 1399.91  5241.1 1406.64  5297.7 1410.35  5311.8 1411.70  5318.9 1413.05
  5325.9 1414.38  5368.4 1417.38  5382.5 1419.15  5410.8 1424.43  5424.9 1424.58
#Mann=8,-1,0
  4640.1    0.12       0  4667.9   0.035       0  4788.6    0.07       0
  4962.6   0.035       0  4966.6    0.07       0  4974.7   0.035       0
  5035.5    0.12       0  5318.9    0.07       0
Bank Sta=4962.6,4966.6
Exp/Cntr=0.3,0.1

Type RM Length L Ch R = 1,2741,471,471,471
BEGIN DESCRIPTION:
Stream0062_DS 5.0
END DESCRIPTION:
XS GIS Cut Line= 3
      2061925.01     13915275.05      2061875.00     13915075.00
      2061574.98     13914774.98
#Sta/Elev= 30
  4793.6 1402.68  4804.0 1402.15  4811.7 1400.85  4834.9 1399.21  4869.2 1394.95
  4935.4 1389.52  4940.5 1389.46  4954.8 1387.37  4968.9 1384.76  4974.6 1384.26
  4974.9 1383.76  4978.4 1383.76  4978.6 1384.26  4989.5 1386.98  5003.3 1387.67
  5013.9 1388.82  5091.5 1389.83  5155.4 1390.60  5235.0 1393.22  5247.3 1393.78
  5254.4 1395.45  5268.5 1396.46  5282.6 1398.61  5296.8 1399.73  5325.1 1403.17
  5362.5 1406.07  5381.6 1408.30  5392.8 1410.48  5409.9 1412.97  5424.1 1414.21
#Mann=9,-1,0
  4793.6   0.035       0  4869.2    0.07       0  4954.8   0.035       0
  4974.6   0.035       0  4978.6   0.035       0  5091.5    0.12       0
  5235.0    0.07       0  5362.5    0.12       0  5392.8    0.07       0
Bank Sta=4974.6,4978.6
Exp/Cntr=0.3,0.1

Type RM Length L Ch R = 1,2270,452,452,452
BEGIN DESCRIPTION:
Stream0062_DS 4.0
END DESCRIPTION:
XS GIS Cut Line= 3
      2062302.39     13915230.82      2062275.00     13914875.00
      2061975.03     13914575.03
#Sta/Elev= 30
  4643.0 1405.05  4699.0 1403.00  4719.0 1400.80  4739.1 1400.21  4769.2 1397.99
  4779.2 1396.36  4834.1 1392.69  4919.6 1385.73  4929.7 1384.16  4939.7 1380.04
  4949.7 1378.41  4989.8 1376.35  5003.4 1377.48  5012.0 1376.32  5012.3 1375.82
  5016.0 1376.32  5033.0 1378.14  5056.4 1380.89  5141.3 1383.35  5183.7 1387.77
  5212.0 1389.62  5240.3 1390.98  5254.4 1390.08  5268.6 1395.59  5282.7 1399.30
  5311.0 1401.62  5325.1 1403.85  5367.6 1406.91  5395.9 1412.02  5424.1 1414.93
#Mann=6,-1,0
  4643.0   0.035       0  4834.1    0.07       0  4949.7    0.12       0
  5012.0    0.05       0  5016.0    0.12       0  5033.0    0.07       0
Bank Sta=5012,5016
Exp/Cntr=0.3,0.1

Type RM Length L Ch R = 1,1818,290,290,290
BEGIN DESCRIPTION:
Stream0062_DS 3.0
END DESCRIPTION:
XS GIS Cut Line= 3
      2062432.59     13915282.97      2062675.00     13914725.00
      2062524.97     13914524.96
#Sta/Elev= 30
  4391.7 1403.55  4408.1 1403.66  4444.0 1400.32  4460.4 1400.91  4476.7 1399.88
  4565.1 1392.29  4606.6 1391.30  4763.6 1383.86  4792.9 1377.53  4834.0 1373.85
  4886.3 1372.16  4901.9 1368.48  4923.7 1370.96  4956.4 1371.08  4981.9 1369.62
  5003.2 1369.49  5007.3 1365.68  5013.6 1365.37  5019.9 1362.42  5020.2 1361.92
  5023.9 1362.42  5028.2 1362.94  5042.8 1370.39  5104.4 1373.12  5128.2 1374.35
  5150.1 1373.71  5171.9 1375.32  5192.8 1381.45  5211.6 1383.81  5250.1 1385.80
#Mann=6,-1,0
  4391.7    0.07       0  4981.9    0.12       0  5019.9    0.05       0
  5023.9    0.12       0  5104.4   0.035       0  5211.6    0.07       0
Bank Sta=5019.9,5023.9
Exp/Cntr=0.3,0.1

Type RM Length L Ch R = 1,1528,595,595,595
BEGIN DESCRIPTION:
Stream0062_DS 2.5
END DESCRIPTION:
XS GIS Cut Line= 4
      2062576.85     13915268.79      2062901.73     13914701.53
      2062874.06     13914577.25      2062643.27     13914311.50
#Sta/Elev= 30
  4346.3 1393.03  4446.0 1387.67  4478.3 1385.09  4553.1 1382.85  4617.8 1375.25
  4648.8 1374.60  4655.3 1373.08  4720.0 1370.63  4788.6 1370.23  4810.6 1367.45
  4842.3 1366.07  4912.8 1366.78  4946.4 1363.48  4971.8 1363.44  4993.4 1360.15
  5007.9 1360.02  5008.1 1359.52  5011.9 1360.02  5047.7 1362.09  5052.7 1365.96
  5149.5 1369.00  5296.5 1368.98  5341.3 1370.42  5362.2 1368.99  5390.7 1370.50
  5404.9 1372.79  5411.5 1376.17  5425.8 1379.61  5454.3 1383.39  5479.3 1383.98
#Mann=9,-1,0
  4346.3   0.035       0  4446.0    0.07       0  4648.8    0.12       0
  4842.3    0.07       0  4946.4    0.12       0  5007.9    0.05       0
  5011.9    0.12       0  5052.7   0.035       0  5296.5    0.07       0
Bank Sta=5007.9,5011.9
Exp/Cntr=0.3,0.1

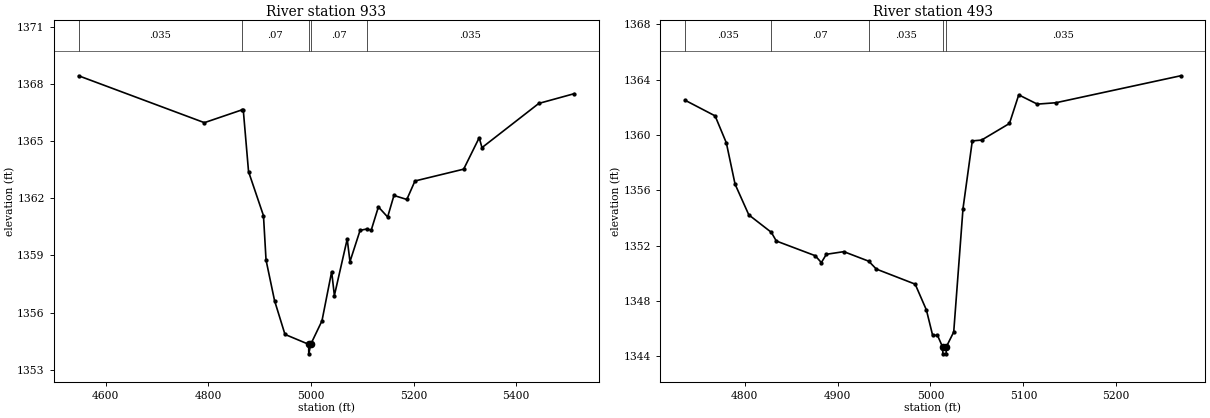
Type RM Length L Ch R = 1,933,440,440,440
BEGIN DESCRIPTION:
Stream0062_DS 2.0
END DESCRIPTION:
XS GIS Cut Line= 3
      2063401.35     13915121.45      2063325.00     13914675.00
      2062844.10     13914496.48
#Sta/Elev= 30
  4547.1 1368.43  4792.2 1365.97  4865.3 1366.64  4868.1 1366.61  4878.3 1363.40
  4907.4 1361.09  4912.4 1358.76  4929.0 1356.63  4949.3 1354.86  4995.5 1354.34
  4995.7 1353.84  4999.5 1354.34  5021.4 1355.57  5040.3 1358.15  5045.6 1356.90
  5070.6 1359.86  5076.0 1358.68  5095.7 1360.32  5108.7 1360.39  5117.4 1360.33
  5131.4 1361.55  5149.4 1361.02  5161.7 1362.15  5186.8 1361.94  5202.7 1362.91
  5297.6 1363.53  5327.9 1365.18  5333.3 1364.66  5444.1 1366.98  5513.0 1367.49
#Mann=5,-1,0
  4547.1   0.035       0  4865.3    0.07       0  4995.5    0.05       0
  4999.5    0.07       0  5108.7   0.035       0
Bank Sta=4995.5,4999.5
Exp/Cntr=0.3,0.1

Type RM Length L Ch R = 1,493,0,0,0
BEGIN DESCRIPTION:
Stream0062_DS 1.0
END DESCRIPTION:
XS GIS Cut Line= 3
      2063524.97     13914474.99      2063275.00     13914375.00
      2063010.74     13914371.90
#Sta/Elev= 30
  4735.8 1362.52  4768.1 1361.39  4780.2 1359.44  4789.6 1356.45  4804.4 1354.23
  4828.6 1352.97  4834.0 1352.34  4875.8 1351.28  4882.5 1350.78  4887.9 1351.38
  4906.7 1351.57  4933.5 1350.88  4941.7 1350.31  4983.5 1349.22  4995.6 1347.35
  5002.3 1345.52  5007.5 1345.52  5013.0 1344.68  5013.3 1344.18  5016.8 1344.18
  5017.0 1344.68  5025.0 1345.76  5035.0 1354.69  5045.0 1359.58  5055.0 1359.64
  5085.0 1360.84  5095.0 1362.91  5115.0 1362.24  5135.0 1362.34  5269.3 1364.29
#Mann=5,-1,0
  4735.8   0.035       0  4828.6    0.07       0  4933.5   0.035       0
  5013.0   0.035       0  5017.0   0.035       0
Bank Sta=5013,5017
Exp/Cntr=0.3,0.1

Chan Stop Cuts=-1