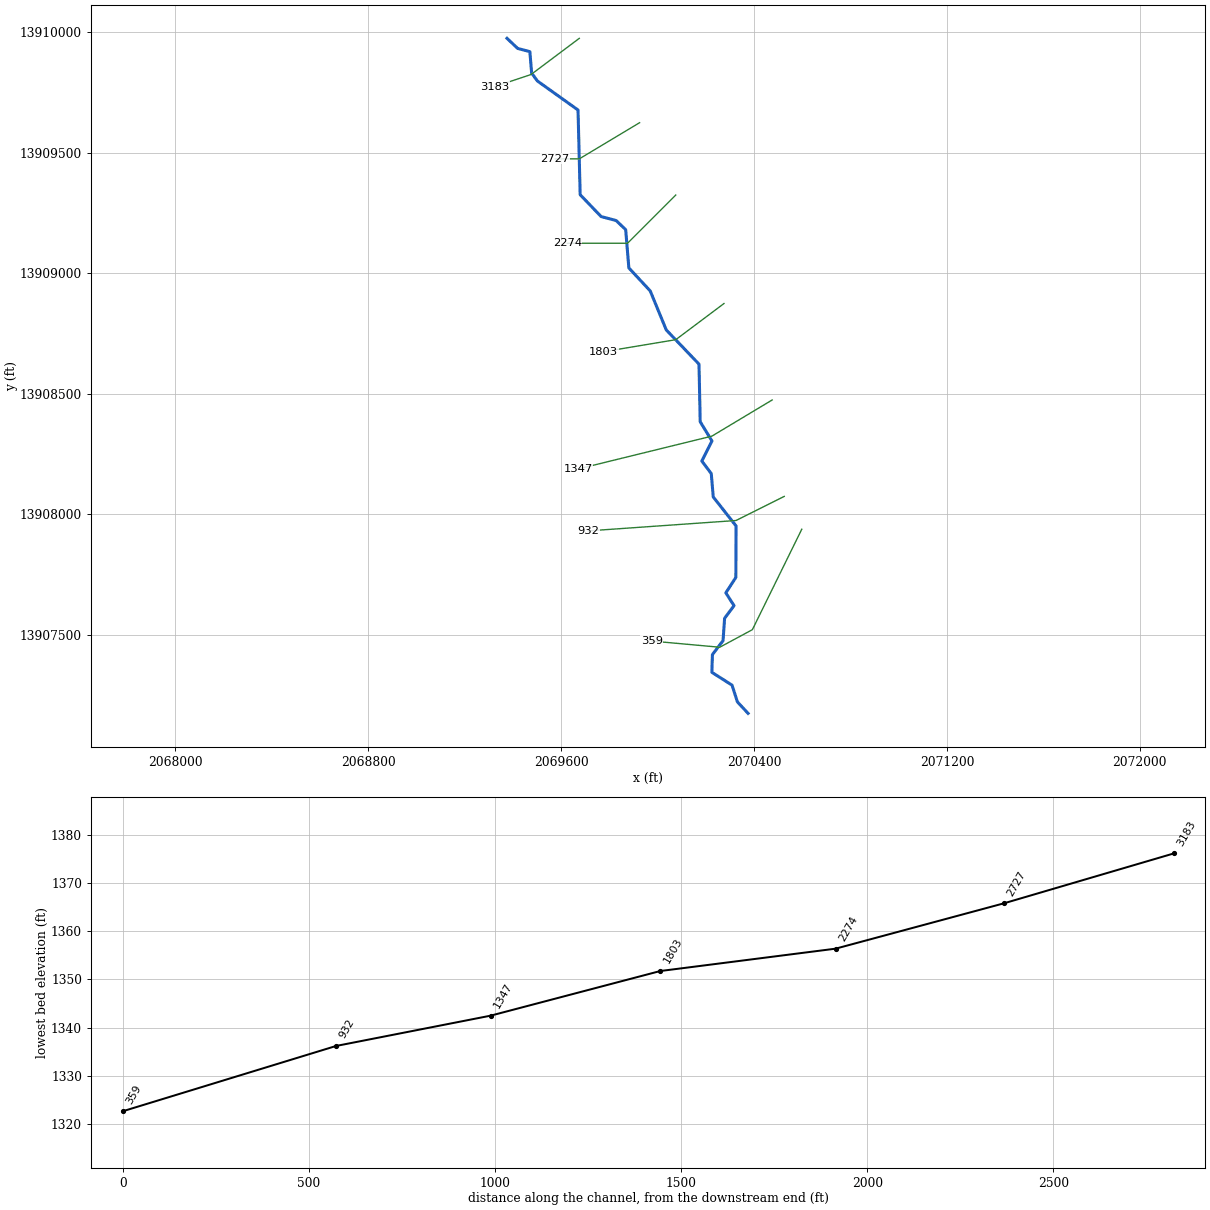
--- Stream0063_DS.prj (project) ---

Proj Title=Stream0063_DS Base Level Engineering
Current Plan=p01
Default Exp/Contr=0.3,0.1
English Units
Geom File=g01
Flow File=f01
Plan File=p01
BEGIN DESCRIPTION:
Stream0063_DS
END DESCRIPTION:

--- Stream0063_DS.p01 (plan) ---

Plan Title=Multiple Run
Short Identifier=Multiple
Geom File=g01
Flow File=f01
Subcritical Flow
K Sum by GR= 0
Std Step Tol= 0.01
Critical Tol= 0.01
Num of Std Step Trials= 20
Max Error Tol= 0.3
Flow Tol Ratio= 0.001
Split Flow NTrial= 30
Split Flow Tol= 0.02
Split Flow Ratio= 0.02
Log Output Level= 0
Friction Slope Method= 1
Unsteady Friction Slope Method= 2
Unsteady Bridges Friction Slope Method= 1
Parabolic Critical Depth
Global Vel Dist=  1 , 1 , 1
Global Log Level= 0
CheckData=True
Encroach Param= -1, 0, 0, 0
BEGIN DESCRIPTION:
Multiple Run
END DESCRIPTION:

--- Stream0063_DS.f01 (steady flow) ---

Flow Title=Multiple
Number of Profiles=7
Profile Names=10-year,25-year,50-year,1pct_min,100-year,1pct_plu,500-year
River Rch & RM= Stream0063_DS,Reach-1,3183
     871    1459    2013    1349    2692    5371    4753
Boundary for River Rch & Prof#=Stream0063_DS,Reach-1,1
Up Type=0
Dn Type=3
Dn Slope=0.005
Boundary for River Rch & Prof#=Stream0063_DS,Reach-1,2
Up Type=0
Dn Type=3
Dn Slope=0.005
Boundary for River Rch & Prof#=Stream0063_DS,Reach-1,3
Up Type=0
Dn Type=3
Dn Slope=0.005
Boundary for River Rch & Prof#=Stream0063_DS,Reach-1,4
Up Type=0
Dn Type=3
Dn Slope=0.005
Boundary for River Rch & Prof#=Stream0063_DS,Reach-1,5
Up Type=0
Dn Type=3
Dn Slope=0.005
Boundary for River Rch & Prof#=Stream0063_DS,Reach-1,6
Up Type=0
Dn Type=3
Dn Slope=0.005
Boundary for River Rch & Prof#=Stream0063_DS,Reach-1,7
Up Type=0
Dn Type=3
Dn Slope=0.005

--- Stream0063_DS.g01 (geometry) ---

Geom Title=Existing Conditions

River Reach=Stream0063_DS,Reach-1
Reach XY= 30
      2069375.00     13909975.00      2069419.36     13909933.15
      2069469.89     13909919.73      2069477.18     13909830.97
      2069501.16     13909798.08      2069669.64     13909677.70
      2069678.53     13909326.45      2069765.32     13909235.78
      2069827.57     13909219.26      2069867.30     13909181.47
      2069880.48     13909022.56      2069969.15     13908927.29
      2070035.77     13908765.32      2070171.46     13908623.54
      2070176.40     13908384.65      2070225.21     13908304.79
      2070183.10     13908221.71      2070222.33     13908169.51
      2070230.54     13908072.58      2070325.19     13907952.35
      2070324.18     13907738.86      2070282.79     13907674.90
      2070316.72     13907621.78      2070277.66     13907569.52
      2070271.14     13907476.59      2070227.13     13907418.94
      2070224.89     13907345.26      2070308.46     13907292.05
      2070330.72     13907222.68      2070375.00     13907175.00

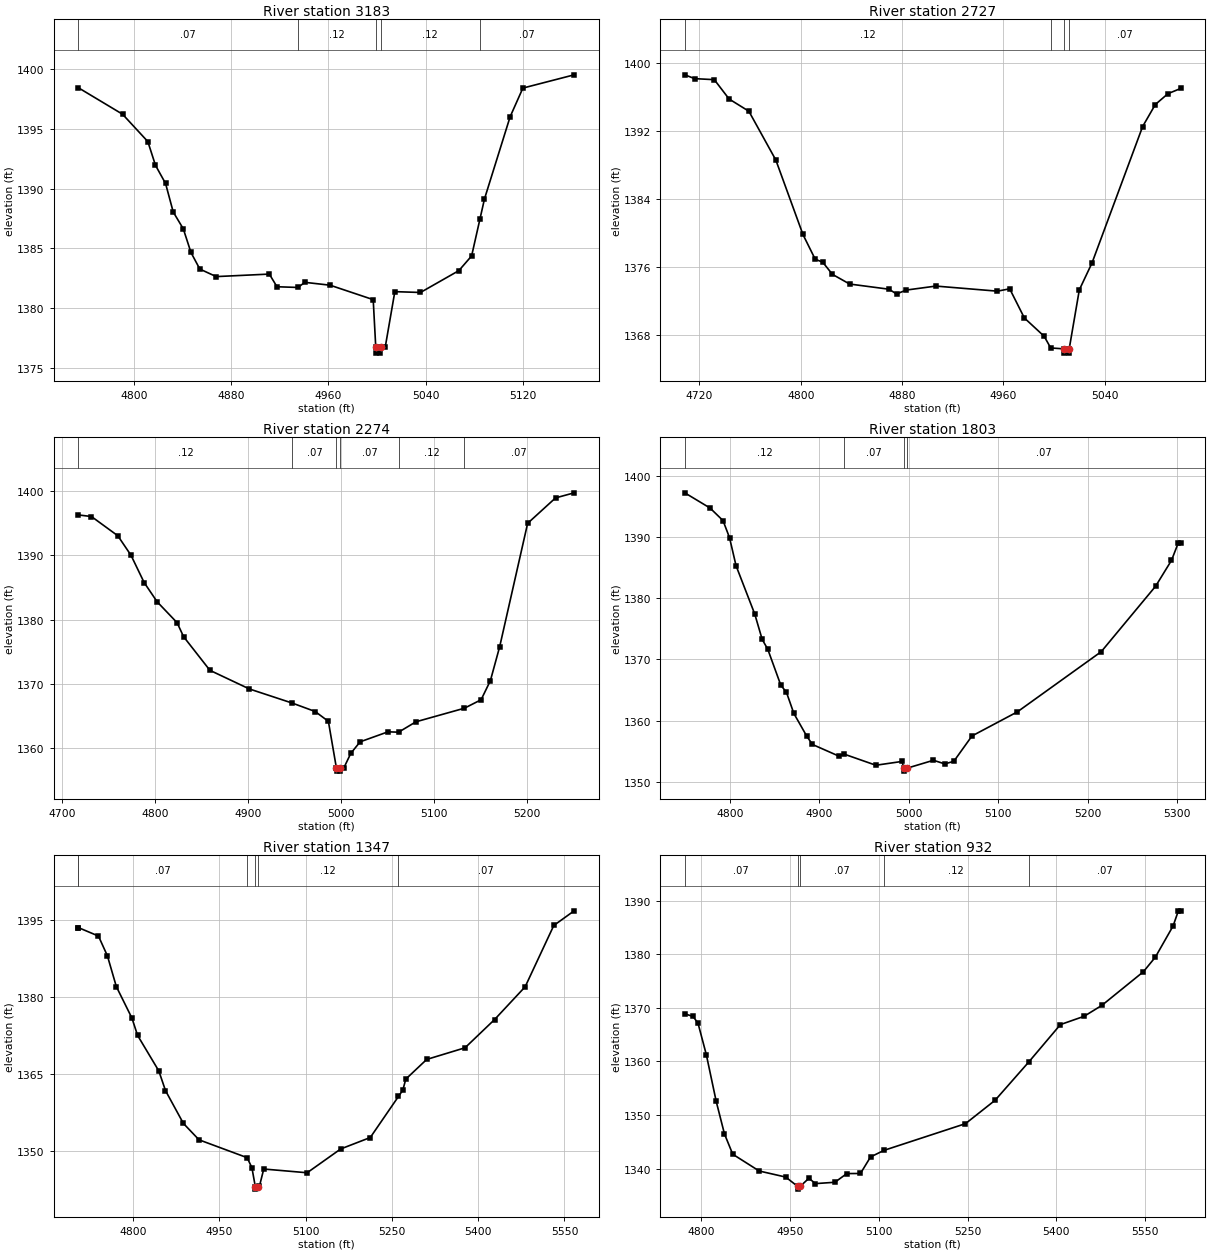
Type RM Length L Ch R = 1,3183,456,456,456
BEGIN DESCRIPTION:
Stream0063_DS 7.0
END DESCRIPTION:
XS GIS Cut Line= 3
      2069674.97     13909974.97      2069475.00     13909825.00
      2069324.97     13909774.99
#Sta/Elev= 30
  4754.2 1398.46  4790.6 1396.24  4811.4 1393.95  4817.7 1391.96  4826.0 1390.44
  4832.3 1388.05  4840.6 1386.64  4846.9 1384.66  4854.2 1383.27  4867.7 1382.64
  4911.4 1382.85  4917.7 1381.79  4935.0 1381.73  4940.6 1382.16  4961.4 1381.92
  4996.9 1380.71  4999.0 1376.73  4999.3 1376.23  5002.8 1376.23  5003.0 1376.73
  5006.8 1376.73  5014.7 1381.38  5035.8 1381.31  5067.4 1383.14  5077.9 1384.37
  5084.8 1387.48  5088.5 1389.15  5109.6 1396.03  5120.1 1398.43  5162.3 1399.54
#Mann=5,-1,0
  4754.2    0.07       0  4935.0    0.12       0  4999.0    0.05       0
  5003.0    0.12       0  5084.8    0.07       0
Bank Sta=4999,5003
Exp/Cntr=0.3,0.1

Type RM Length L Ch R = 1,2727,453,453,453
BEGIN DESCRIPTION:
Stream0063_DS 6.0
END DESCRIPTION:
XS GIS Cut Line= 3
      2069925.02     13909625.01      2069675.00     13909475.00
      2069574.97     13909475.00
#Sta/Elev= 30
  4708.4 1398.65  4716.2 1398.20  4731.7 1398.08  4743.4 1395.80  4759.0 1394.36
  4780.3 1388.61  4801.7 1379.84  4811.4 1376.92  4817.3 1376.58  4825.0 1375.14
  4838.6 1374.00  4869.7 1373.39  4875.6 1372.83  4883.3 1373.29  4906.7 1373.76
  4955.3 1373.16  4965.0 1373.44  4976.6 1370.00  4992.2 1367.85  4997.4 1366.47
  5008.0 1366.36  5008.2 1365.86  5011.7 1365.86  5012.0 1366.36  5020.0 1373.32
  5030.0 1376.48  5070.0 1392.56  5080.0 1395.15  5090.0 1396.43  5100.0 1397.04
#Mann=4,-1,0
  4708.4    0.12       0  4997.4    0.07       0  5008.0    0.05       0
  5012.0    0.07       0
Bank Sta=5008,5012
Exp/Cntr=0.3,0.1

Type RM Length L Ch R = 1,2274,471,471,471
BEGIN DESCRIPTION:
Stream0063_DS 5.0
END DESCRIPTION:
XS GIS Cut Line= 3
      2070074.99     13909324.99      2069875.00     13909125.00
      2069625.03     13909125.00
#Sta/Elev= 30
  4717.7 1396.29  4731.8 1396.04  4760.1 1393.05  4774.3 1390.01  4788.4 1385.77
  4802.5 1382.75  4823.8 1379.52  4830.8 1377.34  4859.1 1372.10  4901.5 1369.20
  4947.8 1366.99  4972.2 1365.69  4986.4 1364.16  4995.0 1356.91  4995.2 1356.41
  4998.7 1356.41  4999.0 1356.91  5003.0 1356.91  5010.5 1359.18  5020.5 1360.97
  5050.5 1362.53  5061.8 1362.47  5080.5 1364.09  5132.5 1366.20  5150.5 1367.52
  5160.5 1370.50  5170.5 1375.80  5200.5 1394.98  5230.5 1398.94  5250.5 1399.73
#Mann=6,-1,0
  4717.7    0.12       0  4947.8    0.07       0  4995.0    0.05       0
  4999.0    0.07       0  5061.8    0.12       0  5132.5    0.07       0
Bank Sta=4995,4999
Exp/Cntr=0.3,0.1

Type RM Length L Ch R = 1,1803,456,456,456
BEGIN DESCRIPTION:
Stream0063_DS 4.0
END DESCRIPTION:
XS GIS Cut Line= 3
      2070275.03     13908875.02      2070075.00     13908725.00
      2069774.97     13908675.00
#Sta/Elev= 30
  4749.7 1397.18  4777.9 1394.70  4792.4 1392.65  4799.7 1389.86  4807.0 1385.28
  4827.9 1377.39  4836.2 1373.25  4842.4 1371.67  4857.0 1365.79  4863.3 1364.63
  4871.6 1361.17  4886.2 1357.42  4892.4 1356.11  4921.6 1354.23  4927.7 1354.54
  4963.3 1352.72  4992.4 1353.34  4994.6 1352.26  4994.9 1351.76  4998.6 1352.26
  5027.6 1353.53  5040.3 1352.94  5050.4 1353.36  5070.7 1357.50  5121.4 1361.43
  5215.2 1371.26  5276.0 1381.95  5293.7 1386.16  5301.3 1389.01  5303.9 1389.01
#Mann=4,-1,0
  4749.7    0.12       0  4927.7    0.07       0  4994.6    0.05       0
  4998.6    0.07       0
Bank Sta=4994.6,4998.6
Exp/Cntr=0.3,0.1

Type RM Length L Ch R = 1,1347,415,415,415
BEGIN DESCRIPTION:
Stream0063_DS 3.0
END DESCRIPTION:
XS GIS Cut Line= 3
      2070475.02     13908475.01      2070225.00     13908325.00
      2069670.64     13908188.88
#Sta/Elev= 30
  4704.5 1393.59  4704.6 1393.59  4739.5 1391.94  4755.1 1388.06  4770.6 1382.06
  4797.8 1375.89  4807.5 1372.53  4844.5 1365.57  4856.1 1361.73  4887.2 1355.32
  4914.4 1352.11  4998.1 1348.62  5006.4 1346.66  5012.3 1342.97  5012.5 1342.47
  5016.3 1342.97  5019.4 1342.99  5027.0 1346.40  5102.5 1345.67  5160.8 1350.32
  5212.3 1352.56  5261.3 1360.58  5268.8 1361.80  5274.1 1363.98  5310.4 1367.82
  5377.1 1370.10  5428.5 1375.62  5481.7 1382.03  5531.5 1394.01  5566.9 1396.87
#Mann=6,-1,0
  4704.5    0.12       0  4704.6    0.07       0  4998.1    0.12       0
  5012.3    0.05       0  5016.3    0.12       0  5261.3    0.07       0
Bank Sta=5012.3,5016.3
Exp/Cntr=0.3,0.1

Type RM Length L Ch R = 1,932,573,573,573
BEGIN DESCRIPTION:
Stream0063_DS 2.0
END DESCRIPTION:
XS GIS Cut Line= 3
      2070524.96     13908074.98      2070325.00     13907975.00
      2069712.37     13907931.94
#Sta/Elev= 30
  4772.3 1368.87  4786.2 1368.38  4794.6 1367.13  4808.6 1361.28  4825.4 1352.52
  4839.3 1346.47  4853.3 1342.68  4898.0 1339.55  4942.8 1338.42  4963.1 1336.67
  4963.4 1336.17  4967.1 1336.67  4981.9 1338.19  4993.1 1337.20  5025.9 1337.45
  5046.0 1339.07  5069.1 1339.09  5086.1 1342.17  5108.8 1343.40  5246.5 1348.38
  5296.6 1352.75  5353.4 1359.88  5406.9 1366.86  5447.0 1368.41  5477.0 1370.45
  5547.2 1376.73  5567.3 1379.44  5597.3 1385.26  5606.2 1388.08  5610.0 1388.08
#Mann=5,-1,0
  4772.3    0.07       0  4963.1    0.05       0  4967.1    0.07       0
  5108.8    0.12       0  5353.4    0.07       0
Bank Sta=4963.1,4967.1
Exp/Cntr=0.3,0.1

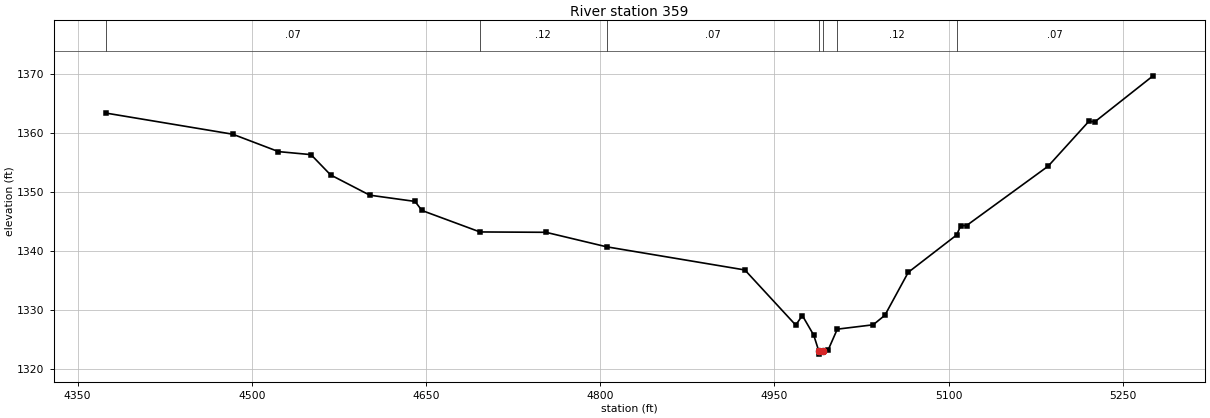
Type RM Length L Ch R = 1,359,0,0,0
BEGIN DESCRIPTION:
Stream0063_DS 1.0
END DESCRIPTION:
XS GIS Cut Line= 4
      2070597.74     13907938.87      2070392.89     13907522.22
      2070257.47     13907449.30      2069975.03     13907475.00
#Sta/Elev= 30
  4374.4 1363.43  4483.6 1359.85  4523.0 1356.90  4551.0 1356.39  4567.9 1352.95
  4601.6 1349.52  4640.6 1348.46  4646.5 1346.93  4696.5 1343.29  4753.3 1343.23
  4805.6 1340.77  4924.6 1336.85  4968.4 1327.51  4974.1 1329.13  4983.9 1325.81
  4988.3 1323.09  4988.6 1322.59  4992.3 1323.09  4996.2 1323.24  5004.2 1326.82
  5035.1 1327.56  5045.2 1329.18  5065.3 1336.45  5107.0 1342.78  5110.5 1344.37
  5115.5 1344.37  5185.8 1354.44  5220.9 1362.05  5225.9 1361.94  5276.1 1369.74
#Mann=7,-1,0
  4374.4    0.07       0  4696.5    0.12       0  4805.6    0.07       0
  4988.3    0.05       0  4992.3    0.07       0  5004.2    0.12       0
  5107.0    0.07       0
Bank Sta=4988.3,4992.3
Exp/Cntr=0.3,0.1

Chan Stop Cuts=-1