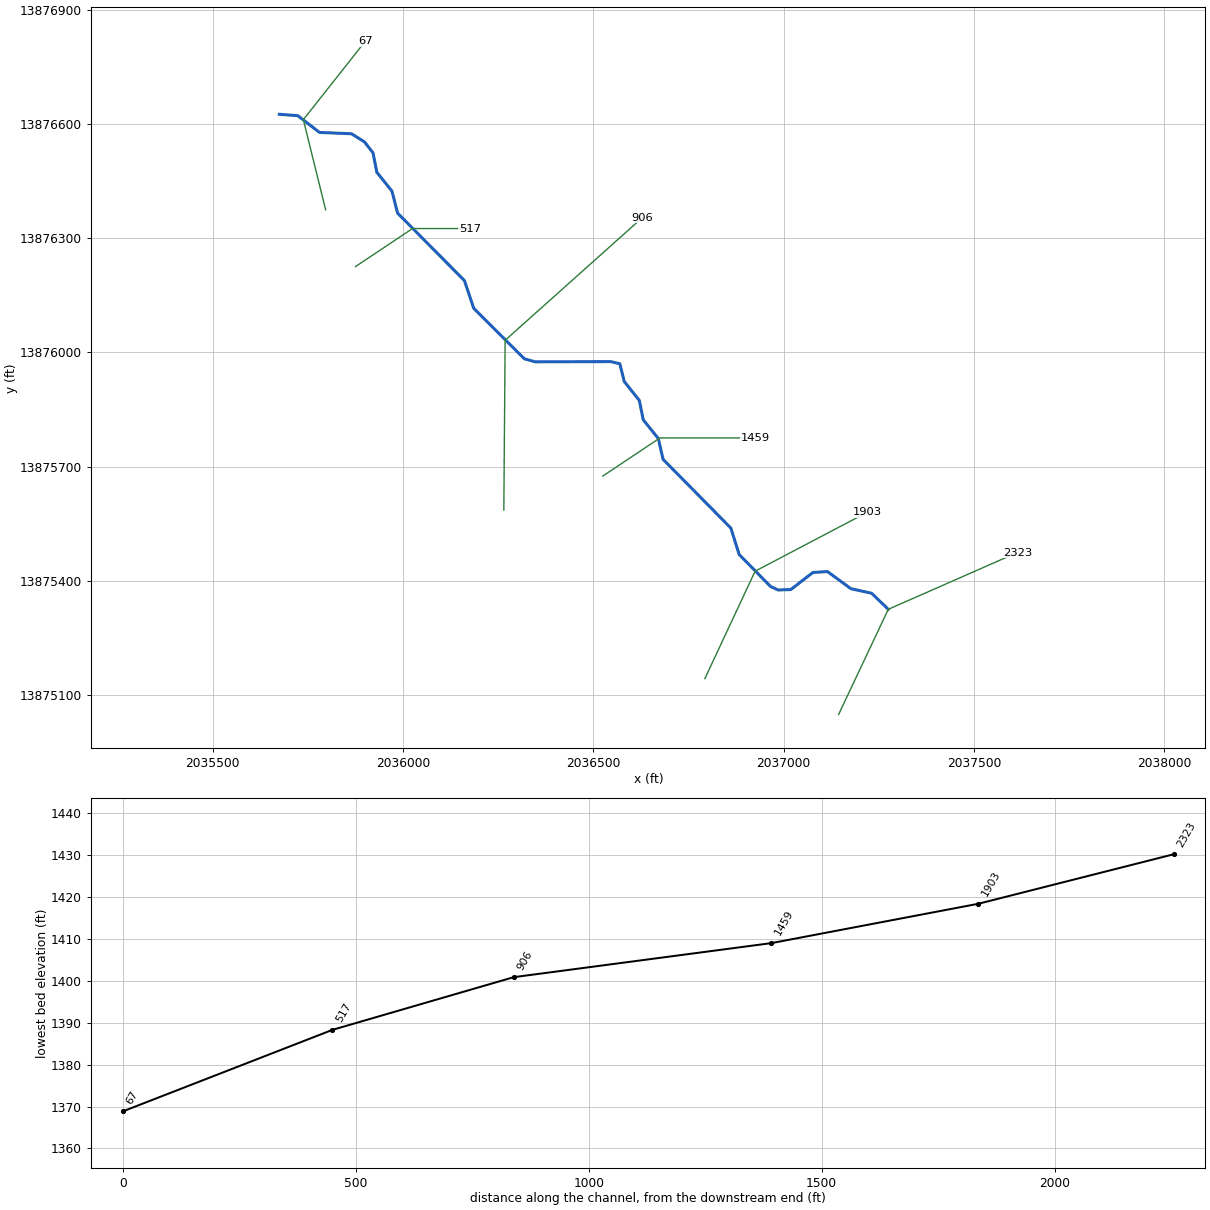
--- Stream0064_DS.prj (project) ---

Proj Title=Stream0064_DS Base Level Engineering
Current Plan=p01
Default Exp/Contr=0.3,0.1
English Units
Geom File=g01
Flow File=f01
Plan File=p01
Y Axis Title=Elevation
X Axis Title(PF)=Main Channel Distance
X Axis Title(XS)=Station
BEGIN DESCRIPTION:
Stream0064_DS
END DESCRIPTION:
DSS Export Rating Curves= 0
DSS Export Rating Curve Sorted= 0
DSS Export Volume Flow Curves= 0
DXF OffsetX= 0
DXF OffsetY= 0
DXF ScaleX= 1
DXF ScaleY= 10

--- Stream0064_DS.p01 (plan) ---

Plan Title=Multiple Run
Short Identifier=Multiple
Geom File=g01
Flow File=f01
Subcritical Flow
K Sum by GR= 0
Std Step Tol= 0.01
Critical Tol= 0.01
Num of Std Step Trials= 20
Max Error Tol= 0.3
Flow Tol Ratio= 0.001
Split Flow NTrial= 30
Split Flow Tol= 0.02
Split Flow Ratio= 0.02
Log Output Level= 0
Friction Slope Method= 1
Unsteady Friction Slope Method= 2
Unsteady Bridges Friction Slope Method= 1
Parabolic Critical Depth
Global Vel Dist=  1 , 1 , 1
Global Log Level= 0
CheckData=True
Encroach Param= -1, 0, 0, 0
BEGIN DESCRIPTION:
Multiple Run
END DESCRIPTION:

--- Stream0064_DS.f01 (steady flow) ---

Flow Title=Multiple
Number of Profiles=7
Profile Names=10-year,25-year,50-year,1pct_min,100-year,1pct_plu,500-year
River Rch & RM= Stream0064_DS,Reach-1,2323
     410     650     864     560    1117    2228    1837
River Rch & RM= Stream0064_DS,Reach-1,1903
     557     903    1218     799    1595    3183    2698
Boundary for River Rch & Prof#=Stream0064_DS,Reach-1,1
Up Type=0
Dn Type=3
Dn Slope=0.005
Boundary for River Rch & Prof#=Stream0064_DS,Reach-1,2
Up Type=0
Dn Type=3
Dn Slope=0.005
Boundary for River Rch & Prof#=Stream0064_DS,Reach-1,3
Up Type=0
Dn Type=3
Dn Slope=0.005
Boundary for River Rch & Prof#=Stream0064_DS,Reach-1,4
Up Type=0
Dn Type=3
Dn Slope=0.005
Boundary for River Rch & Prof#=Stream0064_DS,Reach-1,5
Up Type=0
Dn Type=3
Dn Slope=0.005
Boundary for River Rch & Prof#=Stream0064_DS,Reach-1,6
Up Type=0
Dn Type=3
Dn Slope=0.005
Boundary for River Rch & Prof#=Stream0064_DS,Reach-1,7
Up Type=0
Dn Type=3
Dn Slope=0.005

--- Stream0064_DS.g01 (geometry) ---

Geom Title=Existing Conditions
Program Version=4.10

River Reach=Stream0064_DS   ,Reach-1
Reach XY= 30
        2037275.       13875325.      2037231.15     13875367.09
      2037176.67     13875379.11      2037115.16      13875424.1
      2037076.72      13875421.6      2037018.87     13875376.81
      2036985.62      13875375.6       2036965.3     13875385.18
      2036883.15     13875468.93      2036861.37     13875538.21
      2036683.14     13875718.94      2036670.81     13875773.26
      2036631.08     13875822.81      2036620.85     13875873.31
      2036581.27     13875923.21      2036569.59     13875969.83
      2036545.44     13875975.54      2036347.65      13875974.8
      2036318.81     13875982.81      2036185.78     13876115.32
      2036161.37     13876188.21      2035985.76     13876365.32
      2035970.81     13876423.27      2035931.11     13876472.84
      2035921.15     13876523.61       2035898.9     13876552.28
      2035864.67     13876573.91      2035780.52     13876577.34
      2035723.49     13876621.36        2035675.       13876625.

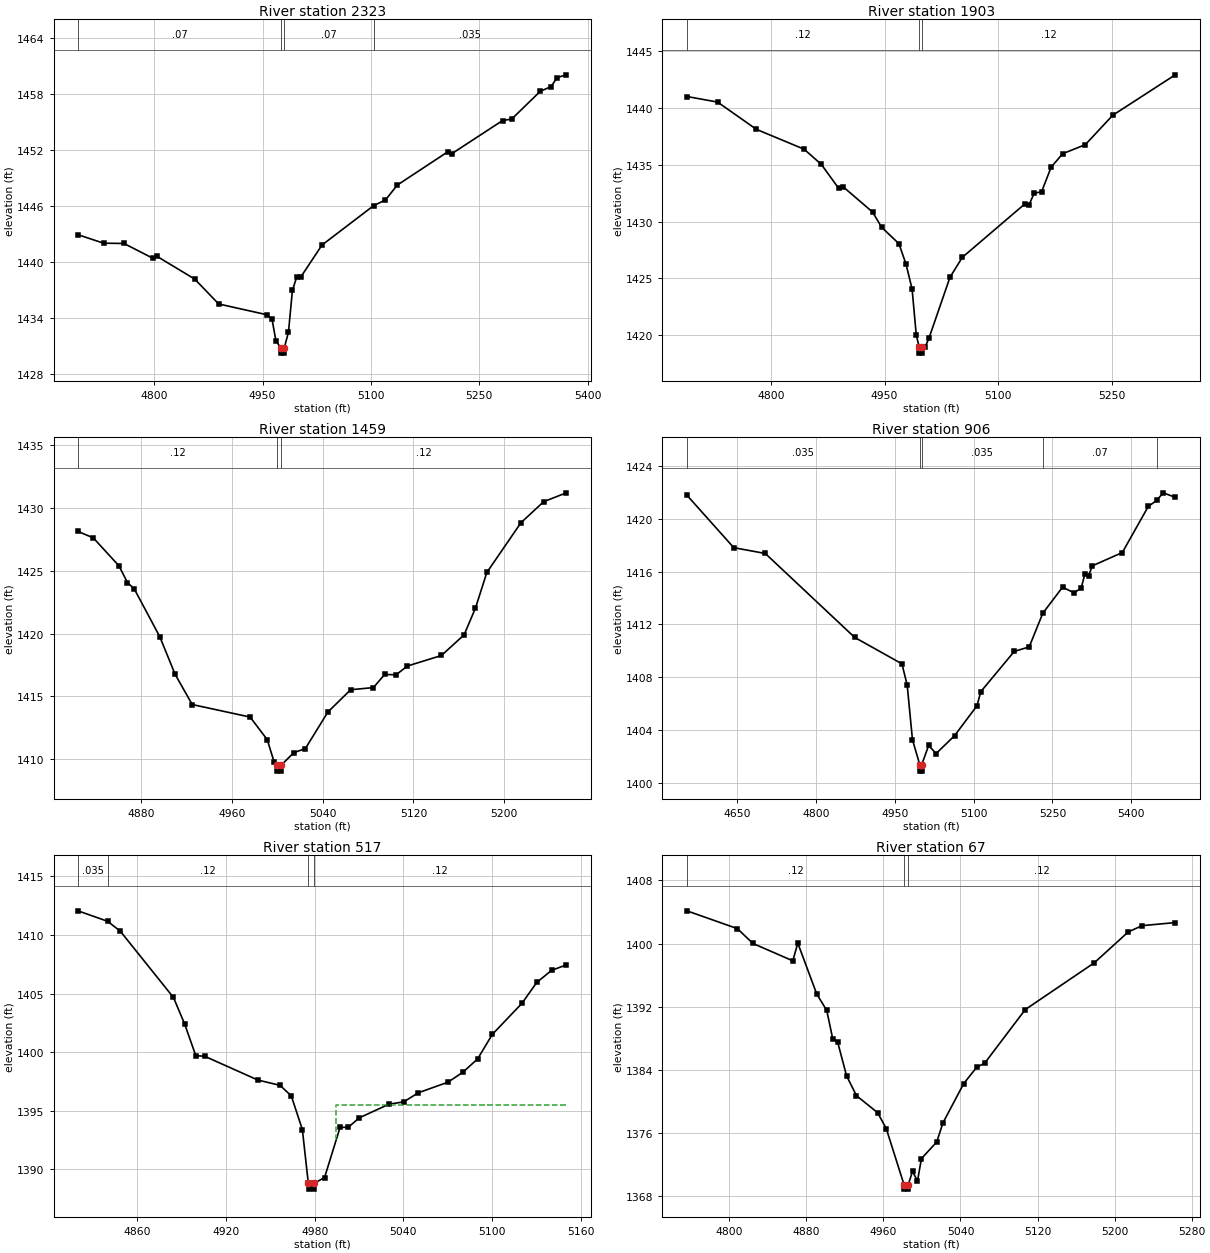
Type RM Length L Ch R = 1 ,2323    ,420,420,420
BEGIN DESCRIPTION:
Stream0064_DS 5.0
END DESCRIPTION:
XS GIS Cut Line= 3
      2037144.48      13875048.9        2037275.       13875325.
      2037614.09     13875474.04
#Sta/Elev= 30
  4694.6 1442.93    4730 1442.02  4758.3 1441.99  4798.2 1440.41  4803.8 1440.62
  4856.2 1438.18  4889.3 1435.52  4955.8 1434.37  4963.1 1433.92  4968.6 1431.56
  4975.9 1430.76  4976.1 1430.26  4979.6 1430.26  4979.9 1430.76  4985.9 1432.49
  4991.4 1436.97  4997.2 1438.37  5002.7 1438.37  5032.3 1441.82  5103.7 1446.03
  5120.2 1446.65  5136.6 1448.24  5206.7 1451.81  5212.1  1451.6  5282.2 1455.14
  5294.9  1455.3  5334.3 1458.26  5349.5 1458.78  5357.7 1459.74  5370.4 1460.03
#Mann= 4 ,-1 , 0
  4694.6     .07       0  4975.9     .05       0  4979.9     .07       0
  5103.7    .035       0
Bank Sta=4975.9,4979.9
XS Rating Curve= 0 ,0
Exp/Cntr=0.3,0.1

Type RM Length L Ch R = 1 ,1903    ,444,444,444
BEGIN DESCRIPTION:
Stream0064_DS 4.0
END DESCRIPTION:
XS GIS Cut Line= 3
      2036793.01     13875142.91        2036925.       13875425.
      2037220.06     13875579.92
#Sta/Elev= 30
  4689.1 1441.02  4729.6 1440.53  4780.8 1438.13  4843.8 1436.38  4866.6 1435.04
  4889.5 1432.93    4895 1433.09  4934.3 1430.84  4946.2  1429.5    4969 1428.06
  4978.5 1426.23  4986.4 1424.06  4991.9 1420.02  4995.8 1418.92    4996 1418.42
  4999.5 1418.42  4999.8 1418.92  5003.4 1418.92  5008.7 1419.74  5036.4  1425.1
  5052.8 1426.86  5135.4 1431.57    5141  1431.5  5147.4 1432.49  5157.4 1432.64
    5170  1434.8  5185.1 1435.98  5215.1 1436.78  5251.3 1439.37  5333.8 1442.93
#Mann= 3 ,-1 , 0
  4689.1     .12       0  4995.8     .05       0  4999.8     .12       0
Bank Sta=4995.8,4999.8
XS Rating Curve= 0 ,0
Exp/Cntr=0.3,0.1

Type RM Length L Ch R = 1 ,1459    ,553,553,553
BEGIN DESCRIPTION:
Stream0064_DS 3.0
END DESCRIPTION:
XS GIS Cut Line= 3
        2036525.       13875675.        2036675.       13875775.
      2036925.02       13875775.
#Sta/Elev= 30
  4824.4 1428.14  4837.9 1427.63  4860.5  1425.4    4868 1424.07    4874 1423.56
  4896.5 1419.75    4910 1416.75  4925.1 1414.34  4976.1 1413.34  4991.2 1411.54
  4997.2 1409.77  4999.7 1409.53  4999.9 1409.03  5003.4 1409.03  5003.7 1409.53
  5014.7 1410.51  5024.7 1410.82  5044.7 1413.75  5064.7 1415.52  5084.7 1415.69
  5094.7 1416.74  5104.7 1416.71  5114.7 1417.41  5144.7 1418.25  5164.7  1419.9
  5174.7 1422.04  5184.7 1424.87  5214.7 1428.83  5234.7 1430.51  5254.7 1431.22
#Mann= 3 ,-1 , 0
  4824.4     .12       0  4999.7     .05       0  5003.7     .12       0
Bank Sta=4999.7,5003.7
XS Rating Curve= 0 ,0
Exp/Cntr=0.3,0.1

Type RM Length L Ch R = 1 ,906     ,389,389,389
BEGIN DESCRIPTION:
Stream0064_DS 2.0
END DESCRIPTION:
XS GIS Cut Line= 3
      2036264.82      13875585.8      2036268.24     13876031.48
      2036628.86      13876353.7
#Sta/Elev= 30
  4554.3 1421.78  4643.5 1417.81  4703.5 1417.37  4873.5 1411.02  4963.5 1409.02
  4973.5 1407.41  4983.5 1403.29  4997.3  1401.4  4997.5  1400.9    5001  1400.9
  5001.3  1401.4  5014.3 1402.84  5028.5 1402.23  5063.6 1403.58  5106.2 1405.84
  5113.7 1406.92  5177.3 1409.96  5205.7  1410.3  5231.6 1412.85  5269.2 1414.82
  5290.7  1414.4  5304.4 1414.73  5311.9 1415.85  5318.6  1415.7  5326.1 1416.44
  5382.9 1417.44  5432.3 1420.93  5448.1 1421.38  5460.7 1421.96  5483.6 1421.62
#Mann= 5 ,-1 , 0
  4554.3    .035       0  4997.3    .035       0  5001.3    .035       0
  5231.6     .07       0  5448.1     .12       0
Bank Sta=4997.3,5001.3
XS Rating Curve= 0 ,0
Exp/Cntr=0.3,0.1

Type RM Length L Ch R = 1 ,517     ,450,450,450
BEGIN DESCRIPTION:
Stream0064_DS 1.0
END DESCRIPTION:
XS GIS Cut Line= 3
      2035874.97     13876224.98        2036025.       13876325.
      2036174.98       13876325.
#Sta/Elev= 30
  4819.9 1412.05  4839.9 1411.16  4848.5 1410.32  4884.5 1404.66    4892 1402.42
  4899.6  1399.7  4905.6 1399.65  4941.6 1397.62  4956.6 1397.17  4964.2 1396.27
  4971.7 1393.39  4975.7 1388.82  4975.9 1388.32  4979.4 1388.32  4979.7 1388.82
  4986.7 1389.31  4997.2 1393.59  5002.7 1393.59  5010.2  1394.4  5030.2 1395.56
  5040.2 1395.76  5050.2 1396.54  5070.2 1397.44  5080.2 1398.28  5090.2 1399.42
  5100.2 1401.52  5120.2 1404.16  5130.2 1405.94  5140.2 1406.97  5150.2 1407.44
#Mann= 4 ,-1 , 0
  4819.9    .035       0  4839.9     .12       0  4975.7     .05       0
  4979.7     .12       0
#XS Ineff= 2 , 0
       0                 4994.45       0 1395.48
Permanent Ineff=
       F       F
Bank Sta=4975.7,4979.7
XS Rating Curve= 0 ,0
Exp/Cntr=0.3,0.1

Type RM Length L Ch R = 1 ,67      ,0,0,0
BEGIN DESCRIPTION:
Stream0064_DS 0.0
END DESCRIPTION:
XS GIS Cut Line= 3
      2035796.62     13876374.18      2035738.03     13876610.93
      2035901.07     13876817.18
#Sta/Elev= 30
  4756.1 1404.15  4808.5 1401.89  4824.6 1400.01    4866 1397.81  4871.2 1400.05
  4890.9 1393.58  4901.2 1391.53  4907.4 1387.94  4912.6 1387.48  4921.8 1383.22
  4932.1  1380.7    4954 1378.55    4963 1376.53  4981.6 1369.35  4981.8 1368.85
  4985.3 1368.85  4985.6 1369.35  4990.3 1371.11  4995.4 1369.87  4999.5 1372.73
  5015.4 1374.83  5021.8 1377.25  5043.4 1382.24    5057 1384.33  5065.1 1384.82
  5107.2 1391.62  5178.9 1397.56  5214.2 1401.48  5228.6 1402.27  5262.9 1402.66
#Mann= 3 ,-1 , 0
  4756.1     .12       0  4981.6     .05       0  4985.6     .12       0
Bank Sta=4981.6,4985.6
XS Rating Curve= 0 ,0
Exp/Cntr=0.3,0.1

Chan Stop Cuts=-1
Use User Specified Reach Order=0
Composite Channel Slope=5