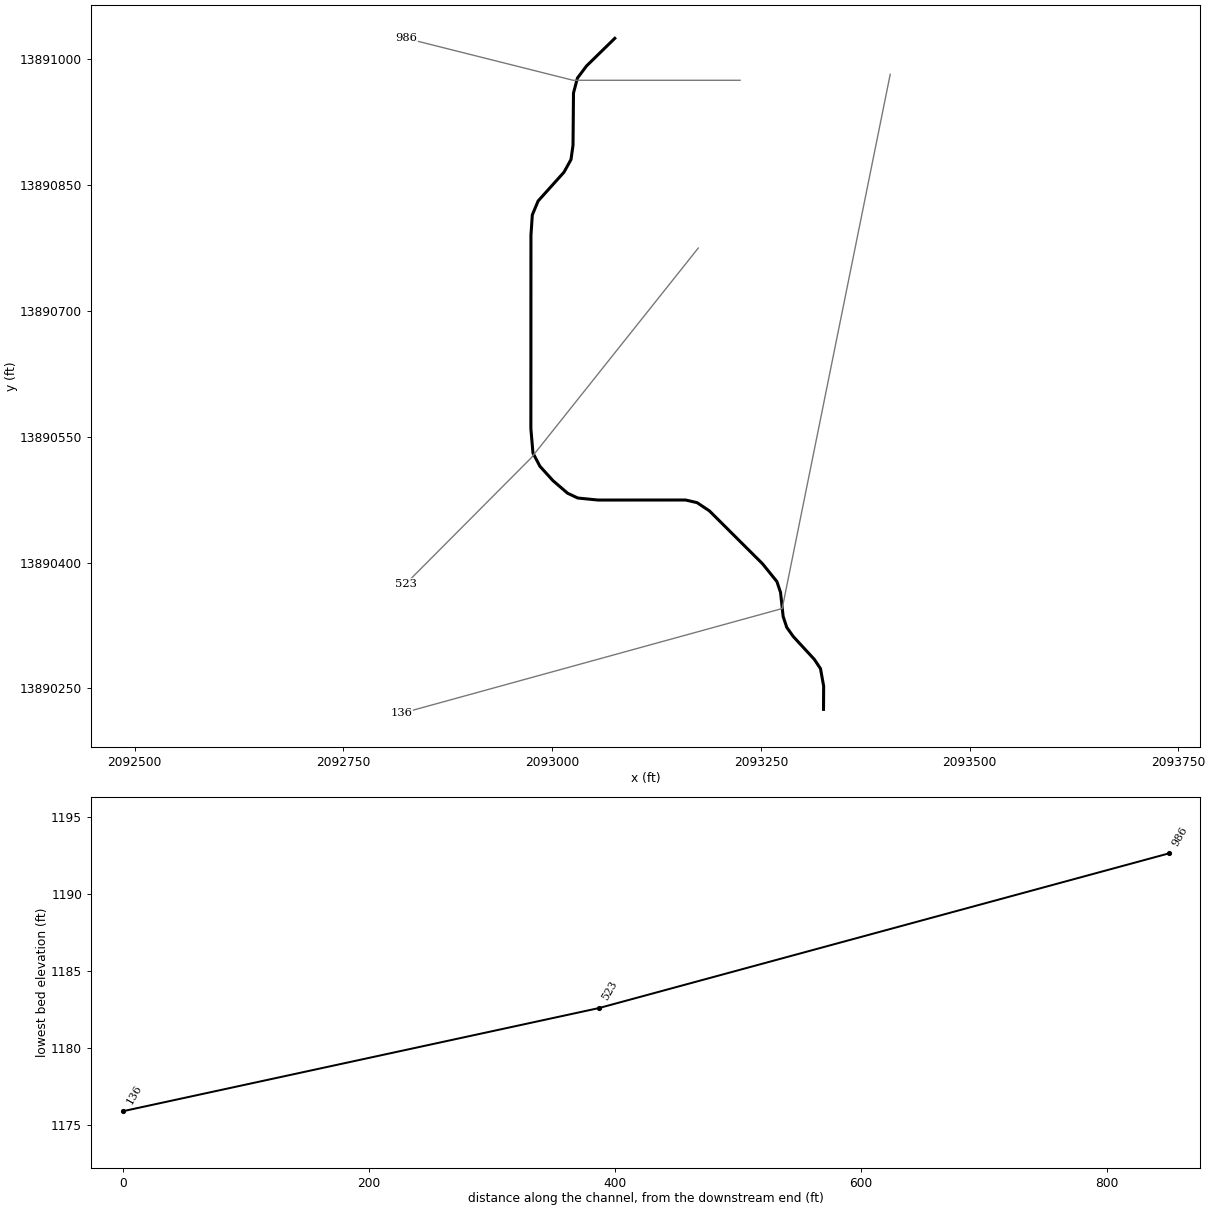
--- Stream0065_DS.prj (project) ---

Proj Title=Stream0065_DS Base Level Engineering
Current Plan=p01
Default Exp/Contr=0.3,0.1
English Units
Geom File=g01
Flow File=f01
Plan File=p01
BEGIN DESCRIPTION:
Stream0065_DS
END DESCRIPTION:

--- Stream0065_DS.p01 (plan) ---

Plan Title=Multiple Run
Short Identifier=Multiple
Geom File=g01
Flow File=f01
Subcritical Flow
K Sum by GR= 0
Std Step Tol= 0.01
Critical Tol= 0.01
Num of Std Step Trials= 20
Max Error Tol= 0.3
Flow Tol Ratio= 0.001
Split Flow NTrial= 30
Split Flow Tol= 0.02
Split Flow Ratio= 0.02
Log Output Level= 0
Friction Slope Method= 1
Unsteady Friction Slope Method= 2
Unsteady Bridges Friction Slope Method= 1
Parabolic Critical Depth
Global Vel Dist=  1 , 1 , 1
Global Log Level= 0
CheckData=True
Encroach Param= -1, 0, 0, 0
BEGIN DESCRIPTION:
Multiple Run
END DESCRIPTION:

--- Stream0065_DS.f01 (steady flow) ---

Flow Title=Multiple
Number of Profiles=7
Profile Names=10-year,25-year,50-year,1pct_min,100-year,1pct_plu,500-year
River Rch & RM= Stream0065_DS,Reach-1,986
     855    1434    1982    1330    2655    5297    4704
Boundary for River Rch & Prof#=Stream0065_DS,Reach-1,1
Up Type=0
Dn Type=3
Dn Slope=0.005
Boundary for River Rch & Prof#=Stream0065_DS,Reach-1,2
Up Type=0
Dn Type=3
Dn Slope=0.005
Boundary for River Rch & Prof#=Stream0065_DS,Reach-1,3
Up Type=0
Dn Type=3
Dn Slope=0.005
Boundary for River Rch & Prof#=Stream0065_DS,Reach-1,4
Up Type=0
Dn Type=3
Dn Slope=0.005
Boundary for River Rch & Prof#=Stream0065_DS,Reach-1,5
Up Type=0
Dn Type=3
Dn Slope=0.005
Boundary for River Rch & Prof#=Stream0065_DS,Reach-1,6
Up Type=0
Dn Type=3
Dn Slope=0.005
Boundary for River Rch & Prof#=Stream0065_DS,Reach-1,7
Up Type=0
Dn Type=3
Dn Slope=0.005

--- Stream0065_DS.g01 (geometry) ---

Geom Title=Existing Conditions

River Reach=Stream0065_DS,Reach-1
Reach XY= 30
      2093075.00     13891025.00      2093041.12     13890992.05
      2093030.22     13890977.55      2093025.53     13890959.78
      2093024.97     13890897.74      2093022.56     13890880.56
      2093014.11     13890865.37      2092983.14     13890831.06
      2092976.22     13890814.50      2092974.57     13890790.18
      2092974.48     13890559.73      2092976.97     13890530.65
      2092985.32     13890514.82      2093000.97     13890497.65
      2093018.48     13890482.68      2093030.65     13890476.98
      2093054.76     13890474.57      2093159.84     13890474.60
      2093173.54     13890471.46      2093188.34     13890461.64
      2093252.02     13890398.52      2093269.19     13890377.32
      2093273.53     13890364.40      2093276.66     13890335.69
      2093280.98     13890322.76      2093288.78     13890311.85
      2093314.02     13890284.60      2093321.40     13890273.51
      2093325.18     13890252.68      2093325.00     13890225.00

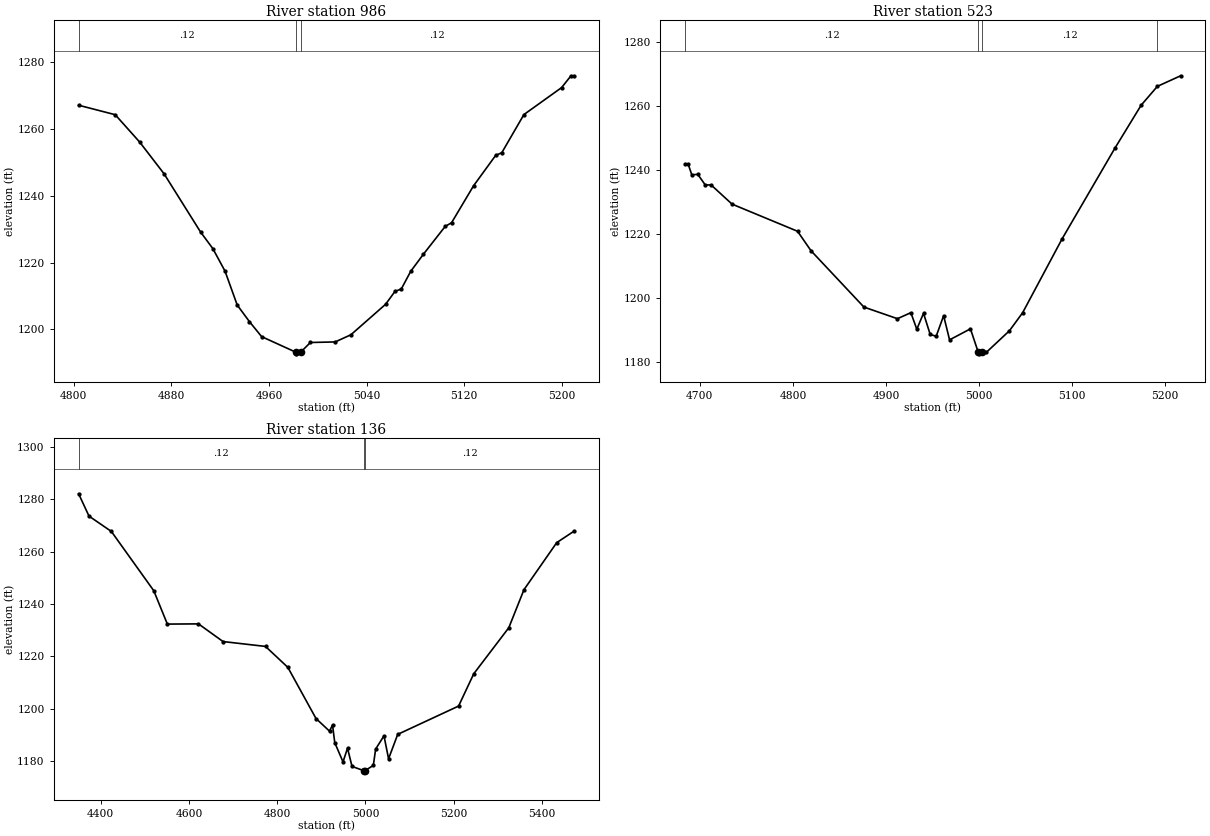
Type RM Length L Ch R = 1,986,463,463,463
BEGIN DESCRIPTION:
Stream0065_DS 2.0
END DESCRIPTION:
XS GIS Cut Line= 3
      2093225.04     13890975.00      2093025.00     13890975.00
      2092825.00     13891025.00
#Sta/Elev= 30
  4804.0 1267.18  4834.0 1264.34  4854.0 1256.15  4874.0 1246.65  4904.0 1229.15
  4914.0 1224.21  4924.0 1217.45  4934.0 1207.28  4944.0 1202.32  4954.0 1197.82
  4982.0 1193.16  4982.3 1192.66  4986.0 1193.16  4994.0 1196.06  5014.3 1196.23
  5027.2 1198.38  5055.6 1207.51  5063.3 1211.37  5068.5 1212.10  5076.2 1217.39
  5086.5 1222.46  5104.5 1230.87  5109.7 1231.96  5127.7 1243.02  5145.8 1252.12
  5150.9 1252.97  5169.0 1264.38  5199.9 1272.47  5207.6 1276.01  5210.2 1276.01
#Mann=3,-1,0
  4804.0    0.12       0  4982.0    0.05       0  4986.0    0.12       0
Bank Sta=4982,4986
Exp/Cntr=0.3,0.1

Type RM Length L Ch R = 1,523,387,387,387
BEGIN DESCRIPTION:
Stream0065_DS 1.0
END DESCRIPTION:
XS GIS Cut Line= 3
      2093174.99     13890774.99      2092975.00     13890525.00
      2092824.98     13890374.98
#Sta/Elev= 30
  4684.2 1241.96  4687.4 1241.96  4691.4 1238.53  4697.8 1238.68  4705.8 1235.39
  4712.2 1235.35  4734.6 1229.38  4805.0 1220.89  4819.5 1214.79  4876.3 1197.20
  4912.3 1193.57  4926.7 1195.45  4933.1 1190.29  4940.3 1195.25  4947.5 1188.64
  4953.9 1188.08  4961.9 1194.50  4968.3 1186.96  4990.7 1190.40  4999.1 1183.09
  4999.4 1182.59  5003.1 1183.09  5007.9 1183.09  5032.6 1189.80  5046.8 1195.45
  5089.2 1218.54  5145.8 1246.81  5174.1 1260.29  5191.5 1266.17  5216.5 1269.48
#Mann=4,-1,0
  4684.2    0.12       0  4999.1    0.05       0  5003.1    0.12       0
  5191.5    0.07       0
Bank Sta=4999.1,5003.1
Exp/Cntr=0.3,0.1

Type RM Length L Ch R = 1,136,0,0,0
BEGIN DESCRIPTION:
Stream0065_DS 0.0
END DESCRIPTION:
XS GIS Cut Line= 3
      2093404.89     13890982.00      2093275.50     13890345.21
      2092819.41     13890220.23
#Sta/Elev= 30
  4350.2 1282.07  4373.7 1273.54  4424.3 1267.69  4520.5 1245.03  4551.2 1232.30
  4621.7 1232.38  4677.4 1225.63  4773.6 1223.77  4824.2 1215.77  4888.0 1196.23
  4918.6 1191.41  4925.4 1193.75  4930.5 1187.01  4949.2 1179.67  4959.4 1184.90
  4969.6 1177.93  4995.6 1176.37  4995.8 1175.87  4999.6 1176.37  5017.9 1178.34
  5023.1 1184.56  5042.0 1189.63  5052.4 1180.86  5073.1 1190.18  5211.0 1200.99
  5245.5 1213.35  5324.8 1230.91  5359.2 1245.45  5433.4 1263.42  5472.9 1267.82
#Mann=3,-1,0
  4350.2    0.12       0  4995.6    0.05       0  4999.6    0.12       0
Bank Sta=4995.6,4999.6
Exp/Cntr=0.3,0.1

Chan Stop Cuts=-1