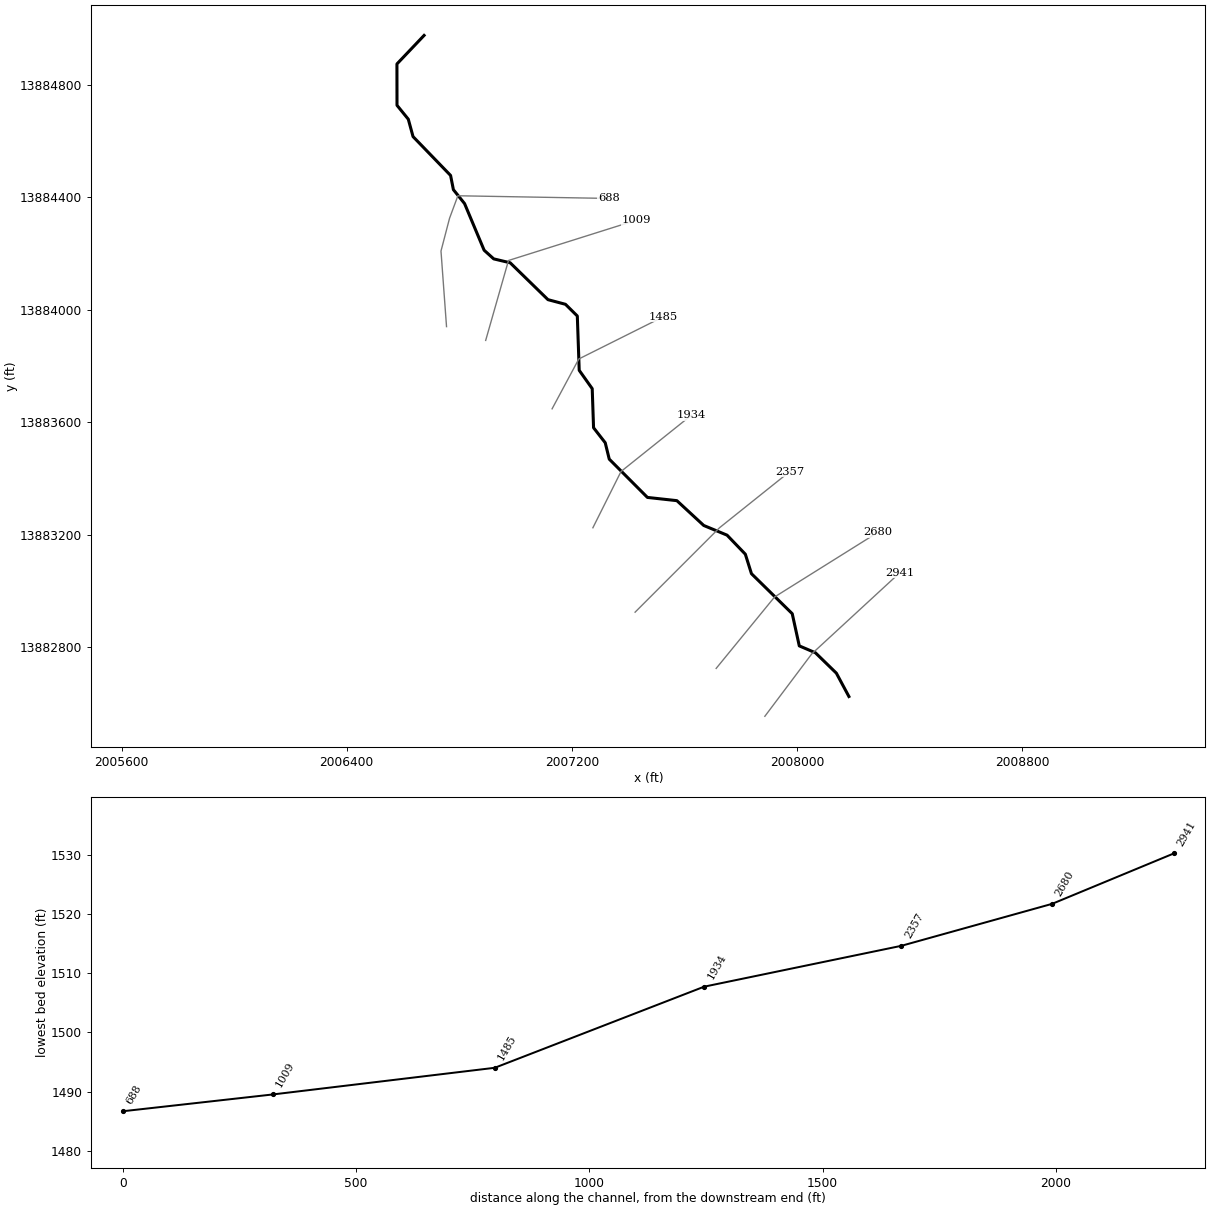
--- Stream0066_DS.prj (project) ---

Proj Title=Stream0066_DS Base Level Engineering
Current Plan=p01
Default Exp/Contr=0.3,0.1
English Units
Geom File=g01
Flow File=f01
Plan File=p01
BEGIN DESCRIPTION:
Stream0066_DS
END DESCRIPTION:

--- Stream0066_DS.p01 (plan) ---

Plan Title=Multiple Run
Short Identifier=Multiple
Geom File=g01
Flow File=f01
Subcritical Flow
K Sum by GR= 0
Std Step Tol= 0.01
Critical Tol= 0.01
Num of Std Step Trials= 20
Max Error Tol= 0.3
Flow Tol Ratio= 0.001
Split Flow NTrial= 30
Split Flow Tol= 0.02
Split Flow Ratio= 0.02
Log Output Level= 0
Friction Slope Method= 1
Unsteady Friction Slope Method= 2
Unsteady Bridges Friction Slope Method= 1
Parabolic Critical Depth
Global Vel Dist=  1 , 1 , 1
Global Log Level= 0
CheckData=True
Encroach Param= -1, 0, 0, 0
BEGIN DESCRIPTION:
Multiple Run
END DESCRIPTION:

--- Stream0066_DS.f01 (steady flow) ---

Flow Title=Multiple
Number of Profiles=7
Profile Names=10-year,25-year,50-year,1pct_min,100-year,1pct_plu,500-year
River Rch & RM= Stream0066_DS,Reach-1,2941
     545     896    1220     809    1614    3219    2786
River Rch & RM= Stream0066_DS,Reach-1,2357
     762    1277    1763    1183    2359    4708    4175
Boundary for River Rch & Prof#=Stream0066_DS,Reach-1,1
Up Type=0
Dn Type=3
Dn Slope=0.005
Boundary for River Rch & Prof#=Stream0066_DS,Reach-1,2
Up Type=0
Dn Type=3
Dn Slope=0.005
Boundary for River Rch & Prof#=Stream0066_DS,Reach-1,3
Up Type=0
Dn Type=3
Dn Slope=0.005
Boundary for River Rch & Prof#=Stream0066_DS,Reach-1,4
Up Type=0
Dn Type=3
Dn Slope=0.005
Boundary for River Rch & Prof#=Stream0066_DS,Reach-1,5
Up Type=0
Dn Type=3
Dn Slope=0.005
Boundary for River Rch & Prof#=Stream0066_DS,Reach-1,6
Up Type=0
Dn Type=3
Dn Slope=0.005
Boundary for River Rch & Prof#=Stream0066_DS,Reach-1,7
Up Type=0
Dn Type=3
Dn Slope=0.005

--- Stream0066_DS.g01 (geometry) ---

Geom Title=Existing Conditions

River Reach=Stream0066_DS,Reach-1
Reach XY= 30
      2008184.97     13882625.25      2008140.38     13882708.26
      2008065.93     13882780.73      2008008.60     13882805.17
      2007983.57     13882919.56      2007838.63     13883061.79
      2007816.85     13883131.07      2007751.88     13883198.73
      2007668.96     13883233.18      2007573.50     13883321.37
      2007468.83     13883332.86      2007333.14     13883468.94
      2007318.86     13883527.17      2007277.36     13883580.52
      2007272.61     13883719.47      2007226.38     13883784.66
      2007219.64     13883977.70      2007177.58     13884019.26
      2007115.34     13884035.79      2006981.03     13884166.83
      2006922.46     13884180.75      2006888.47     13884211.43
      2006818.92     13884377.20      2006779.19     13884426.74
      2006769.17     13884477.30      2006635.76     13884615.32
      2006618.86     13884677.17      2006578.74     13884726.56
      2006578.48     13884873.55      2006675.00     13884975.00

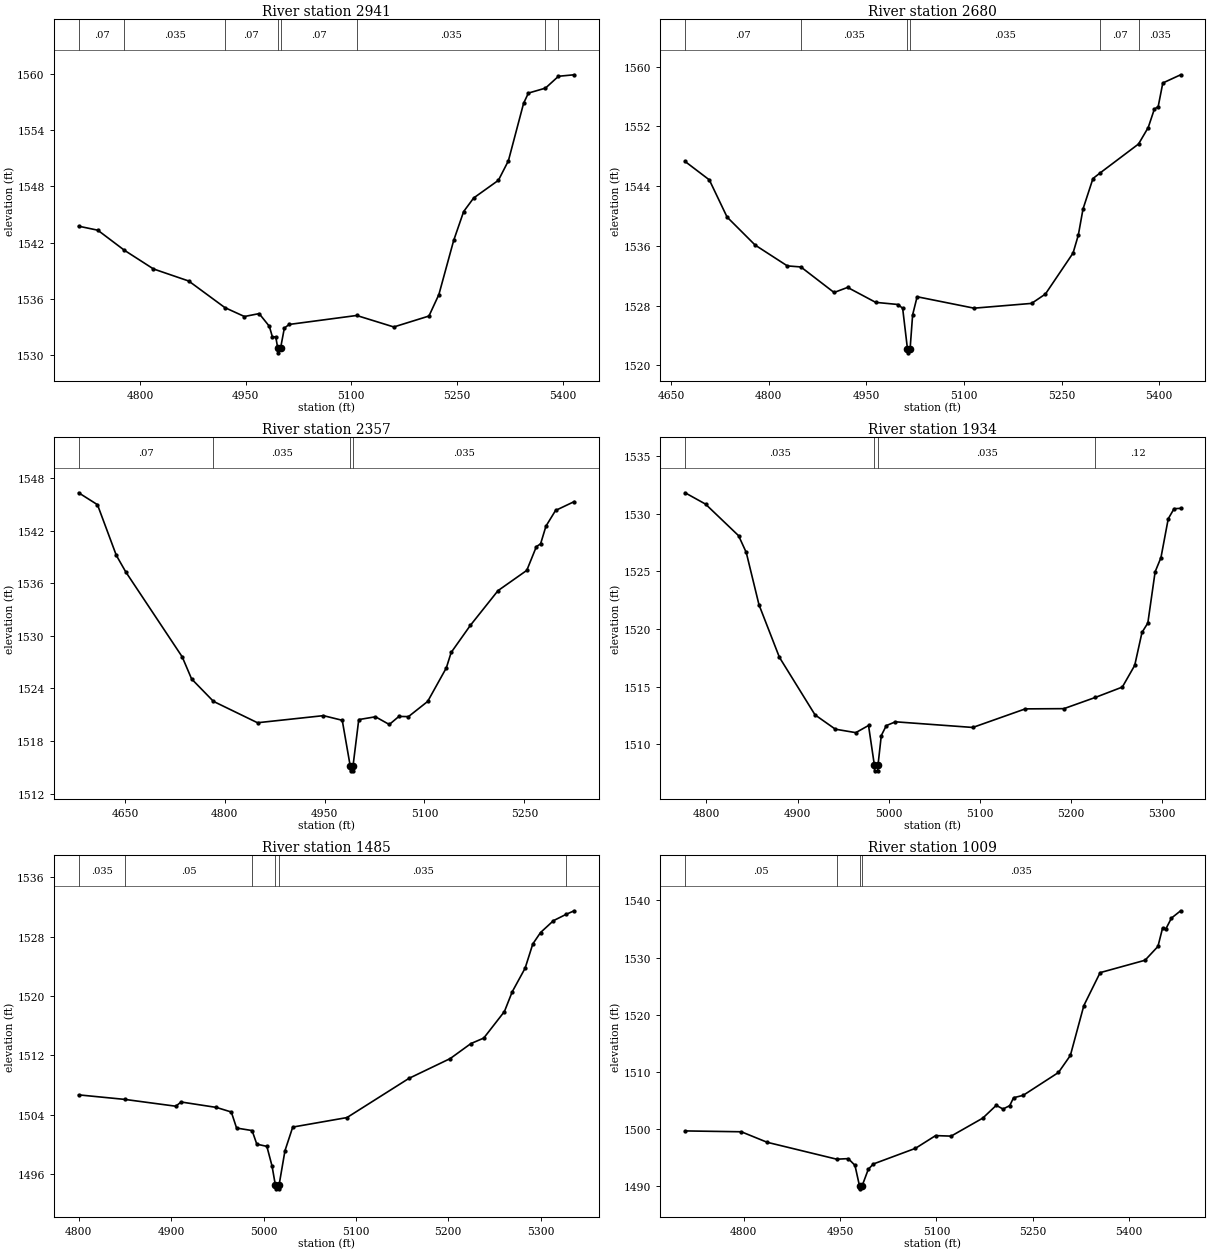
Type RM Length L Ch R = 1,2941,261,261,261
BEGIN DESCRIPTION:
Stream0066_DS 6.0
END DESCRIPTION:
XS GIS Cut Line= 3
      2007886.21     13882554.91      2008052.94     13882776.77
      2008366.23     13883065.55
#Sta/Elev= 30
  4712.9 1543.75  4740.1 1543.32  4777.9 1541.17  4819.2 1539.17  4869.2 1537.88
  4920.6 1535.03  4948.3 1534.08  4969.2 1534.39  4983.7 1533.03  4988.0 1531.90
  4992.8 1531.90  4995.6 1530.69  4995.9 1530.19  4999.6 1530.69  5005.0 1532.84
  5011.8 1533.23  5107.7 1534.19  5160.4 1532.96  5210.3 1534.13  5224.4 1536.43
  5245.4 1542.22  5259.6 1545.32  5273.8 1546.77  5308.9 1548.66  5323.1 1550.75
  5344.7 1556.91  5351.5 1558.00  5375.7 1558.53  5394.2 1559.80  5416.5 1559.96
#Mann=8,-1,0
  4712.9    0.07       0  4777.9   0.035       0  4920.6    0.07       0
  4995.6    0.05       0  4999.6    0.07       0  5107.7   0.035       0
  5375.7    0.07       0  5394.2   0.035       0
Bank Sta=4995.6,4999.6
Exp/Cntr=0.3,0.1

Type RM Length L Ch R = 1,2680,323,323,323
BEGIN DESCRIPTION:
Stream0066_DS 5.0
END DESCRIPTION:
XS GIS Cut Line= 3
      2007713.18     13882725.14      2007920.86     13882979.08
      2008288.24     13883208.91
#Sta/Elev= 30
  4671.4 1547.30  4708.6 1544.84  4735.9 1539.86  4779.0 1536.11  4828.5 1533.32
  4849.3 1533.18  4900.3 1529.76  4921.1 1530.44  4964.2 1528.44  4998.8 1528.15
  5005.7 1527.63  5013.1 1522.18  5013.4 1521.68  5017.1 1522.18  5021.0 1526.77
  5027.9 1529.19  5115.4 1527.66  5203.8 1528.30  5225.0 1529.55  5267.5 1535.04
  5275.6 1537.45  5282.8 1540.94  5298.1 1545.02  5309.6 1545.80  5368.1 1549.64
  5383.0 1551.85  5392.4 1554.31  5398.3 1554.65  5405.4 1557.81  5432.8 1558.91
#Mann=6,-1,0
  4671.4    0.07       0  4849.3   0.035       0  5013.1   0.035       0
  5017.1   0.035       0  5309.6    0.07       0  5368.1   0.035       0
Bank Sta=5013.1,5017.1
Exp/Cntr=0.3,0.1

Type RM Length L Ch R = 1,2357,423,423,423
BEGIN DESCRIPTION:
Stream0066_DS 4.0
END DESCRIPTION:
XS GIS Cut Line= 3
      2007424.98     13882924.98      2007725.00     13883225.00
      2007974.96     13883424.97
#Sta/Elev= 30
  4580.5 1546.34  4608.8 1544.98  4637.1 1539.20  4651.2 1537.32  4736.1 1527.61
  4750.2 1525.09  4783.0 1522.53  4849.2 1520.09  4948.2 1520.90  4976.5 1520.37
  4988.6 1515.10  4988.9 1514.60  4992.4 1514.60  4992.6 1515.10  5001.3 1520.45
  5026.4 1520.77  5047.2 1519.89  5061.6 1520.81  5076.0 1520.79  5104.8 1522.52
  5132.9 1526.36  5140.1 1528.11  5168.9 1531.20  5210.5 1535.17  5253.7 1537.48
  5268.1 1540.19  5274.5 1540.52  5282.5 1542.53  5296.9 1544.32  5324.9 1545.33
#Mann=4,-1,0
  4580.5    0.07       0  4783.0   0.035       0  4988.6   0.035       0
  4992.6   0.035       0
Bank Sta=4988.6,4992.6
Exp/Cntr=0.3,0.1

Type RM Length L Ch R = 1,1934,449,449,449
BEGIN DESCRIPTION:
Stream0066_DS 3.0
END DESCRIPTION:
XS GIS Cut Line= 3
      2007274.98     13883224.97      2007375.00     13883425.00
      2007625.00     13883625.00
#Sta/Elev= 30
  4776.6 1531.80  4799.0 1530.82  4835.3 1528.08  4843.7 1526.63  4857.7 1522.09
  4880.1 1517.54  4919.2 1512.55  4941.5 1511.31  4963.9 1511.01  4977.9 1511.63
  4984.3 1508.20  4984.5 1507.70  4988.0 1507.70  4988.3 1508.20  4991.9 1510.76
  4997.4 1511.62  5007.4 1511.95  5092.3 1511.46  5149.9 1513.07  5192.3 1513.09
  5226.7 1514.06  5256.4 1514.96  5270.0 1516.84  5278.0 1519.70  5284.4 1520.51
  5292.4 1524.95  5298.8 1526.18  5306.8 1529.55  5313.2 1530.42  5320.4 1530.45
#Mann=4,-1,0
  4776.6   0.035       0  4984.3   0.035       0  4988.3   0.035       0
  5226.7    0.12       0
Bank Sta=4984.3,4988.3
Exp/Cntr=0.3,0.1

Type RM Length L Ch R = 1,1485,476,476,476
BEGIN DESCRIPTION:
Stream0066_DS 2.0
END DESCRIPTION:
XS GIS Cut Line= 3
      2007130.02     13883647.80      2007225.00     13883825.00
      2007525.04     13883975.02
#Sta/Elev= 30
  4799.8 1506.67  4849.7 1506.06  4905.0 1505.14  4910.7 1505.71  4948.9 1504.98
  4965.1 1504.36  4970.8 1502.20  4987.6 1501.86  4992.7 1500.03  5003.6 1499.73
  5009.2 1497.08  5012.8 1494.51  5013.1 1494.01  5016.6 1494.01  5016.8 1494.51
  5023.2 1499.15  5031.6 1502.33  5090.3 1503.61  5157.4 1508.89  5202.1 1511.56
  5224.5 1513.58  5238.4 1514.32  5260.8 1517.90  5269.2 1520.55  5283.2 1523.74
  5291.5 1527.00  5299.9 1528.54  5313.9 1530.14  5327.6 1530.99  5336.3 1531.47
#Mann=6,-1,0
  4799.8   0.035       0  4849.7    0.05       0  4987.6   0.035       0
  5012.8   0.035       0  5016.8   0.035       0  5327.6    0.07       0
Bank Sta=5012.8,5016.8
Exp/Cntr=0.3,0.1

Type RM Length L Ch R = 1,1009,321,321,321
BEGIN DESCRIPTION:
Stream0066_DS 1.0
END DESCRIPTION:
XS GIS Cut Line= 3
      2006893.92     13883890.86      2006975.00     13884175.00
      2007428.62     13884317.96
#Sta/Elev= 30
  4708.9 1499.65  4796.4 1499.50  4836.6 1497.66  4944.8 1494.70  4962.8 1494.80
  4973.2 1493.63  4980.3 1490.01  4980.5 1489.51  4984.3 1490.01  4994.0 1492.94
  5001.8 1493.86  5067.3 1496.60  5098.7 1498.83  5122.9 1498.74  5172.1 1501.89
  5193.1 1504.13  5203.6 1503.48  5214.1 1504.08  5220.0 1505.46  5235.0 1505.88
  5289.9 1509.88  5308.4 1512.86  5329.4 1521.60  5354.7 1527.36  5424.6 1529.53
  5444.7 1531.95  5451.8 1535.13  5457.0 1535.02  5465.7 1536.91  5480.0 1538.19
#Mann=4,-1,0
  4708.9    0.05       0  4944.8   0.035       0  4980.3   0.035       0
  4984.3   0.035       0
Bank Sta=4980.3,4984.3
Exp/Cntr=0.3,0.1

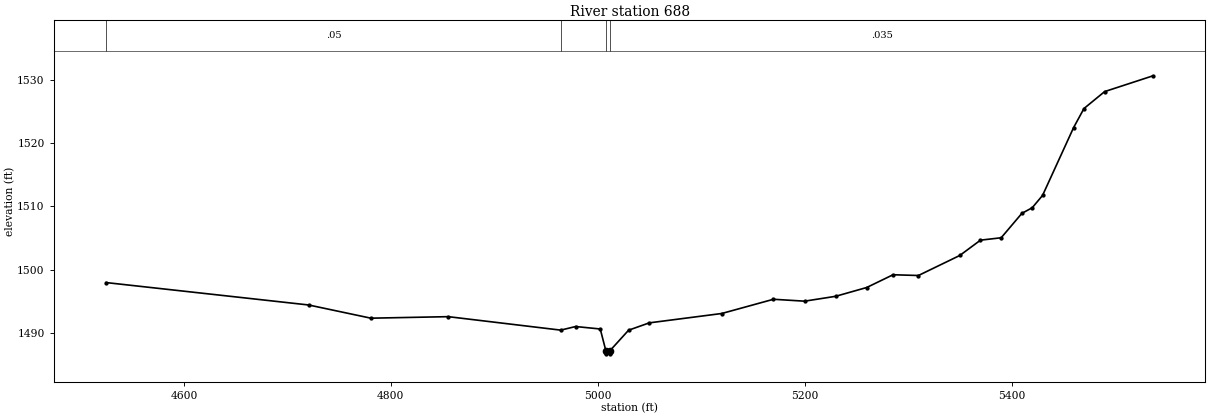
Type RM Length L Ch R = 1,688,0,0,0
BEGIN DESCRIPTION:
Stream0066_DS 0.0
END DESCRIPTION:
XS GIS Cut Line= 5
      2006754.77     13883939.92      2006735.10     13884208.54
      2006765.50     13884325.07      2006795.18     13884405.07
      2007331.80     13884395.55
#Sta/Elev= 30
  4524.9 1497.95  4720.5 1494.41  4780.7 1492.32  4855.5 1492.56  4964.2 1490.43
  4978.6 1491.00  5002.4 1490.61  5007.8 1487.18  5008.1 1486.68  5011.6 1486.68
  5011.8 1487.18  5029.8 1490.42  5049.8 1491.58  5119.8 1493.06  5169.8 1495.31
  5199.9 1495.01  5229.9 1495.78  5259.9 1497.17  5285.4 1499.19  5309.9 1499.07
  5349.9 1502.24  5369.9 1504.66  5389.9 1505.04  5409.9 1508.90  5419.9 1509.79
  5429.9 1511.74  5459.9 1522.47  5469.9 1525.48  5489.9 1528.16  5536.7 1530.66
#Mann=4,-1,0
  4524.9    0.05       0  4964.2   0.035       0  5007.8   0.035       0
  5011.8   0.035       0
Bank Sta=5007.8,5011.8
Exp/Cntr=0.3,0.1

Chan Stop Cuts=-1