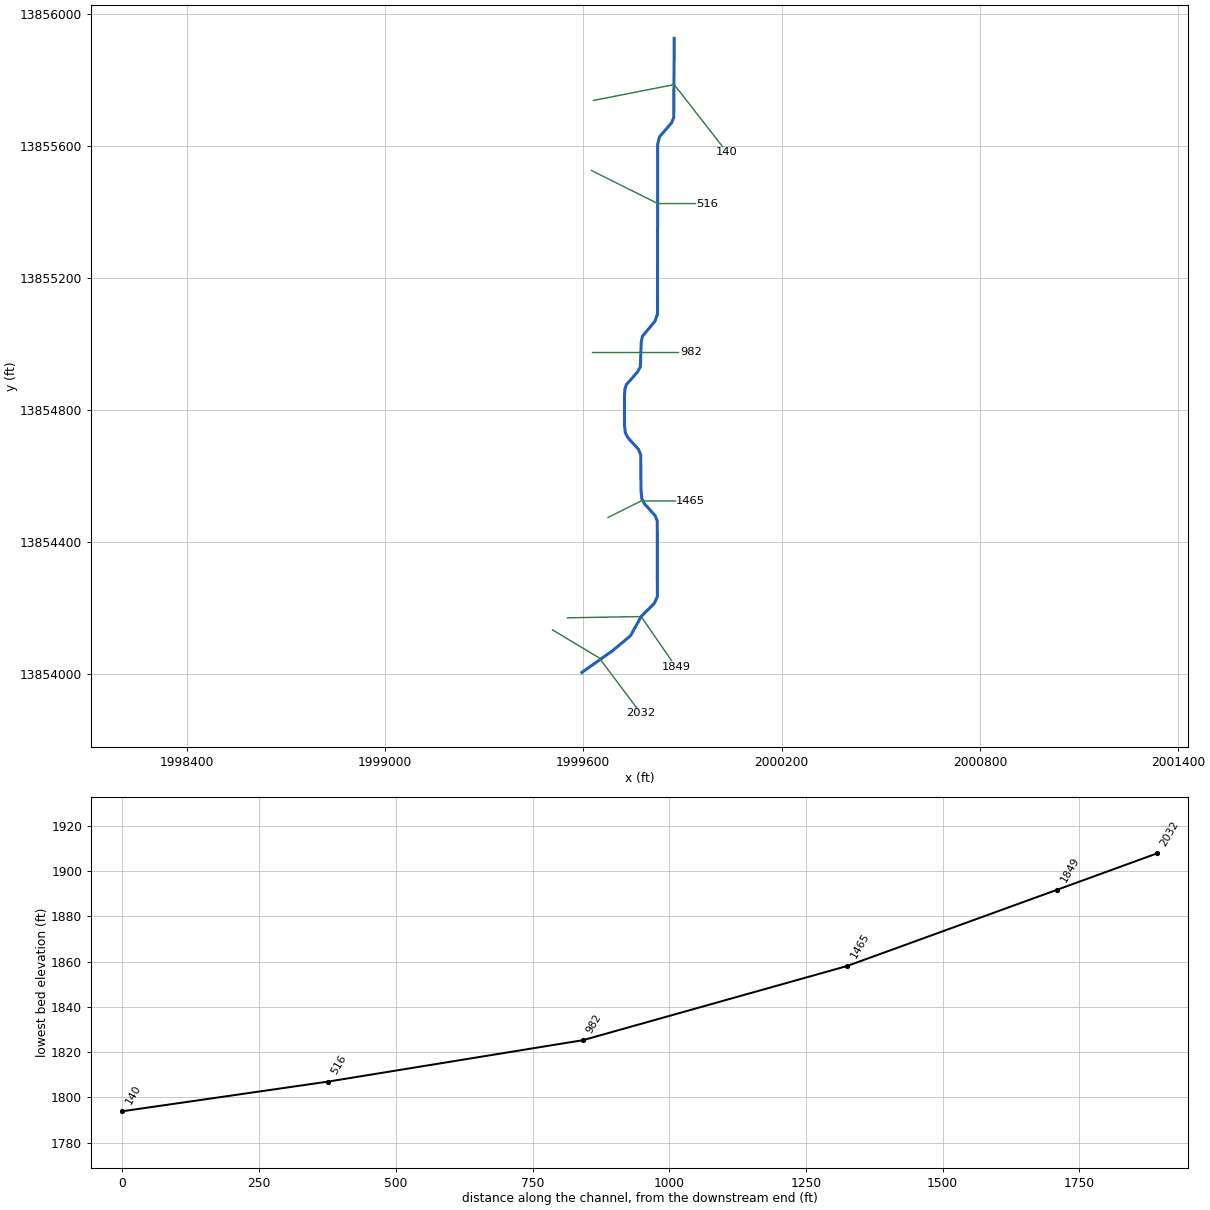
--- Stream0067_DS.prj (project) ---

Proj Title=Stream0067_DS Base Level Engineering
Current Plan=p01
Default Exp/Contr=0.3,0.1
English Units
Geom File=g01
Flow File=f01
Plan File=p01
BEGIN DESCRIPTION:
Stream0067_DS
END DESCRIPTION:

--- Stream0067_DS.p01 (plan) ---

Plan Title=Multiple Run
Short Identifier=Multiple
Geom File=g01
Flow File=f01
Subcritical Flow
K Sum by GR= 0
Std Step Tol= 0.01
Critical Tol= 0.01
Num of Std Step Trials= 20
Max Error Tol= 0.3
Flow Tol Ratio= 0.001
Split Flow NTrial= 30
Split Flow Tol= 0.02
Split Flow Ratio= 0.02
Log Output Level= 0
Friction Slope Method= 1
Unsteady Friction Slope Method= 2
Unsteady Bridges Friction Slope Method= 1
Parabolic Critical Depth
Global Vel Dist=  1 , 1 , 1
Global Log Level= 0
CheckData=True
Encroach Param= -1, 0, 0, 0
BEGIN DESCRIPTION:
Multiple Run
END DESCRIPTION:

--- Stream0067_DS.f01 (steady flow) ---

Flow Title=Multiple
Number of Profiles=7
Profile Names=10-year,25-year,50-year,1pct_min,100-year,1pct_plu,500-year
River Rch & RM= Stream0067_DS,Reach-1,2032
     250     386     506     323     645    1288    1033
Boundary for River Rch & Prof#=Stream0067_DS,Reach-1,1
Up Type=0
Dn Type=3
Dn Slope=0.005
Boundary for River Rch & Prof#=Stream0067_DS,Reach-1,2
Up Type=0
Dn Type=3
Dn Slope=0.005
Boundary for River Rch & Prof#=Stream0067_DS,Reach-1,3
Up Type=0
Dn Type=3
Dn Slope=0.005
Boundary for River Rch & Prof#=Stream0067_DS,Reach-1,4
Up Type=0
Dn Type=3
Dn Slope=0.005
Boundary for River Rch & Prof#=Stream0067_DS,Reach-1,5
Up Type=0
Dn Type=3
Dn Slope=0.005
Boundary for River Rch & Prof#=Stream0067_DS,Reach-1,6
Up Type=0
Dn Type=3
Dn Slope=0.005
Boundary for River Rch & Prof#=Stream0067_DS,Reach-1,7
Up Type=0
Dn Type=3
Dn Slope=0.005

--- Stream0067_DS.g01 (geometry) ---

Geom Title=Existing Conditions

River Reach=Stream0067_DS,Reach-1
Reach XY= 30
      1999595.86     13854005.99      1999688.30     13854071.43
      1999742.69     13854116.75      1999775.54     13854175.62
      1999814.95     13854215.02      1999824.04     13854235.40
      1999823.78     13854464.50      1999816.86     13854481.06
      1999785.86     13854515.36      1999777.27     13854530.94
      1999774.68     13854554.87      1999773.77     13854664.49
      1999766.85     13854681.05      1999735.85     13854715.35
      1999727.25     13854730.94      1999724.61     13854754.87
      1999724.61     13854845.13      1999726.20     13854864.49
      1999730.74     13854877.33      1999764.10     13854915.37
      1999772.64     13854930.98      1999775.24     13855004.90
      1999778.86     13855023.40      1999816.86     13855068.94
      1999824.48     13855090.22      1999825.07     13855604.97
      1999830.75     13855627.33      1999866.86     13855668.94
      1999873.78     13855685.50      1999875.00     13855925.00

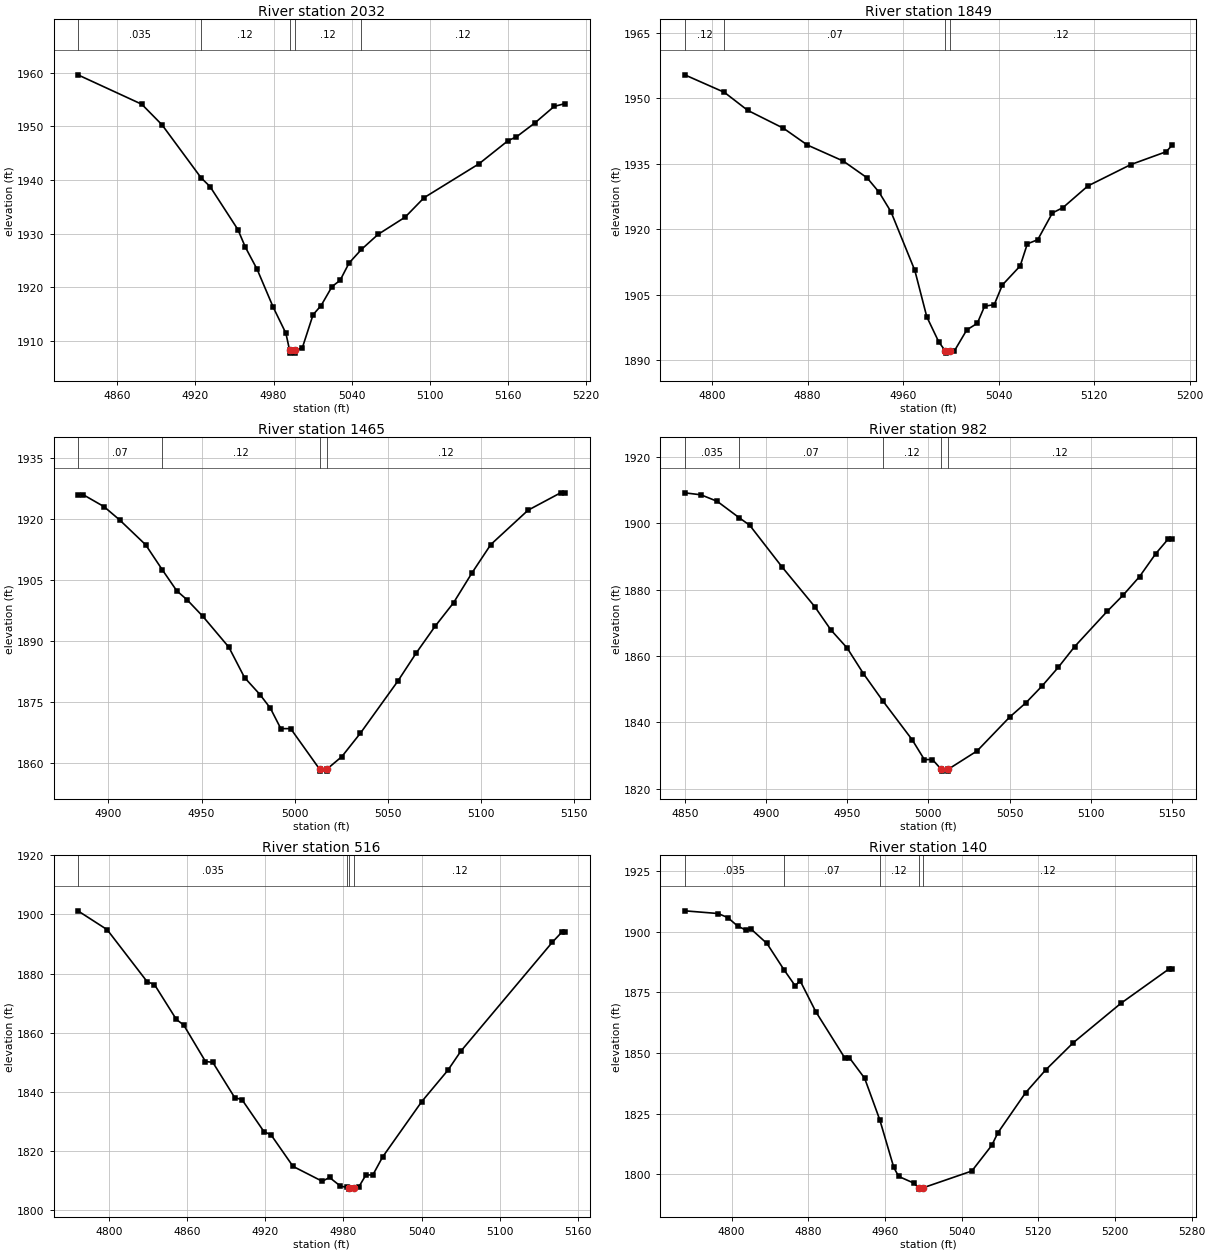
Type RM Length L Ch R = 1,2032,183,183,183
BEGIN DESCRIPTION:
Stream0067_DS 5.0
END DESCRIPTION:
XS GIS Cut Line= 3
      1999506.89     13854134.70      1999648.53     13854049.57
      1999774.15     13853881.98
#Sta/Elev= 30
  4829.6 1959.57  4878.7 1954.09  4894.3 1950.25  4924.3 1940.39  4931.2 1938.75
  4952.6 1930.75  4958.4 1927.44  4967.4 1923.34  4979.8 1916.26  4989.5 1911.44
  4992.4 1908.23  4992.7 1907.73  4996.2 1907.73  4996.4 1908.23  5002.1 1908.68
  5010.4 1914.88  5016.6 1916.60  5025.0 1920.13  5031.2 1921.29  5038.1 1924.52
  5047.6 1927.05  5060.4 1929.85  5081.2 1933.06  5095.8 1936.69  5138.0 1943.00
  5160.4 1947.32  5166.7 1948.00  5181.2 1950.66  5195.8 1953.69  5204.3 1954.22
#Mann=5,-1,0
  4829.6   0.035       0  4924.3    0.12       0  4992.4    0.05       0
  4996.4    0.12       0  5047.6    0.12       0
Bank Sta=4992.4,4996.4
Exp/Cntr=0.3,0.1

Type RM Length L Ch R = 1,1849,384,384,384
BEGIN DESCRIPTION:
Stream0067_DS 4.0
END DESCRIPTION:
XS GIS Cut Line= 3
      1999552.31     13854171.30      1999775.00     13854175.00
      1999880.32     13854022.44
#Sta/Elev= 30
  4777.1 1955.39  4810.3 1951.38  4829.8 1947.26  4859.8 1943.15  4879.8 1939.31
  4909.8 1935.65  4929.8 1931.80  4939.8 1928.52  4949.8 1924.03  4969.8 1910.58
  4979.8 1899.97  4989.8 1894.24  4995.3 1892.15  4995.6 1891.65  4999.3 1892.15
  5002.9 1892.15  5013.3 1896.97  5022.1 1898.48  5028.2 1902.39  5036.3 1902.76
  5043.1 1907.26  5058.0 1911.62  5064.0 1916.68  5072.7 1917.62  5085.0 1923.76
  5093.8 1924.97  5114.7 1929.94  5150.6 1934.83  5180.3 1937.78  5185.2 1939.27
#Mann=4,-1,0
  4777.1    0.12       0  4810.3    0.07       0  4995.3    0.05       0
  4999.3    0.12       0
Bank Sta=4995.3,4999.3
Exp/Cntr=0.3,0.1

Type RM Length L Ch R = 1,1465,483,483,483
BEGIN DESCRIPTION:
Stream0067_DS 3.0
END DESCRIPTION:
XS GIS Cut Line= 3
      1999674.98     13854474.99      1999775.00     13854525.00
      1999924.98     13854525.00
#Sta/Elev= 30
  4883.6 1926.00  4886.4 1926.00  4897.6 1923.06  4906.0 1919.79  4920.0 1913.67
  4929.0 1907.48  4936.7 1902.36  4942.3 1900.12  4950.7 1896.08  4964.7 1888.48
  4973.1 1881.03  4981.4 1876.84  4987.0 1873.48  4992.6 1868.46  4997.9 1868.46
  5013.4 1858.51  5013.7 1858.01  5017.2 1858.01  5017.4 1858.51  5025.4 1861.59
  5035.4 1867.37  5055.4 1880.10  5065.4 1887.10  5075.4 1893.58  5085.4 1899.42
  5095.4 1906.83  5105.4 1913.73  5125.4 1922.17  5142.9 1926.45  5145.4 1926.45
#Mann=4,-1,0
  4883.6    0.07       0  4929.0    0.12       0  5013.4    0.05       0
  5017.4    0.12       0
Bank Sta=5013.4,5017.4
Exp/Cntr=0.3,0.1

Type RM Length L Ch R = 1,982,466,466,466
BEGIN DESCRIPTION:
Stream0067_DS 2.0
END DESCRIPTION:
XS GIS Cut Line= 3
      1999625.00     13854975.00      1999775.00     13854975.00
      1999925.00     13854975.00
#Sta/Elev= 30
  4850.0 1909.23  4860.0 1908.63  4870.0 1906.67  4883.6 1901.69  4890.0 1899.45
  4910.0 1886.81  4930.0 1874.92  4940.0 1867.86  4950.0 1862.41  4960.0 1854.69
  4971.9 1846.50  4990.0 1834.75  4997.5 1828.77  5002.5 1828.77  5008.0 1825.78
  5008.3 1825.28  5011.8 1825.28  5012.0 1825.78  5030.0 1831.38  5050.0 1841.57
  5060.0 1845.88  5070.0 1850.97  5080.0 1856.62  5090.0 1862.83  5110.0 1873.45
  5120.0 1878.43  5130.0 1883.97  5140.0 1890.91  5147.5 1895.23  5150.0 1895.23
#Mann=5,-1,0
  4850.0   0.035       0  4883.6    0.07       0  4971.9    0.12       0
  5008.0    0.05       0  5012.0    0.12       0
Bank Sta=5008,5012
Exp/Cntr=0.3,0.1

Type RM Length L Ch R = 1,516,376,376,376
BEGIN DESCRIPTION:
Stream0067_DS 1.0
END DESCRIPTION:
XS GIS Cut Line= 3
      1999625.00     13855525.00      1999825.00     13855425.00
      1999974.99     13855425.00
#Sta/Elev= 30
  4776.4 1901.23  4798.8 1894.86  4829.5 1877.22  4835.1 1876.26  4851.9 1864.44
  4857.5 1862.57  4874.2 1850.21  4879.8 1849.93  4896.6 1837.99  4902.2 1837.29
  4919.0 1826.48  4924.5 1825.35  4941.3 1814.71  4963.7 1809.66  4969.3 1810.95
  4977.7 1808.00  4982.9 1807.59  4984.0 1807.50  4984.3 1807.00  4988.0 1807.50
  4991.6 1807.65  4997.2 1811.80  5002.5 1811.80  5010.0 1817.90  5040.0 1836.65
  5060.0 1847.24  5070.0 1853.73  5140.0 1890.55  5147.5 1894.07  5150.0 1894.07
#Mann=4,-1,0
  4776.4   0.035       0  4982.9    0.12       0  4984.0    0.05       0
  4988.0    0.12       0
Bank Sta=4984,4988
Exp/Cntr=0.3,0.1

Type RM Length L Ch R = 1,140,0,0,0
BEGIN DESCRIPTION:
Stream0067_DS 0.0
END DESCRIPTION:
XS GIS Cut Line= 3
      1999630.81     13855737.03      1999875.05     13855784.98
      2000034.56     13855580.29
#Sta/Elev= 30
  4751.1 1908.58  4785.9 1907.47  4796.1 1905.78  4806.3 1902.30  4814.9 1900.66
  4820.0 1901.18  4836.9 1895.12  4854.8 1884.22  4866.4 1877.65  4871.4 1879.84
  4887.8 1867.05  4917.8 1848.14  4922.9 1848.04  4938.8 1839.59  4954.6 1822.46
  4969.2 1802.84  4974.3 1799.15  4989.8 1796.45  4995.4 1794.42  4995.7 1793.92
  4999.4 1794.42  5050.6 1801.38  5071.4 1811.95  5077.8 1817.14  5106.7 1833.64
  5127.5 1842.97  5156.5 1854.27  5206.2 1870.50  5255.8 1884.49  5259.5 1884.49
#Mann=5,-1,0
  4751.1   0.035       0  4854.8    0.07       0  4954.6    0.12       0
  4995.4    0.05       0  4999.4    0.12       0
Bank Sta=4995.4,4999.4
Exp/Cntr=0.3,0.1

Chan Stop Cuts=-1