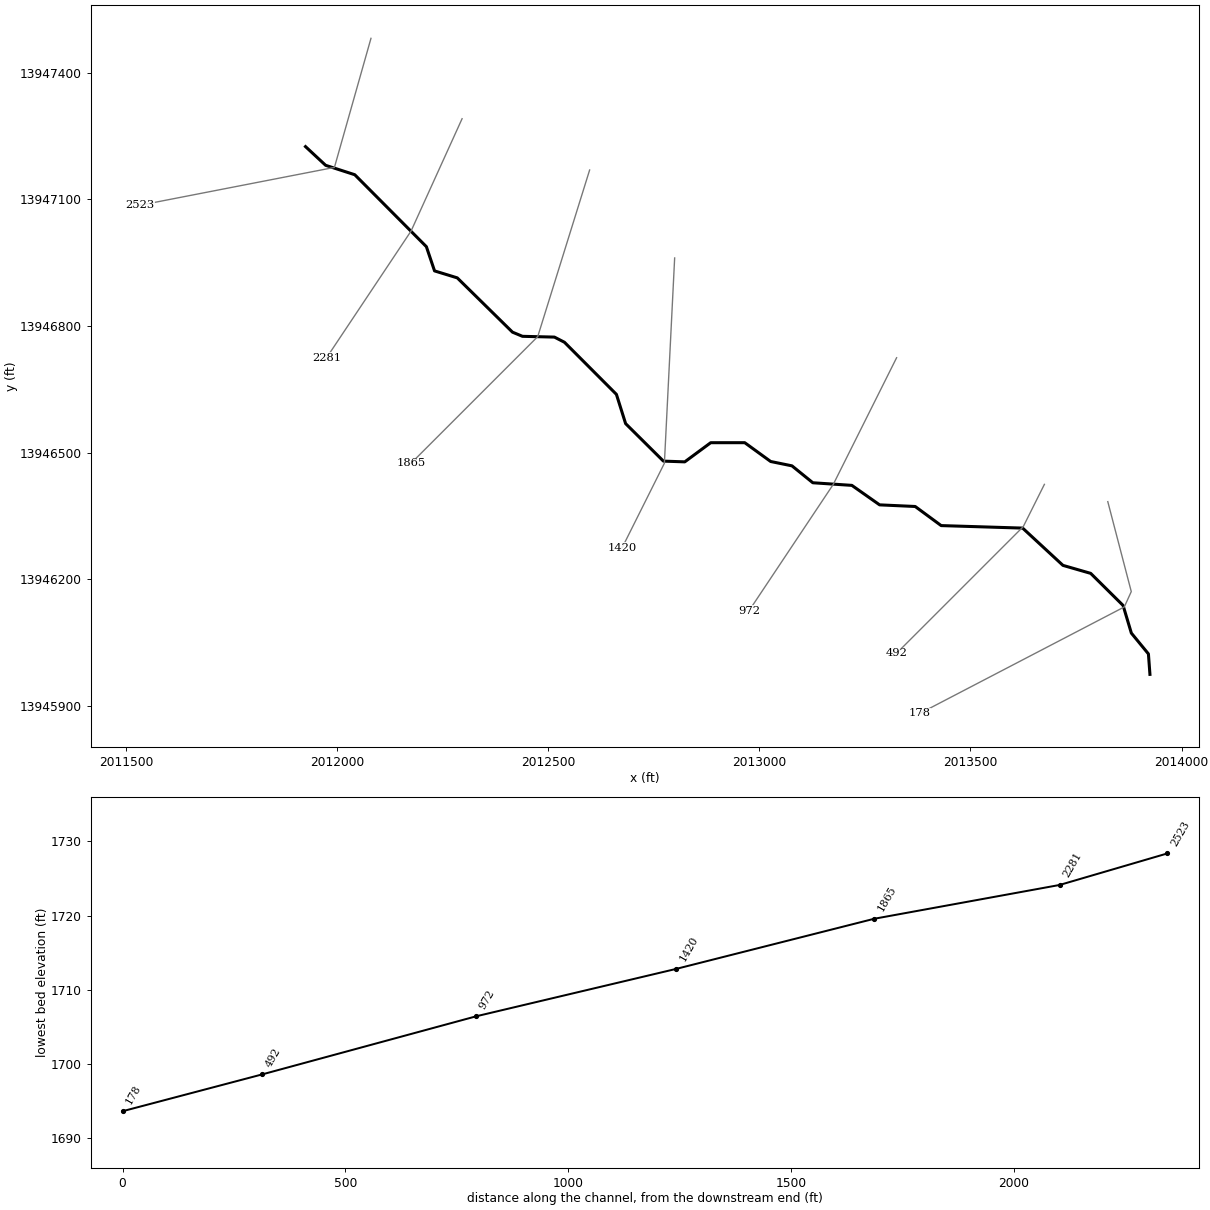
--- Stream0068_DS.prj (project) ---

Proj Title=Stream0068_DS Base Level Engineering
Current Plan=p01
Default Exp/Contr=0.3,0.1
English Units
Geom File=g01
Flow File=f01
Plan File=p01
Y Axis Title=Elevation
X Axis Title(PF)=Main Channel Distance
X Axis Title(XS)=Station
BEGIN DESCRIPTION:
Stream0068_DS
END DESCRIPTION:
DSS Export Rating Curves= 0
DSS Export Rating Curve Sorted= 0
DSS Export Volume Flow Curves= 0
DXF OffsetX= 0
DXF OffsetY= 0
DXF ScaleX= 1
DXF ScaleY= 10

--- Stream0068_DS.p01 (plan) ---

Plan Title=Multiple Run
Short Identifier=Multiple
Geom File=g01
Flow File=f01
Subcritical Flow
K Sum by GR= 0
Std Step Tol= 0.01
Critical Tol= 0.01
Num of Std Step Trials= 20
Max Error Tol= 0.3
Flow Tol Ratio= 0.001
Split Flow NTrial= 30
Split Flow Tol= 0.02
Split Flow Ratio= 0.02
Log Output Level= 0
Friction Slope Method= 1
Unsteady Friction Slope Method= 2
Unsteady Bridges Friction Slope Method= 1
Parabolic Critical Depth
Global Vel Dist=  1 , 1 , 1
Global Log Level= 0
CheckData=True
Encroach Param= -1, 0, 0, 0
BEGIN DESCRIPTION:
Multiple Run
END DESCRIPTION:

--- Stream0068_DS.f01 (steady flow) ---

Flow Title=Multiple
Number of Profiles=7
Profile Names=10-year,25-year,50-year,1pct_min,100-year,1pct_plu,500-year
River Rch & RM= Stream0068_DS,Reach-1,2523
     828    1413    1975    1342    2677    5342    4877
River Rch & RM= Stream0068_DS,Reach-1,2281
     954    1638    2298    1566    3124    6234    5727
Boundary for River Rch & Prof#=Stream0068_DS,Reach-1,1
Up Type=0
Dn Type=3
Dn Slope=0.005
Boundary for River Rch & Prof#=Stream0068_DS,Reach-1,2
Up Type=0
Dn Type=3
Dn Slope=0.005
Boundary for River Rch & Prof#=Stream0068_DS,Reach-1,3
Up Type=0
Dn Type=3
Dn Slope=0.005
Boundary for River Rch & Prof#=Stream0068_DS,Reach-1,4
Up Type=0
Dn Type=3
Dn Slope=0.005
Boundary for River Rch & Prof#=Stream0068_DS,Reach-1,5
Up Type=0
Dn Type=3
Dn Slope=0.005
Boundary for River Rch & Prof#=Stream0068_DS,Reach-1,6
Up Type=0
Dn Type=3
Dn Slope=0.005
Boundary for River Rch & Prof#=Stream0068_DS,Reach-1,7
Up Type=0
Dn Type=3
Dn Slope=0.005

--- Stream0068_DS.g01 (geometry) ---

Geom Title=Existing Conditions
Program Version=4.10

River Reach=Stream0068_DS   ,Reach-1
Reach XY= 30
        2011925.       13947225.      2011972.65     13947180.71
      2012041.69     13947158.39      2012211.27     13946987.98
      2012230.62     13946930.62      2012284.42     13946914.11
      2012415.21     13946785.52      2012438.92     13946775.67
      2012514.52     13946773.83       2012538.3      13946761.6
      2012661.37     13946638.21      2012683.15     13946568.93
      2012772.69     13946480.08      2012823.25     13946478.34
       2012884.7     13946523.71       2012965.3     13946523.75
      2013026.73     13946479.19      2013077.18     13946468.89
      2013126.58     13946428.83      2013219.03     13946422.65
      2013284.71     13946376.49      2013369.02     13946372.64
      2013430.53     13946327.38      2013623.53     13946321.45
      2013718.96     13946233.18       2013784.7     13946214.23
       2013861.4     13946138.24      2013880.98     13946072.76
       2013921.4     13946023.51        2013925.       13945975.

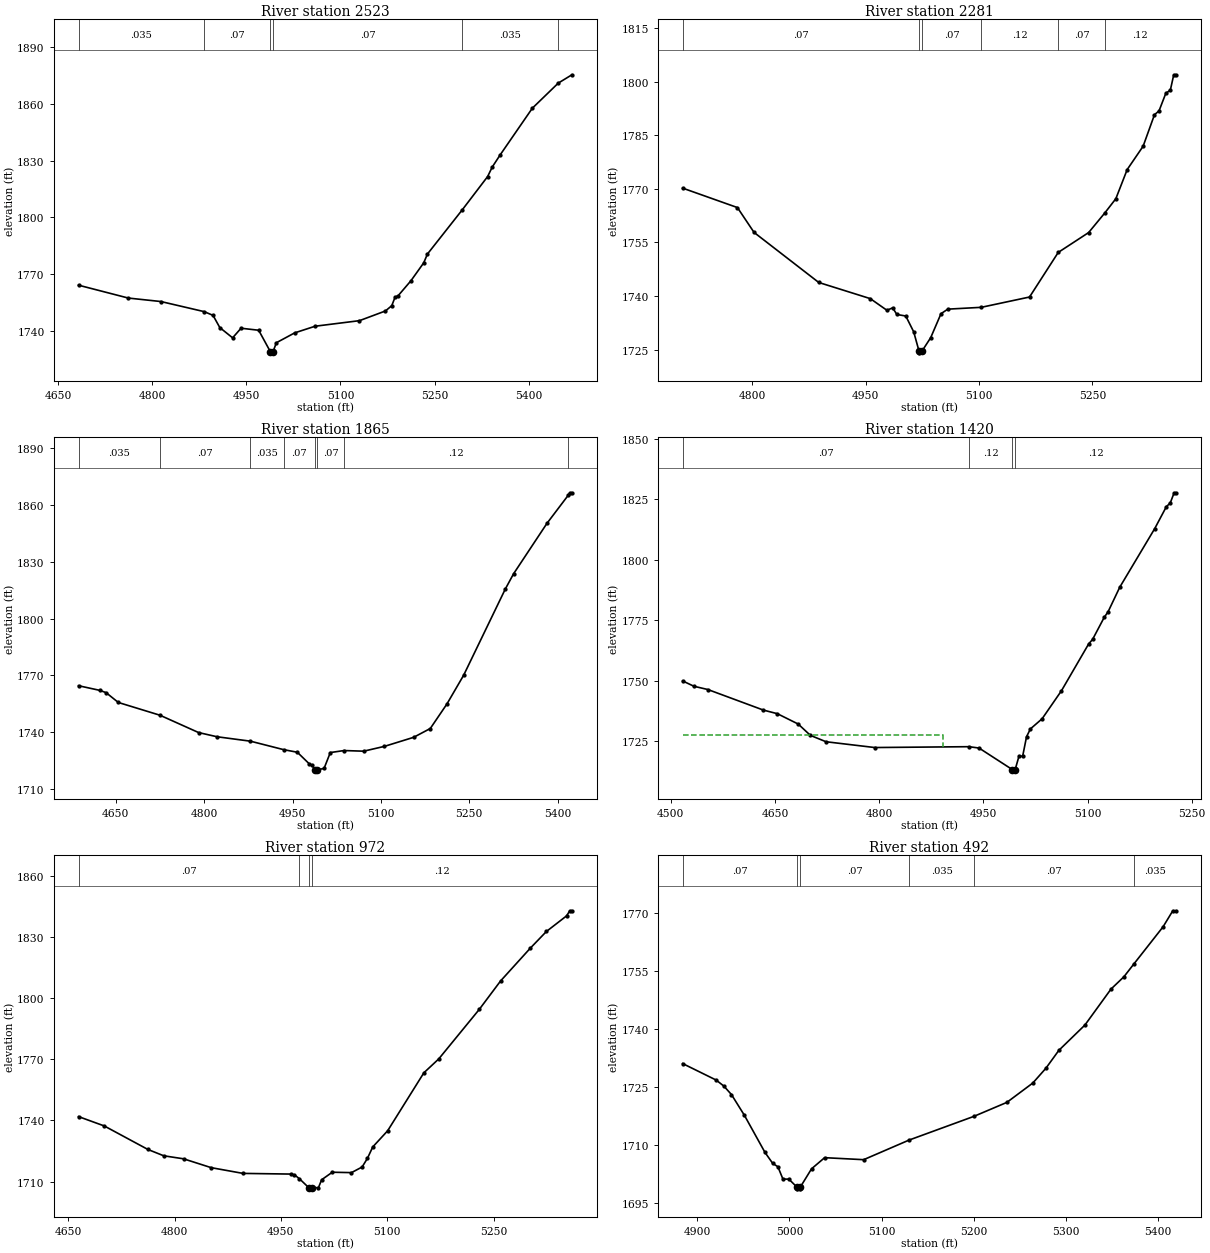
Type RM Length L Ch R = 1 ,2523    ,242,242,242
BEGIN DESCRIPTION:
Stream0068_DS 6.0
END DESCRIPTION:
XS GIS Cut Line= 3
      2012080.05     13947481.43      2011993.49     13947175.75
      2011533.03     13947086.14
#Sta/Elev= 30
  4682.3 1764.17  4761.7 1757.36  4813.7 1755.52  4882.8 1750.17  4896.8  1748.2
  4907.6 1741.75    4928 1736.32  4941.5  1741.4  4969.6 1740.33  4988.4 1728.88
  4988.6 1728.38  4992.4 1728.88  4997.8 1733.73    5027 1738.94  5059.6 1742.46
  5130.3  1745.4  5171.7 1750.53  5181.8 1753.32    5187 1757.74  5192.1 1758.65
  5212.4 1766.52  5232.8 1776.01  5238.7 1780.65  5294.3 1804.06  5334.7 1821.64
    5342 1826.65    5355 1833.26    5406  1857.8  5447.4 1871.09  5469.1 1875.48
#Mann= 6 ,-1 , 0
  4682.3    .035       0  4882.8     .07       0  4988.4     .05       0
  4992.4     .07       0  5294.3    .035       0  5447.4     .07       0
Bank Sta=4988.4,4992.4
XS Rating Curve= 0 ,0
Exp/Cntr=0.3,0.1

Type RM Length L Ch R = 1 ,2281    ,416,416,416
BEGIN DESCRIPTION:
Stream0068_DS 5.0
END DESCRIPTION:
XS GIS Cut Line= 3
      2012295.83     13947291.04        2012175.       13947025.
      2011975.02     13946725.04
#Sta/Elev= 30
    4708  1770.2  4780.5 1764.76  4802.5 1757.81  4888.1 1743.81  4956.3 1739.29
  4978.2 1736.04  4985.9 1736.71  4991.4 1734.86  5003.2 1734.43  5013.7    1730
  5020.7 1724.63    5021 1724.13  5024.7 1724.63  5036.2 1728.38  5049.8 1735.08
  5058.8 1736.35  5103.1 1736.86  5166.9 1739.74  5204.9 1752.22  5245.1 1757.77
  5266.3  1763.2  5281.1 1767.24  5296.1 1775.39  5317.2 1781.92  5332.2 1790.73
  5338.2 1791.79  5347.2 1796.72  5353.2 1797.61  5357.7  1801.9  5360.7  1801.9
#Mann= 6 ,-1 , 0
    4708     .07       0  5020.7     .05       0  5024.7     .07       0
  5103.1     .12       0  5204.9     .07       0  5266.3     .12       0
Bank Sta=5020.7,5024.7
XS Rating Curve= 0 ,0
Exp/Cntr=0.3,0.1

Type RM Length L Ch R = 1 ,1865    ,445,445,445
BEGIN DESCRIPTION:
Stream0068_DS 4.0
END DESCRIPTION:
XS GIS Cut Line= 3
      2012597.93     13947169.57        2012475.       13946775.
      2012175.03     13946475.03
#Sta/Elev= 30
  4586.7 1764.54  4622.9 1762.08  4633.4 1760.89  4654.3 1755.69  4724.9 1748.96
  4790.5  1739.8  4821.9 1737.58  4878.6 1735.24  4934.9 1730.77  4958.1  1729.4
  4978.5 1723.24  4983.7 1722.44  4987.5 1720.08  4987.8 1719.58  4991.5 1720.08
  5003.5 1720.86  5014.1 1729.24  5037.6  1730.3  5070.7 1729.96    5106 1732.51
  5155.5 1737.28  5183.8 1741.94  5212.1 1754.92  5240.4 1770.06  5311.1 1815.59
  5325.2 1823.68  5381.8 1850.28    5418 1865.16  5420.7 1866.45  5424.2 1866.45
#Mann= 8 ,-1 , 0
  4586.7    .035       0  4724.9     .07       0  4878.6    .035       0
  4934.9     .07       0  4987.5     .05       0  4991.5     .07       0
  5037.6     .12       0    5418     .07       0
Bank Sta=4987.5,4991.5
XS Rating Curve= 0 ,0
Exp/Cntr=0.3,0.1

Type RM Length L Ch R = 1 ,1420    ,448,448,448
BEGIN DESCRIPTION:
Stream0068_DS 3.0
END DESCRIPTION:
XS GIS Cut Line= 3
      2012799.31     13946961.23        2012775.       13946475.
      2012675.02     13946275.04
#Sta/Elev= 30
    4517 1749.94  4533.3 1747.73  4553.3 1746.39  4633.4 1737.89  4653.4 1736.41
  4683.4 1732.14    4701 1727.45  4723.5 1724.83  4793.6 1722.44  4929.2 1722.79
  4943.8 1722.23  4991.8 1713.32  4992.1 1712.82  4995.8 1713.32  5001.3 1718.88
  5006.6 1718.88  5012.2 1726.92  5017.8 1730.14  5034.6 1734.32  5062.5  1745.9
  5101.7 1765.25  5107.3 1767.09    5124 1776.17  5129.6 1778.49  5146.4 1788.63
  5196.7  1812.8  5213.5 1821.88  5219.1  1823.4  5224.7 1827.61  5227.4 1827.61
#Mann= 4 ,-1 , 0
    4517     .07       0  4929.2     .12       0  4991.8     .05       0
  4995.8     .12       0
#XS Ineff= 2 , 0
       0  4891.2  1727.6               0
Permanent Ineff=
       F       F
Bank Sta=4991.8,4995.8
XS Rating Curve= 0 ,0
Exp/Cntr=0.3,0.1

Type RM Length L Ch R = 1 ,972     ,480,480,480
BEGIN DESCRIPTION:
Stream0068_DS 2.0
END DESCRIPTION:
XS GIS Cut Line= 3
      2013324.98     13946724.97        2013175.       13946425.
      2012975.02     13946125.03
#Sta/Elev= 30
  4664.6 1741.91  4700.9 1737.32  4762.4 1725.79  4784.8 1722.67  4812.7 1721.19
  4851.8 1716.84  4896.6 1714.03  4963.6  1713.7  4969.2 1713.31  4976.1 1711.43
  4989.6 1706.95  4989.8 1706.45  4993.6 1706.95    5003 1707.05  5007.5  1710.9
  5022.5  1714.6  5049.6 1714.41  5064.6 1717.17  5072.1 1721.43  5079.6 1727.02
  5100.6 1734.95  5151.7 1763.41  5172.7 1770.23  5229.8 1794.51  5259.9 1808.49
  5301.9 1824.61  5324.5 1832.76    5353 1840.44  5357.5 1842.93  5360.5 1842.93
#Mann= 4 ,-1 , 0
  4664.6     .07       0  4976.1     .12       0  4989.6     .05       0
  4993.6     .12       0
Bank Sta=4989.6,4993.6
XS Rating Curve= 0 ,0
Exp/Cntr=0.3,0.1

Type RM Length L Ch R = 1 ,492     ,314,314,314
BEGIN DESCRIPTION:
Stream0068_DS 1.0
END DESCRIPTION:
XS GIS Cut Line= 3
      2013675.01     13946425.03        2013625.       13946325.
        2013325.       13946025.
#Sta/Elev= 30
  4883.9 1730.99  4920.3 1726.73  4928.7 1725.17    4937 1722.97    4951 1717.63
  4973.4 1708.03  4981.8  1705.2  4987.4 1704.34  4992.9 1701.14  4999.3 1701.14
  5007.9 1699.13  5008.1 1698.63  5011.6 1698.63  5011.9 1699.13    5024 1703.81
  5038.2 1706.68  5080.6 1706.16    5130 1711.23  5200.4 1717.35  5236.2 1720.96
  5264.4 1725.96  5278.6 1729.77  5292.7  1734.4    5321 1740.93  5349.3 1750.21
  5363.4 1753.41  5374.2 1756.71  5405.9  1766.3  5416.5 1770.45    5420 1770.45
#Mann= 6 ,-1 , 0
  4883.9     .07       0  5007.9     .05       0  5011.9     .07       0
    5130    .035       0  5200.4     .07       0  5374.2    .035       0
Bank Sta=5007.9,5011.9
XS Rating Curve= 0 ,0
Exp/Cntr=0.3,0.1

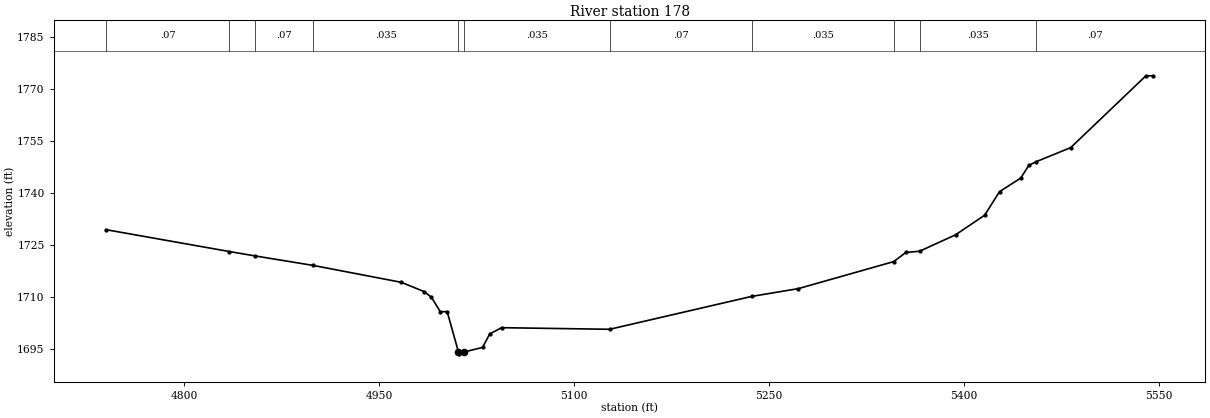
Type RM Length L Ch R = 1 ,178     ,0,0,0
BEGIN DESCRIPTION:
Stream0068_DS 0.0
END DESCRIPTION:
XS GIS Cut Line= 4
      2013825.18     13946384.08      2013880.79     13946171.05
      2013864.25     13946134.71      2013380.15     13945882.63
#Sta/Elev= 30
  4739.9 1729.45  4834.8 1723.15  4854.2 1721.91  4899.4 1719.14  4967.1 1714.28
  4984.7  1711.6  4990.2 1709.99  4997.1 1705.82  5002.4 1705.82  5011.1 1694.16
  5011.4 1693.66  5015.1 1694.16  5029.6 1695.51  5035.2 1699.41  5044.3  1701.2
  5127.5 1700.74  5236.8 1710.22  5272.7 1712.46  5346.2 1720.26  5355.5  1722.9
    5366 1723.23  5393.8 1727.99  5416.1 1733.62  5427.6 1740.42  5443.9 1744.34
  5450.1 1747.97  5455.6 1749.03  5482.4 1753.12  5540.3 1773.83  5545.8 1773.83
#Mann= 11 ,-1 , 0
  4739.9     .07       0  4834.8    .035       0  4854.2     .07       0
  4899.4    .035       0  5011.1    .035       0  5015.1    .035       0
  5127.5     .07       0  5236.8    .035       0  5346.2     .07       0
    5366    .035       0  5455.6     .07       0
Bank Sta=5011.1,5015.1
XS Rating Curve= 0 ,0
Exp/Cntr=0.3,0.1

Chan Stop Cuts=-1
Use User Specified Reach Order=0
Composite Channel Slope=5