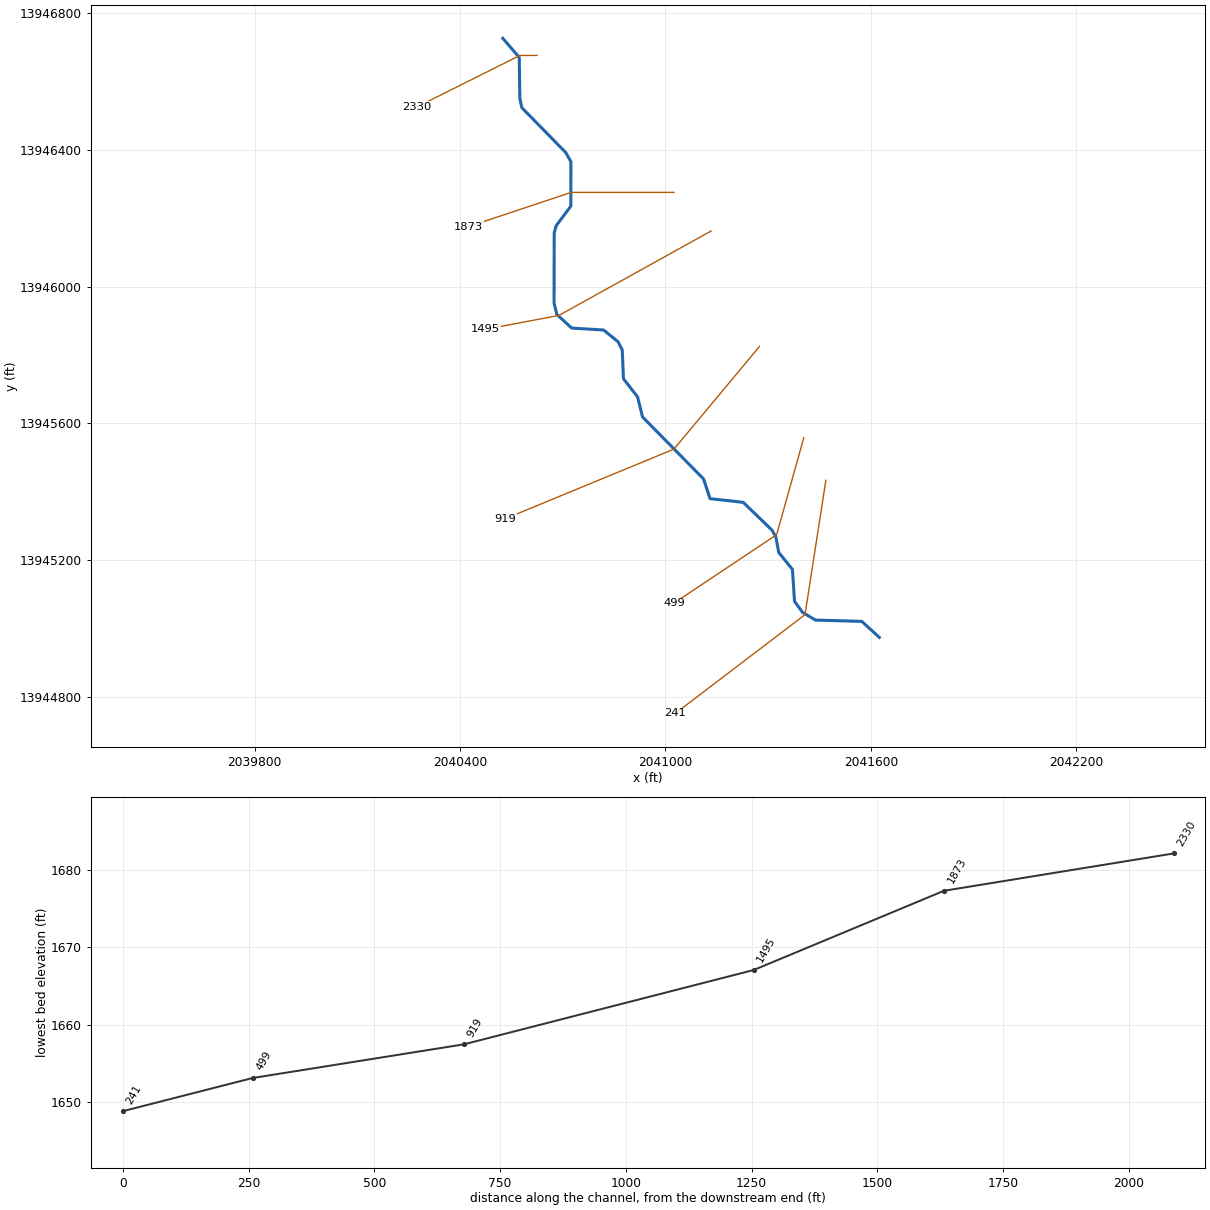
--- Stream0069_DS.prj (project) ---

Proj Title=Stream0069_DS Base Level Engineering
Current Plan=p01
Default Exp/Contr=0.3,0.1
English Units
Geom File=g01
Flow File=f01
Plan File=p01
BEGIN DESCRIPTION:
Stream0069_DS
END DESCRIPTION:

--- Stream0069_DS.p01 (plan) ---

Plan Title=Multiple Run
Short Identifier=Multiple
Geom File=g01
Flow File=f01
Subcritical Flow
K Sum by GR= 0
Std Step Tol= 0.01
Critical Tol= 0.01
Num of Std Step Trials= 20
Max Error Tol= 0.3
Flow Tol Ratio= 0.001
Split Flow NTrial= 30
Split Flow Tol= 0.02
Split Flow Ratio= 0.02
Log Output Level= 0
Friction Slope Method= 1
Unsteady Friction Slope Method= 2
Unsteady Bridges Friction Slope Method= 1
Parabolic Critical Depth
Global Vel Dist=  1 , 1 , 1
Global Log Level= 0
CheckData=True
Encroach Param= -1, 0, 0, 0
BEGIN DESCRIPTION:
Multiple Run
END DESCRIPTION:

--- Stream0069_DS.f01 (steady flow) ---

Flow Title=Multiple
Number of Profiles=7
Profile Names=10-year,25-year,50-year,1pct_min,100-year,1pct_plu,500-year
River Rch & RM= Stream0069_DS,Reach-1,2330
     685    1158    1608    1087    2169    4327    3907
River Rch & RM= Stream0069_DS,Reach-1,1873
     822    1403    1960    1331    2655    5297    4830
Boundary for River Rch & Prof#=Stream0069_DS,Reach-1,1
Up Type=0
Dn Type=3
Dn Slope=0.005
Boundary for River Rch & Prof#=Stream0069_DS,Reach-1,2
Up Type=0
Dn Type=3
Dn Slope=0.005
Boundary for River Rch & Prof#=Stream0069_DS,Reach-1,3
Up Type=0
Dn Type=3
Dn Slope=0.005
Boundary for River Rch & Prof#=Stream0069_DS,Reach-1,4
Up Type=0
Dn Type=3
Dn Slope=0.005
Boundary for River Rch & Prof#=Stream0069_DS,Reach-1,5
Up Type=0
Dn Type=3
Dn Slope=0.005
Boundary for River Rch & Prof#=Stream0069_DS,Reach-1,6
Up Type=0
Dn Type=3
Dn Slope=0.005
Boundary for River Rch & Prof#=Stream0069_DS,Reach-1,7
Up Type=0
Dn Type=3
Dn Slope=0.005

--- Stream0069_DS.g01 (geometry) ---

Geom Title=Existing Conditions

River Reach=Stream0069_DS,Reach-1
Reach XY= 30
      2040525.00     13946725.00      2040573.09     13946669.21
      2040574.72     13946549.88      2040580.46     13946522.55
      2040708.57     13946391.76      2040723.96     13946364.56
      2040723.63     13946234.67      2040680.75     13946177.33
      2040675.21     13946156.73      2040674.59     13945952.03
      2040682.68     13945918.48      2040726.25     13945878.51
      2040819.31     13945872.93      2040861.77     13945838.72
      2040873.91     13945814.69      2040877.45     13945730.56
      2040918.86     13945677.17      2040933.14     13945618.94
      2041111.26     13945437.95      2041130.47     13945380.26
      2041227.38     13945369.46      2041311.39     13945288.24
      2041322.51     13945268.98      2041331.14     13945222.83
      2041371.17     13945173.41      2041377.17     13945080.27
      2041400.98     13945047.66      2041438.71     13945025.48
      2041573.63     13945021.70      2041625.00     13944975.00

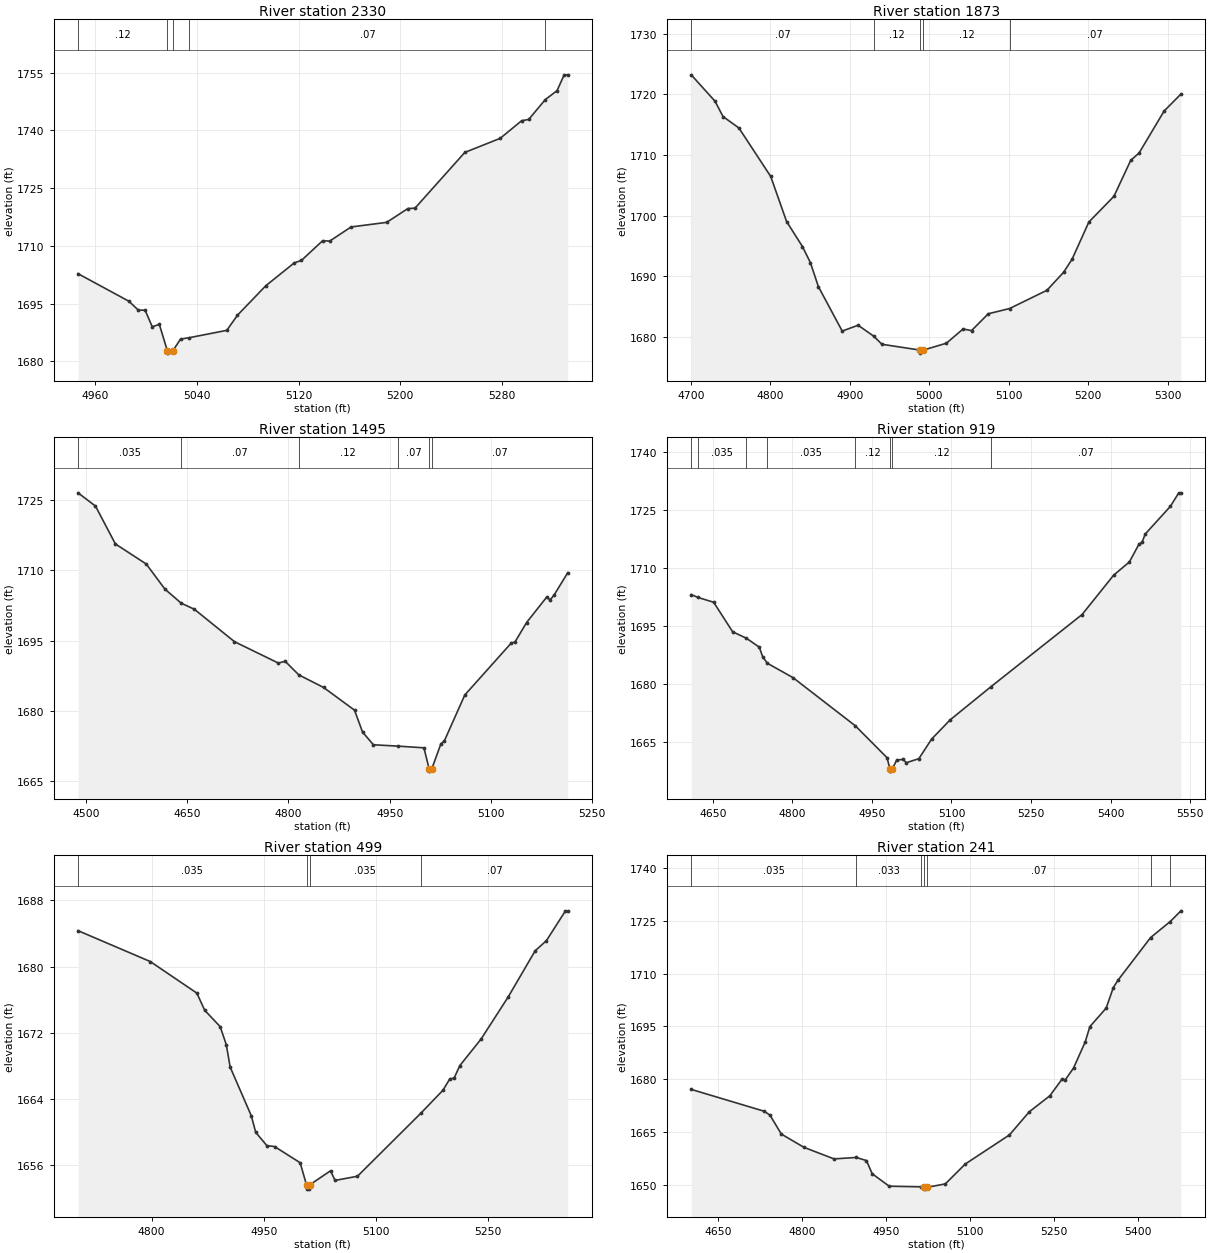
Type RM Length L Ch R = 1,2330,457,457,457
BEGIN DESCRIPTION:
Stream0069_DS 5.0
END DESCRIPTION:
XS GIS Cut Line= 3
      2040625.00     13946675.00      2040575.00     13946675.00
      2040275.01     13946525.00
#Sta/Elev= 30
  4946.4 1702.75  4986.4 1695.60  4993.9 1693.27  4999.2 1693.27  5004.8 1688.97
  5010.4 1689.57  5016.8 1682.61  5017.0 1682.11  5020.8 1682.61  5027.1 1685.76
  5034.1 1686.13  5063.5 1688.03  5071.9 1691.97  5094.2 1699.62  5116.6 1705.56
  5122.2 1706.19  5138.9 1711.31  5144.5 1711.22  5161.3 1714.89  5189.3 1716.08
  5206.0 1719.67  5211.6 1719.77  5250.8 1734.25  5278.7 1737.92  5295.5 1742.48
  5301.1 1742.82  5314.1 1747.96  5323.4 1750.30  5329.0 1754.41  5331.8 1754.41
#Mann=5,-1,0
  4946.4    0.12       0  5016.8    0.05       0  5020.8    0.12       0
  5034.1    0.07       0  5314.1    0.12       0
Bank Sta=5016.8,5020.8
Exp/Cntr=0.3,0.1

Type RM Length L Ch R = 1,1873,378,378,378
BEGIN DESCRIPTION:
Stream0069_DS 4.0
END DESCRIPTION:
XS GIS Cut Line= 3
      2041024.98     13946275.00      2040725.00     13946275.00
      2040425.01     13946175.00
#Sta/Elev= 30
  4700.5 1723.24  4730.5 1718.87  4740.5 1716.35  4760.5 1714.46  4800.5 1706.46
  4820.5 1699.01  4840.5 1694.87  4850.5 1692.21  4860.5 1688.26  4890.5 1680.92
  4910.5 1681.89  4929.9 1680.10  4940.5 1678.74  4988.5 1677.78  4988.7 1677.28
  4992.5 1677.78  5021.6 1678.92  5042.6 1681.27  5053.2 1681.00  5074.3 1683.78
  5101.2 1684.65  5148.1 1687.66  5169.1 1690.64  5179.7 1692.78  5200.8 1698.92
  5232.4 1703.18  5253.5 1709.11  5264.0 1710.32  5295.6 1717.27  5316.7 1720.06
#Mann=5,-1,0
  4700.5    0.07       0  4929.9    0.12       0  4988.5    0.05       0
  4992.5    0.12       0  5101.2    0.07       0
Bank Sta=4988.5,4992.5
Exp/Cntr=0.3,0.1

Type RM Length L Ch R = 1,1495,576,576,576
BEGIN DESCRIPTION:
Stream0069_DS 3.0
END DESCRIPTION:
XS GIS Cut Line= 3
      2041133.43     13946162.10      2040688.95     13945915.56
      2040475.04     13945875.01
#Sta/Elev= 30
  4488.0 1726.61  4513.9 1723.77  4543.4 1715.67  4589.1 1711.38  4616.9 1705.99
  4641.1 1702.98  4660.4 1701.70  4719.9 1694.76  4785.1 1690.17  4795.0 1690.57
  4815.3 1687.65  4852.1 1684.95  4897.9 1680.10  4909.8 1675.42  4925.9 1672.69
  4962.3 1672.40  5000.8 1672.04  5008.5 1667.55  5008.7 1667.05  5012.5 1667.55
  5025.9 1672.86  5031.0 1673.49  5061.4 1683.34  5130.5 1694.50  5135.6 1694.63
  5153.0 1698.85  5182.8 1704.29  5187.9 1703.69  5193.7 1704.71  5214.0 1709.51
#Mann=6,-1,0
  4488.0   0.035       0  4641.1    0.07       0  4815.3    0.12       0
  4962.3    0.07       0  5008.5    0.05       0  5012.5    0.07       0
Bank Sta=5008.5,5012.5
Exp/Cntr=0.3,0.1

Type RM Length L Ch R = 1,919,420,420,420
BEGIN DESCRIPTION:
Stream0069_DS 2.0
END DESCRIPTION:
XS GIS Cut Line= 3
      2041274.99     13945824.99      2041025.00     13945525.00
      2040532.68     13945321.80
#Sta/Elev= 30
  4609.5 1703.19  4622.1 1702.45  4651.8 1701.20  4687.6 1693.54  4713.1 1691.91
  4737.7 1689.58  4744.2 1687.08  4753.0 1685.40  4801.5 1681.66  4919.0 1669.17
  4978.5 1660.94  4984.3 1657.95  4984.6 1657.45  4988.3 1657.95  4996.7 1660.31
  5009.3 1660.51  5014.7 1659.62  5038.6 1660.68  5062.5 1665.73  5097.4 1670.71
  5174.2 1679.29  5346.2 1698.01  5406.0 1708.25  5435.3 1711.62  5453.8 1716.31
  5459.2 1716.69  5465.2 1718.86  5512.5 1726.01  5528.6 1729.55  5532.6 1729.55
#Mann=8,-1,0
  4609.5    0.07       0  4622.1   0.035       0  4713.1    0.07       0
  4753.0   0.035       0  4919.0    0.12       0  4984.3    0.05       0
  4988.3    0.12       0  5174.2    0.07       0
Bank Sta=4984.3,4988.3
Exp/Cntr=0.3,0.1

Type RM Length L Ch R = 1,499,258,258,258
BEGIN DESCRIPTION:
Stream0069_DS 1.0
END DESCRIPTION:
XS GIS Cut Line= 3
      2041404.22     13945557.91      2041325.00     13945275.00
      2041025.04     13945075.03
#Sta/Elev= 30
  4701.8 1684.35  4798.3 1680.62  4860.6 1676.80  4871.0 1674.73  4891.7 1672.75
  4899.9 1670.57  4905.1 1667.85  4933.3 1661.97  4939.2 1659.97  4954.1 1658.36
  4964.4 1658.25  4998.6 1656.29  5007.1 1653.60  5007.4 1653.10  5010.9 1653.10
  5011.1 1653.60  5039.2 1655.32  5045.2 1654.15  5075.2 1654.66  5160.2 1662.31
  5189.4 1665.06  5198.4 1666.41  5204.4 1666.54  5211.9 1668.03  5240.5 1671.27
  5276.5 1676.33  5312.6 1681.92  5327.6 1683.14  5353.1 1686.75  5356.1 1686.75
#Mann=4,-1,0
  4701.8   0.035       0  5007.1   0.035       0  5011.1   0.035       0
  5160.2    0.07       0
Bank Sta=5007.1,5011.1
Exp/Cntr=0.3,0.1

Type RM Length L Ch R = 1,241,0,0,0
BEGIN DESCRIPTION:
Stream0069_DS 0.0
END DESCRIPTION:
XS GIS Cut Line= 3
      2041468.75     13945433.84      2041407.78     13945041.24
      2041029.01     13944752.96
#Sta/Elev= 30
  4602.7 1677.12  4733.1 1670.91  4743.2 1669.79  4763.4 1664.44  4803.9 1660.66
  4857.4 1657.39  4896.8 1657.80  4915.2 1656.92  4925.4 1653.18  4955.7 1649.64
  5012.1 1649.46  5018.5 1649.31  5018.7 1648.81  5022.5 1649.31  5055.8 1650.29
  5091.5 1655.95  5170.2 1664.20  5205.5 1670.76  5242.3 1675.32  5263.7 1679.97
  5270.0 1679.89  5284.5 1683.19  5305.3 1690.60  5313.6 1694.94  5342.7 1700.21
  5355.4 1706.02  5363.5 1708.07  5421.9 1720.23  5456.9 1724.78  5476.0 1727.82
#Mann=7,-1,0
  4602.7   0.035       0  4896.8   0.033       0  5012.1    0.07       0
  5018.5   0.033       0  5022.5    0.07       0  5421.9   0.035       0
  5456.9    0.07       0
Bank Sta=5018.5,5022.5
Exp/Cntr=0.3,0.1

Chan Stop Cuts=-1