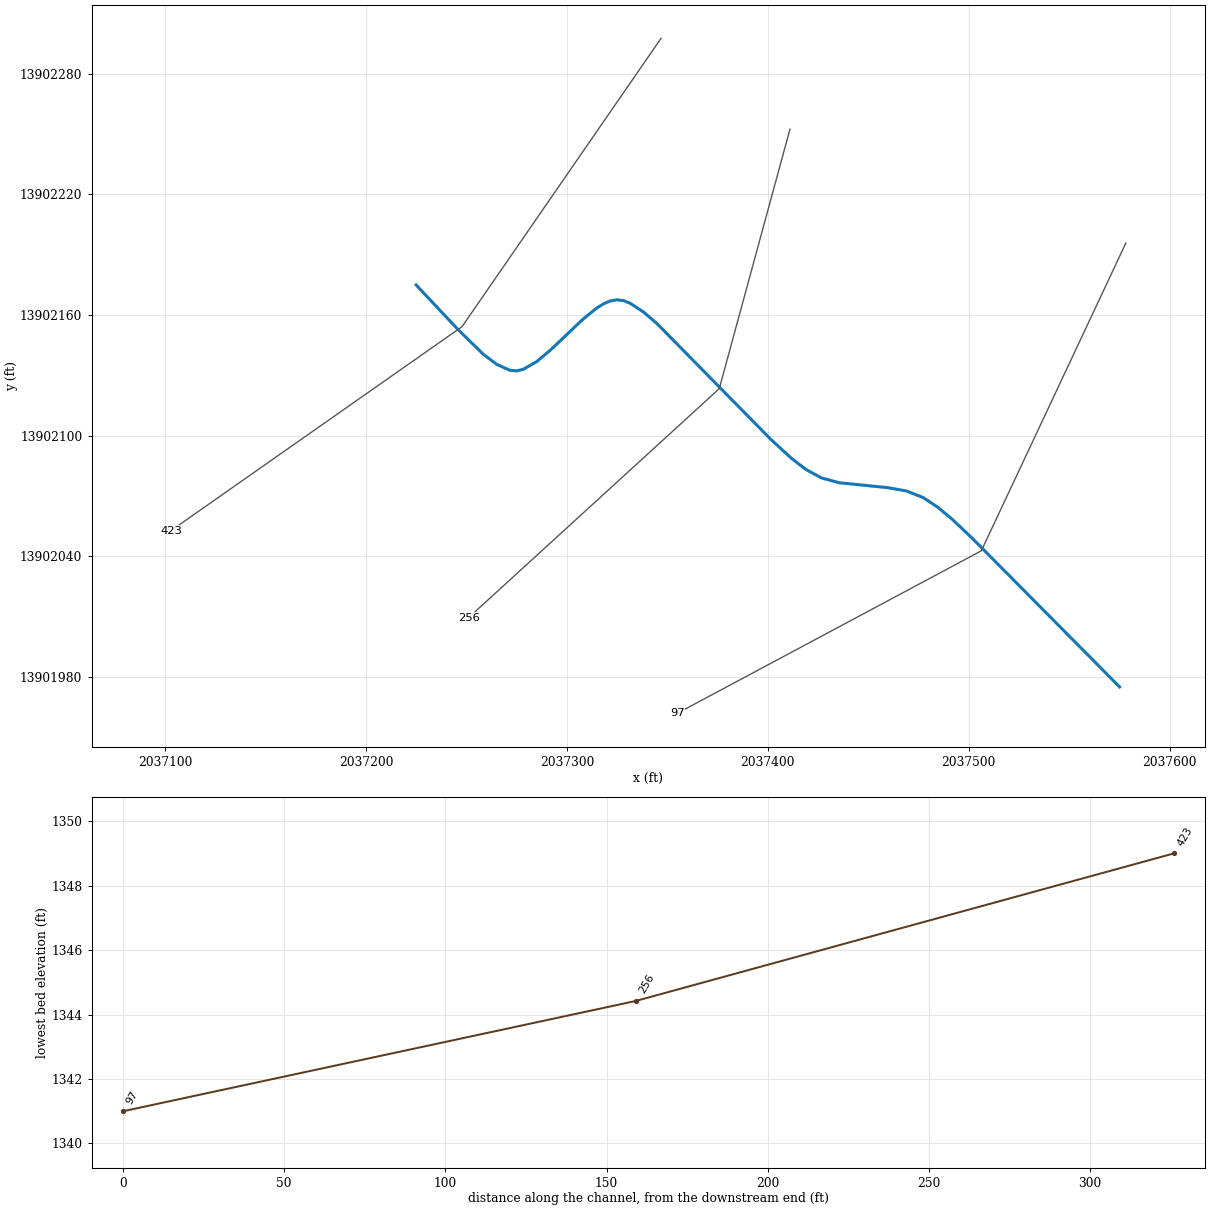
--- Stream0070_DS.prj (project) ---

Proj Title=Stream0070_DS Base Level Engineering
Current Plan=p01
Default Exp/Contr=0.3,0.1
English Units
Geom File=g01
Flow File=f01
Plan File=p01
BEGIN DESCRIPTION:
Stream0070_DS
END DESCRIPTION:

--- Stream0070_DS.p01 (plan) ---

Plan Title=Multiple Run
Short Identifier=Multiple
Geom File=g01
Flow File=f01
Subcritical Flow
K Sum by GR= 0
Std Step Tol= 0.01
Critical Tol= 0.01
Num of Std Step Trials= 20
Max Error Tol= 0.3
Flow Tol Ratio= 0.001
Split Flow NTrial= 30
Split Flow Tol= 0.02
Split Flow Ratio= 0.02
Log Output Level= 0
Friction Slope Method= 1
Unsteady Friction Slope Method= 2
Unsteady Bridges Friction Slope Method= 1
Parabolic Critical Depth
Global Vel Dist=  1 , 1 , 1
Global Log Level= 0
CheckData=True
Encroach Param= -1, 0, 0, 0
BEGIN DESCRIPTION:
Multiple Run
END DESCRIPTION:

--- Stream0070_DS.f01 (steady flow) ---

Flow Title=Multiple
Number of Profiles=7
Profile Names=10-year,25-year,50-year,1pct_min,100-year,1pct_plu,500-year
River Rch & RM= Stream0070_DS,Reach-1,423
     349     547     723     465     927    1850    1504
Boundary for River Rch & Prof#=Stream0070_DS,Reach-1,1
Up Type=0
Dn Type=3
Dn Slope=0.005
Boundary for River Rch & Prof#=Stream0070_DS,Reach-1,2
Up Type=0
Dn Type=3
Dn Slope=0.005
Boundary for River Rch & Prof#=Stream0070_DS,Reach-1,3
Up Type=0
Dn Type=3
Dn Slope=0.005
Boundary for River Rch & Prof#=Stream0070_DS,Reach-1,4
Up Type=0
Dn Type=3
Dn Slope=0.005
Boundary for River Rch & Prof#=Stream0070_DS,Reach-1,5
Up Type=0
Dn Type=3
Dn Slope=0.005
Boundary for River Rch & Prof#=Stream0070_DS,Reach-1,6
Up Type=0
Dn Type=3
Dn Slope=0.005
Boundary for River Rch & Prof#=Stream0070_DS,Reach-1,7
Up Type=0
Dn Type=3
Dn Slope=0.005

--- Stream0070_DS.g01 (geometry) ---

Geom Title=Existing Conditions

River Reach=Stream0070_DS,Reach-1
Reach XY= 30
      2037225.00     13902175.00      2037245.64     13902153.00
      2037258.22     13902140.69      2037265.00     13902135.53
      2037271.67     13902132.52      2037275.00     13902132.24
      2037278.33     13902133.01      2037285.00     13902136.85
      2037291.67     13902142.44      2037308.33     13902158.23
      2037315.00     13902163.58      2037318.33     13902165.64
      2037321.66     13902167.05      2037325.00     13902167.61
      2037328.33     13902167.13      2037331.66     13902165.79
      2037338.32     13902161.38      2037344.98     13902155.61
      2037401.53     13902098.12      2037411.79     13902088.68
      2037418.95     13902083.19      2037426.64     13902078.99
      2037435.63     13902076.55      2037459.64     13902074.13
      2037468.96     13902072.48      2037477.31     13902069.19
      2037484.70     13902064.28      2037491.71     13902058.43
      2037501.86     13902048.80      2037575.00     13901975.00

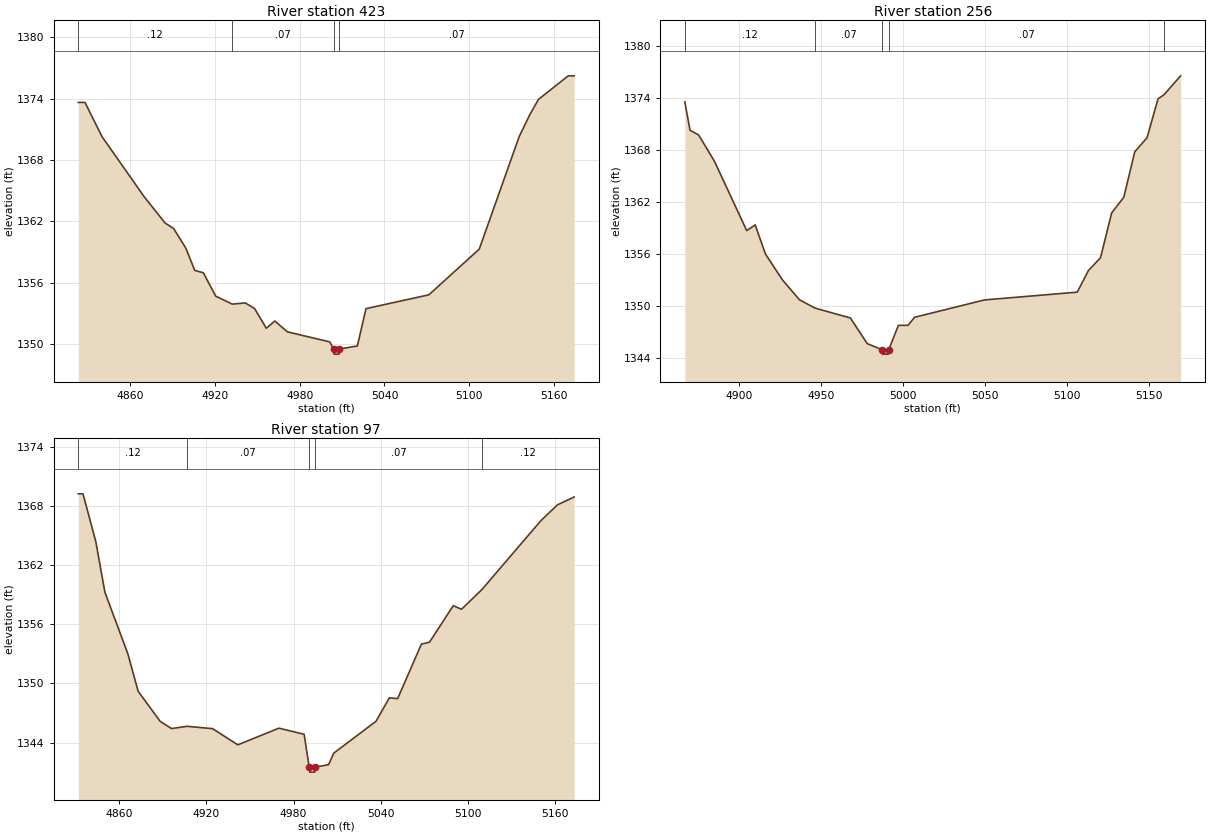
Type RM Length L Ch R = 1,423,167,167,167
BEGIN DESCRIPTION:
Stream0070_DS 3.0
END DESCRIPTION:
XS GIS Cut Line= 3
      2037346.87     13902297.70      2037247.84     13902154.22
      2037103.08     13902052.78
#Sta/Elev= 30
  4823.2 1373.62  4827.9 1373.62  4840.0 1370.27  4869.8 1364.40  4884.6 1361.83
  4890.7 1361.28  4899.4 1359.35  4905.6 1357.19  4911.7 1356.96  4920.5 1354.67
  4932.2 1353.89  4941.4 1354.01  4948.0 1353.46  4956.3 1351.53  4962.4 1352.24
  4971.2 1351.18  5001.2 1350.20  5004.0 1349.50  5004.3 1349.00  5007.8 1349.00
  5008.0 1349.50  5020.8 1349.80  5026.9 1353.45  5071.4 1354.80  5107.1 1359.27
  5135.3 1370.25  5142.9 1372.42  5149.0 1373.91  5170.1 1376.22  5174.3 1376.22
#Mann=4,-1,0
  4823.2    0.12       0  4932.2    0.07       0  5004.0    0.05       0
  5008.0    0.07       0
Bank Sta=5004,5008
Exp/Cntr=0.3,0.1

Type RM Length L Ch R = 1,256,159,159,159
BEGIN DESCRIPTION:
Stream0070_DS 2.0
END DESCRIPTION:
XS GIS Cut Line= 3
      2037411.02     13902252.51      2037375.84     13902123.38
      2037251.16     13902009.49
#Sta/Elev= 30
  4866.9 1373.52  4870.1 1370.24  4875.3 1369.71  4885.0 1366.67  4904.7 1358.67
  4909.9 1359.32  4916.1 1355.98  4926.5 1352.99  4936.9 1350.69  4946.4 1349.73
  4968.0 1348.59  4978.3 1345.63  4987.4 1344.92  4987.6 1344.42  4991.1 1344.42
  4991.4 1344.92  4997.3 1347.74  5003.2 1347.74  5007.2 1348.67  5049.8 1350.67
  5106.5 1351.57  5113.3 1354.06  5120.7 1355.54  5127.5 1360.71  5134.9 1362.51
  5141.6 1367.76  5149.1 1369.38  5155.8 1373.86  5159.5 1374.35  5169.6 1376.52
#Mann=5,-1,0
  4866.9    0.12       0  4946.4    0.07       0  4987.4    0.05       0
  4991.4    0.07       0  5159.5    0.12       0
Bank Sta=4987.4,4991.4
Exp/Cntr=0.3,0.1

Type RM Length L Ch R = 1,97,0,0,0
BEGIN DESCRIPTION:
Stream0070_DS 1.0
END DESCRIPTION:
XS GIS Cut Line= 3
      2037578.15     13902195.84      2037506.24     13902042.70
      2037354.88     13901961.81
#Sta/Elev= 30
  4832.1 1369.24  4835.3 1369.24  4844.1 1364.40  4850.4 1359.24  4866.2 1352.98
  4873.2 1349.21  4888.3 1346.16  4896.1 1345.42  4906.9 1345.65  4924.4 1345.41
  4941.7 1343.77  4970.0 1345.46  4987.3 1344.84  4990.8 1341.50  4991.1 1341.00
  4994.6 1341.00  4994.8 1341.50  5004.1 1341.76  5007.7 1342.93  5036.7 1346.16
  5045.9 1348.54  5051.6 1348.46  5067.9 1353.99  5073.5 1354.19  5089.8 1357.89
  5095.5 1357.53  5109.4 1359.51  5150.0 1366.51  5161.4 1368.12  5172.9 1368.92
#Mann=5,-1,0
  4832.1    0.12       0  4906.9    0.07       0  4990.8    0.05       0
  4994.8    0.07       0  5109.4    0.12       0
Bank Sta=4990.8,4994.8
Exp/Cntr=0.3,0.1

Chan Stop Cuts=-1