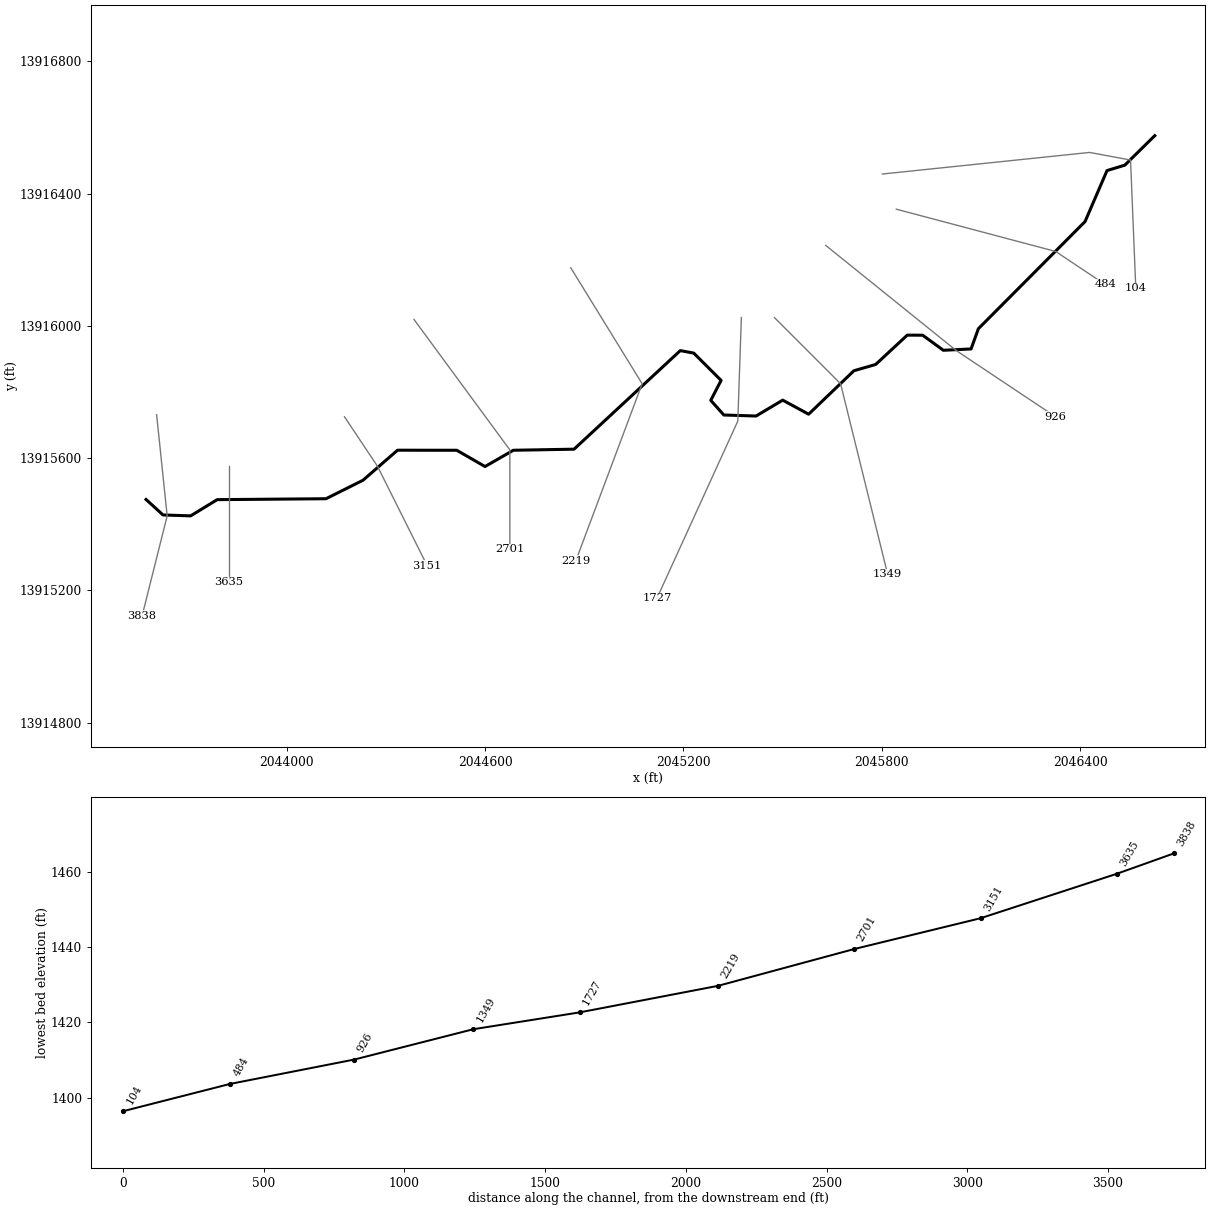
--- Stream0074_DS.prj (project) ---

Proj Title=Stream0074_DS Base Level Engineering
Current Plan=p01
Default Exp/Contr=0.3,0.1
English Units
Geom File=g01
Flow File=f01
Plan File=p01
BEGIN DESCRIPTION:
Stream0074_DS
END DESCRIPTION:

--- Stream0074_DS.p01 (plan) ---

Plan Title=Multiple Run
Short Identifier=Multiple
Geom File=g01
Flow File=f01
Subcritical Flow
K Sum by GR= 0
Std Step Tol= 0.01
Critical Tol= 0.01
Num of Std Step Trials= 20
Max Error Tol= 0.3
Flow Tol Ratio= 0.001
Split Flow NTrial= 30
Split Flow Tol= 0.02
Split Flow Ratio= 0.02
Log Output Level= 0
Friction Slope Method= 1
Unsteady Friction Slope Method= 2
Unsteady Bridges Friction Slope Method= 1
Parabolic Critical Depth
Global Vel Dist=  1 , 1 , 1
Global Log Level= 0
CheckData=True
Encroach Param= -1, 0, 0, 0
BEGIN DESCRIPTION:
Multiple Run
END DESCRIPTION:

--- Stream0074_DS.f01 (steady flow) ---

Flow Title=Multiple
Number of Profiles=7
Profile Names=10-year,25-year,50-year,1pct_min,100-year,1pct_plu,500-year
River Rch & RM= Stream0074_DS,Reach-1,3838
     452     737    1001     662    1322    2637    2278
River Rch & RM= Stream0074_DS,Reach-1,3635
     786    1324    1836    1238    2471    4930    4428
Boundary for River Rch & Prof#=Stream0074_DS,Reach-1,1
Up Type=0
Dn Type=3
Dn Slope=0.005
Boundary for River Rch & Prof#=Stream0074_DS,Reach-1,2
Up Type=0
Dn Type=3
Dn Slope=0.005
Boundary for River Rch & Prof#=Stream0074_DS,Reach-1,3
Up Type=0
Dn Type=3
Dn Slope=0.005
Boundary for River Rch & Prof#=Stream0074_DS,Reach-1,4
Up Type=0
Dn Type=3
Dn Slope=0.005
Boundary for River Rch & Prof#=Stream0074_DS,Reach-1,5
Up Type=0
Dn Type=3
Dn Slope=0.005
Boundary for River Rch & Prof#=Stream0074_DS,Reach-1,6
Up Type=0
Dn Type=3
Dn Slope=0.005
Boundary for River Rch & Prof#=Stream0074_DS,Reach-1,7
Up Type=0
Dn Type=3
Dn Slope=0.005

--- Stream0074_DS.g01 (geometry) ---

Geom Title=Existing Conditions

River Reach=Stream0074_DS,Reach-1
Reach XY= 30
      2043575.00     13915475.00      2043626.40     13915428.19
      2043709.75     13915425.37      2043790.22     13915474.48
      2044119.07     13915477.24      2044231.05     13915533.16
      2044335.44     13915623.95      2044514.50     13915623.76
      2044600.00     13915574.60      2044685.50     13915623.76
      2044869.15     13915627.06      2045190.37     13915925.11
      2045231.08     13915917.54      2045313.76     13915835.02
      2045282.46     13915774.75      2045322.03     13915730.40
      2045419.43     13915727.31      2045500.04     13915775.31
      2045578.41     13915732.82      2045715.32     13915864.22
      2045781.04     13915883.18      2045876.64     13915971.86
      2045923.26     13915971.65      2045985.65     13915926.08
      2046069.53     13915930.11      2046091.74     13915991.45
      2046414.23     13916315.32      2046480.58     13916469.40
      2046534.42     13916485.83      2046625.00     13916575.00

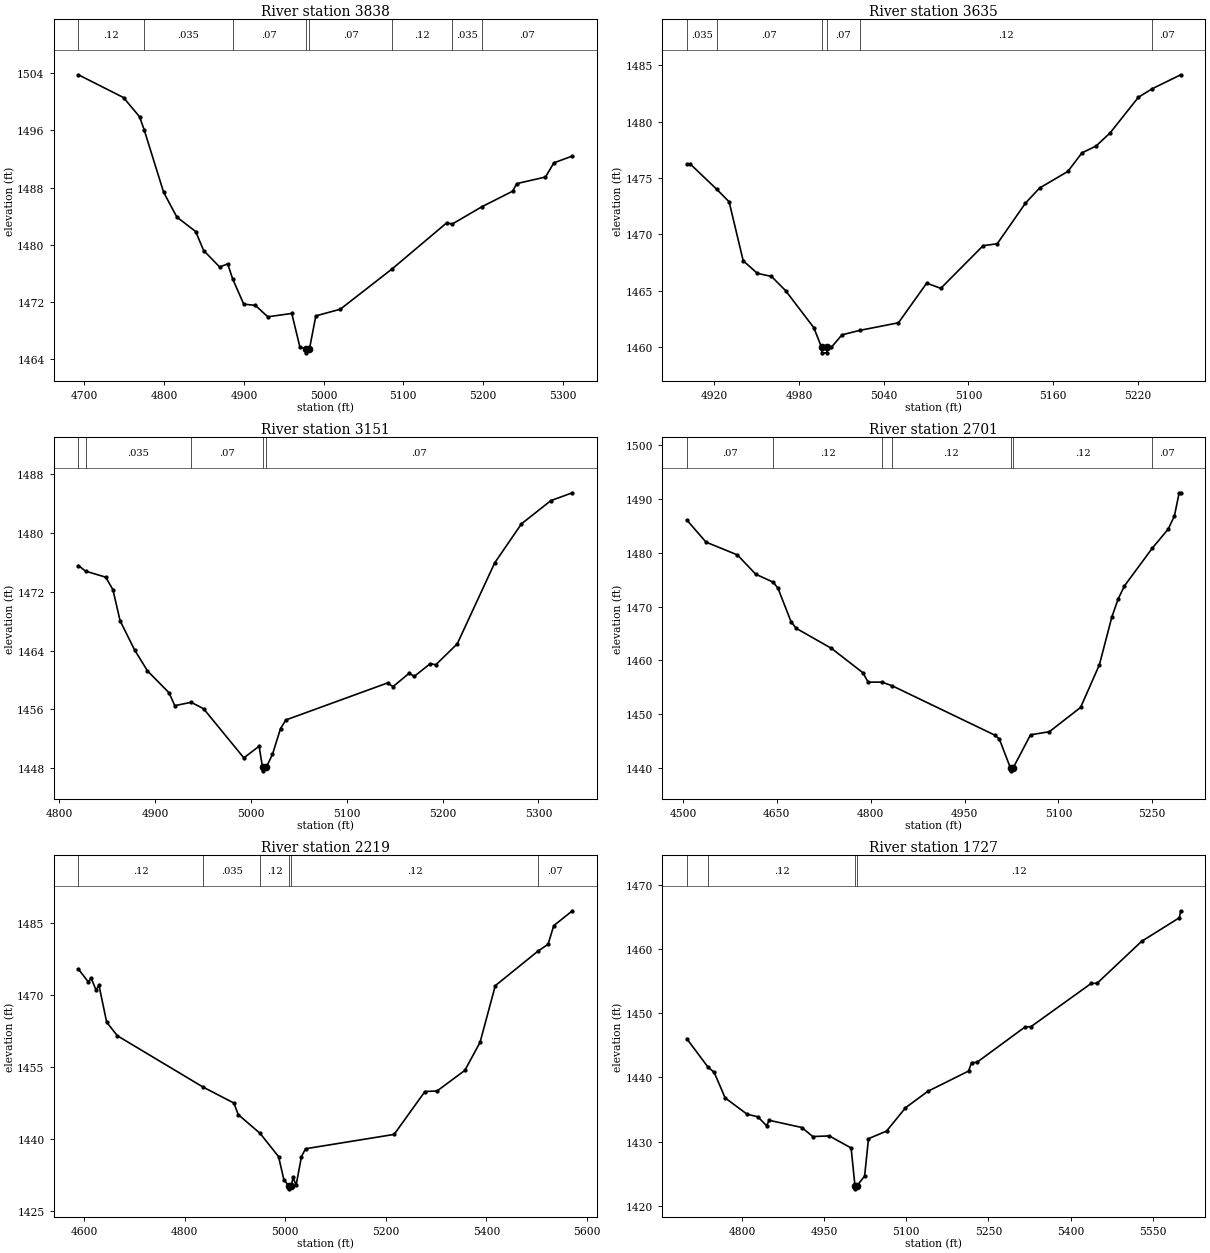
Type RM Length L Ch R = 1,3838,203,203,203
BEGIN DESCRIPTION:
Stream0074_DS 9.0
END DESCRIPTION:
XS GIS Cut Line= 3
      2043607.03     13915731.28      2043638.91     13915425.33
      2043562.97     13915122.51
#Sta/Elev= 30
  4692.4 1503.78  4749.0 1500.59  4769.1 1497.91  4774.9 1496.08  4799.3 1487.35
  4815.9 1483.88  4839.5 1481.86  4849.5 1479.20  4869.6 1476.90  4879.7 1477.33
  4885.9 1475.24  4899.8 1471.70  4914.4 1471.53  4930.0 1469.93  4960.1 1470.40
  4970.2 1465.74  4978.2 1465.39  4978.5 1464.89  4982.2 1465.39  4990.3 1470.06
  5021.0 1470.99  5086.1 1476.64  5154.9 1483.11  5161.2 1482.89  5198.9 1485.34
  5237.3 1487.50  5242.4 1488.56  5278.4 1489.48  5289.0 1491.46  5312.2 1492.42
#Mann=8,-1,0
  4692.4    0.12       0  4774.9   0.035       0  4885.9    0.07       0
  4978.2    0.05       0  4982.2    0.07       0  5086.1    0.12       0
  5161.2   0.035       0  5198.9    0.07       0
Bank Sta=4978.2,4982.2
Exp/Cntr=0.3,0.1

Type RM Length L Ch R = 1,3635,484,484,484
BEGIN DESCRIPTION:
Stream0074_DS 8.0
END DESCRIPTION:
XS GIS Cut Line= 3
      2043825.00     13915574.99      2043825.00     13915475.00
      2043825.00     13915224.99
#Sta/Elev= 30
  4900.4 1476.24  4902.9 1476.24  4921.8 1473.98  4930.4 1472.89  4940.4 1467.65
  4950.4 1466.53  4960.4 1466.26  4970.4 1465.00  4990.4 1461.71  4995.9 1459.97
  4996.1 1459.47  4999.6 1459.47  4999.9 1459.97  5002.9 1459.97  5010.4 1461.07
  5022.8 1461.46  5050.4 1462.14  5070.4 1465.66  5080.4 1465.20  5110.4 1468.99
  5120.4 1469.16  5140.4 1472.77  5150.4 1474.11  5170.4 1475.58  5180.4 1477.23
  5190.4 1477.84  5200.4 1479.01  5220.4 1482.17  5230.2 1482.93  5250.4 1484.17
#Mann=6,-1,0
  4900.4   0.035       0  4921.8    0.07       0  4995.9    0.05       0
  4999.9    0.07       0  5022.8    0.12       0  5230.2    0.07       0
Bank Sta=4995.9,4999.9
Exp/Cntr=0.3,0.1

Type RM Length L Ch R = 1,3151,450,450,450
BEGIN DESCRIPTION:
Stream0074_DS 7.0
END DESCRIPTION:
XS GIS Cut Line= 3
      2044175.02     13915724.97      2044275.00     13915575.00
      2044425.02     13915274.96
#Sta/Elev= 30
  4819.8 1475.54  4827.2 1474.78  4848.3 1473.96  4855.8 1472.26  4863.3 1468.04
  4878.4 1464.09  4891.9 1461.23  4914.4 1458.26  4920.4 1456.51  4937.5 1456.97
  4950.5 1456.09  4992.5 1449.42  5008.4 1451.00  5012.0 1448.16  5012.3 1447.66
  5016.0 1448.16  5022.4 1449.90  5030.8 1453.40  5036.4 1454.57  5142.6 1459.60
  5148.2 1459.09  5165.0 1460.90  5170.5 1460.50  5187.3 1462.23  5192.9 1462.06
  5215.3 1464.91  5254.4 1475.90  5282.3 1481.20  5313.1 1484.36  5335.5 1485.42
#Mann=5,-1,0
  4819.8    0.07       0  4827.2   0.035       0  4937.5    0.07       0
  5012.0    0.05       0  5016.0    0.07       0
Bank Sta=5012,5016
Exp/Cntr=0.3,0.1

Type RM Length L Ch R = 1,2701,482,482,482
BEGIN DESCRIPTION:
Stream0074_DS 6.0
END DESCRIPTION:
XS GIS Cut Line= 3
      2044385.16     13916019.34      2044675.00     13915625.00
      2044675.00     13915325.00
#Sta/Elev= 30
  4506.0 1486.11  4536.7 1481.98  4586.9 1479.60  4616.2 1476.01  4644.1 1474.53
  4651.7 1473.42  4672.7 1467.17  4681.0 1465.94  4737.3 1462.22  4787.5 1457.69
  4795.9 1455.94  4817.9 1455.95  4834.2 1455.27  4997.9 1446.11  5005.4 1445.40
  5023.4 1439.95  5023.7 1439.45  5027.4 1439.95  5055.4 1446.15  5085.4 1446.72
  5135.4 1451.24  5165.4 1459.16  5185.4 1468.08  5195.4 1471.40  5205.4 1473.82
  5250.1 1480.87  5275.4 1484.39  5285.4 1486.87  5292.9 1491.15  5295.4 1491.15
#Mann=7,-1,0
  4506.0    0.07       0  4644.1    0.12       0  4817.9   0.035       0
  4834.2    0.12       0  5023.4    0.05       0  5027.4    0.12       0
  5250.1    0.07       0
Bank Sta=5023.4,5027.4
Exp/Cntr=0.3,0.1

Type RM Length L Ch R = 1,2219,492,492,492
BEGIN DESCRIPTION:
Stream0074_DS 5.0
END DESCRIPTION:
XS GIS Cut Line= 3
      2044859.10     13916175.61      2045075.00     13915825.00
      2044874.72     13915290.22
#Sta/Elev= 30
  4588.3 1475.40  4607.9 1472.75  4613.7 1473.53  4623.3 1471.05  4629.1 1472.07
  4644.5 1464.37  4665.8 1461.54  4836.4 1450.86  4897.7 1447.54  4906.1 1445.16
  4949.8 1441.23  4986.5 1436.40  4997.1 1431.58  5007.8 1430.20  5008.1 1429.70
  5011.8 1430.20  5015.2 1432.10  5021.4 1430.47  5032.1 1436.41  5040.1 1438.04
  5216.4 1441.02  5277.7 1449.94  5301.9 1450.06  5357.1 1454.33  5387.4 1460.18
  5417.7 1471.96  5503.5 1479.22  5522.7 1480.56  5534.0 1484.44  5571.1 1487.54
#Mann=6,-1,0
  4588.3    0.12       0  4836.4   0.035       0  4949.8    0.12       0
  5007.8    0.05       0  5011.8    0.12       0  5503.5    0.07       0
Bank Sta=5007.8,5011.8
Exp/Cntr=0.3,0.1

Type RM Length L Ch R = 1,1727,378,378,378
BEGIN DESCRIPTION:
Stream0074_DS 4.0
END DESCRIPTION:
XS GIS Cut Line= 3
      2045375.00     13916025.02      2045364.30     13915712.08
      2045119.75     13915176.16
#Sta/Elev= 30
  4699.0 1446.05  4737.8 1441.61  4749.1 1440.80  4769.1 1436.81  4809.1 1434.28
  4829.1 1433.86  4844.7 1432.47  4849.7 1433.32  4909.1 1432.20  4929.2 1430.79
  4959.2 1430.89  4999.2 1429.01  5006.2 1423.14  5006.4 1422.64  5010.2 1423.14
  5023.9 1424.64  5030.9 1430.46  5063.9 1431.64  5098.5 1435.27  5139.1 1437.83
  5213.7 1441.00  5219.2 1442.32  5228.8 1442.35  5316.9 1447.87  5327.7 1447.92
  5437.6 1454.65  5448.6 1454.69  5529.7 1461.21  5598.8 1464.90  5601.2 1465.98
#Mann=4,-1,0
  4699.0   0.035       0  4737.8    0.12       0  5006.2    0.05       0
  5010.2    0.12       0
Bank Sta=5006.2,5010.2
Exp/Cntr=0.3,0.1

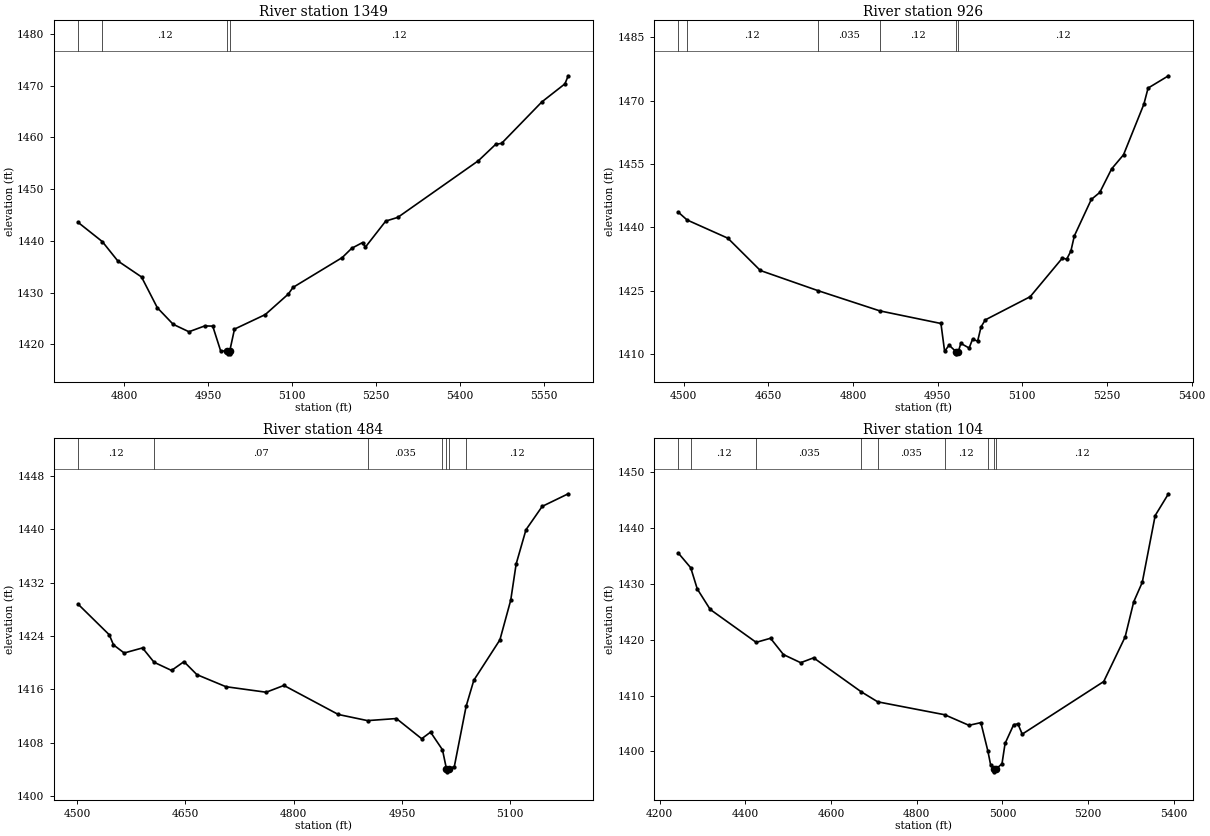
Type RM Length L Ch R = 1,1349,423,423,423
BEGIN DESCRIPTION:
Stream0074_DS 3.0
END DESCRIPTION:
XS GIS Cut Line= 3
      2045475.03     13916024.97      2045675.00     13915825.00
      2045817.23     13915249.31
#Sta/Elev= 30
  4717.4 1443.56  4760.5 1439.86  4788.1 1436.13  4830.5 1433.03  4858.8 1427.07
  4887.1 1423.87  4915.3 1422.43  4943.6 1423.56  4957.8 1423.52  4971.9 1418.75
  4984.1 1418.66  4984.3 1418.16  4987.8 1418.16  4988.1 1418.66  4996.7 1422.94
  5051.7 1425.75  5092.9 1429.72  5101.2 1431.00  5189.3 1436.78  5206.2 1438.57
  5225.6 1439.68  5230.7 1438.80  5267.0 1443.83  5288.6 1444.55  5432.8 1455.52
  5463.7 1458.69  5474.0 1458.85  5546.1 1466.88  5587.3 1470.37  5593.2 1471.93
#Mann=4,-1,0
  4717.4   0.035       0  4760.5    0.12       0  4984.1    0.05       0
  4988.1    0.12       0
Bank Sta=4984.1,4988.1
Exp/Cntr=0.3,0.1

Type RM Length L Ch R = 1,926,442,442,442
BEGIN DESCRIPTION:
Stream0074_DS 2.0
END DESCRIPTION:
XS GIS Cut Line= 3
      2045629.95     13916243.31      2046025.00     13915925.00
      2046325.01     13915724.99
#Sta/Elev= 30
  4490.9 1443.58  4506.2 1441.77  4578.4 1437.46  4635.9 1429.82  4737.6 1425.07
  4847.4 1420.27  4955.8 1417.28  4962.3 1410.69  4970.2 1412.16  4982.6 1410.60
  4982.9 1410.10  4986.6 1410.60  4991.0 1412.58  5005.7 1411.47  5011.8 1413.55
  5020.8 1413.11  5026.8 1416.47  5034.3 1418.13  5113.9 1423.62  5171.0 1432.78
  5178.5 1432.48  5186.0 1434.43  5192.0 1437.98  5222.1 1446.63  5237.1 1448.28
  5258.1 1453.86  5279.2 1457.20  5315.2 1469.15  5322.7 1472.98  5358.8 1475.89
#Mann=6,-1,0
  4490.9    0.07       0  4506.2    0.12       0  4737.6   0.035       0
  4847.4    0.12       0  4982.6    0.05       0  4986.6    0.12       0
Bank Sta=4982.6,4986.6
Exp/Cntr=0.3,0.1

Type RM Length L Ch R = 1,484,380,380,380
BEGIN DESCRIPTION:
Stream0074_DS 1.0
END DESCRIPTION:
XS GIS Cut Line= 3
      2045843.48     13916352.70      2046325.00     13916225.00
      2046474.96     13916125.02
#Sta/Elev= 30
  4501.8 1428.76  4544.8 1424.18  4550.6 1422.67  4565.4 1421.45  4590.8 1422.21
  4606.8 1420.06  4631.0 1418.83  4648.2 1420.15  4666.1 1418.20  4706.3 1416.39
  4762.0 1415.56  4786.6 1416.58  4861.9 1412.22  4902.3 1411.30  4942.3 1411.61
  4977.3 1408.58  4989.6 1409.57  5006.1 1406.92  5011.5 1404.11  5011.7 1403.61
  5015.5 1404.11  5022.5 1404.40  5038.8 1413.43  5049.5 1417.36  5085.6 1423.42
  5100.6 1429.38  5108.1 1434.81  5121.7 1439.95  5144.2 1443.46  5180.2 1445.35
#Mann=7,-1,0
  4501.8    0.12       0  4606.8    0.07       0  4902.3   0.035       0
  5006.1    0.07       0  5011.5   0.035       0  5015.5    0.07       0
  5038.8    0.12       0
Bank Sta=5011.5,5015.5
Exp/Cntr=0.3,0.1

Type RM Length L Ch R = 1,104,0,0,0
BEGIN DESCRIPTION:
Stream0074_DS 0.0
END DESCRIPTION:
XS GIS Cut Line= 4
      2045801.34     13916459.02      2046427.86     13916524.28
      2046551.73     13916501.26      2046567.55     13916113.98
#Sta/Elev= 30
  4244.1 1435.45  4272.7 1432.86  4288.0 1429.06  4318.2 1425.40  4425.4 1419.52
  4458.9 1420.25  4489.1 1417.33  4529.3 1415.88  4559.5 1416.75  4670.3 1410.69
  4709.1 1408.88  4865.4 1406.57  4922.0 1404.68  4949.8 1405.16  4966.1 1400.10
  4972.8 1397.53  4981.0 1396.86  4981.2 1396.36  4985.0 1396.86  4999.1 1397.80
  5006.3 1401.44  5026.3 1404.79  5036.3 1404.94  5046.3 1403.10  5236.5 1412.51
  5286.5 1420.49  5306.5 1426.77  5326.5 1430.26  5356.6 1442.20  5387.6 1446.09
#Mann=9,-1,0
  4244.1    0.07       0  4272.7    0.12       0  4425.4   0.035       0
  4670.3    0.07       0  4709.1   0.035       0  4865.4    0.12       0
  4966.1   0.035       0  4981.0    0.05       0  4985.0    0.12       0
Bank Sta=4981,4985
Exp/Cntr=0.3,0.1

Chan Stop Cuts=-1