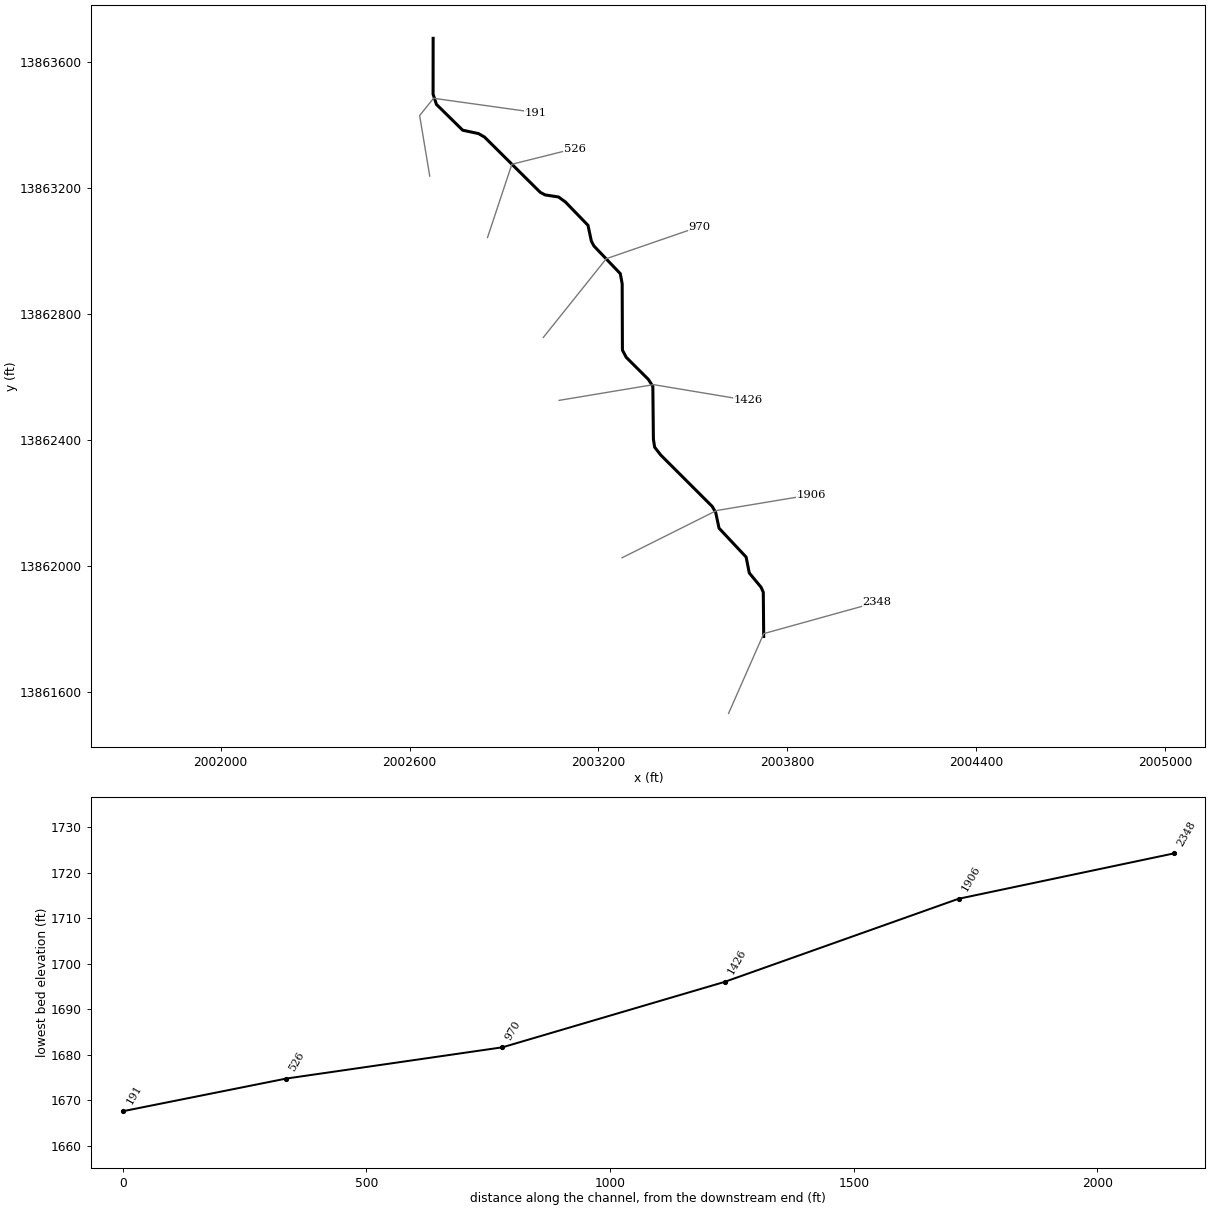
--- Stream0075_DS.prj (project) ---

Proj Title=Stream0075_DS Base Level Engineering
Current Plan=p01
Default Exp/Contr=0.3,0.1
English Units
Geom File=g01
Flow File=f01
Plan File=p01
BEGIN DESCRIPTION:
Stream0075_DS
END DESCRIPTION:

--- Stream0075_DS.p01 (plan) ---

Plan Title=Multiple Run
Short Identifier=Multiple
Geom File=g01
Flow File=f01
Subcritical Flow
K Sum by GR= 0
Std Step Tol= 0.01
Critical Tol= 0.01
Num of Std Step Trials= 20
Max Error Tol= 0.3
Flow Tol Ratio= 0.001
Split Flow NTrial= 30
Split Flow Tol= 0.02
Split Flow Ratio= 0.02
Log Output Level= 0
Friction Slope Method= 1
Unsteady Friction Slope Method= 2
Unsteady Bridges Friction Slope Method= 1
Parabolic Critical Depth
Global Vel Dist=  1 , 1 , 1
Global Log Level= 0
CheckData=True
Encroach Param= -1, 0, 0, 0
BEGIN DESCRIPTION:
Multiple Run
END DESCRIPTION:

--- Stream0075_DS.f01 (steady flow) ---

Flow Title=Multiple
Number of Profiles=7
Profile Names=10-year,25-year,50-year,1pct_min,100-year,1pct_plu,500-year
River Rch & RM= Stream0075_DS,Reach-1,2348
     644    1068    1464     976    1948    3887    3405
River Rch & RM= Stream0075_DS,Reach-1,1906
     763    1276    1760    1180    2355    4699    4163
Boundary for River Rch & Prof#=Stream0075_DS,Reach-1,1
Up Type=0
Dn Type=3
Dn Slope=0.005
Boundary for River Rch & Prof#=Stream0075_DS,Reach-1,2
Up Type=0
Dn Type=3
Dn Slope=0.005
Boundary for River Rch & Prof#=Stream0075_DS,Reach-1,3
Up Type=0
Dn Type=3
Dn Slope=0.005
Boundary for River Rch & Prof#=Stream0075_DS,Reach-1,4
Up Type=0
Dn Type=3
Dn Slope=0.005
Boundary for River Rch & Prof#=Stream0075_DS,Reach-1,5
Up Type=0
Dn Type=3
Dn Slope=0.005
Boundary for River Rch & Prof#=Stream0075_DS,Reach-1,6
Up Type=0
Dn Type=3
Dn Slope=0.005
Boundary for River Rch & Prof#=Stream0075_DS,Reach-1,7
Up Type=0
Dn Type=3
Dn Slope=0.005

--- Stream0075_DS.g01 (geometry) ---

Geom Title=Existing Conditions

River Reach=Stream0075_DS,Reach-1
Reach XY= 30
      2003725.00     13861775.00      2003723.69     13861915.37
      2003716.92     13861931.08      2003679.22     13861976.75
      2003669.16     13862027.29      2003583.18     13862118.96
      2003572.36     13862169.36      2003561.37     13862188.21
      2003397.86     13862351.47      2003378.54     13862376.46
      2003374.63     13862402.12      2003372.82     13862569.55
      2003358.53     13862591.75      2003288.40     13862661.69
      2003276.21     13862684.59      2003275.43     13862895.18
      2003269.53     13862927.45      2003185.80     13863015.33
      2003177.65     13863030.65      2003166.85     13863081.07
      2003095.13     13863155.23      2003073.36     13863171.03
      2003030.64     13863177.65      2003015.32     13863185.78
      2002838.21     13863361.37      2002818.95     13863372.46
      2002768.93     13863383.15      2002685.46     13863465.17
      2002674.79     13863497.64      2002675.00     13863675.00

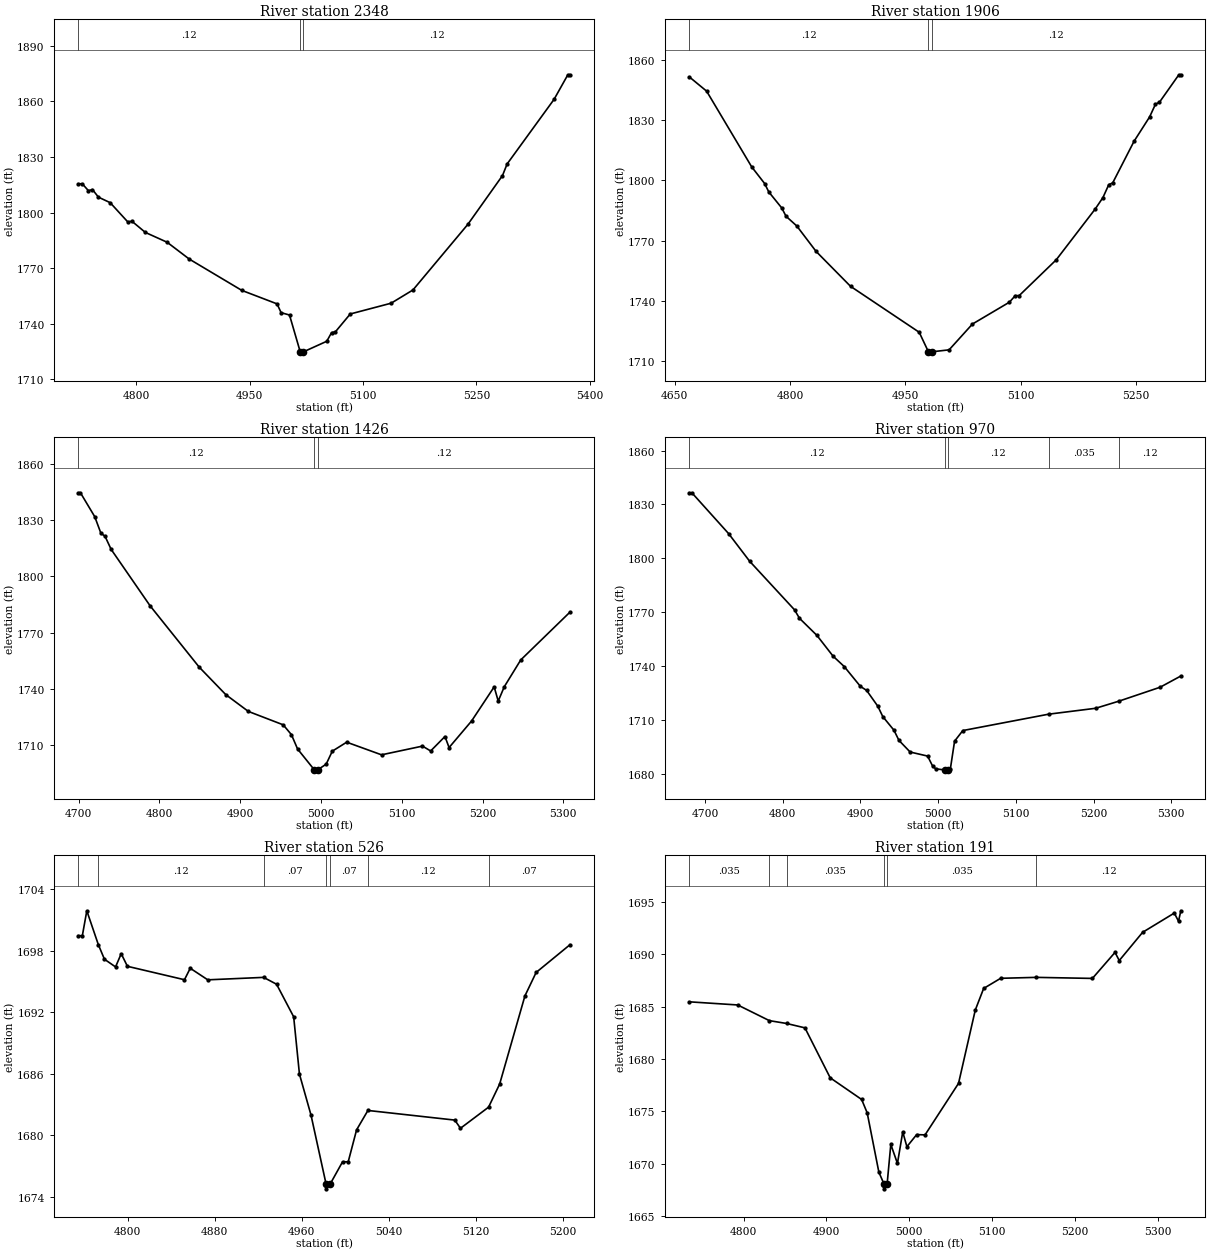
Type RM Length L Ch R = 1,2348,442,442,442
BEGIN DESCRIPTION:
Stream0075_DS 5.0
END DESCRIPTION:
XS GIS Cut Line= 3
      2003613.44     13861530.79      2003725.02     13861784.10
      2004085.10     13861884.08
#Sta/Elev= 30
  4723.2 1815.53  4728.3 1815.53  4736.4 1811.81  4741.8 1812.40  4749.7 1808.30
  4765.2 1805.33  4788.5 1794.95  4794.0 1795.30  4811.8 1789.25  4840.6 1783.95
  4869.9 1774.86  4939.4 1757.95  4986.1 1750.66  4991.5 1745.90  5002.6 1744.64
  5016.8 1724.71  5017.0 1724.21  5020.8 1724.71  5051.9 1730.46  5058.2 1735.08
  5063.4 1735.60  5083.0 1745.20  5137.1 1751.02  5166.0 1758.18  5238.7 1793.64
  5284.5 1819.96  5290.6 1826.22  5352.8 1861.16  5371.0 1874.41  5373.7 1874.41
#Mann=3,-1,0
  4723.2    0.12       0  5016.8    0.05       0  5020.8    0.12       0
Bank Sta=5016.8,5020.8
Exp/Cntr=0.3,0.1

Type RM Length L Ch R = 1,1906,480,480,480
BEGIN DESCRIPTION:
Stream0075_DS 4.0
END DESCRIPTION:
XS GIS Cut Line= 3
      2003274.98     13862024.99      2003575.00     13862175.00
      2003875.03     13862225.00
#Sta/Elev= 30
  4668.9 1851.43  4691.3 1844.39  4750.0 1806.71  4766.8 1798.45  4772.3 1794.22
  4789.1 1786.29  4794.7 1782.15  4808.7 1777.32  4833.8 1764.68  4878.6 1747.33
  4968.0 1724.47  4980.0 1714.74  4980.2 1714.24  4984.0 1714.74  5006.9 1715.73
  5037.3 1728.57  5085.4 1739.43  5093.0 1742.68  5098.1 1742.70  5146.3 1760.49
  5197.0 1785.74  5207.1 1791.45  5214.7 1797.87  5219.8 1798.75  5247.6 1819.45
  5267.9 1831.59  5275.5 1837.91  5280.6 1838.83  5305.9 1852.52  5308.5 1852.52
#Mann=3,-1,0
  4668.9    0.12       0  4980.0    0.05       0  4984.0    0.12       0
Bank Sta=4980,4984
Exp/Cntr=0.3,0.1

Type RM Length L Ch R = 1,1426,456,456,456
BEGIN DESCRIPTION:
Stream0075_DS 3.0
END DESCRIPTION:
XS GIS Cut Line= 3
      2003075.04     13862525.01      2003375.00     13862575.00
      2003674.96     13862525.01
#Sta/Elev= 30
  4699.9 1844.76  4702.4 1844.76  4720.1 1831.96  4727.7 1823.13  4732.8 1821.51
  4740.4 1814.47  4788.6 1784.28  4849.4 1751.46  4882.3 1736.75  4910.2 1727.78
  4953.3 1720.61  4963.5 1715.35  4971.1 1707.69  4991.9 1696.49  4992.1 1695.99
  4995.9 1696.49  5006.5 1699.57  5014.1 1706.52  5031.9 1711.32  5075.0 1704.56
  5125.7 1709.22  5135.8 1706.62  5153.5 1714.36  5158.6 1708.45  5186.5 1722.68
  5214.4 1740.92  5219.4 1733.33  5227.0 1741.05  5247.3 1755.33  5308.1 1780.86
#Mann=3,-1,0
  4699.9    0.12       0  4991.9    0.05       0  4995.9    0.12       0
Bank Sta=4991.9,4995.9
Exp/Cntr=0.3,0.1

Type RM Length L Ch R = 1,970,444,444,444
BEGIN DESCRIPTION:
Stream0075_DS 2.0
END DESCRIPTION:
XS GIS Cut Line= 3
      2003024.99     13862724.99      2003225.00     13862975.00
      2003520.24     13863076.90
#Sta/Elev= 30
  4679.8 1836.46  4683.0 1836.46  4730.2 1813.76  4757.4 1798.31  4815.1 1771.29
  4821.5 1766.56  4843.9 1757.06  4864.7 1745.49  4879.1 1739.69  4899.9 1728.65
  4907.9 1726.41  4922.3 1717.60  4928.7 1711.83  4943.1 1704.23  4949.5 1698.58
  4963.9 1692.10  4986.4 1689.84  4992.8 1684.29  4996.8 1682.74  5008.3 1682.12
  5008.5 1681.62  5012.3 1682.12  5015.6 1682.52  5021.1 1698.14  5031.7 1704.05
  5142.0 1713.16  5202.7 1716.46  5232.7 1720.44  5285.6 1728.17  5312.3 1734.43
#Mann=5,-1,0
  4679.8    0.12       0  5008.3    0.05       0  5012.3    0.12       0
  5142.0   0.035       0  5232.7    0.12       0
Bank Sta=5008.3,5012.3
Exp/Cntr=0.3,0.1

Type RM Length L Ch R = 1,526,335,335,335
BEGIN DESCRIPTION:
Stream0075_DS 1.0
END DESCRIPTION:
XS GIS Cut Line= 3
      2002847.73     13863042.30      2002925.00     13863275.00
      2003125.05     13863325.01
#Sta/Elev= 30
  4754.8 1699.46  4758.4 1699.46  4762.5 1701.89  4773.1 1698.58  4778.7 1697.16
  4788.9 1696.41  4794.1 1697.70  4799.8 1696.47  4852.2 1695.16  4857.5 1696.28
  4873.6 1695.15  4924.9 1695.39  4936.8 1694.72  4952.5 1691.54  4957.8 1685.95
  4968.4 1681.96  4982.2 1675.25  4982.4 1674.75  4986.2 1675.25  4997.4 1677.39
  5002.6 1677.39  5010.3 1680.51  5020.7 1682.40  5100.5 1681.46  5105.7 1680.66
  5131.5 1682.72  5141.7 1684.98  5164.9 1693.58  5175.2 1695.87  5206.2 1698.57
#Mann=7,-1,0
  4754.8   0.035       0  4773.1    0.12       0  4924.9    0.07       0
  4982.2    0.05       0  4986.2    0.07       0  5020.7    0.12       0
  5131.5    0.07       0
Bank Sta=4982.2,4986.2
Exp/Cntr=0.3,0.1

Type RM Length L Ch R = 1,191,0,0,0
BEGIN DESCRIPTION:
Stream0075_DS 0.0
END DESCRIPTION:
XS GIS Cut Line= 4
      2002664.19     13863237.46      2002632.10     13863429.70
      2002676.19     13863484.58      2003000.65     13863439.31
#Sta/Elev= 30
  4734.7 1685.47  4793.0 1685.17  4831.2 1683.67  4851.9 1683.40  4874.1 1682.98
  4904.6 1678.20  4942.5 1676.13  4949.2 1674.85  4963.3 1669.17  4969.3 1668.08
  4969.6 1667.58  4973.3 1668.08  4977.7 1671.83  4985.7 1670.01  4992.1 1673.03
  4997.1 1671.61  5008.9 1672.77  5019.0 1672.74  5059.4 1677.67  5079.6 1684.68
  5089.7 1686.75  5110.2 1687.72  5153.0 1687.81  5220.9 1687.71  5248.2 1690.20
  5253.3 1689.42  5281.5 1692.12  5319.7 1693.96  5324.8 1693.18  5327.6 1694.18
#Mann=6,-1,0
  4734.7   0.035       0  4831.2    0.12       0  4851.9   0.035       0
  4969.3   0.035       0  4973.3   0.035       0  5153.0    0.12       0
Bank Sta=4969.3,4973.3
Exp/Cntr=0.3,0.1

Chan Stop Cuts=-1