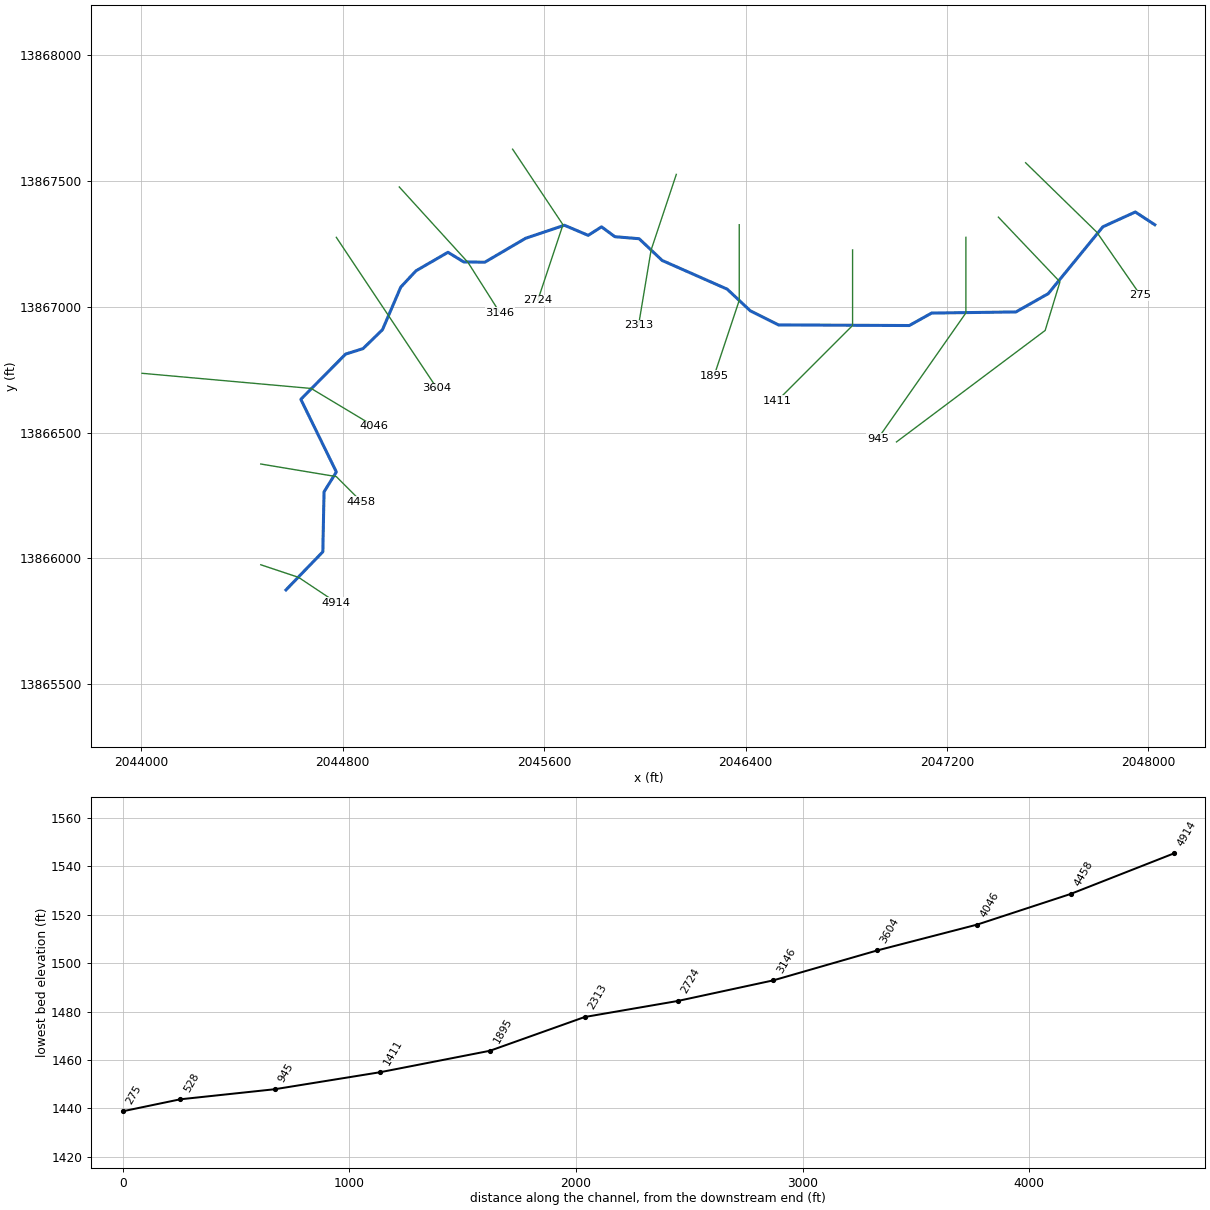
--- Stream0077_DS.prj (project) ---

Proj Title=Stream0077_DS Base Level Engineering
Current Plan=p01
Default Exp/Contr=0.3,0.1
English Units
Geom File=g01
Flow File=f01
Plan File=p01
BEGIN DESCRIPTION:
Stream0077_DS
END DESCRIPTION:

--- Stream0077_DS.p01 (plan) ---

Plan Title=Multiple Run
Short Identifier=Multiple
Geom File=g01
Flow File=f01
Subcritical Flow
K Sum by GR= 0
Std Step Tol= 0.01
Critical Tol= 0.01
Num of Std Step Trials= 20
Max Error Tol= 0.3
Flow Tol Ratio= 0.001
Split Flow NTrial= 30
Split Flow Tol= 0.02
Split Flow Ratio= 0.02
Log Output Level= 0
Friction Slope Method= 1
Unsteady Friction Slope Method= 2
Unsteady Bridges Friction Slope Method= 1
Parabolic Critical Depth
Global Vel Dist=  1 , 1 , 1
Global Log Level= 0
CheckData=True
Encroach Param= -1, 0, 0, 0
BEGIN DESCRIPTION:
Multiple Run
END DESCRIPTION:

--- Stream0077_DS.f01 (steady flow) ---

Flow Title=Multiple
Number of Profiles=7
Profile Names=10-year,25-year,50-year,1pct_min,100-year,1pct_plu,500-year
River Rch & RM= Stream0077_DS,Reach-1,4914
     351     553     735     477     951    1898    1566
River Rch & RM= Stream0077_DS,Reach-1,4046
    1005    1701    2366    1598    3188    6361    5718
Boundary for River Rch & Prof#=Stream0077_DS,Reach-1,1
Up Type=0
Dn Type=3
Dn Slope=0.005
Boundary for River Rch & Prof#=Stream0077_DS,Reach-1,2
Up Type=0
Dn Type=3
Dn Slope=0.005
Boundary for River Rch & Prof#=Stream0077_DS,Reach-1,3
Up Type=0
Dn Type=3
Dn Slope=0.005
Boundary for River Rch & Prof#=Stream0077_DS,Reach-1,4
Up Type=0
Dn Type=3
Dn Slope=0.005
Boundary for River Rch & Prof#=Stream0077_DS,Reach-1,5
Up Type=0
Dn Type=3
Dn Slope=0.005
Boundary for River Rch & Prof#=Stream0077_DS,Reach-1,6
Up Type=0
Dn Type=3
Dn Slope=0.005
Boundary for River Rch & Prof#=Stream0077_DS,Reach-1,7
Up Type=0
Dn Type=3
Dn Slope=0.005

--- Stream0077_DS.g01 (geometry) ---

Geom Title=Existing Conditions

River Reach=Stream0077_DS,Reach-1
Reach XY= 30
      2044575.00     13865875.00      2044721.47     13866026.46
      2044726.24     13866264.50      2044775.18     13866343.43
      2044634.11     13866631.73      2044811.79     13866811.37
      2044881.07     13866833.15      2044958.37     13866908.29
      2045030.83     13867077.31      2045091.42     13867142.09
      2045218.38     13867215.59      2045280.49     13867177.49
      2045364.45     13867176.09      2045526.58     13867271.17
      2045680.73     13867323.02      2045775.08     13867282.83
      2045828.22     13867316.73      2045880.89     13867277.55
      2045977.42     13867269.47      2046068.95     13867183.16
      2046327.29     13867069.15      2046418.95     13866983.16
      2046530.93     13866927.24      2047050.08     13866924.80
      2047138.92     13866974.32      2047473.45     13866978.75
      2047601.82     13867051.29      2047818.93     13867316.87
      2047947.74     13867375.57      2048025.00     13867325.00

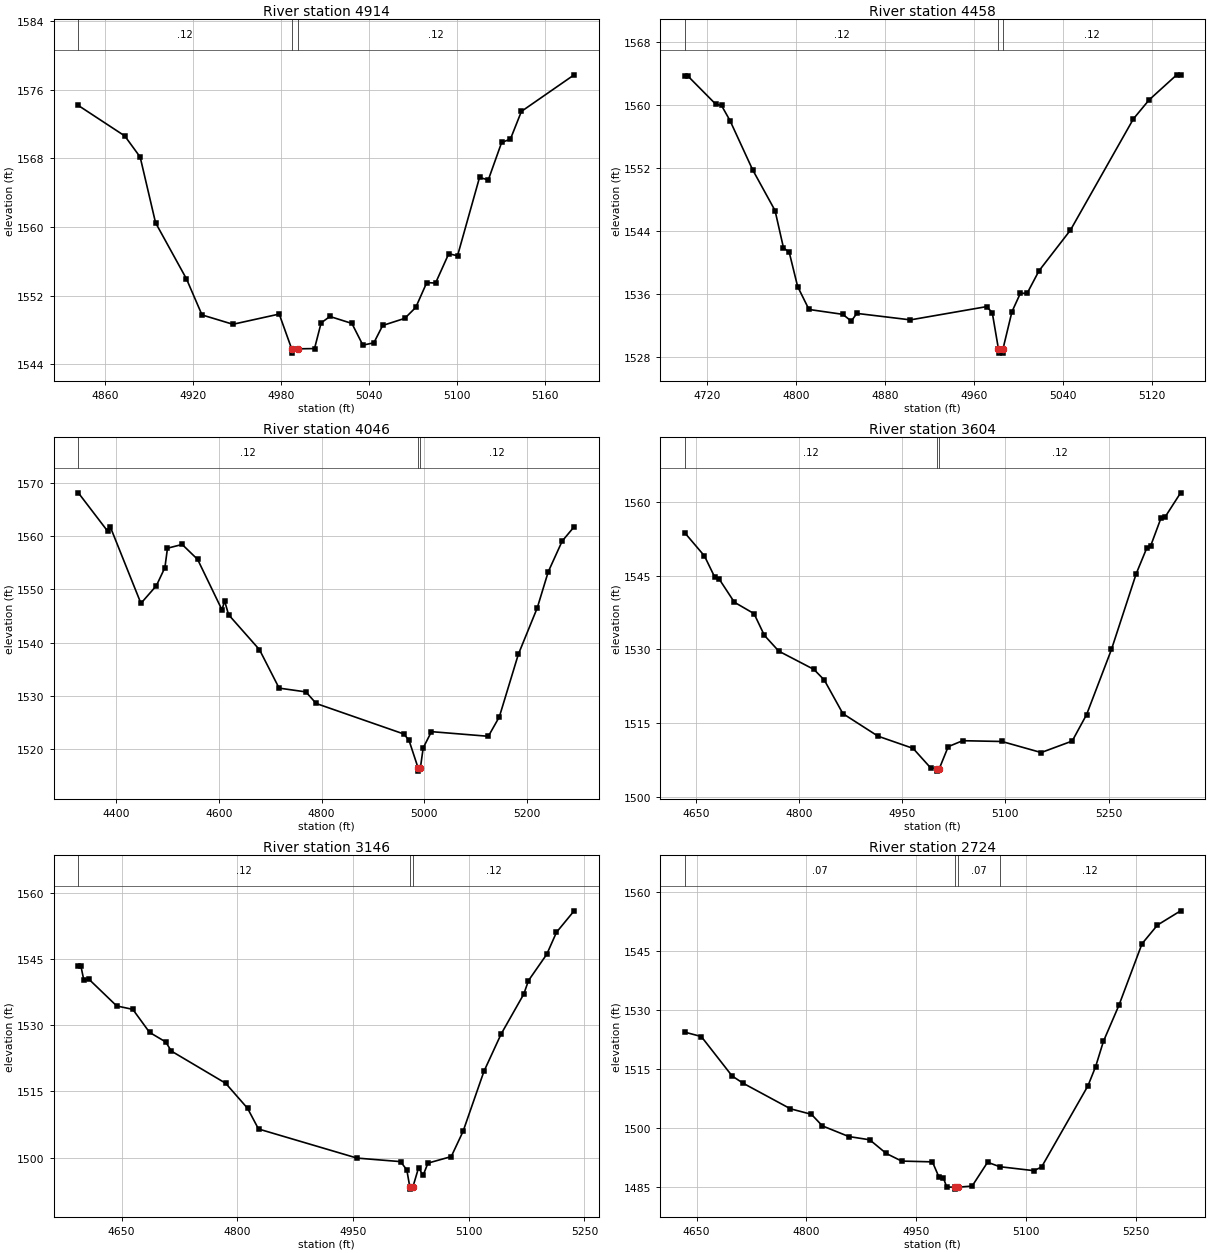
Type RM Length L Ch R = 1,4914,456,456,456
BEGIN DESCRIPTION:
Stream0077_DS 10.0
END DESCRIPTION:
XS GIS Cut Line= 3
      2044474.96     13865975.01      2044625.00     13865925.00
      2044774.97     13865825.02
#Sta/Elev= 30
  4841.8 1574.16  4873.5 1570.61  4884.0 1568.15  4894.5 1560.50  4915.6 1553.96
  4926.2 1549.76  4947.3 1548.67  4978.9 1549.86  4987.4 1545.81  4987.7 1545.31
  4991.4 1545.81  5003.0 1545.84  5007.5 1548.83  5013.5 1549.58  5028.5 1548.77
  5036.0 1546.24  5043.5 1546.51  5049.5 1548.53  5064.6 1549.36  5072.1 1550.64
  5079.6 1553.53  5085.6 1553.47  5094.6 1556.89  5100.6 1556.65  5115.6 1565.77
  5121.6 1565.49  5130.7 1569.85  5136.7 1570.24  5144.2 1573.47  5180.2 1577.73
#Mann=3,-1,0
  4841.8    0.12       0  4987.4    0.05       0  4991.4    0.12       0
Bank Sta=4987.4,4991.4
Exp/Cntr=0.3,0.1

Type RM Length L Ch R = 1,4458,412,412,412
BEGIN DESCRIPTION:
Stream0077_DS 9.0
END DESCRIPTION:
XS GIS Cut Line= 3
      2044474.96     13866375.01      2044775.00     13866325.00
      2044875.00     13866225.00
#Sta/Elev= 30
  4699.8 1563.73  4702.4 1563.73  4727.7 1560.12  4732.8 1559.97  4740.4 1558.06
  4760.7 1551.83  4780.9 1546.64  4788.5 1541.90  4793.6 1541.37  4801.2 1537.00
  4811.4 1534.09  4841.8 1533.47  4849.4 1532.61  4854.4 1533.59  4902.6 1532.77
  4971.0 1534.45  4976.1 1533.70  4981.7 1529.05  4982.0 1528.55  4985.5 1528.55
  4985.7 1529.05  4993.8 1533.80  5001.4 1536.15  5007.5 1536.15  5018.1 1538.99
  5046.4 1544.16  5103.0 1558.28  5117.1 1560.68  5141.9 1563.86  5145.4 1563.86
#Mann=3,-1,0
  4699.8    0.12       0  4981.7    0.05       0  4985.7    0.12       0
Bank Sta=4981.7,4985.7
Exp/Cntr=0.3,0.1

Type RM Length L Ch R = 1,4046,442,442,442
BEGIN DESCRIPTION:
Stream0077_DS 8.0
END DESCRIPTION:
XS GIS Cut Line= 3
      2044003.61     13866735.19      2044675.00     13866675.00
      2044924.98     13866525.01
#Sta/Elev= 30
  4326.4 1568.08  4383.8 1560.85  4388.8 1561.66  4448.3 1547.36  4478.4 1550.67
  4495.0 1554.07  4500.0 1557.70  4528.6 1558.40  4558.7 1555.60  4606.2 1546.13
  4611.2 1547.84  4619.0 1545.23  4679.2 1538.67  4717.4 1531.47  4769.6 1530.76
  4789.6 1528.59  4960.3 1522.87  4970.4 1521.68  4988.4 1516.41  4988.7 1515.91
  4992.4 1516.41  4998.0 1520.27  5014.1 1523.31  5124.9 1522.44  5146.3 1526.09
  5183.2 1537.78  5220.1 1546.50  5241.5 1553.27  5268.7 1559.04  5292.0 1561.72
#Mann=3,-1,0
  4326.4    0.12       0  4988.4    0.05       0  4992.4    0.12       0
Bank Sta=4988.4,4992.4
Exp/Cntr=0.3,0.1

Type RM Length L Ch R = 1,3604,458,458,458
BEGIN DESCRIPTION:
Stream0077_DS 7.0
END DESCRIPTION:
XS GIS Cut Line= 3
      2044774.99     13867275.02      2044975.00     13866975.00
      2045174.98     13866675.03
#Sta/Elev= 30
  4633.7 1553.69  4662.3 1548.98  4677.3 1544.66  4683.3 1544.37  4705.8 1539.57
  4734.4 1537.25  4749.4 1532.84  4770.4 1529.62  4821.5 1525.90  4836.5 1523.76
  4863.6 1516.91  4914.7 1512.32  4965.7 1509.84  4991.3 1505.86  4999.8 1505.71
  5000.0 1505.21  5003.8 1505.71  5016.8 1510.19  5037.8 1511.40  5094.9 1511.24
  5152.0 1508.99  5197.1 1511.33  5218.1 1516.73  5254.2 1529.96  5290.2 1545.37
  5305.3 1550.51  5311.3 1551.06  5326.3 1556.72  5332.3 1556.93  5354.8 1561.83
#Mann=3,-1,0
  4633.7    0.12       0  4999.8    0.05       0  5003.8    0.12       0
Bank Sta=4999.8,5003.8
Exp/Cntr=0.3,0.1

Type RM Length L Ch R = 1,3146,422,422,422
BEGIN DESCRIPTION:
Stream0077_DS 6.0
END DESCRIPTION:
XS GIS Cut Line= 3
      2045024.98     13867475.02      2045298.19     13867174.95
      2045425.01     13866974.99
#Sta/Elev= 30
  4594.0 1543.32  4597.4 1543.32  4601.1 1540.23  4607.9 1540.38  4643.7 1534.36
  4664.6 1533.58  4686.3 1528.37  4707.2 1526.21  4714.6 1524.13  4784.9 1516.85
  4813.3 1511.18  4827.5 1506.49  4955.2 1499.90  5011.6 1499.10  5019.7 1497.23
  5023.6 1493.37  5023.9 1492.87  5027.6 1493.37  5034.9 1497.67  5040.9 1496.02
  5047.1 1498.76  5077.3 1500.24  5092.6 1505.94  5119.7 1519.55  5141.9 1527.98
  5171.3 1537.04  5177.4 1540.10  5201.1 1546.06  5213.7 1551.04  5236.6 1555.90
#Mann=3,-1,0
  4594.0    0.12       0  5023.6    0.05       0  5027.6    0.12       0
Bank Sta=5023.6,5027.6
Exp/Cntr=0.3,0.1

Type RM Length L Ch R = 1,2724,411,411,411
BEGIN DESCRIPTION:
Stream0077_DS 5.0
END DESCRIPTION:
XS GIS Cut Line= 3
      2045475.00     13867625.00      2045675.00     13867325.00
      2045574.99     13867024.98
#Sta/Elev= 30
  4634.0 1524.31  4656.5 1523.20  4698.6 1513.15  4713.6 1511.31  4778.2 1504.80
  4806.8 1503.40  4821.8 1500.45  4857.8 1497.74  4886.4 1496.91  4908.9 1493.44
  4930.0 1491.49  4972.0 1491.29  4981.0 1487.38  4987.0 1487.20  4991.5 1484.88
  5003.1 1484.85  5003.3 1484.35  5007.1 1484.85  5026.2 1485.13  5047.3 1491.19
  5063.9 1490.06  5110.5 1489.05  5121.0 1489.98  5184.3 1510.65  5194.8 1515.55
  5205.4 1521.96  5226.5 1531.11  5258.1 1546.82  5279.2 1551.58  5310.8 1555.20
#Mann=4,-1,0
  4634.0    0.07       0  5003.1    0.05       0  5007.1    0.07       0
  5063.9    0.12       0
Bank Sta=5003.1,5007.1
Exp/Cntr=0.3,0.1

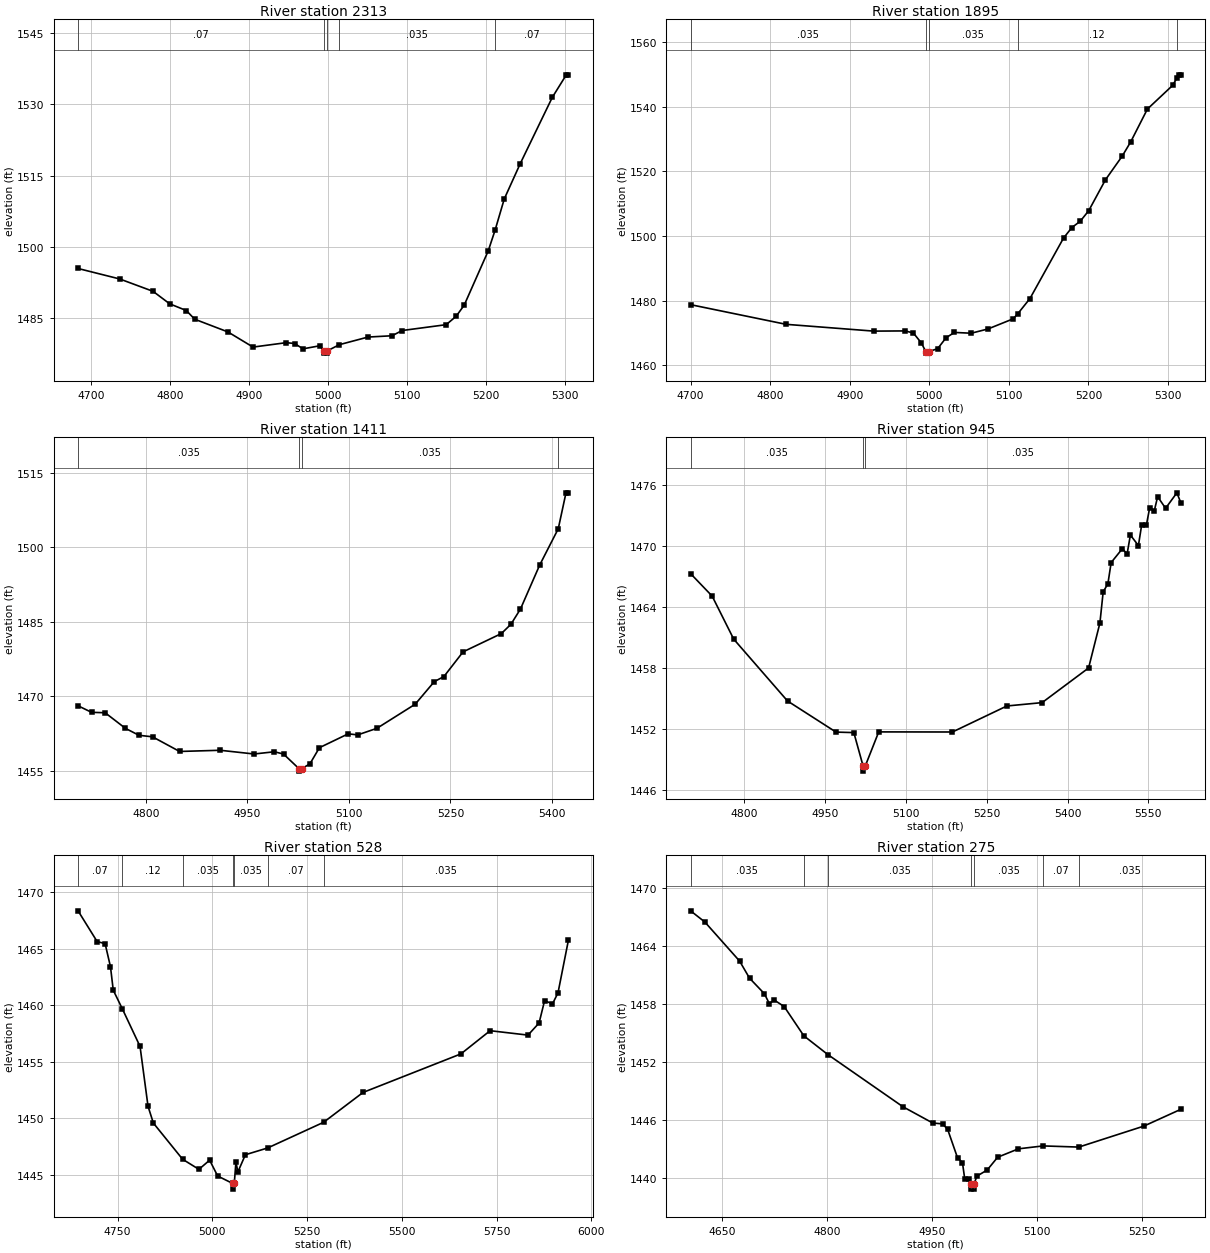
Type RM Length L Ch R = 1,2313,418,418,418
BEGIN DESCRIPTION:
Stream0077_DS 4.0
END DESCRIPTION:
XS GIS Cut Line= 3
      2046125.00     13867525.00      2046025.00     13867225.00
      2045974.99     13866924.96
#Sta/Elev= 30
  4683.8 1495.51  4736.5 1493.31  4778.7 1490.71  4799.7 1488.09  4820.8 1486.67
  4831.4 1484.85  4873.5 1482.17  4905.2 1478.99  4947.3 1479.92  4957.9 1479.74
  4968.4 1478.62  4989.5 1479.26  4995.4 1478.22  4995.6 1477.72  4999.1 1477.72
  4999.4 1478.22  5014.5 1479.50  5050.7 1481.10  5081.1 1481.37  5093.8 1482.47
  5149.6 1483.70  5162.2 1485.46  5172.4 1487.80  5202.8 1499.21  5211.5 1503.57
  5223.1 1510.13  5243.3 1517.55  5283.9 1531.49  5301.6 1536.22  5304.2 1536.22
#Mann=5,-1,0
  4683.8    0.07       0  4995.4    0.05       0  4999.4    0.07       0
  5014.5   0.035       0  5211.5    0.07       0
Bank Sta=4995.4,4999.4
Exp/Cntr=0.3,0.1

Type RM Length L Ch R = 1,1895,484,484,484
BEGIN DESCRIPTION:
Stream0077_DS 3.0
END DESCRIPTION:
XS GIS Cut Line= 3
      2046375.00     13867325.00      2046375.00     13867025.00
      2046275.01     13866725.03
#Sta/Elev= 30
  4700.0 1478.77  4820.0 1472.69  4930.0 1470.59  4970.0 1470.65  4980.0 1469.99
  4990.0 1466.94  4995.5 1464.28  4995.7 1463.78  4999.2 1463.78  4999.5 1464.28
  5010.5 1465.16  5021.1 1468.55  5031.6 1470.18  5052.7 1469.94  5073.8 1471.26
  5105.4 1474.39  5111.3 1476.00  5126.5 1480.67  5168.7 1499.38  5179.2 1502.63
  5189.7 1504.58  5200.3 1507.82  5221.4 1517.41  5242.4 1524.71  5253.0 1529.08
  5274.1 1539.28  5305.7 1546.58  5311.1 1548.83  5313.6 1549.87  5316.2 1549.87
#Mann=5,-1,0
  4700.0   0.035       0  4995.5   0.035       0  4999.5   0.035       0
  5111.3    0.12       0  5311.1    0.07       0
Bank Sta=4995.5,4999.5
Exp/Cntr=0.3,0.1

Type RM Length L Ch R = 1,1411,466,466,466
BEGIN DESCRIPTION:
Stream0077_DS 2.0
END DESCRIPTION:
XS GIS Cut Line= 3
      2046825.00     13867224.97      2046825.00     13866925.00
      2046525.03     13866625.03
#Sta/Elev= 30
  4700.0 1468.09  4720.0 1466.77  4740.0 1466.69  4770.0 1463.54  4790.0 1462.15
  4810.0 1461.84  4850.0 1458.89  4910.0 1459.13  4960.0 1458.38  4990.0 1458.83
  5003.5 1458.37  5026.3 1455.43  5026.5 1454.93  5030.3 1455.43  5042.4 1456.38
  5056.5 1459.65  5099.0 1462.44  5113.1 1462.23  5141.4 1463.55  5198.0 1468.41
  5226.2 1472.96  5240.4 1473.98  5268.7 1478.95  5325.2 1482.63  5339.4 1484.51
  5353.5 1487.59  5381.8 1496.42  5409.3 1503.75  5420.7 1510.98  5424.2 1510.98
#Mann=4,-1,0
  4700.0   0.035       0  5026.3   0.035       0  5030.3   0.035       0
  5409.3    0.07       0
Bank Sta=5026.3,5030.3
Exp/Cntr=0.3,0.1

Type RM Length L Ch R = 1,945,417,417,417
BEGIN DESCRIPTION:
Stream0077_DS 1.0
END DESCRIPTION:
XS GIS Cut Line= 3
      2047275.00     13867275.03      2047275.00     13866975.00
      2046924.98     13866474.97
#Sta/Elev= 30
  4700.0 1467.32  4740.0 1465.11  4780.0 1460.88  4880.0 1454.79  4970.0 1451.73
  5003.1 1451.68  5020.3 1448.39  5020.5 1447.89  5024.3 1448.39  5049.3 1451.75
  5186.2 1451.74  5287.3 1454.30  5352.7 1454.63  5439.0 1458.04  5460.0 1462.46
  5466.1 1465.54  5474.8 1466.31  5480.9 1468.41  5501.8 1469.78  5510.5 1469.25
  5516.6 1471.12  5531.5 1470.08  5537.6 1472.13  5546.3 1472.09  5552.4 1473.79
  5561.1 1473.53  5567.2 1474.89  5582.0 1473.75  5602.9 1475.27  5610.4 1474.28
#Mann=3,-1,0
  4700.0   0.035       0  5020.3   0.035       0  5024.3   0.035       0
Bank Sta=5020.3,5024.3
Exp/Cntr=0.3,0.1

Type RM Length L Ch R = 1,528,253,253,253
BEGIN DESCRIPTION:
Stream0077_DS 0.1
END DESCRIPTION:
XS GIS Cut Line= 4
      2047404.00     13867355.17      2047648.41     13867098.25
      2047589.76     13866905.31      2046999.41     13866462.71
#Sta/Elev= 30
  4645.4 1468.34  4695.8 1465.62  4716.8 1465.44  4731.0 1463.39  4738.3 1461.32
  4762.2 1459.68  4809.0 1456.35  4830.1 1451.05  4844.2 1449.57  4921.4 1446.37
  4964.4 1445.48  4992.7 1446.29  5013.9 1444.89  5053.7 1444.23  5053.9 1443.73
  5057.7 1444.23  5062.1 1446.12  5067.3 1445.25  5087.0 1446.77  5145.8 1447.37
  5293.5 1449.64  5397.6 1452.28  5656.0 1455.69  5733.0 1457.74  5833.0 1457.35
  5862.2 1458.42  5876.8 1460.40  5897.6 1460.11  5912.2 1461.09  5939.5 1465.72
#Mann=7,-1,0
  4645.4    0.07       0  4762.2    0.12       0  4921.4   0.035       0
  5053.7   0.035       0  5057.7   0.035       0  5145.8    0.07       0
  5293.5   0.035       0
Bank Sta=5053.7,5057.7
Exp/Cntr=0.3,0.1

Type RM Length L Ch R = 1,275,0,0,0
BEGIN DESCRIPTION:
Stream0077_DS 0.0
END DESCRIPTION:
XS GIS Cut Line= 3
      2047512.14     13867571.08      2047794.77     13867295.42
      2047968.72     13867044.40
#Sta/Elev= 30
  4605.2 1467.59  4625.6 1466.43  4675.2 1462.39  4689.4 1460.62  4710.5 1459.02
  4717.6 1458.00  4724.6 1458.36  4738.8 1457.69  4766.9 1454.66  4801.2 1452.72
  4908.5 1447.32  4951.0 1445.64  4965.1 1445.55  4972.3 1444.98  4986.4 1442.04
  4993.4 1441.55  4996.7 1439.86  5003.3 1439.86  5005.9 1439.30  5006.1 1438.80
  5009.6 1438.80  5009.9 1439.30  5014.0 1440.14  5028.8 1440.78  5043.7 1442.10
  5073.4 1442.97  5108.7 1443.27  5159.6 1443.15  5252.5 1445.32  5305.4 1447.06
#Mann=7,-1,0
  4605.2   0.035       0  4766.9    0.07       0  4801.2   0.035       0
  5005.9   0.035       0  5009.9   0.035       0  5108.7    0.07       0
  5159.6   0.035       0
Bank Sta=5005.9,5009.9
Exp/Cntr=0.3,0.1

Chan Stop Cuts=-1