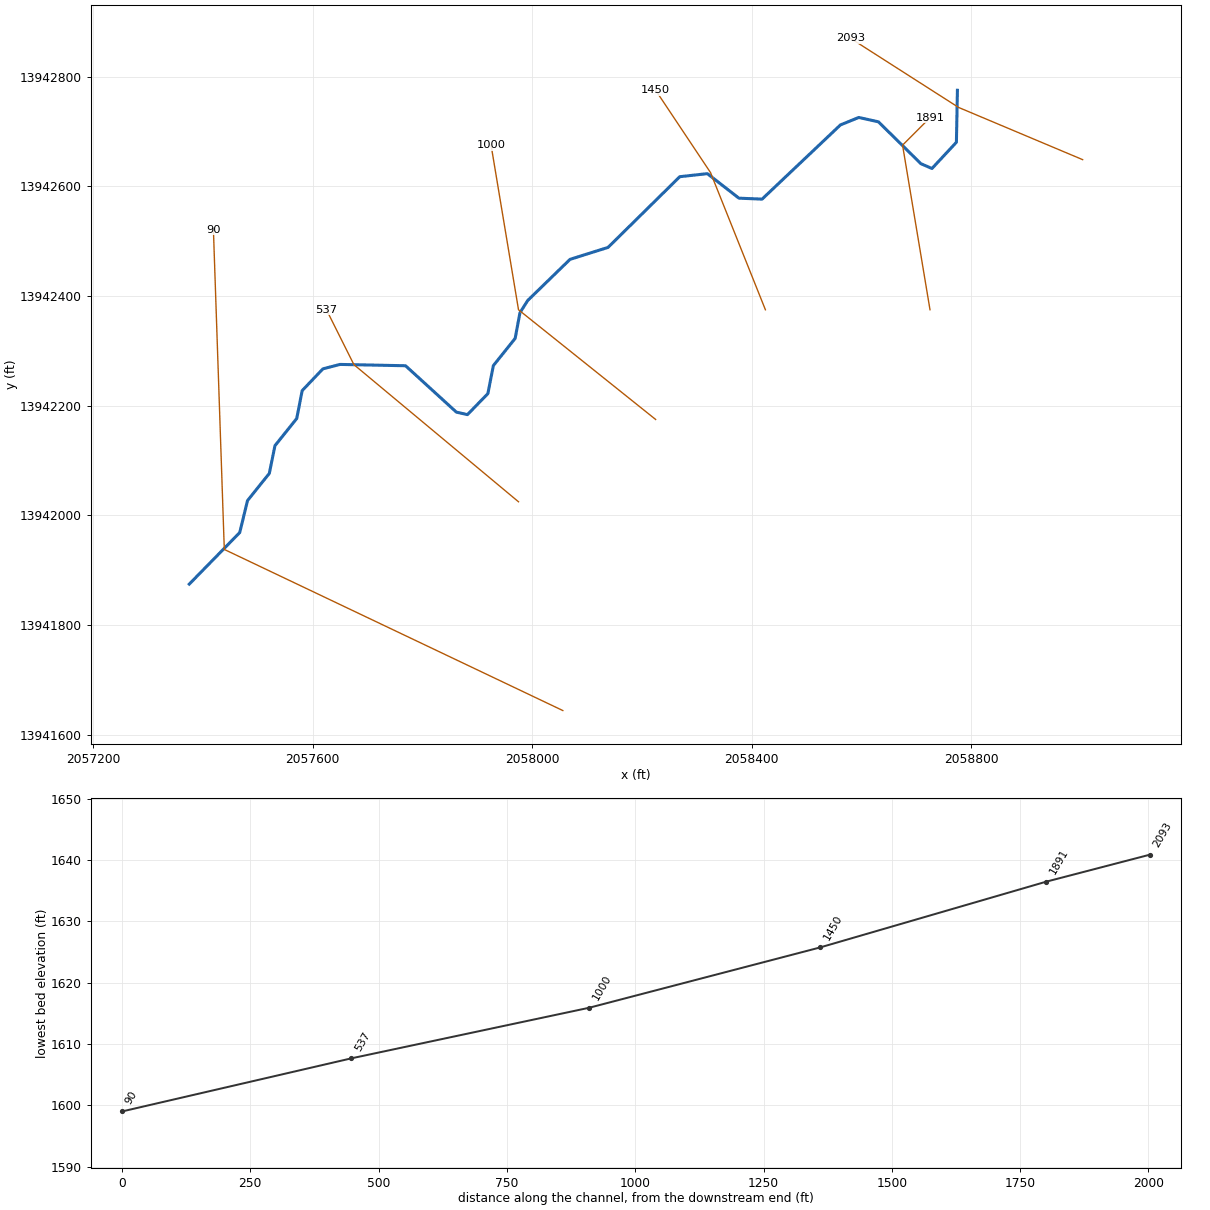
--- Stream0078_DS.prj (project) ---

Proj Title=Stream0078_DS Base Level Engineering
Current Plan=p01
Default Exp/Contr=0.3,0.1
English Units
Geom File=g01
Flow File=f01
Plan File=p01
BEGIN DESCRIPTION:
Stream0078_DS
END DESCRIPTION:

--- Stream0078_DS.p01 (plan) ---

Plan Title=Multiple Run
Short Identifier=Multiple
Geom File=g01
Flow File=f01
Subcritical Flow
K Sum by GR= 0
Std Step Tol= 0.01
Critical Tol= 0.01
Num of Std Step Trials= 20
Max Error Tol= 0.3
Flow Tol Ratio= 0.001
Split Flow NTrial= 30
Split Flow Tol= 0.02
Split Flow Ratio= 0.02
Log Output Level= 0
Friction Slope Method= 1
Unsteady Friction Slope Method= 2
Unsteady Bridges Friction Slope Method= 1
Parabolic Critical Depth
Global Vel Dist=  1 , 1 , 1
Global Log Level= 0
CheckData=True
Encroach Param= -1, 0, 0, 0
BEGIN DESCRIPTION:
Multiple Run
END DESCRIPTION:

--- Stream0078_DS.f01 (steady flow) ---

Flow Title=Multiple
Number of Profiles=7
Profile Names=10-year,25-year,50-year,1pct_min,100-year,1pct_plu,500-year
River Rch & RM= Stream0078_DS,Reach-1,2093
    1029    1773    2494    1705    3401    6787    6269
Boundary for River Rch & Prof#=Stream0078_DS,Reach-1,1
Up Type=0
Dn Type=3
Dn Slope=0.005
Boundary for River Rch & Prof#=Stream0078_DS,Reach-1,2
Up Type=0
Dn Type=3
Dn Slope=0.005
Boundary for River Rch & Prof#=Stream0078_DS,Reach-1,3
Up Type=0
Dn Type=3
Dn Slope=0.005
Boundary for River Rch & Prof#=Stream0078_DS,Reach-1,4
Up Type=0
Dn Type=3
Dn Slope=0.005
Boundary for River Rch & Prof#=Stream0078_DS,Reach-1,5
Up Type=0
Dn Type=3
Dn Slope=0.005
Boundary for River Rch & Prof#=Stream0078_DS,Reach-1,6
Up Type=0
Dn Type=3
Dn Slope=0.005
Boundary for River Rch & Prof#=Stream0078_DS,Reach-1,7
Up Type=0
Dn Type=3
Dn Slope=0.005

--- Stream0078_DS.g01 (geometry) ---

Geom Title=Existing Conditions

River Reach=Stream0078_DS,Reach-1
Reach XY= 30
      2058775.00     13942775.00      2058773.14     13942680.28
      2058728.61     13942632.44      2058708.44     13942641.19
      2058631.05     13942717.50      2058595.16     13942725.47
      2058561.79     13942711.89      2058418.96     13942576.62
      2058376.74     13942578.37      2058319.28     13942623.07
      2058268.94     13942617.52      2058138.21     13942488.63
      2058068.93     13942466.85      2057991.63     13942391.71
      2057977.61     13942369.38      2057968.90     13942322.81
      2057929.19     13942273.20      2057919.17     13942222.13
      2057881.95     13942183.84      2057861.79     13942188.39
      2057769.14     13942272.94      2057649.80     13942275.36
      2057618.52     13942267.31      2057580.71     13942227.59
      2057570.80     13942176.77      2057531.08     13942127.20
      2057520.84     13942076.72      2057481.10     13942027.19
      2057466.91     13941968.92      2057375.00     13941875.00

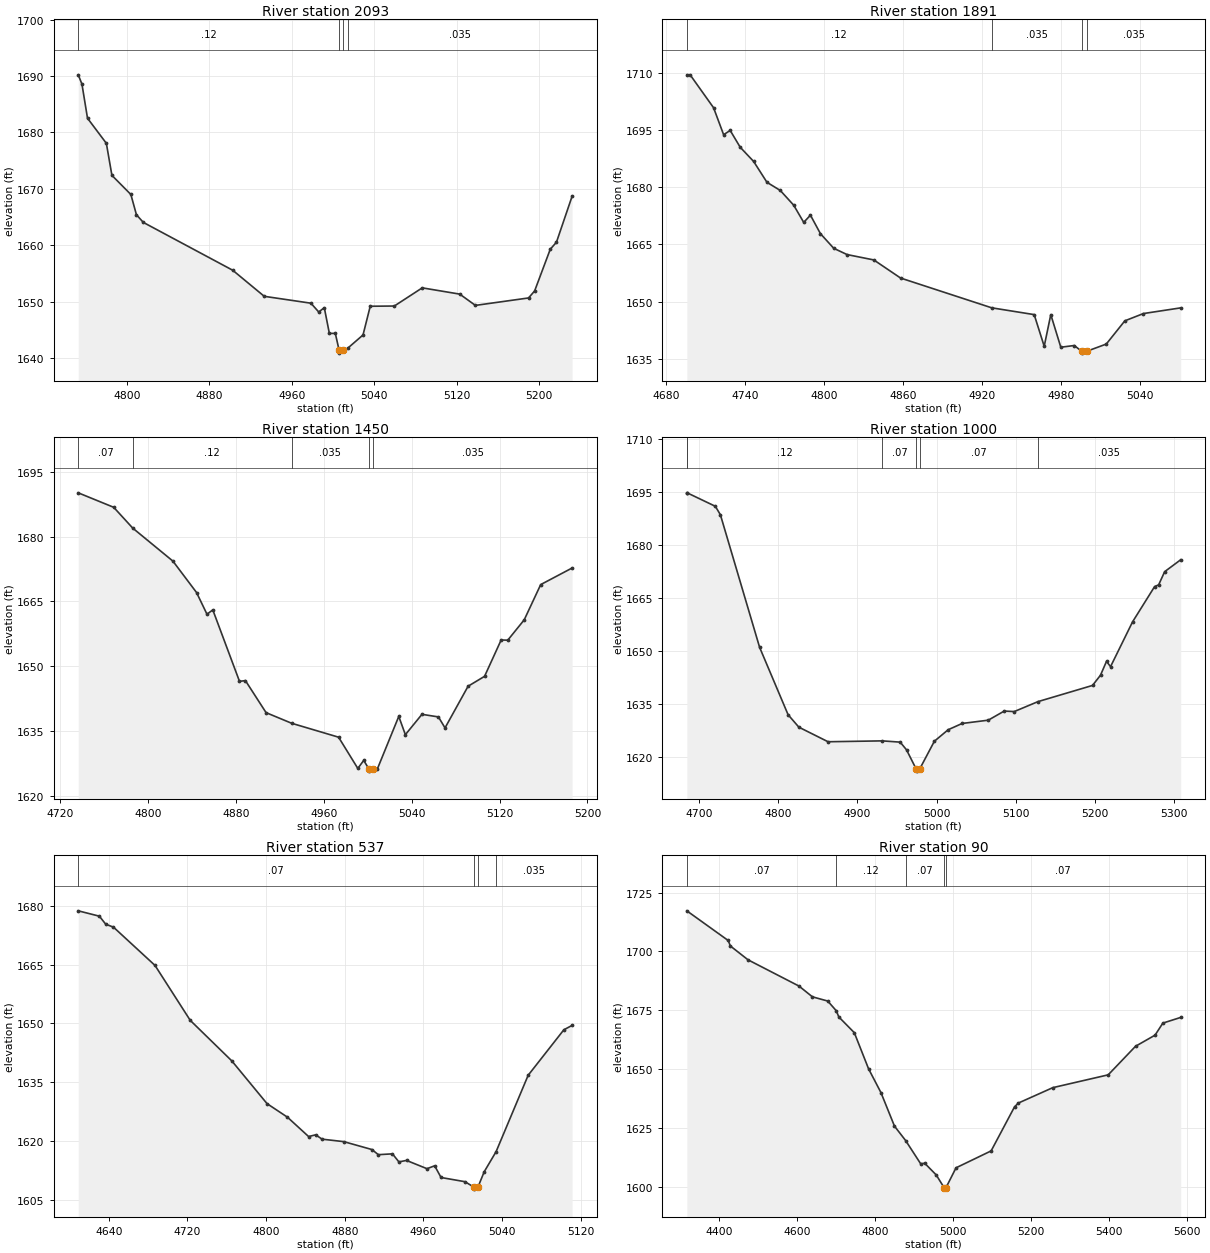
Type RM Length L Ch R = 1,2093,202,202,202
BEGIN DESCRIPTION:
Stream0078_DS 5.0
END DESCRIPTION:
XS GIS Cut Line= 3
      2059003.24     13942648.58      2058777.11     13942743.77
      2058579.85     13942869.94
#Sta/Elev= 30
  4752.6 1690.21  4756.2 1688.57  4761.6 1682.52  4779.9 1678.07  4785.3 1672.39
  4803.7 1669.00  4809.1 1665.41  4815.8 1664.05  4902.6 1655.57  4933.2 1650.95
  4978.5 1649.73  4986.1 1648.17  4991.5 1648.94  4996.4 1644.38  5002.2 1644.38
  5005.9 1641.38  5006.2 1640.88  5009.9 1641.38  5014.3 1641.76  5029.1 1644.10
  5036.1 1649.19  5059.5 1649.23  5086.6 1652.45  5123.0 1651.34  5138.2 1649.34
  5189.8 1650.66  5195.7 1651.90  5210.9 1659.30  5216.9 1660.54  5232.1 1668.69
#Mann=4,-1,0
  4752.6    0.12       0  5005.9    0.05       0  5009.9    0.12       0
  5014.3   0.035       0
Bank Sta=5005.9,5009.9
Exp/Cntr=0.3,0.1

Type RM Length L Ch R = 1,1891,441,441,441
BEGIN DESCRIPTION:
Stream0078_DS 4.0
END DESCRIPTION:
XS GIS Cut Line= 3
      2058725.00     13942375.02      2058675.00     13942675.00
      2058724.98     13942724.98
#Sta/Elev= 30
  4696.0 1709.53  4698.5 1709.53  4716.3 1700.88  4723.9 1693.82  4728.9 1694.93
  4736.5 1690.52  4746.7 1686.79  4756.8 1681.32  4766.9 1679.18  4777.1 1675.31
  4784.7 1670.80  4789.8 1672.69  4797.4 1667.83  4807.5 1663.99  4817.6 1662.35
  4837.9 1660.94  4858.2 1656.19  4927.4 1648.37  4959.6 1646.59  4967.2 1638.28
  4972.2 1646.59  4979.8 1638.03  4990.0 1638.48  4995.6 1636.98  4995.8 1636.48
  4999.6 1636.98  5014.3 1638.86  5028.4 1644.96  5042.5 1646.87  5070.8 1648.36
#Mann=4,-1,0
  4696.0    0.12       0  4927.4   0.035       0  4995.6   0.035       0
  4999.6   0.035       0
Bank Sta=4995.6,4999.6
Exp/Cntr=0.3,0.1

Type RM Length L Ch R = 1,1450,450,450,450
BEGIN DESCRIPTION:
Stream0078_DS 3.0
END DESCRIPTION:
XS GIS Cut Line= 3
      2058425.01     13942374.98      2058325.00     13942625.00
      2058224.98     13942775.03
#Sta/Elev= 30
  4736.5 1690.13  4768.8 1686.78  4786.1 1681.97  4822.7 1674.33  4844.2 1667.07
  4853.7 1662.05  4859.0 1663.05  4883.3 1646.52  4888.7 1646.69  4907.5 1639.28
  4930.8 1636.82  4973.5 1633.60  4991.0 1626.38  4996.4 1628.23  5001.1 1626.25
  5001.3 1625.75  5005.1 1626.25  5008.8 1626.25  5028.3 1638.41  5034.3 1634.18
  5049.4 1638.89  5064.4 1638.29  5070.4 1635.75  5091.4 1645.39  5106.4 1647.68
  5121.5 1656.09  5127.5 1656.04  5142.5 1660.75  5157.5 1668.90  5186.1 1672.74
#Mann=5,-1,0
  4736.5    0.07       0  4786.1    0.12       0  4930.8   0.035       0
  5001.1   0.035       0  5005.1   0.035       0
Bank Sta=5001.1,5005.1
Exp/Cntr=0.3,0.1

Type RM Length L Ch R = 1,1000,463,463,463
BEGIN DESCRIPTION:
Stream0078_DS 2.0
END DESCRIPTION:
XS GIS Cut Line= 3
      2058224.98     13942175.02      2057975.00     13942375.00
      2057924.99     13942675.03
#Sta/Elev= 30
  4684.4 1694.74  4684.8 1694.74  4720.4 1690.93  4726.8 1688.54  4776.4 1650.97
  4812.4 1631.89  4826.0 1628.37  4862.9 1624.24  4931.5 1624.49  4954.1 1624.13
  4962.1 1621.95  4974.5 1616.42  4974.8 1615.92  4978.5 1616.42  4997.3 1624.39
  5014.7 1627.64  5032.4 1629.42  5065.4 1630.35  5085.6 1632.93  5098.3 1632.79
  5128.3 1635.61  5197.2 1640.19  5207.3 1643.09  5214.9 1647.02  5220.0 1645.51
  5247.8 1658.19  5275.7 1668.19  5280.8 1668.68  5288.4 1672.41  5308.7 1675.79
#Mann=6,-1,0
  4684.4    0.07       0  4684.8    0.12       0  4931.5    0.07       0
  4974.5    0.05       0  4978.5    0.07       0  5128.3   0.035       0
Bank Sta=4974.5,4978.5
Exp/Cntr=0.3,0.1

Type RM Length L Ch R = 1,537,447,447,447
BEGIN DESCRIPTION:
Stream0078_DS 1.0
END DESCRIPTION:
XS GIS Cut Line= 3
      2057975.00     13942025.00      2057675.00     13942275.00
      2057625.01     13942374.99
#Sta/Elev= 30
  4608.9 1678.76  4630.4 1677.39  4636.9 1675.33  4644.7 1674.60  4687.0 1664.81
  4722.8 1650.79  4765.1 1640.43  4800.9 1629.52  4821.7 1626.05  4843.2 1621.11
  4850.4 1621.55  4856.9 1620.44  4879.0 1619.81  4907.6 1617.79  4914.1 1616.48
  4928.5 1616.69  4935.0 1614.64  4942.8 1615.01  4963.6 1612.90  4971.4 1613.64
  4977.9 1610.65  5002.2 1609.58  5011.4 1608.18  5011.6 1607.68  5015.4 1608.18
  5021.8 1612.12  5033.9 1617.26  5066.5 1636.76  5102.8 1648.38  5111.2 1649.50
#Mann=4,-1,0
  4608.9    0.07       0  5011.4    0.05       0  5015.4    0.07       0
  5033.9   0.035       0
Bank Sta=5011.4,5015.4
Exp/Cntr=0.3,0.1

Type RM Length L Ch R = 1,90,0,0,0
BEGIN DESCRIPTION:
Stream0078_DS 0.0
END DESCRIPTION:
XS GIS Cut Line= 3
      2058055.77     13941644.51      2057438.78     13941938.15
      2057418.94     13942520.81
#Sta/Elev= 30
  4316.7 1717.22  4422.7 1704.62  4428.3 1702.29  4473.6 1696.41  4604.3 1685.26
  4638.7 1680.69  4678.0 1678.90  4699.9 1674.77  4706.3 1672.16  4746.1 1665.46
  4782.7 1650.10  4814.3 1640.05  4849.1 1625.77  4877.6 1619.67  4916.2 1609.80
  4926.7 1610.00  4956.1 1605.05  4976.8 1599.52  4977.0 1599.02  4980.8 1599.52
  5006.9 1608.07  5096.9 1615.26  5156.9 1633.97  5166.9 1635.59  5255.0 1642.12
  5397.1 1647.56  5467.1 1659.69  5517.2 1664.42  5537.2 1669.53  5583.0 1671.95
#Mann=5,-1,0
  4316.7    0.07       0  4699.9    0.12       0  4877.6    0.07       0
  4976.8    0.05       0  4980.8    0.07       0
Bank Sta=4976.8,4980.8
Exp/Cntr=0.3,0.1

Chan Stop Cuts=-1