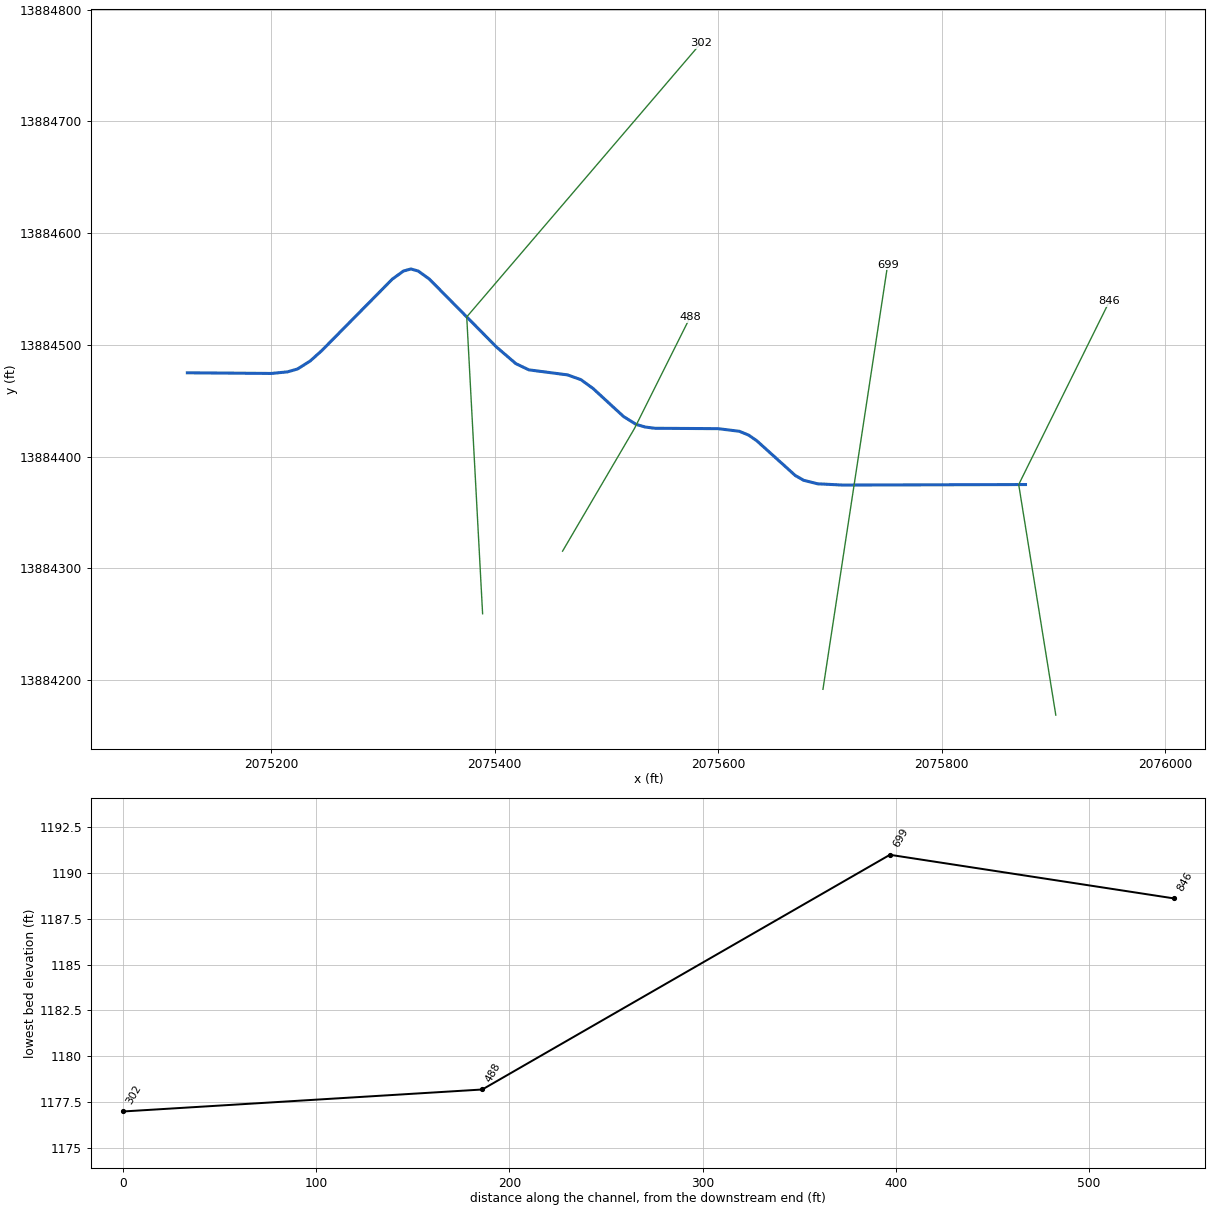
--- Stream0079_DS.prj (project) ---

Proj Title=Stream0079_DS Base Level Engineering
Current Plan=p01
Default Exp/Contr=0.3,0.1
English Units
Geom File=g01
Flow File=f01
Plan File=p01
BEGIN DESCRIPTION:
Stream0079_DS
END DESCRIPTION:

--- Stream0079_DS.p01 (plan) ---

Plan Title=Multiple Run
Short Identifier=Multiple
Geom File=g01
Flow File=f01
Subcritical Flow
K Sum by GR= 0
Std Step Tol= 0.01
Critical Tol= 0.01
Num of Std Step Trials= 20
Max Error Tol= 0.3
Flow Tol Ratio= 0.001
Split Flow NTrial= 30
Split Flow Tol= 0.02
Split Flow Ratio= 0.02
Log Output Level= 0
Friction Slope Method= 1
Unsteady Friction Slope Method= 2
Unsteady Bridges Friction Slope Method= 1
Parabolic Critical Depth
Global Vel Dist=  1 , 1 , 1
Global Log Level= 0
CheckData=True
Encroach Param= -1, 0, 0, 0
BEGIN DESCRIPTION:
Multiple Run
END DESCRIPTION:

--- Stream0079_DS.f01 (steady flow) ---

Flow Title=Multiple
Number of Profiles=7
Profile Names=10-year,25-year,50-year,1pct_min,100-year,1pct_plu,500-year
River Rch & RM= Stream0079_DS,Reach-1,846
     690    1134    1545    1024    2044    4078    3526
Boundary for River Rch & Prof#=Stream0079_DS,Reach-1,1
Up Type=0
Dn Type=3
Dn Slope=0.005
Boundary for River Rch & Prof#=Stream0079_DS,Reach-1,2
Up Type=0
Dn Type=3
Dn Slope=0.005
Boundary for River Rch & Prof#=Stream0079_DS,Reach-1,3
Up Type=0
Dn Type=3
Dn Slope=0.005
Boundary for River Rch & Prof#=Stream0079_DS,Reach-1,4
Up Type=0
Dn Type=3
Dn Slope=0.005
Boundary for River Rch & Prof#=Stream0079_DS,Reach-1,5
Up Type=0
Dn Type=3
Dn Slope=0.005
Boundary for River Rch & Prof#=Stream0079_DS,Reach-1,6
Up Type=0
Dn Type=3
Dn Slope=0.005
Boundary for River Rch & Prof#=Stream0079_DS,Reach-1,7
Up Type=0
Dn Type=3
Dn Slope=0.005

--- Stream0079_DS.g01 (geometry) ---

Geom Title=Existing Conditions

River Reach=Stream0079_DS,Reach-1
Reach XY= 30
      2075875.00     13884375.00      2075711.17     13884374.54
      2075688.91     13884375.67      2075676.56     13884378.77
      2075668.94     13884383.13      2075634.63     13884414.11
      2075627.31     13884419.19      2075619.02     13884422.64
      2075600.00     13884425.00      2075543.33     13884425.36
      2075534.70     13884426.47      2075526.58     13884428.83
      2075515.35     13884435.84      2075488.04     13884460.95
      2075477.17     13884468.86      2075465.13     13884473.13
      2075430.62     13884477.63      2075418.94     13884483.18
      2075401.53     13884498.12      2075341.65     13884558.77
      2075331.66     13884566.02      2075325.00     13884567.91
      2075318.34     13884566.02      2075308.35     13884558.78
      2075245.16     13884494.71      2075234.82     13884485.49
      2075223.60     13884478.41      2075214.66     13884475.83
      2075200.25     13884474.41      2075125.00     13884475.00

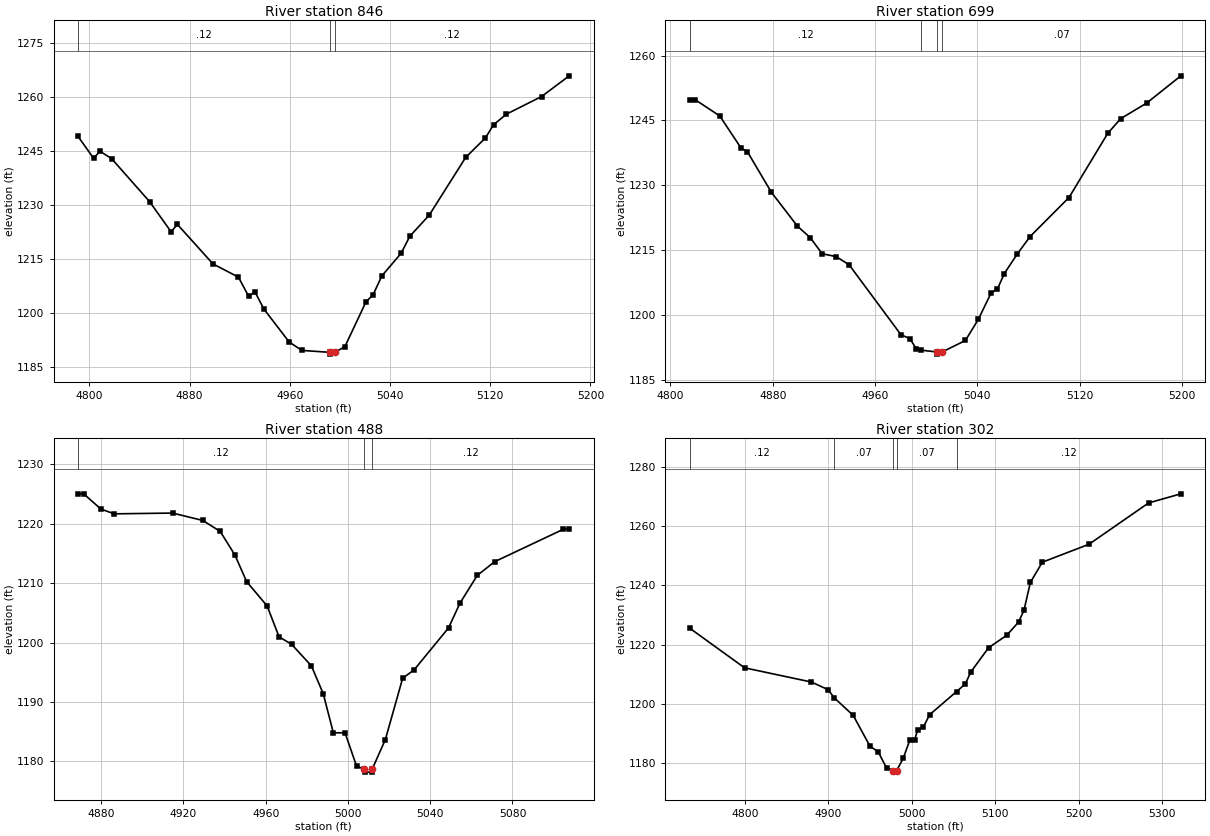
Type RM Length L Ch R = 1,846,147,147,147
BEGIN DESCRIPTION:
Stream0079_DS 3.0
END DESCRIPTION:
XS GIS Cut Line= 3
      2075902.11     13884168.65      2075868.91     13884375.00
      2075950.14     13884539.09
#Sta/Elev= 30
  4791.0 1249.09  4803.4 1243.00  4808.4 1244.99  4817.7 1242.96  4848.1 1230.97
  4865.2 1222.62  4870.3 1224.64  4898.7 1213.67  4919.0 1210.00  4927.1 1204.70
  4932.2 1205.91  4939.2 1201.20  4959.5 1191.99  4969.6 1189.64  4992.0 1189.11
  4992.3 1188.61  4996.0 1189.11  5004.0 1190.69  5020.9 1203.20  5026.4 1205.02
  5033.5 1210.35  5048.9 1216.64  5055.8 1221.35  5071.3 1227.22  5100.4 1243.26
  5116.2 1248.70  5122.7 1252.36  5133.0 1255.30  5161.0 1260.19  5183.1 1265.94
#Mann=3,-1,0
  4791.0    0.12       0  4992.0    0.05       0  4996.0    0.12       0
Bank Sta=4992,4996
Exp/Cntr=0.3,0.1

Type RM Length L Ch R = 1,699,211,211,211
BEGIN DESCRIPTION:
Stream0079_DS 2.0
END DESCRIPTION:
XS GIS Cut Line= 2
      2075693.75     13884191.81      2075751.64     13884571.53
#Sta/Elev= 30
  4815.1 1249.80  4819.3 1249.80  4838.6 1246.04  4855.2 1238.64  4860.2 1237.77
  4879.0 1228.38  4899.2 1220.62  4909.4 1217.89  4918.7 1214.19  4929.6 1213.53
  4939.7 1211.66  4980.2 1195.51  4987.3 1194.55  4992.3 1192.24  4996.1 1191.90
  5008.5 1191.49  5008.8 1190.99  5012.5 1191.49  5030.7 1194.14  5040.9 1199.07
  5050.8 1205.13  5055.8 1206.06  5061.1 1209.60  5071.2 1214.10  5081.3 1218.17
  5111.7 1227.18  5142.0 1242.00  5152.1 1245.41  5172.4 1249.00  5199.2 1255.31
#Mann=4,-1,0
  4815.1    0.12       0  4996.1    0.07       0  5008.5    0.05       0
  5012.5    0.07       0
Bank Sta=5008.5,5012.5
Exp/Cntr=0.3,0.1

Type RM Length L Ch R = 1,488,186,186,186
BEGIN DESCRIPTION:
Stream0079_DS 1.0
END DESCRIPTION:
XS GIS Cut Line= 3
      2075460.75     13884315.41      2075525.00     13884425.00
      2075574.98     13884524.97
#Sta/Elev= 30
  4868.8 1225.04  4871.5 1225.04  4879.9 1222.47  4886.4 1221.67  4914.7 1221.80
  4929.4 1220.56  4937.9 1218.71  4945.0 1214.76  4950.8 1210.23  4960.7 1206.17
  4966.5 1200.97  4972.6 1199.70  4982.2 1196.09  4988.0 1191.38  4992.9 1184.80
  4998.6 1184.80  5004.2 1179.18  5007.8 1178.68  5008.1 1178.18  5011.6 1178.18
  5011.8 1178.68  5018.2 1183.67  5026.6 1193.99  5032.2 1195.41  5048.9 1202.46
  5054.5 1206.65  5062.9 1211.31  5071.3 1213.61  5104.8 1219.08  5107.6 1219.08
#Mann=3,-1,0
  4868.8    0.12       0  5007.8    0.05       0  5011.8    0.12       0
Bank Sta=5007.8,5011.8
Exp/Cntr=0.3,0.1

Type RM Length L Ch R = 1,302,0,0,0
BEGIN DESCRIPTION:
Stream0079_DS 0.1
END DESCRIPTION:
XS GIS Cut Line= 3
      2075389.20     13884259.41      2075375.00     13884525.00
      2075584.60     13884770.02
#Sta/Elev= 30
  4733.9 1225.55  4799.6 1212.18  4879.7 1207.38  4899.7 1204.80  4906.9 1202.09
  4929.8 1196.12  4949.8 1185.76  4959.8 1183.79  4969.8 1178.32  4977.8 1177.48
  4978.1 1176.98  4981.8 1177.48  4989.8 1181.73  4997.4 1187.66  5003.2 1187.66
  5007.0 1191.33  5013.6 1192.07  5021.3 1196.35  5053.6 1204.17  5064.1 1206.75
  5070.7 1210.79  5092.0 1218.97  5113.5 1223.11  5127.8 1227.59  5134.3 1231.54
  5142.0 1240.98  5156.3 1247.81  5212.3 1253.88  5283.6 1267.81  5322.3 1270.89
#Mann=5,-1,0
  4733.9    0.12       0  4906.9    0.07       0  4977.8    0.05       0
  4981.8    0.07       0  5053.6    0.12       0
Bank Sta=4977.8,4981.8
Exp/Cntr=0.3,0.1

Chan Stop Cuts=-1