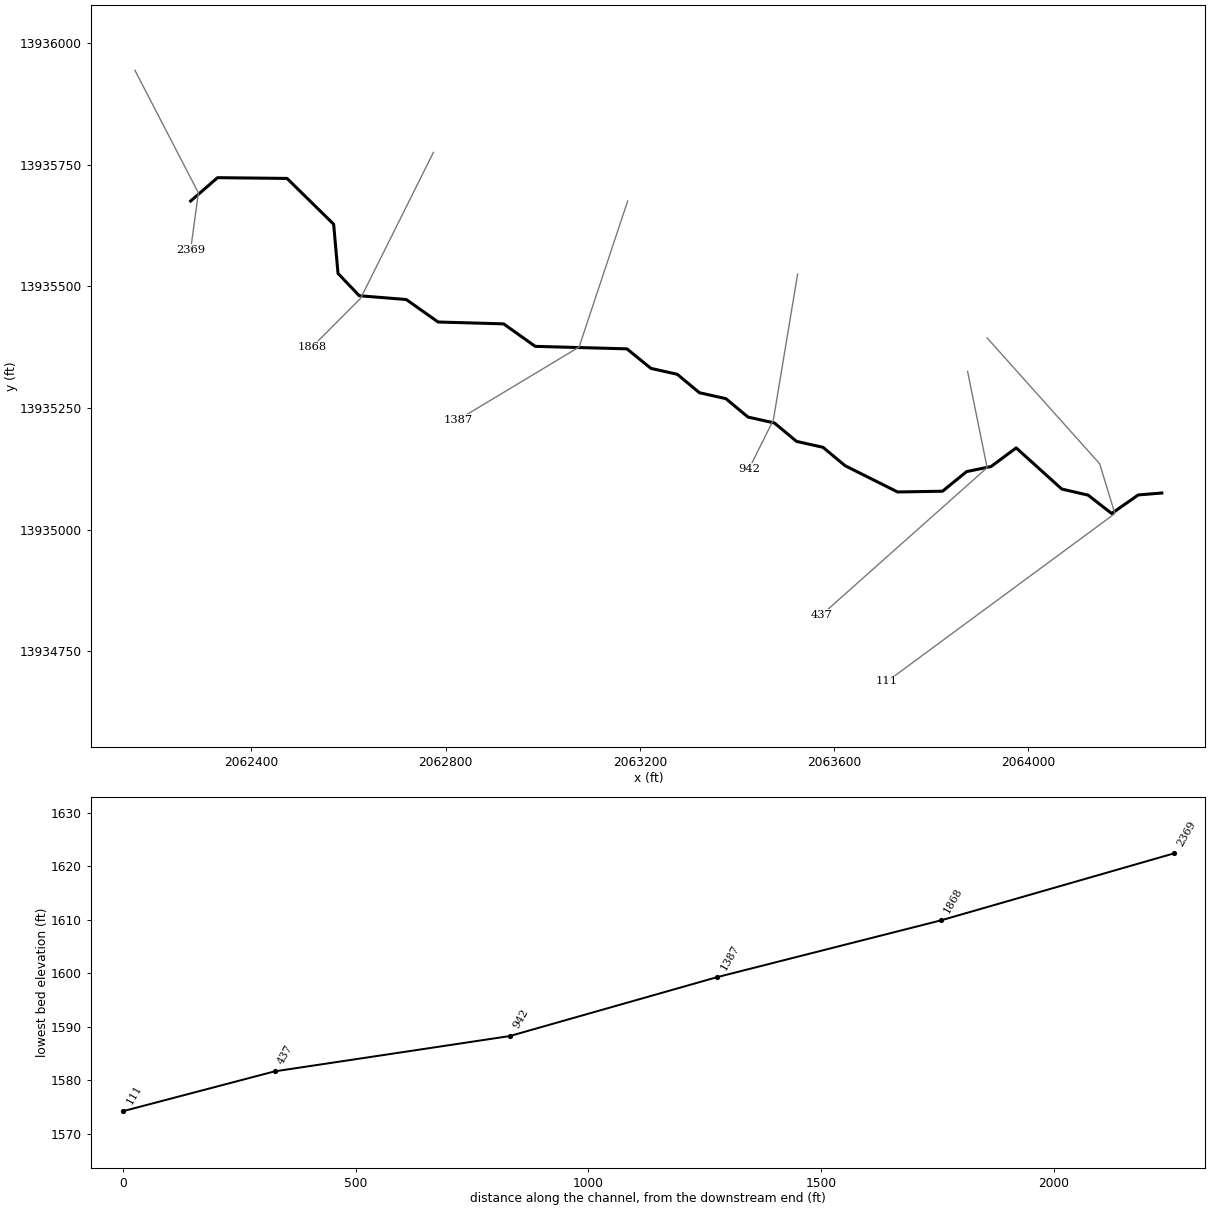
--- Stream0080_DS.prj (project) ---

Proj Title=Stream0080_DS Base Level Engineering
Current Plan=p01
Default Exp/Contr=0.3,0.1
English Units
Geom File=g01
Flow File=f01
Plan File=p01
BEGIN DESCRIPTION:
Stream0080_DS
END DESCRIPTION:

--- Stream0080_DS.p01 (plan) ---

Plan Title=Multiple Run
Short Identifier=Multiple
Geom File=g01
Flow File=f01
Subcritical Flow
K Sum by GR= 0
Std Step Tol= 0.01
Critical Tol= 0.01
Num of Std Step Trials= 20
Max Error Tol= 0.3
Flow Tol Ratio= 0.001
Split Flow NTrial= 30
Split Flow Tol= 0.02
Split Flow Ratio= 0.02
Log Output Level= 0
Friction Slope Method= 1
Unsteady Friction Slope Method= 2
Unsteady Bridges Friction Slope Method= 1
Parabolic Critical Depth
Global Vel Dist=  1 , 1 , 1
Global Log Level= 0
CheckData=True
Encroach Param= -1, 0, 0, 0
BEGIN DESCRIPTION:
Multiple Run
END DESCRIPTION:

--- Stream0080_DS.f01 (steady flow) ---

Flow Title=Multiple
Number of Profiles=7
Profile Names=10-year,25-year,50-year,1pct_min,100-year,1pct_plu,500-year
River Rch & RM= Stream0080_DS,Reach-1,2369
     589     985    1359     914    1824    3638    3246
River Rch & RM= Stream0080_DS,Reach-1,1868
     662    1112    1539    1036    2067    4125    3694
Boundary for River Rch & Prof#=Stream0080_DS,Reach-1,1
Up Type=0
Dn Type=3
Dn Slope=0.005
Boundary for River Rch & Prof#=Stream0080_DS,Reach-1,2
Up Type=0
Dn Type=3
Dn Slope=0.005
Boundary for River Rch & Prof#=Stream0080_DS,Reach-1,3
Up Type=0
Dn Type=3
Dn Slope=0.005
Boundary for River Rch & Prof#=Stream0080_DS,Reach-1,4
Up Type=0
Dn Type=3
Dn Slope=0.005
Boundary for River Rch & Prof#=Stream0080_DS,Reach-1,5
Up Type=0
Dn Type=3
Dn Slope=0.005
Boundary for River Rch & Prof#=Stream0080_DS,Reach-1,6
Up Type=0
Dn Type=3
Dn Slope=0.005
Boundary for River Rch & Prof#=Stream0080_DS,Reach-1,7
Up Type=0
Dn Type=3
Dn Slope=0.005

--- Stream0080_DS.g01 (geometry) ---

Geom Title=Existing Conditions

River Reach=Stream0080_DS,Reach-1
Reach XY= 30
      2062275.00     13935675.00      2062330.38     13935723.02
      2062473.55     13935721.48      2062569.48     13935627.44
      2062578.51     13935526.25      2062622.29     13935480.40
      2062719.02     13935472.64      2062784.67     13935426.39
      2062919.47     13935422.61      2062984.66     13935376.38
      2063173.45     13935371.25      2063222.82     13935331.12
      2063277.20     13935318.92      2063322.80     13935281.08
      2063377.20     13935268.92      2063422.80     13935231.08
      2063477.20     13935218.92      2063522.80     13935181.08
      2063577.20     13935168.92      2063622.80     13935131.08
      2063730.97     13935077.14      2063823.42     13935078.67
      2063872.83     13935118.91      2063923.37     13935129.43
      2063975.08     13935167.70      2064068.95     13935083.16
      2064123.35     13935070.56      2064171.72     13935032.85
      2064226.36     13935071.00      2064275.00     13935075.00

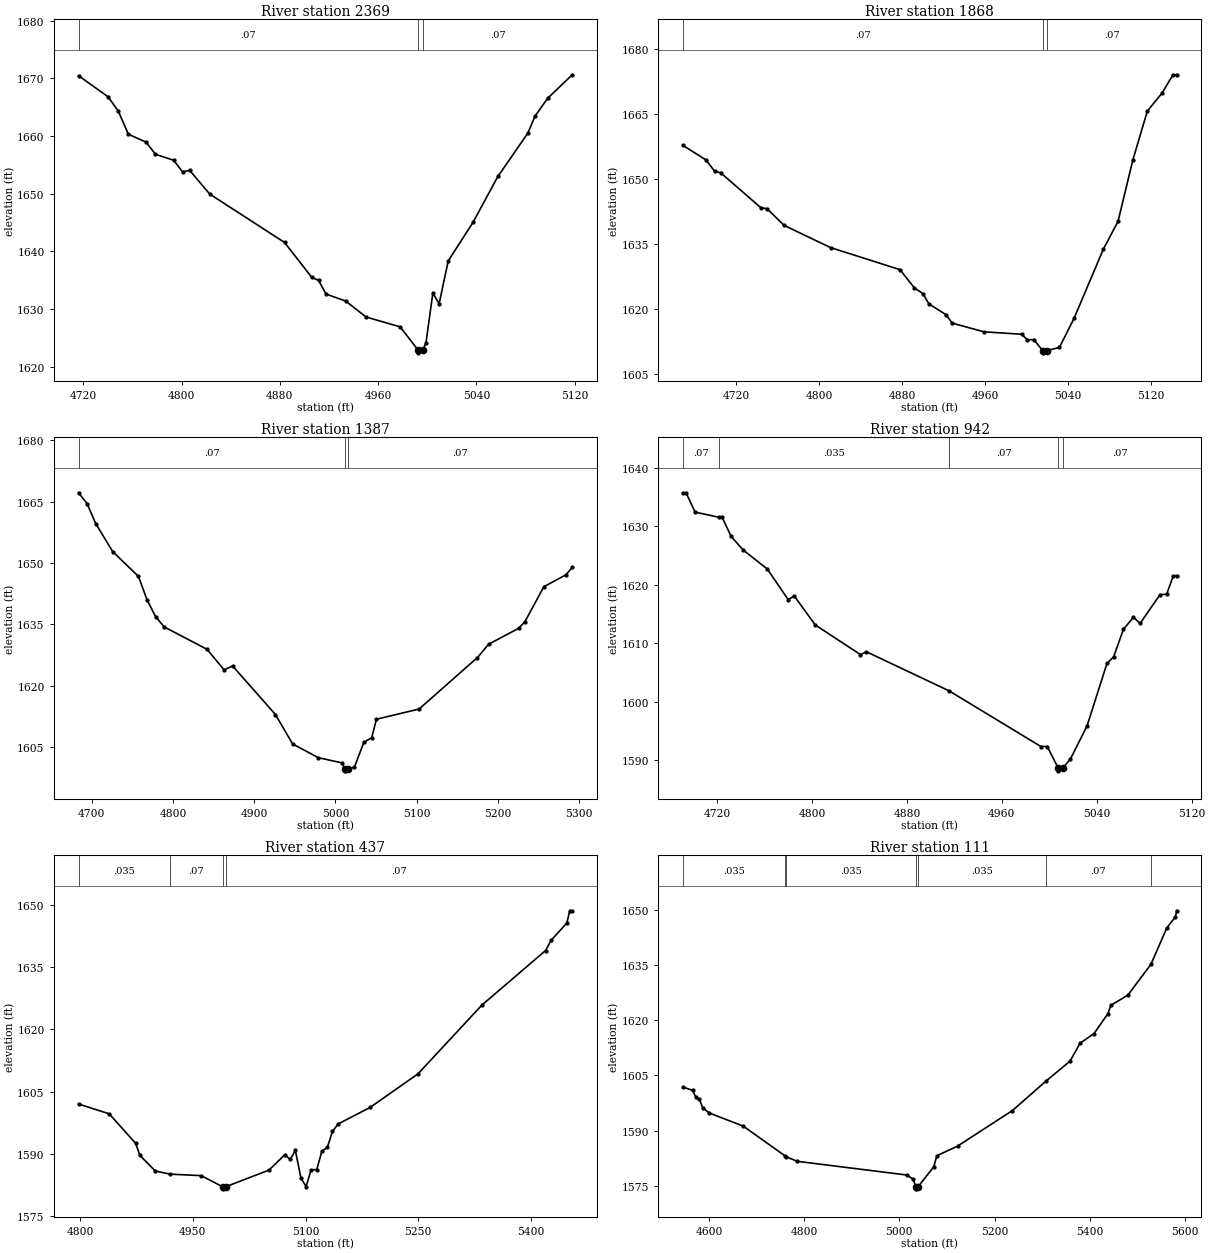
Type RM Length L Ch R = 1,2369,501,501,501
BEGIN DESCRIPTION:
Stream0080_DS 5.0
END DESCRIPTION:
XS GIS Cut Line= 3
      2062160.20     13935943.73      2062290.97     13935691.85
      2062275.00     13935575.04
#Sta/Elev= 30
  4716.2 1670.44  4740.2 1666.79  4748.6 1664.28  4756.7 1660.29  4771.1 1658.92
  4778.8 1656.81  4793.6 1655.77  4800.9 1653.75  4806.6 1654.03  4823.0 1649.90
  4883.8 1641.52  4905.9 1635.48  4911.5 1634.93  4917.6 1632.56  4933.6 1631.35
  4950.1 1628.59  4977.9 1626.88  4992.4 1622.87  4992.6 1622.37  4996.4 1622.87
  4998.9 1624.08  5004.5 1632.74  5009.6 1630.88  5017.0 1638.31  5037.2 1645.01
  5057.4 1652.96  5081.8 1660.48  5087.7 1663.45  5097.8 1666.49  5117.9 1670.60
#Mann=3,-1,0
  4716.2    0.07       0  4992.4    0.05       0  4996.4    0.07       0
Bank Sta=4992.4,4996.4
Exp/Cntr=0.3,0.1

Type RM Length L Ch R = 1,1868,481,481,481
BEGIN DESCRIPTION:
Stream0080_DS 4.0
END DESCRIPTION:
XS GIS Cut Line= 3
      2062774.98     13935774.96      2062625.00     13935475.00
      2062524.99     13935374.99
#Sta/Elev= 30
  4668.4 1657.70  4690.7 1654.33  4699.1 1651.69  4704.7 1651.41  4743.8 1643.28
  4749.4 1643.13  4766.2 1639.23  4810.9 1634.13  4878.0 1629.03  4892.0 1624.79
  4900.3 1623.48  4905.9 1621.13  4922.7 1618.61  4928.3 1616.71  4959.0 1614.69
  4995.4 1614.13  5001.0 1612.87  5007.3 1612.87  5015.9 1610.34  5016.2 1609.84
  5019.9 1610.34  5032.0 1611.10  5046.2 1617.84  5074.5 1633.80  5088.6 1640.16
  5102.8 1654.24  5116.9 1665.62  5131.0 1669.73  5141.7 1673.99  5145.2 1673.99
#Mann=3,-1,0
  4668.4    0.07       0  5015.9    0.05       0  5019.9    0.07       0
Bank Sta=5015.9,5019.9
Exp/Cntr=0.3,0.1

Type RM Length L Ch R = 1,1387,445,445,445
BEGIN DESCRIPTION:
Stream0080_DS 3.0
END DESCRIPTION:
XS GIS Cut Line= 3
      2063174.99     13935674.97      2063075.00     13935375.00
      2062825.04     13935225.02
#Sta/Elev= 30
  4683.8 1667.18  4694.3 1664.54  4704.9 1659.67  4725.9 1652.79  4757.6 1646.73
  4768.1 1641.02  4778.6 1636.92  4789.2 1634.40  4841.9 1628.93  4863.0 1623.90
  4873.5 1624.84  4926.2 1612.98  4947.3 1605.80  4978.9 1602.44  5007.8 1601.18
  5011.6 1599.72  5011.9 1599.22  5015.6 1599.72  5023.3 1600.09  5035.0 1606.18
  5044.7 1607.34  5050.5 1611.83  5103.0 1614.33  5174.9 1626.92  5188.5 1630.15
  5225.5 1634.05  5233.2 1635.65  5256.6 1644.22  5283.8 1647.14  5291.5 1648.94
#Mann=3,-1,0
  4683.8    0.07       0  5011.6    0.05       0  5015.6    0.07       0
Bank Sta=5011.6,5015.6
Exp/Cntr=0.3,0.1

Type RM Length L Ch R = 1,942,505,505,505
BEGIN DESCRIPTION:
Stream0080_DS 2.0
END DESCRIPTION:
XS GIS Cut Line= 3
      2063525.00     13935525.02      2063475.00     13935225.00
      2063424.98     13935124.97
#Sta/Elev= 30
  4691.3 1635.76  4693.9 1635.76  4701.5 1632.46  4722.0 1631.55  4724.3 1631.55
  4731.9 1628.30  4742.0 1625.98  4762.3 1622.74  4780.0 1617.49  4785.1 1618.11
  4802.8 1613.16  4840.9 1608.09  4845.9 1608.58  4915.7 1601.88  4992.9 1592.38
  4998.3 1592.38  5007.4 1588.72  5007.7 1588.22  5011.4 1588.72  5017.8 1590.24
  5031.8 1595.90  5048.6 1606.59  5054.2 1607.70  5062.5 1612.44  5070.9 1614.47
  5076.5 1613.43  5093.3 1618.34  5098.9 1618.42  5104.5 1621.58  5107.3 1621.58
#Mann=5,-1,0
  4691.3    0.07       0  4722.0   0.035       0  4915.7    0.07       0
  5007.4    0.05       0  5011.4    0.07       0
Bank Sta=5007.4,5011.4
Exp/Cntr=0.3,0.1

Type RM Length L Ch R = 1,437,326,326,326
BEGIN DESCRIPTION:
Stream0080_DS 1.0
END DESCRIPTION:
XS GIS Cut Line= 3
      2063875.01     13935324.96      2063915.22     13935127.01
      2063575.02     13934825.02
#Sta/Elev= 30
  4798.0 1602.02  4838.8 1599.67  4873.9 1592.59  4879.6 1589.68  4900.0 1585.92
  4919.9 1585.15  4961.2 1584.80  4989.8 1582.12  4990.1 1581.62  4993.8 1582.12
  5051.4 1586.13  5072.3 1589.78  5079.9 1588.72  5086.5 1590.88  5093.9 1584.22
  5100.8 1582.16  5107.4 1586.17  5115.0 1586.26  5121.7 1590.63  5129.2 1591.64
  5135.9 1595.44  5143.4 1597.22  5186.1 1601.22  5249.6 1609.27  5334.6 1625.80
  5419.4 1638.94  5426.9 1641.42  5447.8 1645.58  5451.6 1648.51  5454.9 1648.51
#Mann=4,-1,0
  4798.0   0.035       0  4919.9    0.07       0  4989.8    0.05       0
  4993.8    0.07       0
Bank Sta=4989.8,4993.8
Exp/Cntr=0.3,0.1

Type RM Length L Ch R = 1,111,0,0,0
BEGIN DESCRIPTION:
Stream0080_DS 0.0
END DESCRIPTION:
XS GIS Cut Line= 4
      2063915.10     13935393.85      2064146.99     13935135.07
      2064178.34     13935032.74      2063709.22     13934687.77
#Sta/Elev= 30
  4545.5 1601.85  4566.0 1600.91  4572.7 1599.03  4580.2 1598.48  4586.9 1596.20
  4601.1 1594.76  4672.1 1591.22  4760.1 1583.11  4762.1 1582.89  4785.7 1581.65
  5015.9 1577.92  5029.0 1576.78  5034.8 1574.67  5035.0 1574.17  5038.8 1574.67
  5072.3 1580.17  5078.6 1583.15  5122.4 1585.80  5237.4 1595.45  5307.7 1603.43
  5358.5 1608.89  5379.4 1613.74  5408.7 1616.37  5437.9 1621.77  5444.1 1624.06
  5479.6 1626.79  5528.2 1635.16  5561.7 1645.11  5579.9 1648.13  5582.3 1649.75
#Mann=7,-1,0
  4545.5   0.035       0  4760.1    0.07       0  4762.1   0.035       0
  5034.8   0.035       0  5038.8   0.035       0  5307.7    0.07       0
  5528.2   0.035       0
Bank Sta=5034.8,5038.8
Exp/Cntr=0.3,0.1

Chan Stop Cuts=-1