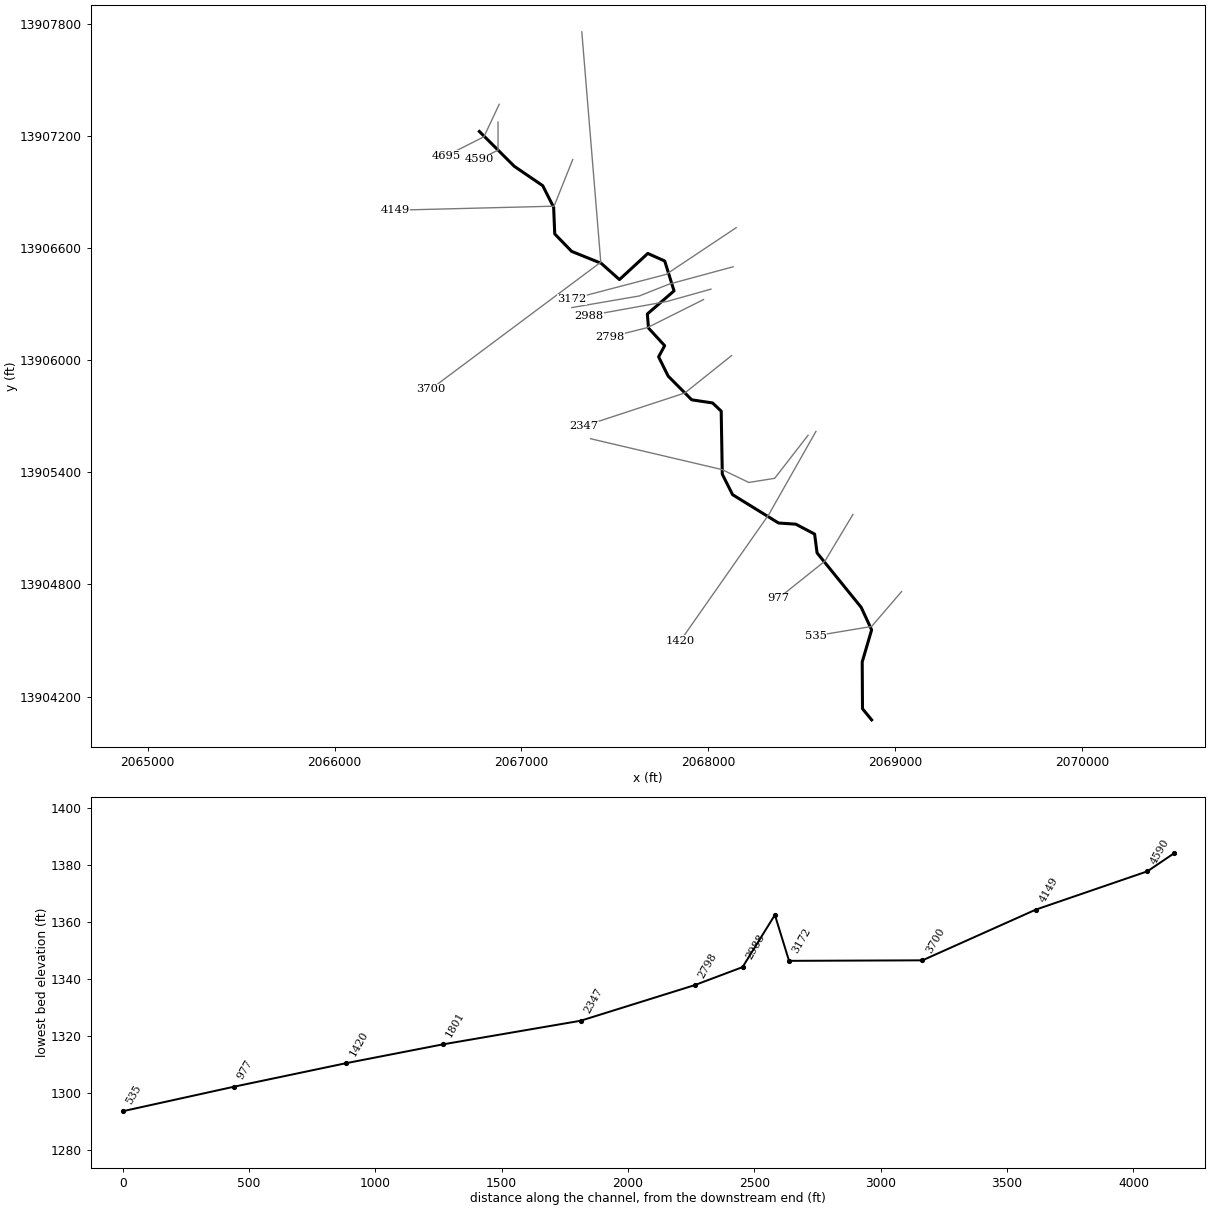
--- Stream0081_DS.prj (project) ---

Proj Title=Stream0081_DS Base Level Engineering
Current Plan=p01
Default Exp/Contr=0.3,0.1
English Units
Geom File=g01
Flow File=f01
Plan File=p01
BEGIN DESCRIPTION:
Stream0081_DS
END DESCRIPTION:

--- Stream0081_DS.p01 (plan) ---

Plan Title=Multiple Run
Short Identifier=Multiple
Geom File=g01
Flow File=f01
Subcritical Flow
K Sum by GR= 0
Std Step Tol= 0.01
Critical Tol= 0.01
Num of Std Step Trials= 20
Max Error Tol= 0.3
Flow Tol Ratio= 0.001
Split Flow NTrial= 30
Split Flow Tol= 0.02
Split Flow Ratio= 0.02
Log Output Level= 0
Friction Slope Method= 1
Unsteady Friction Slope Method= 2
Unsteady Bridges Friction Slope Method= 1
Parabolic Critical Depth
Global Vel Dist=  1 , 1 , 1
Global Log Level= 0
CheckData=True
Encroach Param= -1, 0, 0, 0
BEGIN DESCRIPTION:
Multiple Run
END DESCRIPTION:

--- Stream0081_DS.f01 (steady flow) ---

Flow Title=Multiple
Number of Profiles=7
Profile Names=10-year,25-year,50-year,1pct_min,100-year,1pct_plu,500-year
River Rch & RM= Stream0081_DS,Reach-1,4695
     333     524     694     448     895    1785    1464
River Rch & RM= Stream0081_DS,Reach-1,3700
     823    1374    1891    1264    2523    5034    4434
Boundary for River Rch & Prof#=Stream0081_DS,Reach-1,1
Up Type=0
Dn Type=3
Dn Slope=0.005
Boundary for River Rch & Prof#=Stream0081_DS,Reach-1,2
Up Type=0
Dn Type=3
Dn Slope=0.005
Boundary for River Rch & Prof#=Stream0081_DS,Reach-1,3
Up Type=0
Dn Type=3
Dn Slope=0.005
Boundary for River Rch & Prof#=Stream0081_DS,Reach-1,4
Up Type=0
Dn Type=3
Dn Slope=0.005
Boundary for River Rch & Prof#=Stream0081_DS,Reach-1,5
Up Type=0
Dn Type=3
Dn Slope=0.005
Boundary for River Rch & Prof#=Stream0081_DS,Reach-1,6
Up Type=0
Dn Type=3
Dn Slope=0.005
Boundary for River Rch & Prof#=Stream0081_DS,Reach-1,7
Up Type=0
Dn Type=3
Dn Slope=0.005

--- Stream0081_DS.g01 (geometry) ---

Geom Title=Existing Conditions

River Reach=Stream0081_DS,Reach-1
Reach XY= 30
      2066775.00     13907225.00      2066961.79     13907038.63
      2067114.25     13906934.71      2067172.64     13906819.48
      2067178.54     13906676.46      2067268.93     13906583.13
      2067427.30     13906519.14      2067525.00     13906432.08
      2067676.68     13906571.92      2067767.26     13906531.55
      2067817.21     13906371.57      2067674.33     13906247.96
      2067680.40     13906172.63      2067766.99     13906078.33
      2067734.59     13906018.45      2067785.75     13905915.32
      2067911.70     13905788.40      2068023.75     13905771.49
      2068069.66     13905727.74      2068075.50     13905390.20
      2068130.59     13905280.61      2068376.58     13905128.83
      2068469.06     13905122.68      2068569.75     13905069.56
      2068582.90     13904968.88      2068819.17     13904677.30
      2068874.96     13904556.67      2068824.55     13904385.19
      2068826.10     13904134.55      2068875.00     13904075.00

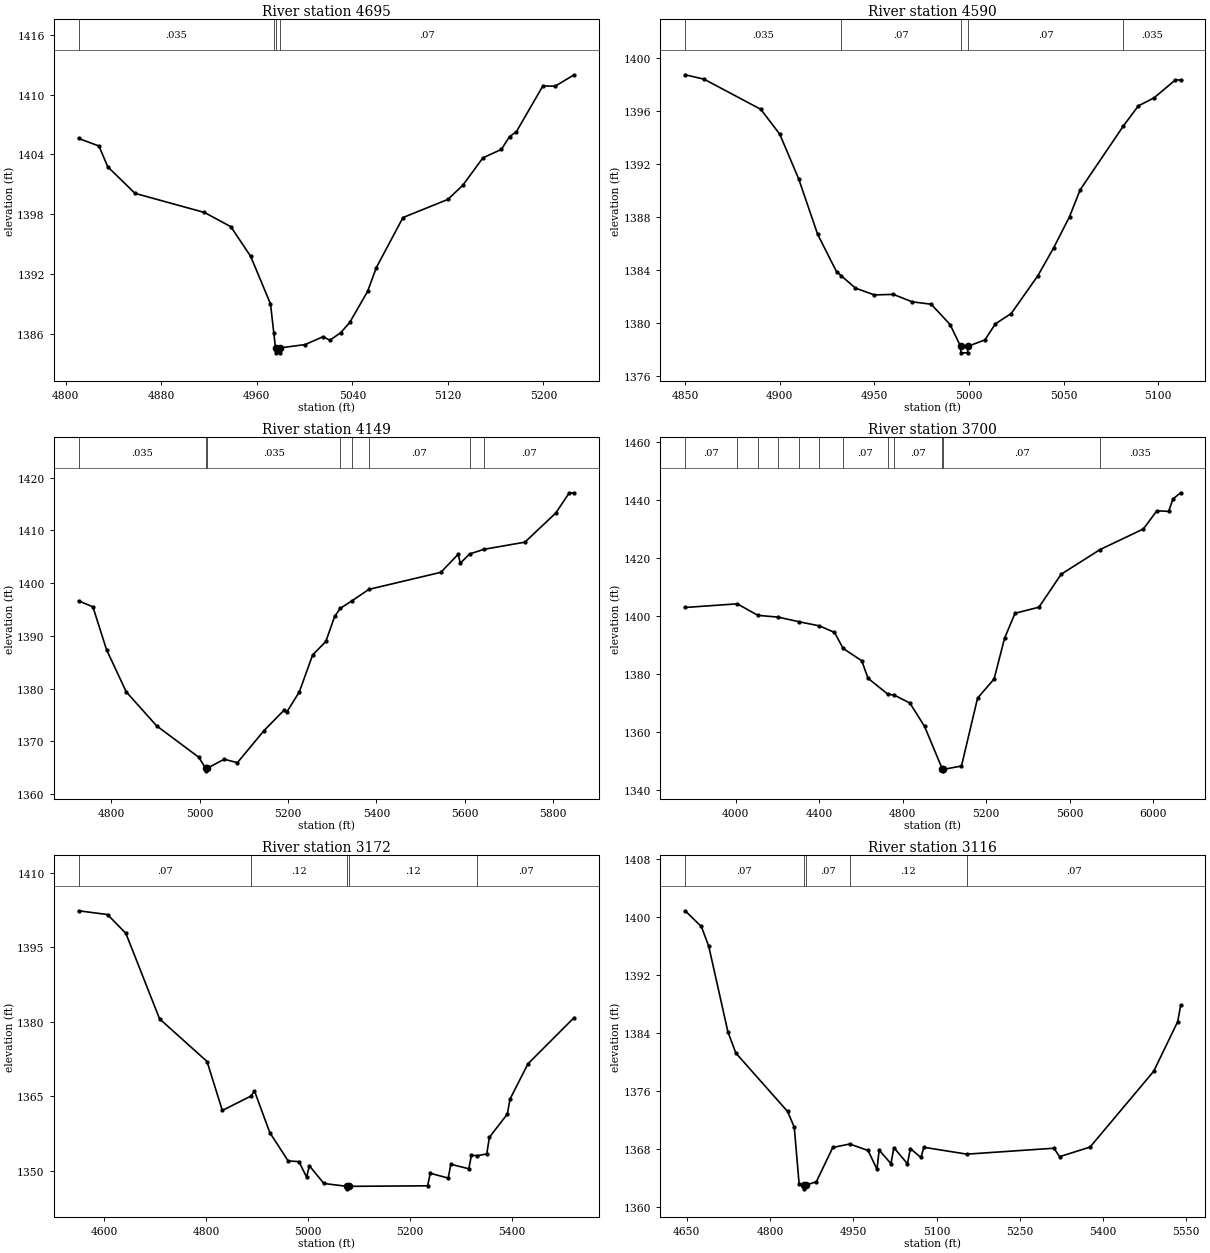
Type RM Length L Ch R = 1,4695,105,105,105
BEGIN DESCRIPTION:
Stream0081_DS 11.0
END DESCRIPTION:
XS GIS Cut Line= 3
      2066881.17     13907370.36      2066799.61     13907196.65
      2066600.69     13907096.08
#Sta/Elev= 30
  4810.9 1405.61  4827.9 1404.85  4835.3 1402.76  4858.1 1400.09  4916.2 1398.17
  4938.3 1396.74  4954.9 1393.76  4971.5 1388.98  4974.3 1386.03  4975.7 1384.56
  4975.9 1384.06  4979.4 1384.06  4979.7 1384.56  5000.5 1384.89  5015.6 1385.69
  5021.2 1385.32  5030.4 1386.10  5037.8 1387.11  5052.8 1390.24  5060.1 1392.63
  5082.4 1397.66  5120.0 1399.48  5132.6 1400.92  5149.3 1403.66  5164.8 1404.51
  5171.6 1405.80  5177.2 1406.26  5199.5 1410.89  5209.7 1410.86  5225.7 1412.01
#Mann=4,-1,0
  4810.9   0.035       0  4974.3    0.07       0  4975.7    0.05       0
  4979.7    0.07       0
Bank Sta=4975.7,4979.7
Exp/Cntr=0.3,0.1

Type RM Length L Ch R = 1,4590,441,441,441
BEGIN DESCRIPTION:
Stream0081_DS 10.0
END DESCRIPTION:
XS GIS Cut Line= 3
      2066875.00     13907274.97      2066875.00     13907125.00
      2066774.98     13907074.99
#Sta/Elev= 30
  4850.0 1398.71  4860.0 1398.38  4890.0 1396.11  4900.0 1394.24  4910.0 1390.88
  4920.0 1386.71  4930.0 1383.89  4932.5 1383.58  4940.0 1382.65  4950.0 1382.14
  4960.0 1382.18  4970.0 1381.62  4980.0 1381.44  4990.0 1379.91  4995.5 1378.28
  4995.7 1377.78  4999.2 1377.78  4999.5 1378.28  5008.4 1378.75  5013.9 1379.96
  5022.3 1380.74  5036.3 1383.57  5044.7 1385.68  5053.1 1388.03  5058.7 1390.05
  5081.6 1394.87  5089.4 1396.36  5097.8 1396.98  5109.0 1398.32  5111.8 1398.32
#Mann=5,-1,0
  4850.0   0.035       0  4932.5    0.07       0  4995.5    0.05       0
  4999.5    0.07       0  5081.6   0.035       0
Bank Sta=4995.5,4999.5
Exp/Cntr=0.3,0.1

Type RM Length L Ch R = 1,4149,449,449,449
BEGIN DESCRIPTION:
Stream0081_DS 9.0
END DESCRIPTION:
XS GIS Cut Line= 3
      2067274.99     13907074.96      2067175.00     13906825.00
      2066323.49     13906803.47
#Sta/Elev= 30
  4726.3 1396.63  4758.6 1395.49  4789.5 1387.35  4834.0 1379.37  4902.6 1372.93
  4998.0 1366.96  5013.5 1364.88  5013.8 1364.38  5017.5 1364.88  5055.5 1366.58
  5085.5 1365.93  5145.6 1372.01  5191.9 1375.97  5196.9 1375.49  5225.6 1379.37
  5255.6 1386.36  5285.6 1388.93  5305.6 1393.71  5318.4 1395.22  5344.2 1396.62
  5382.8 1398.81  5545.7 1402.05  5584.8 1405.46  5589.8 1403.77  5610.7 1405.53
  5643.2 1406.41  5735.8 1407.77  5805.8 1413.31  5835.8 1417.08  5847.3 1417.14
#Mann=8,-1,0
  4726.3   0.035       0  5013.5   0.035       0  5017.5   0.035       0
  5318.4    0.07       0  5344.2   0.035       0  5382.8    0.07       0
  5610.7   0.035       0  5643.2    0.07       0
Bank Sta=5013.5,5017.5
Exp/Cntr=0.3,0.1

Type RM Length L Ch R = 1,3700,528,528,528
BEGIN DESCRIPTION:
Stream0081_DS 8.0
END DESCRIPTION:
XS GIS Cut Line= 3
      2067323.45     13907758.30      2067425.00     13906525.00
      2066514.39     13905845.11
#Sta/Elev= 30
  3757.3 1402.90  4007.2 1404.16  4105.7 1400.19  4204.1 1399.57  4302.6 1397.99
  4401.0 1396.55  4473.0 1394.31  4514.5 1388.78  4603.5 1384.53  4633.6 1378.51
  4727.8 1373.06  4759.2 1372.69  4834.2 1369.96  4904.5 1361.90  4990.3 1347.10
  4990.5 1346.60  4994.3 1347.10  5081.3 1348.26  5158.4 1371.66  5237.6 1378.26
  5287.7 1392.29  5337.7 1400.90  5452.4 1403.00  5558.7 1414.35  5745.5 1422.87
  5952.7 1429.96  6017.3 1436.23  6073.6 1436.01  6094.4 1440.30  6131.2 1442.43
#Mann=12,-1,0
  3757.3    0.07       0  4007.2   0.035       0  4105.7    0.07       0
  4204.1   0.035       0  4302.6    0.07       0  4401.0   0.035       0
  4514.5    0.07       0  4727.8   0.035       0  4759.2    0.07       0
  4990.3    0.05       0  4994.3    0.07       0  5745.5   0.035       0
Bank Sta=4990.3,4994.3
Exp/Cntr=0.3,0.1

Type RM Length L Ch R = 1,3172,56,56,56
BEGIN DESCRIPTION:
Stream0081_DS 7.0
END DESCRIPTION:
XS GIS Cut Line= 3
      2068149.84     13906709.72      2067774.93     13906459.94
      2067269.65     13906327.69
#Sta/Elev= 30
  4549.5 1402.35  4606.2 1401.59  4642.3 1397.80  4708.4 1380.61  4801.6 1372.03
  4831.6 1362.18  4888.1 1365.10  4894.7 1366.10  4924.8 1357.73  4960.8 1352.03
  4981.9 1351.90  4996.9 1348.81  5002.6 1351.05  5030.9 1347.50  5076.1 1346.92
  5076.3 1346.42  5080.1 1346.92  5234.6 1347.03  5239.8 1349.55  5275.0 1348.58
  5280.2 1351.36  5315.5 1350.46  5320.6 1353.18  5332.3 1353.08  5350.7 1353.45
  5355.9 1356.80  5391.1 1361.46  5396.3 1364.46  5431.6 1371.57  5522.3 1380.87
#Mann=5,-1,0
  4549.5    0.07       0  4888.1    0.12       0  5076.1    0.05       0
  5080.1    0.12       0  5332.3    0.07       0
Bank Sta=5076.1,5080.1
Exp/Cntr=0.3,0.1

Type RM Length L Ch R = 1,3116,128,128,128
BEGIN DESCRIPTION:
Stream0081_DS 6.1
END DESCRIPTION:
XS GIS Cut Line= 4
      2068133.32     13906500.51      2067792.39     13906408.25
      2067631.25     13906344.41      2067269.79     13906282.15
#Sta/Elev= 30
  4646.8 1400.90  4676.1 1398.73  4689.4 1396.01  4724.0 1384.17  4738.3 1381.25
  4831.5 1373.19  4843.6 1371.01  4852.3 1363.21  4860.6 1363.00  4860.9 1362.50
  4864.6 1363.00  4883.5 1363.49  4913.0 1368.21  4943.5 1368.69  4976.6 1367.80
  4992.7 1365.20  4996.6 1367.85  5017.9 1365.98  5023.2 1368.19  5047.6 1365.96
  5052.9 1368.06  5071.9 1366.83  5077.3 1368.24  5154.7 1367.29  5311.6 1368.11
  5322.0 1366.94  5376.8 1368.27  5491.5 1378.73  5534.8 1385.59  5540.1 1387.82
#Mann=5,-1,0
  4646.8    0.07       0  4860.6    0.05       0  4864.6    0.07       0
  4943.5    0.12       0  5154.7    0.07       0
Bank Sta=4860.6,4864.6
Exp/Cntr=0.3,0.1

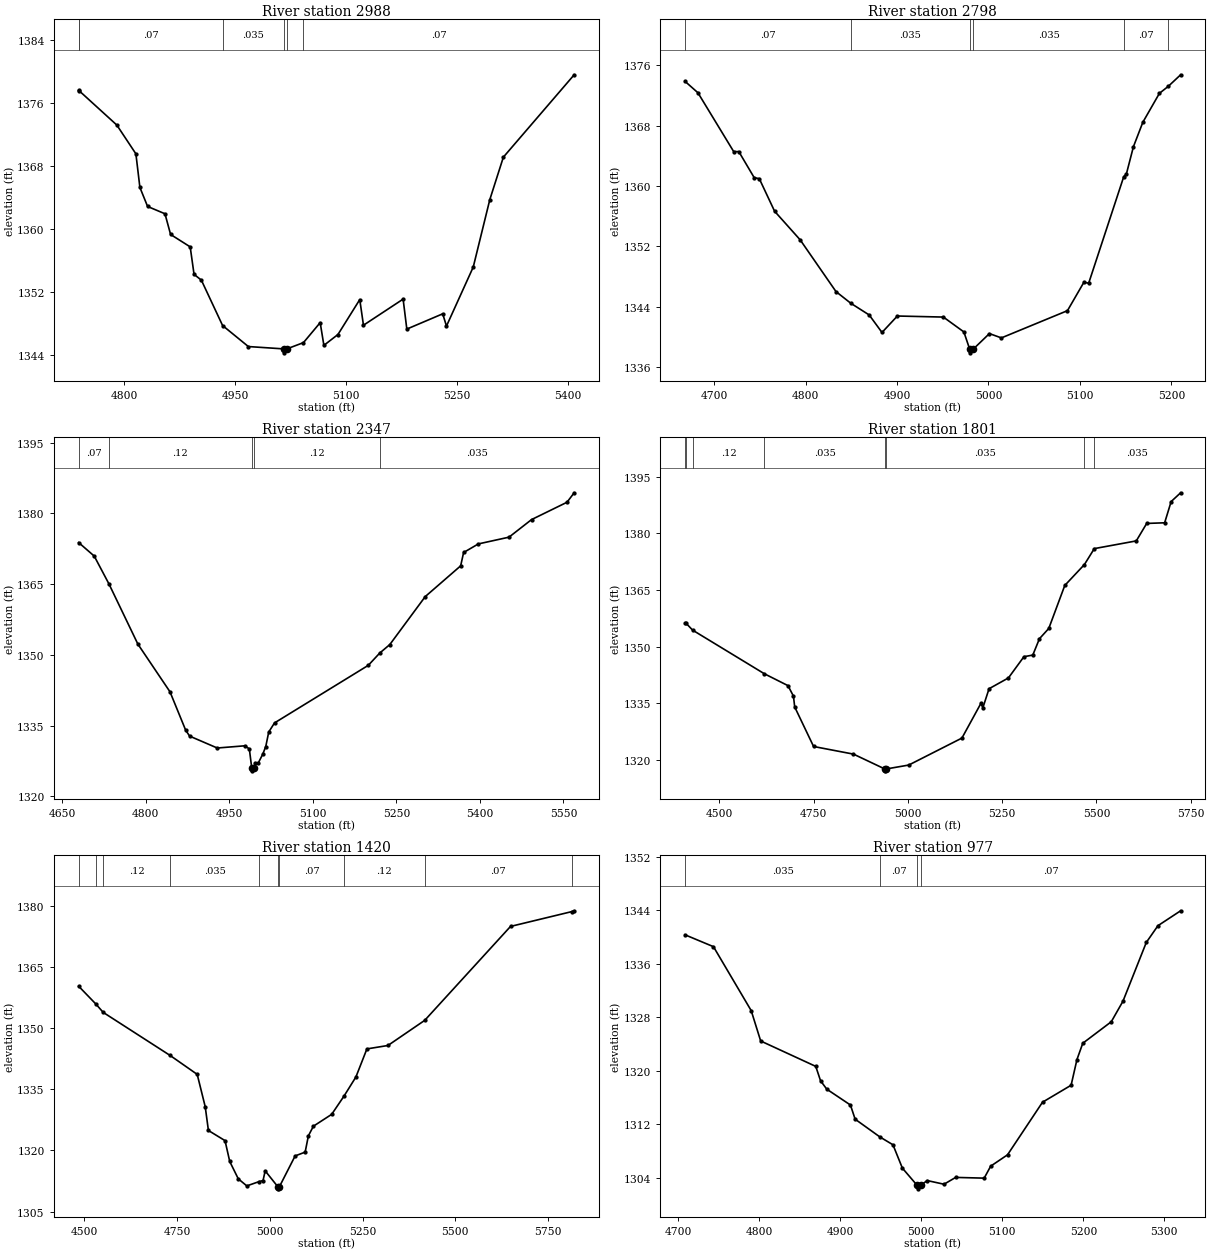
Type RM Length L Ch R = 1,2988,190,190,190
BEGIN DESCRIPTION:
Stream0081_DS 6.2
END DESCRIPTION:
XS GIS Cut Line= 3
      2068014.73     13906380.80      2067778.75     13906314.72
      2067360.78     13906239.17
#Sta/Elev= 30
  4738.3 1377.61  4739.2 1377.52  4789.9 1373.18  4815.7 1369.52  4821.1 1365.25
  4831.5 1362.83  4855.0 1361.90  4862.6 1359.27  4889.1 1357.69  4894.3 1354.20
  4904.2 1353.46  4932.9 1347.69  4967.7 1345.02  5015.7 1344.72  5015.9 1344.22
  5019.7 1344.72  5042.2 1345.52  5064.8 1348.06  5069.8 1345.17  5088.8 1346.55
  5118.3 1350.99  5123.3 1347.73  5176.9 1351.05  5181.9 1347.24  5230.4 1349.18
  5235.5 1347.62  5271.7 1355.13  5294.1 1363.71  5312.4 1369.10  5408.1 1379.57
#Mann=6,-1,0
  4738.3   0.035       0  4739.2    0.07       0  4932.9   0.035       0
  5015.7   0.035       0  5019.7   0.035       0  5042.2    0.07       0
Bank Sta=5015.7,5019.7
Exp/Cntr=0.3,0.1

Type RM Length L Ch R = 1,2798,451,451,451
BEGIN DESCRIPTION:
Stream0081_DS 6.0
END DESCRIPTION:
XS GIS Cut Line= 3
      2067975.00     13906325.00      2067675.00     13906175.00
      2067474.96     13906124.99
#Sta/Elev= 30
  4668.4 1373.86  4682.4 1372.36  4721.5 1364.56  4727.1 1364.56  4743.9 1361.11
  4749.5 1360.97  4766.2 1356.66  4794.2 1352.86  4833.3 1346.01  4849.5 1344.46
  4869.6 1342.91  4883.6 1340.59  4900.4 1342.77  4950.7 1342.63  4973.1 1340.66
  4979.4 1338.39  4979.7 1337.89  4983.4 1338.39  5001.0 1340.44  5014.1 1339.87
  5086.3 1343.48  5104.3 1347.25  5109.5 1347.12  5147.8 1361.23  5150.7 1361.59
  5158.4 1365.21  5168.7 1368.45  5186.8 1372.28  5196.5 1373.21  5210.0 1374.74
#Mann=6,-1,0
  4668.4    0.07       0  4849.5   0.035       0  4979.4   0.035       0
  4983.4   0.035       0  5147.8    0.07       0  5196.5   0.035       0
Bank Sta=4979.4,4983.4
Exp/Cntr=0.3,0.1

Type RM Length L Ch R = 1,2347,546,546,546
BEGIN DESCRIPTION:
Stream0081_DS 5.0
END DESCRIPTION:
XS GIS Cut Line= 3
      2068124.97     13906024.97      2067875.00     13905825.00
      2067333.87     13905647.22
#Sta/Elev= 30
  4679.6 1373.83  4707.6 1370.96  4733.9 1365.09  4786.0 1352.29  4843.6 1342.19
  4871.7 1334.07  4878.9 1332.79  4928.5 1330.27  4978.1 1330.74  4986.1 1330.08
  4990.5 1325.93  4990.8 1325.43  4994.5 1325.93  4996.5 1327.14  5002.3 1327.14
  5010.2 1328.96  5015.6 1330.59  5020.9 1333.66  5031.3 1335.59  5199.7 1347.80
  5220.3 1350.41  5238.3 1352.20  5301.9 1362.37  5365.5 1368.89  5370.8 1371.72
  5397.3 1373.54  5452.3 1374.97  5492.7 1378.69  5556.4 1382.37  5569.3 1384.38
#Mann=5,-1,0
  4679.6    0.07       0  4733.9    0.12       0  4990.5    0.05       0
  4994.5    0.12       0  5220.3   0.035       0
Bank Sta=4990.5,4994.5
Exp/Cntr=0.3,0.1

Type RM Length L Ch R = 1,1801,381,381,381
BEGIN DESCRIPTION:
Stream0081_DS 4.0
END DESCRIPTION:
XS GIS Cut Line= 5
      2068534.78     13905598.67      2068355.93     13905368.16
      2068217.33     13905345.87      2068074.54     13905414.81
      2067370.49     13905580.11
#Sta/Elev= 30
  4409.3 1356.19  4411.8 1356.19  4429.3 1354.36  4619.5 1342.82  4682.1 1339.68
  4696.6 1336.90  4699.9 1334.04  4750.0 1323.58  4855.8 1321.56  4938.7 1317.64
  4938.9 1317.14  4942.7 1317.64  5002.3 1318.67  5143.3 1325.81  5193.6 1334.98
  5198.8 1333.82  5215.2 1338.86  5266.6 1341.72  5307.7 1347.34  5331.2 1347.76
  5348.8 1352.09  5373.6 1354.81  5416.0 1366.18  5468.1 1371.72  5494.3 1375.93
  5605.6 1377.97  5633.2 1382.59  5680.8 1382.76  5698.0 1388.37  5723.2 1390.70
#Mann=8,-1,0
  4409.3    0.12       0  4411.8   0.035       0  4429.3    0.12       0
  4619.5   0.035       0  4938.7   0.035       0  4942.7   0.035       0
  5468.1    0.07       0  5494.3   0.035       0
Bank Sta=4938.7,4942.7
Exp/Cntr=0.3,0.1

Type RM Length L Ch R = 1,1420,443,443,443
BEGIN DESCRIPTION:
Stream0081_DS 3.0
END DESCRIPTION:
XS GIS Cut Line= 3
      2068576.91     13905619.43      2068325.00     13905175.00
      2067851.94     13904498.93
#Sta/Elev= 30
  4484.4 1360.31  4530.5 1355.97  4550.7 1353.88  4731.1 1343.31  4804.1 1338.67
  4825.7 1330.73  4834.3 1324.90  4879.1 1322.41  4891.8 1317.29  4914.8 1313.04
  4937.8 1311.30  4971.3 1312.37  4981.6 1312.61  4987.3 1315.00  5021.6 1311.08
  5021.8 1310.58  5025.6 1311.08  5068.1 1318.66  5095.1 1319.59  5103.8 1323.58
  5117.3 1325.95  5166.6 1328.86  5199.8 1333.33  5232.0 1338.04  5261.6 1344.92
  5318.3 1345.76  5417.5 1351.93  5648.8 1374.98  5813.7 1378.61  5820.4 1378.82
#Mann=10,-1,0
  4484.4    0.12       0  4530.5   0.035       0  4550.7    0.12       0
  4731.1   0.035       0  4971.3    0.07       0  5021.6    0.05       0
  5025.6    0.07       0  5199.8    0.12       0  5417.5    0.07       0
  5813.7    0.12       0
Bank Sta=5021.6,5025.6
Exp/Cntr=0.3,0.1

Type RM Length L Ch R = 1,977,442,442,442
BEGIN DESCRIPTION:
Stream0081_DS 2.0
END DESCRIPTION:
XS GIS Cut Line= 3
      2068775.01     13905175.01      2068625.00     13904925.00
      2068375.01     13904725.01
#Sta/Elev= 30
  4708.4 1340.35  4743.4 1338.58  4790.0 1329.01  4801.7 1324.47  4869.7 1320.67
  4875.6 1318.52  4883.3 1317.26  4912.5 1314.89  4918.3 1312.77  4948.9 1310.11
  4965.0 1308.94  4976.6 1305.45  4995.0 1302.85  4995.3 1302.35  4999.0 1302.85
  5007.2 1303.59  5028.0 1303.04  5042.4 1304.06  5077.6 1303.95  5085.6 1305.74
  5106.4 1307.44  5149.6 1315.31  5184.9 1317.85  5192.1 1321.69  5199.3 1324.13
  5234.5 1327.35  5248.9 1330.42  5277.7 1339.21  5292.1 1341.72  5320.1 1343.95
#Mann=4,-1,0
  4708.4   0.035       0  4948.9    0.07       0  4995.0    0.05       0
  4999.0    0.07       0
Bank Sta=4995,4999
Exp/Cntr=0.3,0.1

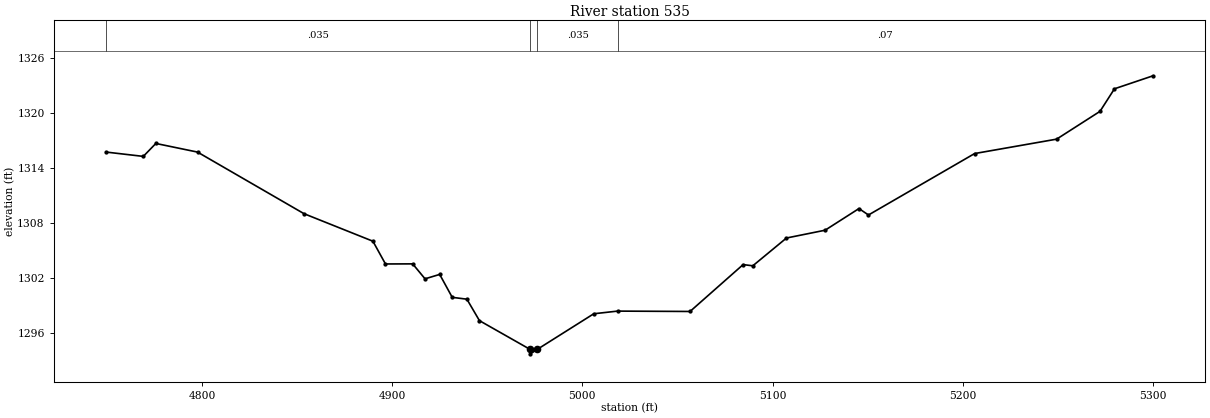
Type RM Length L Ch R = 1,535,0,0,0
BEGIN DESCRIPTION:
Stream0081_DS 1.0
END DESCRIPTION:
XS GIS Cut Line= 3
      2069035.25     13904761.80      2068875.00     13904575.00
      2068574.96     13904524.99
#Sta/Elev= 30
  4749.7 1315.73  4769.2 1315.26  4775.8 1316.67  4797.7 1315.73  4853.7 1309.01
  4889.9 1306.01  4896.5 1303.53  4910.8 1303.54  4917.3 1301.91  4925.0 1302.39
  4931.6 1299.89  4939.3 1299.69  4945.9 1297.35  4972.4 1294.23  4972.7 1293.73
  4976.4 1294.23  5006.0 1298.10  5018.5 1298.39  5056.6 1298.35  5084.5 1303.46
  5089.6 1303.33  5107.3 1306.36  5127.6 1307.21  5145.4 1309.57  5150.4 1308.87
  5206.2 1315.57  5249.3 1317.14  5272.1 1320.17  5279.7 1322.63  5300.0 1324.05
#Mann=4,-1,0
  4749.7   0.035       0  4972.4   0.035       0  4976.4   0.035       0
  5018.5    0.07       0
Bank Sta=4972.4,4976.4
Exp/Cntr=0.3,0.1

Chan Stop Cuts=-1