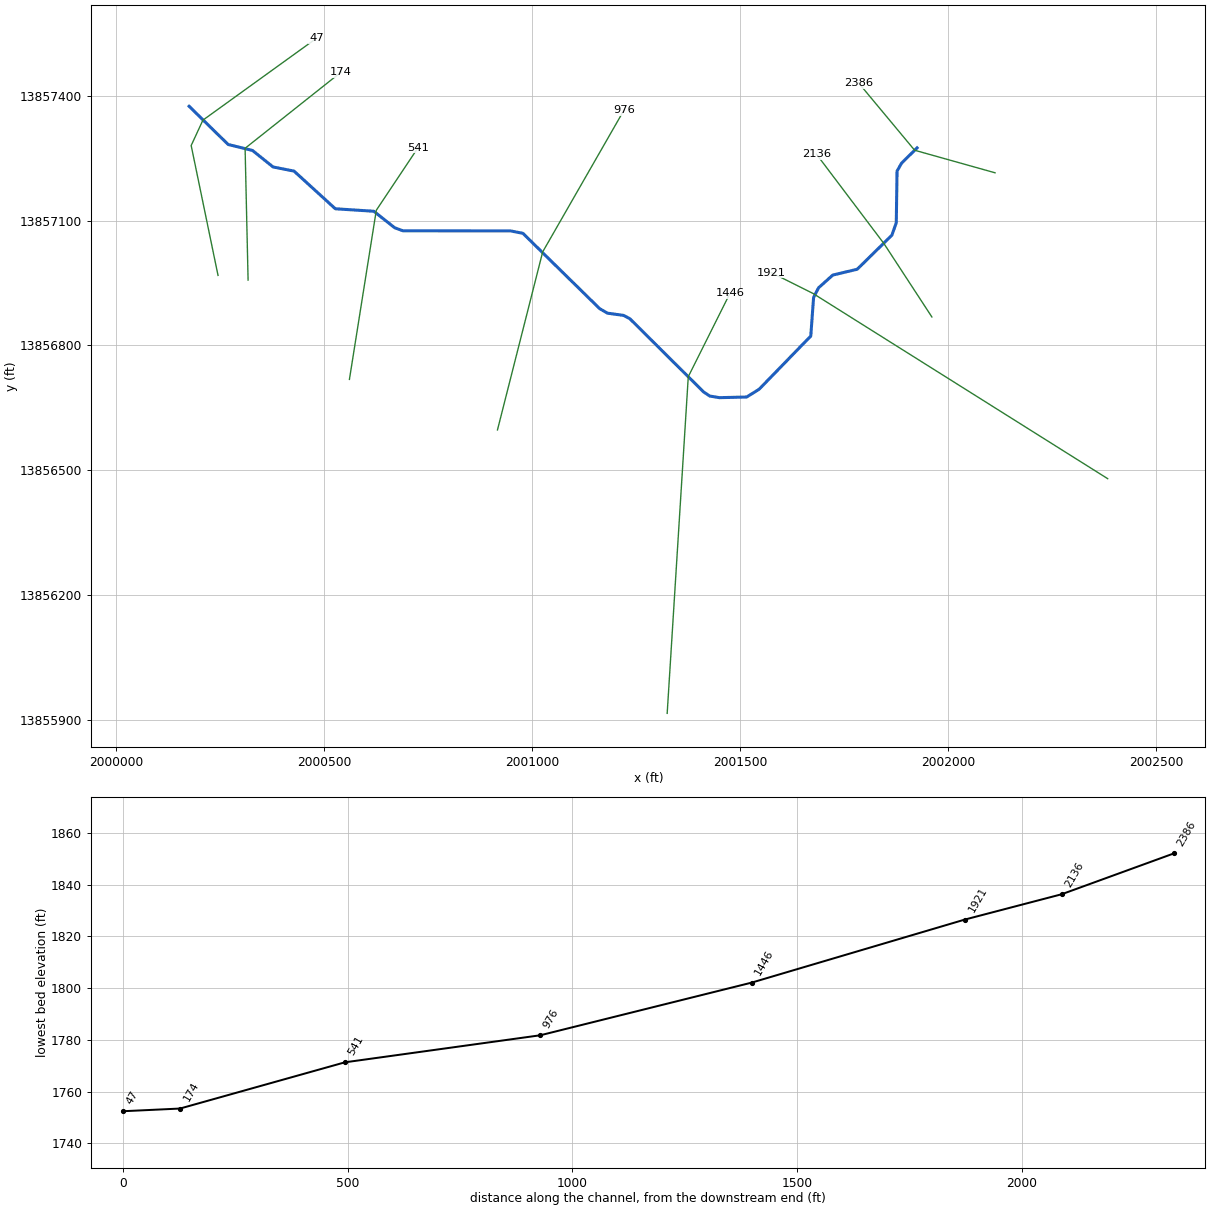
--- Stream0082_DS.prj (project) ---

Proj Title=Stream0082_DS Base Level Engineering
Current Plan=p01
Default Exp/Contr=0.3,0.1
English Units
Geom File=g01
Flow File=f01
Plan File=p01
BEGIN DESCRIPTION:
Stream0082_DS
END DESCRIPTION:

--- Stream0082_DS.p01 (plan) ---

Plan Title=Multiple Run
Short Identifier=Multiple
Geom File=g01
Flow File=f01
Subcritical Flow
K Sum by GR= 0
Std Step Tol= 0.01
Critical Tol= 0.01
Num of Std Step Trials= 20
Max Error Tol= 0.3
Flow Tol Ratio= 0.001
Split Flow NTrial= 30
Split Flow Tol= 0.02
Split Flow Ratio= 0.02
Log Output Level= 0
Friction Slope Method= 1
Unsteady Friction Slope Method= 2
Unsteady Bridges Friction Slope Method= 1
Parabolic Critical Depth
Global Vel Dist=  1 , 1 , 1
Global Log Level= 0
CheckData=True
Encroach Param= -1, 0, 0, 0
BEGIN DESCRIPTION:
Multiple Run
END DESCRIPTION:

--- Stream0082_DS.f01 (steady flow) ---

Flow Title=Multiple
Number of Profiles=7
Profile Names=10-year,25-year,50-year,1pct_min,100-year,1pct_plu,500-year
River Rch & RM= Stream0082_DS,Reach-1,2386
     237     365     476     304     606    1208     963
River Rch & RM= Stream0082_DS,Reach-1,1446
     446     720     970     637    1270    2535    2149
Boundary for River Rch & Prof#=Stream0082_DS,Reach-1,1
Up Type=0
Dn Type=3
Dn Slope=0.005
Boundary for River Rch & Prof#=Stream0082_DS,Reach-1,2
Up Type=0
Dn Type=3
Dn Slope=0.005
Boundary for River Rch & Prof#=Stream0082_DS,Reach-1,3
Up Type=0
Dn Type=3
Dn Slope=0.005
Boundary for River Rch & Prof#=Stream0082_DS,Reach-1,4
Up Type=0
Dn Type=3
Dn Slope=0.005
Boundary for River Rch & Prof#=Stream0082_DS,Reach-1,5
Up Type=0
Dn Type=3
Dn Slope=0.005
Boundary for River Rch & Prof#=Stream0082_DS,Reach-1,6
Up Type=0
Dn Type=3
Dn Slope=0.005
Boundary for River Rch & Prof#=Stream0082_DS,Reach-1,7
Up Type=0
Dn Type=3
Dn Slope=0.005

--- Stream0082_DS.g01 (geometry) ---

Geom Title=Existing Conditions

River Reach=Stream0082_DS,Reach-1
Reach XY= 30
      2001925.00     13857275.00      2001887.92     13857238.50
      2001876.91     13857219.21      2001875.03     13857094.98
      2001864.53     13857065.18      2001781.05     13856983.16
      2001722.43     13856969.26      2001688.26     13856938.65
      2001676.25     13856915.52      2001669.47     13856822.58
      2001545.16     13856694.58      2001515.36     13856676.09
      2001449.96     13856674.49      2001426.50     13856678.46
      2001411.70     13856688.34      2001234.68     13856864.22
      2001219.36     13856872.36      2001180.64     13856877.64
      2001161.79     13856888.63      2000977.45     13857069.54
      2000947.88     13857075.37      2000688.92     13857075.68
      2000668.94     13857083.14      2000619.02     13857122.64
      2000526.50     13857128.62      2000427.29     13857219.15
      2000376.73     13857229.19      2000327.19     13857268.91
      2000268.92     13857283.09      2000175.00     13857375.00

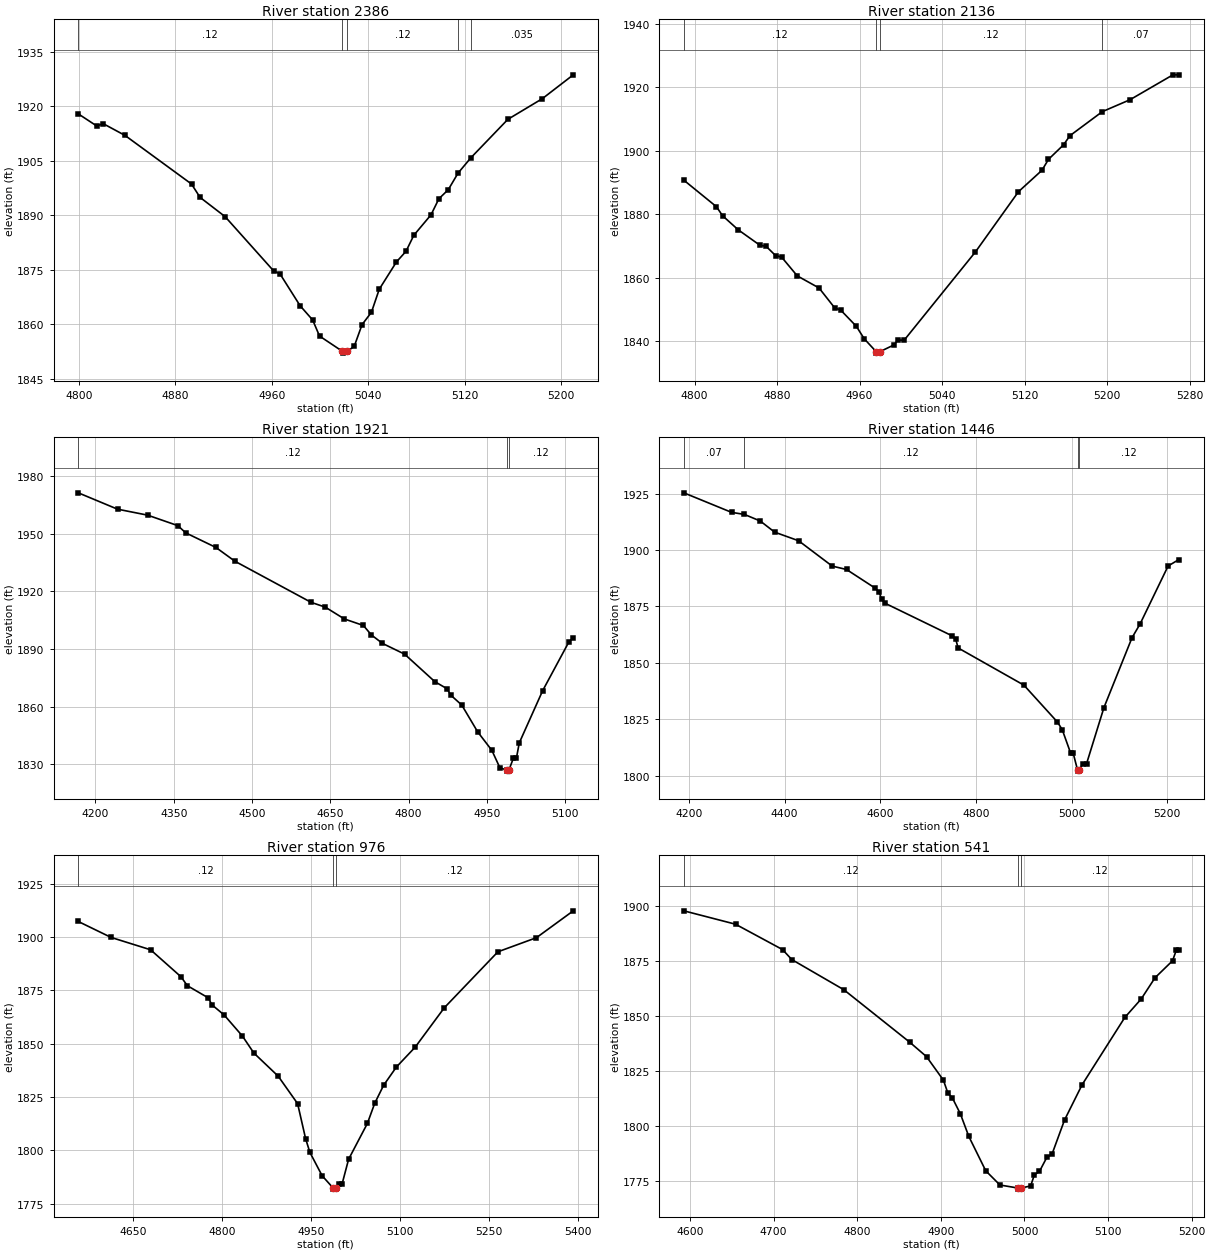
Type RM Length L Ch R = 1,2386,250,250,250
BEGIN DESCRIPTION:
Stream0082_DS 6.0
END DESCRIPTION:
XS GIS Cut Line= 3
      2002112.38     13857215.15      2001919.14     13857269.34
      2001784.60     13857430.98
#Sta/Elev= 30
  4799.3 1917.87  4814.7 1914.52  4819.9 1915.19  4838.1 1911.94  4893.3 1898.57
  4900.4 1894.90  4921.2 1889.60  4961.5 1874.67  4966.7 1873.89  4983.5 1865.08
  4993.9 1861.17  4999.6 1856.75  5018.6 1852.55  5018.8 1852.05  5022.6 1852.55
  5028.4 1853.90  5034.9 1859.88  5042.7 1863.29  5049.2 1869.63  5063.5 1877.15
  5071.4 1880.06  5077.9 1884.47  5092.2 1890.11  5098.7 1894.51  5106.5 1897.01
  5114.6 1901.56  5125.3 1905.80  5156.0 1916.37  5184.6 1922.05  5210.3 1928.61
#Mann=5,-1,0
  4799.3    0.12       0  5018.6    0.05       0  5022.6    0.12       0
  5114.6    0.07       0  5125.3   0.035       0
Bank Sta=5018.6,5022.6
Exp/Cntr=0.3,0.1

Type RM Length L Ch R = 1,2136,215,215,215
BEGIN DESCRIPTION:
Stream0082_DS 5.0
END DESCRIPTION:
XS GIS Cut Line= 3
      2001960.59     13856868.57      2001845.52     13857044.72
      2001683.13     13857259.93
#Sta/Elev= 30
  4789.6 1890.72  4821.2 1882.37  4827.2 1879.51  4842.3 1875.10  4863.4 1870.22
  4869.4 1869.89  4878.5 1866.99  4884.5 1866.46  4899.6 1860.58  4920.7 1856.77
  4935.8 1850.54  4941.8 1849.78  4956.9 1844.69  4964.5 1840.78  4976.0 1836.75
  4976.2 1836.25  4980.0 1836.75  4993.1 1838.80  4997.2 1840.34  5003.3 1840.34
  5072.4 1868.14  5114.1 1887.09  5136.9 1893.84  5143.2 1897.28  5157.8 1901.85
  5164.0 1904.73  5195.4 1912.30  5222.3 1916.06  5263.9 1923.90  5269.6 1923.90
#Mann=4,-1,0
  4789.6    0.12       0  4976.0    0.05       0  4980.0    0.12       0
  5195.4    0.07       0
Bank Sta=4976,4980
Exp/Cntr=0.3,0.1

Type RM Length L Ch R = 1,1921,475,475,475
BEGIN DESCRIPTION:
Stream0082_DS 4.0
END DESCRIPTION:
XS GIS Cut Line= 3
      2002383.34     13856479.73      2001675.00     13856925.00
      2001574.97     13856975.02
#Sta/Elev= 30
  4167.2 1971.31  4242.4 1962.80  4300.1 1959.69  4357.9 1954.24  4373.2 1950.46
  4430.9 1942.89  4467.4 1935.70  4613.4 1914.31  4640.5 1911.83  4677.0 1905.68
  4713.5 1902.28  4728.8 1897.37  4750.1 1892.95  4792.5 1887.36  4850.3 1873.07
  4873.9 1869.35  4880.8 1866.07  4902.0 1860.88  4932.6 1846.88  4959.7 1837.30
  4975.0 1828.27  4988.3 1826.99  4988.6 1826.49  4992.3 1826.99  5000.9 1833.21
  5006.7 1833.21  5012.2 1841.18  5057.0 1868.34  5107.3 1893.73  5115.7 1895.96
#Mann=3,-1,0
  4167.2    0.12       0  4988.3    0.05       0  4992.3    0.12       0
Bank Sta=4988.3,4992.3
Exp/Cntr=0.3,0.1

Type RM Length L Ch R = 1,1446,470,470,470
BEGIN DESCRIPTION:
Stream0082_DS 3.0
END DESCRIPTION:
XS GIS Cut Line= 3
      2001324.28     13855915.53      2001375.00     13856725.00
      2001475.01     13856925.03
#Sta/Elev= 30
  4189.3 1925.32  4289.0 1916.68  4315.9 1915.76  4349.1 1912.83  4379.1 1907.91
  4429.2 1904.10  4499.4 1892.88  4529.4 1891.37  4589.6 1883.07  4597.6 1881.37
  4602.6 1878.26  4609.6 1876.46  4749.9 1862.02  4757.7 1860.45  4762.7 1856.63
  4900.2 1840.16  4970.3 1823.81  4980.3 1820.45  4997.9 1810.03  5003.2 1810.03
  5012.3 1802.59  5012.6 1802.09  5016.3 1802.59  5022.7 1805.16  5031.1 1805.35
  5067.4 1830.18  5126.1 1861.14  5142.9 1867.21  5201.6 1892.92  5224.0 1895.77
#Mann=4,-1,0
  4189.3    0.07       0  4315.9    0.12       0  5012.3    0.05       0
  5016.3    0.12       0
Bank Sta=5012.3,5016.3
Exp/Cntr=0.3,0.1

Type RM Length L Ch R = 1,976,435,435,435
BEGIN DESCRIPTION:
Stream0082_DS 2.0
END DESCRIPTION:
XS GIS Cut Line= 3
      2000916.30     13856596.97      2001025.00     13857025.00
      2001220.08     13857365.11
#Sta/Elev= 30
  4558.1 1907.27  4613.3 1899.80  4679.9 1894.00  4731.0 1881.36  4741.8 1877.16
  4777.1 1871.44  4783.0 1868.23  4803.7 1863.44  4834.6 1853.52  4853.8 1845.58
  4894.8 1834.72  4927.5 1821.84  4940.9 1805.49  4948.1 1799.03  4968.8 1788.03
  4987.4 1782.25  4987.6 1781.75  4991.4 1782.25  4997.1 1784.37  5002.6 1784.37
  5013.4 1795.78  5045.0 1812.56  5057.4 1822.03  5072.4 1830.47  5093.9 1839.02
  5125.6 1848.36  5174.5 1866.78  5264.9 1893.06  5329.8 1899.68  5391.8 1912.27
#Mann=3,-1,0
  4558.1    0.12       0  4987.4    0.05       0  4991.4    0.12       0
Bank Sta=4987.4,4991.4
Exp/Cntr=0.3,0.1

Type RM Length L Ch R = 1,541,367,367,367
BEGIN DESCRIPTION:
Stream0082_DS 1.0
END DESCRIPTION:
XS GIS Cut Line= 3
      2000560.38     13856718.43      2000625.00     13857125.00
      2000724.97     13857274.96
#Sta/Elev= 30
  4592.7 1897.73  4654.5 1891.65  4710.7 1880.13  4721.8 1875.59  4784.0 1861.89
  4862.6 1838.11  4882.9 1831.48  4903.1 1820.79  4908.5 1814.86  4913.6 1812.89
  4923.4 1805.48  4933.5 1795.21  4953.7 1779.64  4970.7 1773.16  4992.2 1771.79
  4992.5 1771.29  4996.2 1771.79  5007.4 1772.75  5011.9 1777.79  5017.9 1779.31
  5026.9 1785.80  5032.9 1787.11  5047.9 1802.66  5069.0 1818.76  5120.0 1849.28
  5139.6 1857.68  5156.1 1867.30  5177.1 1875.05  5181.6 1879.87  5184.6 1879.87
#Mann=3,-1,0
  4592.7    0.12       0  4992.2    0.05       0  4996.2    0.12       0
Bank Sta=4992.2,4996.2
Exp/Cntr=0.3,0.1

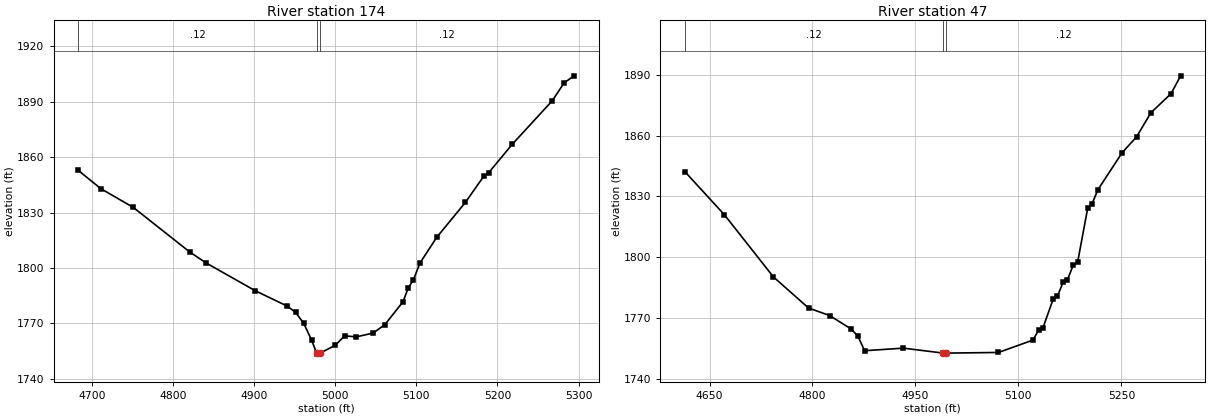
Type RM Length L Ch R = 1,174,127,127,127
BEGIN DESCRIPTION:
Stream0082_DS 0.1
END DESCRIPTION:
XS GIS Cut Line= 3
      2000316.78     13856957.20      2000309.59     13857274.02
      2000540.33     13857457.18
#Sta/Elev= 30
  4683.1 1852.77  4710.9 1842.91  4750.9 1832.78  4820.9 1808.53  4840.9 1802.69
  4901.0 1787.78  4941.0 1779.33  4951.0 1776.01  4961.0 1770.12  4971.0 1760.80
  4977.0 1753.92  4977.3 1753.42  4981.0 1753.92  5000.0 1758.19  5011.5 1763.32
  5025.9 1762.75  5046.7 1764.82  5061.1 1769.36  5083.5 1781.74  5090.0 1789.25
  5096.4 1793.65  5104.4 1802.68  5125.2 1816.66  5160.4 1835.45  5182.9 1849.52
  5189.3 1851.59  5218.1 1866.86  5267.8 1890.58  5282.2 1900.14  5294.6 1903.96
#Mann=3,-1,0
  4683.1    0.12       0  4977.0    0.05       0  4981.0    0.12       0
Bank Sta=4977,4981
Exp/Cntr=0.3,0.1

Type RM Length L Ch R = 1,47,0,0,0
BEGIN DESCRIPTION:
Stream0082_DS 0.0
END DESCRIPTION:
XS GIS Cut Line= 4
      2000244.50     13856968.46      2000179.94     13857280.63
      2000208.17     13857341.64      2000480.94     13857538.35
#Sta/Elev= 30
  4614.0 1842.28  4671.7 1821.00  4743.2 1790.36  4794.3 1775.08  4824.9 1771.40
  4855.5 1764.92  4865.8 1761.46  4876.0 1754.06  4932.3 1755.33  4990.7 1752.88
  4990.9 1752.38  4994.7 1752.88  5070.9 1753.20  5121.2 1759.30  5129.8 1764.46
  5135.9 1765.49  5150.6 1779.42  5156.8 1780.83  5165.3 1787.94  5171.5 1789.06
  5180.1 1796.36  5186.2 1797.54  5200.9 1824.25  5207.1 1826.23  5215.7 1833.29
  5251.2 1851.63  5272.1 1859.36  5293.0 1871.25  5322.4 1880.66  5336.3 1889.42
#Mann=3,-1,0
  4614.0    0.12       0  4990.7    0.05       0  4994.7    0.12       0
Bank Sta=4990.7,4994.7
Exp/Cntr=0.3,0.1

Chan Stop Cuts=-1