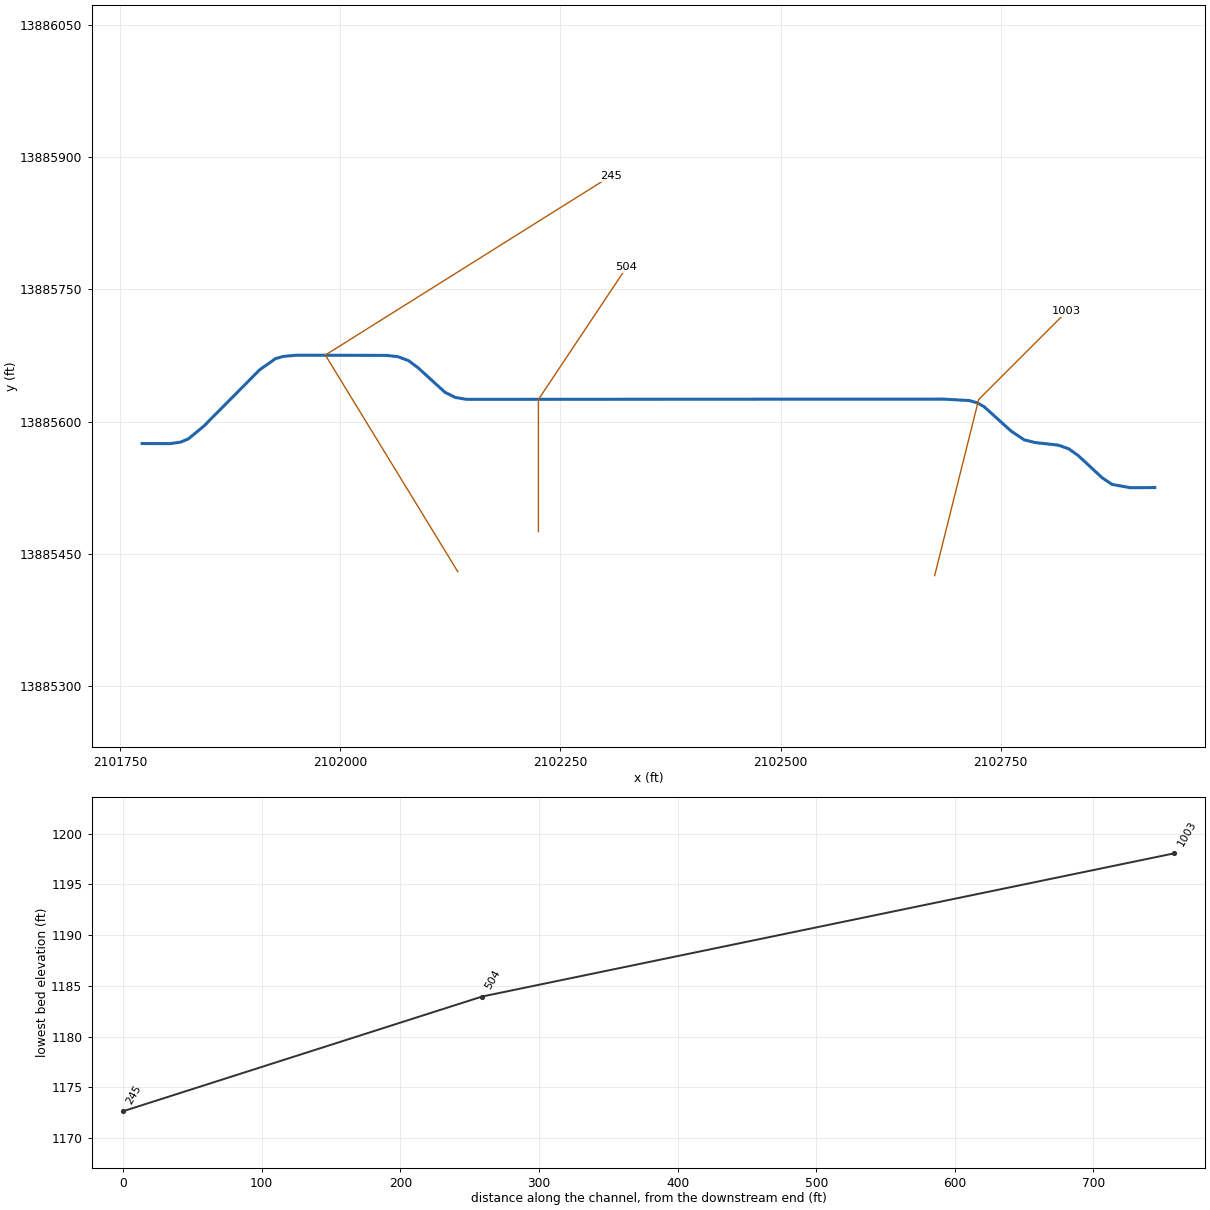
--- Stream0083_DS.prj (project) ---

Proj Title=Stream0083_DS Base Level Engineering
Current Plan=p01
Default Exp/Contr=0.3,0.1
English Units
Geom File=g01
Flow File=f01
Plan File=p01
BEGIN DESCRIPTION:
Stream0083_DS
END DESCRIPTION:

--- Stream0083_DS.p01 (plan) ---

Plan Title=Multiple Run
Short Identifier=Multiple
Geom File=g01
Flow File=f01
Subcritical Flow
K Sum by GR= 0
Std Step Tol= 0.01
Critical Tol= 0.01
Num of Std Step Trials= 20
Max Error Tol= 0.3
Flow Tol Ratio= 0.001
Split Flow NTrial= 30
Split Flow Tol= 0.02
Split Flow Ratio= 0.02
Log Output Level= 0
Friction Slope Method= 1
Unsteady Friction Slope Method= 2
Unsteady Bridges Friction Slope Method= 1
Parabolic Critical Depth
Global Vel Dist=  1 , 1 , 1
Global Log Level= 0
CheckData=True
Encroach Param= -1, 0, 0, 0
BEGIN DESCRIPTION:
Multiple Run
END DESCRIPTION:

--- Stream0083_DS.f01 (steady flow) ---

Flow Title=Multiple
Number of Profiles=7
Profile Names=10-year,25-year,50-year,1pct_min,100-year,1pct_plu,500-year
River Rch & RM= Stream0083_DS,Reach-1,1003
     322     505     666     429     856    1708    1391
Boundary for River Rch & Prof#=Stream0083_DS,Reach-1,1
Up Type=0
Dn Type=3
Dn Slope=0.005
Boundary for River Rch & Prof#=Stream0083_DS,Reach-1,2
Up Type=0
Dn Type=3
Dn Slope=0.005
Boundary for River Rch & Prof#=Stream0083_DS,Reach-1,3
Up Type=0
Dn Type=3
Dn Slope=0.005
Boundary for River Rch & Prof#=Stream0083_DS,Reach-1,4
Up Type=0
Dn Type=3
Dn Slope=0.005
Boundary for River Rch & Prof#=Stream0083_DS,Reach-1,5
Up Type=0
Dn Type=3
Dn Slope=0.005
Boundary for River Rch & Prof#=Stream0083_DS,Reach-1,6
Up Type=0
Dn Type=3
Dn Slope=0.005
Boundary for River Rch & Prof#=Stream0083_DS,Reach-1,7
Up Type=0
Dn Type=3
Dn Slope=0.005

--- Stream0083_DS.g01 (geometry) ---

Geom Title=Existing Conditions

River Reach=Stream0083_DS,Reach-1
Reach XY= 30
      2102925.00     13885525.00      2102897.32     13885524.82
      2102876.49     13885528.60      2102865.41     13885535.98
      2102838.15     13885561.24      2102827.25     13885569.05
      2102815.18     13885573.23      2102789.09     13885576.11
      2102776.73     13885579.17      2102761.96     13885589.04
      2102731.08     13885616.91      2102723.45     13885621.25
      2102714.50     13885623.80      2102685.19     13885625.46
      2102143.27     13885625.21      2102130.53     13885627.38
      2102118.94     13885633.14      2102088.14     13885661.21
      2102077.33     13885669.26      2102065.33     13885673.63
      2102052.30     13885675.12      2101949.89     13885675.32
      2101935.44     13885673.96      2101926.47     13885671.47
      2101908.24     13885658.57      2101845.07     13885594.84
      2101827.51     13885580.33      2101818.85     13885576.69
      2101806.88     13885574.93      2101775.00     13885575.00

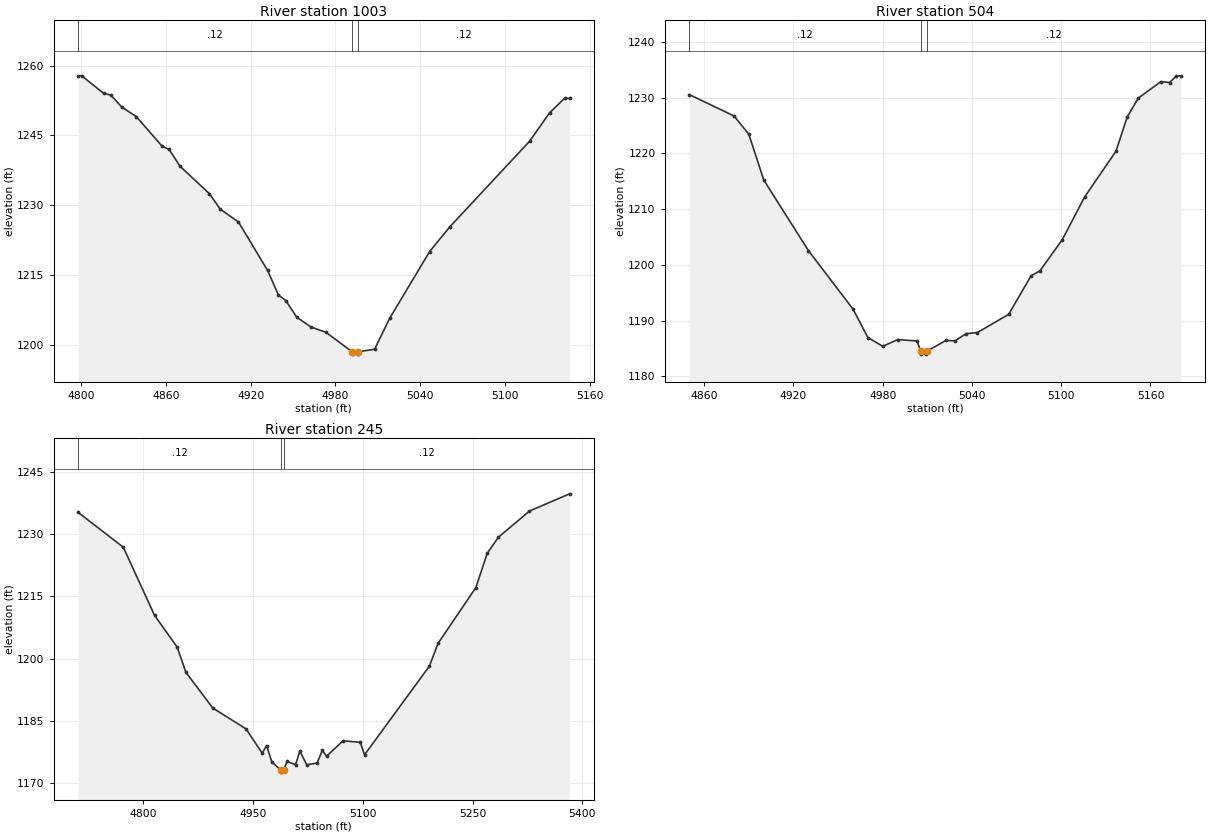
Type RM Length L Ch R = 1,1003,499,499,499
BEGIN DESCRIPTION:
Stream0083_DS 2.0
END DESCRIPTION:
XS GIS Cut Line= 3
      2102675.00     13885425.01      2102725.00     13885625.00
      2102825.02     13885725.02
#Sta/Elev= 30
  4798.0 1257.81  4800.6 1257.81  4816.0 1254.06  4821.2 1253.65  4828.9 1251.10
  4839.2 1249.04  4857.3 1242.74  4862.4 1242.00  4870.1 1238.39  4890.8 1232.53
  4898.5 1229.20  4911.4 1226.43  4932.0 1216.03  4939.7 1210.75  4944.9 1209.56
  4952.6 1205.99  4962.9 1203.84  4973.2 1202.77  4991.8 1198.56  4992.1 1198.06
  4995.6 1198.06  4995.8 1198.56  5007.7 1199.11  5018.3 1205.73  5046.6 1220.08
  5060.7 1225.33  5117.3 1243.77  5131.4 1249.85  5142.0 1252.97  5145.6 1252.97
#Mann=3,-1,0
  4798.0    0.12       0  4991.8    0.05       0  4995.8    0.12       0
Bank Sta=4991.8,4995.8
Exp/Cntr=0.3,0.1

Type RM Length L Ch R = 1,504,259,259,259
BEGIN DESCRIPTION:
Stream0083_DS 1.0
END DESCRIPTION:
XS GIS Cut Line= 3
      2102225.00     13885475.01      2102225.00     13885625.00
      2102325.02     13885775.02
#Sta/Elev= 30
  4850.1 1230.57  4880.1 1226.75  4890.1 1223.44  4900.1 1215.24  4930.1 1202.56
  4960.1 1192.04  4970.1 1186.94  4980.1 1185.36  4990.1 1186.58  5003.1 1186.32
  5005.6 1184.46  5005.9 1183.96  5009.4 1183.96  5009.6 1184.46  5022.6 1186.43
  5028.6 1186.34  5036.1 1187.63  5043.7 1187.84  5064.7 1191.11  5079.7 1198.01
  5085.7 1198.92  5100.7 1204.51  5115.8 1212.22  5136.8 1220.41  5144.3 1226.52
  5151.8 1229.95  5166.9 1232.90  5172.9 1232.75  5177.4 1233.95  5180.4 1233.95
#Mann=3,-1,0
  4850.1    0.12       0  5005.6    0.05       0  5009.6    0.12       0
Bank Sta=5005.6,5009.6
Exp/Cntr=0.3,0.1

Type RM Length L Ch R = 1,245,0,0,0
BEGIN DESCRIPTION:
Stream0083_DS 0.0
END DESCRIPTION:
XS GIS Cut Line= 3
      2102133.47     13885429.43      2101983.02     13885675.48
      2102307.04     13885878.74
#Sta/Elev= 30
  4711.6 1235.19  4773.3 1226.79  4815.9 1210.41  4846.8 1202.75  4858.8 1196.67
  4895.3 1188.11  4940.8 1183.07  4962.9 1177.21  4968.8 1179.06  4976.0 1175.14
  4988.1 1173.16  4988.3 1172.66  4992.1 1173.16  4996.8 1175.24  5008.4 1174.44
  5014.3 1177.72  5023.7 1174.43  5037.8 1174.85  5044.9 1177.88  5050.8 1176.49
  5073.2 1180.20  5096.7 1179.84  5102.6 1176.84  5191.0 1198.15  5203.0 1203.67
  5254.6 1217.10  5270.0 1225.32  5285.3 1229.20  5327.7 1235.50  5382.5 1239.65
#Mann=3,-1,0
  4711.6    0.12       0  4988.1    0.05       0  4992.1    0.12       0
Bank Sta=4988.1,4992.1
Exp/Cntr=0.3,0.1

Chan Stop Cuts=-1