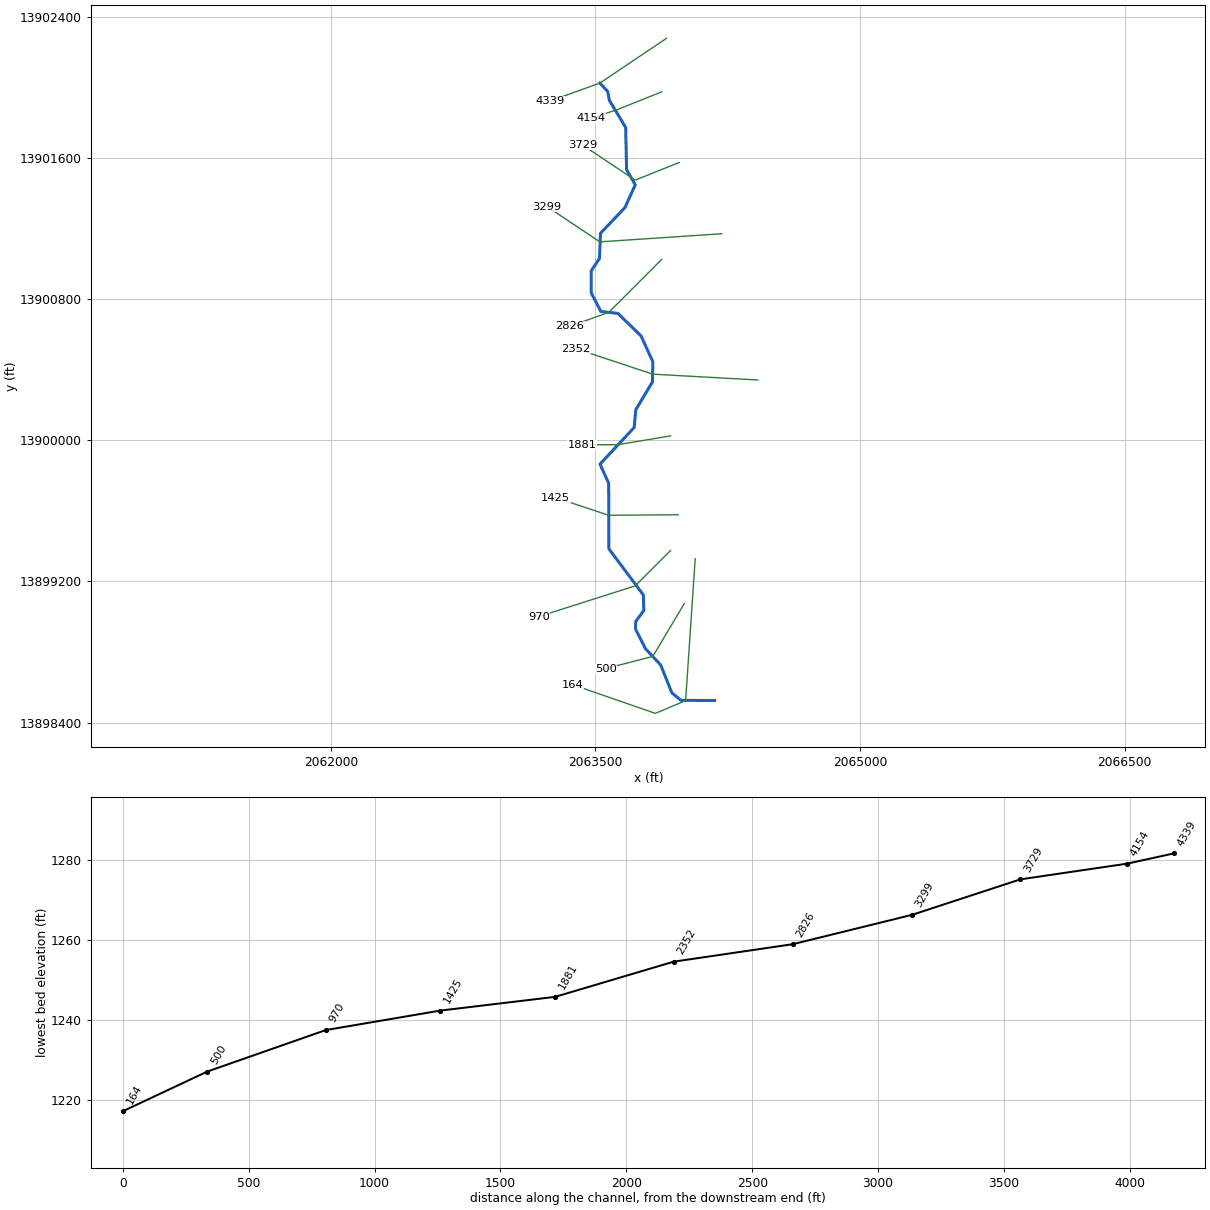
--- Stream0084_DS.prj (project) ---

Proj Title=Stream0084_DS Base Level Engineering
Current Plan=p01
Default Exp/Contr=0.3,0.1
English Units
Geom File=g01
Flow File=f01
Plan File=p01
BEGIN DESCRIPTION:
Stream0084_DS
END DESCRIPTION:

--- Stream0084_DS.p01 (plan) ---

Plan Title=Multiple Run
Short Identifier=Multiple
Geom File=g01
Flow File=f01
Subcritical Flow
K Sum by GR= 0
Std Step Tol= 0.01
Critical Tol= 0.01
Num of Std Step Trials= 20
Max Error Tol= 0.3
Flow Tol Ratio= 0.001
Split Flow NTrial= 30
Split Flow Tol= 0.02
Split Flow Ratio= 0.02
Log Output Level= 0
Friction Slope Method= 1
Unsteady Friction Slope Method= 2
Unsteady Bridges Friction Slope Method= 1
Parabolic Critical Depth
Global Vel Dist=  1 , 1 , 1
Global Log Level= 0
CheckData=True
Encroach Param= -1, 0, 0, 0
BEGIN DESCRIPTION:
Multiple Run
END DESCRIPTION:

--- Stream0084_DS.f01 (steady flow) ---

Flow Title=Multiple
Number of Profiles=7
Profile Names=10-year,25-year,50-year,1pct_min,100-year,1pct_plu,500-year
River Rch & RM= Stream0084_DS,Reach-1,4339
     713    1174    1602    1062    2119    4227    3658
River Rch & RM= Stream0084_DS,Reach-1,4154
     979    1641    2265    1516    3025    6036    5333
Boundary for River Rch & Prof#=Stream0084_DS,Reach-1,1
Up Type=0
Dn Type=3
Dn Slope=0.005
Boundary for River Rch & Prof#=Stream0084_DS,Reach-1,2
Up Type=0
Dn Type=3
Dn Slope=0.005
Boundary for River Rch & Prof#=Stream0084_DS,Reach-1,3
Up Type=0
Dn Type=3
Dn Slope=0.005
Boundary for River Rch & Prof#=Stream0084_DS,Reach-1,4
Up Type=0
Dn Type=3
Dn Slope=0.005
Boundary for River Rch & Prof#=Stream0084_DS,Reach-1,5
Up Type=0
Dn Type=3
Dn Slope=0.005
Boundary for River Rch & Prof#=Stream0084_DS,Reach-1,6
Up Type=0
Dn Type=3
Dn Slope=0.005
Boundary for River Rch & Prof#=Stream0084_DS,Reach-1,7
Up Type=0
Dn Type=3
Dn Slope=0.005

--- Stream0084_DS.g01 (geometry) ---

Geom Title=Existing Conditions

River Reach=Stream0084_DS,Reach-1
Reach XY= 30
      2063525.00     13902025.00      2063569.33     13901977.36
      2063579.04     13901926.67      2063671.25     13901773.45
      2063676.40     13901534.65      2063725.39     13901447.80
      2063666.86     13901318.94      2063528.54     13901173.53
      2063522.73     13901030.94      2063475.67     13900961.07
      2063476.18     13900835.48      2063530.44     13900730.25
      2063627.37     13900719.45      2063758.36     13900591.68
      2063825.40     13900445.14      2063822.77     13900330.93
      2063728.83     13900173.41      2063719.48     13900072.57
      2063525.75     13899865.22      2063574.77     13899756.74
      2063576.21     13899384.59      2063771.53     13899123.50
      2063773.88     13899035.55      2063728.37     13898973.26
      2063726.92     13898930.70      2063783.15     13898818.95
      2063869.15     13898727.29      2063933.00     13898568.61
      2063984.43     13898526.13      2064175.00     13898525.00

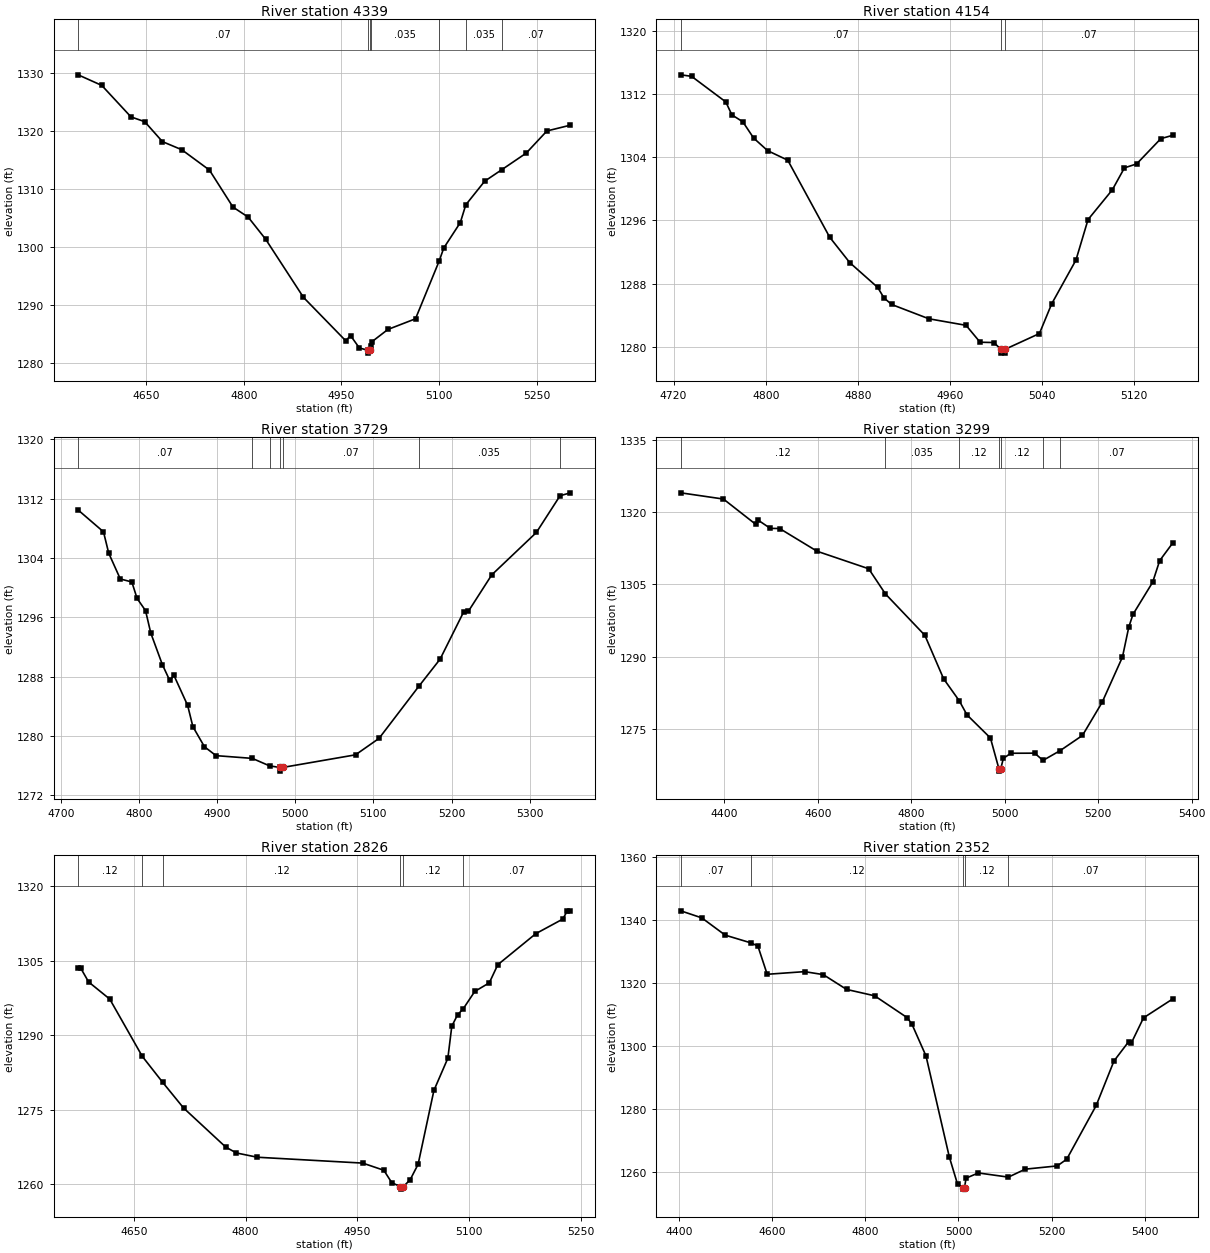
Type RM Length L Ch R = 1,4339,185,185,185
BEGIN DESCRIPTION:
Stream0084_DS 10.0
END DESCRIPTION:
XS GIS Cut Line= 3
      2063902.53     13902278.60      2063525.00     13902025.00
      2063240.96     13901922.40
#Sta/Elev= 30
  4545.2 1329.64  4581.5 1327.82  4626.4 1322.40  4647.5 1321.58  4674.7 1318.15
  4704.5 1316.75  4747.0 1313.25  4783.2 1306.88  4806.5 1305.16  4833.5 1301.34
  4891.6 1291.34  4956.5 1283.88  4963.9 1284.77  4977.5 1282.64  4990.5 1282.25
  4990.8 1281.75  4994.5 1282.25  4995.8 1283.02  4997.0 1283.73  5021.3 1285.82
  5063.8 1287.66  5099.9 1297.52  5107.3 1299.85  5132.7 1304.22  5141.1 1307.27
  5170.1 1311.33  5196.5 1313.32  5233.9 1316.16  5265.8 1319.98  5302.0 1320.98
#Mann=7,-1,0
  4545.2    0.07       0  4990.5   0.035       0  4994.5    0.07       0
  4995.8   0.035       0  5099.9    0.07       0  5141.1   0.035       0
  5196.5    0.07       0
Bank Sta=4990.5,4994.5
Exp/Cntr=0.3,0.1

Type RM Length L Ch R = 1,4154,425,425,425
BEGIN DESCRIPTION:
Stream0084_DS 9.0
END DESCRIPTION:
XS GIS Cut Line= 3
      2063875.02     13901975.01      2063625.00     13901875.00
      2063474.99     13901825.00
#Sta/Elev= 30
  4726.2 1314.43  4735.6 1314.24  4765.3 1311.00  4770.6 1309.36  4780.1 1308.48
  4789.5 1306.42  4801.6 1304.83  4819.1 1303.62  4855.5 1293.87  4873.0 1290.64
  4897.2 1287.51  4902.6 1286.19  4909.3 1285.35  4941.6 1283.54  4973.9 1282.71
  4986.1 1280.57  4998.1 1280.53  5004.0 1279.69  5004.3 1279.19  5007.8 1279.19
  5008.0 1279.69  5037.6 1281.67  5048.2 1285.42  5069.3 1290.97  5079.8 1296.10
  5100.9 1299.87  5111.4 1302.65  5122.0 1303.15  5143.0 1306.35  5153.6 1306.78
#Mann=3,-1,0
  4726.2    0.07       0  5004.0    0.05       0  5008.0    0.07       0
Bank Sta=5004,5008
Exp/Cntr=0.3,0.1

Type RM Length L Ch R = 1,3729,430,430,430
BEGIN DESCRIPTION:
Stream0084_DS 8.0
END DESCRIPTION:
XS GIS Cut Line= 3
      2063975.04     13901575.01      2063725.00     13901475.00
      2063424.96     13901675.03
#Sta/Elev= 30
  4722.3 1310.47  4754.7 1307.53  4761.4 1304.65  4776.2 1301.17  4791.0 1300.76
  4797.7 1298.54  4808.5 1296.90  4815.2 1293.88  4830.0 1289.62  4839.5 1287.47
  4844.9 1288.15  4862.4 1284.10  4869.1 1281.24  4883.9 1278.53  4898.7 1277.33
  4945.1 1276.96  4967.2 1275.95  4980.2 1275.74  4980.4 1275.24  4984.2 1275.74
  5077.2 1277.44  5107.3 1279.66  5158.0 1286.66  5185.4 1290.35  5215.4 1296.69
  5221.5 1296.79  5251.5 1301.72  5308.6 1307.44  5338.9 1312.40  5352.2 1312.79
#Mann=7,-1,0
  4722.3    0.07       0  4945.1   0.035       0  4967.2    0.07       0
  4980.2    0.05       0  4984.2    0.07       0  5158.0   0.035       0
  5338.9    0.07       0
Bank Sta=4980.2,4984.2
Exp/Cntr=0.3,0.1

Type RM Length L Ch R = 1,3299,473,473,473
BEGIN DESCRIPTION:
Stream0084_DS 7.0
END DESCRIPTION:
XS GIS Cut Line= 3
      2064216.18     13901170.94      2063525.00     13901125.00
      2063224.97     13901325.02
#Sta/Elev= 30
  4306.9 1323.97  4398.3 1322.68  4467.7 1317.42  4472.7 1318.30  4498.5 1316.61
  4518.5 1316.58  4598.7 1311.87  4709.0 1308.25  4744.9 1303.03  4829.2 1294.47
  4869.3 1285.47  4902.9 1280.90  4919.3 1278.00  4969.5 1273.21  4987.6 1266.85
  4987.8 1266.35  4991.6 1266.85  4997.1 1268.98  5013.1 1270.05  5064.2 1270.07
  5082.0 1268.57  5118.9 1270.61  5166.4 1273.74  5208.4 1280.58  5252.0 1289.98
  5265.5 1296.17  5274.5 1298.81  5316.6 1305.46  5331.6 1309.93  5360.2 1313.67
#Mann=7,-1,0
  4306.9    0.12       0  4744.9   0.035       0  4902.9    0.12       0
  4987.6    0.05       0  4991.6    0.12       0  5082.0   0.035       0
  5118.9    0.07       0
Bank Sta=4987.6,4991.6
Exp/Cntr=0.3,0.1

Type RM Length L Ch R = 1,2826,474,474,474
BEGIN DESCRIPTION:
Stream0084_DS 6.0
END DESCRIPTION:
XS GIS Cut Line= 3
      2063874.97     13901024.97      2063575.00     13900725.00
      2063352.41     13900645.75
#Sta/Elev= 30
  4575.4 1303.47  4578.9 1303.47  4589.5 1300.70  4617.8 1297.26  4661.4 1285.74
  4688.8 1280.50  4716.8 1275.34  4773.3 1267.48  4787.5 1266.29  4815.8 1265.42
  4957.2 1264.24  4985.5 1262.80  4996.1 1260.31  5007.7 1259.50  5008.0 1259.00
  5011.7 1259.50  5020.9 1260.91  5031.5 1264.00  5052.7 1278.87  5071.4 1285.35
  5076.7 1291.80  5084.5 1294.11  5092.0 1295.30  5107.5 1298.80  5127.0 1300.53
  5138.4 1304.18  5189.4 1310.43  5225.5 1313.36  5231.8 1315.03  5235.9 1315.03
#Mann=6,-1,0
  4575.4    0.12       0  4661.4   0.035       0  4688.8    0.12       0
  5007.7    0.05       0  5011.7    0.12       0  5092.0    0.07       0
Bank Sta=5007.7,5011.7
Exp/Cntr=0.3,0.1

Type RM Length L Ch R = 1,2352,471,471,471
BEGIN DESCRIPTION:
Stream0084_DS 5.0
END DESCRIPTION:
XS GIS Cut Line= 3
      2064420.16     13900341.95      2063825.00     13900375.00
      2063388.56     13900519.44
#Sta/Elev= 30
  4404.4 1342.98  4449.6 1340.74  4499.7 1335.26  4554.3 1332.83  4569.8 1331.81
  4589.8 1322.83  4670.0 1323.67  4710.0 1322.73  4760.1 1318.02  4820.2 1316.00
  4890.3 1309.03  4900.3 1306.96  4930.4 1296.89  4980.4 1264.82  4998.0 1256.20
  5009.0 1255.11  5009.3 1254.61  5013.0 1255.11  5016.3 1258.09  5042.6 1259.75
  5107.1 1258.42  5143.2 1260.95  5211.9 1261.98  5232.2 1264.11  5295.4 1281.17
  5333.5 1295.29  5365.2 1301.47  5370.5 1300.93  5396.9 1309.00  5460.2 1315.07
#Mann=5,-1,0
  4404.4    0.07       0  4554.3    0.12       0  5009.0    0.05       0
  5013.0    0.12       0  5107.1    0.07       0
Bank Sta=5009,5013
Exp/Cntr=0.3,0.1

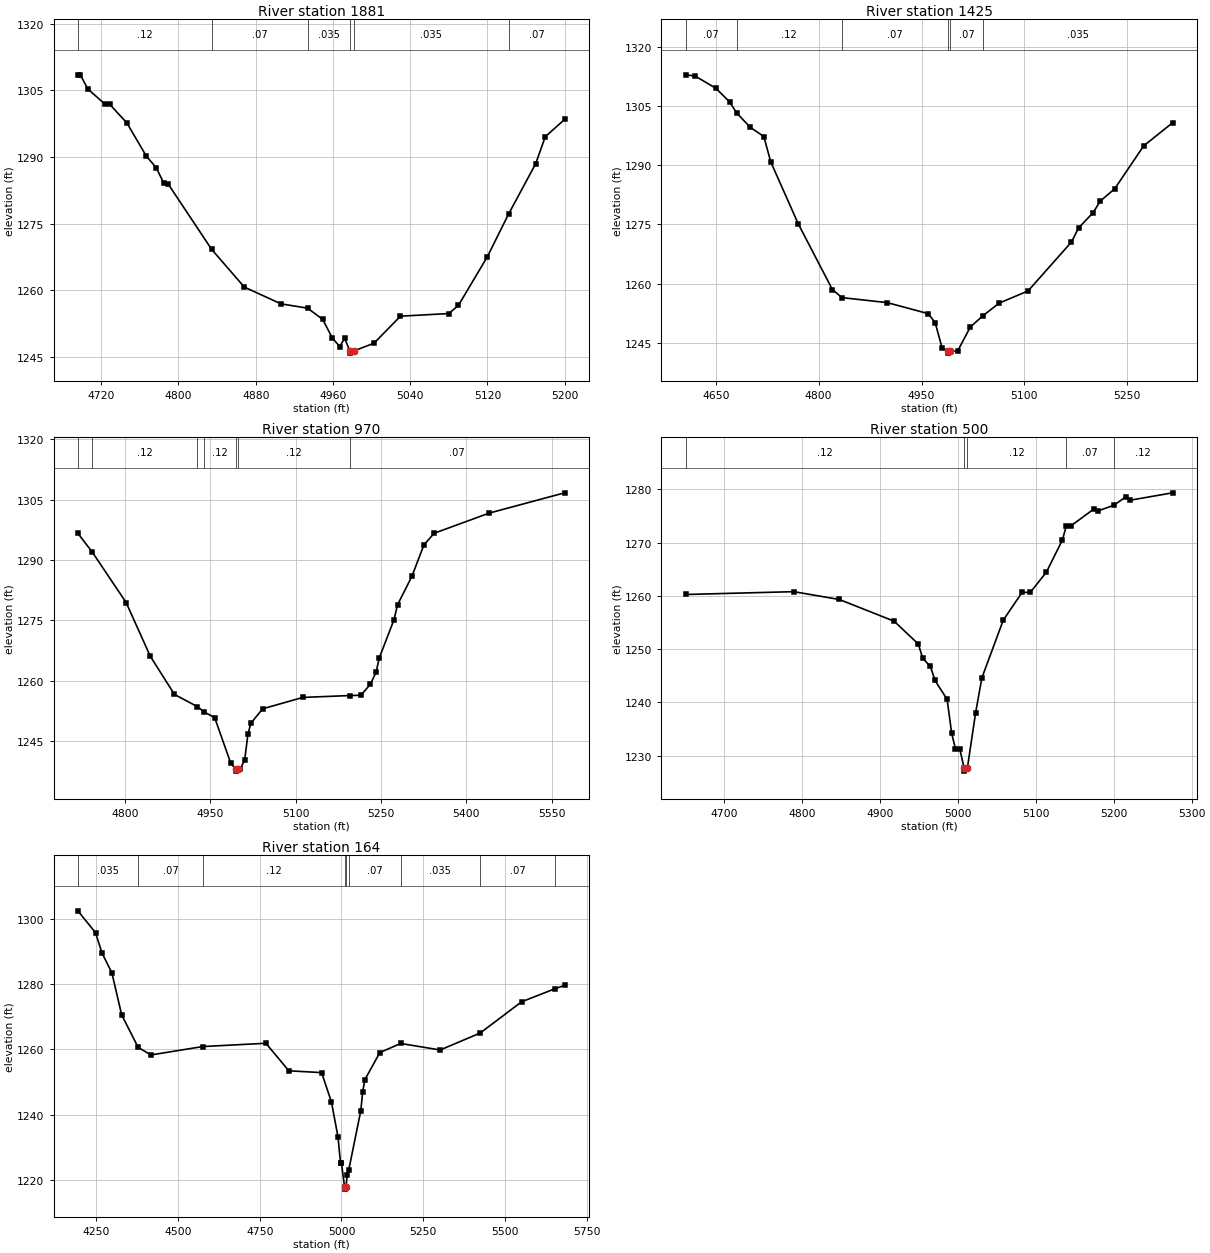
Type RM Length L Ch R = 1,1881,456,456,456
BEGIN DESCRIPTION:
Stream0084_DS 4.0
END DESCRIPTION:
XS GIS Cut Line= 3
      2063925.04     13900025.01      2063625.00     13899975.00
      2063424.98     13899975.00
#Sta/Elev= 30
  4695.8 1308.53  4698.4 1308.53  4706.0 1305.36  4723.7 1301.95  4728.8 1301.88
  4746.5 1297.70  4766.8 1290.17  4776.9 1287.61  4784.6 1284.20  4789.6 1283.83
  4834.3 1269.20  4868.2 1260.68  4906.2 1256.90  4933.7 1255.93  4949.3 1253.42
  4959.4 1249.21  4967.0 1247.28  4972.1 1249.09  4977.7 1246.29  4978.0 1245.79
  4981.7 1246.29  5002.5 1248.02  5030.0 1254.12  5080.0 1254.71  5090.0 1256.55
  5120.0 1267.53  5141.9 1277.12  5170.0 1288.48  5180.0 1294.59  5200.0 1298.47
#Mann=6,-1,0
  4695.8    0.12       0  4834.3    0.07       0  4933.7   0.035       0
  4977.7   0.035       0  4981.7   0.035       0  5141.9    0.07       0
Bank Sta=4977.7,4981.7
Exp/Cntr=0.3,0.1

Type RM Length L Ch R = 1,1425,455,455,455
BEGIN DESCRIPTION:
Stream0084_DS 3.0
END DESCRIPTION:
XS GIS Cut Line= 3
      2063968.78     13899578.06      2063575.00     13899575.00
      2063275.02     13899674.99
#Sta/Elev= 30
  4606.2 1312.95  4620.0 1312.63  4650.0 1309.54  4670.0 1306.10  4680.3 1303.30
  4700.0 1299.66  4720.0 1297.30  4730.0 1290.90  4770.0 1275.22  4820.0 1258.47
  4834.0 1256.43  4900.0 1255.16  4960.0 1252.36  4970.0 1250.05  4980.0 1243.69
  4988.0 1242.85  4988.2 1242.35  4992.0 1242.85  5002.6 1242.86  5021.1 1248.95
  5039.0 1251.75  5063.2 1255.03  5105.4 1258.12  5168.6 1270.51  5179.2 1274.13
  5200.3 1277.98  5210.8 1280.92  5231.9 1284.07  5274.1 1294.93  5316.2 1300.79
#Mann=6,-1,0
  4606.2    0.07       0  4680.3    0.12       0  4834.0    0.07       0
  4988.0    0.05       0  4992.0    0.07       0  5039.0   0.035       0
Bank Sta=4988,4992
Exp/Cntr=0.3,0.1

Type RM Length L Ch R = 1,970,470,470,470
BEGIN DESCRIPTION:
Stream0084_DS 2.0
END DESCRIPTION:
XS GIS Cut Line= 3
      2063924.99     13899374.99      2063725.00     13899175.00
      2063179.41     13899000.99
#Sta/Elev= 30
  4717.2 1296.62  4742.6 1291.94  4802.0 1279.41  4844.5 1266.03  4886.9 1256.55
  4927.2 1253.51  4939.4 1252.15  4957.6 1250.79  4985.9 1239.43  4994.5 1237.96
  4994.7 1237.46  4998.5 1237.96  5002.7 1237.96  5010.5 1240.32  5016.1 1246.69
  5021.4 1249.40  5042.0 1252.97  5112.7 1255.80  5194.8 1256.26  5214.6 1256.33
  5231.0 1259.02  5241.4 1262.08  5246.8 1265.57  5272.9 1275.15  5279.0 1278.82
  5304.4 1285.96  5325.4 1293.74  5343.4 1296.64  5440.0 1301.65  5572.7 1306.70
#Mann=7,-1,0
  4717.2    0.07       0  4742.6    0.12       0  4927.2    0.07       0
  4939.4    0.12       0  4994.5    0.05       0  4998.5    0.12       0
  5194.8    0.07       0
Bank Sta=4994.5,4998.5
Exp/Cntr=0.3,0.1

Type RM Length L Ch R = 1,500,336,336,336
BEGIN DESCRIPTION:
Stream0084_DS 1.0
END DESCRIPTION:
XS GIS Cut Line= 3
      2064003.48     13899074.56      2063825.00     13898775.00
      2063558.25     13898706.13
#Sta/Elev= 30
  4651.3 1260.25  4789.8 1260.78  4848.2 1259.31  4918.5 1255.23  4949.4 1250.95
  4955.2 1248.25  4965.0 1246.73  4970.8 1244.12  4986.4 1240.55  4992.2 1234.20
  4997.1 1231.27  5002.6 1231.27  5008.3 1227.58  5008.6 1227.08  5012.3 1227.58
  5022.9 1238.02  5031.0 1244.60  5058.4 1255.43  5082.6 1260.66  5093.0 1260.63
  5113.6 1264.42  5134.3 1270.50  5139.1 1273.07  5144.9 1273.11  5175.2 1276.37
  5180.4 1275.97  5200.4 1277.02  5215.9 1278.62  5221.0 1277.95  5275.5 1279.34
#Mann=5,-1,0
  4651.3    0.12       0  5008.3    0.05       0  5012.3    0.12       0
  5139.1    0.07       0  5200.4    0.12       0
Bank Sta=5008.3,5012.3
Exp/Cntr=0.3,0.1

Type RM Length L Ch R = 1,164,0,0,0
BEGIN DESCRIPTION:
Stream0084_DS 0.0
END DESCRIPTION:
XS GIS Cut Line= 4
      2064065.29     13899328.74      2064011.10     13898524.46
      2063839.48     13898452.17      2063370.60     13898614.80
#Sta/Elev= 30
  4193.9 1302.56  4247.8 1295.86  4267.7 1289.61  4297.9 1283.50  4327.9 1270.59
  4378.2 1260.65  4417.2 1258.31  4575.8 1260.89  4768.9 1261.90  4839.1 1253.45
  4939.3 1252.89  4969.4 1243.87  4989.4 1233.17  4997.2 1225.13  5000.0 1225.13
  5009.8 1217.62  5010.0 1217.12  5013.8 1217.62  5017.5 1221.46  5022.2 1222.95
  5059.2 1241.21  5064.7 1246.86  5071.7 1250.75  5117.5 1259.05  5181.0 1261.84
  5301.9 1259.84  5423.9 1265.02  5551.0 1274.63  5654.1 1278.69  5682.5 1279.66
#Mann=9,-1,0
  4193.9   0.035       0  4378.2    0.07       0  4575.8    0.12       0
  5009.8    0.05       0  5013.8    0.12       0  5022.2    0.07       0
  5181.0   0.035       0  5423.9    0.07       0  5654.1    0.12       0
Bank Sta=5009.8,5013.8
Exp/Cntr=0.3,0.1

Chan Stop Cuts=-1