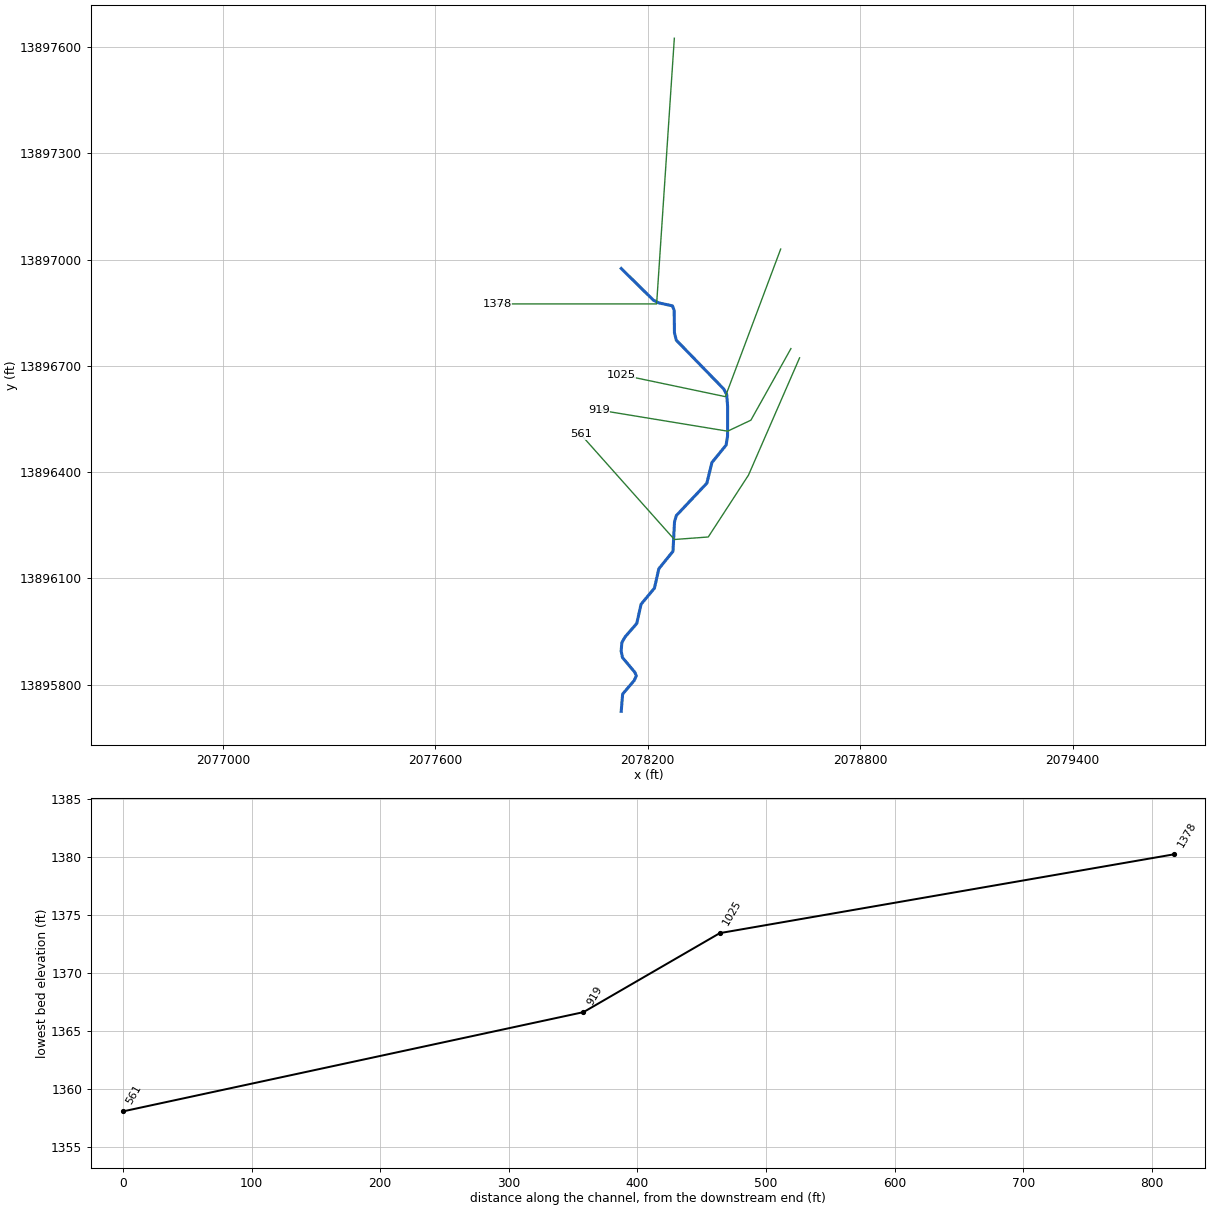
--- Stream0085_DS.prj (project) ---

Proj Title=Stream0085_DS Base Level Engineering
Current Plan=p01
Default Exp/Contr=0.3,0.1
English Units
Geom File=g01
Flow File=f01
Plan File=p01
BEGIN DESCRIPTION:
Stream0085_DS
END DESCRIPTION:

--- Stream0085_DS.p01 (plan) ---

Plan Title=Multiple Run
Short Identifier=Multiple
Geom File=g01
Flow File=f01
Subcritical Flow
K Sum by GR= 0
Std Step Tol= 0.01
Critical Tol= 0.01
Num of Std Step Trials= 20
Max Error Tol= 0.3
Flow Tol Ratio= 0.001
Split Flow NTrial= 30
Split Flow Tol= 0.02
Split Flow Ratio= 0.02
Log Output Level= 0
Friction Slope Method= 1
Unsteady Friction Slope Method= 2
Unsteady Bridges Friction Slope Method= 1
Parabolic Critical Depth
Global Vel Dist=  1 , 1 , 1
Global Log Level= 0
CheckData=True
Encroach Param= -1, 0, 0, 0
BEGIN DESCRIPTION:
Multiple Run
END DESCRIPTION:

--- Stream0085_DS.f01 (steady flow) ---

Flow Title=Multiple
Number of Profiles=7
Profile Names=10-year,25-year,50-year,1pct_min,100-year,1pct_plu,500-year
River Rch & RM= Stream0085_DS,Reach-1,1378
     330     511     668     426     849    1694    1351
Boundary for River Rch & Prof#=Stream0085_DS,Reach-1,1
Up Type=0
Dn Type=3
Dn Slope=0.005
Boundary for River Rch & Prof#=Stream0085_DS,Reach-1,2
Up Type=0
Dn Type=3
Dn Slope=0.005
Boundary for River Rch & Prof#=Stream0085_DS,Reach-1,3
Up Type=0
Dn Type=3
Dn Slope=0.005
Boundary for River Rch & Prof#=Stream0085_DS,Reach-1,4
Up Type=0
Dn Type=3
Dn Slope=0.005
Boundary for River Rch & Prof#=Stream0085_DS,Reach-1,5
Up Type=0
Dn Type=3
Dn Slope=0.005
Boundary for River Rch & Prof#=Stream0085_DS,Reach-1,6
Up Type=0
Dn Type=3
Dn Slope=0.005
Boundary for River Rch & Prof#=Stream0085_DS,Reach-1,7
Up Type=0
Dn Type=3
Dn Slope=0.005

--- Stream0085_DS.g01 (geometry) ---

Geom Title=Existing Conditions

River Reach=Stream0085_DS,Reach-1
Reach XY= 30
      2078125.00     13896975.00      2078215.62     13896885.85
      2078231.12     13896877.83      2078269.75     13896869.54
      2078274.60     13896856.36      2078275.31     13896793.43
      2078280.55     13896772.63      2078414.53     13896634.80
      2078422.95     13896619.14      2078425.55     13896585.19
      2078425.32     13896502.16      2078421.26     13896476.56
      2078381.14     13896427.17      2078366.84     13896368.95
      2078280.54     13896277.42      2078275.53     13896259.78
      2078271.17     13896176.59      2078231.12     13896127.18
      2078218.92     13896072.80      2078181.08     13896027.20
      2078168.84     13895972.80      2078135.52     13895934.54
      2078126.83     13895918.88      2078124.81     13895895.13
      2078128.58     13895876.64      2078163.55     13895834.90
      2078167.65     13895824.97      2078161.50     13895811.73
      2078129.00     13895773.64      2078125.00     13895725.00

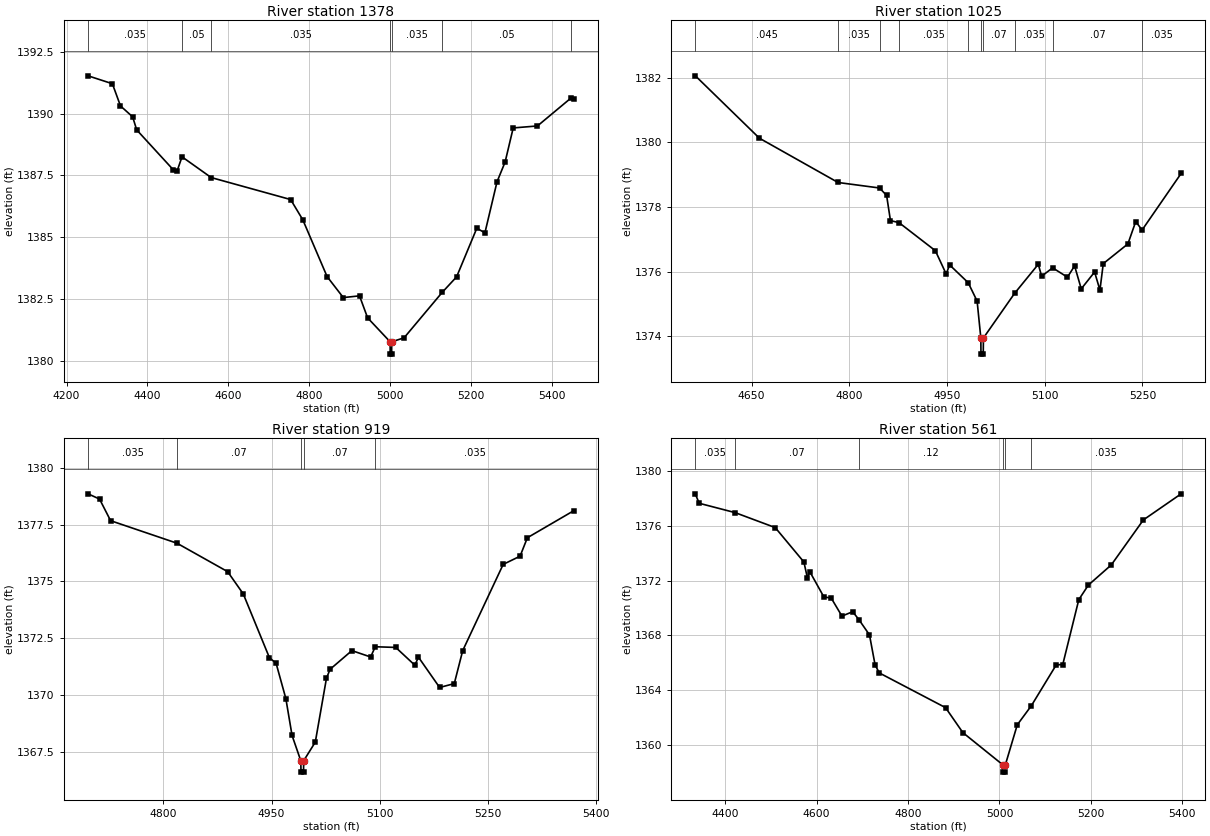
Type RM Length L Ch R = 1,1378,353,353,353
BEGIN DESCRIPTION:
Stream0085_DS 2.0
END DESCRIPTION:
XS GIS Cut Line= 3
      2078275.00     13897625.00      2078225.00     13896875.00
      2077774.97     13896875.00
#Sta/Elev= 30
  4253.3 1391.53  4313.4 1391.21  4333.5 1390.31  4363.5 1389.87  4373.6 1389.34
  4463.8 1387.73  4473.8 1387.69  4485.7 1388.25  4557.9 1387.41  4754.4 1386.52
  4784.5 1385.70  4844.6 1383.40  4884.7 1382.55  4924.8 1382.62  4944.8 1381.73
  5000.5 1380.76  5000.7 1380.26  5004.2 1380.26  5004.5 1380.76  5035.0 1380.92
  5129.3 1382.76  5165.0 1383.39  5215.0 1385.36  5235.0 1385.17  5265.0 1387.24
  5285.0 1388.04  5305.0 1389.42  5365.0 1389.50  5447.2 1390.62  5455.0 1390.60
#Mann=7,-1,0
  4253.3   0.035       0  4485.7    0.05       0  4557.9   0.035       0
  5000.5   0.035       0  5004.5   0.035       0  5129.3    0.05       0
  5447.2    0.07       0
Bank Sta=5000.5,5004.5
Exp/Cntr=0.3,0.1

Type RM Length L Ch R = 1,1025,106,106,106
BEGIN DESCRIPTION:
Stream0085_DS 1.0
END DESCRIPTION:
XS GIS Cut Line= 3
      2078575.35     13897029.84      2078419.11     13896613.19
      2078125.01     13896675.00
#Sta/Elev= 30
  4563.8 1382.06  4662.1 1380.13  4782.8 1378.76  4846.4 1378.59  4857.3 1378.36
  4863.2 1377.58  4876.2 1377.52  4932.1 1376.65  4948.7 1375.93  4954.0 1376.21
  4982.5 1375.66  4996.2 1375.09  5001.9 1373.95  5002.1 1373.45  5005.6 1373.45
  5005.9 1373.95  5053.7 1375.33  5090.1 1376.23  5095.2 1375.86  5112.1 1376.12
  5134.8 1375.83  5145.8 1376.18  5156.0 1375.47  5176.5 1375.99  5184.7 1375.43
  5189.8 1376.25  5227.6 1376.86  5239.6 1377.55  5249.4 1377.29  5309.3 1379.04
#Mann=10,-1,0
  4563.8   0.045       0  4782.8   0.035       0  4846.4   0.045       0
  4876.2   0.035       0  4982.5    0.07       0  5001.9    0.05       0
  5005.9    0.07       0  5053.7   0.035       0  5112.1    0.07       0
  5249.4   0.035       0
Bank Sta=5001.9,5005.9
Exp/Cntr=0.3,0.1

Type RM Length L Ch R = 1,919,358,358,358
BEGIN DESCRIPTION:
Stream0085_DS 0.5
END DESCRIPTION:
XS GIS Cut Line= 4
      2078604.31     13896748.91      2078491.22     13896546.76
      2078425.51     13896515.74      2078061.49     13896575.54
#Sta/Elev= 30
  4695.7 1378.85  4711.6 1378.62  4726.9 1377.67  4818.9 1376.68  4889.1 1375.43
  4910.8 1374.45  4947.0 1371.65  4956.3 1371.40  4969.8 1369.85  4978.4 1368.23
  4990.5 1367.12  4990.8 1366.62  4994.3 1366.62  4994.5 1367.12  5010.6 1367.94
  5026.1 1370.75  5031.1 1371.14  5061.3 1371.96  5087.3 1371.68  5093.7 1372.13
  5122.1 1372.10  5148.5 1371.32  5153.6 1371.67  5182.9 1370.34  5203.2 1370.51
  5214.9 1371.96  5271.0 1375.75  5294.4 1376.11  5304.5 1376.92  5368.9 1378.11
#Mann=5,-1,0
  4695.7   0.035       0  4818.9    0.07       0  4990.5    0.05       0
  4994.5    0.07       0  5093.7   0.035       0
Bank Sta=4990.5,4994.5
Exp/Cntr=0.3,0.1

Type RM Length L Ch R = 1,561,0,0,0
BEGIN DESCRIPTION:
Stream0085_DS 0.0
END DESCRIPTION:
XS GIS Cut Line= 5
      2078628.67     13896722.75      2078484.49     13896391.81
      2078370.84     13896217.06      2078275.14     13896209.94
      2078010.70     13896506.72
#Sta/Elev= 30
  4334.6 1378.29  4343.1 1377.63  4421.6 1376.95  4509.3 1375.86  4572.1 1373.35
  4579.6 1372.21  4585.1 1372.64  4615.7 1370.81  4631.9 1370.72  4655.3 1369.41
  4678.8 1369.73  4692.5 1369.15  4715.6 1368.04  4727.8 1365.86  4737.0 1365.27
  4882.0 1362.74  4919.9 1360.92  5008.6 1358.54  5008.8 1358.04  5012.3 1358.04
  5012.6 1358.54  5039.0 1361.49  5069.6 1362.87  5124.3 1365.86  5138.5 1365.88
  5173.6 1370.61  5194.5 1371.67  5244.7 1373.14  5314.9 1376.42  5397.5 1378.32
#Mann=6,-1,0
  4334.6   0.035       0  4421.6    0.07       0  4692.5    0.12       0
  5008.6    0.05       0  5012.6    0.12       0  5069.6   0.035       0
Bank Sta=5008.6,5012.6
Exp/Cntr=0.3,0.1

Chan Stop Cuts=-1