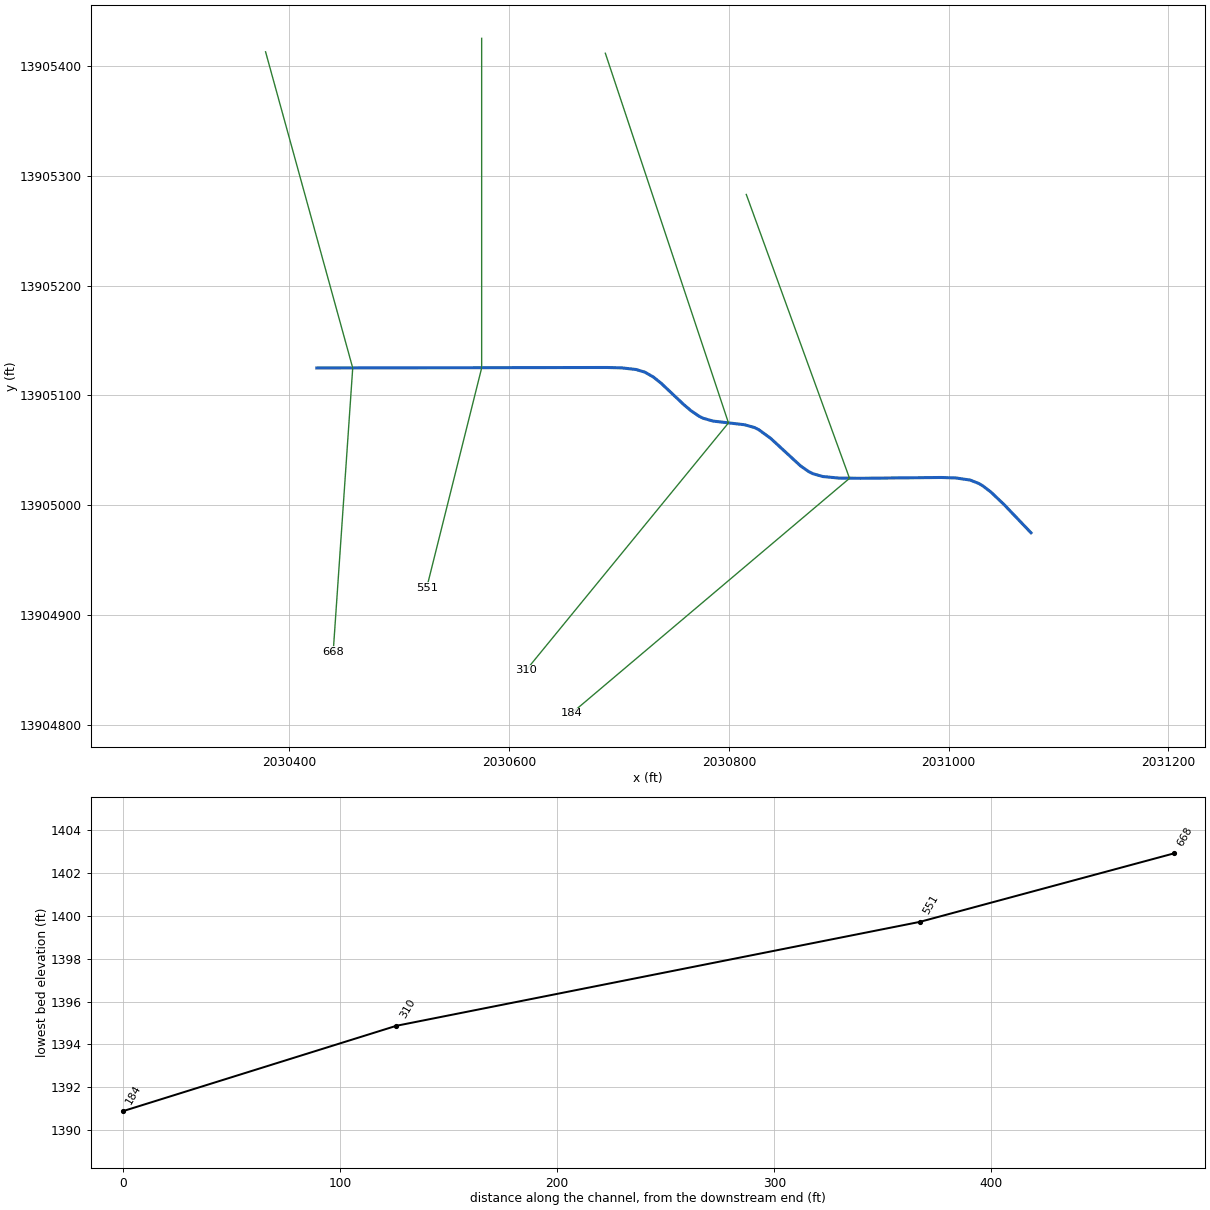
--- Stream0086_DS.prj (project) ---

Proj Title=Stream0086_DS Base Level Engineering
Current Plan=p01
Default Exp/Contr=0.3,0.1
English Units
Geom File=g01
Flow File=f01
Plan File=p01
BEGIN DESCRIPTION:
Stream0086_DS
END DESCRIPTION:

--- Stream0086_DS.p01 (plan) ---

Plan Title=Multiple Run
Short Identifier=Multiple
Geom File=g01
Flow File=f01
Subcritical Flow
K Sum by GR= 0
Std Step Tol= 0.01
Critical Tol= 0.01
Num of Std Step Trials= 20
Max Error Tol= 0.3
Flow Tol Ratio= 0.001
Split Flow NTrial= 30
Split Flow Tol= 0.02
Split Flow Ratio= 0.02
Log Output Level= 0
Friction Slope Method= 1
Unsteady Friction Slope Method= 2
Unsteady Bridges Friction Slope Method= 1
Parabolic Critical Depth
Global Vel Dist=  1 , 1 , 1
Global Log Level= 0
CheckData=True
Encroach Param= -1, 0, 0, 0
BEGIN DESCRIPTION:
Multiple Run
END DESCRIPTION:

--- Stream0086_DS.f01 (steady flow) ---

Flow Title=Multiple
Number of Profiles=7
Profile Names=10-year,25-year,50-year,1pct_min,100-year,1pct_plu,500-year
River Rch & RM= Stream0086_DS,Reach-1,668
     325     511     675     435     868    1732    1414
Boundary for River Rch & Prof#=Stream0086_DS,Reach-1,1
Up Type=0
Dn Type=3
Dn Slope=0.005
Boundary for River Rch & Prof#=Stream0086_DS,Reach-1,2
Up Type=0
Dn Type=3
Dn Slope=0.005
Boundary for River Rch & Prof#=Stream0086_DS,Reach-1,3
Up Type=0
Dn Type=3
Dn Slope=0.005
Boundary for River Rch & Prof#=Stream0086_DS,Reach-1,4
Up Type=0
Dn Type=3
Dn Slope=0.005
Boundary for River Rch & Prof#=Stream0086_DS,Reach-1,5
Up Type=0
Dn Type=3
Dn Slope=0.005
Boundary for River Rch & Prof#=Stream0086_DS,Reach-1,6
Up Type=0
Dn Type=3
Dn Slope=0.005
Boundary for River Rch & Prof#=Stream0086_DS,Reach-1,7
Up Type=0
Dn Type=3
Dn Slope=0.005

--- Stream0086_DS.g01 (geometry) ---

Geom Title=Existing Conditions

River Reach=Stream0086_DS,Reach-1
Reach XY= 30
      2030425.00     13905125.00      2030688.82     13905125.45
      2030702.32     13905125.11      2030715.35     13905123.64
      2030723.45     13905121.25      2030731.08     13905116.91
      2030738.17     13905111.28      2030758.51     13905092.10
      2030765.47     13905086.14      2030772.82     13905081.12
      2030776.74     13905079.19      2030785.69     13905076.67
      2030814.31     13905073.33      2030823.26     13905070.81
      2030827.18     13905068.88      2030838.04     13905060.96
      2030865.33     13905035.80      2030872.65     13905030.71
      2030876.56     13905028.75      2030885.50     13905026.21
      2030899.92     13905024.81      2030919.84     13905024.60
      2030993.32     13905025.34      2031006.77     13905024.88
      2031019.62     13905022.99      2031027.58     13905019.85
      2031031.35     13905017.56      2031038.50     13905012.08
      2031050.29     13905000.88      2031075.00     13904975.00

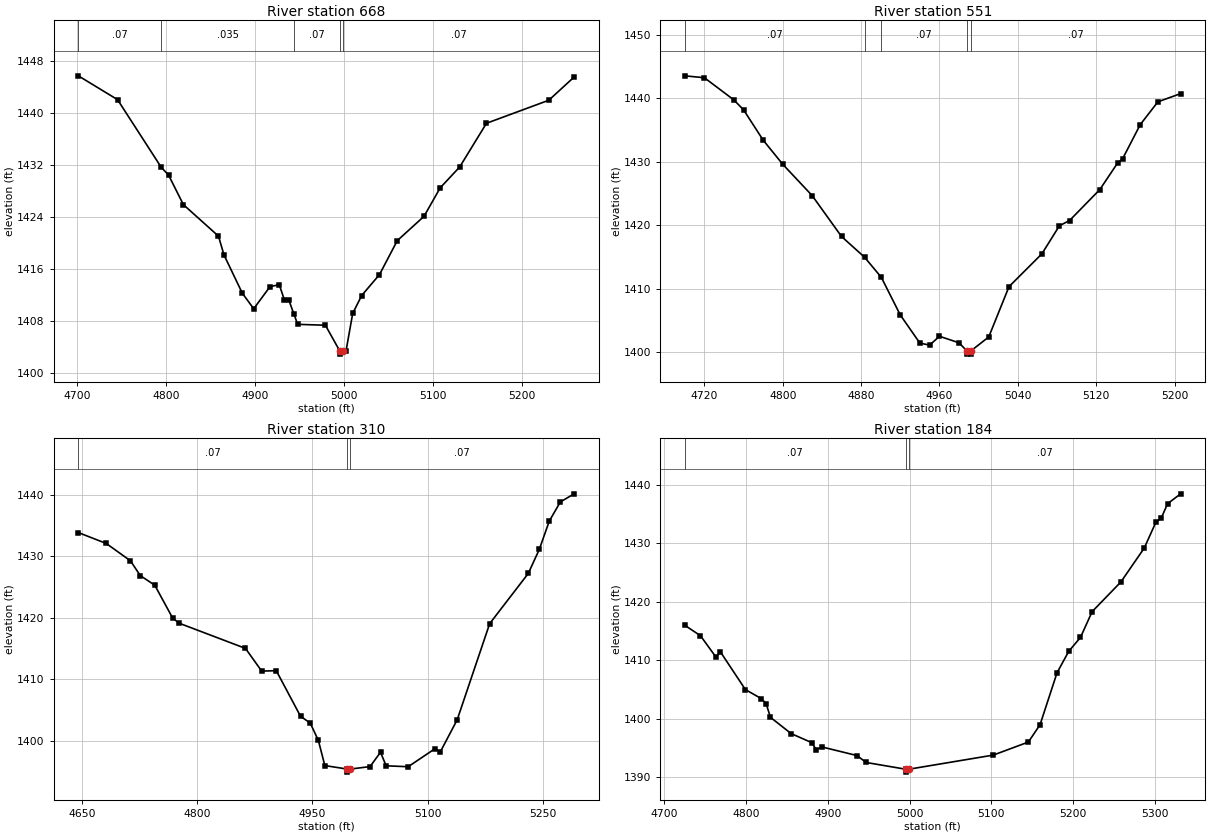
Type RM Length L Ch R = 1,668,117,117,117
BEGIN DESCRIPTION:
Stream0086_DS 3.0
END DESCRIPTION:
XS GIS Cut Line= 3
      2030378.33     13905412.78      2030457.65     13905125.01
      2030439.89     13904866.62
#Sta/Elev= 30
  4701.5 1445.77  4745.6 1442.10  4794.8 1431.66  4802.9 1430.50  4819.6 1425.93
  4859.1 1421.07  4865.2 1418.20  4885.9 1412.28  4898.7 1409.89  4917.0 1413.29
  4927.4 1413.60  4933.1 1411.29  4938.3 1411.18  4943.9 1409.07  4948.1 1407.49
  4979.3 1407.35  4995.4 1403.40  4995.7 1402.90  4999.4 1403.40  5002.5 1403.40
  5010.0 1409.17  5020.1 1411.93  5040.1 1415.15  5060.1 1420.38  5090.2 1424.13
  5108.4 1428.52  5130.3 1431.73  5160.4 1438.46  5230.5 1442.01  5259.0 1445.59
#Mann=5,-1,0
  4701.5    0.07       0  4794.8   0.035       0  4943.9    0.07       0
  4995.4    0.05       0  4999.4    0.07       0
Bank Sta=4995.4,4999.4
Exp/Cntr=0.3,0.1

Type RM Length L Ch R = 1,551,241,241,241
BEGIN DESCRIPTION:
Stream0086_DS 2.0
END DESCRIPTION:
XS GIS Cut Line= 3
      2030575.00     13905425.03      2030575.00     13905125.00
      2030525.00     13904924.99
#Sta/Elev= 30
  4700.0 1443.50  4720.0 1443.20  4750.0 1439.72  4760.0 1438.15  4780.0 1433.38
  4800.0 1429.58  4830.0 1424.66  4860.0 1418.22  4883.5 1414.96  4900.6 1411.80
  4920.0 1405.87  4940.0 1401.44  4950.0 1401.13  4960.0 1402.52  4980.0 1401.49
  4988.0 1400.21  4988.3 1399.71  4991.8 1399.71  4992.0 1400.21  5010.3 1402.41
  5031.0 1410.33  5064.5 1415.48  5082.5 1419.92  5092.8 1420.73  5123.7 1425.60
  5141.8 1429.77  5146.9 1430.43  5165.0 1435.83  5183.0 1439.41  5206.2 1440.70
#Mann=5,-1,0
  4700.0    0.07       0  4883.5   0.035       0  4900.6    0.07       0
  4988.0    0.05       0  4992.0    0.07       0
Bank Sta=4988,4992
Exp/Cntr=0.3,0.1

Type RM Length L Ch R = 1,310,126,126,126
BEGIN DESCRIPTION:
Stream0086_DS 1.0
END DESCRIPTION:
XS GIS Cut Line= 3
      2030687.57     13905411.47      2030799.63     13905075.00
      2030615.45     13904849.89
#Sta/Elev= 30
  4645.4 1433.88  4681.7 1432.11  4713.3 1429.28  4726.0 1426.88  4744.9 1425.31
  4768.2 1419.96  4776.5 1419.13  4863.0 1415.02  4884.1 1411.32  4903.1 1411.39
  4934.7 1403.96  4947.3 1402.86  4957.9 1400.03  4966.3 1395.94  4995.4 1395.37
  4995.7 1394.87  4999.4 1395.37  5025.2 1395.77  5038.8 1398.11  5046.1 1395.90
  5074.8 1395.75  5109.9 1398.70  5116.4 1398.11  5138.6 1403.39  5180.9 1419.05
  5231.2 1427.23  5245.5 1431.14  5258.5 1435.74  5272.9 1438.87  5290.9 1440.19
#Mann=3,-1,0
  4645.4    0.07       0  4995.4    0.05       0  4999.4    0.07       0
Bank Sta=4995.4,4999.4
Exp/Cntr=0.3,0.1

Type RM Length L Ch R = 1,184,0,0,0
BEGIN DESCRIPTION:
Stream0086_DS 0.0
END DESCRIPTION:
XS GIS Cut Line= 3
      2030815.86     13905282.93      2030909.83     13905024.59
      2030656.75     13904810.64
#Sta/Elev= 30
  4725.1 1415.98  4744.2 1414.21  4763.3 1410.53  4768.6 1411.45  4799.2 1405.00
  4818.7 1403.45  4824.5 1402.61  4829.8 1400.26  4855.1 1397.48  4880.3 1395.93
  4885.7 1394.75  4893.2 1395.18  4935.7 1393.72  4946.8 1392.54  4995.1 1391.39
  4995.4 1390.89  4999.1 1391.39  5102.3 1393.80  5145.2 1396.03  5159.5 1398.99
  5180.3 1407.88  5194.6 1411.54  5208.9 1413.90  5223.2 1418.32  5258.3 1423.38
  5286.9 1429.18  5301.2 1433.61  5307.7 1434.31  5315.5 1436.77  5331.4 1438.45
#Mann=3,-1,0
  4725.1    0.07       0  4995.1    0.05       0  4999.1    0.07       0
Bank Sta=4995.1,4999.1
Exp/Cntr=0.3,0.1

Chan Stop Cuts=-1