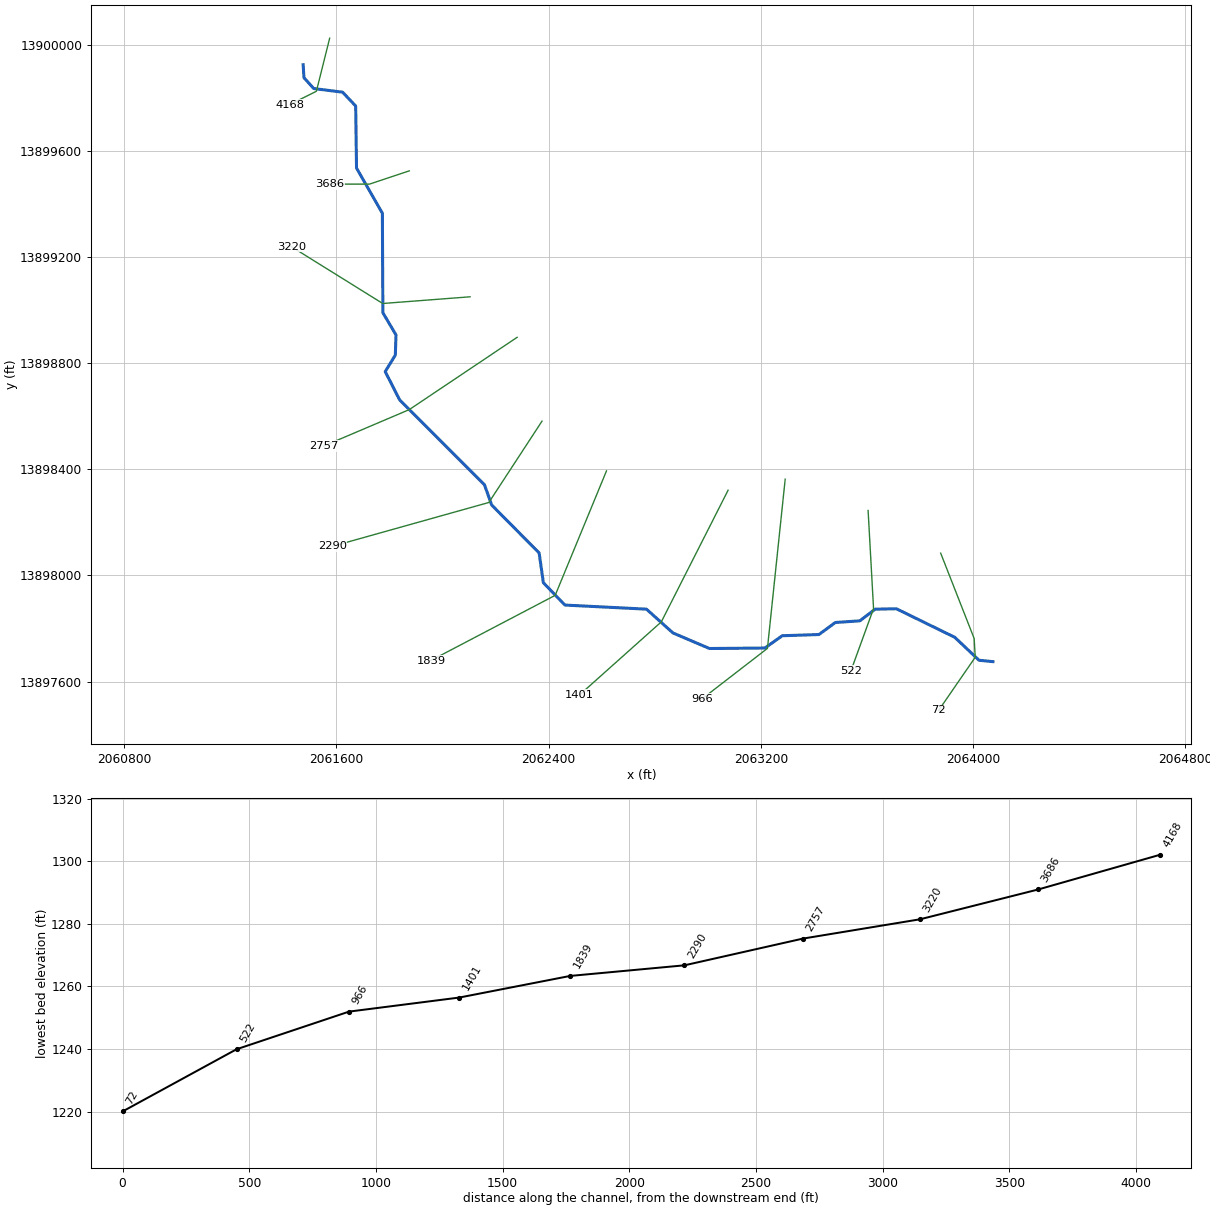
--- Stream0087_DS.prj (project) ---

Proj Title=Stream0087_DS Base Level Engineering
Current Plan=p01
Default Exp/Contr=0.3,0.1
English Units
Geom File=g01
Flow File=f01
Plan File=p01
BEGIN DESCRIPTION:
Stream0087_DS
END DESCRIPTION:

--- Stream0087_DS.p01 (plan) ---

Plan Title=Multiple Run
Short Identifier=Multiple
Geom File=g01
Flow File=f01
Subcritical Flow
K Sum by GR= 0
Std Step Tol= 0.01
Critical Tol= 0.01
Num of Std Step Trials= 20
Max Error Tol= 0.3
Flow Tol Ratio= 0.001
Split Flow NTrial= 30
Split Flow Tol= 0.02
Split Flow Ratio= 0.02
Log Output Level= 0
Friction Slope Method= 1
Unsteady Friction Slope Method= 2
Unsteady Bridges Friction Slope Method= 1
Parabolic Critical Depth
Global Vel Dist=  1 , 1 , 1
Global Log Level= 0
CheckData=True
Encroach Param= -1, 0, 0, 0
BEGIN DESCRIPTION:
Multiple Run
END DESCRIPTION:

--- Stream0087_DS.f01 (steady flow) ---

Flow Title=Multiple
Number of Profiles=7
Profile Names=10-year,25-year,50-year,1pct_min,100-year,1pct_plu,500-year
River Rch & RM= Stream0087_DS,Reach-1,4168
     230     348     449     282     563    1124     874
River Rch & RM= Stream0087_DS,Reach-1,3686
     713    1172    1596    1055    2105    4201    3619
Boundary for River Rch & Prof#=Stream0087_DS,Reach-1,1
Up Type=0
Dn Type=3
Dn Slope=0.005
Boundary for River Rch & Prof#=Stream0087_DS,Reach-1,2
Up Type=0
Dn Type=3
Dn Slope=0.005
Boundary for River Rch & Prof#=Stream0087_DS,Reach-1,3
Up Type=0
Dn Type=3
Dn Slope=0.005
Boundary for River Rch & Prof#=Stream0087_DS,Reach-1,4
Up Type=0
Dn Type=3
Dn Slope=0.005
Boundary for River Rch & Prof#=Stream0087_DS,Reach-1,5
Up Type=0
Dn Type=3
Dn Slope=0.005
Boundary for River Rch & Prof#=Stream0087_DS,Reach-1,6
Up Type=0
Dn Type=3
Dn Slope=0.005
Boundary for River Rch & Prof#=Stream0087_DS,Reach-1,7
Up Type=0
Dn Type=3
Dn Slope=0.005

--- Stream0087_DS.g01 (geometry) ---

Geom Title=Existing Conditions

River Reach=Stream0087_DS,Reach-1
Reach XY= 30
      2061475.00     13899925.00      2061478.12     13899875.99
      2061514.91     13899835.27      2061623.75     13899821.49
      2061673.03     13899769.35      2061676.20     13899535.50
      2061773.64     13899365.35      2061775.52     13898990.22
      2061824.94     13898906.66      2061822.51     13898830.49
      2061784.41     13898768.38      2061838.61     13898661.79
      2062158.35     13898341.67      2062185.78     13898265.32
      2062364.48     13898084.79      2062380.52     13897972.56
      2062461.65     13897888.36      2062769.14     13897872.94
      2062868.95     13897783.16      2063006.65     13897724.60
      2063215.34     13897726.38      2063280.94     13897772.73
      2063419.06     13897777.27      2063480.98     13897822.64
      2063573.40     13897828.86      2063630.97     13897872.83
      2063711.03     13897874.46      2063931.05     13897766.86
      2064022.49     13897680.33      2064075.00     13897675.00

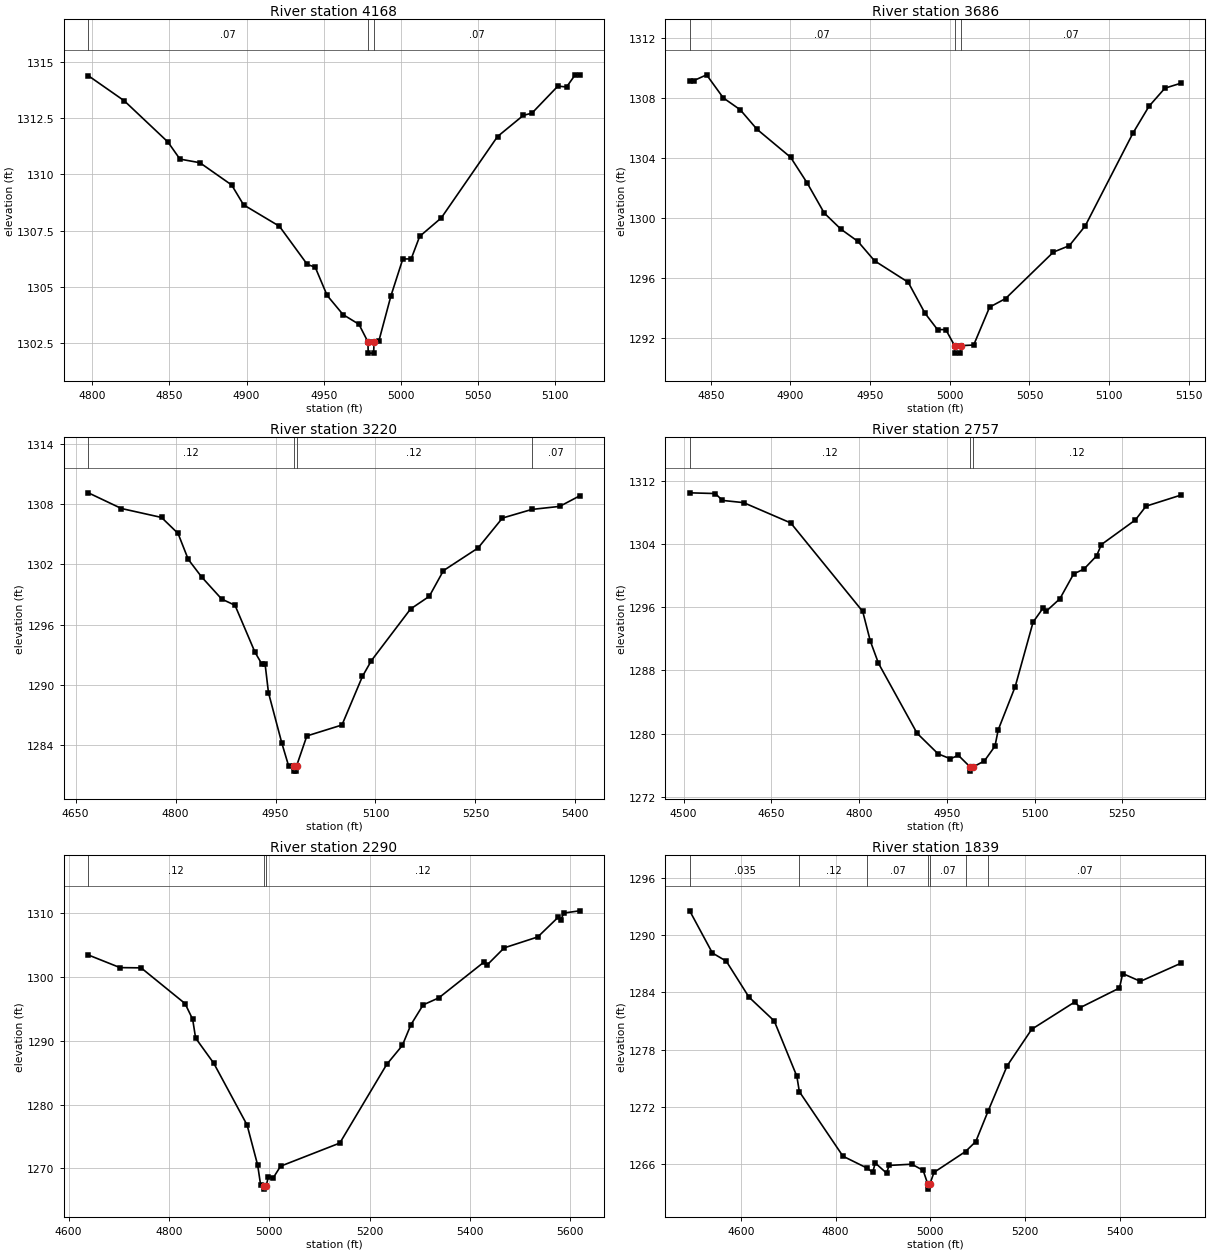
Type RM Length L Ch R = 1,4168,482,482,482
BEGIN DESCRIPTION:
Stream0087_DS 9.0
END DESCRIPTION:
XS GIS Cut Line= 3
      2061575.00     13900025.00      2061525.00     13899825.00
      2061424.97     13899774.98
#Sta/Elev= 30
  4797.6 1314.38  4820.8 1313.27  4849.1 1311.44  4856.9 1310.68  4869.8 1310.52
  4890.4 1309.53  4898.1 1308.65  4921.3 1307.70  4939.3 1306.01  4944.5 1305.88
  4952.2 1304.63  4962.5 1303.78  4972.8 1303.35  4978.6 1302.57  4978.8 1302.07
  4982.3 1302.07  4982.6 1302.57  4985.7 1302.61  4993.5 1304.61  5001.2 1306.25
  5006.6 1306.25  5012.1 1307.25  5026.1 1308.07  5062.5 1311.68  5079.2 1312.62
  5084.8 1312.72  5101.6 1313.92  5107.2 1313.88  5112.8 1314.42  5115.6 1314.42
#Mann=3,-1,0
  4797.6    0.07       0  4978.6    0.05       0  4982.6    0.07       0
Bank Sta=4978.6,4982.6
Exp/Cntr=0.3,0.1

Type RM Length L Ch R = 1,3686,466,466,466
BEGIN DESCRIPTION:
Stream0087_DS 8.0
END DESCRIPTION:
XS GIS Cut Line= 3
      2061875.04     13899525.01      2061725.00     13899475.00
      2061574.96     13899475.00
#Sta/Elev= 30
  4836.8 1309.15  4839.5 1309.15  4847.4 1309.53  4857.9 1307.99  4868.5 1307.20
  4879.0 1305.90  4900.1 1304.03  4910.6 1302.30  4921.2 1300.31  4931.7 1299.23
  4942.3 1298.42  4952.8 1297.12  4973.9 1295.69  4984.4 1293.63  4992.3 1292.53
  4997.5 1292.53  5003.0 1291.46  5003.2 1290.96  5006.7 1290.96  5007.0 1291.46
  5015.0 1291.50  5025.0 1294.03  5035.0 1294.60  5065.0 1297.70  5075.0 1298.13
  5085.0 1299.45  5115.0 1305.65  5125.0 1307.43  5135.0 1308.64  5145.0 1308.97
#Mann=3,-1,0
  4836.8    0.07       0  5003.0    0.05       0  5007.0    0.07       0
Bank Sta=5003,5007
Exp/Cntr=0.3,0.1

Type RM Length L Ch R = 1,3220,463,463,463
BEGIN DESCRIPTION:
Stream0087_DS 7.0
END DESCRIPTION:
XS GIS Cut Line= 3
      2062104.47     13899050.28      2061775.00     13899025.00
      2061429.71     13899239.82
#Sta/Elev= 30
  4669.1 1309.13  4718.7 1307.57  4778.9 1306.68  4803.7 1305.09  4819.0 1302.51
  4839.1 1300.76  4869.2 1298.56  4889.2 1297.94  4919.3 1293.25  4929.3 1292.12
  4934.3 1292.12  4939.4 1289.25  4959.4 1284.24  4969.5 1281.99  4977.5 1281.94
  4977.7 1281.44  4981.2 1281.44  4981.5 1281.94  4997.0 1284.94  5049.7 1286.03
  5080.4 1290.86  5093.8 1292.43  5152.6 1297.57  5180.7 1298.83  5202.0 1301.39
  5253.9 1303.64  5290.5 1306.62  5334.8 1307.48  5376.4 1307.78  5406.2 1308.82
#Mann=4,-1,0
  4669.1    0.12       0  4977.5    0.05       0  4981.5    0.12       0
  5334.8    0.07       0
Bank Sta=4977.5,4981.5
Exp/Cntr=0.3,0.1

Type RM Length L Ch R = 1,2757,467,467,467
BEGIN DESCRIPTION:
Stream0087_DS 6.0
END DESCRIPTION:
XS GIS Cut Line= 3
      2062281.58     13898897.52      2061875.00     13898625.00
      2061552.43     13898487.80
#Sta/Elev= 30
  4510.3 1310.46  4554.0 1310.37  4566.4 1309.50  4602.5 1309.22  4683.1 1306.65
  4806.2 1295.46  4819.2 1291.71  4833.2 1288.89  4899.2 1280.05  4935.2 1277.44
  4956.2 1276.82  4969.7 1277.26  4990.3 1275.76  4990.5 1275.26  4994.3 1275.76
  5014.3 1276.55  5032.4 1278.42  5037.9 1280.47  5067.0 1285.95  5097.6 1294.11
  5114.3 1295.85  5119.7 1295.46  5143.4 1297.06  5167.0 1300.21  5184.5 1300.81
  5206.2 1302.49  5214.3 1303.91  5272.5 1307.03  5290.7 1308.77  5350.3 1310.17
#Mann=3,-1,0
  4510.3    0.12       0  4990.3    0.05       0  4994.3    0.12       0
Bank Sta=4990.3,4994.3
Exp/Cntr=0.3,0.1

Type RM Length L Ch R = 1,2290,451,451,451
BEGIN DESCRIPTION:
Stream0087_DS 5.0
END DESCRIPTION:
XS GIS Cut Line= 3
      2062375.31     13898581.53      2062175.00     13898275.00
      2061584.90     13898109.66
#Sta/Elev= 30
  4639.3 1303.47  4702.4 1301.49  4744.5 1301.45  4832.0 1295.85  4847.2 1293.39
  4853.1 1290.43  4889.3 1286.48  4955.7 1276.79  4976.8 1270.49  4982.8 1267.32
  4989.9 1267.23  4990.2 1266.73  4993.9 1267.23  4997.9 1268.66  5008.1 1268.54
  5022.5 1270.33  5140.5 1273.96  5233.9 1286.29  5265.1 1289.27  5282.1 1292.51
  5306.6 1295.64  5337.8 1296.74  5428.9 1302.42  5434.1 1301.90  5468.2 1304.59
  5535.1 1306.30  5575.7 1309.39  5580.9 1308.96  5587.0 1310.05  5618.3 1310.40
#Mann=3,-1,0
  4639.3    0.12       0  4989.9    0.05       0  4993.9    0.12       0
Bank Sta=4989.9,4993.9
Exp/Cntr=0.3,0.1

Type RM Length L Ch R = 1,1839,438,438,438
BEGIN DESCRIPTION:
Stream0087_DS 4.0
END DESCRIPTION:
XS GIS Cut Line= 3
      2062618.35     13898394.00      2062425.00     13897925.00
      2061956.36     13897679.38
#Sta/Elev= 30
  4492.2 1292.58  4540.1 1288.15  4569.4 1287.29  4617.3 1283.51  4670.6 1281.01
  4718.3 1275.20  4723.6 1273.58  4815.6 1266.80  4867.3 1265.53  4878.3 1265.09
  4883.7 1266.09  4907.6 1265.02  4913.0 1265.83  4960.9 1265.96  4984.8 1265.31
  4994.8 1263.84  4995.0 1263.34  4998.8 1263.84  5007.7 1265.10  5074.2 1267.29
  5095.9 1268.34  5121.7 1271.52  5162.1 1276.30  5214.0 1280.14  5304.3 1282.99
  5316.6 1282.42  5399.1 1284.47  5405.9 1285.99  5443.3 1285.17  5528.6 1287.07
#Mann=7,-1,0
  4492.2   0.035       0  4723.6    0.12       0  4867.3    0.07       0
  4994.8    0.05       0  4998.8    0.07       0  5074.2    0.12       0
  5121.7    0.07       0
Bank Sta=4994.8,4998.8
Exp/Cntr=0.3,0.1

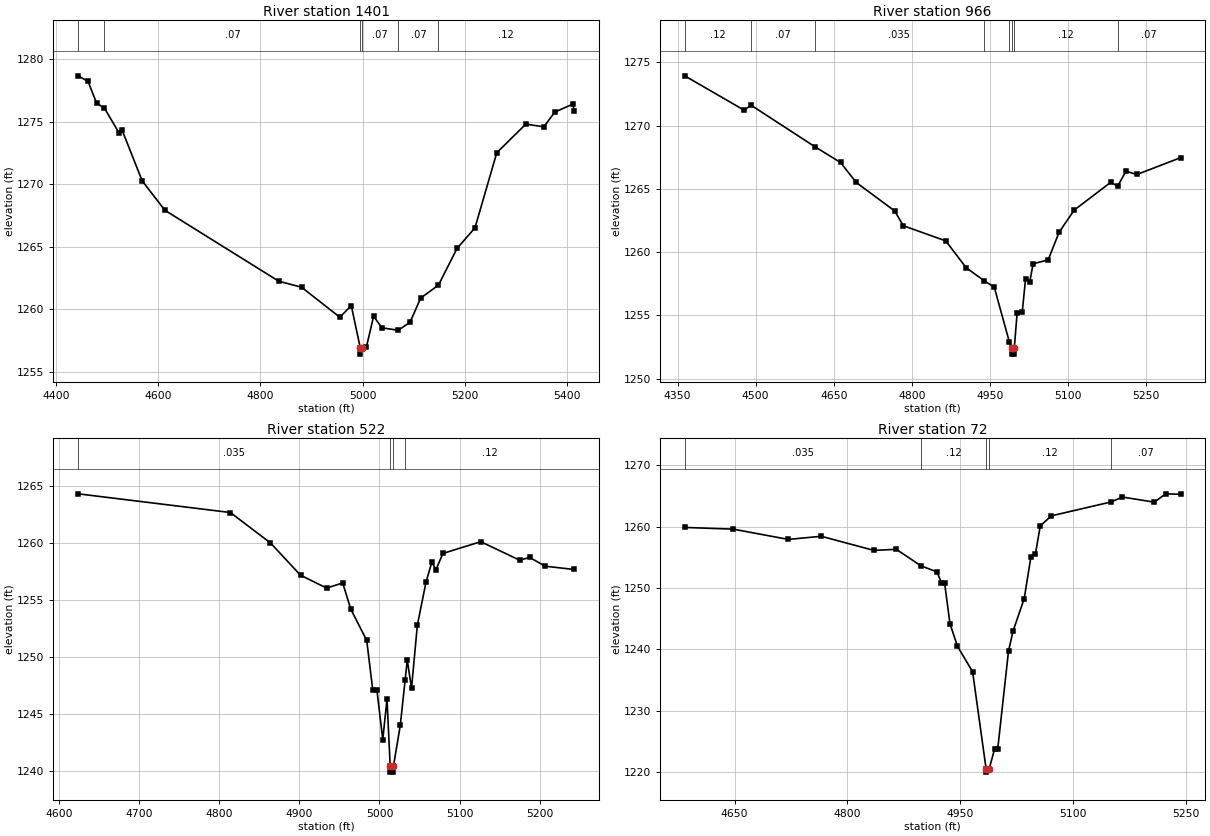
Type RM Length L Ch R = 1,1401,435,435,435
BEGIN DESCRIPTION:
Stream0087_DS 3.0
END DESCRIPTION:
XS GIS Cut Line= 3
      2063076.71     13898321.13      2062825.00     13897825.00
      2062516.75     13897549.58
#Sta/Elev= 30
  4443.7 1278.68  4463.0 1278.23  4479.6 1276.50  4494.9 1276.10  4524.1 1274.08
  4529.8 1274.31  4568.7 1270.29  4613.2 1267.93  4835.8 1262.26  4880.4 1261.78
  4955.2 1259.38  4977.6 1260.31  4995.2 1256.93  4995.5 1256.43  4999.2 1256.93
  5007.1 1256.98  5021.3 1259.46  5037.6 1258.53  5069.4 1258.34  5092.4 1258.97
  5113.3 1260.91  5148.1 1261.95  5184.4 1264.88  5219.5 1266.53  5262.1 1272.53
  5318.9 1274.82  5354.1 1274.60  5375.5 1275.78  5410.9 1276.42  5413.4 1275.90
#Mann=6,-1,0
  4443.7    0.12       0  4494.9    0.07       0  4995.2    0.05       0
  4999.2    0.07       0  5069.4    0.07       0  5148.1    0.12       0
Bank Sta=4995.2,4999.2
Exp/Cntr=0.3,0.1

Type RM Length L Ch R = 1,966,444,444,444
BEGIN DESCRIPTION:
Stream0087_DS 2.0
END DESCRIPTION:
XS GIS Cut Line= 3
      2063291.97     13898362.74      2063225.00     13897725.00
      2062978.52     13897534.61
#Sta/Elev= 30
  4363.6 1273.94  4477.6 1271.23  4491.4 1271.61  4613.6 1268.34  4663.0 1267.09
  4693.1 1265.51  4767.0 1263.26  4783.6 1262.09  4865.2 1260.89  4904.3 1258.77
  4938.3 1257.76  4958.3 1257.24  4987.5 1252.87  4992.8 1252.44  4993.0 1251.94
  4996.5 1251.94  4996.8 1252.44  5002.3 1255.22  5012.1 1255.29  5018.4 1257.86
  5026.6 1257.67  5032.9 1259.08  5061.9 1259.39  5082.7 1261.56  5111.7 1263.32
  5182.3 1265.53  5195.3 1265.21  5211.3 1266.40  5232.3 1266.14  5316.3 1267.47
#Mann=8,-1,0
  4363.6    0.12       0  4491.4    0.07       0  4613.6   0.035       0
  4938.3    0.07       0  4987.5    0.12       0  4992.8    0.05       0
  4996.8    0.12       0  5195.3    0.07       0
Bank Sta=4992.8,4996.8
Exp/Cntr=0.3,0.1

Type RM Length L Ch R = 1,522,450,450,450
BEGIN DESCRIPTION:
Stream0087_DS 1.0
END DESCRIPTION:
XS GIS Cut Line= 3
      2063604.48     13898244.75      2063625.00     13897875.00
      2063539.92     13897641.01
#Sta/Elev= 30
  4623.8 1264.33  4813.8 1262.69  4863.9 1260.02  4901.4 1257.19  4934.0 1256.06
  4954.1 1256.51  4964.1 1254.22  4984.1 1251.46  4991.6 1247.12  4996.8 1247.12
  5004.1 1242.77  5009.4 1246.31  5013.4 1240.41  5013.6 1239.91  5017.1 1239.91
  5017.4 1240.41  5026.0 1244.02  5032.0 1247.97  5034.7 1249.75  5040.0 1247.27
  5047.3 1252.80  5058.0 1256.55  5065.3 1258.32  5070.6 1257.68  5079.2 1259.10
  5126.5 1260.13  5175.0 1258.51  5187.6 1258.75  5206.9 1257.98  5243.1 1257.69
#Mann=4,-1,0
  4623.8   0.035       0  5013.4   0.035       0  5017.4   0.035       0
  5032.0    0.12       0
Bank Sta=5013.4,5017.4
Exp/Cntr=0.3,0.1

Type RM Length L Ch R = 1,72,0,0,0
BEGIN DESCRIPTION:
Stream0087_DS 0.0
END DESCRIPTION:
XS GIS Cut Line= 4
      2063877.97     13898084.13      2064004.23     13897762.23
      2064008.31     13897691.62      2063870.22     13897491.19
#Sta/Elev= 30
  4583.5 1259.86  4648.1 1259.58  4721.4 1257.91  4765.2 1258.42  4835.3 1256.12
  4865.1 1256.30  4897.6 1253.63  4919.3 1252.61  4925.1 1250.87  4929.3 1250.87
  4936.5 1244.19  4946.5 1240.50  4966.6 1236.38  4984.6 1220.53  4984.8 1220.03
  4988.6 1220.53  4995.8 1223.76  5000.0 1223.76  5014.4 1239.75  5020.5 1243.01
  5035.3 1248.29  5044.2 1255.07  5050.2 1255.54  5056.6 1260.10  5071.2 1261.74
  5151.3 1264.02  5165.9 1264.81  5208.5 1263.97  5223.4 1265.33  5243.4 1265.26
#Mann=5,-1,0
  4583.5   0.035       0  4897.6    0.12       0  4984.6    0.05       0
  4988.6    0.12       0  5151.3    0.07       0
Bank Sta=4984.6,4988.6
Exp/Cntr=0.3,0.1

Chan Stop Cuts=-1