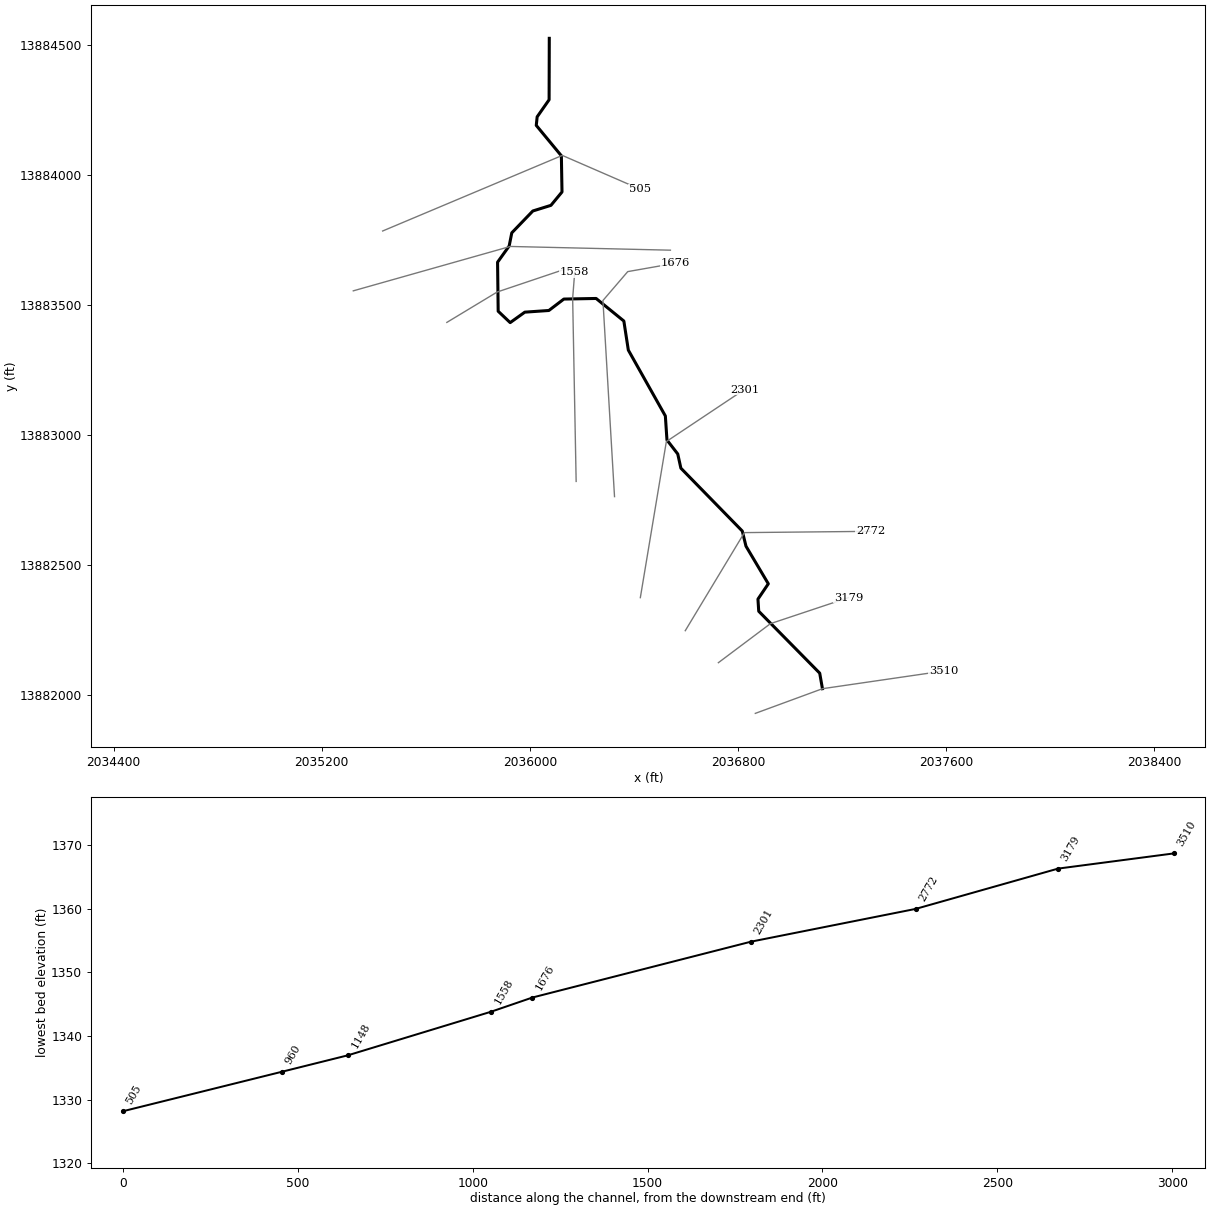
--- Stream0088_DS.prj (project) ---

Proj Title=Stream0088_DS Base Level Engineering
Current Plan=p01
Default Exp/Contr=0.3,0.1
English Units
Geom File=g01
Flow File=f01
Plan File=p01
BEGIN DESCRIPTION:
Stream0088_DS
END DESCRIPTION:

--- Stream0088_DS.p01 (plan) ---

Plan Title=Multiple Run
Short Identifier=Multiple
Geom File=g01
Flow File=f01
Subcritical Flow
K Sum by GR= 0
Std Step Tol= 0.01
Critical Tol= 0.01
Num of Std Step Trials= 20
Max Error Tol= 0.3
Flow Tol Ratio= 0.001
Split Flow NTrial= 30
Split Flow Tol= 0.02
Split Flow Ratio= 0.02
Log Output Level= 0
Friction Slope Method= 1
Unsteady Friction Slope Method= 2
Unsteady Bridges Friction Slope Method= 1
Parabolic Critical Depth
Global Vel Dist=  1 , 1 , 1
Global Log Level= 0
CheckData=True
Encroach Param= -1, 0, 0, 0
BEGIN DESCRIPTION:
Multiple Run
END DESCRIPTION:

--- Stream0088_DS.f01 (steady flow) ---

Flow Title=Multiple
Number of Profiles=7
Profile Names=10-year,25-year,50-year,1pct_min,100-year,1pct_plu,500-year
River Rch & RM= Stream0088_DS,Reach-1,3510
     770    1276    1746    1161    2316    4621    4024
River Rch & RM= Stream0088_DS,Reach-1,3179
     911    1521    2094    1399    2791    5568    4897
Boundary for River Rch & Prof#=Stream0088_DS,Reach-1,1
Up Type=0
Dn Type=3
Dn Slope=0.005
Boundary for River Rch & Prof#=Stream0088_DS,Reach-1,2
Up Type=0
Dn Type=3
Dn Slope=0.005
Boundary for River Rch & Prof#=Stream0088_DS,Reach-1,3
Up Type=0
Dn Type=3
Dn Slope=0.005
Boundary for River Rch & Prof#=Stream0088_DS,Reach-1,4
Up Type=0
Dn Type=3
Dn Slope=0.005
Boundary for River Rch & Prof#=Stream0088_DS,Reach-1,5
Up Type=0
Dn Type=3
Dn Slope=0.005
Boundary for River Rch & Prof#=Stream0088_DS,Reach-1,6
Up Type=0
Dn Type=3
Dn Slope=0.005
Boundary for River Rch & Prof#=Stream0088_DS,Reach-1,7
Up Type=0
Dn Type=3
Dn Slope=0.005

--- Stream0088_DS.g01 (geometry) ---

Geom Title=Existing Conditions

River Reach=Stream0088_DS,Reach-1
Reach XY= 30
      2037125.00     13882025.00      2037114.49     13882084.79
      2036880.11     13882322.71      2036877.10     13882369.36
      2036916.93     13882428.31      2036831.11     13882572.81
      2036816.86     13882631.06      2036580.83     13882872.70
      2036568.86     13882927.17      2036527.33     13882980.97
      2036521.17     13883073.42      2036378.83     13883326.59
      2036361.61     13883438.33      2036255.01     13883525.06
      2036130.94     13883522.75      2036073.40     13883478.85
      2035980.88     13883472.43      2035924.65     13883432.21
      2035878.53     13883475.99      2035876.20     13883664.50
      2035920.78     13883726.75      2035930.82     13883777.31
      2036011.78     13883861.37      2036081.38     13883883.02
      2036123.87     13883934.44      2036121.46     13884073.53
      2036024.96     13884190.34      2036028.34     13884223.25
      2036074.30     13884288.91      2036075.00     13884525.00

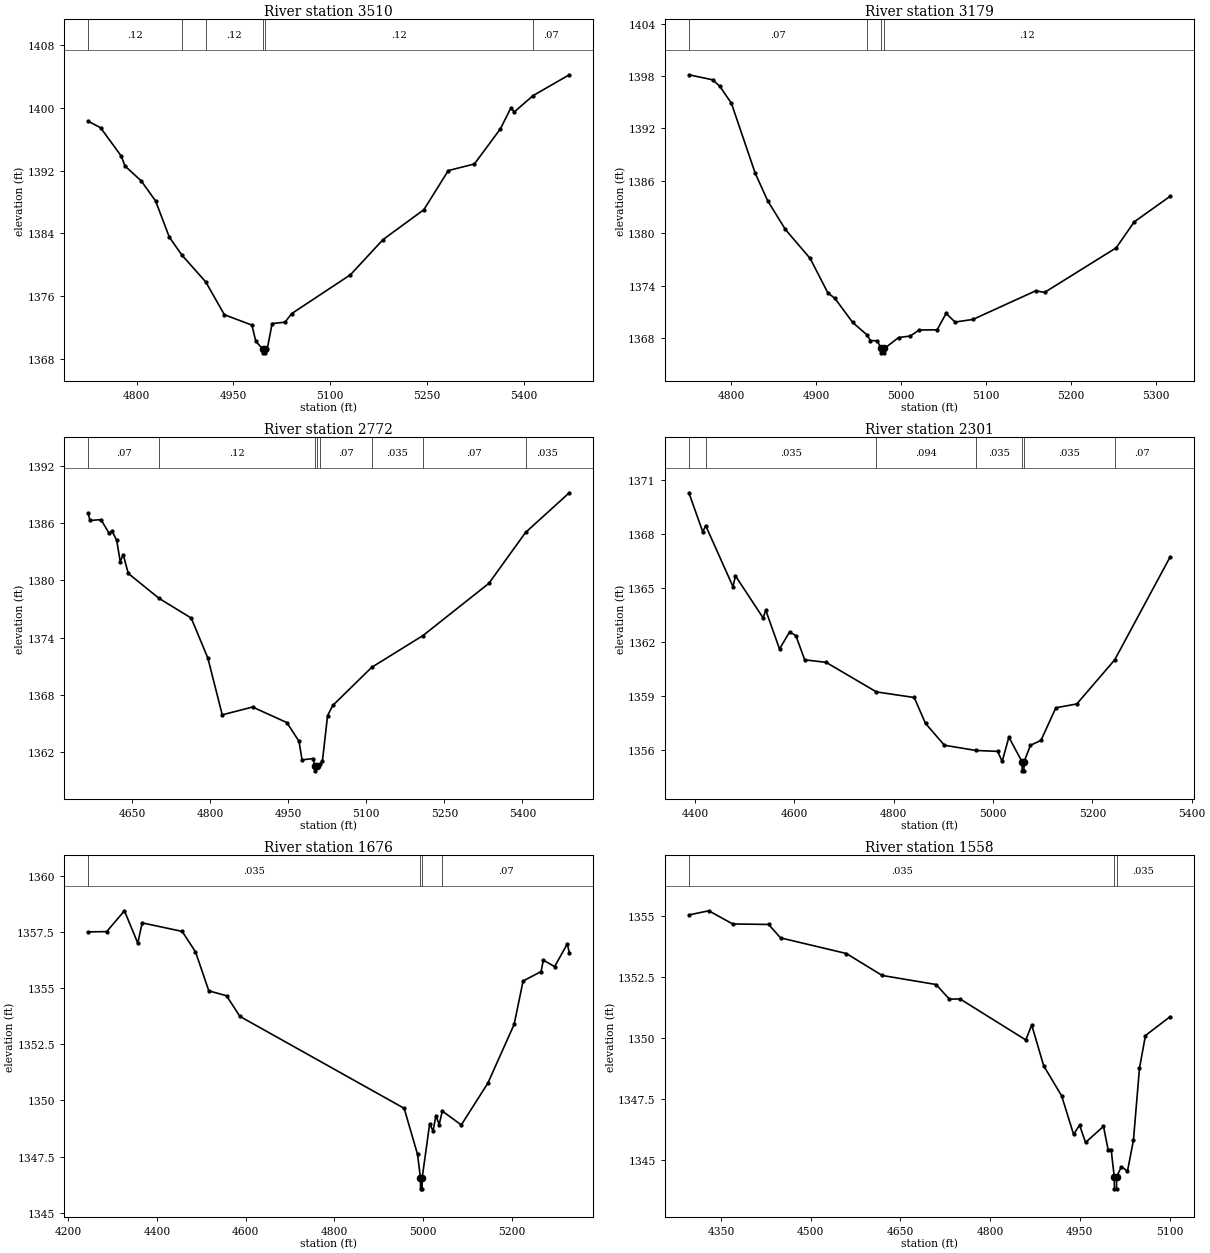
Type RM Length L Ch R = 1,3510,331,331,331
BEGIN DESCRIPTION:
Stream0088_DS 7.0
END DESCRIPTION:
XS GIS Cut Line= 3
      2036866.98     13881930.15      2037125.00     13882025.00
      2037590.48     13882092.88
#Sta/Elev= 30
  4725.1 1398.31  4744.3 1397.48  4776.3 1393.87  4782.1 1392.60  4807.3 1390.69
  4829.5 1388.14  4850.8 1383.52  4870.4 1381.21  4907.3 1377.79  4936.1 1373.61
  4978.7 1372.28  4984.8 1370.22  4995.3 1369.24  4995.6 1368.74  4999.1 1368.74
  4999.3 1369.24  5002.5 1369.24  5010.1 1372.48  5030.0 1372.65  5040.4 1373.75
  5131.4 1378.71  5181.9 1383.20  5245.1 1387.01  5283.0 1392.01  5323.4 1392.85
  5363.8 1397.35  5380.0 1400.03  5385.1 1399.49  5414.3 1401.58  5470.4 1404.24
#Mann=6,-1,0
  4725.1    0.12       0  4870.4    0.07       0  4907.3    0.12       0
  4995.3    0.05       0  4999.3    0.12       0  5414.3    0.07       0
Bank Sta=4995.3,4999.3
Exp/Cntr=0.3,0.1

Type RM Length L Ch R = 1,3179,407,407,407
BEGIN DESCRIPTION:
Stream0088_DS 6.0
END DESCRIPTION:
XS GIS Cut Line= 3
      2036725.03     13882125.02      2036925.00     13882275.00
      2037225.01     13882375.00
#Sta/Elev= 30
  4750.3 1398.14  4778.4 1397.56  4786.7 1396.82  4800.3 1394.89  4828.4 1386.87
  4843.0 1383.74  4863.8 1380.46  4893.0 1377.14  4913.8 1373.21  4922.1 1372.58
  4943.0 1369.83  4960.1 1368.38  4963.8 1367.76  4972.1 1367.72  4976.4 1366.85
  4976.6 1366.35  4980.1 1366.35  4980.4 1366.85  4997.1 1368.10  5010.8 1368.27
  5021.3 1368.96  5042.4 1368.98  5053.0 1370.86  5063.5 1369.87  5084.6 1370.17
  5158.4 1373.44  5168.9 1373.26  5253.2 1378.36  5274.3 1381.32  5316.5 1384.24
#Mann=4,-1,0
  4750.3    0.07       0  4960.1    0.12       0  4976.4    0.05       0
  4980.4    0.12       0
Bank Sta=4976.4,4980.4
Exp/Cntr=0.3,0.1

Type RM Length L Ch R = 1,2772,471,471,471
BEGIN DESCRIPTION:
Stream0088_DS 5.0
END DESCRIPTION:
XS GIS Cut Line= 3
      2036597.73     13882248.01      2036825.00     13882625.00
      2037309.48     13882629.93
#Sta/Elev= 30
  4565.4 1387.09  4568.8 1386.30  4590.1 1386.39  4605.6 1384.96  4611.5 1385.19
  4620.3 1384.20  4627.0 1381.99  4632.8 1382.71  4642.5 1380.74  4701.7 1378.12
  4763.5 1376.05  4795.4 1371.86  4823.1 1365.89  4881.3 1366.71  4947.2 1365.08
  4970.6 1363.12  4976.5 1361.16  4997.8 1361.30  5000.7 1360.51  5000.9 1360.01
  5004.7 1360.51  5011.9 1360.78  5015.6 1361.04  5025.6 1365.82  5035.6 1366.88
  5110.4 1370.88  5209.0 1374.22  5335.6 1379.70  5406.0 1385.04  5490.1 1389.21
#Mann=8,-1,0
  4565.4    0.07       0  4701.7    0.12       0  5000.7    0.05       0
  5004.7    0.12       0  5011.9    0.07       0  5110.4   0.035       0
  5209.0    0.07       0  5406.0   0.035       0
Bank Sta=5000.7,5004.7
Exp/Cntr=0.3,0.1

Type RM Length L Ch R = 1,2301,625,625,625
BEGIN DESCRIPTION:
Stream0088_DS 4.0
END DESCRIPTION:
XS GIS Cut Line= 3
      2036424.99     13882374.95      2036525.00     13882975.00
      2036825.02     13883175.01
#Sta/Elev= 30
  4387.4 1370.28  4415.3 1368.11  4421.2 1368.46  4476.2 1365.07  4481.2 1365.67
  4537.0 1363.33  4542.1 1363.77  4569.9 1361.61  4590.2 1362.56  4602.9 1362.35
  4620.6 1361.01  4663.7 1360.87  4765.0 1359.23  4841.1 1358.92  4863.9 1357.48
  4901.9 1356.27  4965.5 1355.98  5009.2 1355.93  5018.3 1355.37  5031.8 1356.72
  5058.3 1355.35  5058.6 1354.85  5062.1 1354.85  5062.3 1355.35  5075.3 1356.27
  5096.4 1356.54  5126.4 1358.35  5168.5 1358.56  5244.9 1361.01  5356.3 1366.71
#Mann=7,-1,0
  4387.4    0.07       0  4421.2   0.035       0  4765.0   0.094       0
  4965.5   0.035       0  5058.3   0.035       0  5062.3   0.035       0
  5244.9    0.07       0
Bank Sta=5058.3,5062.3
Exp/Cntr=0.3,0.1

Type RM Length L Ch R = 1,1676,118,118,118
BEGIN DESCRIPTION:
Stream0088_DS 3.5
END DESCRIPTION:
XS GIS Cut Line= 4
      2036325.76     13882763.32      2036281.21     13883517.20
      2036376.57     13883628.29      2036557.58     13883660.17
#Sta/Elev= 30
  4244.8 1357.52  4286.6 1357.53  4326.6 1358.46  4356.7 1357.02  4366.7 1357.92
  4456.9 1357.54  4486.9 1356.63  4517.0 1354.89  4557.0 1354.67  4587.1 1353.75
  4957.7 1349.65  4987.8 1347.60  4994.4 1346.56  4994.6 1346.06  4998.1 1346.06
  4998.4 1346.56  5015.2 1348.96  5022.9 1348.64  5029.4 1349.33  5036.6 1348.92
  5043.7 1349.53  5086.5 1348.91  5146.4 1350.77  5205.7 1353.39  5226.0 1355.33
  5266.6 1355.75  5271.6 1356.26  5297.1 1355.97  5325.9 1356.99  5330.2 1356.58
#Mann=4,-1,0
  4244.8   0.035       0  4994.4   0.035       0  4998.4   0.035       0
  5043.7    0.07       0
Bank Sta=4994.4,4998.4
Exp/Cntr=0.3,0.1

Type RM Length L Ch R = 1,1558,410,410,410
BEGIN DESCRIPTION:
Stream0088_DS 3.0
END DESCRIPTION:
XS GIS Cut Line= 3
      2036178.26     13882821.73      2036164.83     13883525.50
      2036172.74     13883625.99
#Sta/Elev= 30
  4296.1 1355.05  4329.4 1355.22  4369.4 1354.68  4429.4 1354.66  4449.4 1354.11
  4559.4 1353.47  4619.4 1352.57  4709.4 1352.20  4731.8 1351.60  4749.5 1351.61
  4859.5 1349.93  4869.5 1350.54  4889.5 1348.87  4919.5 1347.64  4939.5 1346.06
  4949.5 1346.44  4959.5 1345.73  4989.5 1346.39  4997.2 1345.44  5002.3 1345.44
  5007.5 1344.33  5007.8 1343.83  5011.3 1343.83  5011.5 1344.33  5019.6 1344.74
  5029.6 1344.55  5039.6 1345.82  5049.7 1348.77  5059.7 1350.11  5100.8 1350.88
#Mann=3,-1,0
  4296.1   0.035       0  5007.5   0.035       0  5011.5   0.035       0
Bank Sta=5007.5,5011.5
Exp/Cntr=0.3,0.1

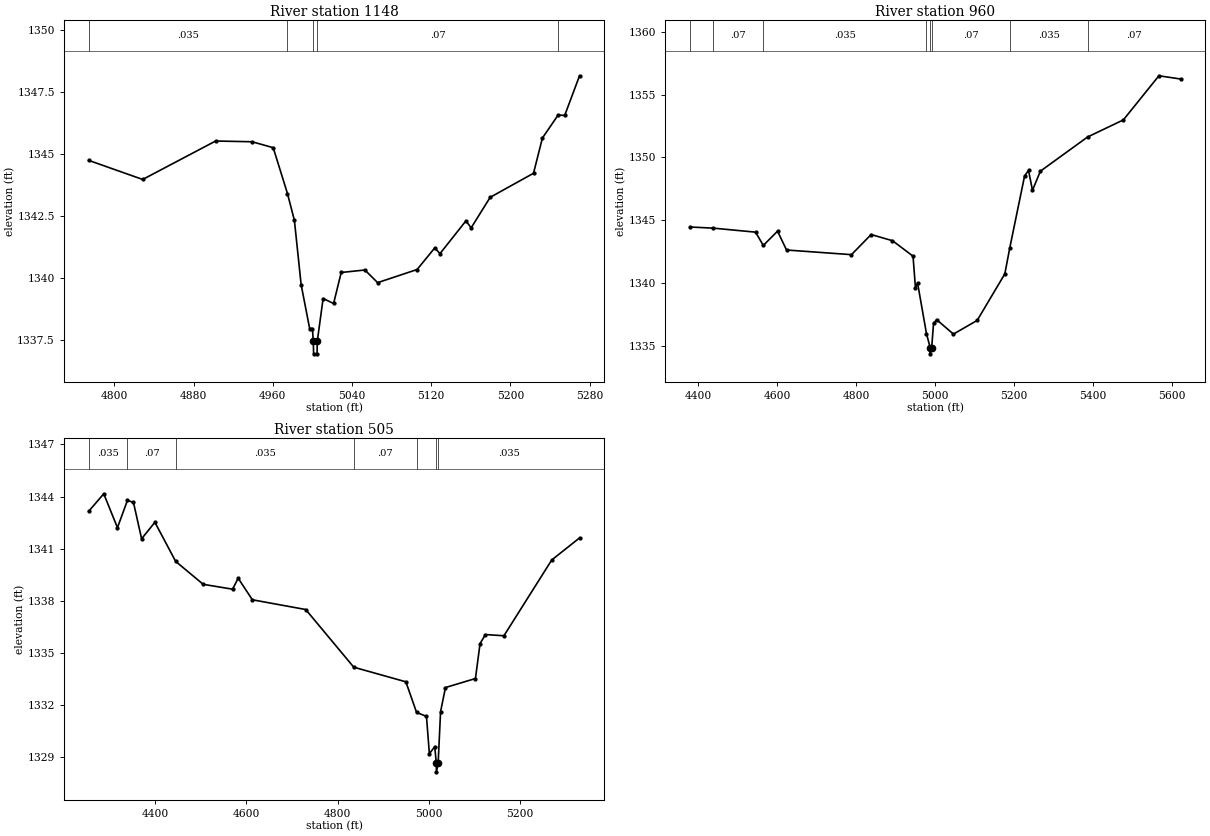
Type RM Length L Ch R = 1,1148,188,188,188
BEGIN DESCRIPTION:
Stream0088_DS 2.5
END DESCRIPTION:
XS GIS Cut Line= 3
      2035681.22     13883433.02      2035874.76     13883549.90
      2036130.56     13883636.01
#Sta/Elev= 30
  4773.9 1344.76  4828.5 1343.99  4902.2 1345.54  4939.1 1345.51  4960.4 1345.27
  4974.8 1343.42  4981.8 1342.34  4988.6 1339.75  4997.2 1337.98  5000.0 1337.98
  5000.9 1337.46  5001.2 1336.96  5004.7 1336.96  5004.9 1337.46  5010.8 1339.19
  5021.4 1338.99  5029.1 1340.24  5053.0 1340.34  5065.9 1339.83  5105.8 1340.36
  5123.6 1341.23  5128.9 1341.00  5155.1 1342.32  5160.4 1342.04  5179.6 1343.27
  5223.4 1344.24  5232.4 1345.66  5248.3 1346.59  5254.9 1346.57  5269.9 1348.17
#Mann=5,-1,0
  4773.9   0.035       0  4974.8    0.07       0  5000.9    0.05       0
  5004.9    0.07       0  5248.3   0.035       0
Bank Sta=5000.9,5004.9
Exp/Cntr=0.3,0.1

Type RM Length L Ch R = 1,960,455,455,455
BEGIN DESCRIPTION:
Stream0088_DS 2.0
END DESCRIPTION:
XS GIS Cut Line= 3
      2035321.63     13883554.39      2035925.00     13883725.00
      2036540.61     13883710.67
#Sta/Elev= 30
  4379.1 1344.47  4438.1 1344.38  4545.2 1344.06  4564.7 1343.00  4600.8 1344.14
  4623.5 1342.64  4787.9 1342.27  4837.7 1343.87  4891.8 1343.38  4943.8 1342.15
  4950.0 1339.60  4955.2 1340.03  4977.8 1335.99  4987.1 1334.88  4987.4 1334.38
  4991.1 1334.88  4995.7 1336.81  5003.5 1337.10  5046.1 1335.95  5106.2 1337.04
  5176.2 1340.74  5188.4 1342.76  5226.2 1348.53  5236.2 1348.97  5246.2 1347.39
  5266.2 1348.91  5385.7 1351.63  5476.3 1352.99  5566.3 1356.50  5621.9 1356.24
#Mann=8,-1,0
  4379.1   0.035       0  4438.1    0.07       0  4564.7   0.035       0
  4977.8    0.07       0  4987.1    0.05       0  4991.1    0.07       0
  5188.4   0.035       0  5385.7    0.07       0
Bank Sta=4987.1,4991.1
Exp/Cntr=0.3,0.1

Type RM Length L Ch R = 1,505,0,0,0
BEGIN DESCRIPTION:
Stream0088_DS 1.0
END DESCRIPTION:
XS GIS Cut Line= 3
      2035434.51     13883784.44      2036125.00     13884075.00
      2036424.14     13883945.01
#Sta/Elev= 30
  4254.7 1343.15  4287.8 1344.16  4317.8 1342.21  4339.7 1343.78  4352.9 1343.66
  4370.7 1341.57  4399.8 1342.52  4445.3 1340.27  4505.6 1338.95  4569.9 1338.67
  4582.3 1339.30  4613.3 1338.06  4730.2 1337.50  4835.5 1334.18  4949.6 1333.34
  4973.0 1331.58  4994.7 1331.35  5001.1 1329.20  5012.8 1329.61  5016.3 1328.66
  5016.5 1328.16  5020.3 1328.66  5025.6 1331.62  5036.3 1333.01  5102.0 1333.53
  5112.1 1335.54  5123.8 1336.06  5164.4 1335.99  5269.1 1340.35  5330.0 1341.62
#Mann=7,-1,0
  4254.7   0.035       0  4339.7    0.07       0  4445.3   0.035       0
  4835.5    0.07       0  4973.0   0.035       0  5016.3   0.035       0
  5020.3   0.035       0
Bank Sta=5016.3,5020.3
Exp/Cntr=0.3,0.1

Chan Stop Cuts=-1