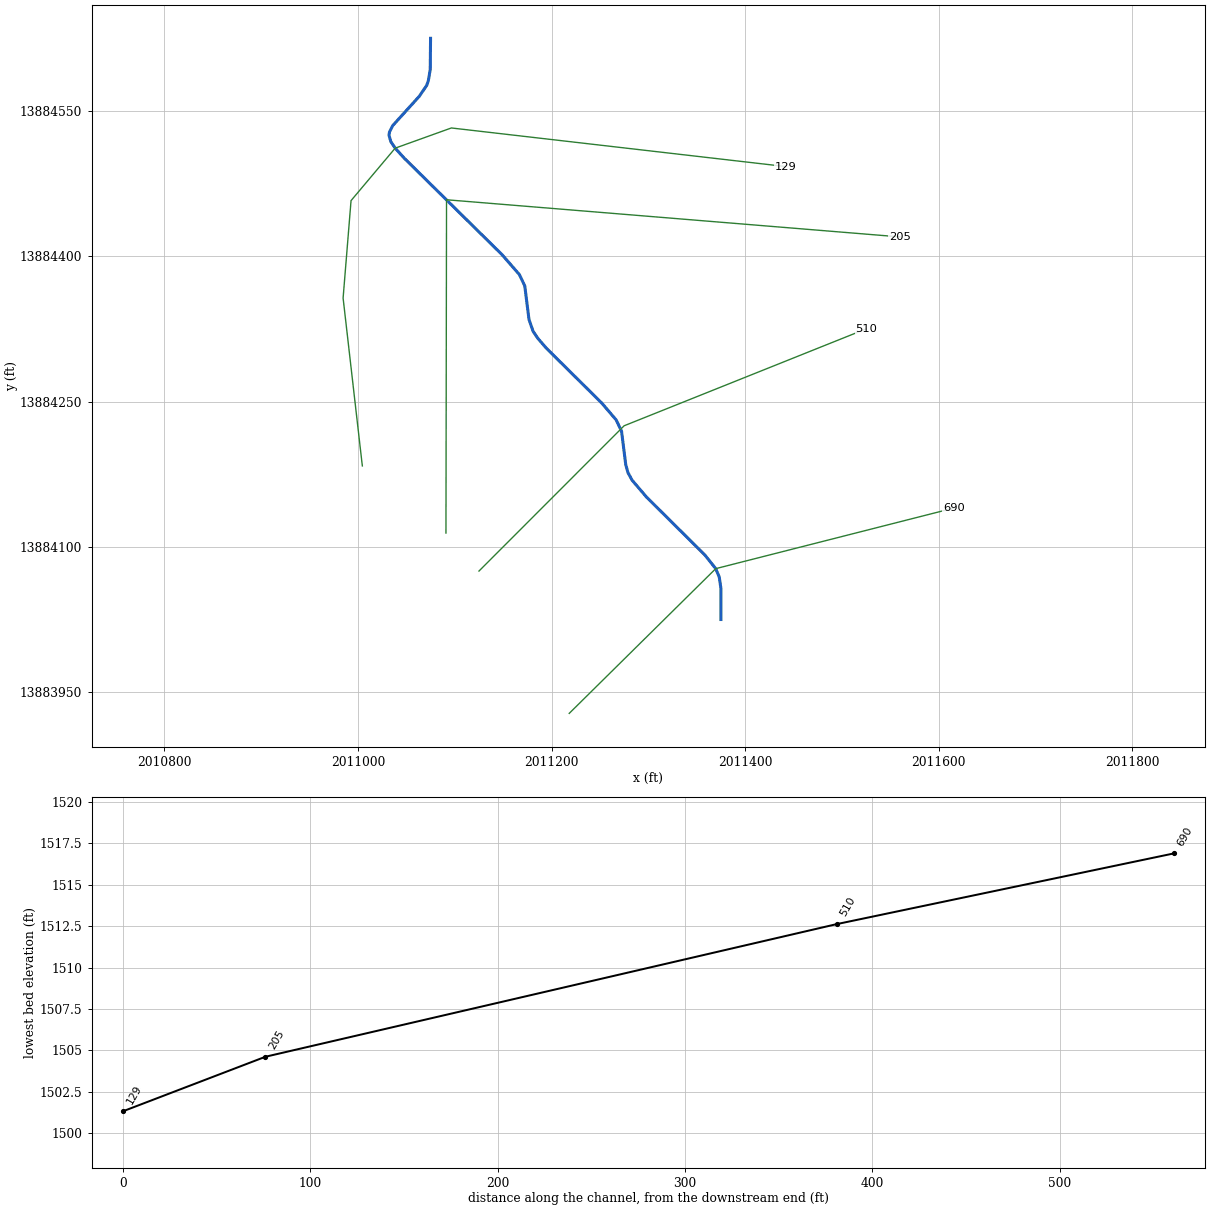
--- Stream0089_DS.prj (project) ---

Proj Title=Stream0089_DS Base Level Engineering
Current Plan=p01
Default Exp/Contr=0.3,0.1
English Units
Geom File=g01
Flow File=f01
Plan File=p01
BEGIN DESCRIPTION:
Stream0089_DS
END DESCRIPTION:

--- Stream0089_DS.p01 (plan) ---

Plan Title=Multiple Run
Short Identifier=Multiple
Geom File=g01
Flow File=f01
Subcritical Flow
K Sum by GR= 0
Std Step Tol= 0.01
Critical Tol= 0.01
Num of Std Step Trials= 20
Max Error Tol= 0.3
Flow Tol Ratio= 0.001
Split Flow NTrial= 30
Split Flow Tol= 0.02
Split Flow Ratio= 0.02
Log Output Level= 0
Friction Slope Method= 1
Unsteady Friction Slope Method= 2
Unsteady Bridges Friction Slope Method= 1
Parabolic Critical Depth
Global Vel Dist=  1 , 1 , 1
Global Log Level= 0
CheckData=True
Encroach Param= -1, 0, 0, 0
BEGIN DESCRIPTION:
Multiple Run
END DESCRIPTION:

--- Stream0089_DS.f01 (steady flow) ---

Flow Title=Multiple
Number of Profiles=7
Profile Names=10-year,25-year,50-year,1pct_min,100-year,1pct_plu,500-year
River Rch & RM= Stream0089_DS,Reach-1,690
     438     706     951     624    1244    2483    2101
Boundary for River Rch & Prof#=Stream0089_DS,Reach-1,1
Up Type=0
Dn Type=3
Dn Slope=0.005
Boundary for River Rch & Prof#=Stream0089_DS,Reach-1,2
Up Type=0
Dn Type=3
Dn Slope=0.005
Boundary for River Rch & Prof#=Stream0089_DS,Reach-1,3
Up Type=0
Dn Type=3
Dn Slope=0.005
Boundary for River Rch & Prof#=Stream0089_DS,Reach-1,4
Up Type=0
Dn Type=3
Dn Slope=0.005
Boundary for River Rch & Prof#=Stream0089_DS,Reach-1,5
Up Type=0
Dn Type=3
Dn Slope=0.005
Boundary for River Rch & Prof#=Stream0089_DS,Reach-1,6
Up Type=0
Dn Type=3
Dn Slope=0.005
Boundary for River Rch & Prof#=Stream0089_DS,Reach-1,7
Up Type=0
Dn Type=3
Dn Slope=0.005

--- Stream0089_DS.g01 (geometry) ---

Geom Title=Existing Conditions

River Reach=Stream0089_DS,Reach-1
Reach XY= 30
      2011375.00     13884025.00      2011375.07     13884056.88
      2011373.31     13884068.85      2011369.67     13884077.51
      2011358.38     13884091.69      2011298.03     13884151.54
      2011283.16     13884168.95      2011278.98     13884176.65
      2011276.70     13884184.80      2011272.35     13884219.36
      2011266.82     13884231.04      2011251.94     13884248.44
      2011194.83     13884304.93      2011185.80     13884315.33
      2011180.87     13884322.72      2011176.71     13884334.80
      2011172.36     13884369.36      2011166.84     13884381.05
      2011148.70     13884401.82      2011047.44     13884501.65
      2011038.46     13884511.63      2011033.98     13884518.29
      2011032.05     13884524.93      2011032.54     13884528.25
      2011035.89     13884534.90      2011063.39     13884565.21
      2011070.98     13884576.36      2011072.70     13884581.14
      2011074.68     13884593.12      2011075.00     13884625.00

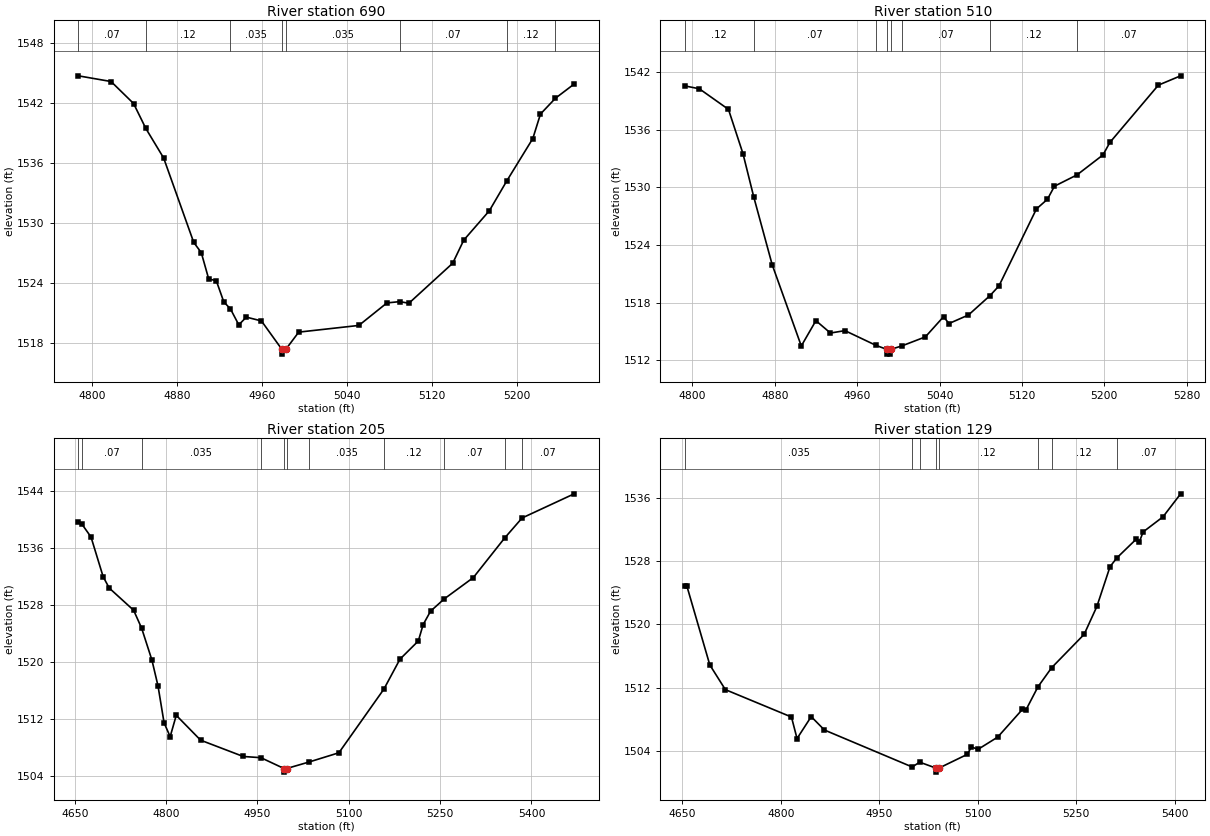
Type RM Length L Ch R = 1,690,180,180,180
BEGIN DESCRIPTION:
Stream0089_DS 2.0
END DESCRIPTION:
XS GIS Cut Line= 3
      2011218.29     13883928.10      2011369.67     13884077.51
      2011615.74     13884140.07
#Sta/Elev= 30
  4787.3 1544.72  4818.1 1544.15  4839.3 1541.95  4850.8 1539.46  4867.6 1536.50
  4895.9 1528.06  4903.0 1527.04  4910.0 1524.40  4917.1 1524.24  4924.2 1522.11
  4930.4 1521.42  4938.3 1519.82  4945.4 1520.59  4959.6 1520.21  4978.7 1517.39
  4979.0 1516.89  4982.7 1517.39  4994.7 1519.09  5051.3 1519.76  5077.7 1522.01
  5089.7 1522.14  5098.4 1521.98  5139.6 1525.98  5150.0 1528.29  5174.1 1531.23
  5190.6 1534.23  5215.0 1538.45  5222.2 1540.90  5236.3 1542.48  5253.9 1543.90
#Mann=8,-1,0
  4787.3    0.07       0  4850.8    0.12       0  4930.4   0.035       0
  4978.7   0.035       0  4982.7   0.035       0  5089.7    0.07       0
  5190.6    0.12       0  5236.3    0.07       0
Bank Sta=4978.7,4982.7
Exp/Cntr=0.3,0.1

Type RM Length L Ch R = 1,510,305,305,305
BEGIN DESCRIPTION:
Stream0089_DS 1.0
END DESCRIPTION:
XS GIS Cut Line= 3
      2011125.02     13884075.02      2011275.00     13884225.00
      2011525.03     13884325.01
#Sta/Elev= 30
  4792.7 1540.59  4806.8 1540.29  4835.1 1538.14  4849.2 1533.52  4859.7 1528.99
  4877.5 1521.96  4905.8 1513.47  4920.0 1516.11  4934.1 1514.82  4948.2 1515.07
  4978.2 1513.54  4988.7 1513.12  4988.9 1512.62  4992.4 1512.62  4992.7 1513.12
  5003.3 1513.47  5026.3 1514.42  5043.9 1516.52  5049.2 1515.81  5068.1 1516.70
  5089.0 1518.72  5097.7 1519.73  5134.1 1527.76  5144.8 1528.77  5151.6 1530.13
  5173.5 1531.31  5198.7 1533.39  5205.4 1534.69  5252.5 1540.67  5274.1 1541.64
#Mann=8,-1,0
  4792.7    0.12       0  4859.7    0.07       0  4978.2   0.035       0
  4988.7   0.035       0  4992.7   0.035       0  5003.3    0.07       0
  5089.0    0.12       0  5173.5    0.07       0
Bank Sta=4988.7,4992.7
Exp/Cntr=0.3,0.1

Type RM Length L Ch R = 1,205,76,76,76
BEGIN DESCRIPTION:
Stream0089_DS 0.1
END DESCRIPTION:
XS GIS Cut Line= 3
      2011090.91     13884114.25      2011091.51     13884458.35
      2011560.04     13884420.00
#Sta/Elev= 30
  4655.9 1539.58  4661.5 1539.34  4676.7 1537.51  4696.7 1531.94  4706.7 1530.36
  4746.7 1527.26  4759.9 1524.74  4776.7 1520.30  4786.7 1516.69  4796.7 1511.51
  4806.7 1509.57  4816.7 1512.56  4856.7 1509.08  4926.7 1506.80  4955.7 1506.63
  4993.8 1505.11  4994.1 1504.61  4997.8 1505.11  5035.3 1506.04  5083.8 1507.32
  5157.7 1516.23  5184.1 1520.42  5214.2 1522.96  5222.1 1525.25  5234.3 1527.13
  5256.8 1528.85  5304.5 1531.83  5356.0 1537.37  5384.6 1540.17  5470.1 1543.55
#Mann=11,-1,0
  4655.9    0.12       0  4661.5    0.07       0  4759.9   0.035       0
  4955.7    0.07       0  4993.8    0.05       0  4997.8    0.07       0
  5035.3   0.035       0  5157.7    0.12       0  5256.8    0.07       0
  5356.0   0.035       0  5384.6    0.07       0
Bank Sta=4993.8,4997.8
Exp/Cntr=0.3,0.1

Type RM Length L Ch R = 1,129,0,0,0
BEGIN DESCRIPTION:
Stream0089_DS 0.0
END DESCRIPTION:
XS GIS Cut Line= 6
      2011004.50     13884183.56      2010984.63     13884356.85
      2010992.83     13884457.45      2011038.46     13884511.63
      2011096.50     13884532.47      2011441.74     13884492.66
#Sta/Elev= 30
  4653.8 1524.78  4657.1 1524.78  4691.9 1514.86  4715.6 1511.74  4816.3 1508.28
  4824.8 1505.56  4846.4 1508.33  4866.5 1506.64  5000.3 1501.97  5011.6 1502.58
  5036.8 1501.82  5037.1 1501.32  5040.8 1501.82  5084.3 1503.57  5090.4 1504.51
  5100.4 1504.19  5130.6 1505.75  5168.2 1509.25  5173.2 1509.12  5191.8 1512.09
  5212.7 1514.51  5262.2 1518.72  5281.6 1522.24  5301.7 1527.28  5312.2 1528.39
  5341.1 1530.71  5346.1 1530.36  5352.1 1531.66  5382.3 1533.56  5409.2 1536.47
#Mann=8,-1,0
  4653.8   0.035       0  5000.3    0.07       0  5011.6    0.12       0
  5036.8   0.035       0  5040.8    0.12       0  5191.8   0.035       0
  5212.7    0.12       0  5312.2    0.07       0
Bank Sta=5036.8,5040.8
Exp/Cntr=0.3,0.1

Chan Stop Cuts=-1