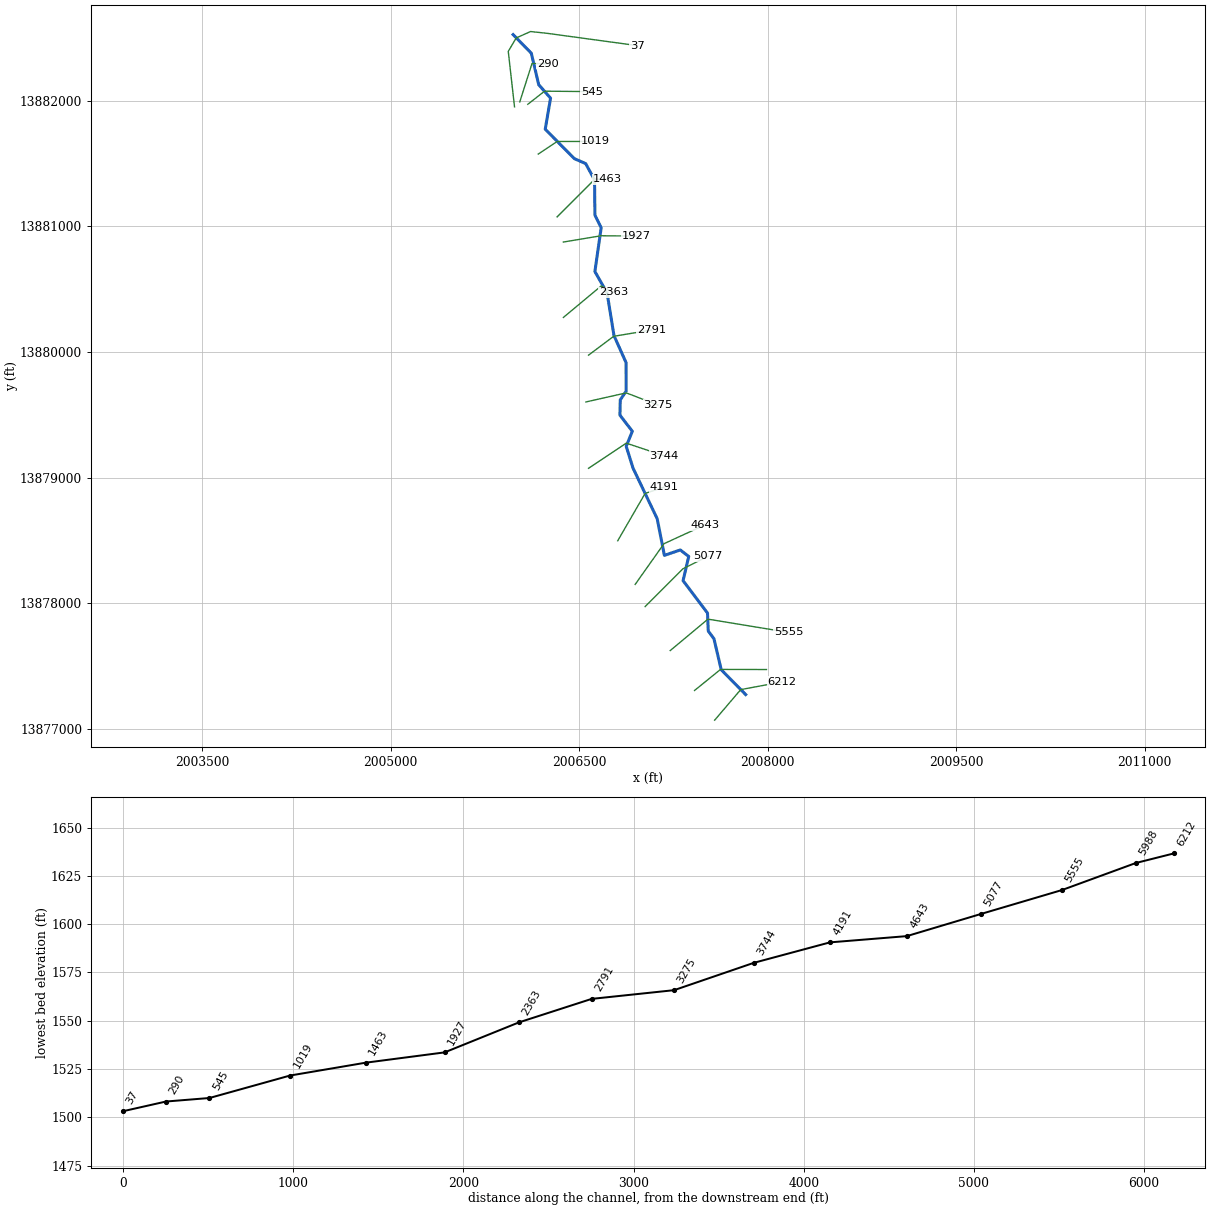
--- Stream0090_DS.prj (project) ---

Proj Title=Stream0090_DS Base Level Engineering
Current Plan=p01
Default Exp/Contr=0.3,0.1
English Units
Geom File=g01
Flow File=f01
Plan File=p01
BEGIN DESCRIPTION:
Stream0090_DS
END DESCRIPTION:

--- Stream0090_DS.p01 (plan) ---

Plan Title=Multiple Run
Short Identifier=Multiple
Geom File=g01
Flow File=f01
Subcritical Flow
K Sum by GR= 0
Std Step Tol= 0.01
Critical Tol= 0.01
Num of Std Step Trials= 20
Max Error Tol= 0.3
Flow Tol Ratio= 0.001
Split Flow NTrial= 30
Split Flow Tol= 0.02
Split Flow Ratio= 0.02
Log Output Level= 0
Friction Slope Method= 1
Unsteady Friction Slope Method= 2
Unsteady Bridges Friction Slope Method= 1
Parabolic Critical Depth
Global Vel Dist=  1 , 1 , 1
Global Log Level= 0
CheckData=True
Encroach Param= -1, 0, 0, 0
BEGIN DESCRIPTION:
Multiple Run
END DESCRIPTION:

--- Stream0090_DS.f01 (steady flow) ---

Flow Title=Multiple
Number of Profiles=7
Profile Names=10-year,25-year,50-year,1pct_min,100-year,1pct_plu,500-year
River Rch & RM= Stream0090_DS,Reach-1,6212
     455     737     997     657    1311    2617    2235
River Rch & RM= Stream0090_DS,Reach-1,5988
    1001    1710    2390    1621    3235    6455    5862
Boundary for River Rch & Prof#=Stream0090_DS,Reach-1,1
Up Type=0
Dn Type=3
Dn Slope=0.005
Boundary for River Rch & Prof#=Stream0090_DS,Reach-1,2
Up Type=0
Dn Type=3
Dn Slope=0.005
Boundary for River Rch & Prof#=Stream0090_DS,Reach-1,3
Up Type=0
Dn Type=3
Dn Slope=0.005
Boundary for River Rch & Prof#=Stream0090_DS,Reach-1,4
Up Type=0
Dn Type=3
Dn Slope=0.005
Boundary for River Rch & Prof#=Stream0090_DS,Reach-1,5
Up Type=0
Dn Type=3
Dn Slope=0.005
Boundary for River Rch & Prof#=Stream0090_DS,Reach-1,6
Up Type=0
Dn Type=3
Dn Slope=0.005
Boundary for River Rch & Prof#=Stream0090_DS,Reach-1,7
Up Type=0
Dn Type=3
Dn Slope=0.005

--- Stream0090_DS.g01 (geometry) ---

Geom Title=Existing Conditions

River Reach=Stream0090_DS,Reach-1
Reach XY= 30
      2007825.00     13877275.00      2007630.52     13877472.57
      2007572.64     13877719.02      2007527.39     13877780.53
      2007521.45     13877923.53      2007326.97     13878180.89
      2007371.96     13878373.64      2007304.99     13878425.43
      2007178.31     13878382.28      2007121.24     13878673.44
      2006928.83     13879076.58      2006874.61     13879250.00
      2006923.25     13879369.37      2006824.78     13879497.66
      2006827.37     13879619.47      2006874.32     13879688.92
      2006873.62     13879915.34      2006777.27     13880130.94
      2006722.64     13880469.48      2006625.49     13880640.22
      2006675.44     13880988.82      2006625.68     13881088.92
      2006622.76     13881369.07      2006552.15     13881498.84
      2006461.80     13881538.64      2006230.40     13881772.57
      2006272.91     13882019.51      2006178.62     13882126.50
      2006119.48     13882377.43      2005975.00     13882525.00

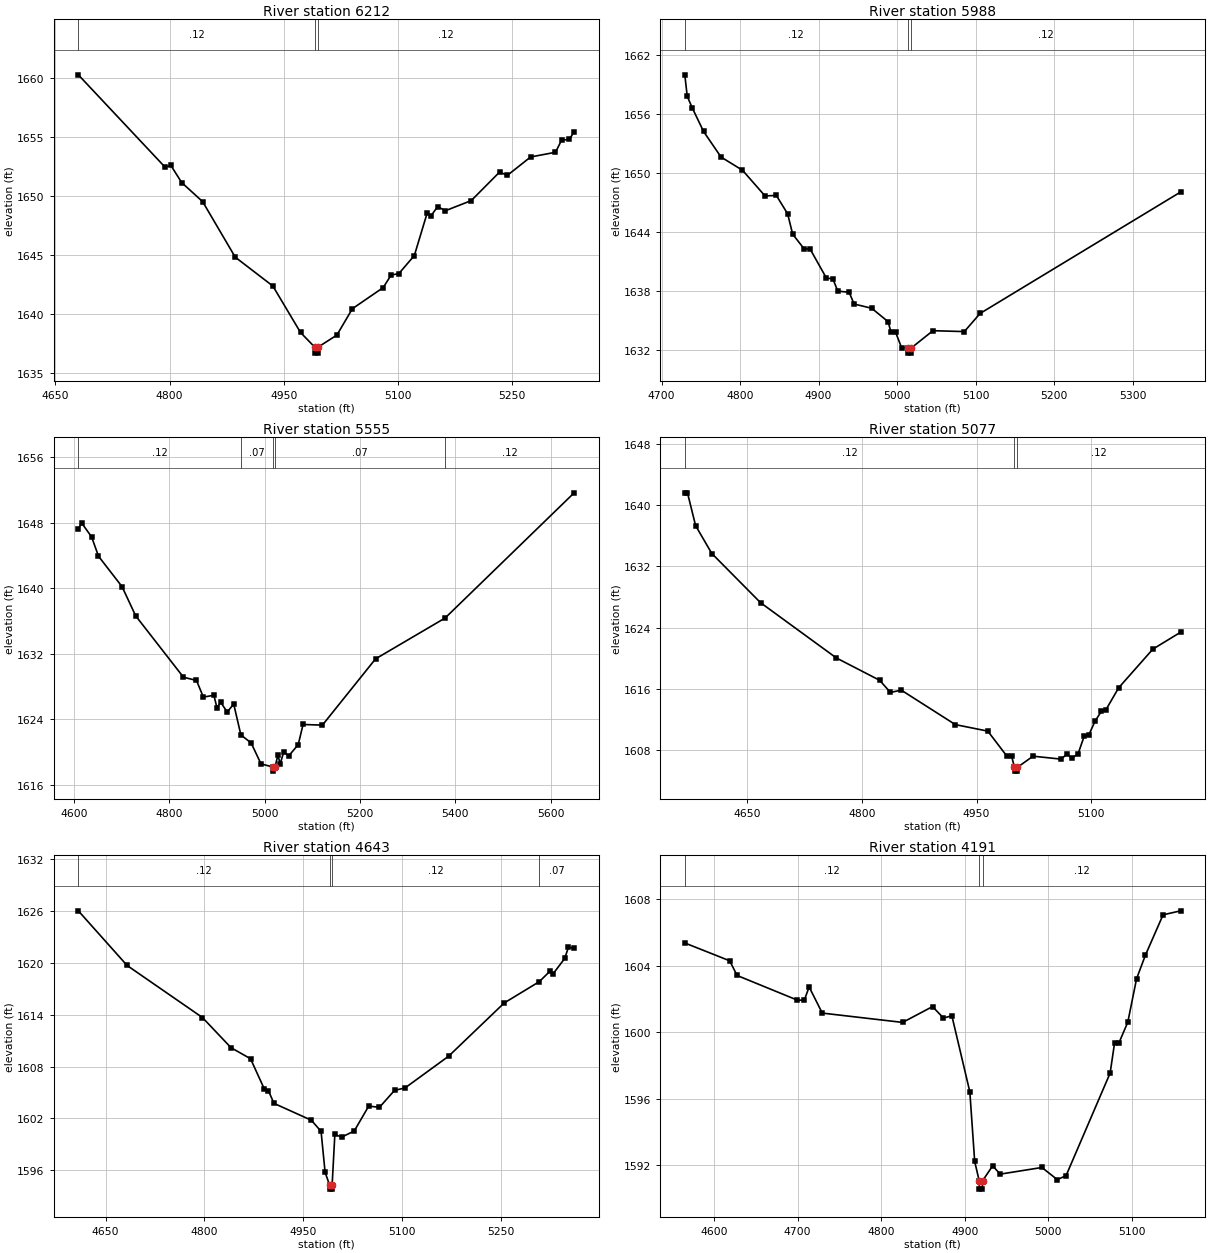
Type RM Length L Ch R = 1,6212,224,224,224
BEGIN DESCRIPTION:
Stream0090_DS 14.0
END DESCRIPTION:
XS GIS Cut Line= 3
      2007578.18     13877071.10      2007785.60     13877314.38
      2008111.20     13877375.02
#Sta/Elev= 30
  4680.3 1660.27  4794.1 1652.44  4801.8 1652.58  4816.0 1651.13  4843.5 1649.51
  4886.3 1644.80  4935.7 1642.35  4972.0 1638.41  4990.8 1637.16  4991.1 1636.66
  4994.6 1636.66  4994.8 1637.16  5019.7 1638.19  5040.1 1640.43  5080.5 1642.22
  5090.9 1643.28  5101.1 1643.41  5121.4 1644.94  5138.3 1648.56  5143.4 1648.32
  5152.0 1649.09  5162.1 1648.74  5196.1 1649.60  5233.3 1652.02  5243.5 1651.74
  5274.0 1653.30  5306.7 1653.70  5314.7 1654.73  5324.9 1654.79  5331.2 1655.45
#Mann=3,-1,0
  4680.3    0.12       0  4990.8    0.05       0  4994.8    0.12       0
Bank Sta=4990.8,4994.8
Exp/Cntr=0.3,0.1

Type RM Length L Ch R = 1,5988,433,433,433
BEGIN DESCRIPTION:
Stream0090_DS 13.0
END DESCRIPTION:
XS GIS Cut Line= 3
      2007418.24     13877307.56      2007625.00     13877475.00
      2007990.54     13877474.22
#Sta/Elev= 30
  4729.6 1659.97  4732.7 1657.79  4739.1 1656.61  4753.5 1654.21  4775.8 1651.61
  4803.1 1650.27  4831.8 1647.66  4846.2 1647.71  4860.6 1645.84  4867.0 1643.77
  4881.4 1642.30  4889.3 1642.25  4910.1 1639.29  4918.1 1639.25  4924.5 1637.98
  4938.9 1637.87  4945.3 1636.67  4967.7 1636.24  4988.5 1634.88  4992.4 1633.79
  4998.2 1633.79  5005.7 1632.24  5013.7 1632.18  5013.9 1631.68  5017.4 1631.68
  5017.7 1632.18  5045.7 1633.96  5085.7 1633.87  5105.7 1635.71  5361.2 1648.06
#Mann=3,-1,0
  4729.6    0.12       0  5013.7    0.05       0  5017.7    0.12       0
Bank Sta=5013.7,5017.7
Exp/Cntr=0.3,0.1

Type RM Length L Ch R = 1,5555,478,478,478
BEGIN DESCRIPTION:
Stream0090_DS 12.0
END DESCRIPTION:
XS GIS Cut Line= 3
      2007225.03     13877625.03      2007525.00     13877875.00
      2008166.24     13877769.69
#Sta/Elev= 30
  4609.2 1647.27  4616.3 1647.95  4637.1 1646.26  4651.5 1643.91  4700.9 1640.20
  4729.6 1636.63  4829.8 1629.15  4857.1 1628.76  4871.5 1626.73  4893.6 1626.95
  4900.1 1625.42  4907.9 1626.09  4921.6 1624.91  4935.2 1625.88  4950.2 1622.12
  4971.7 1621.14  4992.5 1618.58  5017.9 1618.20  5018.2 1617.70  5021.9 1618.20
  5027.8 1619.64  5032.8 1618.59  5040.2 1620.07  5050.3 1619.53  5070.6 1620.94
  5080.7 1623.39  5121.3 1623.31  5232.8 1631.39  5378.7 1636.37  5649.5 1651.64
#Mann=5,-1,0
  4609.2    0.12       0  4950.2    0.07       0  5017.9    0.05       0
  5021.9    0.07       0  5378.7    0.12       0
Bank Sta=5017.9,5021.9
Exp/Cntr=0.3,0.1

Type RM Length L Ch R = 1,5077,434,434,434
BEGIN DESCRIPTION:
Stream0090_DS 11.0
END DESCRIPTION:
XS GIS Cut Line= 3
      2007025.03     13877975.03      2007325.00     13878275.00
      2007524.97     13878374.98
#Sta/Elev= 30
  4568.8 1641.58  4572.3 1641.58  4582.9 1637.30  4604.1 1633.66  4667.8 1627.24
  4766.8 1620.03  4823.3 1617.12  4837.5 1615.53  4851.6 1615.83  4922.3 1611.33
  4964.7 1610.48  4989.5 1607.23  4995.8 1607.23  4999.4 1605.76  4999.7 1605.26
  5003.2 1605.26  5003.4 1605.76  5023.8 1607.21  5060.1 1606.83  5068.5 1607.49
  5074.1 1606.96  5082.5 1607.49  5090.9 1609.90  5096.4 1609.93  5104.8 1611.78
  5113.2 1613.09  5118.8 1613.23  5135.6 1616.13  5180.3 1621.18  5216.6 1623.39
#Mann=3,-1,0
  4568.8    0.12       0  4999.4    0.05       0  5003.4    0.12       0
Bank Sta=4999.4,5003.4
Exp/Cntr=0.3,0.1

Type RM Length L Ch R = 1,4643,452,452,452
BEGIN DESCRIPTION:
Stream0090_DS 10.0
END DESCRIPTION:
XS GIS Cut Line= 3
      2006946.00     13878151.29      2007175.00     13878475.00
      2007498.08     13878623.52
#Sta/Elev= 30
  4608.7 1626.05  4682.7 1619.72  4797.0 1613.69  4840.3 1610.20  4869.9 1608.92
  4890.8 1605.42  4896.9 1605.24  4905.5 1603.75  4962.1 1601.80  4976.9 1600.51
  4983.0 1595.77  4989.7 1594.32  4990.0 1593.82  4993.5 1593.82  4993.7 1594.32
  4997.8 1600.16  5008.0 1599.84  5027.2 1600.55  5049.2 1603.44  5065.4 1603.29
  5088.4 1605.26  5104.3 1605.54  5170.3 1609.21  5254.7 1615.38  5308.0 1617.85
  5323.7 1619.03  5329.2 1618.79  5346.4 1620.53  5352.1 1621.82  5360.8 1621.71
#Mann=4,-1,0
  4608.7    0.12       0  4989.7    0.05       0  4993.7    0.12       0
  5308.0    0.07       0
Bank Sta=4989.7,4993.7
Exp/Cntr=0.3,0.1

Type RM Length L Ch R = 1,4191,447,447,447
BEGIN DESCRIPTION:
Stream0090_DS 9.0
END DESCRIPTION:
XS GIS Cut Line= 3
      2006807.14     13878498.56      2007025.00     13878875.00
      2007174.95     13878924.98
#Sta/Elev= 30
  4565.1 1605.36  4618.8 1604.29  4627.6 1603.41  4699.6 1601.93  4708.0 1601.92
  4713.8 1602.72  4729.5 1601.15  4825.6 1600.59  4861.4 1601.54  4874.5 1600.85
  4884.5 1600.99  4906.0 1596.42  4911.8 1592.24  4917.2 1591.08  4917.4 1590.58
  4920.9 1590.58  4921.2 1591.08  4933.3 1591.98  4942.3 1591.48  4992.2 1591.88
  5010.6 1591.15  5021.1 1591.39  5073.8 1597.55  5079.1 1599.36  5084.4 1599.37
  5094.9 1600.60  5105.4 1603.21  5116.0 1604.63  5137.1 1607.05  5158.1 1607.29
#Mann=3,-1,0
  4565.1    0.12       0  4917.2    0.05       0  4921.2    0.12       0
Bank Sta=4917.2,4921.2
Exp/Cntr=0.3,0.1

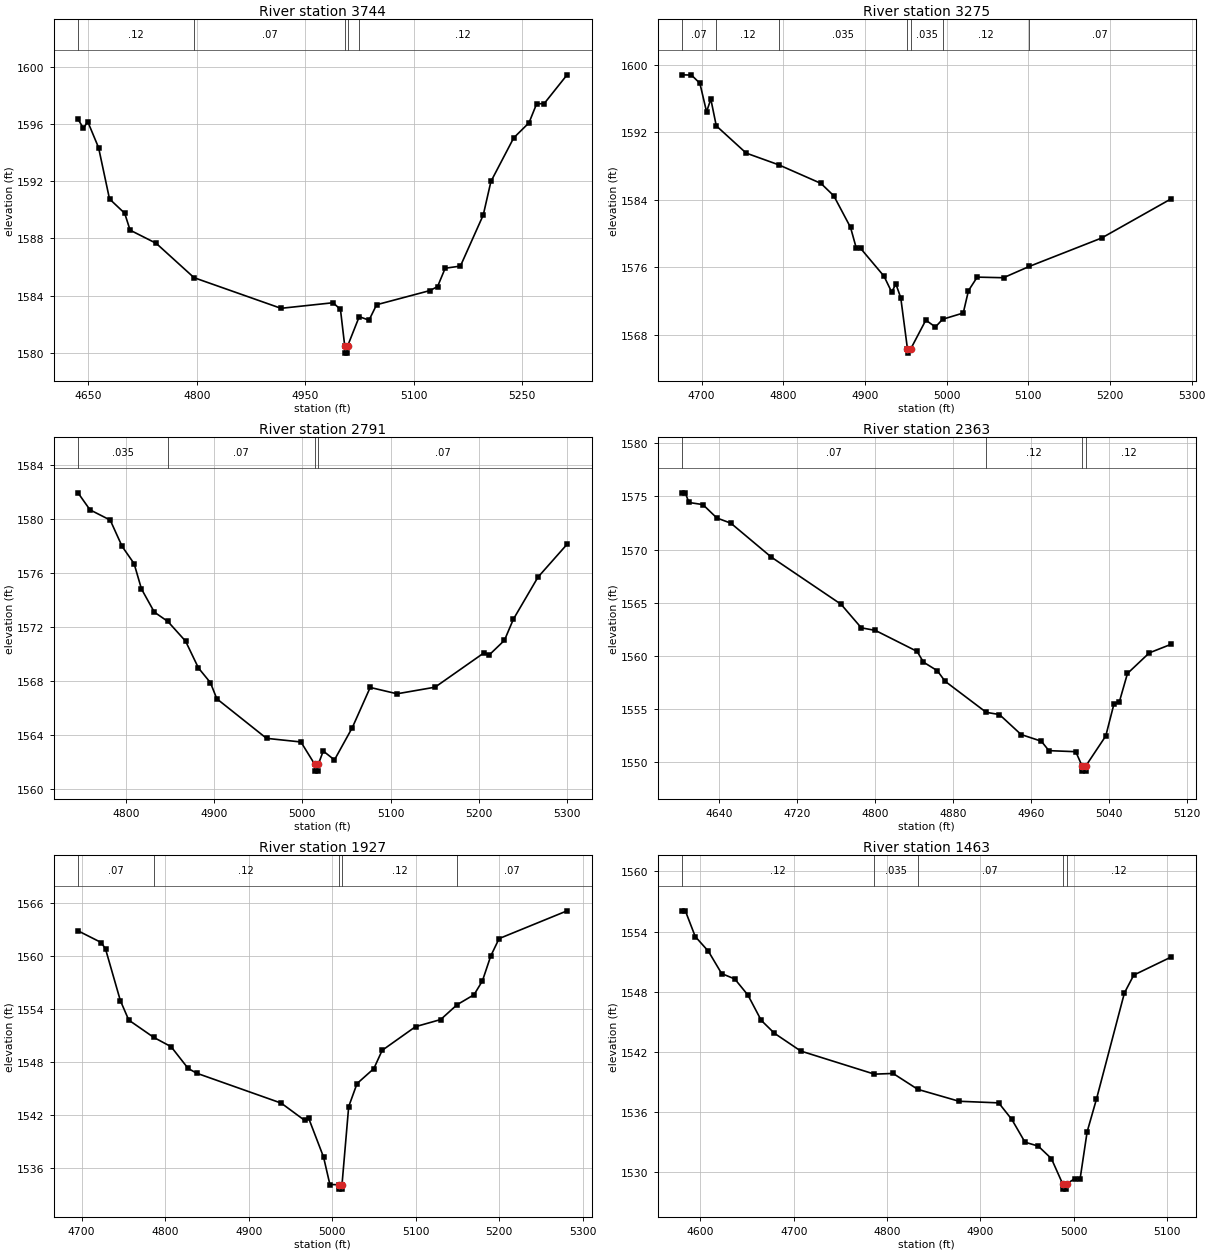
Type RM Length L Ch R = 1,3744,469,469,469
BEGIN DESCRIPTION:
Stream0090_DS 8.0
END DESCRIPTION:
XS GIS Cut Line= 3
      2006575.01     13879075.01      2006875.00     13879275.00
      2007175.03     13879174.99
#Sta/Elev= 30
  4635.6 1596.33  4643.1 1595.70  4649.1 1596.16  4664.1 1594.34  4679.2 1590.76
  4700.2 1589.76  4707.7 1588.58  4743.8 1587.66  4796.2 1585.26  4916.5 1583.12
  4988.6 1583.51  4998.8 1583.04  5004.7 1580.49  5004.9 1579.99  5008.4 1579.99
  5008.7 1580.49  5024.8 1582.54  5038.3 1582.29  5048.8 1583.37  5122.6 1584.36
  5133.2 1584.64  5143.7 1585.92  5164.8 1586.07  5196.4 1589.64  5207.0 1591.98
  5238.6 1595.03  5259.7 1596.08  5270.2 1597.40  5280.7 1597.42  5312.4 1599.43
#Mann=5,-1,0
  4635.6    0.12       0  4796.2    0.07       0  5004.7    0.05       0
  5008.7    0.07       0  5024.8    0.12       0
Bank Sta=5004.7,5008.7
Exp/Cntr=0.3,0.1

Type RM Length L Ch R = 1,3275,484,484,484
BEGIN DESCRIPTION:
Stream0090_DS 7.0
END DESCRIPTION:
XS GIS Cut Line= 3
      2006553.65     13879602.69      2006875.00     13879675.00
      2007126.60     13879578.37
#Sta/Elev= 30
  4675.9 1598.78  4687.5 1598.75  4697.8 1597.78  4706.0 1594.40  4711.2 1595.91
  4717.9 1592.74  4754.5 1589.51  4794.4 1588.12  4846.1 1585.92  4861.8 1584.45
  4882.3 1580.71  4889.4 1578.23  4894.5 1578.24  4923.3 1574.93  4932.7 1573.04
  4937.8 1574.02  4943.8 1572.37  4952.0 1566.32  4952.3 1565.82  4956.0 1566.32
  4974.5 1569.73  4986.2 1568.91  4995.0 1569.83  5020.3 1570.57  5026.7 1573.22
  5037.4 1574.82  5069.6 1574.75  5101.2 1576.09  5189.7 1579.45  5274.8 1584.09
#Mann=7,-1,0
  4675.9    0.07       0  4717.9    0.12       0  4794.4   0.035       0
  4952.0    0.05       0  4956.0   0.035       0  4995.0    0.12       0
  5101.2    0.07       0
Bank Sta=4952,4956
Exp/Cntr=0.3,0.1

Type RM Length L Ch R = 1,2791,428,428,428
BEGIN DESCRIPTION:
Stream0090_DS 6.0
END DESCRIPTION:
XS GIS Cut Line= 3
      2006574.98     13879974.99      2006775.00     13880125.00
      2007075.04     13880175.01
#Sta/Elev= 30
  4745.7 1581.93  4759.3 1580.67  4782.2 1579.91  4795.7 1577.96  4809.3 1576.68
  4817.6 1574.81  4832.2 1573.09  4847.5 1572.40  4867.6 1570.94  4882.2 1568.95
  4895.7 1567.87  4903.0 1566.67  4959.3 1563.74  4998.3 1563.47  5014.0 1561.81
  5014.2 1561.31  5017.7 1561.31  5018.0 1561.81  5023.6 1562.80  5036.3 1562.14
  5056.5 1564.53  5076.8 1567.51  5107.2 1567.04  5150.3 1567.53  5206.1 1570.09
  5211.2 1569.89  5228.9 1571.00  5239.0 1572.56  5266.9 1575.68  5299.9 1578.12
#Mann=4,-1,0
  4745.7   0.035       0  4847.5    0.07       0  5014.0    0.05       0
  5018.0    0.07       0
Bank Sta=5014,5018
Exp/Cntr=0.3,0.1

Type RM Length L Ch R = 1,2363,436,436,436
BEGIN DESCRIPTION:
Stream0090_DS 5.0
END DESCRIPTION:
XS GIS Cut Line= 3
      2006374.96     13880274.97      2006675.00     13880525.00
      2006775.03     13880474.98
#Sta/Elev= 30
  4601.7 1575.34  4605.0 1575.34  4608.9 1574.43  4623.2 1574.23  4637.5 1572.97
  4651.9 1572.48  4693.5 1569.28  4765.1 1564.84  4785.9 1562.62  4800.3 1562.38
  4843.2 1560.40  4849.7 1559.39  4864.0 1558.58  4871.9 1557.59  4914.2 1554.66
  4927.8 1554.45  4950.0 1552.57  4970.8 1551.94  4978.6 1551.05  5006.2 1550.95
  5012.6 1549.62  5012.9 1549.12  5016.4 1549.12  5016.6 1549.62  5037.0 1552.43
  5045.4 1555.44  5051.0 1555.66  5059.3 1558.32  5081.7 1560.26  5104.1 1561.07
#Mann=4,-1,0
  4601.7    0.07       0  4914.2    0.12       0  5012.6    0.05       0
  5016.6    0.12       0
Bank Sta=5012.6,5016.6
Exp/Cntr=0.3,0.1

Type RM Length L Ch R = 1,1927,464,464,464
BEGIN DESCRIPTION:
Stream0090_DS 4.0
END DESCRIPTION:
XS GIS Cut Line= 3
      2006374.99     13880875.00      2006675.00     13880925.00
      2006956.44     13880922.14
#Sta/Elev= 30
  4695.7 1562.82  4723.6 1561.49  4728.7 1560.75  4746.4 1554.93  4756.5 1552.72
  4786.3 1550.77  4807.2 1549.71  4827.5 1547.26  4837.6 1546.72  4939.0 1543.33
  4966.9 1541.39  4972.0 1541.59  4989.7 1537.23  4997.3 1534.12  5007.8 1534.10
  5008.1 1533.60  5011.6 1533.60  5011.8 1534.10  5019.8 1542.93  5029.8 1545.54
  5049.9 1547.23  5059.9 1549.30  5099.9 1551.98  5129.9 1552.78  5149.6 1554.46
  5169.9 1555.59  5179.9 1557.15  5189.9 1559.97  5199.9 1561.94  5281.3 1565.08
#Mann=5,-1,0
  4695.7    0.07       0  4786.3    0.12       0  5007.8    0.05       0
  5011.8    0.12       0  5149.6    0.07       0
Bank Sta=5007.8,5011.8
Exp/Cntr=0.3,0.1

Type RM Length L Ch R = 1,1463,444,444,444
BEGIN DESCRIPTION:
Stream0090_DS 3.0
END DESCRIPTION:
XS GIS Cut Line= 3
      2006324.97     13881074.97      2006625.00     13881375.00
      2006725.00     13881375.00
#Sta/Elev= 30
  4580.2 1556.07  4583.8 1556.07  4594.4 1553.50  4608.5 1552.03  4622.7 1549.80
  4636.8 1549.26  4650.9 1547.65  4665.1 1545.13  4679.2 1543.84  4707.5 1542.06
  4786.5 1539.75  4806.5 1539.82  4833.0 1538.23  4877.2 1537.04  4919.7 1536.88
  4933.8 1535.22  4947.9 1532.95  4962.1 1532.56  4976.2 1531.31  4988.4 1528.76
  4988.6 1528.26  4992.1 1528.26  4992.4 1528.76  5001.0 1529.30  5007.0 1529.30
  5014.5 1533.98  5024.5 1537.25  5054.5 1547.87  5064.5 1549.65  5104.5 1551.45
#Mann=5,-1,0
  4580.2    0.12       0  4786.5   0.035       0  4833.0    0.07       0
  4988.4    0.05       0  4992.4    0.12       0
Bank Sta=4988.4,4992.4
Exp/Cntr=0.3,0.1

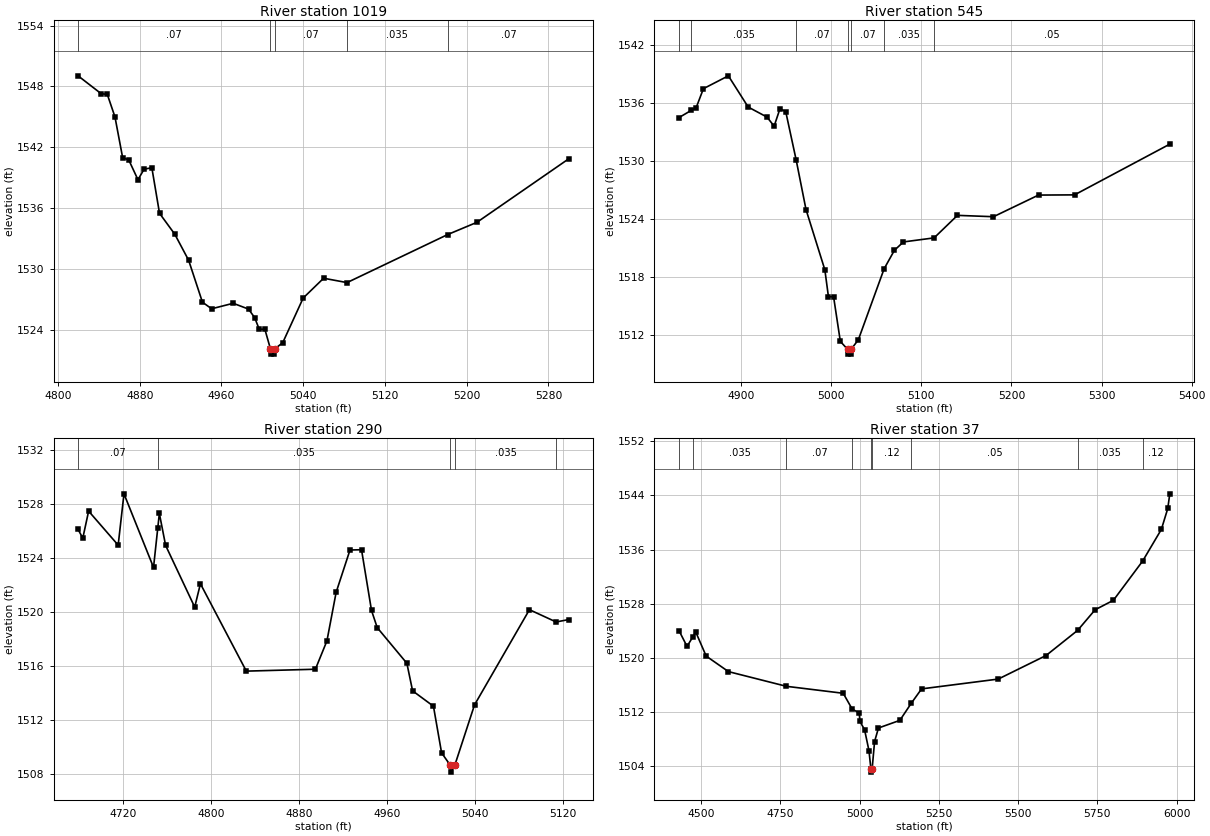
Type RM Length L Ch R = 1,1019,474,474,474
BEGIN DESCRIPTION:
Stream0090_DS 2.0
END DESCRIPTION:
XS GIS Cut Line= 3
      2006174.96     13881574.97      2006325.00     13881675.00
      2006624.98     13881675.00
#Sta/Elev= 30
  4819.7 1549.04  4842.3 1547.28  4848.3 1547.21  4855.8 1544.99  4863.3 1540.98
  4869.3 1540.75  4878.3 1538.80  4884.3 1539.84  4891.9 1539.98  4899.4 1535.49
  4914.4 1533.42  4927.9 1530.86  4941.4 1526.73  4950.4 1526.08  4971.5 1526.62
  4986.5 1526.05  4992.5 1525.21  4997.0 1524.06  5002.5 1524.06  5008.0 1522.11
  5008.3 1521.61  5011.8 1521.61  5012.0 1522.11  5020.0 1522.74  5040.0 1527.14
  5060.0 1529.09  5082.9 1528.66  5181.5 1533.40  5210.0 1534.60  5300.0 1540.87
#Mann=5,-1,0
  4819.7    0.07       0  5008.0    0.05       0  5012.0    0.07       0
  5082.9   0.035       0  5181.5    0.07       0
Bank Sta=5008,5012
Exp/Cntr=0.3,0.1

Type RM Length L Ch R = 1,545,255,255,255
BEGIN DESCRIPTION:
Stream0090_DS 1.0
END DESCRIPTION:
XS GIS Cut Line= 3
      2006091.87     13881970.77      2006225.00     13882075.00
      2006600.70     13882071.62
#Sta/Elev= 30
  4830.9 1534.45  4844.6 1535.20  4849.9 1535.46  4858.0 1537.44  4885.7 1538.77
  4907.7 1535.54  4928.6 1534.50  4936.5 1533.56  4943.0 1535.37  4949.4 1535.06
  4961.0 1530.05  4971.9 1524.93  4992.8 1518.70  4996.8 1515.91  5002.5 1515.91
  5010.0 1511.29  5018.0 1510.47  5018.2 1509.97  5021.7 1509.97  5022.0 1510.47
  5030.0 1511.46  5058.6 1518.80  5070.0 1520.71  5080.0 1521.58  5114.1 1522.00
  5140.0 1524.33  5180.0 1524.19  5230.0 1526.43  5270.0 1526.45  5375.7 1531.70
#Mann=7,-1,0
  4830.9    0.07       0  4844.6   0.035       0  4961.0    0.07       0
  5018.0    0.05       0  5022.0    0.07       0  5058.6   0.035       0
  5114.1    0.05       0
Bank Sta=5018,5022
Exp/Cntr=0.3,0.1

Type RM Length L Ch R = 1,290,253,253,253
BEGIN DESCRIPTION:
Stream0090_DS 0.5
END DESCRIPTION:
XS GIS Cut Line= 3
      2006027.66     13881989.09      2006125.25     13882295.10
      2006250.94     13882293.64
#Sta/Elev= 30
  4678.8 1526.12  4683.1 1525.48  4688.4 1527.48  4715.3 1524.96  4720.6 1528.76
  4747.5 1523.31  4751.4 1526.25  4752.8 1527.31  4758.5 1524.94  4785.0 1520.37
  4790.2 1522.10  4832.0 1515.63  4894.9 1515.77  4905.4 1517.87  4913.8 1521.47
  4926.4 1524.60  4936.9 1524.62  4946.0 1520.12  4951.2 1518.85  4978.2 1516.21
  4983.4 1514.17  5002.4 1513.03  5009.8 1509.58  5017.8 1508.65  5018.0 1508.15
  5021.8 1508.65  5039.8 1513.13  5089.8 1520.18  5114.1 1519.27  5125.7 1519.45
#Mann=5,-1,0
  4678.8    0.07       0  4751.4   0.035       0  5017.8   0.035       0
  5021.8   0.035       0  5114.1    0.05       0
Bank Sta=5017.8,5021.8
Exp/Cntr=0.3,0.1

Type RM Length L Ch R = 1,37,0,0,0
BEGIN DESCRIPTION:
Stream0090_DS 0.0
END DESCRIPTION:
XS GIS Cut Line= 6
      2005986.23     13881949.85      2005936.37     13882391.54
      2005999.59     13882498.46      2006113.77     13882549.70
      2006250.37     13882534.73      2006961.24     13882437.92
#Sta/Elev= 30
  4429.8 1524.03  4455.1 1521.70  4473.9 1523.13  4482.8 1523.81  4515.5 1520.27
  4585.9 1517.97  4768.7 1515.80  4948.0 1514.77  4976.5 1512.42  4998.5 1511.88
  5000.6 1510.64  5015.4 1509.38  5029.3 1506.29  5035.3 1503.62  5035.6 1503.12
  5039.3 1503.62  5047.0 1507.64  5059.2 1509.64  5126.8 1510.77  5162.4 1513.27
  5195.3 1515.42  5437.3 1516.87  5588.1 1520.35  5687.8 1524.07  5742.9 1527.11
  5800.6 1528.51  5892.8 1534.30  5952.0 1538.99  5972.2 1542.08  5978.5 1544.24
#Mann=9,-1,0
  4429.8    0.07       0  4473.9   0.035       0  4768.7    0.07       0
  4976.5    0.12       0  5035.3    0.05       0  5039.3    0.12       0
  5162.4    0.05       0  5687.8   0.035       0  5892.8    0.12       0
Bank Sta=5035.3,5039.3
Exp/Cntr=0.3,0.1

Chan Stop Cuts=-1