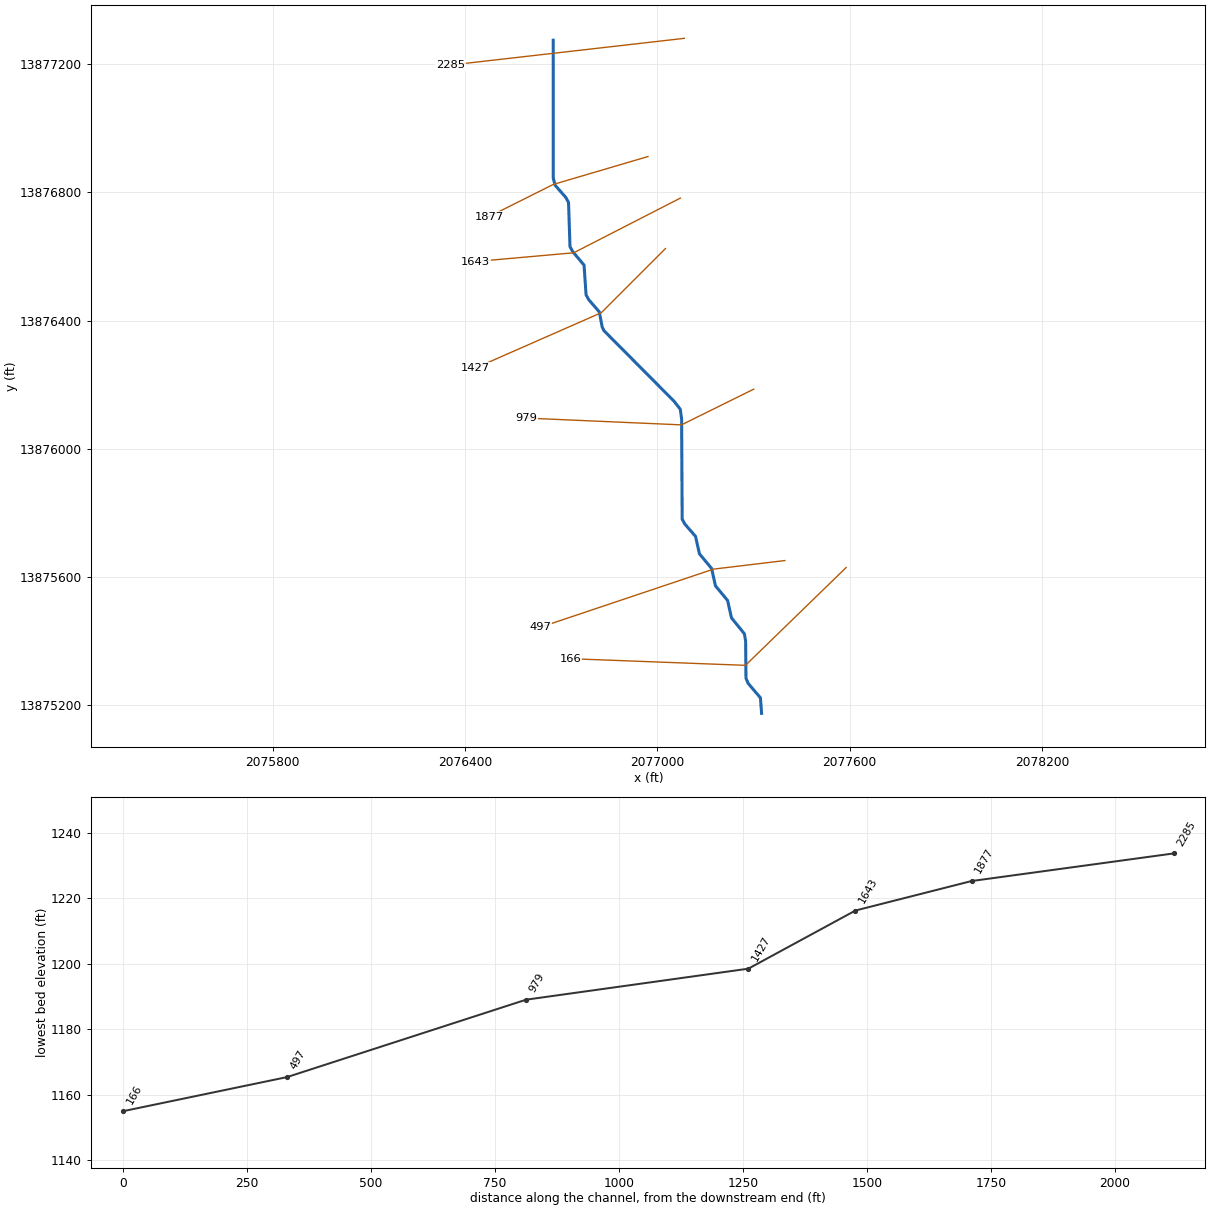
--- Stream0091_DS.prj (project) ---

Proj Title=Stream0091_DS Base Level Engineering
Current Plan=p01
Default Exp/Contr=0.3,0.1
English Units
Geom File=g01
Flow File=f01
Plan File=p01
BEGIN DESCRIPTION:
Stream0091_DS
END DESCRIPTION:

--- Stream0091_DS.p01 (plan) ---

Plan Title=Multiple Run
Short Identifier=Multiple
Geom File=g01
Flow File=f01
Subcritical Flow
K Sum by GR= 0
Std Step Tol= 0.01
Critical Tol= 0.01
Num of Std Step Trials= 20
Max Error Tol= 0.3
Flow Tol Ratio= 0.001
Split Flow NTrial= 30
Split Flow Tol= 0.02
Split Flow Ratio= 0.02
Log Output Level= 0
Friction Slope Method= 1
Unsteady Friction Slope Method= 2
Unsteady Bridges Friction Slope Method= 1
Parabolic Critical Depth
Global Vel Dist=  1 , 1 , 1
Global Log Level= 0
CheckData=True
Encroach Param= -1, 0, 0, 0
BEGIN DESCRIPTION:
Multiple Run
END DESCRIPTION:

--- Stream0091_DS.f01 (steady flow) ---

Flow Title=Multiple
Number of Profiles=7
Profile Names=10-year,25-year,50-year,1pct_min,100-year,1pct_plu,500-year
River Rch & RM= Stream0091_DS,Reach-1,2285
     363     569     750     482     961    1917    1554
River Rch & RM= Stream0091_DS,Reach-1,1877
     588     954    1289     847    1690    3373    2866
Boundary for River Rch & Prof#=Stream0091_DS,Reach-1,1
Up Type=0
Dn Type=3
Dn Slope=0.005
Boundary for River Rch & Prof#=Stream0091_DS,Reach-1,2
Up Type=0
Dn Type=3
Dn Slope=0.005
Boundary for River Rch & Prof#=Stream0091_DS,Reach-1,3
Up Type=0
Dn Type=3
Dn Slope=0.005
Boundary for River Rch & Prof#=Stream0091_DS,Reach-1,4
Up Type=0
Dn Type=3
Dn Slope=0.005
Boundary for River Rch & Prof#=Stream0091_DS,Reach-1,5
Up Type=0
Dn Type=3
Dn Slope=0.005
Boundary for River Rch & Prof#=Stream0091_DS,Reach-1,6
Up Type=0
Dn Type=3
Dn Slope=0.005
Boundary for River Rch & Prof#=Stream0091_DS,Reach-1,7
Up Type=0
Dn Type=3
Dn Slope=0.005

--- Stream0091_DS.g01 (geometry) ---

Geom Title=Existing Conditions

River Reach=Stream0091_DS,Reach-1
Reach XY= 30
      2076675.00     13877275.00      2076675.07     13876845.03
      2076680.75     13876822.67      2076714.14     13876784.64
      2076722.73     13876769.06      2076727.27     13876630.94
      2076735.85     13876615.35      2076771.14     13876573.40
      2076777.44     13876480.56      2076785.84     13876465.35
      2076818.86     13876427.17      2076827.61     13876380.62
      2076833.14     13876368.94      2077052.14     13876148.53
      2077071.46     13876123.54      2077075.46     13876093.37
      2077077.24     13875780.93      2077085.80     13875765.33
      2077118.88     13875727.18      2077131.08     13875672.80
      2077168.92     13875627.20      2077181.08     13875572.80
      2077218.92     13875527.20      2077231.12     13875472.82
      2077271.24     13875423.44      2077275.19     13875400.08
      2077276.28     13875284.62      2077282.90     13875268.84
      2077321.35     13875223.49      2077325.00     13875175.00

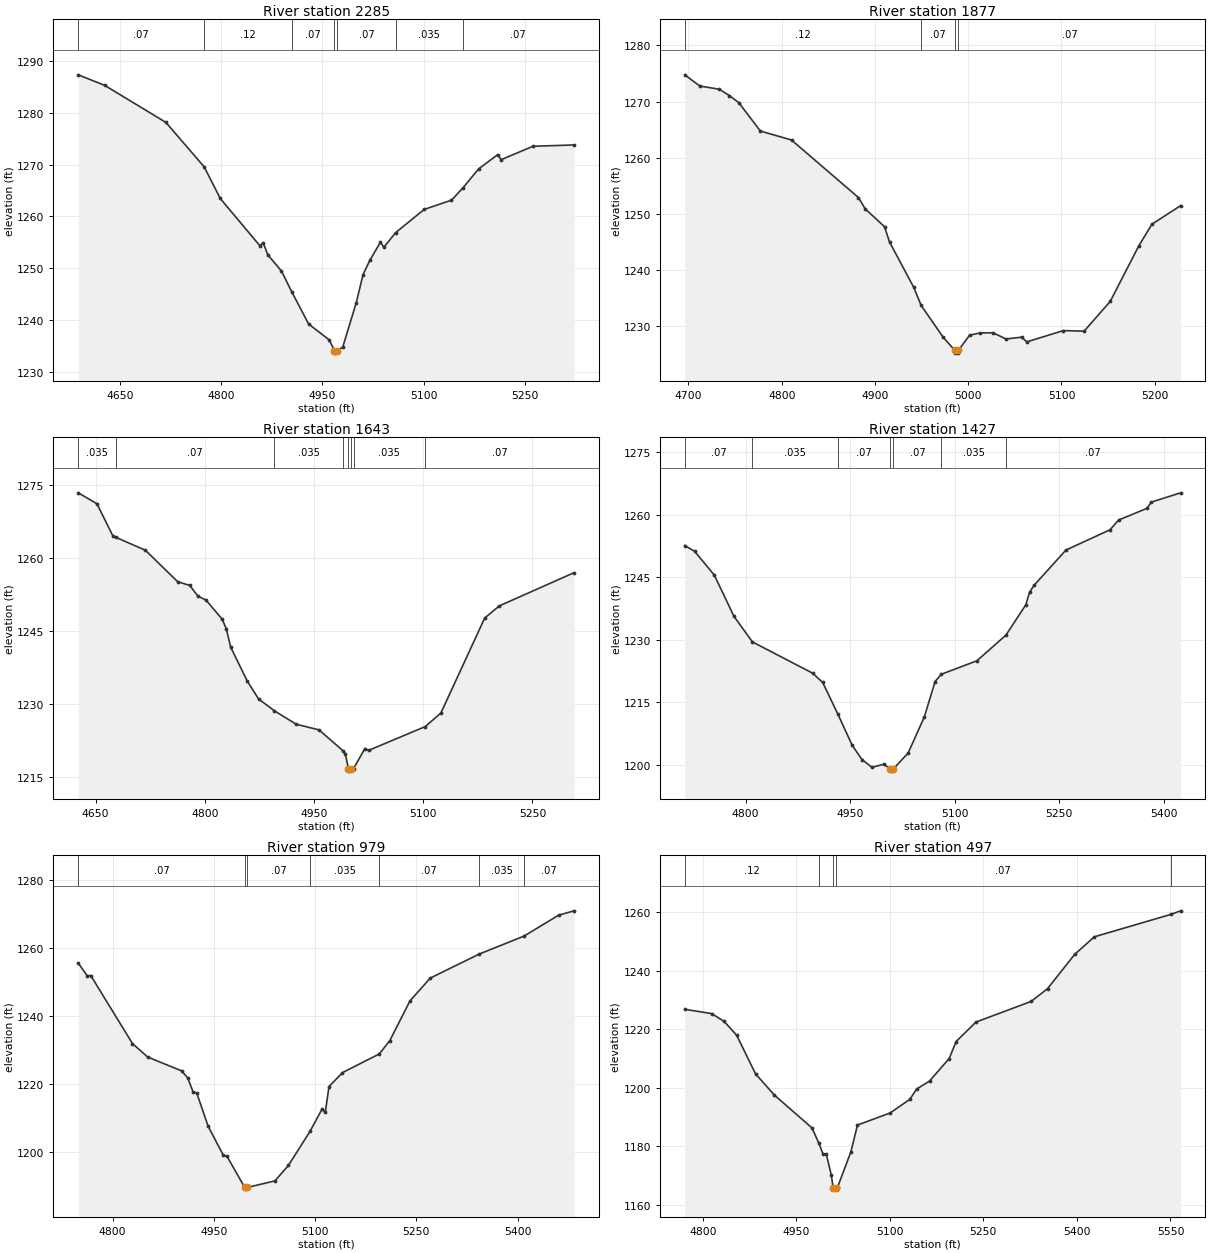
Type RM Length L Ch R = 1,2285,408,408,408
BEGIN DESCRIPTION:
Stream0091_DS 5.0
END DESCRIPTION:
XS GIS Cut Line= 2
      2077083.93     13877280.88      2076354.58     13877197.53
#Sta/Elev= 30
  4588.4 1287.29  4627.6 1285.26  4718.2 1278.12  4774.9 1269.55  4798.7 1263.45
  4857.2 1254.36  4862.2 1254.92  4869.2 1252.57  4889.3 1249.47  4905.0 1245.34
  4929.5 1239.26  4959.7 1236.22  4967.8 1234.14  4968.1 1233.64  4971.8 1234.14
  4979.9 1234.76  5000.0 1243.35  5010.1 1248.78  5020.1 1251.53  5035.9 1255.04
  5040.9 1254.05  5058.5 1256.89  5100.6 1261.34  5140.9 1263.12  5157.3 1265.40
  5181.2 1269.16  5209.5 1271.91  5214.5 1270.93  5261.7 1273.52  5322.5 1273.77
#Mann=7,-1,0
  4588.4    0.07       0  4774.9    0.12       0  4905.0    0.07       0
  4967.8    0.05       0  4971.8    0.07       0  5058.5   0.035       0
  5157.3    0.07       0
Bank Sta=4967.8,4971.8
Exp/Cntr=0.3,0.1

Type RM Length L Ch R = 1,1877,234,234,234
BEGIN DESCRIPTION:
Stream0091_DS 4.0
END DESCRIPTION:
XS GIS Cut Line= 3
      2076970.57     13876912.13      2076675.00     13876825.00
      2076474.96     13876724.98
#Sta/Elev= 30
  4696.0 1274.77  4712.2 1272.78  4733.1 1272.20  4743.8 1271.08  4753.9 1269.83
  4777.1 1264.76  4810.5 1263.16  4882.3 1252.92  4889.5 1250.91  4910.3 1247.71
  4915.6 1245.01  4941.6 1236.92  4949.5 1233.72  4972.9 1228.09  4985.5 1225.71
  4985.7 1225.21  4989.2 1225.21  4989.5 1225.71  5001.5 1228.40  5012.5 1228.80
  5026.5 1228.84  5040.5 1227.73  5057.3 1228.05  5062.8 1227.21  5102.0 1229.22
  5124.3 1229.12  5152.3 1234.42  5183.0 1244.33  5197.0 1248.16  5227.8 1251.48
#Mann=4,-1,0
  4696.0    0.12       0  4949.5    0.07       0  4985.5    0.05       0
  4989.5    0.07       0
Bank Sta=4985.5,4989.5
Exp/Cntr=0.3,0.1

Type RM Length L Ch R = 1,1643,216,216,216
BEGIN DESCRIPTION:
Stream0091_DS 3.5
END DESCRIPTION:
XS GIS Cut Line= 3
      2077071.50     13876782.45      2076738.79     13876611.86
      2076432.70     13876584.60
#Sta/Elev= 30
  4626.1 1273.31  4651.8 1271.07  4674.0 1264.39  4677.7 1264.19  4718.4 1261.53
  4762.8 1255.07  4779.4 1254.31  4790.7 1252.08  4801.6 1251.32  4823.8 1247.40
  4829.4 1245.47  4835.7 1241.60  4858.2 1234.74  4873.8 1231.03  4895.7 1228.59
  4925.6 1225.84  4957.0 1224.68  4989.9 1220.39  4993.0 1219.79  4997.3 1216.72
  4997.6 1216.22  5001.3 1216.72  5004.3 1216.72  5019.9 1220.85  5024.9 1220.47
  5102.9 1225.36  5124.3 1228.14  5184.5 1247.62  5204.6 1250.12  5307.3 1256.93
#Mann=8,-1,0
  4626.1   0.035       0  4677.7    0.07       0  4895.7   0.035       0
  4989.9    0.07       0  4997.3    0.05       0  5001.3    0.07       0
  5004.3   0.035       0  5102.9    0.07       0
Bank Sta=4997.3,5001.3
Exp/Cntr=0.3,0.1

Type RM Length L Ch R = 1,1427,448,448,448
BEGIN DESCRIPTION:
Stream0091_DS 3.0
END DESCRIPTION:
XS GIS Cut Line= 3
      2077024.99     13876624.99      2076825.00     13876425.00
      2076432.39     13876252.41
#Sta/Elev= 30
  4712.6 1252.66  4726.7 1251.28  4755.0 1245.57  4783.3 1235.64  4809.7 1229.51
  4896.4 1221.98  4910.6 1219.77  4932.0 1212.30  4953.0 1204.66  4967.1 1201.23
  4981.3 1199.40  4998.2 1200.13  5007.8 1198.98  5008.1 1198.48  5011.8 1198.98
  5033.2 1202.82  5056.5 1211.51  5071.9 1220.00  5081.0 1221.75  5132.0 1224.98
  5173.6 1231.14  5202.1 1238.41  5207.5 1241.44  5213.9 1243.09  5259.7 1251.57
  5323.1 1256.44  5335.2 1258.77  5376.4 1261.61  5381.9 1263.06  5424.3 1265.31
#Mann=7,-1,0
  4712.6    0.07       0  4809.7   0.035       0  4932.0    0.07       0
  5007.8    0.05       0  5011.8    0.07       0  5081.0   0.035       0
  5173.6    0.07       0
Bank Sta=5007.8,5011.8
Exp/Cntr=0.3,0.1

Type RM Length L Ch R = 1,979,482,482,482
BEGIN DESCRIPTION:
Stream0091_DS 2.0
END DESCRIPTION:
XS GIS Cut Line= 3
      2077300.45     13876186.44      2077075.00     13876075.00
      2076592.16     13876096.16
#Sta/Elev= 30
  4749.0 1255.65  4762.1 1251.95  4767.7 1251.93  4829.4 1231.91  4851.9 1227.95
  4902.3 1223.86  4911.3 1221.78  4919.2 1217.70  4924.7 1217.31  4941.6 1207.52
  4964.0 1199.01  4969.6 1198.66  4995.7 1189.53  4996.0 1189.03  4999.7 1189.53
  5040.5 1191.46  5060.6 1196.04  5092.6 1206.09  5110.1 1212.54  5115.2 1211.75
  5120.6 1219.23  5140.6 1223.36  5195.0 1228.84  5210.7 1232.77  5240.7 1244.52
  5270.8 1251.22  5343.2 1258.28  5409.8 1263.59  5460.9 1269.75  5483.8 1271.02
#Mann=7,-1,0
  4749.0    0.07       0  4995.7    0.05       0  4999.7    0.07       0
  5092.6   0.035       0  5195.0    0.07       0  5343.2   0.035       0
  5409.8    0.07       0
Bank Sta=4995.7,4999.7
Exp/Cntr=0.3,0.1

Type RM Length L Ch R = 1,497,331,331,331
BEGIN DESCRIPTION:
Stream0091_DS 1.0
END DESCRIPTION:
XS GIS Cut Line= 3
      2077397.67     13875651.72      2077175.00     13875625.00
      2076633.82     13875443.40
#Sta/Elev= 30
  4771.2 1226.84  4814.2 1225.38  4834.3 1222.72  4854.5 1217.97  4884.7 1204.80
  4914.9 1197.55  4975.3 1186.32  4986.0 1181.20  4992.9 1177.45  4998.1 1177.45
  5006.0 1170.40  5009.2 1165.92  5009.5 1165.42  5013.2 1165.92  5016.6 1166.27
  5037.5 1178.11  5048.2 1187.30  5100.6 1191.44  5132.1 1196.08  5143.1 1199.61
  5163.7 1202.33  5195.2 1210.02  5206.4 1215.84  5238.1 1222.48  5326.6 1229.52
  5352.9 1233.88  5396.3 1245.56  5427.9 1251.59  5550.6 1259.25  5566.3 1260.47
#Mann=5,-1,0
  4771.2    0.12       0  4986.0    0.07       0  5009.2    0.05       0
  5013.2    0.07       0  5550.6   0.035       0
Bank Sta=5009.2,5013.2
Exp/Cntr=0.3,0.1

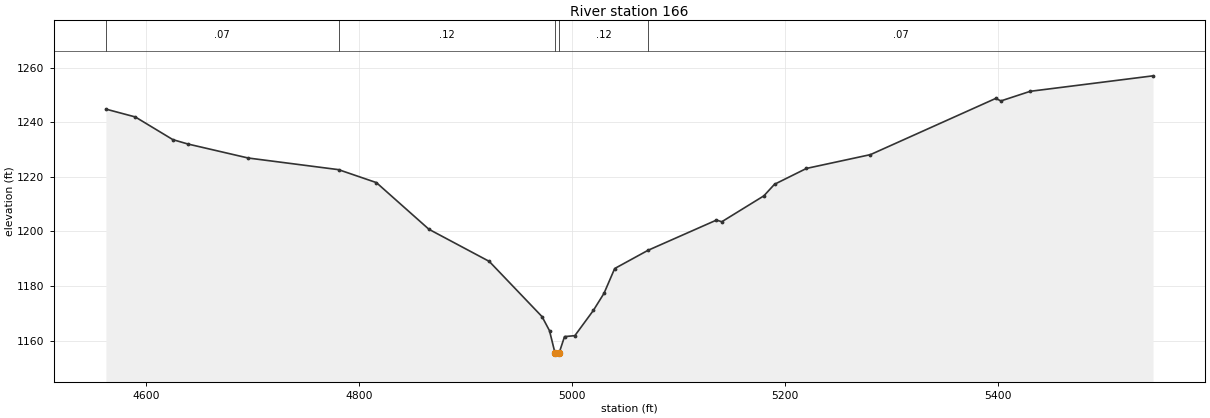
Type RM Length L Ch R = 1,166,0,0,0
BEGIN DESCRIPTION:
Stream0091_DS 0.0
END DESCRIPTION:
XS GIS Cut Line= 3
      2077588.89     13875630.15      2077274.67     13875324.86
      2076729.76     13875345.50
#Sta/Elev= 30
  4561.9 1244.81  4589.5 1241.94  4624.8 1233.62  4638.9 1232.02  4695.5 1226.89
  4780.4 1222.62  4815.9 1217.88  4865.3 1200.76  4921.9 1189.00  4971.5 1168.75
  4978.5 1163.59  4983.6 1155.51  4983.8 1155.01  4987.6 1155.51  4992.6 1161.43
  5002.3 1161.78  5019.7 1171.04  5029.7 1177.31  5039.7 1186.38  5071.0 1193.06
  5135.3 1204.14  5140.3 1203.53  5179.8 1213.02  5189.8 1217.26  5219.8 1223.07
  5279.9 1228.13  5397.5 1248.72  5402.5 1247.82  5430.0 1251.34  5545.3 1257.01
#Mann=5,-1,0
  4561.9    0.07       0  4780.4    0.12       0  4983.6    0.05       0
  4987.6    0.12       0  5071.0    0.07       0
Bank Sta=4983.6,4987.6
Exp/Cntr=0.3,0.1

Chan Stop Cuts=-1