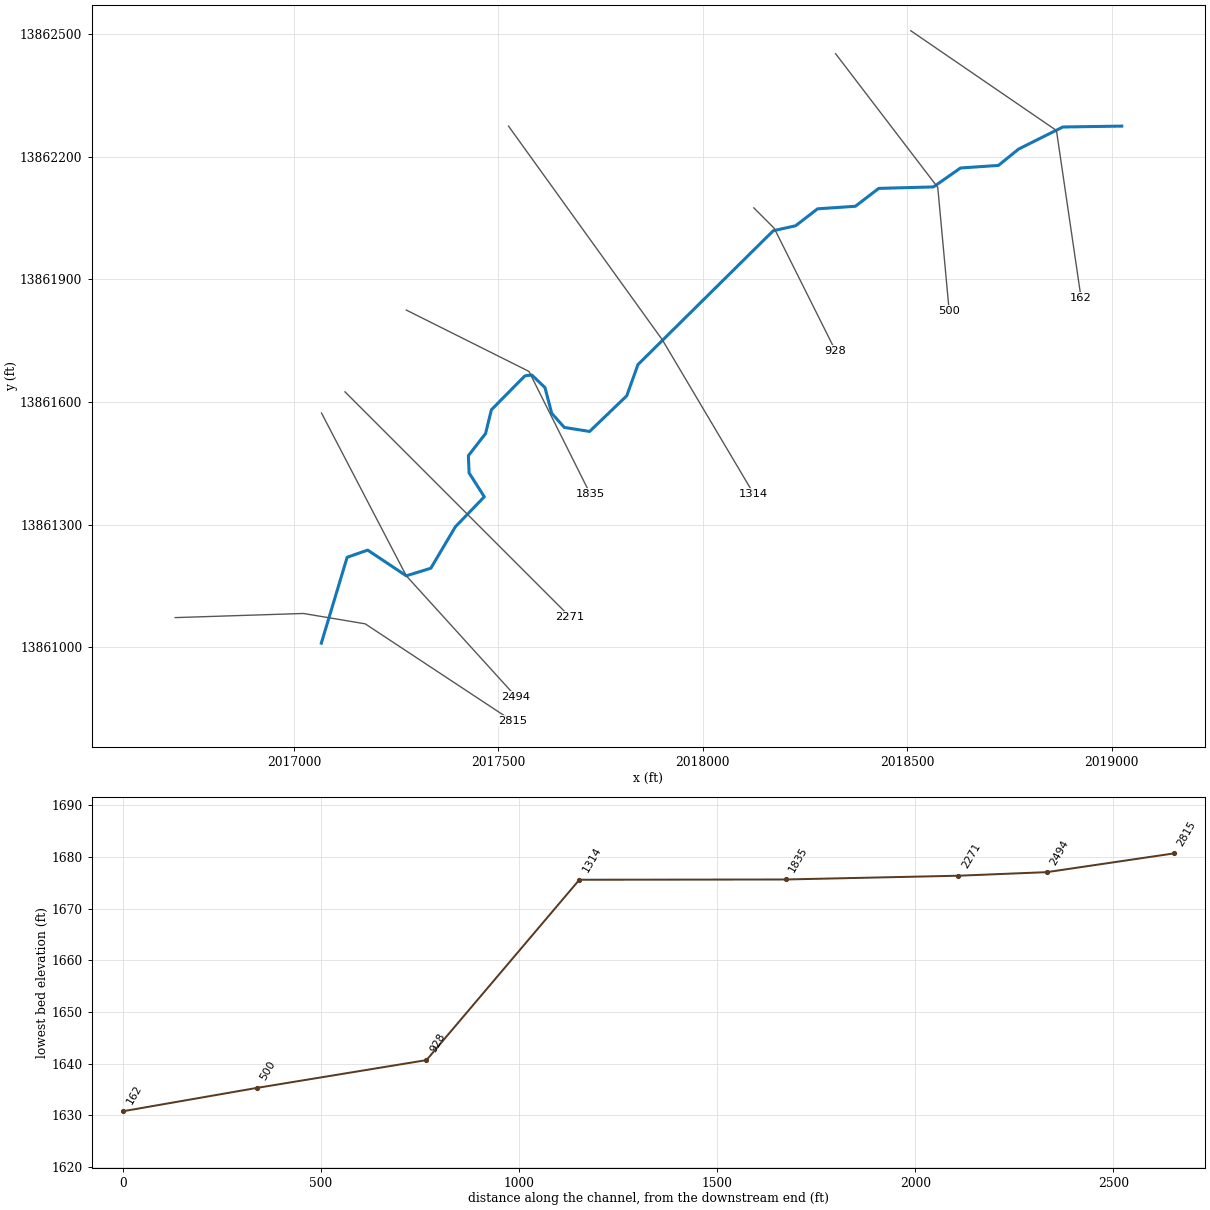
--- Stream0092_DS.prj (project) ---

Proj Title=Stream0092_DS Base Level Engineering
Current Plan=p01
Default Exp/Contr=0.3,0.1
English Units
Geom File=g01
Flow File=f01
Plan File=p01
BEGIN DESCRIPTION:
Stream0092_DS
END DESCRIPTION:

--- Stream0092_DS.p01 (plan) ---

Plan Title=Multiple Run
Short Identifier=Multiple
Geom File=g01
Flow File=f01
Subcritical Flow
K Sum by GR= 0
Std Step Tol= 0.01
Critical Tol= 0.01
Num of Std Step Trials= 20
Max Error Tol= 0.3
Flow Tol Ratio= 0.001
Split Flow NTrial= 30
Split Flow Tol= 0.02
Split Flow Ratio= 0.02
Log Output Level= 0
Friction Slope Method= 1
Unsteady Friction Slope Method= 2
Unsteady Bridges Friction Slope Method= 1
Parabolic Critical Depth
Global Vel Dist=  1 , 1 , 1
Global Log Level= 0
CheckData=True
Encroach Param= -1, 0, 0, 0
BEGIN DESCRIPTION:
Multiple Run
END DESCRIPTION:

--- Stream0092_DS.f01 (steady flow) ---

Flow Title=Multiple
Number of Profiles=7
Profile Names=10-year,25-year,50-year,1pct_min,100-year,1pct_plu,500-year
River Rch & RM= Stream0092_DS,Reach-1,2815
     874    1476    2050    1382    2758    5502    4933
River Rch & RM= Stream0092_DS,Reach-1,2271
    1016    1728    2410    1631    3253    6491    5864
Boundary for River Rch & Prof#=Stream0092_DS,Reach-1,1
Up Type=0
Dn Type=3
Dn Slope=0.005
Boundary for River Rch & Prof#=Stream0092_DS,Reach-1,2
Up Type=0
Dn Type=3
Dn Slope=0.005
Boundary for River Rch & Prof#=Stream0092_DS,Reach-1,3
Up Type=0
Dn Type=3
Dn Slope=0.005
Boundary for River Rch & Prof#=Stream0092_DS,Reach-1,4
Up Type=0
Dn Type=3
Dn Slope=0.005
Boundary for River Rch & Prof#=Stream0092_DS,Reach-1,5
Up Type=0
Dn Type=3
Dn Slope=0.005
Boundary for River Rch & Prof#=Stream0092_DS,Reach-1,6
Up Type=0
Dn Type=3
Dn Slope=0.005
Boundary for River Rch & Prof#=Stream0092_DS,Reach-1,7
Up Type=0
Dn Type=3
Dn Slope=0.005

--- Stream0092_DS.g01 (geometry) ---

Geom Title=Existing Conditions

River Reach=Stream0092_DS,Reach-1
Reach XY= 30
      2017067.15     13861010.26      2017130.32     13861220.31
      2017180.51     13861237.88      2017275.00     13861175.00
      2017335.00     13861193.52      2017395.09     13861295.00
      2017465.85     13861368.27      2017428.61     13861426.63
      2017426.84     13861468.88      2017468.82     13861522.82
      2017483.14     13861581.09      2017565.11     13861664.11
      2017581.94     13861666.16      2017614.21     13861635.41
      2017630.75     13861572.44      2017661.44     13861537.97
      2017723.34     13861528.08      2017814.23     13861615.30
      2017841.65     13861691.67      2018172.70     13862019.17
      2018227.17     13862031.14      2018280.97     13862072.67
      2018373.40     13862078.86      2018430.53     13862122.61
      2018564.49     13862126.23      2018630.57     13862172.53
      2018723.42     13862178.83      2018772.82     13862218.89
      2018880.91     13862272.80      2019025.00     13862275.00

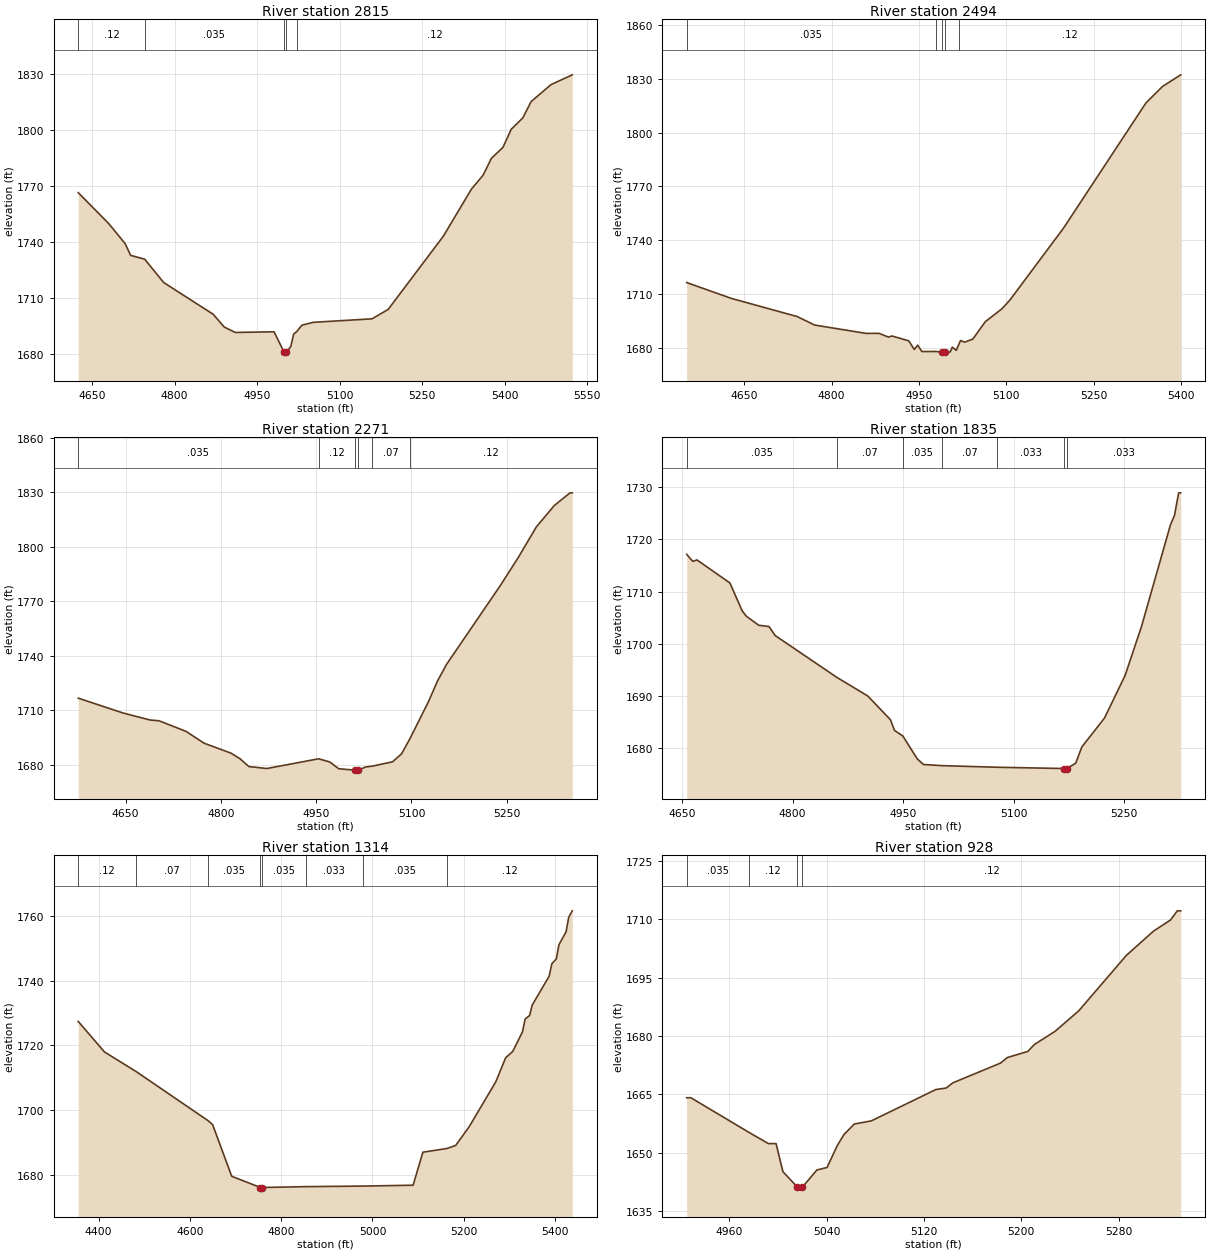
Type RM Length L Ch R = 1,2815,321,321,321
BEGIN DESCRIPTION:
Stream0092_DS 7.0
END DESCRIPTION:
XS GIS Cut Line= 4
      2016709.77     13861072.76      2017023.47     13861082.87
      2017174.41     13861057.56      2017534.36     13860819.98
#Sta/Elev= 30
  4624.8 1766.67  4680.1 1750.15  4710.1 1739.37  4720.1 1733.08  4745.6 1731.05
  4780.1 1718.54  4870.2 1701.52  4890.2 1694.71  4910.2 1691.79  4980.8 1692.14
  4999.1 1681.21  4999.3 1680.71  5003.1 1681.21  5011.2 1684.24  5016.4 1690.84
  5022.3 1692.36  5031.5 1695.67  5051.7 1697.20  5159.1 1699.09  5188.3 1704.14
  5288.5 1743.32  5339.7 1768.60  5360.8 1776.02  5375.9 1785.06  5396.9 1790.92
  5412.0 1800.65  5433.0 1806.69  5448.1 1815.45  5484.2 1824.54  5523.0 1829.80
#Mann=5,-1,0
  4624.8    0.12       0  4745.6   0.035       0  4999.1   0.035       0
  5003.1   0.035       0  5022.3    0.12       0
Bank Sta=4999.1,5003.1
Exp/Cntr=0.3,0.1

Type RM Length L Ch R = 1,2494,223,223,223
BEGIN DESCRIPTION:
Stream0092_DS 6.0
END DESCRIPTION:
XS GIS Cut Line= 3
      2017067.58     13861573.22      2017275.00     13861175.00
      2017543.35     13860879.32
#Sta/Elev= 30
  4551.0 1716.42  4627.9 1707.57  4740.7 1697.48  4770.8 1692.72  4859.2 1688.08
  4881.3 1688.10  4897.7 1686.00  4903.4 1686.65  4932.3 1683.95  4941.9 1679.09
  4947.6 1681.54  4954.9 1677.96  4979.4 1678.01  4989.8 1677.58  4990.0 1677.08
  4993.8 1677.58  5003.4 1677.70  5007.1 1680.42  5013.8 1678.64  5018.4 1682.00
  5021.3 1684.12  5028.0 1683.18  5042.2 1684.85  5063.9 1694.66  5092.2 1701.75
  5106.4 1706.82  5198.3 1746.86  5339.6 1816.53  5368.0 1825.70  5399.3 1832.20
#Mann=5,-1,0
  4551.0   0.035       0  4979.4    0.07       0  4989.8    0.05       0
  4993.8    0.07       0  5018.4    0.12       0
Bank Sta=4989.8,4993.8
Exp/Cntr=0.3,0.1

Type RM Length L Ch R = 1,2271,436,436,436
BEGIN DESCRIPTION:
Stream0092_DS 5.0
END DESCRIPTION:
XS GIS Cut Line= 3
      2017125.02     13861624.98      2017425.00     13861325.00
      2017675.01     13861074.99
#Sta/Elev= 30
  4575.4 1716.59  4646.1 1708.39  4688.5 1704.55  4702.7 1704.13  4745.1 1698.29
  4773.4 1691.80  4815.8 1686.31  4829.9 1683.26  4844.1 1678.90  4872.4 1677.83
  4953.7 1683.18  4971.4 1681.45  4985.5 1677.71  5011.8 1676.89  5012.0 1676.39
  5015.8 1676.89  5027.9 1678.67  5038.5 1679.15  5070.3 1681.54  5084.5 1685.95
  5097.6 1694.27  5126.9 1714.74  5141.1 1726.09  5155.2 1735.17  5240.1 1778.72
  5268.3 1794.15  5296.6 1810.90  5324.9 1822.71  5349.7 1829.69  5353.2 1829.69
#Mann=6,-1,0
  4575.4   0.035       0  4953.7    0.12       0  5011.8    0.05       0
  5015.8    0.12       0  5038.5    0.07       0  5097.6    0.12       0
Bank Sta=5011.8,5015.8
Exp/Cntr=0.3,0.1

Type RM Length L Ch R = 1,1835,521,521,521
BEGIN DESCRIPTION:
Stream0092_DS 4.0
END DESCRIPTION:
XS GIS Cut Line= 3
      2017274.97     13861825.01      2017575.00     13861675.00
      2017725.02     13861374.96
#Sta/Elev= 30
  4656.1 1717.11  4664.5 1715.76  4670.1 1716.04  4714.8 1711.64  4731.6 1706.28
  4737.2 1705.27  4754.0 1703.55  4767.9 1703.31  4776.3 1701.58  4860.9 1693.51
  4902.1 1690.02  4932.8 1685.49  4938.4 1683.43  4949.6 1682.39  4969.2 1678.01
  4977.6 1676.93  5002.7 1676.71  5077.9 1676.40  5168.4 1676.16  5168.7 1675.66
  5172.4 1676.16  5184.4 1677.18  5192.8 1680.30  5223.5 1685.81  5251.5 1693.96
  5273.8 1703.34  5313.0 1722.72  5318.6 1724.59  5324.2 1728.87  5327.0 1728.87
#Mann=7,-1,0
  4656.1   0.035       0  4860.9    0.07       0  4949.6   0.035       0
  5002.7    0.07       0  5077.9   0.033       0  5168.4   0.035       0
  5172.4   0.033       0
Bank Sta=5168.4,5172.4
Exp/Cntr=0.3,0.1

Type RM Length L Ch R = 1,1314,386,386,386
BEGIN DESCRIPTION:
Stream0092_DS 3.0
END DESCRIPTION:
XS GIS Cut Line= 3
      2017525.03     13862274.96      2017901.62     13861751.69
      2018124.98     13861375.04
#Sta/Elev= 30
  4355.3 1727.43  4412.9 1717.99  4482.3 1711.94  4639.6 1696.79  4649.8 1695.54
  4691.6 1679.58  4754.6 1676.11  4754.9 1675.61  4758.6 1676.11  4854.1 1676.38
  4978.8 1676.55  5089.1 1676.82  5110.5 1687.02  5162.9 1688.16  5182.2 1689.09
  5211.9 1694.88  5270.3 1708.78  5291.8 1716.18  5307.4 1718.17  5328.8 1724.22
  5334.6 1728.19  5344.4 1729.27  5350.2 1732.52  5387.3 1741.44  5393.1 1745.28
  5402.9 1746.77  5408.7 1751.15  5424.3 1755.15  5430.1 1759.64  5437.9 1761.62
#Mann=8,-1,0
  4355.3    0.12       0  4482.3    0.07       0  4639.6   0.035       0
  4754.6   0.035       0  4758.6   0.035       0  4854.1   0.033       0
  4978.8   0.035       0  5162.9    0.12       0
Bank Sta=4754.6,4758.6
Exp/Cntr=0.3,0.1

Type RM Length L Ch R = 1,928,428,428,428
BEGIN DESCRIPTION:
Stream0092_DS 2.0
END DESCRIPTION:
XS GIS Cut Line= 3
      2018125.01     13862074.99      2018175.00     13862025.00
      2018325.00     13861725.01
#Sta/Elev= 30
  4925.0 1664.16  4928.5 1664.16  4976.2 1655.26  4992.2 1652.38  4998.5 1652.38
  5004.1 1645.17  5016.1 1641.18  5016.3 1640.68  5019.8 1640.68  5020.1 1641.18
  5032.0 1645.59  5040.4 1646.25  5048.8 1651.87  5054.4 1654.75  5062.8 1657.41
  5076.8 1658.22  5129.9 1666.28  5138.2 1666.65  5143.8 1667.99  5183.0 1673.07
  5188.6 1674.49  5205.3 1676.05  5210.9 1677.86  5227.7 1681.20  5247.3 1686.50
  5286.4 1700.73  5308.7 1706.97  5322.7 1709.83  5328.3 1712.19  5331.1 1712.19
#Mann=4,-1,0
  4925.0   0.035       0  4976.2    0.12       0  5016.1    0.05       0
  5020.1    0.12       0
Bank Sta=5016.1,5020.1
Exp/Cntr=0.3,0.1

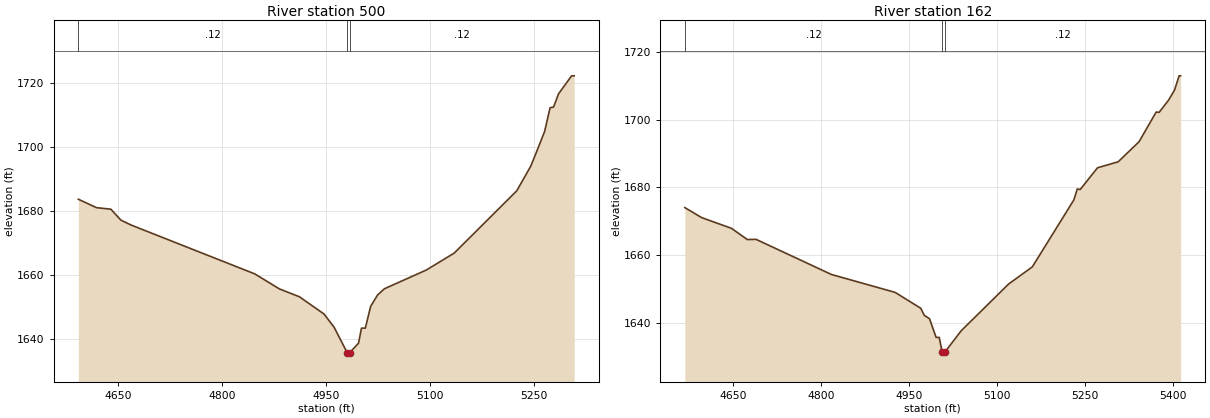
Type RM Length L Ch R = 1,500,338,338,338
BEGIN DESCRIPTION:
Stream0092_DS 1.0
END DESCRIPTION:
XS GIS Cut Line= 3
      2018325.15     13862451.97      2018575.00     13862125.00
      2018602.93     13861822.59
#Sta/Elev= 30
  4592.8 1683.70  4618.9 1681.07  4639.7 1680.58  4654.2 1677.17  4668.7 1675.65
  4847.4 1660.36  4882.8 1655.68  4911.8 1653.21  4947.2 1647.83  4961.7 1643.72
  4980.5 1635.80  4980.8 1635.30  4984.5 1635.80  4997.0 1638.74  5001.2 1643.42
  5006.8 1643.42  5014.4 1650.18  5024.4 1653.76  5034.4 1655.73  5094.7 1661.57
  5134.9 1666.85  5225.2 1686.32  5245.3 1693.98  5255.4 1699.37  5265.4 1704.87
  5273.3 1712.28  5278.3 1712.50  5285.5 1716.62  5304.3 1722.25  5308.0 1722.25
#Mann=3,-1,0
  4592.8    0.12       0  4980.5    0.05       0  4984.5    0.12       0
Bank Sta=4980.5,4984.5
Exp/Cntr=0.3,0.1

Type RM Length L Ch R = 1,162,0,0,0
BEGIN DESCRIPTION:
Stream0092_DS 0.0
END DESCRIPTION:
XS GIS Cut Line= 3
      2018509.07     13862508.20      2018865.33     13862264.21
      2018925.50     13861854.81
#Sta/Elev= 30
  4568.2 1674.02  4597.0 1671.06  4647.8 1667.90  4674.8 1664.59  4689.7 1664.65
  4818.3 1654.28  4926.9 1649.00  4970.7 1644.30  4976.7 1642.21  4985.6 1641.23
  4996.8 1635.72  5002.1 1635.72  5007.3 1631.28  5007.6 1630.78  5011.3 1631.28
  5039.6 1637.68  5120.5 1651.47  5160.9 1656.53  5231.7 1676.28  5237.6 1679.51
  5242.6 1679.37  5272.1 1685.77  5307.3 1687.53  5342.9 1693.45  5372.1 1702.21
  5377.1 1702.12  5393.4 1705.76  5403.5 1708.73  5411.2 1712.90  5413.8 1712.90
#Mann=3,-1,0
  4568.2    0.12       0  5007.3    0.05       0  5011.3    0.12       0
Bank Sta=5007.3,5011.3
Exp/Cntr=0.3,0.1

Chan Stop Cuts=-1