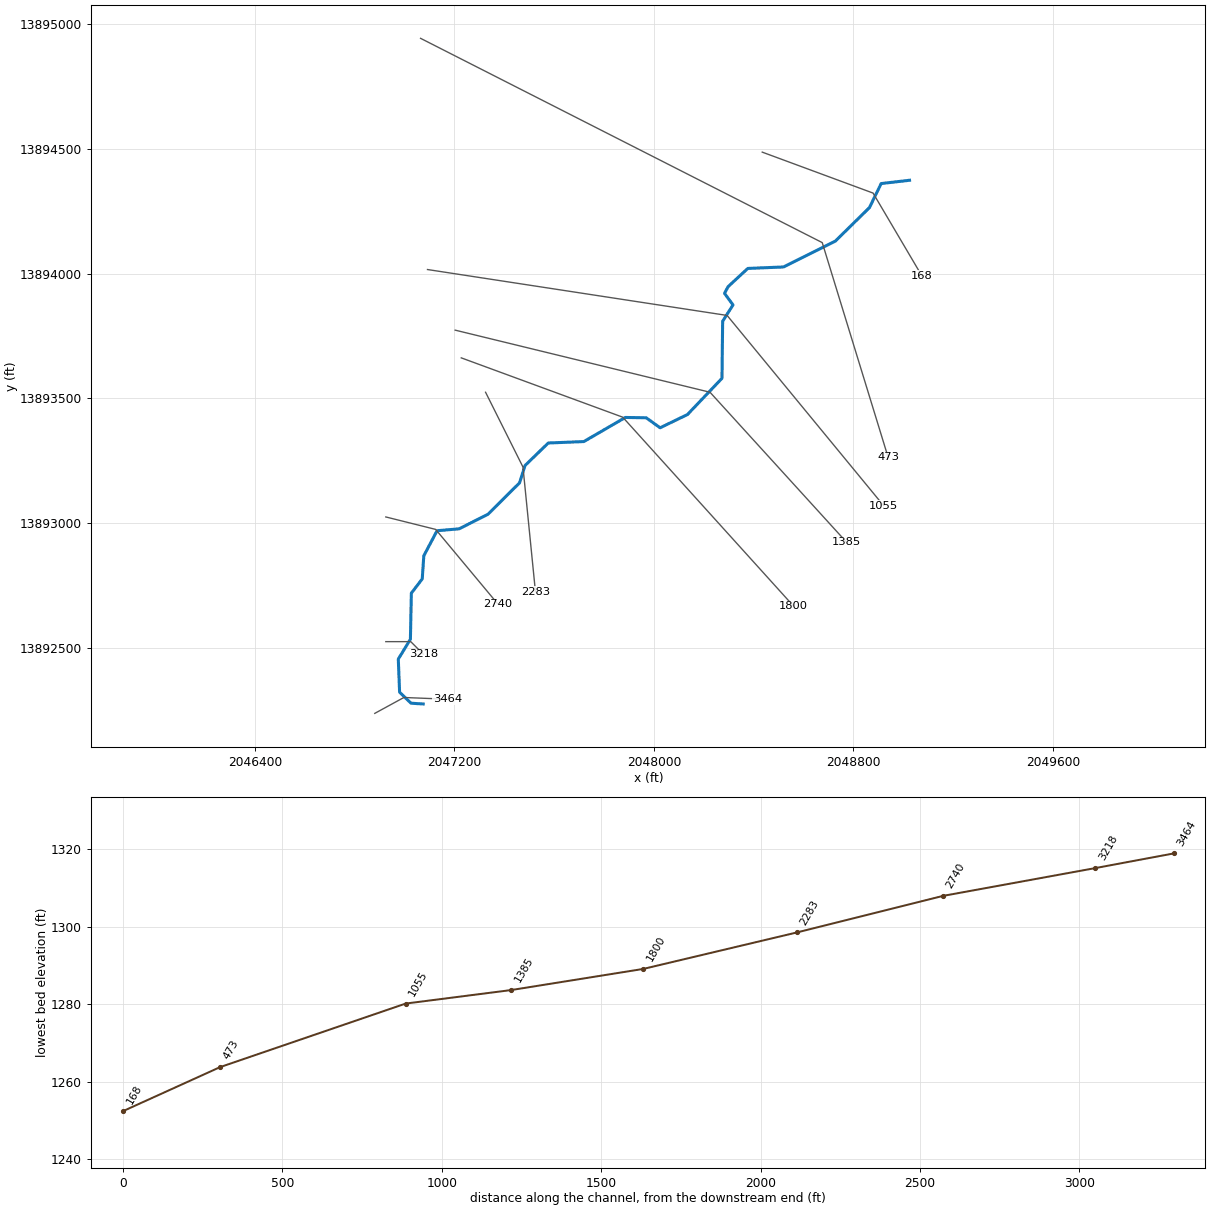
--- Stream0093_DS.prj (project) ---

Proj Title=Stream0093_DS Base Level Engineering
Current Plan=p01
Default Exp/Contr=0.3,0.1
English Units
Geom File=g01
Flow File=f01
Plan File=p01
BEGIN DESCRIPTION:
Stream0093_DS
END DESCRIPTION:

--- Stream0093_DS.p01 (plan) ---

Plan Title=Multiple Run
Short Identifier=Multiple
Geom File=g01
Flow File=f01
Subcritical Flow
K Sum by GR= 0
Std Step Tol= 0.01
Critical Tol= 0.01
Num of Std Step Trials= 20
Max Error Tol= 0.3
Flow Tol Ratio= 0.001
Split Flow NTrial= 30
Split Flow Tol= 0.02
Split Flow Ratio= 0.02
Log Output Level= 0
Friction Slope Method= 1
Unsteady Friction Slope Method= 2
Unsteady Bridges Friction Slope Method= 1
Parabolic Critical Depth
Global Vel Dist=  1 , 1 , 1
Global Log Level= 0
CheckData=True
Encroach Param= -1, 0, 0, 0
BEGIN DESCRIPTION:
Multiple Run
END DESCRIPTION:

--- Stream0093_DS.f01 (steady flow) ---

Flow Title=Multiple
Number of Profiles=7
Profile Names=10-year,25-year,50-year,1pct_min,100-year,1pct_plu,500-year
River Rch & RM= Stream0093_DS,Reach-1,3464
     299     462     604     385     768    1533    1223
River Rch & RM= Stream0093_DS,Reach-1,3218
     878    1464    2013    1344    2681    5349    4696
Boundary for River Rch & Prof#=Stream0093_DS,Reach-1,1
Up Type=0
Dn Type=3
Dn Slope=0.005
Boundary for River Rch & Prof#=Stream0093_DS,Reach-1,2
Up Type=0
Dn Type=3
Dn Slope=0.005
Boundary for River Rch & Prof#=Stream0093_DS,Reach-1,3
Up Type=0
Dn Type=3
Dn Slope=0.005
Boundary for River Rch & Prof#=Stream0093_DS,Reach-1,4
Up Type=0
Dn Type=3
Dn Slope=0.005
Boundary for River Rch & Prof#=Stream0093_DS,Reach-1,5
Up Type=0
Dn Type=3
Dn Slope=0.005
Boundary for River Rch & Prof#=Stream0093_DS,Reach-1,6
Up Type=0
Dn Type=3
Dn Slope=0.005
Boundary for River Rch & Prof#=Stream0093_DS,Reach-1,7
Up Type=0
Dn Type=3
Dn Slope=0.005

--- Stream0093_DS.g01 (geometry) ---

Geom Title=Existing Conditions

River Reach=Stream0093_DS,Reach-1
Reach XY= 30
      2047075.00     13892275.00      2047025.98     13892278.12
      2046980.26     13892322.31      2046975.05     13892454.96
      2047023.62     13892534.66      2047027.38     13892719.47
      2047071.14     13892776.60      2047077.32     13892869.06
      2047130.44     13892969.75      2047218.95     13892977.37
      2047334.68     13893035.76      2047461.37     13893161.79
      2047483.15     13893231.07      2047576.46     13893321.46
      2047719.07     13893327.25      2047885.55     13893423.91
      2047969.11     13893422.63      2048025.01     13893382.53
      2048134.68     13893435.75      2048272.94     13893580.85
      2048275.65     13893809.84      2048317.19     13893875.10
      2048283.14     13893921.68      2048297.49     13893948.39
      2048376.44     13894021.46      2048519.48     13894027.36
      2048727.30     13894130.83      2048864.22     13894265.34
      2048911.28     13894361.81      2049025.00     13894375.00

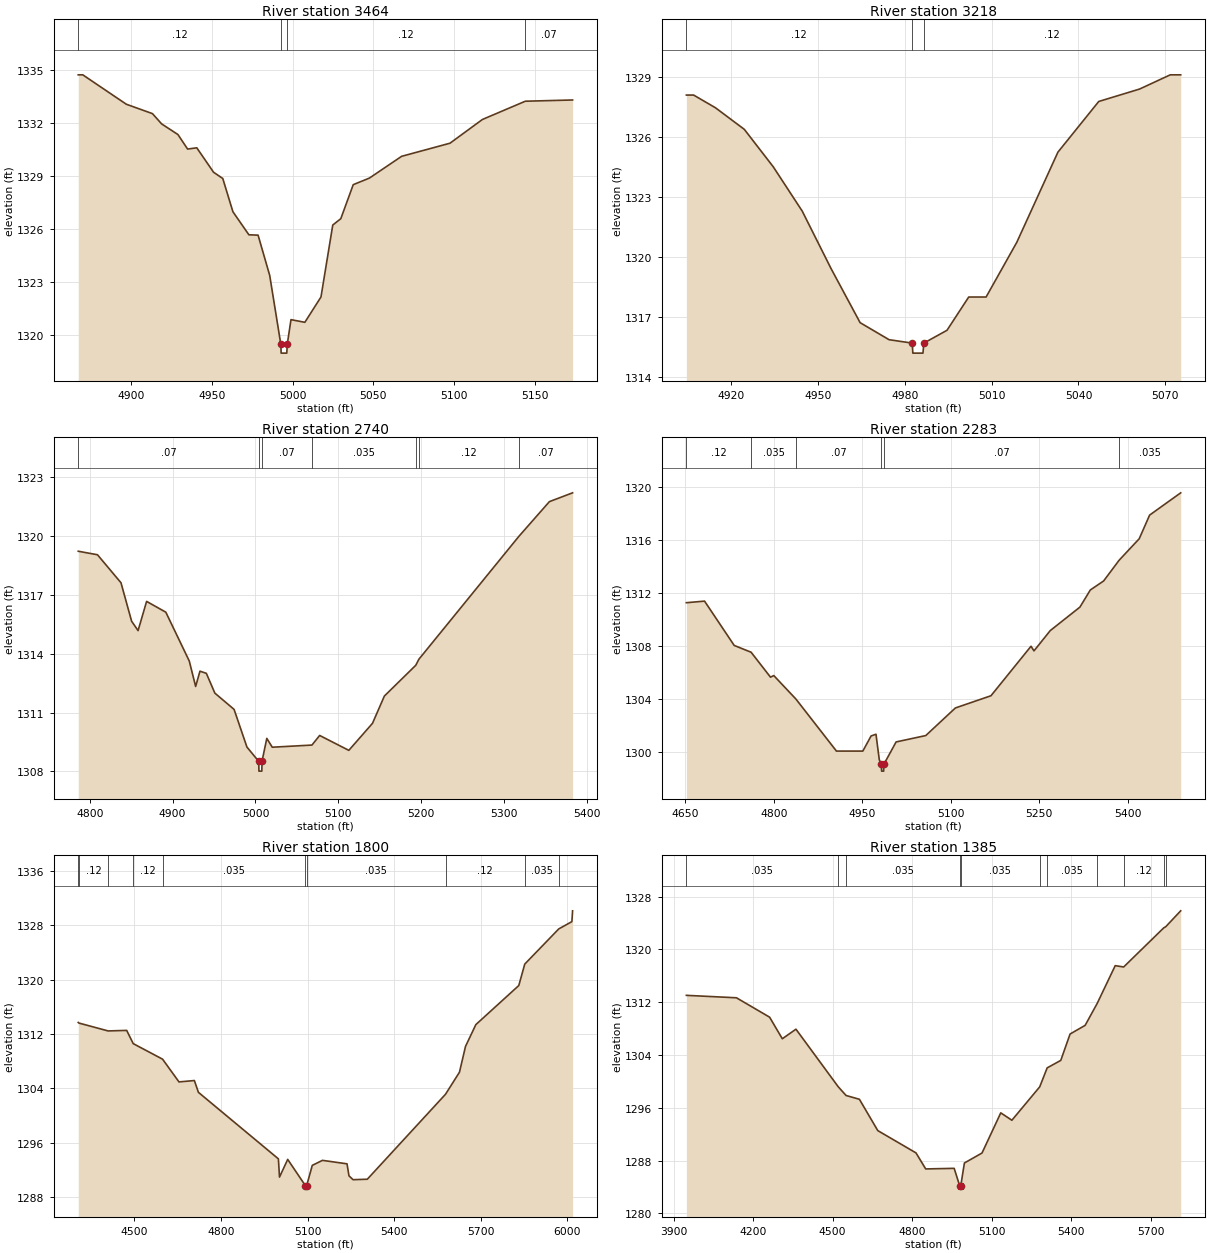
Type RM Length L Ch R = 1,3464,246,246,246
BEGIN DESCRIPTION:
Stream0093_DS 8.0
END DESCRIPTION:
XS GIS Cut Line= 3
      2046880.79     13892237.36      2046997.53     13892301.07
      2047170.90     13892294.19
#Sta/Elev= 30
  4867.0 1334.70  4869.8 1334.70  4896.8 1333.04  4913.0 1332.51  4918.7 1331.93
  4928.8 1331.33  4934.8 1330.51  4940.5 1330.58  4950.9 1329.20  4956.6 1328.85
  4962.9 1326.97  4972.8 1325.67  4978.5 1325.65  4985.7 1323.38  4992.6 1319.49
  4992.8 1318.99  4996.3 1318.99  4996.6 1319.49  4998.9 1320.88  5007.5 1320.73
  5017.5 1322.16  5024.8 1326.22  5029.8 1326.58  5037.5 1328.50  5047.5 1328.87
  5067.5 1330.10  5097.5 1330.84  5117.6 1332.18  5144.2 1333.21  5173.5 1333.28
#Mann=4,-1,0
  4867.0    0.12       0  4992.6    0.05       0  4996.6    0.12       0
  5144.2    0.07       0
Bank Sta=4992.6,4996.6
Exp/Cntr=0.3,0.1

Type RM Length L Ch R = 1,3218,478,478,478
BEGIN DESCRIPTION:
Stream0093_DS 7.0
END DESCRIPTION:
XS GIS Cut Line= 3
      2046925.03     13892525.00      2047025.00     13892525.00
      2047075.01     13892474.99
#Sta/Elev= 23
  4904.6 1328.08  4907.1 1328.08  4914.6 1327.45  4924.6 1326.37  4934.6 1324.50
  4944.6 1322.29  4954.6 1319.41  4964.6 1316.72  4974.6 1315.87  4982.6 1315.70
  4982.8 1315.20  4986.3 1315.20  4986.6 1315.70  4994.6 1316.34  5002.1 1318.00
  5004.6 1318.00  5008.1 1318.00  5018.7 1320.73  5032.9 1325.23  5047.0 1327.76
  5061.1 1328.38  5071.7 1329.09  5075.3 1329.09
#Mann=3,-1,0
  4904.6    0.12       0  4982.6    0.05       0  4986.6    0.12       0
Bank Sta=4982.6,4986.6
Exp/Cntr=0.3,0.1

Type RM Length L Ch R = 1,2740,457,457,457
BEGIN DESCRIPTION:
Stream0093_DS 6.0
END DESCRIPTION:
XS GIS Cut Line= 3
      2046924.98     13893025.00      2047125.00     13892975.00
      2047375.01     13892674.99
#Sta/Elev= 30
  4786.1 1319.23  4809.3 1319.05  4837.7 1317.62  4850.5 1315.66  4858.3 1315.18
  4868.6 1316.67  4891.8 1316.12  4920.1 1313.63  4927.8 1312.33  4933.0 1313.11
  4940.7 1313.00  4951.0 1311.99  4974.2 1311.16  4989.7 1309.24  5003.9 1308.51
  5004.2 1308.01  5007.7 1308.01  5007.9 1308.51  5013.7 1309.68  5020.3 1309.23
  5068.2 1309.34  5077.5 1309.83  5112.7 1309.07  5141.3 1310.45  5155.6 1311.84
  5193.5 1313.41  5197.3 1313.72  5317.8 1319.98  5354.8 1321.76  5382.8 1322.21
#Mann=7,-1,0
  4786.1    0.07       0  5003.9    0.05       0  5007.9    0.07       0
  5068.2   0.035       0  5193.5    0.07       0  5197.3    0.12       0
  5317.8    0.07       0
Bank Sta=5003.9,5007.9
Exp/Cntr=0.3,0.1

Type RM Length L Ch R = 1,2283,483,483,483
BEGIN DESCRIPTION:
Stream0093_DS 5.0
END DESCRIPTION:
XS GIS Cut Line= 3
      2047325.00     13893525.01      2047475.00     13893225.00
      2047525.00     13892725.01
#Sta/Elev= 30
  4651.9 1311.28  4682.7 1311.40  4733.0 1308.06  4761.6 1307.55  4794.5 1305.67
  4800.1 1305.79  4837.6 1304.02  4906.3 1300.10  4951.0 1300.10  4965.0 1301.24
  4973.3 1301.37  4978.9 1299.45  4982.5 1299.09  4982.8 1298.59  4986.3 1298.59
  4986.5 1299.09  5007.4 1300.79  5057.7 1301.27  5107.9 1303.35  5168.2 1304.27
  5236.1 1308.00  5241.1 1307.65  5268.7 1309.18  5319.0 1310.95  5336.6 1312.24
  5359.2 1312.92  5385.4 1314.48  5419.5 1316.10  5437.1 1317.88  5489.8 1319.56
#Mann=6,-1,0
  4651.9    0.12       0  4761.6   0.035       0  4837.6    0.07       0
  4982.5    0.05       0  4986.5    0.07       0  5385.4   0.035       0
Bank Sta=4982.5,4986.5
Exp/Cntr=0.3,0.1

Type RM Length L Ch R = 1,1800,415,415,415
BEGIN DESCRIPTION:
Stream0093_DS 4.0
END DESCRIPTION:
XS GIS Cut Line= 3
      2047227.55     13893662.88      2047875.00     13893425.00
      2048560.43     13892666.88
#Sta/Elev= 30
  4305.9 1313.70  4308.3 1313.61  4409.5 1312.45  4473.6 1312.53  4496.3 1310.58
  4597.9 1308.29  4654.7 1304.94  4708.0 1305.14  4722.1 1303.40  4999.0 1293.60
  5002.8 1290.91  5031.2 1293.52  5092.7 1289.64  5092.9 1289.14  5096.7 1289.64
  5116.3 1292.64  5151.5 1293.38  5236.6 1292.87  5243.4 1291.10  5257.6 1290.53
  5306.9 1290.60  5577.7 1303.12  5626.0 1306.37  5646.9 1310.17  5682.7 1313.38
  5831.4 1319.14  5852.1 1322.30  5969.7 1327.48  6015.3 1328.56  6017.7 1330.15
#Mann=10,-1,0
  4305.9   0.035       0  4308.3    0.12       0  4409.5   0.035       0
  4496.3    0.12       0  4597.9   0.035       0  5092.7   0.035       0
  5096.7   0.035       0  5577.7    0.12       0  5852.1   0.035       0
  5969.7    0.12       0
Bank Sta=5092.7,5096.7
Exp/Cntr=0.3,0.1

Type RM Length L Ch R = 1,1385,330,330,330
BEGIN DESCRIPTION:
Stream0093_DS 3.0
END DESCRIPTION:
XS GIS Cut Line= 3
      2047203.27     13893773.98      2048225.00     13893525.00
      2048772.72     13892923.29
#Sta/Elev= 30
  3948.1 1313.04  4137.1 1312.67  4262.2 1309.73  4310.1 1306.46  4361.6 1307.91
  4521.4 1299.17  4550.8 1297.86  4601.0 1297.29  4670.4 1292.54  4814.6 1289.16
  4851.2 1286.73  4958.6 1286.82  4979.5 1284.17  4979.7 1283.67  4983.5 1284.17
  4997.2 1287.63  5063.6 1289.14  5134.5 1295.23  5176.4 1294.11  5281.4 1299.17
  5309.6 1302.05  5360.9 1303.18  5396.0 1307.18  5452.8 1308.49  5498.1 1311.80
  5566.3 1317.54  5598.2 1317.34  5749.8 1323.28  5756.9 1323.44  5813.4 1325.85
#Mann=11,-1,0
  3948.1   0.035       0  4521.4    0.07       0  4550.8   0.035       0
  4979.5   0.035       0  4983.5   0.035       0  5281.4    0.07       0
  5309.6   0.035       0  5498.1    0.07       0  5598.2    0.12       0
  5749.8    0.07       0  5756.9   0.035       0
Bank Sta=4979.5,4983.5
Exp/Cntr=0.3,0.1

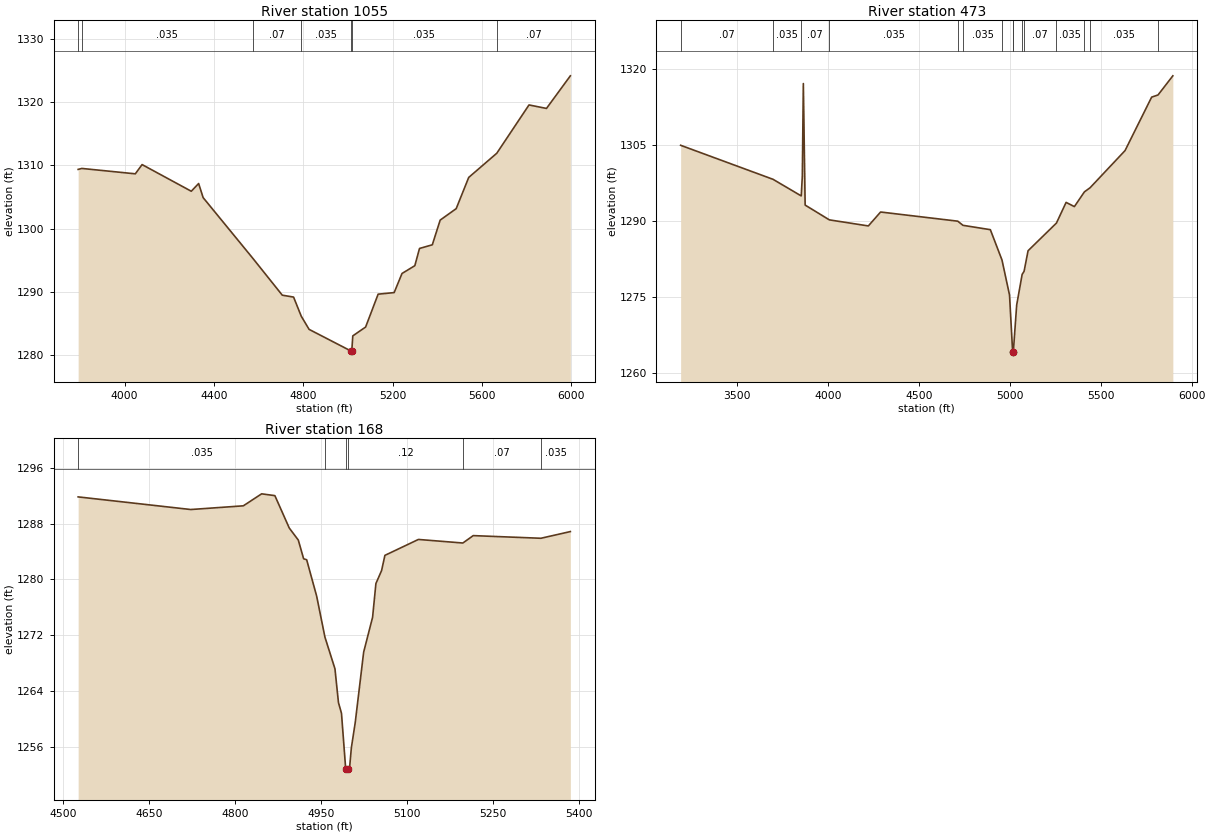
Type RM Length L Ch R = 1,1055,582,582,582
BEGIN DESCRIPTION:
Stream0093_DS 2.0
END DESCRIPTION:
XS GIS Cut Line= 3
      2047092.15     13894017.04      2048293.56     13893833.00
      2048920.63     13893070.83
#Sta/Elev= 30
  3792.5 1309.37  3809.3 1309.52  4048.3 1308.67  4078.6 1310.13  4298.7 1305.92
  4331.6 1307.14  4351.8 1304.91  4573.3 1295.36  4705.9 1289.50  4756.5 1289.20
  4790.8 1286.18  4825.9 1284.10  5012.9 1280.69  5013.2 1280.19  5016.9 1280.69
  5021.4 1283.07  5078.8 1284.47  5134.8 1289.66  5206.5 1289.91  5241.7 1292.93
  5299.0 1294.16  5319.9 1296.88  5377.2 1297.46  5412.4 1301.36  5484.1 1303.17
  5540.1 1308.10  5665.7 1311.92  5809.9 1319.55  5888.1 1319.00  5994.9 1324.15
#Mann=7,-1,0
  3792.5    0.07       0  3809.3   0.035       0  4573.3    0.07       0
  4790.8   0.035       0  5012.9   0.035       0  5016.9   0.035       0
  5665.7    0.07       0
Bank Sta=5012.9,5016.9
Exp/Cntr=0.3,0.1

Type RM Length L Ch R = 1,473,305,305,305
BEGIN DESCRIPTION:
Stream0093_DS 1.0
END DESCRIPTION:
XS GIS Cut Line= 3
      2047064.41     13894944.11      2048675.00     13894125.00
      2048939.39     13893263.58
#Sta/Elev= 30
  3188.5 1305.02  3696.8 1298.30  3852.0 1295.02  3858.0 1298.90  3863.6 1317.21
  3873.5 1293.21  4006.7 1290.29  4221.3 1289.09  4288.6 1291.84  4713.1 1290.03
  4741.9 1289.21  4892.5 1288.35  4956.6 1282.35  4998.0 1275.44  5015.0 1264.27
  5015.3 1263.77  5019.0 1264.27  5037.3 1273.46  5067.4 1279.52  5078.0 1280.12
  5100.0 1284.19  5256.1 1289.66  5309.2 1293.74  5354.8 1292.91  5410.0 1295.82
  5441.1 1296.63  5633.5 1303.97  5779.9 1314.53  5815.0 1314.96  5896.5 1318.74
#Mann=15,-1,0
  3188.5    0.07       0  3696.8   0.035       0  3852.0    0.07       0
  4006.7   0.035       0  4713.1    0.07       0  4741.9   0.035       0
  4956.6    0.07       0  5015.0    0.05       0  5019.0    0.07       0
  5067.4    0.12       0  5078.0    0.07       0  5256.1   0.035       0
  5410.0    0.07       0  5441.1   0.035       0  5815.0    0.12       0
Bank Sta=5015,5019
Exp/Cntr=0.3,0.1

Type RM Length L Ch R = 1,168,0,0,0
BEGIN DESCRIPTION:
Stream0093_DS 0.0
END DESCRIPTION:
XS GIS Cut Line= 3
      2048434.43     13894487.80      2048878.87     13894323.59
      2049074.67     13893991.40
#Sta/Elev= 30
  4526.2 1291.82  4722.9 1290.01  4814.6 1290.54  4846.6 1292.26  4869.7 1292.00
  4894.8 1287.36  4910.6 1285.63  4919.9 1282.95  4925.2 1282.81  4942.6 1277.61
  4957.1 1271.72  4974.6 1267.18  4980.7 1262.34  4986.0 1260.80  4993.3 1252.87
  4993.5 1252.37  4997.3 1252.87  5000.0 1252.87  5003.2 1255.84  5010.0 1259.48
  5024.7 1269.57  5040.3 1274.57  5046.1 1279.40  5056.0 1281.26  5061.8 1283.44
  5120.3 1285.72  5197.9 1285.21  5216.0 1286.27  5334.2 1285.89  5385.6 1286.85
#Mann=6,-1,0
  4526.2   0.035       0  4957.1    0.12       0  4993.3    0.05       0
  4997.3    0.12       0  5197.9    0.07       0  5334.2   0.035       0
Bank Sta=4993.3,4997.3
Exp/Cntr=0.3,0.1

Chan Stop Cuts=-1