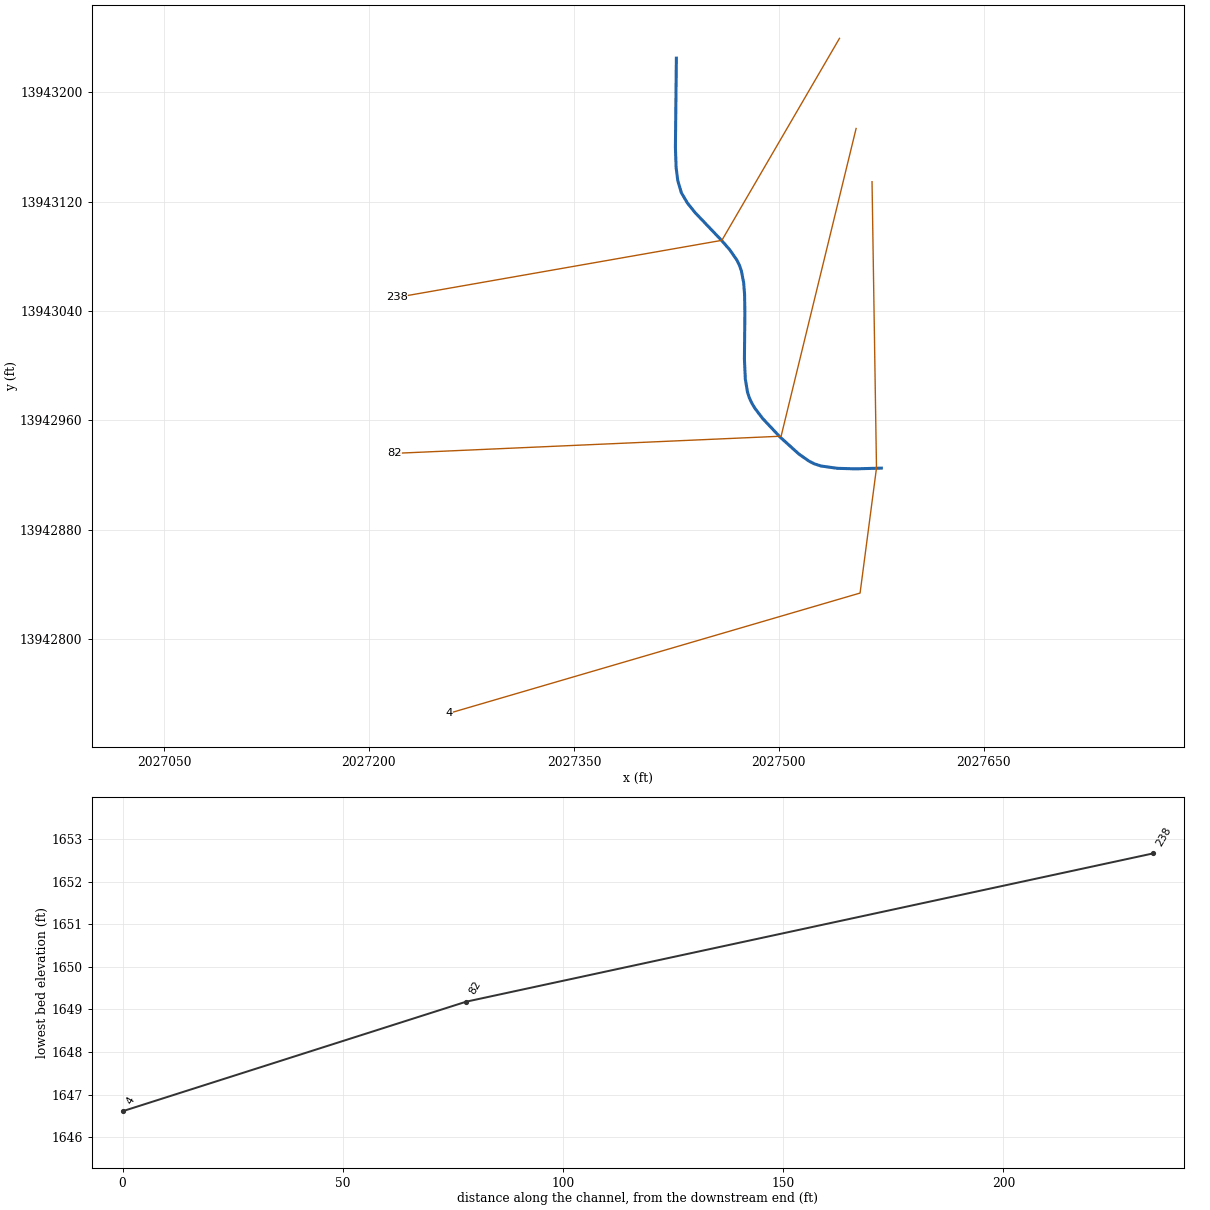
--- Stream0094_DS.prj (project) ---

Proj Title=Stream0094_DS Base Level Engineering
Current Plan=p01
Default Exp/Contr=0.3,0.1
English Units
Geom File=g01
Flow File=f01
Plan File=p01
BEGIN DESCRIPTION:
Stream0094_DS
END DESCRIPTION:

--- Stream0094_DS.p01 (plan) ---

Plan Title=Multiple Run
Short Identifier=Multiple
Geom File=g01
Flow File=f01
Subcritical Flow
K Sum by GR= 0
Std Step Tol= 0.01
Critical Tol= 0.01
Num of Std Step Trials= 20
Max Error Tol= 0.3
Flow Tol Ratio= 0.001
Split Flow NTrial= 30
Split Flow Tol= 0.02
Split Flow Ratio= 0.02
Log Output Level= 0
Friction Slope Method= 1
Unsteady Friction Slope Method= 2
Unsteady Bridges Friction Slope Method= 1
Parabolic Critical Depth
Global Vel Dist=  1 , 1 , 1
Global Log Level= 0
CheckData=True
Encroach Param= -1, 0, 0, 0
BEGIN DESCRIPTION:
Multiple Run
END DESCRIPTION:

--- Stream0094_DS.f01 (steady flow) ---

Flow Title=Multiple
Number of Profiles=7
Profile Names=10-year,25-year,50-year,1pct_min,100-year,1pct_plu,500-year
River Rch & RM= Stream0094_DS,Reach-1,238
     328     526     706     462     922    1840    1555
River Rch & RM= Stream0094_DS,Reach-1,82
    1583    2783    3963    2735    5456   10887   10265
Boundary for River Rch & Prof#=Stream0094_DS,Reach-1,1
Up Type=0
Dn Type=3
Dn Slope=0.005
Boundary for River Rch & Prof#=Stream0094_DS,Reach-1,2
Up Type=0
Dn Type=3
Dn Slope=0.005
Boundary for River Rch & Prof#=Stream0094_DS,Reach-1,3
Up Type=0
Dn Type=3
Dn Slope=0.005
Boundary for River Rch & Prof#=Stream0094_DS,Reach-1,4
Up Type=0
Dn Type=3
Dn Slope=0.005
Boundary for River Rch & Prof#=Stream0094_DS,Reach-1,5
Up Type=0
Dn Type=3
Dn Slope=0.005
Boundary for River Rch & Prof#=Stream0094_DS,Reach-1,6
Up Type=0
Dn Type=3
Dn Slope=0.005
Boundary for River Rch & Prof#=Stream0094_DS,Reach-1,7
Up Type=0
Dn Type=3
Dn Slope=0.005

--- Stream0094_DS.g01 (geometry) ---

Geom Title=Existing Conditions

River Reach=Stream0094_DS,Reach-1
Reach XY= 30
      2027425.00     13943225.00      2027424.29     13943159.71
      2027424.82     13943144.92      2027426.02     13943135.42
      2027428.66     13943126.52      2027433.11     13943118.93
      2027438.81     13943111.87      2027458.14     13943091.59
      2027464.16     13943084.65      2027469.23     13943077.32
      2027471.17     13943073.41      2027472.55     13943069.44
      2027474.20     13943061.03      2027474.91     13943052.23
      2027475.14     13943038.68      2027474.80     13943004.87
      2027475.46     13942990.11      2027477.03     13942980.73
      2027478.46     13942976.30      2027480.33     13942972.34
      2027482.64     13942968.55      2027488.12     13942961.35
      2027500.87     13942947.76      2027514.68     13942935.29
      2027522.06     13942930.13      2027525.99     13942928.12
      2027530.83     13942926.55      2027542.93     13942924.85
      2027555.95     13942924.46      2027575.00     13942925.00

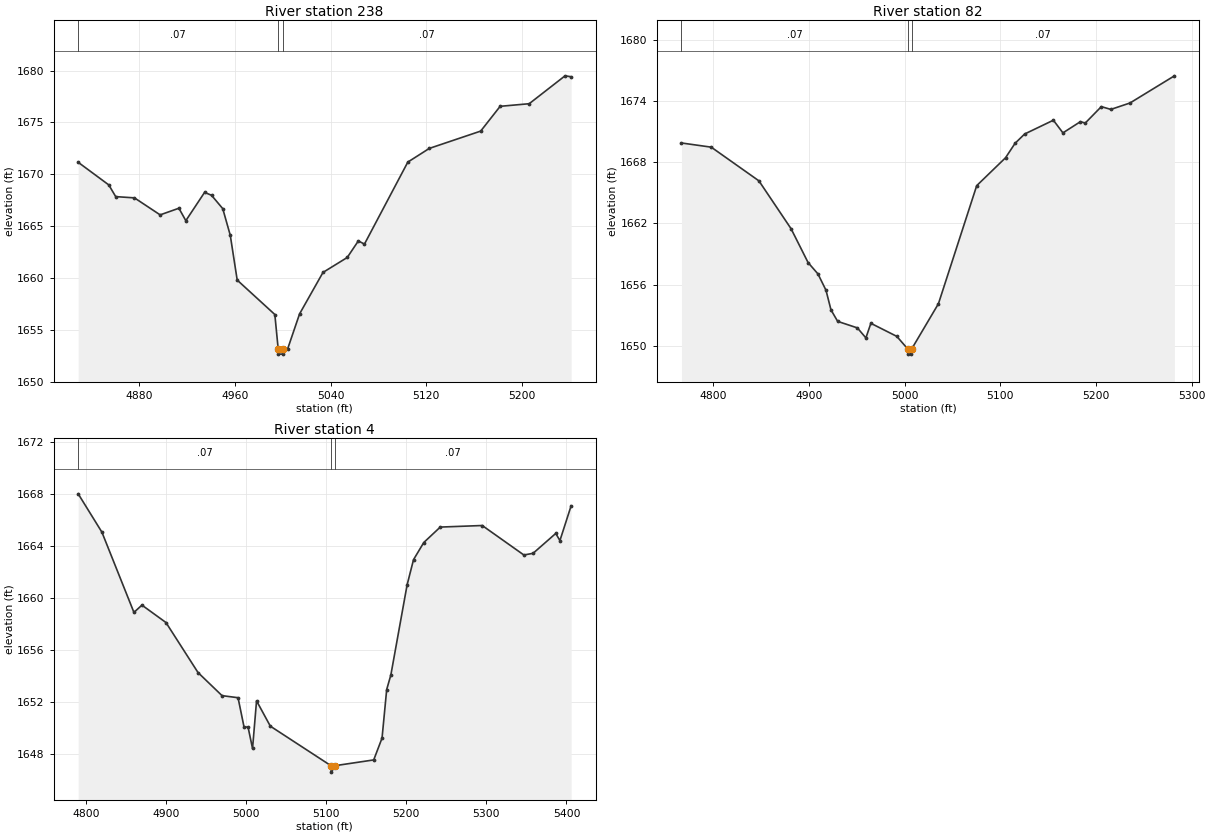
Type RM Length L Ch R = 1,238,156,156,156
BEGIN DESCRIPTION:
Stream0094_DS 1.0
END DESCRIPTION:
XS GIS Cut Line= 3
      2027544.38     13943239.53      2027458.30     13943091.70
      2027220.40     13943049.93
#Sta/Elev= 30
  4828.7 1671.16  4854.3 1668.98  4860.1 1667.85  4875.8 1667.73  4897.3 1666.09
  4913.0 1666.73  4918.8 1665.53  4934.5 1668.26  4940.3 1667.98  4949.7 1666.69
  4956.0 1664.12  4961.8 1659.80  4993.3 1656.48  4996.1 1653.16  4996.3 1652.66
  4999.8 1652.66  5000.1 1653.16  5004.0 1653.16  5014.0 1656.54  5033.6 1660.54
  5053.9 1661.98  5063.2 1663.58  5068.3 1663.27  5104.6 1671.18  5122.6 1672.50
  5165.6 1674.17  5181.9 1676.56  5206.2 1676.81  5236.2 1679.50  5241.3 1679.41
#Mann=3,-1,0
  4828.7    0.07       0  4996.1    0.05       0  5000.1    0.07       0
Bank Sta=4996.1,5000.1
Exp/Cntr=0.3,0.1

Type RM Length L Ch R = 1,82,78,78,78
BEGIN DESCRIPTION:
Stream0094_DS 0.1
END DESCRIPTION:
XS GIS Cut Line= 3
      2027556.54     13943173.56      2027501.65     13942948.35
      2027218.63     13942935.79
#Sta/Elev= 30
  4766.9 1669.87  4798.0 1669.46  4847.8 1666.16  4881.4 1661.47  4899.2 1658.15
  4909.5 1657.04  4917.9 1655.44  4923.1 1653.52  4930.1 1652.39  4950.7 1651.75
  4959.6 1650.77  4964.8 1652.20  4991.9 1650.92  5003.4 1649.68  5003.6 1649.18
  5007.1 1649.18  5007.4 1649.68  5035.4 1654.12  5075.4 1665.69  5105.5 1668.42
  5115.5 1669.84  5125.5 1670.75  5155.5 1672.10  5165.5 1670.86  5183.8 1671.96
  5188.8 1671.82  5205.6 1673.43  5215.6 1673.16  5235.6 1673.79  5282.0 1676.45
#Mann=3,-1,0
  4766.9    0.07       0  5003.4    0.05       0  5007.4    0.07       0
Bank Sta=5003.4,5007.4
Exp/Cntr=0.3,0.1

Type RM Length L Ch R = 1,4,0,0,0
BEGIN DESCRIPTION:
Stream0094_DS 0.0
END DESCRIPTION:
XS GIS Cut Line= 4
      2027568.19     13943134.61      2027571.45     13942925.04
      2027559.44     13942833.57      2027258.42     13942745.51
#Sta/Elev= 30
  4790.3 1668.04  4819.9 1665.09  4859.9 1658.91  4869.9 1659.47  4899.9 1658.13
  4939.9 1654.28  4969.9 1652.50  4989.9 1652.34  4997.4 1650.08  5002.4 1650.08
  5008.0 1648.43  5013.0 1652.10  5030.2 1650.15  5105.8 1647.11  5106.3 1646.61
  5111.4 1647.11  5159.3 1647.55  5169.7 1649.23  5175.5 1652.97  5180.7 1654.09
  5201.0 1661.03  5209.0 1662.97  5221.8 1664.29  5242.4 1665.48  5294.8 1665.60
  5346.8 1663.33  5358.3 1663.46  5386.6 1664.99  5391.8 1664.44  5405.8 1667.12
#Mann=3,-1,0
  4790.3    0.07       0  5105.8    0.05       0  5111.4    0.07       0
Bank Sta=5105.8,5111.4
Exp/Cntr=0.3,0.1

Chan Stop Cuts=-1