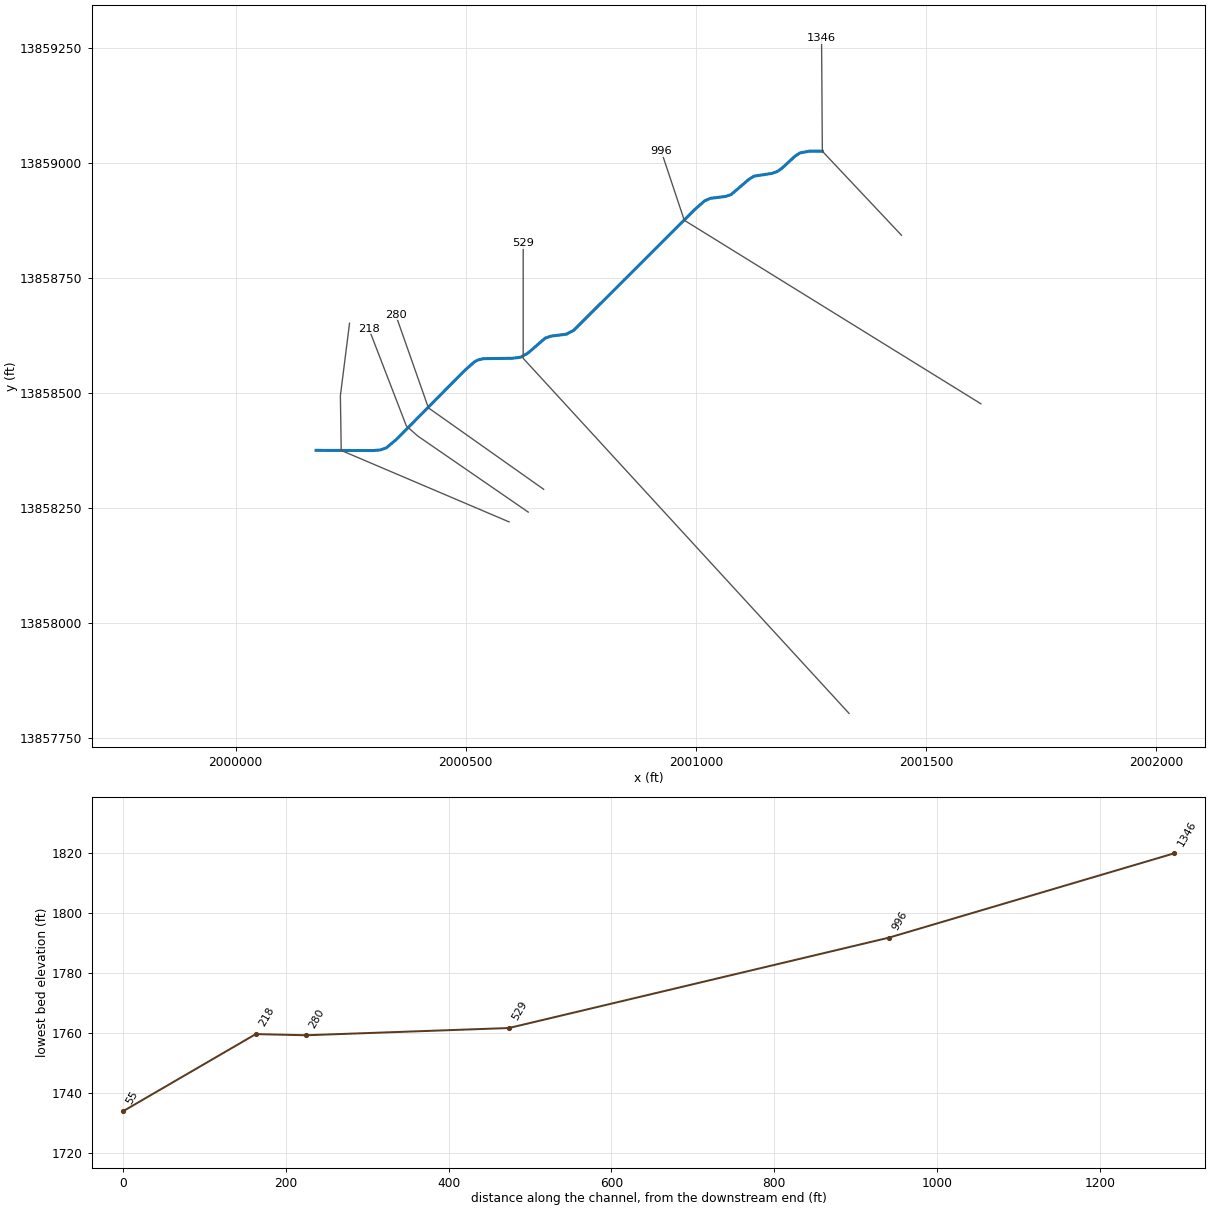
--- Stream0095_DS.prj (project) ---

Proj Title=Stream0095_DS Base Level Engineering
Current Plan=p01
Default Exp/Contr=0.3,0.1
English Units
Geom File=g01
Flow File=f01
Plan File=p01
BEGIN DESCRIPTION:
Stream0095_DS
END DESCRIPTION:

--- Stream0095_DS.p01 (plan) ---

Plan Title=Multiple Run
Short Identifier=Multiple
Geom File=g01
Flow File=f01
Subcritical Flow
K Sum by GR= 0
Std Step Tol= 0.01
Critical Tol= 0.01
Num of Std Step Trials= 20
Max Error Tol= 0.3
Flow Tol Ratio= 0.001
Split Flow NTrial= 30
Split Flow Tol= 0.02
Split Flow Ratio= 0.02
Log Output Level= 0
Friction Slope Method= 1
Unsteady Friction Slope Method= 2
Unsteady Bridges Friction Slope Method= 1
Parabolic Critical Depth
Global Vel Dist=  1 , 1 , 1
Global Log Level= 0
CheckData=True
Encroach Param= -1, 0, 0, 0
BEGIN DESCRIPTION:
Multiple Run
END DESCRIPTION:

--- Stream0095_DS.f01 (steady flow) ---

Flow Title=Multiple
Number of Profiles=7
Profile Names=10-year,25-year,50-year,1pct_min,100-year,1pct_plu,500-year
River Rch & RM= Stream0095_DS,Reach-1,1346
     357     568     758     494     985    1966    1638
Boundary for River Rch & Prof#=Stream0095_DS,Reach-1,1
Up Type=0
Dn Type=3
Dn Slope=0.005
Boundary for River Rch & Prof#=Stream0095_DS,Reach-1,2
Up Type=0
Dn Type=3
Dn Slope=0.005
Boundary for River Rch & Prof#=Stream0095_DS,Reach-1,3
Up Type=0
Dn Type=3
Dn Slope=0.005
Boundary for River Rch & Prof#=Stream0095_DS,Reach-1,4
Up Type=0
Dn Type=3
Dn Slope=0.005
Boundary for River Rch & Prof#=Stream0095_DS,Reach-1,5
Up Type=0
Dn Type=3
Dn Slope=0.005
Boundary for River Rch & Prof#=Stream0095_DS,Reach-1,6
Up Type=0
Dn Type=3
Dn Slope=0.005
Boundary for River Rch & Prof#=Stream0095_DS,Reach-1,7
Up Type=0
Dn Type=3
Dn Slope=0.005

--- Stream0095_DS.g01 (geometry) ---

Geom Title=Existing Conditions

River Reach=Stream0095_DS,Reach-1
Reach XY= 30
      2001275.00     13859025.00      2001247.32     13859025.18
      2001226.49     13859021.40      2001215.41     13859014.02
      2001188.15     13858988.77      2001177.25     13858980.95
      2001165.18     13858976.77      2001126.72     13858970.86
      2001115.45     13858963.92      2001077.19     13858931.10
      2001064.30     13858926.70      2001031.03     13858922.50
      2001018.94     13858916.86      2000998.18     13858898.71
      2000734.68     13858635.76      2000718.97     13858627.50
      2000685.71     13858623.28      2000672.83     13858618.86
      2000634.65     13858585.84      2000619.03     13858577.33
      2000600.00     13858575.00      2000538.91     13858574.33
      2000526.50     13858571.39      2000518.83     13858567.14
      2000498.13     13858548.82      2000348.53     13858397.86
      2000327.46     13858380.43      2000314.59     13858375.99
      2000300.16     13858374.62      2000175.00     13858375.00

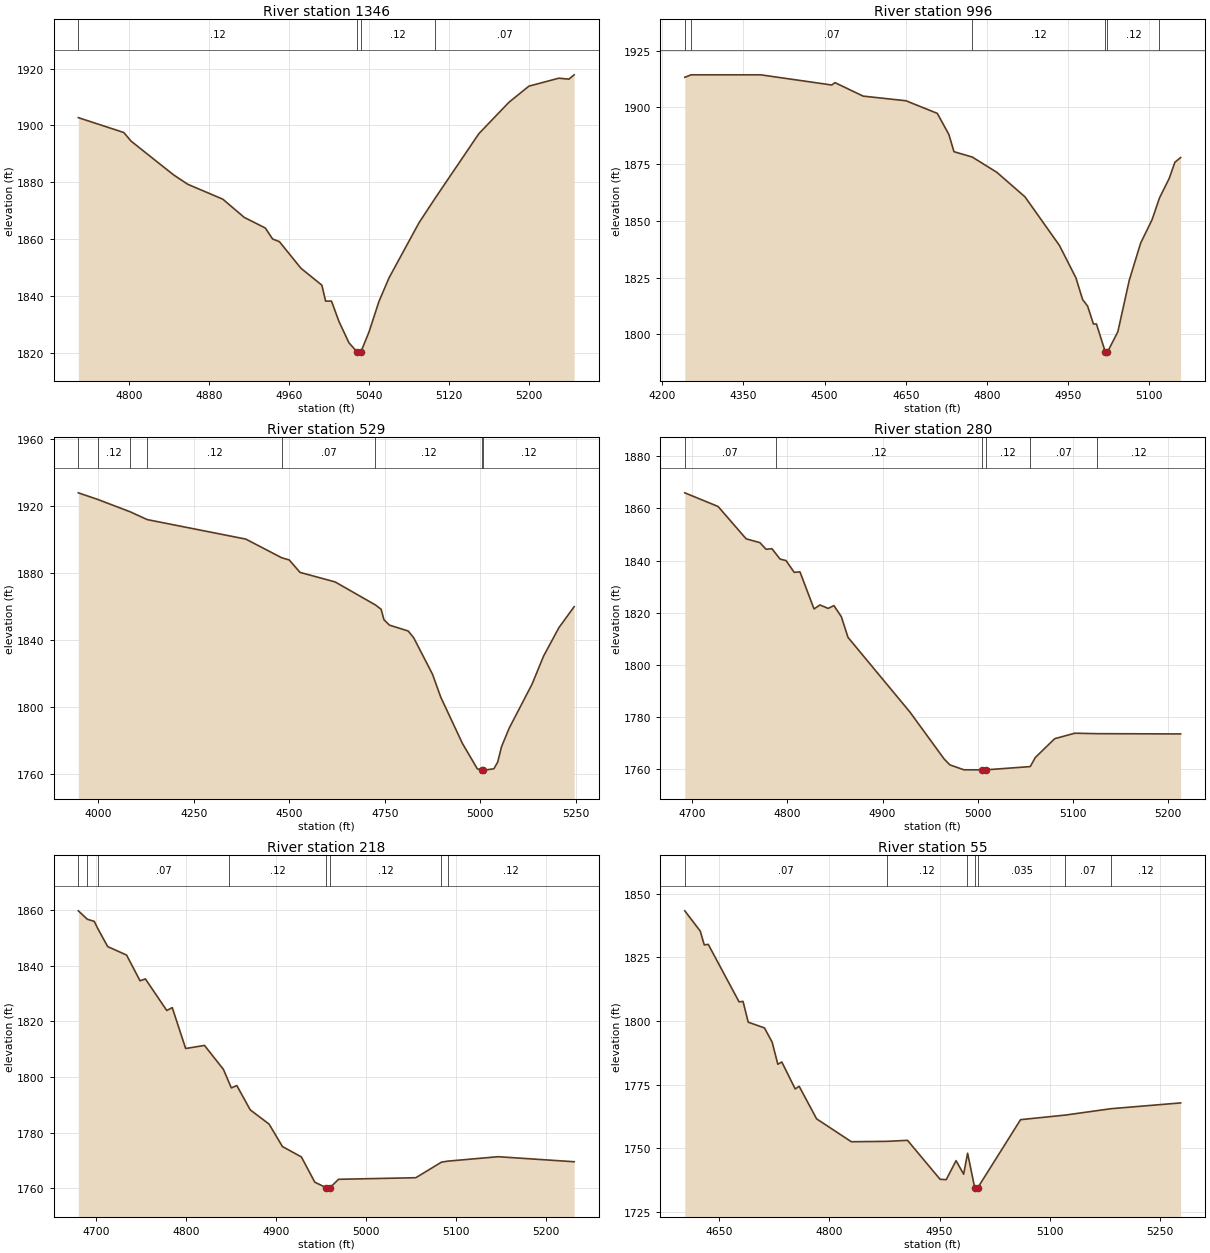
Type RM Length L Ch R = 1,1346,350,350,350
BEGIN DESCRIPTION:
Stream0095_DS 3.0
END DESCRIPTION:
XS GIS Cut Line= 3
      2001446.93     13858842.41      2001275.00     13859025.00
      2001273.30     13859270.29
#Sta/Elev= 30
  4749.2 1902.73  4794.7 1897.50  4802.0 1894.46  4844.4 1882.62  4858.6 1879.30
  4893.8 1874.03  4915.2 1867.63  4936.3 1863.89  4943.6 1860.02  4950.4 1859.09
  4971.9 1849.74  4992.9 1843.77  4996.6 1838.17  5002.5 1838.17  5010.0 1830.99
  5020.0 1823.48  5028.0 1820.36  5028.3 1819.86  5032.0 1820.36  5040.0 1827.27
  5050.0 1838.06  5060.0 1846.30  5090.0 1865.70  5106.1 1874.32  5150.0 1897.11
  5180.0 1908.12  5200.0 1913.81  5230.0 1916.62  5240.0 1916.27  5245.3 1917.80
#Mann=4,-1,0
  4749.2    0.12       0  5028.0    0.05       0  5032.0    0.12       0
  5106.1    0.07       0
Bank Sta=5028,5032
Exp/Cntr=0.3,0.1

Type RM Length L Ch R = 1,996,467,467,467
BEGIN DESCRIPTION:
Stream0095_DS 2.0
END DESCRIPTION:
XS GIS Cut Line= 3
      2001619.45     13858476.26      2000975.00     13858875.00
      2000924.98     13859025.05
#Sta/Elev= 30
  4241.9 1913.26  4253.4 1914.35  4382.2 1914.35  4513.4 1909.87  4519.3 1910.92
  4571.3 1904.98  4650.5 1902.93  4708.4 1897.37  4729.7 1888.12  4739.2 1880.50
  4773.0 1878.14  4818.3 1871.43  4870.4 1860.61  4934.1 1839.18  4964.5 1824.93
  4976.7 1815.46  4986.2 1812.43  4996.8 1804.61  5002.4 1804.61  5018.8 1792.28
  5019.1 1791.78  5022.8 1792.28  5041.9 1801.19  5063.0 1823.85  5084.1 1840.28
  5105.1 1850.51  5118.8 1860.10  5136.8 1868.73  5147.3 1875.85  5157.9 1877.92
#Mann=6,-1,0
  4241.9    0.12       0  4253.4    0.07       0  4773.0    0.12       0
  5018.8    0.05       0  5022.8    0.12       0  5118.8    0.07       0
Bank Sta=5018.8,5022.8
Exp/Cntr=0.3,0.1

Type RM Length L Ch R = 1,529,249,249,249
BEGIN DESCRIPTION:
Stream0095_DS 1.0
END DESCRIPTION:
XS GIS Cut Line= 3
      2001332.97     13857803.53      2000625.00     13858575.00
      2000625.00     13858825.02
#Sta/Elev= 30
  3948.3 1927.69  3998.7 1923.78  4083.2 1916.44  4128.5 1911.72  4386.5 1900.08
  4480.4 1888.94  4500.0 1887.65  4528.3 1880.22  4620.2 1874.52  4725.4 1860.81
  4740.4 1858.24  4747.8 1852.02  4762.0 1848.78  4811.3 1845.24  4825.5 1841.28
  4874.8 1819.48  4896.4 1805.80  4953.1 1778.19  4992.0 1763.06  5003.4 1762.15
  5003.6 1761.65  5007.4 1762.15  5035.4 1763.05  5045.4 1767.06  5055.4 1776.25
  5075.4 1787.26  5135.4 1813.61  5165.4 1830.28  5205.4 1847.21  5245.4 1859.76
#Mann=8,-1,0
  3948.3   0.035       0  3998.7    0.12       0  4083.2   0.035       0
  4128.5    0.12       0  4480.4    0.07       0  4725.4    0.12       0
  5003.4    0.05       0  5007.4    0.12       0
Bank Sta=5003.4,5007.4
Exp/Cntr=0.3,0.1

Type RM Length L Ch R = 1,280,62,62,62
BEGIN DESCRIPTION:
Stream0095_DS 0.2
END DESCRIPTION:
XS GIS Cut Line= 3
      2000669.46     13858290.46      2000419.03     13858467.39
      2000347.86     13858669.92
#Sta/Elev= 30
  4692.1 1866.01  4727.1 1860.77  4756.6 1848.36  4771.0 1846.91  4777.6 1844.35
  4783.7 1844.58  4787.7 1842.72  4792.3 1840.58  4798.5 1840.03  4807.1 1835.51
  4813.2 1835.67  4828.0 1821.46  4834.2 1822.99  4842.8 1821.67  4848.9 1822.74
  4856.7 1818.49  4863.7 1810.55  4929.0 1781.82  4964.7 1763.93  4970.8 1761.64
  4985.6 1759.75  5004.8 1759.74  5005.0 1759.24  5008.8 1759.74  5055.3 1760.98
  5060.6 1764.46  5081.0 1771.69  5102.2 1773.79  5125.9 1773.61  5213.4 1773.51
#Mann=6,-1,0
  4692.1    0.07       0  4787.7    0.12       0  5004.8    0.05       0
  5008.8    0.12       0  5055.3    0.07       0  5125.9    0.12       0
Bank Sta=5004.8,5008.8
Exp/Cntr=0.3,0.1

Type RM Length L Ch R = 1,218,163,163,163
BEGIN DESCRIPTION:
Stream0095_DS 0.1
END DESCRIPTION:
XS GIS Cut Line= 4
      2000635.93     13858240.86      2000395.91     13858406.18
      2000371.11     13858428.16      2000289.77     13858639.03
#Sta/Elev= 30
  4680.7 1859.86  4690.7 1856.83  4698.4 1856.06  4702.5 1853.36  4713.3 1846.98
  4734.3 1843.93  4749.2 1834.67  4755.2 1835.33  4778.9 1823.96  4785.0 1825.00
  4799.9 1810.27  4820.8 1811.38  4841.8 1802.77  4848.0 1798.06  4850.6 1796.08
  4856.7 1796.93  4871.6 1788.17  4892.5 1783.05  4907.4 1774.95  4928.4 1771.22
  4943.3 1762.12  4956.1 1760.12  4956.4 1759.62  4960.1 1760.12  4969.7 1763.16
  5055.5 1763.73  5083.9 1769.33  5091.0 1769.70  5146.9 1771.30  5231.3 1769.48
#Mann=8,-1,0
  4680.7    0.07       0  4690.7    0.12       0  4702.5    0.07       0
  4848.0    0.12       0  4956.1    0.05       0  4960.1    0.12       0
  5083.9    0.07       0  5091.0    0.12       0
Bank Sta=4956.1,4960.1
Exp/Cntr=0.3,0.1

Type RM Length L Ch R = 1,55,0,0,0
BEGIN DESCRIPTION:
Stream0095_DS 0.0
END DESCRIPTION:
XS GIS Cut Line= 4
      2000594.33     13858219.59      2000229.60     13858374.86
      2000227.78     13858493.80      2000247.69     13858651.29
#Sta/Elev= 30
  4603.6 1843.31  4624.6 1835.35  4630.1 1829.91  4635.5 1830.13  4677.4 1807.52
  4682.8 1807.71  4689.8 1799.54  4711.9 1797.29  4722.4 1791.66  4730.1 1782.99
  4735.5 1783.89  4753.7 1773.30  4759.1 1774.33  4782.8 1761.54  4830.0 1752.54
  4878.3 1752.69  4906.4 1753.09  4950.7 1737.76  4959.1 1737.66  4972.4 1745.11
  4982.7 1739.78  4986.9 1746.20  4988.1 1748.03  4997.8 1734.41  4998.0 1733.91
  5001.8 1734.41  5060.1 1761.22  5121.0 1763.02  5182.9 1765.52  5277.7 1767.80
#Mann=7,-1,0
  4603.6    0.07       0  4878.3    0.12       0  4986.9   0.035       0
  4997.8   0.035       0  5001.8   0.035       0  5121.0    0.07       0
  5182.9    0.12       0
Bank Sta=4997.8,5001.8
Exp/Cntr=0.3,0.1

Chan Stop Cuts=-1