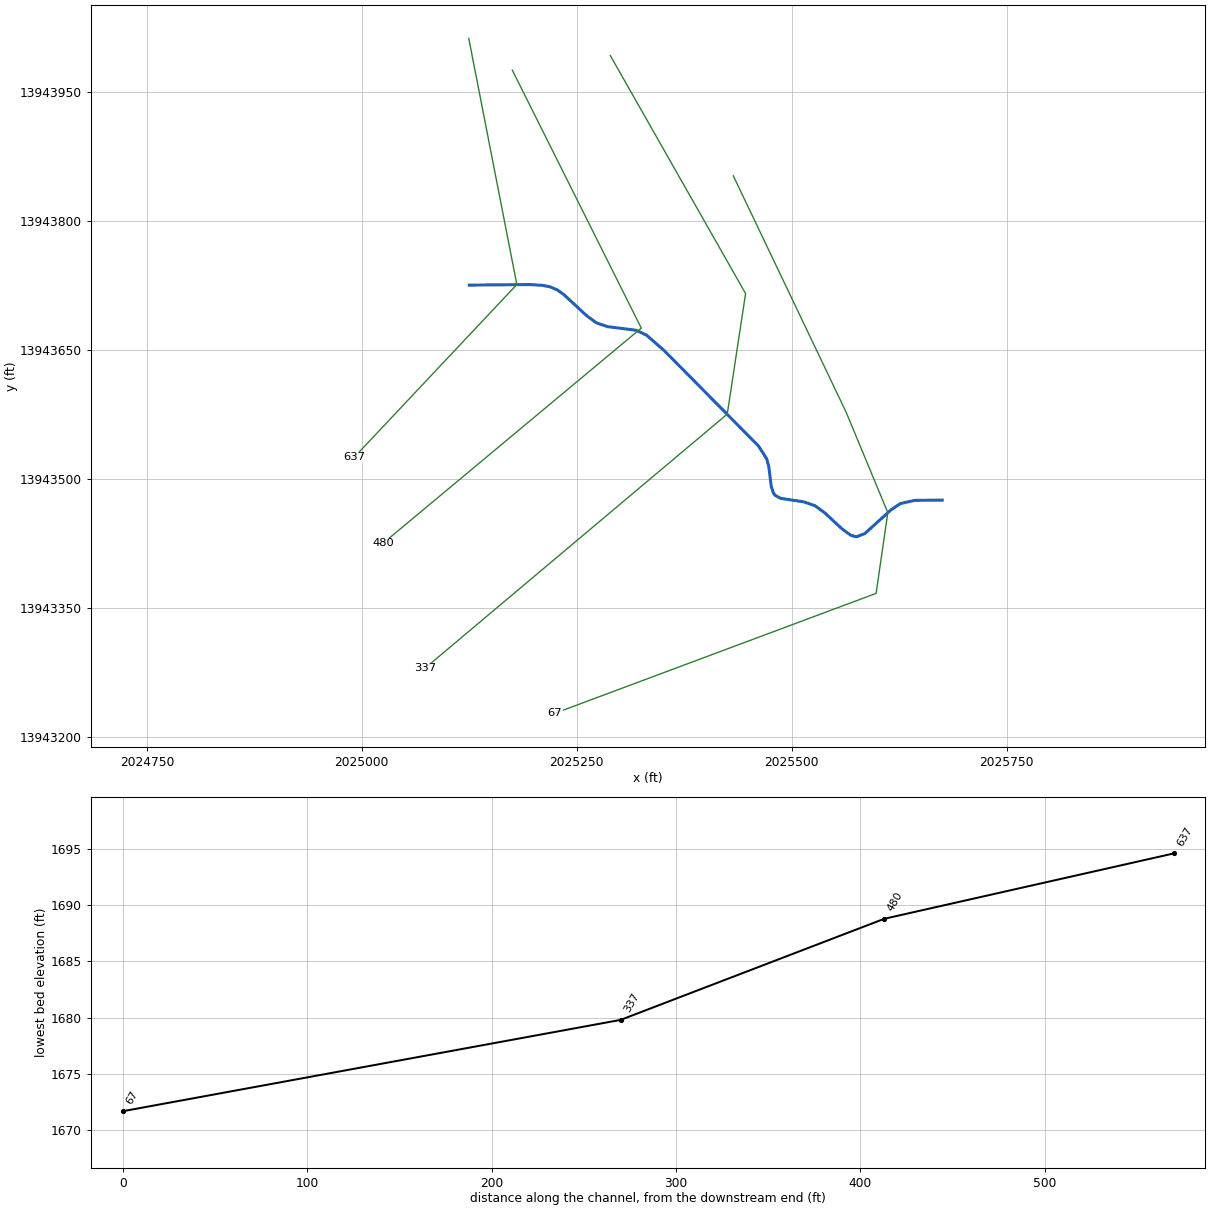
--- Stream0096_DS.prj (project) ---

Proj Title=Stream0096_DS Base Level Engineering
Current Plan=p01
Default Exp/Contr=0.3,0.1
English Units
Geom File=g01
Flow File=f01
Plan File=p01
BEGIN DESCRIPTION:
Stream0096_DS
END DESCRIPTION:

--- Stream0096_DS.p01 (plan) ---

Plan Title=Multiple Run
Short Identifier=Multiple
Geom File=g01
Flow File=f01
Subcritical Flow
K Sum by GR= 0
Std Step Tol= 0.01
Critical Tol= 0.01
Num of Std Step Trials= 20
Max Error Tol= 0.3
Flow Tol Ratio= 0.001
Split Flow NTrial= 30
Split Flow Tol= 0.02
Split Flow Ratio= 0.02
Log Output Level= 0
Friction Slope Method= 1
Unsteady Friction Slope Method= 2
Unsteady Bridges Friction Slope Method= 1
Parabolic Critical Depth
Global Vel Dist=  1 , 1 , 1
Global Log Level= 0
CheckData=True
Encroach Param= -1, 0, 0, 0
BEGIN DESCRIPTION:
Multiple Run
END DESCRIPTION:

--- Stream0096_DS.f01 (steady flow) ---

Flow Title=Multiple
Number of Profiles=7
Profile Names=10-year,25-year,50-year,1pct_min,100-year,1pct_plu,500-year
River Rch & RM= Stream0096_DS,Reach-1,637
     247     387     513     332     662    1320    1087
Boundary for River Rch & Prof#=Stream0096_DS,Reach-1,1
Up Type=0
Dn Type=3
Dn Slope=0.005
Boundary for River Rch & Prof#=Stream0096_DS,Reach-1,2
Up Type=0
Dn Type=3
Dn Slope=0.005
Boundary for River Rch & Prof#=Stream0096_DS,Reach-1,3
Up Type=0
Dn Type=3
Dn Slope=0.005
Boundary for River Rch & Prof#=Stream0096_DS,Reach-1,4
Up Type=0
Dn Type=3
Dn Slope=0.005
Boundary for River Rch & Prof#=Stream0096_DS,Reach-1,5
Up Type=0
Dn Type=3
Dn Slope=0.005
Boundary for River Rch & Prof#=Stream0096_DS,Reach-1,6
Up Type=0
Dn Type=3
Dn Slope=0.005
Boundary for River Rch & Prof#=Stream0096_DS,Reach-1,7
Up Type=0
Dn Type=3
Dn Slope=0.005

--- Stream0096_DS.g01 (geometry) ---

Geom Title=Existing Conditions

River Reach=Stream0096_DS,Reach-1
Reach XY= 30
      2025125.00     13943725.00      2025195.27     13943725.64
      2025209.89     13943724.73      2025219.14     13943722.93
      2025227.38     13943719.37      2025234.67     13943714.21
      2025261.94     13943689.00      2025272.82     13943681.11
      2025285.71     13943676.71      2025318.97     13943672.51
      2025331.06     13943666.86      2025351.82     13943648.71
      2025461.28     13943537.98      2025470.88     13943522.99
      2025473.29     13943513.97      2025476.15     13943491.01
      2025478.55     13943483.45      2025480.62     13943480.56
      2025487.03     13943477.03      2025513.97     13943472.96
      2025526.95     13943468.46      2025537.98     13943460.48
      2025558.39     13943441.61      2025568.36     13943434.26
      2025575.00     13943432.27      2025584.94     13943436.03
      2025615.22     13943463.42      2025626.36     13943471.00
      2025643.12     13943474.69      2025675.00     13943475.00

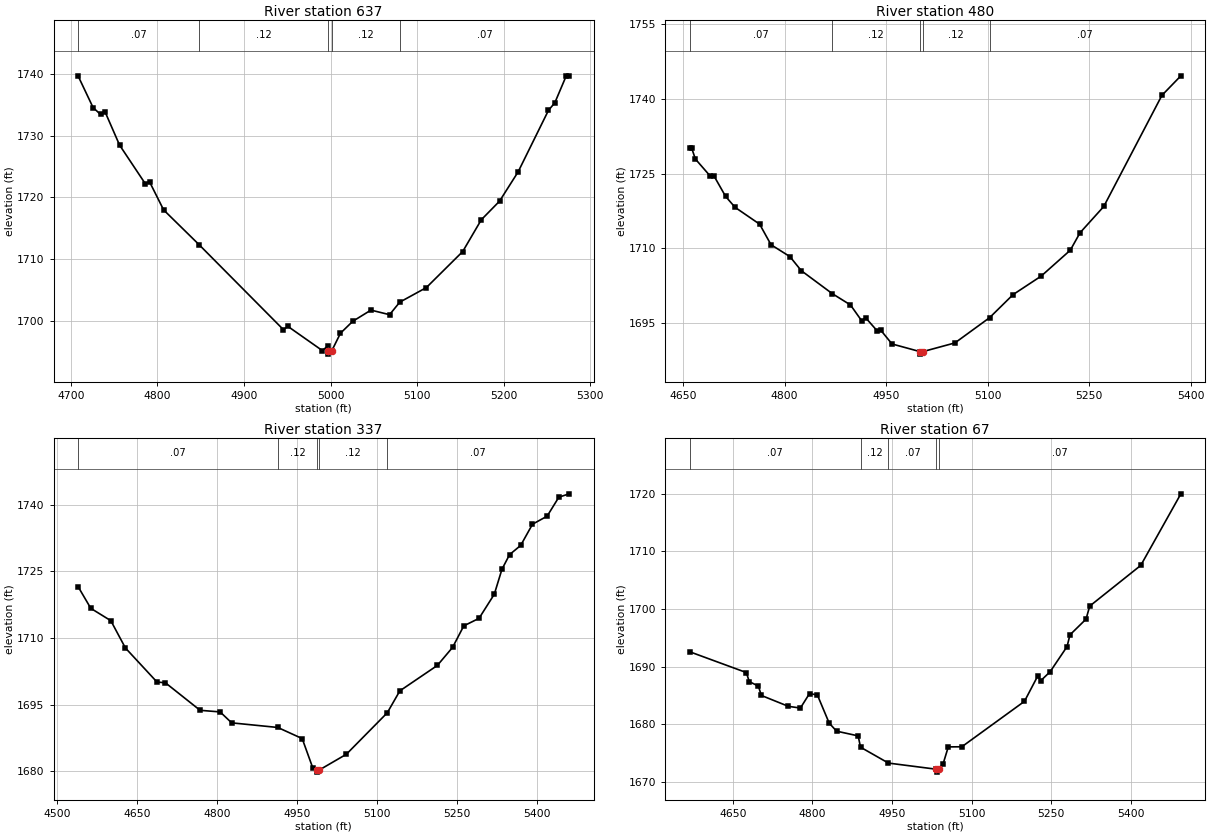
Type RM Length L Ch R = 1,637,157,157,157
BEGIN DESCRIPTION:
Stream0096_DS 3.0
END DESCRIPTION:
XS GIS Cut Line= 3
      2025124.36     13944011.99      2025180.29     13943725.70
      2024991.33     13943524.95
#Sta/Elev= 30
  4708.3 1739.65  4725.6 1734.53  4734.2 1733.42  4739.3 1733.88  4756.2 1728.45
  4785.8 1722.22  4790.8 1722.51  4807.1 1717.95  4847.9 1712.34  4945.5 1698.55
  4950.6 1699.09  4990.5 1695.16  4997.1 1695.97  4997.2 1695.09  4997.5 1694.59
  5001.2 1695.09  5011.4 1697.98  5025.6 1699.91  5046.6 1701.72  5068.1 1700.98
  5079.9 1703.01  5110.6 1705.37  5152.6 1711.21  5174.1 1716.36  5195.1 1719.36
  5216.6 1724.11  5251.7 1734.09  5259.0 1735.30  5272.2 1739.67  5275.7 1739.67
#Mann=5,-1,0
  4708.3    0.07       0  4847.9    0.12       0  4997.2    0.05       0
  5001.2    0.12       0  5079.9    0.07       0
Bank Sta=4997.2,5001.2
Exp/Cntr=0.3,0.1

Type RM Length L Ch R = 1,480,143,143,143
BEGIN DESCRIPTION:
Stream0096_DS 2.0
END DESCRIPTION:
XS GIS Cut Line= 3
      2025175.01     13943974.98      2025325.00     13943675.00
      2025025.00     13943425.00
#Sta/Elev= 30
  4659.6 1730.17  4662.4 1730.17  4668.0 1727.93  4690.3 1724.45  4695.9 1724.44
  4712.7 1720.42  4726.7 1718.23  4763.0 1714.85  4779.8 1710.73  4807.7 1708.35
  4824.5 1705.53  4870.3 1700.92  4897.2 1698.65  4913.9 1695.45  4919.5 1696.10
  4936.3 1693.51  4941.9 1693.60  4958.6 1690.82  5000.1 1689.28  5000.4 1688.78
  5004.1 1689.28  5051.6 1691.03  5102.8 1696.09  5137.5 1700.72  5179.2 1704.45
  5222.1 1709.63  5236.5 1713.13  5271.6 1718.41  5357.5 1740.70  5385.5 1744.62
#Mann=5,-1,0
  4659.6    0.07       0  4870.3    0.12       0  5000.1    0.05       0
  5004.1    0.12       0  5102.8    0.07       0
Bank Sta=5000.1,5004.1
Exp/Cntr=0.3,0.1

Type RM Length L Ch R = 1,337,270,270,270
BEGIN DESCRIPTION:
Stream0096_DS 1.0
END DESCRIPTION:
XS GIS Cut Line= 4
      2025288.98     13943991.95      2025446.32     13943715.20
      2025425.00     13943575.00      2025073.11     13943279.14
#Sta/Elev= 30
  4540.1 1721.53  4563.9 1716.65  4601.4 1713.87  4628.7 1707.73  4687.8 1700.07
  4703.7 1699.89  4768.6 1693.70  4806.1 1693.34  4827.7 1690.88  4914.1 1689.84
  4959.8 1687.34  4980.0 1680.61  4988.1 1680.29  4988.4 1679.79  4992.1 1680.29
  5042.5 1683.81  5119.1 1693.14  5142.7 1698.08  5212.9 1703.80  5241.5 1707.87
  5262.4 1712.70  5291.0 1714.40  5319.6 1719.83  5333.9 1725.44  5348.2 1728.74
  5369.0 1730.81  5391.1 1735.58  5418.5 1737.39  5440.5 1741.67  5460.0 1742.42
#Mann=5,-1,0
  4540.1    0.07       0  4914.1    0.12       0  4988.1    0.05       0
  4992.1    0.12       0  5119.1    0.07       0
Bank Sta=4988.1,4992.1
Exp/Cntr=0.3,0.1

Type RM Length L Ch R = 1,67,0,0,0
BEGIN DESCRIPTION:
Stream0096_DS 0.0
END DESCRIPTION:
XS GIS Cut Line= 5
      2025432.03     13943852.08      2025563.33     13943577.02
      2025611.74     13943460.36      2025598.10     13943366.50
      2025224.24     13943226.95
#Sta/Elev= 30
  4568.9 1692.56  4675.6 1688.95  4681.1 1687.38  4698.3 1686.60  4703.8 1684.98
  4754.7 1683.09  4777.4 1682.79  4794.6 1685.31  4809.4 1685.06  4831.6 1680.18
  4845.5 1678.78  4886.2 1677.96  4890.6 1676.00  4943.2 1673.24  5033.7 1672.17
  5034.0 1671.67  5037.7 1672.17  5045.8 1673.00  5055.9 1676.05  5081.4 1676.07
  5199.4 1683.96  5224.4 1688.36  5229.7 1687.51  5247.6 1689.08  5279.6 1693.46
  5285.0 1695.49  5315.3 1698.22  5322.3 1700.49  5418.4 1707.55  5493.9 1719.97
#Mann=5,-1,0
  4568.9    0.07       0  4890.6    0.12       0  4943.2    0.07       0
  5033.7    0.05       0  5037.7    0.07       0
Bank Sta=5033.7,5037.7
Exp/Cntr=0.3,0.1

Chan Stop Cuts=-1