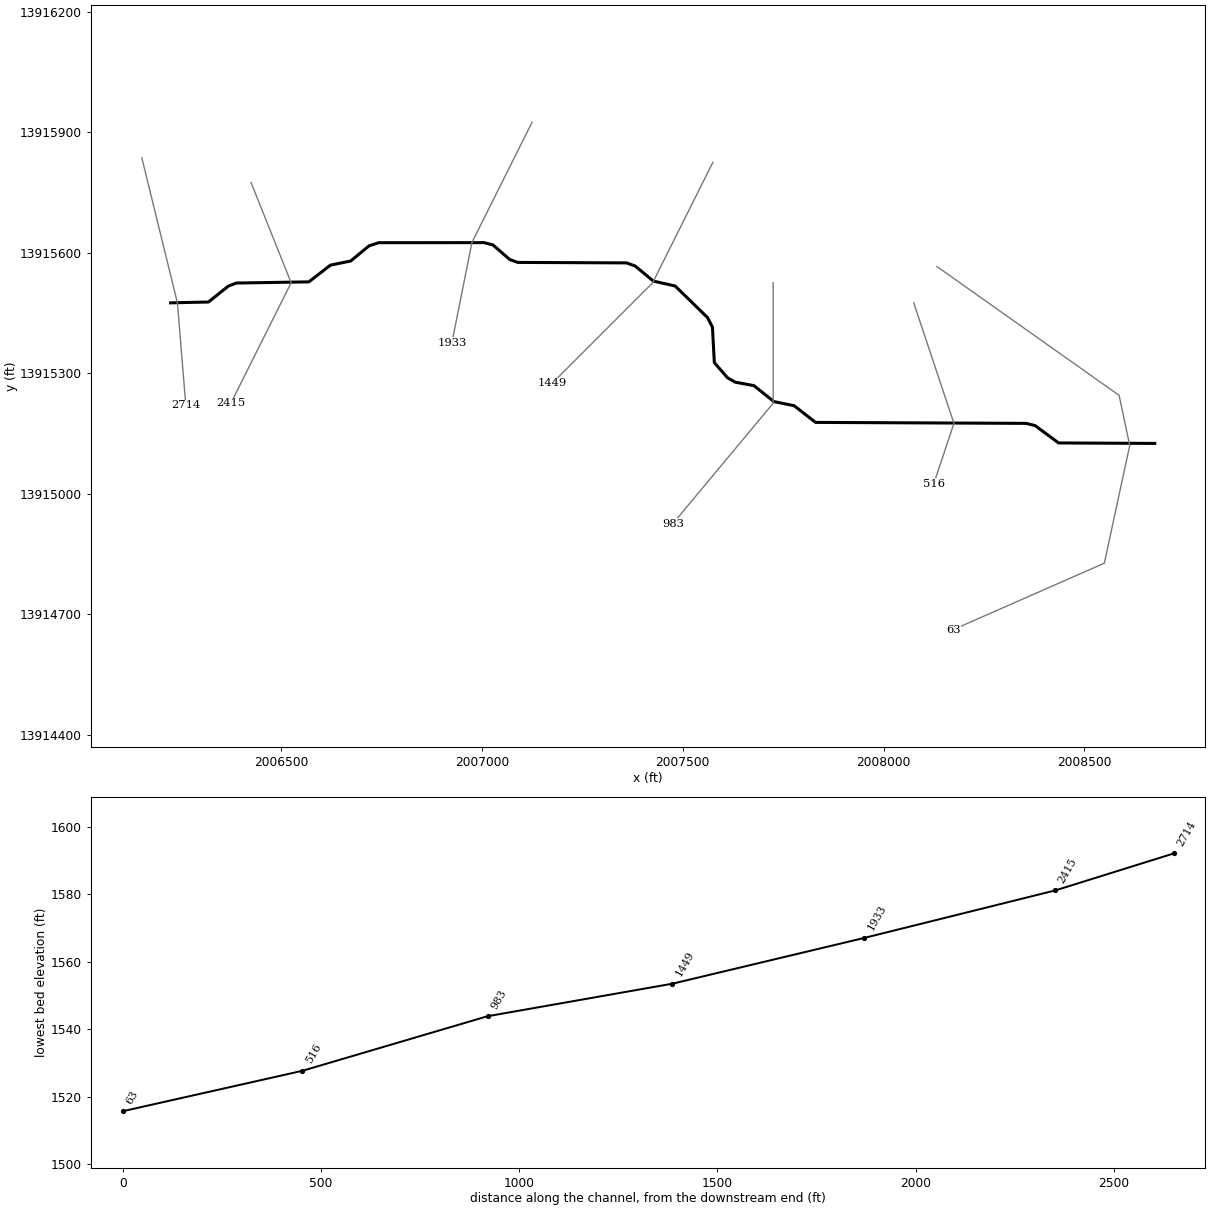
--- Stream0098_DS.prj (project) ---

Proj Title=Stream0098_DS Base Level Engineering
Current Plan=p01
Default Exp/Contr=0.3,0.1
English Units
Geom File=g01
Flow File=f01
Plan File=p01
Y Axis Title=Elevation
X Axis Title(PF)=Main Channel Distance
X Axis Title(XS)=Station
BEGIN DESCRIPTION:
Stream0098_DS
END DESCRIPTION:
DSS Export Rating Curves= 0
DSS Export Rating Curve Sorted= 0
DSS Export Volume Flow Curves= 0
DXF OffsetX= 0
DXF OffsetY= 0
DXF ScaleX= 1
DXF ScaleY= 10

--- Stream0098_DS.p01 (plan) ---

Plan Title=Multiple Run
Short Identifier=Multiple
Geom File=g01
Flow File=f01
Subcritical Flow
K Sum by GR= 0
Std Step Tol= 0.01
Critical Tol= 0.01
Num of Std Step Trials= 20
Max Error Tol= 0.3
Flow Tol Ratio= 0.001
Split Flow NTrial= 30
Split Flow Tol= 0.02
Split Flow Ratio= 0.02
Log Output Level= 0
Friction Slope Method= 1
Unsteady Friction Slope Method= 2
Unsteady Bridges Friction Slope Method= 1
Parabolic Critical Depth
Global Vel Dist=  1 , 1 , 1
Global Log Level= 0
CheckData=True
Encroach Param= -1, 0, 0, 0
BEGIN DESCRIPTION:
Multiple Run
END DESCRIPTION:

--- Stream0098_DS.f01 (steady flow) ---

Flow Title=Multiple
Number of Profiles=7
Profile Names=10-year,25-year,50-year,1pct_min,100-year,1pct_plu,500-year
River Rch & RM= Stream0098_DS,Reach-1,2714
     485     799    1090     725    1447    2887    2521
River Rch & RM= Stream0098_DS,Reach-1,2415
     620    1036    1428     958    1911    3814    3391
Boundary for River Rch & Prof#=Stream0098_DS,Reach-1,1
Up Type=0
Dn Type=3
Dn Slope=0.005
Boundary for River Rch & Prof#=Stream0098_DS,Reach-1,2
Up Type=0
Dn Type=3
Dn Slope=0.005
Boundary for River Rch & Prof#=Stream0098_DS,Reach-1,3
Up Type=0
Dn Type=3
Dn Slope=0.005
Boundary for River Rch & Prof#=Stream0098_DS,Reach-1,4
Up Type=0
Dn Type=3
Dn Slope=0.005
Boundary for River Rch & Prof#=Stream0098_DS,Reach-1,5
Up Type=0
Dn Type=3
Dn Slope=0.005
Boundary for River Rch & Prof#=Stream0098_DS,Reach-1,6
Up Type=0
Dn Type=3
Dn Slope=0.005
Boundary for River Rch & Prof#=Stream0098_DS,Reach-1,7
Up Type=0
Dn Type=3
Dn Slope=0.005

--- Stream0098_DS.g01 (geometry) ---

Geom Title=Existing Conditions
Program Version=4.10

River Reach=Stream0098_DS   ,Reach-1
Reach XY= 30
        2006225.       13915475.      2006319.13      13915477.1
      2006368.93      13915516.9      2006388.91     13915524.33
      2006569.07     13915527.24      2006622.82     13915568.88
      2006673.26     13915579.19      2006718.92     13915616.91
      2006743.26      13915624.8      2007004.97     13915624.93
      2007027.33     13915619.25      2007068.94     13915583.14
      2007088.92     13915575.68      2007359.79     13915574.49
      2007381.08     13915566.91      2007426.75     13915529.22
      2007481.08     13915516.87      2007561.61     13915438.33
      2007573.83     13915414.52      2007578.53     13915326.28
      2007611.37     13915288.45      2007630.42     13915277.52
      2007677.16     13915268.88      2007726.72     13915229.16
      2007777.18     13915218.88      2007830.52     13915177.35
      2008354.97     13915174.93      2008377.33     13915169.25
       2008435.5     13915126.22        2008675.       13915125.

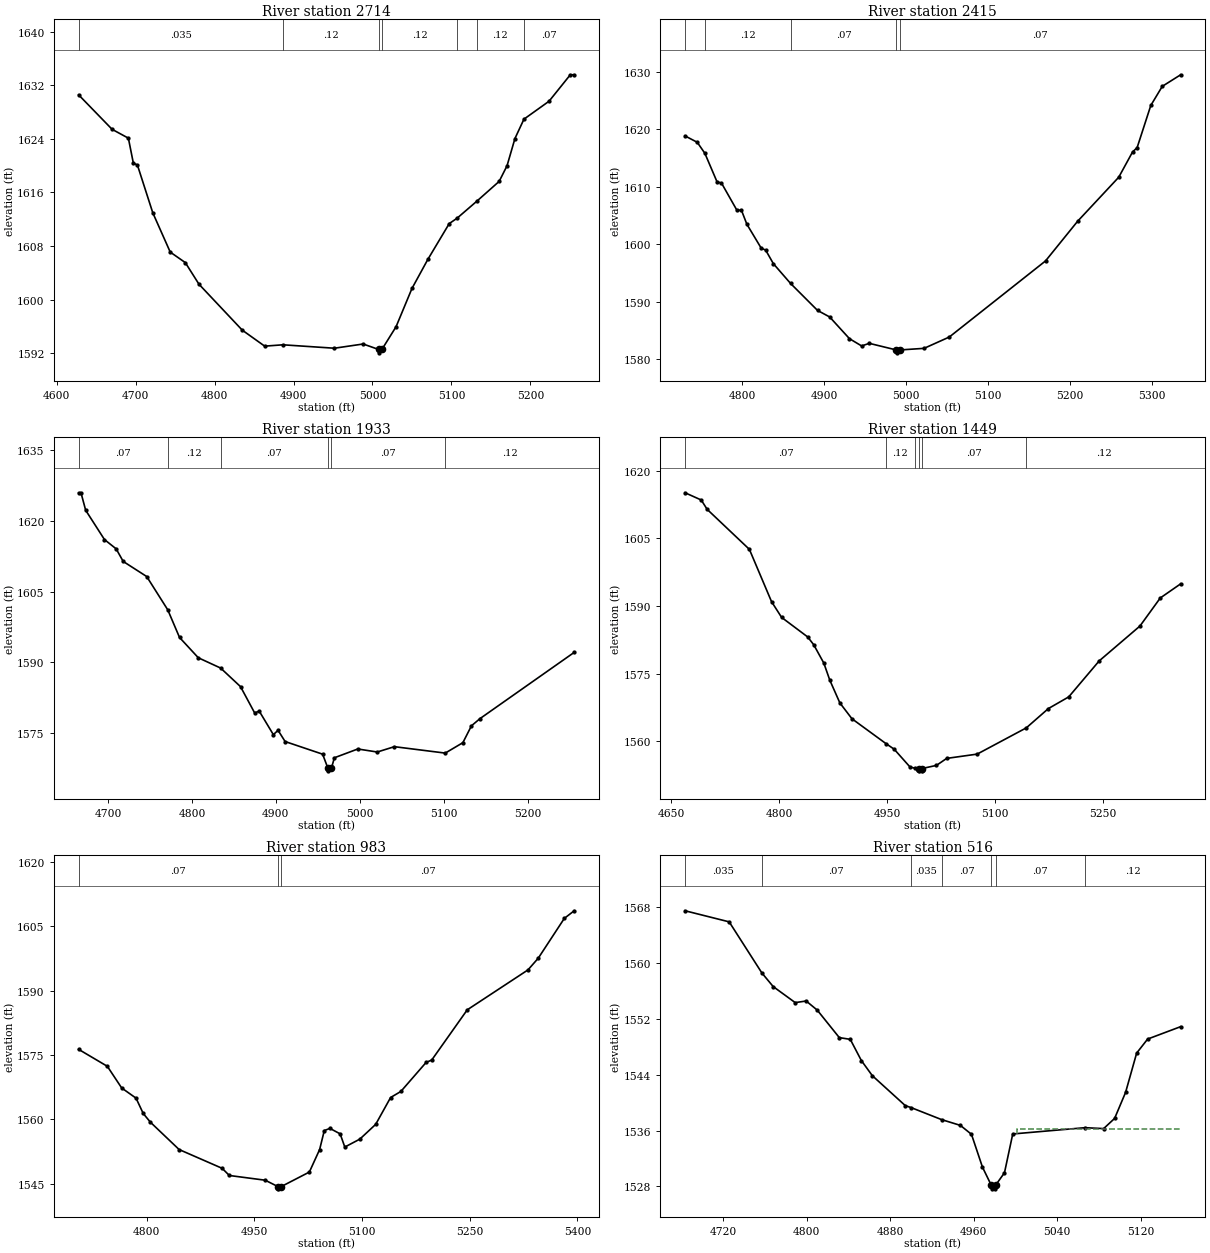
Type RM Length L Ch R = 1 ,2714    ,299,299,299
BEGIN DESCRIPTION:
Stream0098_DS 6.0
END DESCRIPTION:
XS GIS Cut Line= 3
      2006153.25     13915836.22      2006241.91     13915474.75
      2006262.75     13915220.29
#Sta/Elev= 30
  4627.9 1630.58  4670.3 1625.43  4690.9 1624.11  4697.2 1620.37  4702.3 1620.11
  4721.8 1612.96  4743.9 1607.09    4763 1605.52  4780.3 1602.29  4835.1 1595.43
  4863.5 1593.04  4886.6 1593.24  4951.8 1592.73  4988.2 1593.36  5007.9 1592.54
  5008.1 1592.04  5011.9 1592.54  5029.9 1595.95    5050 1601.66  5070.1    1606
  5097.2 1611.35  5107.1 1612.15  5131.9 1614.67  5160.4 1617.65  5170.4 1619.99
  5180.4 1624.06  5191.8 1626.95  5223.6 1629.63  5250.5 1633.58  5255.4 1633.58
#Mann= 7 ,-1 , 0
  4627.9    .035       0  4886.6     .12       0  5007.9     .05       0
  5011.9     .12       0  5107.1     .07       0  5131.9     .12       0
  5191.8     .07       0
Bank Sta=5007.9,5011.9
XS Rating Curve= 0 ,0
Exp/Cntr=0.3,0.1

Type RM Length L Ch R = 1 ,2415    ,482,482,482
BEGIN DESCRIPTION:
Stream0098_DS 5.0
END DESCRIPTION:
XS GIS Cut Line= 3
        2006425.       13915775.        2006525.       13915525.
      2006374.99     13915224.97
#Sta/Elev= 30
  4730.3  1618.8  4745.1  1617.7  4754.4 1615.79  4769.3 1610.81  4774.7 1610.61
  4793.6 1605.86    4799  1605.9  4805.7 1603.44  4823.2 1599.28  4828.6 1598.95
    4838 1596.59    4859 1593.15  4891.9 1588.46  4906.7 1587.32  4930.9 1583.54
  4945.7 1582.28  4955.1 1582.73  4988.1 1581.58  4988.4 1581.08  4992.1 1581.58
  5021.9 1581.86  5052.7 1583.83  5170.1 1597.06  5209.2 1603.95  5259.5 1611.63
  5276.3 1616.01  5281.9 1616.77  5298.6 1624.11  5312.6 1627.43    5335 1629.44
#Mann= 5 ,-1 , 0
  4730.3     .07       0  4754.4     .12       0    4859     .07       0
  4988.1     .05       0  4992.1     .07       0
Bank Sta=4988.1,4992.1
XS Rating Curve= 0 ,0
Exp/Cntr=0.3,0.1

Type RM Length L Ch R = 1 ,1933    ,484,484,484
BEGIN DESCRIPTION:
Stream0098_DS 4.0
END DESCRIPTION:
XS GIS Cut Line= 3
      2007125.01     13915925.02        2006975.       13915625.
        2006925.     13915374.98
#Sta/Elev= 30
    4665 1625.93  4667.8 1625.93  4673.4 1622.22  4695.8 1616.01  4709.7 1614.05
  4718.1 1611.38  4746.1 1608.18  4771.2 1601.12  4785.2 1595.27  4807.6 1590.96
  4834.2 1588.78  4857.9 1584.84  4874.7 1579.28  4880.2 1579.65    4897 1574.67
  4902.6 1575.59    4911 1573.21  4955.7 1570.53  4962.1  1567.5  4962.3    1567
  4966.1  1567.5  4969.7 1569.77  4997.6 1571.63  5020.8 1570.99  5041.2 1572.12
  5101.8 1570.76  5122.8 1572.97    5133 1576.54  5143.2 1578.07  5255.4  1592.1
#Mann= 6 ,-1 , 0
    4665     .07       0  4771.2     .12       0  4834.2     .07       0
  4962.1     .05       0  4966.1     .07       0  5101.8     .12       0
Bank Sta=4962.1,4966.1
XS Rating Curve= 0 ,0
Exp/Cntr=0.3,0.1

Type RM Length L Ch R = 1 ,1449    ,466,466,466
BEGIN DESCRIPTION:
Stream0098_DS 3.0
END DESCRIPTION:
XS GIS Cut Line= 3
        2007575.     13915824.99        2007425.       13915525.
      2007174.97     13915274.97
#Sta/Elev= 30
  4669.2 1615.11  4691.6 1613.51  4699.9 1611.43  4758.6 1602.56  4789.4 1590.96
  4803.4 1587.47  4839.7 1583.13  4848.1 1581.39  4862.1 1577.33  4870.4 1573.55
  4884.4  1568.5  4901.2 1564.99  4948.4 1559.49  4959.9 1558.24  4982.2 1554.24
  4988.4 1554.06  4994.2 1553.94  4994.5 1553.44    4998 1553.44  4998.2 1553.94
  5018.7 1554.65  5032.9  1556.2  5075.3 1557.15  5143.6 1562.97  5174.3 1567.25
  5202.6 1569.84    5245 1577.83  5301.6 1585.55  5329.9 1591.78  5358.2 1594.91
#Mann= 6 ,-1 , 0
  4669.2     .07       0  4948.4     .12       0  4988.4     .07       0
  4994.2     .05       0  4998.2     .07       0  5143.6     .12       0
Bank Sta=4994.2,4998.2
XS Rating Curve= 0 ,0
Exp/Cntr=0.3,0.1

Type RM Length L Ch R = 1 ,983     ,467,467,467
BEGIN DESCRIPTION:
Stream0098_DS 2.0
END DESCRIPTION:
XS GIS Cut Line= 3
        2007725.       13915525.        2007725.       13915225.
      2007475.01     13914925.01
#Sta/Elev= 30
    4705 1576.31    4745 1572.36    4765 1567.31    4785 1564.94    4795 1561.37
    4805 1559.34    4845 1552.97    4905 1548.59    4915 1546.92    4965 1545.82
    4983 1544.31  4983.3 1543.81    4987 1544.31  5026.5 1547.72  5040.8 1552.96
  5047.3 1557.38  5055.1  1557.9  5069.4 1556.62  5075.9 1553.55  5096.8 1555.39
  5118.9 1558.83  5139.7 1565.09    5154  1566.5  5189.2 1573.27    5197 1573.82
  5246.5 1585.52  5331.1 1594.82  5345.4 1597.54  5381.8 1606.83  5395.5  1608.6
#Mann= 3 ,-1 , 0
    4705     .07       0    4983     .05       0    4987     .07       0
Bank Sta=4983,4987
XS Rating Curve= 0 ,0
Exp/Cntr=0.3,0.1

Type RM Length L Ch R = 1 ,516     ,453,453,453
BEGIN DESCRIPTION:
Stream0098_DS 1.0
END DESCRIPTION:
XS GIS Cut Line= 3
        2008075.       13915475.        2008175.       13915175.
      2008125.01     13915025.04
#Sta/Elev= 30
  4683.8 1567.52    4726 1565.93  4757.3  1558.6  4768.1 1556.65  4789.2 1554.35
  4799.7 1554.58  4810.3 1553.27  4831.4 1549.33  4841.9 1549.08  4852.5 1546.04
    4863 1543.87  4894.6 1539.57    4900  1539.3  4929.3 1537.57  4947.3 1536.74
  4957.9 1535.46  4968.4 1530.76  4976.9 1528.14  4977.2 1527.64  4980.7 1527.64
  4980.9 1528.14  4989.5 1529.95  4997.4 1535.51  5066.5 1536.41  5084.4 1536.28
  5094.9 1537.74  5105.4 1541.47    5116 1547.11  5126.5 1549.12  5158.1  1550.9
#Mann= 7 ,-1 , 0
  4683.8    .035       0  4757.3     .07       0    4900    .035       0
  4929.3     .07       0  4976.9     .05       0  4980.9     .07       0
  5066.5     .12       0
#XS Ineff= 2 , 0
       0                 5001.53       0 1536.19
Permanent Ineff=
       F       F
Bank Sta=4976.9,4980.9
XS Rating Curve= 0 ,0
Exp/Cntr=0.3,0.1

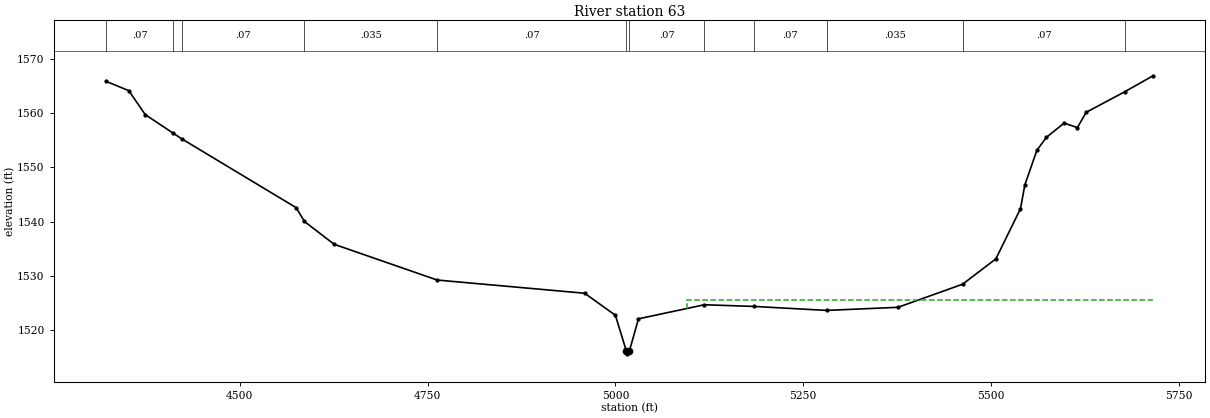
Type RM Length L Ch R = 1 ,63      ,0,0,0
BEGIN DESCRIPTION:
Stream0098_DS 0.0
END DESCRIPTION:
XS GIS Cut Line= 5
      2008132.66     13915565.47      2008586.25     13915244.65
      2008612.66      13915119.9      2008549.43     13914826.82
      2008173.41     13914661.44
#Sta/Elev= 30
  4322.1 1565.85  4352.2 1564.14    4374 1559.74    4411 1556.33  4422.9 1555.25
    4575 1542.59    4586 1540.05  4625.5 1535.85  4762.8 1529.26  4959.1 1526.83
    5000 1522.77  5014.6 1516.17  5014.8 1515.67  5018.6 1516.17  5030.7 1522.12
  5118.5 1524.71  5184.7  1524.4  5281.1 1523.67  5376.2 1524.24  5462.2 1528.49
  5506.5 1533.16  5539.3  1542.4  5545.1 1546.79  5561.1 1553.15  5573.9 1555.55
  5597.3 1558.16  5615.1 1557.34  5626.7 1560.15    5678 1563.93  5715.8 1566.88
#Mann= 12 ,-1 , 0
  4322.1     .07       0    4411    .035       0  4422.9     .07       0
    4586    .035       0  4762.8     .07       0  5014.6     .05       0
  5018.6     .07       0  5118.5    .035       0  5184.7     .07       0
  5281.1    .035       0  5462.2     .07       0    5678     .12       0
#XS Ineff= 2 , 0
       0                 5094.84       0 1525.63
Permanent Ineff=
       F       F
Bank Sta=5014.6,5018.6
XS Rating Curve= 0 ,0
Exp/Cntr=0.3,0.1

Chan Stop Cuts=-1
Use User Specified Reach Order=0
Composite Channel Slope=5