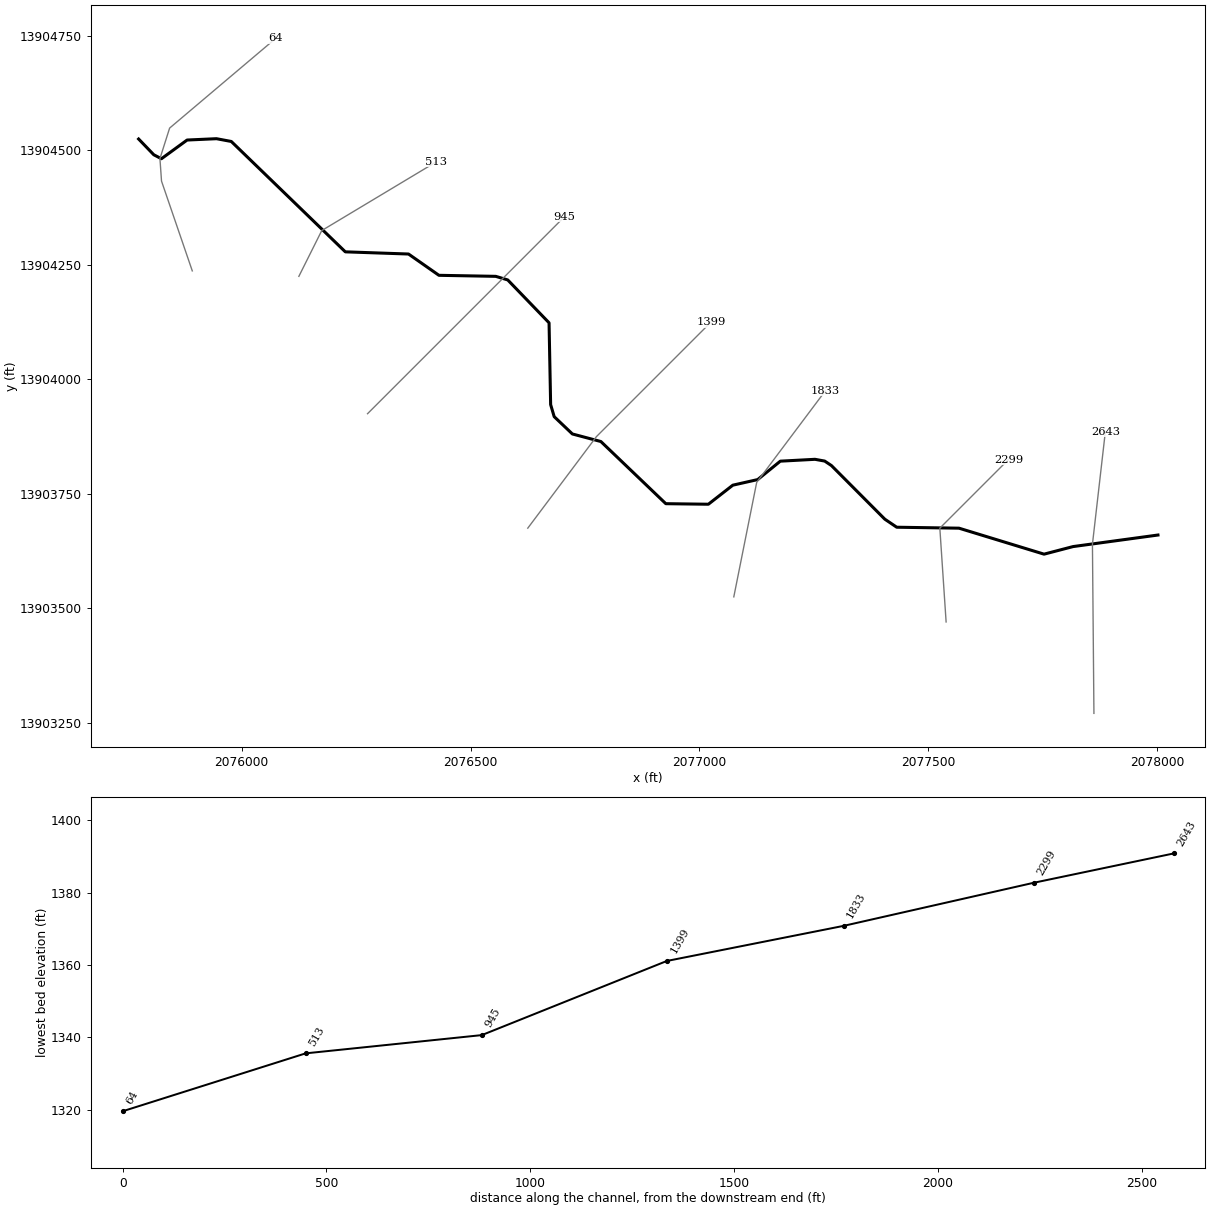
--- Stream0099_DS.prj (project) ---

Proj Title=Stream0099_DS Base Level Engineering
Current Plan=p01
Default Exp/Contr=0.3,0.1
English Units
Geom File=g01
Flow File=f01
Plan File=p01
BEGIN DESCRIPTION:
Stream0099_DS
END DESCRIPTION:

--- Stream0099_DS.p01 (plan) ---

Plan Title=Multiple Run
Short Identifier=Multiple
Geom File=g01
Flow File=f01
Subcritical Flow
K Sum by GR= 0
Std Step Tol= 0.01
Critical Tol= 0.01
Num of Std Step Trials= 20
Max Error Tol= 0.3
Flow Tol Ratio= 0.001
Split Flow NTrial= 30
Split Flow Tol= 0.02
Split Flow Ratio= 0.02
Log Output Level= 0
Friction Slope Method= 1
Unsteady Friction Slope Method= 2
Unsteady Bridges Friction Slope Method= 1
Parabolic Critical Depth
Global Vel Dist=  1 , 1 , 1
Global Log Level= 0
CheckData=True
Encroach Param= -1, 0, 0, 0
BEGIN DESCRIPTION:
Multiple Run
END DESCRIPTION:

--- Stream0099_DS.f01 (steady flow) ---

Flow Title=Multiple
Number of Profiles=7
Profile Names=10-year,25-year,50-year,1pct_min,100-year,1pct_plu,500-year
River Rch & RM= Stream0099_DS,Reach-1,2643
     315     491     647     416     829    1655    1341
River Rch & RM= Stream0099_DS,Reach-1,1833
     542     880    1189     783    1561    3115    2653
Boundary for River Rch & Prof#=Stream0099_DS,Reach-1,1
Up Type=0
Dn Type=3
Dn Slope=0.005
Boundary for River Rch & Prof#=Stream0099_DS,Reach-1,2
Up Type=0
Dn Type=3
Dn Slope=0.005
Boundary for River Rch & Prof#=Stream0099_DS,Reach-1,3
Up Type=0
Dn Type=3
Dn Slope=0.005
Boundary for River Rch & Prof#=Stream0099_DS,Reach-1,4
Up Type=0
Dn Type=3
Dn Slope=0.005
Boundary for River Rch & Prof#=Stream0099_DS,Reach-1,5
Up Type=0
Dn Type=3
Dn Slope=0.005
Boundary for River Rch & Prof#=Stream0099_DS,Reach-1,6
Up Type=0
Dn Type=3
Dn Slope=0.005
Boundary for River Rch & Prof#=Stream0099_DS,Reach-1,7
Up Type=0
Dn Type=3
Dn Slope=0.005

--- Stream0099_DS.g01 (geometry) ---

Geom Title=Existing Conditions

River Reach=Stream0099_DS,Reach-1
Reach XY= 30
      2078001.43     13903660.01      2077816.02     13903634.78
      2077752.63     13903618.22      2077566.86     13903674.96
      2077430.85     13903677.05      2077404.84     13903694.61
      2077288.30     13903811.66      2077273.50     13903821.54
      2077252.28     13903825.38      2077176.59     13903821.33
      2077127.18     13903781.12      2077072.82     13903768.88
      2077019.44     13903727.26      2076926.50     13903728.46
      2076784.66     13903864.21      2076722.42     13903880.74
      2076682.69     13903918.52      2076674.92     13903944.88
      2076671.47     13904123.55      2076581.21     13904217.19
      2076555.01     13904225.02      2076430.94     13904227.27
      2076364.49     13904273.77      2076226.47     13904278.54
      2075977.43     13904519.60      2075945.08     13904525.66
      2075880.88     13904522.74      2075824.86     13904481.91
      2075808.16     13904490.54      2075775.00     13904525.00

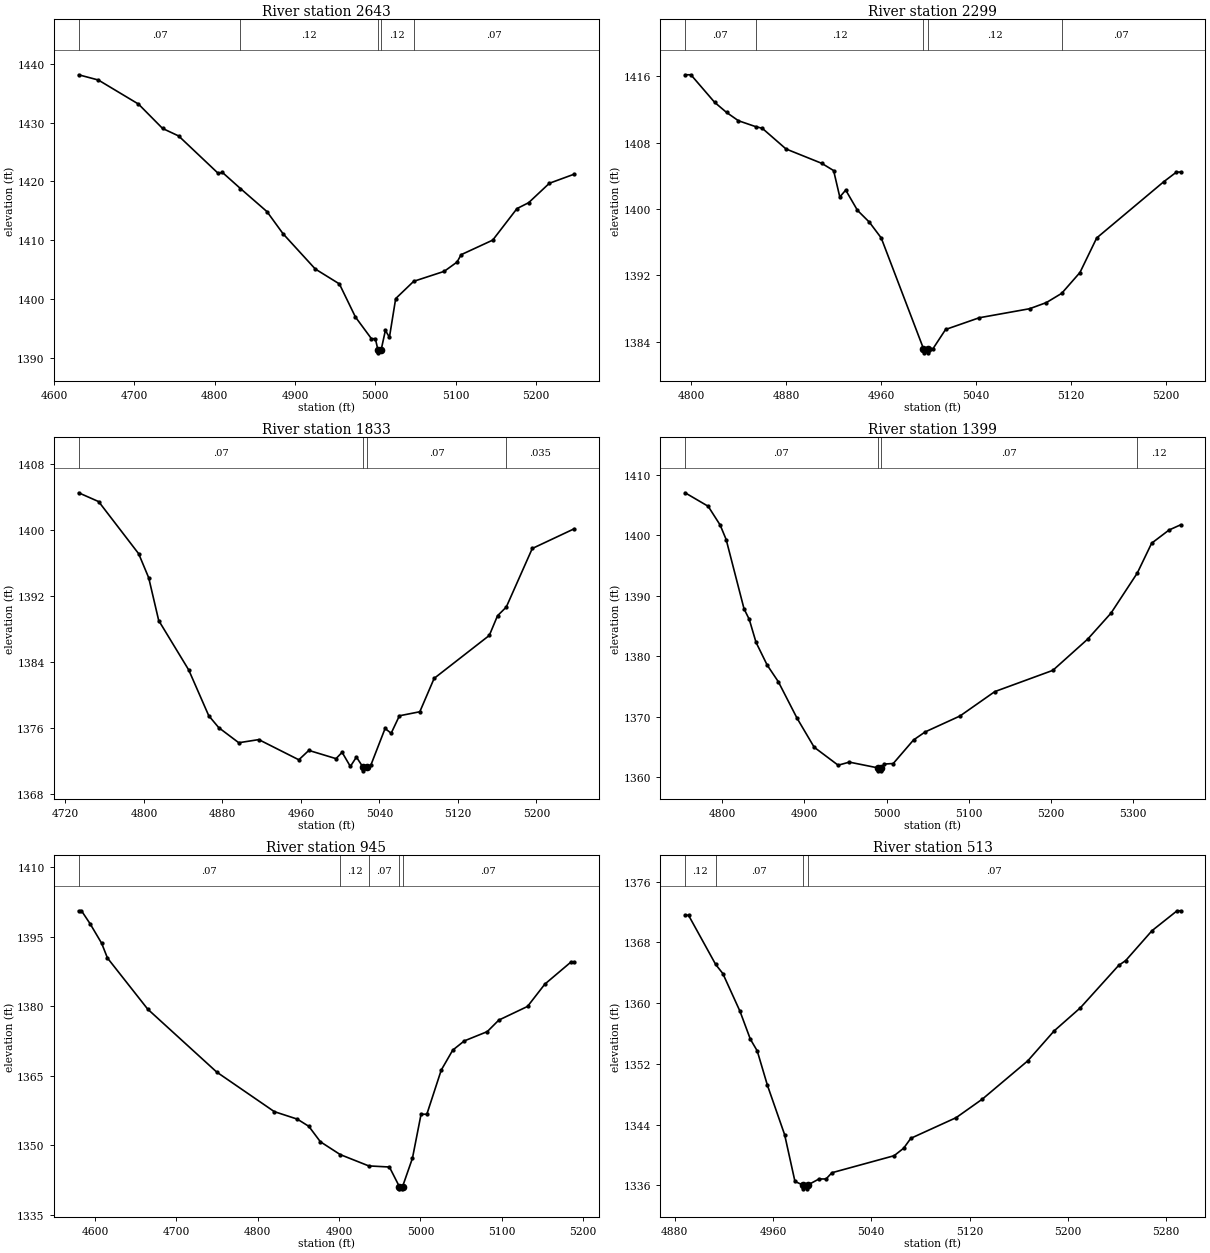
Type RM Length L Ch R = 1,2643,344,344,344
BEGIN DESCRIPTION:
Stream0099_DS 6.0
END DESCRIPTION:
XS GIS Cut Line= 3
      2077861.57     13903270.46      2077858.31     13903639.85
      2077886.52     13903885.73
#Sta/Elev= 30
  4630.6 1438.17  4655.1 1437.28  4705.1 1433.18  4735.1 1429.03  4755.1 1427.75
  4804.5 1421.36  4809.5 1421.55  4832.0 1418.80  4865.1 1414.86  4885.1 1411.09
  4925.2 1405.09  4955.2 1402.55  4975.2 1396.91  4995.1 1393.22  5000.0 1393.22
  5003.2 1391.31  5003.4 1390.81  5007.2 1391.31  5012.5 1394.64  5017.5 1393.45
  5025.3 1400.05  5047.7 1402.99  5085.7 1404.69  5101.7 1406.27  5106.7 1407.52
  5146.1 1410.01  5176.3 1415.38  5190.8 1416.38  5216.6 1419.69  5247.5 1421.24
#Mann=5,-1,0
  4630.6    0.07       0  4832.0    0.12       0  5003.2    0.05       0
  5007.2    0.12       0  5047.7    0.07       0
Bank Sta=5003.2,5007.2
Exp/Cntr=0.3,0.1

Type RM Length L Ch R = 1,2299,466,466,466
BEGIN DESCRIPTION:
Stream0099_DS 5.0
END DESCRIPTION:
XS GIS Cut Line= 3
      2077538.72     13903470.16      2077525.00     13903675.00
      2077674.97     13903824.97
#Sta/Elev= 30
  4794.8 1416.16  4799.7 1416.16  4819.7 1412.84  4829.7 1411.63  4839.7 1410.63
  4854.2 1409.92  4859.8 1409.72  4879.8 1407.23  4909.9 1405.50  4919.9 1404.63
  4925.1 1401.45  4930.1 1402.28  4940.0 1399.84  4950.0 1398.42  4960.0 1396.52
  4995.6 1383.19  4995.8 1382.69  4999.3 1382.69  4999.6 1383.19  5003.6 1383.19
  5014.2 1385.50  5042.5 1386.91  5085.0 1388.00  5099.1 1388.74  5112.0 1389.85
  5127.4 1392.36  5141.5 1396.52  5198.1 1403.30  5208.7 1404.45  5212.2 1404.45
#Mann=5,-1,0
  4794.8    0.07       0  4854.2    0.12       0  4995.6    0.05       0
  4999.6    0.12       0  5112.0    0.07       0
Bank Sta=4995.6,4999.6
Exp/Cntr=0.3,0.1

Type RM Length L Ch R = 1,1833,434,434,434
BEGIN DESCRIPTION:
Stream0099_DS 4.0
END DESCRIPTION:
XS GIS Cut Line= 3
      2077074.99     13903524.95      2077125.00     13903775.00
      2077275.00     13903975.00
#Sta/Elev= 30
  4733.5 1404.53  4753.9 1403.46  4794.7 1397.13  4804.9 1394.22  4815.1 1389.03
  4845.7 1383.03  4866.1 1377.48  4876.3 1376.03  4896.7 1374.20  4917.1 1374.58
  4957.9 1372.13  4968.1 1373.27  4995.8 1372.27  5002.0 1373.04  5010.4 1371.32
  5016.6 1372.46  5023.0 1371.29  5023.2 1370.79  5027.0 1371.29  5031.2 1371.45
  5045.8 1375.93  5052.0 1375.35  5060.4 1377.47  5081.2 1377.96  5095.8 1382.01
  5152.0 1387.22  5160.4 1389.61  5169.3 1390.66  5195.8 1397.77  5238.5 1400.16
#Mann=4,-1,0
  4733.5    0.07       0  5023.0    0.05       0  5027.0    0.07       0
  5169.3   0.035       0
Bank Sta=5023,5027
Exp/Cntr=0.3,0.1

Type RM Length L Ch R = 1,1399,454,454,454
BEGIN DESCRIPTION:
Stream0099_DS 3.0
END DESCRIPTION:
XS GIS Cut Line= 3
      2076625.03     13903675.03      2076775.00     13903875.00
      2077024.99     13904124.99
#Sta/Elev= 30
  4754.6 1407.01  4782.7 1404.78  4797.3 1401.68  4804.6 1399.29  4826.4 1387.83
  4832.7 1386.11  4841.0 1382.30  4854.6 1378.54  4868.1 1375.81  4891.0 1369.76
  4911.8 1364.98  4941.0 1362.01  4954.6 1362.52  4989.0 1361.58  4989.3 1361.08
  4992.8 1361.08  4993.0 1361.58  4997.3 1362.20  5008.1 1362.29  5032.8 1366.18
  5047.0 1367.51  5089.4 1370.14  5131.8 1374.17  5202.5 1377.68  5245.0 1382.85
  5273.3 1387.13  5305.3 1393.75  5322.8 1398.68  5344.0 1400.86  5358.1 1401.72
#Mann=4,-1,0
  4754.6    0.07       0  4989.0    0.05       0  4993.0    0.07       0
  5305.3    0.12       0
Bank Sta=4989,4993
Exp/Cntr=0.3,0.1

Type RM Length L Ch R = 1,945,432,432,432
BEGIN DESCRIPTION:
Stream0099_DS 2.0
END DESCRIPTION:
XS GIS Cut Line= 3
      2076275.00     13903925.00      2076575.00     13904225.00
      2076705.41     13904355.57
#Sta/Elev= 30
  4580.0 1400.59  4583.5 1400.59  4594.1 1397.79  4608.3 1393.57  4615.4 1390.40
  4664.9 1379.36  4749.7 1365.78  4820.4 1357.25  4848.7 1355.63  4862.8 1354.08
  4877.0 1350.75  4901.4 1347.98  4936.4 1345.54  4961.8 1345.30  4974.0 1341.09
  4974.2 1340.59  4977.7 1340.59  4978.0 1341.09  4990.1 1347.19  5000.7 1356.69
  5007.8 1356.69  5025.5 1366.22  5039.6 1370.52  5053.8 1372.51  5082.0 1374.51
  5096.2 1377.00  5131.5 1379.95  5152.8 1384.77  5185.0 1389.55  5188.8 1389.55
#Mann=5,-1,0
  4580.0    0.07       0  4901.4    0.12       0  4936.4    0.07       0
  4974.0    0.05       0  4978.0    0.07       0
Bank Sta=4974,4978
Exp/Cntr=0.3,0.1

Type RM Length L Ch R = 1,513,449,449,449
BEGIN DESCRIPTION:
Stream0099_DS 1.0
END DESCRIPTION:
XS GIS Cut Line= 3
      2076125.02     13904225.03      2076175.00     13904325.00
      2076424.99     13904474.99
#Sta/Elev= 30
  4888.5 1371.56  4891.3 1371.56  4913.4 1365.08  4919.2 1363.89  4933.2 1358.91
  4941.6 1355.25  4947.2 1353.71  4955.5 1349.18  4969.5 1342.68  4977.9 1336.53
  4984.3 1336.05  4984.5 1335.55  4988.0 1335.55  4988.3 1336.05  4997.5 1336.85
  5003.2 1336.85  5008.0 1337.67  5058.6 1339.91  5066.4 1340.90  5072.2 1342.20
  5109.1 1344.92  5130.5 1347.37  5167.4 1352.40  5188.8 1356.33  5210.2 1359.38
  5241.3 1364.95  5247.1 1365.60  5268.5 1369.53  5288.9 1372.15  5291.8 1372.15
#Mann=4,-1,0
  4888.5    0.12       0  4913.4    0.07       0  4984.3    0.05       0
  4988.3    0.07       0
Bank Sta=4984.3,4988.3
Exp/Cntr=0.3,0.1

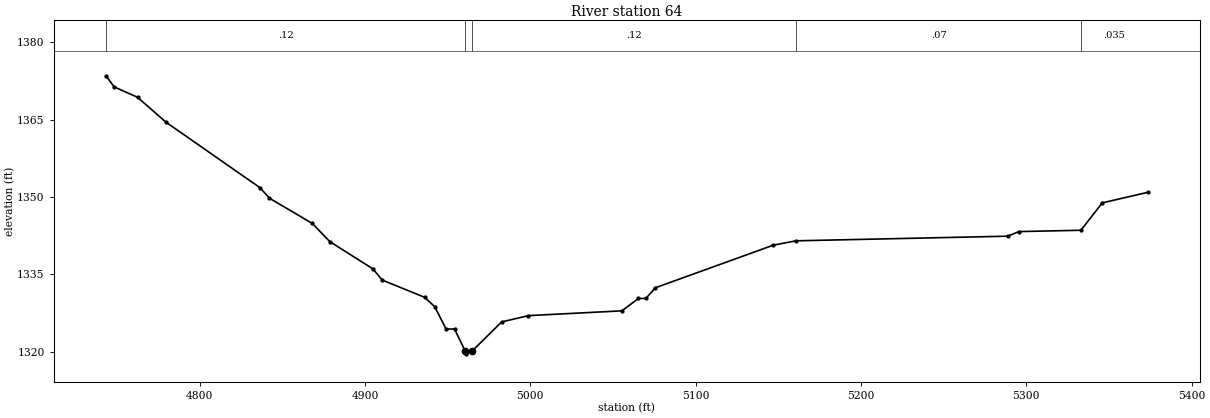
Type RM Length L Ch R = 1,64,0,0,0
BEGIN DESCRIPTION:
Stream0099_DS 0.0
END DESCRIPTION:
XS GIS Cut Line= 5
      2075892.21     13904236.95      2075825.02     13904433.01
      2075821.55     13904482.24      2075842.71     13904548.82
      2076074.57     13904744.87
#Sta/Elev= 30
  4743.4 1373.48  4748.4 1371.32  4762.5 1369.31  4779.7 1364.48  4836.5 1351.78
  4842.3 1349.73  4868.2 1344.84  4878.8 1341.31  4904.8 1336.04  4910.5 1333.85
  4936.1 1330.52  4942.2 1328.70  4949.1 1324.36  4954.2 1324.36  4960.7 1320.05
  4960.9 1319.55  4964.7 1320.05  4982.7 1325.74  4998.9 1326.96  5055.4 1327.89
  5065.4 1330.29  5069.9 1330.29  5075.6 1332.36  5147.0 1340.63  5160.7 1341.47
  5288.7 1342.37  5295.5 1343.26  5333.0 1343.52  5345.9 1348.83  5373.5 1350.88
#Mann=5,-1,0
  4743.4    0.12       0  4960.7    0.05       0  4964.7    0.12       0
  5160.7    0.07       0  5333.0   0.035       0
Bank Sta=4960.7,4964.7
Exp/Cntr=0.3,0.1

Chan Stop Cuts=-1