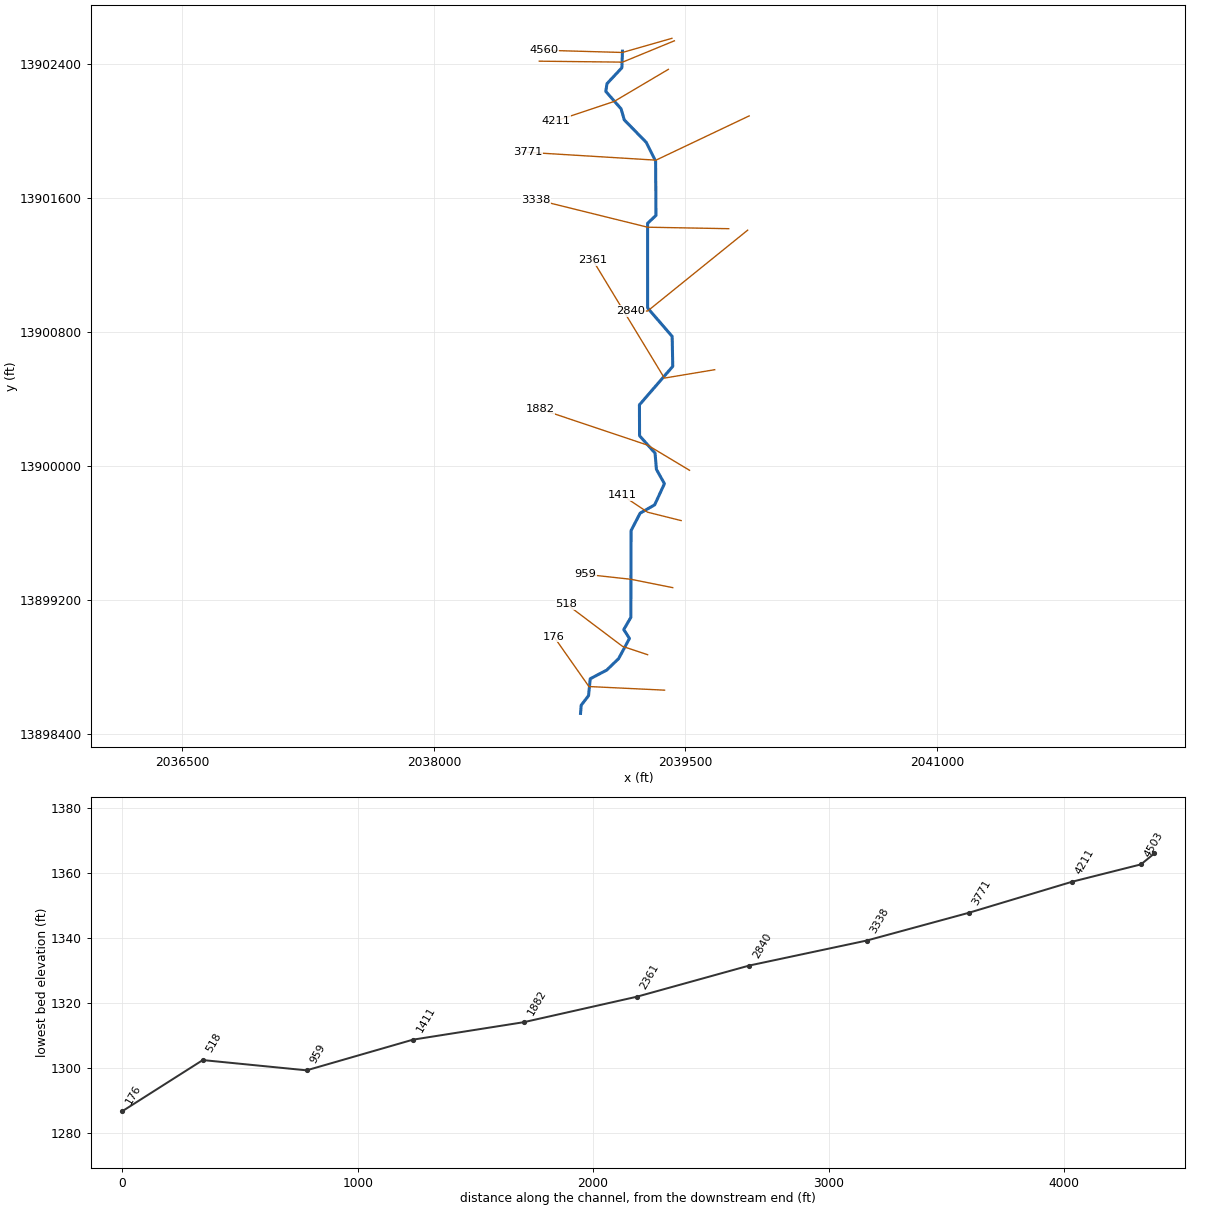
--- Stream0100_DS.prj (project) ---

Proj Title=Stream0100_DS Base Level Engineering
Current Plan=p01
Default Exp/Contr=0.3,0.1
English Units
Geom File=g01
Flow File=f01
Plan File=p01
BEGIN DESCRIPTION:
Stream0100_DS
END DESCRIPTION:

--- Stream0100_DS.p01 (plan) ---

Plan Title=Multiple Run
Short Identifier=Multiple
Geom File=g01
Flow File=f01
Subcritical Flow
K Sum by GR= 0
Std Step Tol= 0.01
Critical Tol= 0.01
Num of Std Step Trials= 20
Max Error Tol= 0.3
Flow Tol Ratio= 0.001
Split Flow NTrial= 30
Split Flow Tol= 0.02
Split Flow Ratio= 0.02
Log Output Level= 0
Friction Slope Method= 1
Unsteady Friction Slope Method= 2
Unsteady Bridges Friction Slope Method= 1
Parabolic Critical Depth
Global Vel Dist=  1 , 1 , 1
Global Log Level= 0
CheckData=True
Encroach Param= -1, 0, 0, 0
BEGIN DESCRIPTION:
Multiple Run
END DESCRIPTION:

--- Stream0100_DS.f01 (steady flow) ---

Flow Title=Multiple
Number of Profiles=7
Profile Names=10-year,25-year,50-year,1pct_min,100-year,1pct_plu,500-year
River Rch & RM= Stream0100_DS,Reach-1,4560
     542     878    1184     777    1550    3093    2621
River Rch & RM= Stream0100_DS,Reach-1,4211
     845    1408    1935    1291    2575    5138    4507
Boundary for River Rch & Prof#=Stream0100_DS,Reach-1,1
Up Type=0
Dn Type=3
Dn Slope=0.005
Boundary for River Rch & Prof#=Stream0100_DS,Reach-1,2
Up Type=0
Dn Type=3
Dn Slope=0.005
Boundary for River Rch & Prof#=Stream0100_DS,Reach-1,3
Up Type=0
Dn Type=3
Dn Slope=0.005
Boundary for River Rch & Prof#=Stream0100_DS,Reach-1,4
Up Type=0
Dn Type=3
Dn Slope=0.005
Boundary for River Rch & Prof#=Stream0100_DS,Reach-1,5
Up Type=0
Dn Type=3
Dn Slope=0.005
Boundary for River Rch & Prof#=Stream0100_DS,Reach-1,6
Up Type=0
Dn Type=3
Dn Slope=0.005
Boundary for River Rch & Prof#=Stream0100_DS,Reach-1,7
Up Type=0
Dn Type=3
Dn Slope=0.005

--- Stream0100_DS.g01 (geometry) ---

Geom Title=Existing Conditions

River Reach=Stream0100_DS,Reach-1
Reach XY= 30
      2039125.00     13902475.00      2039121.60     13902376.41
      2039032.48     13902281.04      2039025.71     13902234.80
      2039116.82     13902131.04      2039135.78     13902065.32
      2039266.86     13901931.06      2039322.76     13901819.07
      2039324.70     13901495.30      2039274.75     13901447.98
      2039275.09     13900943.22      2039421.46     13900773.54
      2039425.04     13900594.98      2039226.20     13900365.41
      2039227.06     13900180.86      2039319.46     13900077.42
      2039327.50     13899980.56      2039375.30     13899895.17
      2039316.94     13899768.68      2039230.62     13899719.38
      2039176.35     13899615.37      2039175.00     13899097.65
      2039132.80     13899024.90      2039166.76     13898971.77
      2039102.02     13898851.49      2039031.05     13898783.16
      2038932.74     13898731.46      2038922.66     13898630.52
      2038878.64     13898573.49      2038875.00     13898525.00

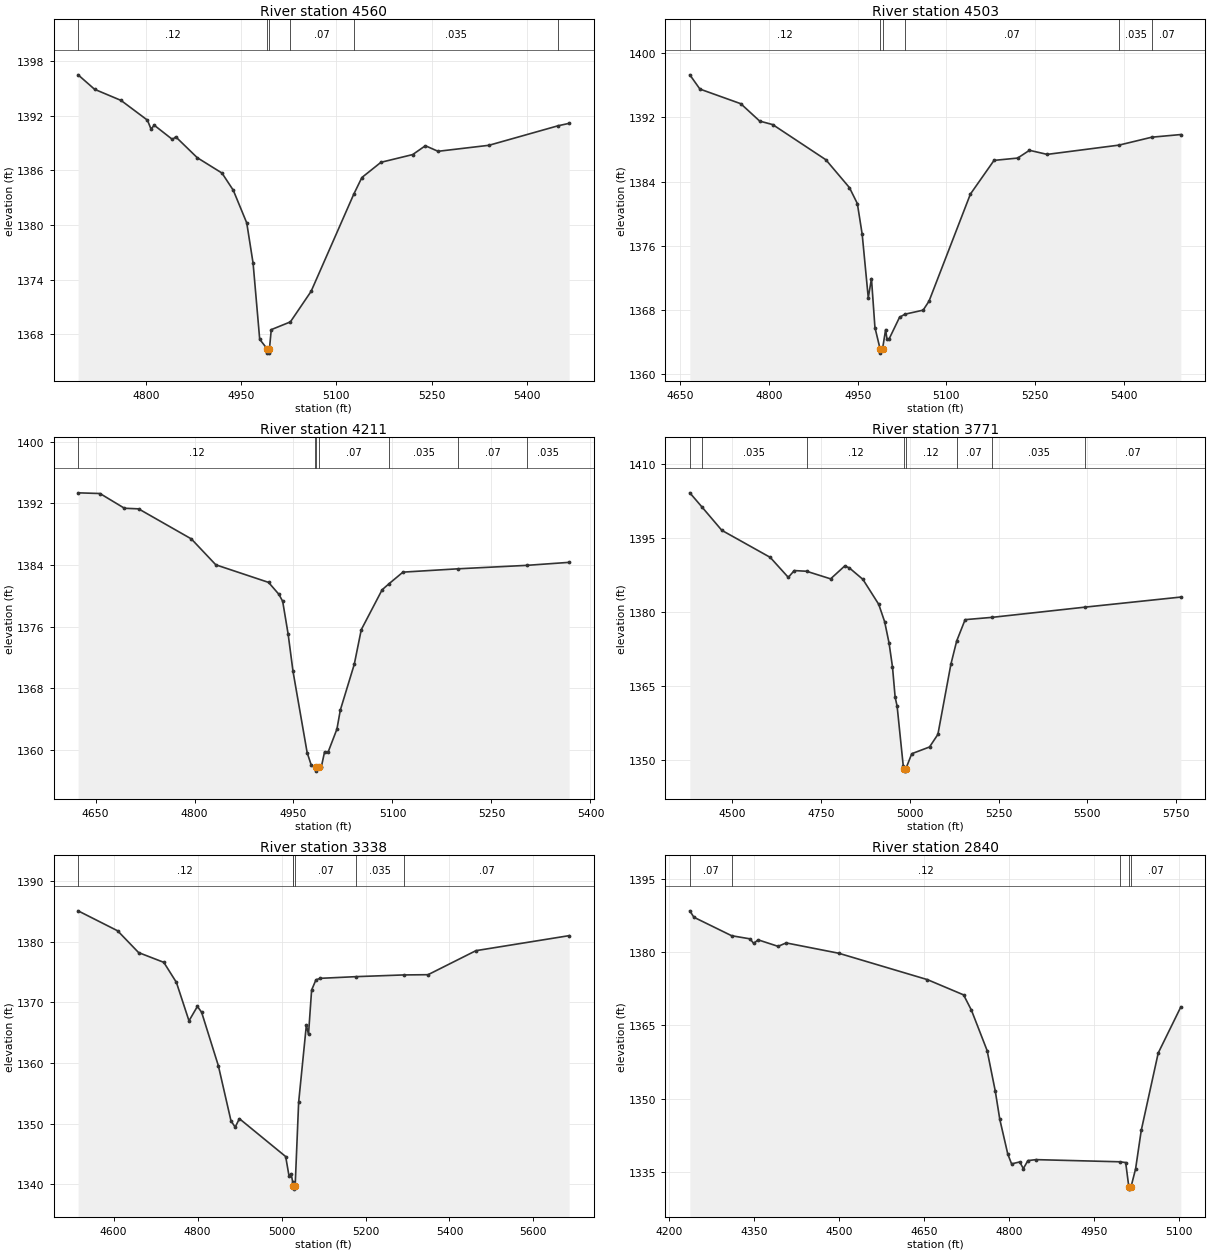
Type RM Length L Ch R = 1,4560,57,57,57
BEGIN DESCRIPTION:
Stream0100_DS 11.0
END DESCRIPTION:
XS GIS Cut Line= 3
      2039420.03     13902551.64      2039125.04     13902467.33
      2038658.73     13902480.54
#Sta/Elev= 30
  4693.2 1396.50  4719.2 1394.91  4760.8 1393.69  4802.4 1391.52  4808.0 1390.55
  4813.2 1390.96  4841.8 1389.40  4847.0 1389.69  4880.8 1387.40  4919.8 1385.71
  4937.6 1383.82  4958.8 1380.23  4968.8 1375.80  4979.2 1367.45  4990.6 1366.43
  4990.8 1365.93  4994.3 1365.93  4994.6 1366.43  4997.4 1368.51  5027.5 1369.36
  5060.1 1372.71  5127.2 1383.37  5140.1 1385.22  5170.1 1386.89  5220.1 1387.74
  5240.1 1388.71  5260.1 1388.10  5340.2 1388.76  5449.4 1390.91  5466.5 1391.17
#Mann=6,-1,0
  4693.2    0.12       0  4990.6    0.05       0  4994.6    0.12       0
  5027.5    0.07       0  5127.2   0.035       0  5449.4    0.07       0
Bank Sta=4990.6,4994.6
Exp/Cntr=0.3,0.1

Type RM Length L Ch R = 1,4503,292,292,292
BEGIN DESCRIPTION:
Stream0100_DS 10.0
END DESCRIPTION:
XS GIS Cut Line= 3
      2039434.81     13902536.95      2039125.79     13902409.67
      2038628.72     13902415.36
#Sta/Elev= 30
  4665.8 1397.33  4682.9 1395.55  4752.1 1393.72  4784.1 1391.55  4806.2 1391.11
  4896.1 1386.72  4936.0 1383.24  4949.4 1381.25  4957.6 1377.42  4967.9 1369.47
  4973.3 1371.88  4979.2 1365.76  4988.0 1363.06  4988.3 1362.56  4992.0 1363.06
  4997.3 1365.50  4999.6 1364.29  5002.9 1364.29  5020.8 1367.03  5029.8 1367.42
  5060.8 1367.93  5070.8 1369.06  5140.8 1382.43  5180.8 1386.64  5220.8 1386.93
  5240.8 1387.90  5270.8 1387.39  5392.5 1388.55  5448.0 1389.54  5497.1 1389.87
#Mann=6,-1,0
  4665.8    0.12       0  4988.0    0.05       0  4992.0    0.12       0
  5029.8    0.07       0  5392.5   0.035       0  5448.0    0.07       0
Bank Sta=4988,4992
Exp/Cntr=0.3,0.1

Type RM Length L Ch R = 1,4211,440,440,440
BEGIN DESCRIPTION:
Stream0100_DS 9.0
END DESCRIPTION:
XS GIS Cut Line= 3
      2039398.90     13902366.67      2039075.00     13902175.00
      2038726.19     13902058.53
#Sta/Elev= 30
  4623.6 1393.35  4656.8 1393.26  4693.8 1391.35  4715.3 1391.27  4795.2 1387.37
  4832.3 1384.01  4912.2 1381.73  4927.8 1380.19  4933.6 1379.28  4941.9 1375.01
  4949.3 1370.17  4970.7 1359.64  4976.7 1358.07  4983.0 1357.80  4984.3 1357.74
  4984.6 1357.24  4988.3 1357.74  4992.1 1357.75  4997.1 1359.74  5002.6 1359.74
  5015.8 1362.69  5021.0 1365.17  5042.1 1371.10  5052.7 1375.59  5084.3 1380.77
  5095.1 1381.58  5115.9 1383.06  5198.9 1383.49  5303.7 1383.94  5367.7 1384.33
#Mann=7,-1,0
  4623.6    0.12       0  4983.0    0.07       0  4984.3    0.05       0
  4988.3    0.07       0  5095.1   0.035       0  5198.9    0.07       0
  5303.7   0.035       0
Bank Sta=4984.3,4988.3
Exp/Cntr=0.3,0.1

Type RM Length L Ch R = 1,3771,433,433,433
BEGIN DESCRIPTION:
Stream0100_DS 8.0
END DESCRIPTION:
XS GIS Cut Line= 3
      2039880.73     13902088.93      2039325.00     13901825.00
      2038558.45     13901871.80
#Sta/Elev= 30
  4380.1 1404.10  4413.6 1401.29  4470.2 1396.50  4606.5 1391.02  4657.5 1386.96
  4674.3 1388.34  4709.0 1388.20  4776.7 1386.66  4816.6 1389.28  4829.3 1388.89
  4867.6 1386.56  4912.3 1381.49  4928.9 1377.97  4941.3 1373.66  4951.0 1368.80
  4958.5 1362.64  4964.0 1360.87  4981.2 1348.80  4984.7 1348.18  4985.0 1347.68
  4988.7 1348.18  5005.3 1351.21  5055.4 1352.58  5078.9 1355.13  5115.5 1369.35
  5131.8 1374.06  5155.6 1378.39  5230.7 1378.85  5493.8 1380.93  5763.3 1382.97
#Mann=8,-1,0
  4380.1    0.07       0  4413.6   0.035       0  4709.0    0.12       0
  4984.7    0.05       0  4988.7    0.12       0  5131.8    0.07       0
  5230.7   0.035       0  5493.8    0.07       0
Bank Sta=4984.7,4988.7
Exp/Cntr=0.3,0.1

Type RM Length L Ch R = 1,3338,498,498,498
BEGIN DESCRIPTION:
Stream0100_DS 7.0
END DESCRIPTION:
XS GIS Cut Line= 3
      2039759.14     13901416.17      2039275.00     13901425.00
      2038609.49     13901589.66
#Sta/Elev= 30
  4515.3 1385.14  4609.5 1381.84  4659.5 1378.24  4719.5 1376.63  4749.5 1373.32
  4779.5 1366.97  4799.5 1369.35  4809.5 1368.40  4849.5 1359.54  4879.5 1350.46
  4889.5 1349.40  4899.5 1350.81  5009.8 1344.55  5017.7 1341.38  5022.8 1341.72
  5026.4 1340.40  5028.4 1339.67  5028.7 1339.17  5032.4 1339.67  5040.7 1353.50
  5059.1 1366.27  5064.2 1364.73  5071.6 1372.05  5081.9 1373.74  5092.2 1373.99
  5178.5 1374.27  5290.6 1374.55  5349.0 1374.59  5463.1 1378.56  5685.1 1381.04
#Mann=6,-1,0
  4515.3    0.12       0  5026.4    0.07       0  5028.4    0.05       0
  5032.4    0.07       0  5178.5   0.035       0  5290.6    0.07       0
Bank Sta=5028.4,5032.4
Exp/Cntr=0.3,0.1

Type RM Length L Ch R = 1,2840,479,479,479
BEGIN DESCRIPTION:
Stream0100_DS 6.0
END DESCRIPTION:
XS GIS Cut Line= 3
      2039871.98     13901407.46      2039275.00     13900925.00
      2039174.96     13900925.00
#Sta/Elev= 30
  4236.5 1388.40  4243.7 1387.09  4310.4 1383.31  4342.9 1382.67  4349.3 1381.74
  4357.2 1382.47  4392.4 1381.14  4406.8 1381.84  4499.6 1379.73  4656.2 1374.34
  4720.2 1371.22  4734.1 1368.08  4761.8 1359.83  4776.2 1351.55  4784.2 1345.76
  4798.3 1338.68  4805.0 1336.67  4819.4 1337.07  4825.8 1335.71  4833.8 1337.34
  4848.1 1337.54  4995.8 1337.10  5006.6 1336.95  5012.1 1332.01  5012.3 1331.51
  5016.1 1332.01  5024.1 1335.64  5034.1 1343.51  5064.1 1359.34  5104.1 1368.77
#Mann=5,-1,0
  4236.5    0.07       0  4310.4    0.12       0  4995.8    0.07       0
  5012.1    0.05       0  5016.1    0.07       0
Bank Sta=5012.1,5016.1
Exp/Cntr=0.3,0.1

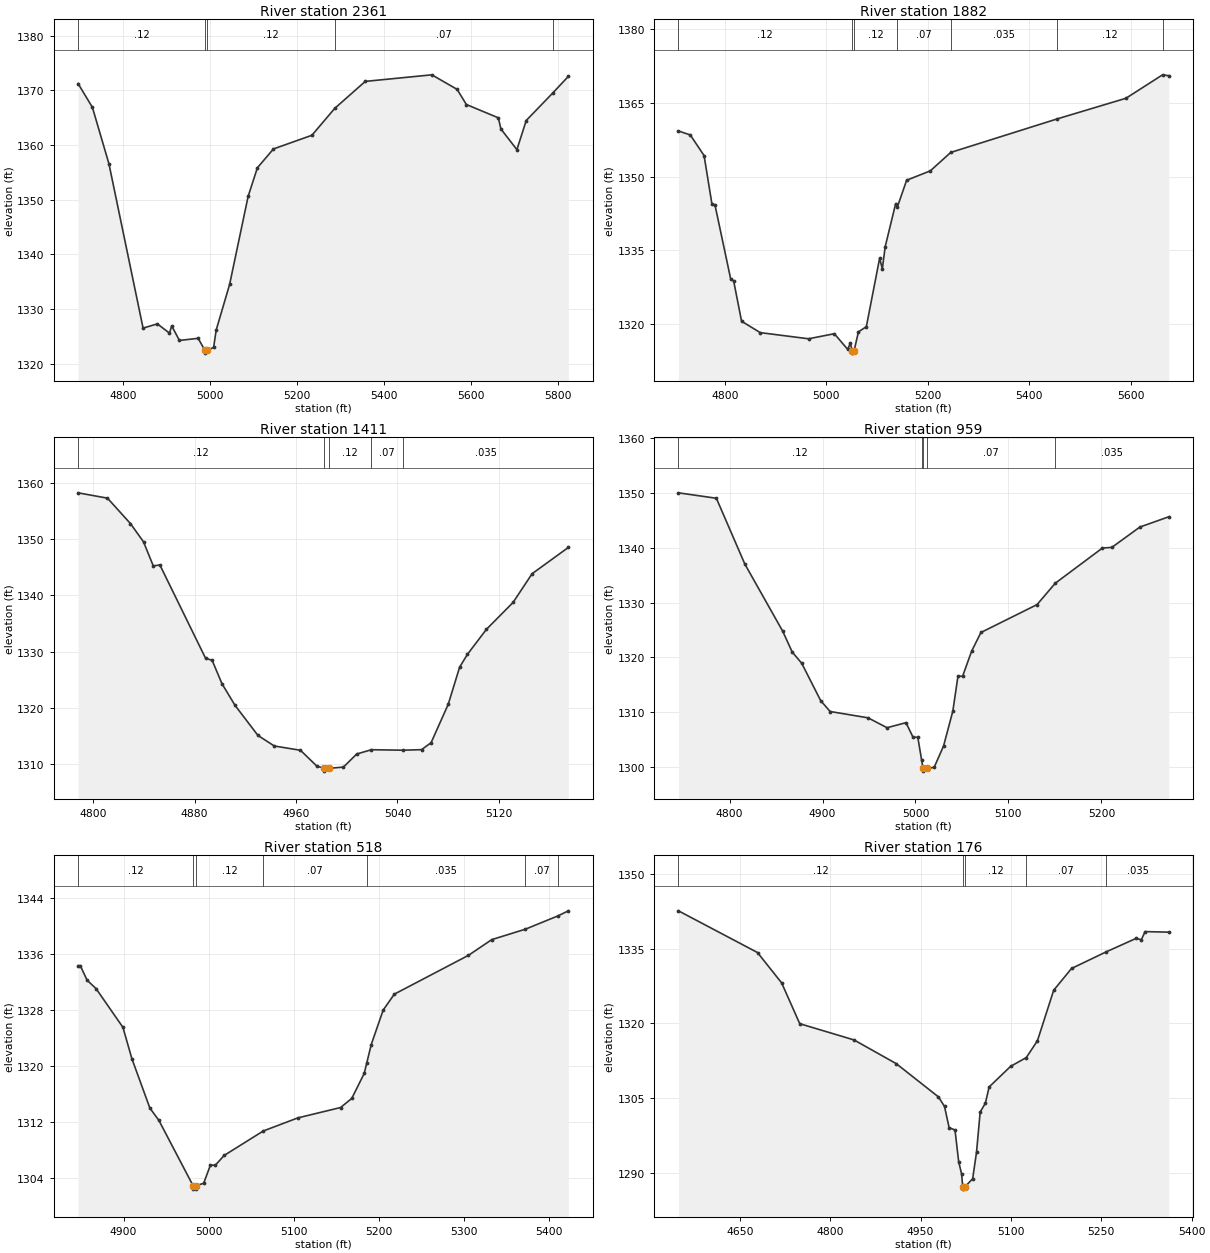
Type RM Length L Ch R = 1,2361,479,479,479
BEGIN DESCRIPTION:
Stream0100_DS 5.0
END DESCRIPTION:
XS GIS Cut Line= 3
      2039675.02     13900575.00      2039375.00     13900525.00
      2038947.56     13901229.51
#Sta/Elev= 30
  4696.3 1371.24  4729.3 1366.88  4767.3 1356.57  4845.9 1326.49  4878.8 1327.26
  4906.7 1325.57  4911.8 1326.90  4929.5 1324.23  4972.6 1324.62  4988.3 1322.41
  4988.6 1321.91  4992.3 1322.41  5008.2 1322.94  5014.1 1326.12  5045.0 1334.47
  5087.7 1350.61  5109.0 1355.83  5145.9 1359.27  5234.4 1361.77  5287.0 1366.70
  5357.2 1371.63  5510.3 1372.83  5568.5 1370.17  5589.8 1367.40  5663.4 1364.96
  5669.3 1362.92  5706.1 1359.14  5727.5 1364.47  5789.6 1369.59  5824.5 1372.55
#Mann=5,-1,0
  4696.3    0.12       0  4988.3    0.05       0  4992.3    0.12       0
  5287.0    0.07       0  5789.6   0.035       0
Bank Sta=4988.3,4992.3
Exp/Cntr=0.3,0.1

Type RM Length L Ch R = 1,1882,471,471,471
BEGIN DESCRIPTION:
Stream0100_DS 4.0
END DESCRIPTION:
XS GIS Cut Line= 3
      2039524.98     13899975.01      2039275.00     13900125.00
      2038635.01     13900339.79
#Sta/Elev= 30
  4708.5 1359.31  4731.8 1358.51  4759.0 1354.31  4774.6 1344.39  4780.4 1344.30
  4811.5 1329.18  4817.3 1328.82  4832.9 1320.60  4869.8 1318.28  4965.0 1317.03
  5015.8 1318.06  5042.1 1314.88  5047.3 1316.14  5050.8 1314.61  5051.0 1314.11
  5054.8 1314.61  5063.3 1318.44  5078.9 1319.49  5105.1 1333.42  5110.4 1331.28
  5116.1 1335.78  5136.7 1344.53  5140.2 1343.88  5158.3 1349.29  5205.0 1351.20
  5245.3 1354.95  5455.4 1361.78  5590.7 1365.97  5662.8 1370.74  5675.1 1370.56
#Mann=7,-1,0
  4708.5    0.12       0  5050.8    0.05       0  5054.8    0.12       0
  5140.2    0.07       0  5245.3   0.035       0  5455.4    0.12       0
  5662.8    0.07       0
Bank Sta=5050.8,5054.8
Exp/Cntr=0.3,0.1

Type RM Length L Ch R = 1,1411,452,452,452
BEGIN DESCRIPTION:
Stream0100_DS 3.0
END DESCRIPTION:
XS GIS Cut Line= 3
      2039475.04     13899674.99      2039275.00     13899725.00
      2039124.98     13899825.02
#Sta/Elev= 30
  4788.2 1358.24  4811.4 1357.29  4829.5 1352.77  4839.8 1349.52  4847.5 1345.24
  4852.7 1345.41  4888.7 1328.82  4893.9 1328.45  4901.6 1324.31  4911.9 1320.45
  4930.0 1315.09  4942.9 1313.21  4963.5 1312.45  4976.4 1309.64  4982.1 1309.24
  4982.3 1308.74  4986.1 1309.24  4997.4 1309.46  5007.9 1311.79  5019.5 1312.55
  5044.1 1312.46  5059.0 1312.56  5066.5 1313.80  5080.0 1320.63  5089.0 1327.24
  5095.1 1329.50  5110.1 1333.96  5131.1 1338.74  5146.1 1343.85  5174.7 1348.53
#Mann=5,-1,0
  4788.2    0.12       0  4982.1    0.05       0  4986.1    0.12       0
  5019.5    0.07       0  5044.1   0.035       0
Bank Sta=4982.1,4986.1
Exp/Cntr=0.3,0.1

Type RM Length L Ch R = 1,959,441,441,441
BEGIN DESCRIPTION:
Stream0100_DS 2.0
END DESCRIPTION:
XS GIS Cut Line= 3
      2039425.05     13899274.99      2039175.00     13899325.00
      2038904.10     13899354.54
#Sta/Elev= 30
  4745.0 1349.97  4785.8 1348.98  4816.4 1337.01  4857.2 1324.77  4867.4 1320.99
  4877.6 1318.95  4898.0 1312.15  4908.2 1310.17  4949.0 1309.02  4969.4 1307.22
  4989.8 1308.14  4997.4 1305.48  5002.5 1305.48  5006.6 1301.34  5008.1 1299.82
  5008.3 1299.32  5012.1 1299.82  5020.1 1300.01  5030.2 1303.89  5040.2 1310.25
  5045.7 1316.60  5050.7 1316.59  5060.4 1321.15  5070.4 1324.55  5130.8 1329.63
  5150.4 1333.52  5201.2 1339.93  5211.2 1340.03  5241.4 1343.74  5272.5 1345.61
#Mann=5,-1,0
  4745.0    0.12       0  5006.6    0.07       0  5008.1    0.05       0
  5012.1    0.07       0  5150.4   0.035       0
Bank Sta=5008.1,5012.1
Exp/Cntr=0.3,0.1

Type RM Length L Ch R = 1,518,342,342,342
BEGIN DESCRIPTION:
Stream0100_DS 1.0
END DESCRIPTION:
XS GIS Cut Line= 3
      2039275.04     13898874.99      2039125.00     13898925.00
      2038791.27     13899176.60
#Sta/Elev= 30
  4846.6 1334.29  4849.3 1334.29  4857.2 1332.23  4867.7 1331.04  4899.3 1325.52
  4909.9 1321.03  4931.0 1314.01  4941.5 1312.28  4981.7 1302.97  4981.9 1302.47
  4985.4 1302.47  4985.7 1302.97  4994.2 1303.31  5002.1 1305.88  5007.9 1305.88
  5018.3 1307.27  5064.2 1310.75  5104.9 1312.62  5155.0 1314.09  5168.2 1315.39
  5182.8 1318.94  5185.8 1320.43  5191.1 1323.07  5205.1 1327.97  5218.2 1330.24
  5305.3 1335.77  5332.7 1338.01  5372.3 1339.50  5410.5 1341.39  5422.7 1342.11
#Mann=7,-1,0
  4846.6    0.12       0  4981.7    0.05       0  4985.7    0.12       0
  5064.2    0.07       0  5185.8   0.035       0  5372.3    0.07       0
  5410.5   0.035       0
Bank Sta=4981.7,4985.7
Exp/Cntr=0.3,0.1

Type RM Length L Ch R = 1,176,0,0,0
BEGIN DESCRIPTION:
Stream0100_DS 0.0
END DESCRIPTION:
XS GIS Cut Line= 3
      2039376.08     13898663.48      2038924.80     13898685.12
      2038716.87     13898981.45
#Sta/Elev= 30
  4548.2 1342.61  4679.4 1334.24  4719.5 1328.14  4749.5 1319.96  4839.6 1316.70
  4909.7 1311.94  4979.8 1305.26  4989.8 1303.35  4997.4 1299.11  5007.2 1298.62
  5013.3 1292.27  5018.2 1289.76  5020.0 1287.26  5020.2 1286.76  5024.0 1287.26
  5036.5 1288.85  5042.9 1294.16  5049.0 1302.23  5057.7 1304.03  5063.8 1307.26
  5099.5 1311.40  5125.5 1313.16  5144.0 1316.53  5171.0 1326.67  5200.6 1331.04
  5258.2 1334.38  5307.8 1337.08  5316.5 1336.81  5322.7 1338.44  5362.0 1338.33
#Mann=5,-1,0
  4548.2    0.12       0  5020.0    0.05       0  5024.0    0.12       0
  5125.5    0.07       0  5258.2   0.035       0
Bank Sta=5020,5024
Exp/Cntr=0.3,0.1

Chan Stop Cuts=-1