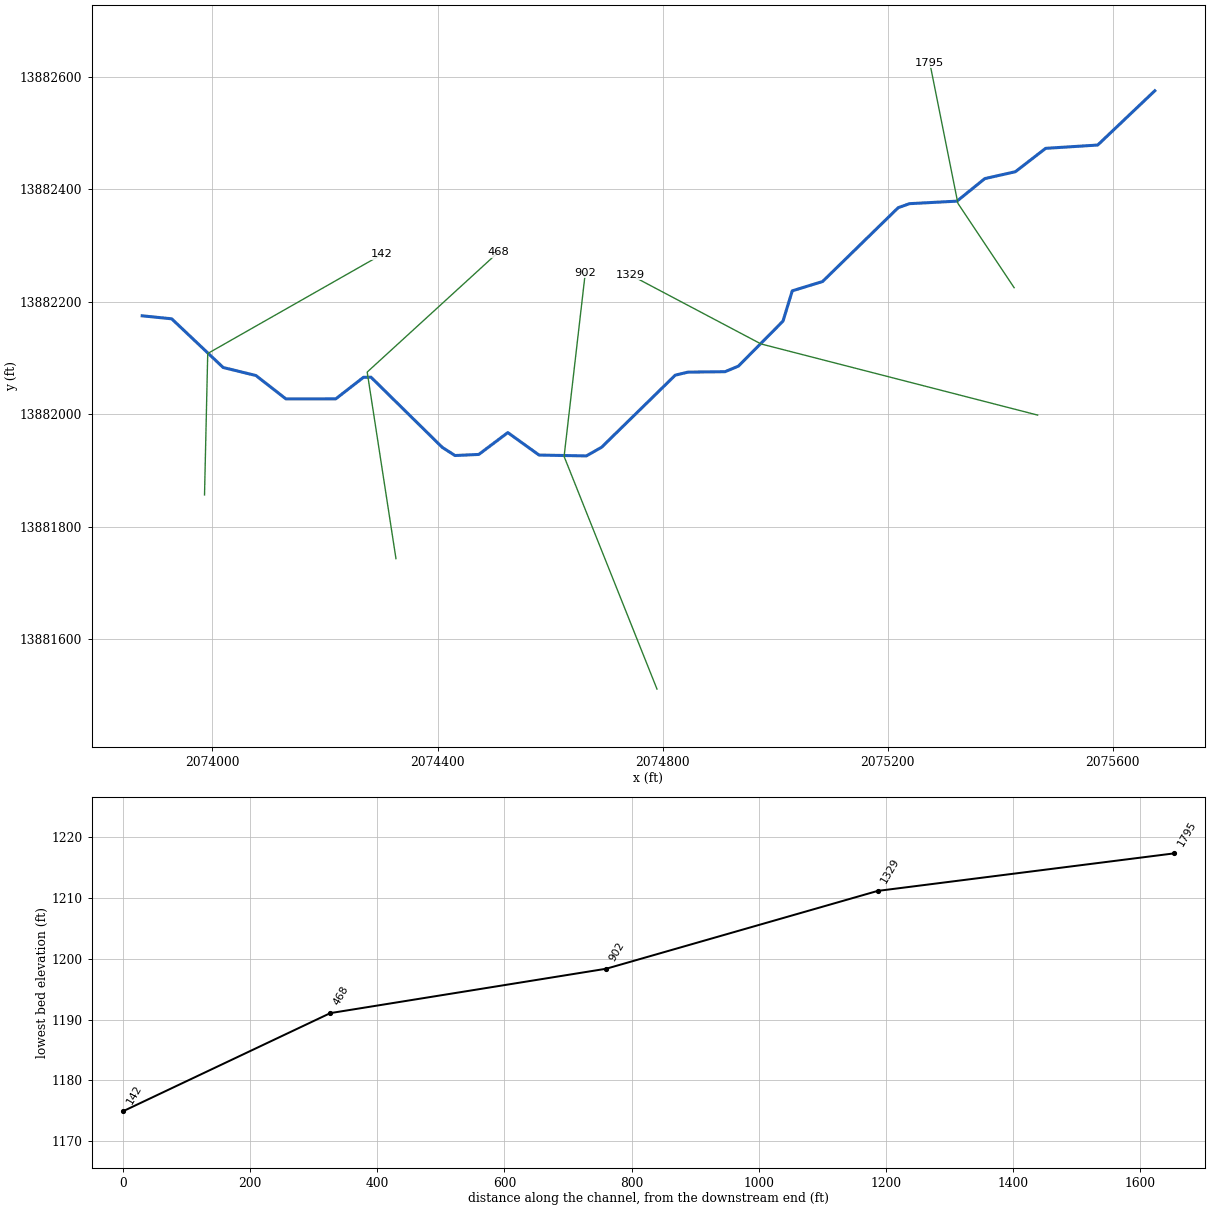
--- Stream0101_DS.prj (project) ---

Proj Title=Stream0101_DS Base Level Engineering
Current Plan=p01
Default Exp/Contr=0.3,0.1
English Units
Geom File=g01
Flow File=f01
Plan File=p01
BEGIN DESCRIPTION:
Stream0101_DS
END DESCRIPTION:

--- Stream0101_DS.p01 (plan) ---

Plan Title=Multiple Run
Short Identifier=Multiple
Geom File=g01
Flow File=f01
Subcritical Flow
K Sum by GR= 0
Std Step Tol= 0.01
Critical Tol= 0.01
Num of Std Step Trials= 20
Max Error Tol= 0.3
Flow Tol Ratio= 0.001
Split Flow NTrial= 30
Split Flow Tol= 0.02
Split Flow Ratio= 0.02
Log Output Level= 0
Friction Slope Method= 1
Unsteady Friction Slope Method= 2
Unsteady Bridges Friction Slope Method= 1
Parabolic Critical Depth
Global Vel Dist=  1 , 1 , 1
Global Log Level= 0
CheckData=True
Encroach Param= -1, 0, 0, 0
BEGIN DESCRIPTION:
Multiple Run
END DESCRIPTION:

--- Stream0101_DS.f01 (steady flow) ---

Flow Title=Multiple
Number of Profiles=7
Profile Names=10-year,25-year,50-year,1pct_min,100-year,1pct_plu,500-year
River Rch & RM= Stream0101_DS,Reach-1,1795
     456     728     974     634    1264    2523    2101
Boundary for River Rch & Prof#=Stream0101_DS,Reach-1,1
Up Type=0
Dn Type=3
Dn Slope=0.005
Boundary for River Rch & Prof#=Stream0101_DS,Reach-1,2
Up Type=0
Dn Type=3
Dn Slope=0.005
Boundary for River Rch & Prof#=Stream0101_DS,Reach-1,3
Up Type=0
Dn Type=3
Dn Slope=0.005
Boundary for River Rch & Prof#=Stream0101_DS,Reach-1,4
Up Type=0
Dn Type=3
Dn Slope=0.005
Boundary for River Rch & Prof#=Stream0101_DS,Reach-1,5
Up Type=0
Dn Type=3
Dn Slope=0.005
Boundary for River Rch & Prof#=Stream0101_DS,Reach-1,6
Up Type=0
Dn Type=3
Dn Slope=0.005
Boundary for River Rch & Prof#=Stream0101_DS,Reach-1,7
Up Type=0
Dn Type=3
Dn Slope=0.005

--- Stream0101_DS.g01 (geometry) ---

Geom Title=Existing Conditions

River Reach=Stream0101_DS,Reach-1
Reach XY= 30
      2075675.00     13882575.00      2075573.52     13882478.56
      2075480.97     13882472.67      2075427.18     13882431.11
      2075372.82     13882418.89      2075323.41     13882378.83
      2075238.91     13882374.33      2075218.83     13882367.14
      2075084.42     13882235.89      2075030.62     13882219.38
      2075014.12     13882165.56      2074934.81     13882085.51
      2074911.09     13882075.67      2074845.06     13882074.87
      2074822.57     13882069.48      2074691.75     13881941.40
      2074664.52     13881925.94      2074580.49     13881927.48
      2074524.99     13881967.40      2074473.35     13881928.57
      2074431.05     13881926.66      2074408.33     13881941.23
      2074281.74     13882065.87      2074268.47     13882065.71
      2074219.11     13882027.37      2074130.56     13882027.26
      2074077.17     13882068.86      2074018.94     13882083.14
      2073927.51     13882169.67      2073875.00     13882175.00

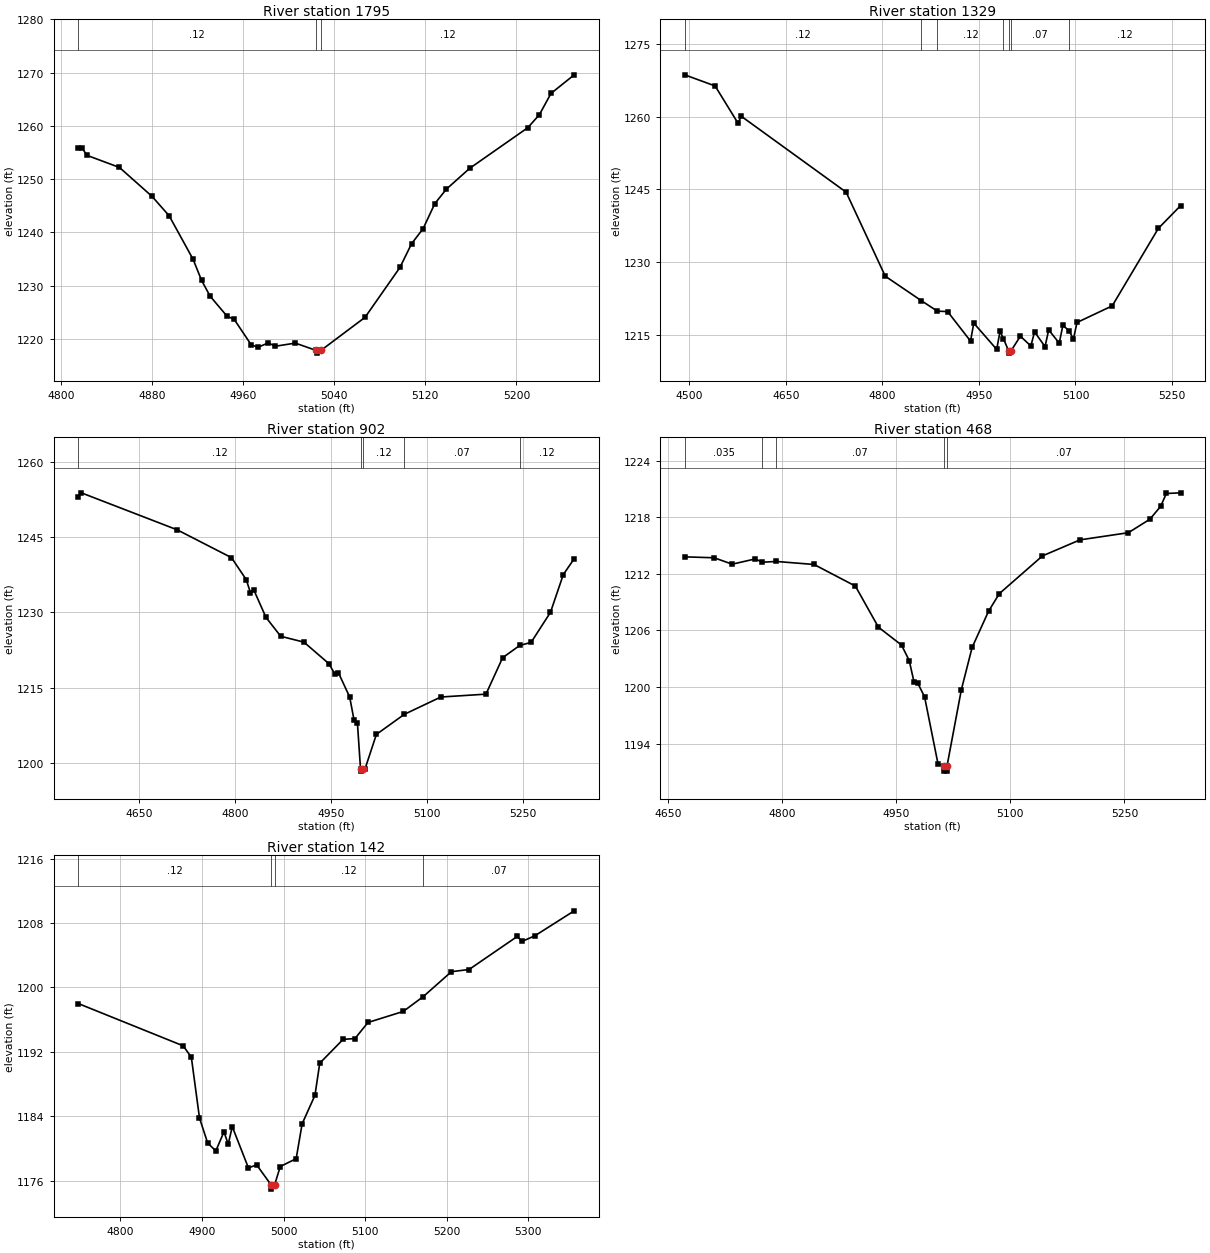
Type RM Length L Ch R = 1,1795,466,466,466
BEGIN DESCRIPTION:
Stream0101_DS 4.0
END DESCRIPTION:
XS GIS Cut Line= 3
      2075425.02     13882224.97      2075325.00     13882375.00
      2075274.99     13882625.03
#Sta/Elev= 30
  4815.4 1255.91  4818.4 1255.91  4823.0 1254.46  4851.5 1252.19  4880.0 1246.78
  4895.1 1243.13  4916.1 1234.97  4923.6 1230.99  4931.1 1228.03  4946.1 1224.24
  4952.1 1223.72  4967.2 1218.90  4973.2 1218.45  4982.2 1219.28  4988.2 1218.64
  5005.9 1219.23  5024.3 1217.85  5024.6 1217.35  5028.3 1217.85  5067.1 1224.07
  5097.7 1233.42  5107.9 1237.87  5118.1 1240.72  5128.3 1245.40  5138.5 1248.12
  5158.9 1252.02  5209.9 1259.64  5220.1 1262.08  5230.3 1266.08  5250.7 1269.57
#Mann=3,-1,0
  4815.4    0.12       0  5024.3    0.05       0  5028.3    0.12       0
Bank Sta=5024.3,5028.3
Exp/Cntr=0.3,0.1

Type RM Length L Ch R = 1,1329,427,427,427
BEGIN DESCRIPTION:
Stream0101_DS 3.0
END DESCRIPTION:
XS GIS Cut Line= 3
      2075466.73     13881998.53      2074975.00     13882125.00
      2074742.59     13882247.81
#Sta/Elev= 30
  4492.8 1268.65  4540.0 1266.35  4575.5 1258.68  4580.7 1260.09  4743.6 1244.42
  4804.4 1227.07  4860.7 1221.99  4885.4 1219.85  4901.3 1219.76  4936.9 1213.67
  4942.0 1217.37  4977.6 1211.95  4982.8 1215.70  4988.0 1214.18  4996.0 1211.68
  4996.2 1211.18  5000.0 1211.68  5014.4 1214.68  5030.7 1212.65  5036.4 1215.57
  5052.7 1212.52  5058.4 1215.98  5074.8 1213.23  5080.4 1216.91  5089.9 1215.82
  5096.8 1214.10  5102.4 1217.51  5157.1 1220.94  5228.8 1236.94  5263.4 1241.64
#Mann=7,-1,0
  4492.8    0.12       0  4860.7    0.07       0  4885.4    0.12       0
  4988.0    0.07       0  4996.0    0.05       0  5000.0    0.07       0
  5089.9    0.12       0
Bank Sta=4996,5000
Exp/Cntr=0.3,0.1

Type RM Length L Ch R = 1,902,434,434,434
BEGIN DESCRIPTION:
Stream0101_DS 2.0
END DESCRIPTION:
XS GIS Cut Line= 3
      2074790.13     13881511.50      2074625.00     13881925.00
      2074662.73     13882251.88
#Sta/Elev= 30
  4555.6 1253.03  4560.3 1253.77  4710.1 1246.40  4794.7 1240.87  4817.8 1236.49
  4824.4 1233.87  4829.8 1234.38  4848.6 1228.98  4871.6 1225.22  4907.9 1224.05
  4947.0 1219.75  4956.4 1217.64  4961.8 1217.94  4979.3 1213.13  4986.0 1208.61
  4991.4 1207.92  4996.2 1198.88  4996.4 1198.38  5000.2 1198.88  5003.4 1198.88
  5021.0 1205.69  5064.7 1209.69  5121.6 1213.13  5192.1 1213.70  5218.1 1220.95
  5244.8 1223.39  5262.6 1224.01  5292.8 1229.98  5312.9 1237.51  5329.9 1240.66
#Mann=5,-1,0
  4555.6    0.12       0  4996.2    0.05       0  5000.2    0.12       0
  5064.7    0.07       0  5244.8    0.12       0
Bank Sta=4996.2,5000.2
Exp/Cntr=0.3,0.1

Type RM Length L Ch R = 1,468,326,326,326
BEGIN DESCRIPTION:
Stream0101_DS 1.0
END DESCRIPTION:
XS GIS Cut Line= 3
      2074326.13     13881743.36      2074275.00     13882075.00
      2074508.45     13882288.47
#Sta/Elev= 30
  4672.0 1213.81  4710.7 1213.71  4734.4 1213.03  4764.7 1213.59  4773.9 1213.24
  4792.4 1213.32  4842.0 1213.00  4896.3 1210.71  4926.6 1206.35  4957.0 1204.45
  4967.1 1202.81  4973.4 1200.54  4978.5 1200.38  4987.3 1198.96  5005.0 1191.83
  5012.7 1191.58  5012.9 1191.08  5016.4 1191.08  5016.7 1191.58  5035.6 1199.70
  5049.8 1204.20  5071.4 1208.04  5085.6 1209.91  5142.3 1213.91  5191.6 1215.61
  5255.2 1216.37  5283.5 1217.80  5297.7 1219.17  5305.1 1220.53  5323.9 1220.60
#Mann=5,-1,0
  4672.0   0.035       0  4773.9    0.12       0  4792.4    0.07       0
  5012.7    0.05       0  5016.7    0.07       0
Bank Sta=5012.7,5016.7
Exp/Cntr=0.3,0.1

Type RM Length L Ch R = 1,142,0,0,0
BEGIN DESCRIPTION:
Stream0101_DS 0.0
END DESCRIPTION:
XS GIS Cut Line= 3
      2073985.83     13881856.57      2073991.53     13882108.00
      2074301.24     13882284.16
#Sta/Elev= 30
  4748.5 1197.99  4877.0 1192.74  4887.0 1191.33  4897.0 1183.78  4907.0 1180.67
  4917.0 1179.69  4927.0 1182.05  4932.2 1180.53  4937.2 1182.70  4957.0 1177.57
  4967.0 1177.96  4985.0 1175.44  4985.2 1174.94  4989.0 1175.44  4996.0 1177.75
  5015.5 1178.72  5022.8 1183.05  5038.5 1186.59  5044.4 1190.58  5073.0 1193.54
  5087.6 1193.65  5103.5 1195.64  5146.7 1197.01  5171.1 1198.84  5205.8 1201.95
  5227.4 1202.22  5286.5 1206.33  5292.3 1205.71  5308.1 1206.41  5356.3 1209.51
#Mann=4,-1,0
  4748.5    0.12       0  4985.0    0.05       0  4989.0    0.12       0
  5171.1    0.07       0
Bank Sta=4985,4989
Exp/Cntr=0.3,0.1

Chan Stop Cuts=-1