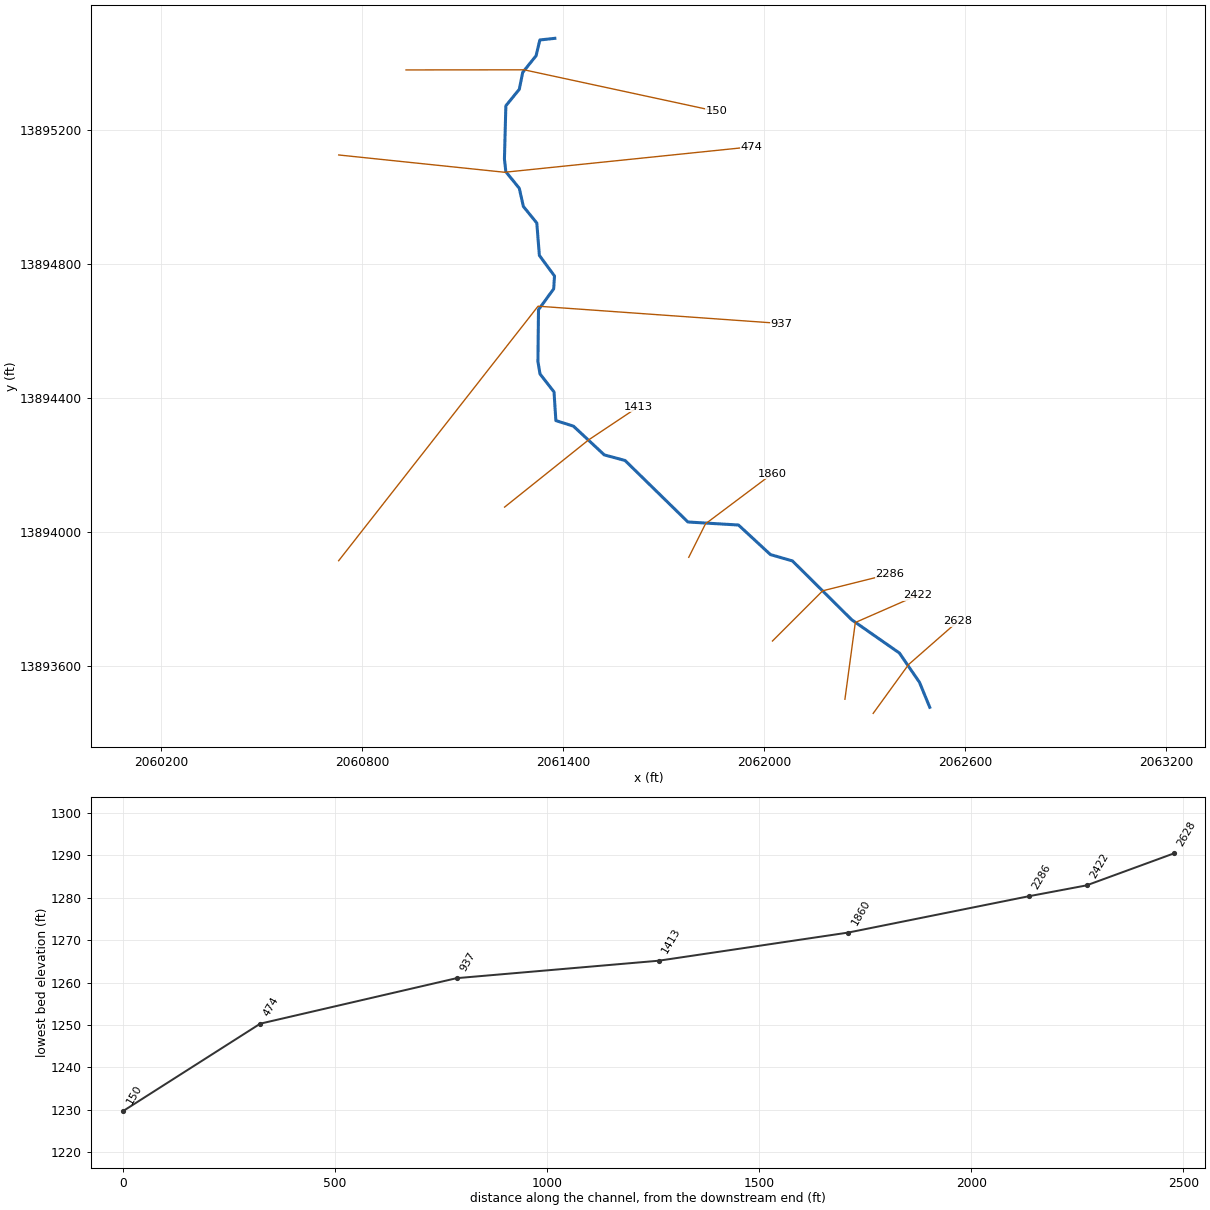
--- Stream0102_DS.prj (project) ---

Proj Title=Stream0102_DS Base Level Engineering
Current Plan=p01
Default Exp/Contr=0.3,0.1
English Units
Geom File=g01
Flow File=f01
Plan File=p01
BEGIN DESCRIPTION:
Stream0102_DS
END DESCRIPTION:

--- Stream0102_DS.p01 (plan) ---

Plan Title=Multiple Run
Short Identifier=Multiple
Geom File=g01
Flow File=f01
Subcritical Flow
K Sum by GR= 0
Std Step Tol= 0.01
Critical Tol= 0.01
Num of Std Step Trials= 20
Max Error Tol= 0.3
Flow Tol Ratio= 0.001
Split Flow NTrial= 30
Split Flow Tol= 0.02
Split Flow Ratio= 0.02
Log Output Level= 0
Friction Slope Method= 1
Unsteady Friction Slope Method= 2
Unsteady Bridges Friction Slope Method= 1
Parabolic Critical Depth
Global Vel Dist=  1 , 1 , 1
Global Log Level= 0
CheckData=True
Encroach Param= -1, 0, 0, 0
BEGIN DESCRIPTION:
Multiple Run
END DESCRIPTION:

--- Stream0102_DS.f01 (steady flow) ---

Flow Title=Multiple
Number of Profiles=7
Profile Names=10-year,25-year,50-year,1pct_min,100-year,1pct_plu,500-year
River Rch & RM= Stream0102_DS,Reach-1,2628
     200     299     383     239     478     953     730
River Rch & RM= Stream0102_DS,Reach-1,1860
     493     791    1060     691    1379    2751    2301
Boundary for River Rch & Prof#=Stream0102_DS,Reach-1,1
Up Type=0
Dn Type=3
Dn Slope=0.005
Boundary for River Rch & Prof#=Stream0102_DS,Reach-1,2
Up Type=0
Dn Type=3
Dn Slope=0.005
Boundary for River Rch & Prof#=Stream0102_DS,Reach-1,3
Up Type=0
Dn Type=3
Dn Slope=0.005
Boundary for River Rch & Prof#=Stream0102_DS,Reach-1,4
Up Type=0
Dn Type=3
Dn Slope=0.005
Boundary for River Rch & Prof#=Stream0102_DS,Reach-1,5
Up Type=0
Dn Type=3
Dn Slope=0.005
Boundary for River Rch & Prof#=Stream0102_DS,Reach-1,6
Up Type=0
Dn Type=3
Dn Slope=0.005
Boundary for River Rch & Prof#=Stream0102_DS,Reach-1,7
Up Type=0
Dn Type=3
Dn Slope=0.005

--- Stream0102_DS.g01 (geometry) ---

Geom Title=Existing Conditions

River Reach=Stream0102_DS,Reach-1
Reach XY= 30
      2062494.82     13893477.01      2062464.15     13893551.64
      2062404.16     13893639.14      2062261.73     13893738.48
      2062084.68     13893914.22      2062018.96     13893933.18
      2061923.53     13894021.45      2061772.55     13894030.47
      2061584.68     13894214.22      2061522.72     13894230.87
      2061430.70     13894316.68      2061378.16     13894333.34
      2061372.60     13894418.94      2061330.74     13894472.66
      2061324.57     13894509.82      2061326.24     13894664.50
      2061371.63     13894726.74      2061374.07     13894765.15
      2061328.89     13894826.58      2061321.17     13894923.42
      2061281.11     13894972.82      2061268.88     13895027.18
      2061228.75     13895076.55      2061224.54     13895114.81
      2061228.75     13895273.45      2061268.88     13895322.82
      2061279.13     13895373.31      2061319.00     13895422.99
      2061330.28     13895470.10      2061375.00     13895475.00

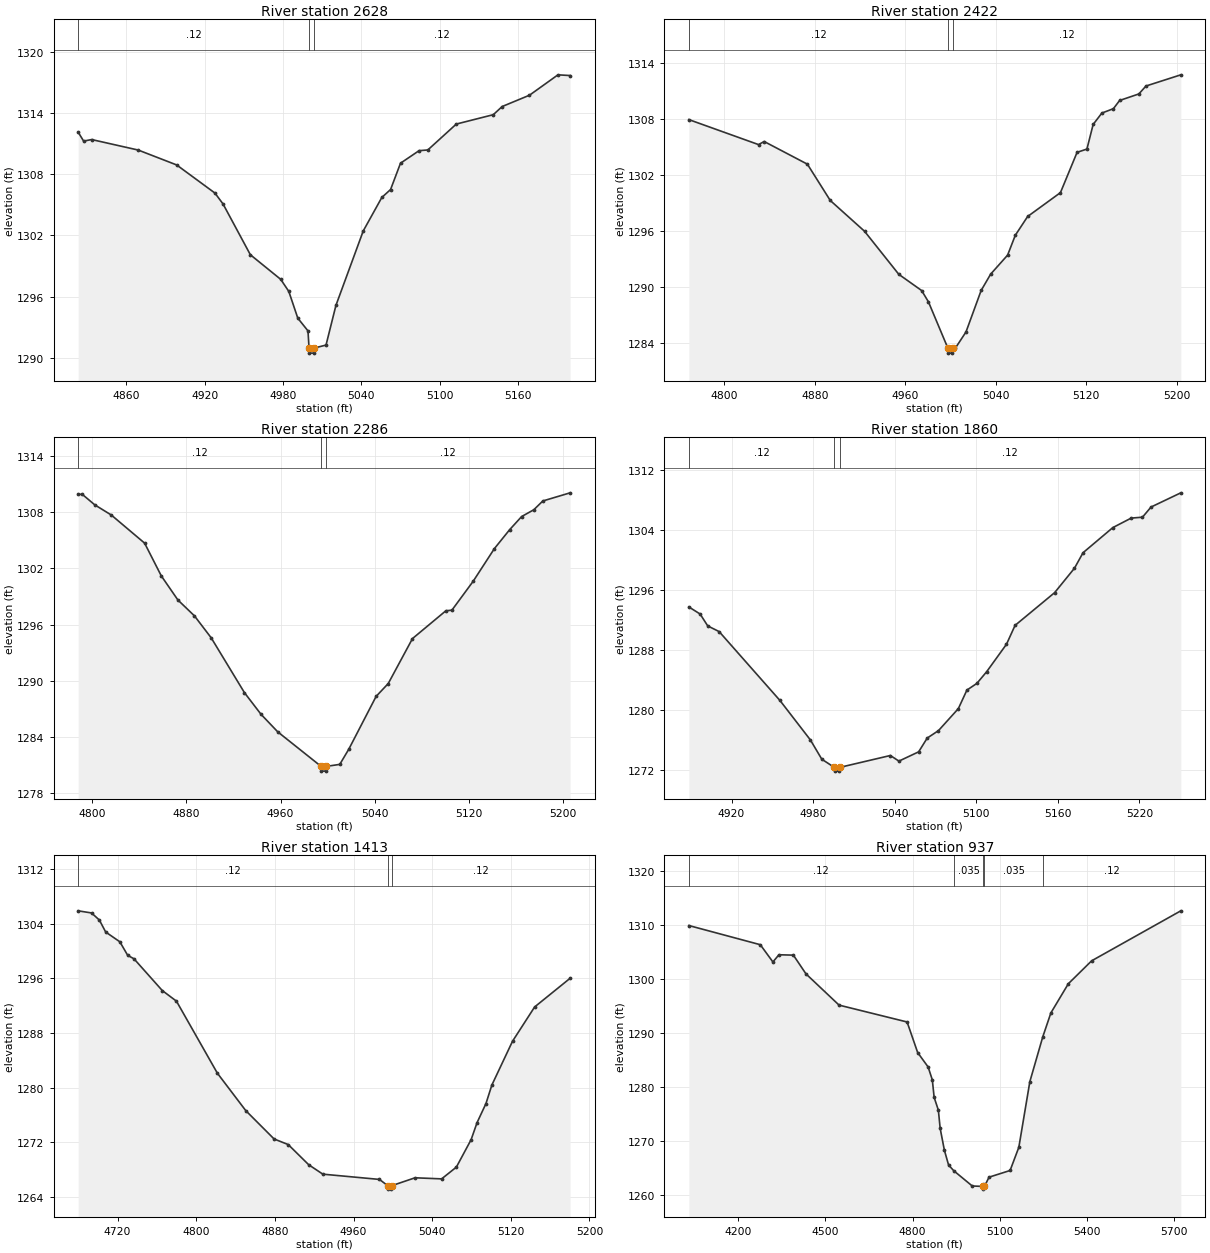
Type RM Length L Ch R = 1,2628,206,206,206
BEGIN DESCRIPTION:
Stream0102_DS 7.0
END DESCRIPTION:
XS GIS Cut Line= 3
      2062325.85     13893458.90      2062431.41     13893604.59
      2062579.24     13893734.17
#Sta/Elev= 30
  4823.2 1312.14  4827.4 1311.26  4833.6 1311.41  4869.2 1310.38  4898.6 1308.92
  4927.9 1306.16  4934.1 1305.09  4955.0 1300.11  4978.2 1297.70  4984.4 1296.52
  4991.3 1293.89  4999.1 1292.64  4999.9 1290.96  5000.2 1290.46  5003.7 1290.46
  5003.9 1290.96  5012.9 1291.25  5020.5 1295.15  5041.4 1302.45  5055.6 1305.73
  5062.3 1306.51  5069.9 1309.09  5084.1 1310.32  5090.8 1310.39  5112.6 1312.93
  5140.9 1313.85  5147.7 1314.65  5168.6 1315.76  5190.4 1317.76  5199.7 1317.69
#Mann=3,-1,0
  4823.2    0.12       0  4999.9    0.05       0  5003.9    0.12       0
Bank Sta=4999.9,5003.9
Exp/Cntr=0.3,0.1

Type RM Length L Ch R = 1,2422,136,136,136
BEGIN DESCRIPTION:
Stream0102_DS 6.0
END DESCRIPTION:
XS GIS Cut Line= 3
      2062241.45     13893501.10      2062272.48     13893730.31
      2062458.98     13893811.99
#Sta/Elev= 30
  4768.7 1307.96  4830.3 1305.28  4835.3 1305.61  4873.5 1303.18  4893.7 1299.29
  4924.0 1295.99  4954.3 1291.37  4974.5 1289.63  4980.5 1288.42  4997.8 1283.42
  4998.1 1282.92  5001.6 1282.92  5001.8 1283.42  5004.1 1283.42  5013.7 1285.19
  5027.1 1289.64  5035.5 1291.39  5050.5 1293.43  5057.3 1295.56  5068.2 1297.57
  5097.2 1300.13  5111.9 1304.45  5120.6 1304.80  5126.1 1307.44  5133.8 1308.66
  5144.0 1309.13  5149.5 1310.01  5166.5 1310.71  5172.8 1311.56  5203.6 1312.76
#Mann=3,-1,0
  4768.7    0.12       0  4997.8    0.05       0  5001.8    0.12       0
Bank Sta=4997.8,5001.8
Exp/Cntr=0.3,0.1

Type RM Length L Ch R = 1,2286,426,426,426
BEGIN DESCRIPTION:
Stream0102_DS 5.0
END DESCRIPTION:
XS GIS Cut Line= 3
      2062025.03     13893675.03      2062175.00     13893825.00
      2062374.96     13893874.99
#Sta/Elev= 30
  4787.9 1309.91  4791.4 1309.91  4802.0 1308.79  4816.1 1307.70  4844.4 1304.70
  4858.6 1301.20  4872.7 1298.63  4886.8 1296.93  4901.0 1294.59  4929.3 1288.73
  4943.4 1286.42  4957.6 1284.55  4994.5 1280.86  4994.7 1280.36  4998.2 1280.36
  4998.5 1280.86  5010.3 1281.08  5018.0 1282.71  5041.2 1288.34  5051.5 1289.71
  5072.1 1294.51  5100.5 1297.48  5105.6 1297.54  5123.7 1300.63  5141.7 1304.11
  5154.6 1306.12  5164.9 1307.54  5175.2 1308.26  5182.9 1309.20  5206.1 1310.07
#Mann=3,-1,0
  4787.9    0.12       0  4994.5    0.05       0  4998.5    0.12       0
Bank Sta=4994.5,4998.5
Exp/Cntr=0.3,0.1

Type RM Length L Ch R = 1,1860,447,447,447
BEGIN DESCRIPTION:
Stream0102_DS 4.0
END DESCRIPTION:
XS GIS Cut Line= 3
      2061775.02     13893925.04      2061825.00     13894025.00
      2062025.04     13894175.03
#Sta/Elev= 30
  4888.6 1293.75  4896.9 1292.80  4902.5 1291.21  4910.9 1290.45  4955.6 1281.24
  4978.0 1275.96  4986.4 1273.38  4995.6 1272.29  4995.8 1271.79  4999.3 1271.79
  4999.6 1272.29  5036.8 1273.88  5043.1 1273.13  5057.6 1274.37  5063.9 1276.21
  5072.2 1277.21  5086.8 1280.15  5093.1 1282.63  5100.4 1283.52  5107.6 1285.08
  5122.2 1288.76  5128.5 1291.28  5157.6 1295.66  5172.2 1298.93  5178.5 1301.00
  5200.4 1304.36  5213.9 1305.63  5222.2 1305.75  5228.5 1307.11  5250.4 1309.01
#Mann=3,-1,0
  4888.6    0.12       0  4995.6    0.05       0  4999.6    0.12       0
Bank Sta=4995.6,4999.6
Exp/Cntr=0.3,0.1

Type RM Length L Ch R = 1,1413,476,476,476
BEGIN DESCRIPTION:
Stream0102_DS 3.0
END DESCRIPTION:
XS GIS Cut Line= 3
      2061225.02     13894075.02      2061475.00     13894275.00
      2061625.00     13894375.00
#Sta/Elev= 30
  4679.9 1305.88  4693.5 1305.57  4701.5 1304.53  4707.9 1302.78  4722.3 1301.35
  4730.3 1299.37  4736.7 1298.86  4765.5 1294.21  4779.9 1292.66  4821.5 1282.12
  4850.4 1276.64  4879.2 1272.49  4893.6 1271.67  4914.4 1268.72  4928.8 1267.34
  4986.4 1266.57  4994.8 1265.65  4995.1 1265.15  4998.6 1265.15  4998.8 1265.65
  5022.6 1266.81  5049.6 1266.65  5064.6 1268.37  5079.6 1272.39  5085.7 1274.90
  5094.7 1277.67  5100.7 1280.38  5121.7 1286.79  5144.2 1291.81  5180.3 1296.01
#Mann=3,-1,0
  4679.9    0.12       0  4994.8    0.05       0  4998.8    0.12       0
Bank Sta=4994.8,4998.8
Exp/Cntr=0.3,0.1

Type RM Length L Ch R = 1,937,463,463,463
BEGIN DESCRIPTION:
Stream0102_DS 2.0
END DESCRIPTION:
XS GIS Cut Line= 3
      2060729.47     13893914.85      2061325.00     13894675.00
      2062051.21     13894623.29
#Sta/Elev= 30
  4029.9 1309.82  4275.9 1306.27  4319.3 1303.08  4340.1 1304.41  4389.8 1304.34
  4433.2 1300.87  4547.1 1295.09  4781.3 1291.97  4817.7 1286.31  4853.6 1283.65
  4868.1 1281.27  4874.4 1278.02  4888.9 1275.66  4895.2 1272.26  4909.7 1268.23
  4924.1 1265.50  4942.2 1264.43  5005.6 1261.62  5043.7 1261.54  5043.9 1261.04
  5047.7 1261.54  5063.3 1263.25  5135.9 1264.49  5166.0 1268.79  5203.9 1280.94
  5248.2 1289.19  5276.3 1293.65  5336.4 1299.05  5416.6 1303.29  5723.6 1312.54
#Mann=5,-1,0
  4029.9    0.12       0  4942.2   0.035       0  5043.7   0.035       0
  5047.7   0.035       0  5248.2    0.12       0
Bank Sta=5043.7,5047.7
Exp/Cntr=0.3,0.1

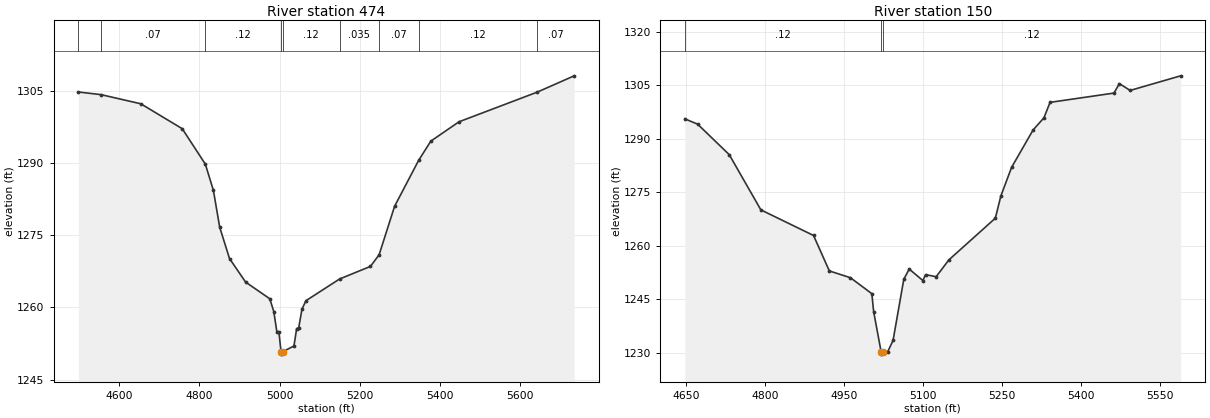
Type RM Length L Ch R = 1,474,324,324,324
BEGIN DESCRIPTION:
Stream0102_DS 1.0
END DESCRIPTION:
XS GIS Cut Line= 3
      2060729.52     13895126.67      2061225.00     13895075.00
      2061961.03     13895150.87
#Sta/Elev= 30
  4497.5 1304.78  4554.3 1304.23  4653.5 1302.33  4757.0 1297.15  4814.7 1289.78
  4834.8 1284.32  4850.5 1276.68  4875.0 1270.17  4915.2 1265.28  4975.6 1261.81
  4985.6 1259.15  4993.2 1254.98  4998.2 1254.98  5003.7 1250.81  5004.0 1250.31
  5007.7 1250.81  5035.9 1252.00  5042.7 1255.63  5047.7 1255.72  5056.0 1259.68
  5066.0 1261.42  5149.8 1265.92  5226.9 1268.54  5248.6 1270.96  5287.2 1281.03
  5347.3 1290.58  5377.7 1294.57  5448.1 1298.59  5643.3 1304.75  5735.6 1308.14
#Mann=9,-1,0
  4497.5    0.12       0  4554.3    0.07       0  4814.7    0.12       0
  5003.7    0.05       0  5007.7    0.12       0  5149.8   0.035       0
  5248.6    0.07       0  5347.3    0.12       0  5643.3    0.07       0
Bank Sta=5003.7,5007.7
Exp/Cntr=0.3,0.1

Type RM Length L Ch R = 1,150,0,0,0
BEGIN DESCRIPTION:
Stream0102_DS 0.0
END DESCRIPTION:
XS GIS Cut Line= 3
      2060930.59     13895380.64      2061283.39     13895380.98
      2061858.66     13895256.94
#Sta/Elev= 30
  4647.2 1295.56  4671.6 1294.06  4731.6 1285.52  4791.6 1270.06  4891.6 1262.89
  4921.6 1252.96  4961.6 1251.06  5002.3 1246.59  5005.7 1241.59  5020.1 1230.16
  5020.4 1229.66  5024.1 1230.16  5032.3 1230.29  5042.6 1233.51  5063.0 1250.66
  5073.3 1253.48  5099.2 1250.26  5104.3 1251.92  5124.4 1251.34  5148.5 1256.05
  5236.8 1267.74  5247.2 1273.94  5267.6 1281.97  5308.5 1292.46  5329.0 1295.83
  5340.6 1300.17  5462.0 1302.77  5472.2 1305.42  5492.7 1303.51  5588.5 1307.60
#Mann=3,-1,0
  4647.2    0.12       0  5020.1    0.05       0  5024.1    0.12       0
Bank Sta=5020.1,5024.1
Exp/Cntr=0.3,0.1

Chan Stop Cuts=-1