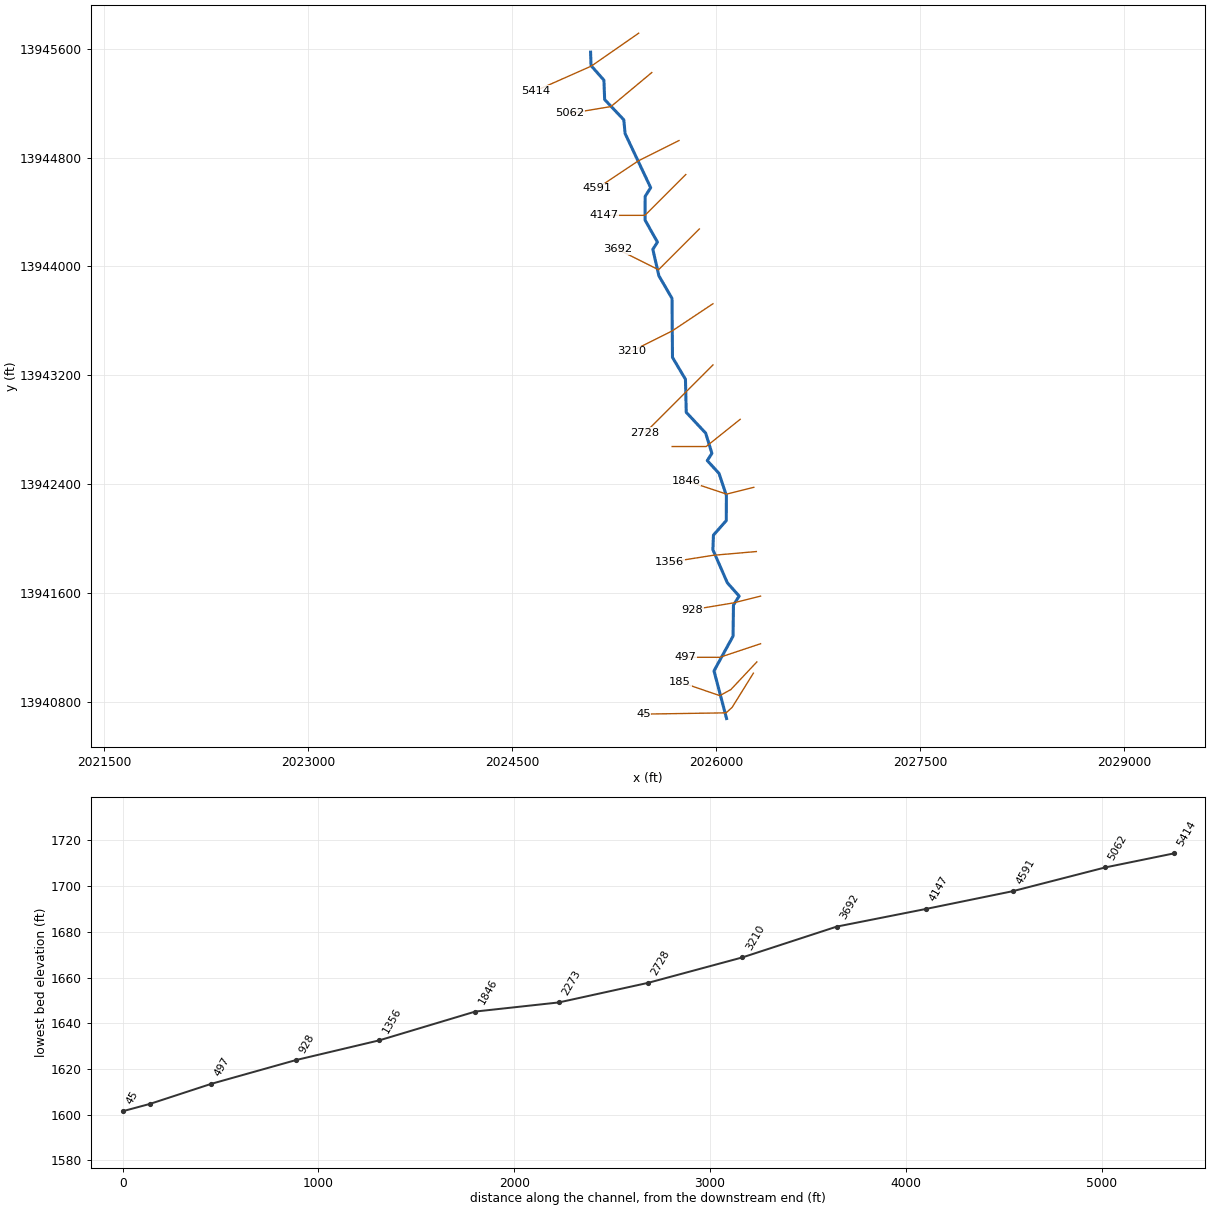
--- Stream0103_DS.prj (project) ---

Proj Title=Stream0103_DS Base Level Engineering
Current Plan=p01
Default Exp/Contr=0.3,0.1
English Units
Geom File=g01
Flow File=f01
Plan File=p01
BEGIN DESCRIPTION:
Stream0103_DS
END DESCRIPTION:

--- Stream0103_DS.p01 (plan) ---

Plan Title=Multiple Run
Short Identifier=Multiple
Geom File=g01
Flow File=f01
Subcritical Flow
K Sum by GR= 0
Std Step Tol= 0.01
Critical Tol= 0.01
Num of Std Step Trials= 20
Max Error Tol= 0.3
Flow Tol Ratio= 0.001
Split Flow NTrial= 30
Split Flow Tol= 0.02
Split Flow Ratio= 0.02
Log Output Level= 0
Friction Slope Method= 1
Unsteady Friction Slope Method= 2
Unsteady Bridges Friction Slope Method= 1
Parabolic Critical Depth
Global Vel Dist=  1 , 1 , 1
Global Log Level= 0
CheckData=True
Encroach Param= -1, 0, 0, 0
BEGIN DESCRIPTION:
Multiple Run
END DESCRIPTION:

--- Stream0103_DS.f01 (steady flow) ---

Flow Title=Multiple
Number of Profiles=7
Profile Names=10-year,25-year,50-year,1pct_min,100-year,1pct_plu,500-year
River Rch & RM= Stream0103_DS,Reach-1,5414
     531     887    1222     820    1635    3263    2902
River Rch & RM= Stream0103_DS,Reach-1,5062
     619    1037    1431     961    1918    3826    3409
River Rch & RM= Stream0103_DS,Reach-1,2728
     866    1478    2065    1402    2798    5582    5090
Boundary for River Rch & Prof#=Stream0103_DS,Reach-1,1
Up Type=0
Dn Type=3
Dn Slope=0.005
Boundary for River Rch & Prof#=Stream0103_DS,Reach-1,2
Up Type=0
Dn Type=3
Dn Slope=0.005
Boundary for River Rch & Prof#=Stream0103_DS,Reach-1,3
Up Type=0
Dn Type=3
Dn Slope=0.005
Boundary for River Rch & Prof#=Stream0103_DS,Reach-1,4
Up Type=0
Dn Type=3
Dn Slope=0.005
Boundary for River Rch & Prof#=Stream0103_DS,Reach-1,5
Up Type=0
Dn Type=3
Dn Slope=0.005
Boundary for River Rch & Prof#=Stream0103_DS,Reach-1,6
Up Type=0
Dn Type=3
Dn Slope=0.005
Boundary for River Rch & Prof#=Stream0103_DS,Reach-1,7
Up Type=0
Dn Type=3
Dn Slope=0.005

--- Stream0103_DS.g01 (geometry) ---

Geom Title=Existing Conditions

River Reach=Stream0103_DS,Reach-1
Reach XY= 30
      2025075.00     13945575.00      2025078.39     13945476.41
      2025172.93     13945369.14      2025178.54     13945226.47
      2025319.48     13945077.43      2025328.83     13944976.59
      2025516.96     13944578.32      2025476.38     13944514.56
      2025475.51     13944340.21      2025566.76     13944178.23
      2025532.80     13944125.10      2025577.36     13943930.52
      2025673.80     13943764.50      2025677.31     13943330.50
      2025772.65     13943169.48      2025778.54     13942926.46
      2025921.39     13942773.50      2025967.20     13942624.90
      2025933.01     13942571.67      2026019.45     13942477.43
      2026073.78     13942314.50      2026072.82     13942130.45
      2025978.54     13942023.53      2025974.49     13941915.74
      2026080.86     13941672.70      2026167.67     13941575.10
      2026125.66     13941509.84      2026122.76     13941280.93
      2025982.53     13941025.01      2026075.00     13940675.00

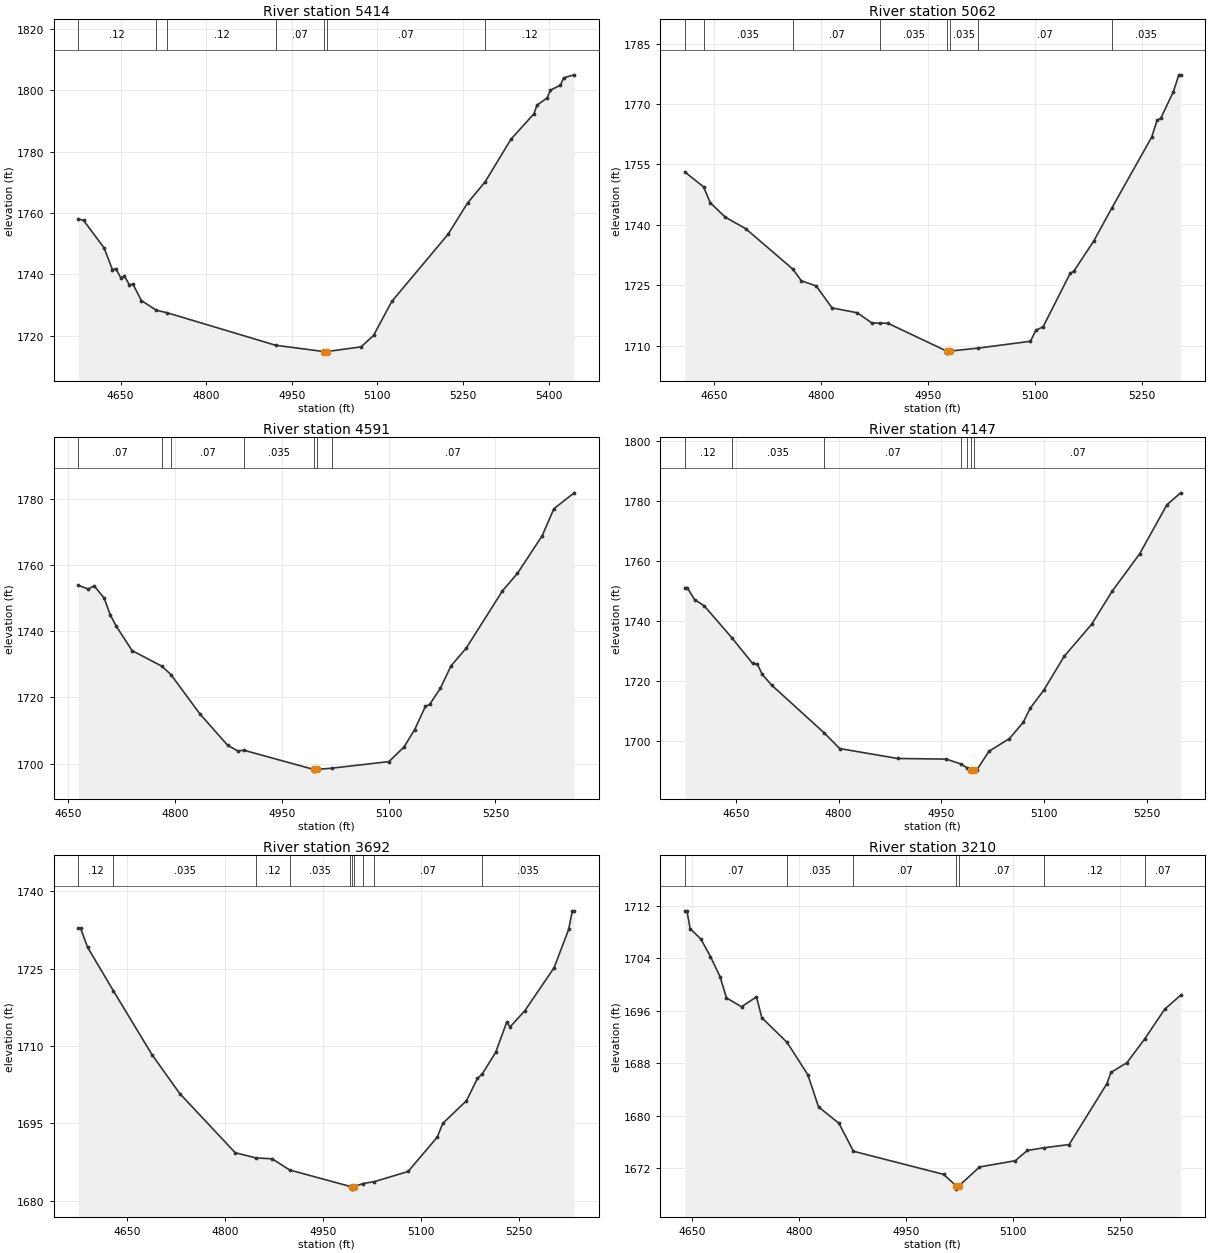
Type RM Length L Ch R = 1,5414,352,352,352
BEGIN DESCRIPTION:
Stream0103_DS 12.0
END DESCRIPTION:
XS GIS Cut Line= 3
      2025428.70     13945714.42      2025080.36     13945472.51
      2024673.75     13945292.20
#Sta/Elev= 30
  4575.9 1758.10  4585.1 1757.60  4620.9 1748.66  4635.7 1741.53  4641.8 1741.81
  4650.6 1738.79  4656.7 1739.44  4665.4 1736.55  4671.5 1736.83  4686.4 1731.44
  4712.5 1728.28  4731.7 1727.45  4921.6 1716.85  5006.8 1714.78  5007.0 1714.28
  5010.8 1714.78  5071.5 1716.33  5093.4 1720.10  5125.1 1731.13  5223.7 1753.04
  5257.9 1763.26  5288.9 1770.21  5334.0 1784.08  5374.3 1792.40  5379.7 1795.24
  5397.5 1797.55  5403.0 1800.09  5420.8 1801.73  5426.3 1804.12  5444.8 1805.11
#Mann=7,-1,0
  4575.9    0.12       0  4712.5   0.035       0  4731.7    0.12       0
  4921.6    0.07       0  5006.8    0.05       0  5010.8    0.07       0
  5288.9    0.12       0
Bank Sta=5006.8,5010.8
Exp/Cntr=0.3,0.1

Type RM Length L Ch R = 1,5062,471,471,471
BEGIN DESCRIPTION:
Stream0103_DS 11.0
END DESCRIPTION:
XS GIS Cut Line= 3
      2025524.96     13945424.97      2025225.00     13945175.00
      2024925.00     13945125.00
#Sta/Elev= 30
  4609.2 1753.14  4635.5 1749.43  4644.9 1745.49  4665.8 1741.92  4694.4 1739.06
  4760.6 1728.99  4772.5 1726.10  4793.3 1724.82  4815.5 1719.35  4850.6 1718.16
  4871.4 1715.61  4883.2 1715.57  4893.6 1715.55  4976.2 1708.62  4976.4 1708.12
  4980.2 1708.62  5019.9 1709.36  5093.4 1711.07  5101.0 1713.79  5111.2 1714.69
  5149.2 1727.97  5154.3 1728.52  5182.1 1735.97  5207.3 1744.14  5263.3 1761.80
  5270.9 1766.03  5275.9 1766.45  5293.7 1773.10  5301.3 1777.27  5303.8 1777.27
#Mann=8,-1,0
  4609.2    0.07       0  4635.5   0.035       0  4760.6    0.07       0
  4883.2   0.035       0  4976.2   0.035       0  4980.2   0.035       0
  5019.9    0.07       0  5207.3   0.035       0
Bank Sta=4976.2,4980.2
Exp/Cntr=0.3,0.1

Type RM Length L Ch R = 1,4591,444,444,444
BEGIN DESCRIPTION:
Stream0103_DS 10.0
END DESCRIPTION:
XS GIS Cut Line= 3
      2025724.97     13944924.99      2025425.00     13944775.00
      2025125.03     13944575.02
#Sta/Elev= 30
  4664.6 1753.84  4678.5 1752.74  4686.9 1753.70  4700.9 1749.98  4709.3 1744.98
  4717.7 1741.55  4740.0 1734.16  4781.9 1729.43  4794.5 1726.93  4835.1 1715.07
  4874.2 1705.56  4888.2 1703.88  4897.3 1704.05  4995.2 1698.26  4995.4 1697.76
  4999.2 1698.26  5021.1 1698.67  5100.6 1700.64  5121.7 1705.05  5136.7 1710.31
  5151.7 1717.30  5157.7 1717.89  5172.7 1722.76  5187.8 1729.59  5208.8 1734.83
  5259.9 1752.19  5280.9 1757.47  5315.5 1768.77  5332.0 1776.96  5360.5 1781.78
#Mann=7,-1,0
  4664.6    0.07       0  4781.9   0.035       0  4794.5    0.07       0
  4897.3   0.035       0  4995.2   0.035       0  4999.2   0.035       0
  5021.1    0.07       0
Bank Sta=4995.2,4999.2
Exp/Cntr=0.3,0.1

Type RM Length L Ch R = 1,4147,455,455,455
BEGIN DESCRIPTION:
Stream0103_DS 9.0
END DESCRIPTION:
XS GIS Cut Line= 3
      2025775.02     13944675.02      2025475.00     13944375.00
      2025174.99     13944375.00
#Sta/Elev= 30
  4575.3 1751.15  4578.9 1751.15  4589.5 1747.16  4603.6 1745.11  4644.1 1734.43
  4674.3 1725.89  4681.4 1725.58  4688.5 1722.20  4702.6 1718.57  4779.3 1702.65
  4801.6 1697.50  4886.5 1694.19  4957.2 1693.99  4978.1 1692.40  4988.0 1691.06
  4994.1 1690.48  4994.3 1689.98  4998.1 1690.48  5002.1 1690.48  5019.6 1696.59
  5049.6 1700.85  5069.6 1706.22  5079.6 1710.86  5099.6 1716.94  5129.6 1728.28
  5169.6 1738.94  5199.6 1749.96  5239.6 1762.38  5279.6 1778.79  5299.6 1782.76
#Mann=7,-1,0
  4575.3    0.12       0  4644.1   0.035       0  4779.3    0.07       0
  4978.1   0.035       0  4988.0    0.07       0  4994.1    0.05       0
  4998.1    0.07       0
Bank Sta=4994.1,4998.1
Exp/Cntr=0.3,0.1

Type RM Length L Ch R = 1,3692,482,482,482
BEGIN DESCRIPTION:
Stream0103_DS 8.0
END DESCRIPTION:
XS GIS Cut Line= 3
      2025874.99     13944274.99      2025575.00     13943975.00
      2025274.96     13944125.02
#Sta/Elev= 30
  4575.4 1732.84  4578.9 1732.84  4589.5 1729.19  4628.9 1720.77  4688.5 1708.30
  4730.9 1700.79  4815.8 1689.33  4847.7 1688.32  4872.4 1688.15  4899.3 1685.98
  4991.2 1682.82  4994.1 1682.77  4994.4 1682.27  4998.1 1682.77  5011.8 1683.36
  5028.5 1683.71  5080.7 1685.69  5125.4 1692.37  5133.8 1695.02  5170.1 1699.42
  5186.9 1703.73  5194.1 1704.57  5214.9 1708.81  5231.6 1714.59  5237.2 1713.77
  5259.6 1716.88  5304.3 1725.20  5326.7 1732.64  5332.3 1736.24  5335.1 1736.24
#Mann=10,-1,0
  4575.4    0.12       0  4628.9   0.035       0  4847.7    0.12       0
  4899.3   0.035       0  4991.2    0.07       0  4994.1    0.05       0
  4998.1    0.07       0  5011.8   0.035       0  5028.5    0.07       0
  5194.1   0.035       0
Bank Sta=4994.1,4998.1
Exp/Cntr=0.3,0.1

Type RM Length L Ch R = 1,3210,482,482,482
BEGIN DESCRIPTION:
Stream0103_DS 7.0
END DESCRIPTION:
XS GIS Cut Line= 3
      2025974.96     13943724.98      2025675.00     13943525.00
      2025375.02     13943375.01
#Sta/Elev= 30
  4639.5 1711.27  4642.5 1711.27  4647.0 1708.55  4662.0 1706.98  4675.5 1704.29
  4689.0 1701.22  4698.0 1697.98  4719.1 1696.63  4740.1 1698.14  4747.6 1694.96
  4782.9 1691.21  4812.2 1686.25  4827.2 1681.35  4855.8 1678.85  4876.2 1674.58
  5002.8 1671.05  5020.4 1669.30  5020.6 1668.80  5024.4 1669.30  5053.1 1672.18
  5103.4 1673.14  5120.2 1674.70  5144.2 1675.12  5178.9 1675.60  5232.0 1684.91
  5237.6 1686.61  5260.0 1688.09  5284.7 1691.68  5313.1 1696.26  5335.4 1698.40
#Mann=7,-1,0
  4639.5    0.07       0  4782.9   0.035       0  4876.2    0.07       0
  5020.4    0.05       0  5024.4    0.07       0  5144.2    0.12       0
  5284.7    0.07       0
Bank Sta=5020.4,5024.4
Exp/Cntr=0.3,0.1

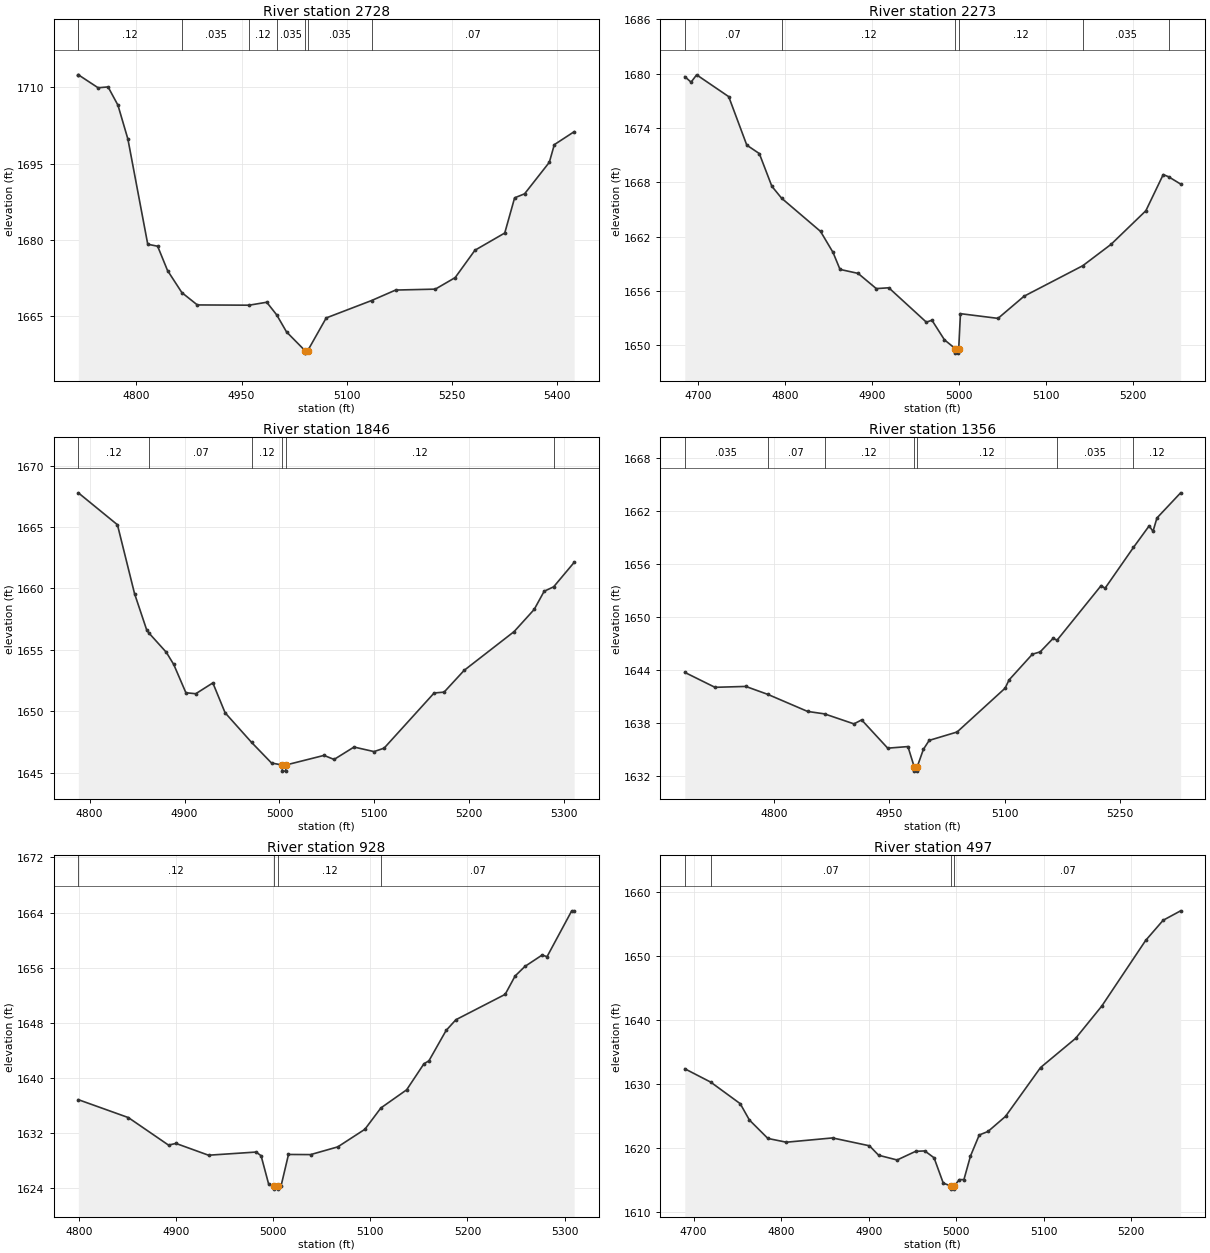
Type RM Length L Ch R = 1,2728,455,455,455
BEGIN DESCRIPTION:
Stream0103_DS 6.0
END DESCRIPTION:
XS GIS Cut Line= 3
      2025974.97     13943274.97      2025775.00     13943075.00
      2025474.98     13942774.98
#Sta/Elev= 30
  4717.3 1712.47  4717.4 1712.47  4745.5 1709.92  4759.7 1710.09  4773.8 1706.49
  4788.0 1699.81  4816.3 1679.11  4830.4 1678.72  4844.5 1673.94  4865.0 1669.58
  4887.0 1667.16  4960.9 1667.11  4986.0 1667.69  5000.2 1665.20  5014.2 1661.85
  5040.5 1658.17  5040.8 1657.67  5044.5 1658.17  5070.8 1664.60  5135.4 1668.02
  5169.8 1670.09  5226.4 1670.27  5254.7 1672.54  5282.9 1677.93  5325.4 1681.32
  5339.5 1688.25  5353.7 1689.04  5389.0 1695.25  5396.1 1698.72  5424.4 1701.27
#Mann=8,-1,0
  4717.3    0.07       0  4717.4    0.12       0  4865.0   0.035       0
  4960.9    0.12       0  5000.2   0.035       0  5040.5    0.05       0
  5044.5   0.035       0  5135.4    0.07       0
Bank Sta=5040.5,5044.5
Exp/Cntr=0.3,0.1

Type RM Length L Ch R = 1,2273,427,427,427
BEGIN DESCRIPTION:
Stream0103_DS 5.0
END DESCRIPTION:
XS GIS Cut Line= 3
      2026175.03     13942875.03      2025925.00     13942675.00
      2025675.00     13942675.00
#Sta/Elev= 30
  4684.4 1679.67  4691.6 1679.06  4698.0 1679.87  4734.9 1677.46  4755.7 1672.10
  4770.1 1671.17  4784.5 1667.56  4795.7 1666.24  4840.5 1662.57  4854.9 1660.24
  4862.9 1658.37  4883.7 1657.93  4904.6 1656.25  4919.0 1656.34  4962.2 1652.54
  4968.6 1652.76  4983.0 1650.59  4995.4 1649.62  4995.6 1649.12  4999.1 1649.12
  4999.4 1649.62  5001.4 1653.48  5044.6 1652.96  5074.6 1655.41  5142.1 1658.78
  5174.6 1661.14  5214.6 1664.85  5234.6 1668.85  5240.7 1668.61  5254.6 1667.80
#Mann=6,-1,0
  4684.4    0.07       0  4795.7    0.12       0  4995.4    0.05       0
  4999.4    0.12       0  5142.1   0.035       0  5240.7    0.07       0
Bank Sta=4995.4,4999.4
Exp/Cntr=0.3,0.1

Type RM Length L Ch R = 1,1846,490,490,490
BEGIN DESCRIPTION:
Stream0103_DS 4.0
END DESCRIPTION:
XS GIS Cut Line= 3
      2026274.96     13942374.99      2026075.00     13942325.00
      2025775.04     13942424.99
#Sta/Elev= 30
  4788.1 1667.78  4829.3 1665.18  4847.3 1659.58  4860.2 1656.60  4862.7 1656.35
  4880.8 1654.80  4888.6 1653.81  4901.4 1651.51  4911.8 1651.43  4929.8 1652.31
  4942.7 1649.88  4970.7 1647.46  4991.6 1645.79  5002.8 1645.63  5003.0 1645.13
  5006.5 1645.13  5006.8 1645.63  5046.9 1646.41  5057.5 1646.08  5078.5 1647.09
  5099.6 1646.72  5110.2 1647.00  5162.9 1651.49  5173.4 1651.56  5194.5 1653.33
  5247.2 1656.49  5268.3 1658.29  5278.8 1659.77  5288.8 1660.13  5310.4 1662.12
#Mann=6,-1,0
  4788.1    0.12       0  4862.7    0.07       0  4970.7    0.12       0
  5002.8    0.05       0  5006.8    0.12       0  5288.8   0.035       0
Bank Sta=5002.8,5006.8
Exp/Cntr=0.3,0.1

Type RM Length L Ch R = 1,1356,428,428,428
BEGIN DESCRIPTION:
Stream0103_DS 3.0
END DESCRIPTION:
XS GIS Cut Line= 3
      2026294.05     13941902.75      2025975.00     13941875.00
      2025654.62     13941824.40
#Sta/Elev= 30
  4684.1 1643.73  4723.3 1642.04  4763.4 1642.14  4792.3 1641.23  4843.7 1639.31
  4865.8 1639.03  4904.0 1637.90  4914.0 1638.35  4947.9 1635.15  4974.2 1635.33
  4982.3 1633.05  4982.5 1632.55  4986.0 1632.55  4986.3 1633.05  4994.3 1635.02
  5001.8 1636.03  5038.1 1636.98  5100.5 1641.94  5105.6 1642.87  5136.0 1645.79
  5146.1 1646.05  5162.9 1647.58  5168.1 1647.38  5225.4 1653.56  5230.4 1653.25
  5267.4 1657.88  5287.8 1660.32  5292.8 1659.70  5297.9 1661.21  5328.7 1664.06
#Mann=7,-1,0
  4684.1   0.035       0  4792.3    0.07       0  4865.8    0.12       0
  4982.3    0.05       0  4986.3    0.12       0  5168.1   0.035       0
  5267.4    0.12       0
Bank Sta=4982.3,4986.3
Exp/Cntr=0.3,0.1

Type RM Length L Ch R = 1,928,431,431,431
BEGIN DESCRIPTION:
Stream0103_DS 2.0
END DESCRIPTION:
XS GIS Cut Line= 3
      2026324.99     13941575.00      2026125.00     13941525.00
      2025824.99     13941475.00
#Sta/Elev= 30
  4799.5 1636.85  4851.0 1634.25  4892.3 1630.26  4900.0 1630.50  4933.5 1628.79
  4982.5 1629.25  4987.6 1628.71  4995.3 1624.64  5001.1 1624.37  5001.3 1623.87
  5004.8 1623.87  5005.1 1624.37  5008.2 1624.37  5015.8 1628.90  5038.6 1628.88
  5066.5 1630.00  5094.4 1632.55  5110.9 1635.65  5137.4 1638.28  5155.2 1642.06
  5160.3 1642.48  5178.0 1646.89  5188.1 1648.45  5238.8 1652.13  5249.0 1654.79
  5259.1 1656.18  5276.8 1657.83  5281.9 1657.60  5307.3 1664.25  5309.8 1664.25
#Mann=4,-1,0
  4799.5    0.12       0  5001.1    0.05       0  5005.1    0.12       0
  5110.9    0.07       0
Bank Sta=5001.1,5005.1
Exp/Cntr=0.3,0.1

Type RM Length L Ch R = 1,497,312,312,312
BEGIN DESCRIPTION:
Stream0103_DS 1.0
END DESCRIPTION:
XS GIS Cut Line= 3
      2026325.05     13941225.02      2026025.00     13941125.00
      2025774.98     13941125.00
#Sta/Elev= 30
  4690.0 1632.34  4719.6 1630.25  4753.3 1626.88  4763.8 1624.32  4784.9 1621.44
  4806.0 1620.85  4858.7 1621.52  4900.9 1620.29  4911.4 1618.81  4932.5 1618.07
  4953.6 1619.42  4964.1 1619.49  4974.7 1618.41  4985.2 1614.45  4993.7 1614.01
  4994.0 1613.51  4997.5 1613.51  4997.7 1614.01  5003.6 1615.00  5008.8 1615.00
  5016.3 1618.69  5026.3 1621.98  5036.3 1622.53  5056.3 1624.89  5096.3 1632.53
  5136.3 1637.09  5166.3 1642.16  5216.3 1652.41  5236.3 1655.57  5256.3 1657.05
#Mann=4,-1,0
  4690.0    0.12       0  4719.6    0.07       0  4993.7    0.05       0
  4997.7    0.07       0
Bank Sta=4993.7,4997.7
Exp/Cntr=0.3,0.1

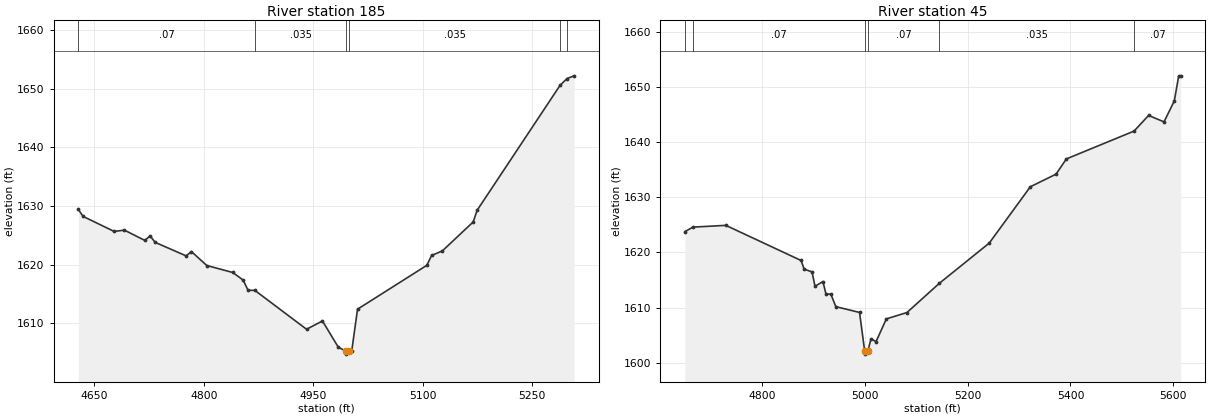
Type RM Length L Ch R = 1,185,140,140,140
BEGIN DESCRIPTION:
Stream0103_DS 0.1
END DESCRIPTION:
XS GIS Cut Line= 4
      2026297.81     13941091.29      2026106.25     13940887.52
      2026025.22     13940843.27      2025734.04     13940943.04
#Sta/Elev= 30
  4628.0 1629.43  4634.6 1628.25  4677.1 1625.69  4691.2 1625.91  4719.1 1624.16
  4726.4 1624.93  4733.3 1623.83  4775.8 1621.52  4783.1 1622.25  4804.1 1619.88
  4839.7 1618.69  4853.9 1617.40  4860.7 1615.66  4870.0 1615.64  4940.9 1609.01
  4962.7 1610.42  4984.6 1605.92  4995.3 1605.27  4995.5 1604.77  4999.3 1605.27
  5002.8 1605.27  5010.8 1612.43  5105.9 1619.92  5112.3 1621.59  5127.1 1622.37
  5169.4 1627.31  5174.8 1629.30  5288.5 1650.60  5298.1 1651.76  5307.8 1652.22
#Mann=6,-1,0
  4628.0    0.07       0  4870.0   0.035       0  4995.3   0.035       0
  4999.3   0.035       0  5288.5    0.07       0  5298.1   0.035       0
Bank Sta=4995.3,4999.3
Exp/Cntr=0.3,0.1

Type RM Length L Ch R = 1,45,0,0,0
BEGIN DESCRIPTION:
Stream0103_DS 0.0
END DESCRIPTION:
XS GIS Cut Line= 4
      2026271.94     13941008.04      2026115.95     13940756.98
      2026071.70     13940716.68      2025462.69     13940707.39
#Sta/Elev= 30
  4649.8 1623.77  4665.6 1624.60  4729.6 1624.92  4876.0 1618.54  4881.9 1616.98
  4897.3 1616.46  4903.1 1613.86  4918.5 1614.72  4924.4 1612.45  4933.9 1612.43
  4943.6 1610.16  4989.7 1609.11  4999.8 1602.04  5000.3 1601.54  5005.8 1602.04
  5011.9 1604.30  5021.9 1603.82  5041.9 1607.94  5081.9 1609.09  5145.1 1614.41
  5242.0 1621.70  5322.0 1631.93  5372.0 1634.22  5392.0 1636.98  5523.8 1642.04
  5552.0 1644.88  5582.0 1643.71  5602.0 1647.51  5610.6 1652.07  5614.3 1652.07
#Mann=6,-1,0
  4649.8    0.12       0  4665.6    0.07       0  4999.8    0.05       0
  5005.8    0.07       0  5145.1   0.035       0  5523.8    0.07       0
Bank Sta=4999.8,5005.8
Exp/Cntr=0.3,0.1

Chan Stop Cuts=-1