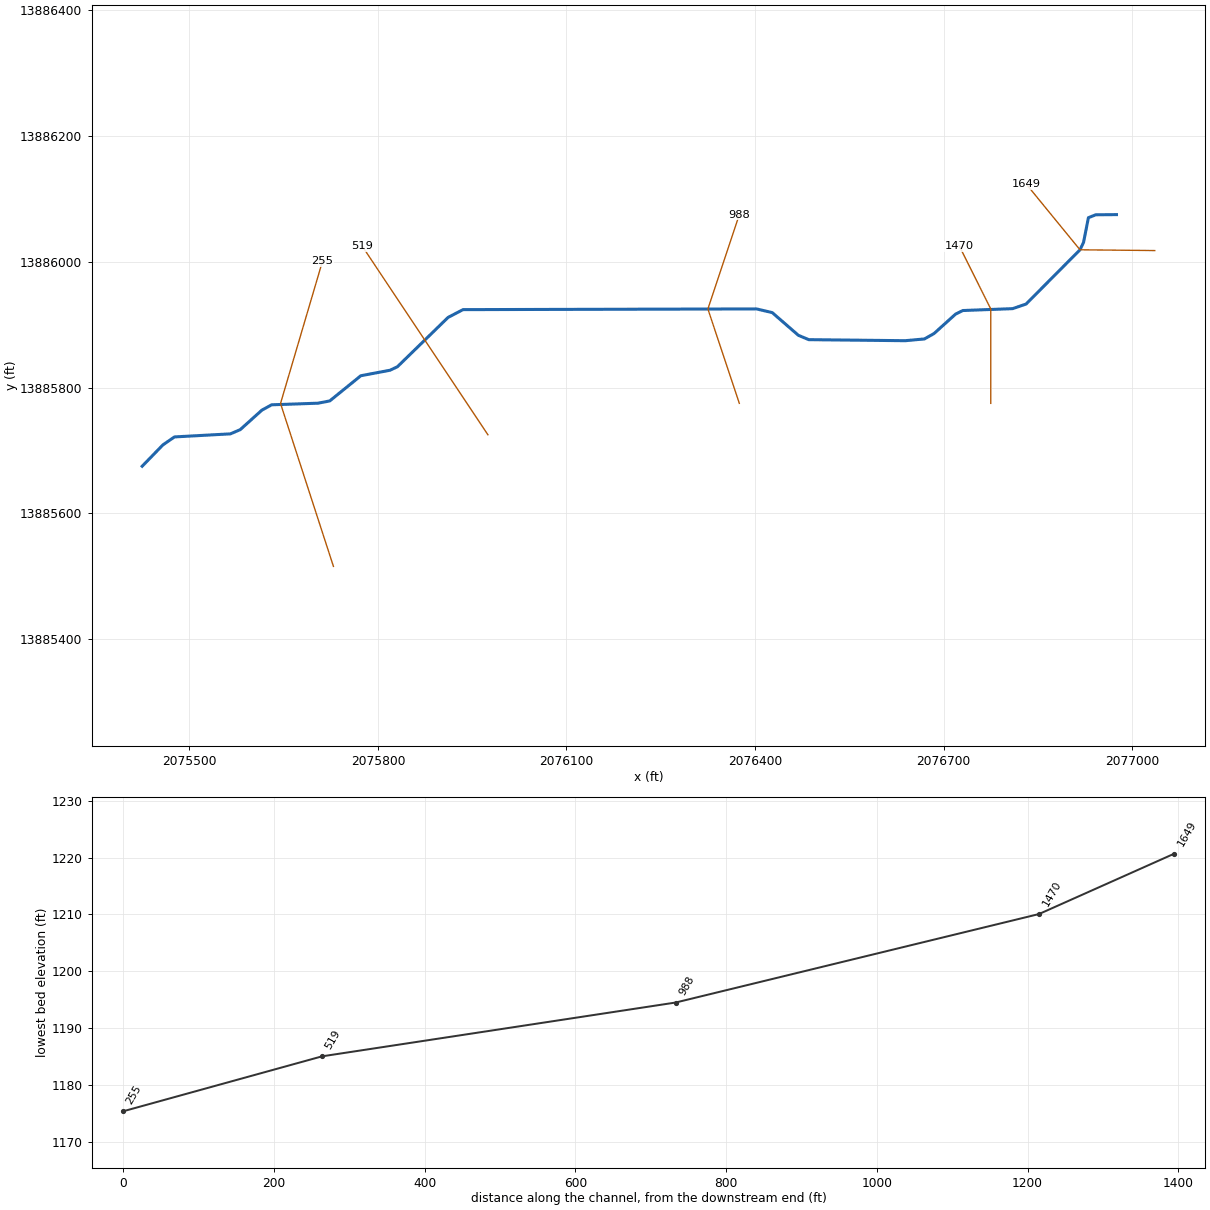
--- Stream0104_DS.prj (project) ---

Proj Title=Stream0104_DS Base Level Engineering
Current Plan=p01
Default Exp/Contr=0.3,0.1
English Units
Geom File=g01
Flow File=f01
Plan File=p01
BEGIN DESCRIPTION:
Stream0104_DS
END DESCRIPTION:

--- Stream0104_DS.p01 (plan) ---

Plan Title=Multiple Run
Short Identifier=Multiple
Geom File=g01
Flow File=f01
Subcritical Flow
K Sum by GR= 0
Std Step Tol= 0.01
Critical Tol= 0.01
Num of Std Step Trials= 20
Max Error Tol= 0.3
Flow Tol Ratio= 0.001
Split Flow NTrial= 30
Split Flow Tol= 0.02
Split Flow Ratio= 0.02
Log Output Level= 0
Friction Slope Method= 1
Unsteady Friction Slope Method= 2
Unsteady Bridges Friction Slope Method= 1
Parabolic Critical Depth
Global Vel Dist=  1 , 1 , 1
Global Log Level= 0
CheckData=True
Encroach Param= -1, 0, 0, 0
BEGIN DESCRIPTION:
Multiple Run
END DESCRIPTION:

--- Stream0104_DS.f01 (steady flow) ---

Flow Title=Multiple
Number of Profiles=7
Profile Names=10-year,25-year,50-year,1pct_min,100-year,1pct_plu,500-year
River Rch & RM= Stream0104_DS,Reach-1,1649
     601     979    1325     872    1740    3471    2959
Boundary for River Rch & Prof#=Stream0104_DS,Reach-1,1
Up Type=0
Dn Type=3
Dn Slope=0.005
Boundary for River Rch & Prof#=Stream0104_DS,Reach-1,2
Up Type=0
Dn Type=3
Dn Slope=0.005
Boundary for River Rch & Prof#=Stream0104_DS,Reach-1,3
Up Type=0
Dn Type=3
Dn Slope=0.005
Boundary for River Rch & Prof#=Stream0104_DS,Reach-1,4
Up Type=0
Dn Type=3
Dn Slope=0.005
Boundary for River Rch & Prof#=Stream0104_DS,Reach-1,5
Up Type=0
Dn Type=3
Dn Slope=0.005
Boundary for River Rch & Prof#=Stream0104_DS,Reach-1,6
Up Type=0
Dn Type=3
Dn Slope=0.005
Boundary for River Rch & Prof#=Stream0104_DS,Reach-1,7
Up Type=0
Dn Type=3
Dn Slope=0.005

--- Stream0104_DS.g01 (geometry) ---

Geom Title=Existing Conditions

River Reach=Stream0104_DS,Reach-1
Reach XY= 30
      2076975.00     13886075.00      2076941.89     13886074.72
      2076930.33     13886070.08      2076922.59     13886030.79
      2076916.95     13886019.08      2076831.19     13885932.85
      2076809.79     13885925.52      2076730.57     13885922.53
      2076718.97     13885916.81      2076684.65     13885885.85
      2076669.47     13885877.37      2076638.82     13885874.56
      2076485.51     13885876.22      2076468.94     13885883.14
      2076427.33     13885919.25      2076402.31     13885925.09
      2075935.44     13885923.95      2075911.69     13885911.60
      2075831.05     13885833.16      2075819.37     13885827.62
      2075772.83     13885818.86      2075723.42     13885778.83
      2075704.91     13885775.23      2075630.97     13885772.65
      2075615.37     13885764.11      2075581.04     13885733.18
      2075565.31     13885726.45      2075476.40     13885721.61
      2075457.95     13885708.88      2075425.00     13885675.00

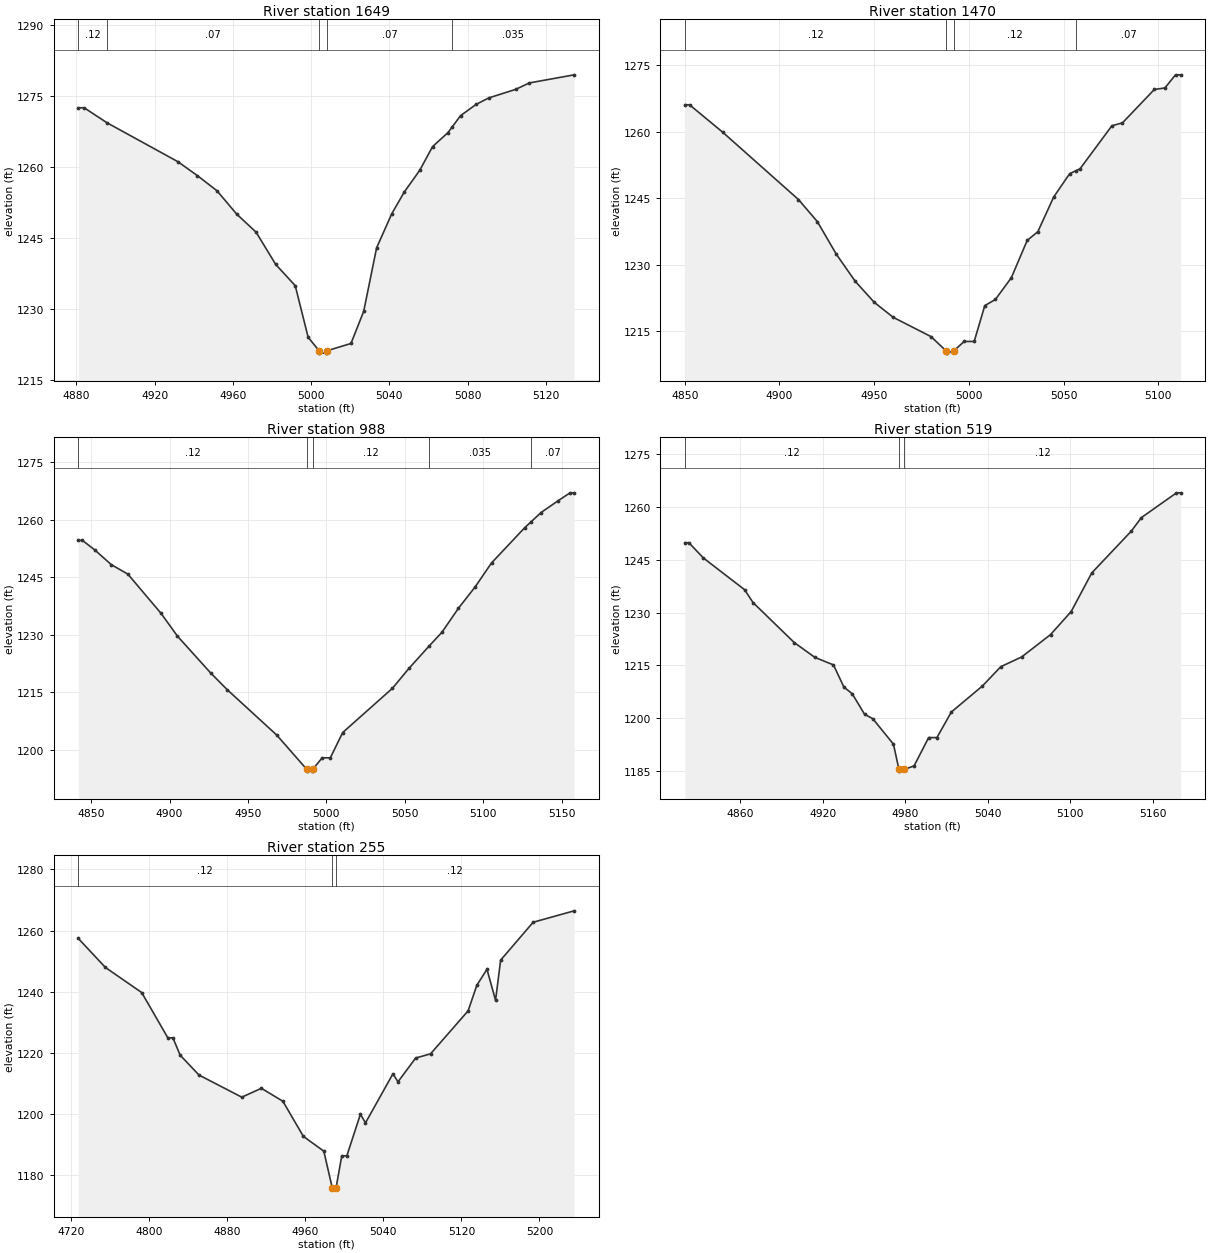
Type RM Length L Ch R = 1,1649,179,179,179
BEGIN DESCRIPTION:
Stream0104_DS 4.0
END DESCRIPTION:
XS GIS Cut Line= 3
      2077035.94     13886017.86      2076916.95     13886019.08
      2076831.77     13886123.17
#Sta/Elev= 30
  4881.0 1272.45  4884.0 1272.45  4895.6 1269.30  4931.9 1261.07  4941.9 1258.12
  4951.9 1254.93  4961.9 1250.03  4971.9 1246.18  4981.9 1239.38  4991.9 1234.89
  4998.5 1223.99  5004.1 1221.15  5004.3 1220.65  5007.8 1220.65  5008.1 1221.15
  5020.4 1222.69  5026.9 1229.48  5033.5 1242.88  5041.3 1250.12  5047.7 1254.70
  5055.6 1259.28  5062.1 1264.25  5070.0 1267.22  5072.0 1268.33  5076.4 1270.78
  5084.3 1273.15  5090.8 1274.53  5104.6 1276.34  5111.6 1277.70  5134.5 1279.41
#Mann=5,-1,0
  4881.0    0.12       0  4895.6    0.07       0  5004.1    0.05       0
  5008.1    0.07       0  5072.0   0.035       0
Bank Sta=5004.1,5008.1
Exp/Cntr=0.3,0.1

Type RM Length L Ch R = 1,1470,482,482,482
BEGIN DESCRIPTION:
Stream0104_DS 3.0
END DESCRIPTION:
XS GIS Cut Line= 3
      2076775.00     13885774.95      2076775.00     13885925.00
      2076725.02     13886024.96
#Sta/Elev= 30
  4850.0 1266.09  4852.5 1266.09  4870.0 1259.91  4910.0 1244.72  4920.0 1239.73
  4930.0 1232.38  4940.0 1226.26  4950.0 1221.54  4960.0 1218.15  4980.0 1213.79
  4988.0 1210.56  4988.3 1210.06  4992.0 1210.56  4997.5 1212.69  5002.8 1212.69
  5008.4 1220.78  5014.0 1222.17  5022.4 1227.06  5030.8 1235.50  5036.4 1237.45
  5044.8 1245.30  5053.2 1250.54  5056.6 1251.23  5058.7 1251.66  5075.5 1261.35
  5081.1 1262.02  5097.9 1269.54  5103.5 1269.89  5109.1 1272.85  5111.8 1272.85
#Mann=4,-1,0
  4850.0    0.12       0  4988.0    0.05       0  4992.0    0.12       0
  5056.6    0.07       0
Bank Sta=4988,4992
Exp/Cntr=0.3,0.1

Type RM Length L Ch R = 1,988,469,469,469
BEGIN DESCRIPTION:
Stream0104_DS 2.0
END DESCRIPTION:
XS GIS Cut Line= 3
      2076375.00     13885775.01      2076325.00     13885925.00
      2076375.00     13886074.99
#Sta/Elev= 30
  4841.8 1254.63  4844.4 1254.63  4852.3 1252.13  4862.9 1248.28  4873.4 1245.83
  4894.5 1235.64  4905.0 1229.68  4926.1 1220.12  4936.7 1215.74  4968.3 1203.91
  4987.4 1195.00  4987.6 1194.50  4991.1 1194.50  4991.4 1195.00  4997.3 1197.97
  5002.5 1197.97  5010.4 1204.56  5042.1 1216.08  5052.6 1221.25  5065.5 1227.10
  5073.7 1230.69  5084.2 1236.94  5094.8 1242.47  5105.3 1248.75  5126.4 1257.90
  5130.3 1259.38  5136.9 1261.89  5147.5 1264.88  5155.4 1267.02  5158.0 1267.02
#Mann=5,-1,0
  4841.8    0.12       0  4987.4    0.05       0  4991.4    0.12       0
  5065.5   0.035       0  5130.3    0.07       0
Bank Sta=4987.4,4991.4
Exp/Cntr=0.3,0.1

Type RM Length L Ch R = 1,519,264,264,264
BEGIN DESCRIPTION:
Stream0104_DS 1.0
END DESCRIPTION:
XS GIS Cut Line= 3
      2075974.99     13885725.02      2075875.00     13885875.00
      2075775.02     13886024.97
#Sta/Elev= 30
  4819.7 1249.81  4822.7 1249.81  4833.2 1245.49  4863.2 1236.48  4869.3 1232.85
  4899.3 1221.49  4914.3 1217.29  4927.8 1215.16  4935.4 1208.86  4941.4 1207.00
  4950.4 1201.16  4956.4 1199.90  4971.4 1192.69  4975.4 1185.54  4975.7 1185.04
  4979.4 1185.54  4986.4 1186.53  4997.0 1194.55  5003.0 1194.55  5013.5 1201.80
  5036.0 1209.15  5049.5 1214.67  5064.6 1217.41  5085.6 1223.75  5100.6 1230.28
  5115.6 1241.25  5144.2 1253.04  5151.7 1256.94  5177.2 1263.96  5180.2 1263.96
#Mann=3,-1,0
  4819.7    0.12       0  4975.4    0.05       0  4979.4    0.12       0
Bank Sta=4975.4,4979.4
Exp/Cntr=0.3,0.1

Type RM Length L Ch R = 1,255,0,0,0
BEGIN DESCRIPTION:
Stream0104_DS 0.0
END DESCRIPTION:
XS GIS Cut Line= 3
      2075729.27     13885515.80      2075645.10     13885774.76
      2075711.79     13886000.62
#Sta/Elev= 30
  4727.7 1257.39  4755.4 1247.92  4792.6 1239.70  4819.3 1224.92  4824.6 1224.85
  4832.0 1219.20  4851.3 1212.70  4895.1 1205.46  4915.2 1208.37  4937.2 1204.12
  4958.2 1192.62  4979.1 1187.80  4987.7 1175.87  4988.0 1175.37  4991.7 1175.87
  4997.5 1186.27  5002.7 1186.27  5016.6 1199.89  5021.8 1197.06  5049.9 1213.11
  5055.1 1210.49  5073.2 1218.28  5088.4 1219.63  5126.9 1233.71  5135.8 1242.06
  5146.2 1247.31  5155.0 1237.16  5160.2 1250.30  5193.5 1262.70  5235.5 1266.44
#Mann=3,-1,0
  4727.7    0.12       0  4987.7    0.05       0  4991.7    0.12       0
Bank Sta=4987.7,4991.7
Exp/Cntr=0.3,0.1

Chan Stop Cuts=-1