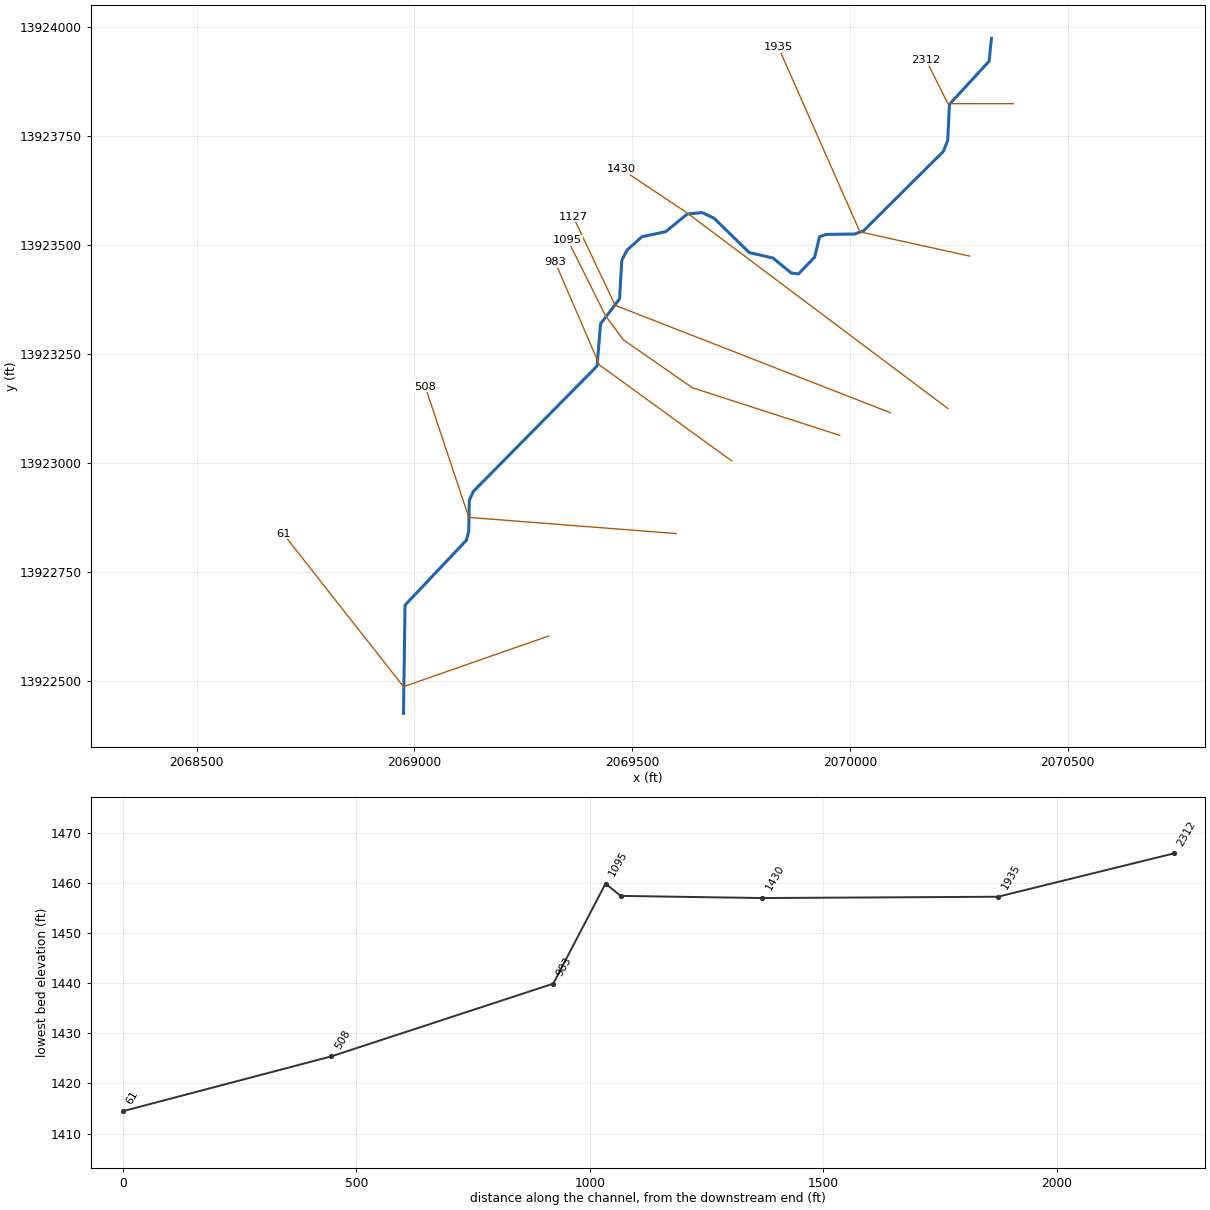
--- Stream0105_DS.prj (project) ---

Proj Title=Stream0105_DS Base Level Engineering
Current Plan=p01
Default Exp/Contr=0.3,0.1
English Units
Geom File=g01
Flow File=f01
Plan File=p01
BEGIN DESCRIPTION:
Stream0105_DS
END DESCRIPTION:

--- Stream0105_DS.p01 (plan) ---

Plan Title=Multiple Run
Short Identifier=Multiple
Geom File=g01
Flow File=f01
Subcritical Flow
K Sum by GR= 0
Std Step Tol= 0.01
Critical Tol= 0.01
Num of Std Step Trials= 20
Max Error Tol= 0.3
Flow Tol Ratio= 0.001
Split Flow NTrial= 30
Split Flow Tol= 0.02
Split Flow Ratio= 0.02
Log Output Level= 0
Friction Slope Method= 1
Unsteady Friction Slope Method= 2
Unsteady Bridges Friction Slope Method= 1
Parabolic Critical Depth
Global Vel Dist=  1 , 1 , 1
Global Log Level= 0
CheckData=True
Encroach Param= -1, 0, 0, 0
BEGIN DESCRIPTION:
Multiple Run
END DESCRIPTION:

--- Stream0105_DS.f01 (steady flow) ---

Flow Title=Multiple
Number of Profiles=7
Profile Names=10-year,25-year,50-year,1pct_min,100-year,1pct_plu,500-year
River Rch & RM= Stream0105_DS,Reach-1,2312
     544     895    1222     813    1622    3236    2823
Boundary for River Rch & Prof#=Stream0105_DS,Reach-1,1
Up Type=0
Dn Type=3
Dn Slope=0.005
Boundary for River Rch & Prof#=Stream0105_DS,Reach-1,2
Up Type=0
Dn Type=3
Dn Slope=0.005
Boundary for River Rch & Prof#=Stream0105_DS,Reach-1,3
Up Type=0
Dn Type=3
Dn Slope=0.005
Boundary for River Rch & Prof#=Stream0105_DS,Reach-1,4
Up Type=0
Dn Type=3
Dn Slope=0.005
Boundary for River Rch & Prof#=Stream0105_DS,Reach-1,5
Up Type=0
Dn Type=3
Dn Slope=0.005
Boundary for River Rch & Prof#=Stream0105_DS,Reach-1,6
Up Type=0
Dn Type=3
Dn Slope=0.005
Boundary for River Rch & Prof#=Stream0105_DS,Reach-1,7
Up Type=0
Dn Type=3
Dn Slope=0.005

--- Stream0105_DS.g01 (geometry) ---

Geom Title=Existing Conditions

River Reach=Stream0105_DS,Reach-1
Reach XY= 30
      2070325.00     13923975.00      2070319.67     13923922.49
      2070228.61     13923823.50      2070224.47     13923740.22
      2070214.48     13923715.21      2070031.12     13923532.88
      2070010.96     13923525.72      2069945.26     13923524.76
      2069930.47     13923519.68      2069918.99     13923472.54
      2069881.99     13923434.04      2069865.25     13923436.23
      2069823.36     13923470.53      2069768.96     13923483.14
      2069688.20     13923561.85      2069660.95     13923574.90
      2069626.73     13923571.69      2069577.16     13923531.19
      2069522.42     13923519.29      2069488.26     13923488.66
      2069476.25     13923465.52      2069471.14     13923376.60
      2069427.47     13923319.43      2069419.48     13923222.57
      2069135.52     13922934.79      2069126.17     13922914.52
      2069124.75     13922843.29      2069119.48     13922822.57
      2068978.54     13922673.54      2068975.00     13922425.00

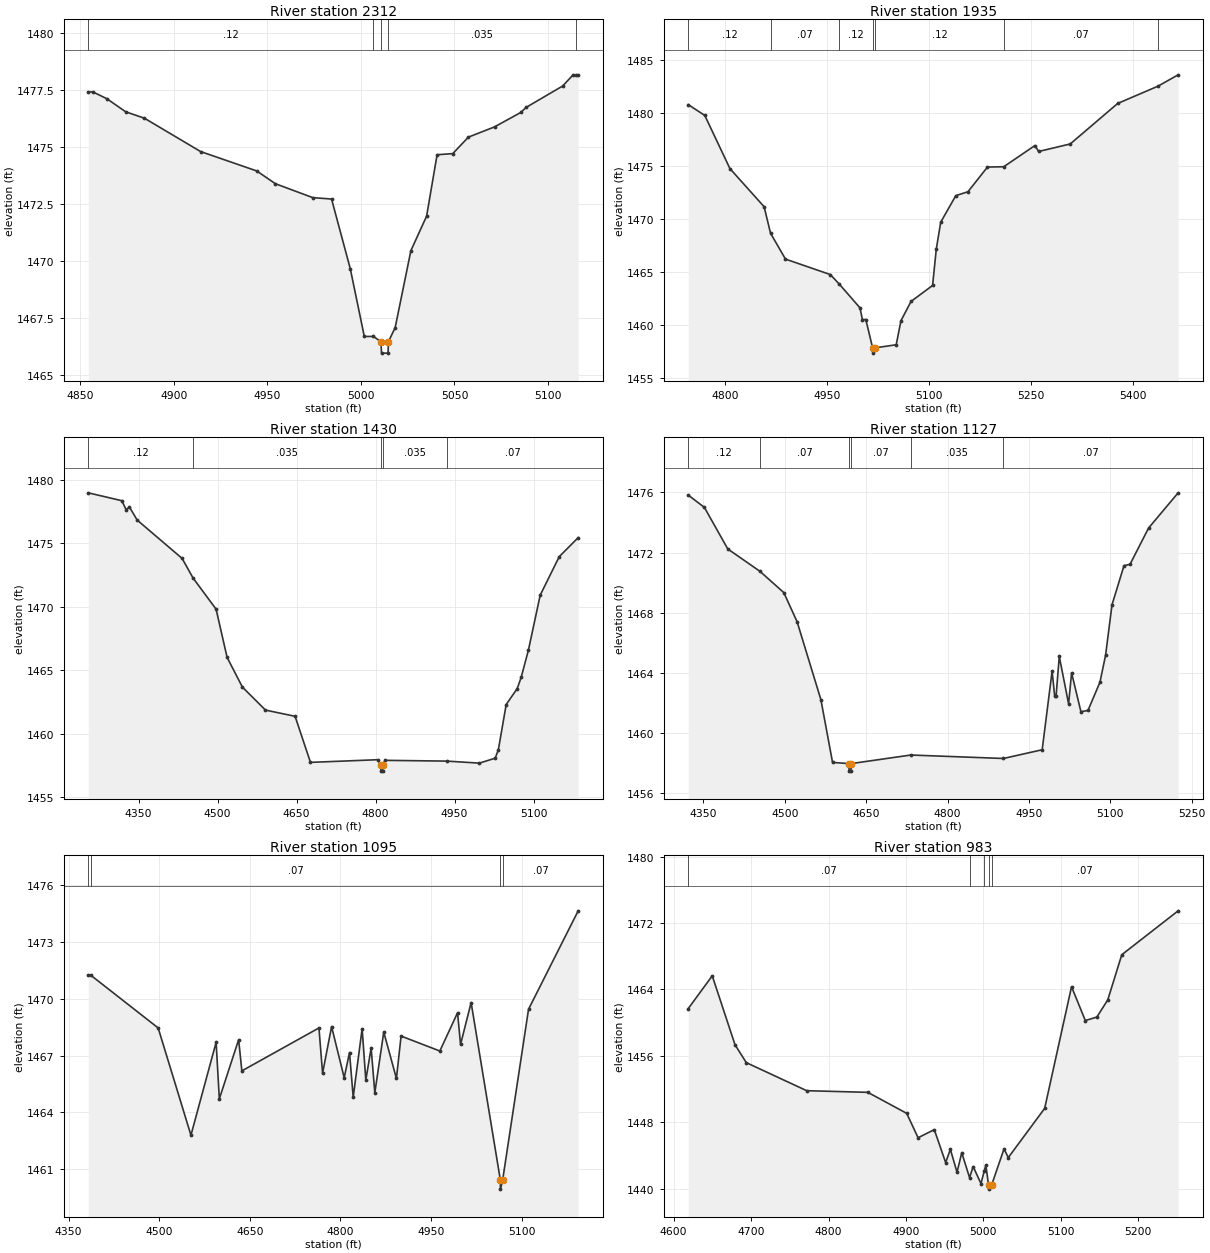
Type RM Length L Ch R = 1,2312,377,377,377
BEGIN DESCRIPTION:
Stream0105_DS 5.0
END DESCRIPTION:
XS GIS Cut Line= 3
      2070375.04     13923825.00      2070225.00     13923825.00
      2070175.02     13923924.96
#Sta/Elev= 30
  4854.3 1477.41  4856.8 1477.41  4864.3 1477.11  4874.3 1476.54  4884.3 1476.26
  4914.3 1474.80  4944.3 1473.95  4954.3 1473.39  4974.3 1472.78  4984.3 1472.72
  4994.3 1469.67  5001.8 1466.70  5006.7 1466.70  5010.7 1466.47  5011.0 1465.97
  5014.5 1465.97  5014.7 1466.47  5018.3 1467.09  5026.7 1470.46  5035.1 1471.97
  5040.7 1474.66  5049.1 1474.71  5057.4 1475.43  5071.4 1475.88  5085.4 1476.51
  5088.2 1476.73  5107.8 1477.67  5113.4 1478.16  5115.0 1478.16  5116.1 1478.16
#Mann=5,-1,0
  4854.3    0.12       0  5006.7   0.035       0  5010.7    0.05       0
  5014.7   0.035       0  5115.0    0.07       0
Bank Sta=5010.7,5014.7
Exp/Cntr=0.3,0.1

Type RM Length L Ch R = 1,1935,505,505,505
BEGIN DESCRIPTION:
Stream0105_DS 4.0
END DESCRIPTION:
XS GIS Cut Line= 3
      2070274.95     13923475.01      2070023.06     13923530.56
      2069835.55     13923955.04
#Sta/Elev= 30
  4745.1 1480.75  4769.5 1479.73  4806.5 1474.72  4856.9 1471.12  4866.4 1468.62
  4888.4 1466.18  4954.5 1464.72  4968.0 1463.80  4998.2 1461.58  5001.8 1460.48
  5006.8 1460.48  5016.8 1457.81  5017.1 1457.31  5020.8 1457.81  5051.6 1458.10
  5058.6 1460.37  5073.5 1462.19  5105.2 1463.69  5110.7 1467.14  5117.2 1469.66
  5139.5 1472.17  5157.3 1472.53  5186.1 1474.86  5210.1 1474.89  5256.0 1476.89
  5261.5 1476.33  5308.1 1477.04  5378.0 1480.86  5437.4 1482.49  5467.1 1483.56
#Mann=7,-1,0
  4745.1    0.12       0  4866.4    0.07       0  4968.0    0.12       0
  5016.8    0.05       0  5020.8    0.12       0  5210.1    0.07       0
  5437.4   0.035       0
Bank Sta=5016.8,5020.8
Exp/Cntr=0.3,0.1

Type RM Length L Ch R = 1,1430,303,303,303
BEGIN DESCRIPTION:
Stream0105_DS 3.0
END DESCRIPTION:
XS GIS Cut Line= 3
      2070225.02     13923124.98      2069625.00     13923575.00
      2069475.01     13923675.00
#Sta/Elev= 30
  4254.4 1478.98  4318.0 1478.36  4326.3 1477.65  4332.6 1477.86  4347.1 1476.84
  4432.6 1473.81  4453.3 1472.27  4497.1 1469.81  4518.0 1466.01  4547.1 1463.67
  4590.9 1461.86  4647.1 1461.37  4676.3 1457.74  4804.4 1457.95  4809.7 1457.55
  4810.0 1457.05  4813.5 1457.05  4813.7 1457.55  4818.0 1457.90  4935.0 1457.84
  4997.1 1457.68  5027.0 1458.07  5033.0 1458.71  5048.0 1462.30  5069.0 1463.56
  5076.5 1464.45  5090.1 1466.57  5112.6 1470.92  5148.7 1473.95  5184.7 1475.45
#Mann=5,-1,0
  4254.4    0.12       0  4453.3   0.035       0  4809.7    0.05       0
  4813.7   0.035       0  4935.0    0.07       0
Bank Sta=4809.7,4813.7
Exp/Cntr=0.3,0.1

Type RM Length L Ch R = 1,1127,32,32,32
BEGIN DESCRIPTION:
Stream0105_DS 2.5
END DESCRIPTION:
XS GIS Cut Line= 3
      2070092.81     13923115.44      2069461.18     13923361.87
      2069364.73     13923565.15
#Sta/Elev= 30
  4322.0 1475.82  4351.8 1475.00  4394.9 1472.24  4454.0 1470.76  4498.2 1469.34
  4522.7 1467.40  4566.5 1462.23  4588.0 1458.06  4618.2 1457.98  4618.5 1457.48
  4622.0 1457.48  4622.2 1457.98  4732.3 1458.55  4902.9 1458.32  4974.4 1458.90
  4992.7 1464.13  4997.4 1462.46  5000.0 1462.46  5005.9 1465.10  5023.1 1461.95
  5028.6 1464.01  5045.8 1461.43  5058.8 1461.51  5080.9 1463.39  5091.3 1465.19
  5103.1 1468.53  5125.2 1471.13  5136.3 1471.22  5170.5 1473.63  5225.0 1475.97
#Mann=6,-1,0
  4322.0    0.12       0  4454.0    0.07       0  4618.2    0.05       0
  4622.2    0.07       0  4732.3   0.035       0  4902.9    0.07       0
Bank Sta=4618.2,4622.2
Exp/Cntr=0.3,0.1

Type RM Length L Ch R = 1,1095,112,112,112
BEGIN DESCRIPTION:
Stream0105_DS 2.1
END DESCRIPTION:
XS GIS Cut Line= 5
      2069976.73     13923063.37      2069638.32     13923172.69
      2069479.75     13923282.82      2069438.82     13923338.13
      2069352.27     13923511.53
#Sta/Elev= 30
  4382.5 1471.26  4386.5 1471.25  4498.2 1468.46  4552.5 1462.79  4594.2 1467.70
  4599.5 1464.71  4631.5 1467.84  4636.8 1466.19  4764.5 1468.46  4770.5 1466.06
  4785.4 1468.53  4806.3 1465.83  4815.1 1467.16  4821.2 1464.80  4836.0 1468.42
  4842.1 1465.70  4850.9 1467.40  4857.0 1465.03  4871.8 1468.24  4892.8 1465.79
  4900.5 1468.03  4964.7 1467.24  4994.0 1469.26  4999.0 1467.59  5016.5 1469.80
  5064.8 1460.44  5065.1 1459.94  5068.8 1460.44  5111.6 1469.45  5193.8 1474.65
#Mann=4,-1,0
  4382.5    0.12       0  4386.5    0.07       0  5064.8    0.05       0
  5068.8    0.07       0
Bank Sta=5064.8,5068.8
Exp/Cntr=0.3,0.1

Type RM Length L Ch R = 1,983,475,475,475
BEGIN DESCRIPTION:
Stream0105_DS 2.0
END DESCRIPTION:
XS GIS Cut Line= 3
      2069728.79     13923004.51      2069425.00     13923225.00
      2069323.15     13923461.42
#Sta/Elev= 30
  4618.8 1461.69  4649.8 1465.64  4679.2 1457.34  4693.8 1455.18  4771.8 1451.80
  4850.8 1451.60  4901.0 1449.07  4915.7 1446.13  4936.6 1447.11  4951.3 1443.14
  4957.4 1444.73  4966.0 1441.97  4972.1 1444.33  4982.2 1441.32  4986.8 1442.66
  4996.9 1440.61  5001.1 1442.10  5003.2 1442.84  5006.7 1440.44  5006.9 1439.94
  5010.7 1440.44  5026.7 1444.79  5032.2 1443.74  5079.2 1449.67  5113.9 1464.33
  5131.7 1460.25  5146.6 1460.67  5160.7 1462.74  5178.8 1468.18  5251.6 1473.47
#Mann=5,-1,0
  4618.8    0.07       0  4982.2    0.12       0  5001.1    0.07       0
  5006.7    0.05       0  5010.7    0.07       0
Bank Sta=5006.7,5010.7
Exp/Cntr=0.3,0.1

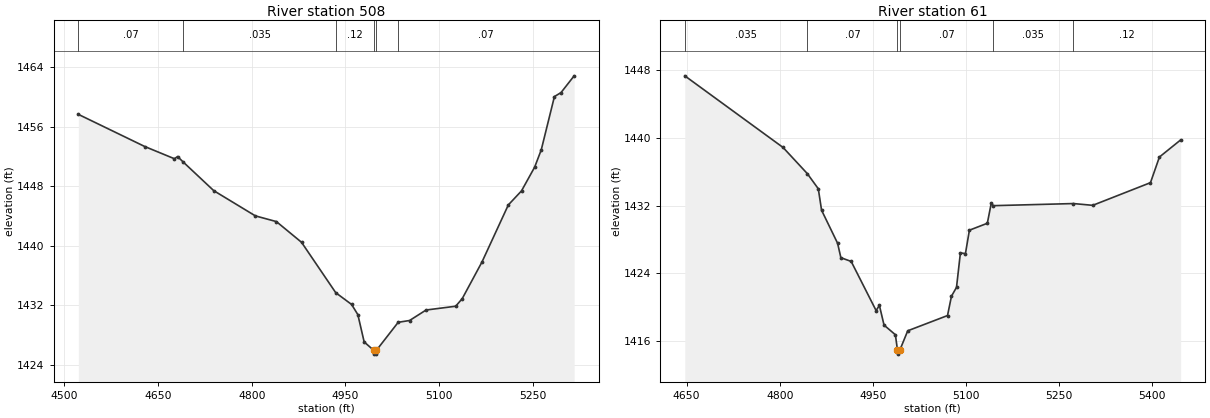
Type RM Length L Ch R = 1,508,447,447,447
BEGIN DESCRIPTION:
Stream0105_DS 1.0
END DESCRIPTION:
XS GIS Cut Line= 3
      2069601.17     13922837.85      2069125.00     13922875.00
      2069025.01     13923174.96
#Sta/Elev= 30
  4522.4 1457.66  4628.9 1453.33  4676.3 1451.69  4681.3 1451.99  4690.2 1451.26
  4739.2 1447.40  4805.8 1444.01  4839.5 1443.24  4879.7 1440.46  4934.5 1433.68
  4959.9 1432.10  4969.9 1430.73  4980.0 1427.06  4995.5 1425.92  4995.8 1425.42
  4999.3 1425.42  4999.5 1425.92  5034.5 1429.70  5052.7 1429.94  5079.1 1431.35
  5126.5 1431.86  5137.0 1432.88  5168.7 1437.82  5210.8 1445.48  5231.9 1447.37
  5253.0 1450.57  5263.5 1452.88  5284.6 1460.05  5295.2 1460.59  5316.2 1462.84
#Mann=6,-1,0
  4522.4    0.07       0  4690.2   0.035       0  4934.5    0.12       0
  4995.5    0.05       0  4999.5    0.12       0  5034.5    0.07       0
Bank Sta=4995.5,4999.5
Exp/Cntr=0.3,0.1

Type RM Length L Ch R = 1,61,0,0,0
BEGIN DESCRIPTION:
Stream0105_DS 0.0
END DESCRIPTION:
XS GIS Cut Line= 3
      2069308.27     13922602.62      2068974.98     13922486.33
      2068699.14     13922837.18
#Sta/Elev= 30
  4647.0 1447.35  4805.4 1438.88  4844.5 1435.79  4862.2 1434.00  4867.5 1431.46
  4893.3 1427.56  4898.6 1425.85  4915.2 1425.41  4955.4 1419.60  4960.7 1420.21
  4968.2 1417.88  4986.5 1416.74  4989.8 1414.95  4990.0 1414.45  4993.8 1414.95
  5006.4 1417.21  5070.5 1419.01  5076.9 1421.30  5085.0 1422.34  5091.3 1426.42
  5099.4 1426.33  5105.8 1429.10  5134.7 1429.92  5141.0 1432.28  5144.3 1432.00
  5273.6 1432.25  5304.6 1432.04  5397.7 1434.72  5412.1 1437.75  5446.3 1439.77
#Mann=6,-1,0
  4647.0   0.035       0  4844.5    0.07       0  4989.8    0.05       0
  4993.8    0.07       0  5144.3   0.035       0  5273.6    0.12       0
Bank Sta=4989.8,4993.8
Exp/Cntr=0.3,0.1

Chan Stop Cuts=-1