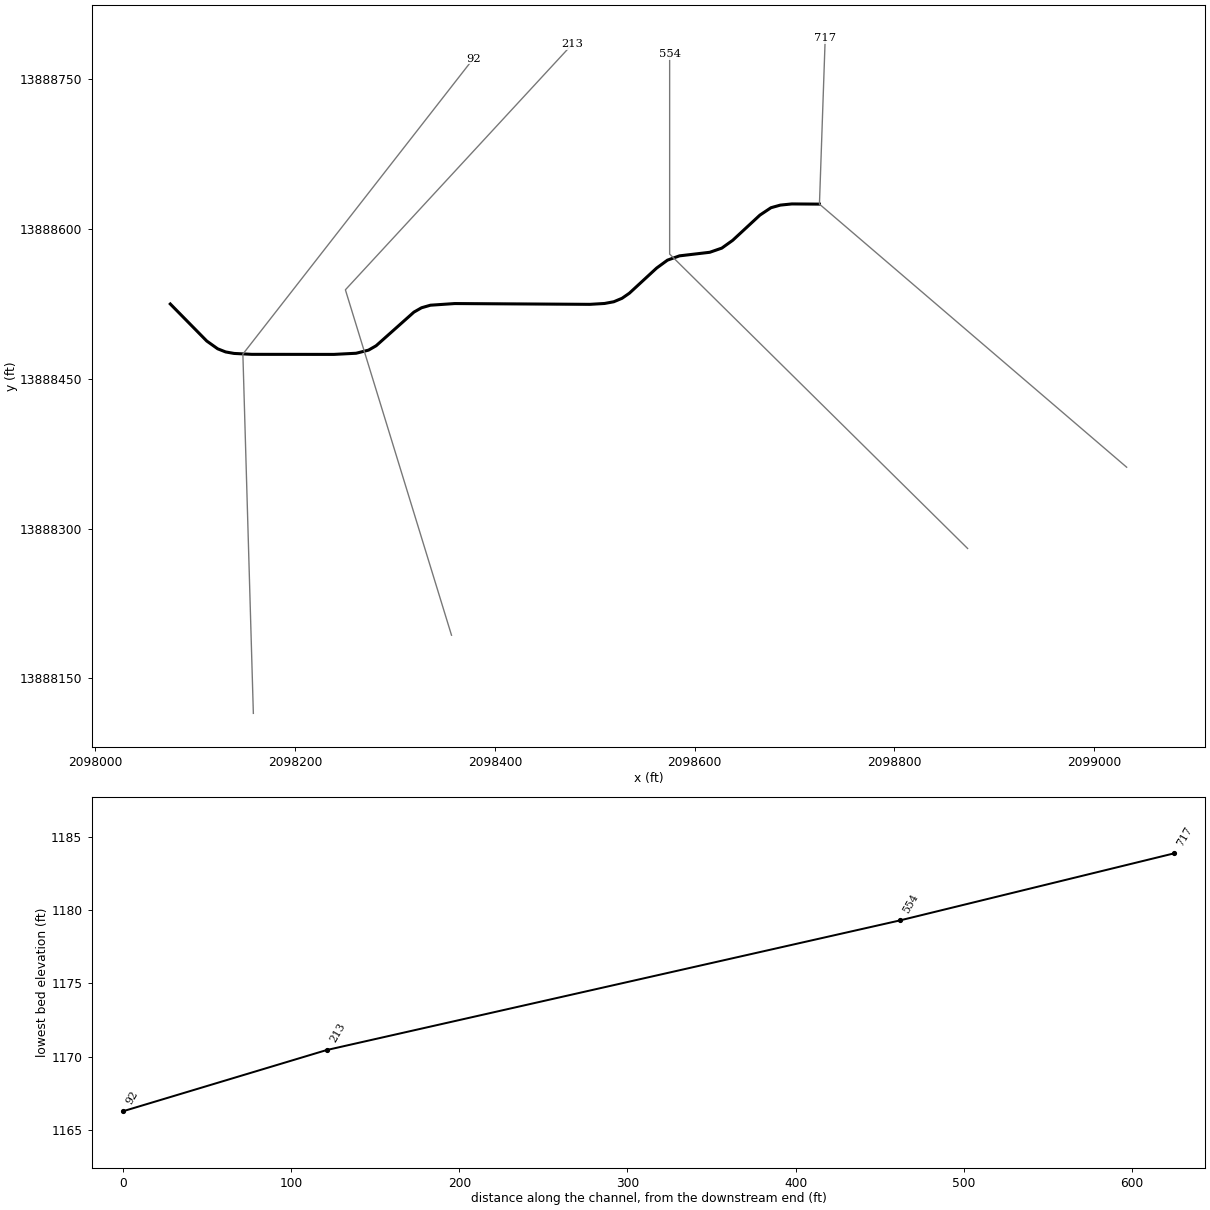
--- Stream0106_DS.prj (project) ---

Proj Title=Stream0106_DS Base Level Engineering
Current Plan=p01
Default Exp/Contr=0.3,0.1
English Units
Geom File=g01
Flow File=f01
Plan File=p01
BEGIN DESCRIPTION:
Stream0106_DS
END DESCRIPTION:

--- Stream0106_DS.p01 (plan) ---

Plan Title=Multiple Run
Short Identifier=Multiple
Geom File=g01
Flow File=f01
Subcritical Flow
K Sum by GR= 0
Std Step Tol= 0.01
Critical Tol= 0.01
Num of Std Step Trials= 20
Max Error Tol= 0.3
Flow Tol Ratio= 0.001
Split Flow NTrial= 30
Split Flow Tol= 0.02
Split Flow Ratio= 0.02
Log Output Level= 0
Friction Slope Method= 1
Unsteady Friction Slope Method= 2
Unsteady Bridges Friction Slope Method= 1
Parabolic Critical Depth
Global Vel Dist=  1 , 1 , 1
Global Log Level= 0
CheckData=True
Encroach Param= -1, 0, 0, 0
BEGIN DESCRIPTION:
Multiple Run
END DESCRIPTION:

--- Stream0106_DS.f01 (steady flow) ---

Flow Title=Multiple
Number of Profiles=7
Profile Names=10-year,25-year,50-year,1pct_min,100-year,1pct_plu,500-year
River Rch & RM= Stream0106_DS,Reach-1,717
     359     568     755     489     976    1948    1607
Boundary for River Rch & Prof#=Stream0106_DS,Reach-1,1
Up Type=0
Dn Type=3
Dn Slope=0.005
Boundary for River Rch & Prof#=Stream0106_DS,Reach-1,2
Up Type=0
Dn Type=3
Dn Slope=0.005
Boundary for River Rch & Prof#=Stream0106_DS,Reach-1,3
Up Type=0
Dn Type=3
Dn Slope=0.005
Boundary for River Rch & Prof#=Stream0106_DS,Reach-1,4
Up Type=0
Dn Type=3
Dn Slope=0.005
Boundary for River Rch & Prof#=Stream0106_DS,Reach-1,5
Up Type=0
Dn Type=3
Dn Slope=0.005
Boundary for River Rch & Prof#=Stream0106_DS,Reach-1,6
Up Type=0
Dn Type=3
Dn Slope=0.005
Boundary for River Rch & Prof#=Stream0106_DS,Reach-1,7
Up Type=0
Dn Type=3
Dn Slope=0.005

--- Stream0106_DS.g01 (geometry) ---

Geom Title=Existing Conditions

River Reach=Stream0106_DS,Reach-1
Reach XY= 30
      2098725.00     13888625.00      2098697.32     13888625.18
      2098685.85     13888624.01      2098676.49     13888621.40
      2098665.41     13888614.02      2098638.15     13888588.76
      2098627.25     13888580.95      2098615.18     13888576.77
      2098584.84     13888573.19      2098572.82     13888568.89
      2098561.96     13888560.96      2098534.67     13888535.79
      2098527.35     13888530.71      2098519.07     13888527.24
      2098509.79     13888525.51      2098495.15     13888524.64
      2098359.82     13888525.43      2098335.51     13888523.78
      2098326.57     13888521.22      2098318.94     13888516.86
      2098281.05     13888483.14      2098273.43     13888478.77
      2098261.08     13888475.67      2098238.81     13888474.52
      2098156.68     13888474.58      2098138.85     13888475.48
      2098130.38     13888476.99      2098122.42     13888480.13
      2098111.50     13888487.91      2098075.00     13888525.00

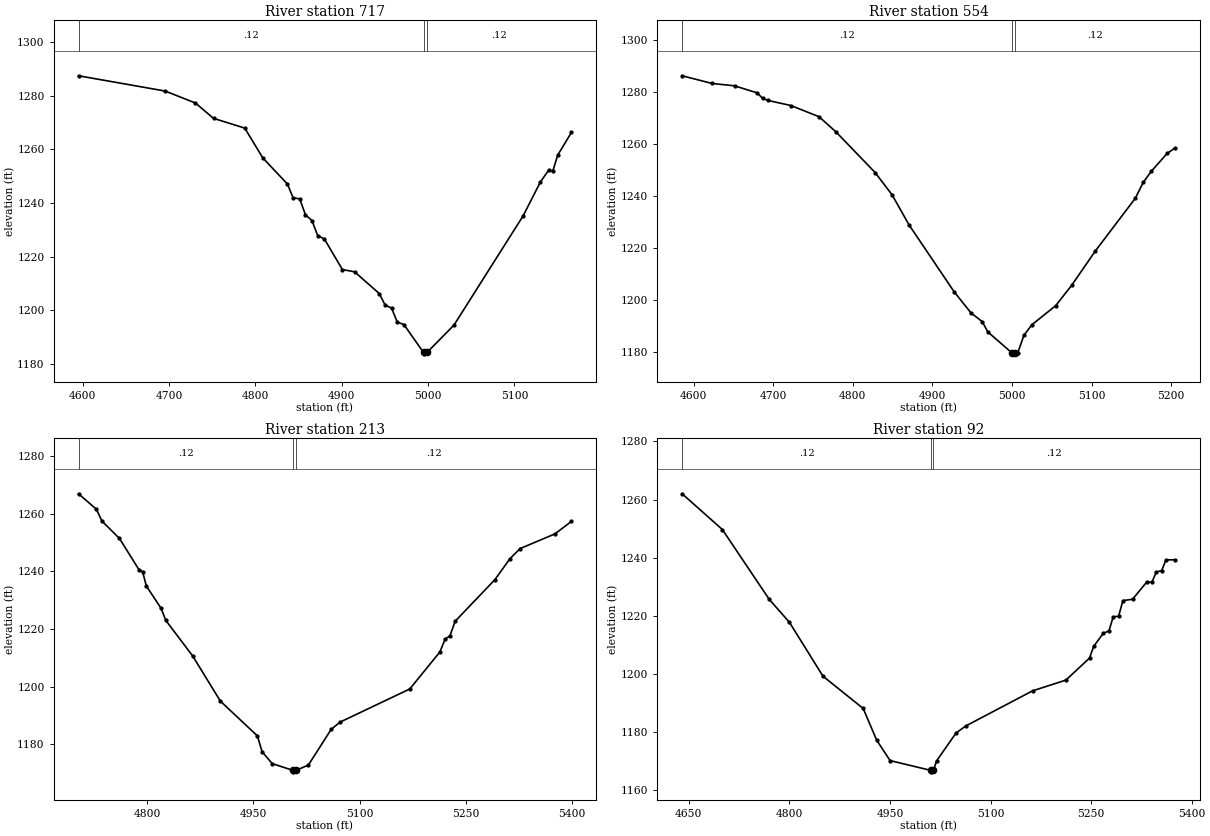
Type RM Length L Ch R = 1,717,163,163,163
BEGIN DESCRIPTION:
Stream0106_DS 3.0
END DESCRIPTION:
XS GIS Cut Line= 3
      2099032.61     13888361.56      2098725.00     13888625.00
      2098730.76     13888791.00
#Sta/Elev= 30
  4595.0 1287.45  4695.4 1281.76  4730.5 1277.30  4751.4 1271.59  4787.6 1267.96
  4808.5 1256.86  4837.0 1247.13  4843.6 1242.02  4851.3 1241.57  4857.9 1235.69
  4865.5 1233.47  4872.1 1227.91  4879.8 1226.66  4900.7 1215.26  4914.9 1214.40
  4943.5 1206.30  4950.1 1202.10  4957.7 1200.86  4964.3 1195.70  4972.0 1194.75
  4994.7 1184.35  4995.0 1183.85  4998.7 1184.35  5030.0 1194.56  5110.1 1235.26
  5130.1 1247.87  5139.6 1252.24  5144.6 1252.05  5150.1 1257.84  5166.1 1266.37
#Mann=3,-1,0
  4595.0    0.12       0  4994.7    0.05       0  4998.7    0.12       0
Bank Sta=4994.7,4998.7
Exp/Cntr=0.3,0.1

Type RM Length L Ch R = 1,554,341,341,341
BEGIN DESCRIPTION:
Stream0106_DS 2.0
END DESCRIPTION:
XS GIS Cut Line= 3
      2098873.35     13888280.20      2098575.00     13888575.00
      2098575.00     13888774.97
#Sta/Elev= 30
  4585.6 1286.16  4623.2 1283.21  4651.5 1282.30  4679.8 1279.59  4686.8 1277.48
  4693.9 1276.66  4722.2 1274.73  4757.5 1270.45  4778.8 1264.63  4828.2 1248.94
  4849.5 1240.36  4870.7 1228.86  4927.2 1203.22  4948.5 1195.03  4962.6 1191.70
  4969.7 1187.72  4999.5 1179.79  4999.8 1179.29  5003.5 1179.79  5007.5 1179.79
  5015.0 1186.39  5025.0 1190.45  5055.0 1197.81  5075.0 1205.60  5105.0 1218.91
  5155.0 1239.07  5165.0 1245.18  5175.0 1249.40  5195.0 1256.31  5205.0 1258.41
#Mann=3,-1,0
  4585.6    0.12       0  4999.5    0.05       0  5003.5    0.12       0
Bank Sta=4999.5,5003.5
Exp/Cntr=0.3,0.1

Type RM Length L Ch R = 1,213,121,121,121
BEGIN DESCRIPTION:
Stream0106_DS 1.0
END DESCRIPTION:
XS GIS Cut Line= 3
      2098356.58     13888193.33      2098250.32     13888539.20
      2098477.48     13888785.12
#Sta/Elev= 30
  4702.9 1266.92  4728.1 1261.58  4736.0 1257.46  4760.8 1251.42  4788.3 1240.61
  4793.5 1239.89  4798.8 1234.92  4819.7 1227.15  4826.2 1223.02  4864.2 1210.67
  4903.4 1194.99  4955.7 1182.94  4962.3 1177.47  4976.6 1173.33  5006.0 1170.97
  5006.3 1170.47  5010.0 1170.97  5027.7 1172.80  5059.9 1185.18  5072.4 1187.71
  5171.1 1199.22  5213.6 1212.07  5221.0 1216.52  5227.8 1217.64  5235.1 1222.70
  5291.3 1237.13  5312.8 1244.47  5327.0 1247.92  5376.3 1253.02  5399.5 1257.35
#Mann=3,-1,0
  4702.9    0.12       0  5006.0    0.05       0  5010.0    0.12       0
Bank Sta=5006,5010
Exp/Cntr=0.3,0.1

Type RM Length L Ch R = 1,92,0,0,0
BEGIN DESCRIPTION:
Stream0106_DS 0.0
END DESCRIPTION:
XS GIS Cut Line= 3
      2098158.16     13888115.07      2098147.67     13888474.82
      2098378.43     13888770.67
#Sta/Elev= 30
  4640.1 1261.97  4700.1 1249.67  4770.1 1225.61  4800.1 1217.76  4850.1 1199.22
  4910.1 1188.11  4930.2 1177.21  4950.2 1170.18  5010.9 1166.81  5011.2 1166.31
  5014.9 1166.81  5019.6 1170.10  5048.6 1179.68  5063.1 1182.10  5162.6 1194.17
  5212.3 1197.86  5247.6 1205.45  5253.9 1209.51  5268.4 1214.03  5276.5 1214.75
  5282.9 1219.60  5291.0 1219.88  5297.4 1225.21  5311.8 1225.69  5332.6 1231.51
  5340.8 1231.59  5347.1 1235.06  5355.2 1235.52  5361.6 1239.24  5375.2 1239.25
#Mann=3,-1,0
  4640.1    0.12       0  5010.9    0.05       0  5014.9    0.12       0
Bank Sta=5010.9,5014.9
Exp/Cntr=0.3,0.1

Chan Stop Cuts=-1