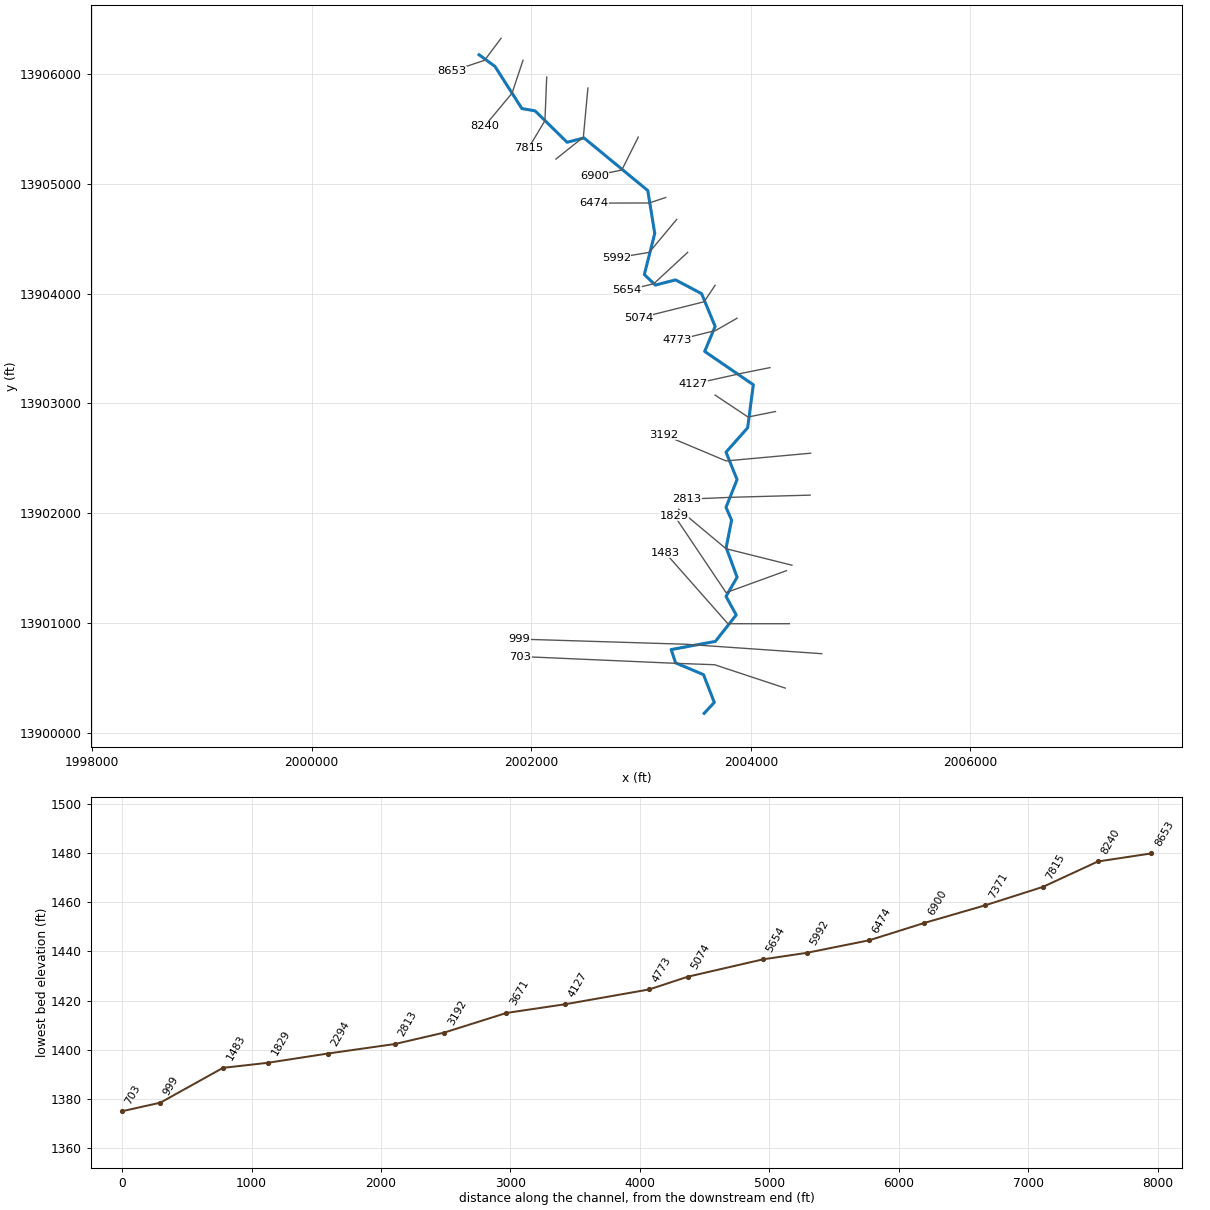
--- Stream0108_DS.prj (project) ---

Proj Title=Stream0108_DS Base Level Engineering
Current Plan=p01
Default Exp/Contr=0.3,0.1
English Units
Geom File=g01
Flow File=f01
Plan File=p01
BEGIN DESCRIPTION:
Stream0108_DS
END DESCRIPTION:

--- Stream0108_DS.p01 (plan) ---

Plan Title=Multiple Run
Short Identifier=Multiple
Geom File=g01
Flow File=f01
Subcritical Flow
K Sum by GR= 0
Std Step Tol= 0.01
Critical Tol= 0.01
Num of Std Step Trials= 20
Max Error Tol= 0.3
Flow Tol Ratio= 0.001
Split Flow NTrial= 30
Split Flow Tol= 0.02
Split Flow Ratio= 0.02
Log Output Level= 0
Friction Slope Method= 1
Unsteady Friction Slope Method= 2
Unsteady Bridges Friction Slope Method= 1
Parabolic Critical Depth
Global Vel Dist=  1 , 1 , 1
Global Log Level= 0
CheckData=True
Encroach Param= -1, 0, 0, 0
BEGIN DESCRIPTION:
Multiple Run
END DESCRIPTION:

--- Stream0108_DS.f01 (steady flow) ---

Flow Title=Multiple
Number of Profiles=7
Profile Names=10-year,25-year,50-year,1pct_min,100-year,1pct_plu,500-year
River Rch & RM= Stream0108_DS,Reach-1,8653
     575     943    1282     847    1691    3374    2904
River Rch & RM= Stream0108_DS,Reach-1,8240
    1062    1800    2502    1684    3360    6704    6000
River Rch & RM= Stream0108_DS,Reach-1,999
    1694    2949    4172    2854    5695   11363   10514
Boundary for River Rch & Prof#=Stream0108_DS,Reach-1,1
Up Type=0
Dn Type=3
Dn Slope=0.005
Boundary for River Rch & Prof#=Stream0108_DS,Reach-1,2
Up Type=0
Dn Type=3
Dn Slope=0.005
Boundary for River Rch & Prof#=Stream0108_DS,Reach-1,3
Up Type=0
Dn Type=3
Dn Slope=0.005
Boundary for River Rch & Prof#=Stream0108_DS,Reach-1,4
Up Type=0
Dn Type=3
Dn Slope=0.005
Boundary for River Rch & Prof#=Stream0108_DS,Reach-1,5
Up Type=0
Dn Type=3
Dn Slope=0.005
Boundary for River Rch & Prof#=Stream0108_DS,Reach-1,6
Up Type=0
Dn Type=3
Dn Slope=0.005
Boundary for River Rch & Prof#=Stream0108_DS,Reach-1,7
Up Type=0
Dn Type=3
Dn Slope=0.005

--- Stream0108_DS.g01 (geometry) ---

Geom Title=Existing Conditions

River Reach=Stream0108_DS,Reach-1
Reach XY= 30
      2001525.00     13906175.00      2001669.42     13906069.40
      2001914.90     13905685.39      2002034.78     13905664.48
      2002326.63     13905378.13      2002481.06     13905417.52
      2003061.63     13904938.32      2003125.38     13904547.81
      2003030.39     13904172.56      2003130.88     13904076.96
      2003314.32     13904124.25      2003552.30     13903998.90
      2003675.50     13903700.03      2003580.06     13903472.70
      2004023.38     13903168.97      2003971.46     13902776.46
      2003774.79     13902554.95      2003875.11     13902304.90
      2003774.61     13902052.20      2003825.50     13901935.17
      2003776.09     13901685.54      2003875.55     13901415.72
      2003775.02     13901240.41      2003867.22     13901071.60
      2003677.47     13900830.45      2003274.97     13900756.58
      2003314.93     13900635.61      2003569.60     13900527.71
      2003667.81     13900274.91      2003575.00     13900175.00

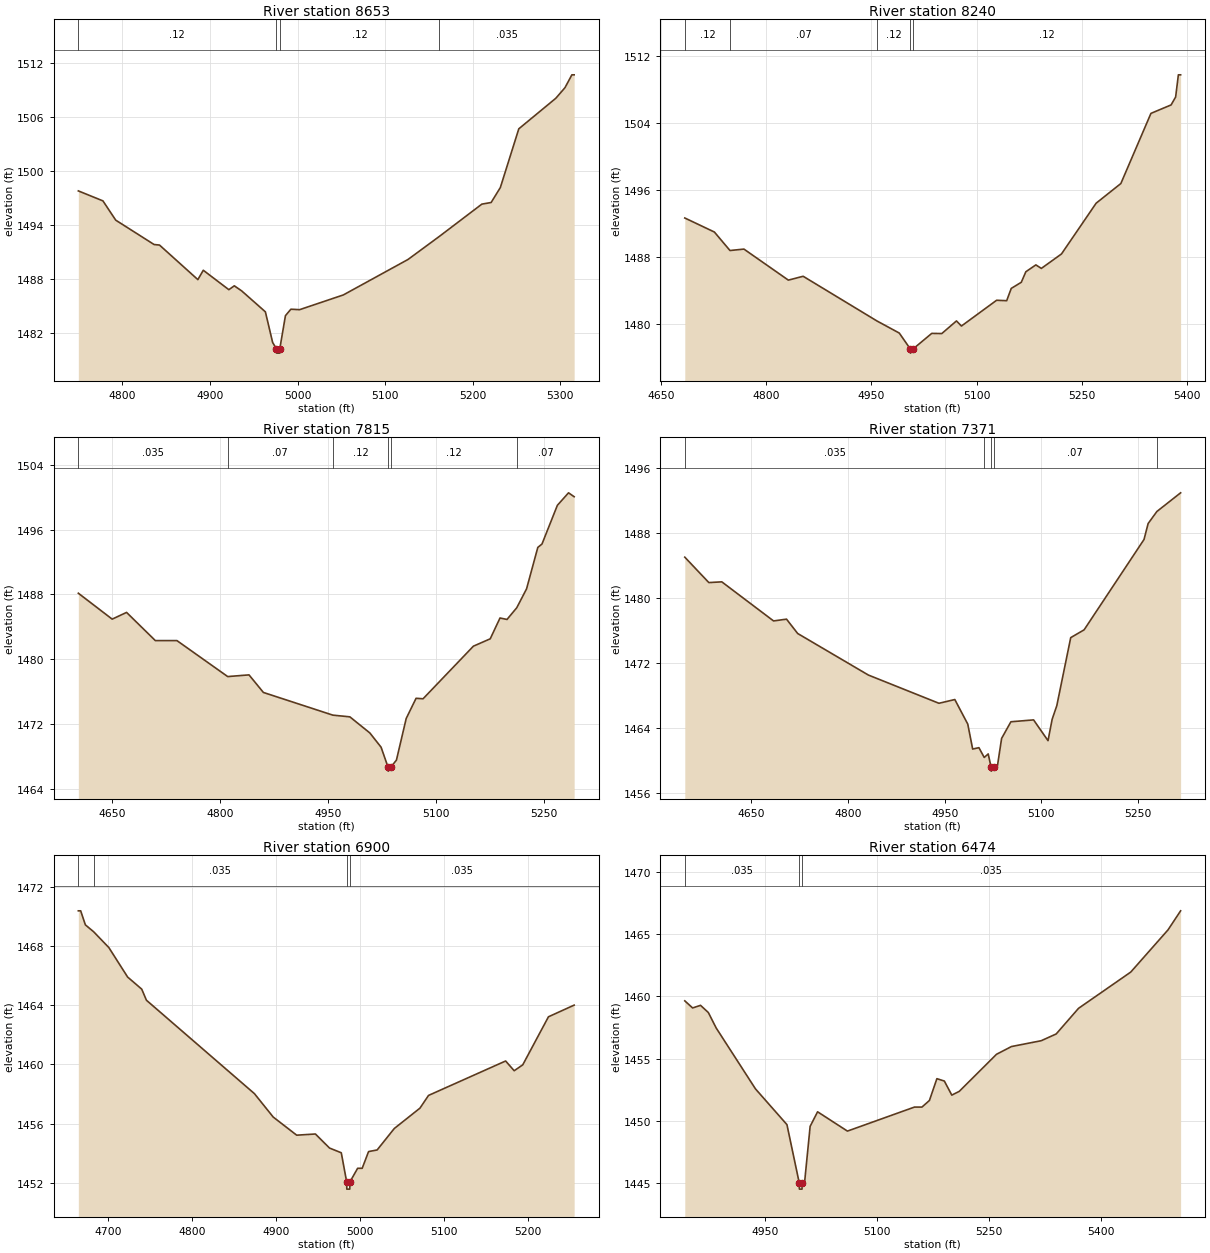
Type RM Length L Ch R = 1,8653,413,413,413
BEGIN DESCRIPTION:
Stream0108_DS 19.0
END DESCRIPTION:
XS GIS Cut Line= 3
      2001725.01     13906325.01      2001575.00     13906125.00
      2001275.04     13906025.01
#Sta/Elev= 30
  4749.7 1497.82  4777.8 1496.71  4792.4 1494.57  4836.2 1491.86  4842.4 1491.80
  4886.2 1487.96  4892.4 1489.00  4921.6 1486.84  4927.8 1487.27  4936.2 1486.71
  4963.3 1484.38  4971.6 1480.97  4975.8 1480.29  4976.1 1479.79  4979.6 1479.79
  4979.8 1480.29  4986.2 1483.95  4992.4 1484.67  5002.4 1484.62  5052.4 1486.26
  5126.2 1490.20  5161.8 1492.75  5210.5 1496.35  5221.1 1496.53  5231.6 1498.19
  5252.7 1504.72  5294.9 1508.11  5305.4 1509.29  5313.3 1510.72  5315.9 1510.72
#Mann=4,-1,0
  4749.7    0.12       0  4975.8    0.05       0  4979.8    0.12       0
  5161.8   0.035       0
Bank Sta=4975.8,4979.8
Exp/Cntr=0.3,0.1

Type RM Length L Ch R = 1,8240,425,425,425
BEGIN DESCRIPTION:
Stream0108_DS 18.0
END DESCRIPTION:
XS GIS Cut Line= 3
      2001925.00     13906125.00      2001825.00     13905825.00
      2001575.03     13905525.03
#Sta/Elev= 30
  4684.0 1492.67  4726.2 1490.99  4748.4 1488.78  4768.3 1488.95  4831.6 1485.24
  4852.7 1485.70  4958.0 1480.35  4989.7 1478.91  5005.4 1477.01  5005.6 1476.51
  5009.4 1477.01  5036.0 1478.87  5050.3 1478.85  5071.2 1480.36  5078.3 1479.75
  5128.4 1482.83  5142.8 1482.78  5149.3 1484.25  5163.6 1484.98  5170.1 1486.24
  5184.4 1487.06  5192.2 1486.64  5220.9 1488.37  5270.3 1494.44  5305.5 1496.79
  5348.4 1505.18  5377.1 1506.19  5383.6 1507.14  5387.5 1509.79  5390.7 1509.79
#Mann=5,-1,0
  4684.0    0.12       0  4748.4    0.07       0  4958.0    0.12       0
  5005.4    0.05       0  5009.4    0.12       0
Bank Sta=5005.4,5009.4
Exp/Cntr=0.3,0.1

Type RM Length L Ch R = 1,7815,444,444,444
BEGIN DESCRIPTION:
Stream0108_DS 17.0
END DESCRIPTION:
XS GIS Cut Line= 3
      2002140.87     13905971.92      2002125.00     13905575.00
      2001974.99     13905324.99
#Sta/Elev= 30
  4602.8 1488.15  4649.8 1484.95  4669.8 1485.78  4709.8 1482.30  4739.8 1482.30
  4810.3 1477.86  4839.9 1478.07  4859.9 1475.90  4956.4 1473.10  4980.0 1472.89
  5007.8 1470.90  5023.4 1469.14  5033.0 1466.69  5033.3 1466.19  5037.0 1466.69
  5044.7 1467.55  5058.3 1472.69  5072.0 1475.18  5081.7 1475.12  5151.6 1481.61
  5175.0 1482.52  5188.6 1485.09  5198.3 1484.91  5211.9 1486.36  5225.5 1488.69
  5241.1 1493.80  5246.9 1494.22  5268.3 1499.00  5283.8 1500.54  5291.6 1500.06
#Mann=6,-1,0
  4602.8   0.035       0  4810.3    0.07       0  4956.4    0.12       0
  5033.0    0.05       0  5037.0    0.12       0  5211.9    0.07       0
Bank Sta=5033,5037
Exp/Cntr=0.3,0.1

Type RM Length L Ch R = 1,7371,471,471,471
BEGIN DESCRIPTION:
Stream0108_DS 16.0
END DESCRIPTION:
XS GIS Cut Line= 3
      2002516.31     13905872.16      2002475.00     13905425.00
      2002225.02     13905225.01
#Sta/Elev= 30
  4546.8 1485.01  4584.1 1481.89  4604.2 1481.98  4684.5 1477.18  4704.6 1477.40
  4721.9 1475.64  4831.5 1470.54  4941.1 1467.07  4965.7 1467.53  4985.8 1464.51
  4993.4 1461.45  5003.1 1461.62  5011.3 1460.42  5017.5 1460.85  5021.9 1459.24
  5022.1 1458.74  5025.9 1459.24  5031.9 1459.43  5038.3 1462.76  5052.7 1464.80
  5087.9 1465.03  5110.3 1462.48  5116.7 1465.11  5123.9 1466.77  5145.5 1475.13
  5166.3 1476.09  5259.2 1487.18  5265.6 1489.14  5279.2 1490.62  5316.0 1492.91
#Mann=5,-1,0
  4546.8   0.035       0  5011.3    0.07       0  5021.9   0.035       0
  5025.9    0.07       0  5279.2   0.035       0
Bank Sta=5021.9,5025.9
Exp/Cntr=0.3,0.1

Type RM Length L Ch R = 1,6900,426,426,426
BEGIN DESCRIPTION:
Stream0108_DS 15.0
END DESCRIPTION:
XS GIS Cut Line= 3
      2002975.01     13905425.02      2002825.00     13905125.00
      2002574.98     13905075.00
#Sta/Elev= 30
  4664.3 1470.39  4667.1 1470.39  4672.7 1469.44  4682.6 1468.97  4700.7 1467.90
  4723.0 1465.91  4739.8 1465.09  4745.4 1464.34  4874.0 1458.02  4896.3 1456.44
  4924.3 1455.21  4946.6 1455.29  4963.4 1454.34  4977.4 1454.02  4983.8 1452.06
  4984.0 1451.56  4987.5 1451.56  4987.8 1452.06  4996.9 1452.97  5002.3 1452.97
  5009.9 1454.10  5020.1 1454.21  5040.5 1455.66  5071.1 1457.04  5081.3 1457.90
  5173.1 1460.23  5183.3 1459.57  5193.5 1459.97  5224.1 1463.22  5254.7 1464.01
#Mann=4,-1,0
  4664.3    0.07       0  4682.6   0.035       0  4983.8   0.035       0
  4987.8   0.035       0
Bank Sta=4983.8,4987.8
Exp/Cntr=0.3,0.1

Type RM Length L Ch R = 1,6474,482,482,482
BEGIN DESCRIPTION:
Stream0108_DS 14.0
END DESCRIPTION:
XS GIS Cut Line= 3
      2003224.98     13904874.99      2003075.00     13904825.00
      2002568.09     13904823.96
#Sta/Elev= 30
  4842.0 1459.64  4852.5 1459.07  4863.1 1459.28  4873.6 1458.70  4884.1 1457.46
  4936.8 1452.57  4979.0 1449.70  4995.5 1445.02  4995.7 1444.52  4999.2 1444.52
  4999.5 1445.02  5002.6 1445.02  5010.1 1449.56  5020.1 1450.73  5060.1 1449.18
  5150.1 1451.11  5160.1 1451.11  5170.1 1451.64  5180.1 1453.39  5190.1 1453.20
  5200.1 1452.07  5210.1 1452.37  5260.1 1455.35  5280.1 1455.97  5320.1 1456.44
  5340.1 1456.98  5370.1 1459.04  5440.1 1461.95  5490.1 1465.34  5507.0 1466.87
#Mann=3,-1,0
  4842.0   0.035       0  4995.5   0.035       0  4999.5   0.035       0
Bank Sta=4995.5,4999.5
Exp/Cntr=0.3,0.1

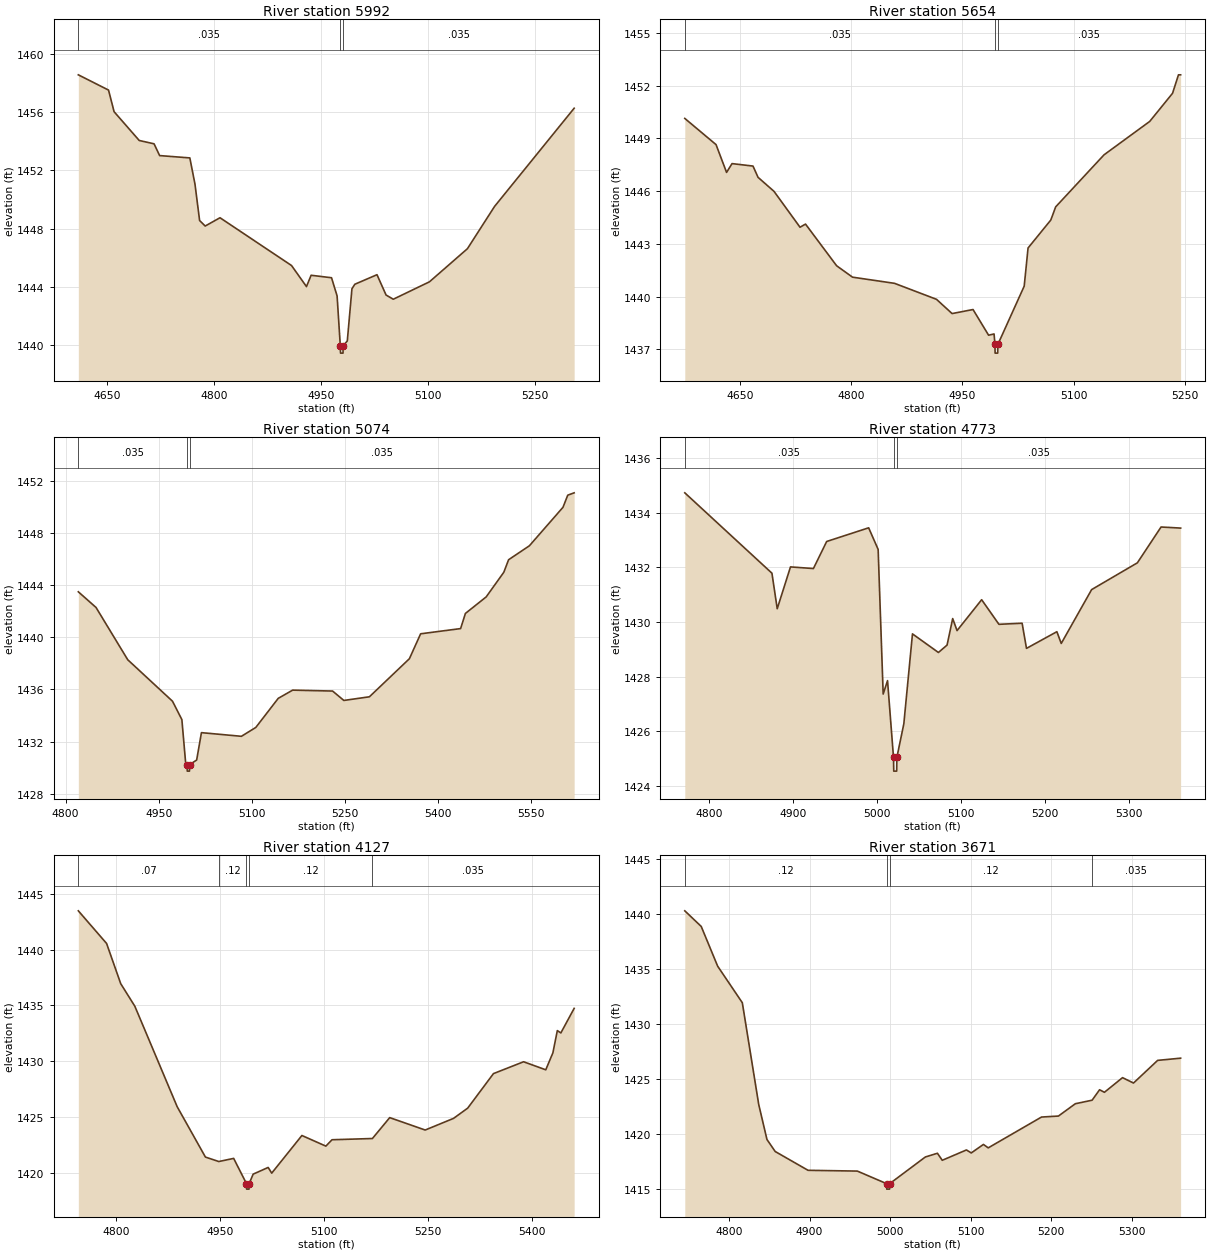
Type RM Length L Ch R = 1,5992,338,338,338
BEGIN DESCRIPTION:
Stream0108_DS 13.0
END DESCRIPTION:
XS GIS Cut Line= 3
      2003325.00     13904675.00      2003075.00     13904375.00
      2002775.05     13904325.01
#Sta/Elev= 30
  4610.0 1458.58  4652.3 1457.53  4660.1 1456.04  4695.3 1454.06  4716.1 1453.83
  4723.9 1453.02  4766.2 1452.86  4773.4 1451.06  4779.9 1448.55  4787.7 1448.17
  4808.5 1448.74  4908.7 1445.45  4929.6 1444.00  4936.1 1444.78  4964.7 1444.61
  4972.5 1443.36  4977.0 1439.92  4977.3 1439.42  4980.8 1439.42  4981.0 1439.92
  4986.8 1440.26  4993.3 1443.85  4997.3 1444.16  5028.4 1444.82  5041.1 1443.42
  5051.2 1443.13  5101.9 1444.33  5155.1 1446.61  5193.1 1449.52  5304.6 1456.28
#Mann=3,-1,0
  4610.0   0.035       0  4977.0   0.035       0  4981.0   0.035       0
Bank Sta=4977,4981
Exp/Cntr=0.3,0.1

Type RM Length L Ch R = 1,5654,580,580,580
BEGIN DESCRIPTION:
Stream0108_DS 12.0
END DESCRIPTION:
XS GIS Cut Line= 3
      2003425.00     13904375.00      2003115.27     13904088.28
      2002874.35     13904031.85
#Sta/Elev= 30
  4575.1 1450.13  4617.3 1448.64  4631.5 1447.06  4638.9 1447.56  4667.2 1447.42
  4674.0 1446.78  4695.6 1445.98  4730.7 1443.94  4738.1 1444.12  4780.1 1441.75
  4801.6 1441.10  4858.3 1440.75  4915.0 1439.84  4936.0 1439.03  4964.3 1439.26
  4985.3 1437.80  4992.7 1437.87  4993.9 1437.28  4994.1 1436.78  4997.6 1436.78
  4997.9 1437.28  5033.4 1440.59  5038.6 1442.76  5069.3 1444.35  5075.9 1445.10
  5141.2 1448.06  5202.9 1449.96  5233.7 1451.56  5241.7 1452.61  5244.6 1452.61
#Mann=3,-1,0
  4575.1   0.035       0  4993.9   0.035       0  4997.9   0.035       0
Bank Sta=4993.9,4997.9
Exp/Cntr=0.3,0.1

Type RM Length L Ch R = 1,5074,301,301,301
BEGIN DESCRIPTION:
Stream0108_DS 11.0
END DESCRIPTION:
XS GIS Cut Line= 3
      2003675.00     13904075.00      2003575.00     13903925.00
      2002975.04     13903775.01
#Sta/Elev= 30
  4820.4 1443.49  4848.9 1442.29  4900.0 1438.28  4972.1 1435.10  4987.2 1433.69
  4993.2 1430.41  4995.7 1430.24  4995.9 1429.74  4999.4 1429.74  4999.7 1430.24
  5011.0 1430.59  5018.7 1432.69  5083.1 1432.41  5106.3 1433.09  5142.4 1435.32
  5165.6 1435.95  5230.0 1435.88  5248.1 1435.16  5289.3 1435.44  5353.7 1438.36
  5371.8 1440.27  5436.2 1440.67  5443.9 1441.83  5477.4 1443.10  5505.8 1444.99
  5513.5 1445.95  5547.0 1447.02  5601.1 1449.97  5608.8 1450.90  5619.1 1451.08
#Mann=3,-1,0
  4820.4   0.035       0  4995.7   0.035       0  4999.7   0.035       0
Bank Sta=4995.7,4999.7
Exp/Cntr=0.3,0.1

Type RM Length L Ch R = 1,4773,646,646,646
BEGIN DESCRIPTION:
Stream0108_DS 10.0
END DESCRIPTION:
XS GIS Cut Line= 3
      2003875.02     13903775.01      2003679.50     13903662.93
      2003325.01     13903575.00
#Sta/Elev= 30
  4770.8 1434.72  4874.6 1431.78  4880.9 1430.48  4896.7 1432.01  4924.0 1431.95
  4939.8 1432.94  4989.8 1433.44  5001.1 1432.65  5007.1 1427.36  5012.3 1427.85
  5019.4 1425.04  5019.7 1424.54  5023.2 1424.54  5023.4 1425.04  5031.7 1426.27
  5042.0 1429.56  5072.9 1428.88  5083.2 1429.15  5089.9 1430.12  5095.1 1429.68
  5124.4 1430.81  5145.0 1429.91  5172.6 1429.95  5177.8 1429.03  5214.0 1429.64
  5219.2 1429.21  5255.4 1431.18  5309.9 1432.16  5338.1 1433.47  5361.4 1433.43
#Mann=3,-1,0
  4770.8   0.035       0  5019.4   0.035       0  5023.4   0.035       0
Bank Sta=5019.4,5023.4
Exp/Cntr=0.3,0.1

Type RM Length L Ch R = 1,4127,456,456,456
BEGIN DESCRIPTION:
Stream0108_DS 9.0
END DESCRIPTION:
XS GIS Cut Line= 3
      2004174.97     13903324.99      2003925.00     13903275.00
      2003474.99     13903175.00
#Sta/Elev= 30
  4745.4 1443.47  4786.2 1440.55  4806.6 1436.95  4827.0 1434.93  4888.1 1425.94
  4928.9 1421.43  4948.2 1421.03  4969.7 1421.31  4988.1 1419.06  4988.4 1418.56
  4991.9 1418.56  4992.1 1419.06  4997.8 1419.90  5019.5 1420.50  5024.6 1419.99
  5068.2 1423.36  5102.8 1422.41  5111.7 1422.98  5170.0 1423.09  5195.0 1424.96
  5246.2 1423.85  5287.1 1424.89  5307.6 1425.81  5344.8 1428.90  5388.3 1429.96
  5420.3 1429.24  5430.6 1430.76  5437.0 1432.75  5442.1 1432.54  5461.3 1434.74
#Mann=5,-1,0
  4745.4    0.07       0  4948.2    0.12       0  4988.1    0.05       0
  4992.1    0.12       0  5170.0   0.035       0
Bank Sta=4988.1,4992.1
Exp/Cntr=0.3,0.1

Type RM Length L Ch R = 1,3671,479,479,479
BEGIN DESCRIPTION:
Stream0108_DS 8.0
END DESCRIPTION:
XS GIS Cut Line= 3
      2004225.03     13902925.01      2003975.00     13902875.00
      2003675.03     13903074.98
#Sta/Elev= 30
  4745.1 1440.29  4765.5 1438.87  4785.9 1435.26  4816.5 1431.94  4836.9 1422.68
  4847.1 1419.51  4857.3 1418.42  4898.1 1416.71  4959.3 1416.64  4995.5 1415.50
  4995.8 1415.00  4999.3 1415.00  4999.5 1415.50  5043.7 1417.92  5058.7 1418.26
  5064.7 1417.62  5094.7 1418.56  5100.7 1418.29  5115.8 1419.06  5121.8 1418.75
  5187.9 1421.55  5208.9 1421.64  5229.9 1422.76  5250.7 1423.08  5260.0 1424.03
  5266.0 1423.80  5288.5 1425.13  5302.1 1424.64  5332.1 1426.70  5360.6 1426.90
#Mann=4,-1,0
  4745.1    0.12       0  4995.5    0.05       0  4999.5    0.12       0
  5250.7   0.035       0
Bank Sta=4995.5,4999.5
Exp/Cntr=0.3,0.1

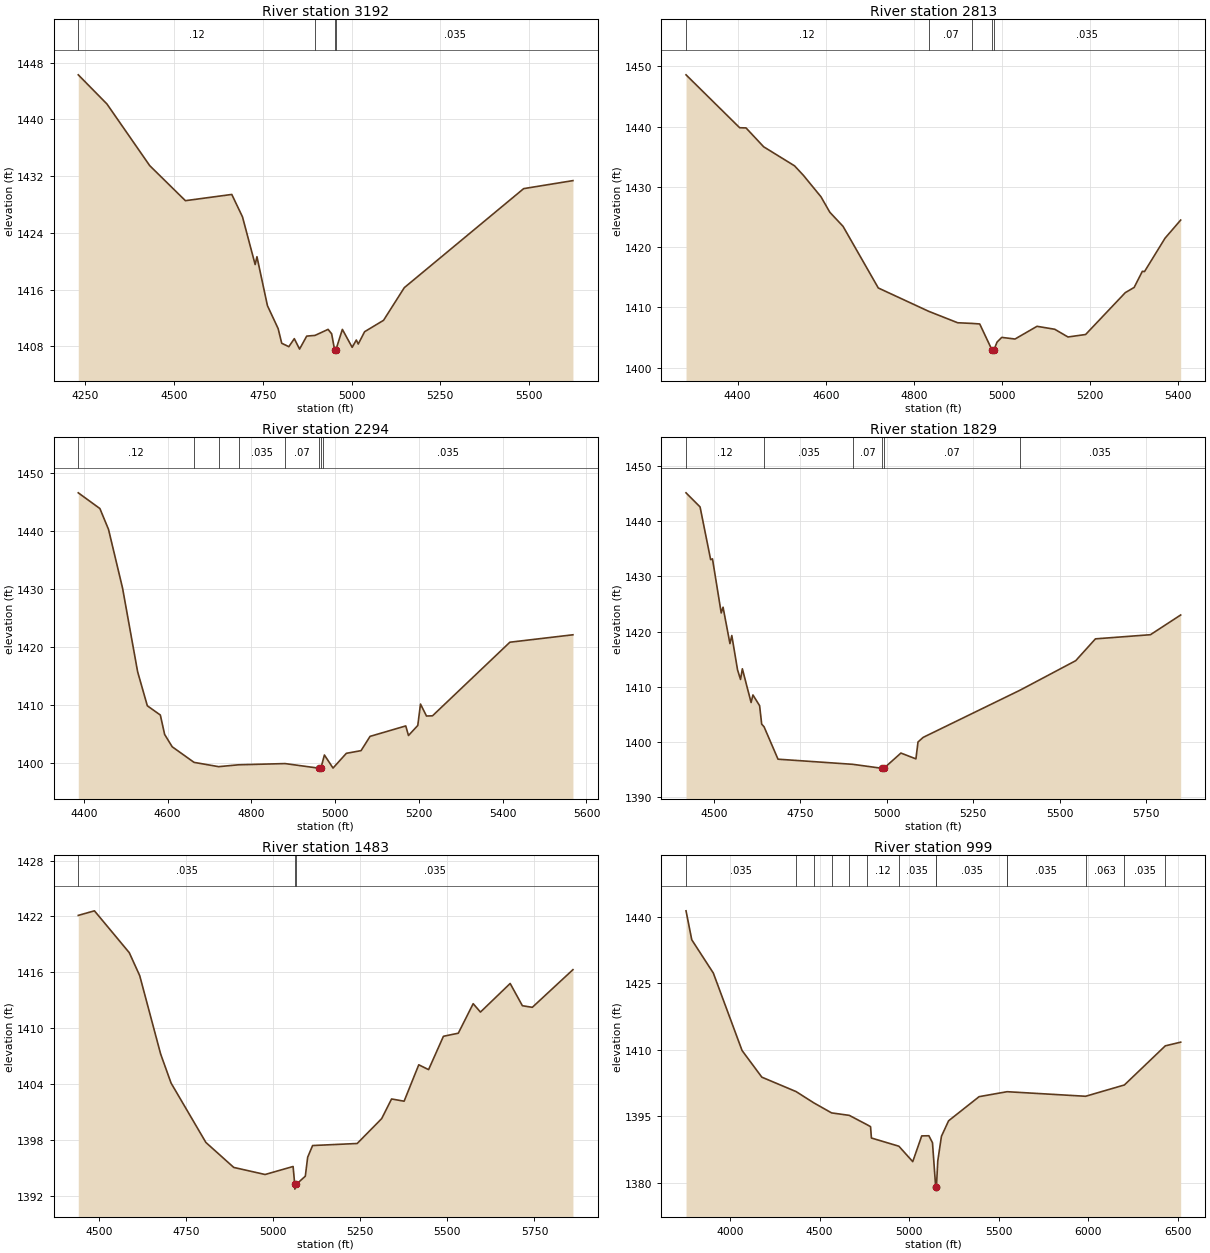
Type RM Length L Ch R = 1,3192,379,379,379
BEGIN DESCRIPTION:
Stream0108_DS 7.0
END DESCRIPTION:
XS GIS Cut Line= 3
      2004545.39     13902545.31      2003775.00     13902475.00
      2003204.24     13902714.58
#Sta/Elev= 30
  4230.7 1446.30  4311.4 1442.19  4431.9 1433.49  4532.3 1428.55  4662.9 1429.43
  4693.0 1426.27  4728.7 1419.54  4733.7 1420.65  4763.3 1413.74  4793.4 1410.51
  4803.5 1408.44  4823.5 1407.96  4838.9 1409.09  4853.7 1407.62  4873.8 1409.45
  4897.2 1409.55  4934.0 1410.40  4944.0 1409.78  4952.2 1407.55  4952.4 1407.05
  4956.2 1407.55  4974.2 1410.40  5001.8 1407.87  5013.5 1408.90  5018.9 1408.33
  5036.8 1410.07  5090.2 1411.68  5148.5 1416.28  5484.6 1430.25  5623.3 1431.38
#Mann=4,-1,0
  4230.7    0.12       0  4897.2   0.035       0  4952.2   0.035       0
  4956.2   0.035       0
Bank Sta=4952.2,4956.2
Exp/Cntr=0.3,0.1

Type RM Length L Ch R = 1,2813,519,519,519
BEGIN DESCRIPTION:
Stream0108_DS 6.0
END DESCRIPTION:
XS GIS Cut Line= 3
      2004541.07     13902163.37      2003831.41     13902143.84
      2003419.51     13902126.49
#Sta/Elev= 30
  4283.0 1448.60  4404.7 1439.82  4419.1 1439.79  4459.1 1436.66  4529.2 1433.50
  4549.2 1431.93  4589.2 1428.36  4609.2 1425.80  4639.2 1423.46  4719.2 1413.23
  4833.5 1409.36  4899.3 1407.46  4932.0 1407.35  4949.3 1407.26  4977.3 1402.92
  4977.6 1402.42  4981.3 1402.92  4988.6 1404.25  4999.3 1405.03  5029.4 1404.76
  5079.3 1406.87  5119.5 1406.38  5149.5 1405.10  5189.5 1405.51  5279.6 1412.46
  5299.6 1413.32  5318.2 1415.99  5323.2 1415.96  5369.7 1421.49  5405.2 1424.50
#Mann=5,-1,0
  4283.0    0.12       0  4833.5    0.07       0  4932.0   0.035       0
  4977.3   0.035       0  4981.3   0.035       0
Bank Sta=4977.3,4981.3
Exp/Cntr=0.3,0.1

Type RM Length L Ch R = 1,2294,465,465,465
BEGIN DESCRIPTION:
Stream0108_DS 5.0
END DESCRIPTION:
XS GIS Cut Line= 3
      2004375.01     13901525.00      2003775.00     13901675.00
      2003343.15     13902035.31
#Sta/Elev= 30
  4386.8 1446.51  4438.4 1443.80  4459.0 1440.21  4492.5 1430.09  4528.5 1415.67
  4551.7 1409.80  4582.7 1408.21  4593.0 1404.86  4611.0 1402.74  4663.2 1400.05
  4721.9 1399.31  4769.4 1399.63  4880.5 1399.84  4962.0 1399.04  4962.3 1398.54
  4966.0 1399.04  4970.5 1400.26  4974.4 1401.32  4995.0 1399.07  5026.8 1401.61
  5061.9 1402.07  5083.4 1404.53  5168.6 1406.33  5175.1 1404.68  5197.3 1406.41
  5203.8 1410.10  5218.1 1408.04  5232.4 1408.07  5417.2 1420.76  5567.7 1422.04
#Mann=8,-1,0
  4386.8    0.12       0  4663.2   0.035       0  4721.9    0.07       0
  4769.4   0.035       0  4880.5    0.07       0  4962.0   0.035       0
  4966.0    0.07       0  4970.5   0.035       0
Bank Sta=4962,4966
Exp/Cntr=0.3,0.1

Type RM Length L Ch R = 1,1829,346,346,346
BEGIN DESCRIPTION:
Stream0108_DS 4.0
END DESCRIPTION:
XS GIS Cut Line= 3
      2004325.01     13901475.00      2003775.00     13901275.00
      2003304.04     13901976.77
#Sta/Elev= 30
  4419.9 1445.14  4460.5 1442.59  4491.1 1433.05  4496.4 1433.19  4521.7 1423.40
  4527.0 1424.44  4546.9 1417.85  4552.3 1419.31  4568.9 1413.09  4577.5 1411.36
  4582.8 1413.29  4608.1 1407.19  4613.4 1408.56  4632.7 1406.61  4638.7 1403.27
  4645.6 1402.79  4685.9 1396.93  4902.4 1396.00  4987.8 1395.27  4988.1 1394.77
  4991.8 1395.27  5041.3 1398.04  5084.7 1396.99  5090.7 1400.04  5105.7 1400.88
  5385.8 1409.42  5546.8 1414.76  5603.8 1418.71  5762.8 1419.46  5850.3 1423.03
#Mann=6,-1,0
  4419.9    0.12       0  4645.6   0.035       0  4902.4    0.07       0
  4987.8    0.05       0  4991.8    0.07       0  5385.8   0.035       0
Bank Sta=4987.8,4991.8
Exp/Cntr=0.3,0.1

Type RM Length L Ch R = 1,1483,484,484,484
BEGIN DESCRIPTION:
Stream0108_DS 3.0
END DESCRIPTION:
XS GIS Cut Line= 3
      2004351.42     13900991.93      2003791.72     13900991.67
      2003222.35     13901636.87
#Sta/Elev= 30
  4440.3 1422.11  4486.7 1422.60  4586.7 1418.11  4616.7 1415.64  4676.7 1407.24
  4706.7 1404.11  4806.7 1397.73  4886.7 1395.05  4976.7 1394.29  5057.1 1395.15
  5061.8 1393.22  5062.0 1392.72  5065.8 1393.22  5092.2 1394.11  5098.9 1396.14
  5113.1 1397.40  5241.1 1397.62  5311.4 1400.29  5339.8 1402.40  5375.8 1402.16
  5417.9 1406.07  5446.1 1405.55  5488.7 1409.13  5531.4 1409.46  5574.1 1412.63
  5595.0 1411.73  5680.3 1414.80  5715.4 1412.41  5743.9 1412.24  5860.5 1416.28
#Mann=3,-1,0
  4440.3   0.035       0  5061.8   0.035       0  5065.8   0.035       0
Bank Sta=5061.8,5065.8
Exp/Cntr=0.3,0.1

Type RM Length L Ch R = 1,999,296,296,296
BEGIN DESCRIPTION:
Stream0108_DS 2.0
END DESCRIPTION:
XS GIS Cut Line= 3
      2004646.93     13900718.71      2003405.02     13900804.92
      2001890.85     13900851.75
#Sta/Elev= 30
  3755.1 1441.37  3787.1 1434.84  3907.4 1427.33  4067.8 1409.85  4178.1 1403.84
  4369.1 1400.59  4468.2 1398.04  4567.2 1395.78  4666.2 1395.22  4765.2 1393.11
  4784.5 1392.68  4789.5 1390.11  4942.8 1388.26  5020.0 1384.78  5070.1 1390.59
  5110.1 1390.62  5130.1 1389.05  5148.0 1379.08  5148.3 1378.58  5152.1 1379.08
  5159.7 1384.96  5180.1 1390.50  5220.1 1394.00  5390.2 1399.44  5543.2 1400.54
  5547.3 1400.56  5984.4 1399.53  6200.8 1402.08  6429.2 1410.91  6514.9 1411.74
#Mann=14,-1,0
  3755.1   0.035       0  4369.1    0.07       0  4468.2    0.12       0
  4567.2    0.12       0  4666.2    0.12       0  4765.2    0.12       0
  4942.8   0.035       0  5148.0   0.035       0  5152.1   0.035       0
  5543.2    0.07       0  5547.3   0.035       0  5984.4   0.063       0
  6200.8   0.035       0  6429.2   0.063       0
Bank Sta=5148,5152.1
Exp/Cntr=0.3,0.1

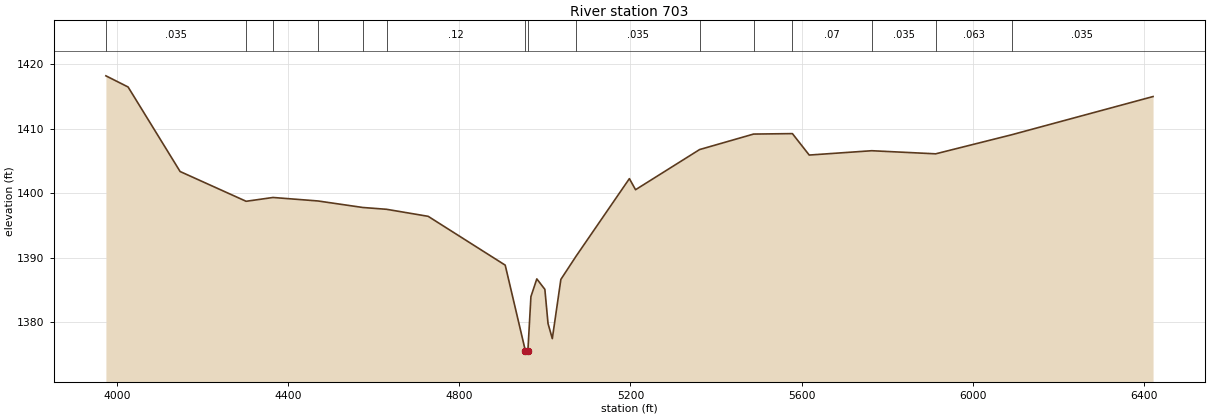
Type RM Length L Ch R = 1,703,0,0,0
BEGIN DESCRIPTION:
Stream0108_DS 1.0
END DESCRIPTION:
XS GIS Cut Line= 4
      2004314.08     13900405.31      2003670.75     13900618.17
      2003322.41     13900630.72      2001901.98     13900693.16
#Sta/Elev= 30
  3973.8 1418.20  4025.7 1416.47  4147.3 1403.38  4301.6 1398.77  4364.5 1399.36
  4469.5 1398.82  4574.4 1397.81  4629.9 1397.53  4727.2 1396.44  4907.3 1388.88
  4954.5 1375.60  4955.0 1375.10  4960.3 1375.60  4967.4 1384.00  4981.2 1386.75
  5000.0 1385.13  5007.4 1379.84  5017.4 1377.50  5037.4 1386.67  5072.6 1390.23
  5197.6 1402.28  5212.0 1400.56  5361.7 1406.78  5487.9 1409.18  5578.7 1409.25
  5618.0 1405.93  5764.2 1406.60  5913.6 1406.12  6091.1 1409.07  6421.8 1414.99
#Mann=15,-1,0
  3973.8   0.035       0  4301.6    0.07       0  4364.5   0.035       0
  4469.5    0.07       0  4574.4    0.12       0  4629.9    0.12       0
  4954.5    0.05       0  4960.3    0.12       0  5072.6   0.035       0
  5361.7    0.07       0  5487.9   0.035       0  5578.7    0.07       0
  5764.2   0.035       0  5913.6   0.063       0  6091.1   0.035       0
Bank Sta=4954.5,4960.3
Exp/Cntr=0.3,0.1

Chan Stop Cuts=-1