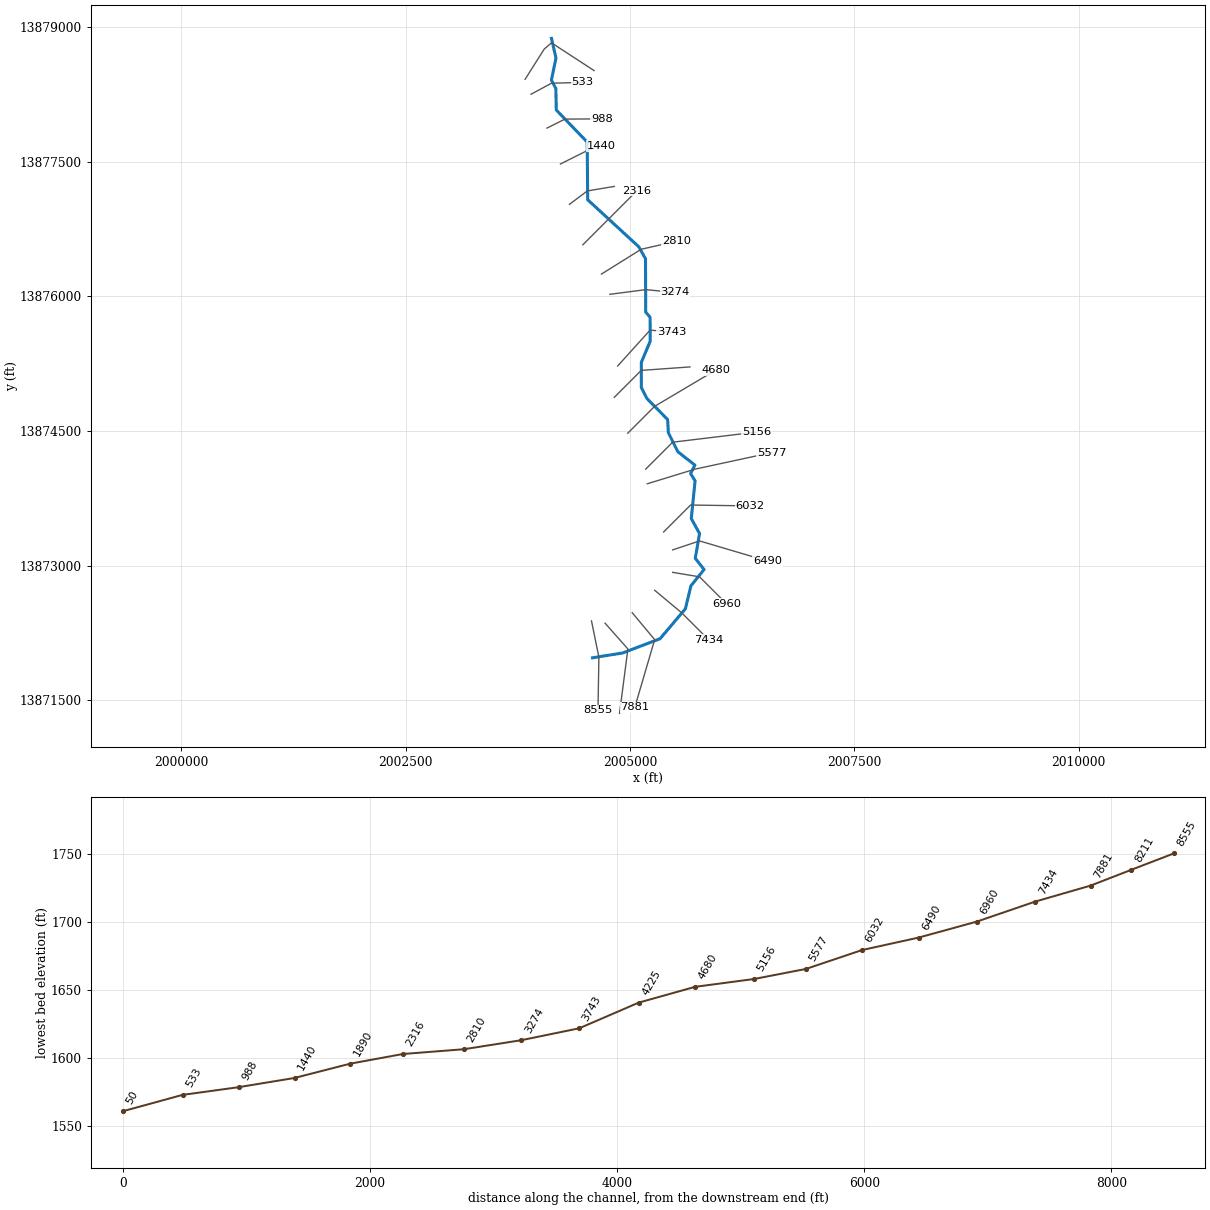
--- Stream0109_DS.prj (project) ---

Proj Title=Stream0109_DS Base Level Engineering
Current Plan=p01
Default Exp/Contr=0.3,0.1
English Units
Geom File=g01
Flow File=f01
Plan File=p01
BEGIN DESCRIPTION:
Stream0109_DS
END DESCRIPTION:

--- Stream0109_DS.p01 (plan) ---

Plan Title=Multiple Run
Short Identifier=Multiple
Geom File=g01
Flow File=f01
Subcritical Flow
K Sum by GR= 0
Std Step Tol= 0.01
Critical Tol= 0.01
Num of Std Step Trials= 20
Max Error Tol= 0.3
Flow Tol Ratio= 0.001
Split Flow NTrial= 30
Split Flow Tol= 0.02
Split Flow Ratio= 0.02
Log Output Level= 0
Friction Slope Method= 1
Unsteady Friction Slope Method= 2
Unsteady Bridges Friction Slope Method= 1
Parabolic Critical Depth
Global Vel Dist=  1 , 1 , 1
Global Log Level= 0
CheckData=True
Encroach Param= -1, 0, 0, 0
BEGIN DESCRIPTION:
Multiple Run
END DESCRIPTION:

--- Stream0109_DS.f01 (steady flow) ---

Flow Title=Multiple
Number of Profiles=7
Profile Names=10-year,25-year,50-year,1pct_min,100-year,1pct_plu,500-year
River Rch & RM= Stream0109_DS,Reach-1,8555
     314     494     654     422     842    1680    1376
River Rch & RM= Stream0109_DS,Reach-1,8211
     603     993    1354     899    1793    3578    3103
River Rch & RM= Stream0109_DS,Reach-1,5577
     836    1410    1955    1316    2626    5240    4686
River Rch & RM= Stream0109_DS,Reach-1,3274
    1249    2157    3035    2071    4132    8245    7579
River Rch & RM= Stream0109_DS,Reach-1,50
    2148    3807    5454    3778    7537   15039   14264
Boundary for River Rch & Prof#=Stream0109_DS,Reach-1,1
Up Type=0
Dn Type=3
Dn Slope=0.005
Boundary for River Rch & Prof#=Stream0109_DS,Reach-1,2
Up Type=0
Dn Type=3
Dn Slope=0.005
Boundary for River Rch & Prof#=Stream0109_DS,Reach-1,3
Up Type=0
Dn Type=3
Dn Slope=0.005
Boundary for River Rch & Prof#=Stream0109_DS,Reach-1,4
Up Type=0
Dn Type=3
Dn Slope=0.005
Boundary for River Rch & Prof#=Stream0109_DS,Reach-1,5
Up Type=0
Dn Type=3
Dn Slope=0.005
Boundary for River Rch & Prof#=Stream0109_DS,Reach-1,6
Up Type=0
Dn Type=3
Dn Slope=0.005
Boundary for River Rch & Prof#=Stream0109_DS,Reach-1,7
Up Type=0
Dn Type=3
Dn Slope=0.005

--- Stream0109_DS.g01 (geometry) ---

Geom Title=Existing Conditions

River Reach=Stream0109_DS,Reach-1
Reach XY= 30
      2004582.24     13871972.58      2004918.73     13872026.99
      2005335.10     13872185.39      2005617.14     13872518.83
      2005678.61     13872773.50      2005825.37     13872956.59
      2005727.06     13873080.86      2005774.96     13873356.67
      2005682.76     13873525.08      2005725.36     13873945.15
      2005675.00     13874025.00      2005723.43     13874119.64
      2005533.13     13874268.93      2005427.25     13874480.93
      2005419.53     13874627.45      2005188.62     13874861.78
      2005126.20     13874985.50      2005126.22     13875264.50
      2005225.20     13875499.92      2005223.90     13875765.45
      2005175.00     13875825.00      2005172.76     13876419.07
      2005098.71     13876551.82      2004528.53     13877076.45
      2004522.94     13877719.15      2004178.54     13878076.46
      2004173.78     13878314.50      2004124.56     13878411.18
      2004175.28     13878654.82      2004125.00     13878875.00

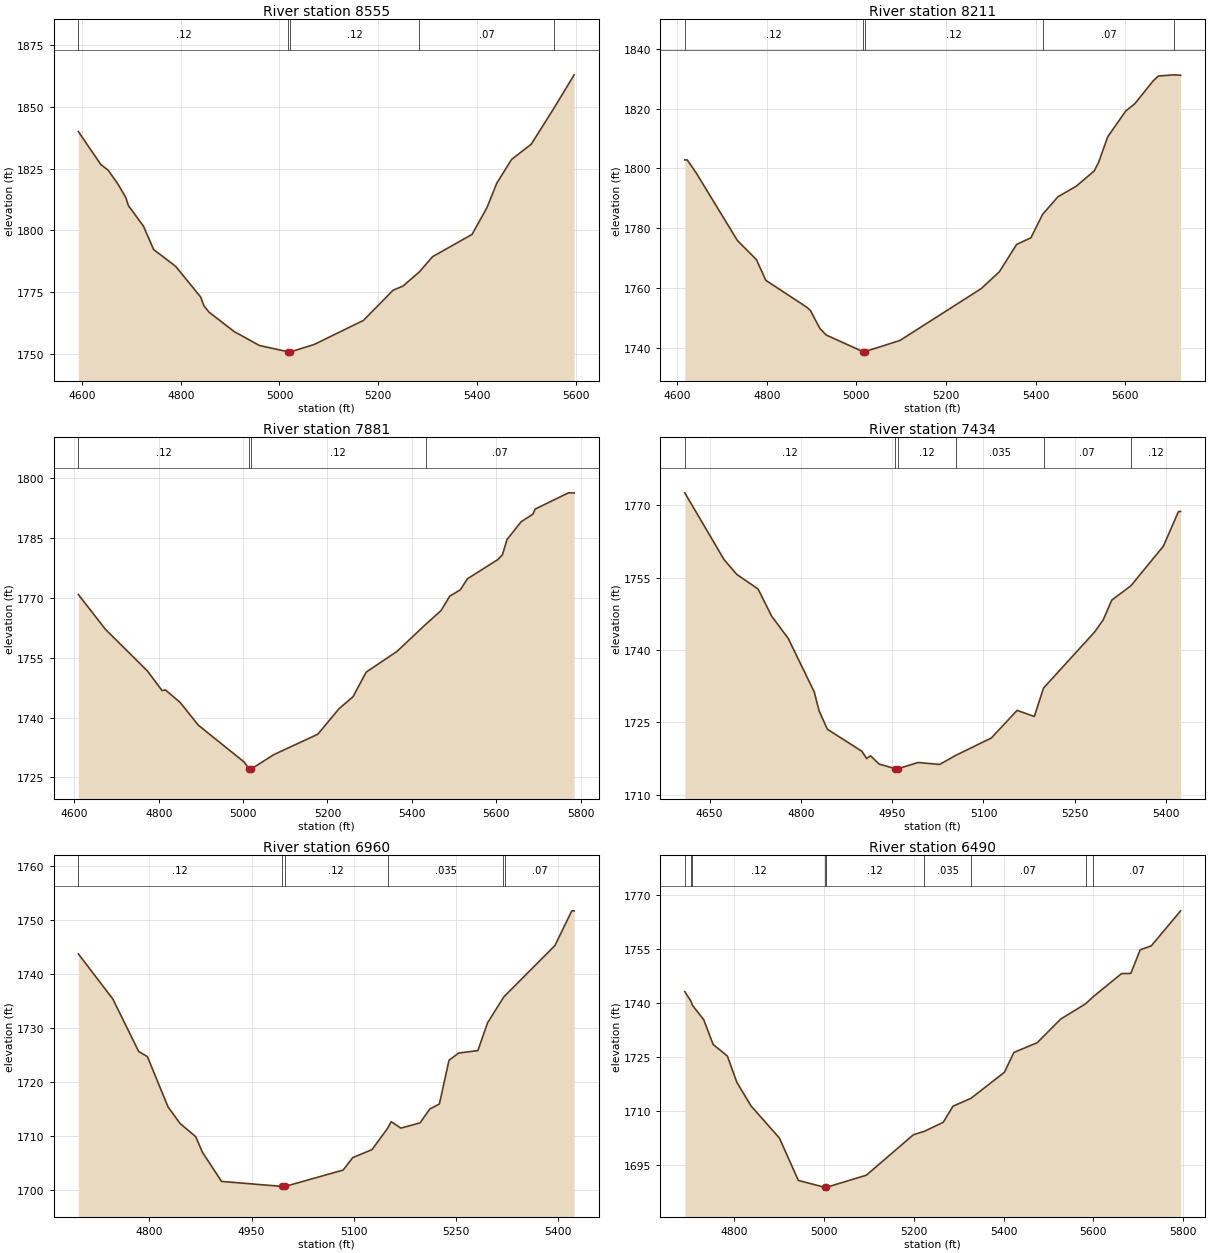
Type RM Length L Ch R = 1,8555,344,344,344
BEGIN DESCRIPTION:
Stream0109_DS 19.0
END DESCRIPTION:
XS GIS Cut Line= 3
      2004570.90     13872384.48      2004653.39     13871979.24
      2004643.18     13871388.18
#Sta/Elev= 30
  4592.4 1839.98  4637.9 1826.65  4653.1 1824.26  4673.5 1818.45  4688.5 1813.28
  4693.9 1809.97  4724.5 1801.62  4744.9 1792.21  4789.6 1785.40  4840.2 1772.98
  4847.0 1769.38  4857.2 1766.85  4908.2 1758.97  4959.3 1753.34  5018.2 1750.74
  5018.4 1750.24  5022.2 1750.74  5070.2 1753.73  5170.2 1763.50  5230.2 1775.72
  5250.2 1777.40  5283.4 1783.13  5310.2 1789.30  5390.3 1798.33  5420.3 1809.12
  5440.3 1819.05  5470.3 1828.68  5510.3 1834.88  5556.5 1849.55  5597.1 1862.94
#Mann=5,-1,0
  4592.4    0.12       0  5018.2    0.05       0  5022.2    0.12       0
  5283.4    0.07       0  5556.5    0.12       0
Bank Sta=5018.2,5022.2
Exp/Cntr=0.3,0.1

Type RM Length L Ch R = 1,8211,330,330,330
BEGIN DESCRIPTION:
Stream0109_DS 18.0
END DESCRIPTION:
XS GIS Cut Line= 3
      2004722.57     13872358.28      2004976.53     13872071.31
      2004883.25     13871353.55
#Sta/Elev= 30
  4616.8 1802.85  4622.3 1802.85  4642.2 1798.52  4734.2 1775.90  4776.8 1769.48
  4797.7 1762.57  4889.7 1753.51  4897.3 1752.46  4918.2 1746.51  4932.4 1744.28
  5014.5 1738.71  5014.7 1738.21  5018.5 1738.71  5097.1 1742.44  5278.5 1759.79
  5319.0 1765.40  5357.6 1774.56  5389.6 1776.80  5415.7 1784.66  5450.1 1790.55
  5490.4 1794.02  5530.7 1799.13  5540.8 1802.04  5561.0 1810.58  5601.3 1819.23
  5621.5 1821.64  5661.8 1829.18  5674.2 1830.92  5709.2 1831.32  5723.8 1831.17
#Mann=5,-1,0
  4616.8    0.12       0  5014.5    0.05       0  5018.5    0.12       0
  5415.7    0.07       0  5709.2    0.12       0
Bank Sta=5014.5,5018.5
Exp/Cntr=0.3,0.1

Type RM Length L Ch R = 1,7881,447,447,447
BEGIN DESCRIPTION:
Stream0109_DS 17.0
END DESCRIPTION:
XS GIS Cut Line= 3
      2005024.98     13872475.03      2005275.00     13872175.00
      2005053.65     13871422.12
#Sta/Elev= 30
  4609.4 1770.84  4673.9 1762.08  4772.8 1751.72  4807.9 1746.76  4815.8 1746.92
  4850.9 1743.77  4893.9 1738.08  5002.6 1728.84  5014.6 1727.07  5014.9 1726.57
  5018.6 1727.07  5072.9 1730.71  5177.1 1735.82  5227.2 1742.20  5260.5 1745.21
  5291.8 1751.39  5364.8 1756.57  5432.5 1763.33  5469.0 1766.79  5489.8 1770.42
  5515.0 1772.02  5531.5 1774.76  5604.5 1779.64  5614.9 1780.85  5625.5 1784.60
  5658.8 1789.05  5687.0 1790.98  5692.2 1792.25  5771.3 1796.32  5784.7 1796.29
#Mann=4,-1,0
  4609.4    0.12       0  5014.6    0.05       0  5018.6    0.12       0
  5432.5    0.07       0
Bank Sta=5014.6,5018.6
Exp/Cntr=0.3,0.1

Type RM Length L Ch R = 1,7434,474,474,474
BEGIN DESCRIPTION:
Stream0109_DS 16.0
END DESCRIPTION:
XS GIS Cut Line= 3
      2005274.98     13872725.01      2005575.00     13872475.00
      2005875.00     13872175.00
#Sta/Elev= 30
  4609.2 1772.59  4673.7 1758.74  4694.5 1755.68  4729.6 1752.64  4751.8 1747.03
  4779.1 1742.40  4822.0 1731.27  4829.9 1727.35  4843.5 1723.55  4900.2 1718.98
  4908.0 1717.47  4914.5 1718.03  4928.8 1716.31  4955.4 1715.36  4955.7 1714.86
  4959.4 1715.36  4992.6 1716.65  5028.0 1716.25  5054.8 1718.15  5112.9 1721.73
  5155.3 1727.46  5183.6 1726.20  5198.7 1732.09  5282.6 1743.71  5296.7 1746.22
  5310.9 1750.33  5342.5 1753.34  5395.7 1761.53  5420.5 1768.72  5424.0 1768.72
#Mann=6,-1,0
  4609.2    0.12       0  4955.4    0.05       0  4959.4    0.12       0
  5054.8   0.035       0  5198.7    0.07       0  5342.5    0.12       0
Bank Sta=4955.4,4959.4
Exp/Cntr=0.3,0.1

Type RM Length L Ch R = 1,6960,470,470,470
BEGIN DESCRIPTION:
Stream0109_DS 15.0
END DESCRIPTION:
XS GIS Cut Line= 3
      2005474.99     13872925.00      2005775.00     13872875.00
      2006074.99     13872575.01
#Sta/Elev= 30
  4695.6 1743.69  4746.3 1735.32  4784.3 1725.59  4797.0 1724.66  4827.4 1715.33
  4845.1 1712.26  4868.0 1709.83  4878.1 1706.89  4906.0 1701.53  4995.2 1700.60
  4995.5 1700.10  4999.2 1700.60  5084.6 1703.63  5098.7 1705.94  5127.0 1707.41
  5150.0 1711.38  5155.3 1712.59  5169.4 1711.40  5197.7 1712.38  5211.9 1714.94
  5226.0 1715.87  5240.2 1723.98  5254.3 1725.31  5282.6 1725.77  5296.7 1730.89
  5320.0 1735.58  5321.8 1735.86  5395.7 1745.22  5420.5 1751.66  5424.0 1751.66
#Mann=6,-1,0
  4695.6    0.12       0  4995.2    0.05       0  4999.2    0.12       0
  5150.0   0.035       0  5320.0    0.12       0  5321.8    0.07       0
Bank Sta=4995.2,4999.2
Exp/Cntr=0.3,0.1

Type RM Length L Ch R = 1,6490,458,458,458
BEGIN DESCRIPTION:
Stream0109_DS 14.0
END DESCRIPTION:
XS GIS Cut Line= 3
      2005475.00     13873175.00      2005775.00     13873275.00
      2006531.41     13873051.03
#Sta/Elev= 30
  4689.5 1743.14  4703.0 1740.55  4706.5 1739.37  4731.7 1735.36  4752.7 1728.49
  4784.4 1725.28  4805.4 1718.03  4837.1 1711.45  4900.3 1702.56  4942.5 1690.79
  5001.1 1688.87  5001.3 1688.37  5005.1 1688.87  5094.1 1692.23  5199.1 1703.46
  5223.4 1704.40  5265.6 1706.93  5287.3 1711.38  5327.1 1713.54  5402.0 1720.79
  5422.9 1726.27  5475.0 1728.98  5527.2 1735.53  5582.8 1739.77  5599.8 1741.74
  5662.8 1748.14  5683.6 1748.21  5704.5 1754.74  5729.2 1755.84  5794.6 1765.56
#Mann=9,-1,0
  4689.5    0.12       0  4703.0    0.07       0  4706.5    0.12       0
  5001.1    0.05       0  5005.1    0.12       0  5223.4   0.035       0
  5327.1    0.07       0  5582.8    0.12       0  5599.8    0.07       0
Bank Sta=5001.1,5005.1
Exp/Cntr=0.3,0.1

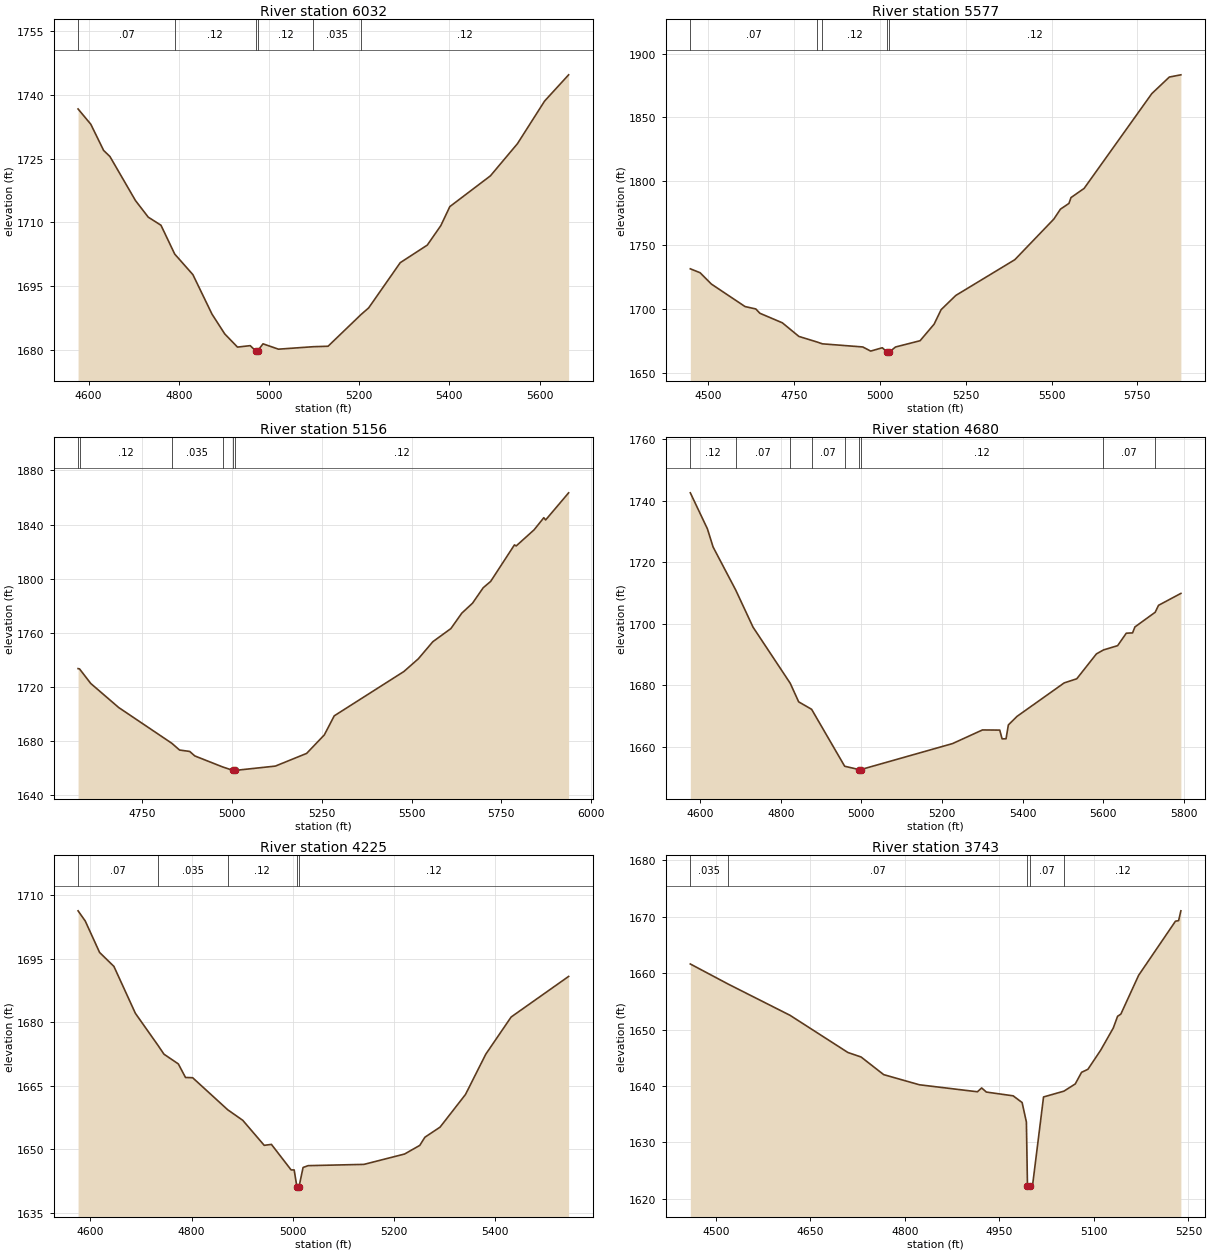
Type RM Length L Ch R = 1,6032,455,455,455
BEGIN DESCRIPTION:
Stream0109_DS 13.0
END DESCRIPTION:
XS GIS Cut Line= 3
      2005375.00     13873375.00      2005675.00     13873675.00
      2006338.37     13873665.19
#Sta/Elev= 30
  4576.6 1736.67  4604.9 1733.06  4633.2 1726.92  4647.3 1725.47  4703.9 1715.11
  4732.2 1711.21  4760.4 1709.31  4790.9 1702.52  4831.2 1697.68  4873.6 1688.38
  4901.9 1683.72  4930.1 1680.63  4958.4 1680.97  4970.6 1679.71  4970.8 1679.21
  4974.6 1679.71  4986.7 1681.40  5020.9 1680.14  5098.0 1680.72  5130.9 1680.83
  5204.2 1688.31  5220.9 1689.85  5290.9 1700.49  5350.9 1704.63  5380.9 1709.21
  5400.9 1713.69  5490.9 1720.93  5550.9 1728.51  5610.9 1738.51  5664.3 1744.70
#Mann=6,-1,0
  4576.6    0.07       0  4790.9    0.12       0  4970.6    0.05       0
  4974.6    0.12       0  5098.0   0.035       0  5204.2    0.12       0
Bank Sta=4970.6,4974.6
Exp/Cntr=0.3,0.1

Type RM Length L Ch R = 1,5577,421,421,421
BEGIN DESCRIPTION:
Stream0109_DS 12.0
END DESCRIPTION:
XS GIS Cut Line= 3
      2005192.55     13873911.72      2005725.00     13874075.00
      2006577.97     13874258.94
#Sta/Elev= 30
  4447.3 1731.37  4475.8 1728.31  4508.5 1719.45  4606.8 1701.79  4638.1 1699.92
  4650.0 1696.54  4715.4 1689.07  4763.7 1678.39  4816.0 1674.07  4832.2 1672.58
  4949.9 1670.13  4972.8 1666.90  5006.8 1669.52  5021.8 1665.80  5022.0 1665.30
  5025.8 1665.80  5045.1 1670.10  5116.8 1675.02  5157.7 1688.00  5178.1 1699.36
  5220.9 1710.51  5393.0 1738.54  5506.5 1770.33  5525.9 1778.15  5550.6 1782.61
  5556.6 1787.21  5594.8 1794.38  5792.0 1868.66  5843.1 1881.66  5876.8 1883.40
#Mann=5,-1,0
  4447.3    0.07       0  4816.0   0.035       0  4832.2    0.12       0
  5021.8    0.05       0  5025.8    0.12       0
Bank Sta=5021.8,5025.8
Exp/Cntr=0.3,0.1

Type RM Length L Ch R = 1,5156,476,476,476
BEGIN DESCRIPTION:
Stream0109_DS 11.0
END DESCRIPTION:
XS GIS Cut Line= 3
      2005175.01     13874075.01      2005475.00     13874375.00
      2006410.65     13874488.03
#Sta/Elev= 30
  4571.0 1733.64  4575.1 1733.41  4606.3 1722.66  4684.1 1704.90  4832.0 1678.50
  4853.8 1673.47  4882.1 1672.43  4896.2 1669.12  4974.2 1660.94  5003.3 1658.39
  5003.6 1657.89  5007.3 1658.39  5120.7 1661.61  5207.8 1670.99  5257.1 1684.66
  5284.7 1698.74  5478.7 1731.48  5519.0 1740.88  5559.3 1753.49  5609.7 1763.21
  5639.9 1774.55  5670.1 1782.00  5699.6 1793.34  5720.5 1798.06  5786.7 1825.02
  5791.7 1824.28  5841.4 1836.15  5868.6 1845.12  5873.7 1843.47  5937.7 1863.50
#Mann=6,-1,0
  4571.0    0.07       0  4575.1    0.12       0  4832.0   0.035       0
  4974.2    0.12       0  5003.3    0.05       0  5007.3    0.12       0
Bank Sta=5003.3,5007.3
Exp/Cntr=0.3,0.1

Type RM Length L Ch R = 1,4680,455,455,455
BEGIN DESCRIPTION:
Stream0109_DS 10.0
END DESCRIPTION:
XS GIS Cut Line= 3
      2004975.03     13874475.03      2005275.00     13874775.00
      2005956.47     13875179.11
#Sta/Elev= 30
  4575.8 1742.56  4618.2 1730.85  4632.3 1724.95  4688.4 1710.97  4731.3 1698.92
  4823.5 1680.70  4844.5 1674.66  4876.6 1672.23  4958.6 1653.73  4994.5 1652.65
  4994.7 1652.15  4998.5 1652.65  5226.1 1661.10  5300.2 1665.53  5343.1 1665.48
  5348.9 1662.64  5358.7 1662.65  5364.5 1667.16  5385.9 1669.93  5502.9 1680.81
  5534.1 1682.15  5582.8 1690.23  5600.3 1691.52  5635.4 1692.91  5656.9 1696.96
  5672.5 1697.06  5678.3 1698.99  5728.5 1703.75  5736.8 1706.01  5792.3 1709.89
#Mann=9,-1,0
  4575.8    0.12       0  4688.4    0.07       0  4823.5   0.035       0
  4876.6    0.07       0  4958.6    0.12       0  4994.5    0.05       0
  4998.5    0.12       0  5600.3    0.07       0  5728.5    0.12       0
Bank Sta=4994.5,4998.5
Exp/Cntr=0.3,0.1

Type RM Length L Ch R = 1,4225,482,482,482
BEGIN DESCRIPTION:
Stream0109_DS 9.0
END DESCRIPTION:
XS GIS Cut Line= 3
      2004824.97     13874874.97      2005125.00     13875175.00
      2005668.21     13875213.80
#Sta/Elev= 30
  4575.8 1706.37  4590.0 1703.96  4618.3 1696.53  4646.6 1693.23  4689.0 1682.14
  4733.8 1674.54  4745.5 1672.47  4773.8 1670.18  4788.0 1666.97  4802.1 1666.91
  4871.4 1659.33  4901.1 1656.84  4943.5 1650.92  4957.7 1651.15  4996.6 1645.11
  5002.6 1645.11  5008.1 1641.07  5008.4 1640.57  5012.1 1641.07  5020.2 1645.69
  5030.2 1646.12  5140.5 1646.42  5220.7 1648.87  5250.7 1650.91  5260.8 1652.84
  5290.8 1655.23  5341.0 1662.95  5381.1 1672.48  5431.2 1681.27  5544.7 1690.86
#Mann=5,-1,0
  4575.8    0.07       0  4733.8   0.035       0  4871.4    0.12       0
  5008.1    0.05       0  5012.1    0.12       0
Bank Sta=5008.1,5012.1
Exp/Cntr=0.3,0.1

Type RM Length L Ch R = 1,3743,469,469,469
BEGIN DESCRIPTION:
Stream0109_DS 8.0
END DESCRIPTION:
XS GIS Cut Line= 3
      2004862.68     13875224.22      2005225.00     13875625.00
      2005461.64     13875599.41
#Sta/Elev= 30
  4459.7 1661.63  4520.2 1658.04  4617.8 1652.53  4709.7 1645.93  4730.6 1645.13
  4766.5 1642.00  4823.2 1640.20  4915.2 1638.96  4921.9 1639.64  4929.4 1638.91
  4971.9 1638.24  4986.1 1637.05  4992.9 1633.59  4994.6 1622.19  4994.9 1621.69
  4998.6 1622.19  5002.5 1622.19  5020.1 1638.04  5052.4 1639.07  5070.4 1640.35
  5080.4 1642.41  5090.5 1642.95  5110.6 1646.31  5130.7 1650.26  5137.6 1652.36
  5142.7 1652.73  5171.0 1659.63  5229.4 1669.22  5234.4 1669.32  5238.0 1671.06
#Mann=5,-1,0
  4459.7   0.035       0  4520.2    0.07       0  4994.6    0.05       0
  4998.6    0.07       0  5052.4    0.12       0
Bank Sta=4994.6,4998.6
Exp/Cntr=0.3,0.1

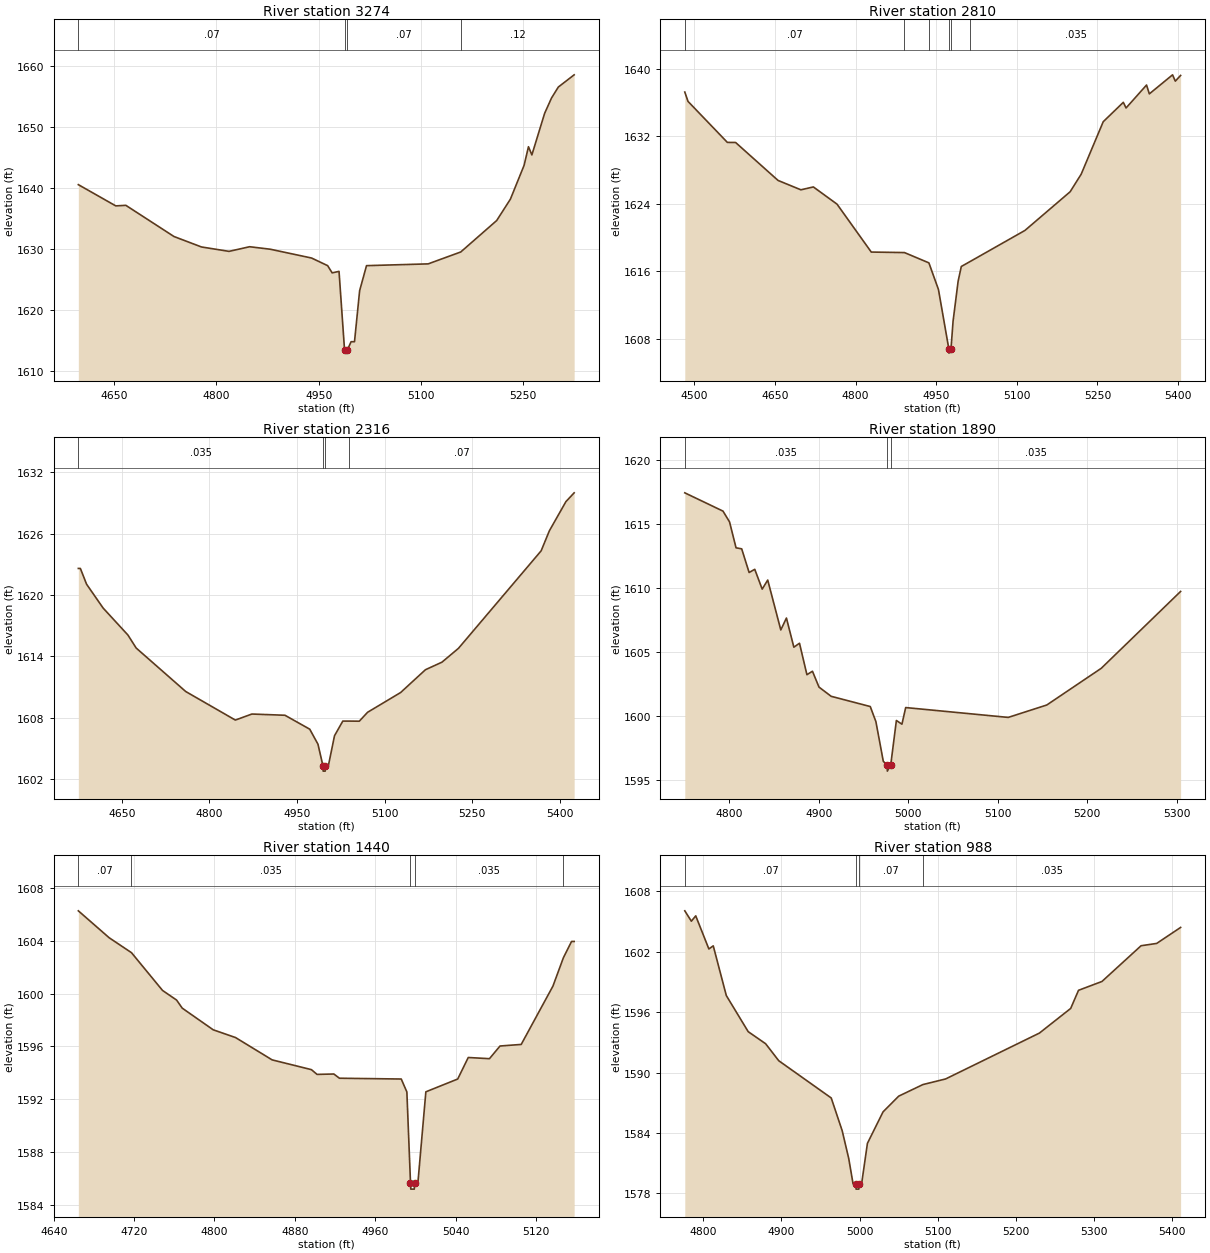
Type RM Length L Ch R = 1,3274,464,464,464
BEGIN DESCRIPTION:
Stream0109_DS 7.0
END DESCRIPTION:
XS GIS Cut Line= 3
      2004775.90     13876022.83      2005175.00     13876075.00
      2005498.09     13876043.66
#Sta/Elev= 30
  4597.5 1640.52  4652.4 1637.04  4667.2 1637.13  4737.8 1632.02  4778.1 1630.31
  4818.5 1629.59  4848.7 1630.35  4879.0 1629.94  4939.5 1628.50  4963.1 1627.25
  4969.7 1626.07  4979.8 1626.31  4987.9 1613.42  4988.2 1612.92  4991.9 1613.42
  4997.5 1614.79  5002.5 1614.79  5010.0 1623.14  5020.1 1627.25  5110.5 1627.54
  5158.3 1629.49  5211.0 1634.64  5231.1 1638.14  5251.2 1643.69  5257.6 1646.73
  5262.6 1645.39  5281.3 1652.20  5291.4 1654.71  5301.4 1656.51  5324.6 1658.51
#Mann=4,-1,0
  4597.5    0.07       0  4987.9    0.05       0  4991.9    0.07       0
  5158.3    0.12       0
Bank Sta=4987.9,4991.9
Exp/Cntr=0.3,0.1

Type RM Length L Ch R = 1,2810,494,494,494
BEGIN DESCRIPTION:
Stream0109_DS 6.0
END DESCRIPTION:
XS GIS Cut Line= 3
      2004682.13     13876248.53      2005125.00     13876525.00
      2005515.50     13876613.12
#Sta/Elev= 30
  4482.3 1637.25  4488.3 1636.14  4561.5 1631.28  4576.8 1631.27  4655.8 1626.77
  4698.3 1625.66  4721.5 1626.00  4765.5 1623.96  4829.2 1618.28  4890.9 1618.22
  4936.4 1617.00  4954.2 1613.84  4973.5 1606.80  4973.7 1606.30  4977.5 1606.80
  4981.4 1610.10  4990.8 1614.83  4996.7 1616.57  5013.4 1617.17  5115.0 1620.84
  5199.2 1625.43  5219.7 1627.51  5260.7 1633.73  5298.1 1636.03  5303.2 1635.36
  5341.3 1638.08  5346.5 1637.03  5389.7 1639.29  5394.8 1638.54  5404.7 1639.22
#Mann=6,-1,0
  4482.3    0.07       0  4890.9   0.035       0  4936.4    0.07       0
  4973.5    0.05       0  4977.5    0.07       0  5013.4   0.035       0
Bank Sta=4973.5,4977.5
Exp/Cntr=0.3,0.1

Type RM Length L Ch R = 1,2316,426,426,426
BEGIN DESCRIPTION:
Stream0109_DS 5.0
END DESCRIPTION:
XS GIS Cut Line= 3
      2004475.00     13876575.00      2004775.00     13876875.00
      2005074.98     13877174.98
#Sta/Elev= 30
  4575.7 1622.60  4579.2 1622.60  4589.8 1621.06  4618.1 1618.73  4660.6 1616.09
  4674.7 1614.82  4759.5 1610.57  4844.4 1607.78  4872.7 1608.37  4929.3 1608.25
  4971.7 1606.89  4985.8 1605.42  4994.4 1603.29  4994.7 1602.79  4998.2 1602.79
  4998.4 1603.29  5003.5 1603.29  5014.1 1606.25  5028.3 1607.68  5039.6 1607.68
  5056.5 1607.67  5070.7 1608.54  5127.2 1610.47  5169.7 1612.70  5198.0 1613.44
  5226.2 1614.79  5367.7 1624.32  5381.8 1626.28  5410.1 1629.13  5424.2 1629.99
#Mann=4,-1,0
  4575.7   0.035       0  4994.4   0.035       0  4998.4   0.035       0
  5039.6    0.07       0
Bank Sta=4994.4,4998.4
Exp/Cntr=0.3,0.1

Type RM Length L Ch R = 1,1890,450,450,450
BEGIN DESCRIPTION:
Stream0109_DS 4.0
END DESCRIPTION:
XS GIS Cut Line= 3
      2004324.98     13877024.98      2004525.00     13877175.00
      2004825.03     13877225.01
#Sta/Elev= 30
  4750.1 1617.44  4792.8 1616.01  4800.1 1615.17  4807.4 1613.14  4813.7 1613.06
  4822.0 1611.21  4828.3 1611.46  4836.6 1609.91  4842.8 1610.62  4857.4 1606.72
  4863.7 1607.65  4872.0 1605.37  4878.3 1605.68  4886.6 1603.22  4892.8 1603.49
  4900.1 1602.25  4913.7 1601.53  4957.4 1600.73  4963.7 1599.55  4972.0 1596.44
  4976.3 1596.18  4976.5 1595.68  4980.3 1596.18  4986.6 1599.64  4992.8 1599.35
  4997.0 1600.65  5111.6 1599.88  5154.7 1600.85  5215.6 1603.72  5304.3 1609.73
#Mann=3,-1,0
  4750.1   0.035       0  4976.3   0.035       0  4980.3   0.035       0
Bank Sta=4976.3,4980.3
Exp/Cntr=0.3,0.1

Type RM Length L Ch R = 1,1440,452,452,452
BEGIN DESCRIPTION:
Stream0109_DS 3.0
END DESCRIPTION:
XS GIS Cut Line= 3
      2004225.01     13877475.00      2004525.00     13877625.00
      2004674.99     13877675.00
#Sta/Elev= 30
  4664.5 1606.27  4695.2 1604.23  4717.4 1603.10  4748.3 1600.24  4762.3 1599.51
  4767.9 1598.90  4798.7 1597.26  4821.0 1596.67  4857.4 1594.98  4896.5 1594.24
  4902.1 1593.88  4918.8 1593.91  4924.4 1593.59  4985.9 1593.53  4991.5 1592.55
  4995.1 1585.69  4995.4 1585.19  4998.9 1585.19  4999.1 1585.69  5002.5 1585.69
  5010.4 1592.56  5042.1 1593.53  5052.6 1595.16  5073.7 1595.07  5084.2 1596.03
  5105.3 1596.15  5136.9 1600.57  5147.3 1602.72  5155.4 1603.95  5158.0 1603.95
#Mann=5,-1,0
  4664.5    0.07       0  4717.4   0.035       0  4995.1   0.035       0
  4999.1   0.035       0  5147.3    0.12       0
Bank Sta=4995.1,4999.1
Exp/Cntr=0.3,0.1

Type RM Length L Ch R = 1,988,455,455,455
BEGIN DESCRIPTION:
Stream0109_DS 2.0
END DESCRIPTION:
XS GIS Cut Line= 3
      2004074.98     13877874.99      2004275.00     13877975.00
      2004685.56     13877977.69
#Sta/Elev= 30
  4776.4 1606.07  4784.8 1605.04  4790.4 1605.57  4807.2 1602.28  4812.8 1602.59
  4829.5 1597.65  4857.5 1594.06  4879.8 1592.86  4896.6 1591.17  4963.7 1587.47
  4977.7 1584.22  4986.1 1581.45  4991.6 1578.95  4995.2 1578.91  4995.5 1578.41
  4999.0 1578.41  4999.2 1578.91  5002.5 1578.91  5010.0 1582.96  5030.0 1586.09
  5050.0 1587.65  5080.9 1588.80  5110.0 1589.36  5230.0 1593.92  5270.0 1596.37
  5280.0 1598.17  5310.0 1599.05  5360.0 1602.60  5380.0 1602.83  5410.6 1604.42
#Mann=4,-1,0
  4776.4    0.07       0  4995.2    0.05       0  4999.2    0.07       0
  5080.9   0.035       0
Bank Sta=4995.2,4999.2
Exp/Cntr=0.3,0.1

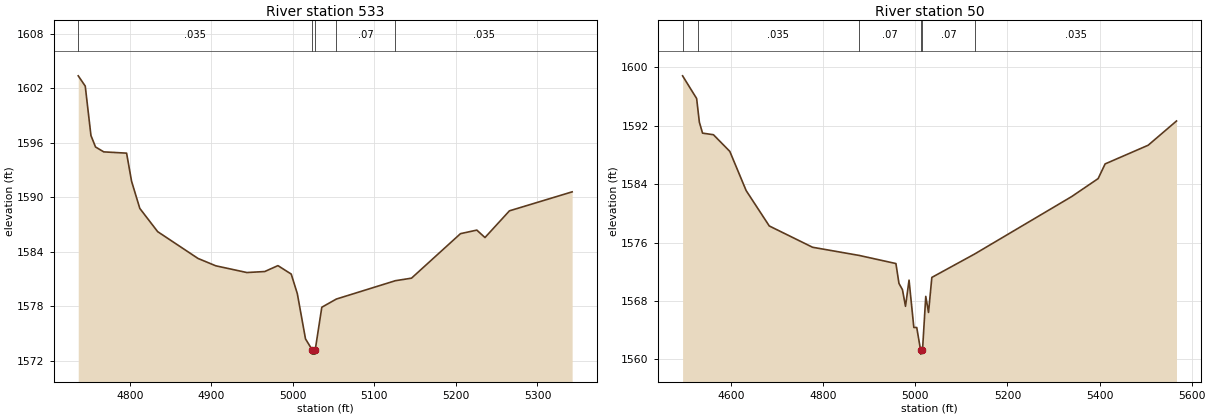
Type RM Length L Ch R = 1,533,483,483,483
BEGIN DESCRIPTION:
Stream0109_DS 1.0
END DESCRIPTION:
XS GIS Cut Line= 3
      2003897.42     13878252.01      2004125.00     13878375.00
      2004471.90     13878383.89
#Sta/Elev= 30
  4736.8 1603.36  4745.4 1602.23  4752.4 1596.79  4758.0 1595.53  4768.1 1594.99
  4796.1 1594.85  4802.2 1591.76  4812.3 1588.77  4834.2 1586.21  4883.7 1583.26
  4905.5 1582.45  4943.6 1581.71  4965.5 1581.82  4981.7 1582.47  4998.0 1581.54
  5005.5 1579.38  5015.5 1574.41  5023.5 1573.23  5023.7 1572.73  5027.2 1572.73
  5027.5 1573.23  5035.5 1577.89  5053.3 1578.79  5125.7 1580.81  5145.5 1581.09
  5205.6 1585.99  5225.6 1586.38  5235.6 1585.56  5265.6 1588.50  5342.5 1590.59
#Mann=5,-1,0
  4736.8   0.035       0  5023.5   0.035       0  5027.5   0.035       0
  5053.3    0.07       0  5125.7   0.035       0
Bank Sta=5023.5,5027.5
Exp/Cntr=0.3,0.1

Type RM Length L Ch R = 1,50,0,0,0
BEGIN DESCRIPTION:
Stream0109_DS 0.0
END DESCRIPTION:
XS GIS Cut Line= 4
      2003831.05     13878418.37      2004044.43     13878755.67
      2004124.89     13878824.95      2004600.19     13878515.62
#Sta/Elev= 30
  4494.7 1598.85  4525.2 1595.74  4527.1 1594.70  4531.1 1592.51  4538.0 1591.00
  4561.7 1590.78  4597.2 1588.50  4632.7 1583.13  4682.9 1578.28  4777.0 1575.36
  4878.3 1574.24  4957.9 1573.13  4964.5 1570.41  4972.1 1569.55  4978.7 1567.27
  4986.4 1570.86  4996.8 1564.37  5003.1 1564.37  5011.6 1561.22  5011.8 1560.72
  5015.6 1561.22  5022.7 1568.63  5028.7 1566.43  5035.9 1571.23  5128.9 1574.44
  5339.6 1582.31  5397.0 1584.77  5412.1 1586.78  5505.6 1589.34  5567.1 1592.66
#Mann=6,-1,0
  4494.7    0.07       0  4527.1   0.035       0  4878.3    0.07       0
  5011.6    0.05       0  5015.6    0.07       0  5128.9   0.035       0
Bank Sta=5011.6,5015.6
Exp/Cntr=0.3,0.1

Chan Stop Cuts=-1