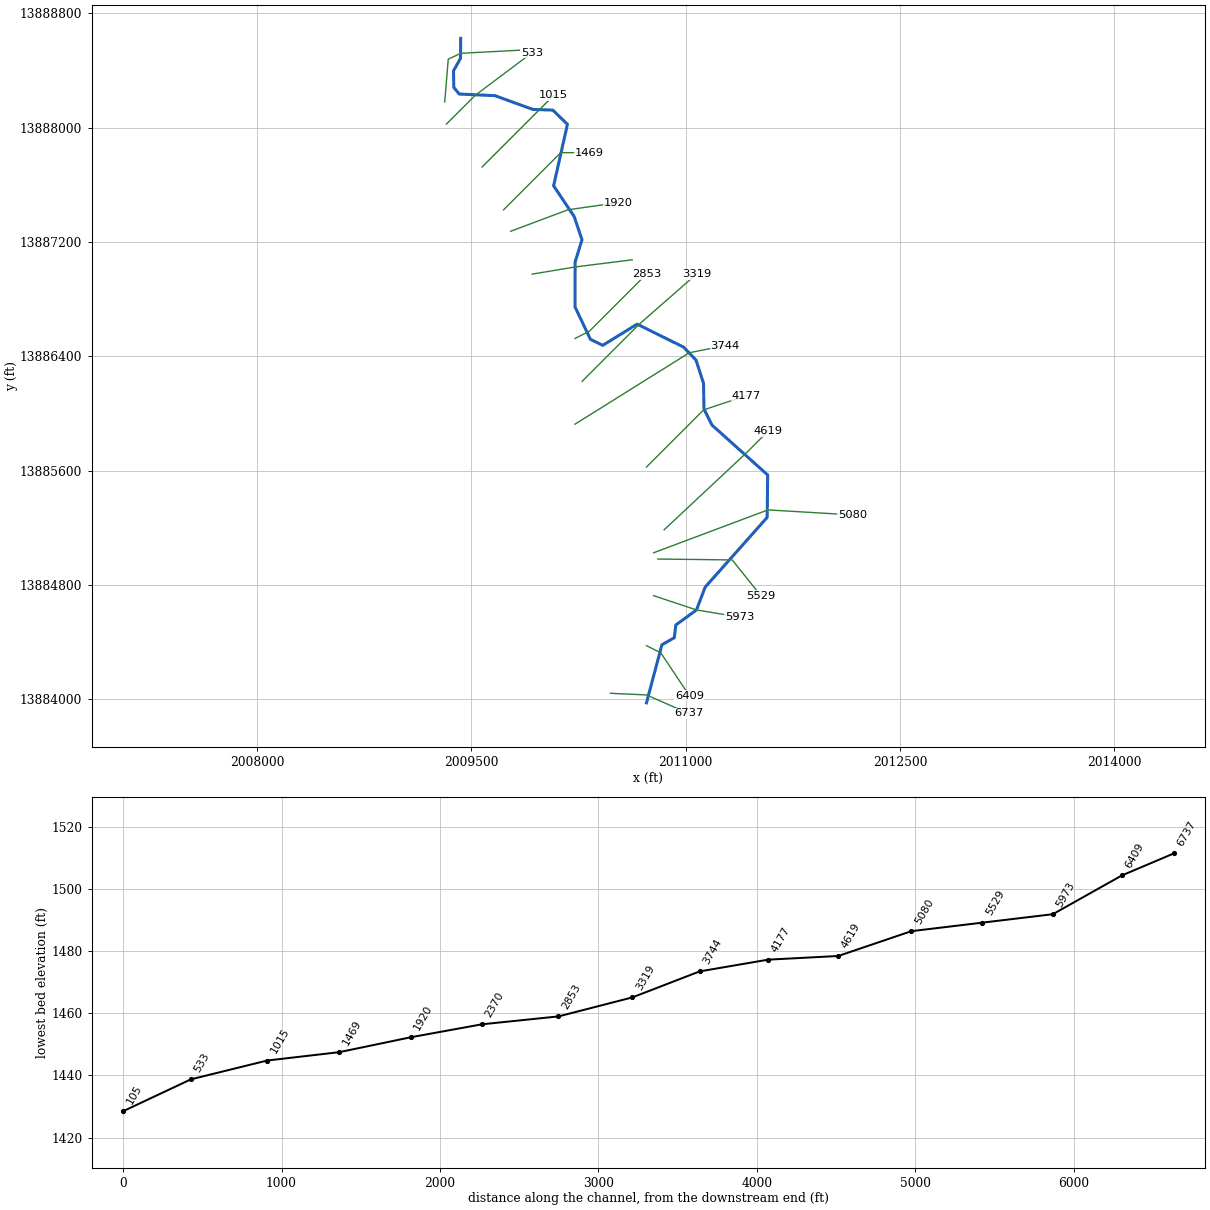
--- Stream0110_DS.prj (project) ---

Proj Title=Stream0110_DS Base Level Engineering
Current Plan=p01
Default Exp/Contr=0.3,0.1
English Units
Geom File=g01
Flow File=f01
Plan File=p01
BEGIN DESCRIPTION:
Stream0110_DS
END DESCRIPTION:

--- Stream0110_DS.p01 (plan) ---

Plan Title=Multiple Run
Short Identifier=Multiple
Geom File=g01
Flow File=f01
Subcritical Flow
K Sum by GR= 0
Std Step Tol= 0.01
Critical Tol= 0.01
Num of Std Step Trials= 20
Max Error Tol= 0.3
Flow Tol Ratio= 0.001
Split Flow NTrial= 30
Split Flow Tol= 0.02
Split Flow Ratio= 0.02
Log Output Level= 0
Friction Slope Method= 1
Unsteady Friction Slope Method= 2
Unsteady Bridges Friction Slope Method= 1
Parabolic Critical Depth
Global Vel Dist=  1 , 1 , 1
Global Log Level= 0
CheckData=True
Encroach Param= -1, 0, 0, 0
BEGIN DESCRIPTION:
Multiple Run
END DESCRIPTION:

--- Stream0110_DS.f01 (steady flow) ---

Flow Title=Multiple
Number of Profiles=7
Profile Names=10-year,25-year,50-year,1pct_min,100-year,1pct_plu,500-year
River Rch & RM= Stream0110_DS,Reach-1,6737
     844    1424    1975    1332    2657    5302    4751
River Rch & RM= Stream0110_DS,Reach-1,5973
    1506    2635    3745    2580    5149   10273    9629
River Rch & RM= Stream0110_DS,Reach-1,5080
    1931    3422    4901    3398    6779   13526   12846
Boundary for River Rch & Prof#=Stream0110_DS,Reach-1,1
Up Type=0
Dn Type=3
Dn Slope=0.005
Boundary for River Rch & Prof#=Stream0110_DS,Reach-1,2
Up Type=0
Dn Type=3
Dn Slope=0.005
Boundary for River Rch & Prof#=Stream0110_DS,Reach-1,3
Up Type=0
Dn Type=3
Dn Slope=0.005
Boundary for River Rch & Prof#=Stream0110_DS,Reach-1,4
Up Type=0
Dn Type=3
Dn Slope=0.005
Boundary for River Rch & Prof#=Stream0110_DS,Reach-1,5
Up Type=0
Dn Type=3
Dn Slope=0.005
Boundary for River Rch & Prof#=Stream0110_DS,Reach-1,6
Up Type=0
Dn Type=3
Dn Slope=0.005
Boundary for River Rch & Prof#=Stream0110_DS,Reach-1,7
Up Type=0
Dn Type=3
Dn Slope=0.005

--- Stream0110_DS.g01 (geometry) ---

Geom Title=Existing Conditions

River Reach=Stream0110_DS,Reach-1
Reach XY= 30
      2010725.00     13883975.00      2010833.07     13884381.32
      2010919.68     13884430.56      2010930.28     13884519.47
      2011075.00     13884625.00      2011135.75     13884784.69
      2011569.54     13885272.55      2011573.20     13885569.33
      2011183.14     13885918.94      2011127.35     13886030.52
      2011124.32     13886211.08      2011071.39     13886373.52
      2010984.70     13886464.23      2010659.60     13886624.91
      2010418.91     13886476.57      2010333.02     13886518.56
      2010225.06     13886745.03      2010225.52     13887059.78
      2010273.73     13887215.29      2010219.46     13887377.42
      2010075.18     13887593.27      2010171.88     13888023.38
      2010069.56     13888122.83      2009930.53     13888127.39
      2009664.50     13888223.78      2009414.82     13888235.32
      2009376.96     13888280.65      2009374.69     13888397.83
      2009423.67     13888484.64      2009425.00     13888625.00

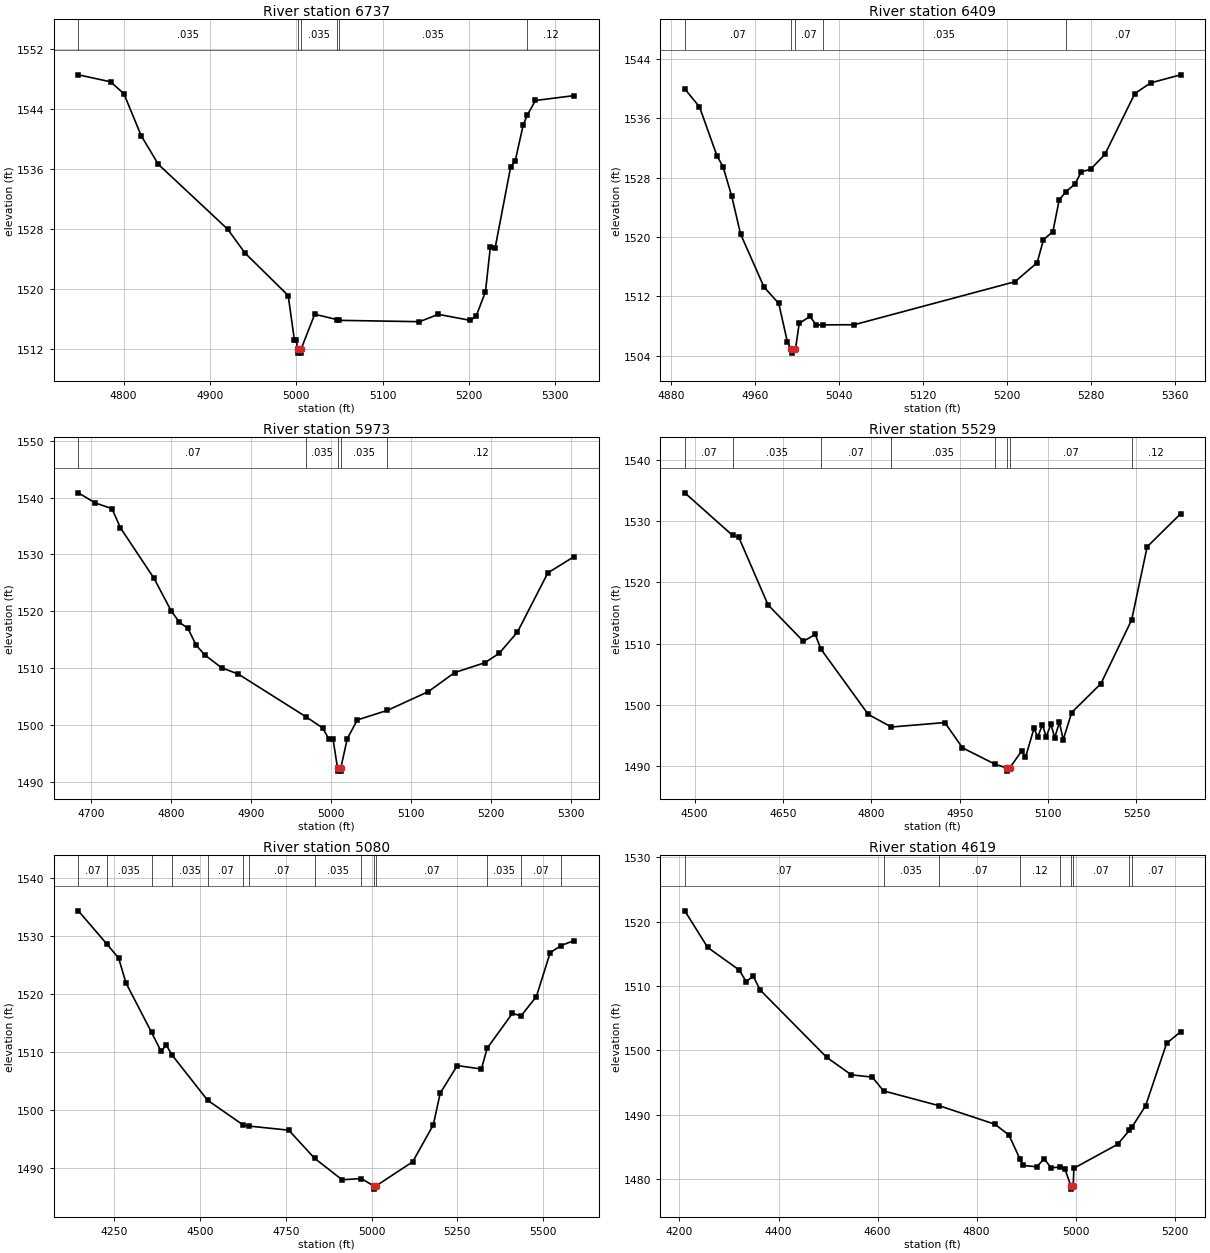
Type RM Length L Ch R = 1,6737,328,328,328
BEGIN DESCRIPTION:
Stream0110_DS 15.0
END DESCRIPTION:
XS GIS Cut Line= 3
      2010472.26     13884041.67      2010724.30     13884030.29
      2011019.06     13883901.16
#Sta/Elev= 30
  4747.7 1548.50  4785.1 1547.57  4800.5 1545.97  4820.5 1540.38  4840.5 1536.55
  4920.6 1527.93  4940.6 1524.76  4990.7 1519.08  4997.8 1513.22  5000.0 1513.22
  5001.5 1511.91  5001.7 1511.41  5005.2 1511.41  5005.5 1511.91  5021.4 1516.59
  5047.1 1515.88  5049.4 1515.78  5142.7 1515.60  5164.5 1516.58  5201.4 1515.78
  5208.2 1516.30  5219.1 1519.58  5224.8 1525.58  5230.3 1525.43  5248.2 1536.18
  5253.6 1537.05  5262.8 1541.82  5267.6 1543.15  5277.0 1545.08  5321.8 1545.73
#Mann=6,-1,0
  4747.7   0.035       0  5001.5   0.035       0  5005.5   0.035       0
  5047.1    0.07       0  5049.4   0.035       0  5267.6    0.12       0
Bank Sta=5001.5,5005.5
Exp/Cntr=0.3,0.1

Type RM Length L Ch R = 1,6409,436,436,436
BEGIN DESCRIPTION:
Stream0110_DS 14.0
END DESCRIPTION:
XS GIS Cut Line= 3
      2010724.99     13884375.01      2010825.00     13884325.00
      2011025.01     13884024.98
#Sta/Elev= 30
  4892.8 1539.95  4906.8 1537.53  4923.6 1530.87  4929.2 1529.48  4937.5 1525.49
  4945.9 1520.40  4968.3 1513.23  4982.3 1511.03  4990.6 1505.81  4994.2 1504.83
  4994.5 1504.33  4998.2 1504.83  5001.8 1508.35  5012.1 1509.27  5018.1 1508.11
  5024.3 1508.14  5054.2 1508.16  5207.4 1513.96  5228.5 1516.52  5234.5 1519.62
  5243.5 1520.72  5249.5 1524.98  5255.9 1526.10  5264.5 1527.11  5270.5 1528.76
  5279.5 1529.12  5293.1 1531.14  5321.6 1539.33  5336.6 1540.76  5365.2 1541.85
#Mann=5,-1,0
  4892.8    0.07       0  4994.2    0.05       0  4998.2    0.07       0
  5024.3   0.035       0  5255.9    0.07       0
Bank Sta=4994.2,4998.2
Exp/Cntr=0.3,0.1

Type RM Length L Ch R = 1,5973,444,444,444
BEGIN DESCRIPTION:
Stream0110_DS 13.0
END DESCRIPTION:
XS GIS Cut Line= 3
      2010775.03     13884724.99      2011075.00     13884625.00
      2011374.96     13884575.01
#Sta/Elev= 30
  4683.8 1540.85  4704.9 1539.07  4725.9 1538.06  4736.5 1534.68  4778.6 1525.77
  4799.7 1520.13  4810.3 1518.05  4820.8 1517.00  4831.3 1514.02  4841.9 1512.32
  4863.0 1510.05  4884.0 1508.93  4969.0 1501.38  4989.5 1499.45  4997.4 1497.45
  5002.5 1497.45  5008.1 1492.35  5008.4 1491.85  5011.9 1491.85  5012.1 1492.35
  5020.3 1497.59  5032.9 1500.87  5070.5 1502.55  5121.7 1505.85  5154.6 1509.20
  5192.6 1510.95  5210.4 1512.60  5233.2 1516.35  5271.2 1526.76  5304.1 1529.62
#Mann=5,-1,0
  4683.8    0.07       0  4969.0   0.035       0  5008.1   0.035       0
  5012.1   0.035       0  5070.5    0.12       0
Bank Sta=5008.1,5012.1
Exp/Cntr=0.3,0.1

Type RM Length L Ch R = 1,5529,449,449,449
BEGIN DESCRIPTION:
Stream0110_DS 12.0
END DESCRIPTION:
XS GIS Cut Line= 3
      2010803.70     13884981.16      2011325.00     13884975.00
      2011525.00     13884724.99
#Sta/Elev= 30
  4483.4 1534.63  4564.6 1527.66  4574.7 1527.43  4624.7 1516.31  4684.7 1510.35
  4704.7 1511.49  4714.6 1509.06  4794.7 1498.42  4834.0 1496.35  4924.7 1497.08
  4954.7 1492.95  5010.3 1490.25  5030.7 1489.64  5031.0 1489.14  5034.7 1489.64
  5055.2 1492.44  5061.6 1491.38  5076.0 1496.12  5082.4 1494.72  5090.4 1496.74
  5096.8 1494.74  5104.8 1496.82  5111.2 1494.60  5119.2 1497.13  5125.6 1494.26
  5140.0 1498.72  5189.6 1503.44  5241.8 1513.86  5268.1 1525.81  5324.9 1531.21
#Mann=8,-1,0
  4483.4    0.07       0  4564.6   0.035       0  4714.6    0.07       0
  4834.0   0.035       0  5010.3    0.07       0  5030.7   0.035       0
  5034.7    0.07       0  5241.8    0.12       0
Bank Sta=5030.7,5034.7
Exp/Cntr=0.3,0.1

Type RM Length L Ch R = 1,5080,461,461,461
BEGIN DESCRIPTION:
Stream0110_DS 11.0
END DESCRIPTION:
XS GIS Cut Line= 3
      2010775.03     13885025.01      2011575.00     13885325.00
      2012164.80     13885290.19
#Sta/Elev= 30
  4145.2 1534.30  4227.8 1528.62  4262.7 1526.16  4284.0 1521.89  4358.7 1513.36
  4386.4 1510.11  4401.5 1511.21  4417.9 1509.51  4522.0 1501.69  4626.0 1497.42
  4641.5 1497.25  4758.4 1496.54  4834.1 1491.68  4914.1 1488.00  4970.0 1488.21
  5007.6 1486.89  5007.8 1486.39  5011.6 1486.89  5119.8 1491.10  5179.9 1497.45
  5199.9 1502.90  5249.6 1507.66  5320.1 1507.07  5336.8 1510.64  5410.3 1516.64
  5435.7 1516.22  5480.4 1519.55  5520.5 1527.10  5552.5 1528.32  5590.4 1529.19
#Mann=14,-1,0
  4145.2    0.07       0  4227.8   0.035       0  4358.7    0.07       0
  4417.9   0.035       0  4522.0    0.07       0  4626.0   0.035       0
  4641.5    0.07       0  4834.1   0.035       0  4970.0    0.07       0
  5007.6    0.05       0  5011.6    0.07       0  5336.8   0.035       0
  5435.7    0.07       0  5552.5   0.035       0
Bank Sta=5007.6,5011.6
Exp/Cntr=0.3,0.1

Type RM Length L Ch R = 1,4619,442,442,442
BEGIN DESCRIPTION:
Stream0110_DS 10.0
END DESCRIPTION:
XS GIS Cut Line= 3
      2010848.80     13885186.04      2011425.00     13885725.00
      2011574.99     13885874.99
#Sta/Elev= 30
  4210.8 1521.67  4257.0 1515.98  4320.5 1512.48  4334.7 1510.68  4348.9 1511.51
  4363.0 1509.36  4497.4 1498.89  4547.2 1496.17  4589.2 1495.83  4612.1 1493.68
  4724.1 1491.38  4836.9 1488.50  4865.2 1486.82  4887.1 1483.16  4893.5 1482.10
  4921.9 1481.88  4936.0 1483.15  4950.2 1481.75  4968.4 1481.81  4978.5 1481.50
  4990.3 1478.91  4990.6 1478.41  4995.0 1478.91  4996.4 1481.66  5084.6 1485.37
  5108.4 1487.54  5113.1 1487.99  5141.2 1491.37  5183.6 1501.07  5211.9 1502.88
#Mann=9,-1,0
  4210.8    0.07       0  4612.1   0.035       0  4724.1    0.07       0
  4887.1    0.12       0  4968.4    0.07       0  4990.3    0.05       0
  4995.0    0.07       0  5108.4    0.12       0  5113.1    0.07       0
Bank Sta=4990.3,4995
Exp/Cntr=0.3,0.1

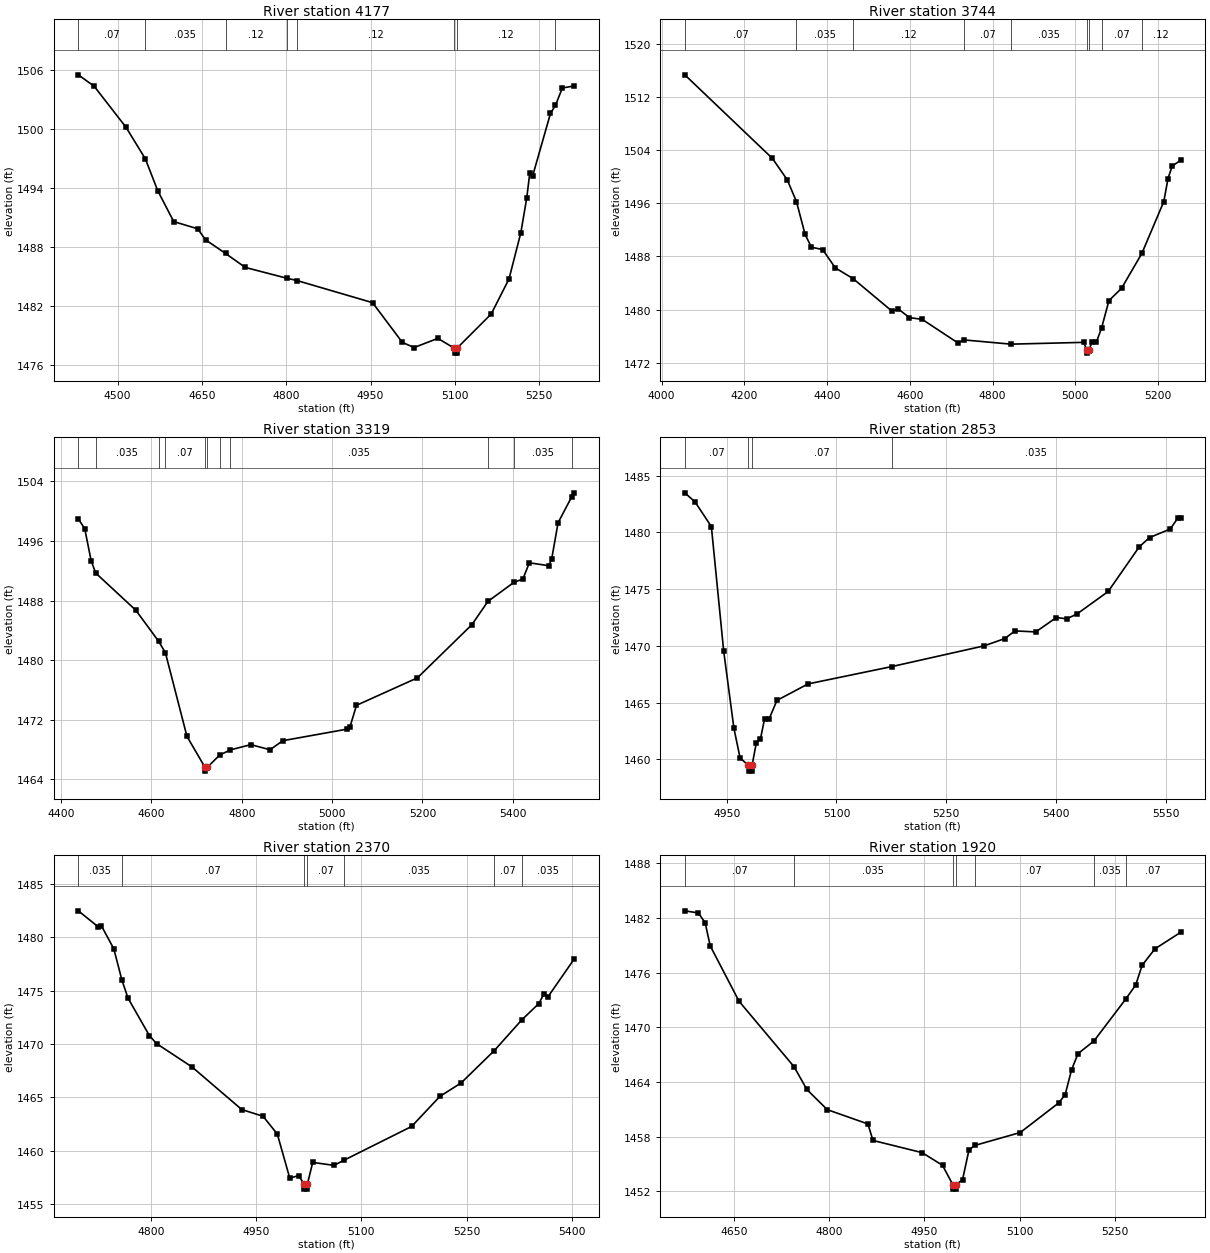
Type RM Length L Ch R = 1,4177,433,433,433
BEGIN DESCRIPTION:
Stream0110_DS 9.0
END DESCRIPTION:
XS GIS Cut Line= 3
      2010724.98     13885624.98      2011125.00     13886025.00
      2011424.96     13886124.99
#Sta/Elev= 30
  4430.2 1505.52  4458.5 1504.35  4515.1 1500.18  4549.3 1496.99  4571.6 1493.72
  4599.9 1490.60  4642.4 1489.87  4656.5 1488.75  4692.1 1487.36  4727.2 1485.94
  4801.3 1484.84  4819.0 1484.61  4953.5 1482.36  5006.5 1478.32  5027.5 1477.80
  5069.7 1478.73  5098.9 1477.73  5099.3 1477.23  5103.4 1477.23  5103.7 1477.73
  5164.6 1481.21  5196.2 1484.77  5217.3 1489.48  5227.8 1493.02  5233.1 1495.50
  5238.4 1495.27  5270.0 1501.60  5278.9 1502.43  5291.1 1504.18  5312.1 1504.39
#Mann=8,-1,0
  4430.2    0.07       0  4549.3   0.035       0  4692.1    0.12       0
  4801.3    0.07       0  4819.0    0.12       0  5098.9    0.05       0
  5103.7    0.12       0  5278.9   0.063       0
Bank Sta=5098.9,5103.7
Exp/Cntr=0.3,0.1

Type RM Length L Ch R = 1,3744,425,425,425
BEGIN DESCRIPTION:
Stream0110_DS 8.0
END DESCRIPTION:
XS GIS Cut Line= 3
      2010225.00     13885925.00      2011025.00     13886425.00
      2011274.95     13886474.99
#Sta/Elev= 30
  4056.0 1515.31  4267.7 1502.74  4303.6 1499.52  4325.9 1496.23  4346.7 1491.31
  4362.0 1489.38  4389.1 1489.03  4419.8 1486.27  4462.9 1484.65  4556.6 1479.77
  4571.9 1480.09  4599.0 1478.79  4629.7 1478.53  4716.4 1474.97  4730.3 1475.44
  4844.3 1474.80  5019.8 1475.07  5027.6 1473.95  5027.9 1473.45  5032.4 1473.95
  5040.2 1475.06  5050.4 1475.05  5063.3 1477.24  5081.0 1481.34  5111.6 1483.21
  5160.6 1488.45  5213.6 1496.24  5223.8 1499.70  5234.0 1501.61  5254.3 1502.44
#Mann=9,-1,0
  4056.0    0.07       0  4325.9   0.035       0  4462.9    0.12       0
  4730.3    0.07       0  4844.3   0.035       0  5027.6   0.035       0
  5032.4   0.035       0  5063.3    0.07       0  5160.6    0.12       0
Bank Sta=5027.6,5032.4
Exp/Cntr=0.3,0.1

Type RM Length L Ch R = 1,3319,466,466,466
BEGIN DESCRIPTION:
Stream0110_DS 7.0
END DESCRIPTION:
XS GIS Cut Line= 3
      2010275.02     13886225.02      2010675.00     13886625.00
      2011075.03     13886975.02
#Sta/Elev= 30
  4438.5 1498.95  4452.6 1497.67  4466.8 1493.37  4476.8 1491.70  4565.8 1486.69
  4615.9 1482.55  4631.1 1481.00  4678.9 1469.74  4718.9 1465.58  4719.3 1465.08
  4723.7 1465.58  4751.1 1467.23  4774.7 1467.93  4820.3 1468.64  4862.7 1467.95
  4891.0 1469.17  5032.2 1470.71  5039.8 1471.06  5054.0 1473.92  5188.8 1477.61
  5309.3 1484.75  5344.8 1487.88  5402.8 1490.46  5422.2 1490.88  5436.5 1493.07
  5479.2 1492.68  5485.8 1493.52  5500.1 1498.45  5530.2 1501.92  5535.7 1502.47
#Mann=11,-1,0
  4438.5    0.07       0  4476.8   0.035       0  4615.9    0.12       0
  4631.1    0.07       0  4718.9   0.035       0  4723.7    0.07       0
  4751.1    0.12       0  4774.7   0.035       0  5344.8    0.07       0
  5402.8   0.035       0  5530.2    0.07       0
Bank Sta=4718.9,4723.7
Exp/Cntr=0.3,0.1

Type RM Length L Ch R = 1,2853,483,483,483
BEGIN DESCRIPTION:
Stream0110_DS 6.0
END DESCRIPTION:
XS GIS Cut Line= 3
      2010225.01     13886525.01      2010325.00     13886575.00
      2010725.02     13886975.02
#Sta/Elev= 30
  4892.8 1483.48  4906.8 1482.68  4929.1 1480.51  4945.9 1469.56  4959.9 1462.75
  4968.3 1460.14  4979.7 1459.47  4980.1 1458.97  4984.4 1458.97  4984.7 1459.47
  4990.6 1461.49  4996.2 1461.81  5001.8 1463.58  5008.1 1463.58  5018.7 1465.20
  5061.2 1466.65  5175.8 1468.18  5301.6 1470.00  5329.9 1470.64  5344.0 1471.32
  5372.3 1471.23  5400.6 1472.50  5414.7 1472.38  5428.9 1472.82  5471.3 1474.79
  5513.7 1478.72  5527.8 1479.54  5556.1 1480.29  5566.7 1481.28  5570.3 1481.28
#Mann=4,-1,0
  4892.8    0.07       0  4979.7    0.05       0  4984.7    0.07       0
  5175.8   0.035       0
Bank Sta=4979.7,4984.7
Exp/Cntr=0.3,0.1

Type RM Length L Ch R = 1,2370,450,450,450
BEGIN DESCRIPTION:
Stream0110_DS 5.0
END DESCRIPTION:
XS GIS Cut Line= 3
      2009925.05     13886975.01      2010225.00     13887025.00
      2010625.00     13887075.00
#Sta/Elev= 30
  4696.3 1482.45  4724.1 1480.98  4729.2 1481.05  4746.9 1478.90  4758.4 1475.99
  4767.2 1474.28  4797.6 1470.79  4807.8 1470.04  4858.5 1467.85  4929.4 1463.87
  4959.8 1463.24  4980.1 1461.58  4997.9 1457.45  5010.5 1457.70  5018.0 1456.93
  5018.4 1456.43  5022.7 1456.43  5023.1 1456.93  5030.6 1458.93  5060.9 1458.65
  5075.7 1459.15  5171.7 1462.29  5212.0 1465.10  5242.3 1466.36  5289.7 1469.39
  5328.6 1472.24  5353.1 1473.78  5360.7 1474.72  5365.7 1474.37  5403.5 1477.94
#Mann=7,-1,0
  4696.3   0.035       0  4758.4    0.07       0  5018.0    0.05       0
  5023.1    0.07       0  5075.7   0.035       0  5289.7    0.07       0
  5328.6   0.035       0
Bank Sta=5018,5023.1
Exp/Cntr=0.3,0.1

Type RM Length L Ch R = 1,1920,451,451,451
BEGIN DESCRIPTION:
Stream0110_DS 4.0
END DESCRIPTION:
XS GIS Cut Line= 3
      2009775.03     13887275.01      2010175.00     13887425.00
      2010524.98     13887475.00
#Sta/Elev= 30
  4572.8 1482.78  4594.1 1482.55  4604.8 1481.48  4612.8 1478.94  4658.2 1472.86
  4744.8 1465.68  4765.0 1463.18  4797.1 1460.97  4861.1 1459.40  4869.1 1457.59
  4946.6 1456.25  4978.6 1454.86  4994.7 1452.75  4995.1 1452.25  4999.6 1452.25
  5000.0 1452.75  5010.1 1453.28  5020.2 1456.53  5029.2 1457.04  5101.0 1458.46
  5161.6 1461.71  5171.7 1462.62  5181.8 1465.34  5191.9 1467.11  5217.0 1468.50
  5267.2 1473.11  5282.8 1474.65  5292.9 1476.81  5313.1 1478.61  5353.5 1480.42
#Mann=7,-1,0
  4572.8    0.07       0  4744.8   0.035       0  4994.7   0.035       0
  5000.0   0.035       0  5029.2    0.07       0  5217.0   0.035       0
  5267.2    0.07       0
Bank Sta=4994.7,5000
Exp/Cntr=0.3,0.1

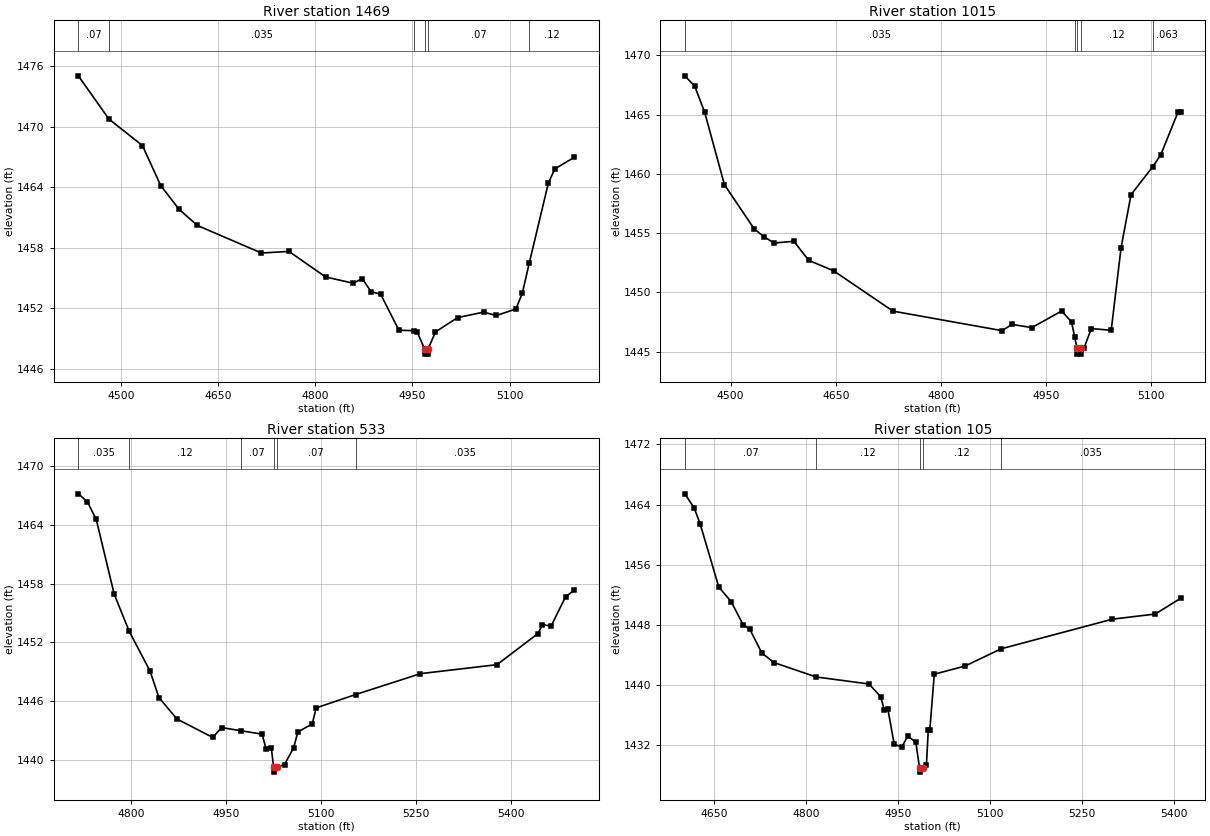
Type RM Length L Ch R = 1,1469,454,454,454
BEGIN DESCRIPTION:
Stream0110_DS 3.0
END DESCRIPTION:
XS GIS Cut Line= 3
      2009725.00     13887425.00      2010125.00     13887825.00
      2010325.01     13887825.00
#Sta/Elev= 30
  4434.0 1475.04  4481.3 1470.75  4533.0 1468.13  4561.3 1464.16  4589.6 1461.81
  4617.8 1460.21  4716.8 1457.48  4759.3 1457.64  4815.8 1455.11  4858.3 1454.49
  4872.4 1454.94  4886.5 1453.62  4900.7 1453.42  4929.0 1449.83  4952.5 1449.78
  4957.3 1449.66  4968.8 1447.96  4969.2 1447.46  4973.7 1447.46  4974.1 1447.96
  4985.5 1449.66  5019.7 1451.08  5059.7 1451.62  5079.7 1451.29  5109.7 1451.93
  5119.7 1453.51  5130.3 1456.47  5159.7 1464.37  5169.7 1465.81  5199.7 1466.96
#Mann=6,-1,0
  4434.0    0.07       0  4481.3   0.035       0  4952.5    0.07       0
  4968.8    0.05       0  4974.1    0.07       0  5130.3    0.12       0
Bank Sta=4968.8,4974.1
Exp/Cntr=0.3,0.1

Type RM Length L Ch R = 1,1015,482,482,482
BEGIN DESCRIPTION:
Stream0110_DS 2.0
END DESCRIPTION:
XS GIS Cut Line= 3
      2009575.03     13887725.03      2009975.00     13888125.00
      2010075.03     13888225.03
#Sta/Elev= 30
  4434.8 1468.28  4448.9 1467.41  4463.0 1465.23  4491.3 1459.09  4533.8 1455.35
  4547.9 1454.69  4562.0 1454.16  4590.3 1454.31  4611.5 1452.70  4646.9 1451.82
  4731.7 1448.41  4887.3 1446.76  4901.4 1447.29  4929.7 1447.02  4972.2 1448.42
  4986.3 1447.50  4990.7 1446.26  4994.2 1445.28  4994.7 1444.78  4999.2 1444.78
  4999.6 1445.28  5004.0 1445.28  5014.6 1446.94  5042.9 1446.79  5057.0 1453.78
  5071.2 1458.25  5102.1 1460.60  5113.6 1461.61  5138.3 1465.24  5141.9 1465.24
#Mann=5,-1,0
  4434.8   0.035       0  4990.7    0.12       0  4994.2    0.05       0
  4999.6    0.12       0  5102.1   0.063       0
Bank Sta=4994.2,4999.6
Exp/Cntr=0.3,0.1

Type RM Length L Ch R = 1,533,428,428,428
BEGIN DESCRIPTION:
Stream0110_DS 1.0
END DESCRIPTION:
XS GIS Cut Line= 3
      2009325.01     13888025.01      2009525.00     13888225.00
      2009924.97     13888524.98
#Sta/Elev= 30
  4717.3 1467.18  4731.4 1466.39  4745.6 1464.56  4773.9 1456.92  4797.7 1453.11
  4830.4 1449.07  4844.6 1446.34  4872.9 1444.16  4929.4 1442.27  4943.6 1443.28
  4973.8 1442.95  5007.4 1442.61  5013.7 1441.09  5022.0 1441.21  5025.6 1439.22
  5026.0 1438.72  5031.0 1439.22  5042.8 1439.49  5057.4 1441.23  5063.7 1442.81
  5086.6 1443.66  5092.8 1445.29  5154.9 1446.65  5257.4 1448.79  5378.3 1449.71
  5442.8 1452.88  5450.1 1453.80  5463.7 1453.66  5486.6 1456.66  5500.1 1457.31
#Mann=6,-1,0
  4717.3   0.035       0  4797.7    0.12       0  4973.8    0.07       0
  5025.6    0.05       0  5031.0    0.07       0  5154.9   0.035       0
Bank Sta=5025.6,5031
Exp/Cntr=0.3,0.1

Type RM Length L Ch R = 1,105,0,0,0
BEGIN DESCRIPTION:
Stream0110_DS 0.0
END DESCRIPTION:
XS GIS Cut Line= 4
      2009313.22     13888179.78      2009337.84     13888478.95
      2009425.52     13888520.24      2009835.95     13888541.94
#Sta/Elev= 30
  4602.9 1465.43  4618.2 1463.56  4628.2 1461.37  4658.3 1453.04  4678.4 1451.12
  4698.4 1447.97  4708.5 1447.50  4728.5 1444.28  4748.6 1443.00  4817.1 1441.10
  4903.1 1440.17  4922.1 1438.49  4928.3 1436.65  4933.8 1436.85  4944.2 1432.16
  4956.6 1431.80  4966.3 1433.24  4979.4 1432.44  4985.6 1428.96  4986.1 1428.46
  4991.1 1428.96  4996.7 1429.41  4999.7 1434.03  5002.2 1434.03  5009.5 1441.47
  5059.6 1442.55  5118.4 1444.84  5299.9 1448.78  5369.6 1449.46  5411.0 1451.55
#Mann=5,-1,0
  4602.9    0.07       0  4817.1    0.12       0  4985.6    0.05       0
  4991.1    0.12       0  5118.4   0.035       0
Bank Sta=4985.6,4991.1
Exp/Cntr=0.3,0.1

Chan Stop Cuts=-1