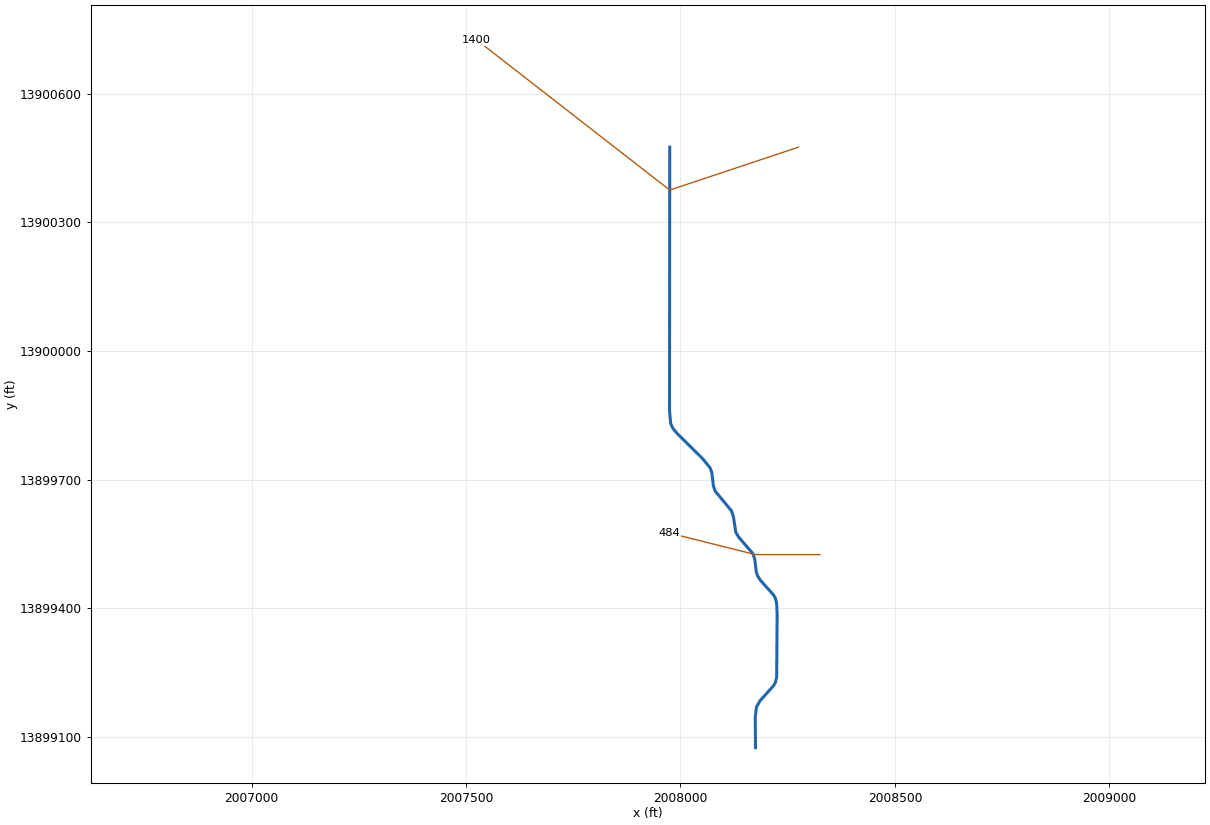
--- Stream0111_DS.prj (project) ---

Proj Title=Stream0111_DS Base Level Engineering
Current Plan=p01
Default Exp/Contr=0.3,0.1
English Units
Geom File=g01
Flow File=f01
Plan File=p01
BEGIN DESCRIPTION:
Stream0111_DS
END DESCRIPTION:

--- Stream0111_DS.p01 (plan) ---

Plan Title=Multiple Run
Short Identifier=Multiple
Geom File=g01
Flow File=f01
Subcritical Flow
K Sum by GR= 0
Std Step Tol= 0.01
Critical Tol= 0.01
Num of Std Step Trials= 20
Max Error Tol= 0.3
Flow Tol Ratio= 0.001
Split Flow NTrial= 30
Split Flow Tol= 0.02
Split Flow Ratio= 0.02
Log Output Level= 0
Friction Slope Method= 1
Unsteady Friction Slope Method= 2
Unsteady Bridges Friction Slope Method= 1
Parabolic Critical Depth
Global Vel Dist=  1 , 1 , 1
Global Log Level= 0
CheckData=True
Encroach Param= -1, 0, 0, 0
BEGIN DESCRIPTION:
Multiple Run
END DESCRIPTION:

--- Stream0111_DS.f01 (steady flow) ---

Flow Title=Multiple
Number of Profiles=7
Profile Names=10-year,25-year,50-year,1pct_min,100-year,1pct_plu,500-year
River Rch & RM= Stream0111_DS,Reach-1,1400
    1237    2131    2995    2040    4071    8122    7443
Boundary for River Rch & Prof#=Stream0111_DS,Reach-1,1
Up Type=0
Dn Type=3
Dn Slope=0.005
Boundary for River Rch & Prof#=Stream0111_DS,Reach-1,2
Up Type=0
Dn Type=3
Dn Slope=0.005
Boundary for River Rch & Prof#=Stream0111_DS,Reach-1,3
Up Type=0
Dn Type=3
Dn Slope=0.005
Boundary for River Rch & Prof#=Stream0111_DS,Reach-1,4
Up Type=0
Dn Type=3
Dn Slope=0.005
Boundary for River Rch & Prof#=Stream0111_DS,Reach-1,5
Up Type=0
Dn Type=3
Dn Slope=0.005
Boundary for River Rch & Prof#=Stream0111_DS,Reach-1,6
Up Type=0
Dn Type=3
Dn Slope=0.005
Boundary for River Rch & Prof#=Stream0111_DS,Reach-1,7
Up Type=0
Dn Type=3
Dn Slope=0.005

--- Stream0111_DS.g01 (geometry) ---

Geom Title=Existing Conditions

River Reach=Stream0111_DS,Reach-1
Reach XY= 30
      2007975.00     13900475.00      2007974.50     13899861.16
      2007977.18     13899830.45      2007982.83     13899818.81
      2007991.46     13899808.25      2008051.94     13899748.44
      2008069.15     13899727.29      2008073.33     13899715.22
      2008076.86     13899684.86      2008081.10     13899672.81
      2008118.92     13899627.20      2008123.35     13899614.31
      2008129.16     13899576.72      2008136.08     13899565.45
      2008168.92     13899527.20      2008173.35     13899514.32
      2008176.67     13899485.69      2008179.19     13899476.74
      2008186.14     13899465.47      2008216.91     13899431.07
      2008221.25     13899423.45      2008224.33     13899411.09
      2008225.46     13899384.28      2008224.33     13899238.91
      2008221.25     13899226.55      2008216.90     13899218.93
      2008185.86     13899184.64      2008177.10     13899169.13
      2008174.37     13899145.26      2008175.00     13899075.00

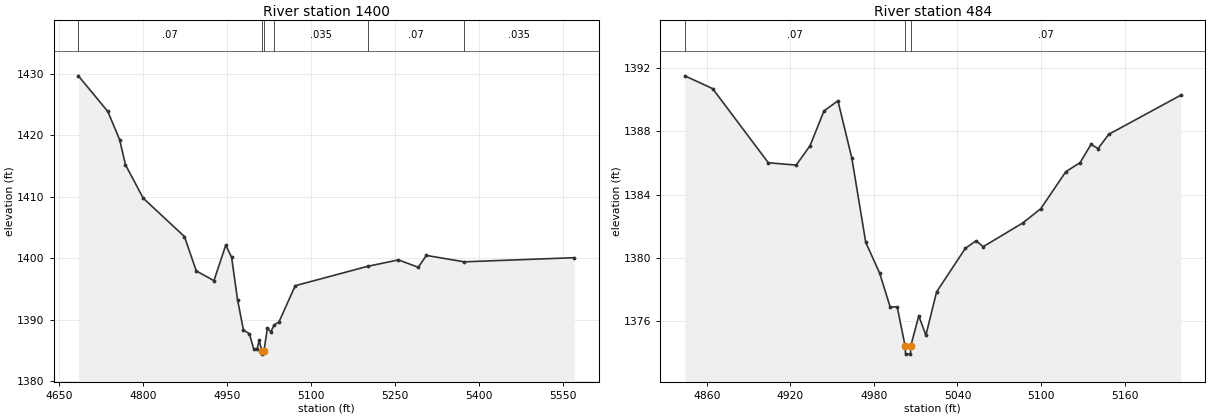
Type RM Length L Ch R = 1,1400,916,916,916
BEGIN DESCRIPTION:
Stream0111_DS 2.0
END DESCRIPTION:
XS GIS Cut Line= 3
      2008274.97     13900474.99      2007975.00     13900375.00
      2007524.99     13900725.01
#Sta/Elev= 30
  4683.8 1429.71  4736.5 1423.91  4757.6 1419.32  4768.1 1415.22  4799.7 1409.80
  4873.5 1403.54  4894.6 1397.95  4926.2 1396.36  4947.3 1402.14  4957.8 1400.17
  4968.4 1393.26  4978.9 1388.33  4989.5 1387.72  4997.4 1385.21  5003.2 1385.21
  5007.2 1386.68  5011.6 1384.90  5011.8 1384.40  5015.6 1384.90  5021.7 1388.62
  5028.0 1388.02  5033.6 1389.13  5042.5 1389.65  5071.5 1395.54  5201.1 1398.70
  5256.1 1399.74  5291.4 1398.54  5305.9 1400.47  5373.5 1399.43  5570.1 1400.10
#Mann=6,-1,0
  4683.8    0.07       0  5011.6    0.05       0  5015.6    0.07       0
  5033.6   0.035       0  5201.1    0.07       0  5373.5   0.035       0
Bank Sta=5011.6,5015.6
Exp/Cntr=0.3,0.1

Type RM Length L Ch R = 1,484,0,0,0
BEGIN DESCRIPTION:
Stream0111_DS 1.0
END DESCRIPTION:
XS GIS Cut Line= 3
      2008325.02     13899525.00      2008175.00     13899525.00
      2007974.98     13899575.01
#Sta/Elev= 30
  4844.1 1391.52  4864.1 1390.71  4904.1 1386.02  4924.1 1385.87  4934.1 1387.10
  4944.1 1389.30  4954.1 1389.94  4964.1 1386.31  4974.1 1380.98  4984.1 1379.03
  4991.6 1376.90  4996.7 1376.90  5002.4 1374.41  5002.7 1373.91  5006.2 1373.91
  5006.4 1374.41  5012.2 1376.33  5017.3 1375.11  5025.0 1377.85  5045.7 1380.61
  5053.4 1381.08  5058.5 1380.71  5086.9 1382.21  5099.8 1383.11  5117.8 1385.45
  5128.1 1386.03  5135.9 1387.18  5141.0 1386.92  5148.7 1387.82  5200.3 1390.29
#Mann=3,-1,0
  4844.1    0.07       0  5002.4    0.05       0  5006.4    0.07       0
Bank Sta=5002.4,5006.4
Exp/Cntr=0.3,0.1

Chan Stop Cuts=-1