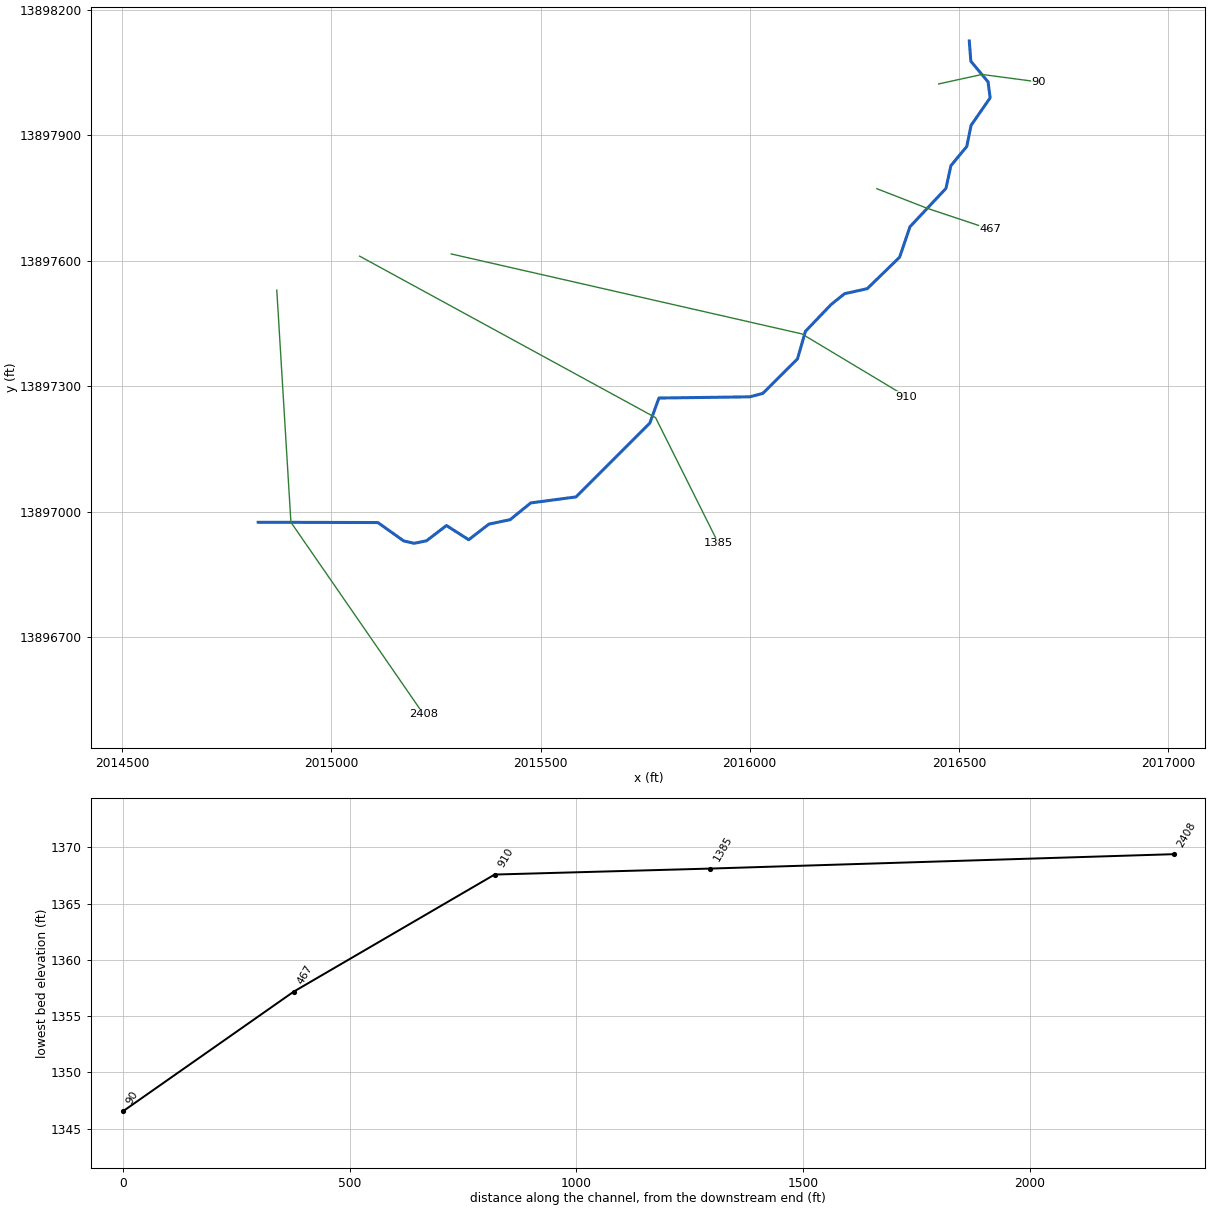
--- Stream0112_DS.prj (project) ---

Proj Title=Stream0112_DS Base Level Engineering
Current Plan=p01
Default Exp/Contr=0.3,0.1
English Units
Geom File=g01
Flow File=f01
Plan File=p01
BEGIN DESCRIPTION:
Stream0112_DS
END DESCRIPTION:

--- Stream0112_DS.p01 (plan) ---

Plan Title=Multiple Run
Short Identifier=Multiple
Geom File=g01
Flow File=f01
Subcritical Flow
K Sum by GR= 0
Std Step Tol= 0.01
Critical Tol= 0.01
Num of Std Step Trials= 20
Max Error Tol= 0.3
Flow Tol Ratio= 0.001
Split Flow NTrial= 30
Split Flow Tol= 0.02
Split Flow Ratio= 0.02
Log Output Level= 0
Friction Slope Method= 1
Unsteady Friction Slope Method= 2
Unsteady Bridges Friction Slope Method= 1
Parabolic Critical Depth
Global Vel Dist=  1 , 1 , 1
Global Log Level= 0
CheckData=True
Encroach Param= -1, 0, 0, 0
BEGIN DESCRIPTION:
Multiple Run
END DESCRIPTION:

--- Stream0112_DS.f01 (steady flow) ---

Flow Title=Multiple
Number of Profiles=7
Profile Names=10-year,25-year,50-year,1pct_min,100-year,1pct_plu,500-year
River Rch & RM= Stream0112_DS,Reach-1,2408
     867    1443    1980    1316    2626    5240    4573
River Rch & RM= Stream0112_DS,Reach-1,1385
     969    1623    2236    1492    2977    5940    5223
Boundary for River Rch & Prof#=Stream0112_DS,Reach-1,1
Up Type=0
Dn Type=3
Dn Slope=0.005
Boundary for River Rch & Prof#=Stream0112_DS,Reach-1,2
Up Type=0
Dn Type=3
Dn Slope=0.005
Boundary for River Rch & Prof#=Stream0112_DS,Reach-1,3
Up Type=0
Dn Type=3
Dn Slope=0.005
Boundary for River Rch & Prof#=Stream0112_DS,Reach-1,4
Up Type=0
Dn Type=3
Dn Slope=0.005
Boundary for River Rch & Prof#=Stream0112_DS,Reach-1,5
Up Type=0
Dn Type=3
Dn Slope=0.005
Boundary for River Rch & Prof#=Stream0112_DS,Reach-1,6
Up Type=0
Dn Type=3
Dn Slope=0.005
Boundary for River Rch & Prof#=Stream0112_DS,Reach-1,7
Up Type=0
Dn Type=3
Dn Slope=0.005

--- Stream0112_DS.g01 (geometry) ---

Geom Title=Existing Conditions

River Reach=Stream0112_DS,Reach-1
Reach XY= 30
      2014825.00     13896975.00      2015111.09     13896974.30
      2015172.83     13896930.40      2015197.84     13896924.70
      2015227.30     13896930.63      2015275.08     13896967.17
      2015328.23     13896933.24      2015376.63     13896970.59
      2015427.17     13896981.09      2015476.59     13897021.17
      2015584.79     13897035.52      2015761.26     13897212.05
      2015783.01     13897271.77      2016000.13     13897274.70
      2016031.21     13897282.80      2016114.23     13897365.30
      2016133.15     13897431.06      2016194.77     13897495.42
      2016226.64     13897521.03      2016281.06     13897533.15
      2016358.36     13897608.29      2016383.18     13897681.04
      2016469.15     13897772.71      2016481.10     13897827.19
      2016518.92     13897872.80      2016529.22     13897923.28
      2016574.81     13897989.09      2016569.88     13898027.25
      2016528.69     13898076.49      2016525.00     13898125.00

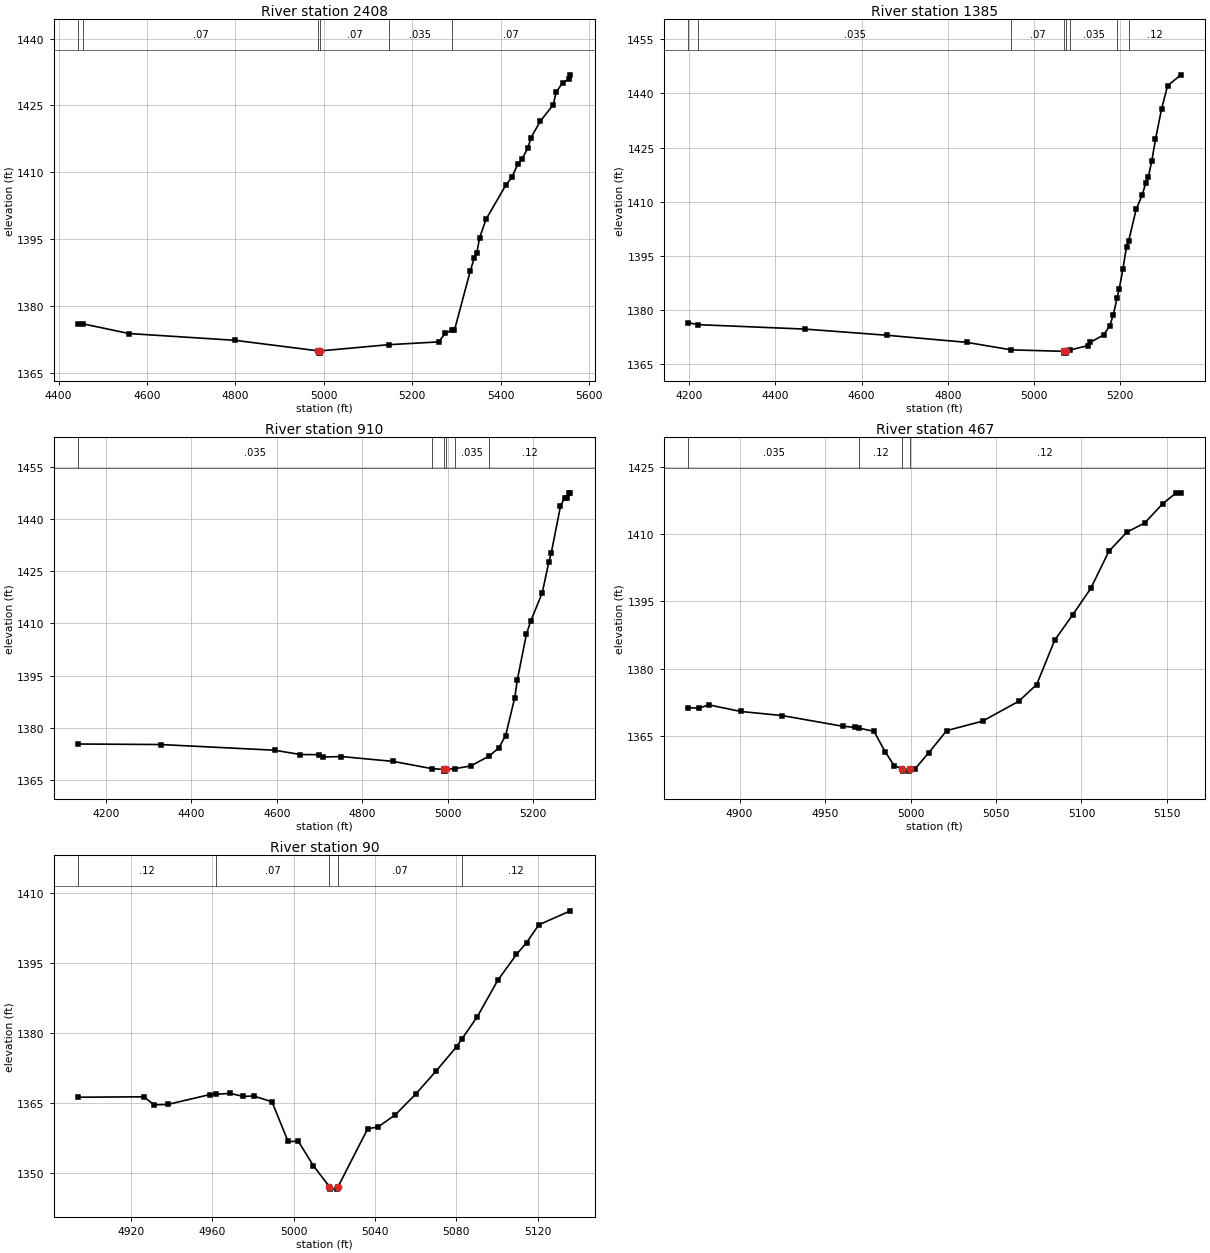
Type RM Length L Ch R = 1,2408,1023,1023,1023
BEGIN DESCRIPTION:
Stream0112_DS 4.0
END DESCRIPTION:
XS GIS Cut Line= 3
      2014869.48     13897529.59      2014903.23     13896975.02
      2015220.45     13896515.96
#Sta/Elev= 30
  4444.4 1376.03  4456.0 1375.95  4559.2 1373.79  4799.6 1372.26  4988.0 1369.89
  4988.2 1369.39  4991.7 1369.39  4992.0 1369.89  5146.5 1371.28  5259.8 1371.91
  5274.6 1373.80  5289.0 1374.53  5295.6 1374.55  5331.4 1387.85  5340.2 1390.69
  5346.1 1391.81  5352.5 1395.30  5367.2 1399.47  5411.9 1407.12  5425.5 1408.87
  5438.9 1411.81  5447.7 1412.85  5461.9 1415.46  5468.6 1417.74  5489.6 1421.42
  5519.3 1425.18  5525.4 1427.97  5540.3 1430.05  5555.1 1430.96  5558.0 1431.85
#Mann=6,-1,0
  4444.4   0.035       0  4456.0    0.07       0  4988.0    0.05       0
  4992.0    0.07       0  5146.5   0.035       0  5289.0    0.07       0
Bank Sta=4988,4992
Exp/Cntr=0.3,0.1

Type RM Length L Ch R = 1,1385,475,475,475
BEGIN DESCRIPTION:
Stream0112_DS 3.0
END DESCRIPTION:
XS GIS Cut Line= 3
      2015067.58     13897610.79      2015775.00     13897225.00
      2015925.00     13896924.99
#Sta/Elev= 30
  4198.9 1376.51  4221.4 1375.99  4467.9 1374.77  4658.7 1373.06  4843.8 1371.09
  4947.4 1369.01  5069.7 1368.61  5070.0 1368.11  5073.6 1368.11  5073.8 1368.61
  5084.1 1368.98  5124.9 1370.20  5130.5 1371.13  5161.2 1373.14  5175.2 1375.62
  5183.6 1378.70  5192.4 1383.38  5197.5 1386.00  5205.9 1391.36  5214.3 1397.60
  5219.3 1399.21  5236.7 1407.93  5250.6 1411.88  5259.0 1415.28  5264.6 1416.73
  5273.0 1421.39  5281.4 1427.28  5295.4 1435.63  5309.3 1442.08  5340.1 1445.15
#Mann=8,-1,0
  4198.9    0.05       0  4221.4   0.035       0  4947.4    0.07       0
  5069.7    0.05       0  5073.8    0.07       0  5084.1   0.035       0
  5192.4    0.07       0  5219.3    0.12       0
Bank Sta=5069.7,5073.8
Exp/Cntr=0.3,0.1

Type RM Length L Ch R = 1,910,443,443,443
BEGIN DESCRIPTION:
Stream0112_DS 2.0
END DESCRIPTION:
XS GIS Cut Line= 3
      2015286.50     13897616.11      2016125.00     13897425.00
      2016375.04     13897274.98
#Sta/Elev= 30
  4135.6 1375.37  4328.9 1375.22  4595.6 1373.58  4655.1 1372.35  4698.1 1372.31
  4708.4 1371.63  4751.3 1371.77  4872.5 1370.37  4963.5 1368.28  4990.9 1368.08
  4991.2 1367.58  4994.8 1367.58  4995.1 1368.08  5017.2 1368.30  5053.9 1369.06
  5097.4 1371.94  5120.0 1374.32  5135.5 1377.81  5156.9 1388.69  5162.8 1393.75
  5184.1 1406.88  5193.9 1410.57  5221.1 1418.79  5236.6 1427.64  5242.4 1430.33
  5263.8 1443.66  5273.5 1446.10  5279.4 1445.97  5284.2 1447.51  5287.2 1447.51
#Mann=6,-1,0
  4135.6   0.035       0  4963.5    0.07       0  4990.9    0.05       0
  4995.1    0.07       0  5017.2   0.035       0  5097.4    0.12       0
Bank Sta=4990.9,4995.1
Exp/Cntr=0.3,0.1

Type RM Length L Ch R = 1,467,377,377,377
BEGIN DESCRIPTION:
Stream0112_DS 1.0
END DESCRIPTION:
XS GIS Cut Line= 3
      2016303.90     13897772.04      2016425.00     13897725.00
      2016574.97     13897675.01
#Sta/Elev= 30
  4870.1 1371.30  4876.2 1371.19  4882.0 1371.93  4900.7 1370.46  4924.9 1369.55
  4960.5 1367.16  4967.8 1366.92  4970.1 1366.73  4978.6 1366.05  4985.1 1361.52
  4990.4 1358.40  4995.2 1357.68  4995.5 1357.18  4999.1 1357.18  4999.4 1357.68
  5002.6 1357.68  5010.6 1361.24  5021.1 1366.19  5042.2 1368.32  5063.3 1372.74
  5073.8 1376.46  5084.3 1386.31  5094.9 1392.00  5105.4 1397.84  5116.0 1406.11
  5126.5 1410.37  5137.0 1412.44  5147.6 1416.75  5155.5 1419.14  5158.1 1419.14
#Mann=4,-1,0
  4870.1   0.035       0  4970.1    0.12       0  4995.2    0.05       0
  4999.4    0.12       0
Bank Sta=4995.2,4999.4
Exp/Cntr=0.3,0.1

Type RM Length L Ch R = 1,90,0,0,0
BEGIN DESCRIPTION:
Stream0112_DS 0.0
END DESCRIPTION:
XS GIS Cut Line= 3
      2016451.83     13898022.38      2016555.48     13898045.02
      2016690.49     13898027.04
#Sta/Elev= 30
  4893.9 1366.26  4926.2 1366.35  4931.3 1364.63  4938.1 1364.72  4958.6 1366.82
  4961.9 1366.90  4968.8 1367.08  4975.2 1366.43  4980.3 1366.53  4989.3 1365.28
  4997.2 1356.78  5002.3 1356.78  5009.6 1351.61  5017.6 1347.04  5017.9 1346.54
  5021.5 1346.54  5021.8 1347.04  5036.4 1359.50  5041.5 1359.88  5050.0 1362.49
  5060.0 1366.92  5070.1 1371.90  5080.2 1377.13  5082.9 1378.84  5090.3 1383.52
  5100.4 1391.34  5109.6 1396.89  5114.6 1399.44  5120.6 1403.26  5136.2 1406.26
#Mann=5,-1,0
  4893.9    0.12       0  4961.9    0.07       0  5017.6    0.05       0
  5021.8    0.07       0  5082.9    0.12       0
Bank Sta=5017.6,5021.8
Exp/Cntr=0.3,0.1

Chan Stop Cuts=-1