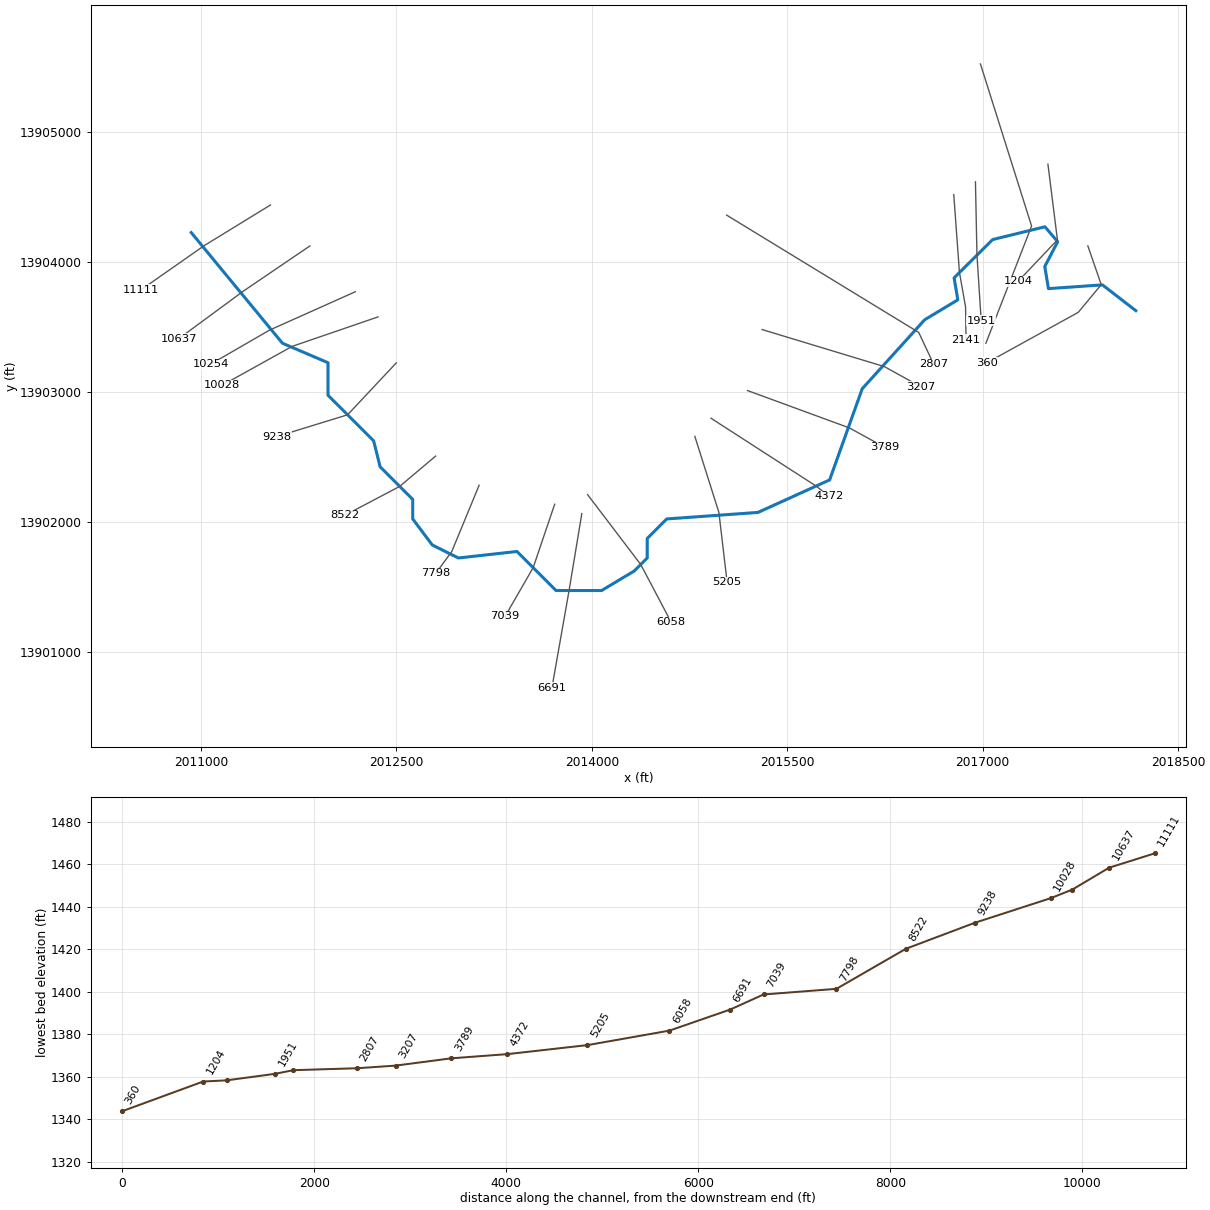
--- Stream0113_DS.prj (project) ---

Proj Title=Stream0113_DS Base Level Engineering
Current Plan=p01
Default Exp/Contr=0.3,0.1
English Units
Geom File=g01
Flow File=f01
Plan File=p01
BEGIN DESCRIPTION:
Stream0113_DS
END DESCRIPTION:

--- Stream0113_DS.p01 (plan) ---

Plan Title=Multiple Run
Short Identifier=Multiple
Geom File=g01
Flow File=f01
Subcritical Flow
K Sum by GR= 0
Std Step Tol= 0.01
Critical Tol= 0.01
Num of Std Step Trials= 20
Max Error Tol= 0.3
Flow Tol Ratio= 0.001
Split Flow NTrial= 30
Split Flow Tol= 0.02
Split Flow Ratio= 0.02
Log Output Level= 0
Friction Slope Method= 1
Unsteady Friction Slope Method= 2
Unsteady Bridges Friction Slope Method= 1
Parabolic Critical Depth
Global Vel Dist=  1 , 1 , 1
Global Log Level= 0
CheckData=True
Encroach Param= -1, 0, 0, 0
BEGIN DESCRIPTION:
Multiple Run
END DESCRIPTION:

--- Stream0113_DS.f01 (steady flow) ---

Flow Title=Multiple
Number of Profiles=7
Profile Names=10-year,25-year,50-year,1pct_min,100-year,1pct_plu,500-year
River Rch & RM= Stream0113_DS,Reach-1,11111
     320     504     667     431     859    1714    1405
River Rch & RM= Stream0113_DS,Reach-1,10637
     999    1691    2348    1580    3153    6291    5626
River Rch & RM= Stream0113_DS,Reach-1,3207
    1482    2567    3620    2471    4930    9837    9054
River Rch & RM= Stream0113_DS,Reach-1,2807
    1576    2736    3862    2638    5263   10502    9682
Boundary for River Rch & Prof#=Stream0113_DS,Reach-1,1
Up Type=0
Dn Type=3
Dn Slope=0.005
Boundary for River Rch & Prof#=Stream0113_DS,Reach-1,2
Up Type=0
Dn Type=3
Dn Slope=0.005
Boundary for River Rch & Prof#=Stream0113_DS,Reach-1,3
Up Type=0
Dn Type=3
Dn Slope=0.005
Boundary for River Rch & Prof#=Stream0113_DS,Reach-1,4
Up Type=0
Dn Type=3
Dn Slope=0.005
Boundary for River Rch & Prof#=Stream0113_DS,Reach-1,5
Up Type=0
Dn Type=3
Dn Slope=0.005
Boundary for River Rch & Prof#=Stream0113_DS,Reach-1,6
Up Type=0
Dn Type=3
Dn Slope=0.005
Boundary for River Rch & Prof#=Stream0113_DS,Reach-1,7
Up Type=0
Dn Type=3
Dn Slope=0.005

--- Stream0113_DS.g01 (geometry) ---

Geom Title=Existing Conditions

River Reach=Stream0113_DS,Reach-1
Reach XY= 30
      2010925.00     13904225.00      2011625.00     13903375.00
      2011975.00     13903225.00      2011975.00     13902975.00
      2012325.00     13902625.00      2012375.00     13902425.00
      2012625.00     13902175.00      2012625.00     13902025.00
      2012775.00     13901825.00      2012975.00     13901725.00
      2013425.00     13901775.00      2013725.00     13901475.00
      2014075.00     13901475.00      2014325.00     13901625.00
      2014425.00     13901725.00      2014425.00     13901875.00
      2014575.00     13902025.00      2015275.00     13902075.00
      2015825.00     13902325.00      2016075.00     13903025.00
      2016554.52     13903555.38      2016808.72     13903708.26
      2016780.40     13903877.43      2017076.47     13904171.46
      2017477.47     13904269.55      2017575.41     13904154.87
      2017476.19     13903964.50      2017504.34     13903794.40
      2017918.89     13903823.20      2018175.00     13903625.00

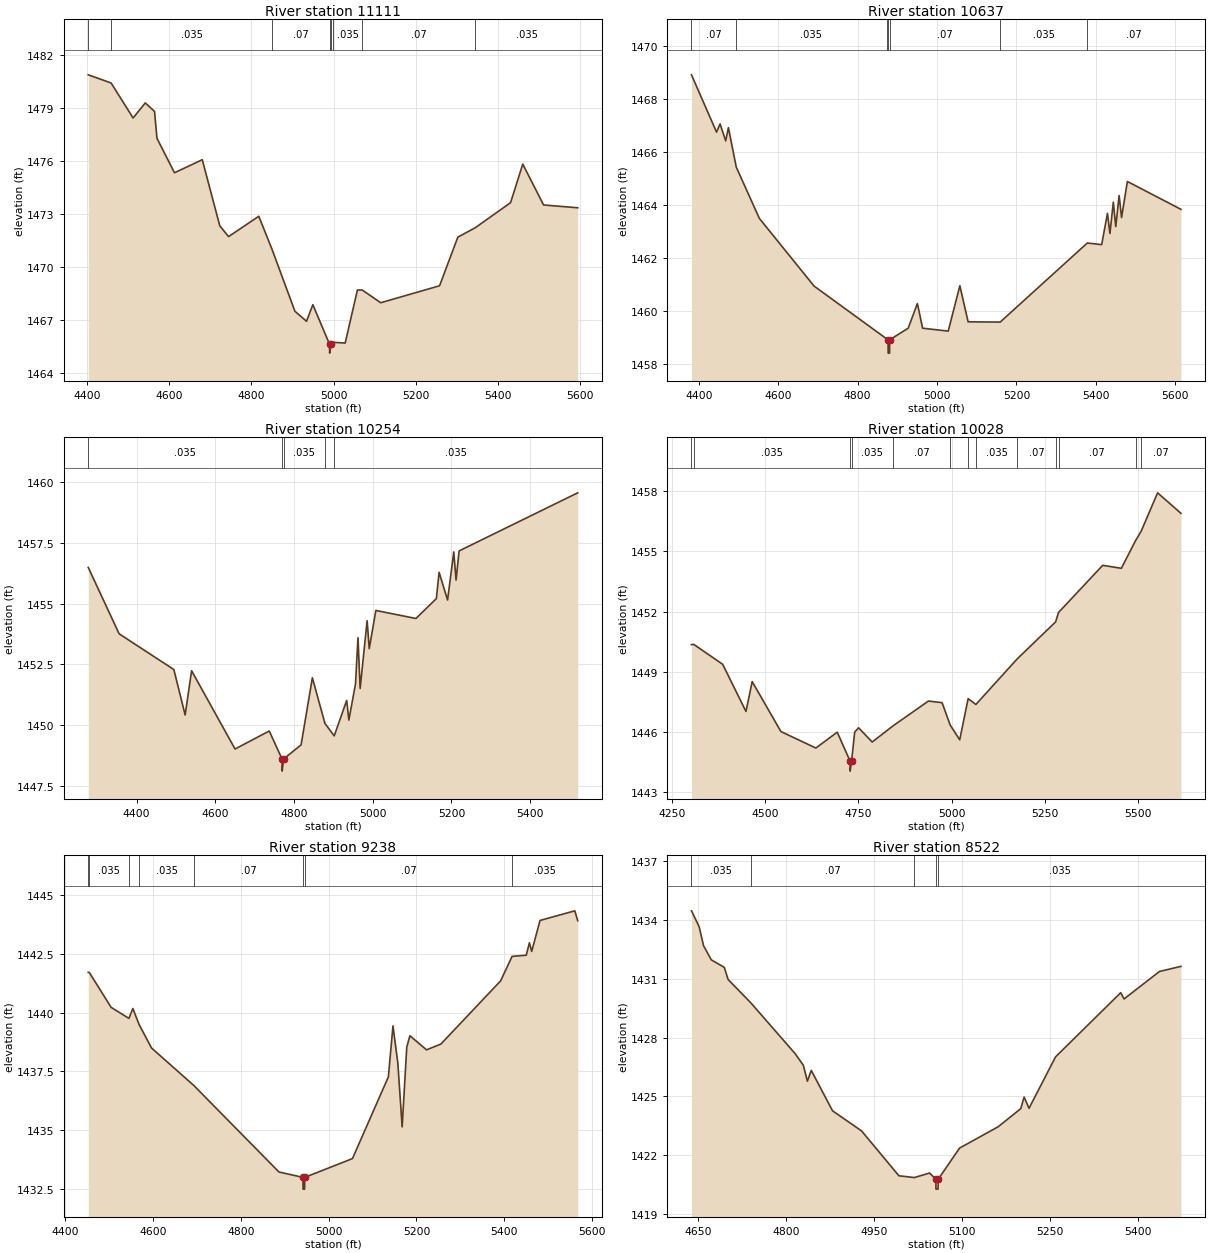
Type RM Length L Ch R = 1,11111,474,474,474
BEGIN DESCRIPTION:
Stream0113_DS 19.0
END DESCRIPTION:
XS GIS Cut Line= 3
      2011533.13     13904436.86      2011025.00     13904125.00
      2010538.76     13903784.69
#Sta/Elev= 30
  4403.8 1480.89  4459.3 1480.43  4512.8 1478.45  4542.4 1479.30  4564.9 1478.82
  4570.8 1477.30  4613.4 1475.35  4680.9 1476.09  4723.5 1472.35  4744.8 1471.74
  4818.3 1472.89  4850.0 1471.05  4906.1 1467.52  4934.3 1466.95  4949.7 1467.89
  4990.3 1465.65  4990.5 1465.15  4994.3 1465.65  4999.4 1465.76  5028.3 1465.72
  5058.0 1468.72  5069.7 1468.72  5114.7 1468.00  5257.7 1468.96  5302.1 1471.71
  5344.3 1472.24  5430.3 1473.66  5459.9 1475.84  5510.5 1473.53  5593.5 1473.37
#Mann=8,-1,0
  4403.8    0.07       0  4459.3   0.035       0  4850.0    0.07       0
  4990.3   0.035       0  4994.3    0.07       0  4999.4   0.035       0
  5069.7    0.07       0  5344.3   0.035       0
Bank Sta=4990.3,4994.3
Exp/Cntr=0.3,0.1

Type RM Length L Ch R = 1,10637,383,383,383
BEGIN DESCRIPTION:
Stream0113_DS 18.0
END DESCRIPTION:
XS GIS Cut Line= 3
      2011836.26     13904122.71      2011325.00     13903775.00
      2010830.51     13903410.68
#Sta/Elev= 30
  4381.7 1468.90  4444.8 1466.74  4453.7 1467.05  4467.9 1466.41  4474.7 1466.91
  4494.5 1465.42  4552.6 1463.49  4690.2 1460.94  4873.0 1458.95  4876.7 1458.91
  4877.0 1458.41  4880.5 1458.41  4880.7 1458.91  4927.4 1459.35  4950.6 1460.28
  4963.7 1459.35  5028.2 1459.24  5057.5 1460.95  5078.3 1459.59  5159.0 1459.58
  5378.4 1462.56  5414.6 1462.50  5429.2 1463.68  5435.4 1462.92  5443.9 1464.10
  5450.1 1463.18  5458.5 1464.35  5464.7 1463.52  5479.3 1464.88  5614.2 1463.83
#Mann=7,-1,0
  4381.7    0.07       0  4494.5   0.035       0  4873.0    0.07       0
  4876.7    0.05       0  4880.7    0.07       0  5159.0   0.035       0
  5378.4    0.07       0
Bank Sta=4876.7,4880.7
Exp/Cntr=0.3,0.1

Type RM Length L Ch R = 1,10254,226,226,226
BEGIN DESCRIPTION:
Stream0113_DS 17.0
END DESCRIPTION:
XS GIS Cut Line= 3
      2012184.68     13903770.65      2011525.00     13903475.00
      2011074.12     13903214.14
#Sta/Elev= 30
  4277.1 1456.49  4355.5 1453.76  4494.6 1452.29  4523.3 1450.42  4539.7 1452.24
  4650.1 1449.02  4737.0 1449.76  4769.5 1448.61  4769.8 1448.11  4773.5 1448.61
  4817.9 1449.19  4846.6 1451.95  4878.6 1450.07  4902.1 1449.56  4933.8 1451.02
  4939.3 1450.21  4956.2 1451.70  4962.5 1453.60  4968.0 1451.51  4985.7 1454.30
  4991.1 1453.15  5007.9 1454.72  5109.8 1454.39  5161.7 1455.21  5168.6 1456.29
  5190.2 1455.15  5205.9 1457.13  5211.7 1455.97  5219.5 1457.17  5520.9 1459.56
#Mann=5,-1,0
  4277.1   0.035       0  4769.5   0.035       0  4773.5   0.035       0
  4878.6    0.07       0  4902.1   0.035       0
Bank Sta=4769.5,4773.5
Exp/Cntr=0.3,0.1

Type RM Length L Ch R = 1,10028,790,790,790
BEGIN DESCRIPTION:
Stream0113_DS 16.0
END DESCRIPTION:
XS GIS Cut Line= 3
      2012358.92     13903577.26      2011699.37     13903350.63
      2011161.62     13903051.61
#Sta/Elev= 30
  4302.6 1450.36  4309.0 1450.37  4386.3 1449.38  4448.8 1447.03  4465.4 1448.52
  4542.5 1446.03  4636.2 1445.21  4693.5 1446.00  4728.0 1444.56  4728.2 1444.06
  4732.0 1444.56  4740.3 1446.00  4750.7 1446.22  4787.2 1445.51  4843.6 1446.32
  4938.1 1447.55  4974.7 1447.47  4996.3 1446.36  5022.0 1445.62  5044.6 1447.67
  5065.4 1447.38  5176.2 1449.65  5279.1 1451.49  5287.0 1451.96  5405.5 1454.31
  5455.5 1454.16  5493.6 1455.54  5508.7 1456.01  5552.7 1457.92  5615.3 1456.90
#Mann=13,-1,0
  4302.6    0.07       0  4309.0   0.035       0  4728.0   0.035       0
  4732.0   0.035       0  4843.6    0.07       0  4996.3   0.035       0
  5044.6    0.07       0  5065.4   0.035       0  5176.2    0.07       0
  5279.1   0.035       0  5287.0    0.07       0  5493.6   0.035       0
  5508.7    0.07       0
Bank Sta=4728,4732
Exp/Cntr=0.3,0.1

Type RM Length L Ch R = 1,9238,716,716,716
BEGIN DESCRIPTION:
Stream0113_DS 15.0
END DESCRIPTION:
XS GIS Cut Line= 3
      2012499.24     13903224.21      2012125.00     13902825.00
      2011582.97     13902658.24
#Sta/Elev= 30
  4452.8 1441.71  4455.0 1441.71  4504.9 1440.22  4545.4 1439.75  4554.3 1440.17
  4568.5 1439.49  4596.8 1438.49  4693.3 1436.89  4886.9 1433.21  4941.6 1432.98
  4941.8 1432.48  4945.3 1432.48  4945.6 1432.98  5054.3 1433.78  5136.0 1437.26
  5146.5 1439.43  5157.6 1437.84  5167.4 1435.13  5177.9 1438.53  5185.1 1439.01
  5223.0 1438.41  5255.7 1438.66  5391.7 1441.35  5417.6 1442.39  5449.9 1442.44
  5457.1 1442.97  5462.3 1442.60  5481.3 1443.92  5560.4 1444.33  5567.1 1443.91
#Mann=8,-1,0
  4452.8    0.07       0  4455.0   0.035       0  4545.4    0.07       0
  4568.5   0.035       0  4693.3    0.07       0  4941.6    0.05       0
  4945.6    0.07       0  5417.6   0.035       0
Bank Sta=4941.6,4945.6
Exp/Cntr=0.3,0.1

Type RM Length L Ch R = 1,8522,724,724,724
BEGIN DESCRIPTION:
Stream0113_DS 14.0
END DESCRIPTION:
XS GIS Cut Line= 3
      2012800.76     13902507.82      2012525.00     13902275.00
      2012105.88     13902053.83
#Sta/Elev= 30
  4639.1 1434.46  4652.2 1433.65  4659.7 1432.68  4673.0 1431.96  4695.1 1431.58
  4701.6 1430.96  4739.8 1429.79  4816.0 1427.18  4829.9 1426.59  4836.8 1425.78
  4843.4 1426.33  4879.7 1424.27  4929.1 1423.25  4992.9 1420.96  5019.3 1420.87
  5045.2 1421.10  5055.9 1420.78  5056.1 1420.28  5059.6 1420.28  5059.9 1420.78
  5096.3 1422.37  5162.3 1423.46  5200.7 1424.38  5206.4 1424.97  5214.8 1424.40
  5260.1 1427.02  5371.2 1430.29  5376.9 1429.97  5437.3 1431.37  5473.9 1431.63
#Mann=5,-1,0
  4639.1   0.035       0  4739.8    0.07       0  5019.3   0.035       0
  5055.9    0.05       0  5059.9   0.035       0
Bank Sta=5055.9,5059.9
Exp/Cntr=0.3,0.1

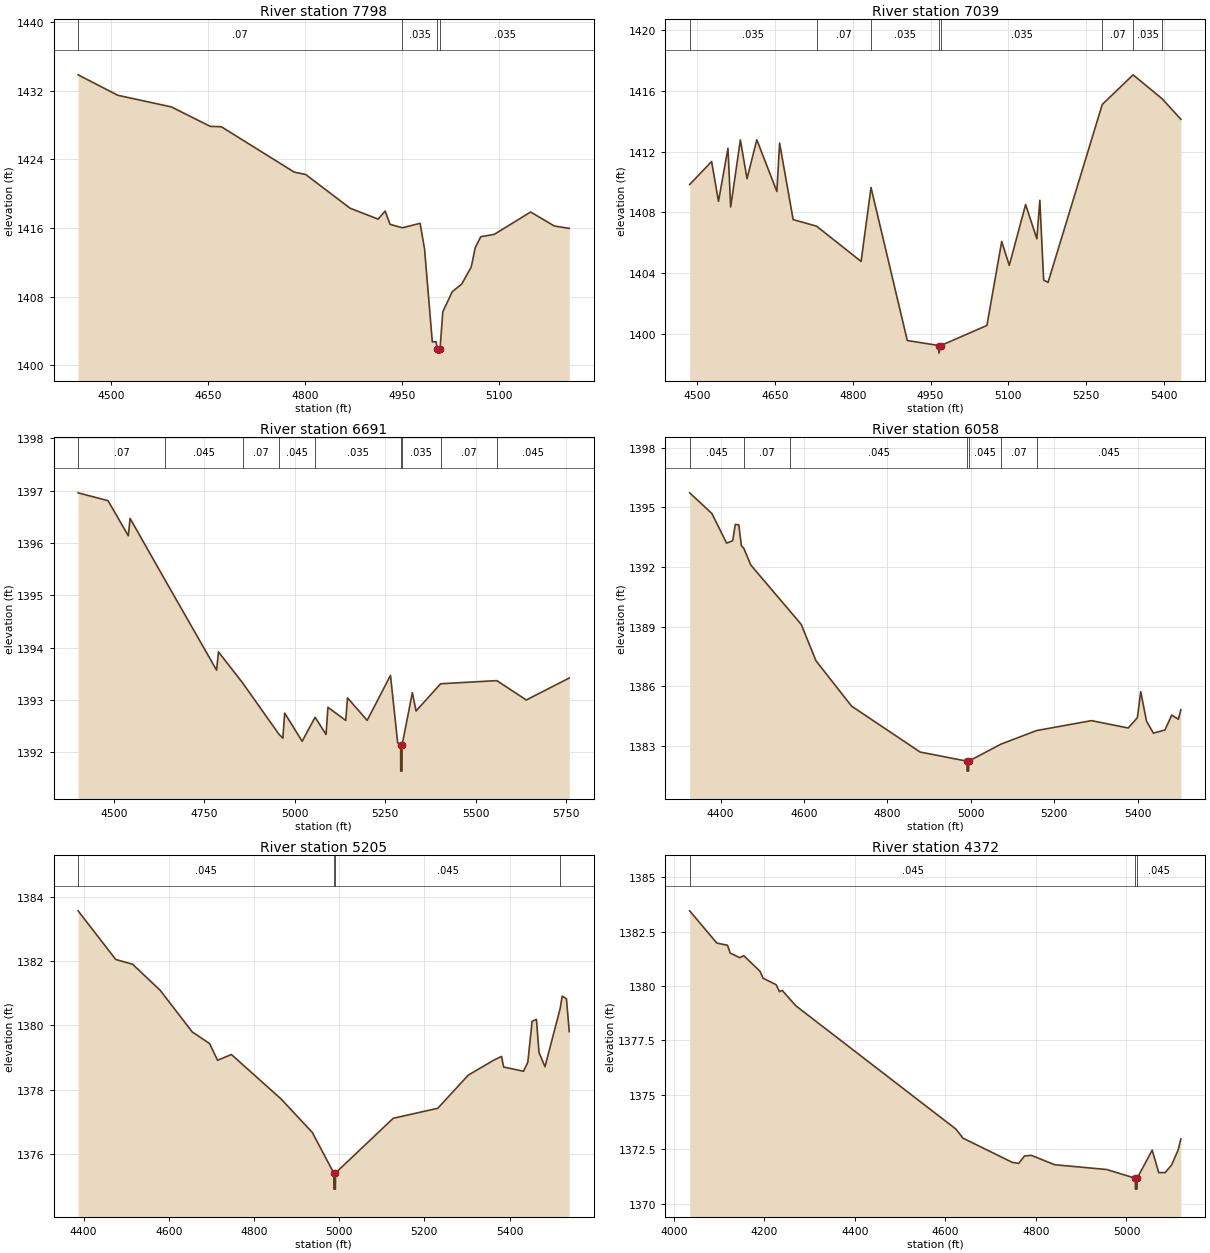
Type RM Length L Ch R = 1,7798,759,759,759
BEGIN DESCRIPTION:
Stream0113_DS 13.0
END DESCRIPTION:
XS GIS Cut Line= 3
      2013134.69     13902284.00      2012925.00     13901775.00
      2012801.48     13901606.29
#Sta/Elev= 30
  4449.5 1433.85  4511.1 1431.46  4593.8 1430.11  4653.9 1427.84  4671.0 1427.80
  4783.7 1422.51  4801.5 1422.23  4870.2 1418.30  4913.5 1417.03  4924.3 1417.97
  4932.0 1416.42  4951.0 1416.02  4978.4 1416.54  4985.3 1413.55  4997.3 1402.73
  5003.1 1402.73  5005.3 1401.91  5005.6 1401.41  5009.1 1401.41  5009.3 1401.91
  5013.5 1406.23  5028.2 1408.58  5042.8 1409.46  5057.5 1411.46  5063.7 1413.70
  5072.2 1414.98  5093.0 1415.25  5149.4 1417.86  5185.9 1416.23  5209.1 1415.95
#Mann=4,-1,0
  4449.5    0.07       0  4951.0   0.035       0  5005.3   0.035       0
  5009.3   0.035       0
Bank Sta=5005.3,5009.3
Exp/Cntr=0.3,0.1

Type RM Length L Ch R = 1,7039,348,348,348
BEGIN DESCRIPTION:
Stream0113_DS 12.0
END DESCRIPTION:
XS GIS Cut Line= 3
      2013714.45     13902137.57      2013549.43     13901650.57
      2013333.51     13901275.82
#Sta/Elev= 30
  4485.8 1409.84  4528.1 1411.35  4541.3 1408.73  4559.6 1412.22  4564.8 1408.36
  4583.5 1412.77  4596.3 1410.22  4615.2 1412.78  4653.8 1409.38  4659.1 1412.56
  4685.2 1407.53  4730.3 1407.10  4816.2 1404.78  4835.3 1409.64  4905.2 1399.58
  4966.0 1399.25  4966.2 1398.75  4970.0 1399.25  5058.7 1400.57  5087.2 1406.09
  5101.8 1404.52  5133.3 1408.52  5154.9 1406.27  5160.7 1408.80  5168.0 1403.56
  5176.5 1403.40  5281.0 1415.10  5340.4 1417.05  5396.6 1415.47  5432.5 1414.13
#Mann=8,-1,0
  4485.8   0.035       0  4730.3    0.07       0  4835.3   0.035       0
  4966.0   0.035       0  4970.0   0.035       0  5281.0    0.07       0
  5340.4   0.035       0  5396.6    0.07       0
Bank Sta=4966,4970
Exp/Cntr=0.3,0.1

Type RM Length L Ch R = 1,6691,633,633,633
BEGIN DESCRIPTION:
Stream0113_DS 11.0
END DESCRIPTION:
XS GIS Cut Line= 3
      2013922.83     13902065.75      2013825.00     13901475.00
      2013693.56     13900728.08
#Sta/Elev= 30
  4401.2 1396.96  4483.9 1396.81  4539.9 1396.14  4544.9 1396.47  4641.8 1395.29
  4783.9 1393.57  4789.0 1393.92  4855.5 1393.33  4955.7 1392.35  4967.0 1392.27
  4972.0 1392.75  5020.3 1392.21  5056.1 1392.67  5086.4 1392.34  5091.5 1392.86
  5140.7 1392.61  5145.7 1393.04  5200.0 1392.61  5264.4 1393.47  5284.3 1392.18
  5292.5 1392.14  5292.7 1391.64  5296.2 1391.64  5296.5 1392.14  5324.9 1393.14
  5335.1 1392.79  5402.9 1393.31  5558.2 1393.37  5639.7 1393.00  5758.4 1393.42
#Mann=9,-1,0
  4401.2    0.07       0  4641.8   0.045       0  4855.5    0.07       0
  4955.7   0.045       0  5056.1   0.035       0  5292.5   0.045       0
  5296.5   0.035       0  5402.9    0.07       0  5558.2   0.045       0
Bank Sta=5292.5,5296.5
Exp/Cntr=0.3,0.1

Type RM Length L Ch R = 1,6058,853,853,853
BEGIN DESCRIPTION:
Stream0113_DS 10.0
END DESCRIPTION:
XS GIS Cut Line= 3
      2013967.24     13902211.54      2014375.00     13901675.00
      2014609.71     13901229.89
#Sta/Elev= 30
  4326.1 1395.73  4379.3 1394.69  4414.6 1393.20  4429.2 1393.32  4435.4 1394.14
  4443.7 1394.12  4450.0 1393.07  4456.0 1392.93  4472.5 1392.10  4567.6 1389.75
  4593.4 1389.11  4628.8 1387.28  4714.1 1385.00  4878.4 1382.69  4990.7 1382.23
  4991.0 1381.73  4994.5 1381.73  4994.7 1382.23  5072.3 1383.09  5157.3 1383.77
  5288.9 1384.27  5377.0 1383.90  5399.0 1384.42  5407.0 1385.73  5421.0 1384.24
  5437.4 1383.64  5465.1 1383.80  5481.4 1384.55  5497.4 1384.34  5503.2 1384.82
#Mann=7,-1,0
  4326.1   0.045       0  4456.0    0.07       0  4567.6   0.045       0
  4990.7   0.045       0  4994.7   0.045       0  5072.3    0.07       0
  5157.3   0.045       0
Bank Sta=4990.7,4994.7
Exp/Cntr=0.3,0.1

Type RM Length L Ch R = 1,5205,833,833,833
BEGIN DESCRIPTION:
Stream0113_DS 9.0
END DESCRIPTION:
XS GIS Cut Line= 3
      2014790.42     13902659.24      2014975.00     13902075.00
      2015038.16     13901538.40
#Sta/Elev= 30
  4387.3 1383.56  4475.6 1382.05  4515.5 1381.90  4580.2 1381.09  4655.3 1379.80
  4695.9 1379.44  4714.7 1378.92  4747.1 1379.10  4863.7 1377.72  4937.1 1376.68
  4987.5 1375.42  4987.8 1374.92  4991.3 1374.92  4991.5 1375.42  5127.1 1377.12
  5231.6 1377.43  5303.3 1378.46  5362.5 1378.92  5381.3 1379.04  5386.3 1378.71
  5433.0 1378.58  5443.0 1378.86  5453.1 1380.13  5463.2 1380.19  5469.3 1379.16
  5483.3 1378.72  5519.0 1380.53  5523.6 1380.91  5533.7 1380.83  5540.3 1379.81
#Mann=4,-1,0
  4387.3   0.045       0  4987.5   0.045       0  4991.5   0.045       0
  5519.0   0.035       0
Bank Sta=4987.5,4991.5
Exp/Cntr=0.3,0.1

Type RM Length L Ch R = 1,4372,583,583,583
BEGIN DESCRIPTION:
Stream0113_DS 8.0
END DESCRIPTION:
XS GIS Cut Line= 3
      2014914.66     13902798.45      2015725.00     13902275.00
      2015818.52     13902199.64
#Sta/Elev= 30
  4035.3 1383.45  4095.2 1381.97  4118.8 1381.87  4124.8 1381.51  4145.9 1381.30
  4154.8 1381.39  4190.5 1380.68  4197.4 1380.36  4226.2 1380.06  4233.6 1379.74
  4239.6 1379.80  4269.9 1379.09  4623.6 1373.43  4638.8 1373.02  4747.6 1371.91
  4761.9 1371.86  4774.7 1372.20  4789.9 1372.23  4841.3 1371.80  4956.1 1371.58
  5019.6 1371.18  5019.8 1370.68  5023.3 1370.68  5023.6 1371.18  5056.8 1372.47
  5071.2 1371.44  5085.6 1371.44  5100.0 1371.80  5114.3 1372.49  5120.1 1372.98
#Mann=3,-1,0
  4035.3   0.045       0  5019.6   0.045       0  5023.6   0.045       0
Bank Sta=5019.6,5023.6
Exp/Cntr=0.3,0.1

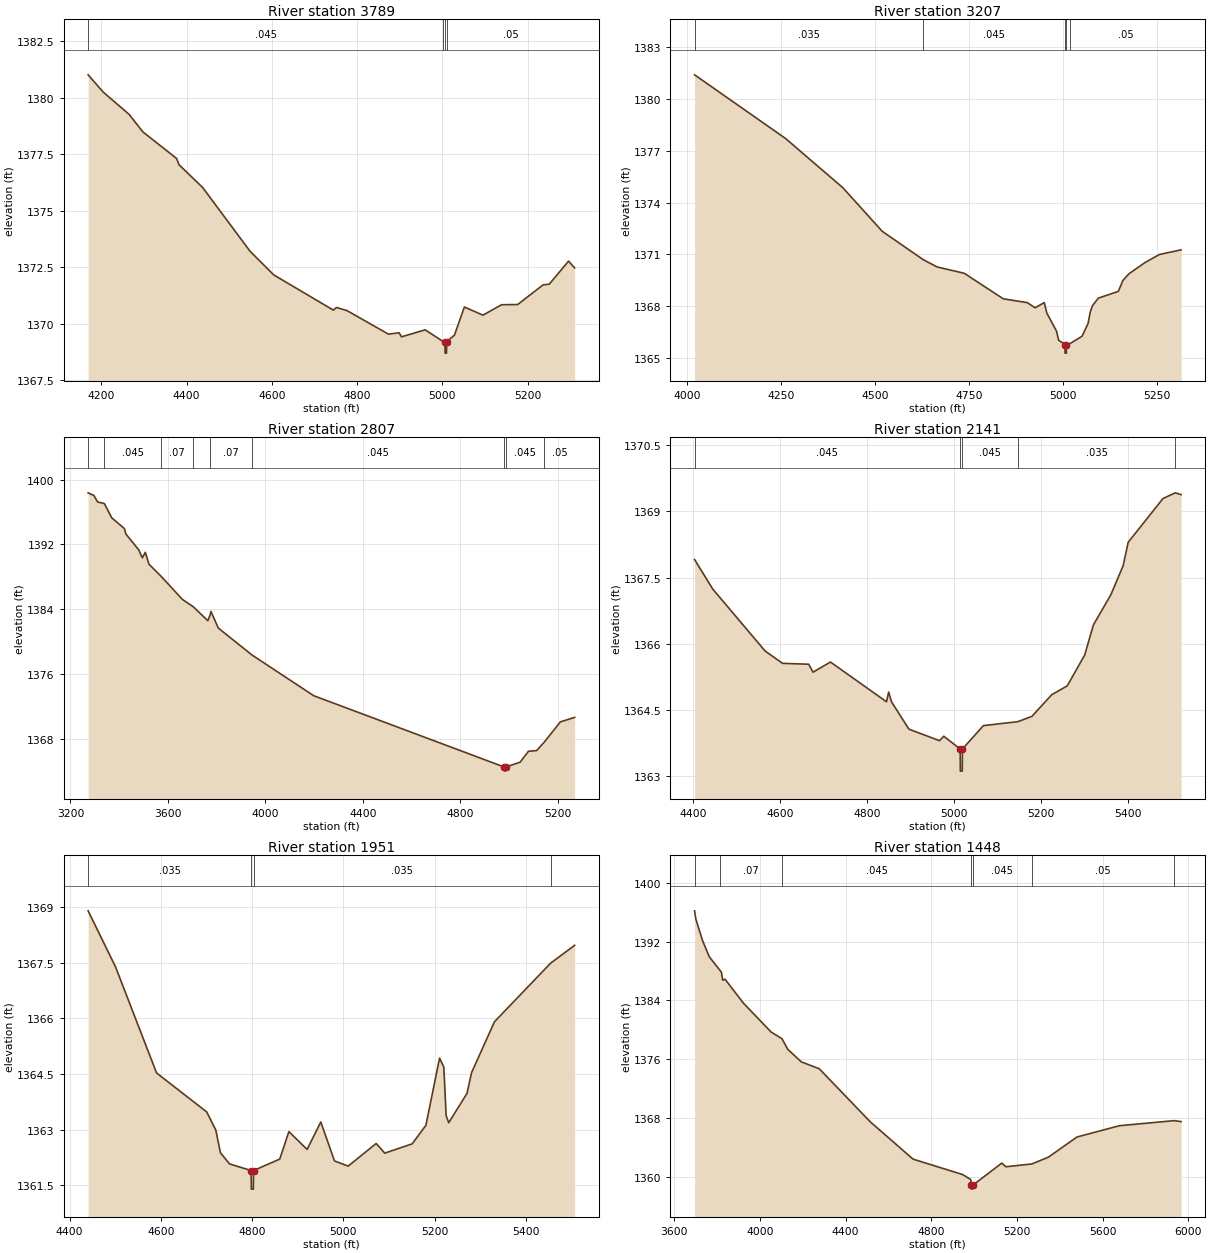
Type RM Length L Ch R = 1,3789,582,582,582
BEGIN DESCRIPTION:
Stream0113_DS 7.0
END DESCRIPTION:
XS GIS Cut Line= 3
      2015194.55     13903011.27      2015975.00     13902725.00
      2016247.17     13902575.77
#Sta/Elev= 30
  4168.7 1381.02  4203.9 1380.26  4265.0 1379.27  4297.0 1378.50  4376.3 1377.32
  4382.2 1377.04  4437.3 1376.04  4548.6 1373.22  4604.3 1372.17  4744.4 1370.61
  4751.4 1370.73  4776.3 1370.59  4873.4 1369.55  4898.6 1369.61  4904.1 1369.43
  4959.6 1369.74  5002.2 1369.22  5006.1 1369.21  5006.3 1368.71  5009.8 1368.71
  5010.1 1369.21  5028.5 1369.51  5051.7 1370.75  5095.3 1370.39  5138.9 1370.85
  5176.8 1370.86  5236.5 1371.73  5250.9 1371.76  5296.2 1372.78  5310.4 1372.48
#Mann=4,-1,0
  4168.7   0.045       0  5002.2    0.05       0  5006.1   0.045       0
  5010.1    0.05       0
Bank Sta=5006.1,5010.1
Exp/Cntr=0.3,0.1

Type RM Length L Ch R = 1,3207,400,400,400
BEGIN DESCRIPTION:
Stream0113_DS 6.0
END DESCRIPTION:
XS GIS Cut Line= 3
      2015306.80     13903479.91      2016245.28     13903195.28
      2016521.24     13903042.35
#Sta/Elev= 30
  4019.3 1381.41  4261.6 1377.72  4414.5 1374.86  4519.0 1372.34  4627.8 1370.70
  4665.3 1370.27  4737.9 1369.90  4841.8 1368.42  4905.7 1368.20  4926.6 1367.90
  4951.0 1368.20  4957.9 1367.59  4983.7 1366.54  4989.3 1366.02  5006.1 1365.77
  5006.4 1365.27  5009.9 1365.27  5010.1 1365.77  5019.9 1365.83  5051.6 1366.25
  5067.7 1366.99  5073.4 1367.65  5079.7 1368.03  5095.1 1368.46  5148.3 1368.85
  5160.4 1369.48  5176.4 1369.87  5219.9 1370.53  5257.7 1370.99  5315.5 1371.26
#Mann=5,-1,0
  4019.3   0.035       0  4627.8   0.045       0  5006.1   0.045       0
  5010.1   0.045       0  5019.9    0.05       0
Bank Sta=5006.1,5010.1
Exp/Cntr=0.3,0.1

Type RM Length L Ch R = 1,2807,666,666,666
BEGIN DESCRIPTION:
Stream0113_DS 5.0
END DESCRIPTION:
XS GIS Cut Line= 3
      2015034.55     13904358.95      2016508.61     13903457.98
      2016623.38     13903213.59
#Sta/Elev= 30
  3272.4 1398.36  3296.4 1398.03  3311.3 1397.23  3339.1 1397.04  3369.4 1395.28
  3421.6 1393.95  3427.5 1393.28  3479.7 1391.35  3495.1 1390.35  3507.3 1391.02
  3522.3 1389.56  3572.6 1388.05  3659.7 1385.21  3704.5 1384.30  3764.1 1382.59
  3773.3 1383.29  3776.9 1383.73  3806.7 1381.69  3945.8 1378.35  4198.8 1373.34
  4981.5 1364.54  4981.9 1364.04  4986.1 1364.04  4986.5 1364.54  5046.1 1365.14
  5080.6 1366.49  5113.8 1366.57  5145.3 1367.61  5211.3 1370.11  5270.0 1370.67
#Mann=9,-1,0
  3272.4   0.035       0  3339.1   0.045       0  3572.6    0.07       0
  3704.5   0.045       0  3773.3    0.07       0  3945.8   0.045       0
  4981.5   0.045       0  4986.5   0.045       0  5145.3    0.05       0
Bank Sta=4981.5,4986.5
Exp/Cntr=0.3,0.1

Type RM Length L Ch R = 1,2141,190,190,190
BEGIN DESCRIPTION:
Stream0113_DS 4.0
END DESCRIPTION:
XS GIS Cut Line= 4
      2016777.74     13904516.79      2016821.01     13903921.46
      2016868.41     13903652.50      2016871.73     13903403.33
#Sta/Elev= 30
  4403.1 1367.91  4445.0 1367.24  4565.3 1365.84  4605.4 1365.56  4665.6 1365.54
  4675.6 1365.36  4715.7 1365.59  4844.6 1364.69  4849.6 1364.91  4856.1 1364.69
  4896.2 1364.07  4966.4 1363.81  4976.4 1363.91  5014.1 1363.62  5014.5 1363.12
  5018.9 1363.12  5019.3 1363.62  5067.5 1364.15  5146.9 1364.24  5179.2 1364.36
  5224.8 1364.85  5260.4 1365.05  5300.6 1365.75  5320.6 1366.43  5360.6 1367.11
  5389.0 1367.77  5400.6 1368.30  5480.6 1369.29  5508.8 1369.42  5522.3 1369.38
#Mann=5,-1,0
  4403.1   0.045       0  5014.1   0.045       0  5019.3   0.045       0
  5146.9   0.035       0  5508.8    0.05       0
Bank Sta=5014.1,5019.3
Exp/Cntr=0.3,0.1

Type RM Length L Ch R = 1,1951,503,503,503
BEGIN DESCRIPTION:
Stream0113_DS 3.0
END DESCRIPTION:
XS GIS Cut Line= 3
      2016944.16     13904615.07      2016955.63     13904055.68
      2016988.05     13903549.52
#Sta/Elev= 30
  4440.5 1368.90  4500.6 1367.39  4590.6 1364.53  4700.6 1363.48  4720.5 1362.99
  4730.6 1362.38  4750.6 1362.08  4798.0 1361.90  4798.4 1361.40  4802.8 1361.40
  4803.2 1361.90  4860.7 1362.21  4880.7 1362.95  4920.7 1362.47  4950.7 1363.21
  4980.7 1362.16  5010.7 1362.02  5072.1 1362.63  5090.9 1362.37  5151.0 1362.62
  5181.1 1363.12  5211.1 1364.93  5220.4 1364.69  5225.5 1363.38  5231.2 1363.19
  5271.2 1363.98  5281.3 1364.54  5331.4 1365.91  5454.6 1367.49  5507.2 1367.97
#Mann=4,-1,0
  4440.5   0.035       0  4798.0   0.035       0  4803.2   0.035       0
  5454.6    0.05       0
Bank Sta=4798,4803.2
Exp/Cntr=0.3,0.1

Type RM Length L Ch R = 1,1448,244,244,244
BEGIN DESCRIPTION:
Stream0113_DS 2.0
END DESCRIPTION:
XS GIS Cut Line= 3
      2016982.46     13905520.42      2017375.00     13904275.00
      2017024.13     13903374.57
#Sta/Elev= 30
  3694.7 1396.17  3700.4 1395.07  3731.8 1392.13  3763.3 1389.93  3811.1 1388.16
  3820.3 1387.80  3826.2 1386.73  3836.7 1386.88  3922.6 1383.63  4052.0 1379.70
  4103.1 1378.78  4130.3 1377.33  4193.2 1375.64  4277.1 1374.70  4515.6 1367.48
  4715.0 1362.42  4946.7 1360.32  4984.3 1359.65  4987.4 1358.84  4987.8 1358.34
  4992.3 1358.34  4992.7 1358.84  5129.6 1361.88  5148.7 1361.38  5269.8 1361.76
  5347.1 1362.68  5480.3 1365.42  5678.7 1366.96  5935.2 1367.65  5966.9 1367.52
#Mann=7,-1,0
  3694.7   0.035       0  3811.1    0.07       0  4103.1   0.045       0
  4987.4   0.035       0  4992.7   0.045       0  5269.8    0.05       0
  5935.2   0.035       0
Bank Sta=4987.4,4992.7
Exp/Cntr=0.3,0.1

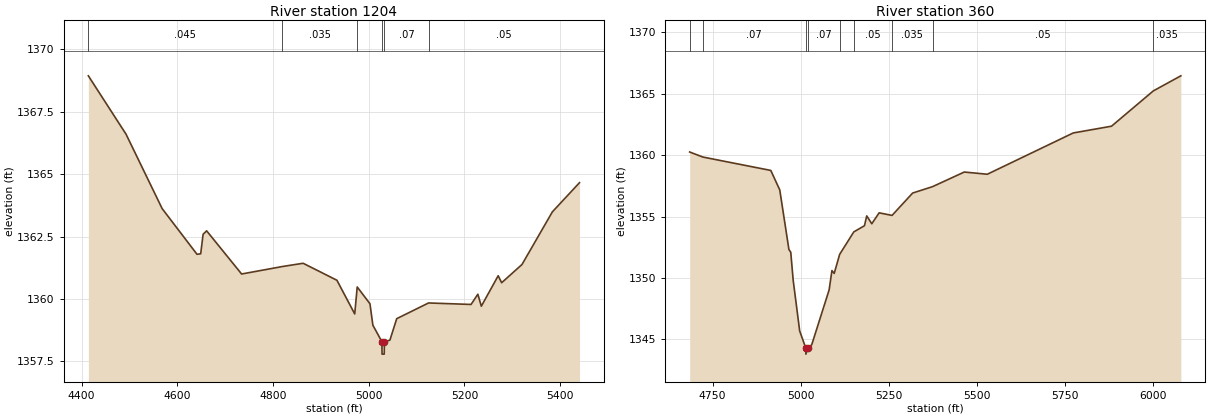
Type RM Length L Ch R = 1,1204,844,844,844
BEGIN DESCRIPTION:
Stream0113_DS 1.0
END DESCRIPTION:
XS GIS Cut Line= 3
      2017500.45     13904750.22      2017573.39     13904168.97
      2017270.51     13903849.40
#Sta/Elev= 30
  4414.2 1368.94  4493.0 1366.60  4568.4 1363.62  4641.2 1361.79  4648.9 1361.81
  4653.9 1362.59  4661.3 1362.73  4734.4 1361.00  4819.6 1361.30  4862.9 1361.43
  4933.5 1360.75  4970.7 1359.40  4975.9 1360.48  5002.5 1359.81  5008.6 1358.95
  5027.4 1358.29  5027.8 1357.79  5032.3 1357.79  5032.7 1358.29  5044.2 1358.35
  5058.4 1359.21  5124.9 1359.84  5213.7 1359.78  5227.9 1360.19  5235.2 1359.71
  5270.4 1360.93  5277.6 1360.65  5320.1 1361.38  5383.6 1363.49  5440.3 1364.66
#Mann=6,-1,0
  4414.2   0.045       0  4819.6   0.035       0  4975.9    0.07       0
  5027.4    0.05       0  5032.7    0.07       0  5124.9    0.05       0
Bank Sta=5027.4,5032.7
Exp/Cntr=0.3,0.1

Type RM Length L Ch R = 1,360,0,0,0
BEGIN DESCRIPTION:
Stream0113_DS 0.0
END DESCRIPTION:
XS GIS Cut Line= 4
      2017806.81     13904122.78      2017909.61     13903824.92
      2017732.95     13903611.98      2017029.69     13903223.73
#Sta/Elev= 30
  4684.9 1360.25  4722.3 1359.84  4915.3 1358.75  4940.8 1357.16  4966.7 1352.32
  4972.0 1352.09  4978.8 1349.83  4997.3 1345.69  5014.5 1344.30  5015.0 1343.80
  5019.9 1344.30  5031.5 1344.56  5081.0 1349.03  5088.9 1350.60  5095.4 1350.37
  5110.9 1351.92  5151.1 1353.75  5181.3 1354.25  5187.8 1355.05  5202.1 1354.41
  5223.0 1355.30  5259.7 1355.09  5318.2 1356.91  5374.7 1357.43  5464.9 1358.62
  5530.2 1358.44  5774.3 1361.80  5883.1 1362.35  6001.6 1365.22  6080.0 1366.45
#Mann=9,-1,0
  4684.9   0.045       0  4722.3    0.07       0  5014.5    0.05       0
  5019.9    0.07       0  5110.9   0.035       0  5151.1    0.05       0
  5259.7   0.035       0  5374.7    0.05       0  6001.6   0.035       0
Bank Sta=5014.5,5019.9
Exp/Cntr=0.3,0.1

Chan Stop Cuts=-1