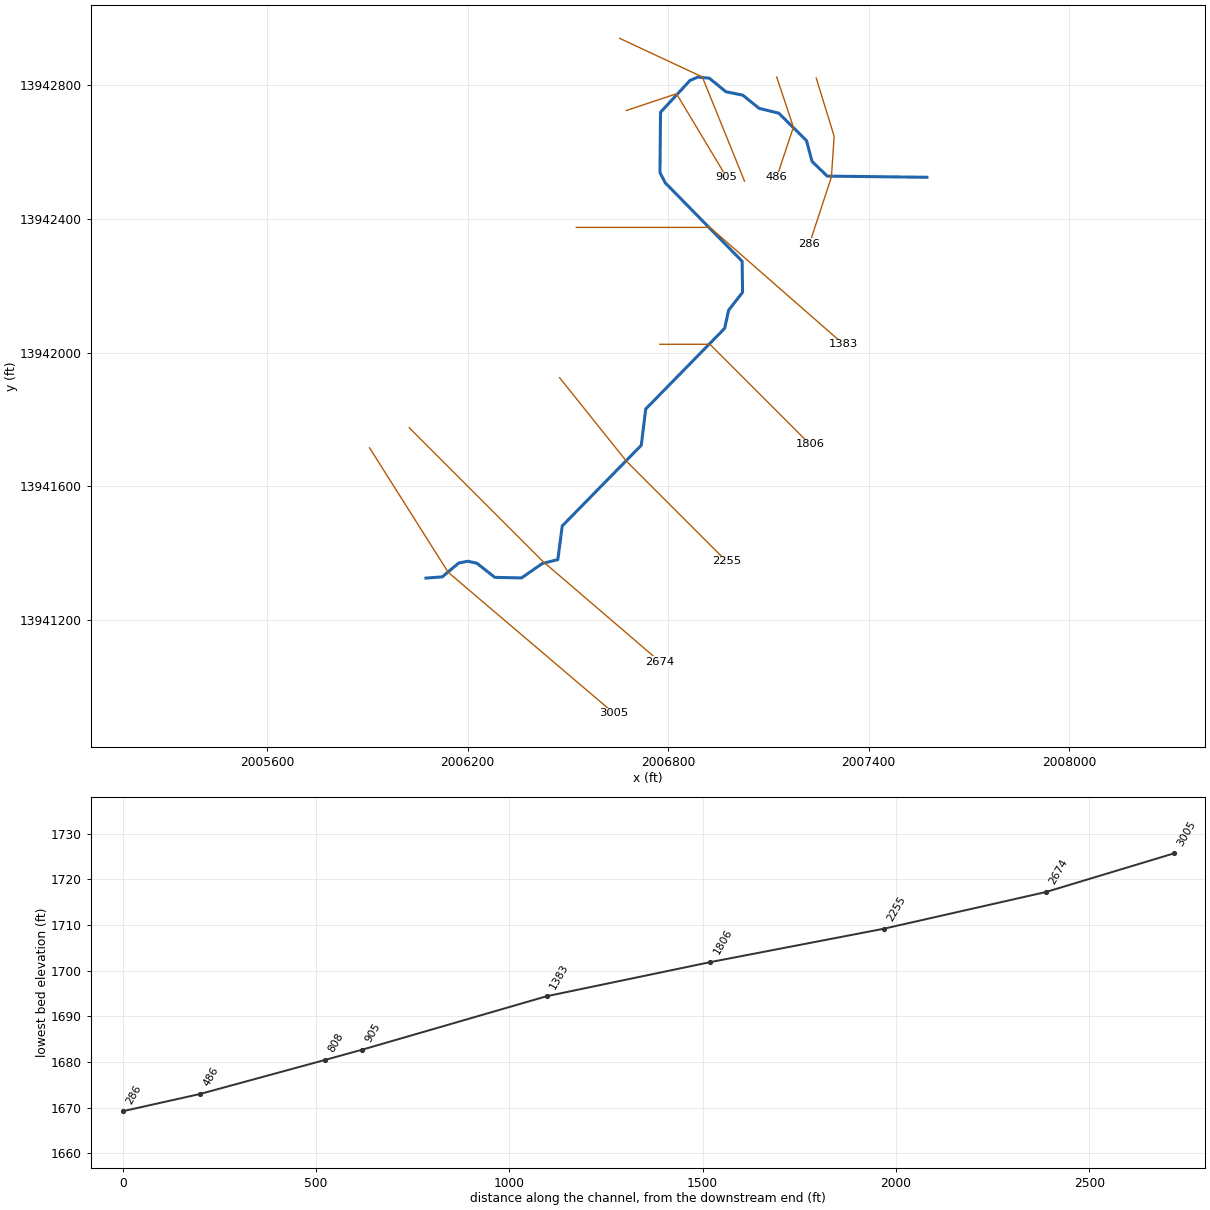
--- Stream0114_DS.prj (project) ---

Proj Title=Stream0114_DS Base Level Engineering
Current Plan=p01
Default Exp/Contr=0.3,0.1
English Units
Geom File=g01
Flow File=f01
Plan File=p01
BEGIN DESCRIPTION:
Stream0114_DS
END DESCRIPTION:

--- Stream0114_DS.p01 (plan) ---

Plan Title=Multiple Run
Short Identifier=Multiple
Geom File=g01
Flow File=f01
Subcritical Flow
K Sum by GR= 0
Std Step Tol= 0.01
Critical Tol= 0.01
Num of Std Step Trials= 20
Max Error Tol= 0.3
Flow Tol Ratio= 0.001
Split Flow NTrial= 30
Split Flow Tol= 0.02
Split Flow Ratio= 0.02
Log Output Level= 0
Friction Slope Method= 1
Unsteady Friction Slope Method= 2
Unsteady Bridges Friction Slope Method= 1
Parabolic Critical Depth
Global Vel Dist=  1 , 1 , 1
Global Log Level= 0
CheckData=True
Encroach Param= -1, 0, 0, 0
BEGIN DESCRIPTION:
Multiple Run
END DESCRIPTION:

--- Stream0114_DS.f01 (steady flow) ---

Flow Title=Multiple
Number of Profiles=7
Profile Names=10-year,25-year,50-year,1pct_min,100-year,1pct_plu,500-year
River Rch & RM= Stream0114_DS,Reach-1,3005
    1070    1847    2600    1776    3543    7069    6527
Boundary for River Rch & Prof#=Stream0114_DS,Reach-1,1
Up Type=0
Dn Type=3
Dn Slope=0.005
Boundary for River Rch & Prof#=Stream0114_DS,Reach-1,2
Up Type=0
Dn Type=3
Dn Slope=0.005
Boundary for River Rch & Prof#=Stream0114_DS,Reach-1,3
Up Type=0
Dn Type=3
Dn Slope=0.005
Boundary for River Rch & Prof#=Stream0114_DS,Reach-1,4
Up Type=0
Dn Type=3
Dn Slope=0.005
Boundary for River Rch & Prof#=Stream0114_DS,Reach-1,5
Up Type=0
Dn Type=3
Dn Slope=0.005
Boundary for River Rch & Prof#=Stream0114_DS,Reach-1,6
Up Type=0
Dn Type=3
Dn Slope=0.005
Boundary for River Rch & Prof#=Stream0114_DS,Reach-1,7
Up Type=0
Dn Type=3
Dn Slope=0.005

--- Stream0114_DS.g01 (geometry) ---

Geom Title=Existing Conditions

River Reach=Stream0114_DS,Reach-1
Reach XY= 30
      2006075.00     13941325.00      2006123.51     13941328.69
      2006172.75     13941369.88      2006200.00     13941375.47
      2006227.19     13941369.63      2006280.97     13941327.19
      2006361.05     13941325.53      2006423.22     13941368.69
      2006469.75     13941380.44      2006482.88     13941481.12
      2006719.48     13941722.57      2006732.86     13941831.17
      2006969.17     13942072.70      2006981.15     13942127.17
      2007022.74     13942180.56      2007021.54     13942273.50
      2006791.43     13942508.24      2006775.53     13942538.86
      2006777.16     13942719.57      2006865.29     13942814.82
      2006889.04     13942824.91      2006923.26     13942821.69
      2006972.80     13942781.16      2007023.28     13942770.85
      2007072.82     13942731.10      2007131.07     13942716.87
      2007214.22     13942634.68      2007230.74     13942572.43
      2007276.25     13942528.45      2007575.00     13942525.00

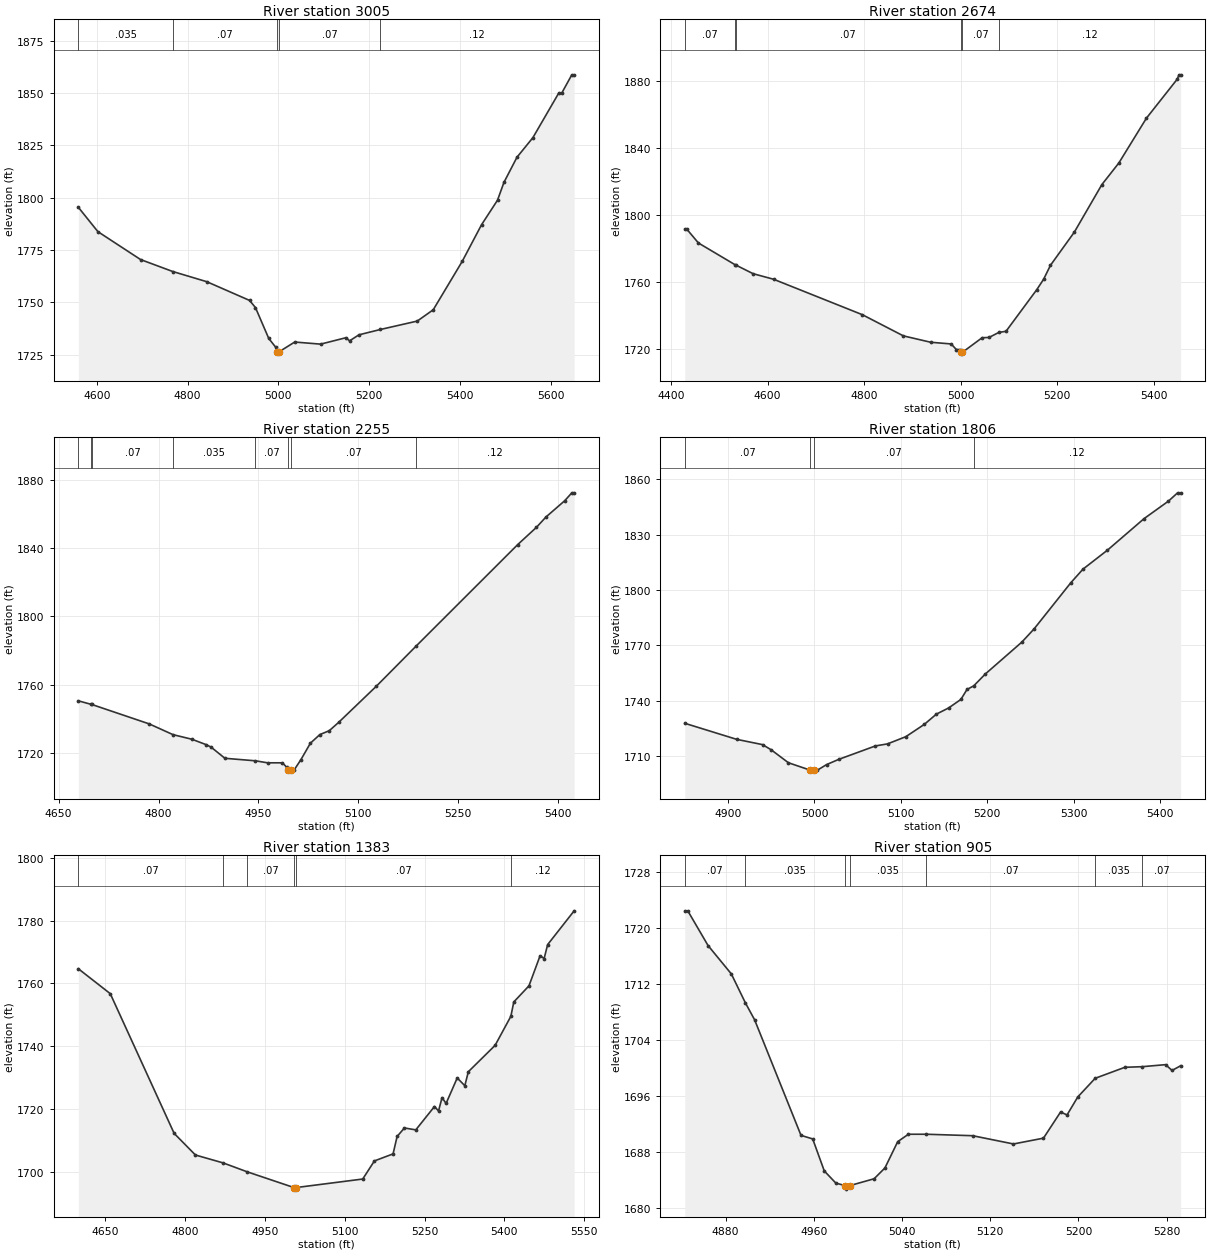
Type RM Length L Ch R = 1,3005,331,331,331
BEGIN DESCRIPTION:
Stream0114_DS 7.0
END DESCRIPTION:
XS GIS Cut Line= 3
      2005906.07     13941715.01      2006141.48     13941342.34
      2006637.95     13940920.01
#Sta/Elev= 30
  4559.2 1795.40  4602.3 1783.76  4696.4 1770.42  4767.3 1764.71  4842.3 1759.84
  4936.4 1750.91  4949.5 1747.49  4978.8 1732.73  4994.1 1728.53  4996.6 1726.21
  4996.9 1725.71  5000.6 1726.21  5036.0 1731.01  5093.1 1730.01  5149.1 1733.09
  5156.8 1731.56  5177.6 1734.46  5224.9 1737.01  5306.1 1741.03  5341.3 1746.44
  5405.0 1769.51  5447.8 1787.10  5482.9 1798.79  5497.2 1807.36  5525.8 1819.32
  5560.9 1828.69  5618.0 1850.04  5624.6 1850.03  5646.6 1858.70  5651.8 1858.40
#Mann=5,-1,0
  4559.2   0.035       0  4767.3    0.07       0  4996.6    0.05       0
  5000.6    0.07       0  5224.9    0.12       0
Bank Sta=4996.6,5000.6
Exp/Cntr=0.3,0.1

Type RM Length L Ch R = 1,2674,419,419,419
BEGIN DESCRIPTION:
Stream0114_DS 6.0
END DESCRIPTION:
XS GIS Cut Line= 3
      2006024.97     13941775.03      2006425.00     13941375.00
      2006775.00     13941075.00
#Sta/Elev= 30
  4428.6 1791.65  4432.2 1791.65  4456.9 1783.18  4533.2 1770.09  4533.9 1770.04
  4570.1 1764.81  4612.5 1761.48  4796.3 1740.26  4881.2 1727.58  4937.8 1723.76
  4980.2 1722.75  4990.8 1719.42  4997.6 1719.42  4999.5 1717.75  4999.7 1717.25
  5003.5 1717.75  5044.3 1726.48  5058.5 1726.62  5079.0 1729.67  5093.7 1730.31
  5157.3 1755.20  5171.6 1761.48  5185.8 1769.85  5235.2 1789.70  5292.3 1818.20
  5327.4 1831.11  5384.5 1857.94  5448.2 1881.26  5452.0 1883.89  5455.3 1883.89
#Mann=6,-1,0
  4428.6    0.07       0  4533.2   0.035       0  4533.9    0.07       0
  4999.5    0.05       0  5003.5    0.07       0  5079.0    0.12       0
Bank Sta=4999.5,5003.5
Exp/Cntr=0.3,0.1

Type RM Length L Ch R = 1,2255,449,449,449
BEGIN DESCRIPTION:
Stream0114_DS 5.0
END DESCRIPTION:
XS GIS Cut Line= 3
      2006475.00     13941925.00      2006675.00     13941675.00
      2006974.99     13941375.01
#Sta/Elev= 30
  4679.6 1750.46  4698.7 1748.42  4699.7 1748.34  4786.0 1736.93  4821.8 1730.61
  4850.1 1727.92  4871.7 1724.72  4878.9 1723.30  4899.7 1716.74  4945.5 1715.27
  4963.7 1714.09  4986.1 1714.09  4992.5 1711.43  4994.5 1709.71  4994.8 1709.21
  4998.6 1709.71  5003.3 1709.71  5013.9 1716.03  5028.0 1725.60  5042.2 1730.66
  5056.3 1732.93  5070.5 1737.85  5127.0 1759.03  5186.6 1782.55  5339.2 1842.13
  5367.4 1852.29  5381.6 1858.32  5409.9 1867.92  5420.5 1872.53  5424.0 1872.53
#Mann=8,-1,0
  4679.6    0.07       0  4698.7   0.035       0  4699.7    0.07       0
  4821.8   0.035       0  4945.5    0.07       0  4994.5    0.05       0
  4998.6    0.07       0  5186.6    0.12       0
Bank Sta=4994.5,4998.6
Exp/Cntr=0.3,0.1

Type RM Length L Ch R = 1,1806,423,423,423
BEGIN DESCRIPTION:
Stream0114_DS 4.0
END DESCRIPTION:
XS GIS Cut Line= 3
      2006775.02     13942025.00      2006925.00     13942025.00
      2007224.97     13941725.03
#Sta/Elev= 30
  4849.8 1727.82  4909.8 1719.13  4939.8 1716.26  4949.8 1713.47  4969.8 1706.43
  4995.2 1702.39  4995.5 1701.89  4999.3 1702.39  5003.3 1702.39  5013.9 1705.41
  5028.1 1708.27  5070.5 1715.54  5084.6 1716.66  5105.8 1720.57  5127.1 1727.21
  5141.2 1732.80  5155.3 1736.13  5169.5 1740.74  5176.6 1746.15  5184.4 1748.11
  5197.8 1754.53  5240.2 1771.86  5254.3 1778.99  5296.8 1803.99  5310.9 1811.37
  5339.2 1821.65  5381.6 1838.74  5409.9 1848.25  5420.5 1852.75  5424.0 1852.75
#Mann=4,-1,0
  4849.8    0.07       0  4995.2    0.05       0  4999.3    0.07       0
  5184.4    0.12       0
Bank Sta=4995.2,4999.3
Exp/Cntr=0.3,0.1

Type RM Length L Ch R = 1,1383,478,478,478
BEGIN DESCRIPTION:
Stream0114_DS 3.0
END DESCRIPTION:
XS GIS Cut Line= 3
      2006524.97     13942375.00      2006925.00     13942375.00
      2007324.97     13942025.03
#Sta/Elev= 30
  4599.6 1764.70  4659.6 1756.75  4779.6 1712.20  4819.6 1705.30  4871.7 1702.78
  4916.5 1699.96  5004.7 1694.92  5005.0 1694.42  5008.8 1694.92  5133.9 1697.64
  5155.8 1703.41  5190.9 1705.66  5198.5 1711.22  5212.2 1713.92  5233.6 1713.32
  5268.7 1720.77  5276.3 1719.34  5282.9 1723.60  5290.5 1721.75  5311.4 1729.87
  5325.7 1727.40  5332.3 1731.86  5382.6 1740.27  5412.2 1749.54  5417.7 1754.11
  5446.2 1759.25  5467.1 1768.85  5474.7 1767.96  5481.3 1772.40  5531.1 1783.17
#Mann=6,-1,0
  4599.6    0.07       0  4871.7   0.035       0  4916.5    0.07       0
  5004.7    0.05       0  5008.8    0.07       0  5412.2    0.12       0
Bank Sta=5004.7,5008.8
Exp/Cntr=0.3,0.1

Type RM Length L Ch R = 1,905,97,97,97
BEGIN DESCRIPTION:
Stream0114_DS 2.0
END DESCRIPTION:
XS GIS Cut Line= 3
      2006674.98     13942724.99      2006825.00     13942775.00
      2006975.01     13942524.98
#Sta/Elev= 30
  4843.0 1722.44  4845.7 1722.44  4864.1 1717.48  4885.2 1713.43  4898.0 1709.28
  4906.3 1706.88  4948.4 1690.37  4959.0 1689.86  4969.5 1685.29  4980.0 1683.55
  4988.5 1683.19  4988.8 1682.69  4992.6 1683.19  5014.7 1684.17  5024.5 1685.71
  5036.1 1689.47  5045.8 1690.53  5062.1 1690.53  5104.1 1690.32  5141.1 1689.14
  5168.3 1689.97  5183.8 1693.70  5189.7 1693.29  5199.4 1695.85  5215.2 1698.52
  5242.1 1700.09  5258.0 1700.18  5279.1 1700.47  5284.9 1699.64  5292.7 1700.31
#Mann=7,-1,0
  4843.0    0.07       0  4898.0   0.035       0  4988.5   0.035       0
  4992.6   0.035       0  5062.1    0.07       0  5215.2   0.035       0
  5258.0    0.07       0
Bank Sta=4988.5,4992.6
Exp/Cntr=0.3,0.1

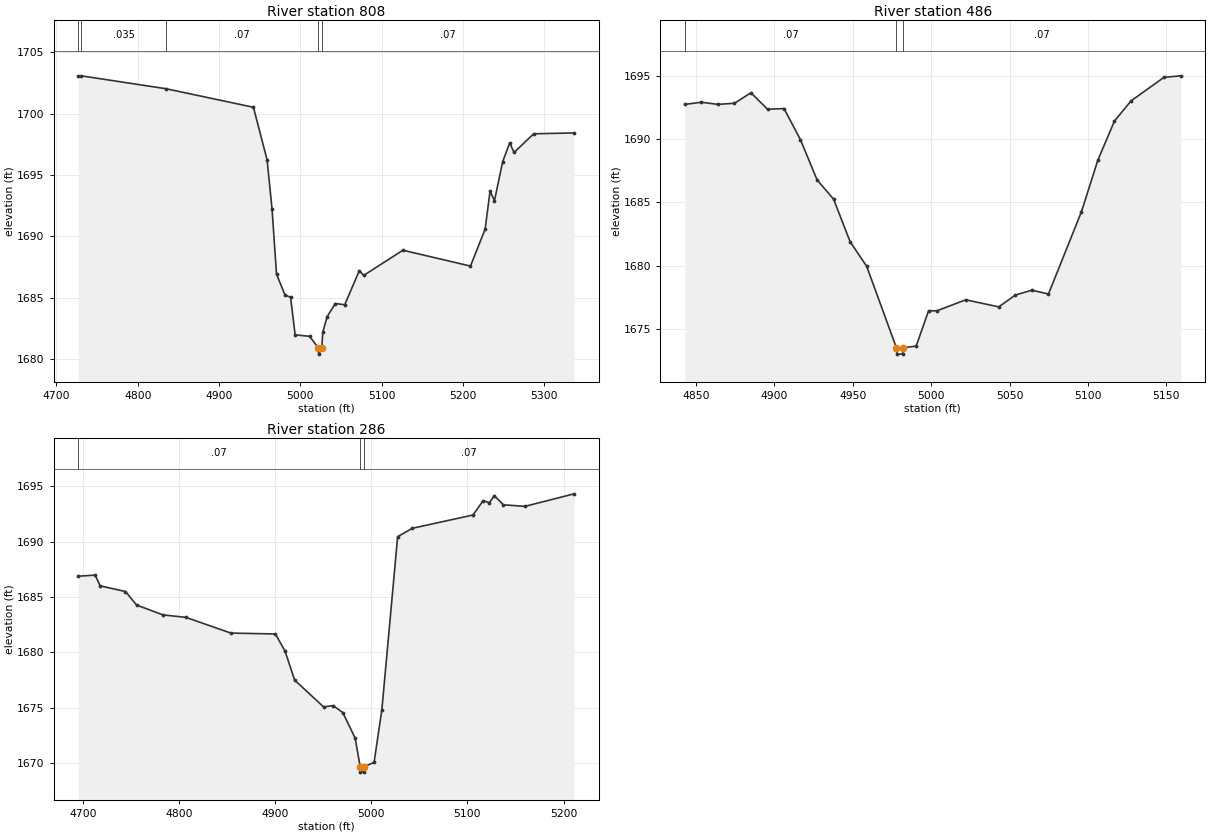
Type RM Length L Ch R = 1,808,322,322,322
BEGIN DESCRIPTION:
Stream0114_DS 1.5
END DESCRIPTION:
XS GIS Cut Line= 3
      2006654.68     13942940.96      2006902.16     13942825.48
      2007028.57     13942513.51
#Sta/Elev= 30
  4726.9 1703.06  4730.4 1703.08  4834.7 1702.03  4942.2 1700.52  4959.0 1696.24
  4965.1 1692.23  4970.6 1686.93  4981.1 1685.23  4987.9 1685.05  4993.5 1681.99
  5011.3 1681.87  5022.1 1680.92  5022.4 1680.42  5026.2 1680.92  5027.5 1682.20
  5032.9 1683.48  5042.9 1684.54  5054.5 1684.44  5072.4 1687.22  5077.8 1686.83
  5126.0 1688.88  5209.1 1687.59  5227.1 1690.59  5233.2 1693.69  5238.6 1692.91
  5248.7 1696.09  5257.3 1697.62  5262.7 1696.84  5286.8 1698.36  5336.6 1698.43
#Mann=5,-1,0
  4726.9    0.07       0  4730.4   0.035       0  4834.7    0.07       0
  5022.1    0.05       0  5026.2    0.07       0
Bank Sta=5022.1,5026.2
Exp/Cntr=0.3,0.1

Type RM Length L Ch R = 1,486,200,200,200
BEGIN DESCRIPTION:
Stream0114_DS 1.0
END DESCRIPTION:
XS GIS Cut Line= 3
      2007124.98     13942825.05      2007175.00     13942675.00
      2007124.99     13942524.98
#Sta/Elev= 30
  4842.8 1692.76  4853.4 1692.93  4863.9 1692.76  4874.5 1692.85  4885.0 1693.68
  4895.6 1692.37  4906.1 1692.43  4916.6 1689.96  4927.2 1686.78  4937.7 1685.26
  4948.3 1681.88  4958.8 1679.95  4977.8 1673.49  4978.1 1672.99  4981.7 1672.99
  4982.0 1673.49  4990.4 1673.63  4998.3 1676.42  5003.6 1676.42  5022.0 1677.29
  5043.1 1676.73  5053.7 1677.67  5064.2 1678.05  5074.8 1677.75  5095.8 1684.25
  5106.4 1688.38  5116.9 1691.44  5127.5 1693.04  5148.5 1694.90  5159.1 1695.02
#Mann=3,-1,0
  4842.8    0.07       0  4977.8    0.05       0  4982.0    0.07       0
Bank Sta=4977.8,4982
Exp/Cntr=0.3,0.1

Type RM Length L Ch R = 1,286,0,0,0
BEGIN DESCRIPTION:
Stream0114_DS 0.0
END DESCRIPTION:
XS GIS Cut Line= 4
      2007243.34     13942821.82      2007297.00     13942647.68
      2007288.73     13942525.48      2007222.77     13942325.05
#Sta/Elev= 30
  4695.3 1686.88  4712.8 1686.98  4718.0 1686.01  4744.3 1685.50  4755.9 1684.28
  4783.4 1683.39  4807.1 1683.17  4854.0 1681.75  4900.3 1681.67  4910.3 1680.12
  4920.3 1677.51  4950.4 1675.09  4960.4 1675.21  4970.4 1674.58  4983.3 1672.26
  4988.4 1669.71  4988.7 1669.21  4992.3 1669.21  4992.6 1669.71  5002.9 1670.08
  5011.0 1674.84  5027.4 1690.44  5042.6 1691.20  5105.8 1692.40  5116.3 1693.69
  5122.7 1693.51  5128.0 1694.14  5137.4 1693.32  5159.8 1693.18  5211.0 1694.31
#Mann=3,-1,0
  4695.3    0.07       0  4988.4    0.05       0  4992.6    0.07       0
Bank Sta=4988.4,4992.6
Exp/Cntr=0.3,0.1

Chan Stop Cuts=-1