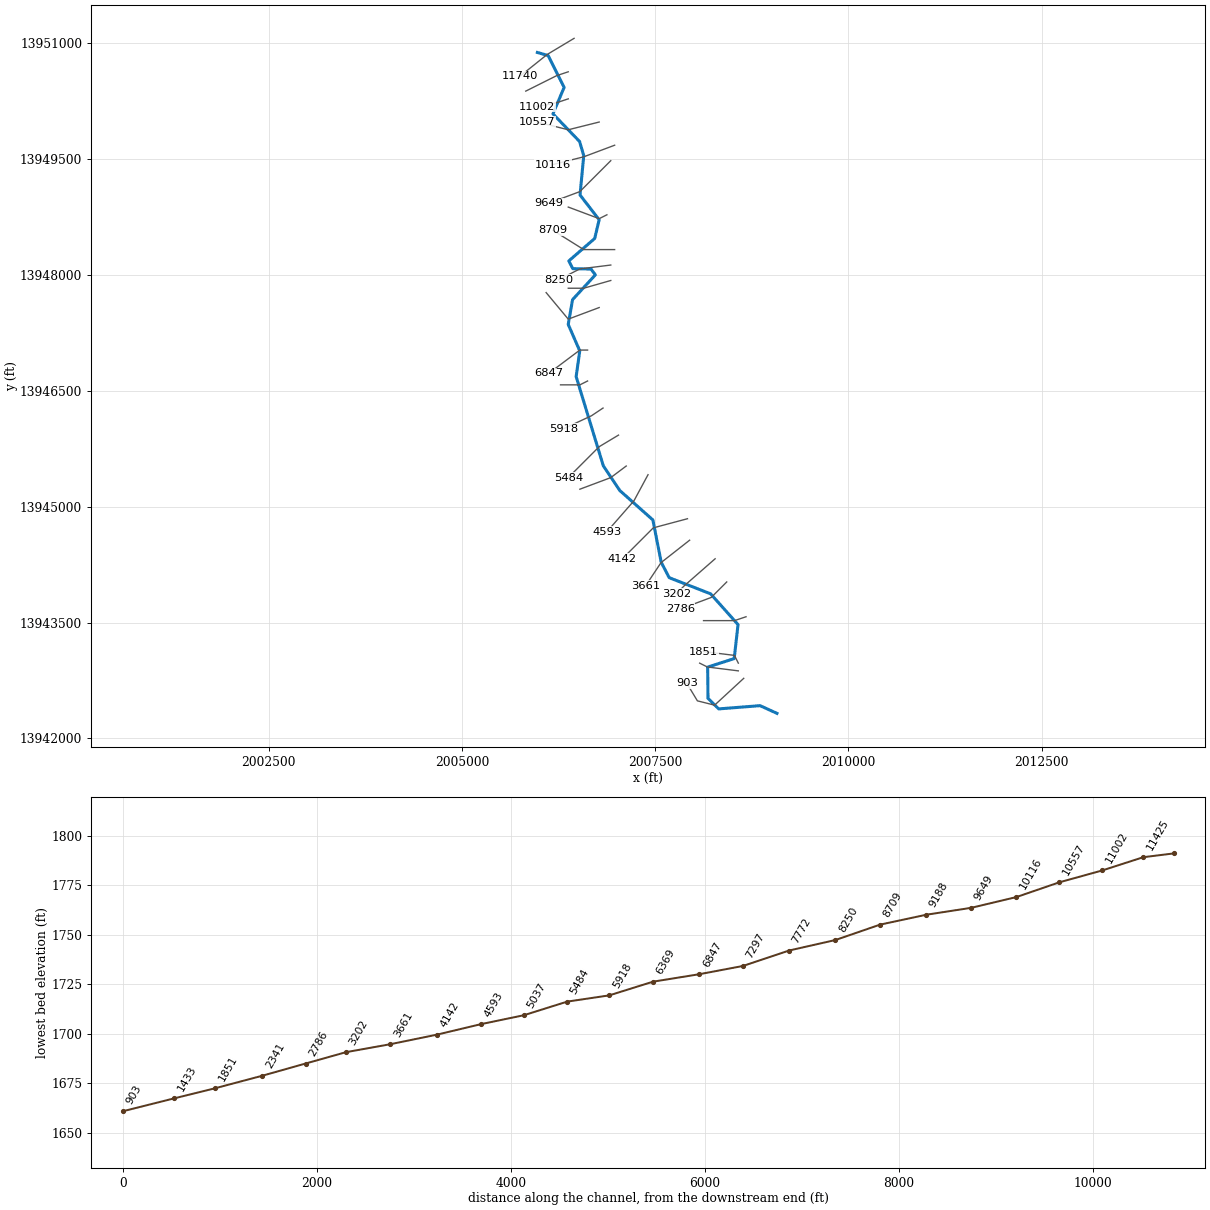
--- Stream0115_DS.prj (project) ---

Proj Title=Stream0115_DS Base Level Engineering
Current Plan=p01
Default Exp/Contr=0.3,0.1
English Units
Geom File=g01
Flow File=f01
Plan File=p01
Y Axis Title=Elevation
X Axis Title(PF)=Main Channel Distance
X Axis Title(XS)=Station
BEGIN DESCRIPTION:
Stream0115_DS
END DESCRIPTION:
DSS Export Rating Curves= 0
DSS Export Rating Curve Sorted= 0
DSS Export Volume Flow Curves= 0
DXF OffsetX= 0
DXF OffsetY= 0
DXF ScaleX= 1
DXF ScaleY= 10

--- Stream0115_DS.p01 (plan) ---

Plan Title=Multiple Run
Short Identifier=Multiple
Geom File=g01
Flow File=f01
Subcritical Flow
K Sum by GR= 0
Std Step Tol= 0.01
Critical Tol= 0.01
Num of Std Step Trials= 20
Max Error Tol= 0.3
Flow Tol Ratio= 0.001
Split Flow NTrial= 30
Split Flow Tol= 0.02
Split Flow Ratio= 0.02
Log Output Level= 0
Friction Slope Method= 1
Unsteady Friction Slope Method= 2
Unsteady Bridges Friction Slope Method= 1
Parabolic Critical Depth
Global Vel Dist=  1 , 1 , 1
Global Log Level= 0
CheckData=True
Encroach Param= -1, 0, 0, 0
BEGIN DESCRIPTION:
Multiple Run
END DESCRIPTION:

--- Stream0115_DS.f01 (steady flow) ---

Flow Title=Multiple
Number of Profiles=7
Profile Names=10-year,25-year,50-year,1pct_min,100-year,1pct_plu,500-year
River Rch & RM= Stream0115_DS,Reach-1,11740
    1310    2282    3231    2218    4426    8830    8239
River Rch & RM= Stream0115_DS,Reach-1,7297
    1789    3154    4501    3109    6204   12378   11703
Boundary for River Rch & Prof#=Stream0115_DS,Reach-1,1
Up Type=0
Dn Type=3
Dn Slope=0.005
Boundary for River Rch & Prof#=Stream0115_DS,Reach-1,2
Up Type=0
Dn Type=3
Dn Slope=0.005
Boundary for River Rch & Prof#=Stream0115_DS,Reach-1,3
Up Type=0
Dn Type=3
Dn Slope=0.005
Boundary for River Rch & Prof#=Stream0115_DS,Reach-1,4
Up Type=0
Dn Type=3
Dn Slope=0.005
Boundary for River Rch & Prof#=Stream0115_DS,Reach-1,5
Up Type=0
Dn Type=3
Dn Slope=0.005
Boundary for River Rch & Prof#=Stream0115_DS,Reach-1,6
Up Type=0
Dn Type=3
Dn Slope=0.005
Boundary for River Rch & Prof#=Stream0115_DS,Reach-1,7
Up Type=0
Dn Type=3
Dn Slope=0.005

--- Stream0115_DS.g01 (geometry) ---

Geom Title=Existing Conditions
Program Version=4.10

River Reach=Stream0115_DS   ,Reach-1
Reach XY= 30
        2005975.       13950875.      2006114.66     13950835.16
      2006321.69     13950423.27      2006176.96     13950080.89
      2006521.19     13949723.44      2006575.43     13949540.18
      2006527.24     13949030.93      2006774.77     13948710.91
      2006717.18     13948468.81      2006382.66     13948178.63
      2006433.25     13948078.07      2006669.38     13948073.02
       2006725.6     13947997.88      2006430.83      13947677.3
       2006374.6     13947356.65      2006523.78      13947014.5
      2006477.14     13946680.97      2006828.82     13945526.58
      2007041.64     13945208.29      2007469.48     13944827.43
      2007577.35     13944280.52      2007680.58     13944080.58
       2008216.8     13943871.31      2008571.45     13943473.53
       2008521.5     13943033.46      2008178.43     13942923.78
      2008182.81     13942518.81      2008321.58     13942382.79
      2008856.66     13942424.94        2009075.       13942325.

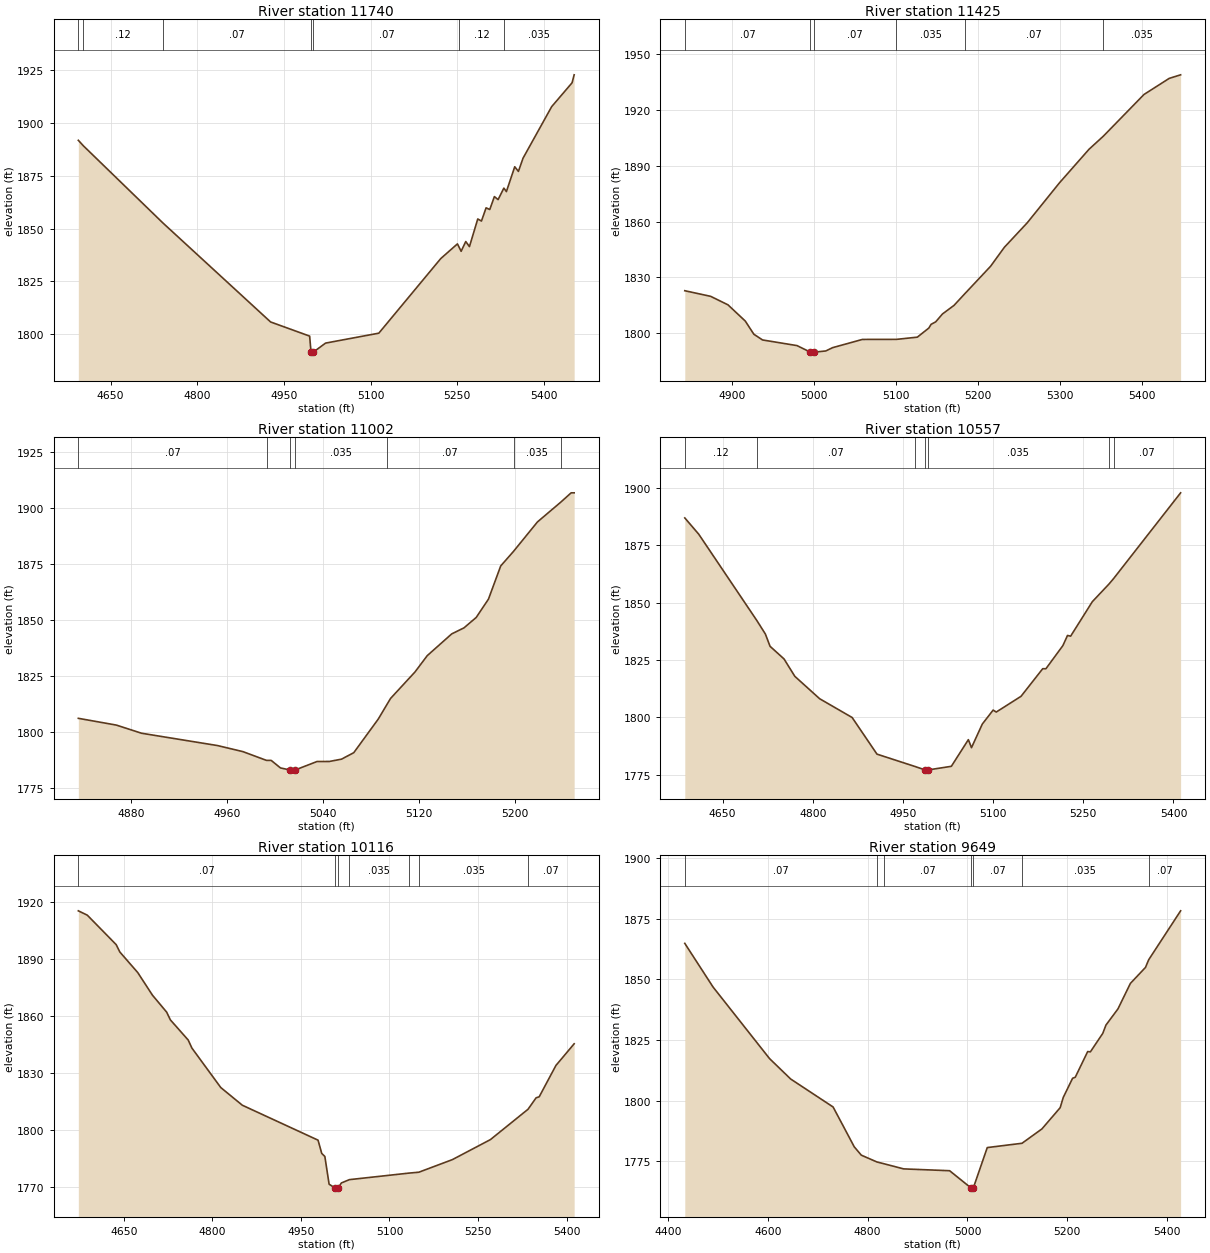
Type RM Length L Ch R = 1 ,11740   ,315,315,315
BEGIN DESCRIPTION:
Stream0115_DS 24.0
END DESCRIPTION:
XS GIS Cut Line= 3
      2006450.49     13951057.74      2006102.37     13950849.02
      2005748.92     13950566.31
#Sta/Elev= 30
  4594.1  1891.7    4603 1889.06  4740.7  1852.6    4927 1805.85  4994.6 1799.16
    4997 1791.62  4997.2 1791.12  5001.1 1791.62  5022.2 1795.86  5114.4 1800.55
  5221.6  1835.8  5250.5 1842.75  5253.7    1841  5256.9 1839.25  5264.9 1843.85
  5271.3 1841.47  5285.7 1854.52  5292.1 1853.55  5300.1 1859.78  5306.5 1858.99
  5314.5  1865.1  5320.9 1863.67  5330.9 1869.11  5335.3 1867.46  5349.7  1879.2
  5356.1 1877.01  5364.1 1883.26  5413.7 1907.62    5449 1918.89  5452.6 1922.65
#Mann= 7 ,-1 , 0
  4594.1     .07       0    4603     .12       0  4740.7     .07       0
    4997     .05       0  5001.1     .07       0  5253.7     .12       0
  5330.9    .035       0
Bank Sta=4997,5001.1
XS Rating Curve= 0 ,0
Exp/Cntr=0.3,0.1

Type RM Length L Ch R = 1 ,11425   ,423,423,423
BEGIN DESCRIPTION:
Stream0115_DS 23.0
END DESCRIPTION:
XS GIS Cut Line= 3
        2006375.       13950625.        2006225.       13950575.
      2005825.03     13950375.01
#Sta/Elev= 30
  4841.9 1822.79  4873.5 1819.76  4894.6  1815.2  4915.7 1806.48  4926.2 1799.38
  4936.8  1796.3  4978.9 1793.26  4995.3 1789.71  4995.6 1789.21  4999.4 1789.71
    5014 1790.38  5022.4 1792.16  5058.7 1796.58  5100.3 1796.61  5125.8 1797.81
  5139.8 1802.69  5142.6 1804.71  5148.2 1806.04  5156.5 1810.29  5170.5 1814.88
  5183.6  1821.1  5215.2 1835.94    5232 1846.14    5260 1859.36  5299.1 1880.74
  5335.4 1898.91  5352.7 1905.87  5402.5 1928.38  5433.3 1937.04  5447.2 1938.95
#Mann= 6 ,-1 , 0
  4841.9     .07       0  4995.3     .05       0  4999.4     .07       0
  5100.3    .035       0  5183.6     .07       0  5352.7    .035       0
Bank Sta=4995.3,4999.4
XS Rating Curve= 0 ,0
Exp/Cntr=0.3,0.1

Type RM Length L Ch R = 1 ,11002   ,445,445,445
BEGIN DESCRIPTION:
Stream0115_DS 22.0
END DESCRIPTION:
XS GIS Cut Line= 3
      2006375.04     13950275.01        2006225.       13950225.
      2005975.01       13950175.
#Sta/Elev= 30
  4836.1 1806.12  4867.8 1803.09  4888.8 1799.45  4952.1 1793.94  4973.2 1791.24
  4992.9 1787.31  4996.8 1787.31  5004.5 1783.95  5012.6 1783.02  5012.9 1782.52
  5016.7 1783.02    5035 1786.82  5045.2 1786.83  5055.4 1787.87  5065.6 1790.77
    5086 1805.79  5092.9 1812.01  5096.2 1814.98  5116.6 1826.84  5126.8 1834.12
  5147.2 1843.85  5157.4 1846.54  5167.6  1851.2  5177.8 1859.38    5188  1874.2
  5198.7 1880.74  5218.6 1893.87    5238  1902.7  5246.7 1906.89  5249.2 1906.89
#Mann= 7 ,-1 , 0
  4836.1     .07       0  4992.9    .035       0  5012.6    .035       0
  5016.7    .035       0  5092.9     .07       0  5198.7    .035       0
    5238     .07       0
Bank Sta=5012.6,5016.7
XS Rating Curve= 0 ,0
Exp/Cntr=0.3,0.1

Type RM Length L Ch R = 1 ,10557   ,441,441,441
BEGIN DESCRIPTION:
Stream0115_DS 21.0
END DESCRIPTION:
XS GIS Cut Line= 3
      2006775.03     13949975.01        2006375.       13949875.
      2005975.05     13949974.99
#Sta/Elev= 30
  4587.3 1886.88  4610.5 1879.78  4707.4 1842.03  4721.3 1836.26  4729.1  1830.9
  4752.3  1825.4  4770.3 1817.81  4811.5 1808.06  4865.6 1799.86  4906.9 1783.89
  4969.7 1778.54  4987.3 1776.98  4987.5 1776.48  4991.4 1776.98  5030.6 1778.58
  5058.9  1790.2  5064.1  1786.7  5082.1 1797.01  5100.1 1803.09  5105.3 1802.24
  5146.5  1809.1  5182.6 1821.15  5187.8  1821.1  5216.1 1831.21  5223.8 1835.64
    5229 1835.33  5265.1 1850.37  5292.7 1858.03  5300.5 1860.45  5411.9 1897.82
#Mann= 7 ,-1 , 0
  4587.3     .12       0  4707.4     .07       0  4969.7    .035       0
  4987.3     .05       0  4991.4    .035       0  5292.7    .035       0
  5300.5     .07       0
Bank Sta=4987.3,4991.4
XS Rating Curve= 0 ,0
Exp/Cntr=0.3,0.1

Type RM Length L Ch R = 1 ,10116   ,467,467,467
BEGIN DESCRIPTION:
Stream0115_DS 20.0
END DESCRIPTION:
XS GIS Cut Line= 3
      2006975.03     13949675.01        2006575.       13949525.
      2006175.04     13949425.01
#Sta/Elev= 30
  4573.2 1915.25  4588.4 1912.97  4637.3 1897.49  4643.5 1893.62  4673.8 1882.82
  4698.7 1870.94  4722.8 1862.01    4729 1857.98  4759.2 1847.39  4765.5 1843.15
  4814.4 1822.41  4850.9 1813.12  4979.1 1794.77  4985.3 1787.81  4990.6 1786.21
  4997.8 1771.64  5008.4 1769.55  5008.7 1769.05    5013 1769.55  5018.5 1772.28
  5032.1 1774.03  5132.9 1777.46  5149.8 1777.94  5206.6 1784.56    5271 1795.08
  5334.6 1811.01  5348.3 1817.03  5353.5 1817.56  5381.8    1834  5412.7  1845.4
#Mann= 7 ,-1 , 0
  4573.2     .07       0  5008.4     .05       0    5013     .07       0
  5032.1    .035       0  5132.9     .07       0  5149.8    .035       0
  5334.6     .07       0
Bank Sta=5008.4,5013
XS Rating Curve= 0 ,0
Exp/Cntr=0.3,0.1

Type RM Length L Ch R = 1 ,9649    ,461,461,461
BEGIN DESCRIPTION:
Stream0115_DS 19.0
END DESCRIPTION:
XS GIS Cut Line= 3
      2006924.98     13949474.98        2006525.       13949075.
      2006124.96     13948924.99
#Sta/Elev= 30
  4433.9 1864.79  4490.4 1846.84  4603.6 1817.35    4646 1808.93  4730.9 1797.42
  4773.3    1781  4787.4 1777.58  4818.8 1774.77  4833.8 1773.99  4872.3 1771.93
  4964.2 1771.18    5007  1764.1  5007.3  1763.6  5011.7  1764.1  5039.6 1780.71
  5109.2 1782.48  5149.1  1788.4  5185.6 1797.13  5191.8 1801.37  5210.5 1809.25
  5215.8 1809.67  5240.7 1820.24  5246.1 1820.13    5271 1827.76  5277.2 1831.13
  5301.3 1837.81  5326.2  1848.3  5356.4 1854.88    5363 1858.09  5426.8 1878.19
#Mann= 7 ,-1 , 0
  4433.9     .07       0  4818.8    .035       0  4833.8     .07       0
    5007     .05       0  5011.7     .07       0  5109.2    .035       0
    5363     .07       0
Bank Sta=5007,5011.7
XS Rating Curve= 0 ,0
Exp/Cntr=0.3,0.1

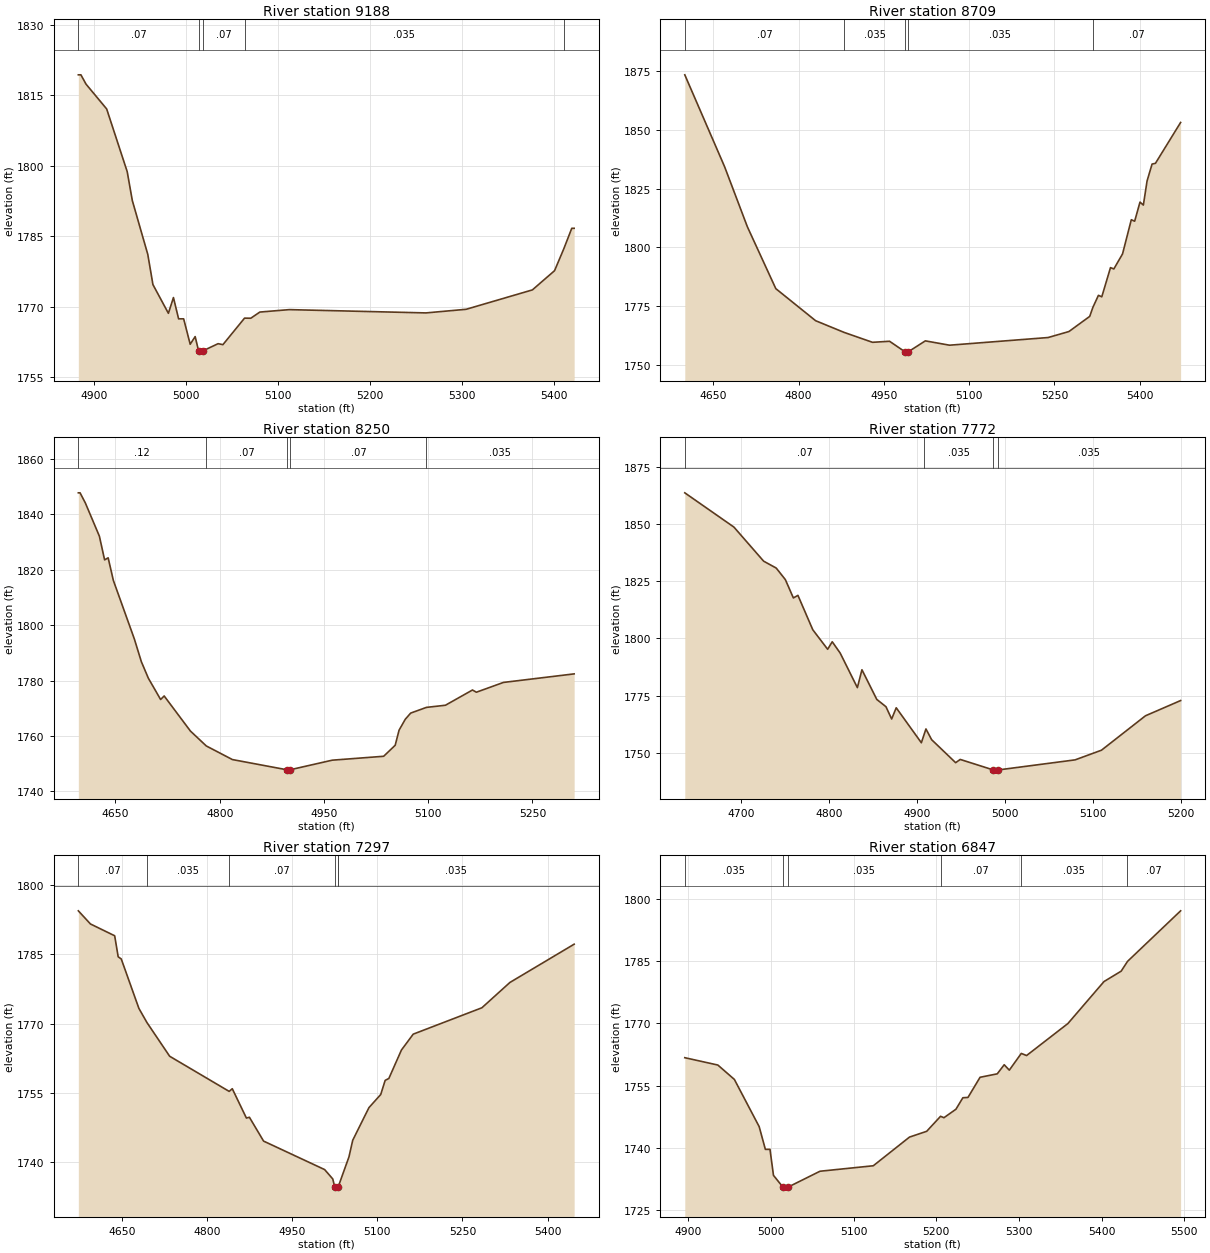
Type RM Length L Ch R = 1 ,9188    ,479,479,479
BEGIN DESCRIPTION:
Stream0115_DS 18.0
END DESCRIPTION:
XS GIS Cut Line= 3
      2006875.03     13948775.01        2006775.       13948725.
      2006375.03     13948874.99
#Sta/Elev= 30
  4882.6 1819.37  4885.4 1819.37    4891 1817.38  4913.4 1812.11  4935.7 1798.78
  4941.3  1792.6  4958.1 1781.15  4963.7 1774.72  4980.5 1768.61    4986 1771.96
  4991.6 1767.43  4997.1 1767.43  5004.2 1762.02  5009.6 1763.65  5013.3 1760.63
  5013.7 1760.13  5018.2 1760.63  5034.5 1762.14  5039.8 1761.94  5063.3 1767.58
  5070.1 1767.56  5079.9 1768.87  5111.9 1769.39  5260.5 1768.69  5304.2 1769.46
  5376.2 1773.59  5400.3 1777.68  5410.2 1782.27    5419  1786.7  5421.6  1786.7
#Mann= 5 ,-1 , 0
  4882.6     .07       0  5013.3     .05       0  5018.2     .07       0
  5063.3    .035       0  5410.2     .07       0
Bank Sta=5013.3,5018.2
XS Rating Curve= 0 ,0
Exp/Cntr=0.3,0.1

Type RM Length L Ch R = 1 ,8709    ,459,459,459
BEGIN DESCRIPTION:
Stream0115_DS 17.0
END DESCRIPTION:
XS GIS Cut Line= 3
      2006974.95       13948325.        2006575.       13948325.
      2006174.96     13948575.03
#Sta/Elev= 30
  4600.1 1873.39  4670.1 1834.32  4710.1 1808.81  4760.1 1782.51  4830.1 1768.88
  4880.3  1763.9  4930.1  1759.7  4960.1 1760.14  4987.6  1755.6    4988  1755.1
  4992.5  1755.6    5023 1760.31  5065.5 1758.47  5238.8 1761.73  5275.4 1764.27
    5312 1770.72  5317.5 1774.53  5327.3 1779.67  5333.2 1779.04  5348.5 1791.44
  5354.4 1790.88  5369.7 1797.28  5385.1 1811.81    5391 1811.17  5400.4 1819.31
  5406.3 1818.03  5412.8 1828.26  5421.6 1835.46  5427.5 1835.77  5471.8 1853.14
#Mann= 5 ,-1 , 0
  4600.1     .07       0  4880.3    .035       0  4987.6    .035       0
  4992.5    .035       0  5317.5     .07       0
Bank Sta=4987.6,4992.5
XS Rating Curve= 0 ,0
Exp/Cntr=0.3,0.1

Type RM Length L Ch R = 1 ,8250    ,478,478,478
BEGIN DESCRIPTION:
Stream0115_DS 16.0
END DESCRIPTION:
XS GIS Cut Line= 3
      2006925.02       13948125.        2006525.       13948075.
      2006248.57     13947934.11
#Sta/Elev= 30
  4596.6 1847.79  4599.1 1847.79  4606.7 1844.13  4626.9 1832.13  4634.4 1823.59
  4639.5 1824.33    4647 1816.17  4677.2 1795.04  4687.3 1786.82  4697.4 1780.86
    4715 1773.19  4720.1 1774.47  4757.9  1761.8  4780.7 1756.43  4818.3 1751.51
  4896.5 1747.84  4896.9 1747.34  4901.5 1747.84  4961.9 1751.29  5035.9  1752.7
  5052.5 1756.67  5058.1 1762.13  5067.1 1766.09  5074.8 1768.29  5097.4 1770.34
  5124.8 1771.12  5163.7 1776.62  5169.3 1775.82  5208.2 1779.35    5310 1782.44
#Mann= 5 ,-1 , 0
  4596.6     .12       0  4780.7     .07       0  4896.5     .05       0
  4901.5     .07       0  5097.4    .035       0
Bank Sta=4896.5,4901.5
XS Rating Curve= 0 ,0
Exp/Cntr=0.3,0.1

Type RM Length L Ch R = 1 ,7772    ,475,475,475
BEGIN DESCRIPTION:
Stream0115_DS 15.0
END DESCRIPTION:
XS GIS Cut Line= 3
      2006925.01       13947925.        2006575.       13947825.
      2006375.02       13947825.
#Sta/Elev= 30
    4636 1863.65  4691.9 1848.67  4725.7 1833.78    4740 1830.77  4750.4 1825.72
  4759.5 1817.72  4764.7 1818.84  4781.6  1803.8  4798.5 1795.28  4803.7 1798.57
  4812.8 1793.59  4832.3 1778.51  4837.5 1786.33  4854.4 1773.36  4864.8 1770.19
  4871.3 1764.81  4876.5 1769.71  4905.1 1754.43  4908.4 1758.26  4910.3 1760.46
  4916.8 1755.76  4944.1 1745.72  4949.3 1747.14  4987.1 1742.53  4987.5 1742.03
  4992.1 1742.53    5080 1746.95    5110 1751.18    5160 1766.21    5200 1772.87
#Mann= 4 ,-1 , 0
    4636     .07       0  4908.4    .035       0  4987.1    .035       0
  4992.1    .035       0
Bank Sta=4987.1,4992.1
XS Rating Curve= 0 ,0
Exp/Cntr=0.3,0.1

Type RM Length L Ch R = 1 ,7297    ,450,450,450
BEGIN DESCRIPTION:
Stream0115_DS 14.0
END DESCRIPTION:
XS GIS Cut Line= 3
      2006775.03     13947575.01        2006375.       13947425.
      2006088.84     13947768.62
#Sta/Elev= 30
  4572.6 1794.37    4594 1791.53  4636.7 1788.98  4642.9 1784.43  4648.3 1783.97
  4679.4 1773.29  4693.7 1770.21  4733.7 1762.94  4838.6 1755.35  4844.1 1755.93
    4869 1749.59  4874.3 1749.76  4899.3 1744.61    5007 1738.45  5021.3 1736.43
  5024.7 1734.73  5025.2 1734.23  5030.9 1734.73    5031 1734.75  5049.9 1741.21
  5056.5 1744.79  5085.1 1751.84  5105.9 1754.68  5113.7 1757.73  5120.2 1758.14
  5142.4 1764.29  5163.2 1767.72  5284.3 1773.42  5333.7 1778.89    5447 1787.16
#Mann= 6 ,-1 , 0
  4572.6     .07       0  4693.7    .035       0  4838.6     .07       0
  5024.7     .05       0  5030.9     .07       0    5031    .035       0
Bank Sta=5024.7,5030.9
XS Rating Curve= 0 ,0
Exp/Cntr=0.3,0.1

Type RM Length L Ch R = 1 ,6847    ,478,478,478
BEGIN DESCRIPTION:
Stream0115_DS 13.0
END DESCRIPTION:
XS GIS Cut Line= 3
      2006625.02       13947025.        2006525.       13947025.
      2006125.01     13946725.01
#Sta/Elev= 30
  4895.7 1761.73  4935.7 1759.96  4955.7 1756.49  4985.7 1745.12  4993.2 1739.64
  4998.8 1739.64    5003 1733.38  5014.4 1730.56  5014.9 1730.06  5020.8 1730.56
  5059.3 1734.37  5123.8 1735.69  5167.6  1742.6  5188.4 1743.99  5205.2 1747.61
  5209.3 1747.27  5223.8 1749.31  5232.2 1752.08  5238.4 1752.16    5253 1757.01
  5273.8 1757.84  5282.2 1760.03  5288.4 1758.73  5302.9 1762.76  5309.3 1762.25
  5359.3 1769.96    5403 1780.08  5423.8 1782.59  5431.4 1784.93  5495.7 1797.12
#Mann= 6 ,-1 , 0
  4895.7    .035       0  5014.4    .035       0  5020.8    .035       0
  5205.2     .07       0  5302.9    .035       0  5431.4     .07       0
Bank Sta=5014.4,5020.8
XS Rating Curve= 0 ,0
Exp/Cntr=0.3,0.1

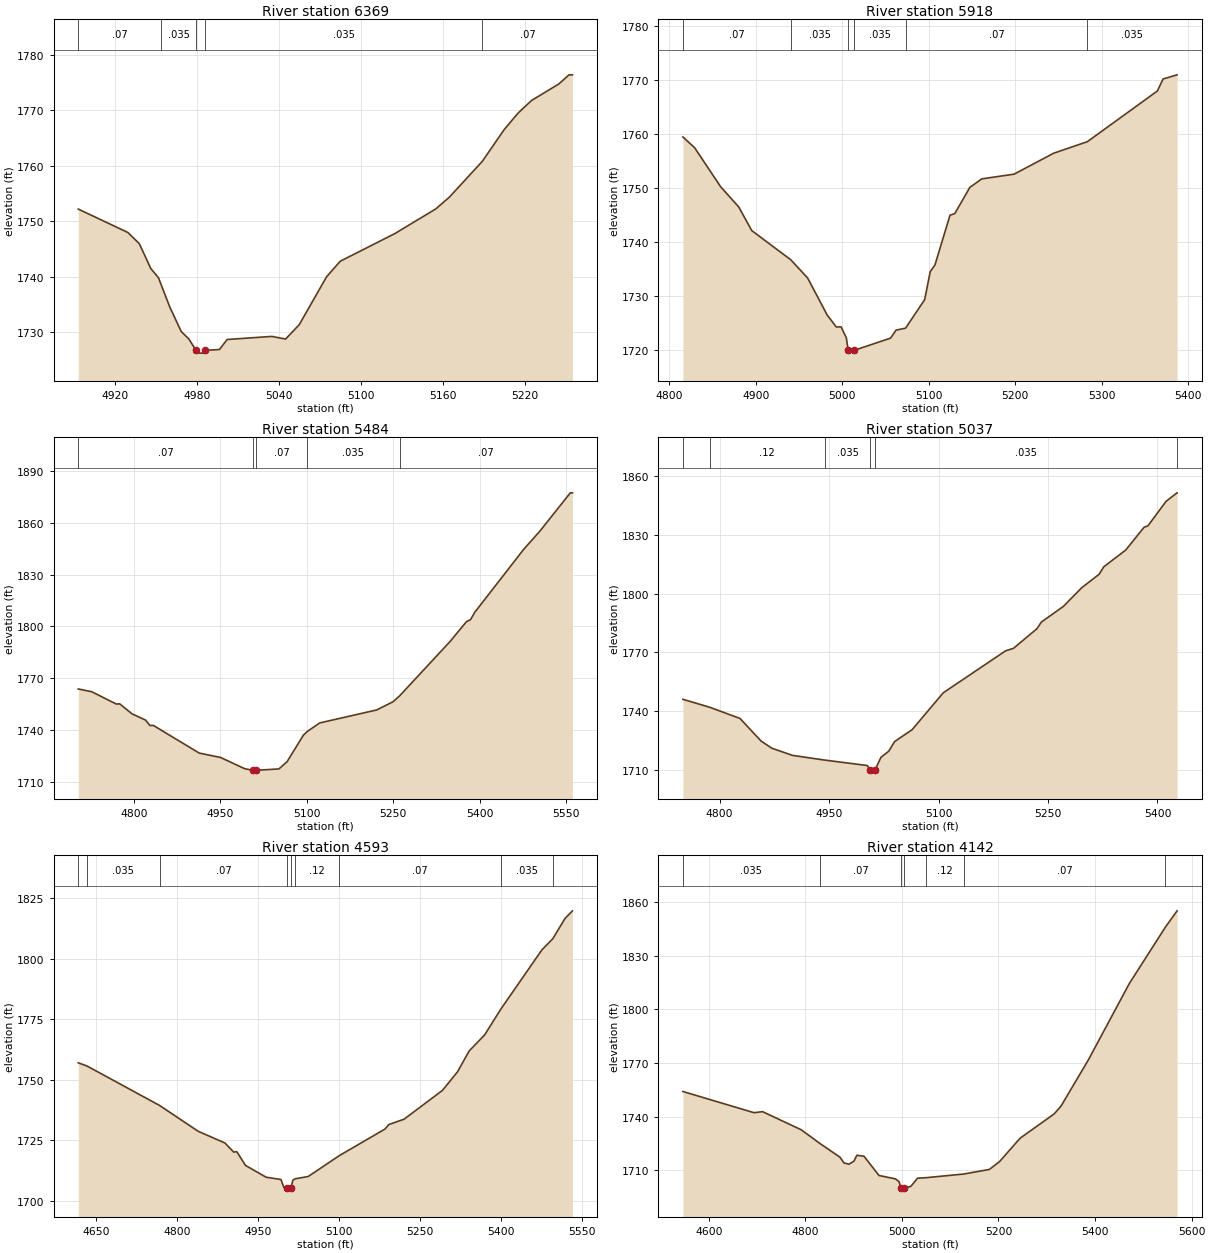
Type RM Length L Ch R = 1 ,6369    ,451,451,451
BEGIN DESCRIPTION:
Stream0115_DS 12.0
END DESCRIPTION:
XS GIS Cut Line= 3
      2006624.97     13946624.98        2006525.       13946575.
      2006274.96       13946575.
#Sta/Elev= 30
  4892.8  1752.2  4929.1 1747.99  4937.5 1745.98  4945.9 1741.51  4951.5 1739.86
  4953.4 1738.65  4959.8 1734.59  4968.2 1730.16  4973.8 1728.83    4979 1726.78
  4979.5 1726.28  4984.9 1726.28  4985.4 1726.78  4996.2 1726.93  5001.8 1728.73
  5034.6 1729.29  5044.6 1728.81  5054.6  1731.4  5074.6 1740.01  5084.6 1742.81
  5124.6 1747.79  5154.6 1752.23  5164.6 1754.37  5188.6 1760.78  5204.6 1766.49
  5214.6 1769.41  5224.6 1771.72  5244.6  1774.7  5252.1 1776.35  5254.6 1776.35
#Mann= 5 ,-1 , 0
  4892.8     .07       0  4953.4    .035       0    4979    .035       0
  4985.4    .035       0  5188.6     .07       0
Bank Sta=4979,4985.4
XS Rating Curve= 0 ,0
Exp/Cntr=0.3,0.1

Type RM Length L Ch R = 1 ,5918    ,434,434,434
BEGIN DESCRIPTION:
Stream0115_DS 11.0
END DESCRIPTION:
XS GIS Cut Line= 3
      2006825.01     13946275.01        2006675.       13946175.
      2006320.33      13946009.9
#Sta/Elev= 30
  4815.6 1759.37  4829.1  1757.4  4859.2 1750.17  4880.2 1746.41  4895.2 1742.05
  4940.3 1736.65  4959.8 1733.28  4982.4 1726.43  4992.9 1724.21  4998.6 1724.21
  5004.6 1722.18  5006.8 1719.86  5007.3 1719.36  5013.3 1719.86  5055.8 1722.14
  5062.1 1723.62  5073.1 1723.98  5095.2 1729.26  5101.6 1734.43  5107.1 1735.69
  5124.5  1744.9    5130 1745.18  5147.4 1750.04  5161.3 1751.62  5198.6 1752.49
  5244.4 1756.37  5283.3  1758.5  5364.3 1767.89  5370.9 1770.11  5387.1 1770.88
#Mann= 6 ,-1 , 0
  4815.6     .07       0  4940.3    .035       0  5006.8    .035       0
  5013.3    .035       0  5073.1     .07       0  5283.3    .035       0
Bank Sta=5006.8,5013.3
XS Rating Curve= 0 ,0
Exp/Cntr=0.3,0.1

Type RM Length L Ch R = 1 ,5484    ,447,447,447
BEGIN DESCRIPTION:
Stream0115_DS 10.0
END DESCRIPTION:
XS GIS Cut Line= 3
      2007025.02     13945925.01        2006775.       13945775.
      2006374.97     13945374.97
#Sta/Elev= 30
  4703.8  1763.8  4727.1 1762.22  4769.9 1755.05  4775.7 1755.19  4797.1 1749.38
  4820.4  1745.8  4828.2 1742.65  4834.1 1742.68  4913.7 1726.65  4950.7 1724.12
  4992.5 1717.61  5006.2  1716.7  5006.7  1716.2  5012.8  1716.7  5051.9 1717.47
  5066.1 1721.67  5094.4 1737.04  5101.1 1739.17  5122.7 1744.12  5221.6 1751.64
  5249.9  1756.4  5261.2 1759.77  5348.9 1791.33  5377.2 1802.77  5384.3 1803.94
  5391.4  1808.1  5476.2 1844.55  5504.5 1855.19  5557.5 1877.43  5561.1 1877.43
#Mann= 5 ,-1 , 0
  4703.8     .07       0  5006.2     .05       0  5012.8     .07       0
  5101.1    .035       0  5261.2     .07       0
Bank Sta=5006.2,5012.8
XS Rating Curve= 0 ,0
Exp/Cntr=0.3,0.1

Type RM Length L Ch R = 1 ,5037    ,444,444,444
BEGIN DESCRIPTION:
Stream0115_DS 9.0
END DESCRIPTION:
XS GIS Cut Line= 3
      2007125.04     13945525.03        2006925.       13945375.
      2006525.05     13945225.02
#Sta/Elev= 30
  4749.7 1745.99  4786.3 1741.96  4827.9 1736.23    4857 1724.63  4871.6 1721.02
  4899.7 1717.38  4944.5 1714.93  5002.4 1712.18  5006.2 1709.82  5006.7 1709.32
  5012.9 1709.82  5021.1 1716.38  5031.8 1719.51  5039.8  1724.4  5063.8 1730.49
  5106.5 1749.33    5192 1770.77  5202.7 1772.03  5234.7 1781.99  5240.9 1785.44
  5271.2 1793.47  5296.1 1802.93  5320.1 1809.87  5326.4 1813.64  5356.6 1822.25
  5381.6 1833.82  5386.9 1834.55  5411.8 1847.09  5426.8 1851.43  5426.9 1851.43
#Mann= 6 ,-1 , 0
  4749.7     .07       0  4786.3     .12       0  4944.5    .035       0
  5006.2    .035       0  5012.9    .035       0  5426.8     .07       0
Bank Sta=5006.2,5012.9
XS Rating Curve= 0 ,0
Exp/Cntr=0.3,0.1

Type RM Length L Ch R = 1 ,4593    ,451,451,451
BEGIN DESCRIPTION:
Stream0115_DS 8.0
END DESCRIPTION:
XS GIS Cut Line= 3
      2007406.96     13945412.61        2007225.       13945075.
      2006875.02     13944675.02
#Sta/Elev= 30
  4616.7 1757.01  4633.1 1755.66  4767.2 1739.39  4838.8  1728.7  4888.3 1723.86
  4904.5  1720.1  4910.2 1720.29  4926.4 1714.58  4964.5 1709.72  4992.1 1708.75
  4997.4 1705.46  5003.9 1705.29  5004.4 1704.79  5010.7 1705.29    5014 1708.47
  5018.4 1709.07  5042.5 1710.01  5100.1 1718.64  5184.8 1729.65  5191.5 1731.47
  5219.9 1733.69  5291.1 1745.61  5319.1 1753.33  5340.5 1761.91    5369  1768.5
  5399.5 1779.32  5475.3 1803.73  5495.4 1808.31    5518 1816.69  5531.7 1819.83
#Mann= 9 ,-1 , 0
  4616.7     .07       0  4633.1    .035       0  4767.2     .07       0
  5003.9     .05       0  5010.7     .07       0  5018.4     .12       0
  5100.1     .07       0  5399.5    .035       0  5495.4     .07       0
Bank Sta=5003.9,5010.7
XS Rating Curve= 0 ,0
Exp/Cntr=0.3,0.1

Type RM Length L Ch R = 1 ,4142    ,481,481,481
BEGIN DESCRIPTION:
Stream0115_DS 7.0
END DESCRIPTION:
XS GIS Cut Line= 3
      2007917.35     13944843.14        2007475.       13944725.
      2007075.03     13944325.03
#Sta/Elev= 30
  4546.4 1754.09  4693.7 1742.24  4711.4 1742.83  4791.6 1732.67  4829.6 1725.14
  4871.7 1717.36    4880 1714.14  4890.4 1713.47  4900.7 1715.15  4906.6 1718.43
  4921.4 1717.93  4952.5 1707.14  4986.8 1705.22  4993.9 1703.73  4998.2 1700.01
  4998.7 1699.51  5005.1 1700.01  5018.4 1701.03  5032.5 1705.64  5048.9 1705.87
  5127.6 1707.94    5181  1710.5  5202.2  1714.9  5244.7 1727.96  5315.4 1741.58
  5329.5 1745.92  5386.1 1771.74  5470.9 1814.42  5545.5 1845.92  5569.9  1855.1
#Mann= 7 ,-1 , 0
  4546.4    .035       0  4829.6     .07       0  4998.2     .05       0
  5005.1     .07       0  5048.9     .12       0  5127.6     .07       0
  5545.5    .035       0
Bank Sta=4998.2,5005.1
XS Rating Curve= 0 ,0
Exp/Cntr=0.3,0.1

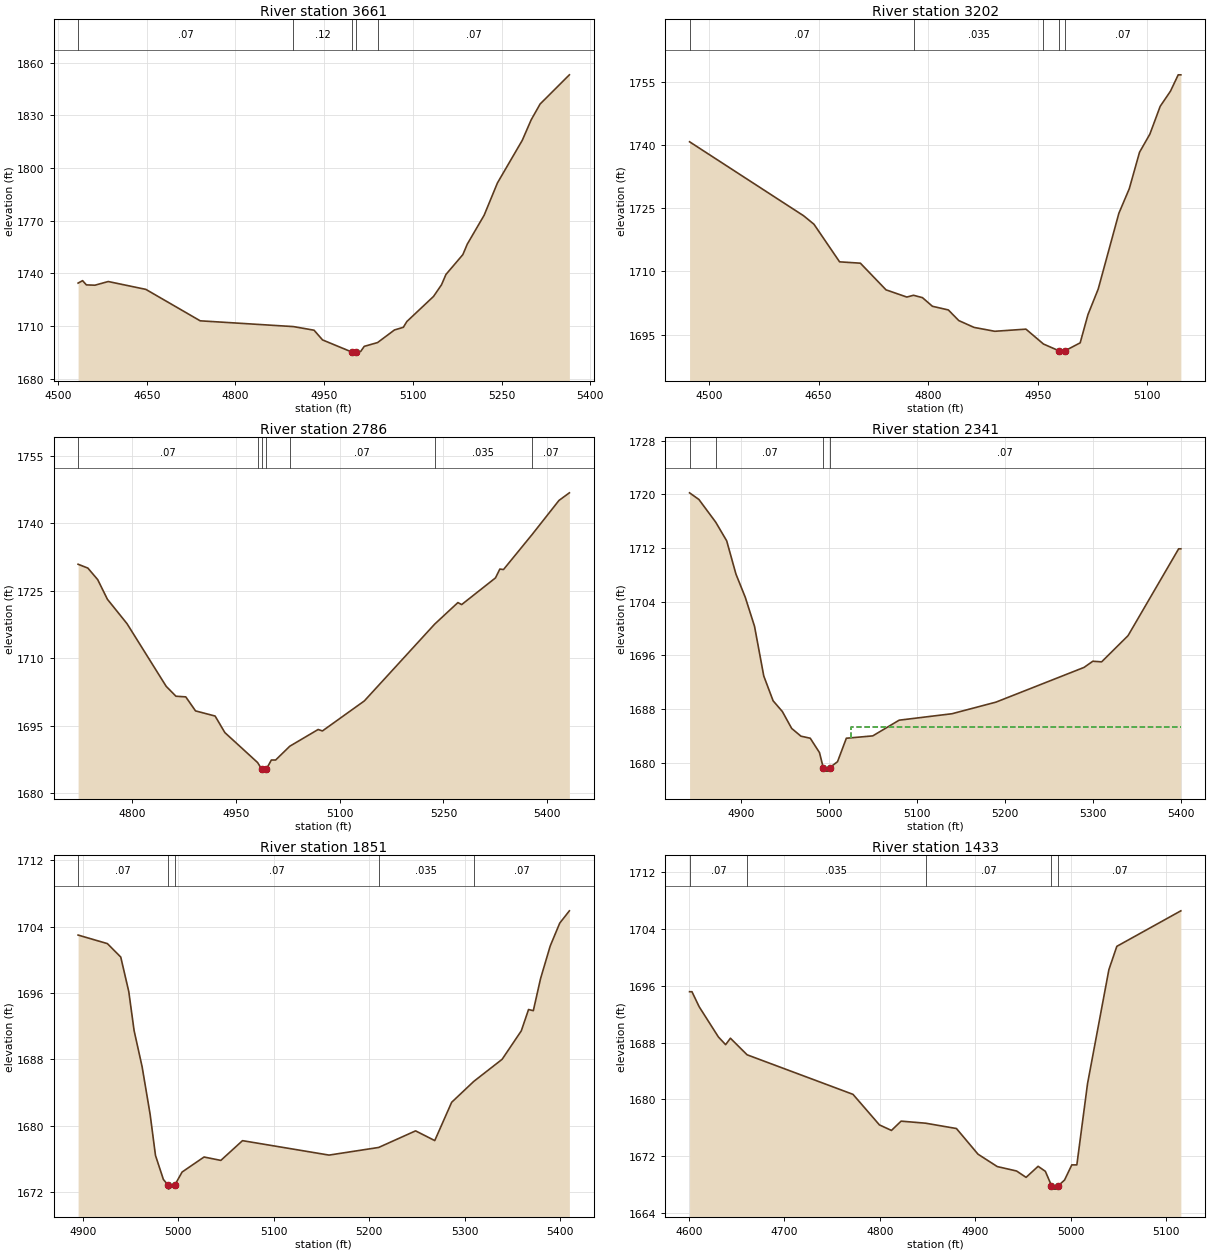
Type RM Length L Ch R = 1 ,3661    ,459,459,459
BEGIN DESCRIPTION:
Stream0115_DS 6.0
END DESCRIPTION:
XS GIS Cut Line= 3
      2007945.17     13944565.39        2007575.       13944275.
      2007375.02     13943975.03
#Sta/Elev= 30
  4533.8 1734.53  4541.4 1735.93  4547.8 1733.51  4562.3 1733.34  4584.8 1735.43
  4648.4 1730.96  4740.3 1713.07    4898 1709.78  4932.9 1707.72  4947.3 1702.19
  4997.7 1695.18  4998.2 1694.68  5004.6 1695.18  5011.8 1695.64  5017.8 1698.53
  5040.4  1700.7  5068.9 1707.86  5083.9 1709.37  5089.9 1712.67    5135 1726.94
  5148.5 1733.58    5156 1739.44  5184.6 1750.74  5192.1 1756.71  5220.6 1773.15
  5243.1 1791.53  5285.2 1815.85  5300.2 1827.48  5315.3 1836.45  5364.8 1853.06
#Mann= 5 ,-1 , 0
  4533.8     .07       0    4898     .12       0  4997.7     .05       0
  5004.6     .12       0  5040.4     .07       0
Bank Sta=4997.7,5004.6
XS Rating Curve= 0 ,0
Exp/Cntr=0.3,0.1

Type RM Length L Ch R = 1 ,3202    ,416,416,416
BEGIN DESCRIPTION:
Stream0115_DS 5.0
END DESCRIPTION:
XS GIS Cut Line= 3
      2008275.04     13944325.03        2007875.       13943975.
      2007774.98     13943874.98
#Sta/Elev= 30
  4473.2 1740.75  4629.4 1723.21  4643.6  1721.2  4678.7 1712.28  4707.2 1711.96
  4742.3 1705.64  4770.8 1703.93    4780 1704.35  4792.2 1703.79  4805.9 1701.74
  4827.7 1700.87    4842 1698.35  4862.9 1696.73  4891.3 1695.81    4934 1696.32
    4958 1692.79  4979.9 1691.13  4980.4 1690.63  4986.9 1691.13  5008.3 1693.07
  5018.9 1699.74    5033 1705.83  5061.3  1723.8  5075.5  1729.6  5089.6 1738.27
  5103.8 1742.58  5117.9 1749.16    5132 1752.76  5142.6 1756.63  5146.2 1756.63
#Mann= 5 ,-1 , 0
  4473.2     .07       0    4780    .035       0    4958     .07       0
  4979.9     .05       0  4986.9     .07       0
Bank Sta=4979.9,4986.9
XS Rating Curve= 0 ,0
Exp/Cntr=0.3,0.1

Type RM Length L Ch R = 1 ,2786    ,445,445,445
BEGIN DESCRIPTION:
Stream0115_DS 4.0
END DESCRIPTION:
XS GIS Cut Line= 3
      2008424.99     13944024.99        2008225.       13943825.
      2007825.03     13943675.01
#Sta/Elev= 30
  4722.1 1730.86  4736.2 1730.01  4750.4 1727.45  4764.5 1723.07  4792.8 1717.66
  4849.4 1703.74  4863.5 1701.54  4877.7  1701.4  4891.8 1698.28  4920.1 1697.14
  4934.2 1693.46  4981.5 1686.81  4987.2  1685.4  4987.7  1684.9  4994.3  1685.4
  5001.4 1687.37  5007.6 1687.37    5028 1690.43    5069 1694.15  5075.2 1693.83
  5135.8  1700.5  5237.3 1717.54    5271 1722.35  5276.4  1721.9  5325.3 1727.83
  5331.6 1729.79  5336.9 1729.69  5378.2 1737.46    5417 1745.03  5432.1 1746.73
#Mann= 7 ,-1 , 0
  4722.1     .07       0  4981.5    .035       0  4987.2    .035       0
  4994.3    .035       0    5028     .07       0  5237.3    .035       0
  5378.2     .07       0
Bank Sta=4987.2,4994.3
XS Rating Curve= 0 ,0
Exp/Cntr=0.3,0.1

Type RM Length L Ch R = 1 ,2341    ,490,490,490
BEGIN DESCRIPTION:
Stream0115_DS 3.0
END DESCRIPTION:
XS GIS Cut Line= 3
      2008675.02     13943575.01        2008525.       13943525.
      2008125.03       13943525.
#Sta/Elev= 30
  4841.9 1720.21  4852.5 1719.22  4871.6 1715.84  4884.1 1713.05  4894.6  1708.1
  4905.2 1704.64  4915.7 1700.32  4926.2 1692.92  4936.8 1689.23  4947.3 1687.63
  4957.9 1685.11  4968.4 1683.96    4979 1683.65  4989.5 1681.51  4993.8 1679.25
  4994.3 1678.75  5000.5 1678.75    5001 1679.25    5010 1680.16    5020 1683.65
    5050    1684    5080 1686.34    5140  1687.3    5190 1689.03    5290  1694.2
    5300 1695.12    5310 1695.03    5340 1698.93  5397.5 1711.87    5400 1711.87
#Mann= 4 ,-1 , 0
  4841.9    .035       0  4871.6     .07       0  4993.8     .05       0
    5001     .07       0
#XS Ineff= 2 , 0
       0                    5025       0  1685.3
Permanent Ineff=
       F       F
Bank Sta=4993.8,5001
XS Rating Curve= 0 ,0
Exp/Cntr=0.3,0.1

Type RM Length L Ch R = 1 ,1851    ,418,418,418
BEGIN DESCRIPTION:
Stream0115_DS 2.0
END DESCRIPTION:
XS GIS Cut Line= 3
        2008575.       13942975.        2008525.       13943075.
      2008125.02       13943125.
#Sta/Elev= 30
    4895 1702.98  4925.7 1701.95  4939.7 1700.33  4948.1 1696.18  4953.7 1691.46
  4962.1 1687.11  4970.5 1681.37  4976.1 1676.43  4984.4 1673.53  4989.2 1672.87
  4989.7 1672.37  4996.4 1672.87    5004 1674.43    5027 1676.24  5044.6 1675.83
  5067.3 1678.21    5158 1676.47    5210 1677.39  5248.7 1679.39  5268.8 1678.22
  5286.5 1682.83  5309.7 1685.35  5339.4 1688.01  5359.5 1691.44  5367.1 1694.01
  5372.1 1693.87  5379.7 1697.74  5389.8 1701.66  5399.8 1704.42  5409.9  1705.9
#Mann= 5 ,-1 , 0
    4895     .07       0  4989.2     .05       0  4996.4     .07       0
    5210    .035       0  5309.7     .07       0
Bank Sta=4989.2,4996.4
XS Rating Curve= 0 ,0
Exp/Cntr=0.3,0.1

Type RM Length L Ch R = 1 ,1433    ,530,530,530
BEGIN DESCRIPTION:
Stream0115_DS 1.0
END DESCRIPTION:
XS GIS Cut Line= 3
      2008575.01       13942875.        2008175.       13942925.
      2008075.02     13942974.99
#Sta/Elev= 30
  4600.7 1695.17  4603.2 1695.17  4610.8 1693.04  4630.9 1688.79  4638.5  1687.7
  4643.5 1688.61    4661 1686.27    4772 1680.69  4799.7 1676.38  4812.3  1675.6
  4822.4 1676.91  4848.1 1676.62  4880.4 1675.87    4903 1672.25  4923.2  1670.5
  4943.4 1669.88  4953.4 1668.98    4966 1670.54  4973.6 1669.83    4980 1667.82
  4980.5 1667.32  4986.8 1667.32  4987.3 1667.82  4993.7  1668.6  5001.3 1670.74
  5006.6 1670.74  5017.8  1682.2  5040.2 1698.29  5048.5 1701.57  5115.6 1706.58
#Mann= 5 ,-1 , 0
  4600.7     .07       0    4661    .035       0  4848.1     .07       0
    4980     .05       0  4987.3     .07       0
Bank Sta=4980,4987.3
XS Rating Curve= 0 ,0
Exp/Cntr=0.3,0.1

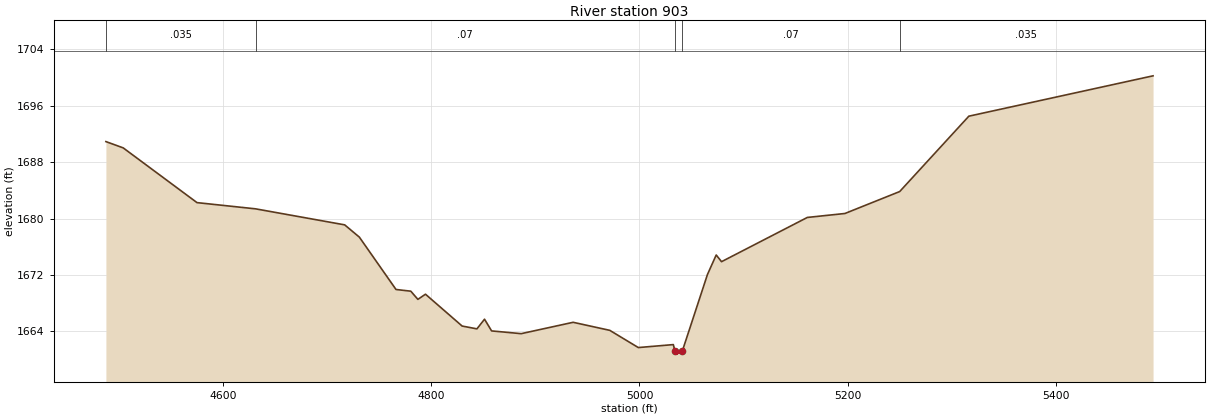
Type RM Length L Ch R = 1 ,903     ,0,0,0
BEGIN DESCRIPTION:
Stream0115_DS 0.0
END DESCRIPTION:
XS GIS Cut Line= 4
      2008645.12     13942778.55      2008268.31     13942431.32
      2008045.65     13942487.06      2007909.33     13942712.75
#Sta/Elev= 30
  4487.6 1690.91  4504.2 1690.02  4575.1 1682.26  4631.3 1681.38  4716.9 1679.11
    4731 1677.37  4766.2 1669.95  4780.4 1669.71  4787.2 1668.55  4794.5 1669.28
  4829.7 1664.77  4843.9 1664.37  4851.2 1665.74    4858 1664.08  4886.4 1663.69
  4936.3  1665.3  4971.5 1664.16  4998.9 1661.72  5032.5 1662.14    5034 1661.29
  5034.5 1660.79  5041.3 1661.29  5065.3 1672.08  5073.7 1674.84  5078.8 1673.89
  5161.2 1680.16  5197.3 1680.72  5249.9 1683.83  5316.3 1694.51  5493.2 1700.23
#Mann= 5 ,-1 , 0
  4487.6    .035       0  4631.3     .07       0    5034     .05       0
  5041.3     .07       0  5249.9    .035       0
Bank Sta=5034,5041.3
XS Rating Curve= 0 ,0
Exp/Cntr=0.3,0.1

Chan Stop Cuts=-1
Use User Specified Reach Order=0
Composite Channel Slope=5