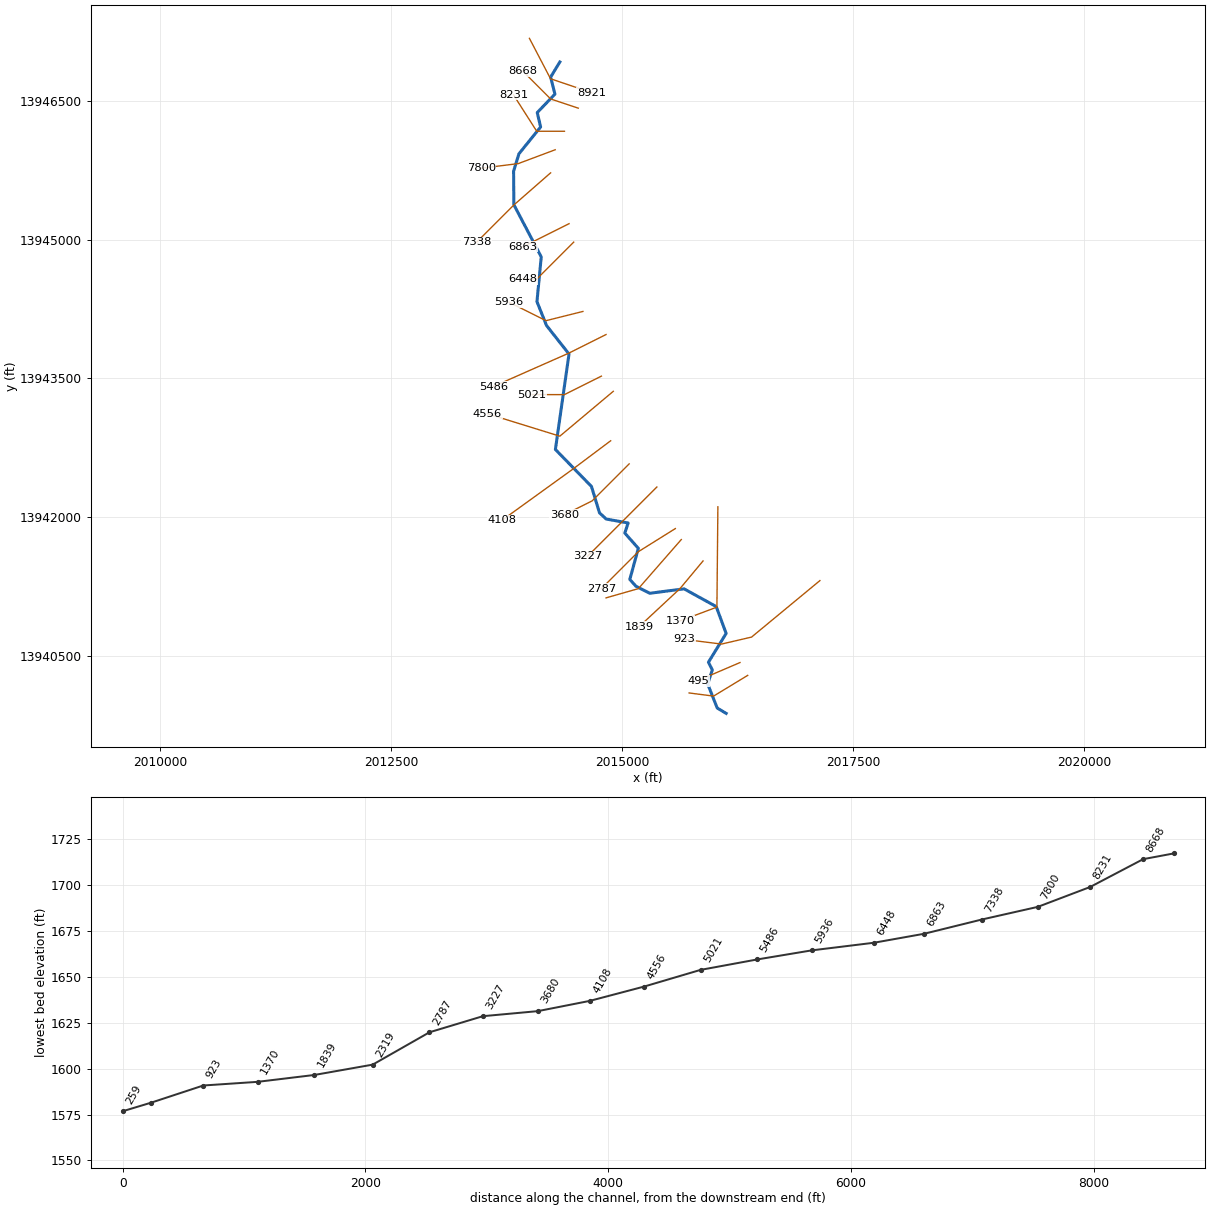
--- Stream0116_DS.prj (project) ---

Proj Title=Stream0116_DS Base Level Engineering
Current Plan=p01
Default Exp/Contr=0.3,0.1
English Units
Geom File=g01
Flow File=f01
Plan File=p01
Y Axis Title=Elevation
X Axis Title(PF)=Main Channel Distance
X Axis Title(XS)=Station
BEGIN DESCRIPTION:
Stream0116_DS
END DESCRIPTION:
DSS Export Rating Curves= 0
DSS Export Rating Curve Sorted= 0
DSS Export Volume Flow Curves= 0
DXF OffsetX= 0
DXF OffsetY= 0
DXF ScaleX= 1
DXF ScaleY= 10

--- Stream0116_DS.p01 (plan) ---

Plan Title=Multiple Run
Short Identifier=Multiple
Geom File=g01
Flow File=f01
Subcritical Flow
K Sum by GR= 0
Std Step Tol= 0.01
Critical Tol= 0.01
Num of Std Step Trials= 20
Max Error Tol= 0.3
Flow Tol Ratio= 0.001
Split Flow NTrial= 30
Split Flow Tol= 0.02
Split Flow Ratio= 0.02
Log Output Level= 0
Friction Slope Method= 1
Unsteady Friction Slope Method= 2
Unsteady Bridges Friction Slope Method= 1
Parabolic Critical Depth
Global Vel Dist=  1 , 1 , 1
Global Log Level= 0
CheckData=True
Encroach Param= -1, 0, 0, 0
BEGIN DESCRIPTION:
Multiple Run
END DESCRIPTION:

--- Stream0116_DS.f01 (steady flow) ---

Flow Title=Multiple
Number of Profiles=7
Profile Names=10-year,25-year,50-year,1pct_min,100-year,1pct_plu,500-year
River Rch & RM= Stream0116_DS,Reach-1,8921
     566     944    1300     872    1740    3471    3082
River Rch & RM= Stream0116_DS,Reach-1,7800
    1812    3214    4607    3197    6379   12728   12147
Boundary for River Rch & Prof#=Stream0116_DS,Reach-1,1
Up Type=0
Dn Type=3
Dn Slope=0.005
Boundary for River Rch & Prof#=Stream0116_DS,Reach-1,2
Up Type=0
Dn Type=3
Dn Slope=0.005
Boundary for River Rch & Prof#=Stream0116_DS,Reach-1,3
Up Type=0
Dn Type=3
Dn Slope=0.005
Boundary for River Rch & Prof#=Stream0116_DS,Reach-1,4
Up Type=0
Dn Type=3
Dn Slope=0.005
Boundary for River Rch & Prof#=Stream0116_DS,Reach-1,5
Up Type=0
Dn Type=3
Dn Slope=0.005
Boundary for River Rch & Prof#=Stream0116_DS,Reach-1,6
Up Type=0
Dn Type=3
Dn Slope=0.005
Boundary for River Rch & Prof#=Stream0116_DS,Reach-1,7
Up Type=0
Dn Type=3
Dn Slope=0.005

--- Stream0116_DS.g01 (geometry) ---

Geom Title=Existing Conditions
Program Version=4.10

River Reach=Stream0116_DS   ,Reach-1
Reach XY= 30
        2014325.       13946925.       2014225.4     13946761.09
      2014271.87     13946576.63       2014080.4     13946377.43
      2014116.96     13946221.68       2013882.5     13945931.32
      2013824.61     13945743.34      2013827.18     13945380.45
      2014123.64     13944815.35      2014077.38     13944330.53
      2014180.83      13944072.7      2014424.25     13943764.32
      2014276.96     13942730.89      2014667.18     13942331.19
      2014754.58     13942044.76      2014826.45     13941978.53
      2015064.04     13941935.43      2015028.16     13941826.65
       2015174.6     13941661.09      2015082.31     13941324.89
      2015148.05     13941251.29      2015297.68     13941174.89
      2015669.47     13941222.63      2016017.15     13941031.19
      2016124.93     13940740.39      2015933.07     13940428.31
      2015975.21     13940345.21      2015925.04     13940193.33
       2016028.2     13939932.89        2016125.       13939875.

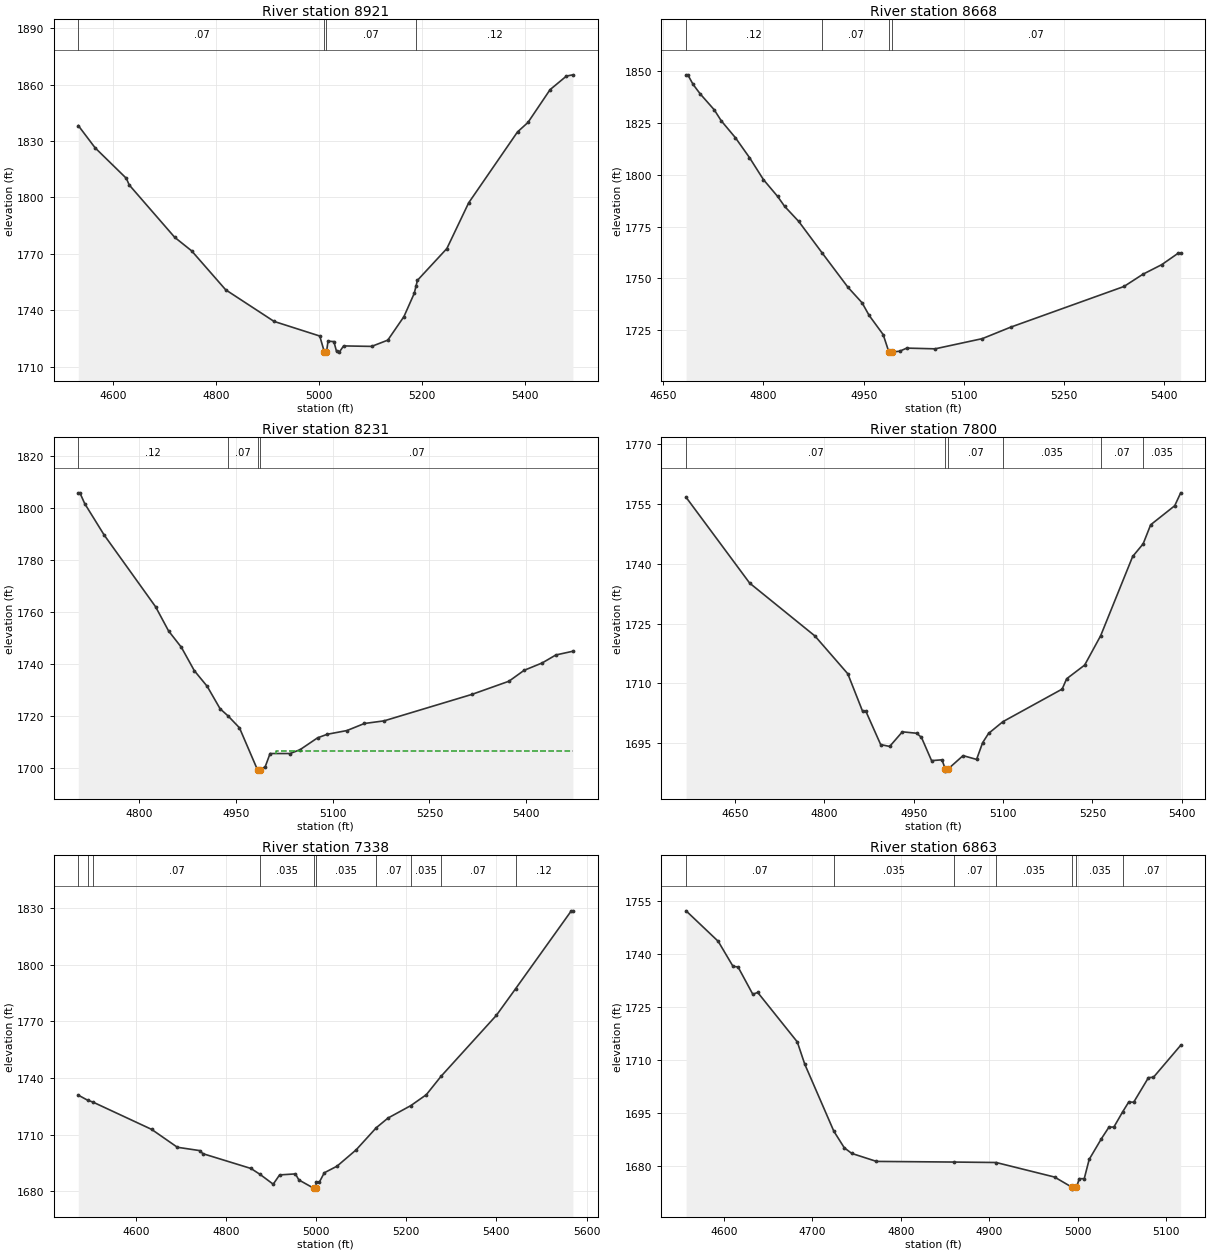
Type RM Length L Ch R = 1 ,8921    ,253,253,253
BEGIN DESCRIPTION:
Stream0116_DS 20.0
END DESCRIPTION:
XS GIS Cut Line= 3
      2013995.76     13947180.78      2014224.29     13946743.27
      2014666.92     13946593.45
#Sta/Elev= 30
4532.701 1838.234565.401 1826.384626.001 1810.174631.701 1806.624720.001 1778.78
4752.901 1771.584819.101 1750.844913.101 1734.035001.801 1726.265010.901 1717.66
5011.201 1717.165014.901 1717.665017.901 1723.525029.301 1723.295034.401  1718.1
5039.701 1717.665048.201    17215102.601 1720.745134.001 1724.075165.401  1736.6
5185.401 1748.965189.001 1752.985191.601 1755.895248.801 1772.815291.101  1797.1
5386.001 1834.845406.301 1839.865449.301 1857.335481.001 1864.545493.601 1865.21
#Mann= 4 ,-1 , 0
4532.701     .07       05010.901     .05       05014.901     .07       0
5189.001     .12       0
Bank Sta=5010.901,5014.901
XS Rating Curve= 0 ,0
Exp/Cntr=0.3,0.1

Type RM Length L Ch R = 1 ,8668    ,437,437,437
BEGIN DESCRIPTION:
Stream0116_DS 19.0
END DESCRIPTION:
XS GIS Cut Line= 3
        2014525.       13946425.        2014225.       13946525.
      2013924.99     13946825.01
#Sta/Elev= 30
  4684.1 1848.12  4686.7 1848.12  4694.6 1843.52  4705.2 1838.96  4726.3 1831.26
  4736.8 1825.96  4757.9 1817.85    4779 1808.27    4800  1797.6  4821.1 1789.56
  4831.7 1784.74  4852.8 1777.47  4888.3 1762.11  4926.5 1745.75  4947.6 1738.29
  4958.2  1732.2  4979.2 1722.96  4987.8 1714.53    4988 1714.03  4991.8 1714.53
  5003.9 1714.96  5014.5 1716.45  5056.9  1716.1  5127.6 1721.01    5170 1726.53
  5339.7 1746.14    5368 1752.03  5396.3 1756.67  5421.1 1762.23  5424.6 1762.23
#Mann= 4 ,-1 , 0
  4684.1     .12       0  4888.3     .07       0  4987.8     .05       0
  4991.8     .07       0
Bank Sta=4987.8,4991.8
XS Rating Curve= 0 ,0
Exp/Cntr=0.3,0.1

Type RM Length L Ch R = 1 ,8231    ,431,431,431
BEGIN DESCRIPTION:
Stream0116_DS 18.0
END DESCRIPTION:
XS GIS Cut Line= 3
      2014374.98       13946175.        2014075.       13946175.
      2013823.62     13946568.83
#Sta/Elev= 30
  4705.3 1805.68  4707.8 1805.68  4715.3 1801.54  4745.3 1789.55  4825.3 1761.93
  4845.3 1752.71  4865.3 1746.37  4885.3 1737.43  4905.3 1731.41  4925.3 1722.81
  4937.8 1720.03  4955.3 1715.51  4983.3 1699.38  4983.5 1698.88  4987.3 1699.38
  4995.3 1700.59  5002.8 1705.63    5034 1705.64  5049.3 1707.11  5076.5 1711.66
  5091.6 1713.03    5122 1714.45  5149.1 1717.16  5179.6 1718.17  5315.8 1728.32
  5373.3 1733.38  5396.8 1737.56  5424.9  1740.4  5446.1 1743.46  5472.5 1744.89
#Mann= 4 ,-1 , 0
  4705.3     .12       0  4937.8     .07       0  4983.3     .05       0
  4987.3     .07       0
#XS Ineff= 2 , 0
       0                 5012.22       0 1706.57
Permanent Ineff=
       F       F
Bank Sta=4983.3,4987.3
XS Rating Curve= 0 ,0
Exp/Cntr=0.3,0.1

Type RM Length L Ch R = 1 ,7800    ,462,462,462
BEGIN DESCRIPTION:
Stream0116_DS 17.0
END DESCRIPTION:
XS GIS Cut Line= 3
      2014275.02     13945975.01        2013875.       13945825.
      2013475.04       13945775.
#Sta/Elev= 30
  4567.8  1756.6  4674.6 1735.11  4784.1 1721.89  4839.3 1712.42  4864.2 1703.01
  4869.5 1703.08  4894.5  1694.7  4909.6 1694.24  4930.9  1697.9    4955 1697.54
    4963 1696.48  4979.9 1690.69  4997.5 1690.89  5002.9 1688.56  5003.2 1688.06
  5007.4 1688.56  5032.8 1691.94  5055.5 1690.99  5065.6 1695.17  5075.6  1697.5
  5099.7 1700.44  5199.1 1708.59  5206.7 1711.18  5236.9  1714.6  5263.8 1721.96
  5317.5 1741.78  5335.1 1744.95  5347.7 1749.71  5388.1 1754.48  5398.1 1757.71
#Mann= 6 ,-1 , 0
  4567.8     .07       0  5002.9     .05       0  5007.4     .07       0
  5099.7    .035       0  5263.8     .07       0  5335.1    .035       0
Bank Sta=5002.9,5007.4
XS Rating Curve= 0 ,0
Exp/Cntr=0.3,0.1

Type RM Length L Ch R = 1 ,7338    ,475,475,475
BEGIN DESCRIPTION:
Stream0116_DS 16.0
END DESCRIPTION:
XS GIS Cut Line= 3
      2014225.02     13945725.02        2013825.       13945375.
      2013425.02     13944975.02
#Sta/Elev= 30
  4472.6 1730.91  4493.4 1728.21  4505.1 1727.23  4635.4 1712.77  4692.4 1703.32
  4741.7 1701.56  4749.3  1699.9  4855.6  1692.1  4875.9 1688.96    4905 1683.77
  4919.2 1688.68  4954.3 1689.22  4961.9 1686.03  4994.7 1681.66    4995 1681.16
  4999.4 1681.66  5000.8 1685.01  5007.7 1685.01  5018.3  1689.8  5046.6 1693.31
    5089 1701.95  5133.8 1713.69  5159.7 1718.78  5210.4 1725.38  5244.6 1731.12
  5277.3 1740.86  5400.1 1773.15  5442.5 1787.15  5566.3 1828.45  5569.8 1828.45
#Mann= 10 ,-1 , 0
  4472.6     .07       0  4493.4    .035       0  4505.1     .07       0
  4875.9    .035       0  4994.7    .035       0  4999.4    .035       0
  5133.8     .07       0  5210.4    .035       0  5277.3     .07       0
  5442.5     .12       0
Bank Sta=4994.7,4999.4
XS Rating Curve= 0 ,0
Exp/Cntr=0.3,0.1

Type RM Length L Ch R = 1 ,6863    ,415,415,415
BEGIN DESCRIPTION:
Stream0116_DS 15.0
END DESCRIPTION:
XS GIS Cut Line= 3
      2014424.96     13945174.98        2014025.       13944975.
      2013924.97     13944924.99
#Sta/Elev= 30
  4557.4 1752.33  4593.7 1743.69  4610.5 1736.57  4616.1 1736.43  4632.8 1728.68
  4638.4 1729.18  4683.1 1715.16  4691.5 1708.87  4724.4 1689.84  4736.2 1685.14
  4744.6 1683.54  4772.6 1681.27  4859.7 1681.09  4907.8 1680.96  4973.8 1676.84
  4993.8 1673.91  4994.1 1673.41  4998.6 1673.91  5001.8 1676.37  5007.4 1676.37
    5013 1681.85  5026.9 1687.75  5035.3 1690.98  5040.9 1691.02  5050.9 1695.36
  5057.7 1698.12  5063.3 1698.06    5080 1705.04  5085.6 1705.12  5116.4  1714.2
#Mann= 7 ,-1 , 0
  4557.4     .07       0  4724.4    .035       0  4859.7     .07       0
  4907.8    .035       0  4993.8    .035       0  4998.6    .035       0
  5050.9     .07       0
Bank Sta=4993.8,4998.6
XS Rating Curve= 0 ,0
Exp/Cntr=0.3,0.1

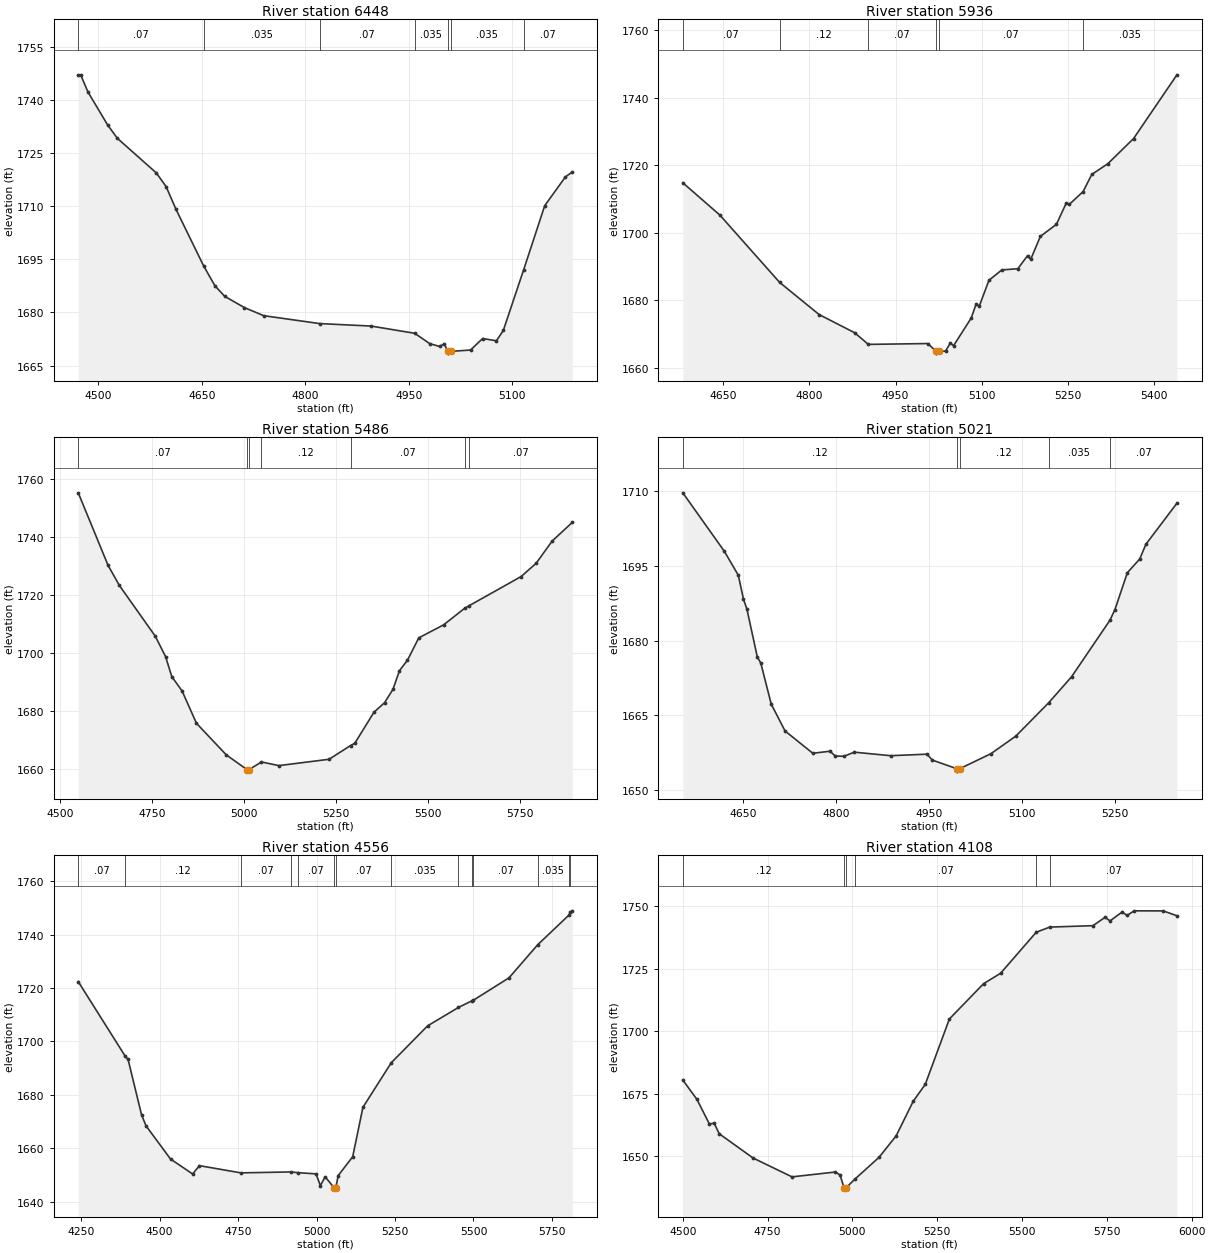
Type RM Length L Ch R = 1 ,6448    ,512,512,512
BEGIN DESCRIPTION:
Stream0116_DS 14.0
END DESCRIPTION:
XS GIS Cut Line= 3
        2014475.       13944975.        2014075.       13944575.
      2013924.98       13944575.
#Sta/Elev= 30
  4471.1 1747.07  4474.6 1747.07  4485.2 1742.21  4513.5 1732.97  4527.7 1729.16
  4584.2 1719.38  4598.4 1715.51  4612.5 1709.18  4652.7 1693.14  4669.1 1687.52
  4683.2 1684.55  4711.5 1681.39  4739.8 1679.08  4820.7 1676.85  4895.4 1676.15
  4958.4 1674.11  4980.2  1671.2  4994.4 1670.39  5001.4 1671.17  5006.1 1669.01
  5006.5 1668.51    5011 1669.01  5039.3 1669.38  5056.8 1672.63  5076.8    1672
  5086.8 1674.91  5116.3 1692.06  5146.8 1710.14  5176.8 1718.26  5186.8 1719.66
#Mann= 7 ,-1 , 0
  4471.1     .07       0  4652.7    .035       0  4820.7     .07       0
  4958.4    .035       0  5006.1    .035       0    5011    .035       0
  5116.3     .07       0
Bank Sta=5006.1,5011
XS Rating Curve= 0 ,0
Exp/Cntr=0.3,0.1

Type RM Length L Ch R = 1 ,5936    ,450,450,450
BEGIN DESCRIPTION:
Stream0116_DS 13.0
END DESCRIPTION:
XS GIS Cut Line= 3
      2014575.01       13944225.        2014175.       13944125.
      2013775.03     13944324.99
#Sta/Elev= 30
  4579.9 1714.81  4644.3 1705.25  4748.3 1685.31    4817 1675.78  4878.8  1670.4
  4902.6 1666.95  5006.2  1667.2  5020.5 1664.86  5020.9 1664.36  5025.4 1664.86
  5036.9 1664.97  5045.3 1667.34  5050.9 1666.57  5081.7 1674.79    5090 1678.86
  5095.6 1678.27  5112.4 1685.93  5134.8    1689  5162.7 1689.36  5179.5 1693.21
  5185.1 1692.15  5201.8 1698.91  5229.8 1702.51  5246.6  1708.7  5252.2  1708.4
  5276.2 1712.21  5291.3 1717.28  5319.2 1720.45    5364 1727.91  5439.4 1746.78
#Mann= 6 ,-1 , 0
  4579.9     .07       0  4748.3     .12       0  4902.6     .07       0
  5020.5     .05       0  5025.4     .07       0  5276.2    .035       0
Bank Sta=5020.5,5025.4
XS Rating Curve= 0 ,0
Exp/Cntr=0.3,0.1

Type RM Length L Ch R = 1 ,5486    ,465,465,465
BEGIN DESCRIPTION:
Stream0116_DS 12.0
END DESCRIPTION:
XS GIS Cut Line= 3
      2014825.02     13943975.01        2014425.       13943775.
      2013604.84     13943412.58
#Sta/Elev= 30
    4549 1755.17  4630.1 1730.22  4660.8 1723.31  4758.7  1705.8  4786.6 1698.79
  4803.4 1691.94  4831.3 1687.02  4870.5 1675.88  4951.5 1665.02  5008.2 1659.91
  5008.5 1659.41  5013.1 1659.91  5047.4 1662.56  5094.6 1661.31  5231.3 1663.49
  5289.6 1668.21  5301.2 1668.99  5353.3 1679.68    5382 1682.93  5405.3 1687.62
  5422.6 1693.95  5444.5 1697.59  5475.2 1705.27  5542.9 1709.75  5599.9 1715.44
  5612.5 1716.35  5753.5 1726.36  5794.3 1730.92  5838.1 1738.59  5892.9 1745.01
#Mann= 7 ,-1 , 0
    4549     .07       0  5008.2     .05       0  5013.1     .07       0
  5047.4     .12       0  5289.6     .07       0  5599.9    .035       0
  5612.5     .07       0
Bank Sta=5008.2,5013.1
XS Rating Curve= 0 ,0
Exp/Cntr=0.3,0.1

Type RM Length L Ch R = 1 ,5021    ,465,465,465
BEGIN DESCRIPTION:
Stream0116_DS 11.0
END DESCRIPTION:
XS GIS Cut Line= 3
      2014775.03     13943525.01        2014375.       13943325.
      2014025.04       13943325.
#Sta/Elev= 30
  4552.8 1709.68  4619.9 1697.91  4642.3 1693.12  4650.7  1688.3  4656.2 1686.31
    4673 1676.68  4678.6 1675.48  4695.4 1667.23  4717.7 1661.83  4762.5 1657.34
  4790.4 1657.75  4798.8 1656.78  4812.8 1656.74  4829.5 1657.56  4888.2 1656.85
  4946.9 1657.16  4955.3 1655.97  4994.6 1654.25    4995 1653.75  4999.8 1654.25
    5050 1657.26    5090 1660.78  5143.2  1667.5    5180 1672.71  5241.8 1684.05
    5250 1686.22    5270 1693.62    5290 1696.39    5300 1699.35    5350  1707.6
#Mann= 5 ,-1 , 0
  4552.8     .12       0  4994.6     .05       0  4999.8     .12       0
  5143.2    .035       0  5241.8     .07       0
Bank Sta=4994.6,4999.8
XS Rating Curve= 0 ,0
Exp/Cntr=0.3,0.1

Type RM Length L Ch R = 1 ,4556    ,448,448,448
BEGIN DESCRIPTION:
Stream0116_DS 10.0
END DESCRIPTION:
XS GIS Cut Line= 3
      2014903.51     13943360.53        2014325.       13942875.
      2013542.35     13943117.45
#Sta/Elev= 30
  4240.6  1722.4  4390.5 1694.42  4399.4 1693.25  4442.3 1672.53  4456.6 1668.38
  4534.7 1655.94    4605 1650.35    4627 1653.46  4758.8 1650.76  4918.3 1651.11
  4941.8 1650.83  4998.5 1650.38  5012.2 1645.96  5027.3  1649.3  5056.1 1645.17
  5056.5 1644.67  5061.3 1645.17  5069.1 1649.76  5115.2  1656.8  5147.8 1675.31
    5238    1692  5353.9 1705.83  5452.3 1712.73  5496.3 1715.29    5499 1715.38
  5613.5 1723.83  5704.8 1736.22    5804 1747.29    5809 1748.42  5815.2 1748.92
#Mann= 14 ,-1 , 0
  4240.6     .07       0  4390.5     .12       0  4758.8     .07       0
  4918.3     .12       0  4941.8     .07       0  5056.1     .05       0
  5061.3     .07       0    5238    .035       0  5452.3     .07       0
  5496.3    .035       0    5499     .07       0  5704.8    .035       0
    5804     .07       0    5809    .035       0
Bank Sta=5056.1,5061.3
XS Rating Curve= 0 ,0
Exp/Cntr=0.3,0.1

Type RM Length L Ch R = 1 ,4108    ,428,428,428
BEGIN DESCRIPTION:
Stream0116_DS 9.0
END DESCRIPTION:
XS GIS Cut Line= 3
      2014875.01       13942825.        2014475.       13942525.
      2013699.32     13941965.18
#Sta/Elev= 30
    4500 1680.47  4541.7 1672.72  4578.1 1662.97  4592.7 1663.15  4607.3    1659
  4707.3 1649.29  4821.9 1641.77    4950 1643.71  4963.5 1642.52  4975.4 1637.37
  4975.8 1636.87  4980.9 1637.37  5007.2 1640.86  5078.5 1649.59  5128.8 1658.14
  5179.1 1671.95  5214.7 1678.74  5285.9 1704.88  5386.5 1718.96  5436.8 1723.14
  5541.8 1739.53  5581.7 1741.59  5709.1 1742.16  5744.7 1745.49  5759.4 1744.07
    5795 1747.61  5809.7 1746.27  5830.6 1748.09  5916.5 1748.05  5956.6 1746.12
#Mann= 6 ,-1 , 0
    4500     .12       0  4975.4     .05       0  4980.9     .12       0
  5007.2     .07       0  5541.8    .035       0  5581.7     .07       0
Bank Sta=4975.4,4980.9
XS Rating Curve= 0 ,0
Exp/Cntr=0.3,0.1

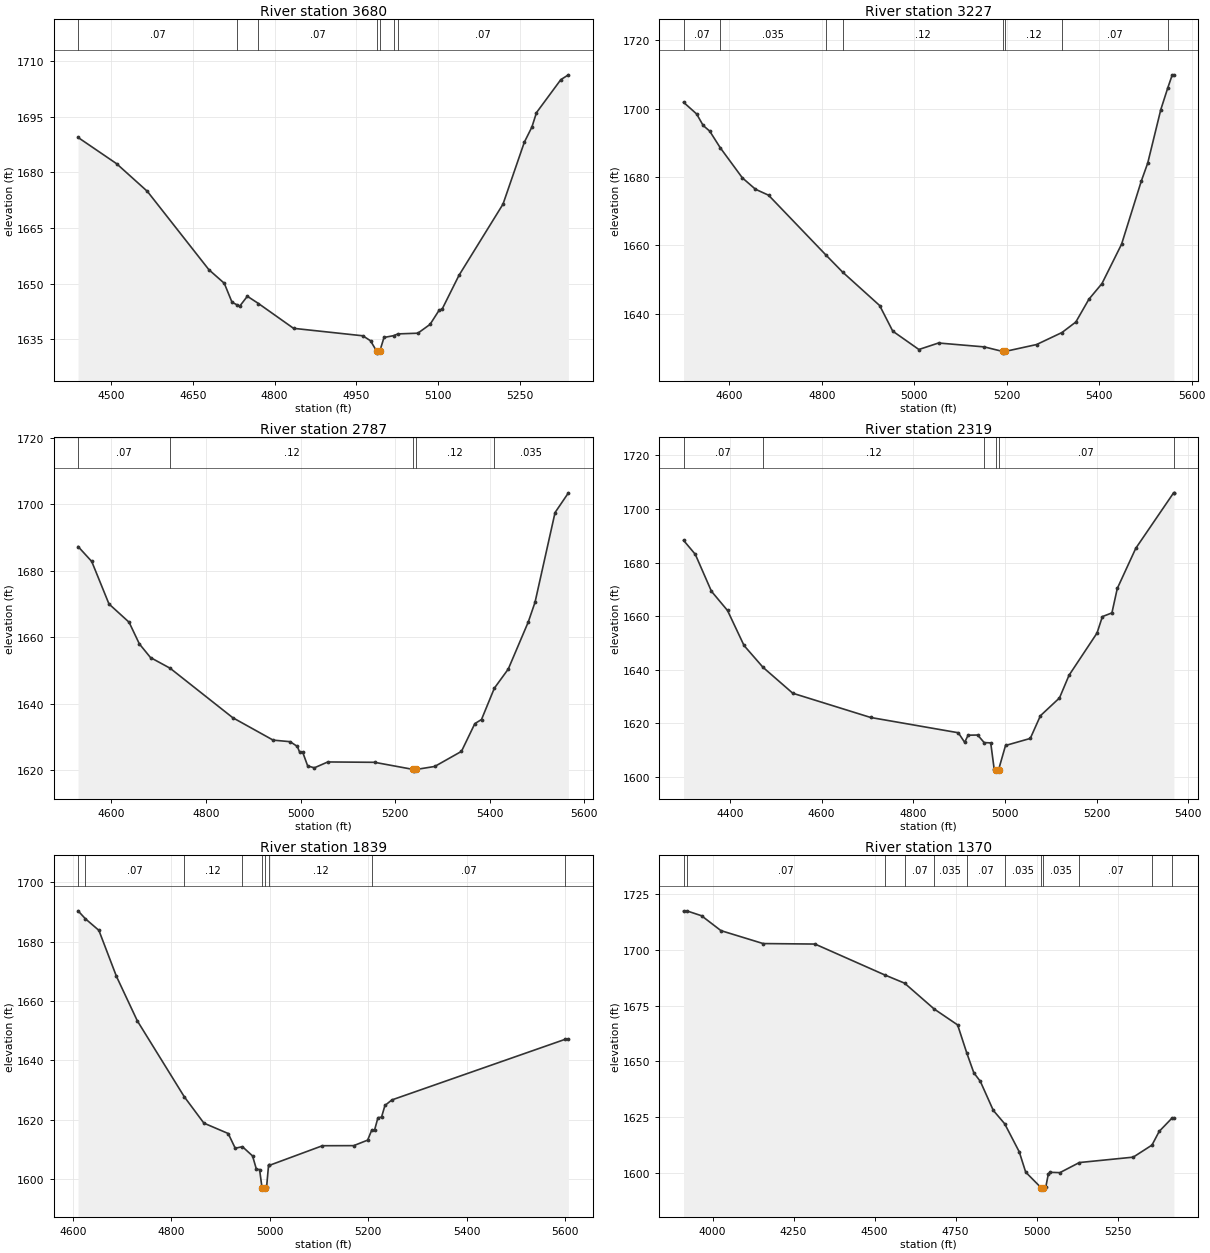
Type RM Length L Ch R = 1 ,3680    ,453,453,453
BEGIN DESCRIPTION:
Stream0116_DS 8.0
END DESCRIPTION:
XS GIS Cut Line= 3
      2015075.01     13942575.01        2014675.       13942175.
      2014375.01     13942025.01
#Sta/Elev= 30
  4438.8  1689.4  4509.5 1682.34  4566.1 1674.88  4679.2 1653.77  4707.5 1650.11
  4721.7    1645  4730.9  1644.3  4735.8 1643.93  4749.9 1646.61  4770.3 1644.66
  4834.8 1637.97  4962.1 1635.96  4976.2 1634.62  4987.6 1631.79    4988 1631.29
  4993.2 1631.79    5001 1635.51  5018.5 1635.99  5026.7 1636.47  5063.2 1636.66
  5085.6 1639.03  5102.3 1642.85  5107.9 1643.17  5138.7 1652.23  5219.7 1671.44
  5258.9 1688.13  5272.8 1692.21  5281.2 1696.09  5325.9 1704.97  5339.9 1706.27
#Mann= 7 ,-1 , 0
  4438.8     .07       0  4730.9     .12       0  4770.3     .07       0
  4987.6     .05       0  4993.2     .07       0  5018.5     .12       0
  5026.7     .07       0
Bank Sta=4987.6,4993.2
XS Rating Curve= 0 ,0
Exp/Cntr=0.3,0.1

Type RM Length L Ch R = 1 ,3227    ,440,440,440
BEGIN DESCRIPTION:
Stream0116_DS 7.0
END DESCRIPTION:
XS GIS Cut Line= 3
      2015375.02     13942325.02        2015025.       13941975.
      2014624.99     13941574.99
#Sta/Elev= 30
  4500.9 1701.85  4529.2 1698.43  4543.4 1695.06  4557.5 1693.42  4580.2 1688.58
  4628.2 1679.75  4656.5 1676.43  4684.8 1674.69  4808.7 1657.24  4845.1 1652.21
  4925.2 1642.44  4953.5 1634.96    5010  1629.6  5052.5  1631.5  5151.5 1630.36
    5191 1629.04  5191.5 1628.54  5196.7 1629.04  5264.6 1631.05  5319.5 1634.56
  5349.5 1637.63  5377.7 1644.28    5406 1648.86  5448.4 1660.36  5490.9 1678.73
    5505 1684.08  5533.3 1699.71  5548.4 1706.06  5558.1 1709.86  5561.6 1709.86
#Mann= 8 ,-1 , 0
  4500.9     .07       0  4580.2    .035       0  4808.7     .07       0
  4845.1     .12       0    5191     .05       0  5196.7     .12       0
  5319.5     .07       0  5548.4    .035       0
Bank Sta=5191,5196.7
XS Rating Curve= 0 ,0
Exp/Cntr=0.3,0.1

Type RM Length L Ch R = 1 ,2787    ,468,468,468
BEGIN DESCRIPTION:
Stream0116_DS 6.0
END DESCRIPTION:
XS GIS Cut Line= 3
        2015575.       13941875.        2015175.       13941625.
      2014774.99     13941224.99
#Sta/Elev= 30
  4529.3 1687.31  4558.2 1682.82  4594.7 1670.04  4637.2 1664.55    4659 1658.03
  4682.6 1653.92  4724.1 1650.71  4856.5 1635.85    4942  1629.1    4978 1628.63
  4993.3 1627.19    4998 1625.48  5004.5 1625.48  5015.1 1621.33  5029.3 1620.78
  5057.6 1622.54  5156.6 1622.43  5238.6 1620.28    5239 1619.78  5244.3 1620.28
  5283.8 1621.18  5340.4 1625.72  5368.7 1634.06  5382.8  1635.3    5410 1644.72
  5439.4 1650.46  5481.8 1664.64    5496 1670.53  5538.4 1697.52  5566.7 1703.45
#Mann= 5 ,-1 , 0
  4529.3     .07       0  4724.1     .12       0  5238.6     .05       0
  5244.3     .12       0    5410    .035       0
Bank Sta=5238.6,5244.3
XS Rating Curve= 0 ,0
Exp/Cntr=0.3,0.1

Type RM Length L Ch R = 1 ,2319    ,480,480,480
BEGIN DESCRIPTION:
Stream0116_DS 5.0
END DESCRIPTION:
XS GIS Cut Line= 3
       2015639.6     13941756.34        2015175.       13941225.
      2014825.02     13941125.01
#Sta/Elev= 30
  4298.8 1688.29  4324.5 1683.06  4359.7 1669.28  4394.8  1662.1  4430.8 1649.04
  4472.2  1640.9  4537.2 1631.22  4707.1 1622.18  4898.3 1616.48  4912.1  1612.9
  4919.7 1615.57  4940.5 1615.63  4954.7 1612.81    4969  1612.7  4976.6 1602.81
  4980.4 1602.66  4980.9 1602.16  4986.1 1602.66  5001.3 1611.73  5055.3 1614.36
  5077.4 1622.83    5119 1629.47  5139.8 1637.92  5200.9 1653.69  5212.6 1659.82
  5233.4 1661.21  5245.1 1670.32  5285.4  1685.3    5368 1706.01  5368.6 1706.01
#Mann= 6 ,-1 , 0
  4298.8     .07       0  4472.2     .12       0  4954.7     .07       0
  4980.4     .05       0  4986.1     .07       0    5368    .035       0
Bank Sta=4980.4,4986.1
XS Rating Curve= 0 ,0
Exp/Cntr=0.3,0.1

Type RM Length L Ch R = 1 ,1839    ,469,469,469
BEGIN DESCRIPTION:
Stream0116_DS 4.0
END DESCRIPTION:
XS GIS Cut Line= 3
      2015874.99     13941524.98        2015625.       13941225.
      2015181.23     13940811.87
#Sta/Elev= 30
  4610.1 1690.41    4625 1687.73  4652.4 1683.83  4688.2 1668.28  4730.5 1653.32
  4825.8 1627.75  4865.9  1618.8  4915.3  1615.3  4929.6 1610.33  4944.2 1610.86
  4964.8 1607.74  4972.6 1603.26  4979.1 1603.14    4984 1597.04  4984.5 1596.54
  4989.8 1597.04  4993.4 1597.32  4997.3 1604.54  4998.7 1604.54  5106.9 1611.18
  5170.4 1611.21  5198.7 1613.06  5207.2  1616.5  5212.9 1616.52  5219.7 1620.63
    5227 1620.83  5233.9 1624.75    5248 1626.63  5600.4 1647.08  5606.9 1647.06
#Mann= 9 ,-1 , 0
  4610.1     .12       0    4625     .07       0  4825.8     .12       0
  4944.2     .07       0    4984     .05       0  4989.8     .07       0
  4998.7     .12       0  5207.2     .07       0  5600.4    .035       0
Bank Sta=4984,4989.8
XS Rating Curve= 0 ,0
Exp/Cntr=0.3,0.1

Type RM Length L Ch R = 1 ,1370    ,447,447,447
BEGIN DESCRIPTION:
Stream0116_DS 3.0
END DESCRIPTION:
XS GIS Cut Line= 3
      2016035.42     13942110.54        2016025.       13941025.
      2015624.99       13940875.
#Sta/Elev= 30
  3910.5  1717.3  3920.3 1717.51    3966 1715.31    4026 1708.63  4156.1 1702.84
  4316.1 1702.62    4531  1688.8  4592.4  1685.1  4683.8 1673.51  4756.1 1666.38
    4784 1653.96  4806.1 1644.92  4826.1  1641.1  4866.1 1628.09  4901.3 1622.08
  4946.1 1609.55  4966.1 1600.41  5014.5 1593.29    5015 1592.79  5020.3 1593.29
  5028.1 1593.72  5036.1  1599.7  5041.5 1600.32  5071.7 1600.18  5131.6  1604.7
  5297.8 1607.12  5355.7 1612.53  5377.9 1618.66  5416.6 1624.49  5423.3 1624.73
#Mann= 12 ,-1 , 0
  3910.5    .035       0  3920.3     .07       0    4531     .12       0
  4592.4     .07       0  4683.8    .035       0    4784     .07       0
  4901.3    .035       0  5014.5    .035       0  5020.3    .035       0
  5131.6     .07       0  5355.7    .035       0  5416.6     .07       0
Bank Sta=5014.5,5020.3
XS Rating Curve= 0 ,0
Exp/Cntr=0.3,0.1

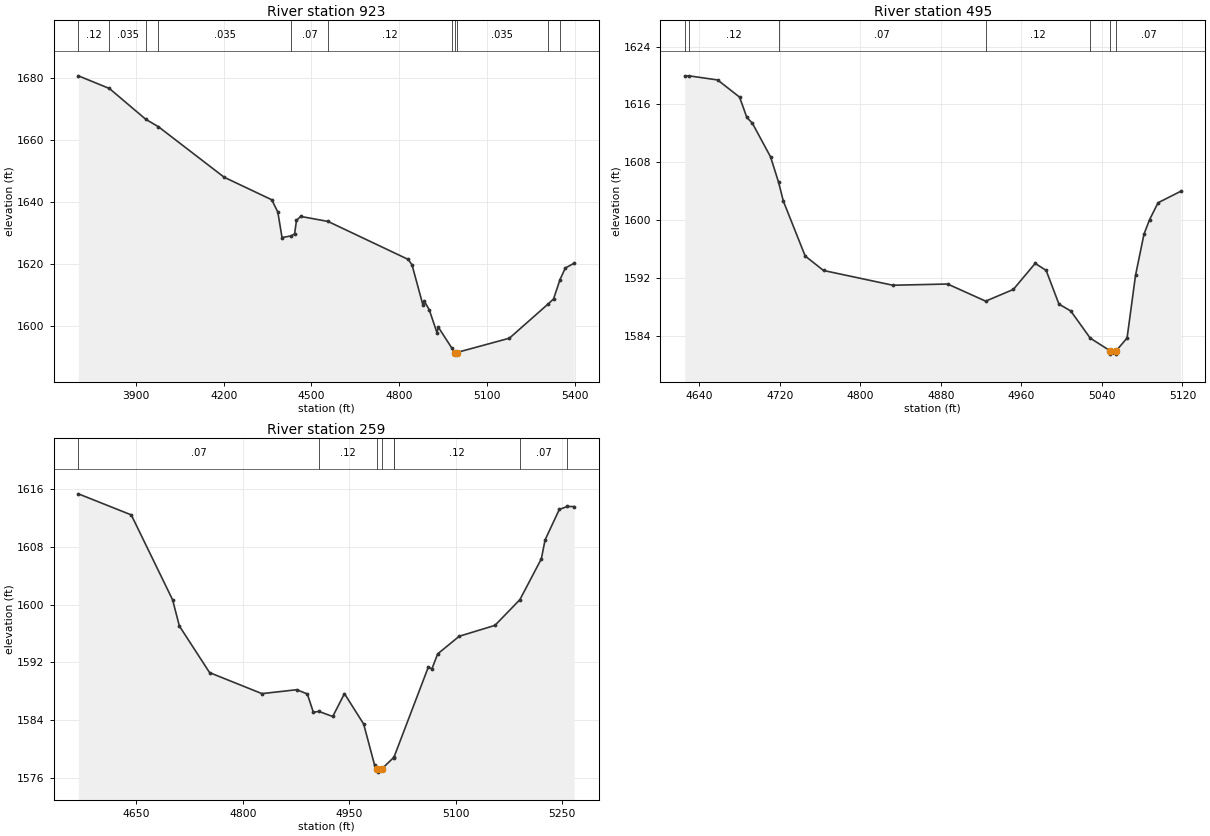
Type RM Length L Ch R = 1 ,923     ,428,428,428
BEGIN DESCRIPTION:
Stream0116_DS 2.0
END DESCRIPTION:
XS GIS Cut Line= 4
      2017139.57     13941311.88      2016400.01     13940700.78
        2016075.       13940625.      2015675.01       13940675.
#Sta/Elev= 30
  3702.4 1680.55  3808.6 1676.47  3933.3 1666.52  3976.5 1664.13  4201.3 1647.85
  4364.1 1640.58  4384.9  1636.6  4399.2  1628.4  4430.2 1628.92  4442.2 1629.56
  4448.7 1633.94  4463.1 1635.21  4556.6 1633.59  4831.2 1621.33    4844 1619.55
  4881.4 1606.58  4886.5 1607.81  4903.1 1605.06  4929.1 1597.77  4934.2 1599.46
    4979 1592.91  4989.6  1591.3  4990.1  1590.8  4996.2  1591.3  5176.9 1595.93
  5309.4 1606.96  5328.1 1608.59  5350.3 1614.86  5368.4 1618.58  5398.6 1620.12
#Mann= 11 ,-1 , 0
  3702.4     .12       0  3808.6    .035       0  3933.3     .07       0
  3976.5    .035       0  4430.2     .07       0  4556.6     .12       0
    4979    .035       0  4989.6    .035       0  4996.2    .035       0
  5309.4     .07       0  5350.3    .035       0
Bank Sta=4989.6,4996.2
XS Rating Curve= 0 ,0
Exp/Cntr=0.3,0.1

Type RM Length L Ch R = 1 ,495     ,236,236,236
BEGIN DESCRIPTION:
Stream0116_DS 1.0
END DESCRIPTION:
XS GIS Cut Line= 3
      2016274.96     13940424.98        2015925.       13940275.
      2015824.96     13940224.98
#Sta/Elev= 30
  4625.6 1619.94  4629.7 1619.95  4658.2 1619.38    4680 1617.01  4687.2 1614.21
  4692.7 1613.41  4710.8 1608.75  4718.7 1605.27  4723.5 1602.64  4745.2 1595.05
  4763.4 1593.05  4832.3 1591.01  4886.7 1591.18  4924.5 1588.81    4952 1590.43
  4973.7 1594.03  4984.6 1593.06  4997.3 1588.41  5009.1 1587.45  5028.4  1583.7
  5047.7 1581.99  5048.2 1581.49  5053.9 1581.49  5054.4 1581.99    5065 1583.72
  5073.4 1592.38  5081.8 1598.07  5087.4 1600.09  5095.8 1602.41  5118.2 1603.99
#Mann= 7 ,-1 , 0
  4625.6     .07       0  4629.7     .12       0  4718.7     .07       0
  4924.5     .12       0  5028.4     .07       0  5047.7     .05       0
  5054.4     .07       0
Bank Sta=5047.7,5054.4
XS Rating Curve= 0 ,0
Exp/Cntr=0.3,0.1

Type RM Length L Ch R = 1 ,259     ,0,0,0
BEGIN DESCRIPTION:
Stream0116_DS 0.0
END DESCRIPTION:
XS GIS Cut Line= 3
      2016358.09      13940286.1      2015989.03     13940061.95
       2015724.3      13940095.9
#Sta/Elev= 30
  4568.2 1615.36  4642.8 1612.44    4701 1600.68  4710.6 1597.04  4753.2 1590.58
  4826.9 1587.67    4876 1588.21  4890.9 1587.62  4899.4 1585.08    4907 1585.21
  4926.7  1584.5  4943.2 1587.67  4970.3 1583.45  4985.8 1577.72  4989.7 1577.29
  4990.2 1576.79  4996.4 1577.29  5012.5 1578.81  5013.3 1578.94  5061.4 1591.35
  5066.4 1591.09  5074.6 1593.18  5104.9 1595.62  5155.3 1597.13  5190.4 1600.69
  5220.7 1606.36  5225.9 1608.97    5246  1613.2  5257.4 1613.61  5266.9 1613.59
#Mann= 8 ,-1 , 0
  4568.2     .07       0    4907     .12       0  4989.7     .05       0
  4996.4     .12       0  5012.5     .07       0  5013.3     .12       0
  5190.4     .07       0  5257.4    .035       0
Bank Sta=4989.7,4996.4
XS Rating Curve= 0 ,0
Exp/Cntr=0.3,0.1

Chan Stop Cuts=-1
Use User Specified Reach Order=0
Composite Channel Slope=5