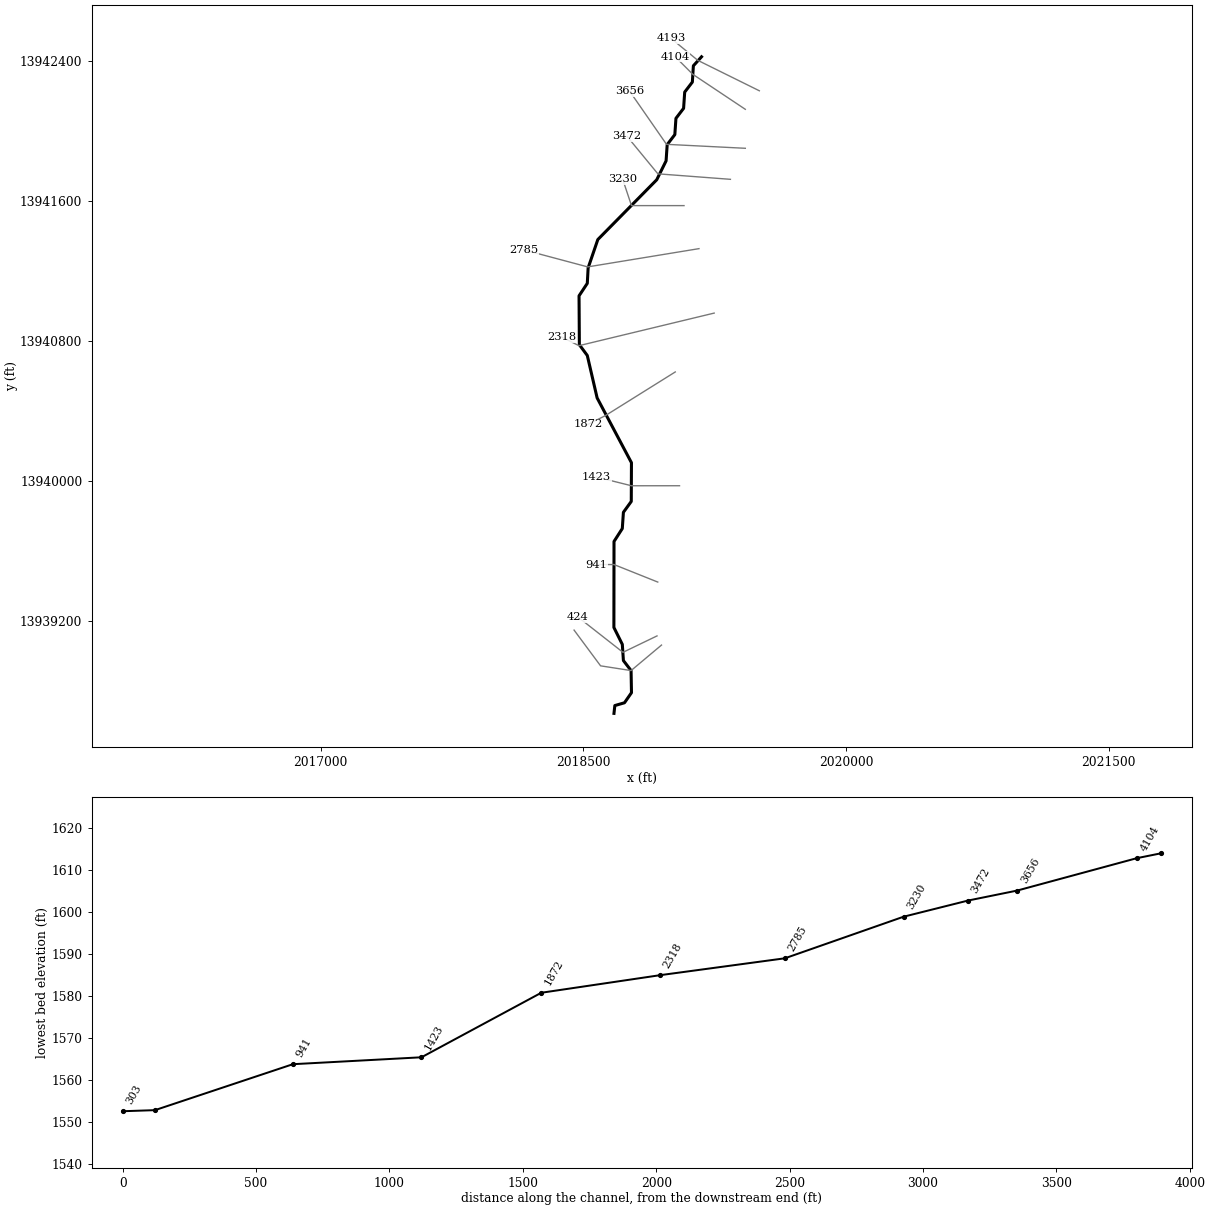
--- Stream0117_DS.prj (project) ---

Proj Title=Stream0117_DS Base Level Engineering
Current Plan=p01
Default Exp/Contr=0.3,0.1
English Units
Geom File=g01
Flow File=f01
Plan File=p01
Y Axis Title=Elevation
X Axis Title(PF)=Main Channel Distance
X Axis Title(XS)=Station
BEGIN DESCRIPTION:
Stream0117_DS
END DESCRIPTION:
DSS Export Rating Curves= 0
DSS Export Rating Curve Sorted= 0
DSS Export Volume Flow Curves= 0
DXF OffsetX= 0
DXF OffsetY= 0
DXF ScaleX= 1
DXF ScaleY= 10

--- Stream0117_DS.p01 (plan) ---

Plan Title=Multiple Run
Short Identifier=Multiple
Geom File=g01
Flow File=f01
Subcritical Flow
K Sum by GR= 0
Std Step Tol= 0.01
Critical Tol= 0.01
Num of Std Step Trials= 20
Max Error Tol= 0.3
Flow Tol Ratio= 0.001
Split Flow NTrial= 30
Split Flow Tol= 0.02
Split Flow Ratio= 0.02
Log Output Level= 0
Friction Slope Method= 1
Unsteady Friction Slope Method= 2
Unsteady Bridges Friction Slope Method= 1
Parabolic Critical Depth
Global Vel Dist=  1 , 1 , 1
Global Log Level= 0
CheckData=True
Encroach Param= -1, 0, 0, 0
BEGIN DESCRIPTION:
Multiple Run
END DESCRIPTION:

--- Stream0117_DS.f01 (steady flow) ---

Flow Title=Multiple
Number of Profiles=7
Profile Names=10-year,25-year,50-year,1pct_min,100-year,1pct_plu,500-year
River Rch & RM= Stream0117_DS,Reach-1,4193
     855    1460    2040    1386    2765    5518    5036
River Rch & RM= Stream0117_DS,Reach-1,2785
    1622    2870    4107    2848    5683   11339   10804
Boundary for River Rch & Prof#=Stream0117_DS,Reach-1,1
Up Type=0
Dn Type=3
Dn Slope=0.005
Boundary for River Rch & Prof#=Stream0117_DS,Reach-1,2
Up Type=0
Dn Type=3
Dn Slope=0.005
Boundary for River Rch & Prof#=Stream0117_DS,Reach-1,3
Up Type=0
Dn Type=3
Dn Slope=0.005
Boundary for River Rch & Prof#=Stream0117_DS,Reach-1,4
Up Type=0
Dn Type=3
Dn Slope=0.005
Boundary for River Rch & Prof#=Stream0117_DS,Reach-1,5
Up Type=0
Dn Type=3
Dn Slope=0.005
Boundary for River Rch & Prof#=Stream0117_DS,Reach-1,6
Up Type=0
Dn Type=3
Dn Slope=0.005
Boundary for River Rch & Prof#=Stream0117_DS,Reach-1,7
Up Type=0
Dn Type=3
Dn Slope=0.005

--- Stream0117_DS.g01 (geometry) ---

Geom Title=Existing Conditions
Program Version=4.10

River Reach=Stream0117_DS   ,Reach-1
Reach XY= 30
        2019175.       13942425.      2019128.39      13942373.6
      2019122.56     13942280.55      2019078.85      13942223.4
      2019072.53     13942130.57      2019028.85      13942073.4
      2019022.53     13941980.57      2018978.85      13941923.4
      2018972.56     13941830.56      2018919.17      13941722.7
      2018582.79      13941381.2      2018527.47     13941219.43
      2018522.64     13941130.98      2018475.52     13941059.78
      2018477.38     13940780.53      2018522.64     13940719.02
      2018578.83     13940476.58       2018774.8     13940106.74
      2018773.78      13939885.5      2018728.86      13939823.4
      2018722.53     13939730.57      2018675.21     13939656.73
      2018674.55     13939165.72      2018722.64     13939069.02
      2018728.86      13938976.6      2018772.63     13938919.47
      2018774.97     13938793.12      2018734.96     13938735.54
      2018679.96     13938719.65        2018675.       13938675.

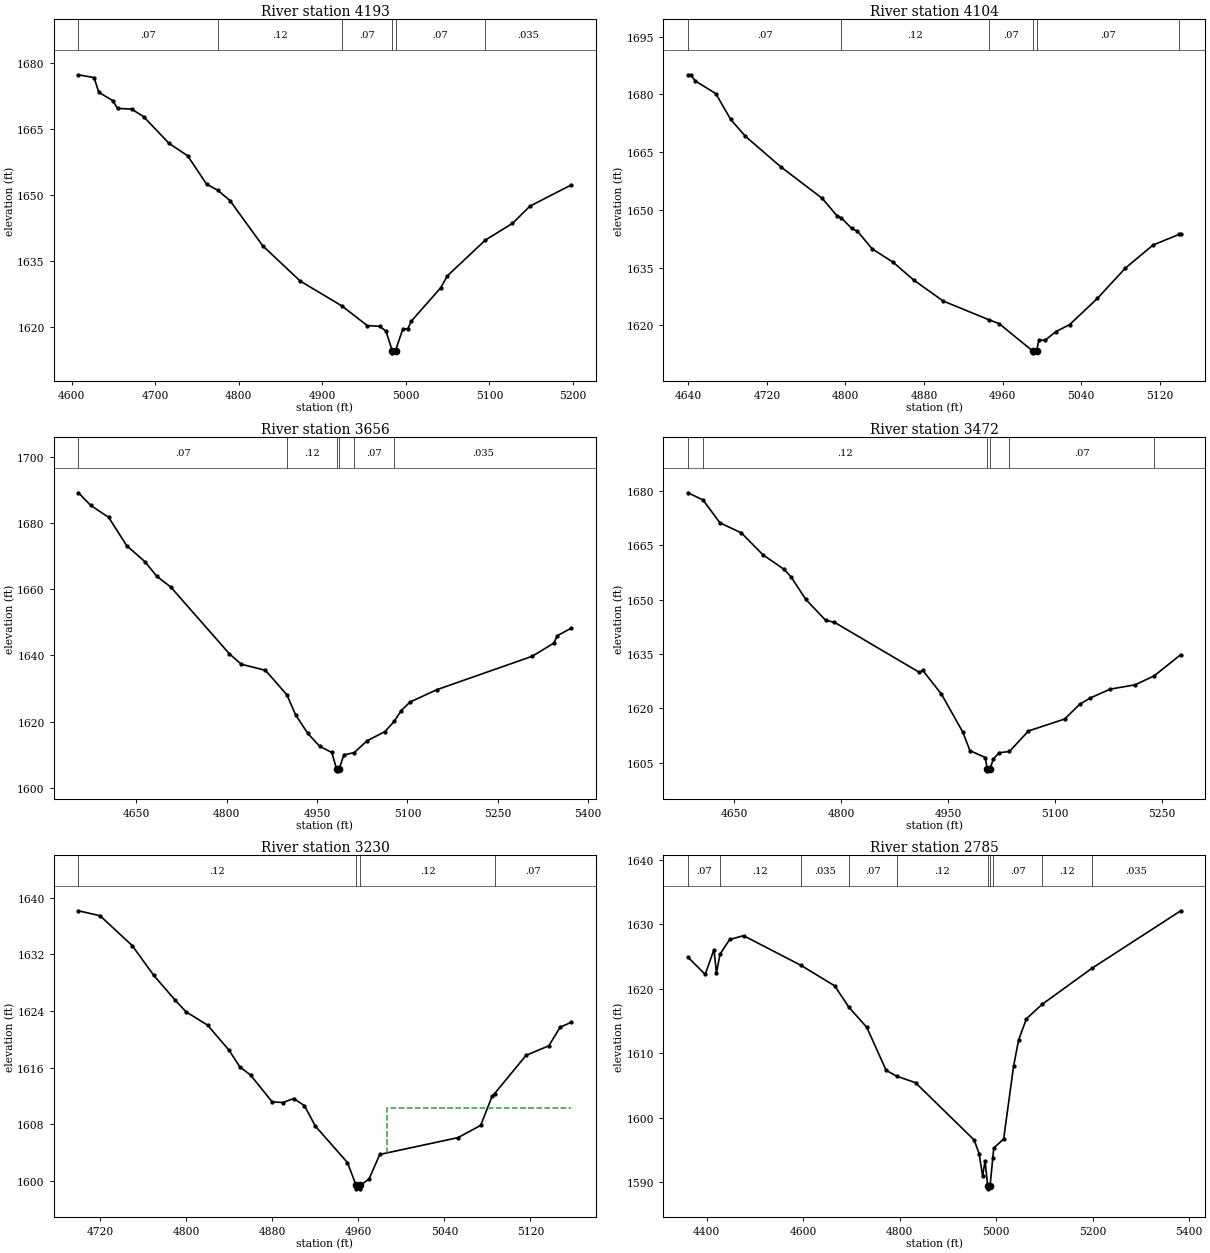
Type RM Length L Ch R = 1 ,4193    ,89,89,89
BEGIN DESCRIPTION:
Stream0117_DS 10.0
END DESCRIPTION:
XS GIS Cut Line= 3
      2019504.99     13942230.85      2019153.63     13942404.67
       2019000.4     13942530.39
#Sta/Elev= 30
    4608 1677.38  4626.7 1676.73  4632.3 1673.37  4649.1  1671.5  4654.7 1669.71
  4671.5 1669.57  4686.1 1667.82  4716.4 1661.75  4738.8 1658.91  4761.3 1652.46
  4774.9 1651.05  4789.3 1648.73  4828.6 1638.41  4873.4 1630.39  4923.2 1624.73
  4953.8 1620.23  4968.7 1620.06  4976.2 1618.96  4983.6 1614.52  4983.9 1614.02
  4987.6 1614.52  4996.4  1619.5  5002.3  1619.5  5006.5 1621.24  5041.7 1628.84
  5049.6 1631.55  5095.1  1639.7  5127.6 1643.51  5148.6 1647.45  5198.2  1652.3
#Mann= 6 ,-1 , 0
    4608     .07       0  4774.9     .12       0  4923.2     .07       0
  4983.6     .05       0  4987.6     .07       0  5095.1    .035       0
Bank Sta=4983.6,4987.6
XS Rating Curve= 0 ,0
Exp/Cntr=0.3,0.1

Type RM Length L Ch R = 1 ,4104    ,448,448,448
BEGIN DESCRIPTION:
Stream0117_DS 9.0
END DESCRIPTION:
XS GIS Cut Line= 3
      2019424.96     13942125.02        2019125.       13942325.
      2019025.02     13942424.98
#Sta/Elev= 30
  4639.6 1685.11  4642.6 1685.11  4647.1 1683.53  4668.1  1680.2  4683.1 1673.55
  4698.1 1669.15  4734.2  1661.2  4776.3 1653.03  4791.3 1648.53  4795.8 1647.94
  4806.3 1645.23  4812.3 1644.46  4827.3 1639.88  4848.4 1636.45  4869.4 1631.82
  4899.5 1626.35  4946.2 1621.46  4956.5 1620.48  4990.6 1613.38  4990.8 1612.88
  4994.6 1613.38  4997.1 1616.18  5003.6 1616.18  5014.3 1618.39  5028.4 1620.22
  5056.7 1627.05    5085 1634.87  5113.2 1640.87  5139.9 1643.66  5141.5 1643.66
#Mann= 6 ,-1 , 0
  4639.6     .07       0  4795.8     .12       0  4946.2     .07       0
  4990.6     .05       0  4994.6     .07       0  5139.9    .035       0
Bank Sta=4990.6,4994.6
XS Rating Curve= 0 ,0
Exp/Cntr=0.3,0.1

Type RM Length L Ch R = 1 ,3656    ,184,184,184
BEGIN DESCRIPTION:
Stream0117_DS 8.0
END DESCRIPTION:
XS GIS Cut Line= 3
      2019424.98     13941902.41        2018975.       13941925.
      2018765.42     13942227.07
#Sta/Elev= 30
    4554  1689.1    4574 1685.33    4604 1681.69  4634.1 1673.12  4664.1 1668.33
  4684.1 1663.87  4707.3 1660.62  4804.3 1640.52  4824.3 1637.34  4864.4  1635.5
    4900 1628.09  4914.4 1622.07  4934.5 1616.49  4954.5 1612.55  4974.5  1610.7
  4982.5 1605.66  4982.8 1605.16  4986.5 1605.66  4994.5 1609.97  5011.8 1610.67
  5032.9 1614.22  5062.6    1617  5078.3 1620.14  5089.7 1623.36  5104.5 1625.94
  5149.1 1629.67  5307.1 1639.74  5342.9  1643.7    5349 1645.96  5372.2 1648.27
#Mann= 6 ,-1 , 0
    4554     .07       0    4900     .12       0  4982.5     .05       0
  4986.5     .12       0  5011.8     .07       0  5078.3    .035       0
Bank Sta=4982.5,4986.5
XS Rating Curve= 0 ,0
Exp/Cntr=0.3,0.1

Type RM Length L Ch R = 1 ,3472    ,242,242,242
BEGIN DESCRIPTION:
Stream0117_DS 7.5
END DESCRIPTION:
XS GIS Cut Line= 3
      2019339.89     13941725.16      2018925.67     13941756.54
      2018750.04      13941970.1
#Sta/Elev= 30
  4584.6 1679.49  4605.8 1677.52  4629.6 1671.21  4659.7 1668.42  4689.8 1662.41
  4719.9 1658.33  4729.9 1656.16    4750 1650.11  4778.1 1644.29  4790.1 1643.79
  4909.4 1629.97  4914.4 1630.48  4940.5 1623.96  4970.6 1613.44  4980.6 1608.34
  5002.2 1606.45  5004.7 1603.28    5005 1602.78  5008.7 1603.28  5013.2 1605.95
  5021.1 1607.75    5036 1608.13  5062.7 1613.78  5113.6 1617.08  5134.4  1621.1
  5148.8 1622.82  5177.5 1625.32  5212.6 1626.52  5239.2 1628.99  5276.5 1634.84
#Mann= 6 ,-1 , 0
  4584.6     .07       0  4605.8     .12       0  5004.7     .05       0
  5008.7     .12       0    5036     .07       0  5239.2    .035       0
Bank Sta=5004.7,5008.7
XS Rating Curve= 0 ,0
Exp/Cntr=0.3,0.1

Type RM Length L Ch R = 1 ,3230    ,445,445,445
BEGIN DESCRIPTION:
Stream0117_DS 7.0
END DESCRIPTION:
XS GIS Cut Line= 3
      2019075.02       13941575.        2018775.       13941575.
      2018725.01     13941724.96
#Sta/Elev= 30
    4700 1638.13    4720 1637.43    4750 1633.21    4770 1629.01    4790  1625.5
    4800 1623.88    4820    1622    4840 1618.45    4850 1616.11    4860 1614.95
    4880 1611.18    4890 1611.09    4900 1611.65    4910 1610.66    4920 1607.79
    4950 1602.62    4958 1599.42  4958.3 1598.92  4961.8 1598.92    4962 1599.42
    4970 1600.29    4980 1603.77  5052.7 1606.14  5073.8 1607.87  5084.4 1611.98
  5086.7 1612.35    5116 1617.75  5137.1 1619.09  5147.6  1621.7  5158.1 1622.42
#Mann= 4 ,-1 , 0
    4700     .12       0    4958     .05       0    4962     .12       0
  5086.7     .07       0
#XS Ineff= 2 , 0
       0                 4987.08       0 1610.33
Permanent Ineff=
       F       F
Bank Sta=4958,4962
XS Rating Curve= 0 ,0
Exp/Cntr=0.3,0.1

Type RM Length L Ch R = 1 ,2785    ,467,467,467
BEGIN DESCRIPTION:
Stream0117_DS 6.0
END DESCRIPTION:
XS GIS Cut Line= 3
      2019160.44     13941329.26        2018525.       13941225.
       2018160.4     13941322.32
#Sta/Elev= 30
  4361.2 1624.92  4397.1 1622.24  4415.3 1626.09  4420.4 1622.46  4427.8 1625.37
  4447.8 1627.65  4476.6 1628.24  4595.3 1623.65  4665.5 1620.46  4694.7 1617.16
  4731.9 1614.04  4772.1 1607.36  4794.1 1606.46  4832.9 1605.45  4954.5 1596.56
  4964.6 1594.46    4972 1590.98    4977 1593.36  4982.3  1589.5  4982.7    1589
  4987.4  1589.5  4992.9 1593.71    4995 1595.32  5015.5 1596.74  5036.2 1608.07
  5046.5 1612.07  5062.7 1615.37  5095.4 1617.61  5198.3 1623.18  5382.5  1632.1
#Mann= 10 ,-1 , 0
  4361.2     .07       0  4427.8     .12       0  4595.3    .035       0
  4694.7     .07       0  4794.1     .12       0  4982.3     .05       0
  4987.4     .12       0  4992.9     .07       0  5095.4     .12       0
  5198.3    .035       0
Bank Sta=4982.3,4987.4
XS Rating Curve= 0 ,0
Exp/Cntr=0.3,0.1

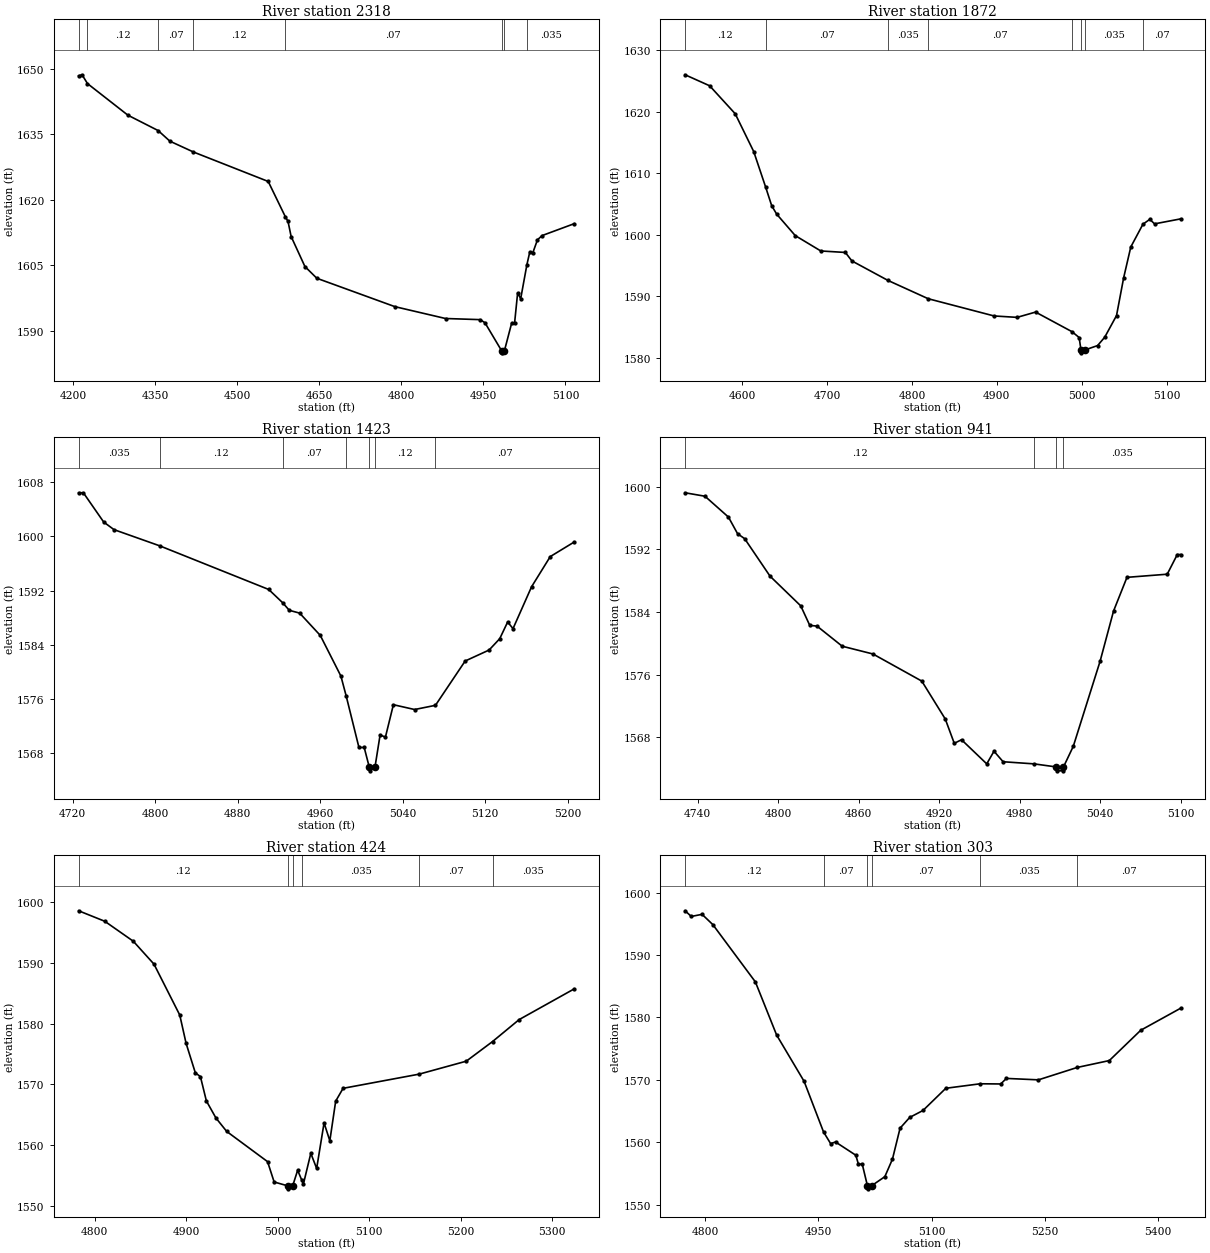
Type RM Length L Ch R = 1 ,2318    ,446,446,446
BEGIN DESCRIPTION:
Stream0117_DS 5.0
END DESCRIPTION:
XS GIS Cut Line= 3
      2019247.26     13940961.21        2018475.       13940775.
      2018374.99       13940825.
#Sta/Elev= 30
  4209.8 1648.39  4216.1 1648.63    4226 1646.61  4299.9 1639.38  4355.2 1635.86
  4376.7 1633.43  4419.8 1630.95  4556.5 1624.21  4587.7 1616.16  4592.7 1615.07
  4598.4 1611.61  4623.6 1604.74  4645.4 1602.05  4788.2 1595.55  4880.7 1592.84
  4943.9 1592.58  4952.8 1591.88  4983.2 1585.48  4983.6 1584.98  4988.5 1585.48
  5001.6 1591.75    5007 1591.75  5012.6 1598.69  5018.2 1597.37  5029.6 1605.19
  5034.9 1608.11  5040.5 1607.93  5048.9 1610.86  5057.3 1611.82    5116 1614.54
#Mann= 8 ,-1 , 0
  4209.8     .07       0    4226     .12       0  4355.2     .07       0
  4419.8     .12       0  4587.7     .07       0  4983.2     .05       0
  4988.5     .07       0  5029.6    .035       0
Bank Sta=4983.2,4988.5
XS Rating Curve= 0 ,0
Exp/Cntr=0.3,0.1

Type RM Length L Ch R = 1 ,1872    ,449,449,449
BEGIN DESCRIPTION:
Stream0117_DS 4.0
END DESCRIPTION:
XS GIS Cut Line= 3
      2019025.01     13940625.01        2018625.       13940375.
      2018525.01     13940325.01
#Sta/Elev= 30
  4532.9 1626.01  4561.8 1624.22  4591.9 1619.67  4613.7 1613.52  4627.7 1607.76
  4634.9  1604.7  4640.8 1603.33  4662.6 1599.85  4692.7 1597.35  4721.6 1597.11
  4729.3 1595.73  4771.9 1592.55  4819.2 1589.58  4896.7 1586.78  4923.8 1586.55
  4945.6 1587.41  4988.5 1584.22  4996.9 1583.27    4999 1581.28  4999.4 1580.78
  5004.3 1581.28  5018.6 1581.96    5027 1583.32  5040.9 1586.84  5049.3 1592.99
  5057.7    1598    5072  1601.7  5080.1  1602.5  5085.7 1601.76  5116.4 1602.57
#Mann= 8 ,-1 , 0
  4532.9     .12       0  4627.7     .07       0  4771.9    .035       0
  4819.2     .07       0  4988.5    .035       0    4999    .035       0
  5004.3    .035       0    5072     .07       0
Bank Sta=4999,5004.3
XS Rating Curve= 0 ,0
Exp/Cntr=0.3,0.1

Type RM Length L Ch R = 1 ,1423    ,482,482,482
BEGIN DESCRIPTION:
Stream0117_DS 3.0
END DESCRIPTION:
XS GIS Cut Line= 3
       2019049.3     13939975.09        2018775.       13939975.
      2018574.96     13940025.01
#Sta/Elev= 30
  4725.8 1606.43  4730.4 1606.43  4750.1 1602.11  4760.1 1600.99  4804.4  1598.6
  4910.1 1592.16  4923.5 1590.22  4930.1 1589.08  4940.1 1588.67  4960.1 1585.38
  4980.1 1579.38  4985.2 1576.46  4997.6 1568.84  5002.7 1568.84  5007.7 1565.89
  5008.2 1565.39  5013.1 1565.89  5018.1 1570.67  5023.3 1570.38    5031 1575.15
  5051.6 1574.44  5071.8 1575.06  5100.6  1581.6  5123.8 1583.22  5134.1 1584.89
  5141.8 1587.36    5147 1586.38    5165 1592.56  5183.1 1597.01  5206.3 1599.16
#Mann= 7 ,-1 , 0
  4725.8    .035       0  4804.4     .12       0  4923.5     .07       0
  4985.2     .12       0  5007.7     .05       0  5013.1     .12       0
  5071.8     .07       0
Bank Sta=5007.7,5013.1
XS Rating Curve= 0 ,0
Exp/Cntr=0.3,0.1

Type RM Length L Ch R = 1 ,941     ,517,517,517
BEGIN DESCRIPTION:
Stream0117_DS 2.0
END DESCRIPTION:
XS GIS Cut Line= 3
      2018925.01       13939425.        2018675.       13939525.
      2018574.97       13939525.
#Sta/Elev= 30
  4730.7 1599.22  4745.5 1598.78    4763 1596.12  4769.8    1594  4775.1 1593.36
    4794 1588.58  4816.9 1584.79  4823.6  1582.3    4829 1582.21  4847.8 1579.64
  4870.7 1578.65  4907.1 1575.19  4924.6 1570.35  4931.3 1567.25  4936.7 1567.71
  4955.5 1564.63  4960.9 1566.24  4967.7  1564.9  4990.7 1564.63  5007.2 1564.24
  5007.7 1563.74  5012.3 1563.74  5012.7 1564.24    5020 1566.87    5040 1577.74
    5050 1584.13    5060 1588.43    5090 1588.83  5097.5 1591.34    5100 1591.34
#Mann= 4 ,-1 , 0
  4730.7     .12       0  4990.7    .035       0  5007.2    .035       0
  5012.7    .035       0
Bank Sta=5007.2,5012.7
XS Rating Curve= 0 ,0
Exp/Cntr=0.3,0.1

Type RM Length L Ch R = 1 ,424     ,121,121,121
BEGIN DESCRIPTION:
Stream0117_DS 1.0
END DESCRIPTION:
XS GIS Cut Line= 3
       2018920.8     13939117.43       2018726.4      13939023.7
      2018469.76     13939224.85
#Sta/Elev= 30
  4782.4 1598.59    4811 1596.86  4842.2 1593.57  4864.8  1589.8    4893 1581.41
  4899.9 1576.76    4910  1571.9  4915.6 1571.26  4922.1 1567.26  4932.6 1564.44
  4944.3 1562.24    4989 1557.26  4996.2 1553.91  5010.9 1553.28  5011.4 1552.78
  5016.5 1553.28  5021.9 1555.84  5026.5 1554.18  5028.2 1553.57  5036.3 1558.63
  5042.7 1556.14  5050.8 1563.65  5057.1 1560.69  5063.5 1567.23  5071.6 1569.34
  5154.9 1571.68  5206.3 1573.81    5235 1577.04  5264.1 1580.66  5324.3 1585.72
#Mann= 6 ,-1 , 0
  4782.4     .12       0  5010.9     .05       0  5016.5     .12       0
  5026.5    .035       0  5154.9     .07       0    5235    .035       0
Bank Sta=5010.9,5016.5
XS Rating Curve= 0 ,0
Exp/Cntr=0.3,0.1

Type RM Length L Ch R = 1 ,303     ,0,0,0
BEGIN DESCRIPTION:
Stream0117_DS 0.0
END DESCRIPTION:
XS GIS Cut Line= 4
      2018946.43     13939065.18      2018772.63     13938919.47
      2018598.45     13938946.53      2018447.12     13939150.69
#Sta/Elev= 30
  4773.2 1597.09  4781.4 1596.18  4795.7 1596.52    4810 1594.87  4866.4 1585.69
  4894.6 1577.17    4931 1569.76  4956.8 1561.64  4966.2 1559.77  4972.7 1560.03
  4999.6 1557.91  5003.1 1556.45  5008.1  1556.5    5015 1553.02  5015.5 1552.52
  5020.6 1553.02  5038.1 1554.47  5048.2 1557.28  5058.3 1562.24  5071.1 1563.97
  5088.7 1565.08    5119 1568.64  5164.6 1569.36  5191.8 1569.33  5199.3 1570.22
  5241.8 1569.99  5293.3 1571.98  5335.8 1573.08  5377.5 1577.94  5430.4 1581.47
#Mann= 6 ,-1 , 0
  4773.2     .12       0  4956.8     .07       0    5015     .05       0
  5020.6     .07       0  5164.6    .035       0  5293.3     .07       0
Bank Sta=5015,5020.6
XS Rating Curve= 0 ,0
Exp/Cntr=0.3,0.1

Chan Stop Cuts=-1
Use User Specified Reach Order=0
Composite Channel Slope=5