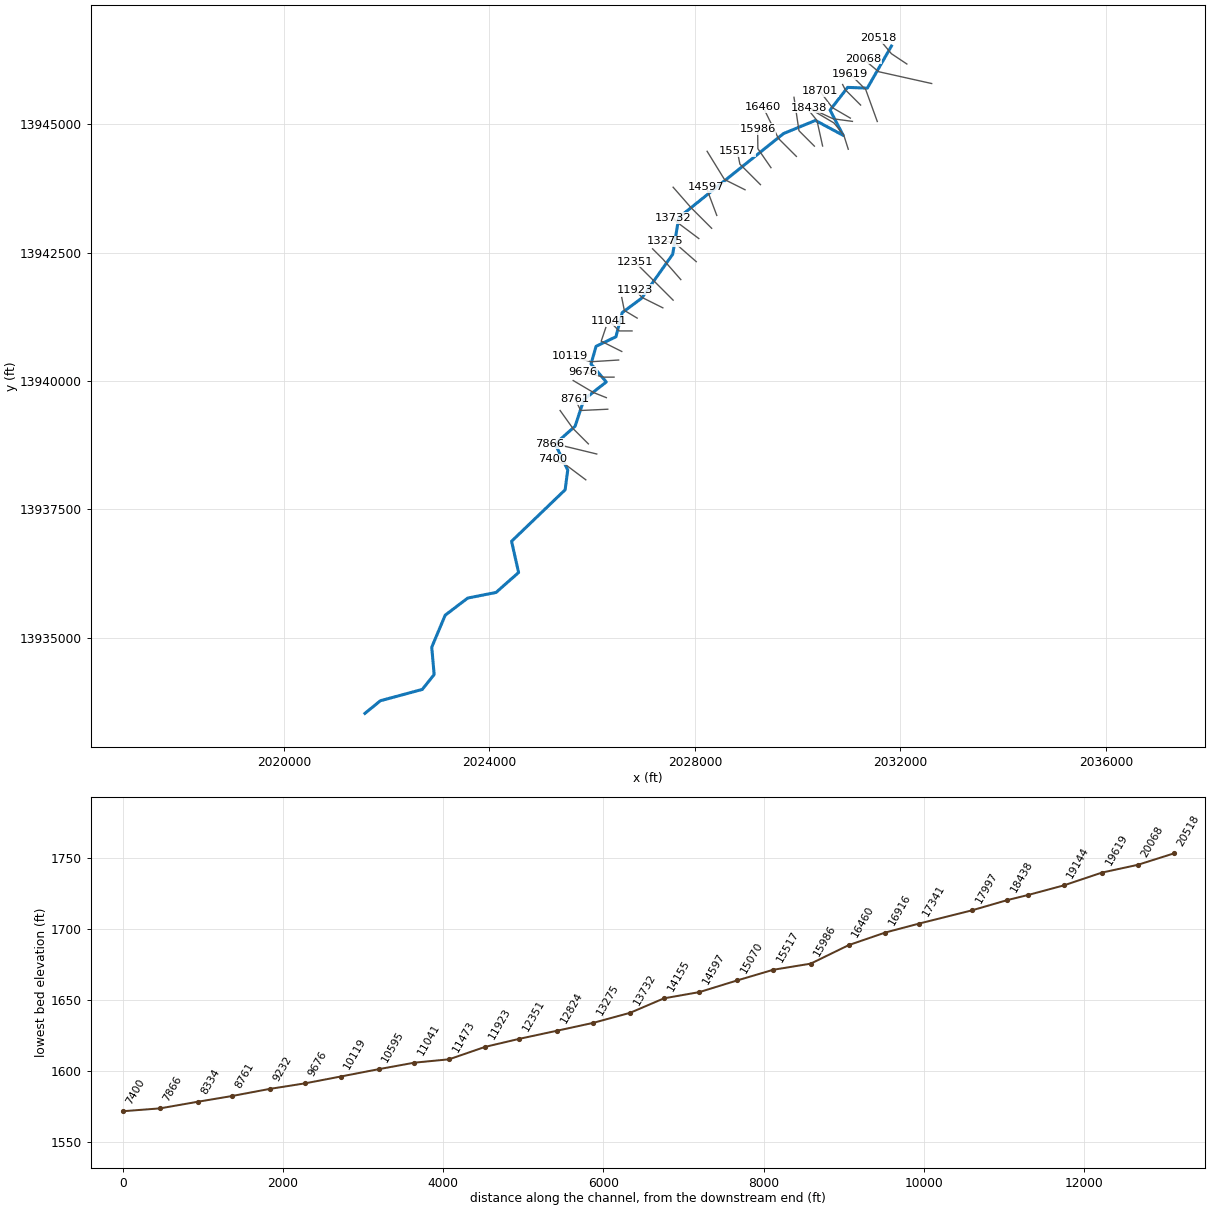
--- Stream0118_DS.prj (project) ---

Proj Title=Stream0118_DS Base Level Engineering
Current Plan=p01
Default Exp/Contr=0.3,0.1
English Units
Geom File=g01
Flow File=f01
Plan File=p01
Y Axis Title=Elevation
X Axis Title(PF)=Main Channel Distance
X Axis Title(XS)=Station
BEGIN DESCRIPTION:
Stream0118_DS
END DESCRIPTION:
DSS Export Rating Curves= 0
DSS Export Rating Curve Sorted= 0
DSS Export Volume Flow Curves= 0
DXF OffsetX= 0
DXF OffsetY= 0
DXF ScaleX= 1
DXF ScaleY= 10

--- Stream0118_DS.p01 (plan) ---

Plan Title=Multiple Run
Short Identifier=Multiple
Geom File=g01
Flow File=f01
Subcritical Flow
K Sum by GR= 0
Std Step Tol= 0.01
Critical Tol= 0.01
Num of Std Step Trials= 20
Max Error Tol= 0.3
Flow Tol Ratio= 0.001
Split Flow NTrial= 30
Split Flow Tol= 0.02
Split Flow Ratio= 0.02
Log Output Level= 0
Friction Slope Method= 1
Unsteady Friction Slope Method= 2
Unsteady Bridges Friction Slope Method= 1
Parabolic Critical Depth
Global Vel Dist=  1 , 1 , 1
Global Log Level= 0
CheckData=True
Encroach Param= -1, 0, 0, 0
BEGIN DESCRIPTION:
Multiple Run
END DESCRIPTION:

--- Stream0118_DS.f01 (steady flow) ---

Flow Title=Multiple
Number of Profiles=7
Profile Names=10-year,25-year,50-year,1pct_min,100-year,1pct_plu,500-year
River Rch & RM= Stream0118_DS,Reach-1,20518
    1021    1756    2466    1681    3354    6692    6152
River Rch & RM= Stream0118_DS,Reach-1,16460
    1386    2423    3439    2366    4722    9421    8831
River Rch & RM= Stream0118_DS,Reach-1,13275
    1583    2783    3963    2735    5456   10887   10265
River Rch & RM= Stream0118_DS,Reach-1,10119
    2060    3667    5268    3663    7308   14582   13967
River Rch & RM= Stream0118_DS,Reach-1,8334
    2974    5385    7826    5497   10969   21885   21403
River Rch & RM= Stream0118_DS,Reach-1,5578
    3256    5901    8578    6025   12021   23985   23450
Boundary for River Rch & Prof#=Stream0118_DS,Reach-1,1
Up Type=0
Dn Type=3
Dn Slope=0.005
Boundary for River Rch & Prof#=Stream0118_DS,Reach-1,2
Up Type=0
Dn Type=3
Dn Slope=0.005
Boundary for River Rch & Prof#=Stream0118_DS,Reach-1,3
Up Type=0
Dn Type=3
Dn Slope=0.005
Boundary for River Rch & Prof#=Stream0118_DS,Reach-1,4
Up Type=0
Dn Type=3
Dn Slope=0.005
Boundary for River Rch & Prof#=Stream0118_DS,Reach-1,5
Up Type=0
Dn Type=3
Dn Slope=0.005
Boundary for River Rch & Prof#=Stream0118_DS,Reach-1,6
Up Type=0
Dn Type=3
Dn Slope=0.005
Boundary for River Rch & Prof#=Stream0118_DS,Reach-1,7
Up Type=0
Dn Type=3
Dn Slope=0.005

--- Stream0118_DS.g01 (geometry) ---

Geom Title=Existing Conditions
Program Version=4.10

River Reach=Stream0118_DS   ,Reach-1
Reach XY= 30
        2031825.       13946525.      2031355.39      13945704.8
      2030972.57      13945719.6      2030630.41     13945277.42
      2030885.17     13944785.28      2030345.04     13945075.61
      2029722.57     13944819.48      2027685.52     13943184.79
        2027567.     13942468.62      2026961.63     13941611.68
      2026583.14     13941331.06      2026461.55     13940861.37
        2026075.       13940675.       2025976.8     13940331.11
      2026273.42     13939981.05      2025838.36     13939638.34
      2025666.86     13939118.94      2025278.12     13938773.37
      2025523.64     13938265.35      2025472.64     13937880.52
      2024430.09      13936877.3      2024566.86     13936268.94
      2024127.43     13935880.52      2023576.55     13935771.25
      2023138.62     13935438.22      2022876.22      13934814.5
      2022922.76     13934280.93      2022691.75     13933991.46
      2021876.58     13933771.17        2021575.       13933525.

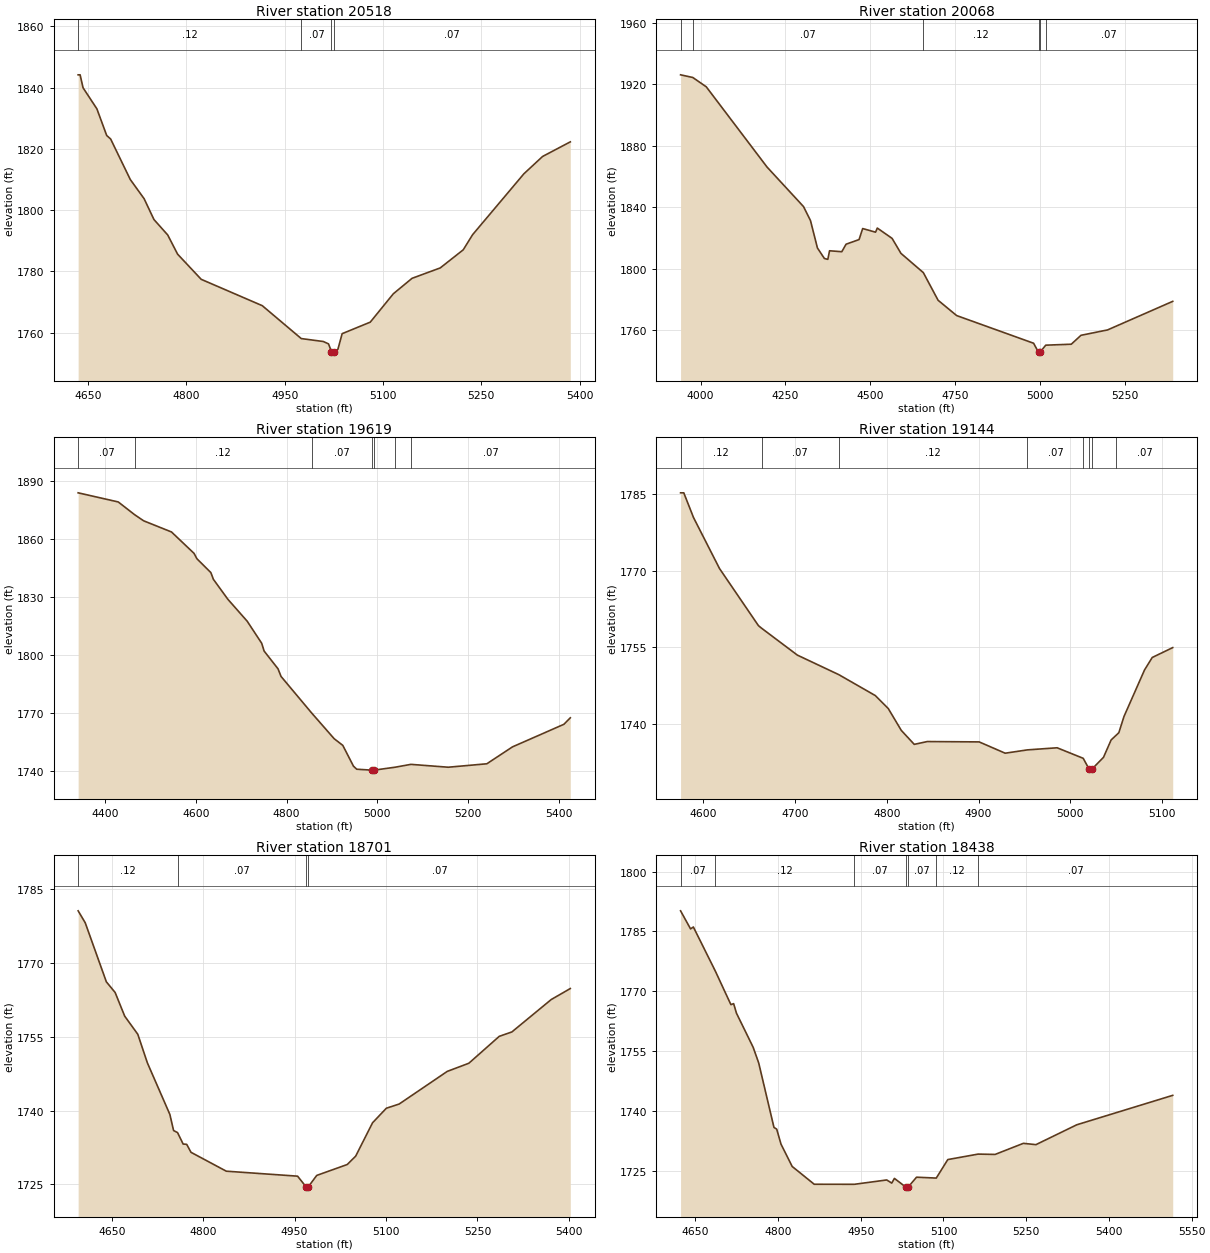
Type RM Length L Ch R = 1 ,20518   ,450,450,450
BEGIN DESCRIPTION:
Stream0118_DS 45.0
END DESCRIPTION:
XS GIS Cut Line= 3
      2032125.02     13946174.99        2031825.       13946375.
        2031575.     13946675.01
#Sta/Elev= 30
  4634.7 1844.15  4637.7 1844.15  4642.2 1839.92  4663.3 1833.05  4678.3 1824.34
  4684.3  1823.2  4714.3 1809.97  4735.4 1803.71  4750.4 1796.91  4771.4 1791.88
  4786.5 1785.61  4822.5  1777.4  4915.7  1768.8  4975.2 1758.06  5008.9  1757.1
  5016.8 1756.33  5021.3 1753.81  5021.5 1753.31  5025.3 1753.81  5031.1 1754.54
  5037.6 1759.66  5080.5 1763.42  5115.7 1772.68  5144.3 1777.73  5187.3 1781.12
  5222.4 1787.03  5236.7 1791.97  5314.9 1811.83  5343.5  1817.5  5385.8 1822.27
#Mann= 4 ,-1 , 0
  4634.7     .12       0  4975.2     .07       0  5021.3     .05       0
  5025.3     .07       0
Bank Sta=5021.3,5025.3
XS Rating Curve= 0 ,0
Exp/Cntr=0.3,0.1

Type RM Length L Ch R = 1 ,20068   ,449,449,449
BEGIN DESCRIPTION:
Stream0118_DS 44.0
END DESCRIPTION:
XS GIS Cut Line= 3
      2032608.32     13945794.54        2031575.       13946025.
      2031275.02     13946274.99
#Sta/Elev= 30
  3941.3 1926.05  3977.2 1924.33  4016.9 1918.28  4195.9 1866.15  4303.3 1840.47
  4323.8  1831.4  4344.3 1813.57  4364.8 1806.75  4374.9 1806.18    4380 1811.76
    4416 1811.14  4428.6 1816.02  4466.9 1819.04  4477.5 1826.19  4515.5 1823.84
  4520.6 1826.51  4564.1 1819.82  4590.2 1810.08  4656.1 1797.57  4699.6 1779.61
  4754.1 1769.68  4980.8 1751.69  4995.4 1745.77  4995.7 1745.27  4999.4 1745.77
  5016.6 1750.44  5091.8 1751.06  5120.4 1756.85  5198.5 1760.33  5390.5  1778.9
#Mann= 6 ,-1 , 0
  3941.3     .12       0  3977.2     .07       0  4656.1     .12       0
  4995.4     .05       0  4999.4     .12       0  5016.6     .07       0
Bank Sta=4995.4,4999.4
XS Rating Curve= 0 ,0
Exp/Cntr=0.3,0.1

Type RM Length L Ch R = 1 ,19619   ,475,475,475
BEGIN DESCRIPTION:
Stream0118_DS 43.0
END DESCRIPTION:
XS GIS Cut Line= 3
       2031549.3     13945054.98        2031325.       13945675.
        2031025.       13945975.
#Sta/Elev= 30
  4341.2  1883.8  4429.5 1879.08  4465.3 1872.53  4485.4 1869.32  4546.7 1863.55
  4596.4 1852.47  4602.7 1849.69  4633.4 1842.52    4639 1839.03  4670.9  1828.7
  4713.4 1817.36  4745.3 1805.96  4750.7  1801.9  4781.3 1792.73  4787.9 1788.79
    4855 1769.96  4904.8 1756.58  4923.9  1753.1  4947.4 1742.35  4954.6 1740.77
  4988.5 1740.28  4988.8 1739.78  4992.5 1740.28  5039.4 1741.82  5073.8 1743.28
  5156.1  1741.8    5241 1743.58  5297.5 1752.33  5410.7 1764.01  5424.8 1767.37
#Mann= 7 ,-1 , 0
  4341.2     .07       0  4465.3     .12       0    4855     .07       0
  4988.5     .05       0  4992.5     .07       0  5039.4     .12       0
  5073.8     .07       0
Bank Sta=4988.5,4992.5
XS Rating Curve= 0 ,0
Exp/Cntr=0.3,0.1

Type RM Length L Ch R = 1 ,19144   ,443,443,443
BEGIN DESCRIPTION:
Stream0118_DS 42.0
END DESCRIPTION:
XS GIS Cut Line= 3
      2031224.97     13945375.03        2030925.       13945675.
      2030875.01     13945774.98
#Sta/Elev= 30
  4575.5 1785.26    4579 1785.26  4589.6 1780.42  4617.9 1770.44  4660.3 1759.26
    4664 1758.72  4702.7 1753.49  4747.8 1749.67  4787.6 1745.57  4801.7 1743.03
  4815.9 1738.75    4830 1736.02  4844.2 1736.57  4900.7  1736.5    4929 1734.29
  4953.3 1734.94  4985.6 1735.35    5014 1733.29  5020.1 1731.28  5020.3 1730.78
  5023.8 1730.78  5024.1 1731.28  5036.1 1733.48  5044.4 1736.88  5050.1 1737.84
  5052.8  1738.3  5058.4 1741.47  5080.8 1750.59  5089.2 1753.03  5111.5 1754.96
#Mann= 8 ,-1 , 0
  4575.5     .12       0    4664     .07       0  4747.8     .12       0
  4953.3     .07       0    5014     .12       0  5020.1     .05       0
  5024.1     .12       0  5050.1     .07       0
Bank Sta=5020.1,5024.1
XS Rating Curve= 0 ,0
Exp/Cntr=0.3,0.1

Type RM Length L Ch R = 1 ,18701   ,263,263,263
BEGIN DESCRIPTION:
Stream0118_DS 41.0
END DESCRIPTION:
XS GIS Cut Line= 3
        2031025.     13945120.93        2030675.       13945325.
      2030431.25     13945645.24
#Sta/Elev= 30
  4594.8 1780.53  4606.4 1778.11  4641.1 1766.12  4655.5 1763.96  4671.2 1759.16
  4692.7 1755.48  4708.4 1749.68  4745.3 1739.22  4751.4 1735.95  4757.9 1735.53
  4767.1 1733.21  4772.9 1733.15    4780 1731.53  4837.9  1727.7  4954.9 1726.69
  4968.6 1724.56  4968.8 1724.06  4972.6 1724.56  4986.3 1726.84  5036.3 1729.05
  5050.2 1730.75  5077.9 1737.52  5100.5 1740.47  5121.6 1741.33  5200.5 1747.95
  5235.9  1749.6  5285.8 1755.06  5306.6 1755.96  5371.1 1762.53  5402.4 1764.76
#Mann= 4 ,-1 , 0
  4594.8     .12       0  4757.9     .07       0  4968.6     .05       0
  4972.6     .07       0
Bank Sta=4968.6,4972.6
XS Rating Curve= 0 ,0
Exp/Cntr=0.3,0.1

Type RM Length L Ch R = 1 ,18438   ,441,441,441
BEGIN DESCRIPTION:
Stream0118_DS 40.0
END DESCRIPTION:
XS GIS Cut Line= 3
      2031065.49     13945057.27      2030688.78     13945107.61
      2030224.96     13945325.02
#Sta/Elev= 30
  4623.4 1790.18  4641.5 1785.65  4646.6 1786.13  4686.6 1775.02  4714.6 1766.67
  4719.6 1766.91  4724.8  1764.5    4755 1755.97  4765.1 1752.02  4792.7 1735.89
  4797.7 1735.44  4805.5 1731.68  4825.7  1726.1  4865.7 1721.63  4938.6 1721.62
  4997.2 1722.71  5006.3 1721.92  5011.1  1723.1  5031.9 1720.91  5032.2 1720.41
  5035.9 1720.91  5051.2  1723.4    5087 1723.18  5107.9 1727.82  5162.9 1729.19
  5193.7 1729.11  5244.9 1731.89  5267.7 1731.56  5341.7 1736.54  5515.7 1743.92
#Mann= 7 ,-1 , 0
  4623.4     .07       0  4686.6     .12       0  4938.6     .07       0
  5031.9     .05       0  5035.9     .07       0    5087     .12       0
  5162.9     .07       0
Bank Sta=5031.9,5035.9
XS Rating Curve= 0 ,0
Exp/Cntr=0.3,0.1

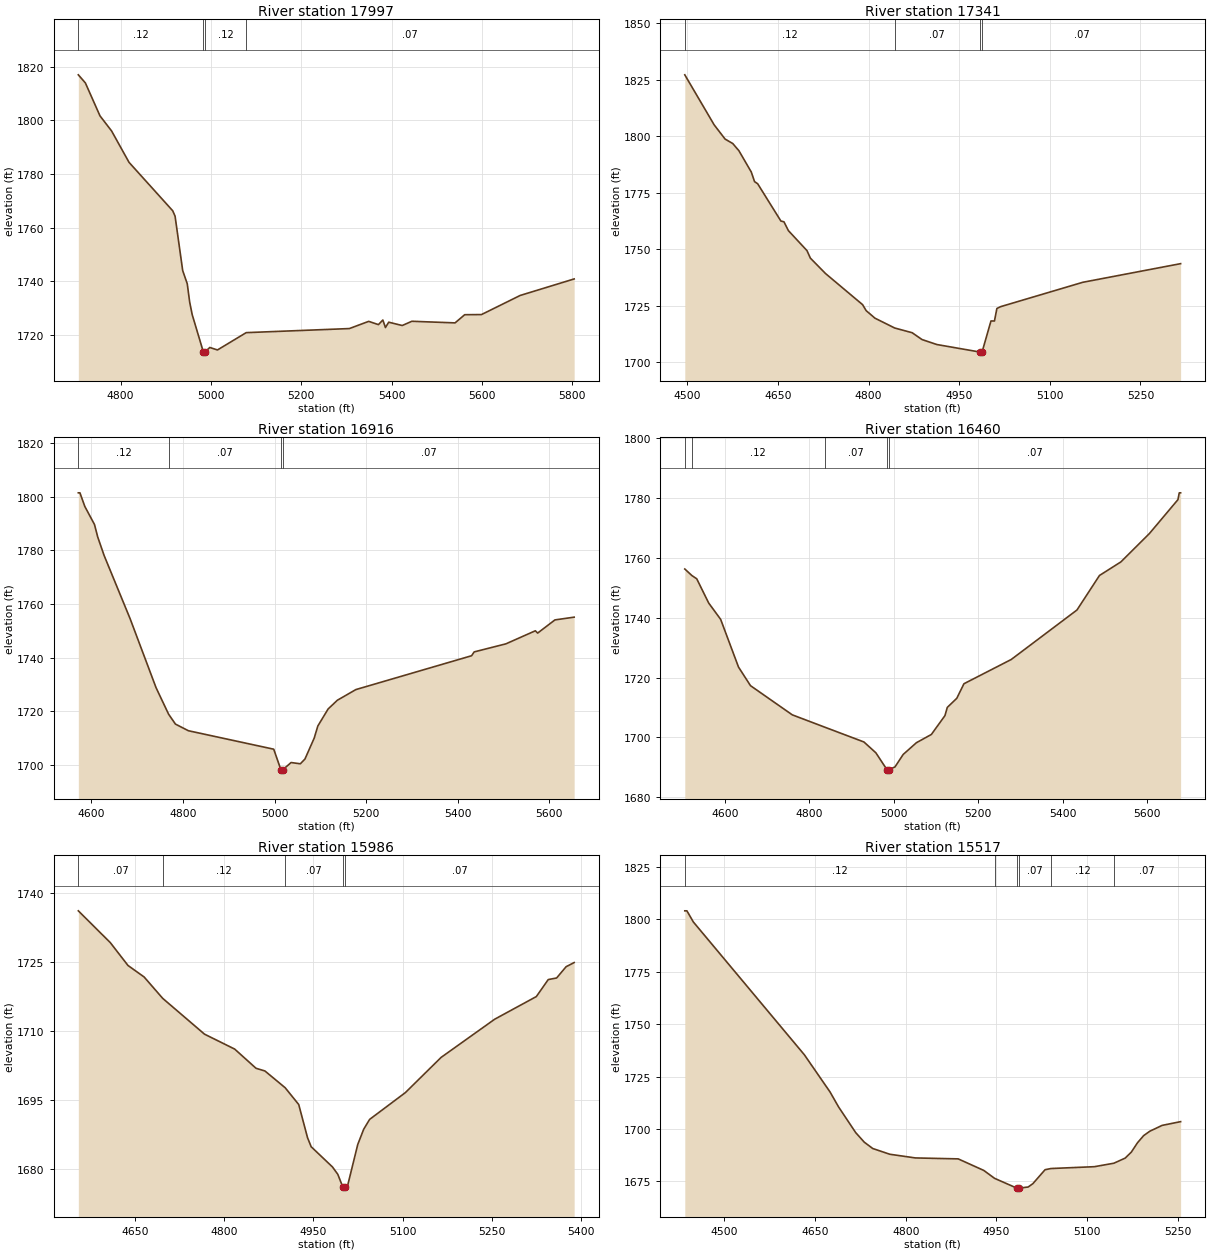
Type RM Length L Ch R = 1 ,17997   ,656,656,656
BEGIN DESCRIPTION:
Stream0118_DS 39.0
END DESCRIPTION:
XS GIS Cut Line= 4
      2030984.65      13944514.8      2030895.66     13944794.38
      2030705.68     13945026.59      2030271.66     13945283.53
#Sta/Elev= 30
  4706.6 1816.99  4722.2 1813.97  4754.5  1801.7  4780.3 1796.04  4818.9 1784.34
  4915.6 1766.28  4920.8 1764.28  4937.7 1743.96  4947.8 1739.04  4953.1 1732.25
  4958.7 1727.56  4983.3 1713.69  4983.5 1713.19  4987.3 1713.69  4997.7  1715.3
  5014.6 1714.37  5078.3 1720.83  5306.7 1722.35  5349.5 1725.04    5371 1723.82
  5380.8 1725.54  5386.6 1722.74  5393.8 1724.73  5423.7 1723.49  5445.1 1725.07
  5540.7 1724.47  5562.1 1727.52  5599.2 1727.57  5684.9  1734.7  5804.4 1740.86
#Mann= 4 ,-1 , 0
  4706.6     .12       0  4983.3     .05       0  4987.3     .12       0
  5078.3     .07       0
Bank Sta=4983.3,4987.3
XS Rating Curve= 0 ,0
Exp/Cntr=0.3,0.1

Type RM Length L Ch R = 1 ,17341   ,425,425,425
BEGIN DESCRIPTION:
Stream0118_DS 38.0
END DESCRIPTION:
XS GIS Cut Line= 3
      2030484.99     13944577.51        2030375.       13945075.
      2030178.96     13945316.95
#Sta/Elev= 30
  4495.7  1827.2  4544.3 1805.05  4562.4 1798.75  4575.1 1796.77  4585.3 1793.58
  4605.8 1784.14  4611.2 1779.89  4616.3 1778.97  4654.8 1762.44  4659.9 1762.09
  4667.2  1758.2    4698 1749.33  4703.6 1746.01  4728.7 1739.18  4790.1 1725.39
    4796 1722.74  4810.6  1719.4  4843.2 1715.06  4872.1 1712.97  4888.4 1709.95
    4913 1707.74  4983.9 1704.43  4984.2 1703.93  4987.9 1704.43  5002.6 1718.17
  5008.4 1718.17  5012.4 1723.71  5018.8 1724.53  5154.7 1735.31  5316.6 1743.56
#Mann= 4 ,-1 , 0
  4495.7     .12       0  4843.2     .07       0  4983.9     .05       0
  4987.9     .07       0
Bank Sta=4983.9,4987.9
XS Rating Curve= 0 ,0
Exp/Cntr=0.3,0.1

Type RM Length L Ch R = 1 ,16916   ,456,456,456
BEGIN DESCRIPTION:
Stream0118_DS 37.0
END DESCRIPTION:
XS GIS Cut Line= 3
      2030324.98     13944575.02        2030025.       13944875.
       2029927.9     13945526.57
#Sta/Elev= 30
  4571.5 1801.52    4575 1801.52  4585.6 1796.46  4606.8 1789.68  4613.9    1785
    4628 1778.04  4684.6 1754.51  4741.2 1728.77  4768.6 1718.86  4783.6 1715.14
  4811.9 1712.66  4998.3 1705.76    5014 1698.07  5014.2 1697.57    5018 1698.07
  5036.2 1700.78  5056.4 1700.31  5066.5 1702.09  5086.7  1709.9  5094.6 1714.41
  5117.1 1720.79  5137.3 1724.05  5177.7 1728.03  5430.5 1740.67  5436.1  1742.1
  5505.4 1745.11  5569.7 1749.99  5574.8 1749.14  5612.5 1754.05  5654.5 1755.08
#Mann= 4 ,-1 , 0
  4571.5     .12       0  4768.6     .07       0    5014     .05       0
    5018     .07       0
Bank Sta=5014,5018
XS Rating Curve= 0 ,0
Exp/Cntr=0.3,0.1

Type RM Length L Ch R = 1 ,16460   ,474,474,474
BEGIN DESCRIPTION:
Stream0118_DS 36.0
END DESCRIPTION:
XS GIS Cut Line= 3
      2029975.02     13944374.98        2029625.       13944725.
      2029327.19     13945335.65
#Sta/Elev= 30
    4505 1756.32  4521.6 1754.15  4533.3 1753.04  4561.6 1744.94  4589.9 1739.49
  4632.3 1723.51  4660.6 1717.31  4759.6 1707.55  4836.1 1703.45  4929.3 1698.48
  4957.6 1694.85  4983.8 1689.23  4984.1 1688.73  4987.9 1689.23  5002.8 1690.13
  5022.3 1694.31  5053.6 1698.23    5089 1700.99  5121.2 1707.29  5126.7 1710.03
  5149.2 1713.08  5166.2 1717.95  5278.2 1726.06  5433.9 1742.61  5487.2 1754.15
  5537.9 1758.69  5605.5 1768.18  5673.1 1779.52  5676.2 1781.79  5679.4 1781.79
#Mann= 5 ,-1 , 0
    4505     .07       0  4521.6     .12       0  4836.1     .07       0
  4983.8     .05       0  4987.9     .07       0
Bank Sta=4983.8,4987.9
XS Rating Curve= 0 ,0
Exp/Cntr=0.3,0.1

Type RM Length L Ch R = 1 ,15986   ,469,469,469
BEGIN DESCRIPTION:
Stream0118_DS 35.0
END DESCRIPTION:
XS GIS Cut Line= 3
      2029479.97     13944155.09        2029225.       13944525.
      2029219.57     13944908.49
#Sta/Elev= 30
  4555.2 1736.08  4608.9 1729.18  4638.6 1724.22  4665.7 1721.72  4696.9 1717.08
  4767.1 1709.31  4817.8 1706.07  4853.7  1701.9  4868.6 1701.32  4902.6 1697.68
  4925.4 1694.03  4940.2 1686.82  4946.3 1684.87  4982.1 1680.48    4991 1678.89
  4999.3 1676.17  4999.6 1675.67  5003.5 1676.17    5007 1676.17  5024.5 1685.35
  5034.5 1688.67  5044.5 1690.81  5104.5 1696.62  5164.5 1704.26  5254.5 1712.55
  5324.5 1717.47  5344.5 1721.16  5358.5  1721.5  5374.5 1723.95    5388 1724.85
#Mann= 5 ,-1 , 0
  4555.2     .07       0  4696.9     .12       0  4902.6     .07       0
  4999.3     .05       0  5003.5     .07       0
Bank Sta=4999.3,5003.5
XS Rating Curve= 0 ,0
Exp/Cntr=0.3,0.1

Type RM Length L Ch R = 1 ,15517   ,447,447,447
BEGIN DESCRIPTION:
Stream0118_DS 34.0
END DESCRIPTION:
XS GIS Cut Line= 3
      2029274.98     13943825.02        2028875.       13944225.
        2028825.     13944474.99
#Sta/Elev= 30
  4434.3 1803.95  4437.8 1803.95  4448.4 1798.66  4632.3 1735.32  4674.7 1717.64
  4688.8 1710.52  4717.1  1698.3  4731.3 1693.73  4745.4  1690.7  4773.7 1687.96
  4816.1 1686.21  4886.8 1685.76  4929.2 1680.25  4946.9  1676.5  4983.7 1671.85
    4984 1671.35    4988 1671.85  5002.5 1672.35  5010.2 1673.91  5030.6 1680.61
  5040.5 1681.17  5112.1 1682.04  5144.4 1683.69  5163.1 1686.12  5173.3 1688.99
  5183.5 1693.43  5193.7 1696.84  5203.9 1698.94  5224.3 1701.72  5254.9  1703.5
#Mann= 6 ,-1 , 0
  4434.3     .12       0  4946.9     .07       0  4983.7     .05       0
    4988     .07       0  5040.5     .12       0  5144.4     .07       0
Bank Sta=4983.7,4988
XS Rating Curve= 0 ,0
Exp/Cntr=0.3,0.1

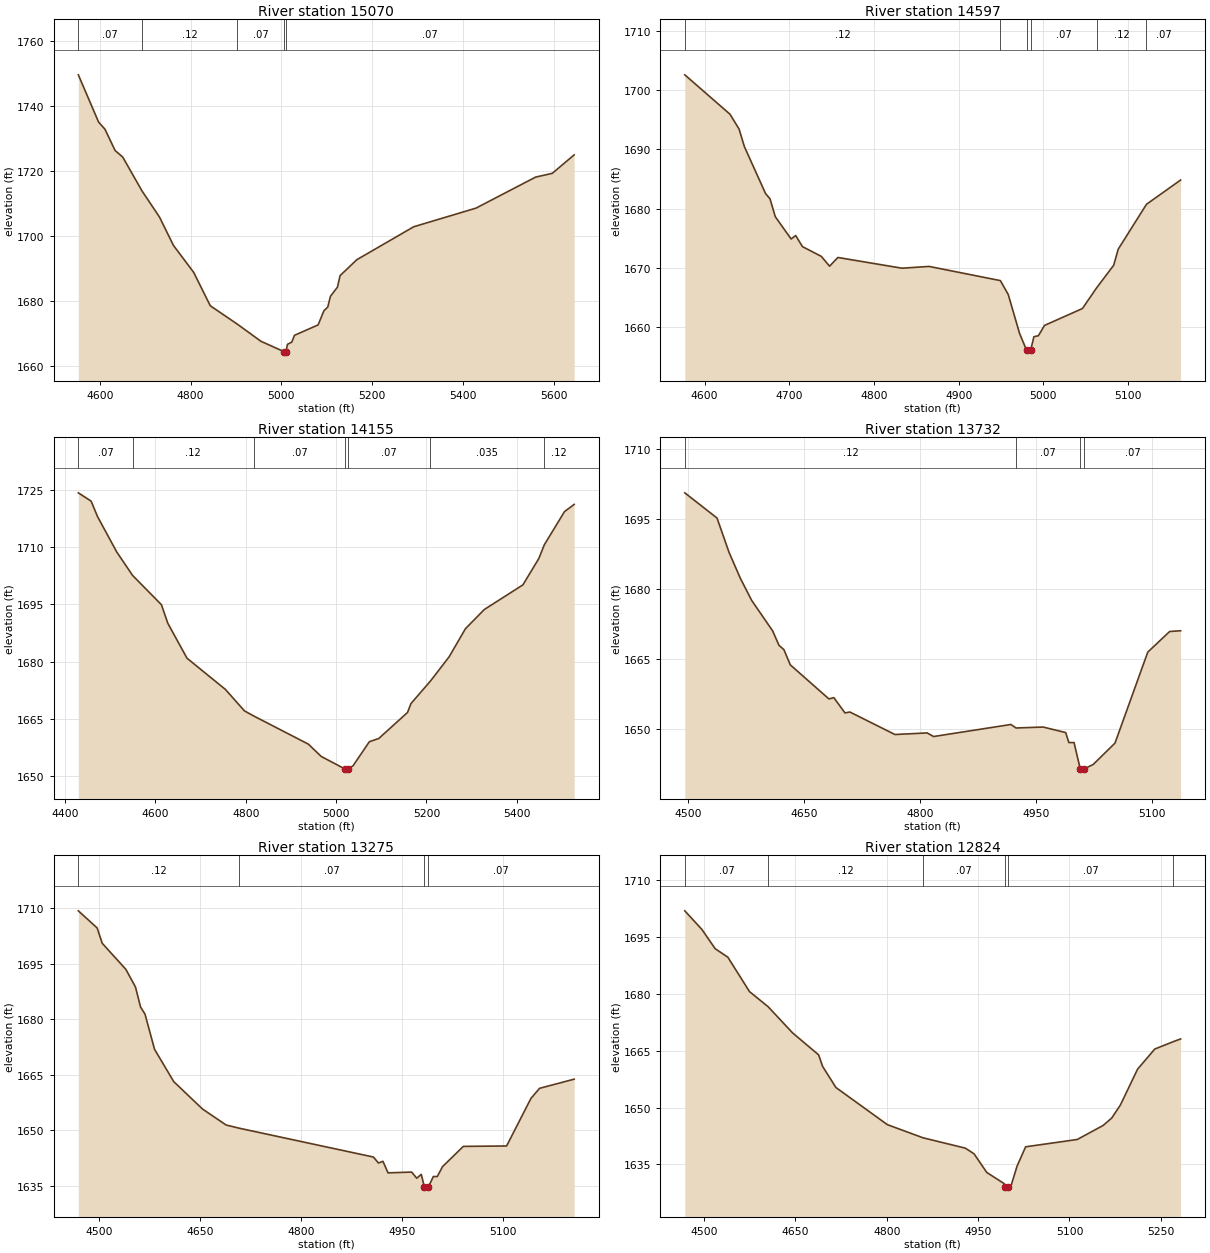
Type RM Length L Ch R = 1 ,15070   ,473,473,473
BEGIN DESCRIPTION:
Stream0118_DS 33.0
END DESCRIPTION:
XS GIS Cut Line= 3
      2028974.98     13943725.01        2028575.       13943925.
      2028236.91     13944474.53
#Sta/Elev= 30
  4552.8 1749.51  4597.5 1734.96  4611.5 1732.77  4633.8 1726.23  4650.6 1724.21
  4692.9 1713.84  4731.7 1705.72  4762.4 1697.02  4807.1 1688.69  4843.5 1678.46
  4903.4 1672.77  4955.3 1667.51  5005.3 1664.38  5005.7 1663.88  5010.2 1664.38
  5013.6 1666.59  5023.1 1667.27    5029 1669.36  5081.1 1672.56  5093.9 1676.92
  5102.4 1678.06  5108.2 1681.35  5123.7 1684.19  5129.5 1687.72  5166.2 1692.61
  5291.7 1702.76    5429  1708.5  5560.3 1718.04    5597  1719.2  5645.2 1724.88
#Mann= 5 ,-1 , 0
  4552.8     .07       0  4692.9     .12       0  4903.4     .07       0
  5005.3     .05       0  5010.2     .07       0
Bank Sta=5005.3,5010.2
XS Rating Curve= 0 ,0
Exp/Cntr=0.3,0.1

Type RM Length L Ch R = 1 ,14597   ,442,442,442
BEGIN DESCRIPTION:
Stream0118_DS 32.0
END DESCRIPTION:
XS GIS Cut Line= 3
      2028425.01     13943224.97        2028275.       13943625.
      2028225.02     13943774.95
#Sta/Elev= 30
  4576.7 1702.58  4630.1 1695.93  4640.8 1693.43    4647 1690.49    4672 1682.57
  4677.3 1681.67  4683.5 1678.66  4702.2  1674.9  4707.6 1675.48  4715.6 1673.61
  4737.8 1671.97  4747.6 1670.31  4757.4 1671.78  4833.1 1669.97  4865.1 1670.27
  4949.2 1667.88  4958.5 1665.54  4971.9 1658.97  4980.1 1656.15  4980.5 1655.65
    4985 1656.15  4988.8 1658.42  4994.1 1658.58  5001.3 1660.32  5046.1 1663.17
  5062.8 1666.65    5083 1670.47  5088.3 1673.17  5121.7 1680.75    5162 1684.84
#Mann= 6 ,-1 , 0
  4576.7     .12       0  4949.2     .07       0  4980.1     .05       0
    4985     .07       0  5062.8     .12       0  5121.7     .07       0
Bank Sta=4980.1,4985
XS Rating Curve= 0 ,0
Exp/Cntr=0.3,0.1

Type RM Length L Ch R = 1 ,14155   ,423,423,423
BEGIN DESCRIPTION:
Stream0118_DS 31.0
END DESCRIPTION:
XS GIS Cut Line= 3
      2028325.03     13942974.97        2027925.       13943375.
      2027575.03     13943774.97
#Sta/Elev= 30
  4429.6 1724.28  4457.9  1722.1  4472.1 1718.05  4514.5 1708.78  4549.5 1702.63
  4613.5 1694.92  4627.6 1690.05  4670.1 1680.88  4754.9 1672.71  4797.3 1667.05
  4817.6 1665.73  4938.8 1658.32    4967 1655.11  5020.7 1651.75  5021.1 1651.25
  5025.9 1651.75  5037.6 1652.67  5073.6 1658.97  5094.5 1659.82  5158.1 1666.65
  5165.7 1668.98  5208.7 1674.87  5250.2 1681.26  5286.2 1688.62    5328 1693.66
  5413.4 1700.13  5448.5 1707.02  5460.9 1710.67  5505.5 1719.36  5526.8 1721.24
#Mann= 7 ,-1 , 0
  4429.6     .07       0  4549.5     .12       0  4817.6     .07       0
  5020.7     .05       0  5025.9     .07       0  5208.7    .035       0
  5460.9     .12       0
Bank Sta=5020.7,5025.9
XS Rating Curve= 0 ,0
Exp/Cntr=0.3,0.1

Type RM Length L Ch R = 1 ,13732   ,457,457,457
BEGIN DESCRIPTION:
Stream0118_DS 30.0
END DESCRIPTION:
XS GIS Cut Line= 3
      2028075.04     13942774.97        2027675.       13943075.
      2027574.98     13943175.02
#Sta/Elev= 30
  4495.6 1700.65  4537.3 1695.25  4552.9 1687.88  4567.5 1682.34  4582.1 1677.62
  4609.2  1671.1  4617.5 1667.98  4623.8 1667.08  4632.1 1663.81  4682.1 1656.51
  4688.4 1656.79  4702.9 1653.51  4709.2 1653.71  4767.5 1648.89  4809.2 1649.23
  4817.5 1648.46  4917.5 1651.04  4924.2 1650.29  4959.2 1650.49  4988.4 1649.31
  4992.5 1647.17  4999.2 1647.17  5007.2 1641.55  5007.6 1641.05  5012.4 1641.55
  5023.9 1642.46  5052.2 1647.05  5094.6 1666.54  5122.9 1670.95  5137.1 1671.11
#Mann= 4 ,-1 , 0
  4495.6     .12       0  4924.2     .07       0  5007.2     .05       0
  5012.4     .07       0
Bank Sta=5007.2,5012.4
XS Rating Curve= 0 ,0
Exp/Cntr=0.3,0.1

Type RM Length L Ch R = 1 ,13275   ,451,451,451
BEGIN DESCRIPTION:
Stream0118_DS 29.0
END DESCRIPTION:
XS GIS Cut Line= 3
      2028025.02     13942324.98        2027625.       13942675.
      2027424.99       13942725.
#Sta/Elev= 30
  4468.6 1709.29  4496.6 1704.66  4504.2  1700.5  4539.3 1693.47  4553.6  1688.7
  4561.2 1683.27  4567.8 1681.35    4582 1671.84  4610.5 1663.11  4653.2 1655.71
  4688.4 1651.37  4707.9  1650.5  4907.6  1642.7  4915.2 1641.08  4921.8 1641.55
  4929.4 1638.42  4964.5 1638.63  4972.1 1636.97  4978.8 1638.01  4983.6 1634.52
    4984 1634.02  4989.2 1634.52  4996.8 1637.43  5002.7 1637.43  5010.4 1640.09
  5041.4 1645.58  5105.8 1645.69  5141.9 1658.52  5154.8 1661.28  5206.3 1663.76
#Mann= 4 ,-1 , 0
  4468.6     .12       0  4707.9     .07       0  4983.6     .05       0
  4989.2     .07       0
Bank Sta=4983.6,4989.2
XS Rating Curve= 0 ,0
Exp/Cntr=0.3,0.1

Type RM Length L Ch R = 1 ,12824   ,473,473,473
BEGIN DESCRIPTION:
Stream0118_DS 28.0
END DESCRIPTION:
XS GIS Cut Line= 3
      2027725.02     13941974.97        2027375.       13942375.
      2027174.99     13942575.01
#Sta/Elev= 30
  4468.2 1701.89  4496.2    1697  4518.1  1691.9  4538.9 1689.66  4574.5 1680.58
  4605.1 1676.59  4645.2  1669.7    4688  1663.9  4694.6 1660.85  4716.4 1655.29
  4800.9 1645.49  4859.5 1642.02    4929 1639.29  4943.3  1637.8  4964.2 1632.88
  4992.6 1629.95  4993.5 1628.98    4994 1628.48  4999.3 1628.98  5003.3 1628.98
  5013.9 1634.52    5028 1639.64  5112.9 1641.58  5155.3 1645.27  5169.4 1647.23
  5183.6 1650.65  5211.9 1660.12  5240.2 1665.44  5270.6 1667.38  5282.6  1668.1
#Mann= 6 ,-1 , 0
  4468.2     .07       0  4605.1     .12       0  4859.5     .07       0
  4993.5     .05       0  4999.3     .07       0  5270.6    .035       0
Bank Sta=4993.5,4999.3
XS Rating Curve= 0 ,0
Exp/Cntr=0.3,0.1

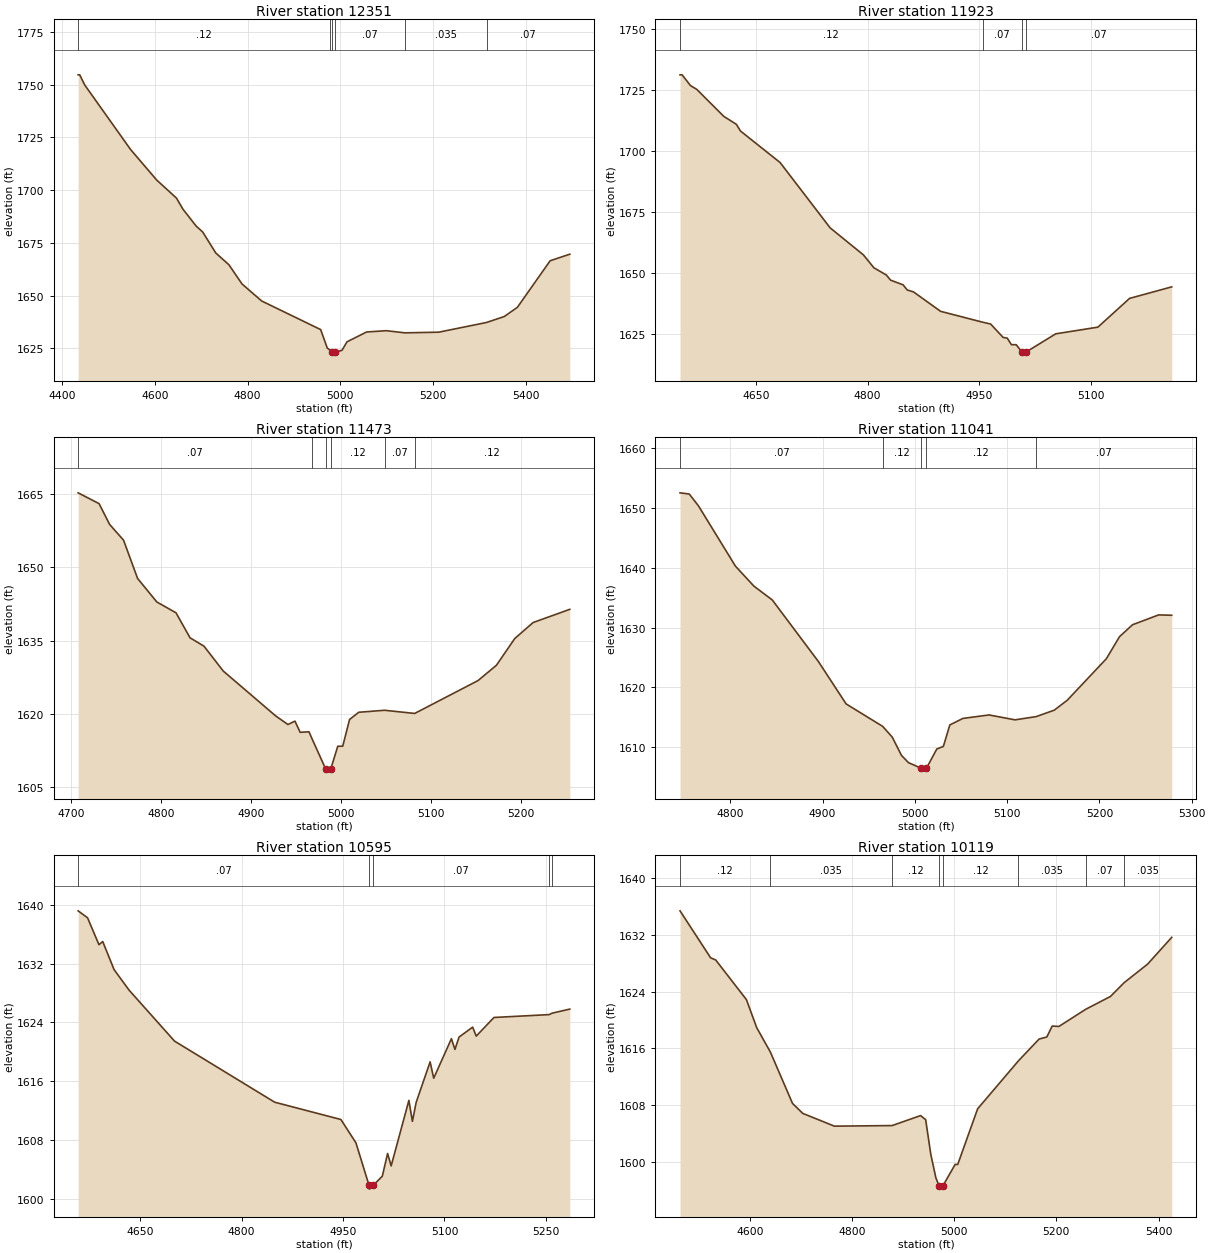
Type RM Length L Ch R = 1 ,12351   ,428,428,428
BEGIN DESCRIPTION:
Stream0118_DS 27.0
END DESCRIPTION:
XS GIS Cut Line= 3
      2027574.99     13941575.01        2027175.       13941975.
      2026825.03     13942324.97
#Sta/Elev= 30
  4434.6 1754.69  4438.1 1754.69  4448.7 1749.92  4547.7  1719.3  4604.3 1704.76
  4646.7 1696.26  4660.9 1690.94  4689.1 1683.01  4703.3 1680.18  4731.6 1670.21
  4759.9 1664.64  4788.1 1655.55  4830.6 1647.46  4957.8 1633.91    4972 1625.17
  4978.9 1623.99  4983.2 1623.25  4983.7 1622.75    4989 1623.25  5003.8 1624.07
  5014.4 1628.08  5056.8 1632.77  5099.3 1633.39  5139.6 1632.37  5212.4 1632.68
  5315.6 1637.28  5353.8  1640.1  5382.1 1644.47  5452.8 1666.55  5495.2 1669.66
#Mann= 6 ,-1 , 0
  4434.6     .12       0  4978.9     .07       0  4983.2     .05       0
    4989     .07       0  5139.6    .035       0  5315.6     .07       0
Bank Sta=4983.2,4989
XS Rating Curve= 0 ,0
Exp/Cntr=0.3,0.1

Type RM Length L Ch R = 1 ,11923   ,450,450,450
BEGIN DESCRIPTION:
Stream0118_DS 26.0
END DESCRIPTION:
XS GIS Cut Line= 3
      2027375.01     13941424.99        2026975.       13941625.
      2026824.97     13941775.03
#Sta/Elev= 30
  4548.5 1731.21  4551.3 1731.21  4562.5  1726.8  4570.9 1725.25  4607.2 1714.17
    4624 1710.92  4629.6 1708.16  4682.7 1695.24  4749.8 1668.45  4794.5 1657.34
  4808.5 1652.07  4825.2  1649.1  4830.8 1647.01  4847.6 1645.09  4853.2 1642.97
  4861.6 1642.18  4897.9 1634.22  4954.3 1629.76    4965 1629.01  4981.8 1623.51
  4987.3 1623.23  4992.9 1620.53  4999.3 1620.53  5006.9 1617.57  5007.4 1617.07
  5012.8 1617.57  5052.3 1624.98  5108.9 1627.73  5151.3 1639.51  5207.9 1644.25
#Mann= 4 ,-1 , 0
  4548.5     .12       0  4954.3     .07       0  5006.9     .05       0
  5012.8     .07       0
Bank Sta=5006.9,5012.8
XS Rating Curve= 0 ,0
Exp/Cntr=0.3,0.1

Type RM Length L Ch R = 1 ,11473   ,432,432,432
BEGIN DESCRIPTION:
Stream0118_DS 25.0
END DESCRIPTION:
XS GIS Cut Line= 3
      2026874.99     13941225.01        2026625.       13941375.
        2026575.     13941625.01
#Sta/Elev= 30
  4708.2 1665.19  4731.5 1662.98  4743.2 1658.74  4758.7 1655.51  4774.3 1647.69
  4795.7 1642.88    4817 1640.67  4832.6 1635.56  4848.1 1633.85  4869.5 1628.77
  4927.8 1619.59  4941.4 1617.84  4949.2 1618.53    4955 1616.24  4964.8 1616.35
  4968.6 1614.76  4983.2 1608.81  4983.6 1608.31  4989.1 1608.81  4996.8  1613.4
  5002.3  1613.4  5009.9 1618.86  5020.1 1620.34  5048.8 1620.75  5082.3  1620.1
  5152.7 1626.82  5173.1 1629.94  5193.5 1635.41  5213.9 1638.68  5254.7 1641.38
#Mann= 6 ,-1 , 0
  4708.2     .07       0  4968.6     .12       0  4983.2     .05       0
  4989.1     .12       0  5048.8     .07       0  5082.3     .12       0
Bank Sta=4983.2,4989.1
XS Rating Curve= 0 ,0
Exp/Cntr=0.3,0.1

Type RM Length L Ch R = 1 ,11041   ,446,446,446
BEGIN DESCRIPTION:
Stream0118_DS 24.0
END DESCRIPTION:
XS GIS Cut Line= 3
      2026775.01       13940975.        2026525.       13940975.
      2026324.96     13941175.04
#Sta/Elev= 30
  4745.5 1652.57  4755.5 1652.37  4765.5 1650.38  4805.5  1640.3  4825.5 1636.95
  4845.5 1634.62  4895.5  1624.3  4925.5 1617.21  4965.1 1613.45  4975.5 1611.65
  4985.5 1608.59    4993 1607.38  5006.6 1606.45  5007.1 1605.95  5012.1 1605.95
  5012.6 1606.45  5023.8 1609.66  5030.9 1610.09  5037.9 1613.69  5052.1 1614.78
  5080.4 1615.36  5108.6 1614.54  5131.4 1615.08  5151.1 1616.16  5165.2 1617.83
  5207.6 1624.79  5221.8 1628.47  5235.9 1630.47  5264.2 1632.12  5278.4 1632.06
#Mann= 5 ,-1 , 0
  4745.5     .07       0  4965.1     .12       0  5006.6     .05       0
  5012.6     .12       0  5131.4     .07       0
Bank Sta=5006.6,5012.6
XS Rating Curve= 0 ,0
Exp/Cntr=0.3,0.1

Type RM Length L Ch R = 1 ,10595   ,476,476,476
BEGIN DESCRIPTION:
Stream0118_DS 23.0
END DESCRIPTION:
XS GIS Cut Line= 3
      2026575.04     13940574.98        2026175.       13940775.
      2026264.61     13941040.21
#Sta/Elev= 30
  4558.2 1639.17  4572.2 1638.22    4589 1634.57  4594.6    1635  4611.4 1631.18
  4633.7 1628.38  4700.8 1621.47  4848.9 1613.17  4946.8 1610.82  4969.1 1607.65
  4988.5 1601.86    4989 1601.36  4994.5 1601.86  5008.1 1603.12  5015.9  1606.2
  5021.2 1604.52  5047.4 1613.42  5052.6 1610.57  5058.2 1613.16  5078.8 1618.65
  5084.1 1616.43  5110.3  1621.8  5115.5 1620.34  5121.6 1622.02  5141.7 1623.37
    5147 1622.15  5173.2 1624.68  5254.8 1625.07  5259.4 1625.27  5285.4 1625.82
#Mann= 5 ,-1 , 0
  4558.2     .07       0  4988.5     .05       0  4994.5     .07       0
  5254.8     .12       0  5259.4     .07       0
Bank Sta=4988.5,4994.5
XS Rating Curve= 0 ,0
Exp/Cntr=0.3,0.1

Type RM Length L Ch R = 1 ,10119   ,443,443,443
BEGIN DESCRIPTION:
Stream0118_DS 22.0
END DESCRIPTION:
XS GIS Cut Line= 3
      2026514.66     13940408.53        2025975.       13940375.
      2025570.24     13940491.88
#Sta/Elev= 30
  4463.7 1635.41  4523.5 1628.79  4533.5 1628.48  4593.6 1622.89  4613.7 1618.94
  4640.5 1615.49  4683.8 1608.25  4703.8 1606.85  4765.7 1605.05  4878.6 1605.13
  4934.3 1606.54  4944.3 1605.96  4954.3 1601.08  4964.3 1597.75  4970.3 1596.67
  4970.8 1596.17  4978.3 1596.67  5001.9 1599.65    5007 1599.65    5046  1607.5
  5125.8 1614.26  5166.2 1617.33  5181.3 1617.62  5191.8 1619.16    5205 1619.11
  5257.5 1621.53  5305.9 1623.34  5332.9  1625.3  5378.4 1627.89  5425.7 1631.67
#Mann= 8 ,-1 , 0
  4463.7     .12       0  4640.5    .035       0  4878.6     .12       0
  4970.3     .05       0  4978.3     .12       0  5125.8    .035       0
  5257.5     .07       0  5332.9    .035       0
Bank Sta=4970.3,4978.3
XS Rating Curve= 0 ,0
Exp/Cntr=0.3,0.1

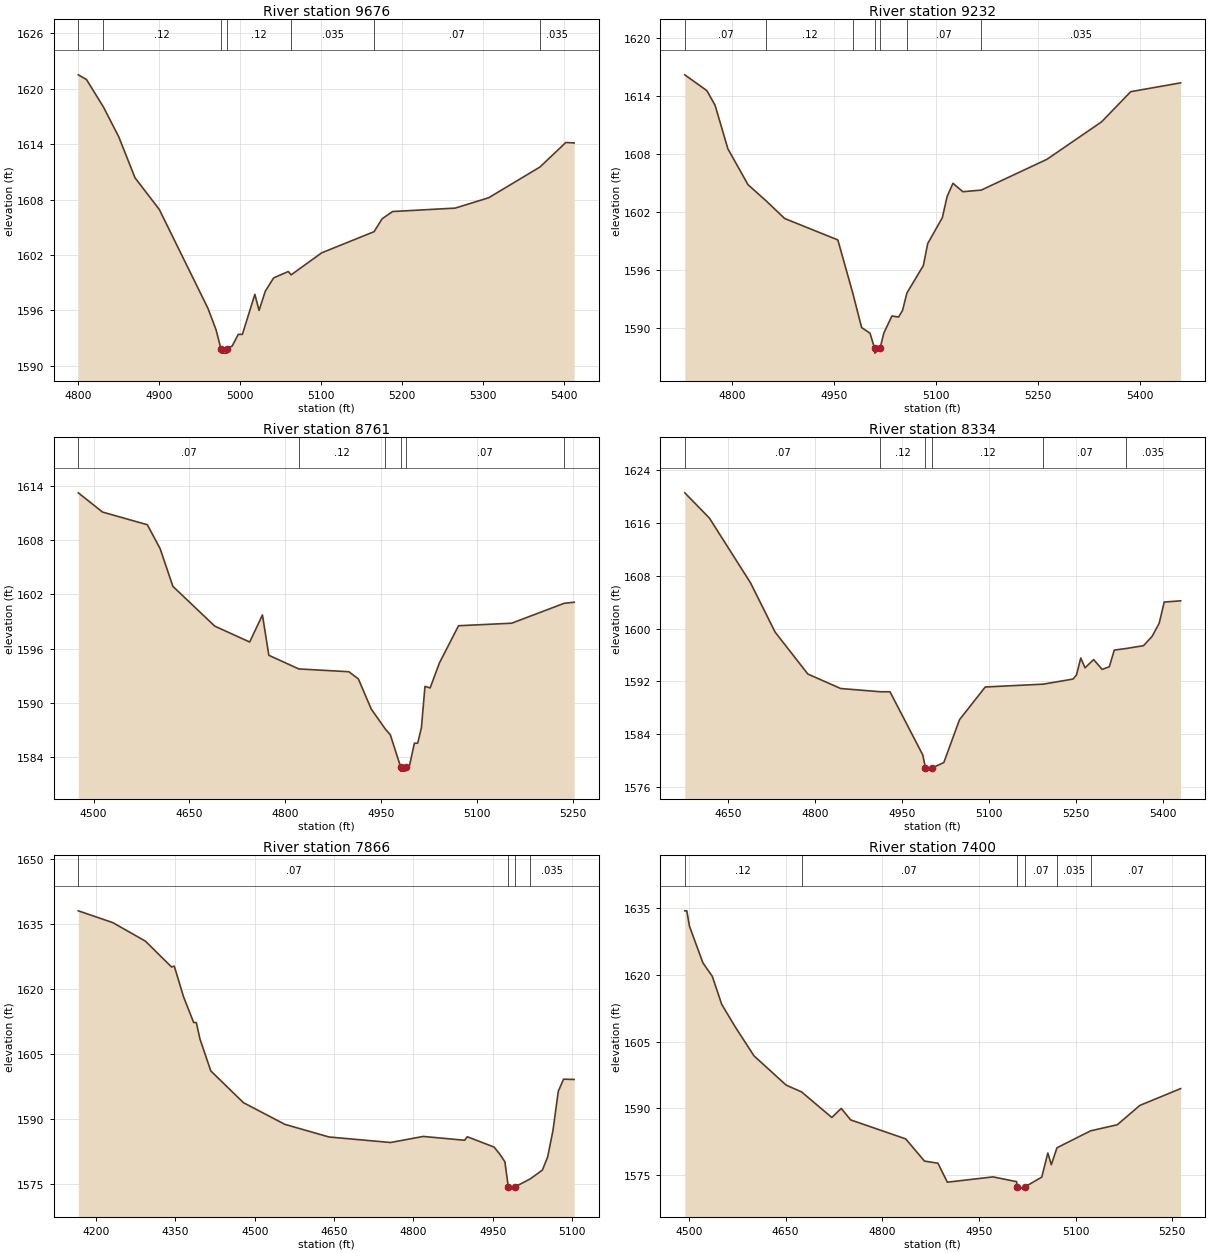
Type RM Length L Ch R = 1 ,9676    ,444,444,444
BEGIN DESCRIPTION:
Stream0118_DS 21.0
END DESCRIPTION:
XS GIS Cut Line= 3
      2026425.01       13940075.        2026225.       13940075.
      2025825.02       13940175.
#Sta/Elev= 30
  4800.7 1621.49  4810.7 1620.99  4831.7 1618.01  4850.7 1614.77  4870.7 1610.35
  4900.7 1606.92  4960.7 1596.24  4970.7 1593.93  4976.7 1591.88  4977.2 1591.38
  4984.3 1591.38  4984.8 1591.88  4990.7 1592.15  4998.2 1593.41  5003.3 1593.41
  5018.7 1597.74  5023.9    1596  5031.6 1598.08  5041.9 1599.52    5060 1600.21
  5063.5 1599.85  5101.2 1602.23  5165.9 1604.52  5175.9 1605.92  5188.8  1606.7
  5266.1 1607.07  5307.4 1608.19  5370.7 1611.51  5402.7 1614.17    5413 1614.12
#Mann= 7 ,-1 , 0
  4800.7     .07       0  4831.7     .12       0  4976.7     .05       0
  4984.8     .12       0  5063.5    .035       0  5165.9     .07       0
  5370.7    .035       0
Bank Sta=4976.7,4984.8
XS Rating Curve= 0 ,0
Exp/Cntr=0.3,0.1

Type RM Length L Ch R = 1 ,9232    ,471,471,471
BEGIN DESCRIPTION:
Stream0118_DS 20.0
END DESCRIPTION:
XS GIS Cut Line= 3
      2026275.04     13939674.98        2026025.       13939775.
      2025629.67     13940009.01
#Sta/Elev= 30
  4730.7  1616.2  4763.1 1614.57  4775.2 1613.06    4794 1608.56  4823.6 1604.85
  4850.3 1603.17  4877.5 1601.35  4955.6 1599.14  4977.4 1593.69  4990.6 1590.08
  5002.9  1589.5  5009.6 1587.94  5010.1 1587.44  5017.7 1587.94  5023.2 1589.51
  5035.1 1591.28  5044.9 1591.17  5050.7 1591.85  5057.1 1593.65  5081.3 1596.49
  5087.7 1598.76  5109.2 1601.44  5116.2 1603.62  5124.8 1604.99  5139.4 1604.12
  5166.5 1604.29  5263.2 1607.48  5343.2 1611.34  5386.1 1614.46  5459.4 1615.37
#Mann= 7 ,-1 , 0
  4730.7     .07       0  4850.3     .12       0  4977.4    .035       0
  5009.6    .035       0  5017.7    .035       0  5057.1     .07       0
  5166.5    .035       0
Bank Sta=5009.6,5017.7
XS Rating Curve= 0 ,0
Exp/Cntr=0.3,0.1

Type RM Length L Ch R = 1 ,8761    ,427,427,427
BEGIN DESCRIPTION:
Stream0118_DS 19.0
END DESCRIPTION:
XS GIS Cut Line= 3
      2026302.87      13939450.2        2025775.       13939425.
       2025667.5     13939648.08
#Sta/Elev= 30
  4476.1 1613.23    4514  1611.1  4584.1  1609.7  4604.1 1607.06  4624.1 1602.88
  4689.6 1598.48  4744.3 1596.72  4764.3 1599.71  4774.3 1595.25  4821.2 1593.74
  4899.6 1593.43  4914.5 1592.63  4934.5 1589.31  4956.7 1587.08  4964.5 1586.45
  4980.4 1582.93  4980.9 1582.43  4988.1 1582.43  4988.6 1582.93  4994.6 1583.07
  5002.1 1585.52  5007.3 1585.52  5013.1 1587.23  5018.7 1591.81  5026.8 1591.64
  5041.3  1594.4  5071.2 1598.52  5154.4  1598.8  5236.8 1601.01  5252.2 1601.12
#Mann= 6 ,-1 , 0
  4476.1     .07       0  4821.2     .12       0  4956.7     .07       0
  4980.4     .05       0  4988.6     .07       0  5236.8    .035       0
Bank Sta=4980.4,4988.6
XS Rating Curve= 0 ,0
Exp/Cntr=0.3,0.1

Type RM Length L Ch R = 1 ,8334    ,468,468,468
BEGIN DESCRIPTION:
Stream0118_DS 18.0
END DESCRIPTION:
XS GIS Cut Line= 3
        2025925.       13938775.        2025625.       13939075.
      2025374.99     13939425.02
#Sta/Elev= 30
    4576  1620.6  4618.4 1616.77  4689.1 1606.97  4731.6 1599.48  4788.1 1593.11
  4844.7 1590.92  4912.9 1590.43  4929.6 1590.43  4986.1 1580.84  4990.7 1578.89
  4991.2 1578.39  5002.8 1578.89  5022.4  1579.7  5049.4 1586.19  5093.7 1591.15
  5193.5 1591.58  5244.8 1592.35    5251 1592.98  5258.3 1595.55  5265.7 1594.06
  5280.5 1595.31  5295.2 1593.82  5307.5 1594.22  5316.1 1596.75  5336.6 1596.99
  5366.5 1597.42  5381.2 1598.82  5393.5 1600.82  5402.1 1604.03  5430.4 1604.22
#Mann= 6 ,-1 , 0
    4576     .07       0  4912.9     .12       0  4990.7     .05       0
  5002.8     .12       0  5193.5     .07       0  5336.6    .035       0
Bank Sta=4990.7,5002.8
XS Rating Curve= 0 ,0
Exp/Cntr=0.3,0.1

Type RM Length L Ch R = 1 ,7866    ,466,466,466
BEGIN DESCRIPTION:
Stream0118_DS 17.0
END DESCRIPTION:
XS GIS Cut Line= 3
      2026088.25      13938577.8        2025275.       13938775.
      2025175.02       13938775.
#Sta/Elev= 30
  4166.8 1637.99  4231.9 1635.27  4293.6 1630.99  4342.9 1625.04  4348.1 1625.22
  4365.6 1618.15  4384.7 1612.22  4389.8 1612.19  4396.5 1608.45  4417.1 1601.04
  4478.8 1593.71    4557 1588.71  4640.6 1585.79  4756.7 1584.52  4818.4 1585.92
  4896.6 1585.04  4901.7 1585.85  4952.2 1583.47  4962.5 1581.93  4972.7 1580.08
  4979.2 1574.26  4979.7 1573.76  4991.4 1574.26  5020.6 1576.12  5043.6 1578.16
  5053.6 1581.22  5063.6 1587.31  5073.6 1596.33  5083.6 1599.14  5103.6 1599.07
#Mann= 4 ,-1 , 0
  4166.8     .07       0  4979.2     .05       0  4991.4     .07       0
  5020.6    .035       0
Bank Sta=4979.2,4991.4
XS Rating Curve= 0 ,0
Exp/Cntr=0.3,0.1

Type RM Length L Ch R = 1 ,7400    ,435,435,435
BEGIN DESCRIPTION:
Stream0118_DS 16.0
END DESCRIPTION:
XS GIS Cut Line= 3
      2025874.97     13938075.02        2025475.       13938375.
      2025225.02     13938474.99
#Sta/Elev= 30
  4493.7 1634.45  4496.8 1634.45    4501 1630.97  4521.8 1622.73  4536.4 1619.67
    4551 1613.37  4571.8 1608.33    4601 1601.78    4651 1595.17  4674.8 1593.65
  4721.8 1587.89  4736.4 1589.93    4751 1587.34  4836.4 1583.06  4865.5 1578.06
  4886.4 1577.58    4901  1573.3  4971.8  1574.5  5008.5 1573.42  5009.1 1572.24
  5009.6 1571.74  5021.3 1572.24  5047.5 1574.45  5056.9 1579.88  5062.3 1577.24
  5071.1 1581.06  5123.3 1584.88  5164.6 1586.24  5199.6  1590.6  5262.9 1594.39
#Mann= 6 ,-1 , 0
  4493.7     .12       0  4674.8     .07       0  5009.1     .05       0
  5021.3     .07       0  5071.1    .035       0  5123.3     .07       0
Bank Sta=5009.1,5021.3
XS Rating Curve= 0 ,0
Exp/Cntr=0.3,0.1