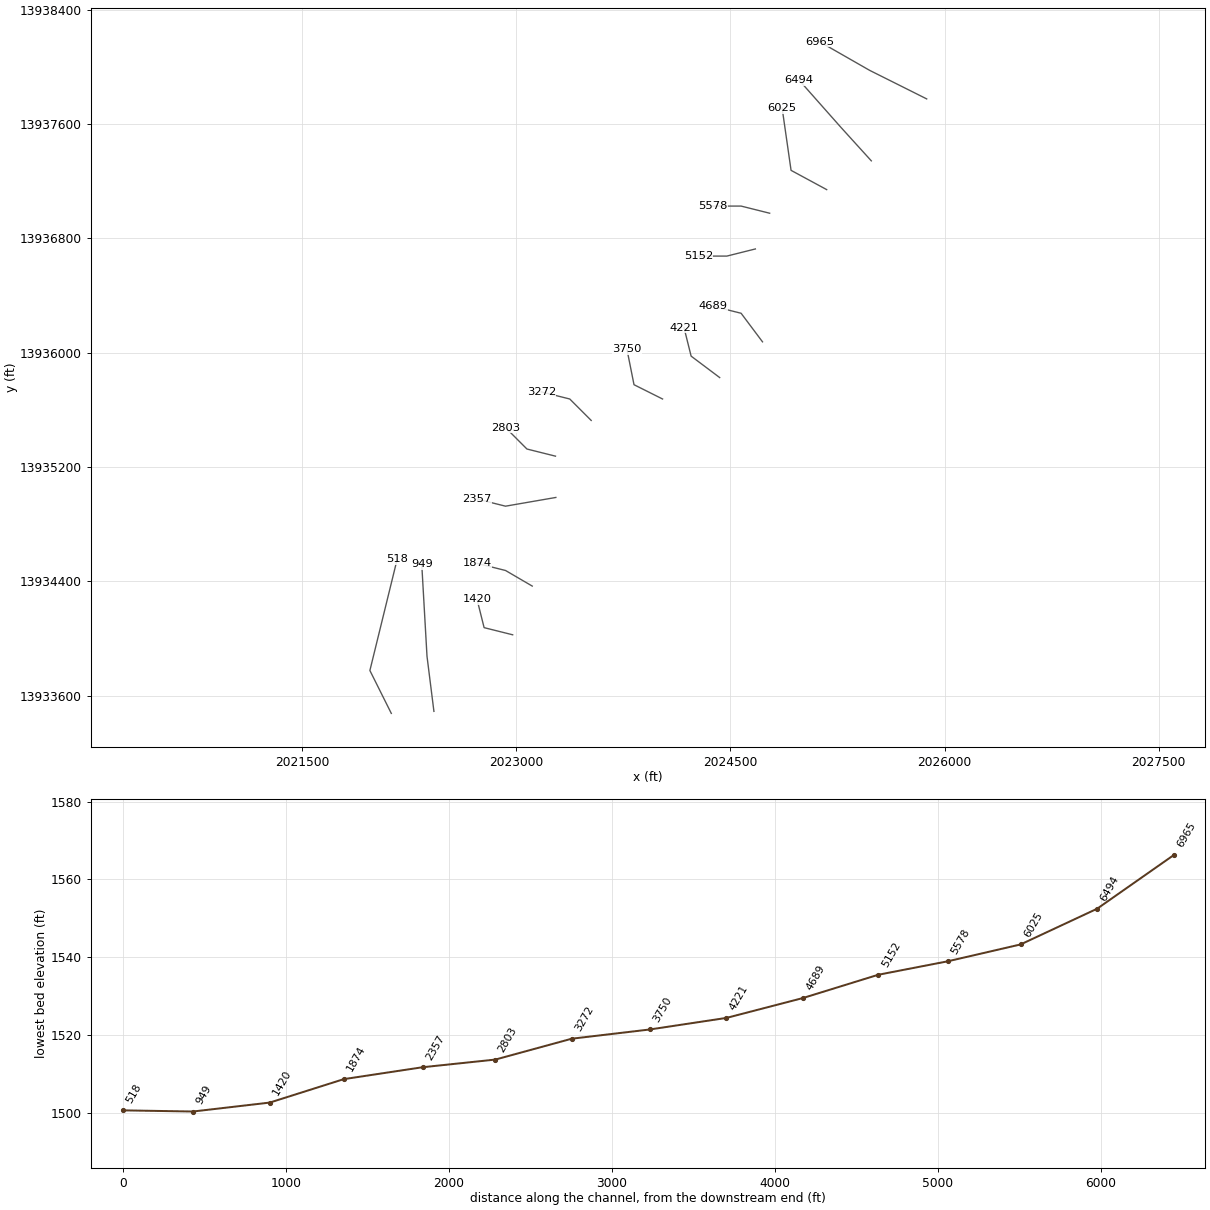
HEC-RAS study Stream0118_DS.prj: Stream0118_DS Base Level Engineering

--- Stream0118_DS.g01 (geometry) --- (continued)

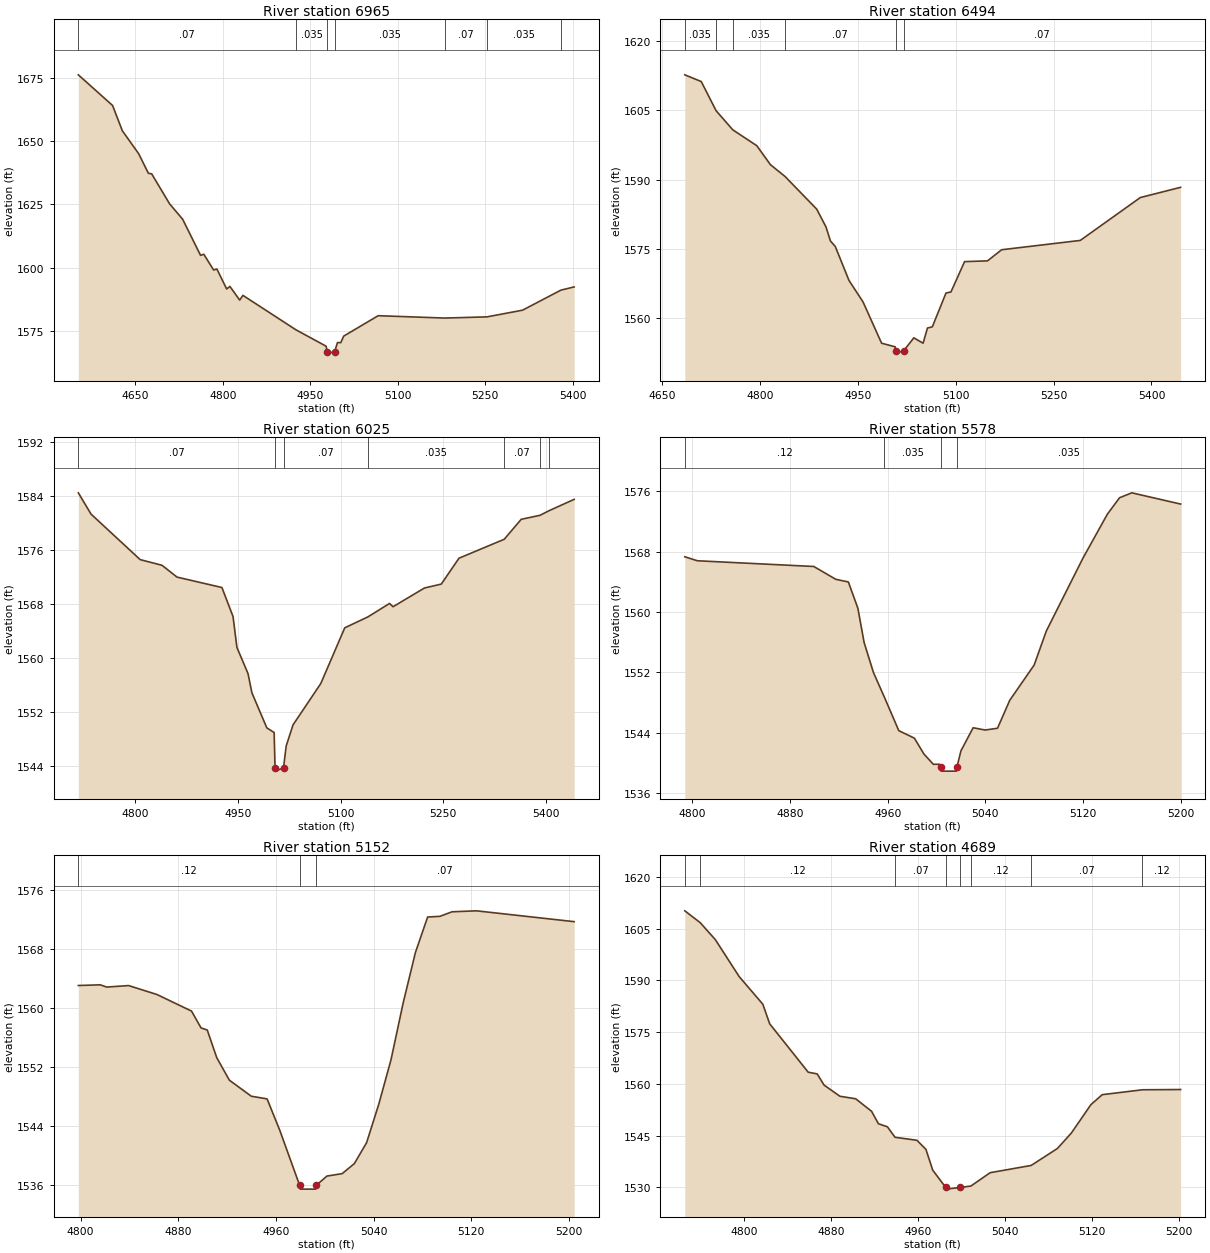
Type RM Length L Ch R = 1 ,6965    ,471,471,471
BEGIN DESCRIPTION:
Stream0118_DS 15.0
END DESCRIPTION:
XS GIS Cut Line= 3
        2025875.       13937775.        2025475.       13937975.
      2025125.03     13938174.99
#Sta/Elev= 30
  4552.4 1676.17  4611.1 1664.07  4627.9 1654.07  4655.8 1645.04  4672.6 1637.28
  4678.2 1637.06  4708.9 1625.22  4731.3 1619.14    4762 1604.87  4767.6  1605.3
  4784.4 1599.09    4790 1599.48  4806.8 1591.58  4812.3 1592.61  4829.1 1587.21
  4834.7 1589.06  4925.6 1575.46  4977.3 1568.99  4979.5 1566.75    4980 1566.25
  4991.8 1566.75  4996.8  1570.4  5002.5  1570.4  5007.5 1572.97  5066.6 1581.03
  5180.8  1580.1  5253.2 1580.57  5314.2 1583.21    5380 1591.13  5402.7  1592.4
#Mann= 7 ,-1 , 0
  4552.4     .07       0  4925.6    .035       0  4979.5    .035       0
  4991.8    .035       0  5180.8     .07       0  5253.2    .035       0
    5380     .07       0
Bank Sta=4979.5,4991.8
XS Rating Curve= 0 ,0
Exp/Cntr=0.3,0.1

Type RM Length L Ch R = 1 ,6494    ,469,469,469
BEGIN DESCRIPTION:
Stream0118_DS 14.0
END DESCRIPTION:
XS GIS Cut Line= 3
       2025487.1     13937341.52        2025275.       13937575.
      2024980.11     13937907.55
#Sta/Elev= 30
  4684.8 1612.67    4710 1611.22  4732.7 1604.92  4758.3 1600.77  4795.1 1597.33
  4816.1 1593.21  4838.3 1590.68    4887 1583.59  4901.2 1579.74    4908 1576.71
  4915.4 1575.52  4936.4 1568.17    4958  1563.5  4986.4 1554.57  5007.3 1553.78
  5007.8 1552.92  5008.3 1552.42  5020.2 1552.92  5035.8 1555.73    5050 1554.57
  5056.7 1557.85  5064.2 1558.12  5085.1 1565.43  5092.7 1565.66  5113.6 1572.23
  5148.7 1572.39  5170.4  1574.8  5290.9 1576.82  5382.9  1586.1  5444.7 1588.32
#Mann= 6 ,-1 , 0
  4684.8    .035       0  4732.7     .07       0  4758.3    .035       0
  4838.3     .07       0  5007.8     .05       0  5020.2     .07       0
Bank Sta=5007.8,5020.2
XS Rating Curve= 0 ,0
Exp/Cntr=0.3,0.1

Type RM Length L Ch R = 1 ,6025    ,447,447,447
BEGIN DESCRIPTION:
Stream0118_DS 13.0
END DESCRIPTION:
XS GIS Cut Line= 3
      2025174.55     13937140.18        2024925.       13937275.
      2024862.29     13937711.58
#Sta/Elev= 30
  4716.6 1584.53  4735.2 1581.37    4807 1574.62  4838.9 1573.78  4860.8 1572.03
  4926.5 1570.48  4942.7 1566.18  4948.4  1561.6  4964.6 1557.71  4970.3 1554.86
  4992.1 1549.66  5002.8 1548.97  5004.1 1543.74  5004.6 1543.24  5016.5 1543.74
  5020.4 1546.97  5030.4  1550.1    5071 1556.24    5106  1564.5    5140 1566.13
  5171.5 1568.12  5176.6 1567.63  5222.5 1570.41  5247.1 1570.99    5273 1574.83
  5339.1 1577.64  5363.9  1580.6  5391.2 1581.19  5405.1  1581.9  5441.3 1583.56
#Mann= 7 ,-1 , 0
  4716.6     .07       0  5004.1     .05       0  5016.5     .07       0
    5140    .035       0  5339.1     .07       0  5391.2    .035       0
  5405.1     .07       0
Bank Sta=5004.1,5016.5
XS Rating Curve= 0 ,0
Exp/Cntr=0.3,0.1

Type RM Length L Ch R = 1 ,5578    ,426,426,426
BEGIN DESCRIPTION:
Stream0118_DS 12.0
END DESCRIPTION:
XS GIS Cut Line= 3
      2024775.02       13936975.        2024575.       13937025.
      2024374.98       13937025.
#Sta/Elev= 30
  4793.8 1567.33  4804.1  1566.8  4899.5 1566.04  4917.5 1564.34  4927.8 1563.99
  4935.6  1560.5  4940.7 1555.96  4948.4 1551.96  4957.3 1548.71  4969.1 1544.27
  4981.9 1543.27  4989.7 1541.17  4997.4 1539.81  5002.5 1539.81  5003.3  1539.4
  5003.8  1538.9  5016.2  1538.9  5016.7  1539.4    5020 1541.58    5030 1544.65
    5040 1544.35    5050 1544.59    5060 1548.29    5080 1552.97    5090 1557.49
    5120 1567.15    5140 1572.98    5150 1575.16    5160 1575.81    5200 1574.32
#Mann= 4 ,-1 , 0
  4793.8     .12       0  4957.3    .035       0  5003.3    .035       0
  5016.7    .035       0
Bank Sta=5003.3,5016.7
XS Rating Curve= 0 ,0
Exp/Cntr=0.3,0.1

Type RM Length L Ch R = 1 ,5152    ,463,463,463
BEGIN DESCRIPTION:
Stream0118_DS 11.0
END DESCRIPTION:
XS GIS Cut Line= 3
      2024674.98     13936724.99        2024475.       13936675.
      2024275.03       13936675.
#Sta/Elev= 30
  4798.1 1563.06  4816.1 1563.15  4821.3 1562.85  4839.3 1563.05  4862.5 1561.84
  4890.8 1559.59  4898.6 1557.31  4903.7 1557.02  4911.5 1553.26  4921.8 1550.22
  4939.8 1548.04  4952.7 1547.68    4963 1543.46  4979.4 1535.94  4979.9 1535.44
  4992.4 1535.44  4992.9 1535.94  5001.7 1537.21  5014.2 1537.54  5024.2 1538.91
  5034.2 1541.74  5044.2 1546.97  5054.2 1552.99  5064.2 1560.73  5074.2 1567.54
  5084.2 1572.35  5094.2 1572.44  5104.2 1573.06  5124.2 1573.19  5204.2 1571.72
#Mann= 3 ,-1 , 0
  4798.1     .12       0  4979.4     .05       0  4992.9     .07       0
Bank Sta=4979.4,4992.9
XS Rating Curve= 0 ,0
Exp/Cntr=0.3,0.1

Type RM Length L Ch R = 1 ,4689    ,468,468,468
BEGIN DESCRIPTION:
Stream0118_DS 10.0
END DESCRIPTION:
XS GIS Cut Line= 3
      2024724.97     13936075.04        2024575.       13936275.
      2024375.01       13936325.
#Sta/Elev= 30
  4745.7  1610.2  4759.8 1606.79  4773.8 1601.84  4795.7 1591.13  4817.5 1583.09
  4823.8 1577.41  4859.2 1563.38  4867.5 1562.87  4873.8 1559.64  4888.4 1556.39
  4902.9 1555.66  4917.5 1552.03  4923.8 1548.42  4932.1 1547.52  4939.1 1544.48
  4959.2 1543.62  4967.5 1540.99  4973.8 1534.93  4985.7 1529.94  4986.2 1529.44
  4999.3 1529.94  5008.9 1530.34  5026.6 1534.21  5064.3 1536.31  5088.4 1541.22
  5101.3 1545.72  5119.3 1553.97  5129.7 1556.85  5166.7 1558.27  5201.8 1558.34
#Mann= 8 ,-1 , 0
  4745.7     .07       0  4759.8     .12       0  4939.1     .07       0
  4985.7     .05       0  4999.3     .07       0  5008.9     .12       0
  5064.3     .07       0  5166.7     .12       0
Bank Sta=4985.7,4999.3
XS Rating Curve= 0 ,0
Exp/Cntr=0.3,0.1

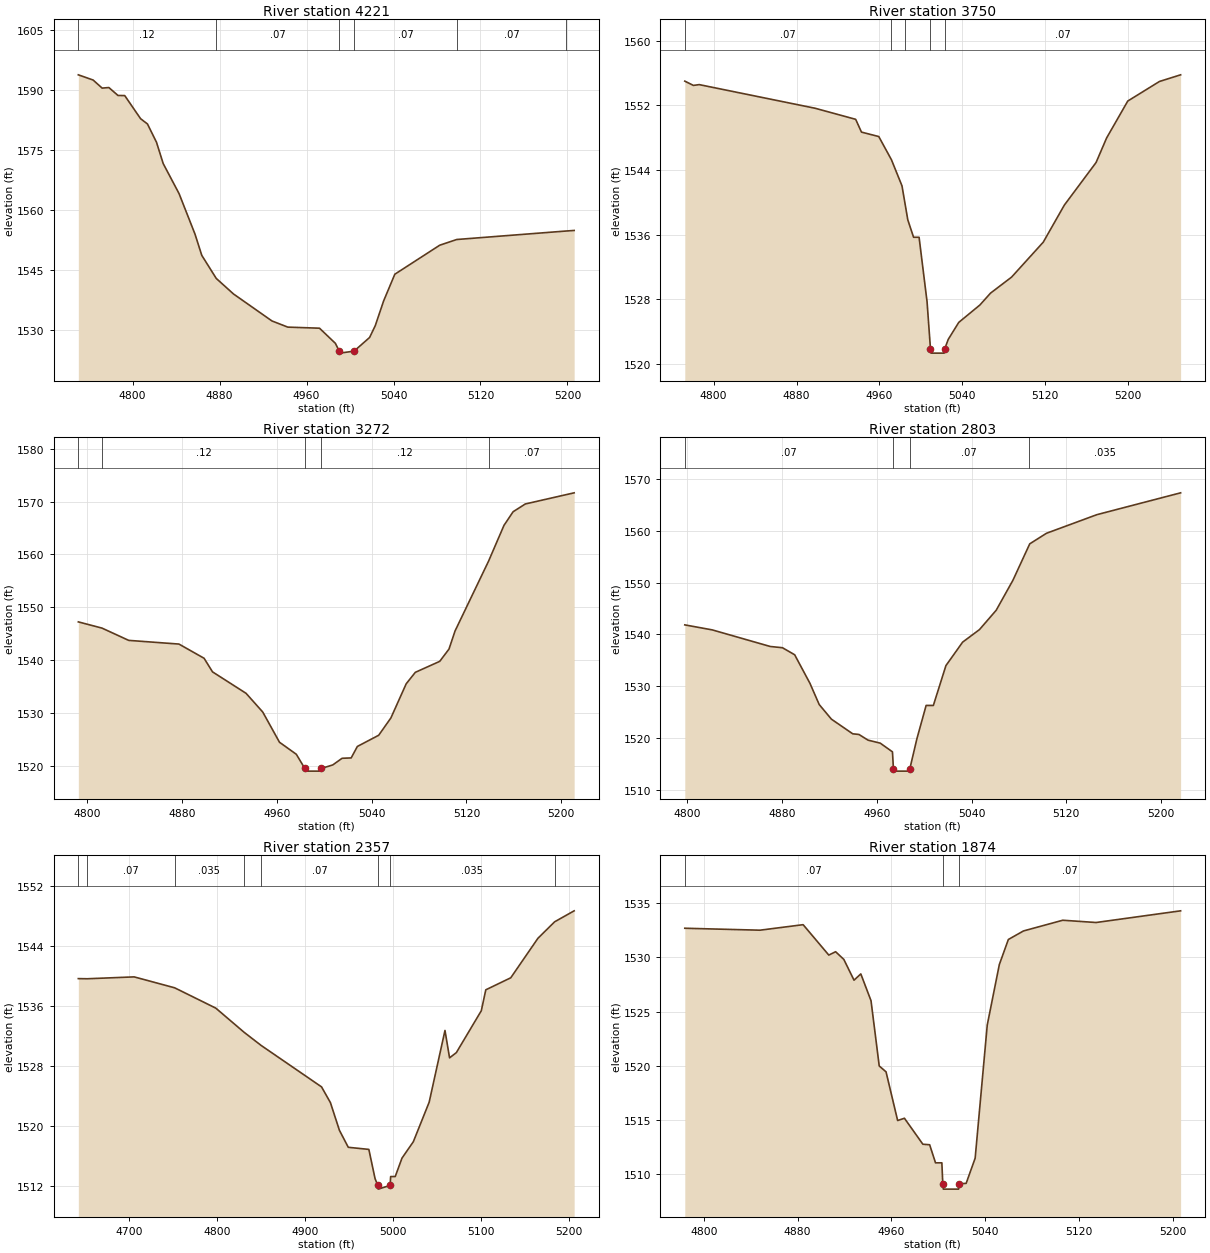
Type RM Length L Ch R = 1 ,4221    ,471,471,471
BEGIN DESCRIPTION:
Stream0118_DS 9.0
END DESCRIPTION:
XS GIS Cut Line= 3
      2024425.01     13935824.99        2024225.       13935975.
      2024174.99     13936175.04
#Sta/Elev= 30
    4750  1593.9  4763.6  1592.6  4771.9 1590.58  4778.1 1590.72  4786.5 1588.74
  4792.7 1588.71  4807.3 1582.93  4813.6 1581.62  4821.9 1577.06  4828.1 1571.71
  4842.7  1564.2  4857.3 1554.12  4863.6 1548.77  4876.9 1543.01  4892.7 1539.14
  4928.1 1532.39  4942.7 1530.84  4971.9 1530.57  4986.5 1526.79  4990.1 1524.84
  4990.6 1524.34  5003.7 1524.84    5018 1528.25  5023.2  1531.2  5030.9 1537.39
  5041.2 1544.06  5082.5 1551.31  5098.2 1552.74  5198.8 1554.86  5206.2    1555
#Mann= 6 ,-1 , 0
    4750     .12       0  4876.9     .07       0  4990.1     .05       0
  5003.7     .07       0  5098.2     .07       0  5198.8     .12       0
Bank Sta=4990.1,5003.7
XS Rating Curve= 0 ,0
Exp/Cntr=0.3,0.1

Type RM Length L Ch R = 1 ,3750    ,478,478,478
BEGIN DESCRIPTION:
Stream0118_DS 8.0
END DESCRIPTION:
XS GIS Cut Line= 3
      2024024.97     13935675.02        2023825.       13935775.
        2023775.     13936024.98
#Sta/Elev= 30
  4772.2 1554.98  4780.5 1554.45  4786.1 1554.55  4897.9 1551.63  4937.1 1550.26
  4942.7 1548.68  4959.4 1548.13  4971.6 1545.27  4981.8 1542.04    4985 1539.64
  4987.4 1537.84    4993 1535.68  4998.3 1535.68    5006 1527.71  5009.3 1521.86
  5009.8 1521.36  5022.5 1521.36    5023 1521.86  5026.4 1523.05  5036.6 1525.16
    5057 1527.31  5067.2 1528.77  5087.6 1530.76  5118.1 1535.07  5138.5 1539.66
  5169.1 1544.92  5179.3 1547.96  5199.7 1552.52  5230.3 1554.94  5250.7 1555.76
#Mann= 5 ,-1 , 0
  4772.2     .07       0  4971.6    .035       0    4985     .07       0
  5009.3     .05       0    5023     .07       0
Bank Sta=5009.3,5023
XS Rating Curve= 0 ,0
Exp/Cntr=0.3,0.1

Type RM Length L Ch R = 1 ,3272    ,469,469,469
BEGIN DESCRIPTION:
Stream0118_DS 7.0
END DESCRIPTION:
XS GIS Cut Line= 3
      2023525.03     13935524.97        2023375.       13935675.
      2023175.03     13935724.99
#Sta/Elev= 30
  4792.6 1547.24  4812.6 1546.06  4835.1 1543.74  4877.5 1543.04  4898.7 1540.35
  4905.8 1537.78  4934.1 1533.72  4948.2 1530.17  4962.3 1524.46  4976.5 1522.18
  4983.7 1519.49  4984.2 1518.99  4997.1 1518.99  4997.6 1519.49  5007.3 1520.17
  5015.1 1521.42  5022.8 1521.49    5028 1523.66    5046 1525.78  5056.3 1529.06
  5069.2 1535.52  5076.9 1537.69  5097.5 1539.77  5105.3 1542.09  5110.4 1545.51
  5138.7 1558.74  5151.7 1565.51  5159.4 1568.09  5169.7 1569.56  5210.9 1571.67
#Mann= 5 ,-1 , 0
  4792.6     .07       0  4812.6     .12       0  4983.7     .05       0
  4997.6     .12       0  5138.7     .07       0
Bank Sta=4983.7,4997.6
XS Rating Curve= 0 ,0
Exp/Cntr=0.3,0.1

Type RM Length L Ch R = 1 ,2803    ,446,446,446
BEGIN DESCRIPTION:
Stream0118_DS 6.0
END DESCRIPTION:
XS GIS Cut Line= 3
      2023274.97     13935275.01        2023075.       13935325.
      2022924.97     13935475.03
#Sta/Elev= 30
  4798.1 1541.85  4821.3 1540.88  4870.2 1537.68  4880.5 1537.44  4890.8 1536.08
  4903.7 1530.56  4911.5 1526.47  4921.8 1523.65  4939.8 1520.82    4945  1520.7
  4952.7  1519.6    4963 1519.02  4973.3 1517.34  4974.1 1514.12  4974.6 1513.62
  4987.5 1513.62    4988 1514.12  4993.9 1519.86  5001.7  1526.3  5007.8  1526.3
  5018.4 1533.99  5032.5 1538.52  5046.7 1540.94  5060.8 1544.67  5074.9 1550.45
  5088.1 1556.99  5089.1 1557.49  5103.2 1559.53  5145.7 1563.12  5216.4 1567.34
#Mann= 4 ,-1 , 0
  4798.1     .07       0  4974.1     .05       0    4988     .07       0
  5088.1    .035       0
Bank Sta=4974.1,4988
XS Rating Curve= 0 ,0
Exp/Cntr=0.3,0.1

Type RM Length L Ch R = 1 ,2357    ,483,483,483
BEGIN DESCRIPTION:
Stream0118_DS 5.0
END DESCRIPTION:
XS GIS Cut Line= 3
      2023277.53     13934986.05        2022925.       13934925.
      2022725.03     13934974.99
#Sta/Elev= 30
  4642.2 1539.63  4652.2 1539.61  4705.7 1539.86  4751.7 1538.41  4798.5 1535.71
  4830.8 1532.49  4850.1 1530.75  4918.8 1525.24  4928.9 1523.15  4939.1 1519.48
  4949.2 1517.21  4972.6 1516.93  4979.7 1513.03  4982.8 1512.15  4983.3 1511.65
  4996.8 1512.15  4997.4 1513.32  5002.6 1513.32  5010.3 1515.77  5023.2 1517.95
  5041.2  1523.2  5059.2 1532.74  5064.4  1529.1  5072.1 1529.79  5100.5 1535.36
  5105.6 1538.14    5134 1539.74  5164.9 1544.99  5183.9 1547.18  5206.1 1548.64
#Mann= 8 ,-1 , 0
  4642.2     .12       0  4652.2     .07       0  4751.7    .035       0
  4830.8     .12       0  4850.1     .07       0  4982.8     .05       0
  4996.8    .035       0  5183.9     .12       0
Bank Sta=4982.8,4996.8
XS Rating Curve= 0 ,0
Exp/Cntr=0.3,0.1

Type RM Length L Ch R = 1 ,1874    ,454,454,454
BEGIN DESCRIPTION:
Stream0118_DS 4.0
END DESCRIPTION:
XS GIS Cut Line= 3
      2023112.15     13934365.83        2022925.       13934475.
      2022725.02       13934525.
#Sta/Elev= 30
  4783.8  1532.7  4847.9 1532.52  4884.7 1533.03  4906.6 1530.22  4912.4 1530.53
  4919.4 1529.82  4928.1  1527.9  4933.9 1528.48  4942.6    1526  4949.6 1519.97
  4955.4 1519.43  4965.3 1514.93  4971.1 1515.14  4986.8 1512.74  4992.6 1512.69
  4997.6 1511.02    5003 1511.02  5003.8 1509.09  5004.3 1508.59  5017.3 1508.59
  5017.8 1509.09  5023.7 1509.12  5031.4 1511.45  5041.7 1523.75    5052 1529.34
  5059.7 1531.66  5072.6 1532.45  5106.1 1533.44  5134.5 1533.23  5206.6 1534.31
#Mann= 3 ,-1 , 0
  4783.8     .07       0  5003.8     .05       0  5017.8     .07       0
Bank Sta=5003.8,5017.8
XS Rating Curve= 0 ,0
Exp/Cntr=0.3,0.1

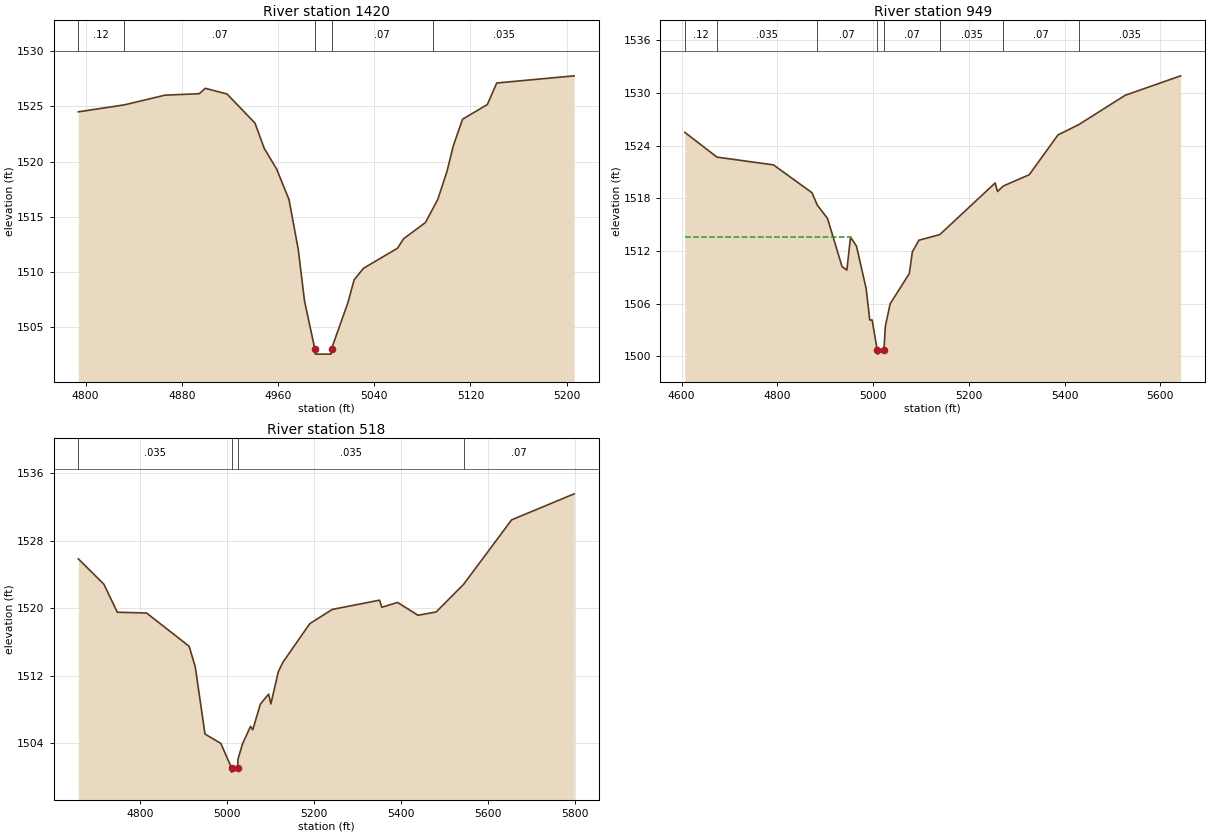
Type RM Length L Ch R = 1 ,1420    ,471,471,471
BEGIN DESCRIPTION:
Stream0118_DS 3.0
END DESCRIPTION:
XS GIS Cut Line= 3
      2022974.98     13934025.01        2022775.       13934075.
        2022725.     13934275.01
#Sta/Elev= 30
  4793.9  1524.5  4832.1 1525.13    4866 1526.01  4894.4 1526.14  4899.5 1526.63
  4917.6 1526.11  4940.8 1523.48  4948.5 1521.19  4958.8 1519.32  4969.1 1516.55
  4976.8 1512.03    4982 1507.37  4990.5 1503.06    4991 1502.56    5004 1502.56
  5004.5 1503.06  5018.1 1507.23  5023.2 1509.28    5031 1510.33  5059.3 1512.15
  5064.5 1513.02  5082.5 1514.47  5088.8 1515.75  5092.8 1516.57  5100.5 1519.13
  5105.7 1521.42  5113.4 1523.83    5134 1525.16  5141.8 1527.11  5206.2 1527.76
#Mann= 5 ,-1 , 0
  4793.9     .12       0  4832.1     .07       0  4990.5     .05       0
  5004.5     .07       0  5088.8    .035       0
Bank Sta=4990.5,5004.5
XS Rating Curve= 0 ,0
Exp/Cntr=0.3,0.1

Type RM Length L Ch R = 1 ,949     ,431,431,431
BEGIN DESCRIPTION:
Stream0118_DS 2.0
END DESCRIPTION:
XS GIS Cut Line= 3
      2022423.49     13933489.19        2022375.       13933875.
      2022338.16      13934520.7
#Sta/Elev= 30
  4606.7 1525.53  4673.9 1522.71    4792 1521.82  4872.4 1518.65  4883.4 1517.24
  4904.8 1515.72  4935.1 1510.24  4945.2 1509.84  4952.8 1513.59  4965.3 1512.57
  4985.5 1507.72    4993 1504.15    4998 1504.15  5008.5 1500.76    5009 1500.26
  5022.7 1500.76  5025.6 1503.44  5035.6 1505.99  5075.7 1509.45    5082 1511.91
  5095.7 1513.24  5139.3 1513.88  5254.9 1519.76  5259.9 1518.79  5271.7 1519.41
  5326.1  1520.7  5386.2 1525.24  5430.2 1526.43  5526.4 1529.75  5642.3 1531.97
#Mann= 8 ,-1 , 0
  4606.7     .12       0  4673.9    .035       0  4883.4     .07       0
  5008.5     .05       0  5022.7     .07       0  5139.3    .035       0
  5271.7     .07       0  5430.2    .035       0
#XS Ineff= 2 , 0
       0  4954.8 1513.65               0
Permanent Ineff=
       F       F
Bank Sta=5008.5,5022.7
XS Rating Curve= 0 ,0
Exp/Cntr=0.3,0.1

Type RM Length L Ch R = 1 ,518     ,0,0,0
BEGIN DESCRIPTION:
Stream0118_DS 1.0
END DESCRIPTION:
XS GIS Cut Line= 3
      2022125.01     13933474.98        2021975.       13933775.
      2022166.31     13934554.43
#Sta/Elev= 30
  4659.1 1525.85  4717.8 1522.84  4748.6 1519.52  4815.7 1519.43  4913.5 1515.48
  4927.5 1513.04  4949.8 1505.08  4986.2 1503.96  5010.8 1501.06  5011.3 1500.56
    5025 1501.06  5025.4 1502.06  5035.7 1503.88  5054.3 1505.99  5059.5 1505.58
  5076.9 1508.63  5095.9 1509.81    5101 1508.64  5118.1 1512.46  5128.4 1513.57
  5190.2 1518.16  5241.7 1519.85  5350.4 1520.95  5355.6 1520.11    5392 1520.68
  5438.7 1519.16  5480.3 1519.55  5543.4 1522.83  5653.5 1530.47  5797.1 1533.56
#Mann= 4 ,-1 , 0
  4659.1    .035       0  5010.8    .035       0    5025    .035       0
  5543.4     .07       0
Bank Sta=5010.8,5025
XS Rating Curve= 0 ,0
Exp/Cntr=0.3,0.1

Chan Stop Cuts=-1
Use User Specified Reach Order=0
Composite Channel Slope=5