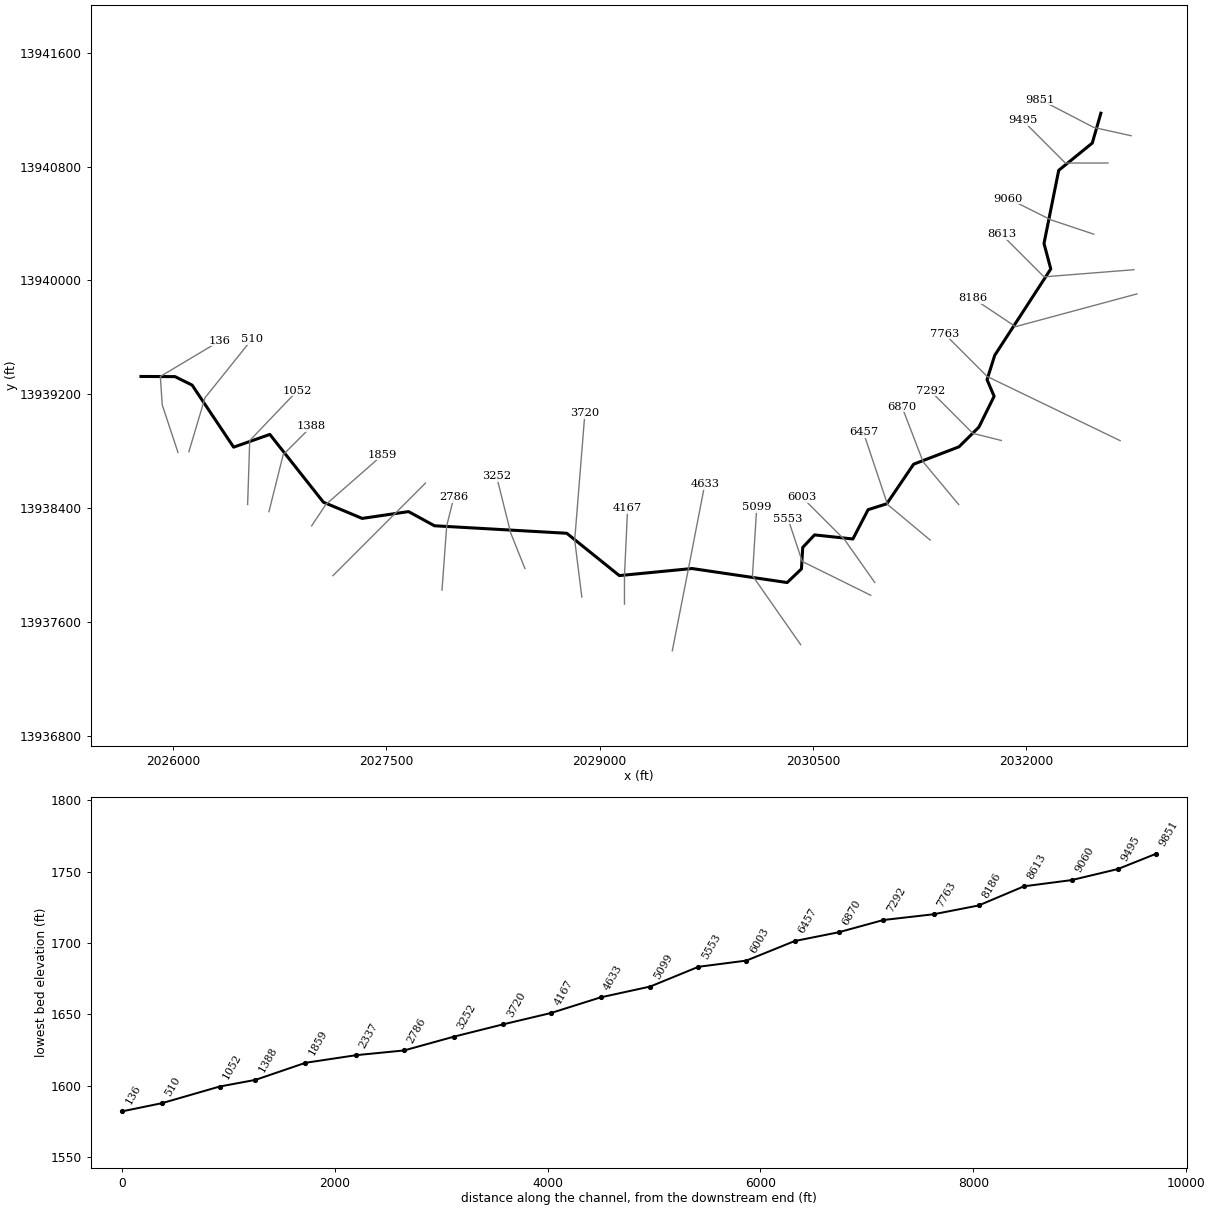
--- Stream0119_DS.prj (project) ---

Proj Title=Stream0119_DS Base Level Engineering
Current Plan=p01
Default Exp/Contr=0.3,0.1
English Units
Geom File=g01
Flow File=f01
Plan File=p01
BEGIN DESCRIPTION:
Stream0119_DS
END DESCRIPTION:

--- Stream0119_DS.p01 (plan) ---

Plan Title=Multiple Run
Short Identifier=Multiple
Geom File=g01
Flow File=f01
Subcritical Flow
K Sum by GR= 0
Std Step Tol= 0.01
Critical Tol= 0.01
Num of Std Step Trials= 20
Max Error Tol= 0.3
Flow Tol Ratio= 0.001
Split Flow NTrial= 30
Split Flow Tol= 0.02
Split Flow Ratio= 0.02
Log Output Level= 0
Friction Slope Method= 1
Unsteady Friction Slope Method= 2
Unsteady Bridges Friction Slope Method= 1
Parabolic Critical Depth
Global Vel Dist=  1 , 1 , 1
Global Log Level= 0
CheckData=True
Encroach Param= -1, 0, 0, 0
BEGIN DESCRIPTION:
Multiple Run
END DESCRIPTION:

--- Stream0119_DS.f01 (steady flow) ---

Flow Title=Multiple
Number of Profiles=7
Profile Names=10-year,25-year,50-year,1pct_min,100-year,1pct_plu,500-year
River Rch & RM= Stream0119_DS,Reach-1,9851
     498     819    1117     741    1479    2951    2568
River Rch & RM= Stream0119_DS,Reach-1,9495
     965    1651    2311    1569    3131    6248    5704
River Rch & RM= Stream0119_DS,Reach-1,4633
    1413    2468    3500    2406    4800    9578    8961
Boundary for River Rch & Prof#=Stream0119_DS,Reach-1,1
Up Type=0
Dn Type=3
Dn Slope=0.005
Boundary for River Rch & Prof#=Stream0119_DS,Reach-1,2
Up Type=0
Dn Type=3
Dn Slope=0.005
Boundary for River Rch & Prof#=Stream0119_DS,Reach-1,3
Up Type=0
Dn Type=3
Dn Slope=0.005
Boundary for River Rch & Prof#=Stream0119_DS,Reach-1,4
Up Type=0
Dn Type=3
Dn Slope=0.005
Boundary for River Rch & Prof#=Stream0119_DS,Reach-1,5
Up Type=0
Dn Type=3
Dn Slope=0.005
Boundary for River Rch & Prof#=Stream0119_DS,Reach-1,6
Up Type=0
Dn Type=3
Dn Slope=0.005
Boundary for River Rch & Prof#=Stream0119_DS,Reach-1,7
Up Type=0
Dn Type=3
Dn Slope=0.005

--- Stream0119_DS.g01 (geometry) ---

Geom Title=Existing Conditions

River Reach=Stream0119_DS,Reach-1
Reach XY= 30
      2032525.00     13941175.00      2032464.53     13940965.18
      2032228.54     13940773.54      2032125.09     13940259.61
      2032172.74     13940080.56      2031778.62     13939473.50
      2031724.63     13939302.19      2031774.39     13939185.63
      2031667.14     13938968.83      2031527.43     13938830.52
      2031208.32     13938708.36      2031019.55     13938430.25
      2030888.24     13938388.72      2030781.21     13938182.80
      2030511.59     13938211.48      2030428.54     13938123.56
      2030419.54     13937972.53      2030318.98     13937876.61
      2029650.08     13937975.20      2029138.86     13937925.54
      2028769.15     13938222.94      2027838.91     13938275.67
      2027656.57     13938375.19      2027330.52     13938327.35
      2027057.87     13938441.30      2026681.34     13938917.64
      2026426.62     13938828.12      2026134.71     13939264.25
      2026014.50     13939323.80      2025775.00     13939325.00

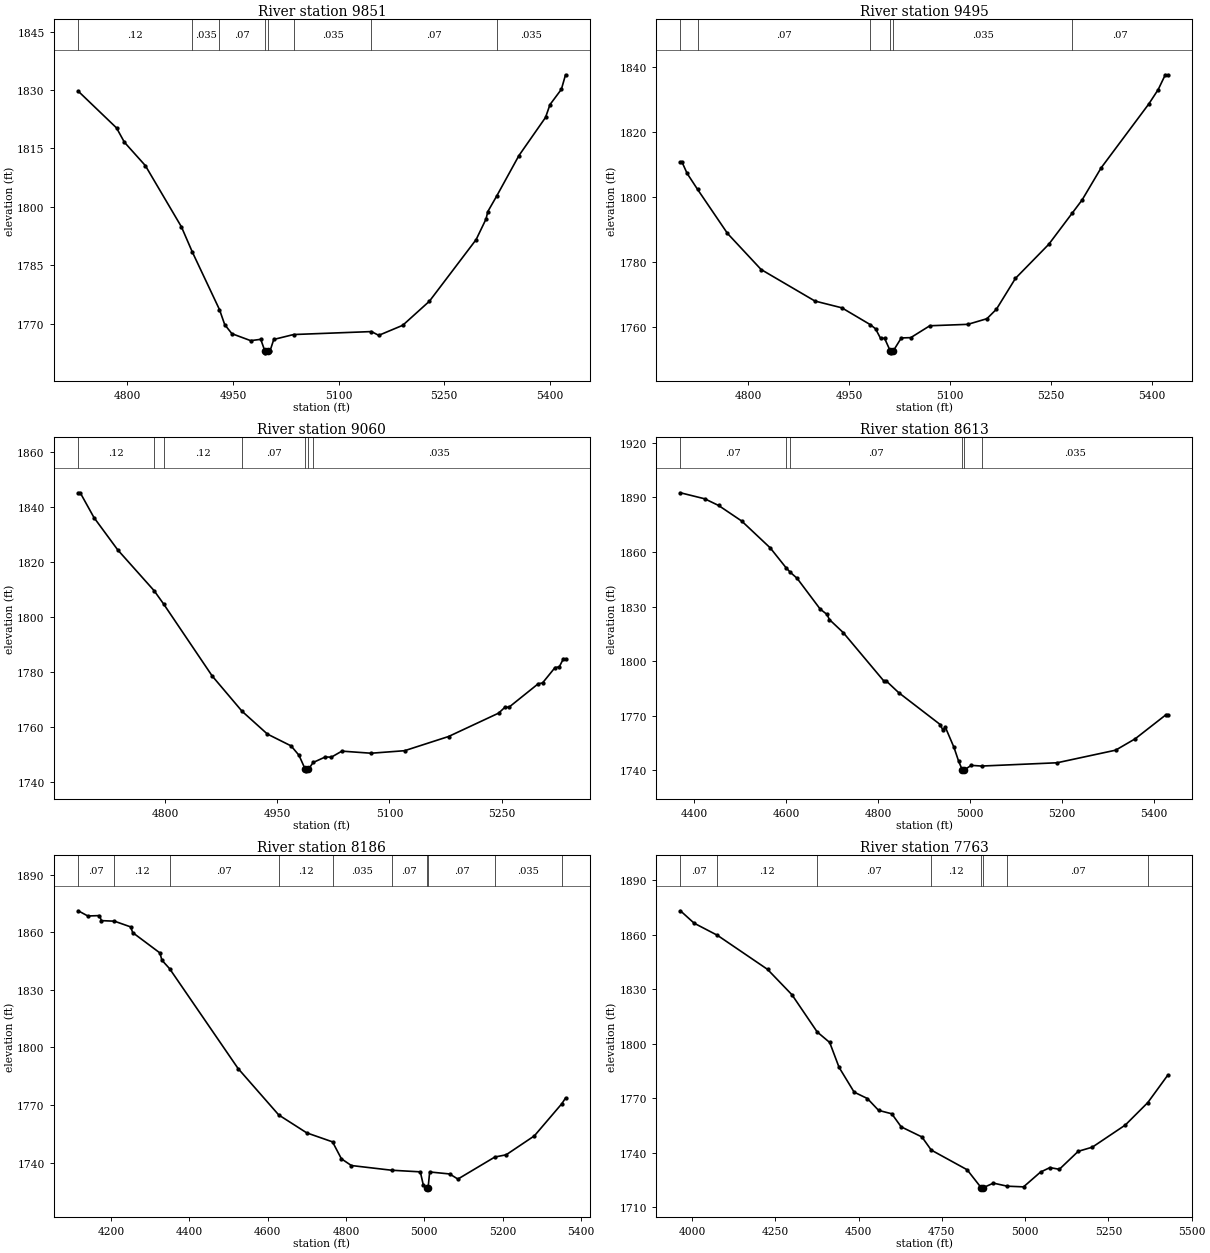
Type RM Length L Ch R = 1,9851,356,356,356
BEGIN DESCRIPTION:
Stream0119_DS 22.0
END DESCRIPTION:
XS GIS Cut Line= 3
      2032738.11     13941016.67      2032474.72     13941075.12
      2032099.77     13941269.85
#Sta/Elev= 30
  4730.2 1829.71  4784.6 1820.28  4795.8 1816.60  4825.6 1810.59  4876.8 1794.88
  4892.2 1788.45  4930.9 1773.62  4938.3 1769.77  4948.5 1767.44  4975.2 1765.65
  4989.5 1765.99  4995.3 1763.02  4995.5 1762.52  4999.3 1763.02  5002.7 1763.02
  5008.0 1765.96  5036.2 1767.22  5146.8 1767.98  5157.1 1767.01  5191.2 1769.59
  5229.1 1775.77  5295.5 1791.60  5309.6 1796.90  5312.0 1798.77  5324.7 1802.78
  5356.2 1813.15  5394.1 1822.97  5400.4 1826.26  5416.6 1830.19  5422.5 1833.92
#Mann=8,-1,0
  4730.2    0.12       0  4892.2   0.035       0  4930.9    0.07       0
  4995.3    0.05       0  4999.3    0.07       0  5036.2   0.035       0
  5146.8    0.07       0  5324.7   0.035       0
Bank Sta=4995.3,4999.3
Exp/Cntr=0.3,0.1

Type RM Length L Ch R = 1,9495,435,435,435
BEGIN DESCRIPTION:
Stream0119_DS 21.0
END DESCRIPTION:
XS GIS Cut Line= 3
      2032574.99     13940825.00      2032275.00     13940825.00
      2031974.97     13941125.03
#Sta/Elev= 30
  4699.5 1810.68  4702.0 1810.68  4709.5 1807.24  4725.0 1802.32  4769.5 1788.73
  4819.5 1777.60  4899.5 1767.88  4939.5 1765.79  4981.7 1760.61  4989.5 1759.33
  4997.0 1756.38  5003.0 1756.38  5011.6 1752.41  5011.9 1751.91  5015.6 1752.41
  5027.8 1756.50  5041.9 1756.60  5070.2 1760.26  5126.8 1760.70  5155.1 1762.44
  5169.2 1765.36  5197.5 1774.88  5247.0 1785.38  5281.9 1795.01  5296.5 1799.04
  5324.8 1808.94  5395.5 1828.61  5409.6 1833.08  5420.2 1837.66  5423.8 1837.66
#Mann=6,-1,0
  4699.5    0.12       0  4725.0    0.07       0  4981.7   0.035       0
  5011.6   0.035       0  5015.6   0.035       0  5281.9    0.07       0
Bank Sta=5011.6,5015.6
Exp/Cntr=0.3,0.1

Type RM Length L Ch R = 1,9060,447,447,447
BEGIN DESCRIPTION:
Stream0119_DS 20.0
END DESCRIPTION:
XS GIS Cut Line= 3
      2032475.05     13940324.98      2032175.00     13940425.00
      2031874.99     13940575.01
#Sta/Elev= 30
  4683.8 1845.21  4686.5 1845.21  4704.9 1836.19  4736.6 1824.47  4785.3 1809.63
  4797.9 1804.84  4863.0 1778.62  4902.9 1765.81  4936.8 1757.52  4968.5 1753.22
  4979.0 1749.83  4987.5 1744.66  4987.8 1744.16  4991.5 1744.66  4998.0 1747.20
  5014.1 1749.19  5022.4 1749.14  5036.4 1751.32  5075.5 1750.56  5120.3 1751.48
  5179.0 1756.63  5246.0 1765.13  5254.4 1767.26  5260.0 1767.31  5299.1 1775.83
  5304.7 1776.09  5321.5 1781.71  5327.1 1781.94  5332.7 1784.91  5335.5 1784.91
#Mann=7,-1,0
  4683.8    0.12       0  4785.3    0.07       0  4797.9    0.12       0
  4902.9    0.07       0  4987.5   0.035       0  4991.5    0.07       0
  4998.0   0.035       0
Bank Sta=4987.5,4991.5
Exp/Cntr=0.3,0.1

Type RM Length L Ch R = 1,8613,427,427,427
BEGIN DESCRIPTION:
Stream0119_DS 19.0
END DESCRIPTION:
XS GIS Cut Line= 3
      2032757.71     13940075.20      2032125.00     13940025.00
      2031824.98     13940325.02
#Sta/Elev= 30
  4370.6 1892.52  4423.5 1889.21  4453.6 1885.55  4503.7 1877.02  4565.9 1862.23
  4600.0 1851.41  4609.5 1848.83  4624.1 1845.58  4674.3 1828.67  4689.3 1825.69
  4694.3 1822.92  4724.4 1815.75  4812.7 1789.15  4817.7 1789.22  4844.8 1782.79
  4935.1 1765.25  4941.1 1762.11  4946.1 1763.95  4965.2 1752.63  4975.2 1745.12
  4983.2 1740.31  4983.5 1739.81  4987.2 1740.31  5002.8 1742.82  5025.0 1742.44
  5189.2 1744.24  5316.4 1751.16  5358.9 1757.41  5426.0 1770.65  5429.6 1770.65
#Mann=6,-1,0
  4370.6    0.07       0  4600.0    0.12       0  4609.5    0.07       0
  4983.2    0.05       0  4987.2    0.07       0  5025.0   0.035       0
Bank Sta=4983.2,4987.2
Exp/Cntr=0.3,0.1

Type RM Length L Ch R = 1,8186,423,423,423
BEGIN DESCRIPTION:
Stream0119_DS 18.0
END DESCRIPTION:
XS GIS Cut Line= 3
      2032778.59     13939905.06      2031925.00     13939675.00
      2031625.00     13939875.00
#Sta/Elev= 30
  4116.0 1871.15  4140.5 1868.44  4170.1 1868.64  4175.3 1866.02  4208.5 1865.73
  4250.0 1862.75  4255.1 1859.79  4324.6 1849.20  4329.8 1845.41  4349.5 1840.97
  4524.3 1789.01  4628.2 1764.82  4699.7 1755.50  4765.5 1750.82  4788.2 1742.00
  4813.6 1738.50  4916.3 1736.05  4989.7 1735.21  4997.5 1728.23  5005.6 1726.86
  5005.8 1726.36  5009.6 1726.86  5013.6 1735.15  5064.6 1734.11  5085.7 1731.45
  5180.1 1742.93  5208.9 1744.08  5281.0 1753.95  5351.5 1770.78  5360.6 1773.68
#Mann=10,-1,0
  4116.0    0.07       0  4208.5    0.12       0  4349.5    0.07       0
  4628.2    0.12       0  4765.5   0.035       0  4916.3    0.07       0
  5005.6    0.05       0  5009.6    0.07       0  5180.1   0.035       0
  5351.5    0.07       0
Bank Sta=5005.6,5009.6
Exp/Cntr=0.3,0.1

Type RM Length L Ch R = 1,7763,471,471,471
BEGIN DESCRIPTION:
Stream0119_DS 17.0
END DESCRIPTION:
XS GIS Cut Line= 3
      2032660.58     13938873.80      2031725.00     13939325.00
      2031424.97     13939625.03
#Sta/Elev= 30
  3965.1 1873.32  4006.3 1866.49  4076.3 1859.81  4226.6 1841.07  4300.2 1827.04
  4375.8 1806.59  4413.3 1800.80  4441.5 1787.08  4486.7 1773.45  4526.4 1769.94
  4560.1 1763.42  4599.7 1761.53  4627.9 1754.34  4690.2 1748.77  4718.1 1741.56
  4825.9 1730.71  4868.6 1720.70  4868.8 1720.20  4872.6 1720.70  4904.8 1723.35
  4946.2 1721.66  4995.3 1721.29  5046.2 1729.43  5074.5 1731.90  5102.8 1730.96
  5159.4 1740.86  5201.8 1743.15  5300.8 1755.34  5368.4 1767.72  5428.1 1782.76
#Mann=8,-1,0
  3965.1    0.07       0  4076.3    0.12       0  4375.8    0.07       0
  4718.1    0.12       0  4868.6    0.05       0  4872.6    0.12       0
  4946.2    0.07       0  5368.4   0.035       0
Bank Sta=4868.6,4872.6
Exp/Cntr=0.3,0.1

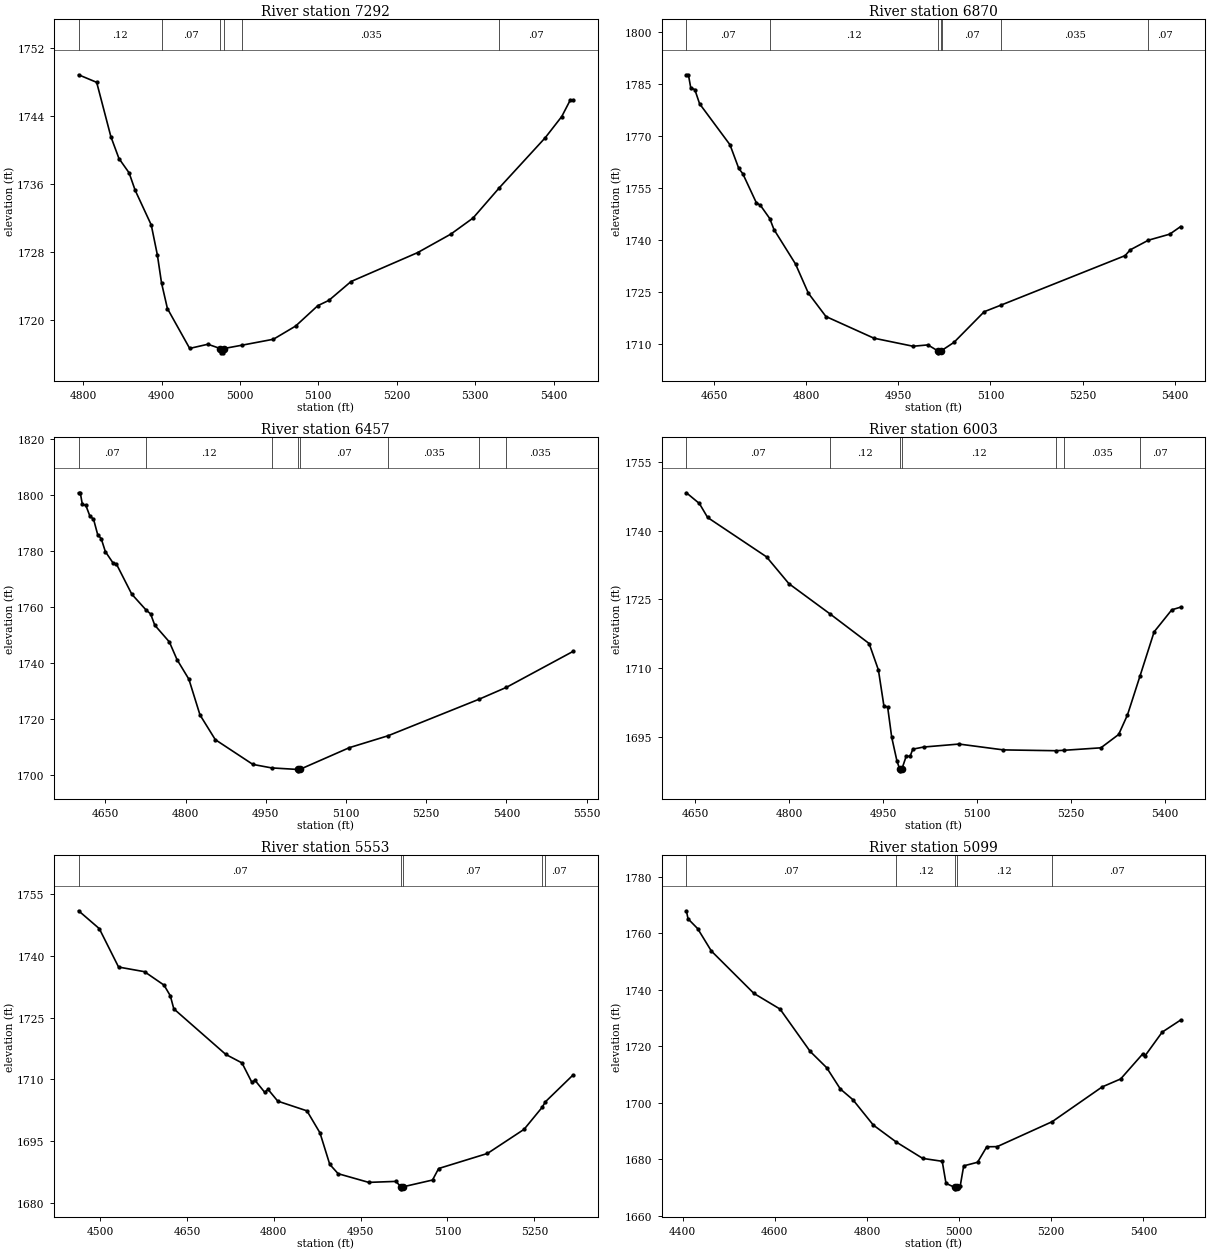
Type RM Length L Ch R = 1,7292,422,422,422
BEGIN DESCRIPTION:
Stream0119_DS 16.0
END DESCRIPTION:
XS GIS Cut Line= 3
      2031824.96     13938875.01      2031625.00     13938925.00
      2031324.98     13939225.02
#Sta/Elev= 30
  4794.2 1748.89  4817.3 1748.00  4835.4 1741.61  4845.7 1739.04  4858.6 1737.36
  4866.3 1735.32  4886.9 1731.22  4894.7 1727.69  4900.0 1724.40  4907.5 1721.39
  4935.9 1716.70  4959.1 1717.19  4975.1 1716.68  4975.4 1716.18  4978.9 1716.18
  4979.1 1716.68  5003.2 1717.09  5042.7 1717.78  5071.0 1719.33  5099.3 1721.73
  5113.4 1722.35  5141.7 1724.57  5226.6 1727.97  5269.0 1730.15  5297.3 1732.04
  5331.0 1735.62  5389.2 1741.47  5410.4 1743.98  5421.0 1745.87  5424.6 1745.87
#Mann=6,-1,0
  4794.2    0.12       0  4900.0    0.07       0  4975.1    0.05       0
  4979.1    0.07       0  5003.2   0.035       0  5331.0    0.07       0
Bank Sta=4975.1,4979.1
Exp/Cntr=0.3,0.1

Type RM Length L Ch R = 1,6870,413,413,413
BEGIN DESCRIPTION:
Stream0119_DS 15.0
END DESCRIPTION:
XS GIS Cut Line= 3
      2031525.03     13938424.97      2031275.00     13938725.00
      2031126.47     13939111.70
#Sta/Elev= 30
  4604.9 1787.79  4608.2 1787.79  4612.1 1783.95  4618.6 1783.53  4626.4 1779.43
  4675.9 1767.59  4690.2 1760.76  4696.7 1759.26  4718.8 1750.86  4725.4 1750.12
  4740.6 1746.32  4747.5 1743.14  4782.6 1733.19  4803.5 1724.77  4832.1 1718.04
  4910.2 1711.79  4974.0 1709.46  4998.1 1709.85  5014.9 1708.06  5015.1 1707.56
  5018.9 1708.06  5021.1 1708.30  5040.5 1710.57  5089.8 1719.43  5117.3 1721.34
  5319.2 1735.61  5327.5 1737.27  5357.1 1740.06  5391.8 1741.80  5409.7 1744.01
#Mann=7,-1,0
  4604.9    0.07       0  4740.6    0.12       0  5014.9    0.05       0
  5018.9    0.12       0  5021.1    0.07       0  5117.3   0.035       0
  5357.1    0.07       0
Bank Sta=5014.9,5018.9
Exp/Cntr=0.3,0.1

Type RM Length L Ch R = 1,6457,454,454,454
BEGIN DESCRIPTION:
Stream0119_DS 14.0
END DESCRIPTION:
XS GIS Cut Line= 3
      2031324.96     13938175.03      2031025.00     13938425.00
      2030855.46     13938931.41
#Sta/Elev= 30
  4600.0 1800.92  4603.2 1800.92  4607.1 1796.74  4613.6 1796.42  4621.4 1792.45
  4627.9 1791.53  4635.8 1785.91  4642.3 1784.53  4650.1 1779.87  4664.4 1775.82
  4670.9 1775.38  4699.5 1764.64  4726.5 1758.91  4734.7 1757.58  4742.5 1753.54
  4769.8 1747.54  4784.1 1741.23  4806.3 1734.21  4827.1 1721.41  4855.7 1712.57
  4926.0 1703.71  4961.0 1702.46  5009.6 1701.91  5009.8 1701.41  5013.6 1701.91
  5106.5 1709.71  5178.8 1713.96  5349.8 1727.10  5400.1 1731.28  5524.5 1744.12
#Mann=8,-1,0
  4600.0    0.07       0  4726.5    0.12       0  4961.0    0.07       0
  5009.6    0.05       0  5013.6    0.07       0  5178.8   0.035       0
  5349.8    0.07       0  5400.1   0.035       0
Bank Sta=5009.6,5013.6
Exp/Cntr=0.3,0.1

Type RM Length L Ch R = 1,6003,450,450,450
BEGIN DESCRIPTION:
Stream0119_DS 13.0
END DESCRIPTION:
XS GIS Cut Line= 3
      2030934.84     13937877.29      2030725.00     13938175.00
      2030424.99     13938475.01
#Sta/Elev= 30
  4636.3 1748.22  4657.0 1745.89  4670.2 1742.84  4764.1 1734.28  4799.8 1728.44
  4865.2 1721.88  4927.8 1715.41  4942.6 1709.66  4951.3 1701.90  4957.4 1701.53
  4963.8 1695.02  4972.2 1689.83  4976.3 1688.20  4976.6 1687.70  4980.3 1688.20
  4987.0 1690.90  4993.1 1690.85  4997.5 1692.42  5014.7 1692.88  5071.2 1693.53
  5141.9 1692.26  5225.1 1692.08  5238.5 1692.17  5297.5 1692.71  5325.8 1695.61
  5339.9 1699.87  5359.9 1708.34  5382.4 1717.95  5410.6 1722.75  5424.8 1723.33
#Mann=7,-1,0
  4636.3    0.07       0  4865.2    0.12       0  4976.3    0.05       0
  4980.3    0.12       0  5225.1    0.07       0  5238.5   0.035       0
  5359.9    0.07       0
Bank Sta=4976.3,4980.3
Exp/Cntr=0.3,0.1

Type RM Length L Ch R = 1,5553,454,454,454
BEGIN DESCRIPTION:
Stream0119_DS 12.0
END DESCRIPTION:
XS GIS Cut Line= 3
      2030907.11     13937786.99      2030425.00     13938025.00
      2030325.00     13938325.01
#Sta/Elev= 30
  4462.7 1750.96  4498.5 1746.62  4531.8 1737.28  4576.6 1736.15  4610.3 1732.89
  4621.2 1730.29  4627.2 1727.12  4717.0 1716.04  4745.0 1713.97  4761.9 1709.29
  4767.5 1709.74  4784.3 1706.82  4789.9 1707.56  4806.8 1704.68  4857.2 1702.32
  4879.7 1696.97  4896.6 1689.31  4911.1 1687.04  4963.9 1684.93  5010.9 1685.17
  5019.4 1683.86  5019.7 1683.36  5023.4 1683.86  5074.1 1685.50  5084.7 1688.30
  5169.0 1691.96  5232.3 1697.83  5263.4 1703.16  5269.1 1704.52  5316.6 1711.00
#Mann=5,-1,0
  4462.7    0.07       0  5019.4    0.05       0  5023.4    0.07       0
  5263.4   0.035       0  5269.1    0.07       0
Bank Sta=5019.4,5023.4
Exp/Cntr=0.3,0.1

Type RM Length L Ch R = 1,5099,466,466,466
BEGIN DESCRIPTION:
Stream0119_DS 11.0
END DESCRIPTION:
XS GIS Cut Line= 3
      2030413.99     13937439.82      2030075.00     13937925.00
      2030104.99     13938405.09
#Sta/Elev= 30
  4408.1 1768.05  4411.7 1765.20  4432.5 1761.74  4462.3 1753.79  4554.7 1738.76
  4611.4 1733.21  4676.8 1718.20  4712.6 1712.44  4742.3 1704.88  4769.3 1701.13
  4813.8 1692.10  4863.8 1686.07  4921.0 1680.29  4963.4 1679.26  4971.6 1671.45
  4990.6 1670.00  4990.8 1669.50  4994.6 1670.00  5002.5 1670.55  5010.0 1677.64
  5040.1 1678.92  5060.1 1684.41  5082.7 1684.46  5202.1 1693.31  5310.6 1705.63
  5350.7 1708.45  5398.4 1717.29  5403.4 1716.59  5440.8 1725.04  5481.0 1729.34
#Mann=5,-1,0
  4408.1    0.07       0  4863.8    0.12       0  4990.6    0.05       0
  4994.6    0.12       0  5202.1    0.07       0
Bank Sta=4990.6,4994.6
Exp/Cntr=0.3,0.1

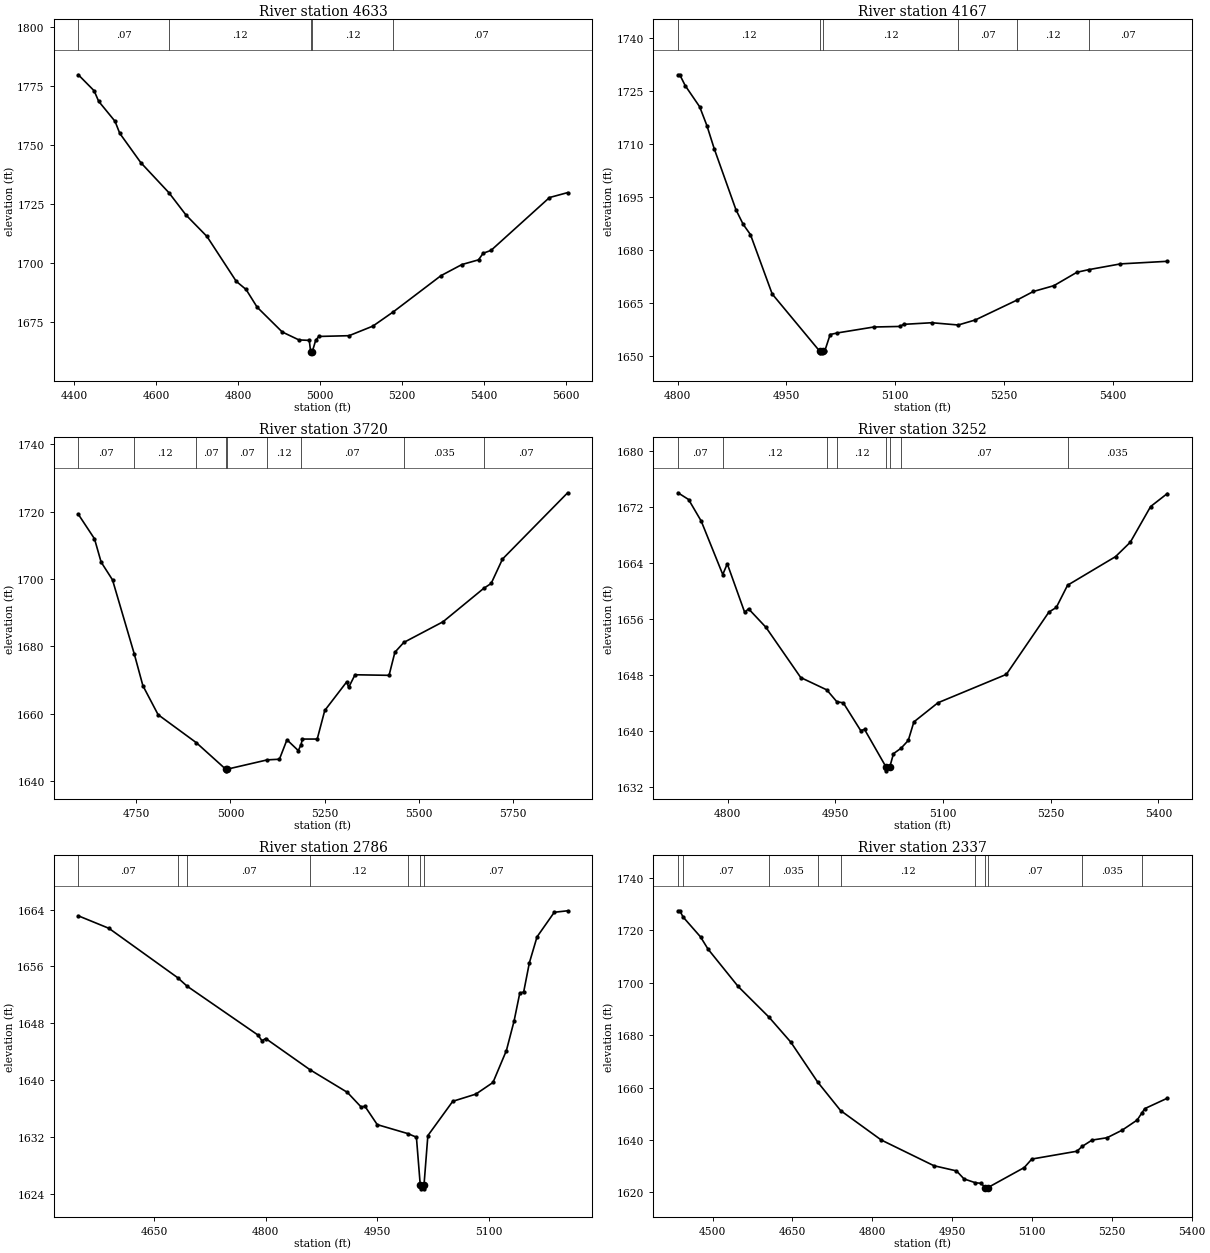
Type RM Length L Ch R = 1,4633,466,466,466
BEGIN DESCRIPTION:
Stream0119_DS 10.0
END DESCRIPTION:
XS GIS Cut Line= 3
      2029511.25     13937397.09      2029625.00     13937975.00
      2029739.96     13938568.46
#Sta/Elev= 30
  4410.6 1779.81  4449.2 1773.02  4460.2 1768.57  4500.2 1760.07  4511.6 1755.00
  4563.0 1742.56  4631.5 1729.82  4673.5 1720.29  4724.4 1711.25  4795.8 1692.23
  4819.8 1688.77  4846.7 1681.28  4907.9 1670.76  4948.6 1667.39  4973.9 1667.19
  4977.2 1662.41  4977.4 1661.91  4981.3 1662.41  4989.4 1667.16  4997.1 1668.86
  5070.9 1669.18  5129.0 1673.24  5179.1 1679.32  5295.0 1694.62  5346.2 1699.35
  5386.7 1701.34  5398.0 1704.14  5417.2 1705.35  5559.8 1727.76  5604.1 1729.85
#Mann=5,-1,0
  4410.6    0.07       0  4631.5    0.12       0  4977.2    0.05       0
  4981.3    0.12       0  5179.1    0.07       0
Bank Sta=4977.2,4981.3
Exp/Cntr=0.3,0.1

Type RM Length L Ch R = 1,4167,447,447,447
BEGIN DESCRIPTION:
Stream0119_DS 9.0
END DESCRIPTION:
XS GIS Cut Line= 3
      2029175.00     13937724.97      2029175.00     13937925.00
      2029197.15     13938399.56
#Sta/Elev= 30
  4800.4 1729.54  4802.9 1729.54  4810.4 1726.48  4830.4 1720.48  4840.4 1715.13
  4850.4 1708.66  4880.4 1691.40  4890.4 1687.26  4900.4 1684.38  4930.4 1667.59
  4995.8 1651.45  4996.1 1650.95  4999.7 1650.95  5000.0 1651.45  5002.9 1651.45
  5010.4 1656.13  5020.4 1656.58  5070.5 1658.25  5106.6 1658.41  5111.6 1659.00
  5150.6 1659.46  5187.1 1658.82  5210.7 1660.25  5268.2 1665.87  5290.7 1668.29
  5319.0 1669.93  5350.8 1673.72  5366.8 1674.45  5410.9 1676.09  5475.5 1676.82
#Mann=6,-1,0
  4800.4    0.12       0  4995.8    0.05       0  5000.0    0.12       0
  5187.1    0.07       0  5268.2    0.12       0  5366.8    0.07       0
Bank Sta=4995.8,5000
Exp/Cntr=0.3,0.1

Type RM Length L Ch R = 1,3720,468,468,468
BEGIN DESCRIPTION:
Stream0119_DS 8.0
END DESCRIPTION:
XS GIS Cut Line= 3
      2028875.00     13937774.98      2028825.00     13938175.00
      2028896.65     13939067.39
#Sta/Elev= 30
  4596.5 1719.26  4639.4 1711.98  4657.0 1705.06  4687.2 1699.78  4745.2 1677.68
  4767.8 1668.35  4808.2 1659.73  4909.3 1651.44  4987.5 1643.55  4987.8 1643.05
  4991.7 1643.55  5098.0 1646.31  5130.1 1646.50  5150.1 1652.27  5180.2 1649.06
  5187.2 1650.78  5191.2 1652.49  5230.4 1652.49  5250.4 1660.98  5308.8 1669.50
  5313.8 1667.83  5330.7 1671.59  5421.0 1671.42  5436.5 1678.28  5460.1 1681.19
  5564.2 1687.33  5672.1 1697.25  5691.9 1698.71  5722.0 1705.96  5894.9 1725.65
#Mann=9,-1,0
  4596.5    0.07       0  4745.2    0.12       0  4909.3    0.07       0
  4987.5    0.05       0  4991.7    0.07       0  5098.0    0.12       0
  5187.2    0.07       0  5460.1   0.035       0  5672.1    0.07       0
Bank Sta=4987.5,4991.7
Exp/Cntr=0.3,0.1

Type RM Length L Ch R = 1,3252,466,466,466
BEGIN DESCRIPTION:
Stream0119_DS 7.0
END DESCRIPTION:
XS GIS Cut Line= 3
      2028475.01     13937974.96      2028375.00     13938225.00
      2028275.00     13938624.99
#Sta/Elev= 30
  4730.8 1673.98  4745.6 1673.02  4763.2 1669.94  4793.2 1662.32  4799.5 1663.85
  4823.7 1656.93  4829.1 1657.43  4853.4 1654.78  4901.8 1647.62  4938.1 1645.86
  4952.1 1644.17  4961.1 1644.01  4985.3 1640.06  4990.7 1640.22  5020.9 1634.81
  5021.2 1634.31  5025.7 1634.81  5031.0 1636.76  5041.6 1637.54  5051.6 1638.65
  5059.4 1641.29  5092.9 1644.02  5188.2 1648.07  5247.5 1656.96  5257.8 1657.62
  5273.5 1660.79  5340.3 1664.87  5360.9 1666.93  5389.2 1672.02  5412.4 1673.87
#Mann=8,-1,0
  4730.8    0.07       0  4793.2    0.12       0  4938.1    0.07       0
  4952.1    0.12       0  5020.9    0.05       0  5025.7    0.12       0
  5041.6    0.07       0  5273.5   0.035       0
Bank Sta=5020.9,5025.7
Exp/Cntr=0.3,0.1

Type RM Length L Ch R = 1,2786,449,449,449
BEGIN DESCRIPTION:
Stream0119_DS 6.0
END DESCRIPTION:
XS GIS Cut Line= 3
      2027891.88     13937823.92      2027925.00     13938275.00
      2027974.99     13938474.95
#Sta/Elev= 30
  4547.8 1663.12  4589.0 1661.36  4681.5 1654.41  4694.0 1653.23  4789.5 1646.34
  4794.9 1645.54  4799.9 1645.85  4859.6 1641.45  4909.8 1638.27  4928.4 1636.20
  4933.4 1636.32  4950.0 1633.73  4991.0 1632.47  5002.7 1631.96  5007.9 1625.19
  5008.3 1624.69  5012.5 1624.69  5012.9 1625.19  5018.1 1632.18  5051.6 1637.01
  5082.6 1638.02  5105.7 1639.66  5123.8 1644.16  5134.1 1648.31  5141.8 1652.25
  5147.0 1652.39  5154.7 1656.51  5165.0 1660.16  5188.2 1663.62  5206.2 1663.83
#Mann=7,-1,0
  4547.8    0.07       0  4681.5   0.035       0  4694.0    0.07       0
  4859.6    0.12       0  4991.0    0.07       0  5007.9    0.05       0
  5012.9    0.07       0
Bank Sta=5007.9,5012.9
Exp/Cntr=0.3,0.1

Type RM Length L Ch R = 1,2337,478,478,478
BEGIN DESCRIPTION:
Stream0119_DS 5.0
END DESCRIPTION:
XS GIS Cut Line= 3
      2027125.02     13937925.02      2027525.00     13938325.00
      2027774.99     13938574.99
#Sta/Elev= 30
  4434.9 1727.46  4438.4 1727.46  4444.5 1725.09  4477.3 1717.50  4491.4 1712.84
  4548.0 1698.58  4605.8 1686.90  4647.0 1677.32  4697.3 1662.14  4740.4 1651.25
  4816.7 1640.03  4915.7 1630.21  4958.1 1628.23  4972.3 1625.17  4993.4 1623.73
  5004.1 1623.50  5012.2 1621.89  5012.6 1621.39  5017.3 1621.89  5085.4 1629.51
  5099.6 1632.75  5184.4 1635.74  5194.1 1637.56  5212.7 1639.98  5241.0 1640.89
  5269.3 1643.77  5297.5 1647.63  5305.7 1650.14  5311.7 1651.98  5354.1 1655.96
#Mann=10,-1,0
  4434.9   0.035       0  4444.5    0.07       0  4605.8   0.035       0
  4697.3    0.07       0  4740.4    0.12       0  4993.4    0.07       0
  5012.2    0.05       0  5017.3    0.07       0  5194.1   0.035       0
  5305.7    0.07       0
Bank Sta=5012.2,5017.3
Exp/Cntr=0.3,0.1

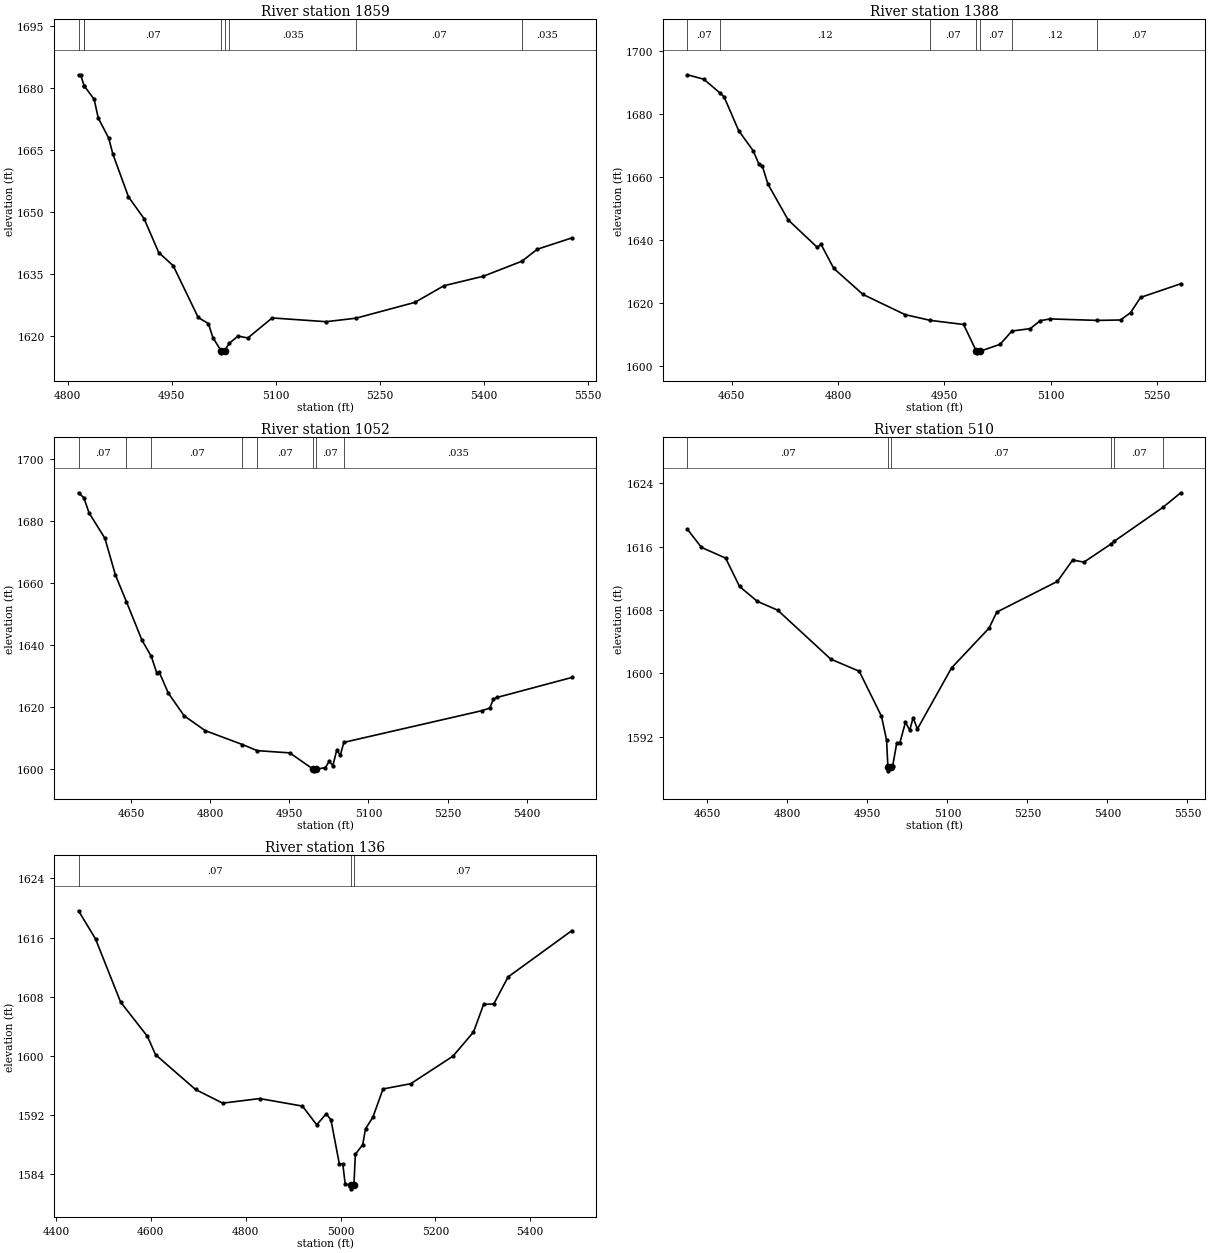
Type RM Length L Ch R = 1,1859,471,471,471
BEGIN DESCRIPTION:
Stream0119_DS 4.0
END DESCRIPTION:
XS GIS Cut Line= 3
      2026975.01     13938275.02      2027075.00     13938425.00
      2027475.03     13938775.02
#Sta/Elev= 30
  4815.4 1683.17  4818.4 1683.17  4823.6 1680.47  4823.8 1680.44  4837.9 1677.26
  4843.9 1672.72  4858.9 1667.89  4865.0 1664.00  4887.5 1653.68  4910.0 1648.43
  4931.1 1640.25  4952.1 1637.04  4988.1 1624.56  5002.8 1623.08  5009.4 1619.67
  5021.1 1616.52  5021.5 1616.02  5026.2 1616.52  5032.6 1618.28  5045.5 1620.07
  5059.7 1619.61  5094.8 1624.45  5172.7 1623.54  5215.8 1624.39  5300.8 1628.21
  5342.6 1632.22  5399.5 1634.52  5455.2 1638.15  5477.3 1641.04  5527.2 1643.77
#Mann=8,-1,0
  4815.4    0.07       0  4823.6    0.12       0  4823.8    0.07       0
  5021.1    0.05       0  5026.2    0.07       0  5032.6   0.035       0
  5215.8    0.07       0  5455.2   0.035       0
Bank Sta=5021.1,5026.2
Exp/Cntr=0.3,0.1

Type RM Length L Ch R = 1,1388,336,336,336
BEGIN DESCRIPTION:
Stream0119_DS 3.0
END DESCRIPTION:
XS GIS Cut Line= 3
      2026674.99     13938374.97      2026775.00     13938775.00
      2026975.01     13938975.01
#Sta/Elev= 30
  4587.9 1692.41  4611.1 1690.99  4633.9 1686.60  4639.5 1685.42  4660.1 1674.66
  4680.7 1668.21  4688.4 1664.13  4693.6 1663.29  4701.3 1657.68  4729.7 1646.32
  4770.9 1637.55  4776.1 1638.55  4794.1 1630.87  4835.3 1622.59  4894.6 1616.18
  4930.1 1614.35  4977.1 1613.04  4995.1 1604.53  4995.5 1604.03  5000.2 1604.53
  5028.5 1606.74  5045.2 1610.96  5071.0 1611.73  5085.1 1614.26  5099.2 1614.81
  5165.4 1614.34  5198.2 1614.47  5212.4 1616.81  5226.5 1621.64  5283.1 1625.99
#Mann=7,-1,0
  4587.9    0.07       0  4633.9    0.12       0  4930.1    0.07       0
  4995.1    0.05       0  5000.2    0.07       0  5045.2    0.12       0
  5165.4    0.07       0
Bank Sta=4995.1,5000.2
Exp/Cntr=0.3,0.1

Type RM Length L Ch R = 1,1052,542,542,542
BEGIN DESCRIPTION:
Stream0119_DS 2.0
END DESCRIPTION:
XS GIS Cut Line= 3
      2026525.00     13938425.00      2026539.88     13938874.25
      2026875.00     13939225.00
#Sta/Elev= 30
  4550.8 1689.05  4560.8 1687.46  4570.8 1682.56  4600.8 1674.37  4620.8 1662.49
  4641.5 1653.96  4670.9 1641.55  4688.6 1636.31  4698.9 1631.04  4703.9 1631.10
  4720.9 1624.45  4750.9 1617.12  4790.9 1612.34  4861.2 1607.87  4889.5 1605.89
  4951.0 1605.17  4995.6 1599.88  4996.0 1599.38  5000.8 1599.88  5018.5 1600.43
  5025.7 1602.45  5032.7 1601.05  5039.9 1605.99  5046.8 1604.47  5053.5 1608.56
  5315.7 1618.81  5329.9 1619.65  5336.8 1622.49  5344.0 1623.06  5485.4 1629.49
#Mann=8,-1,0
  4550.8    0.07       0  4641.5    0.12       0  4688.6    0.07       0
  4861.2    0.12       0  4889.5    0.07       0  4995.6    0.05       0
  5000.8    0.07       0  5053.5   0.035       0
Bank Sta=4995.6,5000.8
Exp/Cntr=0.3,0.1

Type RM Length L Ch R = 1,510,374,374,374
BEGIN DESCRIPTION:
Stream0119_DS 1.0
END DESCRIPTION:
XS GIS Cut Line= 3
      2026112.06     13938796.38      2026225.00     13939175.00
      2026556.54     13939588.11
#Sta/Elev= 30
  4612.6 1618.20  4638.8 1615.92  4684.2 1614.56  4710.3 1610.98  4743.5 1609.11
  4781.8 1607.99  4881.3 1601.81  4934.7 1600.28  4976.4 1594.59  4985.9 1591.60
  4988.4 1588.21  4988.8 1587.71  4993.8 1588.21  4997.3 1588.30  5005.1 1591.26
  5010.9 1591.26  5021.3 1593.85  5029.3 1592.84  5035.7 1594.42  5043.7 1592.99
  5107.7 1600.70  5178.1 1605.73  5192.5 1607.75  5306.1 1611.62  5334.9 1614.33
  5355.8 1614.05  5407.0 1616.36  5412.9 1616.70  5504.0 1620.97  5537.4 1622.81
#Mann=6,-1,0
  4612.6    0.07       0  4988.4    0.05       0  4993.8    0.07       0
  5407.0   0.035       0  5412.9    0.07       0  5504.0   0.035       0
Bank Sta=4988.4,4993.8
Exp/Cntr=0.3,0.1

Type RM Length L Ch R = 1,136,0,0,0
BEGIN DESCRIPTION:
Stream0119_DS 0.0
END DESCRIPTION:
XS GIS Cut Line= 4
      2026035.24     13938790.81      2025924.46     13939125.85
      2025911.38     13939325.04      2026330.37     13939574.85
#Sta/Elev= 30
  4447.5 1619.63  4483.5 1615.80  4536.2 1607.28  4592.8 1602.63  4609.9 1600.15
  4694.2 1595.44  4751.5 1593.59  4829.6 1594.21  4919.8 1593.19  4949.8 1590.65
  4969.9 1592.15  4979.9 1591.31  4997.5 1585.36  5004.8 1585.36  5009.9 1582.61
  5022.7 1582.49  5023.1 1581.99  5028.2 1582.49  5031.3 1586.66  5046.8 1587.98
  5052.7 1590.11  5068.3 1591.70  5089.7 1595.51  5148.1 1596.22  5237.1 1599.95
  5280.4 1603.21  5301.8 1606.96  5323.2 1607.02  5353.5 1610.68  5487.8 1616.94
#Mann=3,-1,0
  4447.5    0.07       0  5022.7    0.05       0  5028.2    0.07       0
Bank Sta=5022.7,5028.2
Exp/Cntr=0.3,0.1

Chan Stop Cuts=-1