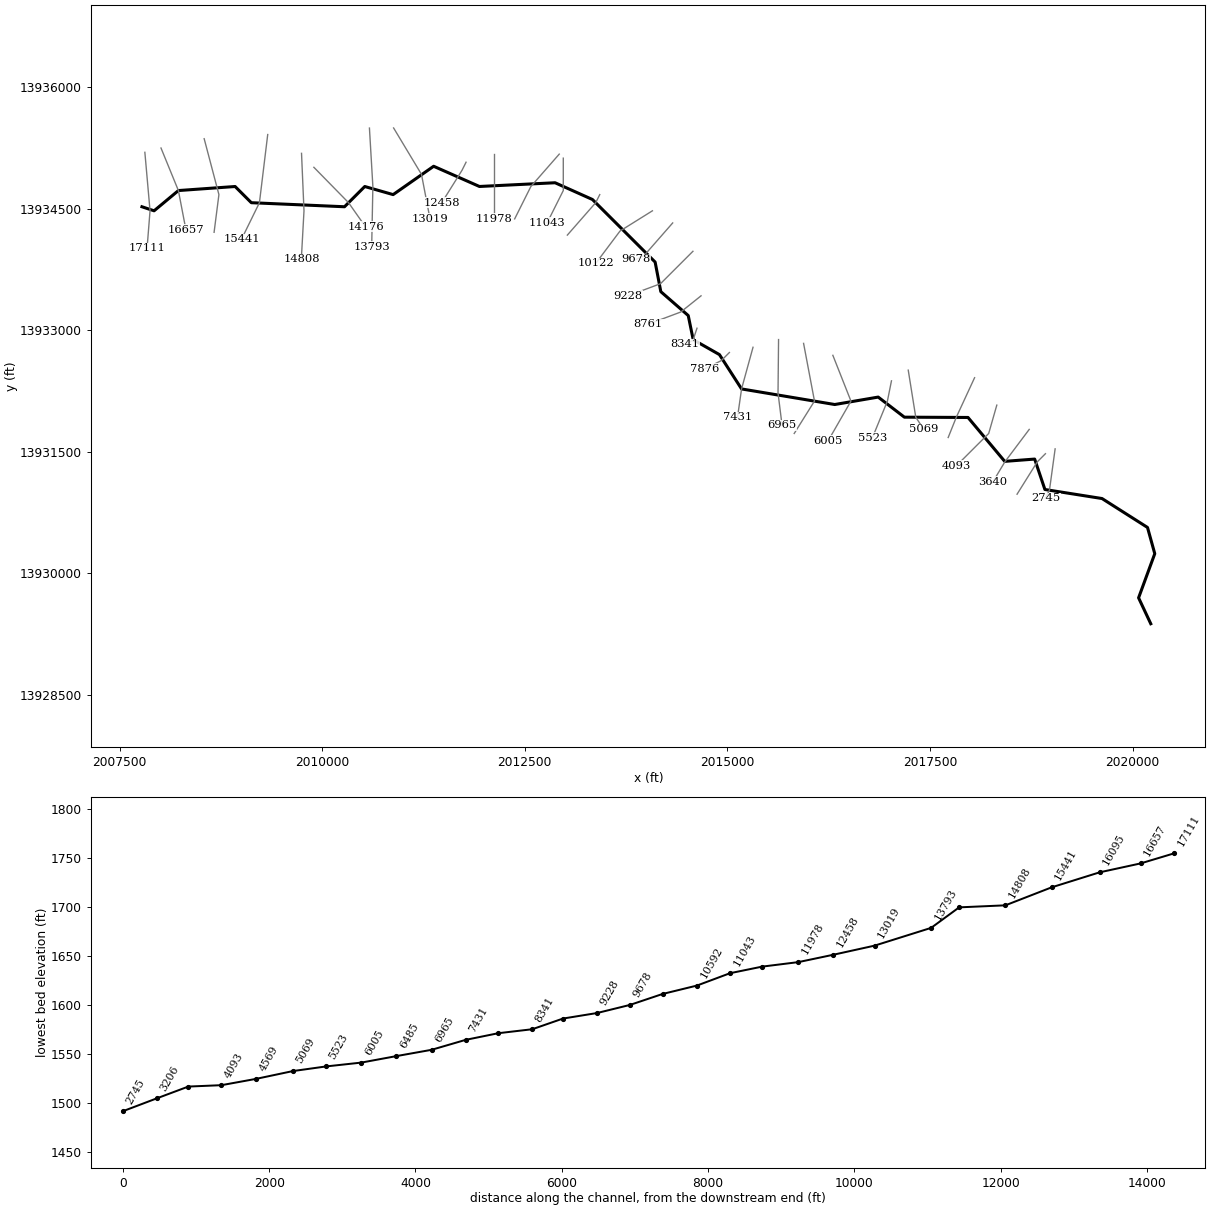
--- Stream0120_DS.prj (project) ---

Proj Title=Stream0120_DS Base Level Engineering
Current Plan=p01
Default Exp/Contr=0.3,0.1
English Units
Geom File=g01
Flow File=f01
Plan File=p01
BEGIN DESCRIPTION:
Stream0120_DS
END DESCRIPTION:

--- Stream0120_DS.p01 (plan) ---

Plan Title=Multiple Run
Short Identifier=Multiple
Geom File=g01
Flow File=f01
Subcritical Flow
K Sum by GR= 0
Std Step Tol= 0.01
Critical Tol= 0.01
Num of Std Step Trials= 20
Max Error Tol= 0.3
Flow Tol Ratio= 0.001
Split Flow NTrial= 30
Split Flow Tol= 0.02
Split Flow Ratio= 0.02
Log Output Level= 0
Friction Slope Method= 1
Unsteady Friction Slope Method= 2
Unsteady Bridges Friction Slope Method= 1
Parabolic Critical Depth
Global Vel Dist=  1 , 1 , 1
Global Log Level= 0
CheckData=True
Encroach Param= -1, 0, 0, 0
BEGIN DESCRIPTION:
Multiple Run
END DESCRIPTION:

--- Stream0120_DS.f01 (steady flow) ---

Flow Title=Multiple
Number of Profiles=7
Profile Names=10-year,25-year,50-year,1pct_min,100-year,1pct_plu,500-year
River Rch & RM= Stream0120_DS,Reach-1,17111
     531     882    1211     811    1617    3227    2853
River Rch & RM= Stream0120_DS,Reach-1,16095
    1195    2085    2958    2036    4062    8105    7601
River Rch & RM= Stream0120_DS,Reach-1,12458
    1462    2570    3662    2530    5048   10071    9516
River Rch & RM= Stream0120_DS,Reach-1,7431
    2485    4473    6474    4533    9045   18047   17534
Boundary for River Rch & Prof#=Stream0120_DS,Reach-1,1
Up Type=0
Dn Type=3
Dn Slope=0.005
Boundary for River Rch & Prof#=Stream0120_DS,Reach-1,2
Up Type=0
Dn Type=3
Dn Slope=0.005
Boundary for River Rch & Prof#=Stream0120_DS,Reach-1,3
Up Type=0
Dn Type=3
Dn Slope=0.005
Boundary for River Rch & Prof#=Stream0120_DS,Reach-1,4
Up Type=0
Dn Type=3
Dn Slope=0.005
Boundary for River Rch & Prof#=Stream0120_DS,Reach-1,5
Up Type=0
Dn Type=3
Dn Slope=0.005
Boundary for River Rch & Prof#=Stream0120_DS,Reach-1,6
Up Type=0
Dn Type=3
Dn Slope=0.005
Boundary for River Rch & Prof#=Stream0120_DS,Reach-1,7
Up Type=0
Dn Type=3
Dn Slope=0.005

--- Stream0120_DS.g01 (geometry) ---

Geom Title=Existing Conditions

River Reach=Stream0120_DS,Reach-1
Reach XY= 30
      2007775.00     13934525.00      2007925.00     13934475.00
      2008225.00     13934725.00      2008925.00     13934775.00
      2009125.00     13934575.00      2010275.00     13934525.00
      2010525.00     13934775.00      2010875.00     13934675.00
      2011375.00     13935025.00      2011940.16     13934775.38
      2012873.53     13934821.45      2013334.80     13934614.52
      2014108.37     13933841.71      2014178.54     13933476.46
      2014516.98     13933181.34      2014578.07     13932883.30
      2014902.14     13932698.84      2015175.00     13932275.00
      2016325.00     13932082.56      2016861.08     13932174.32
      2017184.58     13931926.20      2017969.48     13931922.65
      2018422.56     13931380.47      2018792.31     13931408.73
      2018918.62     13931033.00      2019623.50     13930921.39
      2020184.71     13930564.25      2020274.49     13930240.21
      2020074.70     13929695.17      2020225.00     13929375.00

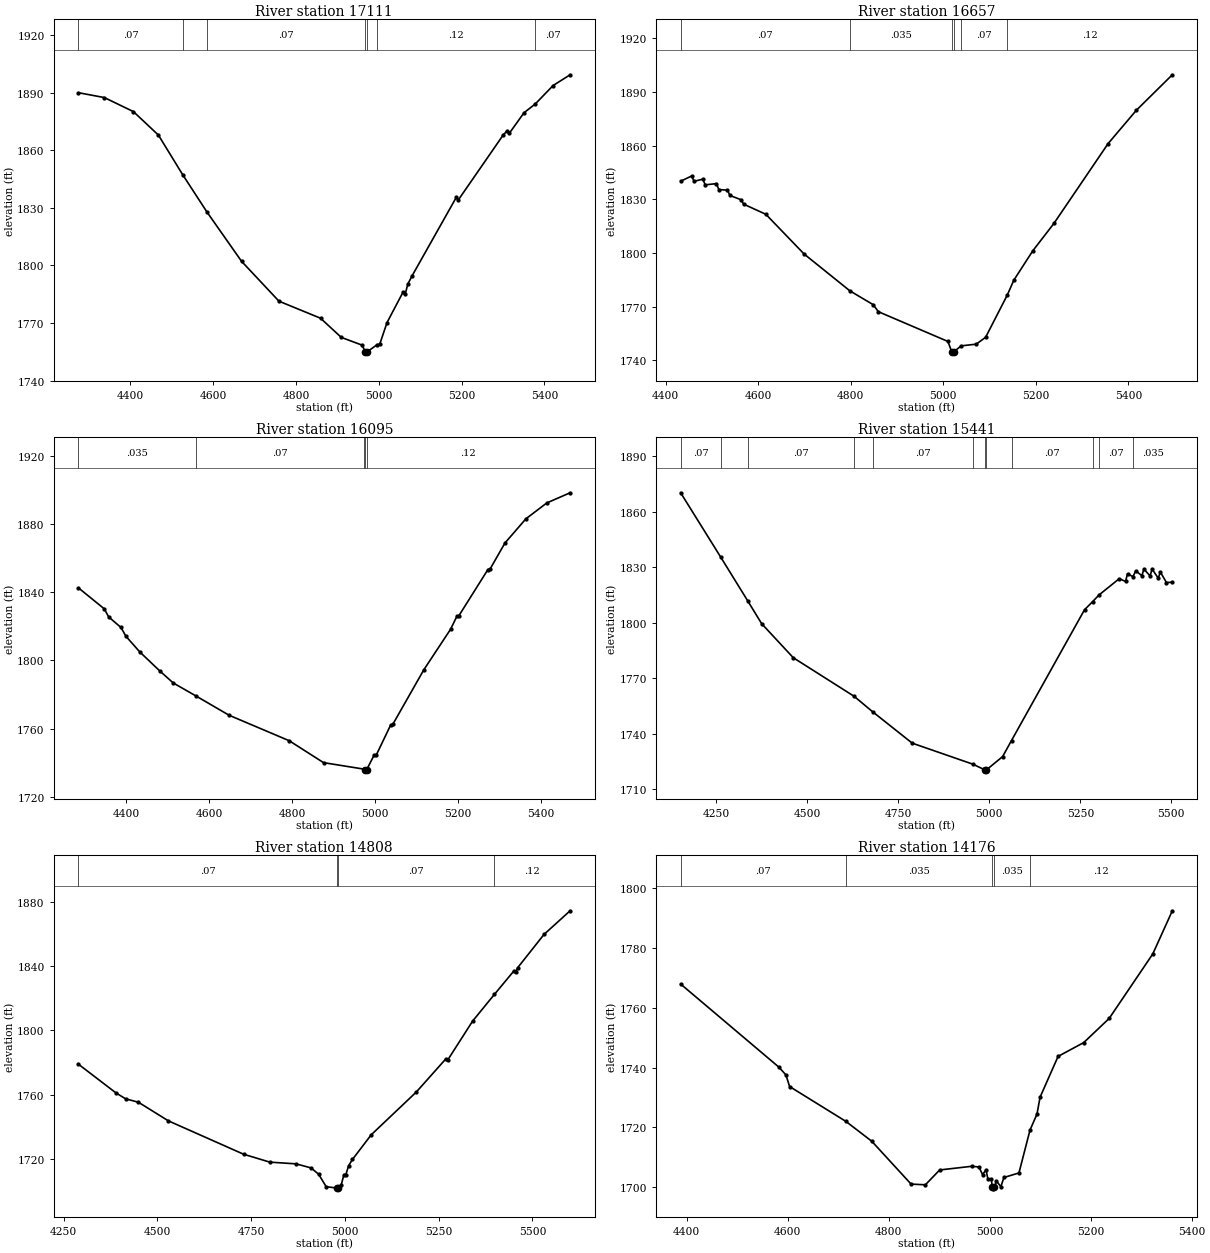
Type RM Length L Ch R = 1,17111,454,454,454
BEGIN DESCRIPTION:
Stream0120_DS 35.0
END DESCRIPTION:
XS GIS Cut Line= 3
      2007811.18     13935197.39      2007875.00     13934475.00
      2007838.35     13934014.16
#Sta/Elev= 30
  4274.8 1890.08  4337.4 1887.55  4407.7 1880.21  4467.9 1868.00  4527.1 1847.16
  4585.2 1827.88  4668.7 1802.20  4759.1 1781.39  4859.5 1772.51  4909.6 1762.52
  4959.8 1758.48  4967.9 1754.96  4968.1 1754.46  4971.9 1754.96  4996.1 1758.70
  5002.5 1758.96  5020.1 1770.24  5059.1 1786.24  5064.1 1785.06  5070.2 1790.25
  5080.3 1794.48  5187.4 1835.52  5192.4 1834.21  5300.9 1868.10  5310.6 1870.30
  5315.7 1868.99  5351.1 1879.67  5377.8 1884.14  5421.3 1893.84  5462.3 1899.43
#Mann=7,-1,0
  4274.8    0.07       0  4527.1   0.035       0  4585.2    0.07       0
  4967.9    0.05       0  4971.9    0.07       0  4996.1    0.12       0
  5377.8    0.07       0
Bank Sta=4967.9,4971.9
Exp/Cntr=0.3,0.1

Type RM Length L Ch R = 1,16657,562,562,562
BEGIN DESCRIPTION:
Stream0120_DS 34.0
END DESCRIPTION:
XS GIS Cut Line= 3
      2008010.35     13935250.34      2008225.00     13934725.00
      2008318.22     13934238.76
#Sta/Elev= 30
  4432.5 1840.10  4456.2 1842.98  4461.6 1840.05  4480.3 1841.20  4485.7 1838.07
  4509.7 1838.73  4515.1 1835.42  4533.7 1835.08  4539.1 1832.11  4563.1 1829.74
  4568.5 1827.29  4616.6 1821.62  4699.4 1799.42  4798.4 1778.84  4848.8 1771.13
  4859.8 1767.23  5010.2 1750.61  5018.4 1744.76  5018.6 1744.26  5022.4 1744.76
  5038.9 1748.16  5071.3 1749.10  5091.6 1752.94  5138.5 1776.57  5152.7 1784.89
  5193.5 1801.21  5239.1 1816.48  5356.4 1861.12  5417.5 1879.73  5495.1 1899.51
#Mann=6,-1,0
  4432.5    0.07       0  4798.4   0.035       0  5018.4   0.035       0
  5022.4   0.035       0  5038.9    0.07       0  5138.5    0.12       0
Bank Sta=5018.4,5022.4
Exp/Cntr=0.3,0.1

Type RM Length L Ch R = 1,16095,654,654,654
BEGIN DESCRIPTION:
Stream0120_DS 33.0
END DESCRIPTION:
XS GIS Cut Line= 3
      2008543.00     13935365.52      2008725.00     13934675.00
      2008665.48     13934209.39
#Sta/Elev= 30
  4285.9 1842.68  4348.0 1830.38  4358.8 1825.58  4388.3 1819.41  4400.2 1814.23
  4433.7 1804.99  4482.9 1793.57  4514.3 1786.75  4568.6 1779.17  4648.4 1767.82
  4793.2 1752.83  4875.9 1739.94  4972.1 1736.17  4975.3 1735.62  4975.5 1735.12
  4979.3 1735.62  4997.4 1744.24  5002.5 1744.24  5037.4 1762.04  5042.4 1762.37
  5117.1 1794.46  5181.5 1818.30  5196.9 1825.99  5201.9 1826.41  5271.6 1853.47
  5276.6 1853.69  5312.5 1869.04  5362.9 1883.27  5413.3 1892.62  5469.4 1898.59
#Mann=5,-1,0
  4285.9   0.035       0  4568.6    0.07       0  4972.1    0.12       0
  4975.3    0.05       0  4979.3    0.12       0
Bank Sta=4975.3,4979.3
Exp/Cntr=0.3,0.1

Type RM Length L Ch R = 1,15441,633,633,633
BEGIN DESCRIPTION:
Stream0120_DS 32.0
END DESCRIPTION:
XS GIS Cut Line= 3
      2009327.36     13935416.90      2009225.00     13934575.00
      2009003.89     13934123.54
#Sta/Elev= 30
  4151.9 1870.21  4262.1 1835.38  4335.7 1811.91  4374.5 1799.41  4461.3 1781.02
  4628.4 1760.17  4679.4 1751.79  4788.1 1734.82  4955.0 1723.43  4987.9 1720.35
  4988.2 1719.85  4991.9 1720.35  5036.5 1727.56  5060.9 1736.25  5261.6 1807.00
  5283.4 1811.26  5301.1 1814.93  5357.1 1823.79  5374.1 1822.25  5379.6 1826.38
  5394.6 1824.85  5402.1 1828.00  5419.1 1825.38  5424.6 1828.94  5441.6 1825.25
  5447.1 1828.97  5464.1 1824.01  5469.7 1827.37  5486.6 1821.68  5502.7 1821.84
#Mann=12,-1,0
  4151.9    0.07       0  4262.1   0.035       0  4335.7    0.07       0
  4628.4   0.035       0  4679.4    0.07       0  4955.0    0.12       0
  4987.9    0.05       0  4991.9    0.12       0  5060.9    0.07       0
  5283.4    0.12       0  5301.1    0.07       0  5394.6   0.035       0
Bank Sta=4987.9,4991.9
Exp/Cntr=0.3,0.1

Type RM Length L Ch R = 1,14808,632,632,632
BEGIN DESCRIPTION:
Stream0120_DS 31.0
END DESCRIPTION:
XS GIS Cut Line= 3
      2009744.58     13935184.75      2009775.00     13934475.00
      2009741.98     13933875.61
#Sta/Elev= 30
  4289.6 1778.95  4389.4 1761.14  4415.4 1757.42  4449.5 1755.30  4529.6 1743.70
  4729.8 1722.99  4799.8 1718.06  4869.9 1716.99  4909.9 1714.45  4929.9 1710.55
  4950.0 1702.80  4978.0 1701.96  4978.2 1701.46  4982.0 1701.96  4990.0 1703.87
  4997.5 1710.33  5002.5 1710.33  5010.0 1715.88  5020.0 1719.71  5070.1 1735.06
  5190.3 1761.65  5269.0 1782.27  5274.0 1781.56  5340.5 1805.78  5398.5 1822.36
  5450.1 1836.83  5455.1 1836.03  5460.7 1839.01  5530.8 1859.65  5600.3 1874.34
#Mann=4,-1,0
  4289.6    0.07       0  4978.0    0.05       0  4982.0    0.07       0
  5398.5    0.12       0
Bank Sta=4978,4982
Exp/Cntr=0.3,0.1

Type RM Length L Ch R = 1,14176,383,383,383
BEGIN DESCRIPTION:
Stream0120_DS 30.0
END DESCRIPTION:
XS GIS Cut Line= 3
      2009897.12     13935012.00      2010325.00     13934575.00
      2010532.71     13934279.01
#Sta/Elev= 30
  4388.4 1767.96  4582.7 1740.16  4596.9 1737.51  4604.0 1733.65  4715.5 1721.97
  4766.6 1715.34  4844.5 1700.98  4872.8 1700.74  4901.1 1705.71  4964.6 1706.94
  4978.8 1706.72  4985.9 1704.19  4992.9 1705.71  4996.5 1702.69  5003.1 1702.69
  5005.4 1699.89  5005.7 1699.39  5009.4 1699.89  5013.5 1702.02  5022.2 1700.11
  5028.3 1703.19  5058.0 1704.71  5079.9 1719.07  5093.7 1724.41  5099.8 1730.07
  5135.5 1743.74  5186.1 1748.34  5236.6 1756.44  5322.9 1778.03  5361.6 1792.49
#Mann=5,-1,0
  4388.4    0.07       0  4715.5   0.035       0  5005.4   0.035       0
  5009.4   0.035       0  5079.9    0.12       0
Bank Sta=5005.4,5009.4
Exp/Cntr=0.3,0.1

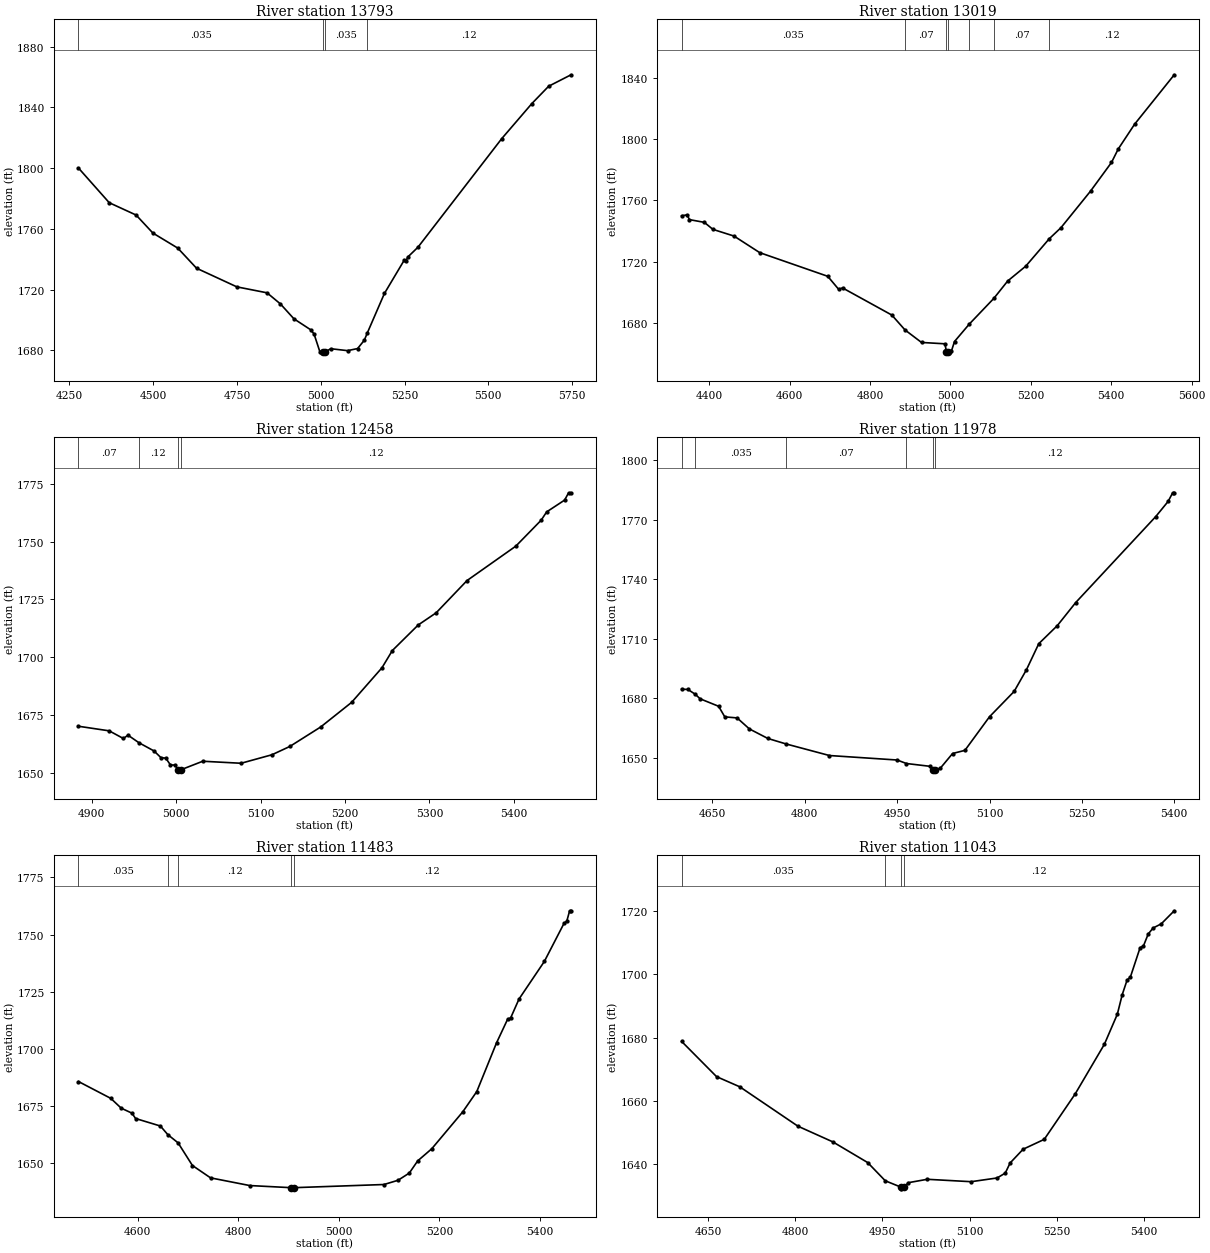
Type RM Length L Ch R = 1,13793,774,774,774
BEGIN DESCRIPTION:
Stream0120_DS 29.0
END DESCRIPTION:
XS GIS Cut Line= 3
      2010582.65     13935496.66      2010625.00     13934775.00
      2010610.30     13934028.24
#Sta/Elev= 30
  4277.1 1800.08  4368.9 1777.26  4449.1 1769.14  4499.1 1757.30  4573.3 1747.40
  4629.4 1734.14  4749.6 1721.88  4839.7 1717.96  4879.8 1710.62  4919.9 1700.86
  4969.9 1693.64  4980.0 1690.88  4997.5 1679.09  5008.0 1678.95  5008.3 1678.45
  5012.0 1678.95  5030.0 1681.16  5080.0 1679.89  5110.0 1681.27  5130.0 1686.77
  5139.3 1691.71  5190.0 1717.53  5249.5 1739.59  5254.5 1738.99  5260.1 1741.59
  5290.1 1747.97  5540.1 1819.45  5630.1 1842.55  5680.1 1853.93  5746.9 1861.47
#Mann=4,-1,0
  4277.1   0.035       0  5008.0   0.035       0  5012.0   0.035       0
  5139.3    0.12       0
Bank Sta=5008,5012
Exp/Cntr=0.3,0.1

Type RM Length L Ch R = 1,13019,561,561,561
BEGIN DESCRIPTION:
Stream0120_DS 28.0
END DESCRIPTION:
XS GIS Cut Line= 3
      2010880.89     13935498.02      2011225.00     13934925.00
      2011329.63     13934378.22
#Sta/Elev= 30
  4331.6 1749.98  4345.1 1750.59  4351.0 1747.45  4387.9 1745.68  4409.3 1741.08
  4461.7 1736.71  4525.8 1725.84  4694.9 1710.37  4722.1 1701.83  4731.7 1702.77
  4854.3 1685.01  4887.1 1675.26  4928.1 1667.09  4986.4 1666.20  4990.2 1660.79
  4990.5 1660.29  4994.2 1660.79  5002.5 1661.47  5010.2 1667.71  5046.9 1679.09
  5108.0 1695.93  5142.5 1707.31  5187.3 1716.99  5246.0 1734.99  5274.9 1742.17
  5348.5 1766.11  5400.6 1784.85  5417.4 1793.68  5458.2 1809.93  5556.7 1842.24
#Mann=7,-1,0
  4331.6   0.035       0  4887.1    0.07       0  4990.2    0.05       0
  4994.2    0.07       0  5046.9    0.12       0  5108.0    0.07       0
  5246.0    0.12       0
Bank Sta=4990.2,4994.2
Exp/Cntr=0.3,0.1

Type RM Length L Ch R = 1,12458,480,480,480
BEGIN DESCRIPTION:
Stream0120_DS 27.0
END DESCRIPTION:
XS GIS Cut Line= 3
      2011775.01     13935075.02      2011725.00     13934975.00
      2011475.01     13934575.02
#Sta/Elev= 30
  4884.3 1670.28  4920.7 1668.30  4937.4 1665.01  4943.0 1666.42  4956.0 1663.15
  4973.8 1659.62  4982.1 1656.69  4987.7 1656.53  4993.3 1653.55  4999.1 1653.55
  5001.7 1651.54  5001.9 1651.04  5005.9 1651.54  5031.5 1655.18  5076.9 1654.31
  5113.5 1657.98  5134.7 1661.57  5171.2 1669.96  5207.8 1680.57  5243.8 1695.51
  5256.1 1702.95  5286.8 1714.00  5308.0 1719.23  5344.6 1733.16  5402.4 1748.01
  5432.4 1759.20  5438.9 1762.78  5460.2 1767.88  5464.9 1771.03  5467.8 1771.03
#Mann=4,-1,0
  4884.3    0.07       0  4956.0    0.12       0  5001.7    0.05       0
  5005.9    0.12       0
Bank Sta=5001.7,5005.9
Exp/Cntr=0.3,0.1

Type RM Length L Ch R = 1,11978,495,495,495
BEGIN DESCRIPTION:
Stream0120_DS 26.0
END DESCRIPTION:
XS GIS Cut Line= 3
      2012125.00     13935174.99      2012125.00     13934775.00
      2012125.00     13934374.99
#Sta/Elev= 30
  4600.0 1684.59  4610.0 1684.49  4621.9 1682.09  4630.0 1679.76  4660.0 1676.00
  4670.0 1670.67  4690.0 1670.14  4710.0 1664.59  4740.0 1659.79  4769.9 1657.00
  4840.0 1651.20  4950.0 1648.94  4965.0 1647.18  5002.5 1645.80  5007.8 1643.99
  5008.1 1643.49  5012.1 1643.99  5020.0 1644.79  5040.0 1652.22  5060.0 1653.80
  5100.0 1670.74  5140.0 1683.49  5160.0 1694.43  5180.0 1707.53  5210.0 1716.59
  5240.0 1728.25  5370.0 1771.55  5390.0 1779.15  5397.5 1783.52  5400.0 1783.52
#Mann=6,-1,0
  4600.0    0.07       0  4621.9   0.035       0  4769.9    0.07       0
  4965.0    0.12       0  5007.8    0.05       0  5012.1    0.12       0
Bank Sta=5007.8,5012.1
Exp/Cntr=0.3,0.1

Type RM Length L Ch R = 1,11483,440,440,440
BEGIN DESCRIPTION:
Stream0120_DS 25.0
END DESCRIPTION:
XS GIS Cut Line= 3
      2012924.99     13935174.99      2012575.00     13934775.00
      2012375.00     13934375.01
#Sta/Elev= 30
  4482.7 1685.79  4546.8 1678.44  4567.6 1674.15  4589.0 1671.96  4596.1 1669.63
  4645.5 1666.34  4660.1 1662.60  4680.6 1658.99  4709.1 1649.09  4745.1 1643.69
  4822.9 1640.33  4905.7 1639.39  4906.0 1638.89  4910.0 1639.39  5089.7 1640.78
  5117.6 1642.63  5140.0 1645.78  5156.7 1651.11  5184.7 1656.42  5246.2 1672.53
  5274.1 1681.41  5313.3 1702.67  5335.6 1713.13  5341.2 1713.50  5358.0 1721.84
  5408.3 1738.26  5447.4 1754.91  5453.0 1755.94  5458.6 1760.42  5461.4 1760.42
#Mann=5,-1,0
  4482.7   0.035       0  4660.1    0.07       0  4680.6    0.12       0
  4905.7    0.05       0  4910.0    0.12       0
Bank Sta=4905.7,4910
Exp/Cntr=0.3,0.1

Type RM Length L Ch R = 1,11043,451,451,451
BEGIN DESCRIPTION:
Stream0120_DS 24.0
END DESCRIPTION:
XS GIS Cut Line= 3
      2012975.00     13935125.05      2012975.00     13934725.00
      2012774.98     13934324.96
#Sta/Elev= 30
  4604.7 1678.77  4664.7 1667.64  4704.7 1664.42  4804.7 1651.96  4864.7 1647.00
  4924.7 1640.45  4954.9 1634.69  4982.4 1632.64  4982.7 1632.14  4987.0 1632.64
  4994.7 1634.09  5027.1 1635.16  5102.6 1634.40  5147.3 1635.58  5161.3 1637.12
  5169.7 1640.33  5192.0 1644.67  5228.4 1647.80  5281.5 1662.14  5331.8 1677.87
  5354.1 1687.39  5362.5 1693.57  5370.9 1698.20  5376.5 1699.13  5393.3 1708.47
  5398.9 1708.94  5407.2 1712.76  5415.6 1714.67  5429.6 1715.98  5452.0 1720.12
#Mann=4,-1,0
  4604.7   0.035       0  4954.9    0.12       0  4982.4    0.05       0
  4987.0    0.12       0
Bank Sta=4982.4,4987
Exp/Cntr=0.3,0.1

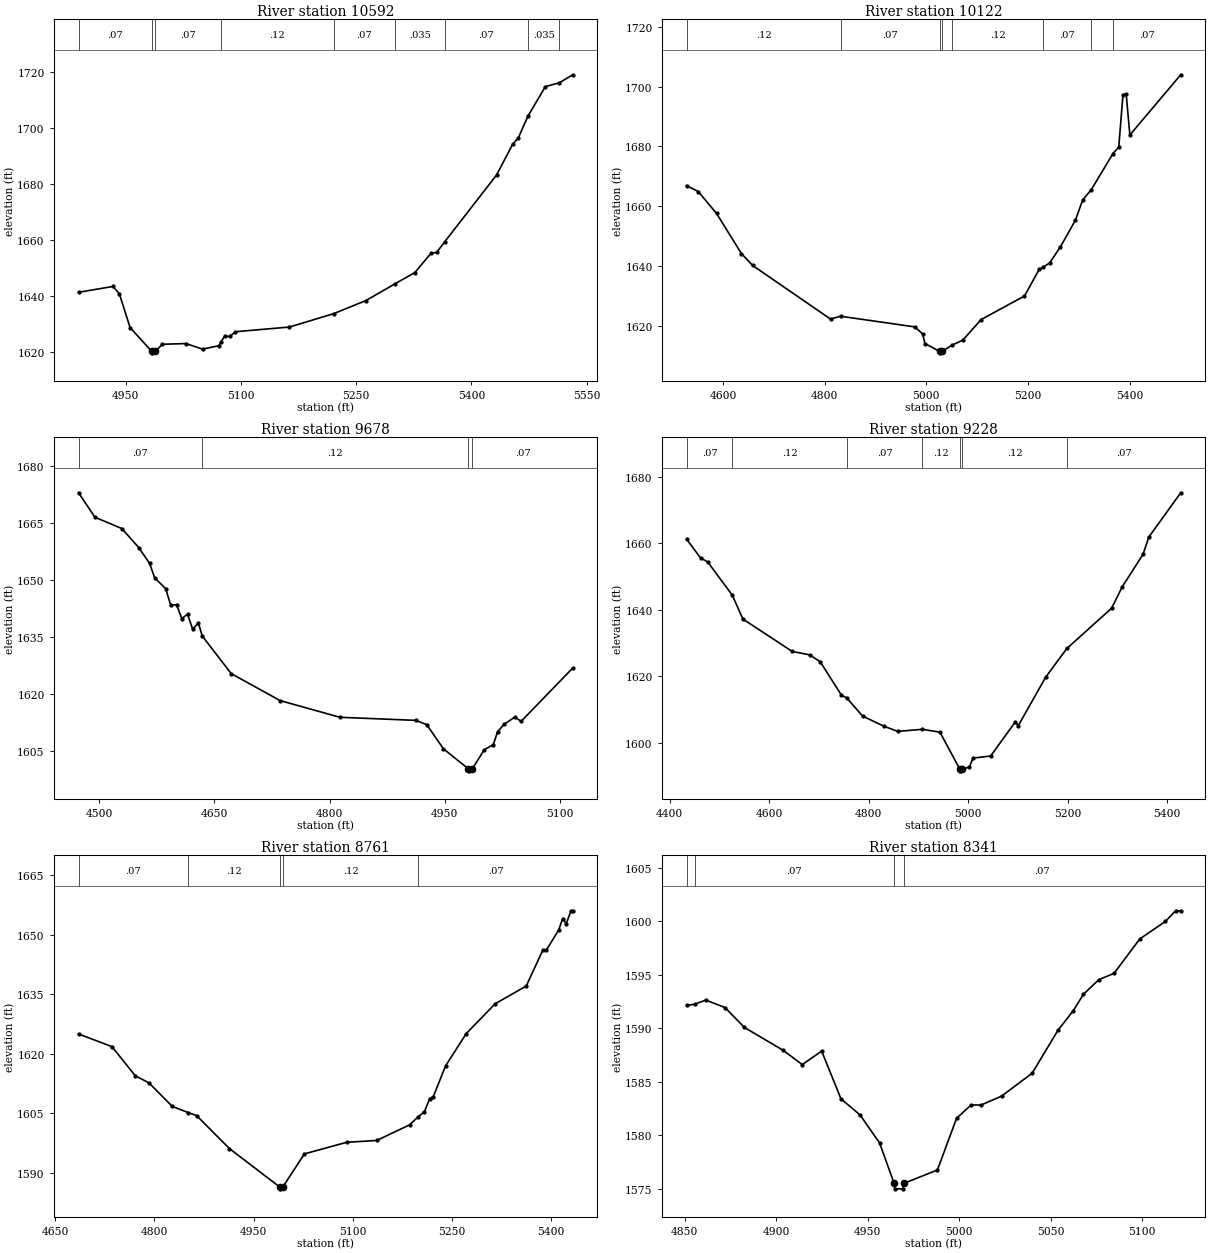
Type RM Length L Ch R = 1,10592,470,470,470
BEGIN DESCRIPTION:
Stream0120_DS 23.0
END DESCRIPTION:
XS GIS Cut Line= 3
      2013424.99     13934674.97      2013375.00     13934575.00
      2013024.99     13934174.99
#Sta/Elev= 30
  4888.5 1641.22  4933.2 1643.30  4941.6 1640.70  4955.6 1628.57  4983.9 1620.05
  4984.3 1619.55  4988.6 1620.05  4997.5 1622.62  5028.3 1622.87  5050.1 1620.87
  5071.0 1622.11  5073.8 1623.36  5078.6 1625.51  5085.2 1625.40  5092.8 1627.11
  5163.0 1628.78  5220.6 1633.57  5262.7 1638.27  5299.8 1644.15  5326.3 1648.28
  5347.2 1655.15  5354.8 1655.52  5365.2 1659.32  5432.6 1683.17  5453.5 1694.14
  5461.1 1696.54  5473.5 1704.26  5496.2 1714.84  5514.4 1716.19  5531.8 1719.06
#Mann=9,-1,0
  4888.5    0.07       0  4983.9    0.05       0  4988.6    0.07       0
  5073.8    0.12       0  5220.6    0.07       0  5299.8   0.035       0
  5365.2    0.07       0  5473.5   0.035       0  5514.4    0.07       0
Bank Sta=4983.9,4988.6
Exp/Cntr=0.3,0.1

Type RM Length L Ch R = 1,10122,444,444,444
BEGIN DESCRIPTION:
Stream0120_DS 22.0
END DESCRIPTION:
XS GIS Cut Line= 3
      2014075.04     13934475.03      2013675.00     13934225.00
      2013375.03     13933825.04
#Sta/Elev= 30
  4528.5 1666.91  4551.5 1664.93  4587.5 1657.59  4636.4 1644.19  4658.3 1640.21
  4811.6 1622.27  4831.3 1623.21  4977.3 1619.65  4992.6 1617.31  4997.3 1614.09
  5025.9 1611.47  5026.3 1610.97  5030.8 1611.47  5051.4 1613.60  5072.1 1615.28
  5107.5 1622.08  5193.0 1629.98  5222.1 1638.95  5229.9 1639.58  5243.0 1641.15
  5263.8 1646.47  5293.0 1655.30  5307.5 1662.11  5324.5 1665.58  5366.9 1677.60
  5378.4 1679.81  5386.7 1697.33  5393.0 1697.60  5400.2 1683.83  5500.2 1703.98
#Mann=8,-1,0
  4528.5    0.12       0  4831.3    0.07       0  5025.9    0.05       0
  5030.8    0.07       0  5051.4    0.12       0  5229.9    0.07       0
  5324.5    0.12       0  5366.9    0.07       0
Bank Sta=5025.9,5030.8
Exp/Cntr=0.3,0.1

Type RM Length L Ch R = 1,9678,450,450,450
BEGIN DESCRIPTION:
Stream0120_DS 21.0
END DESCRIPTION:
XS GIS Cut Line= 3
      2014324.97     13934324.97      2013975.00     13933925.00
      2013874.97     13933874.99
#Sta/Elev= 30
  4473.2 1672.98  4494.5 1666.55  4529.6 1663.56  4551.5 1658.57  4565.7 1654.40
  4572.3 1650.59  4586.6 1647.76  4593.2 1643.38  4600.8 1643.54  4607.5 1639.90
  4615.1 1641.02  4621.7 1637.11  4629.3 1638.68  4634.2 1635.29  4672.0 1625.39
  4735.6 1618.30  4813.4 1613.91  4912.1 1613.10  4926.4 1611.99  4948.2 1605.62
  4980.8 1600.32  4981.2 1599.82  4985.8 1600.32  5001.3 1605.37  5013.1 1606.70
  5018.6 1610.08  5027.0 1612.02  5041.0 1613.95  5049.4 1612.85  5116.5 1626.86
#Mann=4,-1,0
  4473.2    0.07       0  4634.2    0.12       0  4980.8    0.05       0
  4985.8    0.07       0
Bank Sta=4980.8,4985.8
Exp/Cntr=0.3,0.1

Type RM Length L Ch R = 1,9228,467,467,467
BEGIN DESCRIPTION:
Stream0120_DS 20.0
END DESCRIPTION:
XS GIS Cut Line= 3
      2014575.01     13933975.01      2014175.00     13933575.00
      2013775.01     13933425.00
#Sta/Elev= 30
  4434.2 1661.23  4462.5 1655.53  4476.6 1654.38  4526.2 1644.34  4547.4 1637.19
  4646.4 1627.45  4681.7 1626.42  4702.9 1624.32  4745.3 1614.33  4756.0 1613.48
  4787.8 1608.02  4830.2 1604.99  4858.5 1603.40  4908.1 1604.03  4943.3 1603.17
  4983.3 1592.04  4983.6 1591.54  4988.3 1592.04  5002.6 1592.70  5009.7 1595.36
  5045.3 1596.01  5095.1 1606.33  5100.5 1605.05  5155.7 1619.69  5198.4 1628.34
  5288.3 1640.45  5309.6 1646.88  5351.5 1656.69  5363.0 1661.84  5427.1 1675.16
#Mann=7,-1,0
  4434.2    0.07       0  4526.2    0.12       0  4756.0    0.07       0
  4908.1    0.12       0  4983.3    0.05       0  4988.3    0.12       0
  5198.4    0.07       0
Bank Sta=4983.3,4988.3
Exp/Cntr=0.3,0.1

Type RM Length L Ch R = 1,8761,420,420,420
BEGIN DESCRIPTION:
Stream0120_DS 19.0
END DESCRIPTION:
XS GIS Cut Line= 3
      2014675.02     13933425.02      2014425.00     13933225.00
      2014024.99     13933075.00
#Sta/Elev= 30
  4685.2 1624.97  4735.7 1621.78  4770.9 1614.43  4791.7 1612.63  4826.9 1606.69
  4850.9 1605.14  4863.7 1604.37  4913.3 1596.06  4989.2 1586.38  4989.6 1585.88
  4994.3 1586.38  5026.7 1594.70  5090.8 1597.63  5136.2 1598.09  5186.1 1602.05
  5198.9 1604.09  5208.3 1605.35  5216.3 1608.67  5221.7 1609.13  5240.3 1616.91
  5271.5 1625.06  5315.1 1632.57  5362.3 1637.08  5387.2 1646.08  5392.5 1646.12
  5411.2 1651.15  5417.5 1654.12  5422.8 1652.76  5429.9 1656.07  5432.6 1656.07
#Mann=5,-1,0
  4685.2    0.07       0  4850.9    0.12       0  4989.2    0.05       0
  4994.3    0.12       0  5198.9    0.07       0
Bank Sta=4989.2,4994.3
Exp/Cntr=0.3,0.1

Type RM Length L Ch R = 1,8341,465,465,465
BEGIN DESCRIPTION:
Stream0120_DS 18.0
END DESCRIPTION:
XS GIS Cut Line= 3
      2014624.99     13933024.97      2014575.00     13932875.00
      2014474.99     13932824.99
#Sta/Elev= 30
  4851.1 1592.12  4855.5 1592.23  4861.6 1592.62  4872.1 1591.92  4882.7 1590.06
  4903.8 1587.93  4914.3 1586.59  4924.9 1587.85  4935.4 1583.40  4945.9 1581.87
  4956.5 1579.27  4964.5 1575.47  4964.8 1574.97  4969.2 1574.97  4969.6 1575.47
  4988.1 1576.73  4998.6 1581.57  5006.5 1582.81  5012.0 1582.81  5023.2 1583.64
  5039.9 1585.79  5053.9 1589.78  5062.3 1591.62  5067.9 1593.17  5076.3 1594.53
  5084.6 1595.12  5098.6 1598.33  5112.6 1599.97  5118.2 1600.97  5121.0 1600.97
#Mann=4,-1,0
  4851.1    0.12       0  4855.5    0.07       0  4964.5    0.05       0
  4969.6    0.07       0
Bank Sta=4964.5,4969.6
Exp/Cntr=0.3,0.1

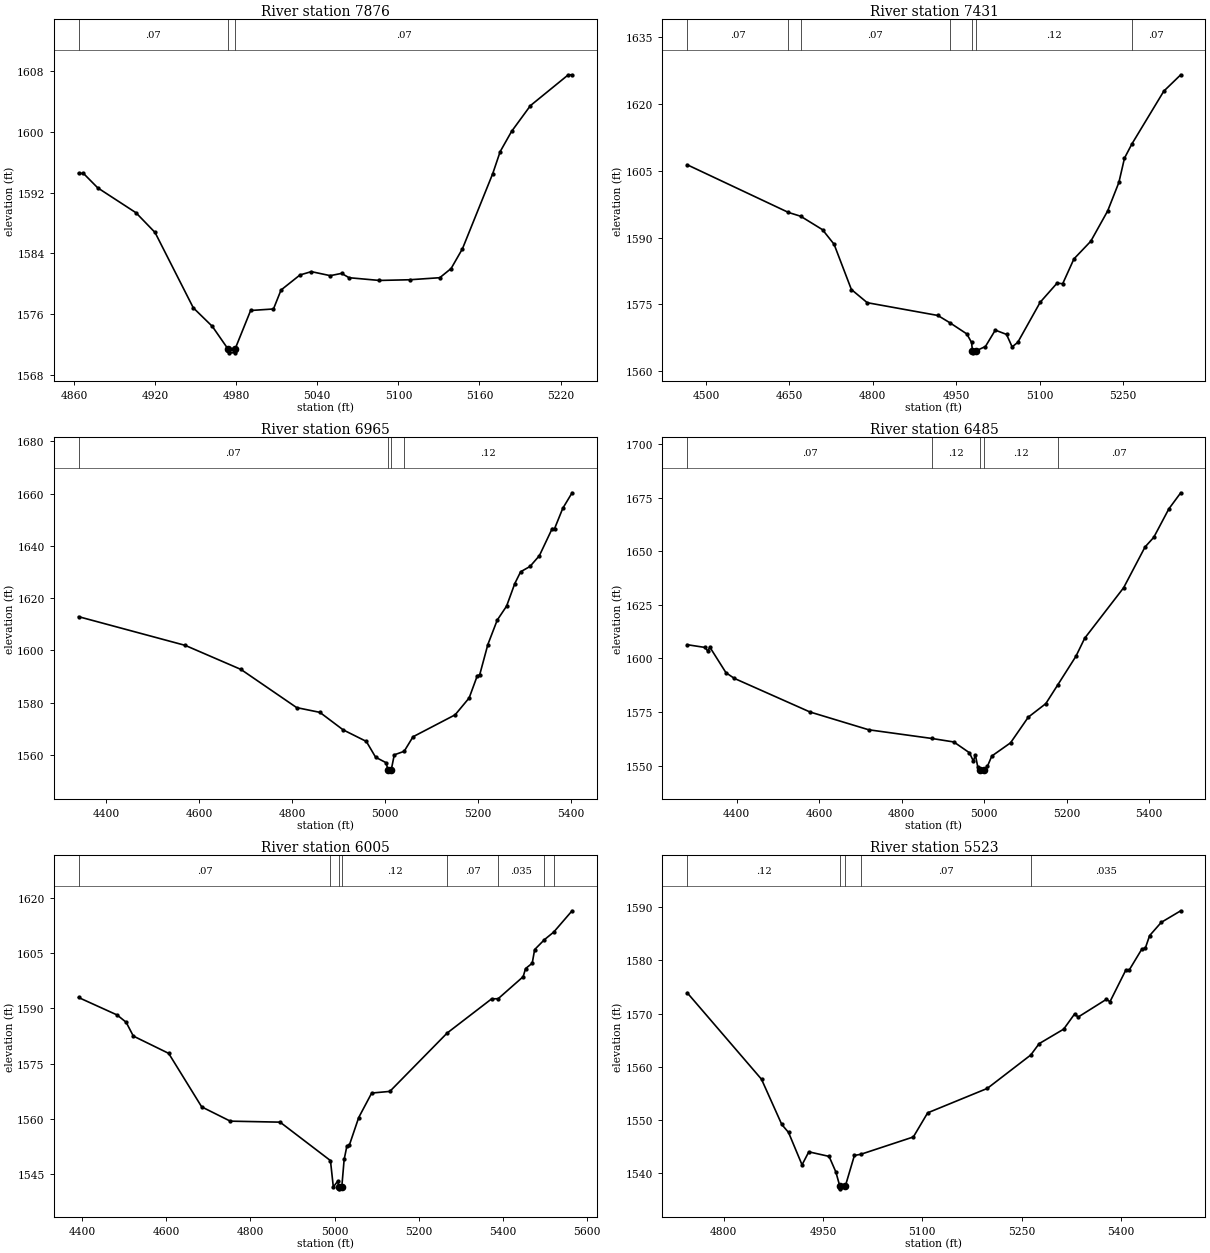
Type RM Length L Ch R = 1,7876,445,445,445
BEGIN DESCRIPTION:
Stream0120_DS 17.0
END DESCRIPTION:
XS GIS Cut Line= 3
      2015025.02     13932725.02      2014925.00     13932625.00
      2014724.96     13932524.98
#Sta/Elev= 30
  4863.4 1594.56  4867.0 1594.56  4877.6 1592.65  4905.9 1589.37  4920.0 1586.77
  4948.3 1576.84  4962.4 1574.39  4974.0 1571.41  4974.4 1570.91  4978.8 1570.91
  4979.2 1571.41  4990.7 1576.49  5007.6 1576.69  5013.2 1579.19  5027.2 1581.17
  5035.6 1581.61  5049.6 1581.08  5058.0 1581.38  5063.5 1580.81  5085.9 1580.45
  5108.3 1580.54  5130.6 1580.81  5139.0 1582.02  5147.4 1584.63  5169.8 1594.53
  5175.3 1597.43  5183.7 1600.08  5197.7 1603.49  5225.7 1607.55  5228.5 1607.55
#Mann=3,-1,0
  4863.4    0.07       0  4974.0    0.05       0  4979.2    0.07       0
Bank Sta=4974,4979.2
Exp/Cntr=0.3,0.1

Type RM Length L Ch R = 1,7431,466,466,466
BEGIN DESCRIPTION:
Stream0120_DS 16.0
END DESCRIPTION:
XS GIS Cut Line= 3
      2015316.47     13932789.61      2015175.00     13932275.00
      2015124.99     13931924.95
#Sta/Elev= 30
  4466.3 1606.36  4648.4 1595.65  4670.3 1594.80  4709.6 1591.78  4730.4 1588.51
  4761.5 1578.35  4790.0 1575.39  4917.0 1572.52  4938.5 1570.89  4968.9 1568.39
  4977.6 1566.46  4979.1 1564.63  4979.6 1564.13  4986.4 1564.63  5002.5 1565.55
  5020.2 1569.23  5040.4 1568.27  5050.5 1565.47  5060.6 1566.48  5101.0 1575.50
  5131.3 1579.78  5141.4 1579.65  5161.6 1585.22  5191.9 1589.19  5222.2 1595.98
  5242.4 1602.39  5252.5 1607.85  5265.8 1611.03  5323.2 1622.89  5353.6 1626.56
#Mann=7,-1,0
  4466.3    0.07       0  4648.4    0.12       0  4670.3    0.07       0
  4938.5    0.12       0  4979.1    0.05       0  4986.4    0.12       0
  5265.8    0.07       0
Bank Sta=4979.1,4986.4
Exp/Cntr=0.3,0.1

Type RM Length L Ch R = 1,6965,480,480,480
BEGIN DESCRIPTION:
Stream0120_DS 15.0
END DESCRIPTION:
XS GIS Cut Line= 3
      2015631.60     13932884.67      2015625.00     13932225.00
      2015675.00     13931825.01
#Sta/Elev= 30
  4340.3 1612.93  4570.0 1601.95  4690.0 1592.75  4810.0 1578.15  4860.0 1576.33
  4910.0 1569.65  4960.0 1565.22  4980.0 1559.18  5002.5 1557.08  5006.4 1554.47
  5006.9 1553.97  5013.8 1554.47  5020.2 1560.09  5041.5 1561.44  5060.5 1566.99
  5151.2 1575.39  5181.4 1581.84  5199.0 1590.36  5204.1 1590.68  5221.7 1602.28
  5241.9 1611.62  5262.0 1616.95  5279.7 1625.59  5292.3 1630.10  5312.4 1632.12
  5332.6 1636.24  5360.3 1646.64  5365.3 1646.57  5383.0 1654.36  5403.1 1660.30
#Mann=4,-1,0
  4340.3    0.07       0  5006.4    0.05       0  5013.8    0.07       0
  5041.5    0.12       0
Bank Sta=5006.4,5013.8
Exp/Cntr=0.3,0.1

Type RM Length L Ch R = 1,6485,480,480,480
BEGIN DESCRIPTION:
Stream0120_DS 14.0
END DESCRIPTION:
XS GIS Cut Line= 3
      2015940.45     13932837.55      2016075.00     13932125.00
      2015825.02     13931725.03
#Sta/Elev= 30
  4280.0 1606.42  4323.3 1605.14  4329.9 1603.44  4335.0 1605.27  4374.2 1593.32
  4394.5 1590.69  4577.7 1575.03  4720.2 1566.72  4873.1 1562.67  4926.6 1561.03
  4964.4 1556.00  4973.9 1552.13  4978.9 1554.92  4984.8 1549.24  4991.2 1548.06
  4991.7 1547.56  4998.7 1548.06  5008.1 1549.69  5018.7 1554.47  5064.1 1560.63
  5107.1 1572.60  5149.6 1578.92  5178.0 1587.49  5222.7 1601.03  5243.9 1609.43
  5338.3 1632.99  5390.2 1652.01  5411.4 1656.52  5447.9 1669.78  5476.8 1677.31
#Mann=5,-1,0
  4280.0    0.07       0  4873.1    0.12       0  4991.2    0.05       0
  4998.7    0.12       0  5178.0    0.07       0
Bank Sta=4991.2,4998.7
Exp/Cntr=0.3,0.1

Type RM Length L Ch R = 1,6005,482,482,482
BEGIN DESCRIPTION:
Stream0120_DS 13.0
END DESCRIPTION:
XS GIS Cut Line= 3
      2016301.80     13932690.06      2016525.00     13932125.00
      2016244.22     13931635.57
#Sta/Elev= 30
  4392.0 1592.95  4483.5 1588.20  4505.0 1586.22  4522.1 1582.46  4606.0 1577.76
  4684.4 1563.21  4752.3 1559.33  4870.5 1559.06  4990.1 1548.61  4996.9 1541.44
  5007.5 1543.04  5009.5 1541.43  5010.0 1540.93  5017.0 1541.43  5022.6 1548.91
  5029.0 1552.49  5034.8 1552.76  5057.2 1560.32  5088.0 1566.97  5131.1 1567.42
  5267.2 1583.29  5372.8 1592.58  5388.2 1592.61  5447.6 1598.60  5453.3 1600.81
  5469.1 1602.26  5474.9 1605.98  5498.2 1608.68  5520.2 1610.73  5563.8 1616.52
#Mann=8,-1,0
  4392.0    0.07       0  4990.1    0.12       0  5009.5    0.05       0
  5017.0    0.12       0  5267.2    0.07       0  5388.2   0.035       0
  5498.2    0.07       0  5520.2   0.035       0
Bank Sta=5009.5,5017
Exp/Cntr=0.3,0.1

Type RM Length L Ch R = 1,5523,454,454,454
BEGIN DESCRIPTION:
Stream0120_DS 12.0
END DESCRIPTION:
XS GIS Cut Line= 3
      2017025.00     13932375.01      2016975.00     13932125.00
      2016789.41     13931671.46
#Sta/Elev= 30
  4745.1 1573.93  4857.3 1557.64  4887.9 1549.12  4898.1 1547.62  4918.5 1541.52
  4928.7 1543.97  4959.3 1543.11  4969.5 1540.19  4975.5 1537.50  4976.0 1537.00
  4983.8 1537.50  4997.5 1543.28  5007.3 1543.51  5086.5 1546.77  5108.1 1551.31
  5198.1 1555.91  5263.7 1562.20  5276.4 1564.34  5313.4 1567.07  5329.9 1569.93
  5335.3 1569.35  5377.9 1572.69  5383.3 1572.24  5407.3 1578.22  5412.7 1578.28
  5431.3 1582.13  5436.7 1582.34  5443.1 1584.68  5460.7 1587.18  5490.1 1589.36
#Mann=5,-1,0
  4745.1    0.12       0  4975.5    0.05       0  4983.8    0.12       0
  5007.3    0.07       0  5263.7   0.035       0
Bank Sta=4975.5,4983.8
Exp/Cntr=0.3,0.1

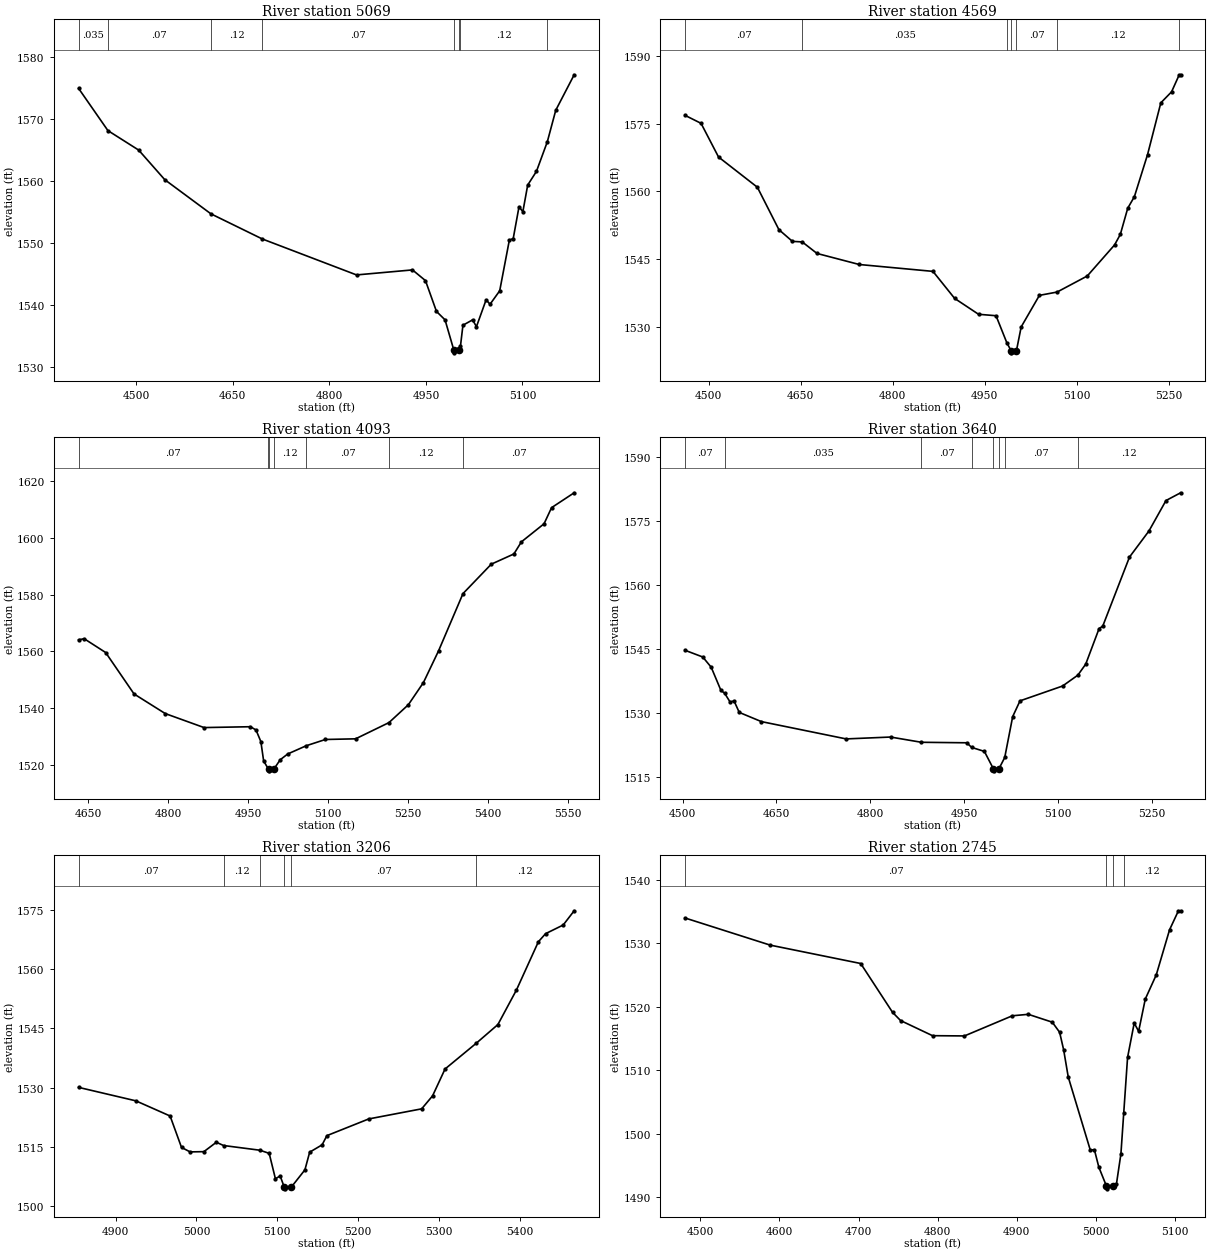
Type RM Length L Ch R = 1,5069,500,500,500
BEGIN DESCRIPTION:
Stream0120_DS 11.0
END DESCRIPTION:
XS GIS Cut Line= 3
      2017232.02     13932507.10      2017325.00     13931925.00
      2017425.02     13931774.96
#Sta/Elev= 30
  4410.5 1574.98  4456.0 1568.17  4503.8 1565.02  4544.3 1560.24  4616.0 1554.72
  4695.8 1550.66  4842.2 1544.85  4929.1 1545.66  4949.3 1543.93  4966.4 1538.95
  4979.7 1537.59  4993.2 1532.76  4993.7 1532.26  5001.6 1532.76  5003.6 1533.29
  5007.5 1536.72  5022.5 1537.59  5028.5 1536.49  5043.5 1540.83  5049.6 1540.11
  5064.6 1542.28  5079.6 1550.47  5085.6 1550.72  5094.6 1555.86  5100.6 1555.07
  5108.1 1559.37  5121.7 1561.58  5138.6 1566.37  5151.7 1571.46  5180.3 1577.19
#Mann=8,-1,0
  4410.5   0.035       0  4456.0    0.07       0  4616.0    0.12       0
  4695.8    0.07       0  4993.2    0.05       0  5001.6    0.07       0
  5003.6    0.12       0  5138.6    0.07       0
Bank Sta=4993.2,5001.6
Exp/Cntr=0.3,0.1

Type RM Length L Ch R = 1,4569,476,476,476
BEGIN DESCRIPTION:
Stream0120_DS 10.0
END DESCRIPTION:
XS GIS Cut Line= 3
      2018050.85     13932413.76      2017825.00     13931925.00
      2017724.99     13931674.98
#Sta/Elev= 30
  4461.6 1576.82  4487.6 1575.06  4516.1 1567.62  4579.4 1560.94  4614.5 1551.57
  4636.5 1548.98  4652.5 1548.86  4676.6 1546.31  4745.4 1543.87  4865.6 1542.35
  4900.9 1536.38  4939.9 1532.87  4968.4 1532.55  4986.0 1526.58  4992.8 1524.85
  4993.3 1524.35  5001.7 1524.85  5009.4 1530.08  5039.1 1537.05  5067.9 1537.78
  5117.1 1541.33  5161.6 1548.19  5171.0 1550.52  5183.1 1556.32  5193.9 1558.85
  5215.4 1568.17  5237.0 1579.59  5254.5 1582.02  5267.0 1585.79  5269.3 1585.79
#Mann=7,-1,0
  4461.6    0.07       0  4652.5   0.035       0  4986.0    0.07       0
  4992.8    0.05       0  5001.7    0.07       0  5067.9    0.12       0
  5267.0    0.07       0
Bank Sta=4992.8,5001.7
Exp/Cntr=0.3,0.1

Type RM Length L Ch R = 1,4093,453,453,453
BEGIN DESCRIPTION:
Stream0120_DS 9.0
END DESCRIPTION:
XS GIS Cut Line= 3
      2018325.01     13932075.04      2018225.00     13931725.00
      2017825.02     13931325.02
#Sta/Elev= 30
  4631.7 1564.08  4642.1 1564.47  4682.4 1559.60  4735.7 1544.98  4794.2 1538.07
  4867.0 1533.13  4954.1 1533.43  4964.5 1532.27  4973.6 1528.18  4978.8 1521.36
  4987.4 1518.60  4988.7 1518.37  4989.2 1517.87  4997.6 1518.37  5009.9 1521.78
  5024.0 1523.82  5058.7 1526.72  5094.7 1528.93  5151.3 1529.16  5213.9 1534.88
  5250.3 1541.18  5278.6 1549.01  5306.9 1560.16  5352.8 1580.38  5405.9 1590.76
  5448.3 1594.36  5462.4 1598.63  5504.9 1605.01  5519.0 1610.69  5561.4 1615.94
#Mann=7,-1,0
  4631.7    0.07       0  4987.4    0.12       0  4988.7    0.05       0
  4997.6    0.12       0  5058.7    0.07       0  5213.9    0.12       0
  5352.8    0.07       0
Bank Sta=4988.7,4997.6
Exp/Cntr=0.3,0.1

Type RM Length L Ch R = 1,3640,434,434,434
BEGIN DESCRIPTION:
Stream0120_DS 8.0
END DESCRIPTION:
XS GIS Cut Line= 3
      2018725.01     13931775.02      2018425.00     13931375.00
      2018274.99     13931124.98
#Sta/Elev= 30
  4504.0 1544.73  4532.2 1543.16  4545.7 1540.76  4561.3 1535.30  4567.0 1534.69
  4575.9 1532.59  4582.2 1532.86  4590.5 1530.16  4625.9 1528.00  4761.3 1523.94
  4832.2 1524.38  4881.5 1523.15  4954.0 1523.03  4961.7 1521.95  4982.1 1521.01
  4996.4 1516.95  4996.9 1516.45  5005.4 1516.95  5014.6 1519.58  5027.3 1529.17
  5039.0 1532.87  5107.0 1536.35  5131.4 1538.90  5144.0 1541.49  5165.3 1549.82
  5171.2 1550.41  5213.9 1566.61  5245.0 1572.73  5272.2 1579.87  5295.6 1581.69
#Mann=8,-1,0
  4504.0    0.07       0  4567.0   0.035       0  4881.5    0.07       0
  4961.7    0.12       0  4996.4    0.05       0  5005.4    0.12       0
  5014.6    0.07       0  5131.4    0.12       0
Bank Sta=4996.4,5005.4
Exp/Cntr=0.3,0.1

Type RM Length L Ch R = 1,3206,461,461,461
BEGIN DESCRIPTION:
Stream0120_DS 7.0
END DESCRIPTION:
XS GIS Cut Line= 3
      2018925.03     13931475.03      2018825.00     13931375.00
      2018574.98     13930974.97
#Sta/Elev= 30
  4854.2 1530.06  4925.0 1526.65  4967.4 1522.80  4981.5 1514.84  4992.1 1513.70
  5009.2 1513.76  5024.6 1516.14  5033.5 1515.32  5078.6 1514.12  5090.0 1513.33
  5097.7 1506.89  5103.6 1507.60  5108.5 1504.83  5109.0 1504.33  5117.6 1504.83
  5134.2 1509.14  5140.1 1513.63  5155.5 1515.49  5161.4 1517.82  5213.2 1522.06
  5278.7 1524.62  5292.2 1527.92  5307.6 1534.72  5346.2 1541.25  5373.0 1545.99
  5396.0 1554.77  5423.1 1566.99  5432.0 1569.04  5453.8 1571.24  5467.4 1574.85
#Mann=6,-1,0
  4854.2    0.07       0  5033.5    0.12       0  5078.6    0.07       0
  5108.5    0.05       0  5117.6    0.07       0  5346.2    0.12       0
Bank Sta=5108.5,5117.6
Exp/Cntr=0.3,0.1

Type RM Length L Ch R = 1,2745,487,487,487
BEGIN DESCRIPTION:
Stream0120_DS 6.0
END DESCRIPTION:
XS GIS Cut Line= 3
      2019044.83     13931534.92      2018975.00     13931025.00
      2018924.99     13930924.98
#Sta/Elev= 30
  4480.7 1534.01  4588.3 1529.73  4702.7 1526.83  4743.0 1519.12  4753.1 1517.83
  4793.5 1515.44  4833.9 1515.40  4894.4 1518.58  4914.6 1518.81  4944.9 1517.57
  4954.2 1515.98  4959.3 1513.20  4965.1 1508.92  4992.9 1497.42  4998.2 1497.42
  5003.8 1494.68  5013.2 1491.77  5013.7 1491.27  5022.3 1491.77  5026.1 1492.08
  5031.7 1496.80  5035.3 1503.31  5040.1 1512.00  5048.5 1517.43  5054.1 1516.13
  5062.5 1521.22  5076.4 1525.04  5093.2 1532.15  5104.4 1535.15  5107.2 1535.15
#Mann=4,-1,0
  4480.7    0.07       0  5013.2    0.05       0  5022.3    0.07       0
  5035.3    0.12       0
Bank Sta=5013.2,5022.3
Exp/Cntr=0.3,0.1