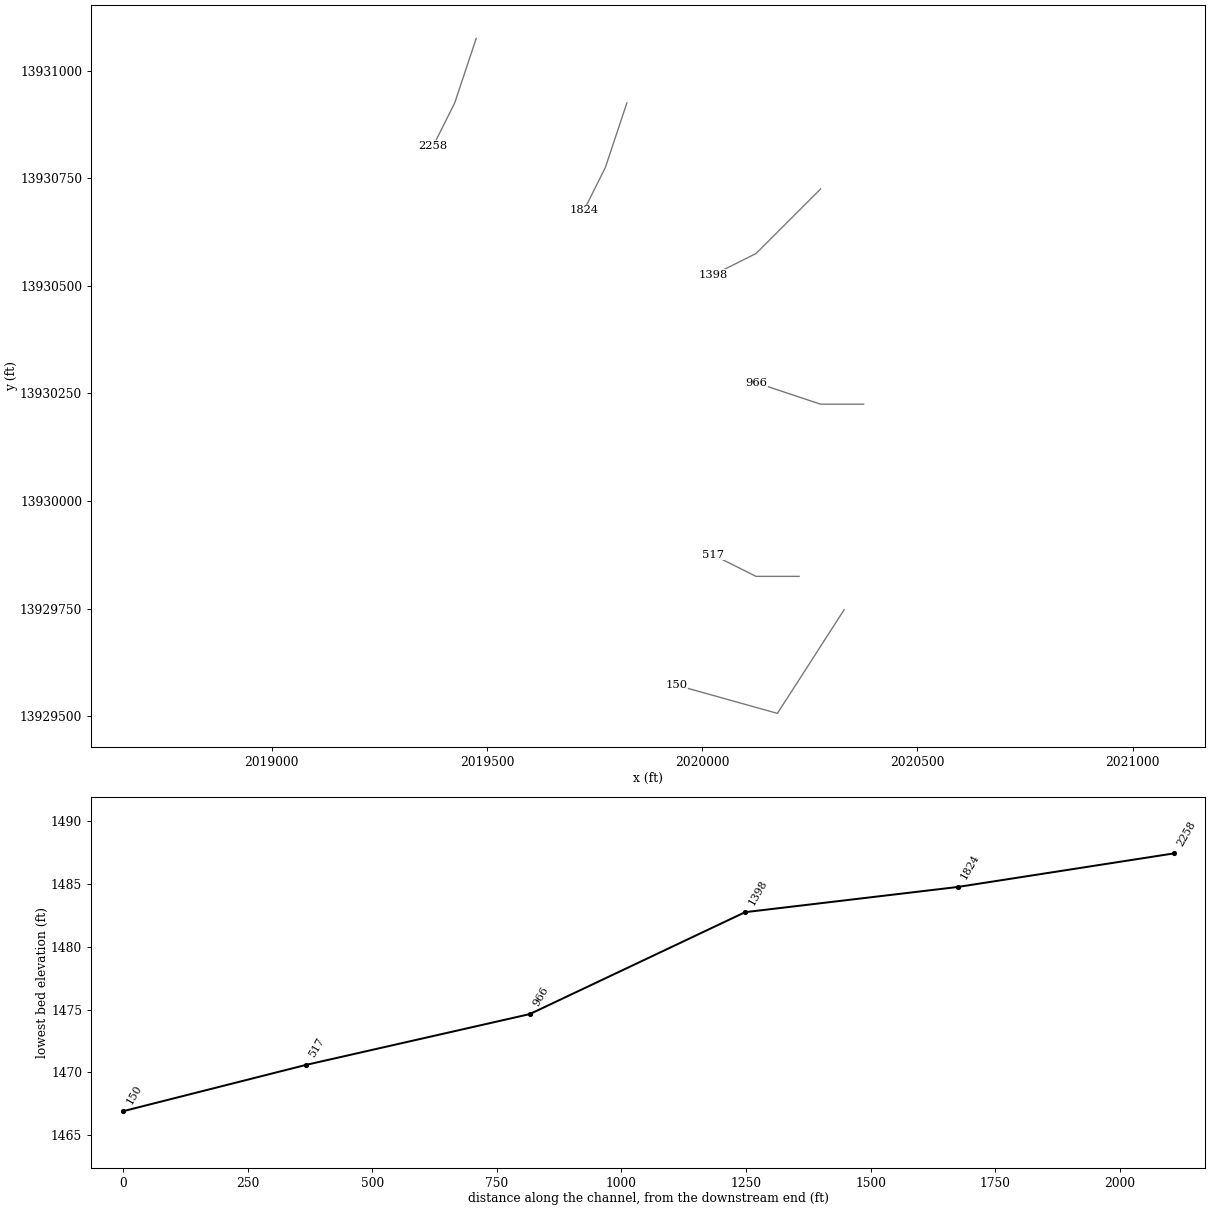
HEC-RAS study Stream0120_DS.prj: Stream0120_DS Base Level Engineering

--- Stream0120_DS.g01 (geometry) --- (continued)

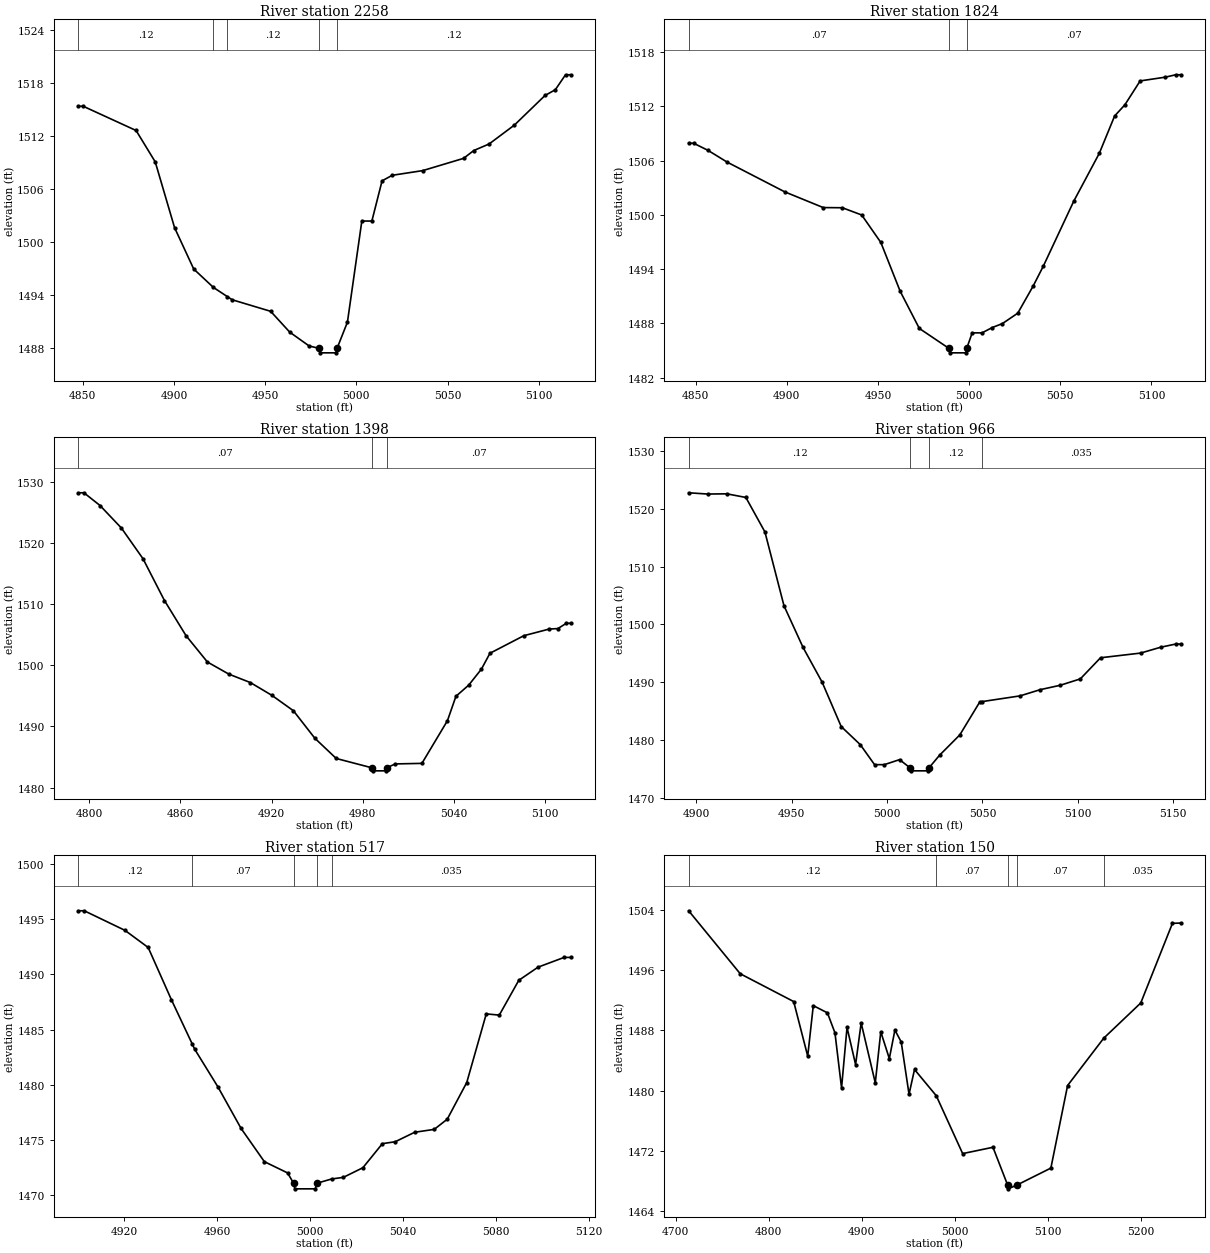
Type RM Length L Ch R = 1,2258,434,434,434
BEGIN DESCRIPTION:
Stream0120_DS 5.0
END DESCRIPTION:
XS GIS Cut Line= 3
      2019474.99     13931074.97      2019425.00     13930925.00
      2019374.99     13930824.99
#Sta/Elev= 30
  4847.6 1515.38  4850.2 1515.38  4879.2 1512.63  4889.7 1509.07  4900.3 1501.61
  4910.8 1496.92  4921.6 1494.83  4929.3 1493.78  4931.9 1493.43  4953.0 1492.12
  4963.5 1489.75  4974.1 1488.19  4979.7 1487.91  4980.2 1487.41  4988.9 1487.41
  4989.4 1487.91  4995.1 1490.89  5003.0 1502.36  5008.5 1502.36  5014.1 1506.92
  5019.7 1507.55  5036.4 1508.08  5058.8 1509.47  5064.4 1510.36  5072.8 1511.10
  5086.7 1513.25  5103.5 1516.61  5109.1 1517.25  5114.7 1518.95  5117.5 1518.95
#Mann=5,-1,0
  4847.6    0.12       0  4921.6    0.07       0  4929.3    0.12       0
  4979.7    0.05       0  4989.4    0.12       0
Bank Sta=4979.7,4989.4
Exp/Cntr=0.3,0.1

Type RM Length L Ch R = 1,1824,426,426,426
BEGIN DESCRIPTION:
Stream0120_DS 4.0
END DESCRIPTION:
XS GIS Cut Line= 3
      2019825.01     13930925.02      2019775.00     13930775.00
      2019725.02     13930675.03
#Sta/Elev= 30
  4846.2 1507.93  4848.9 1507.93  4856.8 1507.14  4867.3 1505.84  4898.9 1502.55
  4920.0 1500.81  4930.5 1500.79  4941.1 1499.99  4951.6 1496.95  4962.2 1491.55
  4972.7 1487.44  4988.9 1485.24  4989.4 1484.74  4998.2 1484.74  4998.7 1485.24
  5001.7 1486.95  5007.1 1486.95  5012.7 1487.54  5018.3 1487.98  5026.7 1489.13
  5035.1 1492.12  5040.7 1494.33  5057.4 1501.52  5071.4 1506.81  5079.8 1510.94
  5085.4 1512.17  5093.8 1514.82  5107.7 1515.24  5113.3 1515.50  5116.1 1515.50
#Mann=3,-1,0
  4846.2    0.07       0  4988.9    0.05       0  4998.7    0.07       0
Bank Sta=4988.9,4998.7
Exp/Cntr=0.3,0.1

Type RM Length L Ch R = 1,1398,432,432,432
BEGIN DESCRIPTION:
Stream0120_DS 3.0
END DESCRIPTION:
XS GIS Cut Line= 3
      2020275.03     13930725.03      2020125.00     13930575.00
      2020024.98     13930524.99
#Sta/Elev= 30
  4792.9 1528.17  4796.5 1528.17  4807.1 1526.09  4821.2 1522.40  4835.4 1517.39
  4849.5 1510.57  4863.7 1504.83  4877.8 1500.52  4891.9 1498.54  4906.1 1497.16
  4920.2 1495.08  4934.4 1492.56  4948.5 1488.07  4962.6 1484.76  4986.0 1483.24
  4986.5 1482.74  4995.3 1482.74  4995.8 1483.24  5001.5 1483.87  5019.0 1483.96
  5035.8 1490.93  5041.4 1494.92  5049.8 1496.74  5058.2 1499.37  5063.8 1501.95
  5086.1 1504.82  5102.9 1505.91  5108.5 1505.98  5114.1 1506.85  5116.9 1506.85
#Mann=3,-1,0
  4792.9    0.07       0  4986.0    0.05       0  4995.8    0.07       0
Bank Sta=4986,4995.8
Exp/Cntr=0.3,0.1

Type RM Length L Ch R = 1,966,449,449,449
BEGIN DESCRIPTION:
Stream0120_DS 2.0
END DESCRIPTION:
XS GIS Cut Line= 3
      2020375.01     13930225.00      2020275.00     13930225.00
      2020125.02     13930274.99
#Sta/Elev= 30
  4895.9 1522.79  4905.9 1522.57  4915.9 1522.61  4925.9 1521.98  4935.9 1516.01
  4945.9 1503.22  4955.9 1496.01  4965.9 1489.99  4975.9 1482.31  4985.9 1479.18
  4993.4 1475.71  4998.5 1475.71  5006.5 1476.58  5012.1 1475.14  5012.6 1474.64
  5021.4 1474.64  5021.9 1475.14  5027.5 1477.35  5038.1 1480.86  5048.6 1486.58
  5049.8 1486.63  5069.7 1487.62  5080.2 1488.69  5090.8 1489.46  5101.3 1490.56
  5111.9 1494.22  5132.9 1495.03  5143.5 1496.05  5151.4 1496.60  5154.0 1496.60
#Mann=4,-1,0
  4895.9    0.12       0  5012.1    0.05       0  5021.9    0.12       0
  5049.8   0.035       0
Bank Sta=5012.1,5021.9
Exp/Cntr=0.3,0.1

Type RM Length L Ch R = 1,517,367,367,367
BEGIN DESCRIPTION:
Stream0120_DS 1.0
END DESCRIPTION:
XS GIS Cut Line= 3
      2020225.01     13929825.00      2020125.00     13929825.00
      2020025.01     13929874.99
#Sta/Elev= 30
  4900.3 1495.76  4902.8 1495.76  4920.3 1493.99  4930.3 1492.44  4940.3 1487.71
  4949.3 1483.69  4950.3 1483.24  4960.3 1479.83  4970.3 1476.06  4980.3 1473.06
  4990.3 1472.04  4992.9 1471.10  4993.4 1470.60  5002.3 1470.60  5002.8 1471.10
  5009.2 1471.49  5014.3 1471.64  5022.7 1472.51  5031.1 1474.69  5036.6 1474.86
  5045.0 1475.72  5053.4 1475.98  5059.0 1476.90  5067.4 1480.22  5075.8 1486.43
  5081.4 1486.32  5089.8 1489.47  5098.1 1490.66  5109.3 1491.54  5112.1 1491.54
#Mann=5,-1,0
  4900.3    0.12       0  4949.3    0.07       0  4992.9    0.05       0
  5002.8    0.07       0  5009.2   0.035       0
Bank Sta=4992.9,5002.8
Exp/Cntr=0.3,0.1

Type RM Length L Ch R = 1,150,0,0,0
BEGIN DESCRIPTION:
Stream0120_DS 0.0
END DESCRIPTION:
XS GIS Cut Line= 3
      2020329.64     13929747.32      2020174.70     13929506.69
      2019940.36     13929572.14
#Sta/Elev= 30
  4713.8 1503.92  4769.3 1495.54  4826.8 1491.84  4841.9 1484.58  4847.9 1491.30
  4863.1 1490.34  4871.2 1487.68  4878.3 1480.35  4884.2 1488.40  4893.4 1483.46
  4899.4 1488.99  4914.6 1481.02  4920.5 1487.82  4929.7 1484.25  4935.7 1488.05
  4942.5 1486.46  4950.9 1479.51  4956.8 1482.80  4980.2 1479.31  5008.6 1471.61
  5041.2 1472.45  5057.0 1467.42  5057.5 1466.92  5066.9 1467.42  5103.5 1469.68
  5121.5 1480.67  5160.4 1486.97  5200.2 1491.65  5234.3 1502.25  5243.3 1502.29
#Mann=5,-1,0
  4713.8    0.12       0  4980.2    0.07       0  5057.0    0.05       0
  5066.9    0.07       0  5160.4   0.035       0
Bank Sta=5057,5066.9
Exp/Cntr=0.3,0.1

Chan Stop Cuts=-1