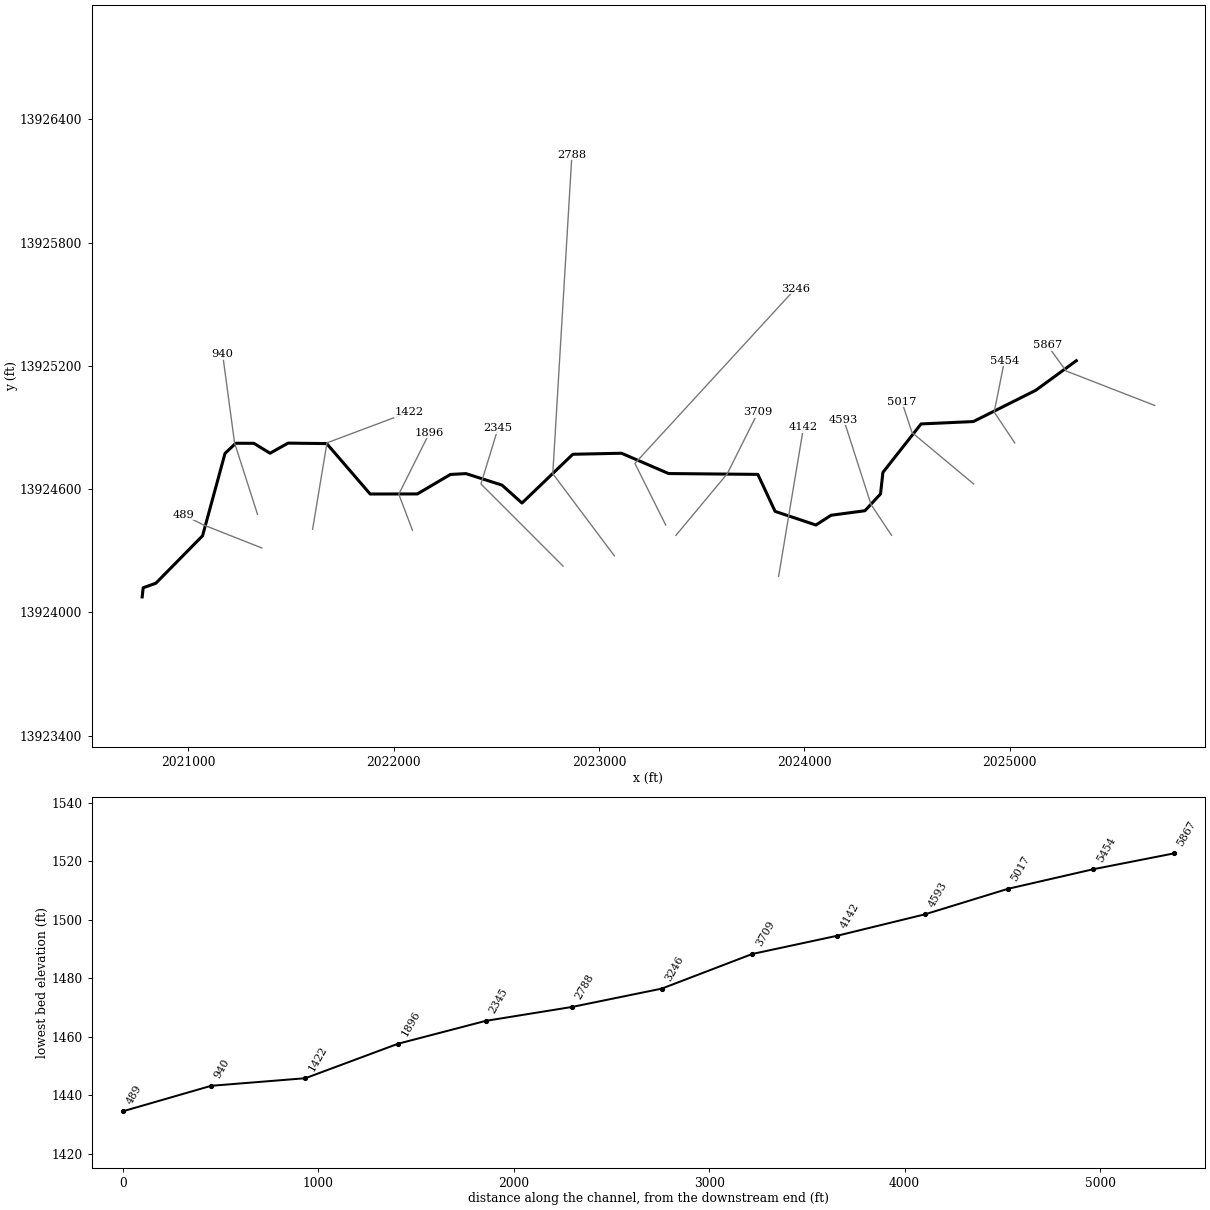
--- Stream0121_DS.prj (project) ---

Proj Title=Stream0121_DS Base Level Engineering
Current Plan=p01
Default Exp/Contr=0.3,0.1
English Units
Geom File=g01
Flow File=f01
Plan File=p01
BEGIN DESCRIPTION:
Stream0121_DS
END DESCRIPTION:

--- Stream0121_DS.p01 (plan) ---

Plan Title=Multiple Run
Short Identifier=Multiple
Geom File=g01
Flow File=f01
Subcritical Flow
K Sum by GR= 0
Std Step Tol= 0.01
Critical Tol= 0.01
Num of Std Step Trials= 20
Max Error Tol= 0.3
Flow Tol Ratio= 0.001
Split Flow NTrial= 30
Split Flow Tol= 0.02
Split Flow Ratio= 0.02
Log Output Level= 0
Friction Slope Method= 1
Unsteady Friction Slope Method= 2
Unsteady Bridges Friction Slope Method= 1
Parabolic Critical Depth
Global Vel Dist=  1 , 1 , 1
Global Log Level= 0
CheckData=True
Encroach Param= -1, 0, 0, 0
BEGIN DESCRIPTION:
Multiple Run
END DESCRIPTION:

--- Stream0121_DS.f01 (steady flow) ---

Flow Title=Multiple
Number of Profiles=7
Profile Names=10-year,25-year,50-year,1pct_min,100-year,1pct_plu,500-year
River Rch & RM= Stream0121_DS,Reach-1,5867
     867    1483    2077    1414    2822    5630    5158
River Rch & RM= Stream0121_DS,Reach-1,5454
    1242    2165    3069    2112    4215    8410    7880
River Rch & RM= Stream0121_DS,Reach-1,2788
    1363    2380    3379    2326    4642    9262    8689
Boundary for River Rch & Prof#=Stream0121_DS,Reach-1,1
Up Type=0
Dn Type=3
Dn Slope=0.005
Boundary for River Rch & Prof#=Stream0121_DS,Reach-1,2
Up Type=0
Dn Type=3
Dn Slope=0.005
Boundary for River Rch & Prof#=Stream0121_DS,Reach-1,3
Up Type=0
Dn Type=3
Dn Slope=0.005
Boundary for River Rch & Prof#=Stream0121_DS,Reach-1,4
Up Type=0
Dn Type=3
Dn Slope=0.005
Boundary for River Rch & Prof#=Stream0121_DS,Reach-1,5
Up Type=0
Dn Type=3
Dn Slope=0.005
Boundary for River Rch & Prof#=Stream0121_DS,Reach-1,6
Up Type=0
Dn Type=3
Dn Slope=0.005
Boundary for River Rch & Prof#=Stream0121_DS,Reach-1,7
Up Type=0
Dn Type=3
Dn Slope=0.005

--- Stream0121_DS.g01 (geometry) ---

Geom Title=Existing Conditions

River Reach=Stream0121_DS,Reach-1
Reach XY= 30
      2025325.00     13925225.00      2025127.29     13925080.85
      2024823.45     13924928.75      2024568.79     13924917.20
      2024382.88     13924681.16      2024371.39     13924576.48
      2024295.21     13924494.59      2024130.53     13924472.61
      2024056.66     13924425.06      2023857.87     13924491.45
      2023773.78     13924671.56      2023338.92     13924675.68
      2023109.78     13924774.48      2022872.55     13924769.54
      2022625.01     13924532.08      2022527.43     13924619.45
      2022352.24     13924675.28      2022276.58     13924671.33
      2022115.35     13924576.36      2021885.43     13924576.05
      2021673.75     13924821.55      2021485.50     13924823.76
      2021397.81     13924774.62      2021319.03     13924822.81
      2021230.69     13924823.12      2021178.51     13924773.75
      2021069.17     13924372.70      2020841.56     13924141.64
      2020779.92     13924119.67      2020775.00     13924075.00

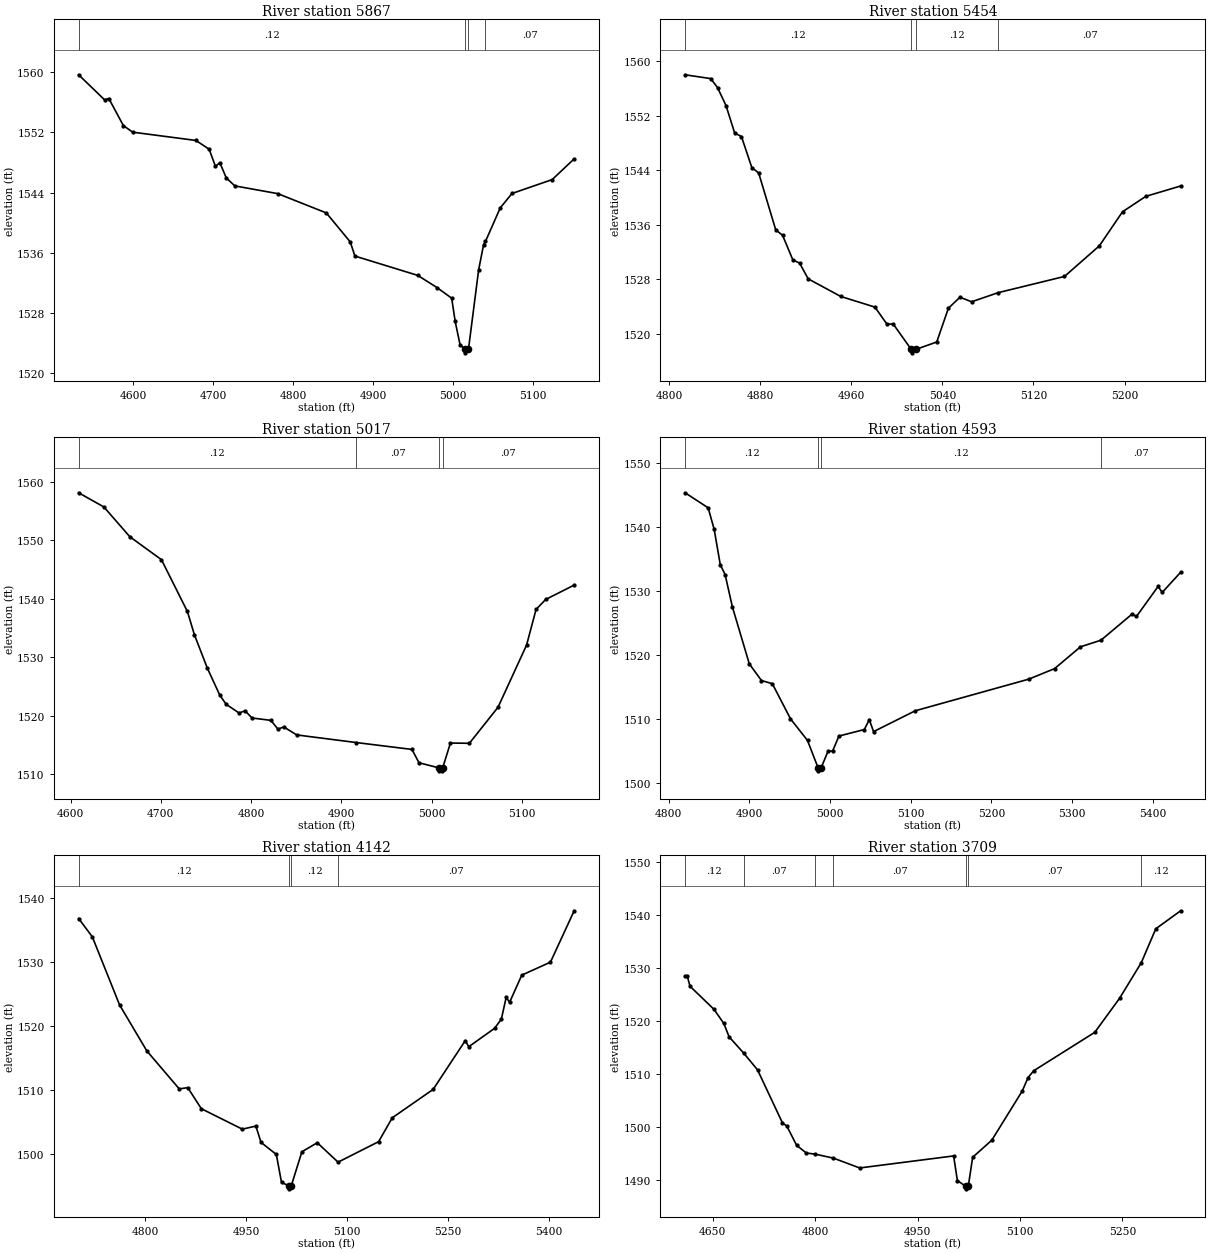
Type RM Length L Ch R = 1,5867,413,413,413
BEGIN DESCRIPTION:
Stream0121_DS 13.0
END DESCRIPTION:
XS GIS Cut Line= 3
      2025707.17     13925007.06      2025275.00     13925175.00
      2025183.20     13925301.43
#Sta/Elev= 30
  4531.9 1559.67  4564.3 1556.34  4569.7 1556.51  4587.9 1552.90  4599.6 1552.03
  4678.6 1550.93  4695.2 1549.76  4703.1 1547.47  4708.5 1547.98  4716.6 1545.94
  4727.3 1544.88  4781.0 1543.85  4841.8 1541.28  4871.7 1537.42  4877.5 1535.54
  4956.1 1532.97  4980.6 1531.32  4998.6 1529.93  5002.9 1526.87  5009.1 1523.71
  5015.6 1523.16  5015.8 1522.66  5019.6 1523.16  5032.3 1533.71  5038.5 1537.07
  5040.8 1537.48  5059.3 1541.95  5074.0 1543.87  5124.3 1545.72  5151.8 1548.48
#Mann=4,-1,0
  4531.9    0.12       0  5015.6    0.05       0  5019.6    0.12       0
  5040.8    0.07       0
Bank Sta=5015.6,5019.6
Exp/Cntr=0.3,0.1

Type RM Length L Ch R = 1,5454,437,437,437
BEGIN DESCRIPTION:
Stream0121_DS 12.0
END DESCRIPTION:
XS GIS Cut Line= 3
      2025024.98     13924825.03      2024925.00     13924975.00
      2024975.00     13925225.00
#Sta/Elev= 30
  4814.1 1557.98  4836.6 1557.42  4842.6 1556.10  4850.1 1553.44  4857.6 1549.46
  4863.6 1548.93  4872.7 1544.39  4878.7 1543.60  4893.7 1535.26  4899.7 1534.47
  4908.7 1530.88  4914.7 1530.38  4922.2 1528.09  4950.8 1525.51  4980.8 1523.95
  4991.3 1521.47  4996.9 1521.47  5012.7 1517.75  5013.0 1517.25  5016.7 1517.75
  5035.1 1518.84  5045.3 1523.77  5055.5 1525.40  5065.7 1524.73  5089.2 1526.07
  5147.3 1528.44  5177.9 1532.92  5198.3 1537.92  5218.7 1540.17  5249.3 1541.69
#Mann=4,-1,0
  4814.1    0.12       0  5012.7    0.05       0  5016.7    0.12       0
  5089.2    0.07       0
Bank Sta=5012.7,5016.7
Exp/Cntr=0.3,0.1

Type RM Length L Ch R = 1,5017,424,424,424
BEGIN DESCRIPTION:
Stream0121_DS 11.0
END DESCRIPTION:
XS GIS Cut Line= 3
      2024824.98     13924625.02      2024525.00     13924875.00
      2024475.00     13925025.00
#Sta/Elev= 30
  4609.0 1558.08  4637.0 1555.65  4665.6 1550.58  4700.7 1546.64  4729.4 1537.79
  4737.2 1533.80  4751.5 1528.10  4765.2 1523.51  4772.3 1521.93  4786.7 1520.43
  4793.2 1520.82  4801.0 1519.58  4821.8 1519.18  4829.6 1517.69  4836.1 1518.05
  4850.4 1516.69  4916.2 1515.39  4978.0 1514.21  4985.8 1511.93  5008.0 1511.05
  5008.3 1510.55  5011.8 1510.55  5012.0 1511.05  5020.6 1515.30  5041.6 1515.26
  5073.3 1521.42  5104.9 1532.04  5115.4 1538.14  5126.0 1539.84  5157.6 1542.30
#Mann=4,-1,0
  4609.0    0.12       0  4916.2    0.07       0  5008.0    0.05       0
  5012.0    0.07       0
Bank Sta=5008,5012
Exp/Cntr=0.3,0.1

Type RM Length L Ch R = 1,4593,451,451,451
BEGIN DESCRIPTION:
Stream0121_DS 10.0
END DESCRIPTION:
XS GIS Cut Line= 3
      2024425.01     13924374.98      2024325.00     13924525.00
      2024191.94     13924938.31
#Sta/Elev= 30
  4820.2 1545.32  4848.8 1542.97  4856.3 1539.58  4863.8 1534.09  4869.8 1532.54
  4878.8 1527.50  4899.8 1518.58  4914.9 1515.97  4928.4 1515.47  4950.9 1509.98
  4972.0 1506.60  4985.0 1502.35  4985.2 1501.85  4989.0 1502.35  4997.5 1504.94
  5003.1 1504.94  5011.0 1507.29  5042.5 1508.31  5048.6 1509.86  5053.9 1507.98
  5105.6 1511.24  5246.3 1516.18  5278.4 1517.83  5310.5 1521.24  5335.9 1522.27
  5374.6 1526.37  5379.9 1525.98  5406.7 1530.67  5411.9 1529.75  5434.7 1532.89
#Mann=4,-1,0
  4820.2    0.12       0  4985.0    0.05       0  4989.0    0.12       0
  5335.9    0.07       0
Bank Sta=4985,4989
Exp/Cntr=0.3,0.1

Type RM Length L Ch R = 1,4142,433,433,433
BEGIN DESCRIPTION:
Stream0121_DS 9.0
END DESCRIPTION:
XS GIS Cut Line= 3
      2023874.99     13924174.95      2023925.00     13924475.00
      2023996.32     13924901.80
#Sta/Elev= 30
  4700.6 1536.85  4720.9 1533.99  4761.5 1523.31  4802.0 1516.11  4850.2 1510.16
  4862.9 1510.35  4883.1 1507.05  4944.0 1503.85  4964.2 1504.33  4971.8 1501.78
  4994.6 1499.89  5002.3 1495.50  5012.9 1495.00  5013.2 1494.50  5016.9 1495.00
  5032.6 1500.31  5055.5 1501.72  5086.4 1498.68  5146.7 1501.89  5167.0 1505.63
  5227.8 1510.08  5275.6 1517.73  5280.7 1516.76  5319.1 1519.64  5329.2 1521.08
  5336.4 1524.49  5341.5 1523.73  5359.6 1527.98  5402.2 1530.01  5437.5 1538.06
#Mann=4,-1,0
  4700.6    0.12       0  5012.9    0.05       0  5016.9    0.12       0
  5086.4    0.07       0
Bank Sta=5012.9,5016.9
Exp/Cntr=0.3,0.1

Type RM Length L Ch R = 1,3709,463,463,463
BEGIN DESCRIPTION:
Stream0121_DS 8.0
END DESCRIPTION:
XS GIS Cut Line= 3
      2023374.97     13924374.96      2023625.00     13924675.00
      2023775.01     13924975.03
#Sta/Elev= 30
  4609.4 1528.39  4612.7 1528.39  4616.6 1526.53  4651.8 1522.16  4666.1 1519.51
  4673.9 1516.98  4695.2 1513.92  4715.5 1510.76  4752.0 1500.75  4758.5 1500.13
  4772.8 1496.51  4787.1 1495.05  4799.5 1494.86  4826.6 1494.10  4865.2 1492.24
  5002.8 1494.51  5008.3 1489.87  5020.3 1488.80  5020.6 1488.30  5024.3 1488.80
  5030.7 1494.26  5058.7 1497.47  5103.4 1506.77  5111.8 1509.28  5120.1 1510.58
  5209.6 1517.83  5245.9 1524.25  5277.7 1530.96  5299.0 1537.37  5335.4 1540.77
#Mann=7,-1,0
  4609.4    0.12       0  4695.2    0.07       0  4799.5    0.12       0
  4826.6    0.07       0  5020.3    0.05       0  5024.3    0.07       0
  5277.7    0.12       0
Bank Sta=5020.3,5024.3
Exp/Cntr=0.3,0.1

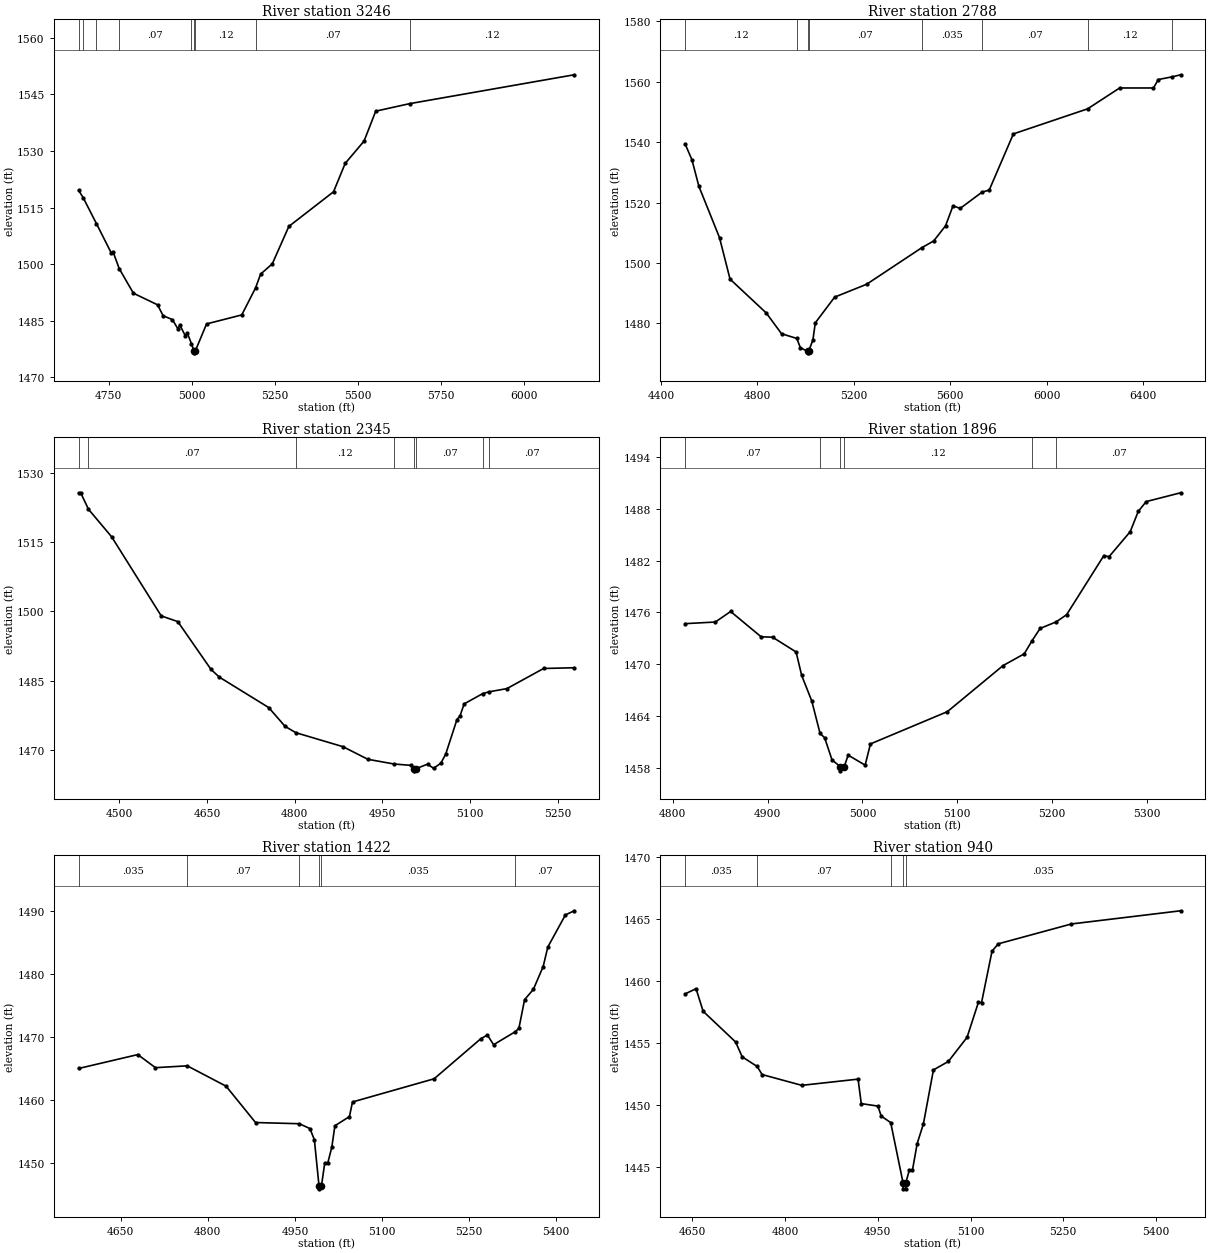
Type RM Length L Ch R = 1,3246,458,458,458
BEGIN DESCRIPTION:
Stream0121_DS 7.0
END DESCRIPTION:
XS GIS Cut Line= 3
      2023325.02     13924424.96      2023175.00     13924725.00
      2023957.54     13925576.34
#Sta/Elev= 30
  4660.0 1519.57  4673.9 1517.60  4713.6 1510.75  4757.9 1503.02  4763.5 1503.31
  4782.2 1498.80  4825.0 1492.28  4897.6 1489.21  4914.4 1486.31  4942.3 1485.29
  4959.1 1482.80  4964.7 1483.85  4981.5 1480.92  4987.1 1481.77  4999.6 1478.89
  5007.3 1476.97  5007.6 1476.47  5011.3 1476.97  5045.1 1484.14  5151.1 1486.53
  5192.7 1493.70  5207.8 1497.34  5243.0 1500.08  5292.9 1510.01  5427.3 1519.19
  5462.5 1526.73  5519.2 1532.63  5554.4 1540.58  5656.4 1542.57  6151.8 1550.23
#Mann=9,-1,0
  4660.0    0.12       0  4673.9    0.07       0  4713.6    0.12       0
  4782.2    0.07       0  4999.6    0.12       0  5007.3    0.05       0
  5011.3    0.12       0  5192.7    0.07       0  5656.4    0.12       0
Bank Sta=5007.3,5011.3
Exp/Cntr=0.3,0.1

Type RM Length L Ch R = 1,2788,443,443,443
BEGIN DESCRIPTION:
Stream0121_DS 6.0
END DESCRIPTION:
XS GIS Cut Line= 3
      2023074.98     13924275.03      2022775.00     13924675.00
      2022868.15     13926227.45
#Sta/Elev= 30
  4500.0 1539.40  4528.1 1534.21  4557.3 1525.34  4642.7 1508.38  4686.4 1494.63
  4836.4 1483.44  4900.0 1476.54  4963.3 1474.99  4978.1 1471.91  5007.9 1470.72
  5008.2 1470.22  5012.1 1470.72  5030.0 1474.45  5040.0 1480.15  5120.2 1488.67
  5252.9 1492.93  5481.7 1505.04  5530.9 1507.26  5580.2 1512.29  5611.1 1518.90
  5641.1 1518.06  5731.6 1523.44  5761.3 1524.12  5861.5 1542.72  6169.4 1551.02
  6302.3 1557.93  6442.6 1557.93  6462.6 1560.73  6521.3 1561.64  6555.2 1562.30
#Mann=8,-1,0
  4500.0    0.12       0  4963.3    0.07       0  5007.9    0.05       0
  5012.1    0.07       0  5481.7   0.035       0  5731.6    0.07       0
  6169.4    0.12       0  6521.3   0.035       0
Bank Sta=5007.9,5012.1
Exp/Cntr=0.3,0.1

Type RM Length L Ch R = 1,2345,449,449,449
BEGIN DESCRIPTION:
Stream0121_DS 5.0
END DESCRIPTION:
XS GIS Cut Line= 3
      2022824.99     13924225.01      2022425.00     13924625.00
      2022507.92     13924894.98
#Sta/Elev= 30
  4430.1 1525.70  4433.6 1525.70  4446.9 1522.14  4486.7 1516.14  4571.5 1499.02
  4599.8 1497.79  4656.4 1487.47  4670.5 1485.79  4755.4 1479.16  4783.6 1475.07
  4802.0 1473.71  4882.6 1470.68  4925.1 1467.95  4970.0 1466.93  4998.4 1466.64
  5004.1 1465.95  5004.4 1465.45  5008.3 1465.95  5027.2 1466.90  5037.6 1466.00
  5050.1 1467.11  5058.5 1469.13  5077.6 1476.57  5082.8 1477.34  5089.9 1479.96
  5121.8 1482.19  5132.8 1482.58  5163.1 1483.27  5225.9 1487.63  5278.2 1487.79
#Mann=8,-1,0
  4430.1    0.12       0  4446.9    0.07       0  4802.0    0.12       0
  4970.0    0.07       0  5004.1    0.05       0  5008.3    0.07       0
  5121.8   0.035       0  5132.8    0.07       0
Bank Sta=5004.1,5008.3
Exp/Cntr=0.3,0.1

Type RM Length L Ch R = 1,1896,474,474,474
BEGIN DESCRIPTION:
Stream0121_DS 4.0
END DESCRIPTION:
XS GIS Cut Line= 3
      2022091.25     13924400.11      2022025.00     13924575.00
      2022174.99     13924874.98
#Sta/Elev= 30
  4813.1 1474.69  4845.0 1474.88  4861.1 1476.10  4893.2 1473.17  4905.3 1473.12
  4930.1 1471.41  4936.0 1468.69  4946.6 1465.74  4955.4 1461.96  4960.2 1461.47
  4968.0 1458.89  4976.6 1458.13  4976.9 1457.63  4980.9 1458.13  4985.0 1459.45
  5002.9 1458.29  5008.5 1460.75  5089.6 1464.49  5148.3 1469.83  5170.6 1471.19
  5178.9 1472.72  5187.4 1474.14  5204.4 1474.90  5215.3 1475.73  5254.5 1482.57
  5260.1 1482.46  5282.4 1485.36  5290.8 1487.70  5299.2 1488.84  5335.5 1489.86
#Mann=6,-1,0
  4813.1    0.07       0  4955.4    0.12       0  4976.6    0.05       0
  4980.9    0.12       0  5178.9   0.035       0  5204.4    0.07       0
Bank Sta=4976.6,4980.9
Exp/Cntr=0.3,0.1

Type RM Length L Ch R = 1,1422,482,482,482
BEGIN DESCRIPTION:
Stream0121_DS 3.0
END DESCRIPTION:
XS GIS Cut Line= 3
      2021605.12     13924404.46      2021675.00     13924825.00
      2022075.00     13924975.00
#Sta/Elev= 30
  4577.5 1465.01  4679.4 1467.22  4709.8 1465.14  4764.6 1465.43  4831.5 1462.19
  4882.2 1456.41  4957.5 1456.22  4975.9 1455.45  4983.5 1453.67  4991.5 1446.36
  4991.8 1445.86  4995.8 1446.36  5001.3 1449.93  5006.5 1449.93  5013.6 1452.51
  5018.9 1455.90  5043.9 1457.35  5049.2 1459.68  5189.8 1463.37  5269.9 1469.72
  5281.5 1470.34  5292.2 1468.79  5329.4 1470.85  5335.8 1471.40  5345.6 1475.96
  5360.7 1477.59  5377.6 1481.23  5385.6 1484.33  5415.9 1489.44  5431.0 1490.10
#Mann=6,-1,0
  4577.5   0.035       0  4764.6    0.07       0  4957.5   0.035       0
  4991.5   0.035       0  4995.8   0.035       0  5329.4    0.07       0
Bank Sta=4991.5,4995.8
Exp/Cntr=0.3,0.1

Type RM Length L Ch R = 1,940,451,451,451
BEGIN DESCRIPTION:
Stream0121_DS 2.0
END DESCRIPTION:
XS GIS Cut Line= 3
      2021336.73     13924477.20      2021225.00     13924825.00
      2021166.76     13925257.39
#Sta/Elev= 30
  4638.3 1458.96  4656.0 1459.38  4667.5 1457.56  4720.0 1455.09  4730.7 1453.89
  4754.9 1453.12  4762.8 1452.47  4827.0 1451.60  4918.1 1452.10  4923.3 1450.13
  4950.2 1449.93  4955.5 1449.13  4970.9 1448.60  4990.8 1443.77  4991.1 1443.27
  4995.1 1443.27  4995.4 1443.77  5001.0 1444.78  5006.1 1444.78  5013.7 1446.91
  5023.8 1448.50  5040.0 1452.84  5064.1 1453.52  5094.4 1455.46  5112.8 1458.29
  5117.8 1458.25  5134.8 1462.40  5144.9 1462.99  5263.3 1464.59  5439.9 1465.65
#Mann=5,-1,0
  4638.3   0.035       0  4754.9    0.07       0  4970.9   0.035       0
  4990.8   0.035       0  4995.4   0.035       0
Bank Sta=4990.8,4995.4
Exp/Cntr=0.3,0.1

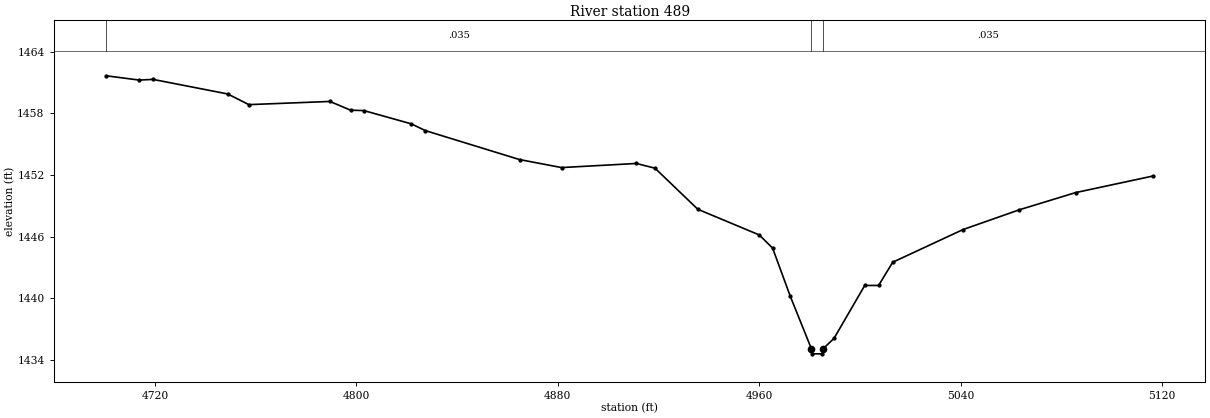
Type RM Length L Ch R = 1,489,0,0,0
BEGIN DESCRIPTION:
Stream0121_DS 1.0
END DESCRIPTION:
XS GIS Cut Line= 3
      2021357.72     13924313.34      2021075.00     13924425.00
      2020974.98     13924475.01
#Sta/Elev= 30
  4700.6 1461.66  4713.8 1461.24  4719.2 1461.31  4748.9 1459.89  4757.3 1458.85
  4789.5 1459.16  4797.7 1458.31  4803.0 1458.27  4821.8 1456.98  4827.4 1456.32
  4864.8 1453.50  4881.5 1452.72  4911.2 1453.12  4918.6 1452.66  4935.6 1448.66
  4960.0 1446.16  4965.3 1444.88  4972.3 1440.20  4980.7 1435.08  4981.1 1434.58
  4985.1 1434.58  4985.4 1435.08  4989.7 1436.09  5001.9 1441.24  5007.4 1441.24
  5013.0 1443.50  5040.9 1446.68  5063.3 1448.61  5085.6 1450.28  5116.4 1451.90
#Mann=3,-1,0
  4700.6   0.035       0  4980.7   0.035       0  4985.4   0.035       0
Bank Sta=4980.7,4985.4
Exp/Cntr=0.3,0.1

Chan Stop Cuts=-1