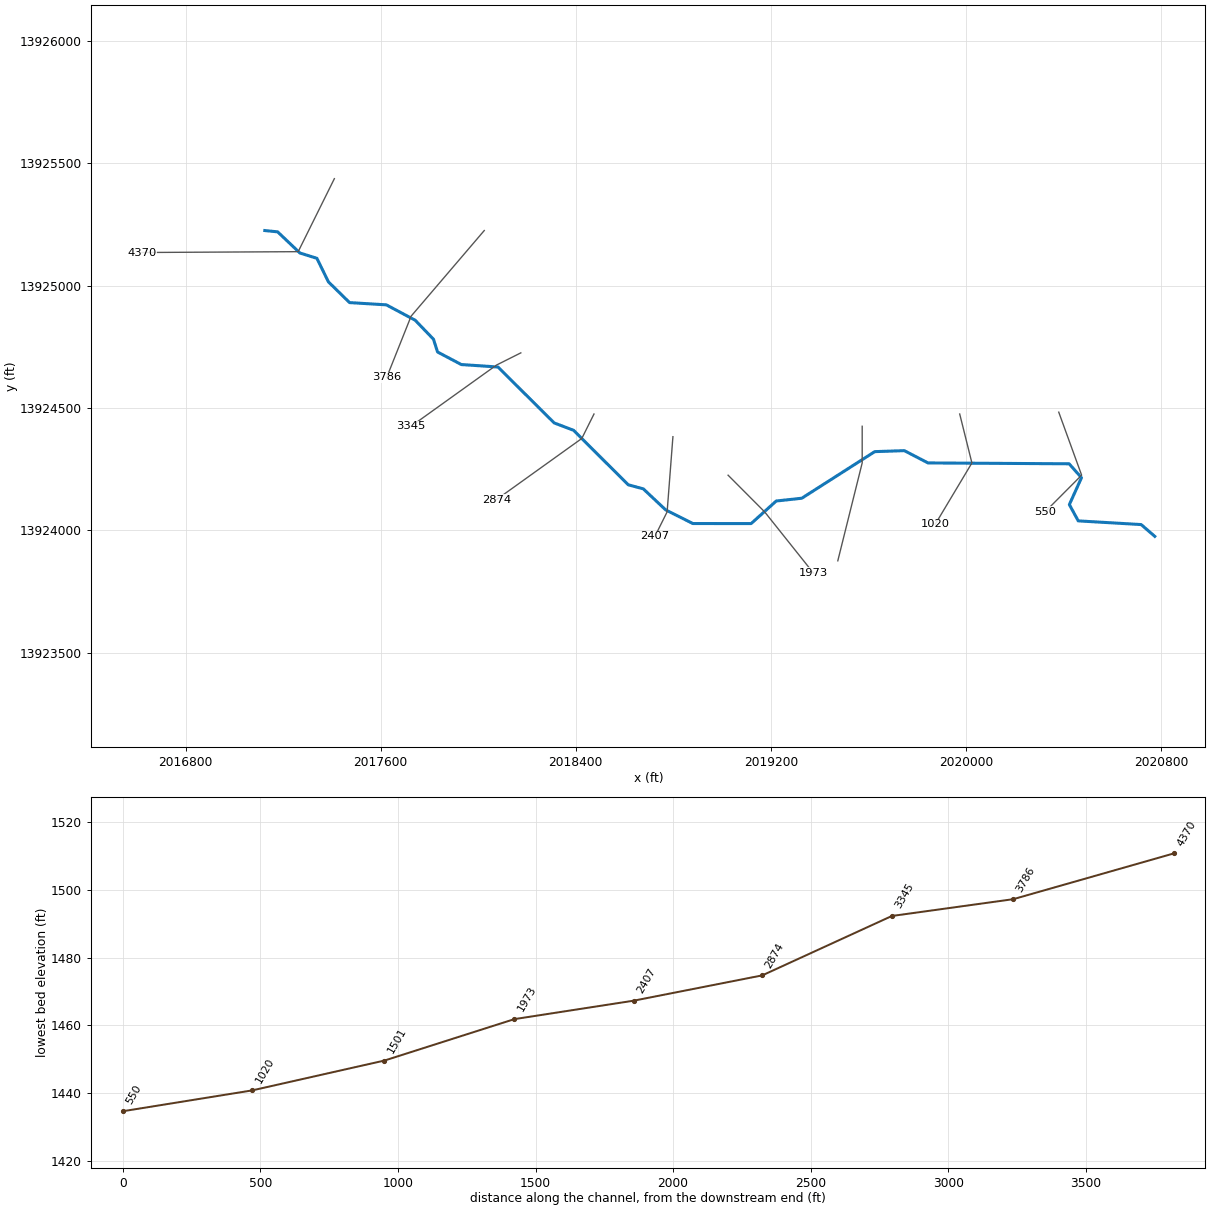
--- Stream0122_DS.prj (project) ---

Proj Title=Stream0122_DS Base Level Engineering
Current Plan=p01
Default Exp/Contr=0.3,0.1
English Units
Geom File=g01
Flow File=f01
Plan File=p01
Y Axis Title=Elevation
X Axis Title(PF)=Main Channel Distance
X Axis Title(XS)=Station
BEGIN DESCRIPTION:
Stream0122_DS
END DESCRIPTION:
DSS Export Rating Curves= 0
DSS Export Rating Curve Sorted= 0
DSS Export Volume Flow Curves= 0
DXF OffsetX= 0
DXF OffsetY= 0
DXF ScaleX= 1
DXF ScaleY= 10

--- Stream0122_DS.p01 (plan) ---

Plan Title=Multiple Run
Short Identifier=Multiple
Geom File=g01
Flow File=f01
Subcritical Flow
K Sum by GR= 0
Std Step Tol= 0.01
Critical Tol= 0.01
Num of Std Step Trials= 20
Max Error Tol= 0.3
Flow Tol Ratio= 0.001
Split Flow NTrial= 30
Split Flow Tol= 0.02
Split Flow Ratio= 0.02
Log Output Level= 0
Friction Slope Method= 1
Unsteady Friction Slope Method= 2
Unsteady Bridges Friction Slope Method= 1
Parabolic Critical Depth
Global Vel Dist=  1 , 1 , 1
Global Log Level= 0
CheckData=True
Encroach Param= -1, 0, 0, 0
BEGIN DESCRIPTION:
Multiple Run
END DESCRIPTION:

--- Stream0122_DS.f01 (steady flow) ---

Flow Title=Multiple
Number of Profiles=7
Profile Names=10-year,25-year,50-year,1pct_min,100-year,1pct_plu,500-year
River Rch & RM= Stream0122_DS,Reach-1,4370
    1351    2361    3353    2310    4609    9197    8638
Boundary for River Rch & Prof#=Stream0122_DS,Reach-1,1
Up Type=0
Dn Type=3
Dn Slope=0.005
Boundary for River Rch & Prof#=Stream0122_DS,Reach-1,2
Up Type=0
Dn Type=3
Dn Slope=0.005
Boundary for River Rch & Prof#=Stream0122_DS,Reach-1,3
Up Type=0
Dn Type=3
Dn Slope=0.005
Boundary for River Rch & Prof#=Stream0122_DS,Reach-1,4
Up Type=0
Dn Type=3
Dn Slope=0.005
Boundary for River Rch & Prof#=Stream0122_DS,Reach-1,5
Up Type=0
Dn Type=3
Dn Slope=0.005
Boundary for River Rch & Prof#=Stream0122_DS,Reach-1,6
Up Type=0
Dn Type=3
Dn Slope=0.005
Boundary for River Rch & Prof#=Stream0122_DS,Reach-1,7
Up Type=0
Dn Type=3
Dn Slope=0.005

--- Stream0122_DS.g01 (geometry) ---

Geom Title=Existing Conditions
Program Version=4.10

River Reach=Stream0122_DS   ,Reach-1
Reach XY= 30
        2017125.       13925225.      2017177.51     13925219.67
      2017268.97     13925133.17      2017338.56     13925111.51
      2017385.78     13925015.31      2017472.54     13924930.46
      2017623.44     13924921.24      2017741.71     13924858.37
      2017816.72     13924780.77      2017833.48     13924728.51
      2017930.91     13924677.24      2018081.19     13924667.18
      2018311.79     13924438.63      2018391.67     13924408.35
      2018615.32     13924185.78      2018677.28     13924169.13
      2018768.95     13924083.16      2018880.52     13924027.35
      2019119.55     13924027.18      2019222.58     13924119.46
      2019327.32     13924130.77      2019626.56     13924321.26
      2019747.83     13924325.31      2019845.03     13924275.07
      2020423.81     13924271.55      2020474.47     13924214.55
      2020424.62     13924104.72      2020461.19     13924038.22
      2020719.22     13924023.11        2020775.       13923975.

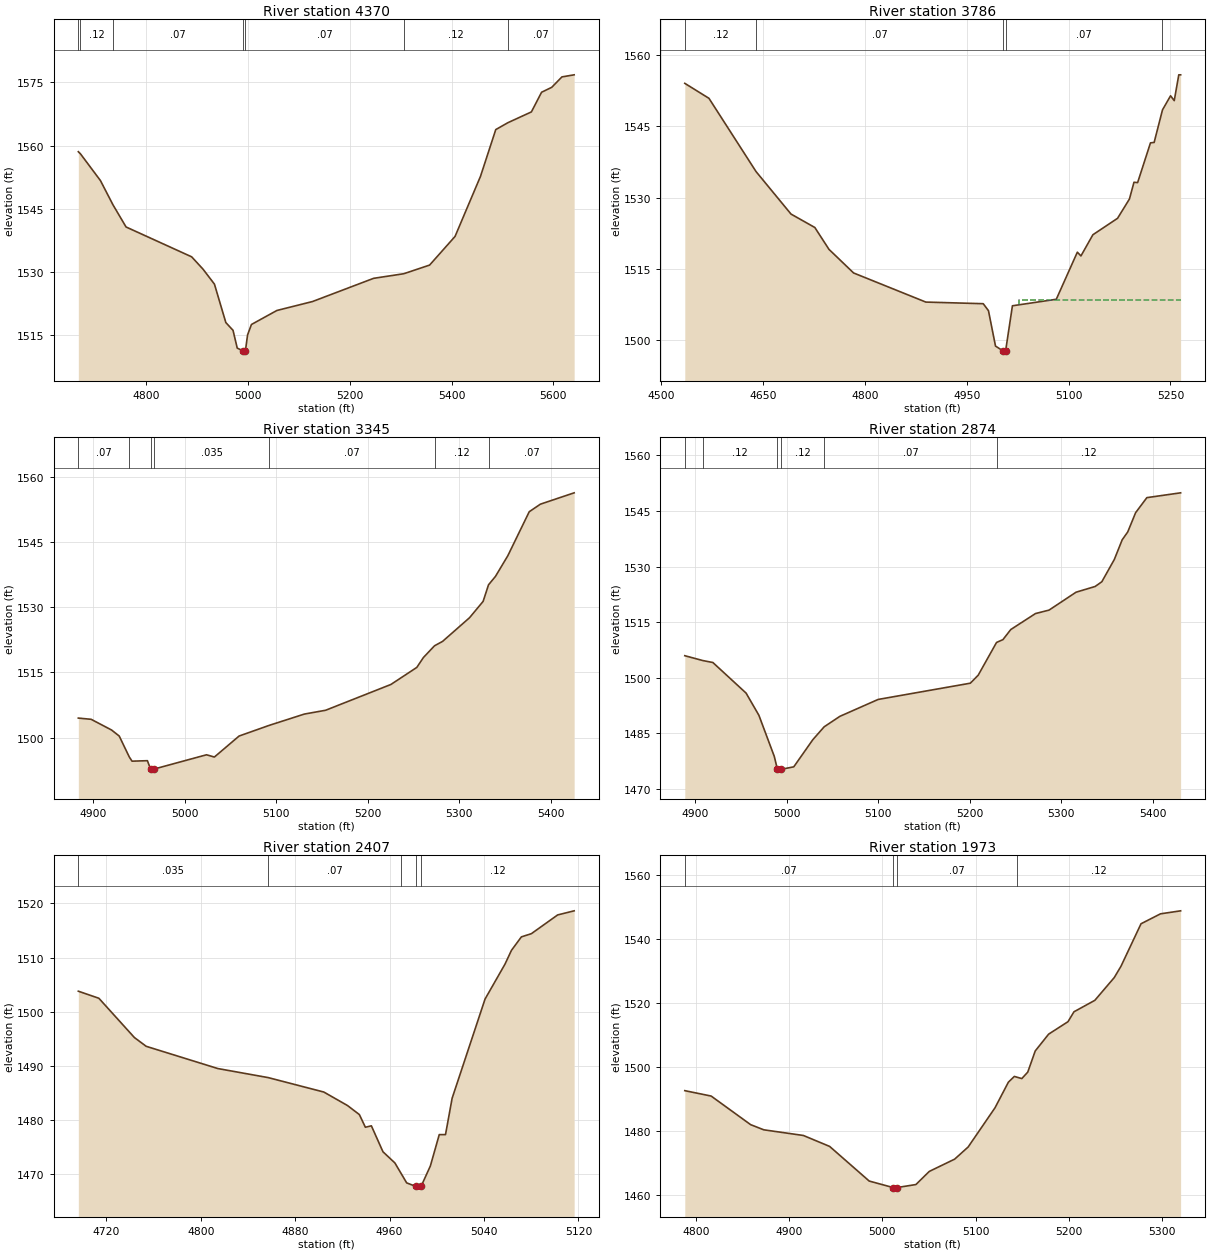
Type RM Length L Ch R = 1 ,4370    ,584,584,584
BEGIN DESCRIPTION:
Stream0122_DS 9.0
END DESCRIPTION:
XS GIS Cut Line= 3
      2017410.25     13925437.06      2017261.81     13925138.64
      2016621.01     13925135.21
#Sta/Elev= 30
  4666.7 1558.53  4670.9 1558.03  4710.1  1551.7  4734.8 1545.94  4760.5 1540.69
  4889.3 1533.62  4911.7 1530.69  4934.1 1527.15  4956.5 1518.03  4970.6  1516.2
  4978.9 1511.98  4990.9 1511.29  4991.1 1510.79  4994.9 1511.29  4999.2 1515.11
  5006.8 1517.58  5056.8  1520.9  5126.8 1523.02  5246.8 1528.52  5306.1 1529.61
  5356.8 1531.66  5406.8 1538.45  5456.8  1552.7  5486.8 1563.78  5510.6 1565.41
  5556.8 1567.97  5576.8 1572.63  5596.8  1573.8  5616.8 1576.27  5640.8 1576.76
#Mann= 7 ,-1 , 0
  4666.7     .07       0  4670.9     .12       0  4734.8     .07       0
  4990.9     .05       0  4994.9     .07       0  5306.1     .12       0
  5510.6     .07       0
Bank Sta=4990.9,4994.9
XS Rating Curve= 0 ,0
Exp/Cntr=0.3,0.1

Type RM Length L Ch R = 1 ,3786    ,441,441,441
BEGIN DESCRIPTION:
Stream0122_DS 8.0
END DESCRIPTION:
XS GIS Cut Line= 3
      2018024.97     13925224.97        2017725.       13924875.
        2017625.     13924624.99
#Sta/Elev= 30
  4534.8 1554.09  4570.4 1550.93  4639.7 1535.51  4691.2 1526.56  4726.3 1523.73
  4747.1 1519.13  4783.4 1514.15  4889.8 1508.02  4974.3 1507.68    4982 1506.21
  4992.4 1498.75  5003.1 1497.77  5003.3 1497.27  5007.3 1497.77  5017.3 1507.24
  5081.9 1508.61  5112.9 1518.53  5118.2 1517.74  5135.8  1522.2  5172.1 1525.66
  5189.6 1529.72  5196.3 1533.25  5201.7 1533.19  5220.6 1541.55    5226 1541.64
  5238.3  1548.5  5250.2 1551.47  5255.6 1550.44  5262.3 1555.88    5265 1555.88
#Mann= 5 ,-1 , 0
  4534.8     .12       0  4639.7     .07       0  5003.1     .05       0
  5007.3     .07       0  5238.3     .12       0
#XS Ineff= 2 , 0
       0                  5027.5       0  1508.5
Permanent Ineff=
       F       F
Bank Sta=5003.1,5007.3
XS Rating Curve= 0 ,0
Exp/Cntr=0.3,0.1

Type RM Length L Ch R = 1 ,3345    ,471,471,471
BEGIN DESCRIPTION:
Stream0122_DS 7.0
END DESCRIPTION:
XS GIS Cut Line= 3
      2018174.99       13924725.        2018075.       13924675.
      2017725.01     13924425.01
#Sta/Elev= 30
  4883.5 1504.51  4897.5 1504.23  4919.8 1501.77  4928.2 1500.38  4939.2 1495.56
  4942.2  1494.6    4959 1494.71  4962.4 1492.81  4962.7 1492.31  4966.4 1492.31
  4966.7 1492.81  5023.6 1496.07  5032.2 1495.55  5059.2 1500.38  5091.9 1502.82
  5130.5 1505.43  5153.8 1506.31  5225.1 1512.24  5253.4 1516.16  5260.7 1518.45
  5272.8 1521.14  5281.6 1522.15  5311.1  1527.6  5325.9 1531.35  5331.8 1535.16
  5339.4  1537.1  5352.9 1541.85  5376.3 1551.97  5388.5 1553.71  5425.4 1556.32
#Mann= 7 ,-1 , 0
  4883.5     .07       0  4939.2    .035       0  4962.4    .035       0
  4966.7    .035       0  5091.9     .07       0  5272.8     .12       0
  5331.8     .07       0
Bank Sta=4962.4,4966.7
XS Rating Curve= 0 ,0
Exp/Cntr=0.3,0.1

Type RM Length L Ch R = 1 ,2874    ,467,467,467
BEGIN DESCRIPTION:
Stream0122_DS 6.0
END DESCRIPTION:
XS GIS Cut Line= 3
      2018474.98     13924474.96        2018425.       13924375.
      2018074.98     13924124.98
#Sta/Elev= 30
  4888.5 1505.93  4908.2 1504.62  4919.2 1504.09  4955.5 1495.83  4969.5 1489.84
  4986.3 1478.75  4989.7 1475.27    4990 1474.77    4994 1475.27  5007.6 1475.93
  5028.5 1483.28  5040.8 1486.73    5058 1489.56  5099.8 1494.12  5200.6 1498.51
  5209.2 1500.68  5229.2  1509.5  5236.2 1510.27  5244.8    1513  5271.8 1517.31
  5286.6 1518.24  5316.1 1523.07    5337 1524.62  5344.3  1525.9  5357.9 1531.89
  5366.5  1537.2  5372.6 1539.34  5381.2 1544.53  5393.5  1548.6  5430.4  1549.9
#Mann= 6 ,-1 , 0
  4888.5     .07       0  4908.2     .12       0  4989.7     .05       0
    4994     .12       0  5040.8     .07       0  5229.2     .12       0
Bank Sta=4989.7,4994
XS Rating Curve= 0 ,0
Exp/Cntr=0.3,0.1

Type RM Length L Ch R = 1 ,2407    ,434,434,434
BEGIN DESCRIPTION:
Stream0122_DS 5.0
END DESCRIPTION:
XS GIS Cut Line= 3
      2018798.76     13924382.37        2018775.       13924075.
        2018725.     13923974.99
#Sta/Elev= 30
  4696.3 1503.79  4713.7 1502.49  4743.8 1495.25  4753.8 1493.63  4814.5 1489.53
  4857.2 1487.86  4904.3  1485.2  4924.3 1482.72  4934.4 1481.05  4939.5 1478.71
  4944.6 1478.97  4954.4 1474.19  4964.5 1472.13  4969.4 1470.33  4974.5 1468.45
  4982.3  1467.8  4982.6  1467.3  4986.4  1467.3  4986.7  1467.8  4994.6 1471.59
  5002.1 1477.35  5007.4 1477.35    5013 1484.05  5040.9 1502.34  5057.7 1508.74
  5063.3 1511.33  5071.7 1513.81  5080.1 1514.39  5102.4 1517.85  5116.4 1518.61
#Mann= 5 ,-1 , 0
  4696.3    .035       0  4857.2     .07       0  4969.4     .12       0
  4982.3     .05       0  4986.7     .12       0
Bank Sta=4982.3,4986.7
XS Rating Curve= 0 ,0
Exp/Cntr=0.3,0.1

Type RM Length L Ch R = 1 ,1973    ,472,472,472
BEGIN DESCRIPTION:
Stream0122_DS 4.0
END DESCRIPTION:
XS GIS Cut Line= 3
      2019025.02     13924224.98        2019175.       13924075.
      2019375.02     13923824.97
#Sta/Elev= 30
  4787.9 1492.63  4816.2 1490.94  4858.6    1482  4872.7 1480.39  4915.2 1478.62
  4943.4  1475.2  4985.9 1464.37  5011.4 1462.35  5011.7 1461.85  5015.8 1462.35
    5036 1463.28  5050.4 1467.39  5077.6 1471.22  5092.1 1475.02  5120.9 1487.26
  5135.3 1495.28  5141.7 1497.08  5144.6 1496.83  5149.7  1496.4  5156.1 1498.43
  5164.1 1505.03  5178.5 1510.29  5199.3 1514.19  5205.7 1517.28  5228.1 1520.86
  5248.9 1527.96  5256.1 1531.47  5277.7  1544.8  5298.6  1547.9  5320.2 1548.84
#Mann= 4 ,-1 , 0
  4787.9     .07       0  5011.4     .05       0  5015.8     .07       0
  5144.6     .12       0
Bank Sta=5011.4,5015.8
XS Rating Curve= 0 ,0
Exp/Cntr=0.3,0.1

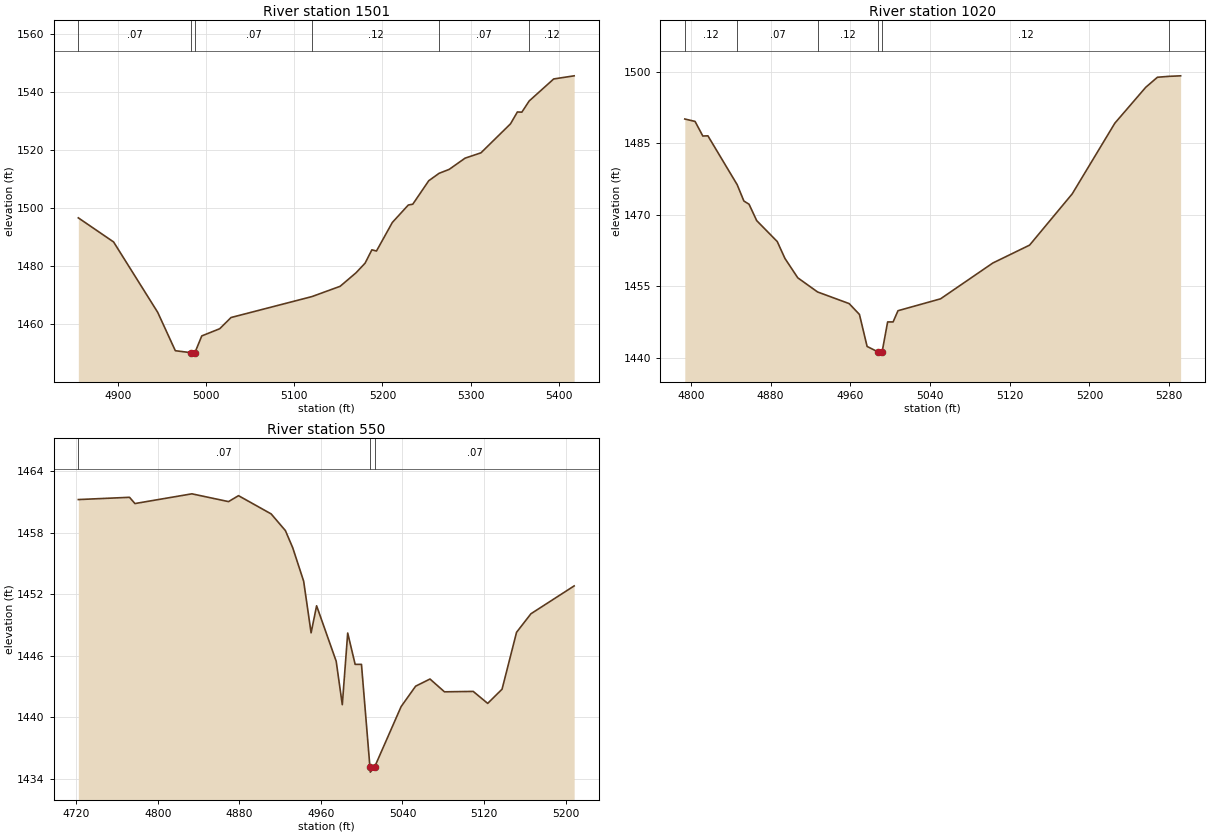
Type RM Length L Ch R = 1 ,1501    ,481,481,481
BEGIN DESCRIPTION:
Stream0122_DS 3.0
END DESCRIPTION:
XS GIS Cut Line= 3
        2019575.     13924424.98        2019575.       13924275.
        2019475.     13923874.99
#Sta/Elev= 30
  4855.1 1496.66  4895.1 1488.34  4945.1 1464.06  4965.1  1450.8  4982.8 1450.12
  4983.1 1449.62  4987.3 1450.12  4995.1 1455.91  5015.4 1458.38  5028.3 1462.26
    5120 1469.48    5152 1473.03    5170 1477.69  5180.3 1481.02    5188 1485.63
  5193.2 1485.21  5211.2 1495.07  5229.3 1501.09  5234.4 1501.38  5252.5 1509.48
  5264.2 1512.03  5275.7  1513.4  5293.7 1517.27  5311.7 1519.11  5345.2 1529.11
    5353 1533.21  5358.1 1533.15  5366.4 1537.01  5394.2 1544.61  5417.4 1545.69
#Mann= 6 ,-1 , 0
  4855.1     .07       0  4982.8     .05       0  4987.3     .07       0
    5120     .12       0  5264.2     .07       0  5366.4     .12       0
Bank Sta=4982.8,4987.3
XS Rating Curve= 0 ,0
Exp/Cntr=0.3,0.1

Type RM Length L Ch R = 1 ,1020    ,470,470,470
BEGIN DESCRIPTION:
Stream0122_DS 2.0
END DESCRIPTION:
XS GIS Cut Line= 3
      2019974.99     13924475.03        2020025.       13924275.
      2019875.02     13924025.03
#Sta/Elev= 30
  4793.8 1490.09  4804.1 1489.58  4811.9 1486.52    4817 1486.56  4846.4 1476.31
  4853.1  1472.9  4858.3 1472.22    4866 1468.78  4886.6  1464.4  4894.3 1460.87
  4907.2  1456.8  4927.1 1453.83  4958.8 1451.39  4969.1 1449.12  4976.8 1442.41
  4987.4  1441.3  4987.7  1440.8  4991.9  1441.3  4997.4 1447.55  5002.9 1447.55
  5007.8  1449.9  5050.5 1452.39    5103  1459.9  5139.9 1463.65  5182.7  1474.4
  5225.5 1489.22  5256.5 1496.74  5268.2 1498.84  5279.7 1499.03  5291.5 1499.14
#Mann= 6 ,-1 , 0
  4793.8     .12       0  4846.4     .07       0  4927.1     .12       0
  4987.4     .05       0  4991.9     .12       0  5279.7     .07       0
Bank Sta=4987.4,4991.9
XS Rating Curve= 0 ,0
Exp/Cntr=0.3,0.1

Type RM Length L Ch R = 1 ,550     ,0,0,0
BEGIN DESCRIPTION:
Stream0122_DS 1.0
END DESCRIPTION:
XS GIS Cut Line= 3
      2020381.16     13924482.64        2020475.       13924225.
      2020325.02     13924075.02
#Sta/Elev= 30
  4722.1 1461.26  4772.3 1461.48  4777.6 1460.87  4833.5 1461.82  4869.4 1461.06
  4879.2 1461.64  4911.2 1459.86  4925.2 1458.23  4932.4 1456.55  4943.1 1453.29
  4950.4 1448.25  4955.8 1450.89    4975 1445.48    4981 1441.23  4986.3 1448.23
  4993.6 1445.17  4999.8 1445.17  5008.1 1435.15  5008.5 1434.65  5012.7 1435.15
  5038.7 1441.05  5052.9 1443.04    5067 1443.74  5081.2 1442.49  5109.4 1442.53
  5123.6 1441.36  5137.7 1442.75  5151.9  1448.3    5166 1450.11  5208.4 1452.83
#Mann= 3 ,-1 , 0
  4722.1     .07       0  5008.1     .05       0  5012.7     .07       0
Bank Sta=5008.1,5012.7
XS Rating Curve= 0 ,0
Exp/Cntr=0.3,0.1

Chan Stop Cuts=-1
Use User Specified Reach Order=0
Composite Channel Slope=5