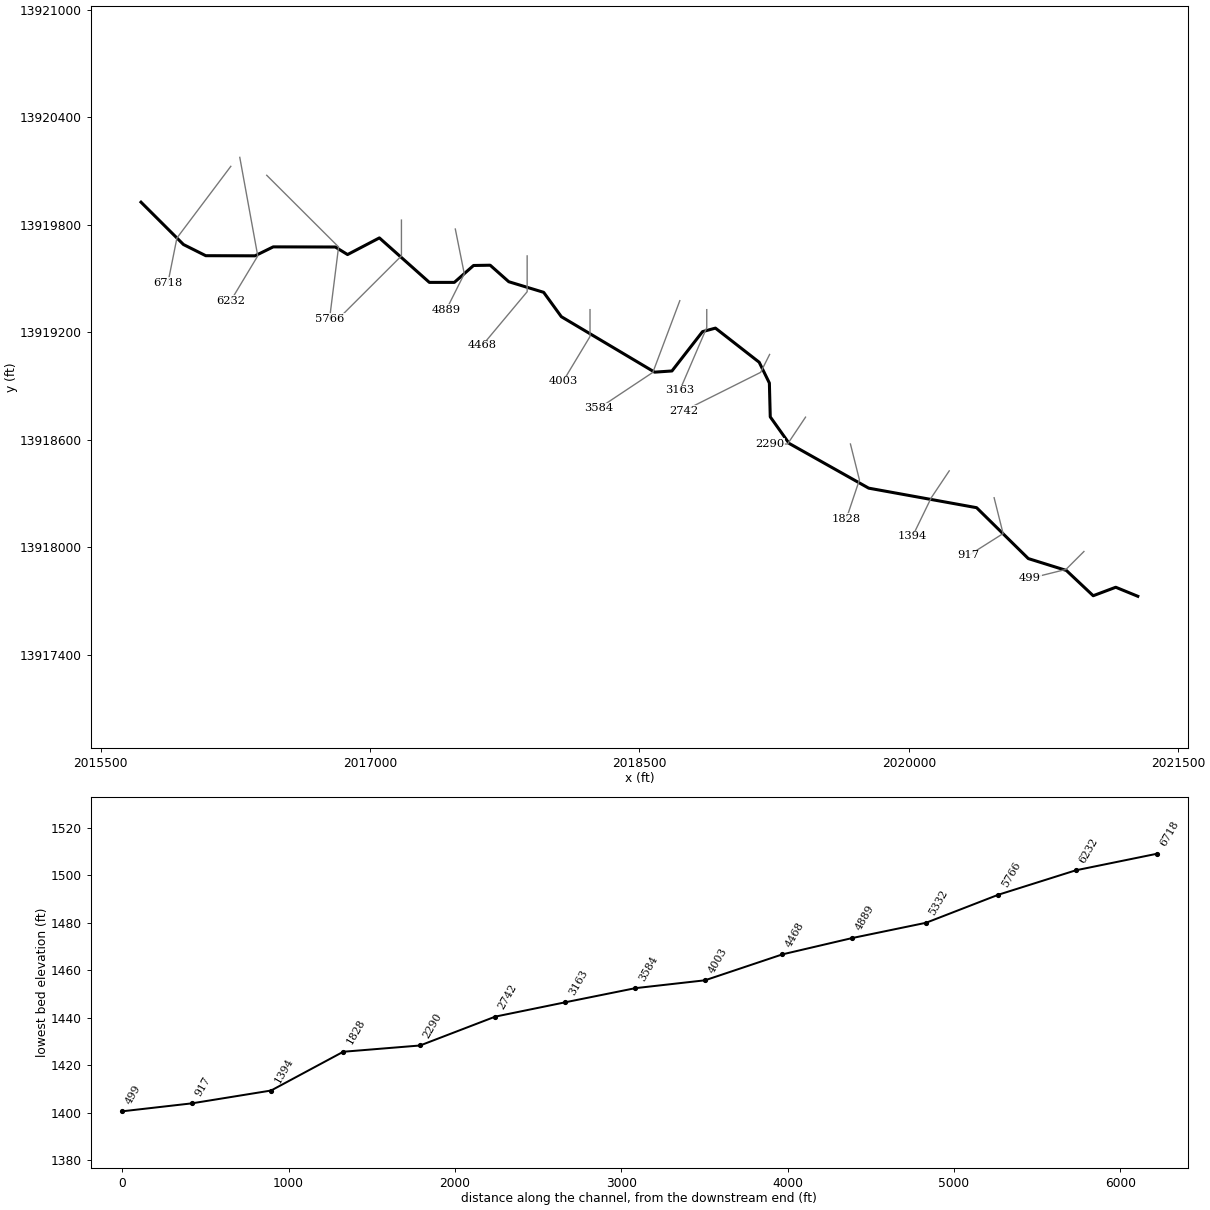
--- Stream0123_DS.prj (project) ---

Proj Title=Stream0123_DS Base Level Engineering
Current Plan=p01
Default Exp/Contr=0.3,0.1
English Units
Geom File=g01
Flow File=f01
Plan File=p01
BEGIN DESCRIPTION:
Stream0123_DS
END DESCRIPTION:

--- Stream0123_DS.p01 (plan) ---

Plan Title=Multiple Run
Short Identifier=Multiple
Geom File=g01
Flow File=f01
Subcritical Flow
K Sum by GR= 0
Std Step Tol= 0.01
Critical Tol= 0.01
Num of Std Step Trials= 20
Max Error Tol= 0.3
Flow Tol Ratio= 0.001
Split Flow NTrial= 30
Split Flow Tol= 0.02
Split Flow Ratio= 0.02
Log Output Level= 0
Friction Slope Method= 1
Unsteady Friction Slope Method= 2
Unsteady Bridges Friction Slope Method= 1
Parabolic Critical Depth
Global Vel Dist=  1 , 1 , 1
Global Log Level= 0
CheckData=True
Encroach Param= -1, 0, 0, 0
BEGIN DESCRIPTION:
Multiple Run
END DESCRIPTION:

--- Stream0123_DS.f01 (steady flow) ---

Flow Title=Multiple
Number of Profiles=7
Profile Names=10-year,25-year,50-year,1pct_min,100-year,1pct_plu,500-year
River Rch & RM= Stream0123_DS,Reach-1,6718
    1581    2784    3974    2750    5486   10946   10375
Boundary for River Rch & Prof#=Stream0123_DS,Reach-1,1
Up Type=0
Dn Type=3
Dn Slope=0.005
Boundary for River Rch & Prof#=Stream0123_DS,Reach-1,2
Up Type=0
Dn Type=3
Dn Slope=0.005
Boundary for River Rch & Prof#=Stream0123_DS,Reach-1,3
Up Type=0
Dn Type=3
Dn Slope=0.005
Boundary for River Rch & Prof#=Stream0123_DS,Reach-1,4
Up Type=0
Dn Type=3
Dn Slope=0.005
Boundary for River Rch & Prof#=Stream0123_DS,Reach-1,5
Up Type=0
Dn Type=3
Dn Slope=0.005
Boundary for River Rch & Prof#=Stream0123_DS,Reach-1,6
Up Type=0
Dn Type=3
Dn Slope=0.005
Boundary for River Rch & Prof#=Stream0123_DS,Reach-1,7
Up Type=0
Dn Type=3
Dn Slope=0.005

--- Stream0123_DS.g01 (geometry) ---

Geom Title=Existing Conditions

River Reach=Stream0123_DS,Reach-1
Reach XY= 30
      2015725.00     13919925.00      2015961.44     13919688.48
      2016085.50     13919626.20      2016359.78     13919625.52
      2016461.18     13919675.44      2016806.78     13919674.67
      2016875.01     13919632.53      2017052.24     13919725.49
      2017330.45     13919477.17      2017469.55     13919477.17
      2017576.50     13919571.53      2017669.10     13919573.03
      2017772.71     13919480.85      2017966.95     13919421.68
      2018065.30     13919285.77      2018584.64     13918976.09
      2018681.19     13918982.75      2018851.49     13919202.32
      2018923.35     13919221.90      2019166.98     13919031.34
      2019223.64     13918915.35      2019228.55     13918726.47
      2019333.48     13918578.51      2019776.50     13918328.62
      2020377.45     13918219.54      2020665.21     13917935.52
      2020877.30     13917869.17      2021026.63     13917728.13
      2021152.19     13917775.45      2021275.00     13917725.00

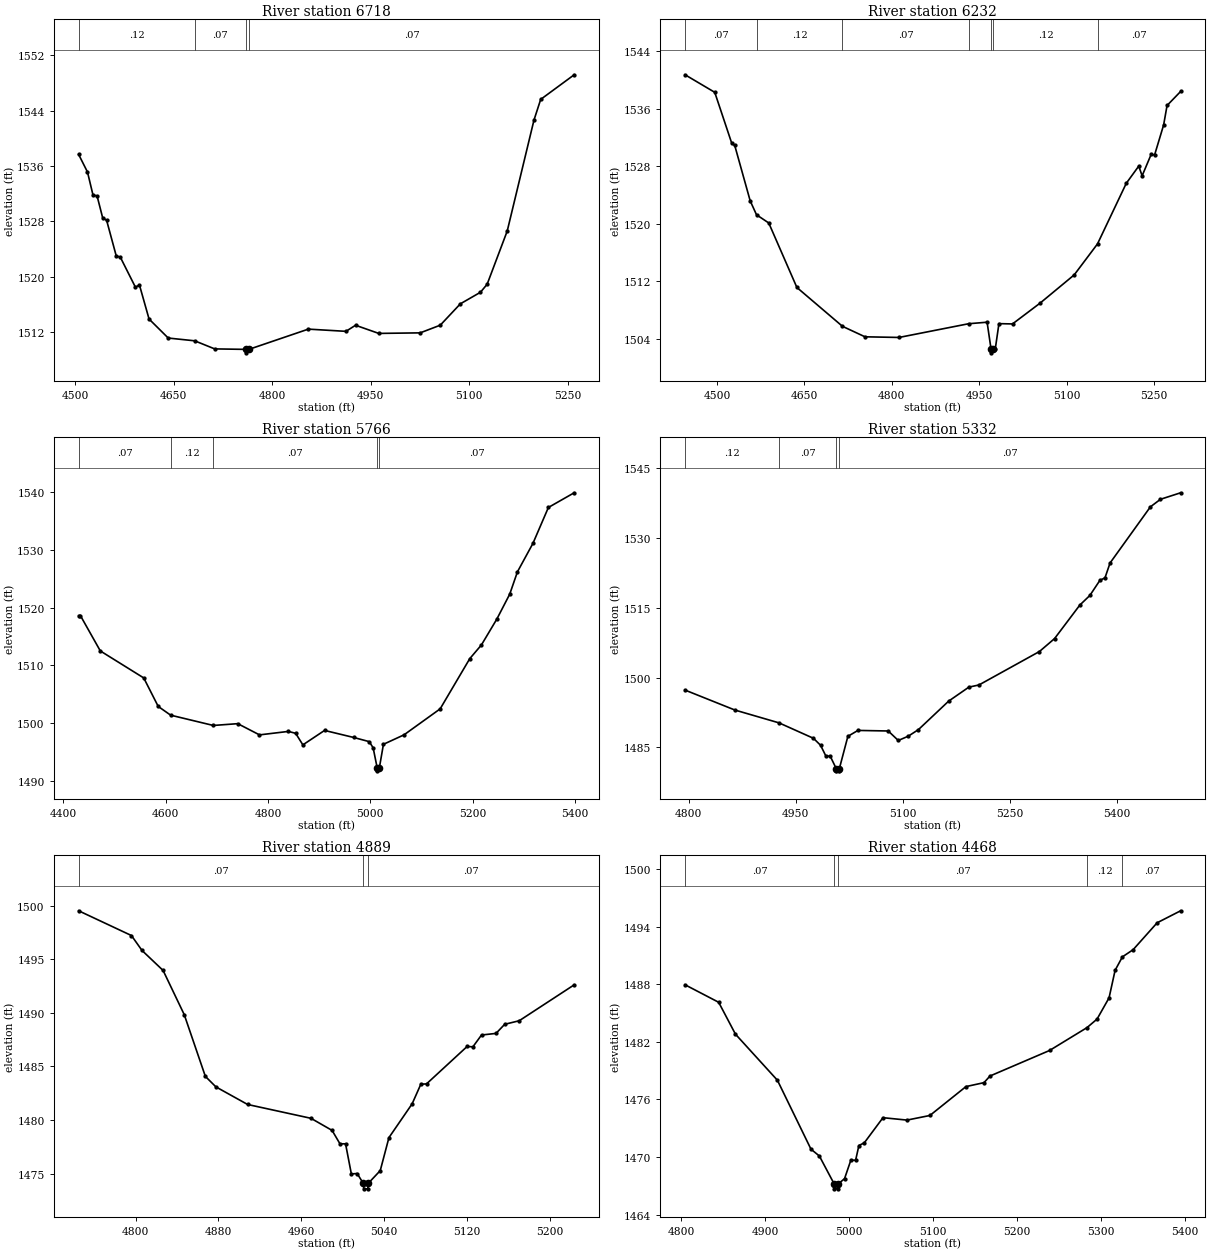
Type RM Length L Ch R = 1,6718,486,486,486
BEGIN DESCRIPTION:
Stream0123_DS 15.0
END DESCRIPTION:
XS GIS Cut Line= 3
      2016225.00     13920125.00      2015925.00     13919725.00
      2015874.99     13919474.95
#Sta/Elev= 30
  4505.1 1537.68  4518.6 1535.13  4527.0 1531.80  4533.2 1531.68  4541.6 1528.55
  4547.8 1528.13  4562.4 1523.00  4568.6 1522.82  4591.6 1518.48  4597.8 1518.78
  4612.4 1513.87  4641.6 1511.12  4681.9 1510.72  4712.4 1509.55  4760.4 1509.48
  4760.6 1508.98  4764.4 1509.48  4855.1 1512.41  4912.4 1512.09  4927.0 1512.97
  4962.4 1511.79  5025.5 1511.87  5056.1 1512.98  5086.7 1516.07  5117.3 1517.74
  5127.5 1518.90  5158.1 1526.60  5198.9 1542.66  5209.1 1545.64  5260.1 1549.20
#Mann=4,-1,0
  4505.1    0.12       0  4681.9    0.07       0  4760.4    0.05       0
  4764.4    0.07       0
Bank Sta=4760.4,4764.4
Exp/Cntr=0.3,0.1

Type RM Length L Ch R = 1,6232,466,466,466
BEGIN DESCRIPTION:
Stream0123_DS 14.0
END DESCRIPTION:
XS GIS Cut Line= 3
      2016274.99     13920175.04      2016375.00     13919625.00
      2016225.00     13919375.00
#Sta/Elev= 30
  4445.2 1540.71  4496.1 1538.27  4525.3 1531.18  4530.4 1530.88  4557.0 1523.16
  4567.8 1521.24  4588.8 1520.10  4637.1 1511.13  4715.3 1505.73  4754.0 1504.27
  4812.4 1504.18  4932.0 1506.09  4963.6 1506.30  4970.4 1502.54  4970.7 1502.04
  4974.5 1502.54  4977.6 1502.57  4983.9 1506.10  5007.2 1506.06  5054.8 1508.97
  5113.1 1512.88  5153.1 1517.19  5202.5 1525.62  5223.9 1528.01  5229.7 1526.66
  5245.3 1529.66  5251.1 1529.56  5266.6 1533.73  5272.5 1536.44  5295.8 1538.39
#Mann=7,-1,0
  4445.2    0.07       0  4567.8    0.12       0  4715.3    0.07       0
  4932.0    0.12       0  4970.4    0.05       0  4974.5    0.12       0
  5153.1    0.07       0
Bank Sta=4970.4,4974.5
Exp/Cntr=0.3,0.1

Type RM Length L Ch R = 1,5766,434,434,434
BEGIN DESCRIPTION:
Stream0123_DS 13.0
END DESCRIPTION:
XS GIS Cut Line= 3
      2016425.00     13920075.00      2016825.00     13919675.00
      2016775.00     13919275.00
#Sta/Elev= 30
  4429.8 1518.61  4433.3 1518.61  4472.2 1512.50  4557.1 1507.83  4585.4 1502.90
  4609.7 1501.39  4693.1 1499.61  4740.9 1499.92  4783.4 1497.98  4839.9 1498.58
  4854.1 1498.25  4868.2 1496.25  4910.6 1498.75  4967.2 1497.54  4998.0 1496.81
  5005.6 1495.74  5013.5 1492.26  5013.8 1491.76  5017.7 1492.26  5025.7 1496.35
  5066.0 1497.99  5136.6 1502.48  5194.5 1511.17  5217.2 1513.53  5247.4 1518.01
  5272.6 1522.32  5287.7 1526.19  5318.0 1531.11  5348.2 1537.32  5398.6 1539.86
#Mann=5,-1,0
  4429.8    0.07       0  4609.7    0.12       0  4693.1    0.07       0
  5013.5    0.05       0  5017.7    0.07       0
Bank Sta=5013.5,5017.7
Exp/Cntr=0.3,0.1

Type RM Length L Ch R = 1,5332,443,443,443
BEGIN DESCRIPTION:
Stream0123_DS 12.0
END DESCRIPTION:
XS GIS Cut Line= 3
      2017175.00     13919825.01      2017175.00     13919625.00
      2016824.99     13919274.99
#Sta/Elev= 30
  4794.9 1497.32  4864.9 1493.03  4926.7 1490.28  4974.9 1486.97  4984.9 1485.47
  4992.4 1483.14  4998.4 1483.14  5006.8 1480.48  5007.1 1479.98  5011.0 1479.98
  5011.3 1480.48  5023.2 1487.39  5037.3 1488.66  5079.8 1488.54  5093.9 1486.50
  5108.0 1487.43  5122.2 1488.84  5164.6 1494.96  5192.9 1497.96  5207.0 1498.42
  5291.9 1505.61  5313.1 1508.39  5348.5 1515.58  5362.6 1517.65  5376.7 1520.90
  5383.8 1521.43  5390.9 1524.62  5447.5 1536.68  5461.6 1538.30  5489.9 1539.70
#Mann=4,-1,0
  4794.9    0.12       0  4926.7    0.07       0  5006.8    0.05       0
  5011.3    0.07       0
Bank Sta=5006.8,5011.3
Exp/Cntr=0.3,0.1

Type RM Length L Ch R = 1,4889,421,421,421
BEGIN DESCRIPTION:
Stream0123_DS 11.0
END DESCRIPTION:
XS GIS Cut Line= 3
      2017474.99     13919775.03      2017525.00     13919525.00
      2017425.00     13919324.99
#Sta/Elev= 30
  4745.0 1499.51  4796.0 1497.20  4806.2 1495.81  4826.6 1493.94  4847.0 1489.82
  4867.4 1484.06  4877.6 1483.08  4908.2 1481.44  4969.4 1480.15  4989.8 1479.02
  4997.4 1477.77  5002.8 1477.77  5008.4 1474.96  5014.0 1475.00  5020.0 1474.07
  5020.4 1473.57  5024.3 1473.57  5024.6 1474.07  5036.3 1475.27  5044.7 1478.35
  5067.1 1481.50  5075.5 1483.33  5081.0 1483.36  5120.2 1486.85  5125.8 1486.82
  5134.1 1487.92  5148.1 1488.07  5156.5 1488.92  5170.5 1489.25  5223.6 1492.60
#Mann=3,-1,0
  4745.0    0.07       0  5020.0    0.05       0  5024.6    0.07       0
Bank Sta=5020,5024.6
Exp/Cntr=0.3,0.1

Type RM Length L Ch R = 1,4468,465,465,465
BEGIN DESCRIPTION:
Stream0123_DS 10.0
END DESCRIPTION:
XS GIS Cut Line= 3
      2017875.00     13919624.98      2017875.00     13919425.00
      2017624.99     13919124.99
#Sta/Elev= 30
  4804.7 1487.93  4844.7 1486.11  4864.7 1482.79  4914.7 1477.99  4954.7 1470.81
  4964.7 1470.10  4982.4 1467.18  4982.7 1466.68  4986.7 1466.68  4987.0 1467.18
  4994.7 1467.74  5002.2 1469.66  5007.9 1469.66  5011.8 1471.19  5018.3 1471.48
  5040.5 1474.09  5069.1 1473.84  5096.4 1474.32  5139.4 1477.33  5160.9 1477.74
  5168.0 1478.43  5239.0 1481.09  5283.6 1483.47  5295.6 1484.36  5309.9 1486.57
  5317.1 1489.44  5325.8 1490.84  5338.6 1491.59  5367.2 1494.39  5395.2 1495.64
#Mann=5,-1,0
  4804.7    0.07       0  4982.4    0.05       0  4987.0    0.07       0
  5283.6    0.12       0  5325.8    0.07       0
Bank Sta=4982.4,4987
Exp/Cntr=0.3,0.1

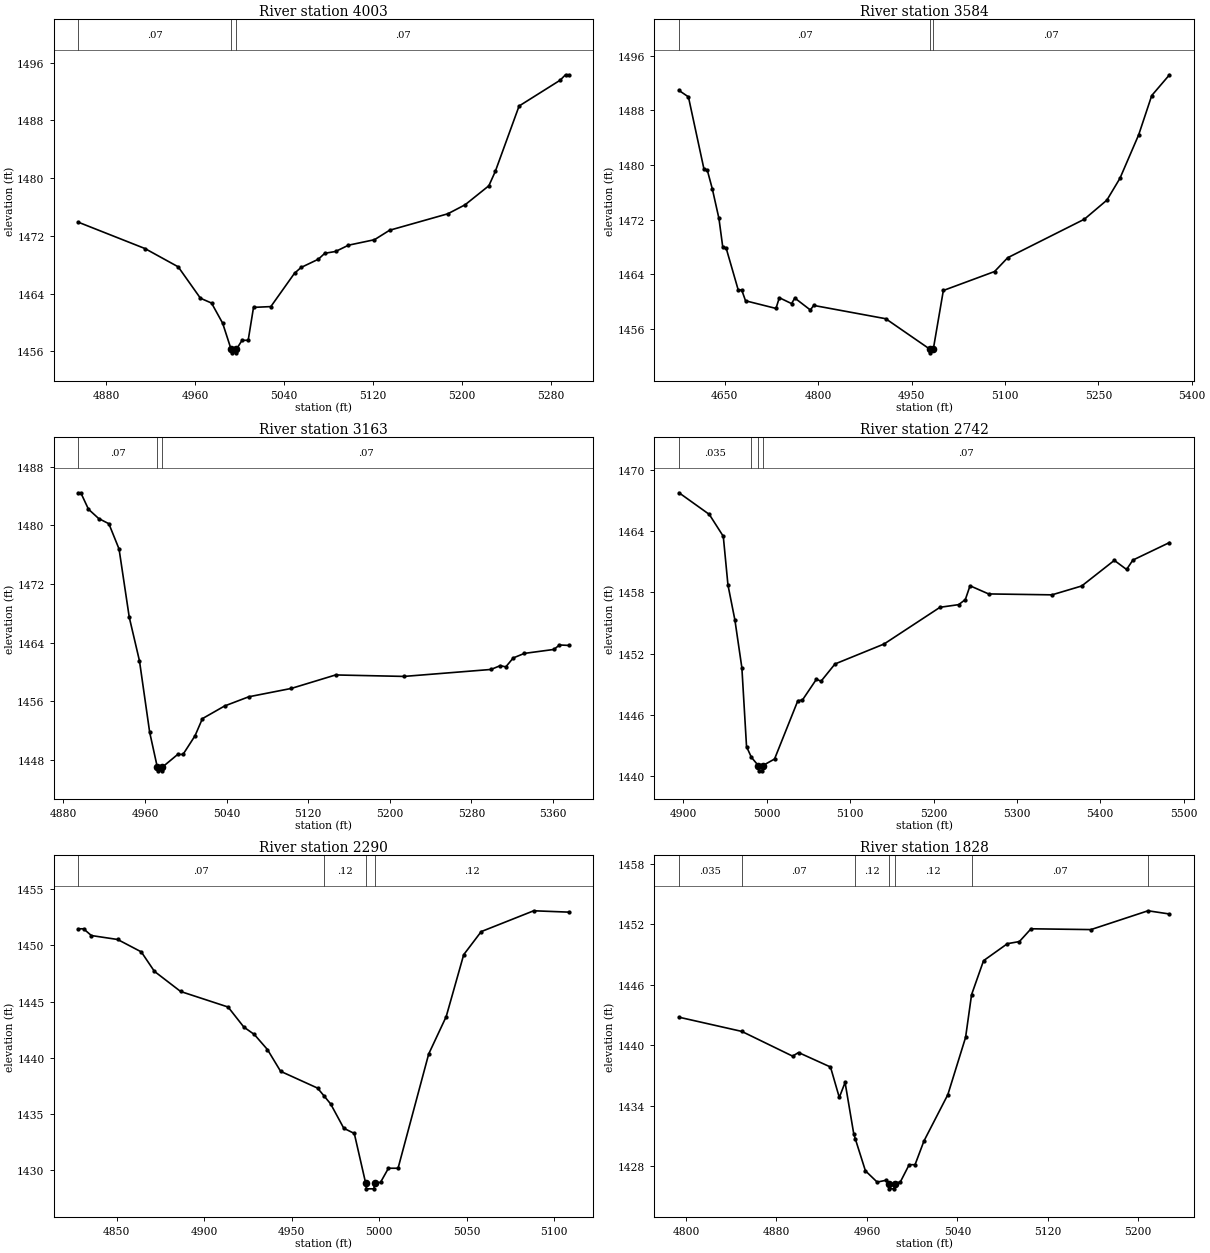
Type RM Length L Ch R = 1,4003,419,419,419
BEGIN DESCRIPTION:
Stream0123_DS 9.0
END DESCRIPTION:
XS GIS Cut Line= 3
      2018225.00     13919325.05      2018225.00     13919175.00
      2018075.00     13918924.99
#Sta/Elev= 30
  4854.7 1473.89  4914.7 1470.24  4944.7 1467.70  4964.7 1463.35  4974.7 1462.68
  4984.7 1459.89  4992.3 1456.28  4992.7 1455.78  4996.8 1455.78  4997.1 1456.28
  5002.2 1457.52  5007.7 1457.52  5012.5 1462.08  5028.1 1462.19  5049.4 1466.81
  5055.3 1467.61  5070.8 1468.75  5076.7 1469.58  5086.4 1469.83  5098.0 1470.70
  5121.4 1471.46  5135.0 1472.77  5187.4 1475.05  5203.0 1476.30  5224.4 1478.94
  5230.2 1480.93  5251.6 1489.99  5288.5 1493.56  5293.4 1494.32  5296.3 1494.32
#Mann=3,-1,0
  4854.7    0.07       0  4992.3    0.05       0  4997.1    0.07       0
Bank Sta=4992.3,4997.1
Exp/Cntr=0.3,0.1

Type RM Length L Ch R = 1,3584,421,421,421
BEGIN DESCRIPTION:
Stream0123_DS 8.0
END DESCRIPTION:
XS GIS Cut Line= 3
      2018725.00     13919374.99      2018575.00     13918975.00
      2018275.04     13918775.03
#Sta/Elev= 30
  4576.6 1490.93  4591.7 1489.99  4616.6 1479.43  4622.0 1479.25  4630.0 1476.53
  4640.7 1472.17  4646.9 1467.93  4652.2 1467.85  4671.8 1461.65  4677.2 1461.71
  4683.4 1460.10  4732.3 1458.98  4737.7 1460.55  4757.3 1459.69  4762.6 1460.50
  4787.5 1458.75  4792.9 1459.42  4908.6 1457.47  4980.0 1452.97  4980.4 1452.47
  4984.9 1452.97  5001.1 1461.61  5083.4 1464.39  5104.4 1466.41  5227.6 1472.06
  5263.7 1474.85  5284.7 1478.05  5314.8 1484.43  5335.8 1490.19  5364.3 1493.23
#Mann=3,-1,0
  4576.6    0.07       0  4980.0    0.05       0  4984.9    0.07       0
Bank Sta=4980,4984.9
Exp/Cntr=0.3,0.1

Type RM Length L Ch R = 1,3163,421,421,421
BEGIN DESCRIPTION:
Stream0123_DS 7.0
END DESCRIPTION:
XS GIS Cut Line= 3
      2018875.00     13919324.99      2018875.00     13919225.00
      2018724.99     13918874.98
#Sta/Elev= 30
  4894.6 1484.46  4897.1 1484.46  4904.6 1482.22  4914.6 1480.95  4924.6 1480.24
  4934.6 1476.79  4944.6 1467.48  4954.6 1461.54  4964.6 1451.80  4972.1 1447.03
  4972.5 1446.53  4976.7 1446.53  4977.0 1447.03  4992.1 1448.77  4997.3 1448.77
  5009.1 1451.32  5016.3 1453.65  5038.1 1455.38  5061.7 1456.63  5103.4 1457.77
  5146.9 1459.61  5214.0 1459.41  5299.2 1460.36  5308.3 1460.88  5313.7 1460.71
  5321.0 1461.93  5331.9 1462.55  5360.9 1463.09  5366.3 1463.70  5375.4 1463.64
#Mann=3,-1,0
  4894.6    0.07       0  4972.1    0.05       0  4977.0    0.07       0
Bank Sta=4972.1,4977
Exp/Cntr=0.3,0.1

Type RM Length L Ch R = 1,2742,452,452,452
BEGIN DESCRIPTION:
Stream0123_DS 6.0
END DESCRIPTION:
XS GIS Cut Line= 3
      2019224.98     13919074.96      2019175.00     13918975.00
      2018748.98     13918761.24
#Sta/Elev= 30
  4894.7 1467.77  4931.0 1465.65  4947.8 1463.50  4953.4 1458.73  4961.7 1455.31
  4970.1 1450.61  4975.7 1442.87  4981.5 1441.83  4990.0 1441.00  4990.4 1440.50
  4994.6 1440.50  4994.9 1441.00  5009.3 1441.66  5037.2 1447.37  5042.8 1447.45
  5059.5 1449.48  5065.1 1449.29  5081.8 1450.98  5140.7 1452.94  5207.8 1456.54
  5230.2 1456.80  5238.2 1457.30  5243.8 1458.65  5266.1 1457.85  5342.1 1457.76
  5377.8 1458.63  5416.9 1461.14  5431.6 1460.25  5439.2 1461.17  5483.1 1462.89
#Mann=4,-1,0
  4894.7   0.035       0  4981.5    0.07       0  4990.0    0.05       0
  4994.9    0.07       0
Bank Sta=4990,4994.9
Exp/Cntr=0.3,0.1

Type RM Length L Ch R = 1,2290,462,462,462
BEGIN DESCRIPTION:
Stream0123_DS 5.0
END DESCRIPTION:
XS GIS Cut Line= 3
      2019424.97     13918724.96      2019325.00     13918575.00
      2019225.03     13918575.00
#Sta/Elev= 30
  4828.1 1451.46  4831.1 1451.46  4835.6 1450.86  4850.6 1450.51  4864.1 1449.41
  4871.6 1447.68  4886.6 1445.89  4913.7 1444.51  4922.7 1442.73  4928.7 1442.07
  4936.2 1440.73  4943.7 1438.80  4964.8 1437.31  4968.7 1436.58  4972.3 1435.90
  4979.8 1433.74  4985.8 1433.28  4992.3 1428.86  4992.7 1428.36  4997.0 1428.36
  4997.4 1428.86  5000.8 1428.94  5005.3 1430.19  5010.8 1430.19  5028.3 1440.34
  5038.3 1443.66  5048.3 1449.16  5058.3 1451.21  5088.3 1453.06  5108.3 1452.94
#Mann=4,-1,0
  4828.1    0.07       0  4968.7    0.12       0  4992.3    0.05       0
  4997.4    0.12       0
Bank Sta=4992.3,4997.4
Exp/Cntr=0.3,0.1

Type RM Length L Ch R = 1,1828,434,434,434
BEGIN DESCRIPTION:
Stream0123_DS 4.0
END DESCRIPTION:
XS GIS Cut Line= 3
      2019675.00     13918575.02      2019725.00     13918375.00
      2019652.72     13918159.05
#Sta/Elev= 30
  4793.8 1442.78  4849.3 1441.37  4894.3 1438.91  4899.5 1439.27  4927.8 1437.83
  4935.6 1434.80  4940.7 1436.30  4948.4 1431.17  4949.8 1430.67  4958.7 1427.51
  4969.1 1426.39  4976.8 1426.57  4979.4 1426.22  4979.8 1425.72  4984.1 1425.72
  4984.5 1426.22  4989.7 1426.43  4997.4 1428.12  5002.6 1428.12  5010.5 1430.48
  5031.6 1435.08  5047.3 1440.77  5052.6 1445.02  5063.2 1448.40  5084.3 1450.09
  5094.9 1450.30  5105.2 1451.57  5158.2 1451.49  5208.7 1453.36  5227.7 1453.04
#Mann=7,-1,0
  4793.8   0.035       0  4849.3    0.07       0  4949.8    0.12       0
  4979.4    0.05       0  4984.5    0.12       0  5052.6    0.07       0
  5208.7   0.035       0
Bank Sta=4979.4,4984.5
Exp/Cntr=0.3,0.1

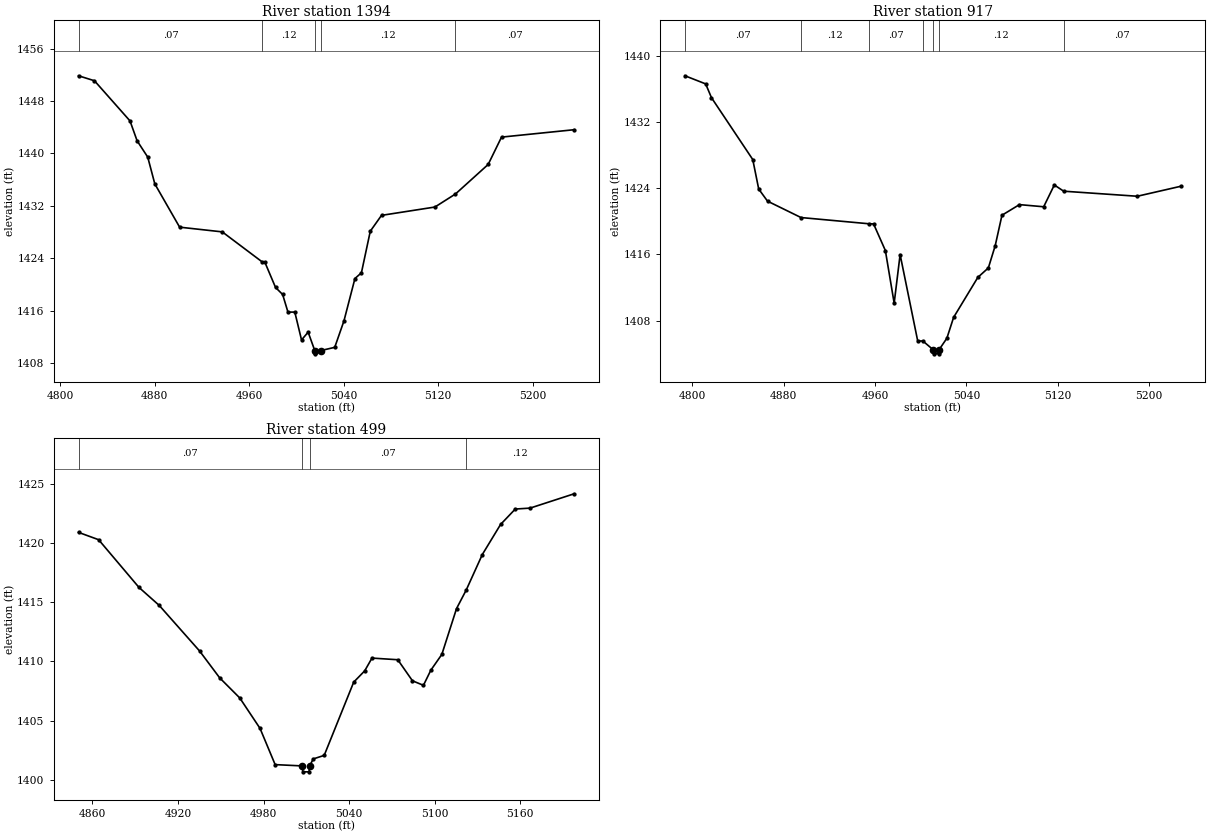
Type RM Length L Ch R = 1,1394,477,477,477
BEGIN DESCRIPTION:
Stream0123_DS 3.0
END DESCRIPTION:
XS GIS Cut Line= 3
      2020225.01     13918425.01      2020125.00     13918275.00
      2020020.64     13918059.64
#Sta/Elev= 30
  4815.6 1451.84  4829.1 1451.08  4859.2 1444.95  4865.2 1441.92  4874.2 1439.43
  4880.2 1435.34  4901.2 1428.74  4937.3 1428.02  4971.3 1423.41  4973.4 1423.37
  4982.4 1419.54  4988.4 1418.47  4992.9 1415.78  4998.7 1415.78  5004.4 1411.53
  5010.0 1412.72  5015.6 1409.91  5015.9 1409.41  5020.7 1409.91  5032.5 1410.40
  5040.3 1414.43  5049.6 1420.90  5055.1 1421.78  5062.6 1428.12  5072.1 1430.54
  5117.3 1431.81  5134.7 1433.80  5162.4 1438.31  5173.7 1442.48  5235.2 1443.61
#Mann=5,-1,0
  4815.6    0.07       0  4971.3    0.12       0  5015.6    0.05       0
  5020.7    0.12       0  5134.7    0.07       0
Bank Sta=5015.6,5020.7
Exp/Cntr=0.3,0.1

Type RM Length L Ch R = 1,917,418,418,418
BEGIN DESCRIPTION:
Stream0123_DS 2.0
END DESCRIPTION:
XS GIS Cut Line= 3
      2020474.99     13918275.03      2020525.00     13918075.00
      2020333.00     13917953.14
#Sta/Elev= 30
  4793.8 1437.57  4811.9 1436.59  4817.0 1434.92  4853.1 1427.46  4858.3 1423.90
  4866.0 1422.44  4895.3 1420.46  4954.6 1419.71  4958.8 1419.69  4969.1 1416.48
  4976.8 1410.13  4982.0 1415.99  4997.4 1405.56  5001.9 1405.56  5010.9 1404.51
  5011.3 1404.01  5015.7 1404.01  5016.1 1404.51  5022.9 1405.89  5028.8 1408.41
  5050.0 1413.24  5059.2 1414.38  5065.2 1417.07  5071.1 1420.74  5086.4 1422.02
  5107.6 1421.76  5116.9 1424.39  5125.1 1423.64  5189.5 1423.03  5227.4 1424.23
#Mann=7,-1,0
  4793.8    0.07       0  4895.3    0.12       0  4954.6    0.07       0
  5001.9    0.12       0  5010.9    0.05       0  5016.1    0.12       0
  5125.1    0.07       0
Bank Sta=5010.9,5016.1
Exp/Cntr=0.3,0.1

Type RM Length L Ch R = 1,499,0,0,0
BEGIN DESCRIPTION:
Stream0123_DS 1.0
END DESCRIPTION:
XS GIS Cut Line= 3
      2020975.00     13917975.00      2020875.00     13917875.00
      2020674.98     13917824.99
#Sta/Elev= 30
  4850.2 1420.90  4864.3 1420.28  4892.6 1416.25  4906.8 1414.73  4935.1 1410.88
  4949.2 1408.61  4963.3 1406.91  4977.5 1404.34  4988.1 1401.28  5007.1 1401.17
  5007.5 1400.67  5011.9 1400.67  5012.3 1401.17  5014.8 1401.76  5022.5 1402.06
  5043.2 1408.25  5050.9 1409.20  5056.0 1410.28  5074.1 1410.14  5084.4 1408.36
  5092.1 1407.98  5097.3 1409.26  5105.0 1410.59  5115.3 1414.46  5122.1 1416.03
  5133.4 1419.03  5146.2 1421.57  5156.5 1422.87  5166.9 1422.95  5197.8 1424.16
#Mann=4,-1,0
  4850.2    0.07       0  5007.1    0.05       0  5012.3    0.07       0
  5122.1    0.12       0
Bank Sta=5007.1,5012.3
Exp/Cntr=0.3,0.1

Chan Stop Cuts=-1