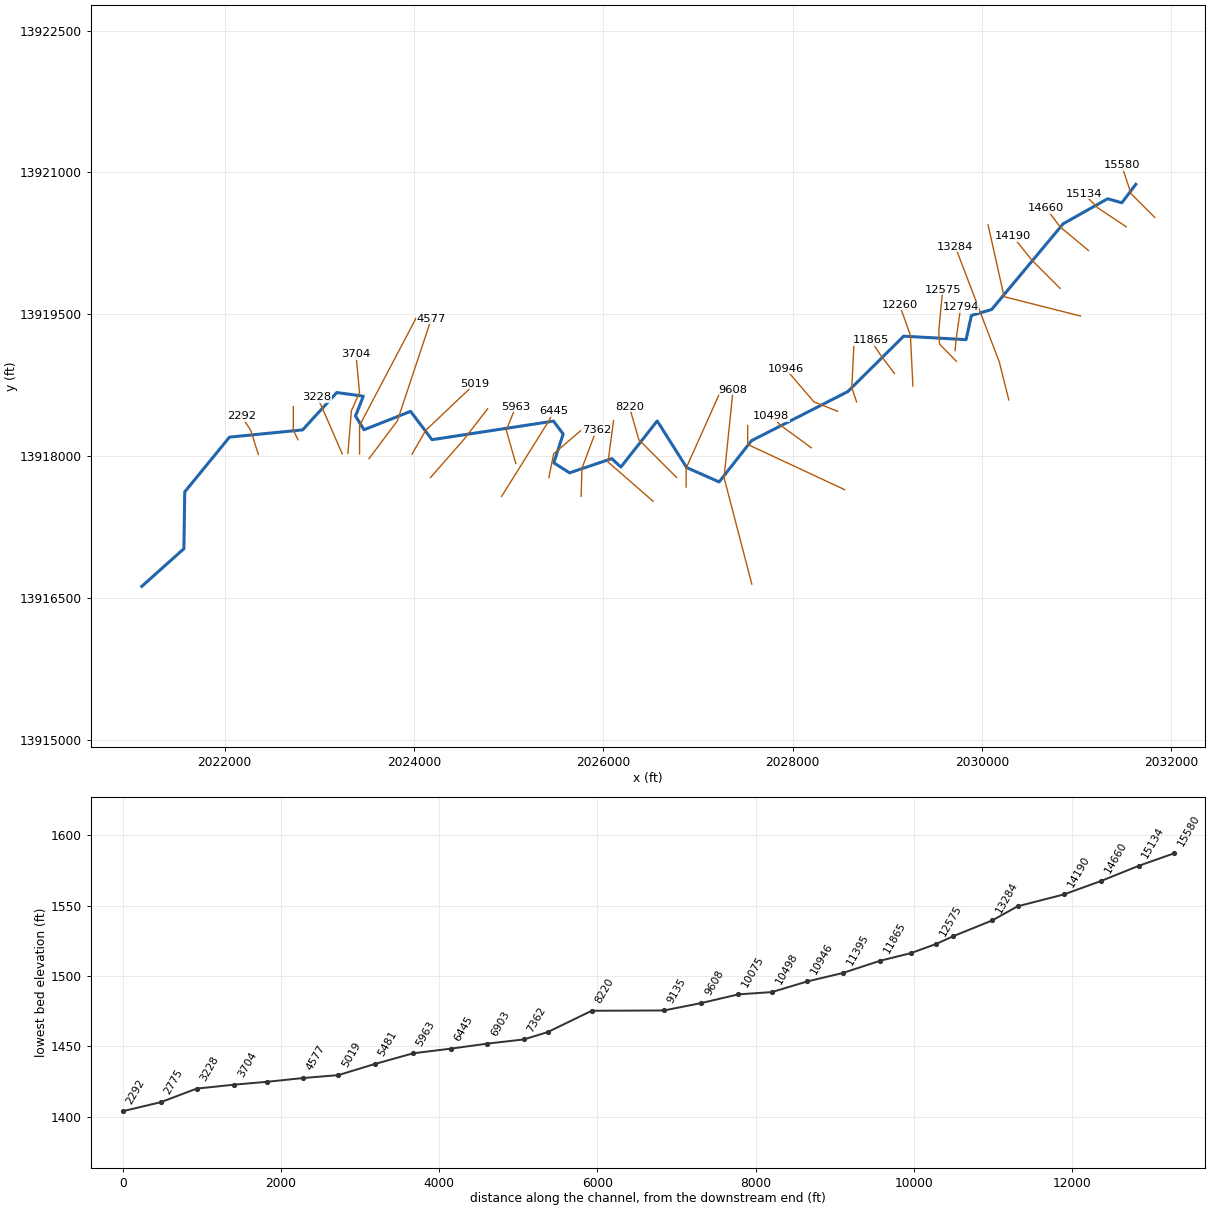
--- Stream0124_DS.prj (project) ---

Proj Title=Stream0124_DS Base Level Engineering
Current Plan=p01
Default Exp/Contr=0.3,0.1
English Units
Geom File=g01
Flow File=f01
Plan File=p01
Y Axis Title=Elevation
X Axis Title(PF)=Main Channel Distance
X Axis Title(XS)=Station
BEGIN DESCRIPTION:
Stream0124_DS
END DESCRIPTION:
DSS Export Rating Curves= 0
DSS Export Rating Curve Sorted= 0
DSS Export Volume Flow Curves= 0
DXF OffsetX= 0
DXF OffsetY= 0
DXF ScaleX= 1
DXF ScaleY= 10

--- Stream0124_DS.p01 (plan) ---

Plan Title=Multiple Run
Short Identifier=Multiple
Geom File=g01
Flow File=f01
Subcritical Flow
K Sum by GR= 0
Std Step Tol= 0.01
Critical Tol= 0.01
Num of Std Step Trials= 20
Max Error Tol= 0.3
Flow Tol Ratio= 0.001
Split Flow NTrial= 30
Split Flow Tol= 0.02
Split Flow Ratio= 0.02
Log Output Level= 0
Friction Slope Method= 1
Unsteady Friction Slope Method= 2
Unsteady Bridges Friction Slope Method= 1
Parabolic Critical Depth
Global Vel Dist=  1 , 1 , 1
Global Log Level= 0
CheckData=True
Encroach Param= -1, 0, 0, 0
BEGIN DESCRIPTION:
Multiple Run
END DESCRIPTION:

--- Stream0124_DS.f01 (steady flow) ---

Flow Title=Multiple
Program Version=4.10
Number of Profiles= 7
Profile Names=10-year,25-year,50-year,1pct_min,100-year,1pct_plu,500-year
River Rch & RM=Stream0124_DS,Reach-1         ,15580
    1321    2297    3252    2235    4459    8896    8307
River Rch & RM=Stream0124_DS,Reach-1         ,13284
    1308    2279    3228    2219    4427    8833    8258
River Rch & RM=Stream0124_DS,Reach-1         ,10946
    2467    4430    6404    4481    8940   17838   17292
River Rch & RM=Stream0124_DS,Reach-1         ,4577
    2601    4669    6747    4715    9409   18773   18164
Boundary for River Rch & Prof#=Stream0124_DS,Reach-1         , 1
Up Type= 0
Dn Type= 3
Dn Slope=0.005
Boundary for River Rch & Prof#=Stream0124_DS,Reach-1         , 2
Up Type= 0
Dn Type= 3
Dn Slope=0.005
Boundary for River Rch & Prof#=Stream0124_DS,Reach-1         , 3
Up Type= 0
Dn Type= 3
Dn Slope=0.005
Boundary for River Rch & Prof#=Stream0124_DS,Reach-1         , 4
Up Type= 0
Dn Type= 3
Dn Slope=0.005
Boundary for River Rch & Prof#=Stream0124_DS,Reach-1         , 5
Up Type= 0
Dn Type= 3
Dn Slope=0.005
Boundary for River Rch & Prof#=Stream0124_DS,Reach-1         , 6
Up Type= 0
Dn Type= 3
Dn Slope=0.005
Boundary for River Rch & Prof#=Stream0124_DS,Reach-1         , 7
Up Type= 0
Dn Type= 3
Dn Slope=0.005
DSS Import GetInterval= 0
DSS Import GetPeak= 0
DSS Import FillOption= 0

--- Stream0124_DS.g01 (geometry) ---

Geom Title=Existing Conditions
Program Version=4.10

River Reach=Stream0124_DS   ,Reach-1
Reach XY= 30
        2031625.       13920875.       2031477.3     13920680.09
      2031326.63     13920721.87      2030858.33     13920458.35
      2030101.87     13919551.17       2029888.2     13919488.74
      2029831.52     13919232.67      2029172.55     13919269.53
      2028581.19     13918682.81      2027565.21     13918164.48
      2027223.45     13917728.66      2026880.47     13917880.26
      2026569.12     13918373.52       2026185.2     13917885.78
      2026089.48     13917974.97      2025643.33     13917825.04
      2025476.89     13917930.71      2025575.83     13918235.07
      2025473.55     13918371.47      2024190.03     13918175.33
      2023964.37     13918474.45       2023472.3     13918280.36
       2023382.3     13918425.08      2023464.72     13918635.16
      2023184.65     13918673.64      2022823.45     13918278.75
      2022051.16     13918202.15      2021578.53     13917623.54
      2021569.48     13917022.57        2021125.       13916625.

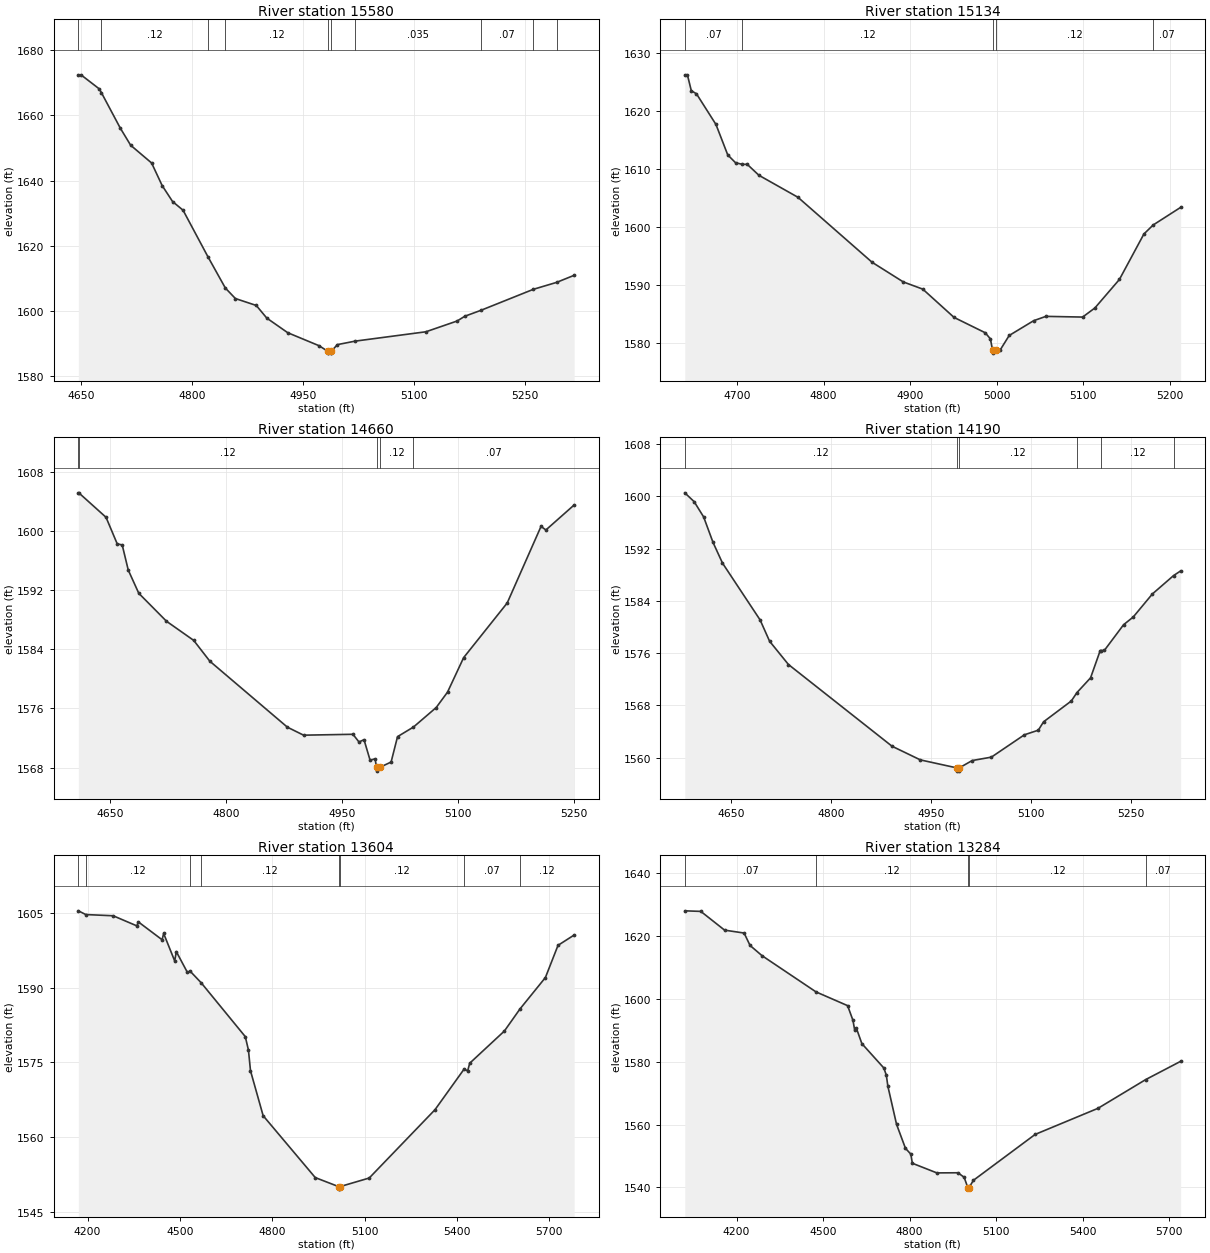
Type RM Length L Ch R = 1 ,15580   ,446,446,446
BEGIN DESCRIPTION:
Stream0124_DS 32.0
END DESCRIPTION:
XS GIS Cut Line= 3
      2031825.02     13920524.98        2031575.       13920775.
        2031475.     13921074.99
#Sta/Elev= 30
  4646.6 1672.38  4650.2 1672.38  4674.9 1668.07  4677.7 1666.95  4703.2 1656.09
  4717.3 1650.81  4745.6 1645.37  4759.8 1638.47  4773.9 1633.57  4788.1  1630.9
  4821.6 1616.68  4845.2 1607.07  4858.8 1603.85    4887 1601.73  4901.2 1597.86
  4929.5 1593.38  4971.9 1589.39    4984 1587.63  4984.3 1587.13  4987.8 1587.13
    4988 1587.63  4996.6 1589.74  5020.7 1590.81  5116.1 1593.67  5158.3 1596.97
  5168.8 1598.44  5190.1 1600.21  5261.3 1606.68  5292.7  1608.8  5316.4 1610.97
#Mann= 10 ,-1 , 0
  4646.6     .07       0  4677.7     .12       0  4821.6     .07       0
  4845.2     .12       0    4984     .05       0    4988     .12       0
  5020.7    .035       0  5190.1     .07       0  5261.3    .035       0
  5292.7     .07       0
Bank Sta=4984,4988
XS Rating Curve= 0 ,0
Exp/Cntr=0.3,0.1

Type RM Length L Ch R = 1 ,15134   ,474,474,474
BEGIN DESCRIPTION:
Stream0124_DS 31.0
END DESCRIPTION:
XS GIS Cut Line= 3
      2031524.99     13920425.01        2031225.       13920625.
      2031074.98     13920775.02
#Sta/Elev= 30
  4639.7 1626.21  4642.7 1626.21  4647.2 1623.48  4653.2 1622.94  4675.7 1617.66
  4689.3 1612.42  4698.3 1611.07  4706.3 1610.79  4711.8  1610.8  4725.3 1608.91
  4770.4 1605.12    4856 1593.93  4892.1 1590.54  4914.6  1589.3  4950.7 1584.43
  4986.7 1581.79  4992.7 1580.73  4995.2 1578.78  4995.5 1578.28  4999.2 1578.78
  5003.8 1578.78  5014.4 1581.32  5042.7 1583.87  5056.8 1584.61  5099.2 1584.49
  5113.4 1586.06  5141.7 1590.97    5170  1598.8  5180.7 1600.35  5212.4 1603.38
#Mann= 5 ,-1 , 0
  4639.7     .07       0  4706.3     .12       0  4995.2     .05       0
  4999.2     .12       0  5180.7     .07       0
Bank Sta=4995.2,4999.2
XS Rating Curve= 0 ,0
Exp/Cntr=0.3,0.1

Type RM Length L Ch R = 1 ,14660   ,470,470,470
BEGIN DESCRIPTION:
Stream0124_DS 30.0
END DESCRIPTION:
XS GIS Cut Line= 3
      2031125.03     13920174.97        2030825.       13920425.
      2030674.97     13920625.03
#Sta/Elev= 30
  4609.2 1605.15  4609.8 1605.15    4645 1601.84  4659.4 1598.26  4665.9  1598.1
  4673.7 1594.71  4687.3 1591.57  4723.1 1587.79  4758.3  1585.2  4779.1 1582.39
  4879.3 1573.47  4900.2 1572.39    4964 1572.51  4971.8 1571.47  4978.3 1571.78
  4986.1 1569.02  4992.6 1569.19  4994.5 1568.03  4994.8 1567.53  4998.5 1568.03
  5013.3 1568.76  5021.6 1572.19  5042.2 1573.49  5071.6 1576.13  5086.2 1578.21
    5107 1582.87  5163.3 1590.26    5207 1600.61  5213.3 1600.13  5249.8 1603.51
#Mann= 5 ,-1 , 0
  4609.2     .07       0  4609.8     .12       0  4994.5     .05       0
  4998.5     .12       0  5042.2     .07       0
Bank Sta=4994.5,4998.5
XS Rating Curve= 0 ,0
Exp/Cntr=0.3,0.1

Type RM Length L Ch R = 1 ,14190   ,586,586,586
BEGIN DESCRIPTION:
Stream0124_DS 29.0
END DESCRIPTION:
XS GIS Cut Line= 3
        2030825.       13919775.        2030525.       13920075.
      2030325.02     13920324.98
#Sta/Elev= 30
  4580.8 1600.52  4594.9 1599.16  4609.1 1596.83  4623.2 1592.93  4637.4 1589.77
  4693.9 1581.07  4708.1 1577.82  4736.4 1574.26  4891.9 1561.76  4934.4 1559.67
  4988.9 1558.45  4989.2 1557.95  4992.7 1557.95  4992.9 1558.45  5012.3 1559.57
  5041.1 1560.09  5090.7 1563.51  5111.5 1564.21  5119.5  1565.5  5161.1 1568.68
  5169.6 1569.97    5190 1572.22  5204.4 1576.37  5206.1 1576.39  5210.8 1576.43
  5239.6 1580.35    5254 1581.52  5282.8 1585.05  5314.7 1587.87  5325.2 1588.57
#Mann= 6 ,-1 , 0
  4580.8     .12       0  4988.9     .05       0  4992.9     .12       0
  5169.6     .07       0  5206.1     .12       0  5314.7     .07       0
Bank Sta=4988.9,4992.9
XS Rating Curve= 0 ,0
Exp/Cntr=0.3,0.1

Type RM Length L Ch R = 1 ,13604   ,320,320,320
BEGIN DESCRIPTION:
Stream0124_DS 28.0
END DESCRIPTION:
XS GIS Cut Line= 3
      2031040.87     13919482.62       2030233.6      13919686.6
      2030064.34     13920446.13
#Sta/Elev= 30
  4169.9 1605.41  4194.2 1604.66    4283 1604.42  4359.9 1602.39    4365 1603.18
    4442  1599.6  4447.1 1600.86    4483 1595.34  4488.2 1597.22    4524 1593.07
  4533.3 1593.28    4569 1590.96  4712.3 1580.14  4722.6 1577.42  4729.2 1573.29
  4770.3 1564.26  4939.6 1551.83  5015.7 1550.01  5015.9 1549.51  5019.7 1550.01
  5114.9 1551.74  5328.7 1565.47  5423.5 1573.65  5434.6 1573.24  5441.4  1574.8
  5554.1 1581.27  5604.7  1585.7  5687.3 1592.01  5728.3 1598.48  5780.7 1600.55
#Mann= 8 ,-1 , 0
  4169.9     .07       0  4194.2     .12       0  4533.3     .07       0
    4569     .12       0  5015.7     .05       0  5019.7     .12       0
  5423.5     .07       0  5604.7     .12       0
Bank Sta=5015.7,5019.7
XS Rating Curve= 0 ,0
Exp/Cntr=0.3,0.1

Type RM Length L Ch R = 1 ,13284   ,490,490,490
BEGIN DESCRIPTION:
Stream0124_DS 27.0
END DESCRIPTION:
XS GIS Cut Line= 3
      2030283.33     13918595.51      2030183.33     13918995.49
      2029717.12     13920216.09
#Sta/Elev= 30
  4020.6 1627.94  4076.2 1627.76  4158.6  1621.8  4226.2 1620.88  4246.8 1616.94
  4288.1  1613.7  4475.5 1602.17    4585  1597.8  4603.6 1593.13  4609.7 1589.94
    4615 1590.75  4634.4 1585.74  4710.7 1577.97  4719.3 1575.68  4724.6 1572.19
  4754.7 1560.07  4785.6 1552.45  4804.1 1550.61  4809.5  1547.7  4894.3 1544.64
  4967.6 1544.68    4989 1543.24  5001.7 1539.98    5002 1539.48  5006.1 1539.98
  5021.1 1542.28  5235.2 1556.87  5452.9 1565.16  5618.4  1574.3  5739.5  1580.1
#Mann= 5 ,-1 , 0
  4020.6     .07       0  4475.5     .12       0  5001.7     .05       0
  5006.1     .12       0  5618.4     .07       0
Bank Sta=5001.7,5006.1
XS Rating Curve= 0 ,0
Exp/Cntr=0.3,0.1

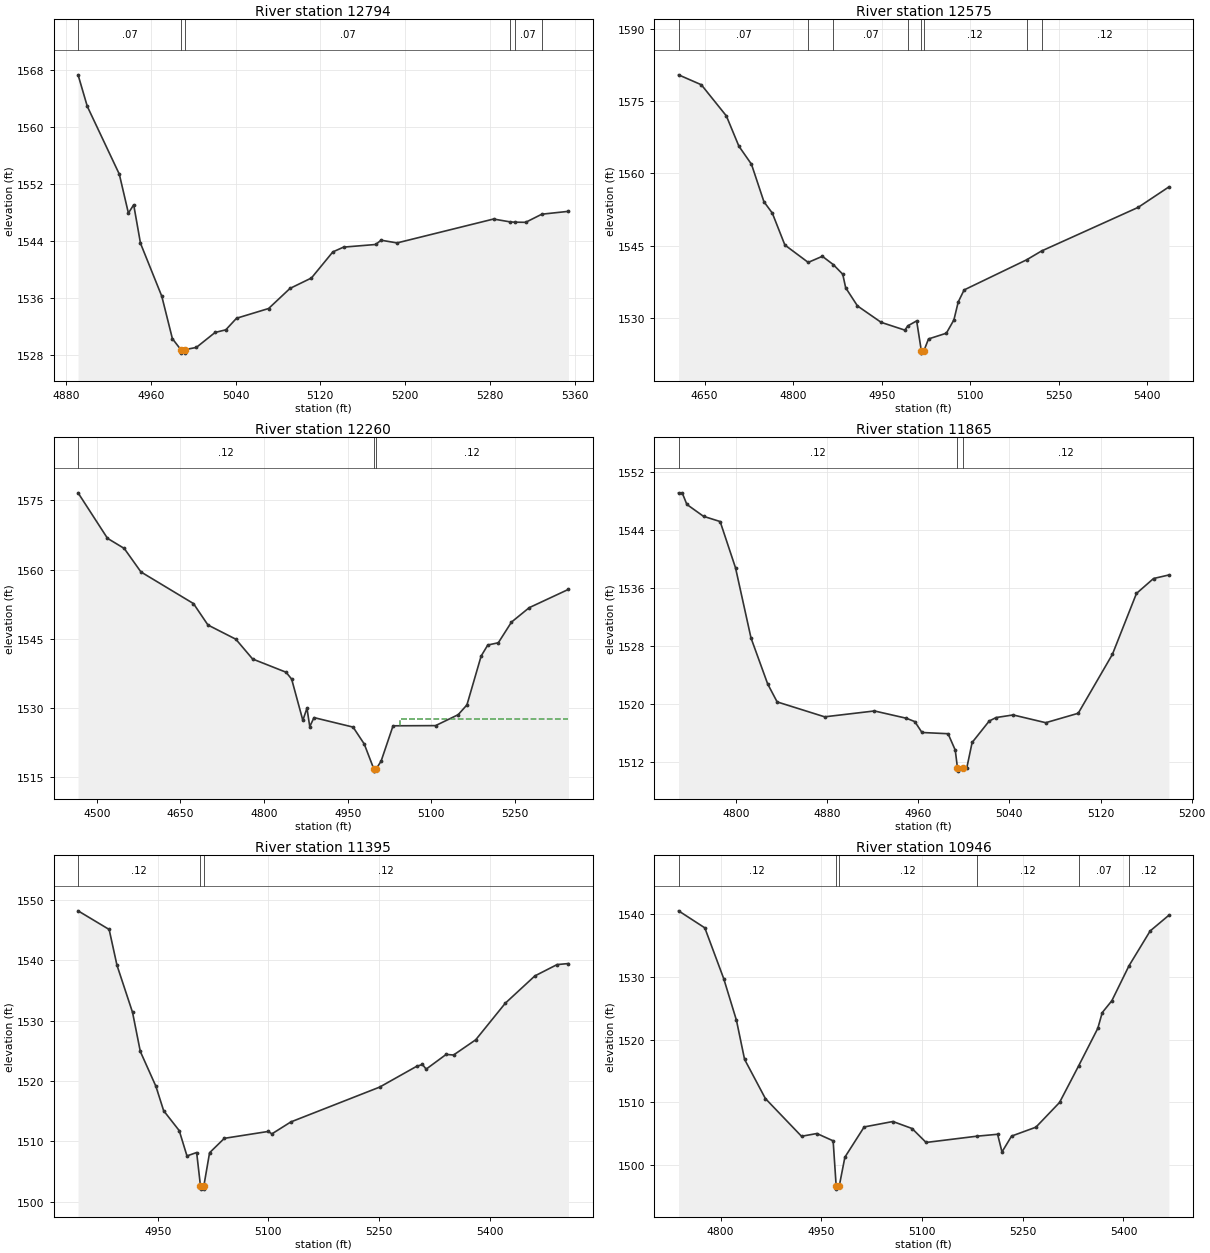
Type RM Length L Ch R = 1 ,12794   ,219,219,219
BEGIN DESCRIPTION:
Stream0124_DS 26.0
END DESCRIPTION:
XS GIS Cut Line= 3
      2029715.58     13919116.29        2029725.       13919225.
        2029775.     13919575.03
#Sta/Elev= 30
  4891.4 1567.36  4900.1 1562.94  4930.3 1553.43  4938.9 1547.96  4943.9 1549.13
  4950.3 1543.73  4970.4  1536.3  4980.4 1530.35  4988.3 1528.82  4988.6 1528.32
  4992.4 1528.32  4992.7 1528.82    5003 1529.12  5020.7 1531.22  5030.8 1531.59
  5040.9 1533.21  5071.2 1534.58  5091.4  1537.4  5111.6 1538.86  5131.8 1542.52
  5141.9 1543.19  5172.2 1543.56  5177.3 1544.16  5192.4 1543.78  5283.4 1547.13
  5299.1 1546.73  5303.2 1546.69  5313.7 1546.67    5329 1547.81  5354.1 1548.21
#Mann= 6 ,-1 , 0
  4891.4     .07       0  4988.3     .05       0  4992.7     .07       0
  5299.1     .12       0  5303.2     .07       0    5329     .12       0
Bank Sta=4988.3,4992.7
XS Rating Curve= 0 ,0
Exp/Cntr=0.3,0.1

Type RM Length L Ch R = 1 ,12575   ,315,315,315
BEGIN DESCRIPTION:
Stream0124_DS 25.5
END DESCRIPTION:
XS GIS Cut Line= 4
      2029729.06      13919004.5      2029551.41     13919185.71
      2029543.27     13919325.71      2029585.16      13919760.3
#Sta/Elev= 30
    4606 1580.43  4644.6 1578.37    4687 1571.91  4708.2 1565.64  4729.5  1561.9
  4750.6 1554.13  4764.8 1551.77  4786.1 1545.15  4825.6 1541.55  4849.6 1542.81
  4868.2 1541.08  4884.1  1539.1  4889.1 1536.28  4909.1 1532.52  4949.2 1529.12
  4989.3 1527.51  4994.4  1528.4  5009.3 1529.42  5017.2 1523.24  5017.5 1522.74
  5021.6 1523.24  5029.4 1525.68  5059.6 1526.87  5072.4 1529.63  5079.7 1533.34
  5089.7 1535.84  5195.5 1542.08  5220.8 1543.91  5384.4 1552.95  5436.6  1557.2
#Mann= 8 ,-1 , 0
    4606     .07       0  4825.6     .12       0  4868.2     .07       0
  4994.4     .12       0  5017.2     .05       0  5021.6     .12       0
  5195.5     .07       0  5220.8     .12       0
Bank Sta=5017.2,5021.6
XS Rating Curve= 0 ,0
Exp/Cntr=0.3,0.1

Type RM Length L Ch R = 1 ,12260   ,395,395,395
BEGIN DESCRIPTION:
Stream0124_DS 25.0
END DESCRIPTION:
XS GIS Cut Line= 3
      2029269.95      13918742.3      2029244.02     13919278.62
      2029128.62     13919601.26
#Sta/Elev= 30
  4466.4 1576.64  4519.2 1566.77  4549.2 1564.58  4579.2 1559.48  4673.4 1552.62
  4699.4 1547.97  4749.4 1544.89  4779.5  1540.6  4839.5 1537.73  4849.5 1536.24
  4869.6 1527.29    4877 1529.94    4882 1525.93  4889.6 1527.89  4959.7 1525.83
  4979.7 1522.17  4996.8 1516.78  4997.1 1516.28  5001.2 1516.78    5010 1518.46
  5031.4 1526.11  5107.7 1526.15  5148.2 1528.52  5163.9 1530.64  5189.4 1541.24
  5201.3 1543.63  5220.2 1544.12  5243.8  1548.6  5275.6 1551.73    5346  1555.7
#Mann= 3 ,-1 , 0
  4466.4     .12       0  4996.8     .05       0  5001.2     .12       0
#XS Ineff= 2 , 0
       0                    5044       0  1527.5
Permanent Ineff=
       F       F
Bank Sta=4996.8,5001.2
XS Rating Curve= 0 ,0
Exp/Cntr=0.3,0.1

Type RM Length L Ch R = 1 ,11865   ,470,470,470
BEGIN DESCRIPTION:
Stream0124_DS 24.0
END DESCRIPTION:
XS GIS Cut Line= 3
      2029075.03     13918874.96        2028925.       13919075.
      2028825.01     13919224.98
#Sta/Elev= 30
  4749.7 1549.15  4752.9 1549.15    4757 1547.55  4771.6 1545.91  4786.2 1545.19
  4799.7  1538.8  4813.3 1529.12  4827.9 1522.79  4836.2 1520.31  4877.9 1518.25
  4921.6 1519.06  4949.7 1518.05    4957 1517.59  4963.3 1516.09  4986.2 1515.92
  4992.5 1513.66  4994.4 1511.26  4994.7 1510.76  4998.9 1511.26  5002.7 1511.26
  5007.3 1514.71  5022.3 1517.67  5028.3 1518.15  5043.3 1518.51  5071.9 1517.44
  5100.4 1518.74  5130.4 1526.87  5151.5 1535.27  5166.5 1537.33    5180 1537.82
#Mann= 3 ,-1 , 0
  4749.7     .12       0  4994.4     .05       0  4998.9     .12       0
Bank Sta=4994.4,4998.9
XS Rating Curve= 0 ,0
Exp/Cntr=0.3,0.1

Type RM Length L Ch R = 1 ,11395   ,449,449,449
BEGIN DESCRIPTION:
Stream0124_DS 23.0
END DESCRIPTION:
XS GIS Cut Line= 3
      2028674.99     13918575.03        2028625.       13918725.
      2028649.38     13919230.43
#Sta/Elev= 30
  4842.2 1548.21  4884.3 1545.12  4894.9 1539.19    4916 1531.37  4926.5  1524.9
  4947.6 1519.13  4958.1 1515.08  4979.2 1511.78  4989.7 1507.58  5002.8 1508.15
    5008 1502.58  5008.3 1502.08  5012.2 1502.08  5012.5 1502.58  5020.3 1508.11
  5040.3  1510.5  5099.7 1511.64  5104.7 1511.24  5130.4 1513.22  5250.6 1518.99
  5300.6 1522.43  5308.6 1522.74  5313.6 1521.97  5340.7 1524.41  5350.7 1524.31
  5380.7 1526.83  5420.8  1532.9  5460.8 1537.42  5490.9  1539.3  5506.3 1539.47
#Mann= 3 ,-1 , 0
  4842.2     .12       0    5008     .05       0  5012.5     .12       0
Bank Sta=5008,5012.5
XS Rating Curve= 0 ,0
Exp/Cntr=0.3,0.1

Type RM Length L Ch R = 1 ,10946   ,448,448,448
BEGIN DESCRIPTION:
Stream0124_DS 22.0
END DESCRIPTION:
XS GIS Cut Line= 3
      2028475.01       13918475.        2028225.       13918575.
      2027925.03     13918924.97
#Sta/Elev= 30
  4737.5 1540.58  4776.6 1537.86  4804.8 1529.73  4823.7 1523.09  4835.8 1516.84
  4866.8 1510.57  4920.6 1504.54  4943.5 1504.98  4967.7 1503.81  4972.2 1496.59
  4972.5 1496.09  4976.8 1496.59  4985.2  1501.2  5013.9 1506.03  5056.7  1506.9
  5085.2 1505.78  5106.1 1503.55  5181.6 1504.55  5212.6 1504.86  5219.1 1502.03
  5233.4 1504.57  5269.6 1505.99  5304.8 1509.94  5333.4 1515.83  5361.8  1521.8
  5368.4 1524.31  5382.7 1526.21  5408.3 1531.81  5439.8 1537.37  5467.7 1539.88
#Mann= 6 ,-1 , 0
  4737.5     .12       0  4972.2     .05       0  4976.8     .12       0
  5181.6     .12       0  5333.4     .07       0  5408.3     .12       0
Bank Sta=4972.2,4976.8
XS Rating Curve= 0 ,0
Exp/Cntr=0.3,0.1

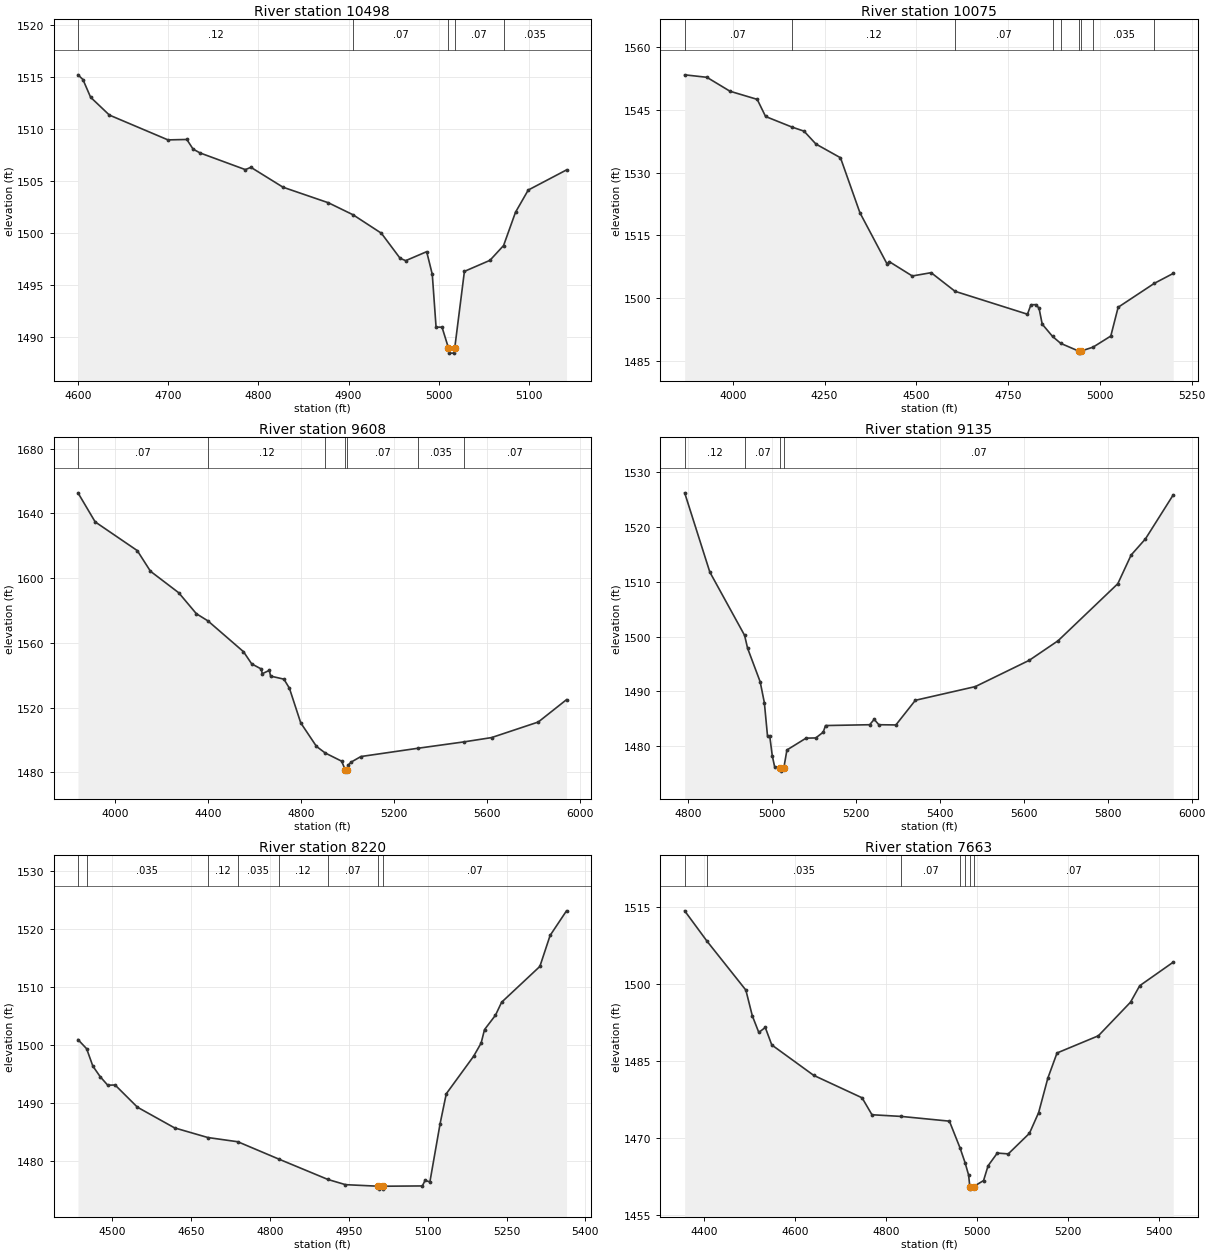
Type RM Length L Ch R = 1 ,10498   ,423,423,423
BEGIN DESCRIPTION:
Stream0124_DS 21.0
END DESCRIPTION:
XS GIS Cut Line= 3
        2028198.     13918089.39        2027875.       13918325.
      2027775.02     13918424.98
#Sta/Elev= 30
  4600.2 1515.19  4605.7 1514.74  4614.2 1513.04    4635 1511.33  4699.9 1508.95
  4720.8 1508.99  4727.7 1508.07  4735.4  1507.7  4785.6  1506.1  4791.8 1506.32
  4827.4 1504.41  4877.6 1502.92  4904.9 1501.77  4936.3    1500  4957.1 1497.59
  4963.3 1497.37  4986.5 1498.23  4992.7 1496.06  4996.9 1490.99  5003.5 1490.99
  5010.6    1489  5011.1  1488.5  5017.1  1488.5  5017.6    1489  5028.3 1496.34
  5056.6  1497.4  5071.7 1498.82  5084.9 1502.01    5099 1504.14  5141.4 1506.07
#Mann= 5 ,-1 , 0
  4600.2     .12       0  4904.9     .07       0  5010.6     .05       0
  5017.6     .07       0  5071.7    .035       0
Bank Sta=5010.6,5017.6
XS Rating Curve= 0 ,0
Exp/Cntr=0.3,0.1

Type RM Length L Ch R = 1 ,10075   ,467,467,467
BEGIN DESCRIPTION:
Stream0124_DS 20.0
END DESCRIPTION:
XS GIS Cut Line= 3
      2028549.58     13917646.67        2027525.       13918125.
        2027525.     13918324.96
#Sta/Elev= 30
  3868.9 1553.34  3929.4 1552.75  3992.4 1549.42  4066.5 1547.48  4089.3 1543.39
  4161.1 1540.87    4194 1539.89  4226.5 1536.81  4293.3 1533.54  4346.3  1520.4
  4420.4 1508.14  4425.9 1508.75  4488.9 1505.31  4540.2  1506.1  4605.4 1501.65
  4802.6 1496.18    4812 1498.44  4825.5 1498.47  4834.1 1497.63  4842.8 1493.81
  4870.9 1490.88  4893.2 1489.22  4941.8 1487.39  4942.3 1486.89  4948.8 1487.39
  4981.3 1488.32  5029.6 1490.97  5049.6 1497.84  5148.3 1503.56  5199.6 1505.92
#Mann= 9 ,-1 , 0
  3868.9     .07       0  4161.1     .12       0  4605.4     .07       0
  4870.9    .035       0  4893.2     .07       0  4941.8    .035       0
  4948.8     .07       0  4981.3    .035       0  5148.3     .07       0
Bank Sta=4941.8,4948.8
XS Rating Curve= 0 ,0
Exp/Cntr=0.3,0.1

Type RM Length L Ch R = 1 ,9608    ,473,473,473
BEGIN DESCRIPTION:
Stream0124_DS 19.0
END DESCRIPTION:
XS GIS Cut Line= 3
      2027568.66     13916648.44        2027275.       13917775.
      2027371.19     13918705.74
#Sta/Elev= 30
  3840.8 1652.73  3914.8 1634.76  4095.6 1617.04  4152.5 1604.25    4274 1590.96
  4349.8    1578  4399.2 1573.61  4552.3 1554.54  4587.6 1547.01  4628.1 1543.89
  4633.3 1540.95  4663.4 1543.02  4668.6 1539.47    4726 1537.57  4749.6    1532
  4798.3 1510.57  4865.9 1496.02  4903.3 1491.96    4974 1486.89  4990.6 1481.23
  4991.1 1480.73  4998.7 1481.23  5002.4 1484.42  5015.1 1486.32    5057 1489.75
  5301.7 1494.86  5500.1 1498.81  5618.3 1501.45  5819.3 1511.08  5940.7 1524.89
#Mann= 7 ,-1 , 0
  3840.8     .07       0  4399.2     .12       0  4903.3     .07       0
  4990.6     .05       0  4998.7     .07       0  5301.7    .035       0
  5500.1     .07       0
Bank Sta=4990.6,4998.7
XS Rating Curve= 0 ,0
Exp/Cntr=0.3,0.1

Type RM Length L Ch R = 1 ,9135    ,915,915,915
BEGIN DESCRIPTION:
Stream0124_DS 18.0
END DESCRIPTION:
XS GIS Cut Line= 3
        2026875.     13917674.98        2026875.       13917875.
      2027269.18     13918755.59
#Sta/Elev= 30
  4791.3 1526.24  4851.3 1511.77  4934.2 1500.22  4941.3 1497.88  4971.3 1491.75
  4981.3 1487.93  4988.8 1481.85  4994.1 1481.85  5000.2 1478.23  5005.7 1476.27
  5019.3 1475.94  5019.8 1475.44  5027.5 1475.94  5035.1  1479.3  5080.7 1481.46
  5103.9  1481.5  5121.6 1482.55  5127.1 1483.76  5232.4 1483.91  5243.1 1484.89
  5254.3 1483.91  5294.9 1483.87  5341.3 1488.37  5484.3 1490.87  5612.9 1495.67
  5681.6 1499.24    5824 1509.65  5855.8 1514.89  5889.9 1517.83  5956.1 1525.86
#Mann= 4 ,-1 , 0
  4791.3     .12       0  4934.2     .07       0  5019.3     .05       0
  5027.5     .07       0
Bank Sta=5019.3,5027.5
XS Rating Curve= 0 ,0
Exp/Cntr=0.3,0.1

Type RM Length L Ch R = 1 ,8220    ,557,557,557
BEGIN DESCRIPTION:
Stream0124_DS 17.0
END DESCRIPTION:
XS GIS Cut Line= 3
      2026775.01     13917774.99        2026375.       13918175.
        2026275.       13918525.
#Sta/Elev= 30
  4434.3 1500.98  4450.8  1499.4  4462.6 1496.41  4476.7 1494.57  4490.9 1493.12
    4505 1493.15  4547.4 1489.33  4618.2 1485.76  4681.5  1484.1  4738.6 1483.37
  4816.4 1480.39  4910.1 1476.87  4943.4 1475.98  5006.1 1475.71  5006.6 1475.21
  5014.1 1475.21  5014.6 1475.71  5089.7 1475.76  5094.9 1476.72    5104 1476.45
  5123.5 1486.51  5135.2 1491.64  5187.2  1498.1  5201.5 1500.37    5208  1502.7
  5228.8 1505.17  5240.5 1507.41  5313.3 1513.58  5332.8 1518.92    5364 1523.16
#Mann= 8 ,-1 , 0
  4434.3     .07       0  4450.8    .035       0  4681.5     .12       0
  4738.6    .035       0  4816.4     .12       0  4910.1     .07       0
  5006.1     .05       0  5014.6     .07       0
Bank Sta=5006.1,5014.6
XS Rating Curve= 0 ,0
Exp/Cntr=0.3,0.1

Type RM Length L Ch R = 1 ,7663    ,301,301,301
BEGIN DESCRIPTION:
Stream0124_DS 16.0
END DESCRIPTION:
XS GIS Cut Line= 3
      2026525.03     13917524.98      2026049.57     13917939.64
      2026108.16     13918377.97
#Sta/Elev= 30
  4357.4 1514.26  4406.4 1508.35  4491.8 1498.81    4506 1493.79  4520.2 1490.56
  4534.5 1491.52  4548.7 1488.12  4640.8 1482.19  4747.1 1477.81  4768.8 1474.51
  4833.5 1474.18  4938.9 1473.26  4962.4 1468.01  4973.4 1465.14  4981.1 1462.75
  4983.7 1460.51  4984.2 1460.01  4992.2 1460.51  5013.9 1461.68  5023.9 1464.57
  5044.1 1467.04  5068.2 1466.88  5114.7 1470.89  5134.9 1474.93  5155.1 1481.64
  5175.3 1486.55  5266.1  1489.9  5336.7 1496.45  5356.9 1499.66  5430.5 1504.25
#Mann= 7 ,-1 , 0
  4357.4     .12       0  4406.4    .035       0  4833.5     .07       0
  4962.4    .035       0  4973.4     .07       0  4983.7     .05       0
  4992.2     .07       0
Bank Sta=4983.7,4992.2
XS Rating Curve= 0 ,0
Exp/Cntr=0.3,0.1

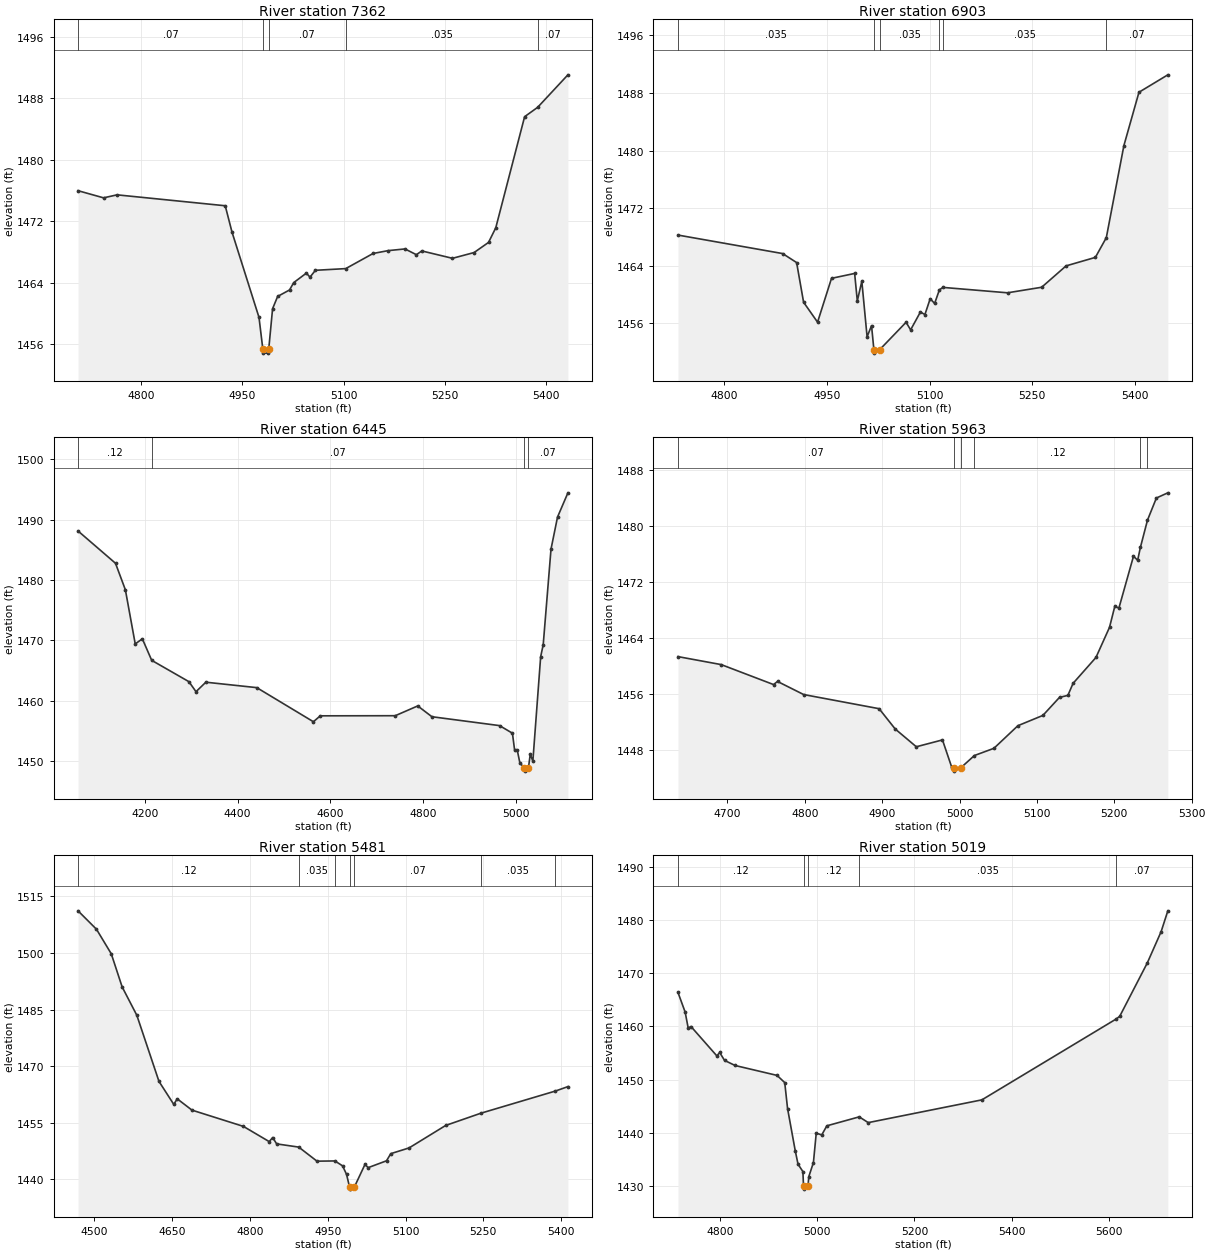
Type RM Length L Ch R = 1 ,7362    ,459,459,459
BEGIN DESCRIPTION:
Stream0124_DS 15.0
END DESCRIPTION:
XS GIS Cut Line= 3
      2025765.28      13917577.2        2025775.       13917875.
      2025925.01     13918275.04
#Sta/Elev= 30
  4706.7 1475.96  4744.5 1475.03  4764.5 1475.42  4924.6    1474  4934.6 1470.58
  4974.6 1459.47  4980.3 1455.32  4980.8 1454.82  4988.5 1454.82    4989 1455.32
  4994.7  1460.6  5002.2  1462.2  5019.8 1463.04    5026    1464  5044.7 1465.23
  5050.1 1464.71  5058.1  1465.6    5103 1465.82  5143.5 1467.79  5165.8 1468.16
  5190.7 1468.38  5207.6 1467.63  5215.6 1468.12    5261 1467.16    5293 1467.91
  5314.4 1469.23  5325.1 1471.13  5367.8 1485.59  5387.1 1486.81  5431.9 1491.04
#Mann= 5 ,-1 , 0
  4706.7     .07       0  4980.3     .05       0    4989     .07       0
    5103    .035       0  5387.1     .07       0
Bank Sta=4980.3,4989
XS Rating Curve= 0 ,0
Exp/Cntr=0.3,0.1

Type RM Length L Ch R = 1 ,6903    ,458,458,458
BEGIN DESCRIPTION:
Stream0124_DS 14.0
END DESCRIPTION:
XS GIS Cut Line= 3
        2025425.       13917775.        2025475.       13918025.
      2025824.98     13918324.98
#Sta/Elev= 30
  4732.1 1468.27  4885.1  1465.7  4905.5 1464.45  4915.7 1458.94  4936.1 1456.17
  4956.5 1462.26  4990.3 1462.94  4994.2 1459.12  5000.8 1461.85  5008.5 1454.14
    5015 1455.69  5018.4 1452.37  5018.9 1451.87  5027.1 1452.37  5065.5 1456.16
  5072.1  1455.1  5086.4 1457.58    5093 1457.23  5100.7 1459.43  5107.2 1458.77
  5114.2 1460.67  5119.4    1461  5213.7 1460.25  5263.6 1461.02  5299.3 1463.99
  5342.1 1465.17  5358.1 1467.91  5383.8 1480.71  5405.8 1488.11    5448 1490.53
#Mann= 6 ,-1 , 0
  4732.1    .035       0  5018.4    .035       0  5027.1    .035       0
  5114.2     .07       0  5119.4    .035       0  5358.1     .07       0
Bank Sta=5018.4,5027.1
XS Rating Curve= 0 ,0
Exp/Cntr=0.3,0.1

Type RM Length L Ch R = 1 ,6445    ,482,482,482
BEGIN DESCRIPTION:
Stream0124_DS 13.0
END DESCRIPTION:
XS GIS Cut Line= 3
      2024925.03     13917575.04        2025425.       13918375.
      2025475.02     13918475.04
#Sta/Elev= 30
  4056.2  1488.1  4136.9 1482.75  4158.2 1478.35  4179.4 1469.39  4194.7 1470.24
  4214.9 1466.67    4295 1463.14  4310.3 1461.48  4331.5 1463.05  4441.2 1462.15
  4563.2  1456.5    4578 1457.48  4739.5  1457.5  4787.9 1459.12  4818.5 1457.33
  4964.2 1455.86  4991.9  1454.6  4996.6  1451.8  5002.3  1451.8  5007.9 1449.69
  5017.6 1448.82  5018.1 1448.32  5026.3 1448.82  5030.3 1451.12  5035.9 1449.98
  5052.7 1467.27  5058.2 1469.26    5075  1485.1    5089  1490.4  5111.4 1494.42
#Mann= 4 ,-1 , 0
  4056.2     .12       0  4214.9     .07       0  5017.6     .05       0
  5026.3     .07       0
Bank Sta=5017.6,5026.3
XS Rating Curve= 0 ,0
Exp/Cntr=0.3,0.1

Type RM Length L Ch R = 1 ,5963    ,482,482,482
BEGIN DESCRIPTION:
Stream0124_DS 12.0
END DESCRIPTION:
XS GIS Cut Line= 3
      2025074.99     13917925.03        2024975.       13918275.
      2025074.99     13918524.97
#Sta/Elev= 30
    4636 1461.32  4691.9 1460.18  4759.5 1457.33  4764.7 1457.77  4798.5  1455.9
    4896 1453.88  4916.8 1450.98  4944.1 1448.44  4977.9 1449.42  4989.6  1445.6
  4992.9 1445.46  4993.4 1444.96  5001.8 1445.46  5019.2 1447.19  5044.4 1448.22
  5075.4 1451.45  5107.7 1452.92  5129.2  1455.5    5140 1455.78  5146.7  1457.5
  5176.3  1461.2  5193.8  1465.5  5200.6 1468.48    5206 1468.27  5224.8 1475.66
  5230.2 1475.09  5233.7 1476.91  5242.9 1480.82  5254.4 1483.98  5269.2 1484.72
#Mann= 6 ,-1 , 0
    4636     .07       0  4992.9     .05       0  5001.8     .07       0
  5019.2     .12       0  5233.7     .07       0  5242.9    .035       0
Bank Sta=4992.9,5001.8
XS Rating Curve= 0 ,0
Exp/Cntr=0.3,0.1

Type RM Length L Ch R = 1 ,5481    ,462,462,462
BEGIN DESCRIPTION:
Stream0124_DS 11.0
END DESCRIPTION:
XS GIS Cut Line= 3
      2024174.99     13917774.99        2024525.       13918175.
       2024777.9     13918501.74
#Sta/Elev= 30
  4468.5 1511.16  4504.1 1506.27  4532.6 1499.77  4553.5 1491.01  4581.9 1483.47
  4624.6 1465.95  4653.1 1459.86  4659.8 1461.33  4688.2 1458.34  4787.4 1454.03
  4837.2 1449.99  4843.9 1451.08  4851.5 1449.39  4894.1 1448.54  4929.3 1444.81
  4963.9 1444.87  4978.7 1443.56  4986.3 1441.31  4992.2  1437.9  4992.7  1437.4
  5001.2  1437.9  5021.8 1443.93  5028.1  1443.1  5063.4 1444.91  5071.6  1446.8
  5106.9 1448.32  5177.5 1454.28  5245.1 1457.51  5389.2  1463.4  5413.2 1464.57
#Mann= 7 ,-1 , 0
  4468.5     .12       0  4894.1    .035       0  4963.9     .07       0
  4992.2     .05       0  5001.2     .07       0  5245.1    .035       0
  5389.2     .07       0
Bank Sta=4992.2,5001.2
XS Rating Curve= 0 ,0
Exp/Cntr=0.3,0.1

Type RM Length L Ch R = 1 ,5019    ,442,442,442
BEGIN DESCRIPTION:
Stream0124_DS 10.0
END DESCRIPTION:
XS GIS Cut Line= 3
      2023979.28     13918022.14        2024125.       13918275.
       2024643.3     13918766.45
#Sta/Elev= 30
  4714.2 1466.39    4729 1462.68  4735.2  1459.7    4741 1459.98  4794.1 1454.47
  4799.9 1455.11  4809.8 1453.63  4831.5 1452.67  4917.7 1450.81  4933.5 1449.46
  4939.3 1444.59    4955 1436.71  4960.8 1434.15  4970.8 1432.76  4972.1 1429.97
  4972.6 1429.47  4981.1 1429.97    4983 1431.83  4992.4 1434.46  4998.2 1439.97
  5009.5 1439.64    5020 1441.35  5086.5 1443.03    5105 1441.95  5338.4 1446.22
  5613.8 1461.37  5621.5  1461.9  5678.1 1471.91  5706.5 1477.78  5720.3 1481.69
#Mann= 5 ,-1 , 0
  4714.2     .12       0  4972.1     .05       0  4981.1     .12       0
  5086.5    .035       0  5613.8     .07       0
Bank Sta=4972.1,4981.1
XS Rating Curve= 0 ,0
Exp/Cntr=0.3,0.1

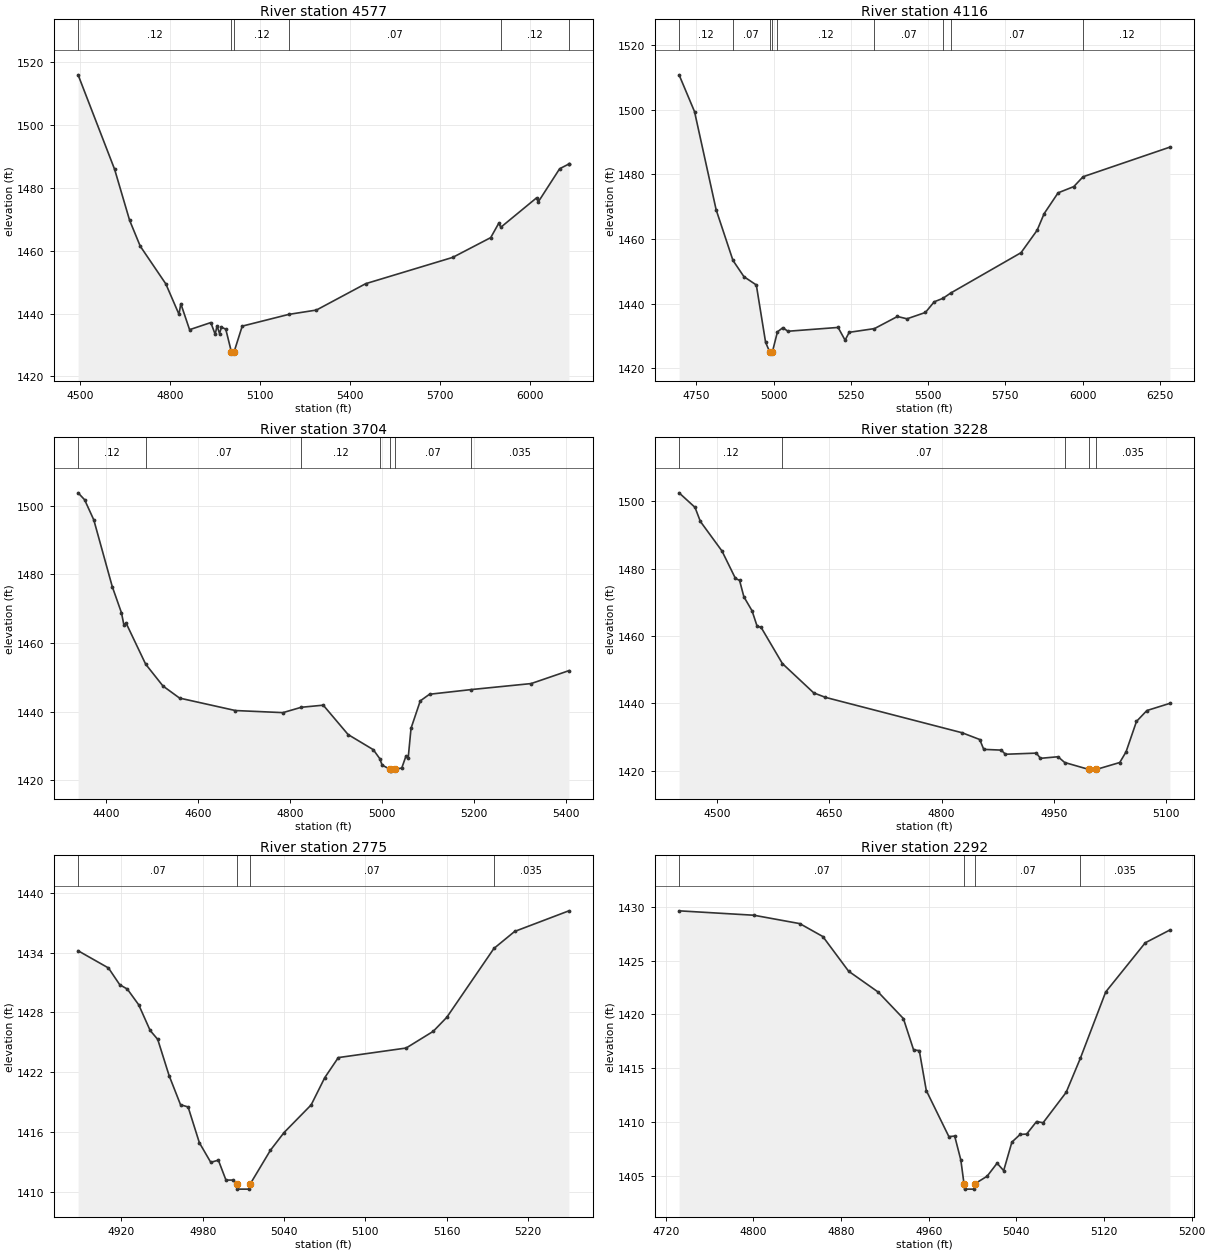
Type RM Length L Ch R = 1 ,4577    ,461,461,461
BEGIN DESCRIPTION:
Stream0124_DS 9.0
END DESCRIPTION:
XS GIS Cut Line= 3
      2023524.99     13917974.99        2023825.       13918375.
      2024183.25     13919454.39
#Sta/Elev= 30
    4494 1515.86  4615.9 1485.81  4665.9 1469.62  4701.3 1461.41  4786.7 1449.41
  4830.5 1439.76  4836.7 1443.12  4865.9 1434.86  4936.7 1437.12  4951.3 1433.39
  4957.6 1436.11  4965.9 1433.61  4972.1 1435.67  4986.7 1435.01  5005.1 1427.91
  5005.6 1427.41  5014.7 1427.91  5041.5 1435.99  5197.3 1439.73    5289  1441.1
  5453.3 1449.48  5743.7 1457.84  5870.4 1464.12  5896.8 1468.62  5904.5 1467.44
  6023.5 1476.77  6028.8 1475.44  6100.3 1486.01  6129.9 1487.46  6131.3 1487.46
#Mann= 6 ,-1 , 0
    4494     .12       0  5005.1     .05       0  5014.7     .12       0
  5197.3     .07       0  5904.5     .12       0  6129.9     .07       0
Bank Sta=5005.1,5014.7
XS Rating Curve= 0 ,0
Exp/Cntr=0.3,0.1

Type RM Length L Ch R = 1 ,4116    ,412,412,412
BEGIN DESCRIPTION:
Stream0124_DS 8.0
END DESCRIPTION:
XS GIS Cut Line= 3
        2023425.     13918025.04        2023425.       13918325.
      2024024.85     13919465.29
#Sta/Elev= 30
  4694.4 1510.82  4744.4 1499.44  4814.4 1469.05  4868.8 1453.39  4904.4 1448.35
  4944.4 1445.79  4974.4 1428.05  4987.1  1425.2  4987.6  1424.7  4996.7  1425.2
  5012.7 1431.28  5030.2 1432.57  5046.6 1431.47    5209 1432.65  5231.6 1428.71
    5245 1431.14  5326.7 1432.29  5401.1 1436.04    5432 1435.32  5491.5 1437.28
  5520.2 1440.59  5548.4 1441.66  5573.2 1443.28    5801 1455.78  5853.1 1462.72
  5875.7 1467.85  5920.9  1474.3  5971.7 1476.23  6001.8 1479.28  6282.8 1488.45
#Mann= 9 ,-1 , 0
  4694.4     .12       0  4868.8     .07       0  4987.1     .05       0
  4996.7     .07       0  5012.7     .12       0  5326.7     .07       0
  5548.4    .035       0  5573.2     .07       0  6001.8     .12       0
Bank Sta=4987.1,4996.7
XS Rating Curve= 0 ,0
Exp/Cntr=0.3,0.1

Type RM Length L Ch R = 1 ,3704    ,476,476,476
BEGIN DESCRIPTION:
Stream0124_DS 7.0
END DESCRIPTION:
XS GIS Cut Line= 4
      2023301.85     13918030.95       2023338.8     13918481.04
        2023425.       13918675.      2023386.81     13919076.83
#Sta/Elev= 30
  4339.8 1503.71  4353.9 1501.71    4374 1495.82  4414.1 1476.42  4434.2 1468.77
  4439.3 1465.32  4444.3 1465.76  4486.8 1453.82  4524.5 1447.46  4560.6 1443.95
  4681.9 1440.33  4785.3 1439.72  4825.3 1441.28    4873 1441.89  4927.1 1433.33
  4981.8 1428.94    4996 1426.31  5000.9 1424.45  5018.8 1423.19  5019.3 1422.69
  5028.7 1423.19  5043.8 1423.61  5052.7 1427.01  5057.7 1426.51  5063.9 1435.16
    5084 1443.14  5104.1 1445.07  5194.6 1446.43  5325.1 1448.18  5407.3 1451.95
#Mann= 7 ,-1 , 0
  4339.8     .12       0  4486.8     .07       0  4825.3     .12       0
    4996     .07       0  5018.8     .05       0  5028.7     .07       0
  5194.6    .035       0
Bank Sta=5018.8,5028.7
XS Rating Curve= 0 ,0
Exp/Cntr=0.3,0.1

Type RM Length L Ch R = 1 ,3228    ,453,453,453
BEGIN DESCRIPTION:
Stream0124_DS 6.0
END DESCRIPTION:
XS GIS Cut Line= 3
      2023242.07     13918025.44        2023025.       13918525.
      2022974.99     13918625.02
#Sta/Elev= 30
  4448.9  1502.5  4470.2 1498.19  4477.4    1494  4506.3 1485.22  4524.3 1477.08
  4529.8 1476.51  4535.6 1471.62  4546.5 1467.48  4553.2 1462.95  4558.7 1462.52
  4587.1  1451.8    4629  1443.1  4644.7 1441.77  4827.5 1431.26    4851 1429.26
  4856.4 1426.33  4879.9 1426.11  4885.3 1424.88  4926.8 1425.22  4932.2 1423.67
  4955.7 1424.14  4964.7 1422.43    4997 1420.37  4997.5 1419.87  5006.9 1420.37
  5038.3 1422.43  5046.7 1425.58  5060.7 1434.64  5074.6 1437.86  5105.4    1440
#Mann= 5 ,-1 , 0
  4448.9     .12       0  4587.1     .07       0  4964.7    .035       0
    4997    .035       0  5006.9    .035       0
Bank Sta=4997,5006.9
XS Rating Curve= 0 ,0
Exp/Cntr=0.3,0.1

Type RM Length L Ch R = 1 ,2775    ,483,483,483
BEGIN DESCRIPTION:
Stream0124_DS 5.0
END DESCRIPTION:
XS GIS Cut Line= 3
        2022775.       13918175.        2022725.       13918275.
        2022725.       13918525.
#Sta/Elev= 30
  4888.2 1434.18  4910.6 1432.45  4918.9 1430.77  4924.5 1430.33  4932.9 1428.75
  4941.3 1426.18  4946.9 1425.28  4955.3 1421.64  4963.7 1418.72  4969.3 1418.49
  4977.6  1414.9    4986 1412.93  4991.6 1413.15  4997.2 1411.15  5002.5 1411.15
    5005 1410.74  5005.5 1410.24  5014.5 1410.24    5015 1410.74    5030 1414.15
    5040 1415.92    5060  1418.7    5070 1421.43    5080 1423.45    5130 1424.41
    5150 1426.09    5160  1427.5  5194.7 1434.41    5210 1436.12    5250 1438.19
#Mann= 4 ,-1 , 0
  4888.2     .07       0    5005     .05       0    5015     .07       0
  5194.7    .035       0
Bank Sta=5005,5015
XS Rating Curve= 0 ,0
Exp/Cntr=0.3,0.1

Type RM Length L Ch R = 1 ,2292    ,443,443,443
BEGIN DESCRIPTION:
Stream0124_DS 4.0
END DESCRIPTION:
XS GIS Cut Line= 3
        2022356.     13918019.93        2022275.       13918275.
        2022175.       13918425.
#Sta/Elev= 30
  4732.2 1429.63  4800.5 1429.22  4842.4 1428.44  4863.4 1427.24  4886.9 1424.02
  4913.9 1422.08  4936.9 1419.62  4946.2 1416.71  4951.4 1416.64  4957.8 1412.93
  4978.4 1408.65  4983.7  1408.7  4989.3 1406.48  4992.2 1404.27  4992.7 1403.77
  5001.7 1403.77  5002.2 1404.27  5013.3 1404.97  5022.4 1406.18  5028.4 1405.49
  5035.9 1408.14  5043.4 1408.85  5049.4 1408.89  5058.4 1410.05  5064.4 1409.94
  5085.4 1412.76  5098.3 1415.91  5121.5 1422.09  5157.6 1426.66  5180.1 1427.85
#Mann= 4 ,-1 , 0
  4732.2     .07       0  4992.2     .05       0  5002.2     .07       0
  5098.3    .035       0
Bank Sta=4992.2,5002.2
XS Rating Curve= 0 ,0
Exp/Cntr=0.3,0.1