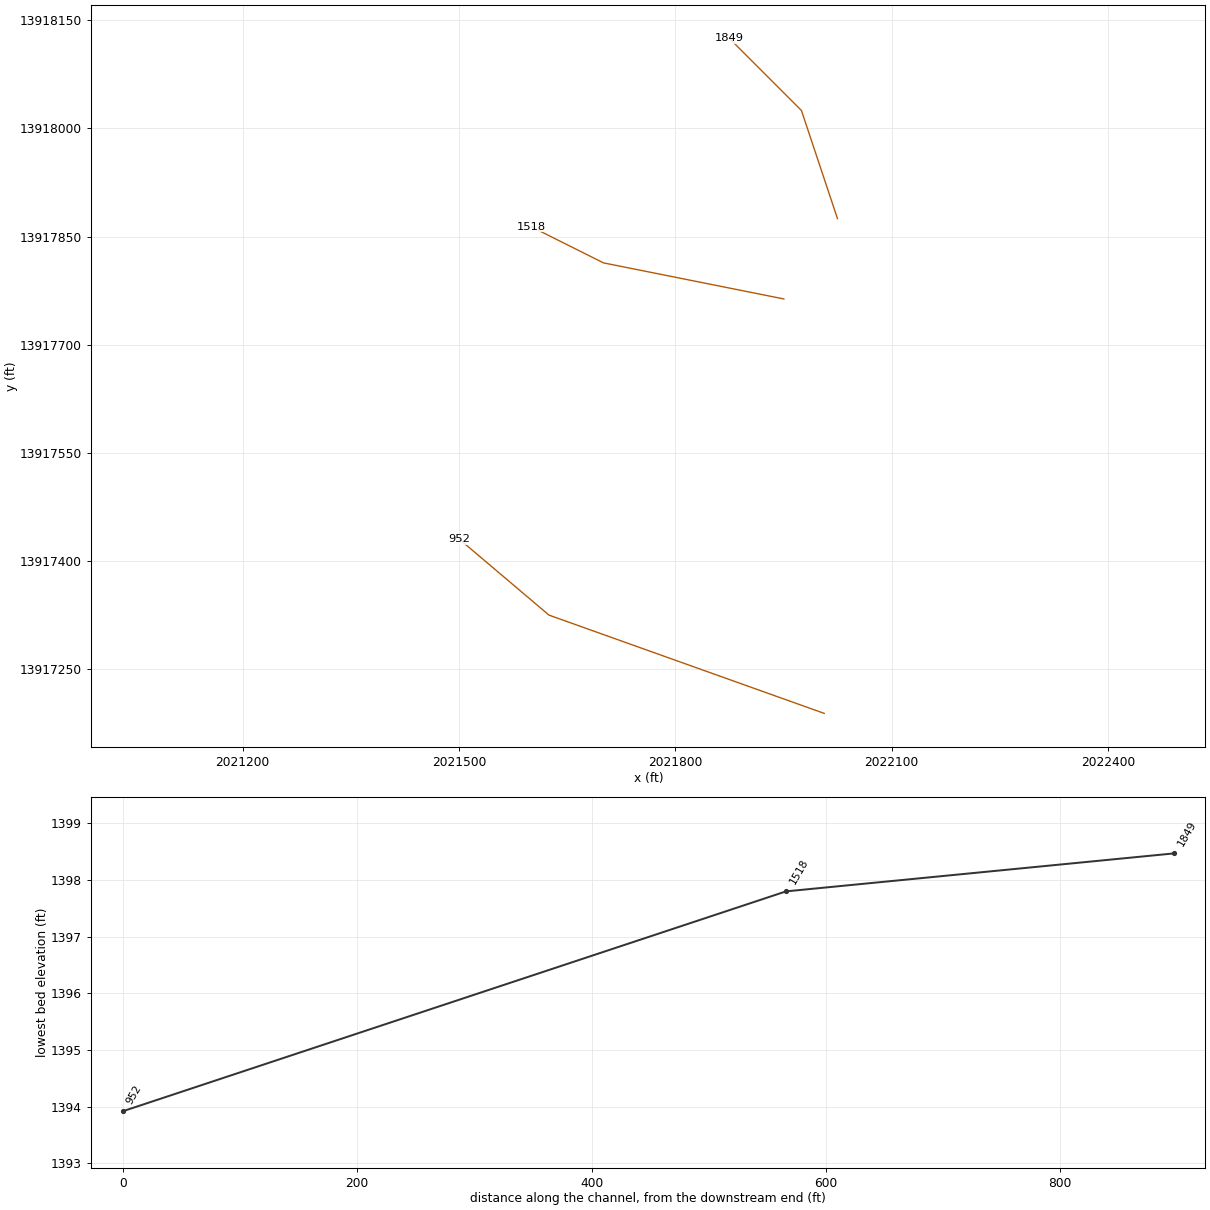
HEC-RAS study Stream0124_DS.prj: Stream0124_DS Base Level Engineering

--- Stream0124_DS.g01 (geometry) --- (continued)

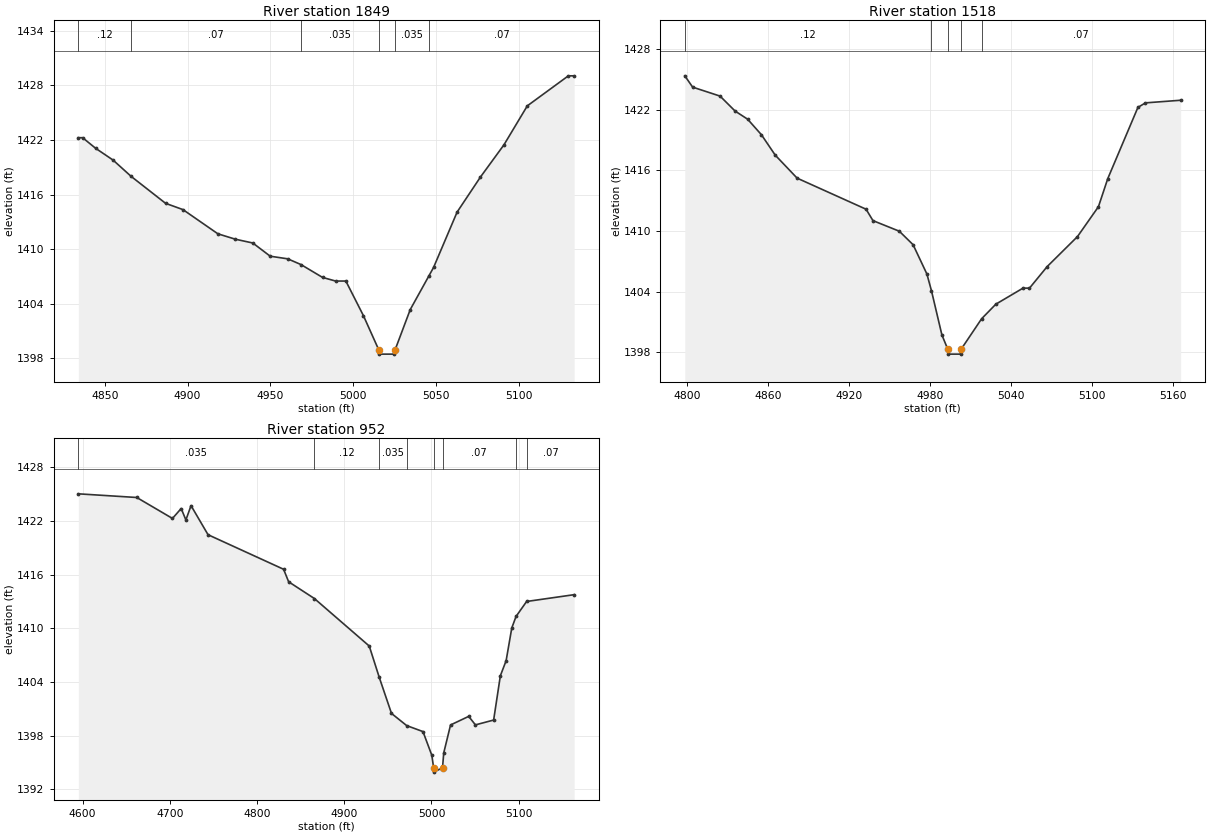
Type RM Length L Ch R = 1 ,1849    ,331,331,331
BEGIN DESCRIPTION:
Stream0124_DS 3.0
END DESCRIPTION:
XS GIS Cut Line= 3
      2022024.99     13917875.04        2021975.       13918025.
        2021875.       13918125.
#Sta/Elev= 30
    4834 1422.25  4836.6 1422.25  4844.5 1421.08    4855 1419.79  4865.9    1418
  4886.7 1415.04  4897.2 1414.35  4918.3 1411.69  4928.8  1411.1  4939.4 1410.68
  4949.9 1409.23  4960.5 1408.94  4968.5 1408.31  4981.5  1406.9  4989.4  1406.5
  4995.6  1406.5  5006.2  1402.7  5015.4 1398.97  5015.9 1398.47  5024.9 1398.47
  5025.4 1398.97  5034.5 1403.37  5045.8 1407.08  5048.6    1408  5062.8 1414.08
  5076.9 1417.93  5091.1 1421.47  5105.2 1425.75    5130 1429.05  5133.5 1429.05
#Mann= 6 ,-1 , 0
    4834     .12       0  4865.9     .07       0  4968.5    .035       0
  5015.4    .035       0  5025.4    .035       0  5045.8     .07       0
Bank Sta=5015.4,5025.4
XS Rating Curve= 0 ,0
Exp/Cntr=0.3,0.1

Type RM Length L Ch R = 1 ,1518    ,566,566,566
BEGIN DESCRIPTION:
Stream0124_DS 2.0
END DESCRIPTION:
XS GIS Cut Line= 3
      2021950.64     13917763.54       2021700.6     13917813.54
       2021600.6     13917863.55
#Sta/Elev= 30
  4798.6 1425.38  4804.4 1424.26  4824.7 1423.37  4835.8 1421.89  4845.1 1421.08
  4855.3 1419.54  4865.5 1417.52  4881.7 1415.24  4932.7 1412.16  4937.8 1411.03
  4957.3 1409.98  4967.5 1408.64  4977.7 1405.74  4981.1 1404.07  4988.8  1399.7
  4993.1  1398.3  4993.6  1397.8  5002.6  1397.8  5003.1  1398.3  5018.2 1401.31
  5028.7 1402.75  5048.8 1404.34  5053.6 1404.34  5066.7 1406.48  5089.1 1409.45
  5104.6 1412.41  5111.5 1415.19  5133.8 1422.25  5139.4  1422.7  5165.4 1422.96
#Mann= 5 ,-1 , 0
  4798.6     .12       0  4981.1    .035       0  4993.1    .035       0
  5003.1    .035       0  5018.2     .07       0
Bank Sta=4993.1,5003.1
XS Rating Curve= 0 ,0
Exp/Cntr=0.3,0.1

Type RM Length L Ch R = 1 ,952     ,0,0,0
BEGIN DESCRIPTION:
Stream0124_DS 1.0
END DESCRIPTION:
XS GIS Cut Line= 3
      2022006.64     13917188.76        2021625.       13917325.
      2021500.46     13917430.42
#Sta/Elev= 30
  4595.2 1425.02  4662.2 1424.61  4703.1 1422.27  4713.1 1423.38  4718.5  1422.1
  4724.4  1423.7  4743.9 1420.45  4830.5 1416.59  4836.3 1415.19  4865.8 1413.32
  4928.7 1408.01  4940.2  1404.5  4954.2 1400.48  4971.6 1399.12  4990.3 1398.45
  5000.4 1395.81  5002.5 1394.42    5003 1393.92  5012.7 1394.42  5014.1 1396.07
  5021.9 1399.19  5042.7 1400.15  5050.4  1399.2  5071.3 1399.74    5079 1404.69
  5085.6 1406.37  5092.1 1410.03    5097 1411.32  5109.1 1412.99  5163.6 1413.75
#Mann= 8 ,-1 , 0
  4595.2    .035       0  4865.8     .12       0  4940.2    .035       0
  4971.6     .07       0  5002.5     .05       0  5012.7     .07       0
    5097    .035       0  5109.1     .07       0
Bank Sta=5002.5,5012.7
XS Rating Curve= 0 ,0
Exp/Cntr=0.3,0.1

Chan Stop Cuts=-1
Use User Specified Reach Order=0
Composite Channel Slope=5