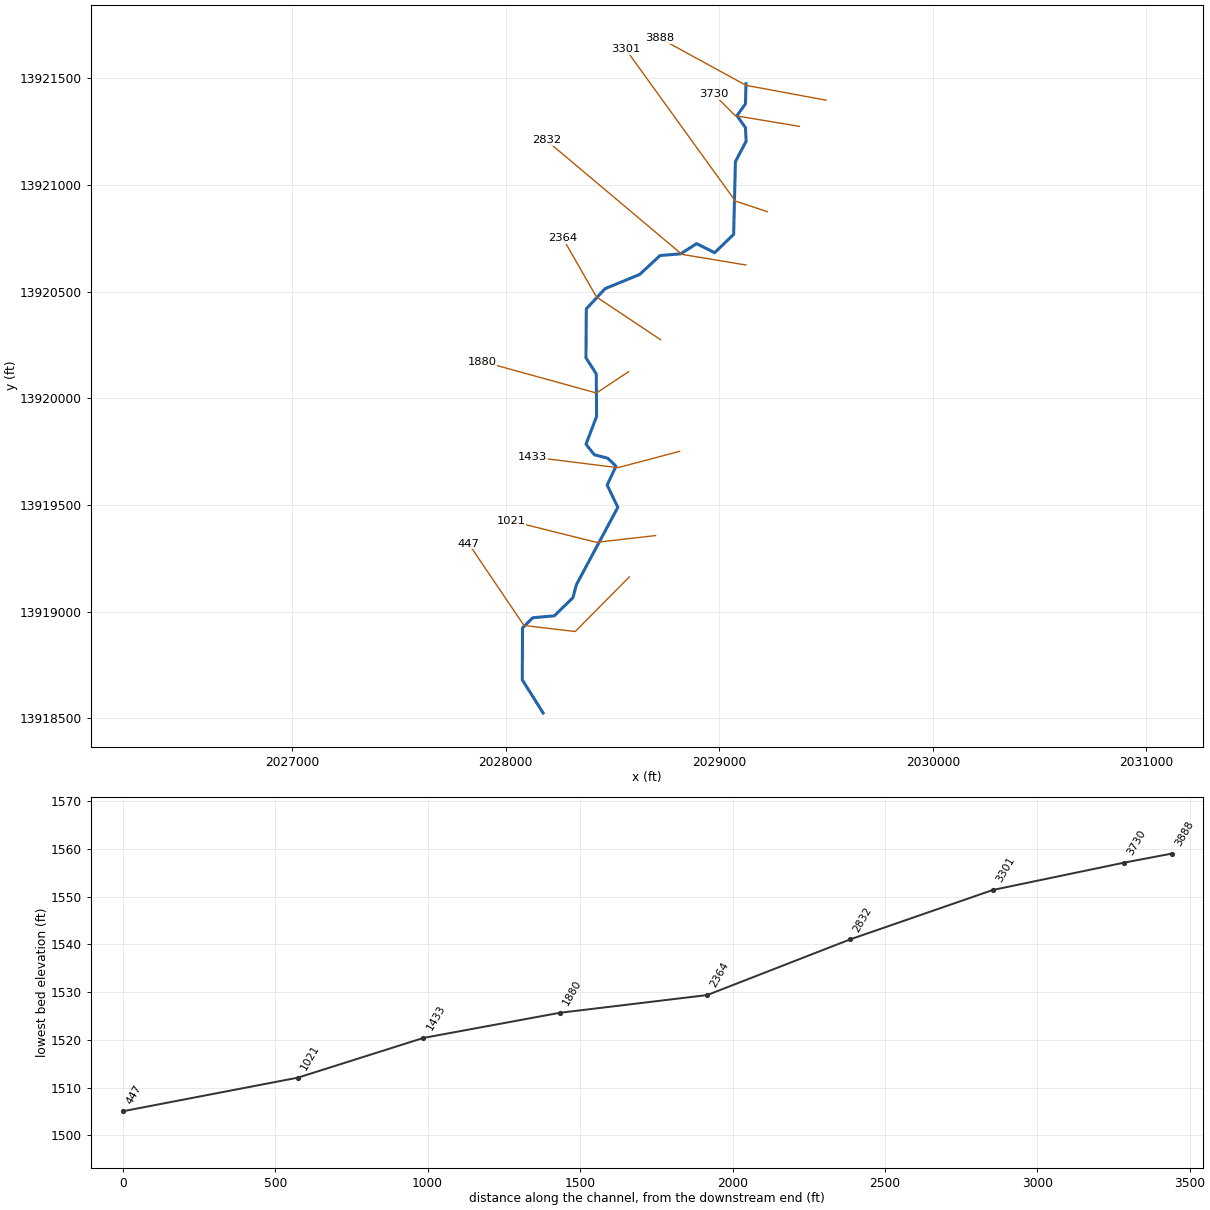
--- Stream0125_DS.prj (project) ---

Proj Title=Stream0125_DS Base Level Engineering
Current Plan=p01
Default Exp/Contr=0.3,0.1
English Units
Geom File=g01
Flow File=f01
Plan File=p01
BEGIN DESCRIPTION:
Stream0125_DS
END DESCRIPTION:

--- Stream0125_DS.p01 (plan) ---

Plan Title=Multiple Run
Short Identifier=Multiple
Geom File=g01
Flow File=f01
Subcritical Flow
K Sum by GR= 0
Std Step Tol= 0.01
Critical Tol= 0.01
Num of Std Step Trials= 20
Max Error Tol= 0.3
Flow Tol Ratio= 0.001
Split Flow NTrial= 30
Split Flow Tol= 0.02
Split Flow Ratio= 0.02
Log Output Level= 0
Friction Slope Method= 1
Unsteady Friction Slope Method= 2
Unsteady Bridges Friction Slope Method= 1
Parabolic Critical Depth
Global Vel Dist=  1 , 1 , 1
Global Log Level= 0
CheckData=True
Encroach Param= -1, 0, 0, 0
BEGIN DESCRIPTION:
Multiple Run
END DESCRIPTION:

--- Stream0125_DS.f01 (steady flow) ---

Flow Title=Multiple
Number of Profiles=7
Profile Names=10-year,25-year,50-year,1pct_min,100-year,1pct_plu,500-year
River Rch & RM= Stream0125_DS,Reach-1,3888
     941    1612    2260    1540    3072    6129    5623
River Rch & RM= Stream0125_DS,Reach-1,3301
    1137    1965    2769    1894    3778    7539    6978
Boundary for River Rch & Prof#=Stream0125_DS,Reach-1,1
Up Type=0
Dn Type=3
Dn Slope=0.005
Boundary for River Rch & Prof#=Stream0125_DS,Reach-1,2
Up Type=0
Dn Type=3
Dn Slope=0.005
Boundary for River Rch & Prof#=Stream0125_DS,Reach-1,3
Up Type=0
Dn Type=3
Dn Slope=0.005
Boundary for River Rch & Prof#=Stream0125_DS,Reach-1,4
Up Type=0
Dn Type=3
Dn Slope=0.005
Boundary for River Rch & Prof#=Stream0125_DS,Reach-1,5
Up Type=0
Dn Type=3
Dn Slope=0.005
Boundary for River Rch & Prof#=Stream0125_DS,Reach-1,6
Up Type=0
Dn Type=3
Dn Slope=0.005
Boundary for River Rch & Prof#=Stream0125_DS,Reach-1,7
Up Type=0
Dn Type=3
Dn Slope=0.005

--- Stream0125_DS.g01 (geometry) ---

Geom Title=Existing Conditions

River Reach=Stream0125_DS,Reach-1
Reach XY= 30
      2029125.00     13921475.00      2029122.54     13921380.37
      2029082.52     13921325.01      2029122.64     13921269.11
      2029125.58     13921204.96      2029075.52     13921109.78
      2029067.19     13920768.77      2028978.42     13920682.81
      2028893.46     13920725.11      2028819.03     13920677.38
      2028722.58     13920669.46      2028627.29     13920580.85
      2028465.29     13920514.25      2028377.17     13920419.57
      2028375.52     13920190.22      2028423.78     13920114.50
      2028425.45     13919915.72      2028375.69     13919784.62
      2028414.92     13919735.65      2028477.82     13919719.14
      2028515.97     13919682.01      2028474.91     13919593.46
      2028524.77     13919489.10      2028331.10     13919127.18
      2028314.25     13919065.29      2028227.44     13918980.52
      2028126.25     13918971.49      2028078.44     13918923.78
      2028077.34     13918680.52      2028175.00     13918525.00

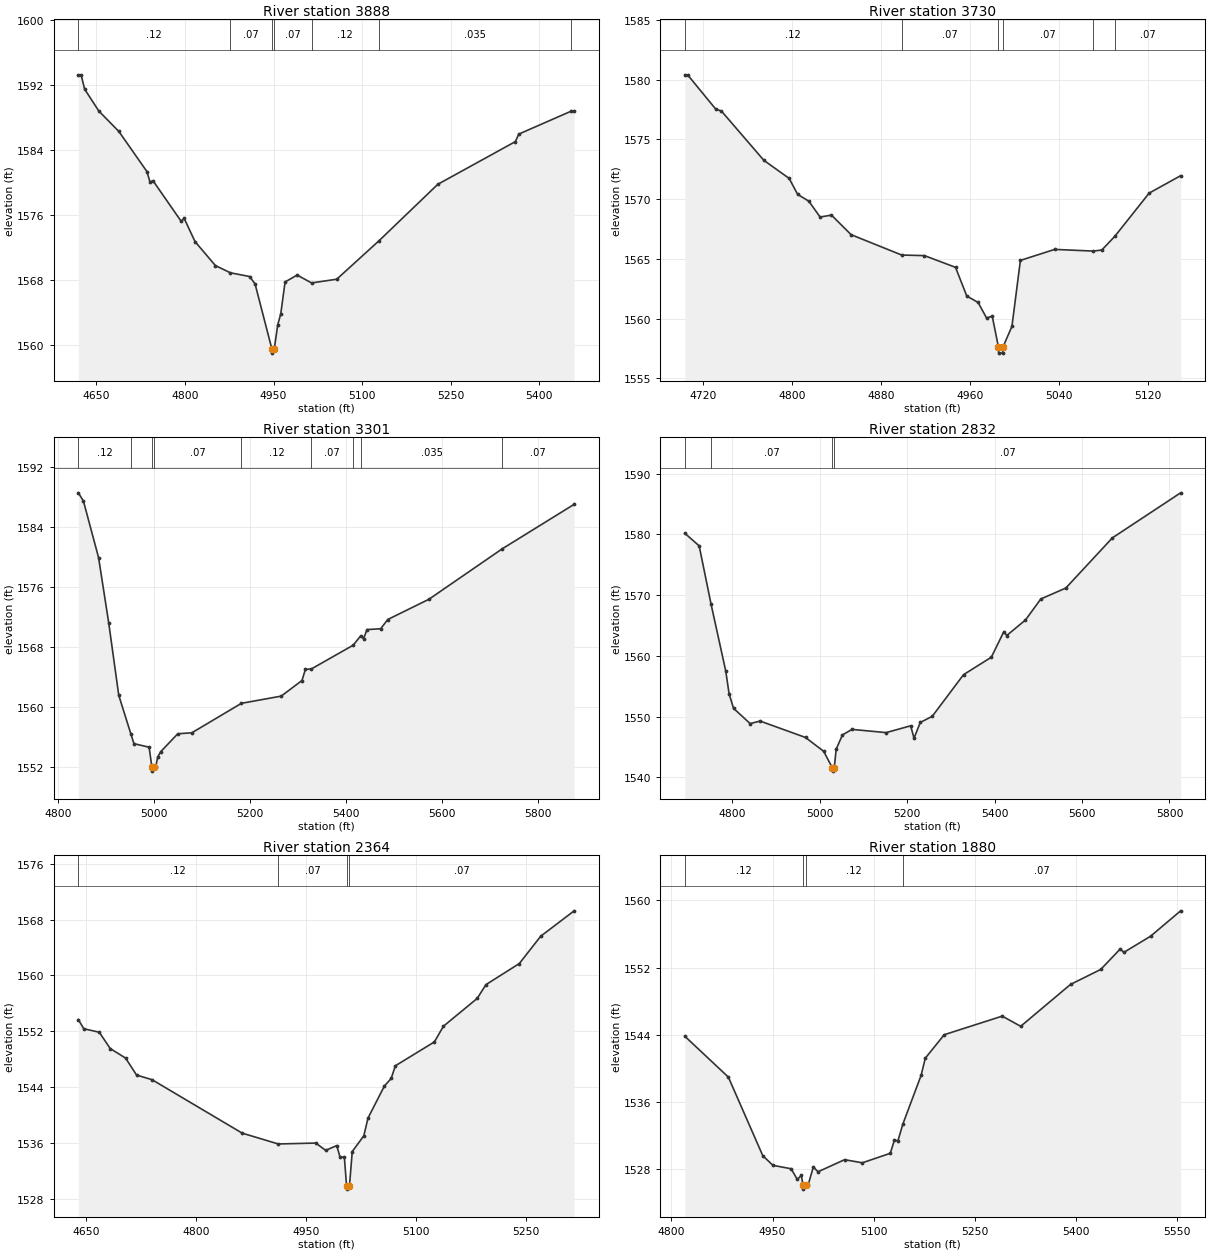
Type RM Length L Ch R = 1,3888,158,158,158
BEGIN DESCRIPTION:
Stream0125_DS 8.0
END DESCRIPTION:
XS GIS Cut Line= 3
      2029499.13     13921397.79      2029125.04     13921467.33
      2028722.51     13921687.70
#Sta/Elev= 30
  4619.5 1593.26  4624.2 1593.26  4630.2 1591.49  4654.2 1588.81  4688.1 1586.30
  4735.6 1581.37  4740.9 1580.07  4745.9 1580.24  4793.6 1575.25  4798.7 1575.61
  4817.0 1572.76  4851.5 1569.81  4876.9 1568.92  4909.4 1568.46  4918.7 1567.55
  4947.2 1559.54  4947.4 1559.04  4951.2 1559.54  4957.1 1562.53  4962.2 1563.87
  4969.5 1567.79  4989.9 1568.64  5014.4 1567.67  5057.0 1568.13  5128.7 1572.87
  5228.1 1579.80  5359.4 1585.05  5365.1 1585.97  5452.8 1588.76  5458.9 1588.77
#Mann=7,-1,0
  4619.5    0.12       0  4876.9    0.07       0  4947.2    0.05       0
  4951.2    0.07       0  5014.4    0.12       0  5128.7   0.035       0
  5452.8    0.07       0
Bank Sta=4947.2,4951.2
Exp/Cntr=0.3,0.1

Type RM Length L Ch R = 1,3730,429,429,429
BEGIN DESCRIPTION:
Stream0125_DS 7.0
END DESCRIPTION:
XS GIS Cut Line= 3
      2029374.99     13921275.00      2029075.00     13921325.00
      2028974.97     13921425.03
#Sta/Elev= 30
  4703.7 1580.41  4706.2 1580.41  4731.6 1577.53  4736.6 1577.38  4774.7 1573.26
  4797.5 1571.74  4805.1 1570.41  4815.2 1569.83  4825.3 1568.51  4835.5 1568.67
  4853.2 1567.03  4898.6 1565.33  4919.1 1565.28  4947.0 1564.30  4957.1 1561.90
  4967.3 1561.36  4974.9 1560.06  4980.0 1560.21  4985.6 1557.62  4985.8 1557.12
  4989.3 1557.12  4989.6 1557.62  4997.7 1559.36  5005.3 1564.88  5036.1 1565.80
  5070.9 1565.66  5078.5 1565.75  5090.3 1566.91  5121.0 1570.51  5149.3 1571.97
#Mann=6,-1,0
  4703.7    0.12       0  4898.6    0.07       0  4985.6    0.05       0
  4989.6    0.07       0  5070.9    0.12       0  5090.3    0.07       0
Bank Sta=4985.6,4989.6
Exp/Cntr=0.3,0.1

Type RM Length L Ch R = 1,3301,469,469,469
BEGIN DESCRIPTION:
Stream0125_DS 6.0
END DESCRIPTION:
XS GIS Cut Line= 3
      2029225.01     13920875.00      2029075.00     13920925.00
      2028562.61     13921635.36
#Sta/Elev= 30
  4841.9 1588.51  4852.5 1587.42  4884.1 1579.88  4905.2 1571.20  4926.2 1561.52
  4951.2 1556.42  4957.9 1555.07  4989.5 1554.60  4995.4 1551.91  4995.6 1551.41
  4999.4 1551.91  5003.1 1551.91  5007.4 1553.28  5013.5 1553.99  5049.3 1556.39
  5078.6 1556.52  5182.0 1560.45  5265.0 1561.41  5308.3 1563.49  5315.4 1564.97
  5327.8 1565.03  5415.1 1568.20  5430.9 1569.45  5436.8 1569.07  5443.9 1570.28
  5472.4 1570.39  5487.1 1571.62  5573.0 1574.32  5726.0 1581.05  5875.9 1586.98
#Mann=9,-1,0
  4841.9    0.12       0  4951.2    0.07       0  4995.4    0.05       0
  4999.4    0.07       0  5182.0    0.12       0  5327.8    0.07       0
  5415.1    0.12       0  5430.9   0.035       0  5726.0    0.07       0
Bank Sta=4995.4,4999.4
Exp/Cntr=0.3,0.1

Type RM Length L Ch R = 1,2832,468,468,468
BEGIN DESCRIPTION:
Stream0125_DS 5.0
END DESCRIPTION:
XS GIS Cut Line= 3
      2029124.97     13920625.00      2028825.00     13920675.00
      2028189.70     13921209.73
#Sta/Elev= 30
  4691.0 1580.18  4723.9 1578.10  4751.2 1568.47  4784.7 1557.50  4792.4 1553.74
  4802.5 1551.37  4840.5 1548.85  4863.3 1549.27  4967.2 1546.57  5008.8 1544.29
  5028.9 1541.53  5029.1 1541.03  5032.9 1541.53  5037.4 1544.65  5051.7 1546.98
  5073.5 1547.90  5151.8 1547.37  5207.8 1548.49  5215.5 1546.45  5229.8 1549.04
  5257.2 1550.05  5328.7 1556.90  5392.4 1559.78  5421.0 1563.98  5427.6 1563.35
  5470.5 1565.90  5505.6 1569.36  5562.8 1571.16  5669.4 1579.42  5825.5 1586.83
#Mann=4,-1,0
  4691.0    0.12       0  4751.2    0.07       0  5028.9    0.05       0
  5032.9    0.07       0
Bank Sta=5028.9,5032.9
Exp/Cntr=0.3,0.1

Type RM Length L Ch R = 1,2364,484,484,484
BEGIN DESCRIPTION:
Stream0125_DS 4.0
END DESCRIPTION:
XS GIS Cut Line= 3
      2028725.02     13920274.99      2028425.00     13920475.00
      2028267.45     13920749.98
#Sta/Elev= 30
  4638.9 1553.67  4646.4 1552.35  4667.5 1551.86  4682.5 1549.52  4703.5 1548.15
  4718.5 1545.72  4739.6 1545.06  4862.8 1537.40  4912.1 1535.85  4963.4 1535.98
  4976.9 1534.93  4992.0 1535.62  4996.5 1533.96  5002.4 1533.96  5005.4 1529.88
  5005.6 1529.38  5009.4 1529.88  5013.2 1534.77  5029.0 1537.02  5034.7 1539.56
  5057.1 1544.15  5066.4 1545.24  5072.1 1547.05  5125.4 1550.47  5137.8 1552.72
  5183.9 1556.70  5195.9 1558.68  5241.5 1561.70  5270.7 1565.61  5316.4 1569.25
#Mann=4,-1,0
  4638.9    0.12       0  4912.1    0.07       0  5005.4    0.05       0
  5009.4    0.07       0
Bank Sta=5005.4,5009.4
Exp/Cntr=0.3,0.1

Type RM Length L Ch R = 1,1880,447,447,447
BEGIN DESCRIPTION:
Stream0125_DS 3.0
END DESCRIPTION:
XS GIS Cut Line= 3
      2028575.03     13920125.02      2028425.00     13920025.00
      2027889.93     13920172.69
#Sta/Elev= 30
  4819.8 1543.84  4884.4 1538.98  4935.5 1529.63  4950.5 1528.49  4977.6 1528.08
  4986.6 1526.82  4992.6 1527.29  4995.1 1526.16  4995.4 1525.66  4999.1 1526.16
  5002.7 1526.16  5010.5 1528.30  5017.3 1527.72  5056.8 1529.16  5083.1 1528.79
  5124.6 1529.92  5130.7 1531.50  5135.9 1531.40  5143.2 1533.39  5170.3 1539.19
  5176.5 1541.23  5204.6 1544.02  5290.6 1546.23  5318.0 1545.02  5391.9 1550.00
  5436.7 1551.78  5465.8 1554.23  5471.0 1553.81  5510.6 1555.73  5555.2 1558.75
#Mann=4,-1,0
  4819.8    0.12       0  4995.1    0.05       0  4999.1    0.12       0
  5143.2    0.07       0
Bank Sta=4995.1,4999.1
Exp/Cntr=0.3,0.1

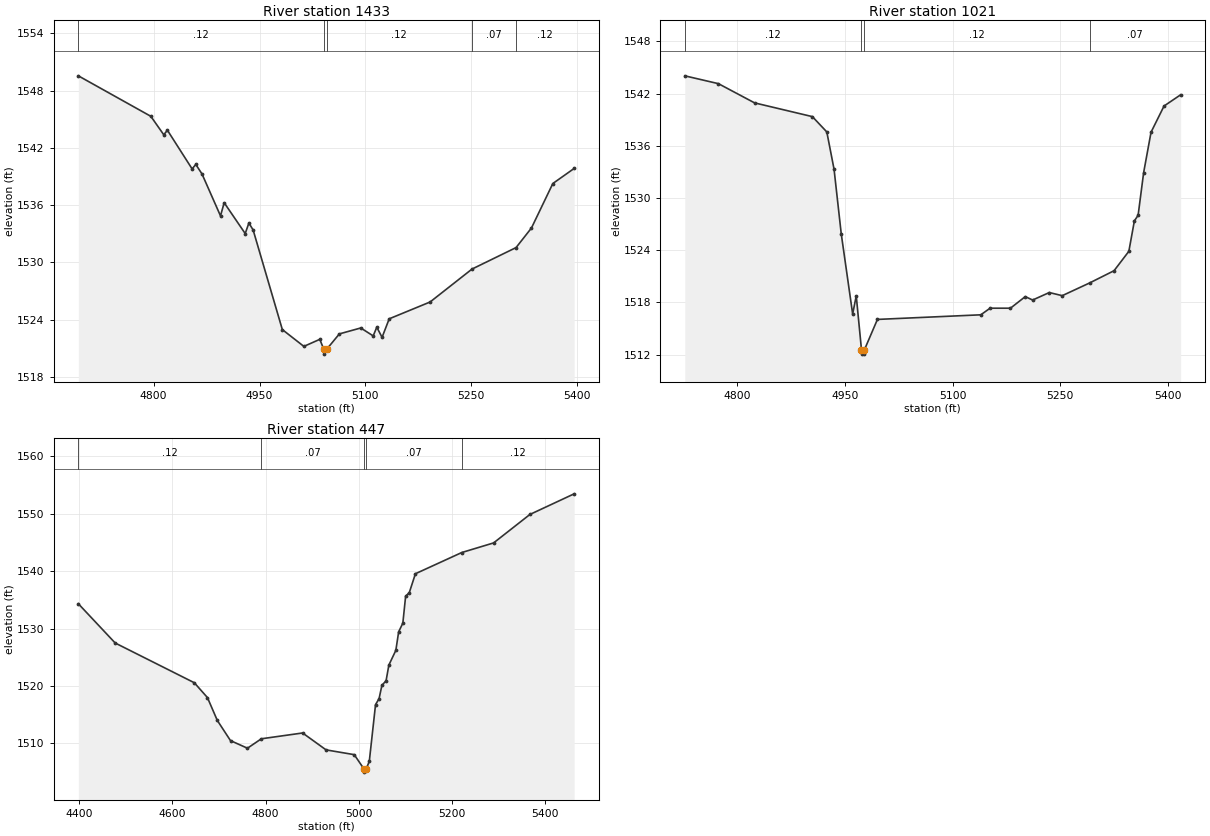
Type RM Length L Ch R = 1,1433,412,412,412
BEGIN DESCRIPTION:
Stream0125_DS 2.0
END DESCRIPTION:
XS GIS Cut Line= 3
      2028814.30     13919751.70      2028525.00     13919675.00
      2028125.01     13919725.00
#Sta/Elev= 30
  4693.3 1549.54  4796.0 1545.30  4814.3 1543.37  4819.5 1543.84  4854.5 1539.79
  4859.7 1540.26  4868.5 1539.26  4894.7 1534.87  4899.9 1536.25  4929.7 1533.02
  4934.9 1534.12  4940.9 1533.40  4982.3 1522.96  5012.8 1521.20  5035.4 1521.94
  5041.0 1520.89  5041.2 1520.39  5045.0 1520.89  5063.1 1522.51  5093.4 1523.13
  5111.0 1522.30  5116.1 1523.21  5123.6 1522.15  5133.7 1524.09  5191.6 1525.85
  5251.0 1529.30  5313.4 1531.55  5335.2 1533.60  5365.5 1538.26  5395.7 1539.84
#Mann=5,-1,0
  4693.3    0.12       0  5041.0    0.05       0  5045.0    0.12       0
  5251.0    0.07       0  5313.4    0.12       0
Bank Sta=5041,5045
Exp/Cntr=0.3,0.1

Type RM Length L Ch R = 1,1021,574,574,574
BEGIN DESCRIPTION:
Stream0125_DS 1.0
END DESCRIPTION:
XS GIS Cut Line= 3
      2028701.52     13919356.75      2028425.00     13919325.00
      2028025.05     13919424.99
#Sta/Elev= 30
  4727.0 1544.05  4773.8 1543.15  4824.2 1540.94  4904.7 1539.36  4924.8 1537.60
  4934.9 1533.31  4944.9 1525.89  4960.8 1516.67  4965.8 1518.76  4973.1 1512.56
  4973.4 1512.06  4976.9 1512.06  4977.2 1512.56  4995.3 1516.05  5139.3 1516.58
  5152.2 1517.34  5180.6 1517.34  5201.2 1518.67  5211.5 1518.28  5234.7 1519.14
  5252.7 1518.78  5290.8 1520.24  5324.9 1521.65  5345.5 1523.88  5353.2 1527.38
  5358.4 1528.02  5366.1 1532.93  5376.4 1537.57  5394.5 1540.58  5417.6 1541.87
#Mann=4,-1,0
  4727.0    0.12       0  4973.1    0.05       0  4977.2    0.12       0
  5290.8    0.07       0
Bank Sta=4973.1,4977.2
Exp/Cntr=0.3,0.1

Type RM Length L Ch R = 1,447,0,0,0
BEGIN DESCRIPTION:
Stream0125_DS 0.0
END DESCRIPTION:
XS GIS Cut Line= 4
      2028578.83     13919163.06      2028325.12     13918907.02
      2028085.32     13918935.17      2027826.51     13919318.24
#Sta/Elev= 30
  4398.1 1534.31  4477.2 1527.48  4647.0 1520.57  4675.2 1517.99  4696.4 1514.01
  4724.7 1510.50  4761.1 1509.18  4790.9 1510.82  4879.5 1511.83  4929.8 1508.89
  4990.3 1508.06  5011.6 1505.52  5011.9 1505.02  5015.7 1505.52  5022.6 1506.89
  5036.0 1516.76  5043.6 1517.81  5049.7 1520.12  5058.6 1520.91  5064.6 1523.64
  5079.6 1526.21  5085.6 1529.42  5094.6 1530.94  5100.6 1535.63  5108.4 1536.23
  5121.6 1539.53  5221.1 1543.22  5289.4 1544.89  5367.3 1549.84  5462.3 1553.43
#Mann=5,-1,0
  4398.1    0.12       0  4790.9    0.07       0  5011.6    0.05       0
  5015.7    0.07       0  5221.1    0.12       0
Bank Sta=5011.6,5015.7
Exp/Cntr=0.3,0.1

Chan Stop Cuts=-1