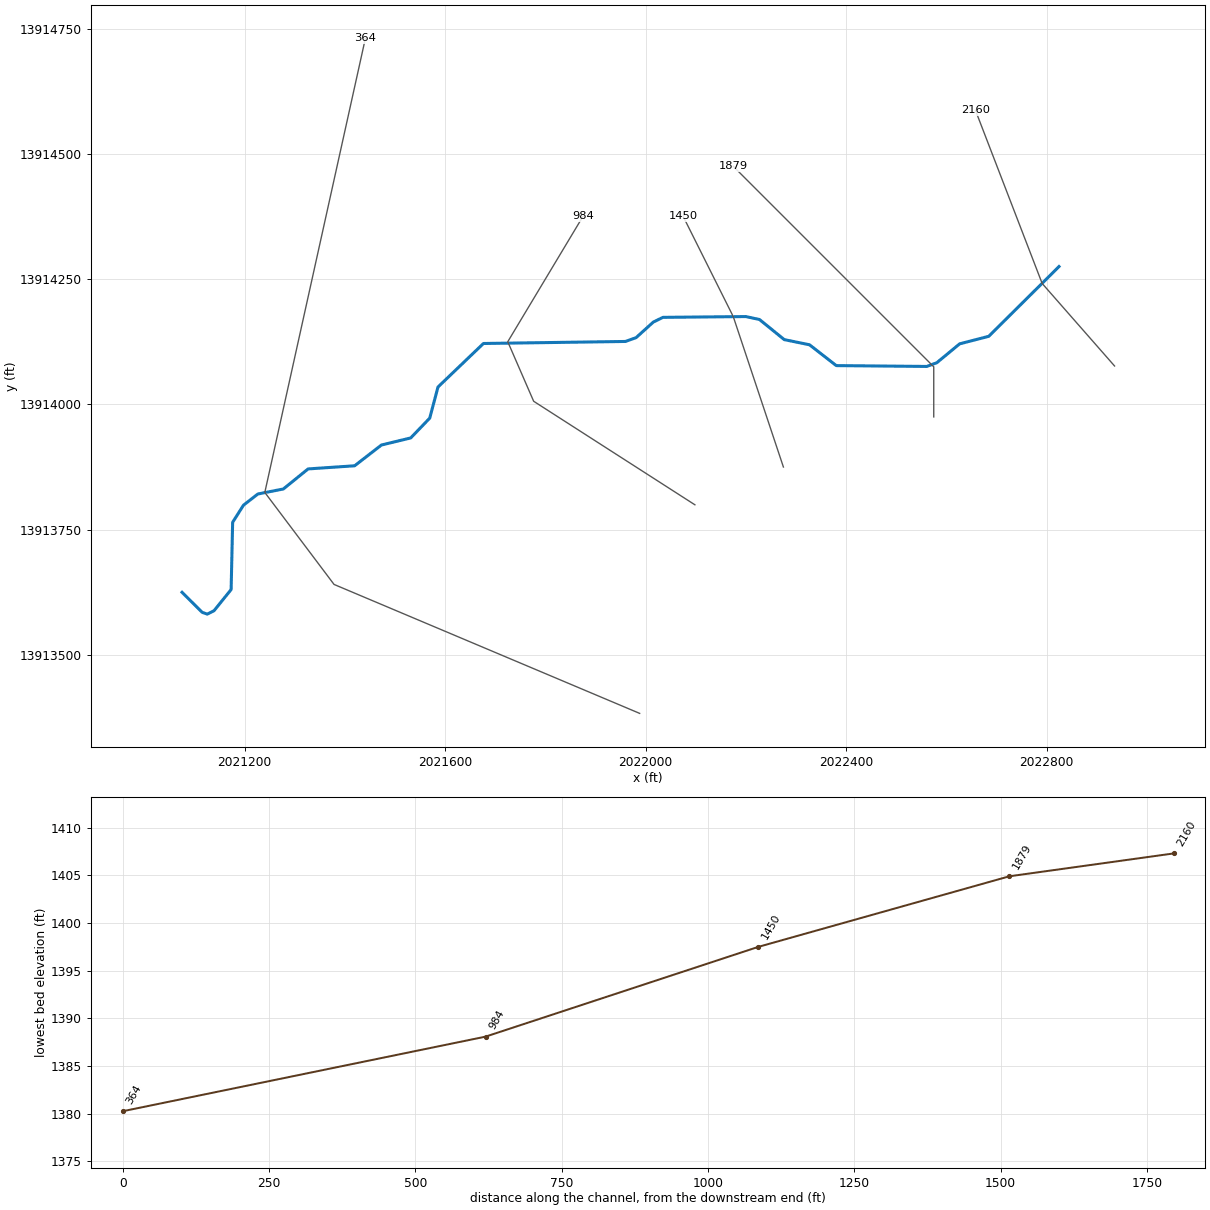
--- Stream0126_DS.prj (project) ---

Proj Title=Stream0126_DS Base Level Engineering
Current Plan=p01
Default Exp/Contr=0.3,0.1
English Units
Geom File=g01
Flow File=f01
Plan File=p01
BEGIN DESCRIPTION:
Stream0126_DS
END DESCRIPTION:

--- Stream0126_DS.p01 (plan) ---

Plan Title=Multiple Run
Short Identifier=Multiple
Geom File=g01
Flow File=f01
Subcritical Flow
K Sum by GR= 0
Std Step Tol= 0.01
Critical Tol= 0.01
Num of Std Step Trials= 20
Max Error Tol= 0.3
Flow Tol Ratio= 0.001
Split Flow NTrial= 30
Split Flow Tol= 0.02
Split Flow Ratio= 0.02
Log Output Level= 0
Friction Slope Method= 1
Unsteady Friction Slope Method= 2
Unsteady Bridges Friction Slope Method= 1
Parabolic Critical Depth
Global Vel Dist=  1 , 1 , 1
Global Log Level= 0
CheckData=True
Encroach Param= -1, 0, 0, 0
BEGIN DESCRIPTION:
Multiple Run
END DESCRIPTION:

--- Stream0126_DS.f01 (steady flow) ---

Flow Title=Multiple
Number of Profiles=7
Profile Names=10-year,25-year,50-year,1pct_min,100-year,1pct_plu,500-year
River Rch & RM= Stream0126_DS,Reach-1,2160
    1284    2242    3182    2192    4373    8726    8192
Boundary for River Rch & Prof#=Stream0126_DS,Reach-1,1
Up Type=0
Dn Type=3
Dn Slope=0.005
Boundary for River Rch & Prof#=Stream0126_DS,Reach-1,2
Up Type=0
Dn Type=3
Dn Slope=0.005
Boundary for River Rch & Prof#=Stream0126_DS,Reach-1,3
Up Type=0
Dn Type=3
Dn Slope=0.005
Boundary for River Rch & Prof#=Stream0126_DS,Reach-1,4
Up Type=0
Dn Type=3
Dn Slope=0.005
Boundary for River Rch & Prof#=Stream0126_DS,Reach-1,5
Up Type=0
Dn Type=3
Dn Slope=0.005
Boundary for River Rch & Prof#=Stream0126_DS,Reach-1,6
Up Type=0
Dn Type=3
Dn Slope=0.005
Boundary for River Rch & Prof#=Stream0126_DS,Reach-1,7
Up Type=0
Dn Type=3
Dn Slope=0.005

--- Stream0126_DS.g01 (geometry) ---

Geom Title=Existing Conditions

River Reach=Stream0126_DS,Reach-1
Reach XY= 30
      2022825.00     13914275.00      2022684.69     13914135.76
      2022626.75     13914120.78      2022581.08     13914083.09
      2022561.09     13914075.67      2022380.52     13914077.35
      2022327.18     13914118.88      2022276.74     13914129.19
      2022227.35     13914169.29      2022200.09     13914175.21
      2022034.66     13914173.62      2022015.35     13914164.15
      2021981.06     13914133.14      2021959.78     13914125.52
      2021676.45     13914121.47      2021585.78     13914034.69
      2021569.25     13913972.46      2021531.34     13913933.02
      2021472.85     13913918.85      2021419.44     13913877.44
      2021326.58     13913871.18      2021277.15     13913831.15
      2021226.39     13913821.16      2021197.70     13913798.91
      2021176.00     13913764.71      2021172.97     13913630.50
      2021138.86     13913588.22      2021125.33     13913581.44
      2021115.21     13913585.01      2021075.00     13913625.00

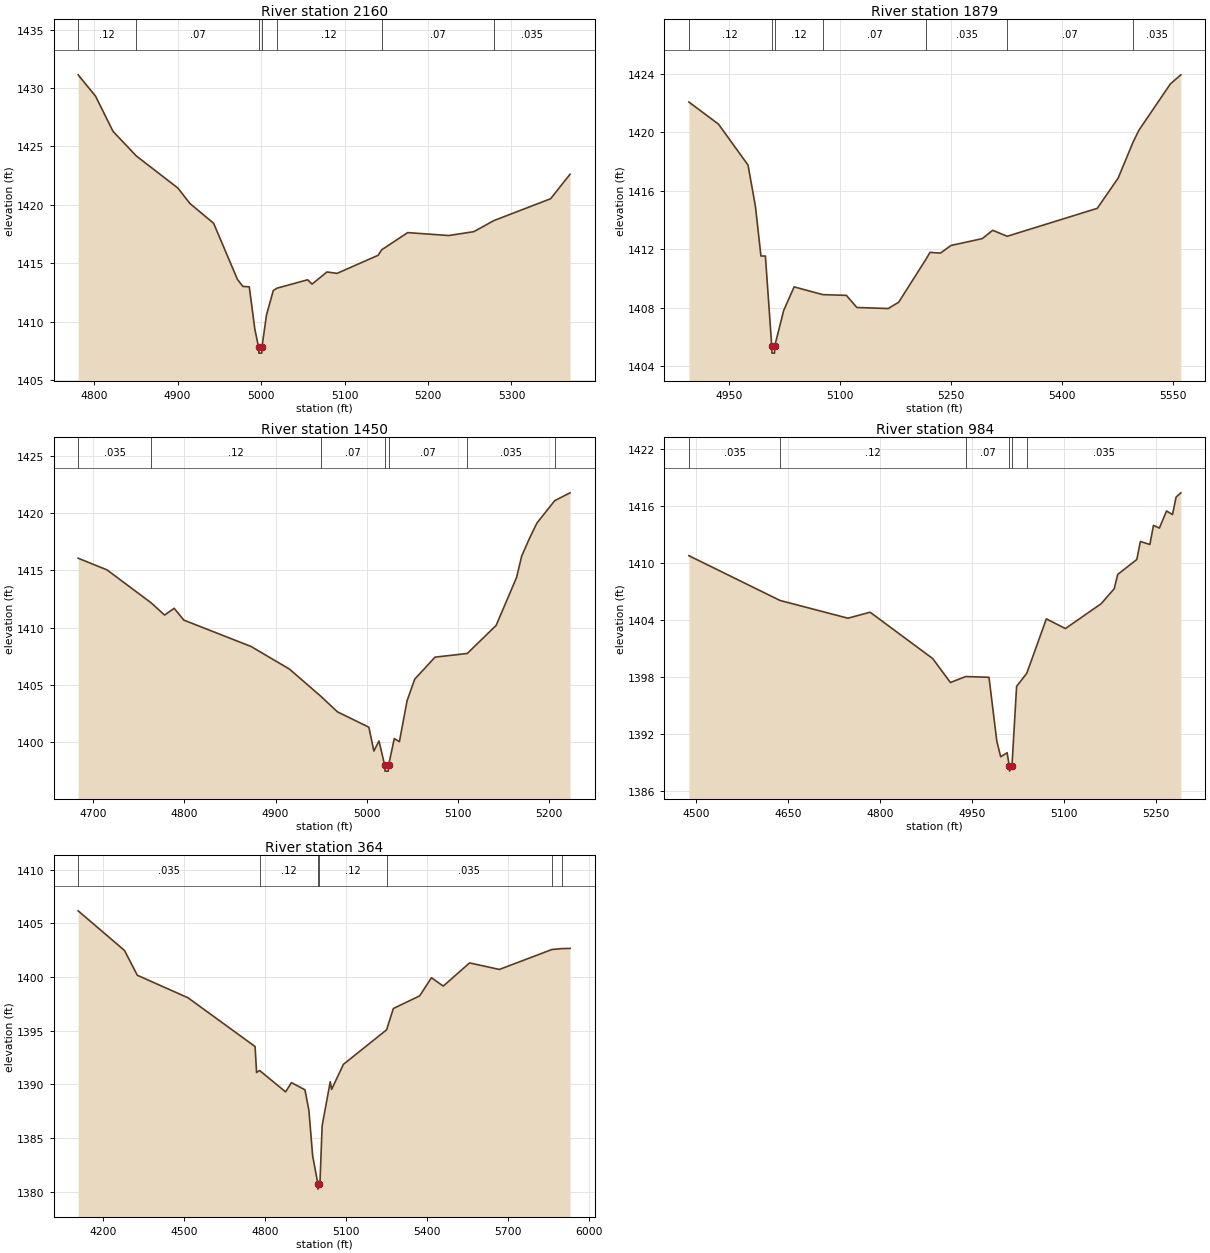
Type RM Length L Ch R = 1,2160,281,281,281
BEGIN DESCRIPTION:
Stream0126_DS 4.0
END DESCRIPTION:
XS GIS Cut Line= 3
      2022935.80     13914076.57      2022791.32     13914241.28
      2022658.24     13914586.74
#Sta/Elev= 30
  4780.9 1431.13  4801.8 1429.30  4822.7 1426.29  4850.5 1424.19  4900.5 1421.43
  4914.7 1420.12  4943.2 1418.42  4971.7 1413.62  4978.3 1413.01  4985.9 1412.98
  4992.6 1409.35  4997.1 1407.80  4997.4 1407.30  5000.9 1407.30  5001.1 1407.80
  5006.5 1410.55  5014.7 1412.66  5019.1 1412.86  5055.8 1413.58  5061.1 1413.21
  5079.0 1414.25  5091.1 1414.13  5140.3 1415.68  5144.6 1416.15  5175.7 1417.62
  5224.9 1417.37  5254.9 1417.70  5279.0 1418.65  5346.9 1420.52  5370.2 1422.62
#Mann=7,-1,0
  4780.9    0.12       0  4850.5    0.07       0  4997.1    0.05       0
  5001.1    0.07       0  5019.1    0.12       0  5144.6    0.07       0
  5279.0   0.035       0
Bank Sta=4997.1,5001.1
Exp/Cntr=0.3,0.1

Type RM Length L Ch R = 1,1879,429,429,429
BEGIN DESCRIPTION:
Stream0126_DS 3.0
END DESCRIPTION:
XS GIS Cut Line= 3
      2022575.00     13913974.99      2022575.00     13914075.00
      2022175.00     13914475.00
#Sta/Elev= 30
  4895.5 1422.07  4935.5 1420.56  4975.5 1417.76  4985.5 1414.95  4993.0 1411.54
  4999.0 1411.54  5007.6 1405.40  5007.9 1404.90  5011.4 1404.90  5011.7 1405.40
  5023.8 1407.82  5037.9 1409.43  5076.6 1408.90  5108.6 1408.85  5122.8 1408.02
  5165.2 1407.95  5179.4 1408.38  5216.8 1411.36  5221.8 1411.79  5235.9 1411.74
  5250.1 1412.26  5292.5 1412.73  5306.6 1413.30  5326.2 1412.89  5448.1 1414.80
  5476.3 1416.86  5496.8 1419.35  5504.6 1420.15  5547.1 1423.31  5561.2 1423.93
#Mann=7,-1,0
  4895.5    0.12       0  5007.6    0.05       0  5011.7    0.12       0
  5076.6    0.07       0  5216.8   0.035       0  5326.2    0.07       0
  5496.8   0.035       0
Bank Sta=5007.6,5011.7
Exp/Cntr=0.3,0.1

Type RM Length L Ch R = 1,1450,466,466,466
BEGIN DESCRIPTION:
Stream0126_DS 2.0
END DESCRIPTION:
XS GIS Cut Line= 3
      2022275.01     13913874.97      2022175.00     13914175.00
      2022074.99     13914375.03
#Sta/Elev= 30
  4683.3 1416.06  4715.0 1415.04  4763.4 1412.17  4778.2 1411.10  4788.7 1411.69
  4799.3 1410.66  4873.1 1408.36  4915.2 1406.39  4949.5 1404.03  4967.9 1402.66
  5002.4 1401.32  5007.9 1399.24  5013.5 1400.12  5019.8 1397.99  5020.1 1397.49
  5023.7 1397.49  5024.0 1397.99  5030.3 1400.33  5035.9 1400.06  5044.3 1403.62
  5052.7 1405.51  5075.0 1407.43  5110.4 1407.75  5142.1 1410.20  5164.5 1414.38
  5170.1 1416.24  5178.4 1417.74  5186.8 1419.12  5206.4 1421.08  5223.2 1421.76
#Mann=7,-1,0
  4683.3   0.035       0  4763.4    0.12       0  4949.5    0.07       0
  5019.8    0.05       0  5024.0    0.07       0  5110.4   0.035       0
  5206.4    0.07       0
Bank Sta=5019.8,5024
Exp/Cntr=0.3,0.1

Type RM Length L Ch R = 1,984,620,620,620
BEGIN DESCRIPTION:
Stream0126_DS 1.0
END DESCRIPTION:
XS GIS Cut Line= 4
      2022098.38     13913799.61      2021776.65     13914006.21
      2021725.00     13914125.00      2021874.98     13914374.97
#Sta/Elev= 30
  4487.6 1410.75  4636.4 1406.04  4747.3 1404.17  4783.6 1404.80  4885.8 1399.92
  4914.7 1397.40  4939.7 1398.03  4977.7 1397.95  4990.5 1391.22  4996.8 1389.58
  5007.3 1390.01  5011.0 1388.57  5011.3 1388.07  5015.2 1388.57  5022.8 1396.99
  5039.5 1398.38  5071.4 1404.10  5102.5 1403.08  5160.8 1405.69  5182.2 1407.27
  5188.0 1408.78  5219.1 1410.35  5225.0 1412.25  5240.5 1411.93  5246.3 1413.94
  5256.0 1413.66  5267.7 1415.46  5277.4 1415.08  5283.3 1416.92  5291.0 1417.37
#Mann=6,-1,0
  4487.6   0.035       0  4636.4    0.12       0  4939.7    0.07       0
  5011.0    0.05       0  5015.2    0.07       0  5039.5   0.035       0
Bank Sta=5011,5015.2
Exp/Cntr=0.3,0.1

Type RM Length L Ch R = 1,364,0,0,0
BEGIN DESCRIPTION:
Stream0126_DS 0.0
END DESCRIPTION:
XS GIS Cut Line= 4
      2021988.15     13913383.39      2021378.36     13913640.68
      2021240.19     13913824.25      2021440.90     13914730.39
#Sta/Elev= 30
  4108.4 1406.16  4279.9 1402.47  4327.3 1400.16  4515.0 1398.06  4763.0 1393.52
  4768.5 1391.10  4779.7 1391.29  4875.8 1389.30  4897.6 1390.16  4947.5 1389.49
  4962.1 1387.56  4975.9 1383.35  4995.2 1380.74  4995.5 1380.24  4999.5 1380.74
  5002.9 1380.74  5011.0 1386.14  5041.0 1390.24  5046.1 1389.53  5089.7 1391.86
  5249.5 1395.08  5274.4 1397.06  5371.8 1398.24  5415.4 1399.93  5459.0 1399.15
  5556.5 1401.31  5666.5 1400.70  5861.2 1402.56  5897.6 1402.64  5928.1 1402.66
#Mann=7,-1,0
  4108.4   0.035       0  4779.7    0.12       0  4995.2    0.05       0
  4999.5    0.12       0  5249.5   0.035       0  5861.2    0.07       0
  5897.6   0.035       0
Bank Sta=4995.2,4999.5
Exp/Cntr=0.3,0.1

Chan Stop Cuts=-1