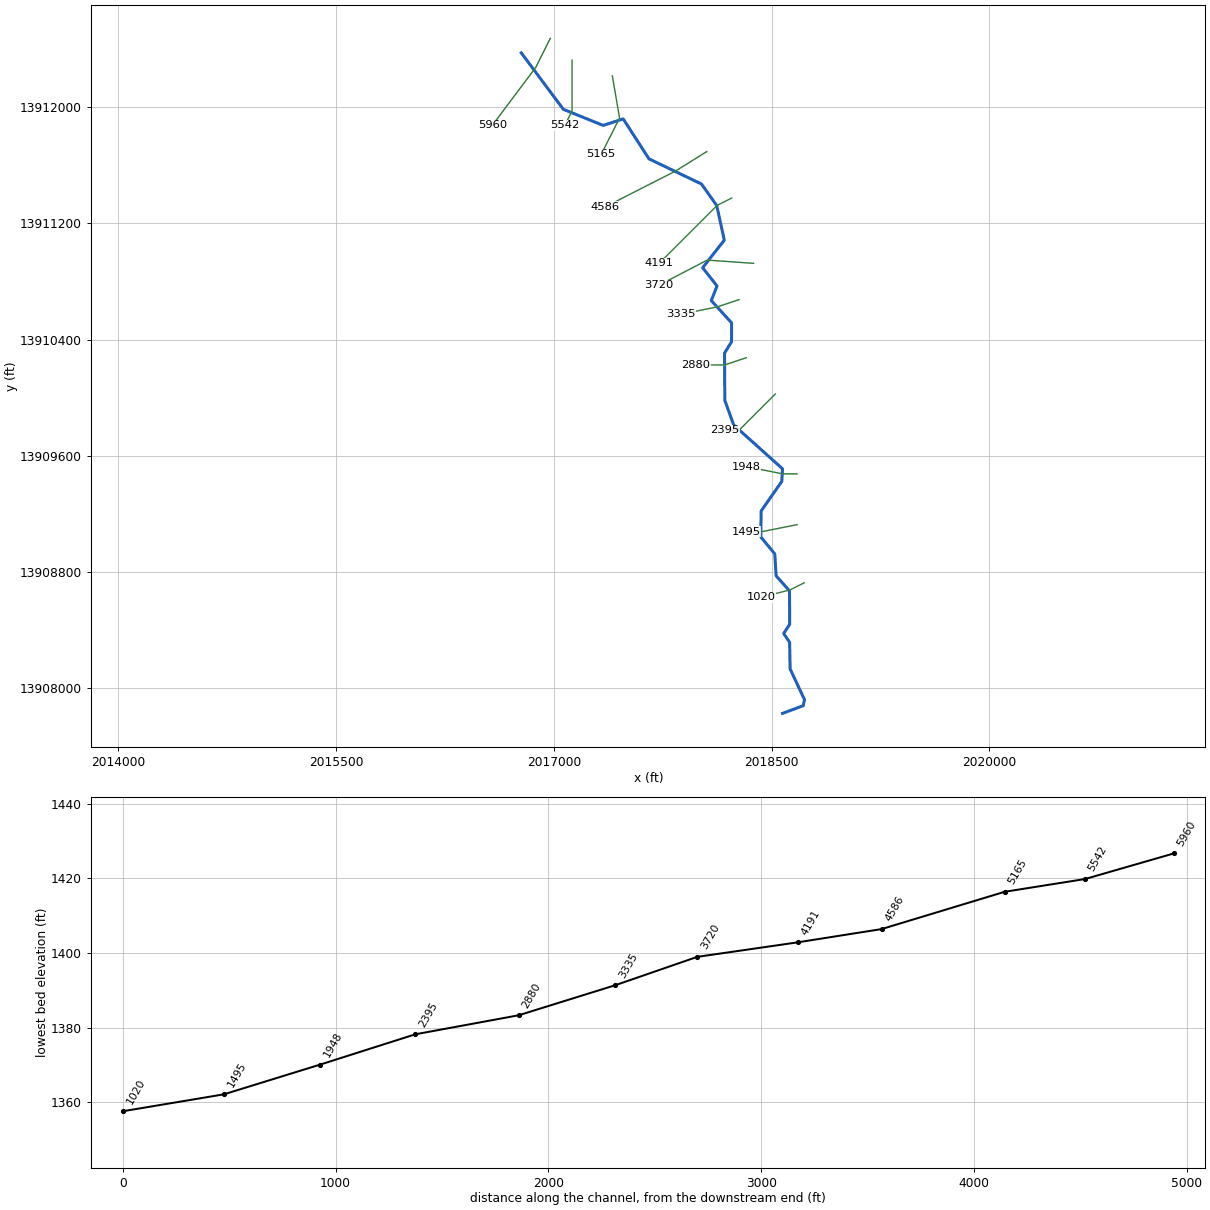
--- Stream0127_DS.prj (project) ---

Proj Title=Stream0127_DS Base Level Engineering
Current Plan=p01
Default Exp/Contr=0.3,0.1
English Units
Geom File=g01
Flow File=f01
Plan File=p01
BEGIN DESCRIPTION:
Stream0127_DS
END DESCRIPTION:

--- Stream0127_DS.p01 (plan) ---

Plan Title=Multiple Run
Short Identifier=Multiple
Geom File=g01
Flow File=f01
Subcritical Flow
K Sum by GR= 0
Std Step Tol= 0.01
Critical Tol= 0.01
Num of Std Step Trials= 20
Max Error Tol= 0.3
Flow Tol Ratio= 0.001
Split Flow NTrial= 30
Split Flow Tol= 0.02
Split Flow Ratio= 0.02
Log Output Level= 0
Friction Slope Method= 1
Unsteady Friction Slope Method= 2
Unsteady Bridges Friction Slope Method= 1
Parabolic Critical Depth
Global Vel Dist=  1 , 1 , 1
Global Log Level= 0
CheckData=True
Encroach Param= -1, 0, 0, 0
BEGIN DESCRIPTION:
Multiple Run
END DESCRIPTION:

--- Stream0127_DS.f01 (steady flow) ---

Flow Title=Multiple
Number of Profiles=7
Profile Names=10-year,25-year,50-year,1pct_min,100-year,1pct_plu,500-year
River Rch & RM= Stream0127_DS,Reach-1,5960
    1752    3092    4417    3056    6098   12166   11505
Boundary for River Rch & Prof#=Stream0127_DS,Reach-1,1
Up Type=0
Dn Type=3
Dn Slope=0.005
Boundary for River Rch & Prof#=Stream0127_DS,Reach-1,2
Up Type=0
Dn Type=3
Dn Slope=0.005
Boundary for River Rch & Prof#=Stream0127_DS,Reach-1,3
Up Type=0
Dn Type=3
Dn Slope=0.005
Boundary for River Rch & Prof#=Stream0127_DS,Reach-1,4
Up Type=0
Dn Type=3
Dn Slope=0.005
Boundary for River Rch & Prof#=Stream0127_DS,Reach-1,5
Up Type=0
Dn Type=3
Dn Slope=0.005
Boundary for River Rch & Prof#=Stream0127_DS,Reach-1,6
Up Type=0
Dn Type=3
Dn Slope=0.005
Boundary for River Rch & Prof#=Stream0127_DS,Reach-1,7
Up Type=0
Dn Type=3
Dn Slope=0.005

--- Stream0127_DS.g01 (geometry) ---

Geom Title=Existing Conditions

River Reach=Stream0127_DS,Reach-1
Reach XY= 30
      2016775.00     13912375.00      2017065.29     13911985.75
      2017339.10     13911875.25      2017477.31     13911919.91
      2017654.87     13911644.77      2018016.52     13911471.49
      2018121.38     13911323.50      2018173.76     13911084.68
      2018024.51     13910895.23      2018123.33     13910768.95
      2018084.15     13910668.27      2018223.81     13910515.41
      2018223.63     13910384.67      2018175.21     13910306.73
      2018177.26     13909980.94      2018238.39     13909811.67
      2018574.76     13909509.78      2018569.59     13909422.58
      2018427.24     13909219.07      2018425.39     13909040.16
      2018521.44     13908923.53      2018530.48     13908772.56
      2018622.93     13908669.14      2018624.17     13908438.86
      2018582.56     13908375.00      2018623.62     13908314.56
      2018627.24     13908130.93      2018726.04     13907919.95
      2018717.45     13907878.14      2018575.00     13907825.00

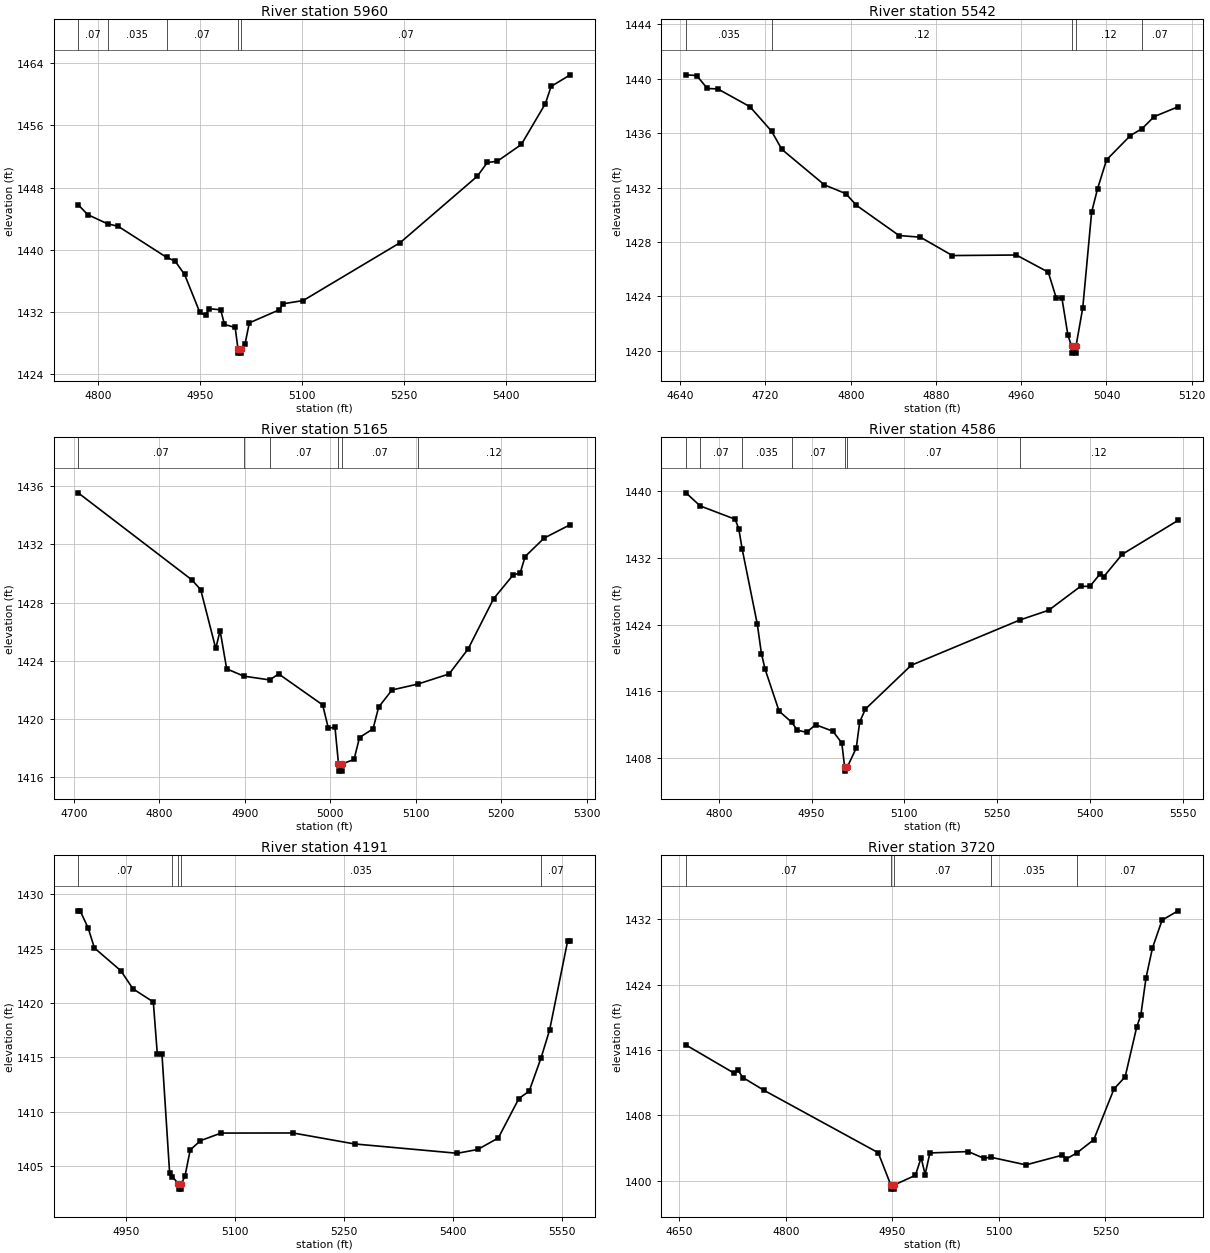
Type RM Length L Ch R = 1,5960,418,418,418
BEGIN DESCRIPTION:
Stream0127_DS 12.0
END DESCRIPTION:
XS GIS Cut Line= 3
      2016975.00     13912475.00      2016875.00     13912275.00
      2016575.00     13911875.01
#Sta/Elev= 30
  4771.2 1445.79  4785.2 1444.51  4814.7 1443.32  4829.9 1443.02  4901.2 1439.02
  4913.7 1438.54  4927.7 1436.82  4950.1 1431.94  4958.5 1431.56  4964.1 1432.41
  4980.8 1432.27  4986.4 1430.39  5002.1 1430.00  5006.3 1427.20  5006.5 1426.70
  5010.1 1426.70  5010.4 1427.20  5016.7 1427.92  5022.9 1430.59  5066.7 1432.26
  5072.9 1433.05  5102.1 1433.46  5244.8 1440.91  5358.3 1449.46  5372.9 1451.22
  5387.5 1451.37  5422.9 1453.53  5458.3 1458.79  5466.7 1461.00  5494.8 1462.49
#Mann=5,-1,0
  4771.2    0.07       0  4814.7   0.035       0  4901.2    0.07       0
  5006.3    0.05       0  5010.4    0.07       0
Bank Sta=5006.3,5010.4
Exp/Cntr=0.3,0.1

Type RM Length L Ch R = 1,5542,377,377,377
BEGIN DESCRIPTION:
Stream0127_DS 11.0
END DESCRIPTION:
XS GIS Cut Line= 3
      2017125.00     13912325.00      2017125.00     13911975.00
      2017075.00     13911875.00
#Sta/Elev= 30
  4645.4 1440.28  4655.4 1440.23  4665.4 1439.28  4675.4 1439.24  4705.4 1437.94
  4725.7 1436.14  4735.4 1434.80  4775.4 1432.19  4795.4 1431.55  4805.4 1430.69
  4845.4 1428.47  4865.4 1428.35  4895.4 1427.00  4955.4 1427.04  4985.4 1425.78
  4992.9 1423.88  4998.2 1423.88  5003.8 1421.17  5007.3 1420.33  5007.6 1419.83
  5011.2 1419.83  5011.4 1420.33  5017.8 1423.17  5026.1 1430.19  5031.7 1431.92
  5040.1 1434.03  5062.5 1435.82  5073.5 1436.33  5084.8 1437.21  5107.2 1437.93
#Mann=5,-1,0
  4645.4   0.035       0  4725.7    0.12       0  5007.3    0.05       0
  5011.4    0.12       0  5073.5    0.07       0
Bank Sta=5007.3,5011.4
Exp/Cntr=0.3,0.1

Type RM Length L Ch R = 1,5165,579,579,579
BEGIN DESCRIPTION:
Stream0127_DS 10.0
END DESCRIPTION:
XS GIS Cut Line= 3
      2017402.38     13912216.43      2017452.24     13911925.47
      2017325.02     13911675.04
#Sta/Elev= 30
  4704.8 1435.55  4838.1 1429.56  4848.3 1428.89  4865.9 1424.85  4871.0 1426.08
  4878.7 1423.45  4898.7 1422.95  4929.0 1422.69  4939.6 1423.10  4991.1 1420.97
  4997.7 1419.37  5005.5 1419.44  5009.6 1416.92  5009.9 1416.42  5013.6 1416.42
  5013.9 1416.92  5027.8 1417.22  5034.2 1418.73  5050.1 1419.33  5056.6 1420.82
  5072.3 1422.00  5102.3 1422.40  5139.1 1423.10  5161.3 1424.81  5191.2 1428.27
  5213.6 1429.87  5222.5 1430.07  5228.1 1431.17  5250.4 1432.44  5280.9 1433.36
#Mann=6,-1,0
  4704.8    0.07       0  4898.7    0.12       0  4929.0    0.07       0
  5009.6    0.05       0  5013.9    0.07       0  5102.3    0.12       0
Bank Sta=5009.6,5013.9
Exp/Cntr=0.3,0.1

Type RM Length L Ch R = 1,4586,395,395,395
BEGIN DESCRIPTION:
Stream0127_DS 9.0
END DESCRIPTION:
XS GIS Cut Line= 3
      2018052.83     13911694.96      2017838.07     13911561.03
      2017354.53     13911314.63
#Sta/Elev= 30
  4746.9 1439.83  4769.8 1438.26  4826.4 1436.66  4832.3 1435.51  4837.8 1433.07
  4862.2 1424.09  4868.9 1420.54  4874.8 1418.67  4897.5 1413.62  4918.2 1412.27
  4926.7 1411.34  4942.0 1411.08  4956.5 1411.99  4984.5 1411.21  4998.9 1409.80
  5003.5 1406.92  5003.8 1406.42  5007.9 1406.92  5022.3 1409.20  5027.9 1412.34
  5037.1 1413.87  5111.2 1419.13  5287.1 1424.57  5333.6 1425.74  5385.0 1428.60
  5400.3 1428.61  5416.9 1430.13  5422.5 1429.76  5452.4 1432.45  5542.7 1436.52
#Mann=7,-1,0
  4746.9   0.035       0  4769.8    0.07       0  4837.8   0.035       0
  4918.2    0.07       0  5003.5    0.05       0  5007.9    0.07       0
  5287.1    0.12       0
Bank Sta=5003.5,5007.9
Exp/Cntr=0.3,0.1

Type RM Length L Ch R = 1,4191,471,471,471
BEGIN DESCRIPTION:
Stream0127_DS 8.0
END DESCRIPTION:
XS GIS Cut Line= 3
      2018225.03     13911375.02      2018125.00     13911325.00
      2017725.02     13910925.02
#Sta/Elev= 30
  4883.8 1428.48  4886.6 1428.48  4897.8 1426.86  4906.2 1425.06  4942.5 1422.97
  4959.3 1421.30  4987.3 1420.09  4992.8 1415.30  4999.2 1415.30  5009.8 1404.30
  5013.4 1404.02  5021.7 1403.36  5022.0 1402.86  5025.8 1402.86  5026.1 1403.36
  5031.0 1404.09  5038.1 1406.47  5052.2 1407.32  5080.5 1408.02  5179.5 1408.03
  5264.3 1407.02  5405.8 1406.16  5434.0 1406.51  5462.3 1407.57  5490.6 1411.20
  5504.8 1411.88  5521.3 1414.97  5533.0 1417.53  5557.8 1425.72  5561.3 1425.72
#Mann=5,-1,0
  4883.8    0.07       0  5013.4   0.035       0  5021.7    0.05       0
  5026.1   0.035       0  5521.3    0.07       0
Bank Sta=5021.7,5026.1
Exp/Cntr=0.3,0.1

Type RM Length L Ch R = 1,3720,385,385,385
BEGIN DESCRIPTION:
Stream0127_DS 7.0
END DESCRIPTION:
XS GIS Cut Line= 3
      2018374.99     13910925.00      2018056.05     13910947.45
      2017725.00     13910775.00
#Sta/Elev= 30
  4659.2 1416.63  4727.4 1413.16  4732.4 1413.54  4739.4 1412.64  4769.5 1411.06
  4929.9 1403.44  4947.7 1399.48  4948.0 1398.98  4951.9 1398.98  4952.2 1399.48
  4982.3 1400.67  4990.4 1402.82  4996.0 1400.77  5002.7 1403.41  5056.7 1403.58
  5078.8 1402.75  5088.3 1402.89  5138.0 1401.95  5189.3 1403.14  5194.9 1402.68
  5209.5 1403.40  5233.5 1405.03  5262.0 1411.25  5277.7 1412.73  5294.1 1418.87
  5299.8 1420.30  5307.1 1424.86  5316.2 1428.52  5329.7 1431.92  5352.2 1433.06
#Mann=5,-1,0
  4659.2    0.07       0  4947.7    0.05       0  4952.2    0.07       0
  5088.3   0.035       0  5209.5    0.07       0
Bank Sta=4947.7,4952.2
Exp/Cntr=0.3,0.1

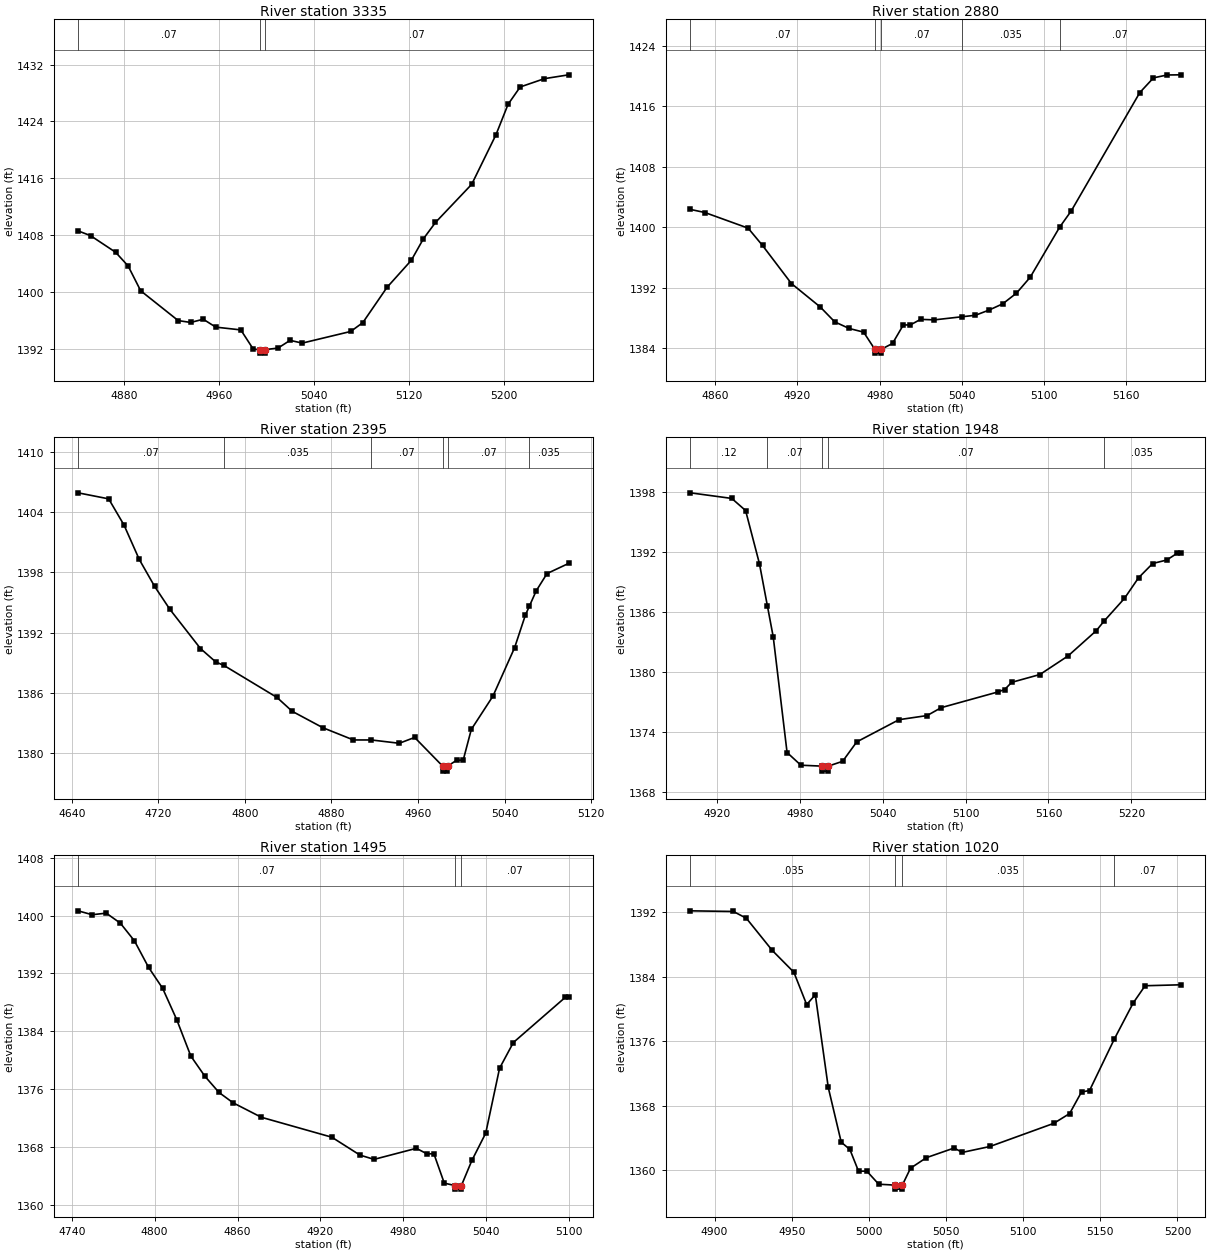
Type RM Length L Ch R = 1,3335,455,455,455
BEGIN DESCRIPTION:
Stream0127_DS 6.0
END DESCRIPTION:
XS GIS Cut Line= 3
      2018274.97     13910674.99      2018125.00     13910625.00
      2017875.03     13910575.01
#Sta/Elev= 30
  4841.5 1408.60  4852.0 1407.93  4873.1 1405.59  4883.6 1403.67  4894.2 1400.17
  4925.8 1395.97  4936.3 1395.71  4946.9 1396.16  4957.4 1395.05  4978.5 1394.66
  4989.0 1391.95  4994.6 1391.89  4995.0 1391.39  4998.9 1391.39  4999.2 1391.89
  5009.8 1392.10  5020.0 1393.19  5030.2 1392.80  5071.0 1394.44  5081.2 1395.68
  5101.6 1400.65  5122.0 1404.45  5132.2 1407.48  5142.4 1409.79  5172.9 1415.16
  5193.3 1422.13  5203.5 1426.42  5213.7 1428.86  5234.1 1430.03  5254.5 1430.57
#Mann=3,-1,0
  4841.5    0.07       0  4994.6    0.05       0  4999.2    0.07       0
Bank Sta=4994.6,4999.2
Exp/Cntr=0.3,0.1

Type RM Length L Ch R = 1,2880,485,485,485
BEGIN DESCRIPTION:
Stream0127_DS 5.0
END DESCRIPTION:
XS GIS Cut Line= 3
      2018325.01     13910275.00      2018175.00     13910225.00
      2017975.02     13910225.00
#Sta/Elev= 30
  4841.8 1402.34  4852.4 1401.93  4884.0 1399.86  4894.5 1397.57  4915.6 1392.53
  4936.7 1389.42  4947.2 1387.46  4957.8 1386.58  4968.3 1386.10  4976.5 1383.82
  4976.8 1383.32  4980.8 1383.32  4981.1 1383.82  4989.4 1384.60  4997.3 1387.05
  5002.4 1387.05  5009.9 1387.79  5019.9 1387.72  5040.4 1388.14  5049.9 1388.33
  5059.9 1389.02  5069.9 1389.85  5079.9 1391.26  5089.9 1393.36  5111.4 1399.99
  5119.9 1402.15  5169.9 1417.80  5179.9 1419.75  5189.9 1420.13  5199.9 1420.15
#Mann=5,-1,0
  4841.8    0.07       0  4976.5    0.05       0  4981.1    0.07       0
  5040.4   0.035       0  5111.4    0.07       0
Bank Sta=4976.5,4981.1
Exp/Cntr=0.3,0.1

Type RM Length L Ch R = 1,2395,447,447,447
BEGIN DESCRIPTION:
Stream0127_DS 4.0
END DESCRIPTION:
XS GIS Cut Line= 3
      2018525.03     13910025.03      2018275.00     13909775.00
      2018175.00     13909775.00
#Sta/Elev= 30
  4645.7 1405.91  4674.0 1405.31  4688.2 1402.70  4702.3 1399.28  4716.5 1396.60
  4730.6 1394.32  4758.9 1390.42  4773.0 1389.09  4780.6 1388.74  4829.6 1385.56
  4843.7 1384.18  4872.0 1382.55  4900.3 1381.33  4916.9 1381.33  4942.7 1381.00
  4956.9 1381.58  4982.8 1378.73  4983.2 1378.23  4987.2 1378.23  4987.5 1378.73
  4995.8 1379.32  5001.8 1379.32  5009.3 1382.38  5029.3 1385.69  5049.3 1390.50
  5059.3 1393.75  5063.0 1394.64  5069.3 1396.16  5079.3 1397.88  5099.3 1398.89
#Mann=6,-1,0
  4645.7    0.07       0  4780.6   0.035       0  4916.9    0.07       0
  4982.8    0.05       0  4987.5    0.07       0  5063.0   0.035       0
Bank Sta=4982.8,4987.5
Exp/Cntr=0.3,0.1

Type RM Length L Ch R = 1,1948,453,453,453
BEGIN DESCRIPTION:
Stream0127_DS 3.0
END DESCRIPTION:
XS GIS Cut Line= 3
      2018674.96     13909475.00      2018575.00     13909475.00
      2018325.01     13909525.00
#Sta/Elev= 30
  4900.9 1397.92  4930.9 1397.36  4940.9 1396.15  4950.9 1390.85  4956.7 1386.60
  4960.9 1383.52  4970.9 1371.98  4980.9 1370.71  4996.0 1370.62  4996.4 1370.12
  5000.4 1370.12  5000.7 1370.62  5011.1 1371.10  5021.3 1373.04  5051.9 1375.26
  5072.2 1375.67  5082.4 1376.46  5123.2 1378.02  5128.3 1378.27  5133.4 1378.99
  5153.8 1379.77  5174.2 1381.63  5194.6 1384.15  5200.0 1385.07  5215.0 1387.38
  5225.2 1389.44  5235.4 1390.86  5245.6 1391.21  5253.3 1391.90  5255.8 1391.90
#Mann=5,-1,0
  4900.9    0.12       0  4956.7    0.07       0  4996.0    0.05       0
  5000.7    0.07       0  5200.0   0.035       0
Bank Sta=4996,5000.7
Exp/Cntr=0.3,0.1

Type RM Length L Ch R = 1,1495,475,475,475
BEGIN DESCRIPTION:
Stream0127_DS 2.0
END DESCRIPTION:
XS GIS Cut Line= 3
      2018675.01     13909125.00      2018425.00     13909075.00
      2018324.96     13909075.00
#Sta/Elev= 30
  4744.6 1400.67  4754.8 1400.13  4765.0 1400.35  4775.2 1398.96  4785.4 1396.51
  4795.6 1392.85  4805.8 1389.94  4816.0 1385.60  4826.2 1380.56  4836.4 1377.76
  4846.6 1375.52  4856.8 1374.09  4877.2 1372.09  4928.2 1369.33  4948.6 1366.85
  4958.8 1366.26  4989.4 1367.79  4997.0 1367.03  5002.1 1367.03  5009.6 1362.97
  5017.2 1362.64  5017.5 1362.14  5021.6 1362.14  5022.0 1362.64  5029.6 1366.12
  5039.6 1369.89  5049.6 1378.87  5059.6 1382.44  5097.1 1388.68  5099.6 1388.68
#Mann=3,-1,0
  4744.6    0.07       0  5017.2    0.05       0  5022.0    0.07       0
Bank Sta=5017.2,5022
Exp/Cntr=0.3,0.1

Type RM Length L Ch R = 1,1020,0,0,0
BEGIN DESCRIPTION:
Stream0127_DS 1.0
END DESCRIPTION:
XS GIS Cut Line= 3
      2018724.98     13908724.99      2018625.00     13908675.00
      2018425.03     13908625.01
#Sta/Elev= 30
  4884.3 1392.19  4912.2 1392.11  4920.6 1391.27  4937.4 1387.27  4951.4 1384.56
  4959.7 1380.54  4965.3 1381.76  4973.7 1370.24  4982.1 1363.44  4987.7 1362.54
  4993.3 1359.84  4998.7 1359.84  5006.4 1358.22  5016.9 1358.11  5017.2 1357.61
  5021.3 1357.61  5021.7 1358.11  5027.0 1360.21  5037.3 1361.52  5055.3 1362.72
  5060.5 1362.17  5078.5 1362.91  5119.8 1365.78  5130.1 1367.00  5137.8 1369.68
  5143.0 1369.86  5159.1 1376.27  5171.3 1380.74  5179.0 1382.88  5202.2 1383.00
#Mann=4,-1,0
  4884.3   0.035       0  5016.9   0.035       0  5021.7   0.035       0
  5159.1    0.07       0
Bank Sta=5016.9,5021.7
Exp/Cntr=0.3,0.1

Chan Stop Cuts=-1