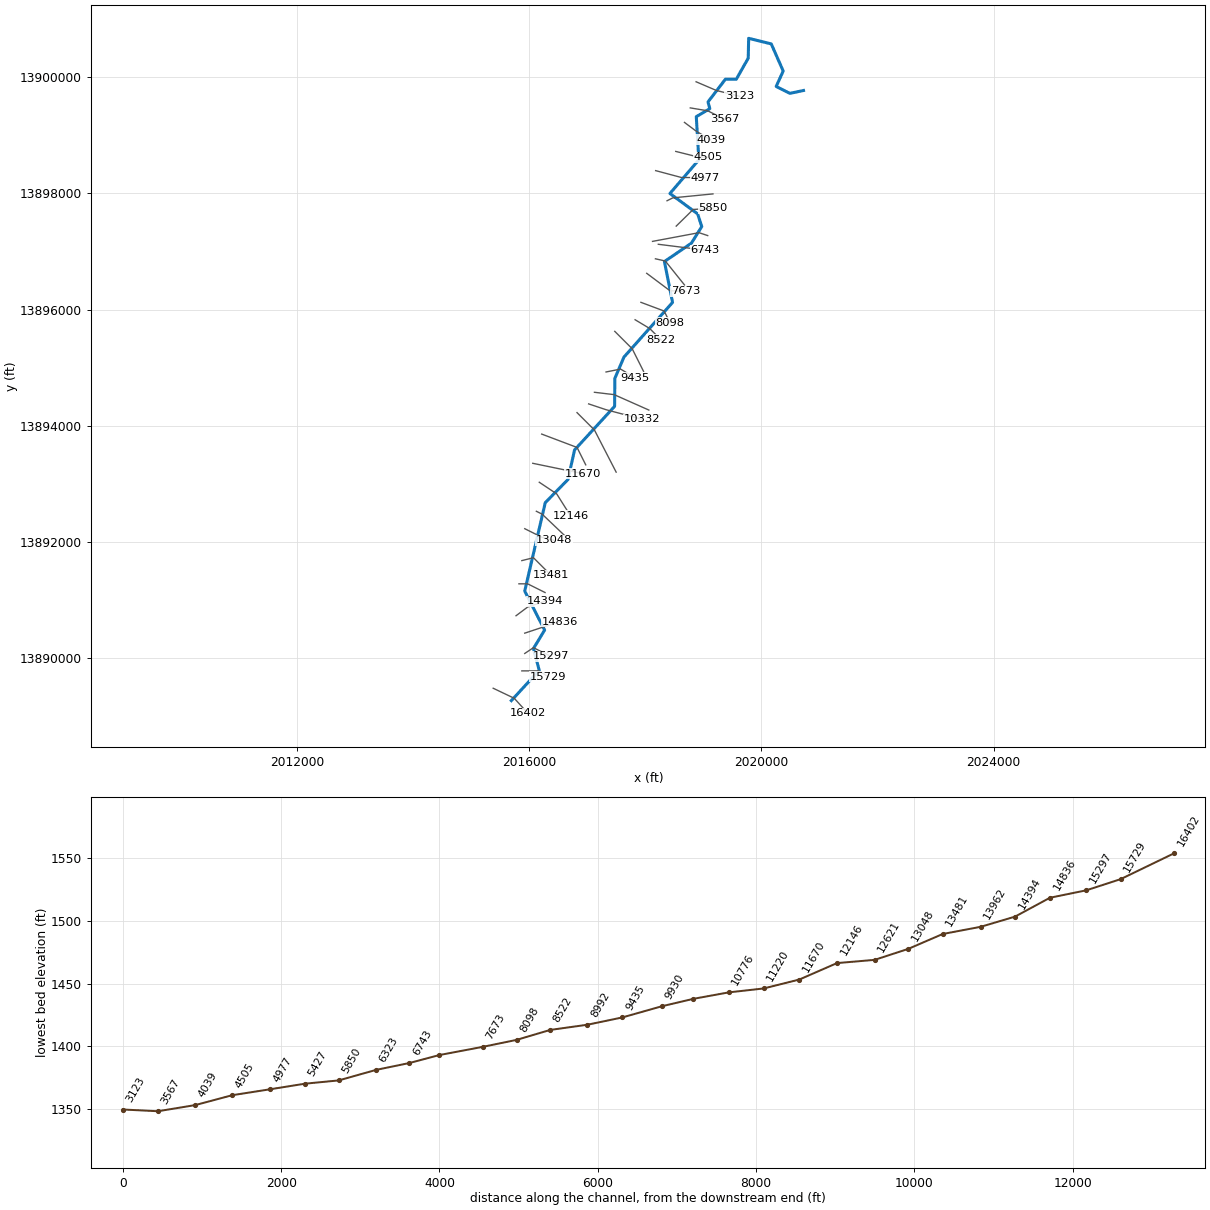
--- Stream0128_DS.prj (project) ---

Proj Title=Stream0128_DS Base Level Engineering
Current Plan=p01
Default Exp/Contr=0.3,0.1
English Units
Geom File=g01
Flow File=f01
Plan File=p01
Y Axis Title=Elevation
X Axis Title(PF)=Main Channel Distance
X Axis Title(XS)=Station
BEGIN DESCRIPTION:
Stream0128_DS
END DESCRIPTION:
DSS Export Rating Curves= 0
DSS Export Rating Curve Sorted= 0
DSS Export Volume Flow Curves= 0
DXF OffsetX= 0
DXF OffsetY= 0
DXF ScaleX= 1
DXF ScaleY= 10

--- Stream0128_DS.p01 (plan) ---

Plan Title=Multiple Run
Short Identifier=Multiple
Geom File=g01
Flow File=f01
Subcritical Flow
K Sum by GR= 0
Std Step Tol= 0.01
Critical Tol= 0.01
Num of Std Step Trials= 20
Max Error Tol= 0.3
Flow Tol Ratio= 0.001
Split Flow NTrial= 30
Split Flow Tol= 0.02
Split Flow Ratio= 0.02
Log Output Level= 0
Friction Slope Method= 1
Unsteady Friction Slope Method= 2
Unsteady Bridges Friction Slope Method= 1
Parabolic Critical Depth
Global Vel Dist=  1 , 1 , 1
Global Log Level= 0
CheckData=True
Encroach Param= -1, 0, 0, 0
BEGIN DESCRIPTION:
Multiple Run
END DESCRIPTION:

--- Stream0128_DS.f01 (steady flow) ---

Flow Title=Multiple
Number of Profiles=7
Profile Names=10-year,25-year,50-year,1pct_min,100-year,1pct_plu,500-year
River Rch & RM= Stream0128_DS,Reach-1,16402
     351     563     755     495     988    1971    1664
River Rch & RM= Stream0128_DS,Reach-1,15729
    1096    1893    2668    1826    3643    7269    6717
River Rch & RM= Stream0128_DS,Reach-1,11670
    1405    2454    3483    2397    4782    9542    8923
River Rch & RM= Stream0128_DS,Reach-1,8522
    1680    2943    4184    2879    5745   11463   10726
Boundary for River Rch & Prof#=Stream0128_DS,Reach-1,1
Up Type=0
Dn Type=3
Dn Slope=0.005
Boundary for River Rch & Prof#=Stream0128_DS,Reach-1,2
Up Type=0
Dn Type=3
Dn Slope=0.005
Boundary for River Rch & Prof#=Stream0128_DS,Reach-1,3
Up Type=0
Dn Type=3
Dn Slope=0.005
Boundary for River Rch & Prof#=Stream0128_DS,Reach-1,4
Up Type=0
Dn Type=3
Dn Slope=0.005
Boundary for River Rch & Prof#=Stream0128_DS,Reach-1,5
Up Type=0
Dn Type=3
Dn Slope=0.005
Boundary for River Rch & Prof#=Stream0128_DS,Reach-1,6
Up Type=0
Dn Type=3
Dn Slope=0.005
Boundary for River Rch & Prof#=Stream0128_DS,Reach-1,7
Up Type=0
Dn Type=3
Dn Slope=0.005

--- Stream0128_DS.g01 (geometry) ---

Geom Title=Existing Conditions
Program Version=4.10

River Reach=Stream0128_DS   ,Reach-1
Reach XY= 30
      2015694.51     13889262.63      2016174.31     13889784.62
      2016074.95     13890159.67      2016267.19     13890478.41
      2015924.77     13891150.07      2016278.45     13892673.75
      2016669.53     13893072.55      2016782.69     13893581.48
      2017472.47     13894333.17       2017476.2      13894814.5
      2017632.88     13895181.17      2018469.55     13896122.55
      2018330.09      13896827.3       2018795.2     13897144.61
      2018972.74     13897430.56      2018902.01     13897648.52
      2018424.49     13897999.96      2018922.83     13898580.44
      2018878.45     13899323.75       2019111.6     13899461.27
      2019080.13     13899577.28      2019380.47     13899969.89
      2019566.85     13899968.31      2019772.65     13900330.52
      2019780.39     13900673.34      2020169.29     13900577.59
      2020374.93      13900109.6      2020254.24     13899844.47
      2020489.04      13899725.1        2020725.       13899775.

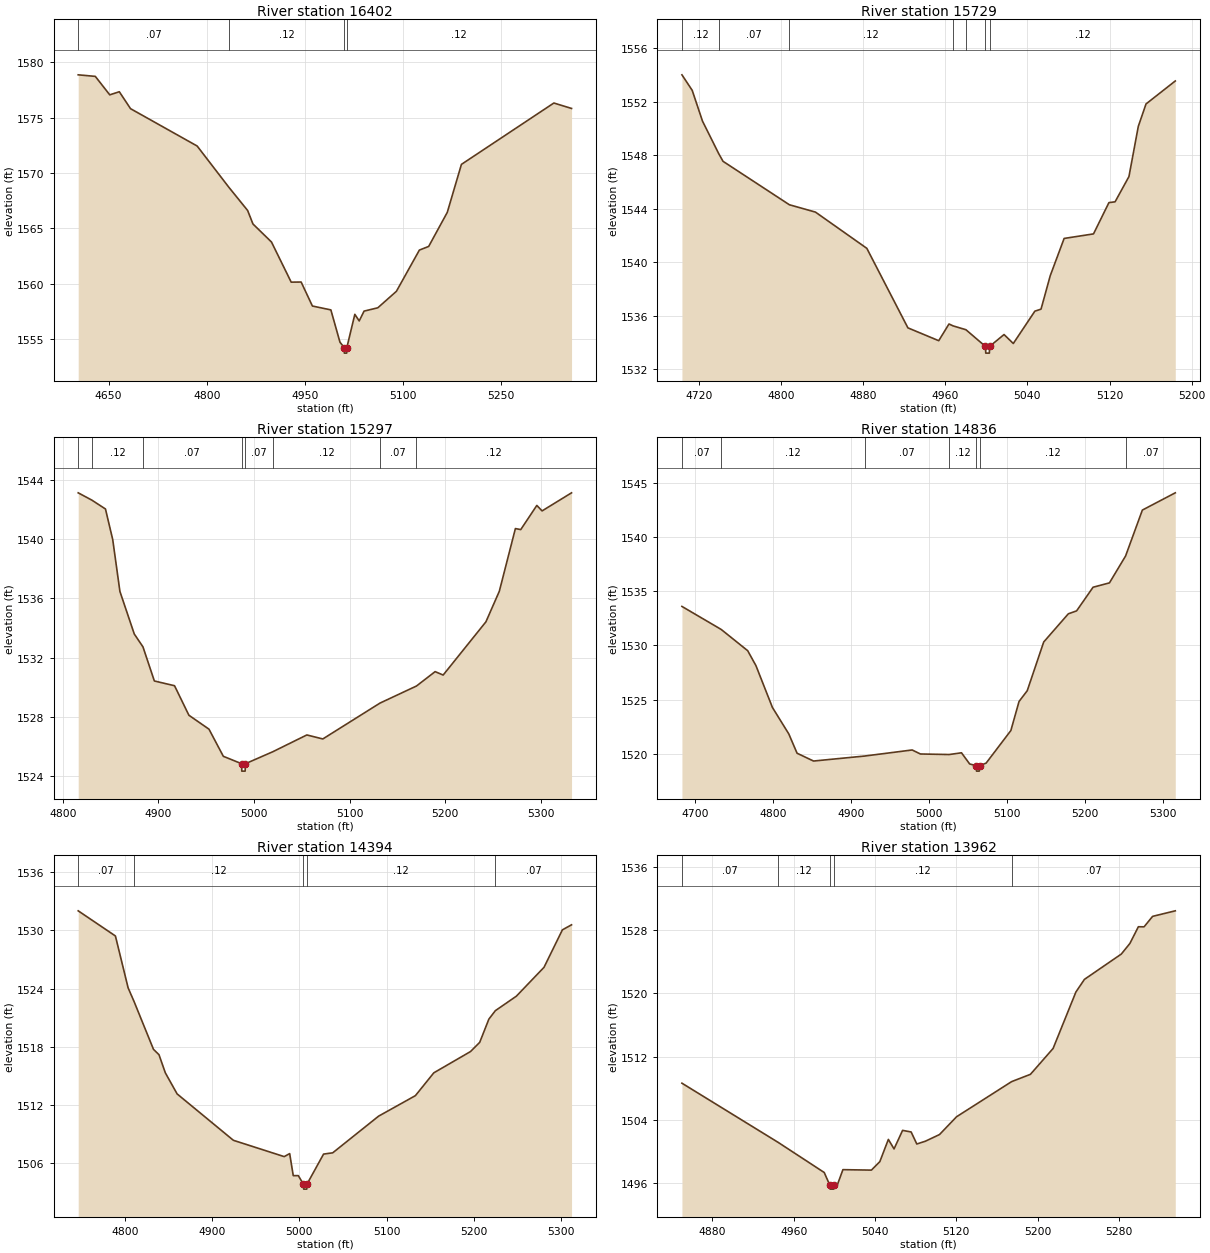
Type RM Length L Ch R = 1 ,16402   ,673,673,673
BEGIN DESCRIPTION:
Stream0128_DS 34.0
END DESCRIPTION:
XS GIS Cut Line= 3
      2015381.48     13889476.15       2015744.6     13889302.74
      2015980.77     13889042.94
#Sta/Elev= 30
  4603.7 1578.88  4629.8 1578.74  4651.9 1577.07  4666.5 1577.35  4683.6 1575.82
  4785.4 1572.44  4833.8 1568.71  4862.5 1566.61  4870.6 1565.39  4898.9 1563.76
    4929 1560.13  4944.2 1560.14  4961.4 1557.97  4989.6 1557.62  5003.5  1554.7
    5010 1554.21  5010.2 1553.71  5013.7 1553.71    5014 1554.21  5026.2 1557.22
  5032.9 1556.62  5040.3 1557.51  5061.3 1557.81  5089.7  1559.3  5124.8 1563.03
    5139 1563.36  5167.4 1566.44    5189 1570.78  5330.2 1576.33  5357.2 1575.84
#Mann= 4 ,-1 , 0
  4603.7     .07       0  4833.8     .12       0    5010     .05       0
    5014     .12       0
Bank Sta=5010,5014
XS Rating Curve= 0 ,0
Exp/Cntr=0.3,0.1

Type RM Length L Ch R = 1 ,15729   ,432,432,432
BEGIN DESCRIPTION:
Stream0128_DS 33.0
END DESCRIPTION:
XS GIS Cut Line= 3
      2015874.96       13889775.        2016175.       13889775.
      2016324.99     13889675.01
#Sta/Elev= 30
  4703.7 1554.03  4713.7 1552.87  4723.7 1550.57  4739.6 1548.12  4743.7 1547.56
  4808.3 1544.31  4833.7 1543.76  4883.7 1541.05  4923.7  1535.1  4953.7 1534.14
  4963.7 1535.39  4967.6 1535.25  4980.2 1534.96  4999.2 1533.71  4999.5 1533.21
    5003 1533.21  5003.2 1533.71  5017.3  1534.6  5026.3 1533.93  5047.3 1536.35
  5053.3  1536.5  5062.3 1539.01  5075.8 1541.79  5104.4 1542.13  5119.4 1544.47
  5125.4 1544.53  5138.9 1546.42    5148 1550.17  5155.5 1551.85    5184 1553.57
#Mann= 7 ,-1 , 0
  4703.7     .12       0  4739.6     .07       0  4808.3     .12       0
  4967.6     .07       0  4980.2     .12       0  4999.2     .05       0
  5003.2     .12       0
Bank Sta=4999.2,5003.2
XS Rating Curve= 0 ,0
Exp/Cntr=0.3,0.1

Type RM Length L Ch R = 1 ,15297   ,461,461,461
BEGIN DESCRIPTION:
Stream0128_DS 32.0
END DESCRIPTION:
XS GIS Cut Line= 3
        2015925.       13890075.        2016075.       13890175.
      2016375.01       13890025.
#Sta/Elev= 30
  4816.2 1543.12  4830.4 1542.63  4844.7 1542.03  4852.3 1539.96  4859.8 1536.47
  4874.8  1533.6  4883.9 1532.73  4895.8 1530.43  4916.9 1530.11  4931.9 1528.12
  4952.9 1527.18  4967.9 1525.35    4987 1524.85  4987.2 1524.35  4990.7 1524.35
    4991 1524.85  5019.7 1525.66  5055.2 1526.79  5071.9 1526.52  5131.7 1528.94
  5169.8 1530.09  5189.3 1531.06  5197.7 1530.83  5242.4 1534.42  5256.4 1536.48
  5273.2 1540.71  5278.8 1540.64  5295.6 1542.27  5301.1  1541.9  5331.9 1543.12
#Mann= 8 ,-1 , 0
  4816.2     .07       0  4830.4     .12       0  4883.9     .07       0
    4987     .05       0    4991     .07       0  5019.7     .12       0
  5131.7     .07       0  5169.8     .12       0
Bank Sta=4987,4991
XS Rating Curve= 0 ,0
Exp/Cntr=0.3,0.1

Type RM Length L Ch R = 1 ,14836   ,442,442,442
BEGIN DESCRIPTION:
Stream0128_DS 31.0
END DESCRIPTION:
XS GIS Cut Line= 3
      2015924.99       13890425.        2016225.       13890525.
      2016525.03     13890625.01
#Sta/Elev= 30
  4683.6 1533.58  4733.9 1531.46  4767.9  1529.5  4778.5 1528.12  4799.6 1524.27
  4820.6 1521.83  4831.2 1520.05  4852.3 1519.33  4917.8 1519.79  4978.8 1520.35
  4989.3 1519.98  5026.3 1519.93    5042 1520.09  5052.5 1519.06  5061.1  1518.9
  5061.3  1518.4  5064.8  1518.4  5065.1  1518.9  5073.6 1519.14  5105.3 1522.14
  5115.8 1524.82  5126.3 1525.81  5147.4  1530.3    5179  1532.9  5189.6 1533.17
  5210.7 1535.35  5231.7 1535.75  5252.4 1538.23  5273.9 1542.46  5316.1 1544.05
#Mann= 7 ,-1 , 0
  4683.6     .07       0  4733.9     .12       0  4917.8     .07       0
  5026.3     .12       0  5061.1     .05       0  5065.1     .12       0
  5252.4     .07       0
Bank Sta=5061.1,5065.1
XS Rating Curve= 0 ,0
Exp/Cntr=0.3,0.1

Type RM Length L Ch R = 1 ,14394   ,432,432,432
BEGIN DESCRIPTION:
Stream0128_DS 30.0
END DESCRIPTION:
XS GIS Cut Line= 3
      2015775.03     13890725.02        2015975.       13890875.
      2016275.01       13890975.
#Sta/Elev= 30
  4746.1 1532.01  4788.8 1529.42  4803.4 1524.07  4810.1 1522.69  4832.5 1517.74
  4838.8 1517.19  4846.1 1515.32  4859.6 1513.15  4924.2 1508.37  4982.5 1506.69
  4988.8    1507  4992.9 1504.73  4998.7 1504.73  5004.6 1503.84  5004.9 1503.34
  5008.4 1503.34  5008.6 1503.84  5027.7 1506.95  5038.2 1507.08  5090.9 1510.86
  5133.1 1512.97  5154.2 1515.32  5196.3 1517.51  5206.9 1518.46  5217.4 1520.85
  5224.8 1521.72    5249 1523.22  5280.7 1526.19  5301.8 1530.05  5312.3 1530.57
#Mann= 5 ,-1 , 0
  4746.1     .07       0  4810.1     .12       0  5004.6     .05       0
  5008.6     .12       0  5224.8     .07       0
Bank Sta=5004.6,5008.6
XS Rating Curve= 0 ,0
Exp/Cntr=0.3,0.1

Type RM Length L Ch R = 1 ,13962   ,481,481,481
BEGIN DESCRIPTION:
Stream0128_DS 29.0
END DESCRIPTION:
XS GIS Cut Line= 3
      2015824.98       13891275.        2015975.       13891275.
      2016274.98     13891125.01
#Sta/Elev= 30
    4850 1508.66  4944.6 1501.19    4990 1497.38  4995.5 1495.78  4995.8 1495.28
  4999.3 1495.28  4999.5 1495.78  5002.8 1495.78  5008.4 1497.74  5036.4 1497.68
  5044.7 1498.75  5053.1 1501.56  5058.7 1500.36  5067.1  1502.7  5075.5  1502.5
  5081.1 1500.98  5089.5 1501.33  5103.4 1502.17  5120.2 1504.42  5174.4 1508.86
  5192.9 1509.78  5215.2 1513.05  5237.6 1520.17    5246 1521.77  5282.3 1524.97
  5290.7  1526.3  5299.1 1528.42  5304.7 1528.41  5313.1 1529.73  5335.4 1530.43
#Mann= 5 ,-1 , 0
    4850     .07       0  4944.6     .12       0  4995.5     .05       0
  4999.5     .12       0  5174.4     .07       0
Bank Sta=4995.5,4999.5
XS Rating Curve= 0 ,0
Exp/Cntr=0.3,0.1

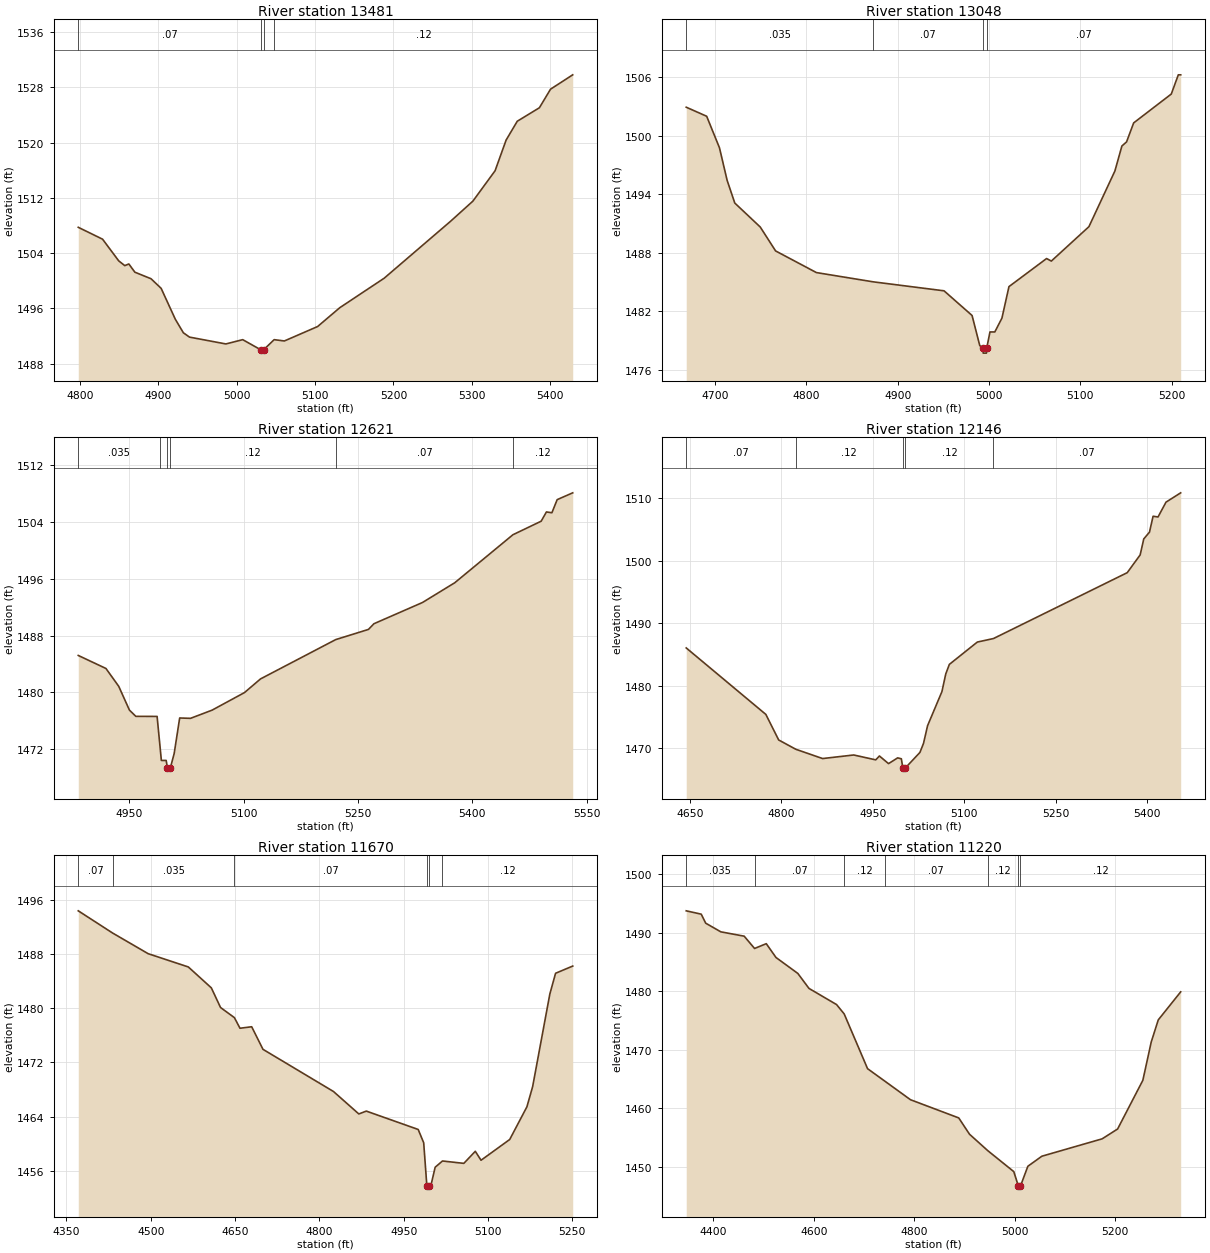
Type RM Length L Ch R = 1 ,13481   ,433,433,433
BEGIN DESCRIPTION:
Stream0128_DS 28.0
END DESCRIPTION:
XS GIS Cut Line= 3
      2015874.95     13891674.99        2016075.       13891725.
      2016375.02     13891424.98
#Sta/Elev= 30
  4798.1 1507.75  4829.1 1506.03  4849.7 1502.89  4857.4  1502.2  4862.6 1502.44
  4870.3 1501.25  4890.9  1500.3  4903.8 1498.91  4921.8 1494.45  4932.1 1492.48
  4939.9 1491.85  4986.3 1490.86  5007.8 1491.48  5030.6 1490.03  5030.8 1489.53
  5034.3 1489.53  5034.6 1490.03  5047.9 1491.48  5060.9 1491.29  5103.3 1493.38
  5131.6 1496.11  5188.2 1500.38    5273 1508.64  5301.3 1511.54  5329.6 1515.94
  5343.7 1520.39  5357.9 1523.11  5386.1 1525.06  5400.3 1527.75  5428.6 1529.83
#Mann= 4 ,-1 , 0
  4798.1     .07       0  5030.6     .05       0  5034.6     .07       0
  5047.9     .12       0
Bank Sta=5030.6,5034.6
XS Rating Curve= 0 ,0
Exp/Cntr=0.3,0.1

Type RM Length L Ch R = 1 ,13048   ,427,427,427
BEGIN DESCRIPTION:
Stream0128_DS 27.0
END DESCRIPTION:
XS GIS Cut Line= 3
      2015924.96     13892225.02        2016225.       13892075.
      2016424.99       13892025.
#Sta/Elev= 30
  4668.4 1502.95  4690.8 1502.02  4704.8 1498.79  4713.2 1495.45  4721.6 1493.12
  4749.5 1490.66  4766.3 1488.21    4811 1485.99  4873.3 1485.04  4950.8 1484.12
  4981.5 1481.59  4989.9 1478.51  4993.5 1478.23  4993.7 1477.73  4997.2 1477.73
  4997.5 1478.23  5001.1  1479.9  5006.4  1479.9  5014.2 1481.32  5021.9 1484.55
  5063.1 1487.43  5068.3 1487.17  5109.5  1490.7  5137.9  1496.4  5145.6 1498.97
  5150.7 1499.39  5158.5 1501.34  5199.7  1504.3  5207.4 1506.27    5210 1506.27
#Mann= 4 ,-1 , 0
  4668.4    .035       0  4873.3     .07       0  4993.5     .05       0
  4997.5     .07       0
Bank Sta=4993.5,4997.5
XS Rating Curve= 0 ,0
Exp/Cntr=0.3,0.1

Type RM Length L Ch R = 1 ,12621   ,475,475,475
BEGIN DESCRIPTION:
Stream0128_DS 26.0
END DESCRIPTION:
XS GIS Cut Line= 3
      2016124.99     13892525.01        2016225.       13892475.
      2016613.73     13892104.98
#Sta/Elev= 30
  4883.2  1485.2  4919.5 1483.37  4936.3 1480.86  4950.3 1477.52  4958.7 1476.64
  4986.6 1476.63  4989.9 1472.98  4992.2 1470.44  4998.5 1470.44  5000.1 1469.44
  5000.3 1468.94  5003.8 1468.94  5004.1 1469.44    5009 1471.42  5016.2 1476.41
  5030.4 1476.36  5058.7 1477.51  5101.2 1479.98  5122.2  1481.9  5220.9 1487.43
  5263.8 1488.86    5271 1489.66  5334.6 1492.64    5377 1495.42  5453.3 1502.17
  5490.3 1504.07  5497.2 1505.37  5504.4 1505.26  5511.3  1507.1  5531.7 1508.06
#Mann= 6 ,-1 , 0
  4883.2    .035       0  4989.9     .12       0  5000.1     .05       0
  5004.1     .12       0  5220.9     .07       0  5453.3     .12       0
Bank Sta=5000.1,5004.1
XS Rating Curve= 0 ,0
Exp/Cntr=0.3,0.1

Type RM Length L Ch R = 1 ,12146   ,476,476,476
BEGIN DESCRIPTION:
Stream0128_DS 25.0
END DESCRIPTION:
XS GIS Cut Line= 3
      2016175.01       13893025.        2016475.       13892825.
      2016715.29     13892443.52
#Sta/Elev= 30
  4643.9 1486.07  4774.6 1475.44  4795.6 1471.36  4823.8 1469.87  4867.7 1468.39
  4918.8 1468.96  4954.9 1468.18  4960.9  1468.8  4975.9 1467.58  4990.9  1468.5
  4996.9 1468.35  4999.4 1466.88  4999.7 1466.38  5003.4 1466.88  5027.4 1469.37
  5033.3 1470.82  5039.9 1473.63  5063.5 1479.09  5069.8 1481.92  5075.7 1483.44
  5121.6 1487.01  5148.1 1487.57  5367.6  1498.1  5388.8 1500.94  5394.7 1503.49
  5404.1 1504.58    5410 1507.12  5418.1    1507  5431.2 1509.37  5455.3 1510.86
#Mann= 5 ,-1 , 0
  4643.9     .07       0  4823.8     .12       0  4999.4     .05       0
  5003.4     .12       0  5148.1     .07       0
Bank Sta=4999.4,5003.4
XS Rating Curve= 0 ,0
Exp/Cntr=0.3,0.1

Type RM Length L Ch R = 1 ,11670   ,450,450,450
BEGIN DESCRIPTION:
Stream0128_DS 24.0
END DESCRIPTION:
XS GIS Cut Line= 3
      2016063.25     13893351.49        2016675.       13893225.
      2016924.96     13893175.01
#Sta/Elev= 30
  4371.1 1494.34  4432.1 1491.07  4495.4 1488.02  4566.9 1486.06  4607.8 1482.98
  4624.2 1480.08  4648.8 1478.59  4658.8 1477.02  4679.6 1477.24  4699.7 1473.91
  4825.1 1467.69  4870.2 1464.38  4883.5  1464.8  4975.8 1462.09  4985.6 1460.13
  4991.2 1453.79  4991.5 1453.29  4995.2 1453.79  4998.3 1453.79    5006 1456.52
    5019 1457.44    5057 1457.09  5077.4 1458.87  5087.6 1457.55  5138.6 1460.61
  5169.2 1465.43  5179.4 1468.41    5210 1482.07  5220.2 1485.13  5250.7 1486.19
#Mann= 6 ,-1 , 0
  4371.1     .07       0  4432.1    .035       0  4648.8     .07       0
  4991.2     .05       0  4995.2     .07       0    5019     .12       0
Bank Sta=4991.2,4995.2
XS Rating Curve= 0 ,0
Exp/Cntr=0.3,0.1

Type RM Length L Ch R = 1 ,11220   ,444,444,444
BEGIN DESCRIPTION:
Stream0128_DS 23.0
END DESCRIPTION:
XS GIS Cut Line= 3
        2016217.     13893854.96        2016825.       13893625.
      2016974.98     13893325.04
#Sta/Elev= 30
  4345.8 1493.71  4375.7 1493.14  4384.6  1491.6  4414.8 1490.12  4461.3 1489.38
    4482 1487.28  4505.3  1488.1  4524.7 1485.74  4568.2 1483.02  4590.4 1480.46
  4645.4  1477.7  4660.6  1476.1  4707.2 1466.75  4741.3 1464.64  4792.7 1461.45
  4888.9 1458.34  4910.3 1455.56  4946.6 1452.76  4998.6 1449.17  5007.8 1446.68
  5008.1 1446.18  5011.8 1446.68  5026.6 1450.08  5054.5  1451.8  5174.7 1454.77
  5205.5 1456.45  5255.8 1464.77  5272.5 1471.31  5286.5 1475.08  5331.2 1479.87
#Mann= 7 ,-1 , 0
  4345.8    .035       0    4482     .07       0  4660.6     .12       0
  4741.3     .07       0  4946.6     .12       0  5007.8     .05       0
  5011.8     .12       0
Bank Sta=5007.8,5011.8
XS Rating Curve= 0 ,0
Exp/Cntr=0.3,0.1

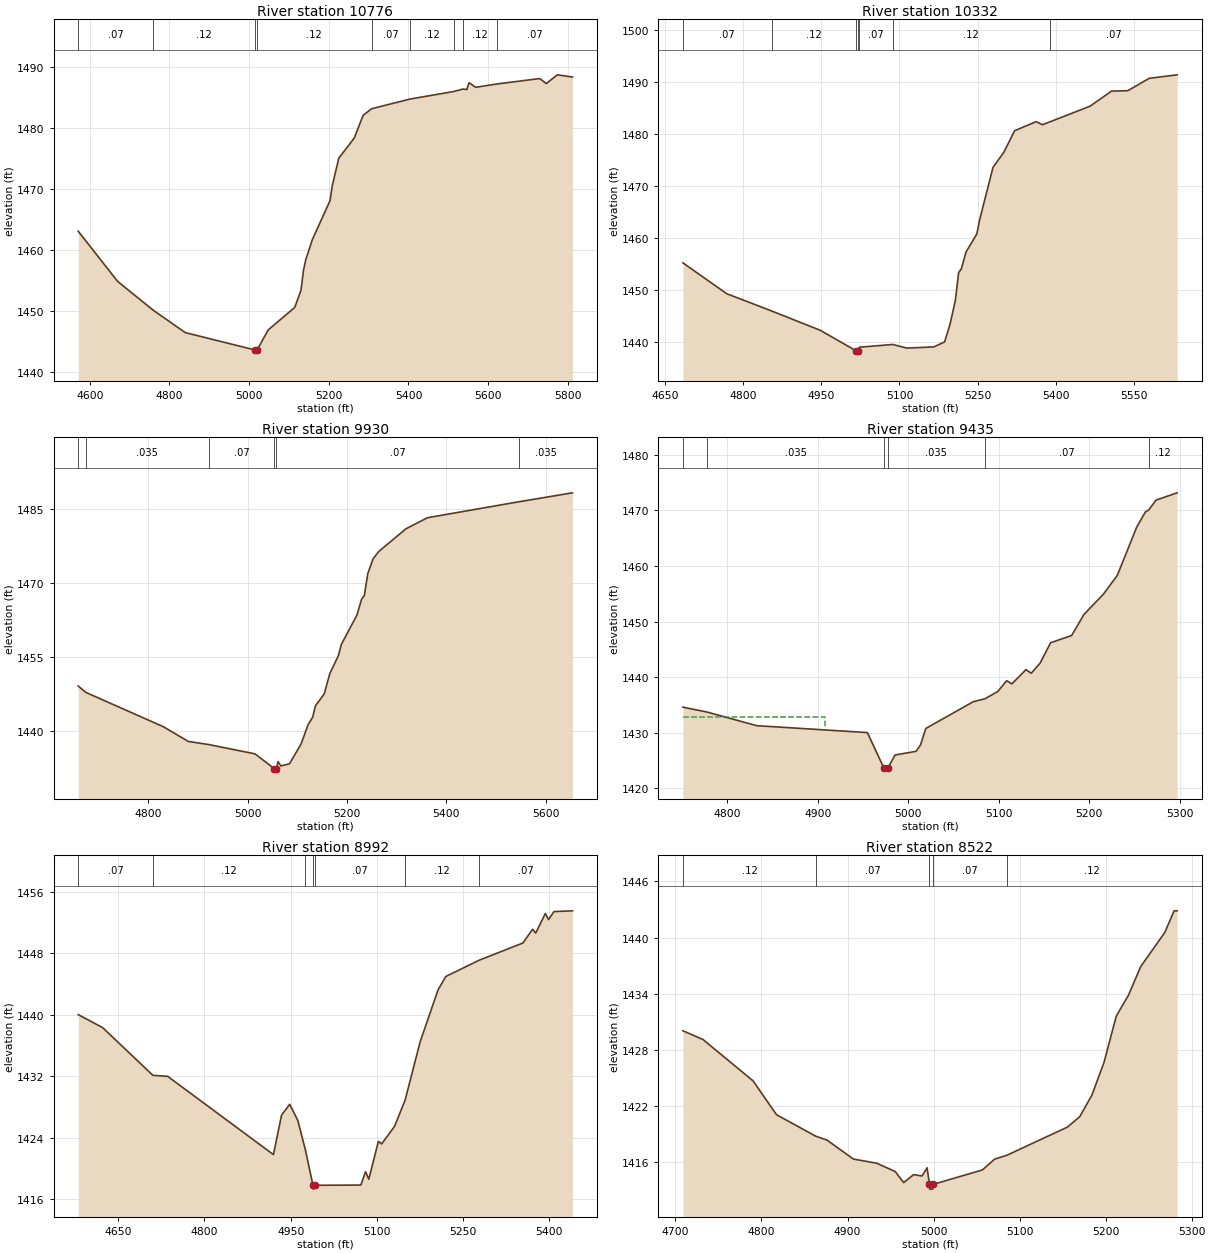
Type RM Length L Ch R = 1 ,10776   ,444,444,444
BEGIN DESCRIPTION:
Stream0128_DS 22.0
END DESCRIPTION:
XS GIS Cut Line= 3
      2016825.01     13894224.99        2017125.       13893925.
      2017498.82     13893199.38
#Sta/Elev= 30
  4571.1 1463.05  4670.1  1454.8  4759.5 1450.07  4839.8  1446.4  5015.8 1443.53
  5016.1 1443.03  5019.8 1443.53    5048 1446.85  5114.5 1450.53  5130.3 1453.37
  5136.6 1456.68  5142.2 1458.37  5158.8 1461.68  5203.1 1468.07  5209.1 1470.64
  5225.3 1475.07    5264 1478.36  5286.2 1482.09  5307.5 1483.17  5404.6 1484.77
  5513.5    1486  5536.6  1486.4  5546.5 1486.33  5552.2 1487.45  5568.7 1486.69
  5622.4 1487.24  5729.5 1488.13    5746 1487.31  5773.8 1488.74  5811.6 1488.38
#Mann= 9 ,-1 , 0
  4571.1     .07       0  4759.5     .12       0  5015.8     .05       0
  5019.8     .12       0  5307.5     .07       0  5404.6     .12       0
  5513.5     .07       0  5536.6     .12       0  5622.4     .07       0
Bank Sta=5015.8,5019.8
XS Rating Curve= 0 ,0
Exp/Cntr=0.3,0.1

Type RM Length L Ch R = 1 ,10332   ,402,402,402
BEGIN DESCRIPTION:
Stream0128_DS 21.0
END DESCRIPTION:
XS GIS Cut Line= 3
      2017025.04     13894374.99        2017325.       13894275.
      2017936.67     13894112.78
#Sta/Elev= 30
  4684.1 1455.24  4768.4 1449.32  4854.4 1446.02  4947.6 1442.32  5015.8 1438.43
    5016 1437.93  5019.8 1438.43  5023.1 1439.07    5087 1439.59  5114.1  1438.9
  5165.8 1439.12  5186.5 1440.07  5196.9 1443.39  5207.2 1448.02  5213.6 1453.38
  5218.8 1454.12  5227.9 1457.35  5248.6  1460.8  5253.8 1463.46  5279.6 1473.57
  5300.3 1476.44    5321 1480.58  5362.4 1482.33  5374.4 1481.74  5388.8 1482.29
  5465.8 1485.29  5507.2 1488.19  5538.3 1488.26  5579.6 1490.64  5633.1 1491.31
#Mann= 7 ,-1 , 0
  4684.1     .07       0  4854.4     .12       0  5015.8     .05       0
  5019.8     .12       0  5023.1     .07       0    5087     .12       0
  5388.8     .07       0
Bank Sta=5015.8,5019.8
XS Rating Curve= 0 ,0
Exp/Cntr=0.3,0.1

Type RM Length L Ch R = 1 ,9930    ,495,495,495
BEGIN DESCRIPTION:
Stream0128_DS 20.0
END DESCRIPTION:
XS GIS Cut Line= 3
      2017124.95     13894575.01      2017464.06     13894534.67
      2018061.68     13894269.02
#Sta/Elev= 30
  4658.5 1449.19    4674  1447.9  4829.7 1440.97  4880.1 1437.98  4921.5 1437.34
  5014.5 1435.46  5053.5 1432.46  5053.7 1431.96  5057.5 1432.46    5061 1433.89
  5066.7 1433.01  5084.2 1433.46  5107.5 1437.48  5121.4 1441.36  5130.7 1442.87
  5136.2 1445.17    5154  1447.6  5165.2  1451.7  5182.7 1455.39  5188.2 1457.57
  5219.9 1463.58  5229.2 1466.77  5234.7 1467.51  5241.8 1471.99  5252.5 1474.98
  5263.7 1476.44  5318.4 1481.04  5362.2  1483.3  5545.5 1486.52    5654 1488.34
#Mann= 6 ,-1 , 0
  4658.5     .07       0    4674    .035       0  4921.5     .07       0
  5053.5     .05       0  5057.5     .07       0  5545.5    .035       0
Bank Sta=5053.5,5057.5
XS Rating Curve= 0 ,0
Exp/Cntr=0.3,0.1

Type RM Length L Ch R = 1 ,9435    ,443,443,443
BEGIN DESCRIPTION:
Stream0128_DS 19.0
END DESCRIPTION:
XS GIS Cut Line= 3
      2017324.99       13894925.        2017575.       13894975.
        2017825.       13894825.
#Sta/Elev= 30
  4750.7 1434.62  4777.3 1433.74  4832.3 1431.29  4954.7 1430.05  4973.1 1423.62
  4973.3 1423.12  4976.8 1423.12  4977.1 1423.62  4985.3 1426.02  5008.6 1426.68
  5013.4 1427.81  5019.3 1430.79  5071.7 1435.59  5084.8 1436.13    5099 1437.45
  5108.7 1439.38  5114.5  1438.8    5130 1441.36  5135.9 1440.72  5145.6 1442.51
  5157.3 1446.19  5180.6  1447.5  5194.2 1451.29  5215.6  1454.9  5231.1 1458.31
  5252.5 1466.97  5262.2 1469.71  5265.6 1470.02  5273.9 1471.83  5297.2 1473.14
#Mann= 6 ,-1 , 0
  4750.7     .12       0  4777.3    .035       0  4973.1    .035       0
  4977.1    .035       0  5084.8     .07       0  5265.6     .12       0
#XS Ineff= 2 , 0
       0 4907.85 1432.83               0
Permanent Ineff=
       F       F
Bank Sta=4973.1,4977.1
XS Rating Curve= 0 ,0
Exp/Cntr=0.3,0.1

Type RM Length L Ch R = 1 ,8992    ,470,470,470
BEGIN DESCRIPTION:
Stream0128_DS 18.0
END DESCRIPTION:
XS GIS Cut Line= 3
      2017475.01     13895624.99        2017775.       13895325.
      2017970.25     13894936.22
#Sta/Elev= 30
  4580.7    1440  4623.1 1438.31  4710.5  1432.1  4736.2 1431.97  4920.1 1421.78
  4934.2 1426.92  4948.4 1428.33  4962.5 1426.23  4975.8 1422.35  4988.8 1417.79
  4989.1 1417.29  4992.8 1417.79  5072.1 1417.82  5080.3 1419.56  5085.9 1418.58
  5102.6 1423.51  5108.2 1423.17  5130.6 1425.45    5149 1428.86  5175.2 1436.46
  5206.4 1443.24  5219.9 1444.97    5278 1447.09  5353.9 1449.32  5370.6 1451.11
  5376.2 1450.62  5392.9 1453.17  5398.5 1452.37  5407.8 1453.41    5440 1453.51
#Mann= 7 ,-1 , 0
  4580.7     .07       0  4710.5     .12       0  4975.8     .07       0
  4988.8     .05       0  4992.8     .07       0    5149     .12       0
    5278     .07       0
Bank Sta=4988.8,4992.8
XS Rating Curve= 0 ,0
Exp/Cntr=0.3,0.1

Type RM Length L Ch R = 1 ,8522    ,424,424,424
BEGIN DESCRIPTION:
Stream0128_DS 17.0
END DESCRIPTION:
XS GIS Cut Line= 3
        2017825.       13895825.        2018075.       13895675.
      2018275.01     13895474.99
#Sta/Elev= 30
  4708.7 1430.05    4732 1429.12  4790.3  1424.7  4817.5 1421.09  4863.3 1418.79
  4875.9  1418.4  4906.9 1416.36  4934.2 1415.91  4955.5 1415.02  4965.3 1413.85
  4976.9  1414.7  4986.6 1414.55  4992.5 1415.43  4995.3 1413.65  4995.6 1413.15
  4999.1 1413.15  4999.3 1413.65  5056.8  1415.2    5071 1416.35  5085.4 1416.77
  5155.8 1419.78    5170 1420.89  5184.1 1423.19  5198.2 1426.69  5212.4 1431.62
  5226.5 1433.83  5240.7 1436.88  5268.9 1440.56  5279.6 1442.85  5283.1 1442.85
#Mann= 5 ,-1 , 0
  4708.7     .12       0  4863.3     .07       0  4995.3     .05       0
  4999.3     .07       0  5085.4     .12       0
Bank Sta=4995.3,4999.3
XS Rating Curve= 0 ,0
Exp/Cntr=0.3,0.1

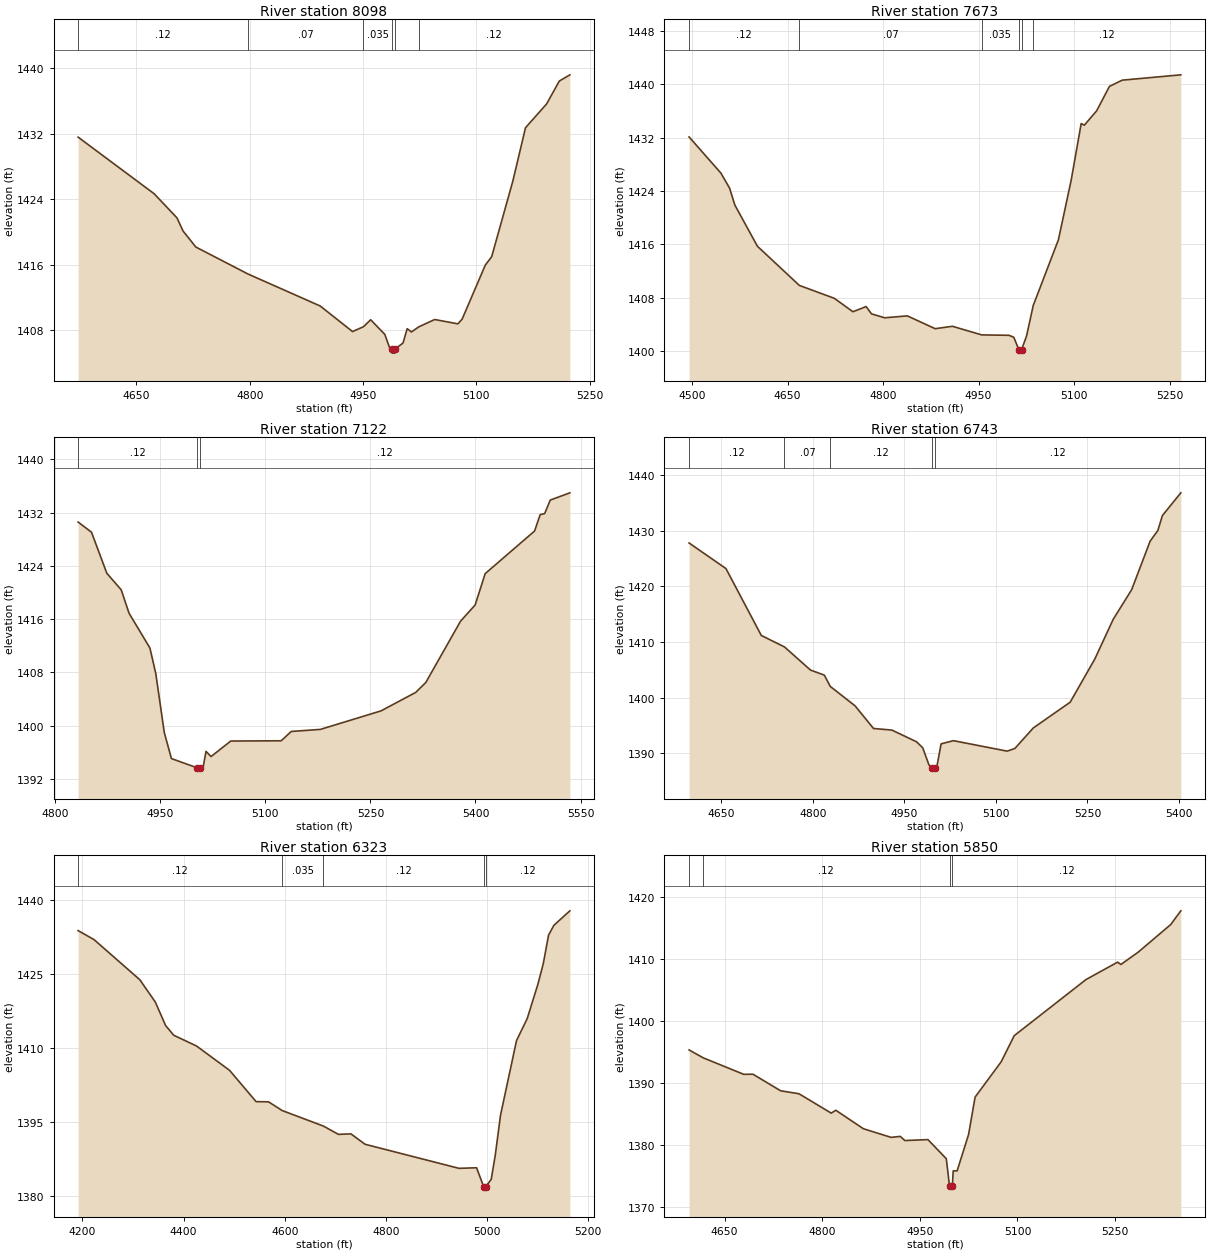
Type RM Length L Ch R = 1 ,8098    ,425,425,425
BEGIN DESCRIPTION:
Stream0128_DS 16.0
END DESCRIPTION:
XS GIS Cut Line= 3
      2017924.96     13896125.02        2018325.       13895975.
      2018425.02     13895774.96
#Sta/Elev= 30
  4572.8 1431.57  4673.4 1424.67  4703.7 1421.72  4711.7 1420.12  4728.6 1418.17
  4797.6 1414.88  4893.2 1410.98    4936 1407.86  4950.5 1408.45    4960  1409.3
  4978.7 1407.52  4984.9 1405.94  4988.2 1405.73  4988.5 1405.23  4992.1 1405.23
  4992.3 1405.73  5002.8 1406.46  5008.4 1408.21    5014 1407.81  5023.6 1408.43
  5044.8 1409.33  5075.5  1408.8  5081.1 1409.38  5111.8 1415.97  5120.2 1416.99
  5148.2 1426.21    5165 1432.72  5192.9 1435.62  5209.7 1438.41  5223.7 1439.17
#Mann= 6 ,-1 , 0
  4572.8     .12       0  4797.6     .07       0  4950.5    .035       0
  4988.2    .035       0  4992.3    .035       0  5023.6     .12       0
Bank Sta=4988.2,4992.3
XS Rating Curve= 0 ,0
Exp/Cntr=0.3,0.1

Type RM Length L Ch R = 1 ,7673    ,551,551,551
BEGIN DESCRIPTION:
Stream0128_DS 15.0
END DESCRIPTION:
XS GIS Cut Line= 3
      2018024.99     13896625.01        2018425.       13896325.
      2018697.03     13896313.31
#Sta/Elev= 30
  4495.3 1432.09  4545.3 1426.67  4558.9 1424.42  4567.2 1421.89  4602.6 1415.72
  4668.5 1409.85  4723.4 1407.92  4752.6 1405.91  4773.4 1406.68  4781.8 1405.59
  4802.6    1405    4838 1405.29  4881.8 1403.37  4908.9 1403.73  4954.9 1402.44
  4997.8 1402.38  5005.3 1402.08  5013.3 1400.21  5013.5 1399.71  5017.4 1400.21
  5025.3 1402.27  5035.8 1406.84  5075.4  1416.7  5095.4 1425.61  5111.1 1434.09
  5116.1 1433.85  5135.4    1436  5155.5 1439.66  5175.5 1440.59  5267.6 1441.39
#Mann= 6 ,-1 , 0
  4495.3     .12       0  4668.5     .07       0  4954.9    .035       0
  5013.3    .035       0  5017.4    .035       0  5035.8     .12       0
Bank Sta=5013.3,5017.4
XS Rating Curve= 0 ,0
Exp/Cntr=0.3,0.1

Type RM Length L Ch R = 1 ,7122    ,379,379,379
BEGIN DESCRIPTION:
Stream0128_DS 14.0
END DESCRIPTION:
XS GIS Cut Line= 3
      2018175.02       13896875.      2018345.51     13896836.74
      2018675.01     13896424.98
#Sta/Elev= 30
  4832.7 1430.59  4851.8 1429.06  4873.7 1422.89  4894.2 1420.41  4905.4 1416.89
  4935.2 1411.66  4943.6 1407.82  4955.7 1398.97  4965.9 1395.05  5002.5 1393.66
  5002.8 1393.16  5006.7 1393.66    5011 1393.66  5015.3 1396.13  5022.5 1395.35
  5050.6 1397.68  5122.6 1397.72    5137 1399.12  5178.6 1399.43  5265.1 1402.21
  5314.7 1404.99  5329.1 1406.48  5378.7 1415.69  5399.5 1418.12  5413.9 1422.84
  5484.4 1429.24  5492.4  1431.7  5498.8 1431.86  5506.8 1433.89  5534.8 1434.98
#Mann= 3 ,-1 , 0
  4832.7     .12       0  5002.5     .05       0  5006.7     .12       0
Bank Sta=5002.5,5006.7
XS Rating Curve= 0 ,0
Exp/Cntr=0.3,0.1

Type RM Length L Ch R = 1 ,6743    ,420,420,420
BEGIN DESCRIPTION:
Stream0128_DS 13.0
END DESCRIPTION:
XS GIS Cut Line= 3
      2018224.98       13897125.        2018625.       13897075.
      2019024.96     13897025.01
#Sta/Elev= 30
  4596.9 1427.78  4657.4 1423.18  4715.3 1411.17  4753.3 1409.11    4796 1404.95
  4818.6 1404.05  4828.4 1402.01    4869 1398.53  4899.3 1394.46  4929.5 1394.17
  4969.8 1392.07  4979.9    1391    4990 1387.97  4995.4  1387.3  4995.7  1386.8
  4999.7  1387.3  5002.6  1387.3  5010.1  1391.7  5030.3 1392.27  5118.4 1390.39
    5131 1390.87  5161.3 1394.56  5221.7 1399.18  5262.1 1406.94  5292.3 1414.08
  5322.5 1419.39  5352.8 1428.11  5365.4 1430.02  5372.9 1432.71  5403.1 1436.79
#Mann= 5 ,-1 , 0
  4596.9     .12       0  4753.3     .07       0  4828.4     .12       0
  4995.4     .05       0  4999.7     .12       0
Bank Sta=4995.4,4999.7
XS Rating Curve= 0 ,0
Exp/Cntr=0.3,0.1

Type RM Length L Ch R = 1 ,6323    ,473,473,473
BEGIN DESCRIPTION:
Stream0128_DS 12.0
END DESCRIPTION:
XS GIS Cut Line= 3
      2018125.04     13897175.01        2018925.       13897325.
      2019074.98     13897275.01
#Sta/Elev= 30
  4191.7 1433.85    4223 1432.04  4313.8 1423.86  4344.3 1419.34  4364.6 1414.58
  4380.7  1412.6  4425.7 1410.42    4491 1405.48  4543.5 1399.12  4568.1 1399.08
  4594.8 1397.32  4676.4 1394.16  4706.3 1392.47  4730.9 1392.57  4758.9 1390.46
  4944.6 1385.57  4979.3 1385.69  4993.3 1381.85  4993.5 1381.35  4997.6 1381.85
  5008.2 1383.33  5016.1 1388.14  5026.7 1396.41  5058.3 1411.53  5079.4 1415.99
  5100.5 1422.96    5111 1427.08  5121.6 1432.94  5132.1 1434.93  5163.7 1437.87
#Mann= 5 ,-1 , 0
  4191.7     .12       0  4594.8    .035       0  4676.4     .12       0
  4993.3     .05       0  4997.6     .12       0
Bank Sta=4993.3,4997.6
XS Rating Curve= 0 ,0
Exp/Cntr=0.3,0.1

Type RM Length L Ch R = 1 ,5850    ,423,423,423
BEGIN DESCRIPTION:
Stream0128_DS 11.0
END DESCRIPTION:
XS GIS Cut Line= 3
        2018533.      13897438.3        2018825.       13897725.
      2019170.47     13897745.56
#Sta/Elev= 30
  4595.6 1395.39  4617.3 1394.12  4679.6 1391.46  4693.7 1391.48  4736.2 1388.81
  4764.4 1388.33  4813.9 1385.21    4821 1385.67  4863.4 1382.69  4905.9  1381.3
    4920 1381.46    4927 1380.79  4962.5 1380.94  4990.7 1377.86  4995.6 1373.46
  4995.9 1372.96  4999.7 1372.96    5000 1373.46  5001.3  1375.9  5007.3  1375.9
  5024.9 1381.76  5034.9 1387.79  5074.9 1393.47    5095 1397.69  5205.2 1406.73
  5253.8 1409.54  5258.8 1409.16  5285.3 1411.14  5335.4  1415.6  5350.9 1417.81
#Mann= 4 ,-1 , 0
  4595.6    .035       0  4617.3     .12       0  4995.6     .05       0
    5000     .12       0
Bank Sta=4995.6,5000
XS Rating Curve= 0 ,0
Exp/Cntr=0.3,0.1

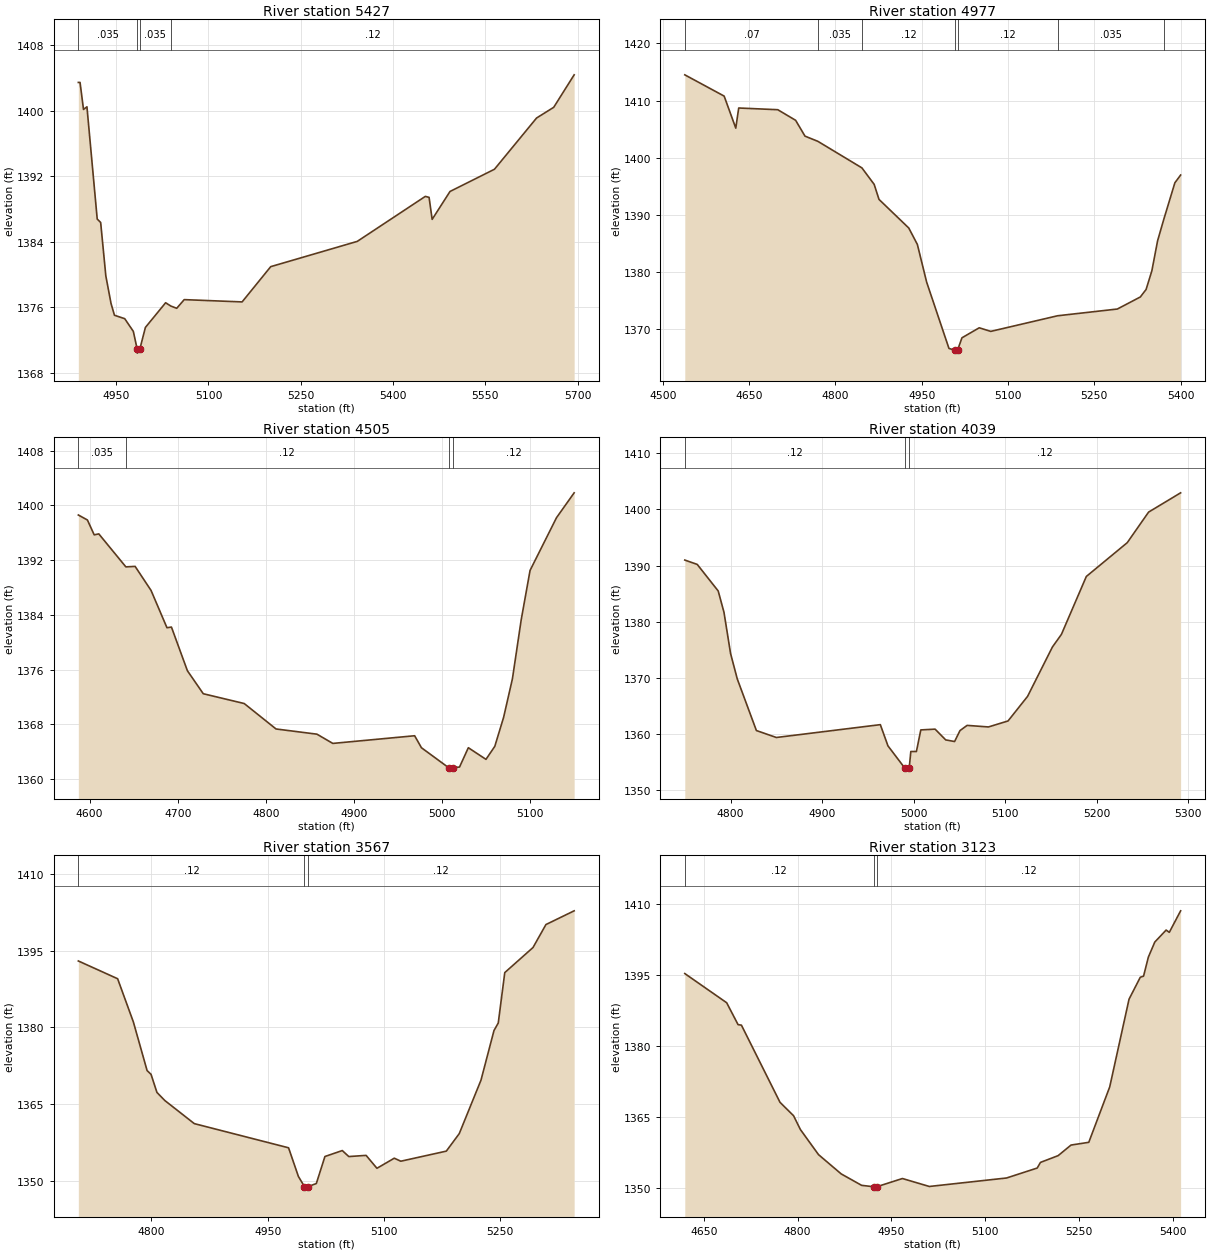
Type RM Length L Ch R = 1 ,5427    ,450,450,450
BEGIN DESCRIPTION:
Stream0128_DS 10.0
END DESCRIPTION:
XS GIS Cut Line= 3
      2018375.02     13897875.01        2018475.       13897925.
      2019165.78     13897992.99
#Sta/Elev= 30
  4888.5 1403.46  4891.3 1403.46  4896.9 1400.16  4902.5 1400.48  4919.2 1386.76
  4924.8 1386.34  4933.2 1379.81  4941.6 1376.46  4947.2    1375  4963.9 1374.58
  4977.9 1373.03  4984.1 1370.87  4984.4 1370.37  4988.5 1370.87  4997.5 1373.51
  5030.4 1376.53  5038.7 1376.13  5048.4 1375.85  5060.6 1376.91  5154.7 1376.63
  5201.2 1380.94  5341.9 1384.03  5452.5 1389.53  5458.6 1389.41  5463.6 1386.72
  5492.6 1390.13  5564.9 1392.85  5633.3 1399.11  5661.2 1400.42  5694.4 1404.39
#Mann= 4 ,-1 , 0
  4888.5    .035       0  4984.1    .035       0  4988.5    .035       0
  5038.7     .12       0
Bank Sta=4984.1,4988.5
XS Rating Curve= 0 ,0
Exp/Cntr=0.3,0.1

Type RM Length L Ch R = 1 ,4977    ,472,472,472
BEGIN DESCRIPTION:
Stream0128_DS 9.0
END DESCRIPTION:
XS GIS Cut Line= 3
      2018178.89     13898394.02        2018625.       13898275.
      2019024.98       13898275.
#Sta/Elev= 30
  4538.3  1414.5  4606.7 1410.78  4626.9 1405.18    4632  1408.7  4699.9  1408.4
  4730.9 1406.55  4747.2 1403.78  4769.6 1402.87  4846.1 1398.23  4867.4 1395.35
  4875.8 1392.72  4927.6 1387.71  4942.5 1384.84  4958.6 1378.26  4997.4 1366.66
  5007.8 1366.34  5008.1 1365.84  5012.3 1366.34    5020 1368.52    5050 1370.27
    5070 1369.64  5186.1 1372.37    5290 1373.55    5330 1375.66    5340 1376.97
    5350 1380.23    5360 1385.49  5370.7 1389.22    5390 1395.62    5400 1396.98
#Mann= 7 ,-1 , 0
  4538.3     .07       0  4769.6    .035       0  4846.1     .12       0
  5007.8     .05       0  5012.3     .12       0  5186.1    .035       0
  5370.7     .12       0
Bank Sta=5007.8,5012.3
XS Rating Curve= 0 ,0
Exp/Cntr=0.3,0.1

Type RM Length L Ch R = 1 ,4505    ,466,466,466
BEGIN DESCRIPTION:
Stream0128_DS 8.0
END DESCRIPTION:
XS GIS Cut Line= 3
      2018525.01       13898725.        2018925.       13898625.
        2019075.       13898625.
#Sta/Elev= 30
  4587.3 1398.61  4597.6 1397.88  4605.3 1395.71  4610.5 1395.85  4641.2 1391.03
  4651.7  1391.1  4669.8 1387.58  4687.8 1382.14  4692.9 1382.23    4711 1375.85
    4729 1372.49  4775.4 1371.06  4811.5 1367.34  4857.9 1366.58  4875.9 1365.23
  4968.7 1366.35  4976.4  1364.6  5007.3 1361.68  5007.6 1361.18  5011.9 1361.68
  5019.6 1361.78  5029.6  1364.6  5049.6  1362.9  5059.6  1364.8  5069.6 1369.04
  5079.6 1374.68  5089.6 1383.34  5099.6 1390.51  5129.6 1398.22  5149.6 1401.85
#Mann= 4 ,-1 , 0
  4587.3    .035       0  4641.2     .12       0  5007.3     .05       0
  5011.9     .12       0
Bank Sta=5007.3,5011.9
XS Rating Curve= 0 ,0
Exp/Cntr=0.3,0.1

Type RM Length L Ch R = 1 ,4039    ,472,472,472
BEGIN DESCRIPTION:
Stream0128_DS 7.0
END DESCRIPTION:
XS GIS Cut Line= 3
      2018674.96     13899225.03        2018875.       13899075.
      2019125.01       13898925.
#Sta/Elev= 30
    4750 1390.98  4763.6  1390.2  4786.5 1385.46  4792.8 1381.66    4800 1374.31
  4807.3 1369.79  4828.2 1360.57    4850 1359.33  4963.6 1361.62  4971.9 1357.84
  4990.5 1353.83  4990.8 1353.33  4995.1 1353.83  4996.9 1356.83    5003 1356.83
  5007.8 1360.68  5023.4 1360.82    5035  1358.9  5044.7 1358.61  5050.6 1360.56
  5058.4 1361.49  5081.7 1361.21  5103.1 1362.28  5124.4 1366.66  5151.6 1375.48
  5161.4 1377.72  5188.6 1388.05  5233.3 1394.08  5256.6 1399.53  5291.6 1402.97
#Mann= 3 ,-1 , 0
    4750     .12       0  4990.5     .05       0  4995.1     .12       0
Bank Sta=4990.5,4995.1
XS Rating Curve= 0 ,0
Exp/Cntr=0.3,0.1

Type RM Length L Ch R = 1 ,3567    ,444,444,444
BEGIN DESCRIPTION:
Stream0128_DS 6.0
END DESCRIPTION:
XS GIS Cut Line= 3
      2018774.98       13899475.        2019075.       13899425.
      2019375.03     13899274.99
#Sta/Elev= 30
  4705.7 1392.97  4756.4  1389.5  4776.7 1381.06  4794.4 1371.57  4799.5 1370.83
  4807.1  1367.3  4817.2 1365.73  4855.3 1361.21  4976.9 1356.49  4989.6 1350.89
  4997.4 1348.92  4997.7 1348.42  5002.1 1348.92  5012.7 1349.51  5023.8 1354.79
  5046.2 1355.95  5054.6 1354.78  5076.9 1355.01  5090.9 1352.49  5113.3 1354.46
  5121.7 1353.87  5180.4 1355.84  5197.1 1359.26  5225.1 1369.69  5241.9 1379.39
  5247.4 1380.86  5255.8  1390.7  5292.2 1395.59  5308.9 1400.08  5345.3 1402.76
#Mann= 3 ,-1 , 0
  4705.7     .12       0  4997.4     .05       0  5002.1     .12       0
Bank Sta=4997.4,5002.1
XS Rating Curve= 0 ,0
Exp/Cntr=0.3,0.1

Type RM Length L Ch R = 1 ,3123    ,499,499,499
BEGIN DESCRIPTION:
Stream0128_DS 5.0
END DESCRIPTION:
XS GIS Cut Line= 3
      2018875.04     13899924.98        2019225.       13899775.
      2019625.04     13899674.99
#Sta/Elev= 30
  4619.5  1395.3  4686.5 1389.14  4704.7 1384.52  4710.1 1384.41  4771.8 1368.12
  4793.5 1365.29  4804.4 1362.38  4833.4 1357.08  4869.7 1353.01  4902.3  1350.6
  4921.7  1350.3    4922  1349.8  4926.5  1350.3  4967.6 1352.04  5010.6 1350.36
  5134.2 1352.15  5183.2 1354.25  5188.4 1355.44  5216.7 1356.87  5237.3  1359.1
  5265.7 1359.68  5299.2 1371.38  5330.1 1389.89  5348.1 1394.52  5353.3 1394.75
    5361 1398.77  5371.3 1401.95  5389.4 1404.48  5394.5    1404  5412.6 1408.54
#Mann= 3 ,-1 , 0
  4619.5     .12       0  4921.7     .05       0  4926.5     .12       0
Bank Sta=4921.7,4926.5
XS Rating Curve= 0 ,0
Exp/Cntr=0.3,0.1