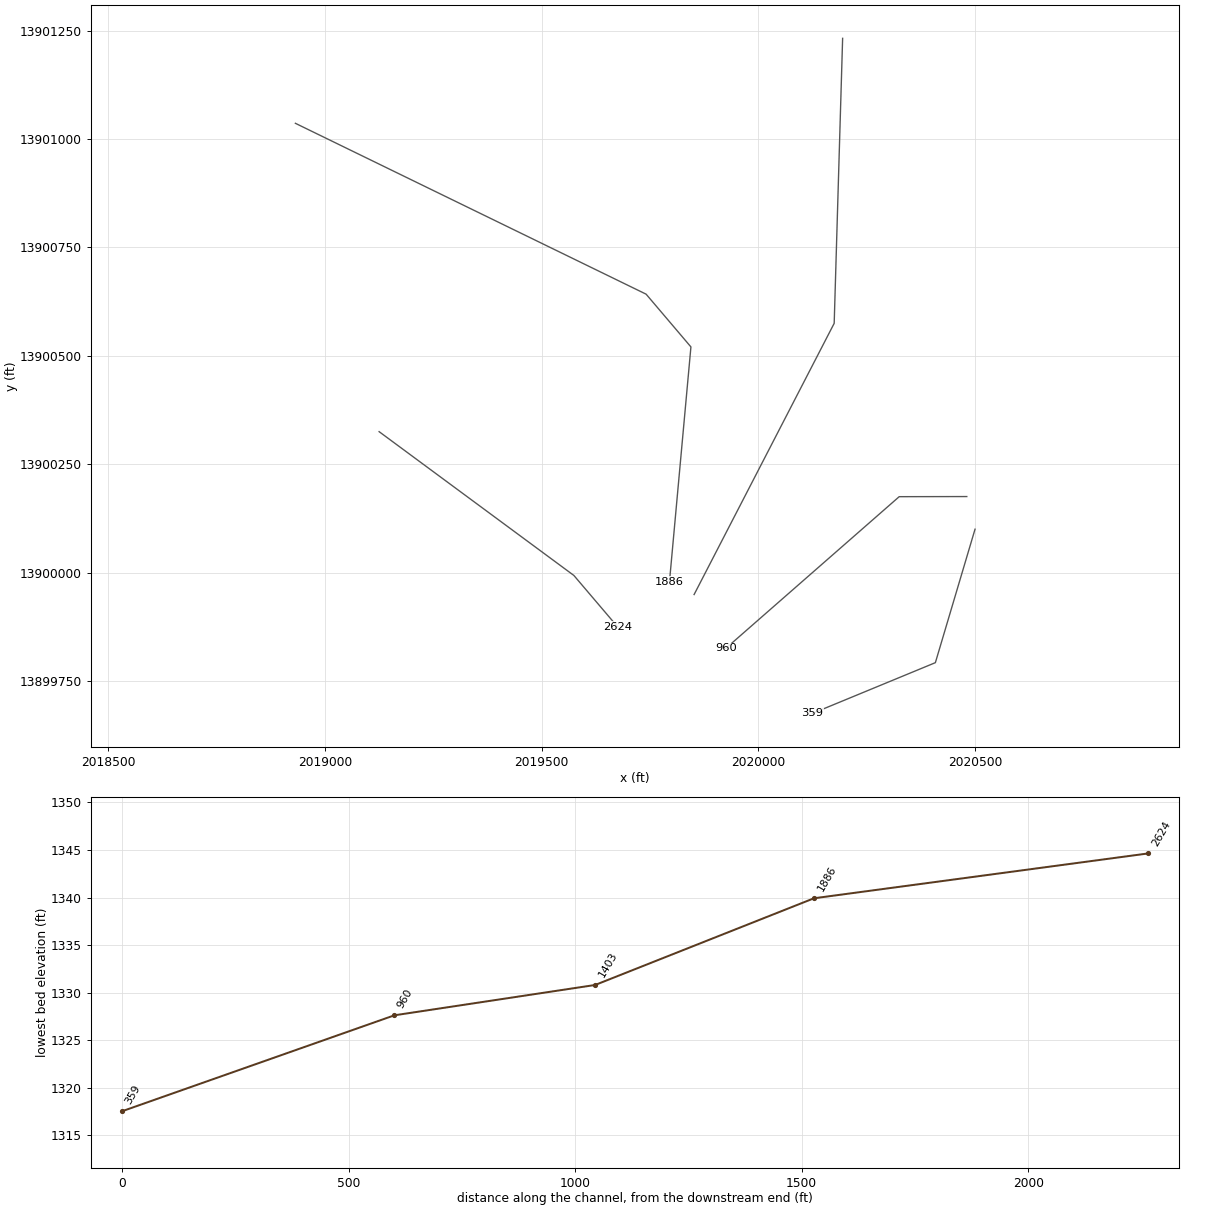
HEC-RAS study Stream0128_DS.prj: Stream0128_DS Base Level Engineering

--- Stream0128_DS.g01 (geometry) --- (continued)

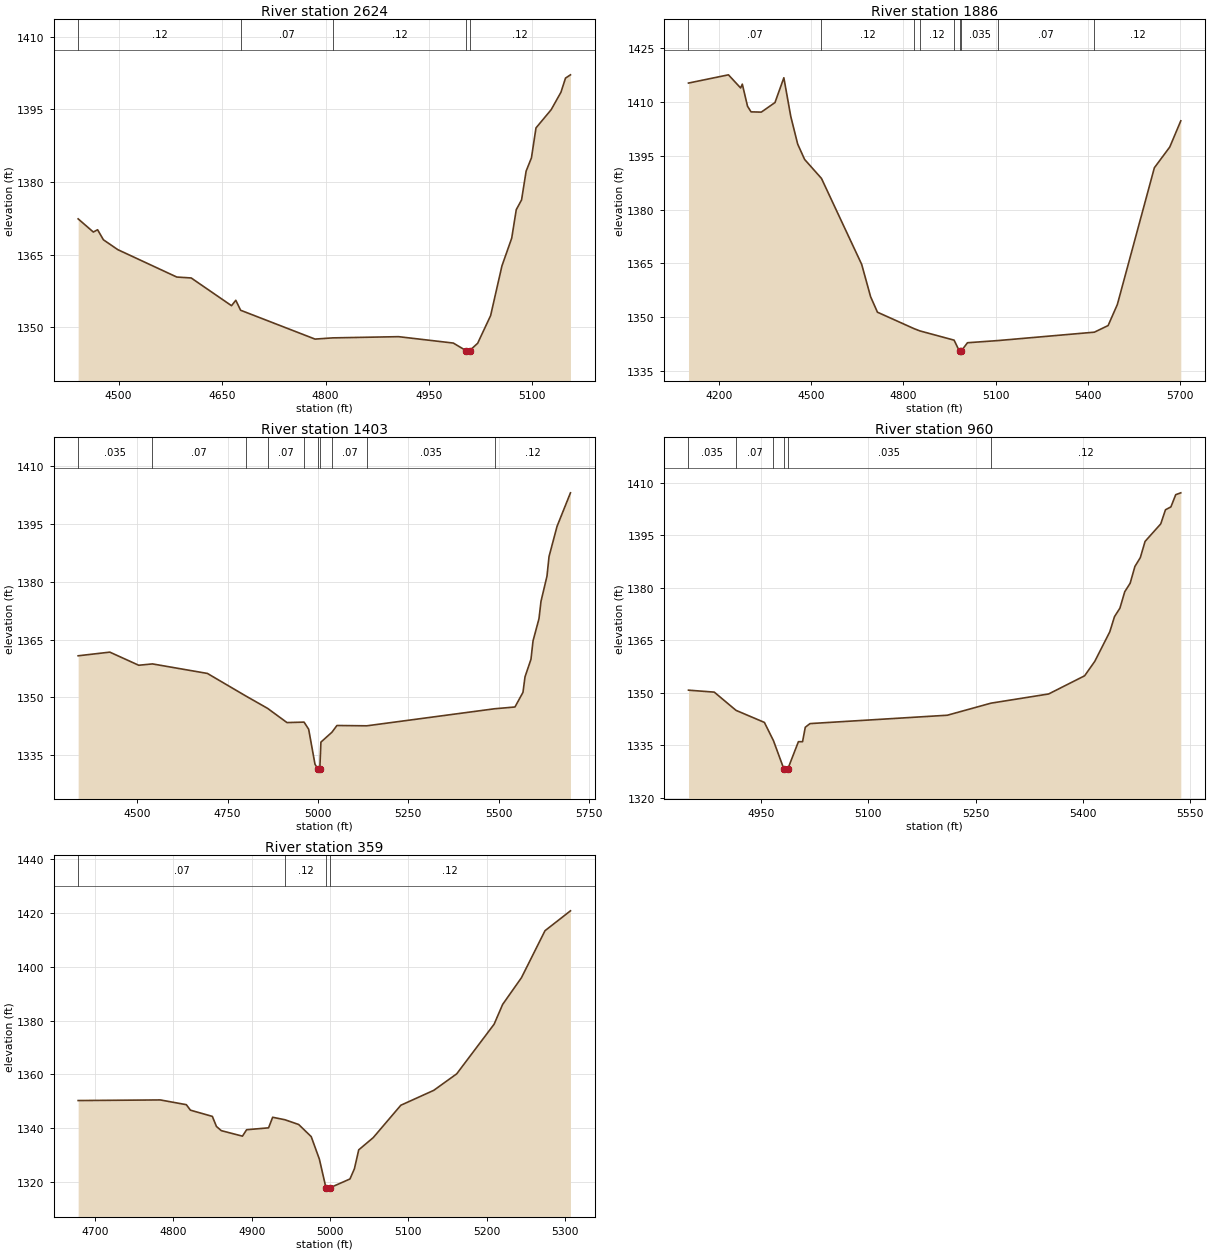
Type RM Length L Ch R = 1 ,2624    ,738,738,738
BEGIN DESCRIPTION:
Stream0128_DS 4.0
END DESCRIPTION:
XS GIS Cut Line= 3
      2019124.98     13900325.01      2019574.45     13899993.16
      2019675.03     13899874.96
#Sta/Elev= 30
  4441.3 1372.38  4463.3 1369.66  4469.5 1370.13  4477.9 1368.06  4498.8 1366.02
  4584.3 1360.36  4605.2 1360.17  4663.7 1354.44  4669.9 1355.56  4676.9  1353.5
  4784.8 1347.54  4810.3 1347.79  4905.9 1348.04  4985.3 1346.72    5004 1345.14
  5004.3 1344.64  5008.8 1345.14  5020.6 1346.67  5039.4 1352.39  5055.8 1362.65
    5070  1368.4  5076.6 1374.28  5084.3  1376.3  5090.9 1382.24  5098.6 1384.98
  5105.2 1391.17  5127.2 1394.93  5141.4 1398.54    5148 1401.46  5155.2 1402.14
#Mann= 5 ,-1 , 0
  4441.3     .12       0  4676.9     .07       0  4810.3     .12       0
    5004     .05       0  5008.8     .12       0
Bank Sta=5004,5008.8
XS Rating Curve= 0 ,0
Exp/Cntr=0.3,0.1

Type RM Length L Ch R = 1 ,1886    ,483,483,483
BEGIN DESCRIPTION:
Stream0128_DS 3.5
END DESCRIPTION:
XS GIS Cut Line= 4
      2018931.79      13901036.5      2019741.06     13900642.23
      2019844.43     13900520.55      2019794.98     13899979.26
#Sta/Elev= 30
  4099.8 1415.32    4230 1417.62  4269.6 1413.95  4275.1 1415.02  4292.1 1408.85
  4303.6 1407.28    4337 1407.21  4381.5 1409.88  4410.4  1416.8  4432.9 1406.02
  4455.4 1398.29    4478    1394  4532.9  1388.7  4663.9  1364.7  4692.9 1355.68
  4715.2 1351.35  4834.3 1346.76  4853.6 1346.12  4964.9 1343.54  4982.5 1340.42
  4982.9 1339.92  4987.4 1340.42  5008.4 1342.82  5108.3 1343.43  5421.8 1345.77
  5466.5 1347.62  5496.6 1353.51  5617.1 1391.67  5667.3 1397.47  5703.2 1404.78
#Mann= 9 ,-1 , 0
  4099.8     .07       0  4532.9     .12       0  4834.3     .07       0
  4853.6     .12       0  4964.9    .035       0  4982.5    .035       0
  4987.4    .035       0  5108.3     .07       0  5421.8     .12       0
Bank Sta=4982.5,4987.4
XS Rating Curve= 0 ,0
Exp/Cntr=0.3,0.1

Type RM Length L Ch R = 1 ,1403    ,443,443,443
BEGIN DESCRIPTION:
Stream0128_DS 3.0
END DESCRIPTION:
XS GIS Cut Line= 3
      2020194.47     13901232.56        2020175.       13900575.
      2019851.78     13899949.19
#Sta/Elev= 30
  4336.4 1360.78    4424 1361.73    4504 1358.32    4542 1358.67  4694.1 1356.19
  4801.1 1350.29  4860.3 1347.13  4914.2 1343.42  4961.5 1343.54  4974.2 1341.69
  4991.7  1332.6    5000  1331.3  5000.4  1330.8    5005  1331.3  5008.1 1338.34
  5038.6 1340.91  5052.4 1342.66  5135.2 1342.58  5488.7 1347.01    5545 1347.47
  5567.2 1351.28  5572.8  1355.3  5589.3 1359.87    5595 1364.64  5611.5 1370.43
  5617.1 1374.96  5633.6 1381.48  5639.3 1386.58  5661.4 1394.41  5698.6 1403.14
#Mann= 10 ,-1 , 0
  4336.4    .035       0    4542     .07       0  4801.1    .035       0
  4860.3     .07       0  4961.5    .035       0    5000    .035       0
    5005    .035       0  5038.6     .07       0  5135.2    .035       0
  5488.7     .12       0
Bank Sta=5000,5005
XS Rating Curve= 0 ,0
Exp/Cntr=0.3,0.1

Type RM Length L Ch R = 1 ,960     ,601,601,601
BEGIN DESCRIPTION:
Stream0128_DS 2.0
END DESCRIPTION:
XS GIS Cut Line= 3
      2020480.97     13900175.28        2020325.       13900175.
      2019924.98     13899824.98
#Sta/Elev= 30
  4849.1 1350.74  4885.1 1350.18  4915.5 1344.97  4955.1 1341.53  4967.8  1336.3
  4982.5 1328.11  4982.9 1327.61  4987.6 1328.11  5002.6 1336.02  5008.4 1336.02
  5012.2 1340.14  5018.8 1341.19  5210.6 1343.58  5271.6 1347.03    5352 1349.65
  5402.3 1354.85  5416.5 1358.98  5437.4  1367.4    5444 1371.74  5451.6 1374.18
  5458.3 1378.85  5465.9 1381.31  5472.5 1386.07  5480.1 1388.63  5486.7 1393.24
  5508.6 1398.25  5515.2 1402.28  5522.8  1403.1  5529.5 1406.59  5536.6 1407.12
#Mann= 6 ,-1 , 0
  4849.1    .035       0  4915.5     .07       0  4967.8    .035       0
  4982.5    .035       0  4987.6    .035       0  5271.6     .12       0
Bank Sta=4982.5,4987.6
XS Rating Curve= 0 ,0
Exp/Cntr=0.3,0.1

Type RM Length L Ch R = 1 ,359     ,0,0,0
BEGIN DESCRIPTION:
Stream0128_DS 1.0
END DESCRIPTION:
XS GIS Cut Line= 3
        2020500.       13900100.      2020408.48     13899792.01
      2020124.98     13899674.99
#Sta/Elev= 30
  4678.7 1350.34  4783.5 1350.57  4816.7 1348.81  4821.9 1346.78  4849.9 1344.47
  4855.1 1340.74  4861.3 1339.19  4888.3 1337.15  4893.6 1339.53  4921.6 1340.23
  4926.8 1344.15  4942.4 1343.23    4960 1341.47    4976 1336.97  4986.4 1328.64
  4994.8 1318.02  4995.2 1317.52  4999.9 1318.02  5025.4 1321.28  5031.1 1325.07
  5036.6 1332.07  5055.1  1336.6  5090.3  1348.6  5132.3 1354.12  5161.6 1360.24
  5209.3 1378.63  5220.2 1385.97  5244.2 1395.87  5274.2 1413.27  5306.7 1420.64
#Mann= 4 ,-1 , 0
  4678.7     .07       0  4942.4     .12       0  4994.8     .05       0
  4999.9     .12       0
Bank Sta=4994.8,4999.9
XS Rating Curve= 0 ,0
Exp/Cntr=0.3,0.1

Chan Stop Cuts=-1
Use User Specified Reach Order=0
Composite Channel Slope=5