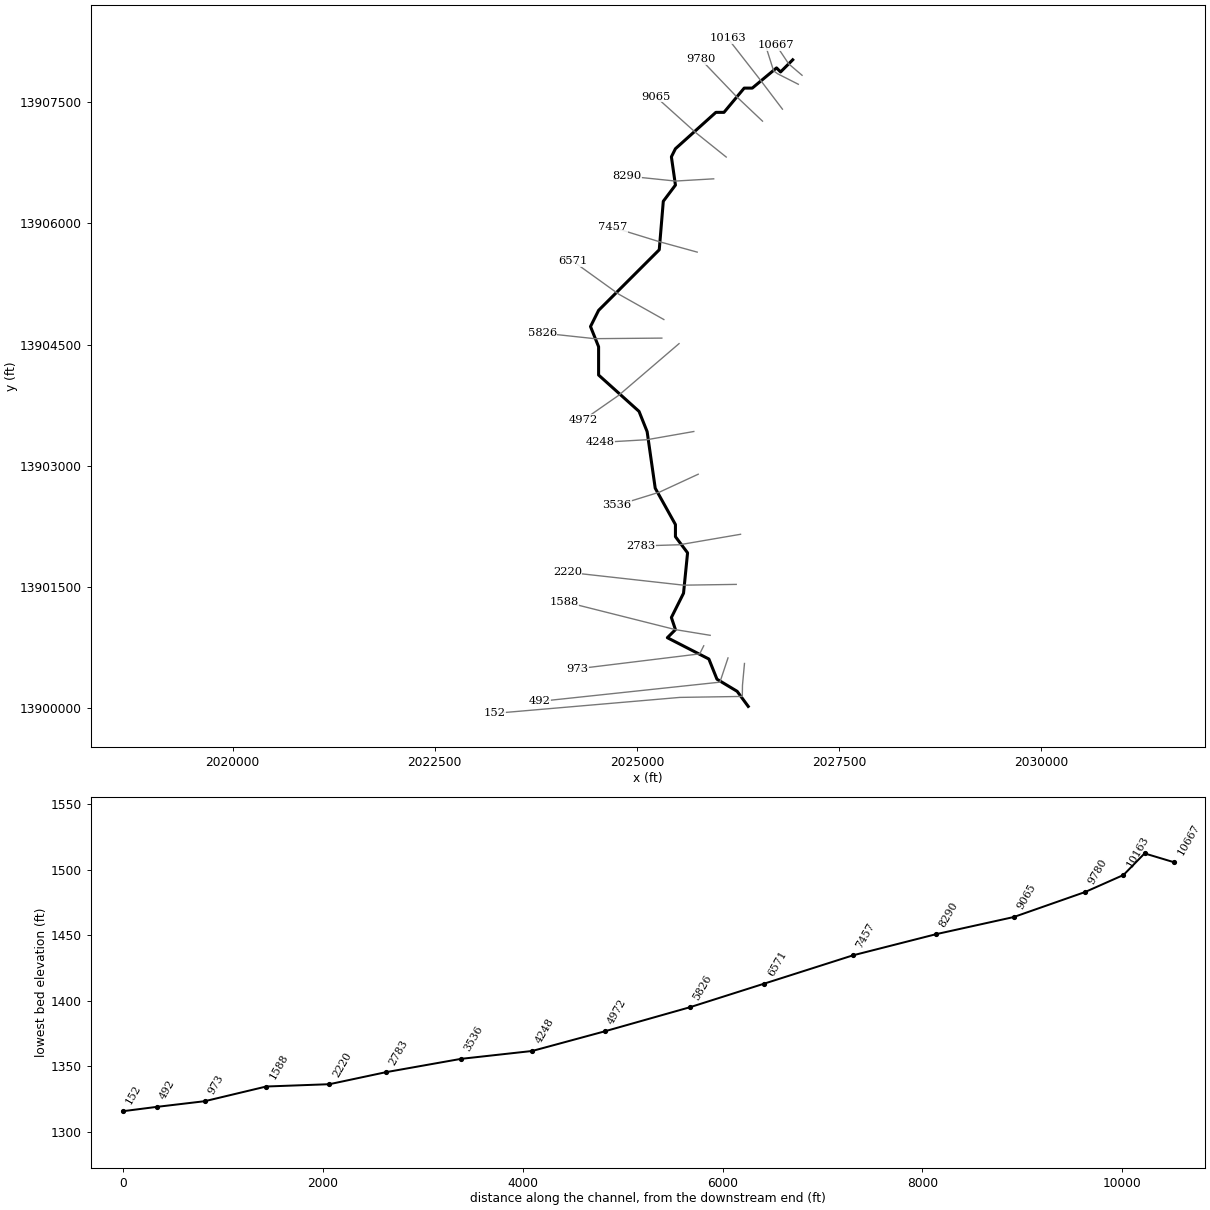
--- Stream0129_DS.prj (project) ---

Proj Title=Stream0129_DS Base Level Engineering
Current Plan=p01
Default Exp/Contr=0.3,0.1
English Units
Geom File=g01
Flow File=f01
Plan File=p01
BEGIN DESCRIPTION:
Stream0129_DS
END DESCRIPTION:

--- Stream0129_DS.p01 (plan) ---

Plan Title=Multiple Run
Short Identifier=Multiple
Geom File=g01
Flow File=f01
Subcritical Flow
K Sum by GR= 0
Std Step Tol= 0.01
Critical Tol= 0.01
Num of Std Step Trials= 20
Max Error Tol= 0.3
Flow Tol Ratio= 0.001
Split Flow NTrial= 30
Split Flow Tol= 0.02
Split Flow Ratio= 0.02
Log Output Level= 0
Friction Slope Method= 1
Unsteady Friction Slope Method= 2
Unsteady Bridges Friction Slope Method= 1
Parabolic Critical Depth
Global Vel Dist=  1 , 1 , 1
Global Log Level= 0
CheckData=True
Encroach Param= -1, 0, 0, 0
BEGIN DESCRIPTION:
Multiple Run
END DESCRIPTION:

--- Stream0129_DS.f01 (steady flow) ---

Flow Title=Multiple
Number of Profiles=7
Profile Names=10-year,25-year,50-year,1pct_min,100-year,1pct_plu,500-year
River Rch & RM= Stream0129_DS,Reach-1,10667
     549     904    1234     821    1638    3267    2844
River Rch & RM= Stream0129_DS,Reach-1,8290
    1122    1927    2704    1842    3675    7333    6713
River Rch & RM= Stream0129_DS,Reach-1,4248
    1840    3241    4625    3196    6376   12723   11999
Boundary for River Rch & Prof#=Stream0129_DS,Reach-1,1
Up Type=0
Dn Type=3
Dn Slope=0.005
Boundary for River Rch & Prof#=Stream0129_DS,Reach-1,2
Up Type=0
Dn Type=3
Dn Slope=0.005
Boundary for River Rch & Prof#=Stream0129_DS,Reach-1,3
Up Type=0
Dn Type=3
Dn Slope=0.005
Boundary for River Rch & Prof#=Stream0129_DS,Reach-1,4
Up Type=0
Dn Type=3
Dn Slope=0.005
Boundary for River Rch & Prof#=Stream0129_DS,Reach-1,5
Up Type=0
Dn Type=3
Dn Slope=0.005
Boundary for River Rch & Prof#=Stream0129_DS,Reach-1,6
Up Type=0
Dn Type=3
Dn Slope=0.005
Boundary for River Rch & Prof#=Stream0129_DS,Reach-1,7
Up Type=0
Dn Type=3
Dn Slope=0.005

--- Stream0129_DS.g01 (geometry) ---

Geom Title=Existing Conditions

River Reach=Stream0129_DS,Reach-1
Reach XY= 30
      2026925.00     13908025.00      2026775.00     13907875.00
      2026725.00     13907925.00      2026425.00     13907675.00
      2026325.00     13907675.00      2026075.00     13907375.00
      2025975.00     13907375.00      2025475.00     13906925.00
      2025425.00     13906825.00      2025475.00     13906475.00
      2025325.00     13906275.00      2025275.00     13905675.00
      2024525.00     13904925.00      2024425.00     13904725.00
      2024525.00     13904475.00      2024525.00     13904125.00
      2025025.00     13903675.00      2025125.00     13903425.00
      2025225.00     13902725.00      2025475.00     13902275.00
      2025475.00     13902125.00      2025625.00     13901925.00
      2025575.00     13901425.00      2025425.00     13901125.00
      2025475.00     13900975.00      2025375.00     13900875.00
      2025888.24     13900611.39      2025988.36     13900361.66
      2026238.22     13900211.38      2026375.00     13900025.00

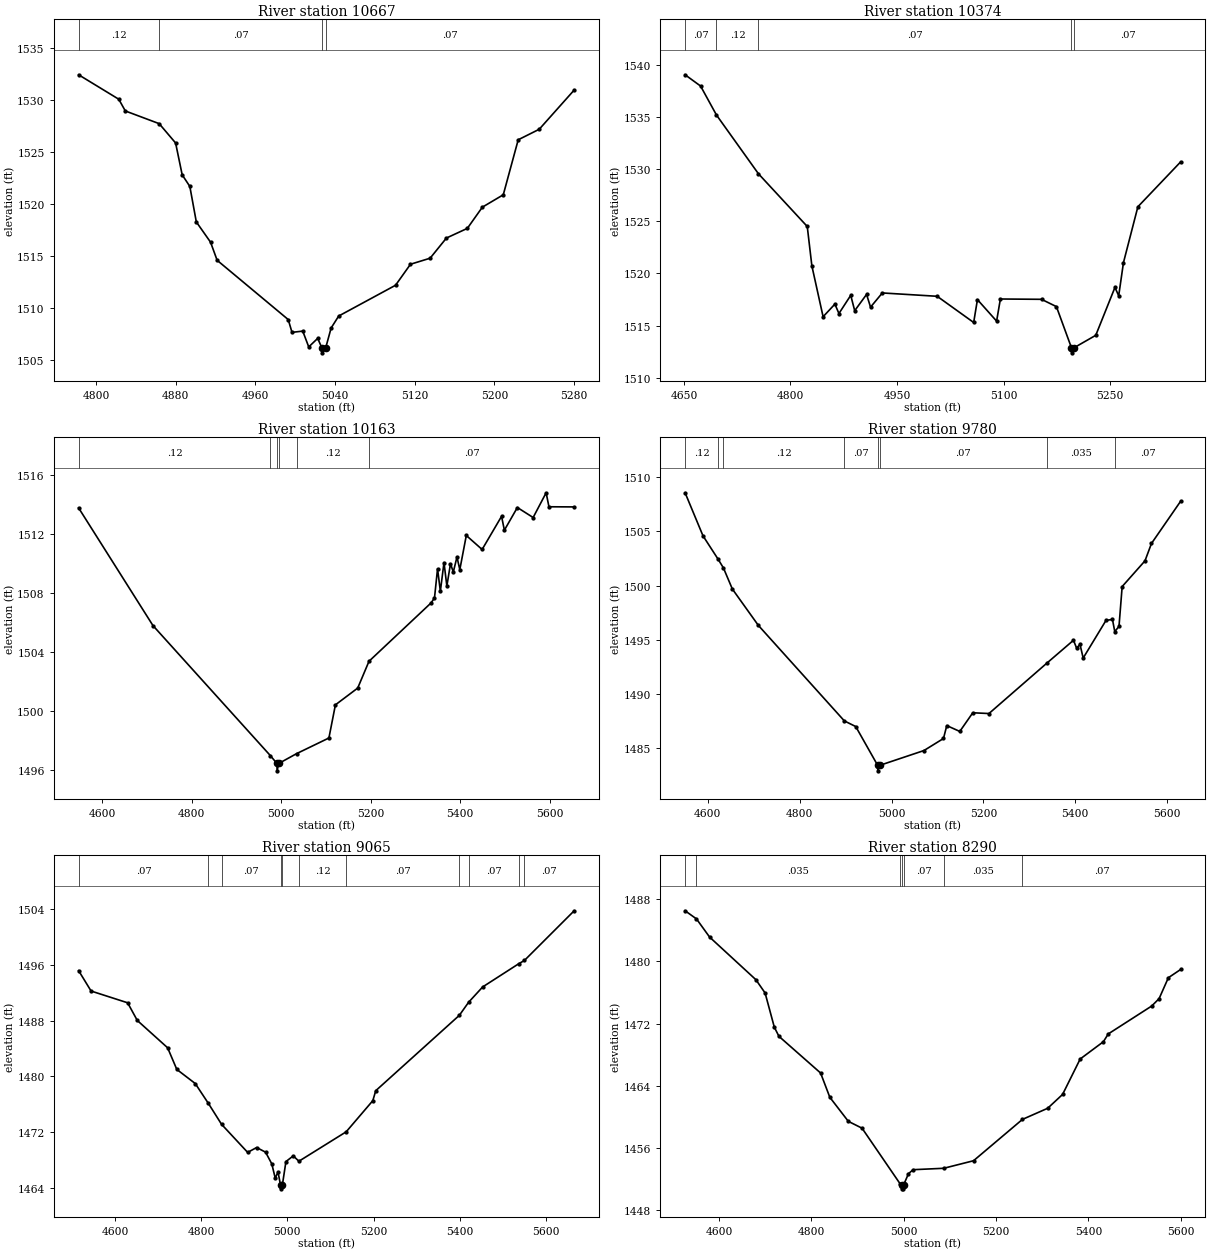
Type RM Length L Ch R = 1,10667,293,293,293
BEGIN DESCRIPTION:
Stream0129_DS 17.0
END DESCRIPTION:
XS GIS Cut Line= 3
      2027040.45     13907833.67      2026875.00     13907975.00
      2026719.86     13908208.21
#Sta/Elev= 30
  4782.4 1532.41  4822.7 1530.06  4829.3 1528.93  4863.3 1527.71  4879.8 1525.85
  4886.4 1522.79  4894.1 1521.67  4900.6 1518.26  4914.9 1516.31  4921.5 1514.57
  4992.9 1508.87  4996.7 1507.64  5007.5 1507.76  5013.5 1506.24  5022.5 1507.06
  5026.6 1506.17  5026.8 1505.67  5030.6 1506.17  5036.0 1508.06  5043.6 1509.21
  5100.7 1512.17  5115.7 1514.19  5135.4 1514.77  5151.8 1516.71  5172.8 1517.64
  5187.9 1519.68  5208.9 1520.87  5223.9 1526.16  5245.0 1527.17  5280.1 1530.94
#Mann=4,-1,0
  4782.4    0.12       0  4863.3    0.07       0  5026.6    0.05       0
  5030.6    0.07       0
Bank Sta=5026.6,5030.6
Exp/Cntr=0.3,0.1

Type RM Length L Ch R = 1,10374,211,211,211
BEGIN DESCRIPTION:
Stream0129_DS 16.0
END DESCRIPTION:
XS GIS Cut Line= 4
      2026994.14     13907722.50      2026736.94     13907853.09
      2026688.78     13907888.78      2026583.20     13908221.74
#Sta/Elev= 30
  4651.6 1539.03  4673.4 1537.95  4695.8 1535.17  4754.9 1529.54  4823.6 1524.49
  4830.1 1520.71  4845.9 1515.84  4862.5 1517.05  4868.2 1516.15  4884.8 1517.89
  4890.4 1516.42  4907.1 1517.98  4912.7 1516.76  4929.3 1518.12  5006.5 1517.80
  5057.9 1515.29  5063.2 1517.48  5090.2 1515.42  5095.5 1517.54  5153.4 1517.51
  5174.4 1516.81  5195.5 1512.88  5195.8 1512.38  5199.5 1512.88  5229.8 1514.06
  5256.8 1518.65  5262.1 1517.85  5268.8 1521.03  5289.1 1526.38  5349.3 1530.68
#Mann=5,-1,0
  4651.6    0.07       0  4695.8    0.12       0  4754.9    0.07       0
  5195.5    0.05       0  5199.5    0.07       0
Bank Sta=5195.5,5199.5
Exp/Cntr=0.3,0.1

Type RM Length L Ch R = 1,10163,383,383,383
BEGIN DESCRIPTION:
Stream0129_DS 15.0
END DESCRIPTION:
XS GIS Cut Line= 3
      2026797.92     13907414.69      2026525.00     13907775.00
      2026122.60     13908290.80
#Sta/Elev= 30
  4548.0 1513.77  4714.0 1505.78  4975.8 1496.96  4990.7 1496.42  4991.0 1495.92
  4994.7 1496.42  5034.7 1497.09  5106.7 1498.15  5121.2 1500.40  5171.0 1501.54
  5196.2 1503.36  5334.7 1507.32  5342.4 1507.66  5349.2 1509.64  5355.5 1508.12
  5363.6 1510.06  5370.0 1508.47  5378.1 1509.98  5384.4 1509.42  5392.6 1510.44
  5398.9 1509.58  5413.4 1511.90  5448.7 1510.95  5492.1 1513.20  5498.4 1512.26
  5527.4 1513.80  5562.6 1513.12  5591.6 1514.80  5597.9 1513.85  5654.2 1513.84
#Mann=6,-1,0
  4548.0    0.12       0  4975.8    0.07       0  4990.7    0.05       0
  4994.7    0.07       0  5034.7    0.12       0  5196.2    0.07       0
Bank Sta=4990.7,4994.7
Exp/Cntr=0.3,0.1

Type RM Length L Ch R = 1,9780,715,715,715
BEGIN DESCRIPTION:
Stream0129_DS 14.0
END DESCRIPTION:
XS GIS Cut Line= 3
      2026551.52     13907266.22      2026225.00     13907575.00
      2025789.75     13908029.64
#Sta/Elev= 30
  4550.6 1508.56  4589.6 1504.59  4622.3 1502.45  4634.1 1501.63  4653.5 1499.69
  4710.1 1496.34  4897.3 1487.54  4922.1 1487.02  4969.9 1483.44  4970.1 1482.94
  4973.9 1483.44  5070.6 1484.81  5113.1 1485.92  5120.3 1487.11  5148.6 1486.57
  5176.9 1488.29  5212.1 1488.22  5338.6 1492.88  5396.1 1494.97  5403.0 1494.24
  5410.3 1494.60  5417.2 1493.33  5466.9 1496.80  5481.0 1496.89  5486.0 1495.77
  5495.2 1496.25  5502.1 1499.92  5551.8 1502.29  5565.9 1503.89  5629.4 1507.78
#Mann=8,-1,0
  4550.6    0.12       0  4622.3   0.035       0  4634.1    0.12       0
  4897.3    0.07       0  4969.9    0.05       0  4973.9    0.07       0
  5338.6   0.035       0  5486.0    0.07       0
Bank Sta=4969.9,4973.9
Exp/Cntr=0.3,0.1

Type RM Length L Ch R = 1,9065,775,775,775
BEGIN DESCRIPTION:
Stream0129_DS 13.0
END DESCRIPTION:
XS GIS Cut Line= 3
      2026102.73     13906822.07      2025725.00     13907125.00
      2025230.27     13907570.27
#Sta/Elev= 30
  4515.8 1495.19  4544.7 1492.26  4629.5 1490.57  4651.9 1488.03  4722.3 1484.10
  4743.6 1480.99  4786.4 1478.96  4816.8 1476.11  4847.4 1473.10  4908.0 1469.06
  4928.8 1469.76  4949.6 1469.09  4964.0 1467.41  4972.0 1465.35  4978.4 1466.25
  4984.4 1464.32  4984.6 1463.82  4988.4 1464.32  4996.8 1467.74  5013.8 1468.56
  5026.9 1467.79  5136.6 1472.02  5198.4 1476.50  5205.2 1477.93  5399.2 1488.77
  5420.7 1490.65  5453.3 1492.85  5536.6 1496.17  5550.2 1496.66  5665.6 1503.80
#Mann=11,-1,0
  4515.8    0.07       0  4816.8   0.035       0  4847.4    0.07       0
  4984.4    0.05       0  4988.4    0.07       0  5026.9    0.12       0
  5136.6    0.07       0  5399.2   0.035       0  5420.7    0.07       0
  5536.6   0.035       0  5550.2    0.07       0
Bank Sta=4984.4,4988.4
Exp/Cntr=0.3,0.1

Type RM Length L Ch R = 1,8290,833,833,833
BEGIN DESCRIPTION:
Stream0129_DS 12.0
END DESCRIPTION:
XS GIS Cut Line= 3
      2025948.00     13906552.60      2025475.00     13906525.00
      2024878.57     13906586.56
#Sta/Elev= 30
  4526.2 1486.49  4550.8 1485.45  4579.3 1483.11  4679.5 1477.64  4699.5 1475.93
  4719.5 1471.53  4729.5 1470.36  4819.7 1465.65  4839.7 1462.53  4879.8 1459.44
  4909.5 1458.56  4992.7 1451.35  4995.5 1451.27  4995.7 1450.77  4999.2 1450.77
  4999.5 1451.27  5010.1 1452.72  5020.1 1453.23  5086.4 1453.41  5151.0 1454.38
  5256.9 1459.69  5311.6 1461.12  5343.9 1462.90  5382.0 1467.45  5432.3 1469.67
  5442.8 1470.67  5536.8 1474.25  5552.9 1475.20  5573.0 1477.89  5599.6 1478.95
#Mann=7,-1,0
  4526.2    0.07       0  4550.8   0.035       0  4992.7    0.07       0
  4995.5    0.05       0  4999.5    0.07       0  5086.4   0.035       0
  5256.9    0.07       0
Bank Sta=4995.5,4999.5
Exp/Cntr=0.3,0.1

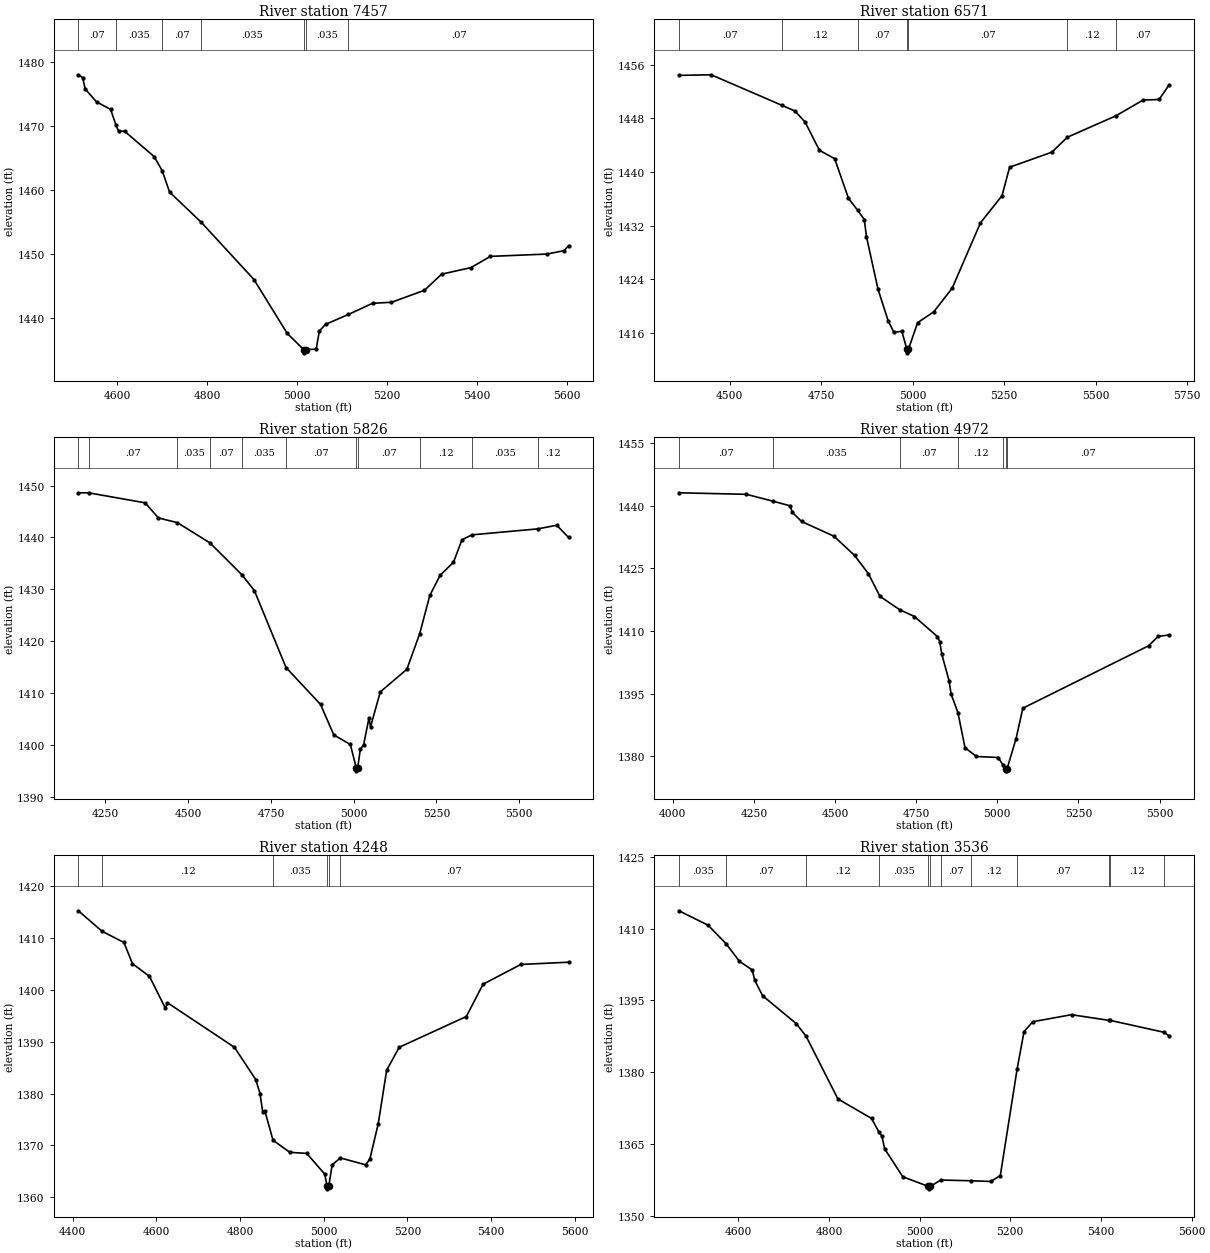
Type RM Length L Ch R = 1,7457,886,886,886
BEGIN DESCRIPTION:
Stream0129_DS 11.0
END DESCRIPTION:
XS GIS Cut Line= 3
      2025744.02     13905645.78      2025275.00     13905775.00
      2024699.00     13905952.76
#Sta/Elev= 30
  4513.5 1478.04  4522.9 1477.61  4528.7 1475.83  4554.0 1473.79  4585.1 1472.64
  4596.6 1470.27  4602.7 1469.25  4616.2 1469.22  4681.8 1465.27  4699.8 1463.05
  4716.2 1459.71  4786.5 1455.00  4903.7 1446.05  4977.6 1437.64  5014.3 1435.10
  5014.6 1434.60  5018.3 1435.10  5041.9 1435.18  5049.0 1438.01  5062.8 1439.05
  5113.7 1440.60  5167.4 1442.34  5209.3 1442.50  5282.6 1444.37  5320.7 1446.89
  5386.0 1447.92  5429.1 1449.67  5554.5 1450.03  5592.4 1450.56  5602.8 1451.33
#Mann=7,-1,0
  4513.5    0.07       0  4596.6   0.035       0  4699.8    0.07       0
  4786.5   0.035       0  5014.3   0.035       0  5018.3   0.035       0
  5113.7    0.07       0
Bank Sta=5014.3,5018.3
Exp/Cntr=0.3,0.1

Type RM Length L Ch R = 1,6571,745,745,745
BEGIN DESCRIPTION:
Stream0129_DS 10.0
END DESCRIPTION:
XS GIS Cut Line= 3
      2025331.79     13904811.66      2024775.00     13905125.00
      2024205.82     13905534.70
#Sta/Elev= 30
  4361.1 1454.38  4449.2 1454.47  4641.8 1449.94  4678.5 1449.06  4705.9 1447.43
  4745.1 1443.22  4786.8 1441.97  4824.4 1436.08  4849.7 1434.28  4867.8 1432.90
  4873.8 1430.33  4905.4 1422.51  4932.8 1417.86  4948.7 1416.11  4970.4 1416.27
  4984.3 1413.55  4984.5 1413.05  4988.3 1413.55  5013.5 1417.54  5057.7 1419.16
  5108.0 1422.68  5185.4 1432.42  5244.2 1436.45  5265.1 1440.70  5380.5 1442.94
  5423.1 1445.17  5556.5 1448.38  5629.7 1450.70  5673.8 1450.79  5701.3 1452.97
#Mann=7,-1,0
  4361.1    0.07       0  4641.8    0.12       0  4849.7    0.07       0
  4984.3    0.05       0  4988.3    0.07       0  5423.1    0.12       0
  5556.5    0.07       0
Bank Sta=4984.3,4988.3
Exp/Cntr=0.3,0.1

Type RM Length L Ch R = 1,5826,854,854,854
BEGIN DESCRIPTION:
Stream0129_DS 9.0
END DESCRIPTION:
XS GIS Cut Line= 3
      2025306.87     13904581.83      2024475.00     13904575.00
      2023829.21     13904644.32
#Sta/Elev= 30
  4168.1 1448.60  4199.4 1448.59  4370.0 1446.66  4410.0 1443.75  4467.0 1442.85
  4565.6 1438.95  4662.3 1432.80  4700.0 1429.74  4795.6 1414.92  4900.0 1407.80
  4940.0 1401.92  4990.0 1400.08  5008.1 1395.50  5008.3 1395.00  5012.1 1395.50
  5020.1 1399.14  5030.2 1400.03  5046.1 1405.12  5051.1 1403.50  5080.5 1410.22
  5160.9 1414.58  5199.4 1421.40  5230.3 1428.83  5261.5 1432.71  5301.7 1435.21
  5327.4 1439.54  5357.3 1440.49  5556.2 1441.64  5613.8 1442.34  5649.5 1439.99
#Mann=11,-1,0
  4168.1    0.12       0  4199.4    0.07       0  4467.0   0.035       0
  4565.6    0.07       0  4662.3   0.035       0  4795.6    0.07       0
  5008.1    0.05       0  5012.1    0.07       0  5199.4    0.12       0
  5357.3   0.035       0  5556.2    0.12       0
Bank Sta=5008.1,5012.1
Exp/Cntr=0.3,0.1

Type RM Length L Ch R = 1,4972,724,724,724
BEGIN DESCRIPTION:
Stream0129_DS 8.0
END DESCRIPTION:
XS GIS Cut Line= 3
      2025519.54     13904513.46      2024775.00     13903875.00
      2024340.54     13903571.80
#Sta/Elev= 30
  4019.2 1443.08  4226.8 1442.71  4310.0 1441.05  4361.8 1439.95  4368.4 1438.40
  4396.9 1436.22  4496.8 1432.69  4560.4 1428.09  4603.2 1423.69  4638.4 1418.32
  4698.9 1415.13  4744.8 1413.48  4815.6 1408.69  4822.7 1407.48  4829.3 1404.42
  4851.3 1398.17  4857.9 1394.91  4878.8 1390.51  4900.7 1382.10  4935.8 1380.00
  5003.0 1379.76  5017.7 1377.95  5026.3 1377.07  5026.6 1376.57  5030.3 1377.07
  5058.0 1384.29  5078.9 1391.55  5466.3 1406.48  5495.9 1408.73  5529.8 1409.07
#Mann=7,-1,0
  4019.2    0.07       0  4310.0   0.035       0  4698.9    0.07       0
  4878.8    0.12       0  5017.7    0.07       0  5026.3    0.05       0
  5030.3    0.07       0
Bank Sta=5026.3,5030.3
Exp/Cntr=0.3,0.1

Type RM Length L Ch R = 1,4248,712,712,712
BEGIN DESCRIPTION:
Stream0129_DS 7.0
END DESCRIPTION:
XS GIS Cut Line= 3
      2025702.27     13903426.36      2025125.00     13903325.00
      2024541.19     13903290.99
#Sta/Elev= 30
  4413.9 1415.29  4470.4 1411.34  4522.8 1409.17  4543.1 1405.07  4583.7 1402.64
  4621.7 1396.48  4626.8 1397.53  4786.8 1388.93  4837.6 1382.70  4847.7 1380.01
  4854.1 1376.53  4859.2 1376.71  4878.8 1371.00  4918.8 1368.66  4959.4 1368.45
  5002.5 1364.44  5008.0 1362.11  5008.3 1361.61  5012.0 1362.11  5020.0 1366.22
  5039.5 1367.58  5100.2 1366.25  5110.2 1367.37  5130.2 1374.18  5150.3 1384.52
  5180.3 1388.94  5340.6 1394.88  5380.6 1401.12  5470.8 1404.93  5584.8 1405.36
#Mann=6,-1,0
  4413.9    0.07       0  4470.4    0.12       0  4878.8   0.035       0
  5008.0   0.035       0  5012.0   0.035       0  5039.5    0.07       0
Bank Sta=5008,5012
Exp/Cntr=0.3,0.1

Type RM Length L Ch R = 1,3536,753,753,753
BEGIN DESCRIPTION:
Stream0129_DS 6.0
END DESCRIPTION:
XS GIS Cut Line= 3
      2025756.67     13902897.80      2025275.00     13902675.00
      2024749.29     13902511.99
#Sta/Elev= 30
  4469.3 1413.72  4533.6 1410.70  4573.5 1406.81  4602.4 1403.18  4630.8 1401.35
  4636.4 1399.19  4653.8 1395.96  4728.1 1390.13  4749.8 1387.47  4819.8 1374.39
  4894.1 1370.31  4910.5 1367.42  4917.0 1366.57  4922.9 1363.96  4962.9 1358.13
  5019.5 1356.10  5019.8 1355.60  5023.5 1356.10  5046.6 1357.44  5112.9 1357.29
  5157.1 1357.14  5178.0 1358.37  5215.1 1380.66  5230.3 1388.47  5249.6 1390.53
  5335.0 1392.00  5418.0 1390.81  5419.5 1390.83  5538.6 1388.33  5550.4 1387.57
#Mann=12,-1,0
  4469.3   0.035       0  4573.5    0.07       0  4749.8    0.12       0
  4910.5   0.035       0  5019.5   0.035       0  5023.5   0.035       0
  5046.6    0.07       0  5112.9    0.12       0  5215.1    0.07       0
  5418.0   0.035       0  5419.5    0.12       0  5538.6    0.07       0
Bank Sta=5019.5,5023.5
Exp/Cntr=0.3,0.1

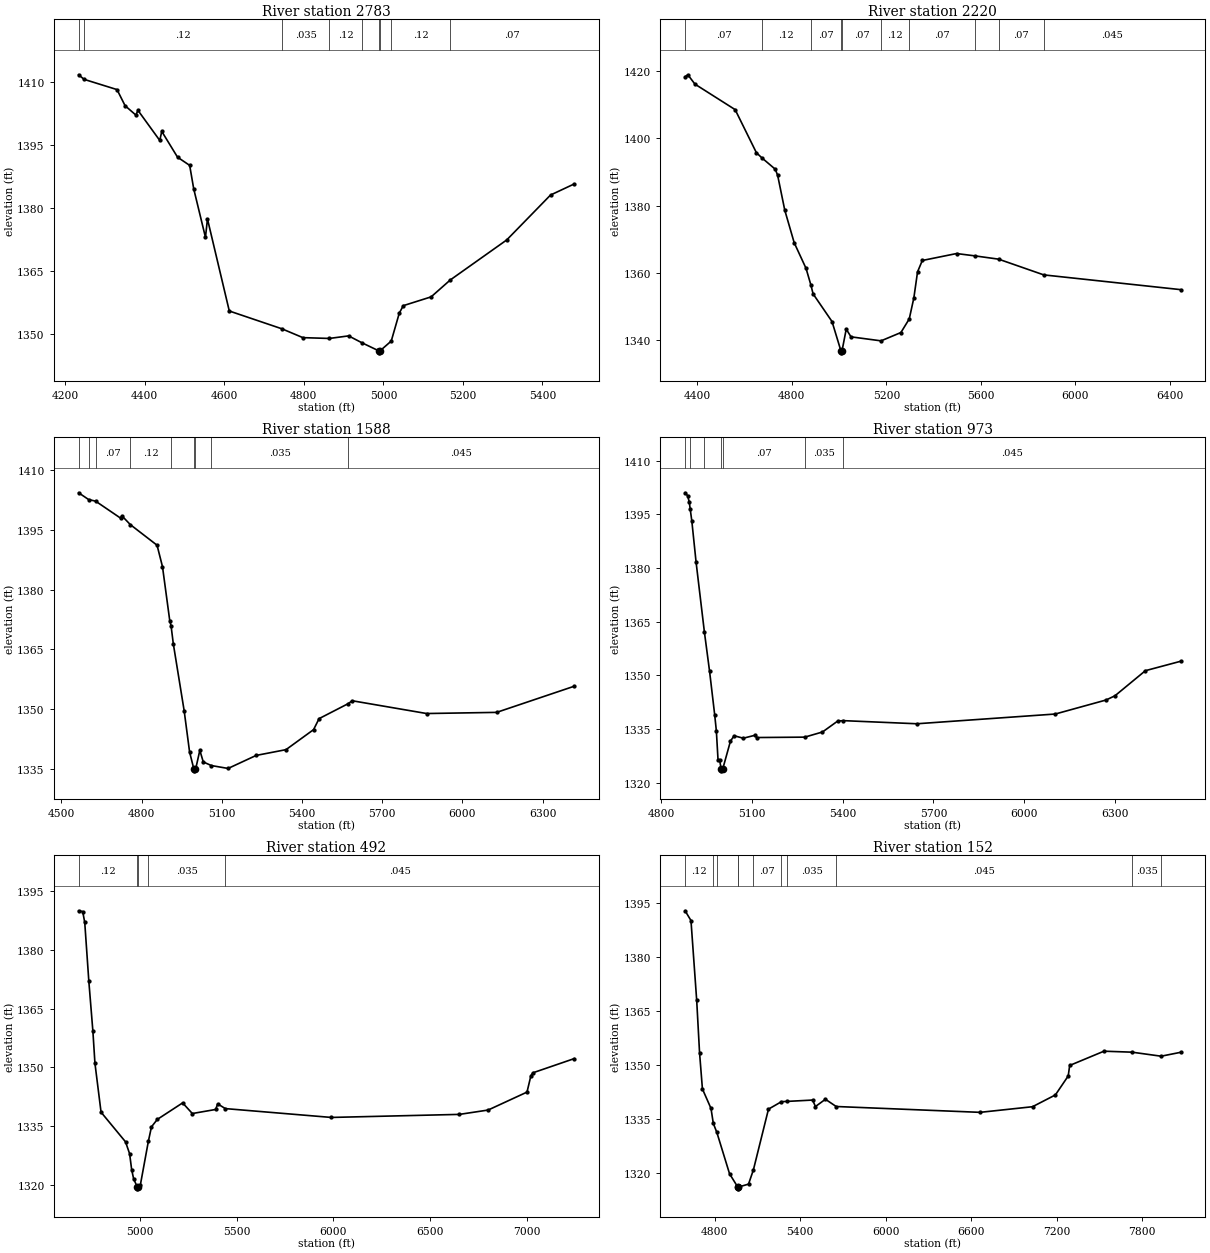
Type RM Length L Ch R = 1,2783,563,563,563
BEGIN DESCRIPTION:
Stream0129_DS 5.0
END DESCRIPTION:
XS GIS Cut Line= 3
      2026280.15     13902154.67      2025525.00     13902025.00
      2025045.52     13902010.32
#Sta/Elev= 30
  4233.8 1411.66  4247.5 1410.57  4330.3 1408.13  4350.6 1404.29  4377.8 1402.05
  4382.9 1403.19  4437.8 1396.01  4442.8 1398.17  4482.5 1392.02  4513.0 1390.07
  4523.1 1384.50  4552.7 1372.92  4557.7 1377.31  4612.6 1355.37  4744.8 1351.13
  4797.7 1349.02  4864.2 1348.83  4912.6 1349.44  4945.4 1347.83  4987.9 1345.90
  4988.1 1345.40  4991.9 1345.90  5019.8 1348.21  5040.0 1354.86  5050.0 1356.64
  5120.1 1358.74  5168.4 1362.78  5310.1 1372.30  5420.2 1383.00  5479.7 1385.64
#Mann=9,-1,0
  4233.8    0.07       0  4247.5    0.12       0  4744.8   0.035       0
  4864.2    0.12       0  4945.4   0.035       0  4987.9   0.035       0
  4991.9   0.035       0  5019.8    0.12       0  5168.4    0.07       0
Bank Sta=4987.9,4991.9
Exp/Cntr=0.3,0.1

Type RM Length L Ch R = 1,2220,632,632,632
BEGIN DESCRIPTION:
Stream0129_DS 4.0
END DESCRIPTION:
XS GIS Cut Line= 3
      2026226.73     13901534.62      2025575.00     13901525.00
      2024138.41     13901685.23
#Sta/Elev= 30
  4348.2 1418.27  4359.9 1418.84  4389.9 1416.06  4560.0 1408.49  4650.0 1395.69
  4673.1 1394.17  4730.0 1390.78  4740.0 1388.95  4770.0 1378.64  4810.0 1368.95
  4860.0 1361.36  4880.1 1356.53  4890.0 1353.76  4970.0 1345.56  5008.1 1336.76
  5008.3 1336.26  5012.1 1336.76  5030.2 1343.30  5050.3 1341.01  5177.5 1339.82
  5261.6 1342.29  5296.9 1346.33  5316.4 1352.59  5332.0 1360.31  5352.2 1363.69
  5497.1 1365.75  5575.6 1365.05  5675.1 1364.08  5866.2 1359.41  6445.5 1355.03
#Mann=10,-1,0
  4348.2    0.07       0  4673.1    0.12       0  4880.1    0.07       0
  5008.1    0.05       0  5012.1    0.07       0  5177.5    0.12       0
  5296.9    0.07       0  5575.6   0.035       0  5675.1    0.07       0
  5866.2   0.045       0
Bank Sta=5008.1,5012.1
Exp/Cntr=0.3,0.1

Type RM Length L Ch R = 1,1588,615,615,615
BEGIN DESCRIPTION:
Stream0129_DS 3.0
END DESCRIPTION:
XS GIS Cut Line= 3
      2025904.48     13900904.66      2025475.00     13900975.00
      2024099.97     13901321.02
#Sta/Elev= 30
  4564.8 1404.32  4601.9 1402.63  4628.4 1402.21  4721.5 1397.96  4726.5 1398.54
  4758.0 1396.33  4858.1 1391.15  4878.4 1385.76  4905.5 1372.24  4910.4 1370.95
  4918.9 1366.38  4959.5 1349.56  4979.7 1339.24  4995.5 1335.00  4995.7 1334.50
  4999.5 1335.00  5002.6 1335.00  5018.0 1339.65  5030.9 1336.74  5060.9 1335.83
  5123.7 1335.10  5228.7 1338.37  5340.3 1339.82  5443.4 1344.85  5464.0 1347.61
  5573.1 1351.38  5587.8 1352.10  5866.2 1348.89  6128.0 1349.18  6417.9 1355.74
#Mann=9,-1,0
  4564.8    0.07       0  4601.9    0.12       0  4628.4    0.07       0
  4758.0    0.12       0  4910.4    0.07       0  4995.5    0.05       0
  4999.5    0.07       0  5060.9   0.035       0  5573.1   0.045       0
Bank Sta=4995.5,4999.5
Exp/Cntr=0.3,0.1

Type RM Length L Ch R = 1,973,481,481,481
BEGIN DESCRIPTION:
Stream0129_DS 2.0
END DESCRIPTION:
XS GIS Cut Line= 3
      2025824.99     13900774.98      2025775.00     13900675.00
      2024259.39     13900489.50
#Sta/Elev= 30
  4878.6 1401.02  4887.0 1400.20  4892.5 1398.36  4895.6 1396.41  4900.9 1393.08
  4914.9 1381.65  4942.3 1362.18  4959.6 1351.08  4976.4 1339.00  4982.0 1334.44
  4987.6 1326.22  4992.9 1326.22  4998.0 1323.79  4998.4 1323.29  5003.0 1323.79
  5028.6 1331.59  5040.7 1333.10  5071.0 1332.41  5110.0 1333.24  5115.1 1332.60
  5274.2 1332.71  5332.9 1334.15  5383.3 1337.21  5402.2 1337.32  5645.2 1336.45
  6102.6 1339.17  6270.6 1343.09  6300.1 1344.27  6400.8 1351.29  6517.3 1353.92
#Mann=7,-1,0
  4878.6    0.07       0  4895.6    0.12       0  4942.3    0.07       0
  4998.0    0.05       0  5003.0    0.07       0  5274.2   0.035       0
  5402.2   0.045       0
Bank Sta=4998,5003
Exp/Cntr=0.3,0.1

Type RM Length L Ch R = 1,492,340,340,340
BEGIN DESCRIPTION:
Stream0129_DS 1.0
END DESCRIPTION:
XS GIS Cut Line= 3
      2026124.99     13900624.98      2026025.00     13900325.00
      2023792.58     13900086.80
#Sta/Elev= 30
  4683.2 1390.06  4704.3 1389.86  4714.8 1387.07  4735.9 1372.06  4757.0 1359.19
  4767.5 1351.06  4799.1 1338.55  4925.6 1330.97  4946.7 1327.93  4957.2 1323.89
  4967.8 1321.44  4986.4 1319.45  4986.7 1318.95  4991.4 1319.45  5001.9 1319.85
  5043.9 1331.18  5059.7 1334.80  5089.9 1336.71  5220.7 1340.93  5270.9 1338.21
  5391.6 1339.25  5401.7 1340.68  5441.5 1339.47  5989.5 1337.21  6651.3 1337.99
  6799.6 1339.10  7000.7 1343.69  7020.8 1347.87  7030.9 1348.62  7244.5 1352.25
#Mann=5,-1,0
  4683.2    0.12       0  4986.4    0.05       0  4991.4    0.12       0
  5043.9   0.035       0  5441.5   0.045       0
Bank Sta=4986.4,4991.4
Exp/Cntr=0.3,0.1

Type RM Length L Ch R = 1,152,0,0,0
BEGIN DESCRIPTION:
Stream0129_DS 0.0
END DESCRIPTION:
XS GIS Cut Line= 5
      2026328.61     13900556.16      2026303.84     13900285.56
      2026301.73     13900148.40      2025529.54     13900136.38
      2023238.33     13899938.75
#Sta/Elev= 30
  4591.1 1392.80  4632.4 1390.09  4672.6 1367.90  4692.7 1353.38  4712.8 1343.35
  4773.0 1337.95  4789.4 1333.77  4814.2 1331.28  4903.4 1319.81  4960.9 1316.13
  4961.2 1315.63  4965.9 1316.13  5036.7 1316.94  5070.9 1320.90  5176.8 1337.75
  5268.0 1339.82  5309.4 1339.90  5486.8 1340.27  5506.8 1338.47  5576.8 1340.49
  5652.4 1338.48  6663.1 1336.86  7031.5 1338.42  7192.1 1341.69  7282.4 1346.96
  7292.5 1349.87  7533.3 1353.83  7730.2 1353.56  7935.0 1352.44  8072.0 1353.52
#Mann=11,-1,0
  4591.1    0.12       0  4789.4    0.07       0  4814.2   0.035       0
  4960.9   0.035       0  4965.9   0.035       0  5070.9    0.07       0
  5268.0    0.12       0  5309.4   0.035       0  5652.4   0.045       0
  7730.2   0.035       0  7935.0    0.07       0
Bank Sta=4960.9,4965.9
Exp/Cntr=0.3,0.1

Chan Stop Cuts=-1