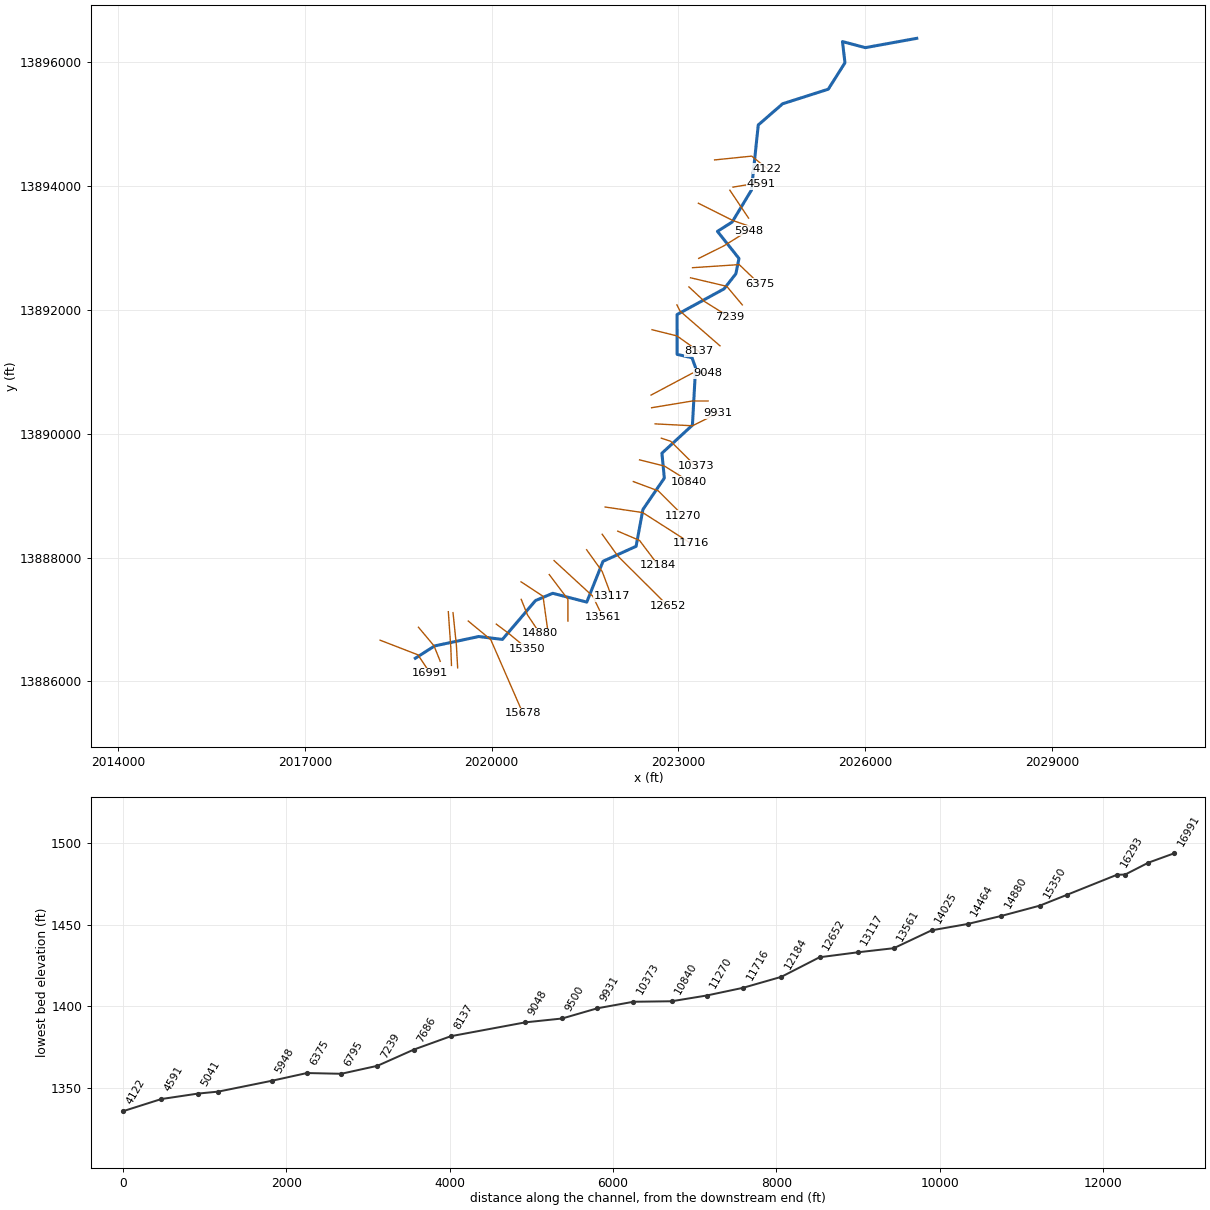
--- Stream0130_DS.prj (project) ---

Proj Title=Stream0130_DS Base Level Engineering
Current Plan=p01
Default Exp/Contr=0.3,0.1
English Units
Geom File=g01
Flow File=f01
Plan File=p01
BEGIN DESCRIPTION:
Stream0130_DS
END DESCRIPTION:

--- Stream0130_DS.p01 (plan) ---

Plan Title=Multiple Run
Short Identifier=Multiple
Geom File=g01
Flow File=f01
Subcritical Flow
K Sum by GR= 0
Std Step Tol= 0.01
Critical Tol= 0.01
Num of Std Step Trials= 20
Max Error Tol= 0.3
Flow Tol Ratio= 0.001
Split Flow NTrial= 30
Split Flow Tol= 0.02
Split Flow Ratio= 0.02
Log Output Level= 0
Friction Slope Method= 1
Unsteady Friction Slope Method= 2
Unsteady Bridges Friction Slope Method= 1
Parabolic Critical Depth
Global Vel Dist=  1 , 1 , 1
Global Log Level= 0
CheckData=True
Encroach Param= -1, 0, 0, 0
BEGIN DESCRIPTION:
Multiple Run
END DESCRIPTION:

--- Stream0130_DS.f01 (steady flow) ---

Flow Title=Multiple
Number of Profiles=7
Profile Names=10-year,25-year,50-year,1pct_min,100-year,1pct_plu,500-year
River Rch & RM= Stream0130_DS,Reach-1,16991
     623    1027    1404     933    1861    3714    3231
River Rch & RM= Stream0130_DS,Reach-1,16680
    1387    2404    3393    2321    4631    9241    8538
River Rch & RM= Stream0130_DS,Reach-1,14025
    2039    3594    5130    3542    7068   14102   13284
River Rch & RM= Stream0130_DS,Reach-1,9500
    2483    4394    6286    4345    8668   17296   16329
Boundary for River Rch & Prof#=Stream0130_DS,Reach-1,1
Up Type=0
Dn Type=3
Dn Slope=0.005
Boundary for River Rch & Prof#=Stream0130_DS,Reach-1,2
Up Type=0
Dn Type=3
Dn Slope=0.005
Boundary for River Rch & Prof#=Stream0130_DS,Reach-1,3
Up Type=0
Dn Type=3
Dn Slope=0.005
Boundary for River Rch & Prof#=Stream0130_DS,Reach-1,4
Up Type=0
Dn Type=3
Dn Slope=0.005
Boundary for River Rch & Prof#=Stream0130_DS,Reach-1,5
Up Type=0
Dn Type=3
Dn Slope=0.005
Boundary for River Rch & Prof#=Stream0130_DS,Reach-1,6
Up Type=0
Dn Type=3
Dn Slope=0.005
Boundary for River Rch & Prof#=Stream0130_DS,Reach-1,7
Up Type=0
Dn Type=3
Dn Slope=0.005

--- Stream0130_DS.g01 (geometry) ---

Geom Title=Existing Conditions

River Reach=Stream0130_DS,Reach-1
Reach XY= 30
      2018775.00     13886375.00      2019085.50     13886573.78
      2019793.43     13886725.19      2020173.54     13886678.54
      2020704.52     13887305.38      2020980.97     13887422.83
      2021527.47     13887280.45      2021788.37     13887938.32
      2022319.39     13888180.59      2022428.54     13888773.54
      2022772.76     13889280.93      2022734.15     13889681.73
      2023223.96     13890135.44      2023274.76     13891060.90
      2023217.14     13891222.34      2022978.61     13891276.48
      2022977.04     13891919.15      2023731.06     13892333.14
      2023921.18     13892576.58      2023971.55     13892823.52
      2023625.53     13893261.13      2023861.38     13893410.98
      2024171.25     13893926.55      2024280.83     13894977.30
      2024672.55     13895319.53      2025405.16     13895554.61
      2025672.91     13895980.49      2025633.09     13896322.53
      2026000.12     13896224.71      2026825.00     13896375.00

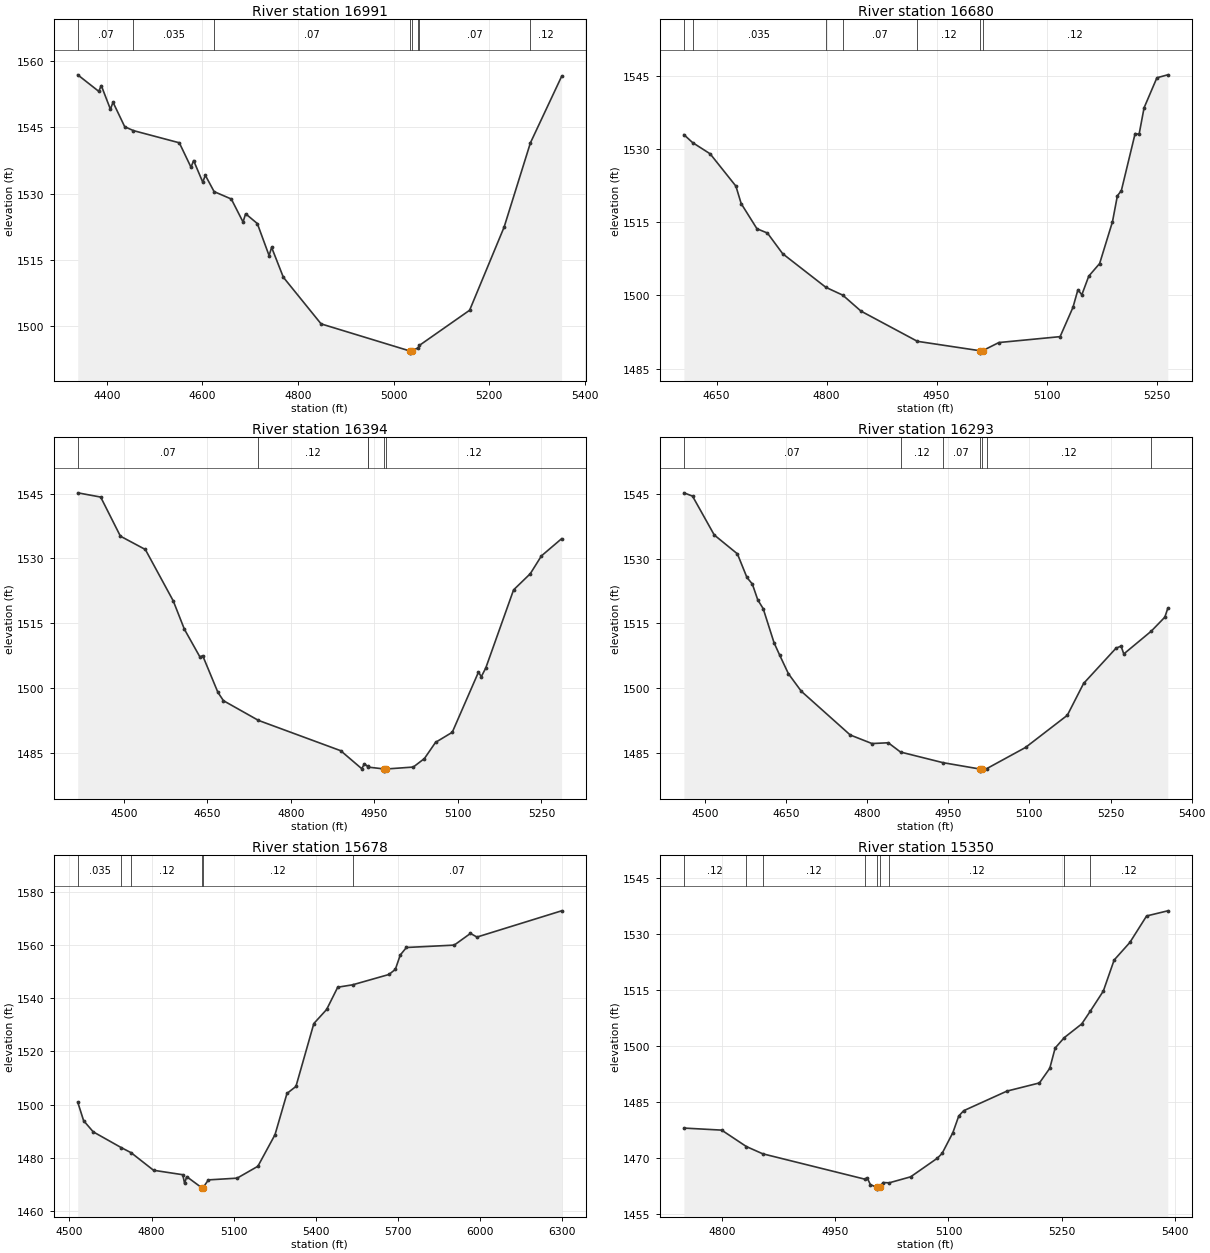
Type RM Length L Ch R = 1,16991,311,311,311
BEGIN DESCRIPTION:
Stream0130_DS 37.0
END DESCRIPTION:
XS GIS Cut Line= 3
      2018209.59     13886666.12      2018817.45     13886429.67
      2019016.11     13886129.48
#Sta/Elev= 30
  4339.0 1556.93  4382.9 1553.19  4388.3 1554.49  4407.4 1549.12  4412.8 1550.72
  4437.3 1545.16  4455.6 1544.28  4551.5 1541.52  4576.0 1535.97  4581.4 1537.50
  4600.5 1532.60  4605.9 1534.16  4624.3 1530.45  4660.3 1528.77  4684.8 1523.56
  4690.2 1525.43  4714.7 1523.21  4739.3 1515.95  4744.6 1517.81  4769.1 1511.04
  4848.1 1500.46  5033.4 1494.33  5033.7 1493.83  5037.4 1494.33  5051.1 1495.03
  5053.8 1495.59  5158.8 1503.55  5231.0 1522.41  5286.0 1541.51  5351.2 1556.56
#Mann=8,-1,0
  4339.0    0.07       0  4455.6   0.035       0  4624.3    0.07       0
  5033.4    0.05       0  5037.4    0.07       0  5051.1    0.12       0
  5053.8    0.07       0  5286.0    0.12       0
Bank Sta=5033.4,5037.4
Exp/Cntr=0.3,0.1

Type RM Length L Ch R = 1,16680,286,286,286
BEGIN DESCRIPTION:
Stream0130_DS 36.0
END DESCRIPTION:
XS GIS Cut Line= 3
      2018825.00     13886875.00      2019075.00     13886575.00
      2019175.01     13886324.97
#Sta/Elev= 30
  4605.4 1532.96  4617.2 1531.34  4641.2 1529.03  4676.3 1522.41  4683.5 1518.83
  4705.0 1513.67  4719.3 1512.79  4740.1 1508.55  4799.0 1501.66  4822.0 1500.06
  4846.9 1496.78  4923.8 1490.59  5008.7 1488.67  5009.0 1488.17  5012.7 1488.67
  5034.9 1490.34  5118.4 1491.55  5135.9 1497.54  5142.7 1501.17  5148.0 1500.13
  5157.5 1503.96  5172.3 1506.54  5189.8 1515.10  5196.5 1520.43  5201.9 1521.48
  5220.7 1533.19  5226.1 1533.03  5232.9 1538.47  5250.4 1544.63  5265.2 1545.23
#Mann=7,-1,0
  4605.4    0.07       0  4617.2   0.035       0  4799.0    0.12       0
  4822.0    0.07       0  4923.8    0.12       0  5008.7    0.05       0
  5012.7    0.12       0
Bank Sta=5008.7,5012.7
Exp/Cntr=0.3,0.1

Type RM Length L Ch R = 1,16394,101,101,101
BEGIN DESCRIPTION:
Stream0130_DS 35.5
END DESCRIPTION:
XS GIS Cut Line= 3
      2019304.70     13887126.09      2019344.83     13886544.77
      2019355.47     13886258.87
#Sta/Elev= 30
  4417.3 1545.18  4458.5 1544.20  4493.9 1535.16  4538.7 1532.08  4588.8 1520.20
  4608.8 1513.65  4636.7 1507.24  4641.7 1507.53  4669.0 1499.05  4679.0 1497.12
  4741.8 1492.57  4889.5 1485.56  4927.2 1481.41  4932.2 1482.54  4937.9 1481.92
  4939.3 1481.76  4967.7 1481.34  4968.0 1480.84  4971.7 1481.34  5019.8 1481.78
  5039.8 1483.75  5059.8 1487.49  5089.8 1489.82  5136.9 1503.74  5141.9 1502.67
  5149.9 1504.66  5199.9 1522.74  5229.9 1526.48  5249.9 1530.60  5286.1 1534.57
#Mann=6,-1,0
  4417.3    0.07       0  4741.8    0.12       0  4937.9    0.07       0
  4939.3    0.12       0  4967.7    0.05       0  4971.7    0.12       0
Bank Sta=4967.7,4971.7
Exp/Cntr=0.3,0.1

Type RM Length L Ch R = 1,16293,615,615,615
BEGIN DESCRIPTION:
Stream0130_DS 35.0
END DESCRIPTION:
XS GIS Cut Line= 3
      2019380.18     13887110.85      2019435.04     13886574.85
      2019454.48     13886219.58
#Sta/Elev= 30
  4461.2 1545.27  4477.1 1544.51  4517.3 1535.49  4560.1 1531.11  4577.7 1525.64
  4587.7 1524.11  4597.8 1520.42  4607.8 1518.39  4627.9 1510.47  4638.0 1507.68
  4654.4 1503.30  4678.2 1499.23  4768.7 1489.08  4808.9 1487.09  4839.0 1487.27
  4861.7 1485.12  4940.0 1482.66  5007.9 1481.19  5008.1 1480.69  5011.9 1481.19
  5021.1 1481.27  5092.8 1486.18  5170.1 1493.65  5200.2 1501.04  5260.2 1509.23
  5269.5 1509.70  5274.5 1507.88  5325.2 1513.16  5350.4 1516.42  5355.8 1518.46
#Mann=7,-1,0
  4461.2    0.07       0  4861.7    0.12       0  4940.0    0.07       0
  5007.9    0.05       0  5011.9    0.07       0  5021.1    0.12       0
  5325.2    0.07       0
Bank Sta=5007.9,5011.9
Exp/Cntr=0.3,0.1

Type RM Length L Ch R = 1,15678,328,328,328
BEGIN DESCRIPTION:
Stream0130_DS 34.0
END DESCRIPTION:
XS GIS Cut Line= 3
      2019625.02     13886974.99      2019986.17     13886674.78
      2020502.67     13885485.53
#Sta/Elev= 30
  4530.6 1500.96  4552.1 1494.00  4587.2 1489.81  4689.2 1483.91  4725.5 1481.98
  4807.3 1475.39  4914.0 1473.72  4920.7 1470.44  4928.3 1473.00  4983.6 1468.81
  4983.9 1468.31  4987.6 1468.81  5007.6 1471.78  5112.4 1472.43  5188.2 1476.89
  5250.7 1488.74  5294.4 1504.23  5327.1 1506.85  5392.5 1530.48  5439.1 1535.74
  5479.7 1544.11  5533.8 1545.00  5666.5 1548.88  5690.0 1550.81  5708.0 1556.21
  5730.5 1559.02  5904.9 1559.91  5964.3 1564.30  5987.8 1562.93  6296.8 1572.78
#Mann=6,-1,0
  4530.6   0.035       0  4689.2    0.07       0  4725.5    0.12       0
  4983.6    0.05       0  4987.6    0.12       0  5533.8    0.07       0
Bank Sta=4983.6,4987.6
Exp/Cntr=0.3,0.1

Type RM Length L Ch R = 1,15350,470,470,470
BEGIN DESCRIPTION:
Stream0130_DS 33.0
END DESCRIPTION:
XS GIS Cut Line= 3
      2020074.96     13886925.03      2020275.00     13886775.00
      2020575.03     13886524.98
#Sta/Elev= 30
  4749.7 1478.07  4799.7 1477.52  4832.4 1473.13  4854.1 1471.19  4988.9 1464.43
  4992.5 1464.68  4996.6 1462.96  5004.9 1462.25  5005.2 1461.75  5008.9 1462.25
  5013.4 1463.52  5021.4 1463.43  5049.9 1465.04  5085.0 1469.98  5091.5 1471.28
  5105.8 1476.85  5113.6 1481.30  5120.2 1482.72  5177.4 1487.95  5220.4 1490.13
  5234.1 1494.05  5241.2 1499.46  5253.3 1502.24  5276.4 1505.90  5287.6 1509.27
  5305.0 1514.69  5319.3 1522.98  5340.1 1527.67  5362.3 1534.76  5390.3 1536.13
#Mann=9,-1,0
  4749.7    0.12       0  4832.4   0.035       0  4854.1    0.12       0
  4988.9   0.035       0  5004.9   0.035       0  5008.9   0.035       0
  5021.4    0.12       0  5253.3    0.07       0  5287.6    0.12       0
Bank Sta=5004.9,5008.9
Exp/Cntr=0.3,0.1

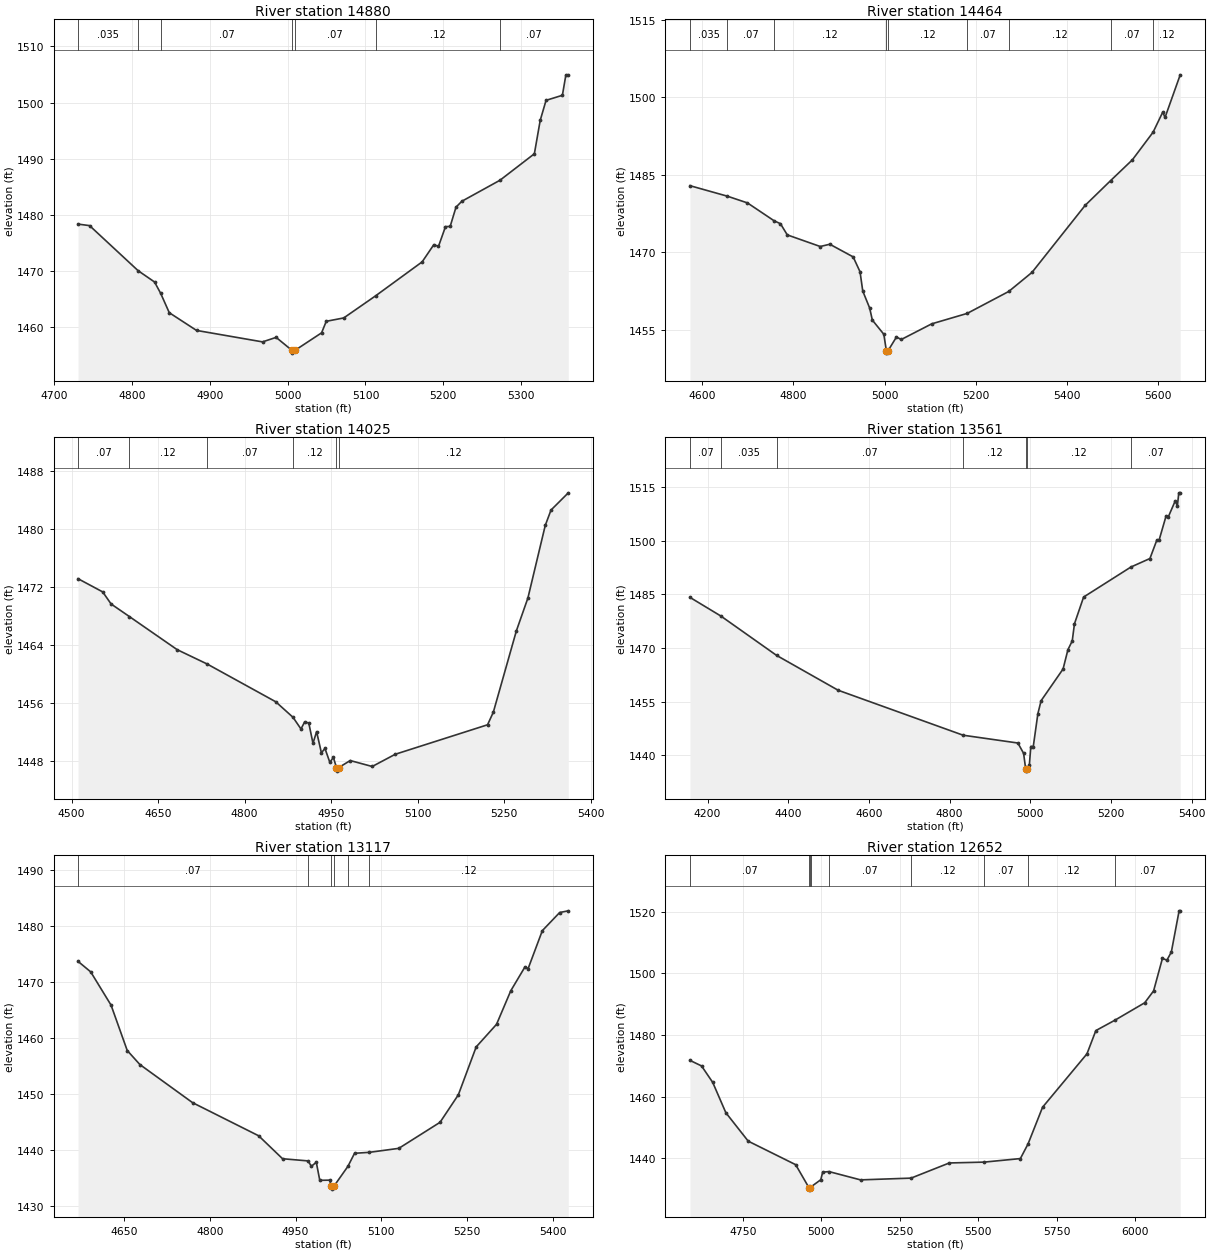
Type RM Length L Ch R = 1,14880,416,416,416
BEGIN DESCRIPTION:
Stream0130_DS 32.0
END DESCRIPTION:
XS GIS Cut Line= 3
      2020474.99     13887325.04      2020575.00     13887075.00
      2020775.03     13886774.96
#Sta/Elev= 30
  4730.7 1478.39  4745.5 1478.12  4807.9 1470.10  4829.0 1468.09  4836.9 1466.06
  4847.9 1462.63  4882.9 1459.48  4967.7 1457.44  4985.2 1458.24  5005.5 1455.94
  5005.8 1455.44  5009.5 1455.94  5043.6 1459.05  5049.6 1461.10  5072.1 1461.70
  5112.9 1465.62  5172.8 1471.67  5187.8 1474.73  5193.8 1474.43  5202.8 1477.94
  5208.8 1477.97  5216.3 1481.40  5223.8 1482.45  5272.8 1486.19  5317.0 1490.90
  5324.5 1496.84  5332.0 1500.40  5353.0 1501.30  5357.5 1504.94  5360.6 1504.94
#Mann=7,-1,0
  4730.7   0.035       0  4807.9    0.12       0  4836.9    0.07       0
  5005.5    0.05       0  5009.5    0.07       0  5112.9    0.12       0
  5272.8    0.07       0
Bank Sta=5005.5,5009.5
Exp/Cntr=0.3,0.1

Type RM Length L Ch R = 1,14464,439,439,439
BEGIN DESCRIPTION:
Stream0130_DS 31.0
END DESCRIPTION:
XS GIS Cut Line= 3
      2020472.24     13887607.96      2020825.00     13887375.00
      2020914.77     13886728.45
#Sta/Elev= 30
  4572.9 1482.88  4655.2 1480.84  4699.1 1479.54  4757.7 1476.07  4771.4 1475.52
  4786.4 1473.35  4858.7 1471.10  4879.7 1471.54  4930.9 1469.09  4946.0 1466.21
  4952.0 1462.47  4967.1 1459.19  4973.0 1456.85  4998.2 1454.10  5003.7 1450.95
  5004.0 1450.45  5007.7 1450.95  5025.9 1453.57  5036.5 1453.09  5103.2 1456.12
  5181.0 1458.14  5272.2 1462.39  5323.3 1466.09  5439.9 1479.07  5495.7 1483.86
  5543.4 1487.88  5588.9 1493.24  5610.1 1497.13  5615.1 1496.09  5648.4 1504.35
#Mann=9,-1,0
  4572.9   0.035       0  4655.2    0.07       0  4757.7    0.12       0
  5003.7    0.05       0  5007.7    0.12       0  5181.0    0.07       0
  5272.2    0.12       0  5495.7    0.07       0  5588.9    0.12       0
Bank Sta=5003.7,5007.7
Exp/Cntr=0.3,0.1

Type RM Length L Ch R = 1,14025,464,464,464
BEGIN DESCRIPTION:
Stream0130_DS 30.0
END DESCRIPTION:
XS GIS Cut Line= 3
      2020924.99     13887725.01      2021225.00     13887325.00
      2021225.00     13886975.01
#Sta/Elev= 30
  4511.3 1473.15  4554.0 1471.33  4568.6 1469.66  4600.4 1467.92  4683.2 1463.35
  4735.2 1461.37  4854.0 1456.16  4884.0 1454.01  4897.8 1452.40  4904.0 1453.35
  4911.3 1453.24  4918.6 1450.42  4924.9 1452.03  4933.2 1449.11  4939.4 1449.71
  4947.8 1447.80  4954.0 1448.47  4959.3 1447.08  4959.5 1446.58  4963.4 1447.08
  4983.2 1448.04  5021.3 1447.22  5061.3 1448.91  5221.3 1452.98  5231.3 1454.72
  5271.3 1465.96  5291.3 1470.50  5321.3 1480.50  5331.3 1482.63  5361.3 1485.01
#Mann=6,-1,0
  4511.3    0.07       0  4600.4    0.12       0  4735.2    0.07       0
  4884.0    0.12       0  4959.3    0.05       0  4963.4    0.12       0
Bank Sta=4959.3,4963.4
Exp/Cntr=0.3,0.1

Type RM Length L Ch R = 1,13561,444,444,444
BEGIN DESCRIPTION:
Stream0130_DS 29.0
END DESCRIPTION:
XS GIS Cut Line= 3
      2021001.82     13887950.79      2021625.00     13887375.00
      2021783.03     13887043.73
#Sta/Elev= 30
  4156.2 1484.17  4233.0 1478.94  4370.8 1467.96  4523.5 1458.21  4833.5 1445.63
  4969.2 1443.45  4983.4 1440.57  4988.7 1436.09  4989.0 1435.59  4992.9 1436.09
  4997.6 1437.18  5001.3 1442.47  5007.4 1442.47  5018.8 1451.65  5026.8 1455.28
  5081.3 1464.15  5093.3 1469.54  5104.0 1471.99  5109.5 1476.78  5132.2 1484.26
  5249.6 1492.66  5296.6 1495.03  5313.8 1500.20  5319.3 1500.16  5336.5 1506.87
  5342.0 1506.63  5359.2 1511.11  5364.7 1509.78  5368.2 1513.40  5371.7 1513.40
#Mann=7,-1,0
  4156.2    0.07       0  4233.0   0.035       0  4370.8    0.07       0
  4833.5    0.12       0  4988.7    0.05       0  4992.9    0.12       0
  5249.6    0.07       0
Bank Sta=4988.7,4992.9
Exp/Cntr=0.3,0.1

Type RM Length L Ch R = 1,13117,465,465,465
BEGIN DESCRIPTION:
Stream0130_DS 28.0
END DESCRIPTION:
XS GIS Cut Line= 3
      2021525.02     13888124.97      2021775.00     13887775.00
      2021925.01     13887374.98
#Sta/Elev= 30
  4569.7 1473.65  4591.8 1471.78  4627.4 1465.85  4655.7 1457.76  4677.8 1455.26
  4770.0 1448.46  4885.5 1442.56  4927.3 1438.47  4971.9 1438.08  4977.7 1437.12
  4986.3 1437.84  4992.4 1434.62  5009.6 1434.65  5012.8 1433.55  5013.1 1433.05
  5017.0 1433.55  5041.6 1437.11  5053.2 1439.44  5079.2 1439.61  5130.6 1440.32
  5202.7 1444.96  5234.7 1449.86  5265.9 1458.40  5301.5 1462.43  5326.4 1468.41
  5351.3 1472.68  5356.7 1472.35  5381.6 1479.13  5411.9 1482.36  5427.0 1482.66
#Mann=6,-1,0
  4569.7    0.07       0  4971.9   0.035       0  5012.8   0.035       0
  5017.0   0.035       0  5041.6    0.07       0  5079.2    0.12       0
Bank Sta=5012.8,5017
Exp/Cntr=0.3,0.1

Type RM Length L Ch R = 1,12652,468,468,468
BEGIN DESCRIPTION:
Stream0130_DS 27.0
END DESCRIPTION:
XS GIS Cut Line= 3
      2021774.98     13888375.02      2022025.00     13888025.00
      2022824.99     13887225.01
#Sta/Elev= 30
  4581.5 1471.79  4618.4 1469.98  4654.0 1464.64  4695.8 1454.81  4767.1 1445.58
  4918.2 1437.95  4960.3 1430.52  4960.6 1430.02  4964.6 1430.52  4965.9 1430.68
  4998.1 1433.06  5004.3 1435.53  5024.3 1435.71  5124.8 1433.02  5285.7 1433.59
  5407.6 1438.51  5518.2 1438.78  5633.9 1439.93  5658.4 1444.69  5704.6 1456.59
  5846.0 1473.91  5874.3 1481.45  5935.0 1484.82  6029.9 1490.47  6058.2 1494.32
  6086.4 1504.88  6100.6 1504.29  6114.7 1506.91  6139.5 1520.30  6143.0 1520.30
#Mann=9,-1,0
  4581.5    0.07       0  4960.3   0.035       0  4964.6    0.07       0
  4965.9   0.035       0  5024.3    0.07       0  5285.7    0.12       0
  5518.2    0.07       0  5658.4    0.12       0  5935.0    0.07       0
Bank Sta=4960.3,4964.6
Exp/Cntr=0.3,0.1

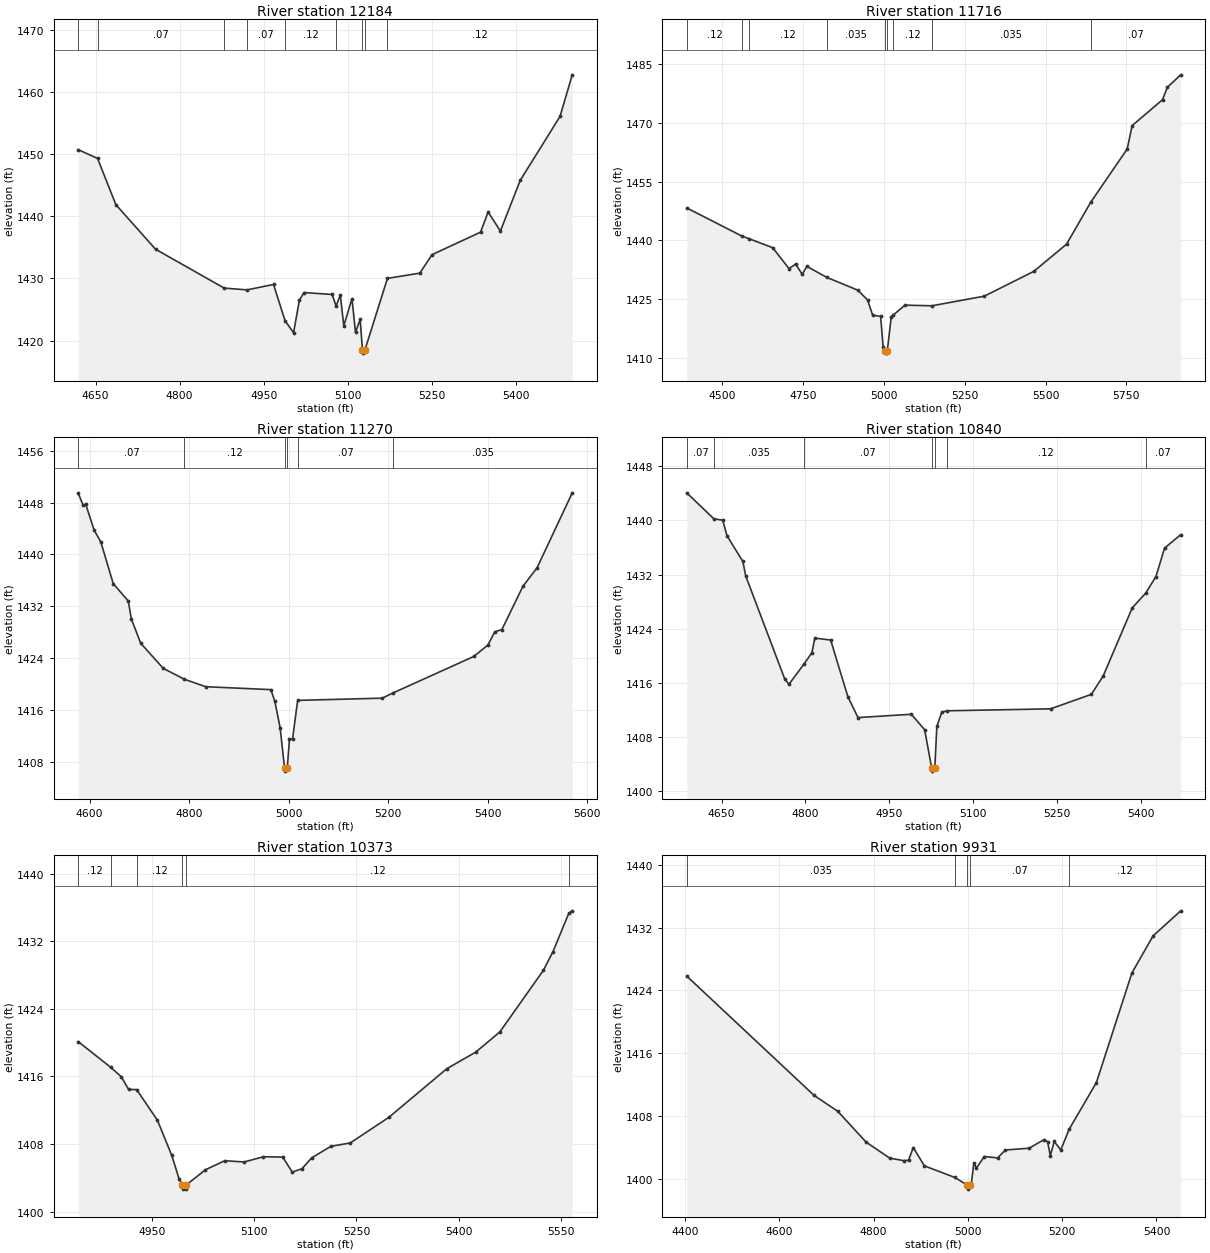
Type RM Length L Ch R = 1,12184,468,468,468
BEGIN DESCRIPTION:
Stream0130_DS 26.0
END DESCRIPTION:
XS GIS Cut Line= 3
      2022025.04     13888424.98      2022375.00     13888275.00
      2022674.98     13887875.03
#Sta/Elev= 30
  4619.2 1450.71  4653.7 1449.29  4686.2 1441.87  4757.0 1434.70  4879.3 1428.45
  4920.1 1428.16  4967.3 1429.03  4988.0 1423.18  5003.1 1421.27  5013.5 1426.53
  5021.8 1427.73  5071.8 1427.42  5078.9 1425.57  5086.4 1427.34  5092.6 1422.37
  5107.2 1426.75  5113.5 1421.34  5121.8 1423.43  5125.9 1418.49  5126.2 1417.99
  5130.2 1418.49  5170.5 1430.01  5228.1 1430.85  5249.9 1433.82  5336.4 1437.44
  5349.9 1440.68  5371.8 1437.62  5407.2 1445.78  5478.1 1456.05  5499.9 1462.74
#Mann=9,-1,0
  4619.2   0.035       0  4653.7    0.07       0  4879.3    0.12       0
  4920.1    0.07       0  4988.0    0.12       0  5078.9    0.07       0
  5125.9    0.05       0  5130.2    0.07       0  5170.5    0.12       0
Bank Sta=5125.9,5130.2
Exp/Cntr=0.3,0.1

Type RM Length L Ch R = 1,11716,446,446,446
BEGIN DESCRIPTION:
Stream0130_DS 25.0
END DESCRIPTION:
XS GIS Cut Line= 3
      2021822.08     13888814.54      2022425.00     13888725.00
      2023196.90     13888229.28
#Sta/Elev= 30
  4390.9 1448.28  4562.7 1441.05  4583.7 1440.43  4656.7 1438.13  4707.2 1432.80
  4727.5 1433.96  4747.7 1431.38  4762.5 1433.36  4824.2 1430.56  4919.6 1427.31
  4949.9 1424.82  4965.7 1420.93  4990.3 1420.64  4997.9 1412.84  5005.3 1411.76
  5005.8 1411.26  5010.7 1411.76  5023.2 1420.52  5029.1 1420.95  5065.5 1423.49
  5148.6 1423.33  5310.6 1425.78  5463.9 1432.11  5564.9 1439.03  5639.6 1449.72
  5752.5 1463.32  5767.7 1469.26  5861.5 1475.87  5876.7 1479.05  5917.8 1482.21
#Mann=9,-1,0
  4390.9    0.12       0  4562.7   0.035       0  4583.7    0.12       0
  4824.2   0.035       0  5005.3   0.035       0  5010.7   0.035       0
  5029.1    0.12       0  5148.6   0.035       0  5639.6    0.07       0
Bank Sta=5005.3,5010.7
Exp/Cntr=0.3,0.1

Type RM Length L Ch R = 1,11270,430,430,430
BEGIN DESCRIPTION:
Stream0130_DS 24.0
END DESCRIPTION:
XS GIS Cut Line= 3
      2022275.01     13889225.00      2022675.00     13889075.00
      2023075.01     13888674.99
#Sta/Elev= 30
  4577.1 1449.45  4586.9 1447.59  4592.2 1447.73  4609.1 1443.73  4622.5 1441.92
  4647.4 1435.49  4677.7 1432.79  4683.9 1430.01  4702.6 1426.28  4748.0 1422.39
  4790.6 1420.71  4833.4 1419.56  4964.2 1419.11  4972.3 1417.30  4982.9 1413.21
  4991.7 1407.02  4992.2 1406.52  4997.3 1407.02  5001.6 1411.46  5007.8 1411.46
  5018.1 1417.45  5188.1 1417.79  5210.1 1418.61  5372.0 1424.23  5400.3 1425.99
  5414.4 1428.04  5428.6 1428.39  5471.0 1435.09  5499.3 1437.93  5570.0 1449.51
#Mann=6,-1,0
  4577.1    0.07       0  4790.6    0.12       0  4991.7    0.05       0
  4997.3    0.12       0  5018.1    0.07       0  5210.1   0.035       0
Bank Sta=4991.7,4997.3
Exp/Cntr=0.3,0.1

Type RM Length L Ch R = 1,10840,467,467,467
BEGIN DESCRIPTION:
Stream0130_DS 23.0
END DESCRIPTION:
XS GIS Cut Line= 3
      2022375.04     13889574.99      2022775.00     13889475.00
      2023175.03     13889224.98
#Sta/Elev= 30
  4587.7 1444.05  4636.5 1440.20  4652.1 1440.02  4659.8 1437.72  4688.2 1433.92
  4693.3 1431.79  4762.9 1416.63  4770.6 1415.80  4798.2 1418.85  4811.8 1420.49
  4817.0 1422.62  4845.3 1422.33  4876.3 1413.92  4894.3 1410.89  4989.7 1411.38
  5013.5 1409.09  5026.0 1403.49  5026.5 1402.99  5031.7 1403.49  5035.3 1409.59
  5044.2 1411.70  5053.4 1411.89  5238.8 1412.18  5311.9 1414.32  5333.1 1417.05
  5385.0 1427.08  5409.0 1429.25  5427.4 1431.70  5442.8 1435.89  5471.7 1437.88
#Mann=7,-1,0
  4587.7    0.07       0  4636.5   0.035       0  4798.2    0.07       0
  5026.0    0.05       0  5031.7    0.07       0  5053.4    0.12       0
  5409.0    0.07       0
Bank Sta=5026,5031.7
Exp/Cntr=0.3,0.1

Type RM Length L Ch R = 1,10373,442,442,442
BEGIN DESCRIPTION:
Stream0130_DS 22.0
END DESCRIPTION:
XS GIS Cut Line= 3
      2022725.00     13889925.00      2022875.00     13889875.00
      2023275.00     13889475.00
#Sta/Elev= 30
  4842.4 1420.12  4889.9 1417.09  4905.6 1415.96  4916.2 1414.47  4927.9 1414.45
  4958.4 1410.83  4979.4 1406.67  4990.0 1403.93  4995.0 1403.18  4995.5 1402.68
  5000.3 1402.68  5000.7 1403.18  5028.8 1404.97  5057.1 1406.04  5085.4 1405.89
  5113.7 1406.51  5141.9 1406.47  5156.1 1404.69  5170.2 1405.09  5184.4 1406.38
  5212.6 1407.74  5240.9 1408.14  5297.5 1411.17  5382.4 1416.92  5424.8 1418.88
  5460.1 1421.27  5523.8 1428.54  5537.9 1430.75  5561.2 1435.31  5566.2 1435.59
#Mann=6,-1,0
  4842.4    0.12       0  4889.9   0.035       0  4927.9    0.12       0
  4995.0    0.05       0  5000.7    0.12       0  5561.2    0.07       0
Bank Sta=4995,5000.7
Exp/Cntr=0.3,0.1

Type RM Length L Ch R = 1,9931,431,431,431
BEGIN DESCRIPTION:
Stream0130_DS 21.0
END DESCRIPTION:
XS GIS Cut Line= 3
      2022625.03     13890155.68      2023225.00     13890125.00
      2023625.03     13890325.02
#Sta/Elev= 30
  4403.4 1425.84  4673.7 1410.62  4723.8 1408.60  4783.9 1404.67  4833.9 1402.63
  4864.0 1402.30  4874.0 1402.35  4884.0 1403.97  4907.6 1401.64  4972.3 1400.16
  4998.7 1399.17  4999.1 1398.67  5004.6 1399.17  5006.9 1399.17  5012.5 1402.00
  5018.1 1401.37  5034.9 1402.83  5062.8 1402.65  5079.6 1403.66  5129.9 1403.89
  5160.7 1404.96  5169.1 1404.73  5174.7 1402.93  5183.0 1404.75  5197.0 1403.67
  5214.6 1406.29  5272.5 1412.26  5347.9 1426.24  5392.7 1430.96  5451.4 1434.16
#Mann=5,-1,0
  4403.4   0.035       0  4972.3    0.07       0  4998.7    0.05       0
  5004.6    0.07       0  5214.6    0.12       0
Bank Sta=4998.7,5004.6
Exp/Cntr=0.3,0.1

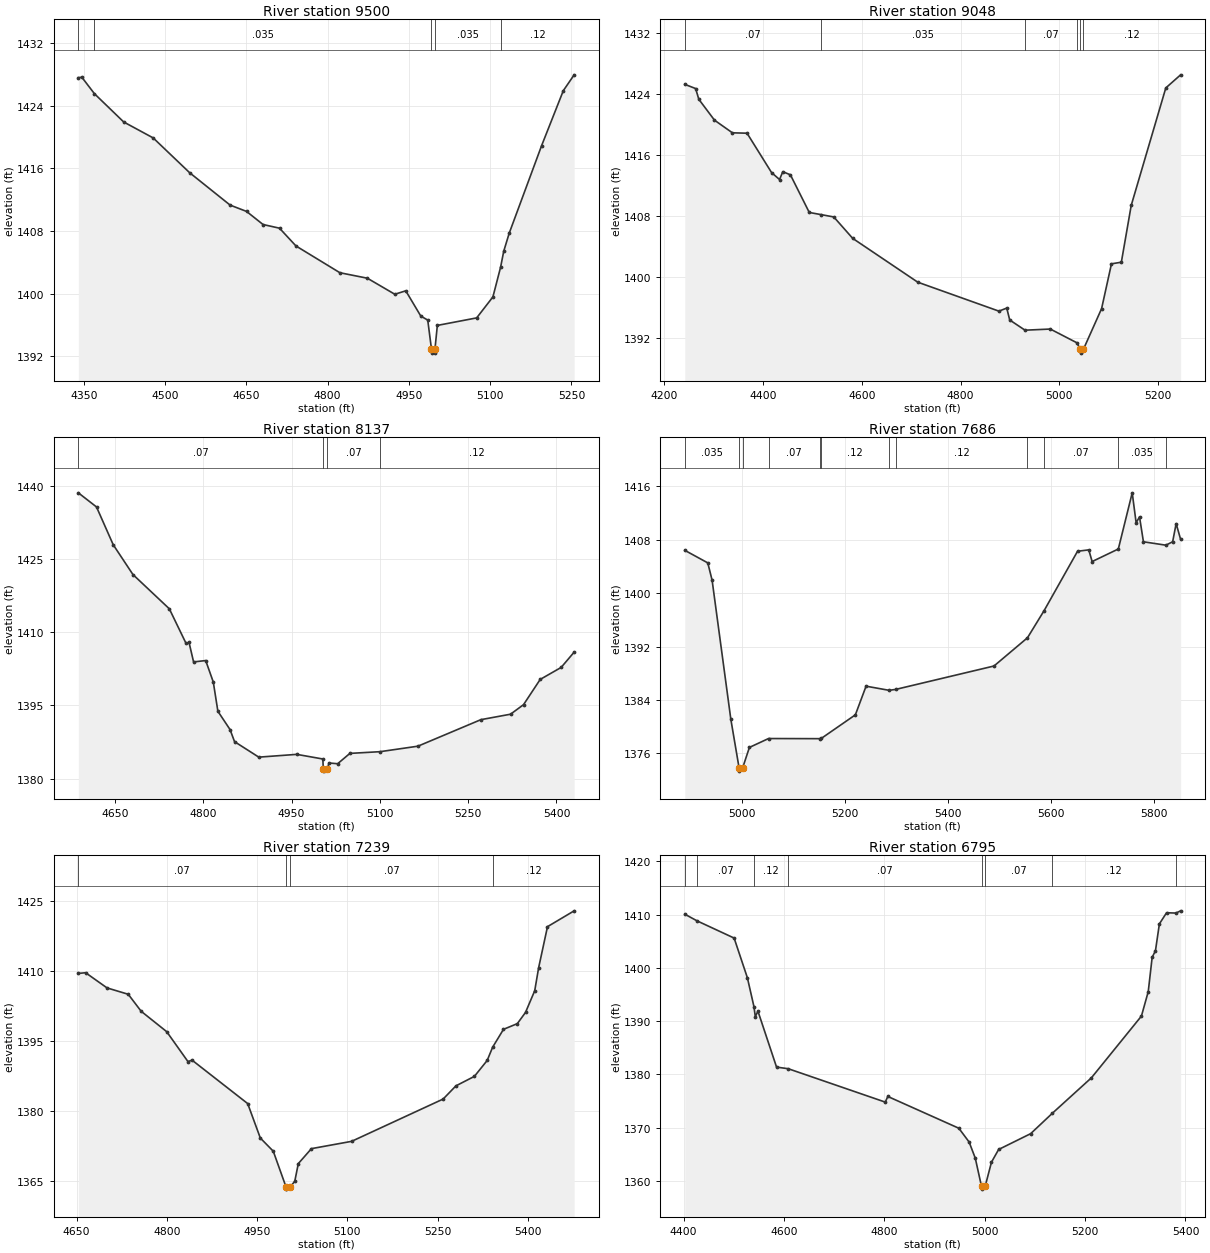
Type RM Length L Ch R = 1,9500,452,452,452
BEGIN DESCRIPTION:
Stream0130_DS 20.0
END DESCRIPTION:
XS GIS Cut Line= 3
      2022568.62     13890416.09      2023225.00     13890525.00
      2023475.04     13890525.00
#Sta/Elev= 30
  4339.7 1427.59  4346.2 1427.64  4369.4 1425.54  4423.4 1421.93  4477.9 1419.89
  4545.3 1415.44  4619.9 1411.31  4650.3 1410.50  4680.7 1408.83  4711.1 1408.36
  4741.5 1406.09  4822.6 1402.67  4873.3 1401.97  4924.0 1399.92  4944.2 1400.36
  4972.0 1397.13  4984.8 1396.62  4991.7 1392.90  4992.2 1392.40  4997.6 1392.40
  4998.1 1392.90  5002.5 1395.94  5075.1 1396.90  5105.1 1399.58  5119.3 1403.38
  5125.1 1405.42  5135.1 1407.70  5195.1 1418.92  5235.1 1425.93  5255.1 1427.95
#Mann=5,-1,0
  4339.7    0.07       0  4369.4   0.035       0  4991.7   0.035       0
  4998.1   0.035       0  5119.3    0.12       0
Bank Sta=4991.7,4998.1
Exp/Cntr=0.3,0.1

Type RM Length L Ch R = 1,9048,911,911,911
BEGIN DESCRIPTION:
Stream0130_DS 19.0
END DESCRIPTION:
XS GIS Cut Line= 3
      2022559.97     13890620.10      2023225.00     13890975.00
      2023475.00     13890975.00
#Sta/Elev= 30
  4241.6 1425.29  4263.5 1424.74  4270.0 1423.33  4301.7 1420.59  4338.0 1418.93
  4367.6 1418.88  4417.3 1413.71  4433.4 1412.80  4440.0 1413.83  4455.4 1413.42
  4493.6 1408.48  4517.2 1408.20  4543.2 1407.89  4581.5 1405.08  4713.2 1399.33
  4877.5 1395.53  4893.4 1395.93  4899.4 1394.37  4930.4 1393.03  4981.6 1393.18
  5035.6 1391.37  5042.2 1390.52  5042.7 1390.02  5048.6 1390.52  5085.4 1395.86
  5105.4 1401.74  5125.4 1401.95  5145.4 1409.41  5215.4 1424.82  5245.4 1426.54
#Mann=6,-1,0
  4241.6    0.07       0  4517.2   0.035       0  4930.4    0.07       0
  5035.6    0.12       0  5042.2    0.05       0  5048.6    0.12       0
Bank Sta=5042.2,5048.6
Exp/Cntr=0.3,0.1

Type RM Length L Ch R = 1,8137,451,451,451
BEGIN DESCRIPTION:
Stream0130_DS 18.0
END DESCRIPTION:
XS GIS Cut Line= 3
      2022575.02     13891675.00      2022975.00     13891575.00
      2023324.99     13891325.00
#Sta/Elev= 30
  4587.7 1438.63  4618.6 1435.73  4647.0 1427.97  4680.5 1421.86  4742.3 1414.83
  4770.6 1407.76  4775.8 1407.92  4783.5 1403.93  4804.1 1404.21  4817.0 1399.80
  4824.8 1393.80  4845.4 1390.06  4853.1 1387.57  4894.3 1384.39  4958.8 1384.96
  5003.1 1384.01  5003.9 1382.02  5004.4 1381.52  5010.9 1382.02  5013.5 1383.19
  5028.3 1383.04  5049.1 1385.16  5100.3 1385.51  5164.7 1386.64  5271.6 1392.08
  5322.0 1393.20  5344.1 1395.16  5372.4 1400.34  5408.0 1402.80  5430.1 1405.94
#Mann=4,-1,0
  4587.7    0.07       0  5003.9    0.05       0  5010.9    0.07       0
  5100.3    0.12       0
Bank Sta=5003.9,5010.9
Exp/Cntr=0.3,0.1

Type RM Length L Ch R = 1,7686,447,447,447
BEGIN DESCRIPTION:
Stream0130_DS 17.0
END DESCRIPTION:
XS GIS Cut Line= 3
      2022974.99     13892075.01      2023025.00     13891975.00
      2023666.69     13891414.39
#Sta/Elev= 30
  4888.7 1406.40  4933.4 1404.52  4941.8 1401.92  4978.2 1381.10  4994.2 1373.84
  4994.7 1373.34  5001.2 1373.84  5014.3 1376.89  5051.5 1378.22  5151.2 1378.20
  5154.1 1378.24  5220.3 1381.77  5241.1 1386.06  5285.8 1385.44  5298.4 1385.57
  5489.8 1389.08  5554.9 1393.31  5587.2 1397.37  5652.2 1406.26  5674.0 1406.47
  5680.6 1404.72  5731.5 1406.60  5758.5 1415.01  5766.1 1410.53  5772.7 1411.41
  5780.3 1407.68  5824.0 1407.17  5837.1 1407.69  5843.9 1410.40  5852.6 1408.04
#Mann=12,-1,0
  4888.7   0.035       0  4994.2   0.035       0  5001.2   0.035       0
  5051.5    0.07       0  5151.2   0.035       0  5154.1    0.12       0
  5285.8    0.07       0  5298.4    0.12       0  5554.9   0.035       0
  5587.2    0.07       0  5731.5   0.035       0  5824.0    0.07       0
Bank Sta=4994.2,5001.2
Exp/Cntr=0.3,0.1

Type RM Length L Ch R = 1,7239,444,444,444
BEGIN DESCRIPTION:
Stream0130_DS 16.0
END DESCRIPTION:
XS GIS Cut Line= 3
      2023167.59     13892364.89      2023425.00     13892125.00
      2023825.03     13891874.98
#Sta/Elev= 30
  4653.0 1409.48  4665.1 1409.63  4700.7 1406.38  4735.9 1405.02  4757.4 1401.38
  4799.8 1397.02  4835.1 1390.62  4841.9 1390.93  4934.3 1381.64  4955.3 1374.27
  4976.8 1371.45  4997.9 1363.84  4998.4 1363.34  5005.0 1363.84  5012.5 1365.01
  5018.4 1368.80  5040.2 1372.00  5106.9 1373.56  5259.0 1382.61  5280.2 1385.43
  5310.9 1387.46  5332.1 1390.86  5341.2 1393.70  5359.2 1397.52  5382.2 1398.74
  5395.8 1401.14  5411.1 1405.78  5417.6 1410.70  5432.3 1419.48  5476.6 1422.87
#Mann=4,-1,0
  4653.0    0.07       0  4997.9    0.05       0  5005.0    0.07       0
  5341.2    0.12       0
Bank Sta=4997.9,5005
Exp/Cntr=0.3,0.1

Type RM Length L Ch R = 1,6795,420,420,420
BEGIN DESCRIPTION:
Stream0130_DS 15.0
END DESCRIPTION:
XS GIS Cut Line= 3
      2023193.68     13892512.44      2023775.00     13892375.00
      2024025.03     13892074.97
#Sta/Elev= 30
  4402.4 1410.09  4426.7 1408.84  4500.7 1405.60  4527.1 1398.14  4540.2 1392.71
  4542.9 1390.82  4548.1 1391.88  4585.2 1381.36  4608.6 1381.05  4801.8 1374.78
  4806.9 1375.84  4948.4 1369.87  4968.9 1367.28  4981.2 1364.24  4993.6 1358.93
  4994.1 1358.43  5000.8 1358.93  5013.4 1363.49  5027.7 1365.88  5091.5 1368.85
  5134.9 1372.70  5212.6 1379.35  5312.2 1390.94  5325.8 1395.54  5333.6 1402.00
  5340.1 1403.19  5348.0 1408.27  5362.3 1410.36  5381.0 1410.30  5390.3 1410.72
#Mann=8,-1,0
  4402.4    0.12       0  4426.7    0.07       0  4540.2    0.12       0
  4608.6    0.07       0  4993.6    0.05       0  5000.8    0.07       0
  5134.9    0.12       0  5381.0    0.07       0
Bank Sta=4993.6,5000.8
Exp/Cntr=0.3,0.1

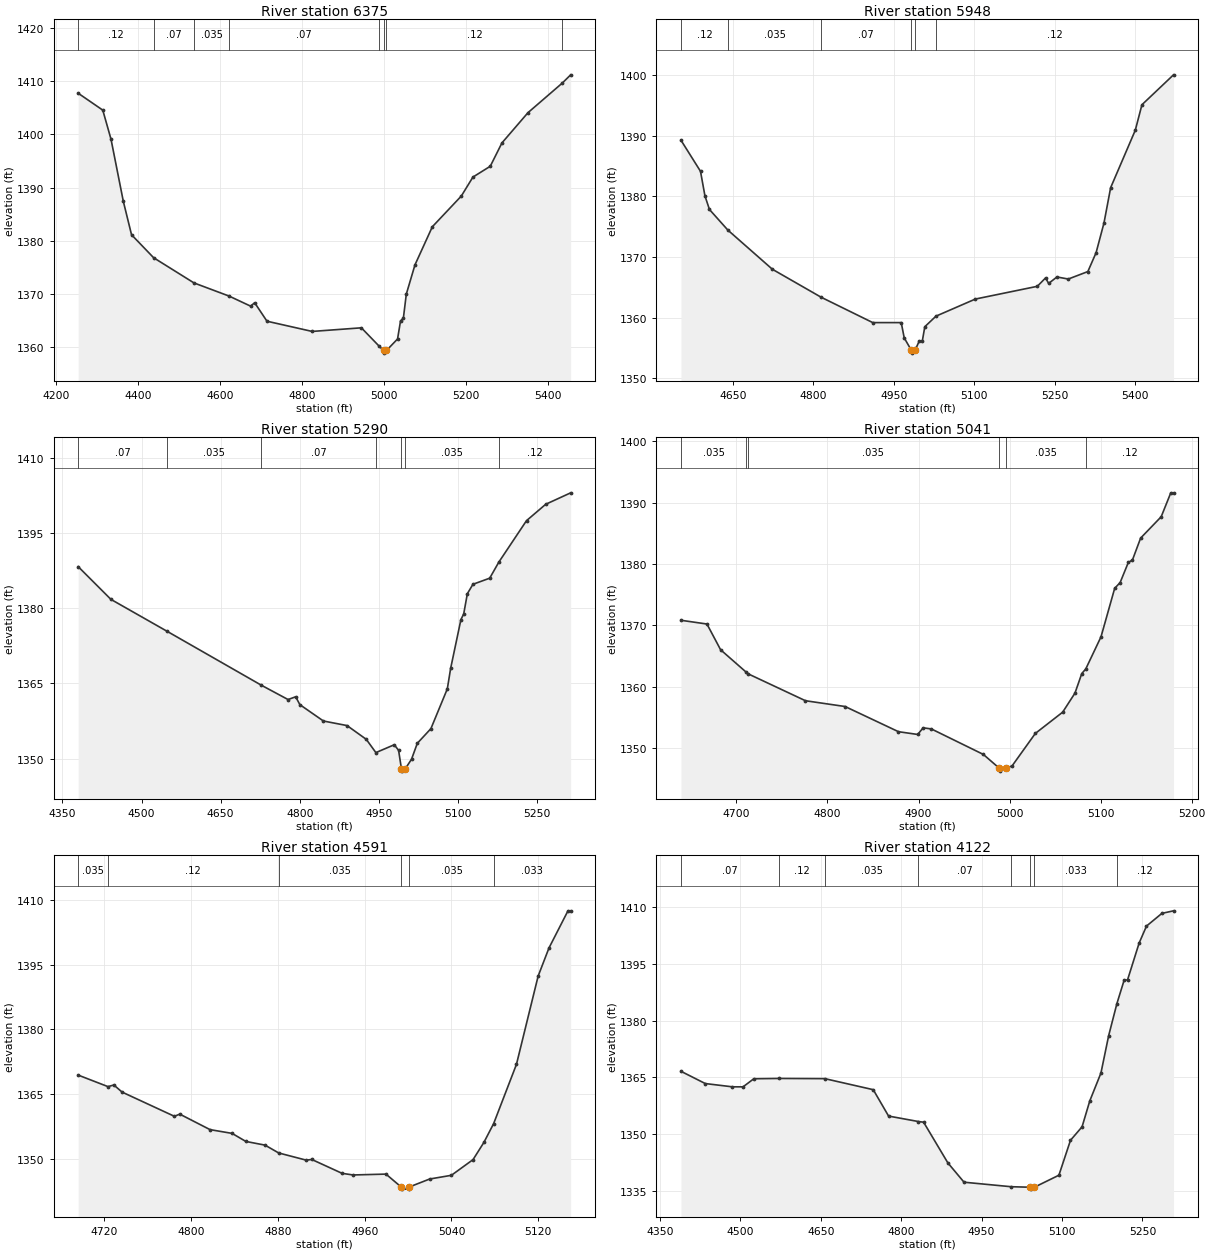
Type RM Length L Ch R = 1,6375,427,427,427
BEGIN DESCRIPTION:
Stream0130_DS 14.0
END DESCRIPTION:
XS GIS Cut Line= 3
      2023224.99     13892675.00      2023975.00     13892725.00
      2024300.22     13892412.80
#Sta/Elev= 30
  4253.0 1407.76  4313.1 1404.58  4333.2 1399.11  4363.3 1387.41  4383.3 1381.15
  4437.2 1376.83  4535.8 1372.09  4621.7 1369.61  4673.9 1367.73  4684.0 1368.36
  4714.0 1364.89  4824.3 1362.97  4944.5 1363.65  4987.7 1360.21  4998.6 1359.39
  4999.1 1358.89  5005.8 1359.39  5032.8 1361.55  5040.1 1364.95  5047.0 1365.46
  5054.2 1369.99  5075.3 1375.48  5117.7 1382.65  5188.5 1388.43  5216.8 1391.99
  5259.2 1394.03  5287.6 1398.41  5351.2 1404.10  5435.3 1409.69  5455.5 1411.22
#Mann=8,-1,0
  4253.0    0.12       0  4437.2    0.07       0  4535.8   0.035       0
  4621.7    0.07       0  4987.7    0.12       0  4998.6    0.05       0
  5005.8    0.12       0  5435.3    0.07       0
Bank Sta=4998.6,5005.8
Exp/Cntr=0.3,0.1

Type RM Length L Ch R = 1,5948,658,658,658
BEGIN DESCRIPTION:
Stream0130_DS 13.0
END DESCRIPTION:
XS GIS Cut Line= 3
      2023324.98     13892824.99      2023725.00     13893025.00
      2024124.97     13893274.98
#Sta/Elev= 30
  4552.8 1389.25  4589.2 1384.13  4597.5 1380.08  4605.9 1377.84  4640.3 1374.44
  4723.3 1367.99  4814.3 1363.38  4910.6 1359.20  4963.7 1359.20  4969.3 1356.68
  4982.4 1354.67  4982.9 1354.17  4989.7 1354.67  4997.2 1356.14  5003.0 1356.14
  5007.7 1358.52  5028.5 1360.26  5102.0 1363.08  5217.6 1365.18  5232.9 1366.55
  5238.8 1365.66  5254.2 1366.72  5275.4 1366.38  5311.9 1367.61  5327.3 1370.73
  5342.0 1375.62  5354.4 1381.43  5400.4 1390.90  5412.8 1395.10  5471.7 1400.03
#Mann=6,-1,0
  4552.8    0.12       0  4640.3   0.035       0  4814.3    0.07       0
  4982.4    0.05       0  4989.7    0.07       0  5028.5    0.12       0
Bank Sta=4982.4,4989.7
Exp/Cntr=0.3,0.1

Type RM Length L Ch R = 1,5290,249,249,249
BEGIN DESCRIPTION:
Stream0130_DS 12.0
END DESCRIPTION:
XS GIS Cut Line= 3
      2023319.53     13893714.69      2023870.72     13893436.93
      2024170.11     13893332.79
#Sta/Elev= 30
  4379.8 1388.33  4441.9 1381.79  4548.0 1375.44  4727.1 1364.65  4777.9 1361.78
  4792.4 1362.33  4800.3 1360.76  4845.0 1357.49  4889.8 1356.58  4926.3 1353.83
  4944.5 1351.18  4979.4 1352.75  4987.6 1351.63  4992.9 1347.98  4993.4 1347.48
  5000.4 1347.98  5012.1 1349.85  5023.1 1353.04  5048.9 1355.97  5080.0 1363.91
  5086.3 1368.00  5105.8 1377.75  5111.1 1378.88  5118.0 1382.92  5128.6 1384.80
  5160.4 1386.02  5177.6 1389.21  5230.2 1397.51  5266.6 1400.78  5314.0 1403.07
#Mann=7,-1,0
  4379.8    0.07       0  4548.0   0.035       0  4727.1    0.07       0
  4944.5   0.035       0  4992.9   0.035       0  5000.4   0.035       0
  5177.6    0.12       0
Bank Sta=4992.9,5000.4
Exp/Cntr=0.3,0.1

Type RM Length L Ch R = 1,5041,450,450,450
BEGIN DESCRIPTION:
Stream0130_DS 11.0
END DESCRIPTION:
XS GIS Cut Line= 3
      2023825.02     13893924.97      2024025.00     13893625.00
      2024125.00     13893475.00
#Sta/Elev= 30
  4639.2 1370.83  4667.7 1370.22  4682.7 1366.03  4710.8 1362.38  4712.5 1362.14
  4775.9 1357.73  4819.4 1356.79  4878.0 1352.69  4899.1 1352.24  4905.1 1353.32
  4914.1 1353.14  4971.2 1348.99  4988.5 1346.77  4989.0 1346.27  4996.0 1346.77
  5002.7 1347.11  5028.3 1352.41  5058.3 1355.87  5071.8 1358.97  5079.3 1362.16
  5083.6 1362.89  5100.4 1368.14  5115.4 1376.03  5121.4 1376.97  5130.4 1380.25
  5134.9 1380.64  5143.9 1384.21  5166.5 1387.69  5177.0 1391.58  5180.0 1391.58
#Mann=6,-1,0
  4639.2   0.035       0  4710.8    0.12       0  4712.5   0.035       0
  4988.5   0.035       0  4996.0   0.035       0  5083.6    0.12       0
Bank Sta=4988.5,4996
Exp/Cntr=0.3,0.1

Type RM Length L Ch R = 1,4591,469,469,469
BEGIN DESCRIPTION:
Stream0130_DS 10.0
END DESCRIPTION:
XS GIS Cut Line= 3
      2023875.04     13893975.01      2024175.00     13894025.00
      2024325.00     13894025.00
#Sta/Elev= 30
  4695.8 1369.39  4723.3 1366.71  4728.7 1367.09  4736.3 1365.44  4784.5 1359.82
  4789.5 1360.32  4817.4 1356.72  4837.7 1355.85  4850.4 1353.98  4868.1 1353.12
  4880.7 1351.30  4906.1 1349.63  4911.2 1349.79  4939.1 1346.57  4949.2 1346.19
  4979.6 1346.39  4993.6 1343.40  4994.1 1342.90  5000.6 1342.90  5001.1 1343.40
  5019.9 1345.25  5039.9 1346.11  5059.9 1349.76  5069.9 1353.76  5078.9 1358.14
  5099.9 1371.88  5119.9 1392.39  5129.9 1398.93  5147.4 1407.55  5149.9 1407.55
#Mann=6,-1,0
  4695.8   0.035       0  4723.3    0.12       0  4880.7   0.035       0
  4993.6   0.035       0  5001.1   0.035       0  5078.9   0.033       0
Bank Sta=4993.6,5001.1
Exp/Cntr=0.3,0.1

Type RM Length L Ch R = 1,4122,491,491,491
BEGIN DESCRIPTION:
Stream0130_DS 9.0
END DESCRIPTION:
XS GIS Cut Line= 3
      2023579.95     13894413.50      2024175.00     13894475.00
      2024425.02     13894274.99
#Sta/Elev= 30
  4389.5 1366.59  4434.8 1363.35  4485.1 1362.49  4505.2 1362.48  4525.3 1364.62
  4571.9 1364.70  4657.7 1364.65  4748.0 1361.73  4776.6 1354.75  4832.3 1353.30
  4841.9 1353.13  4887.2 1342.35  4917.3 1337.25  5004.9 1336.06  5040.8 1335.92
  5041.3 1335.42  5048.4 1335.92  5094.2 1339.10  5115.8 1348.34  5137.4 1351.91
  5151.8 1358.77  5172.6 1366.14  5187.0 1376.04  5202.4 1384.53  5215.8 1390.68
  5222.2 1390.78  5243.8 1400.52  5257.5 1405.01  5286.3 1408.38  5307.9 1409.05
#Mann=8,-1,0
  4389.5    0.07       0  4571.9    0.12       0  4657.7   0.035       0
  4832.3    0.07       0  5004.9   0.033       0  5040.8    0.05       0
  5048.4   0.033       0  5202.4    0.12       0
Bank Sta=5040.8,5048.4
Exp/Cntr=0.3,0.1