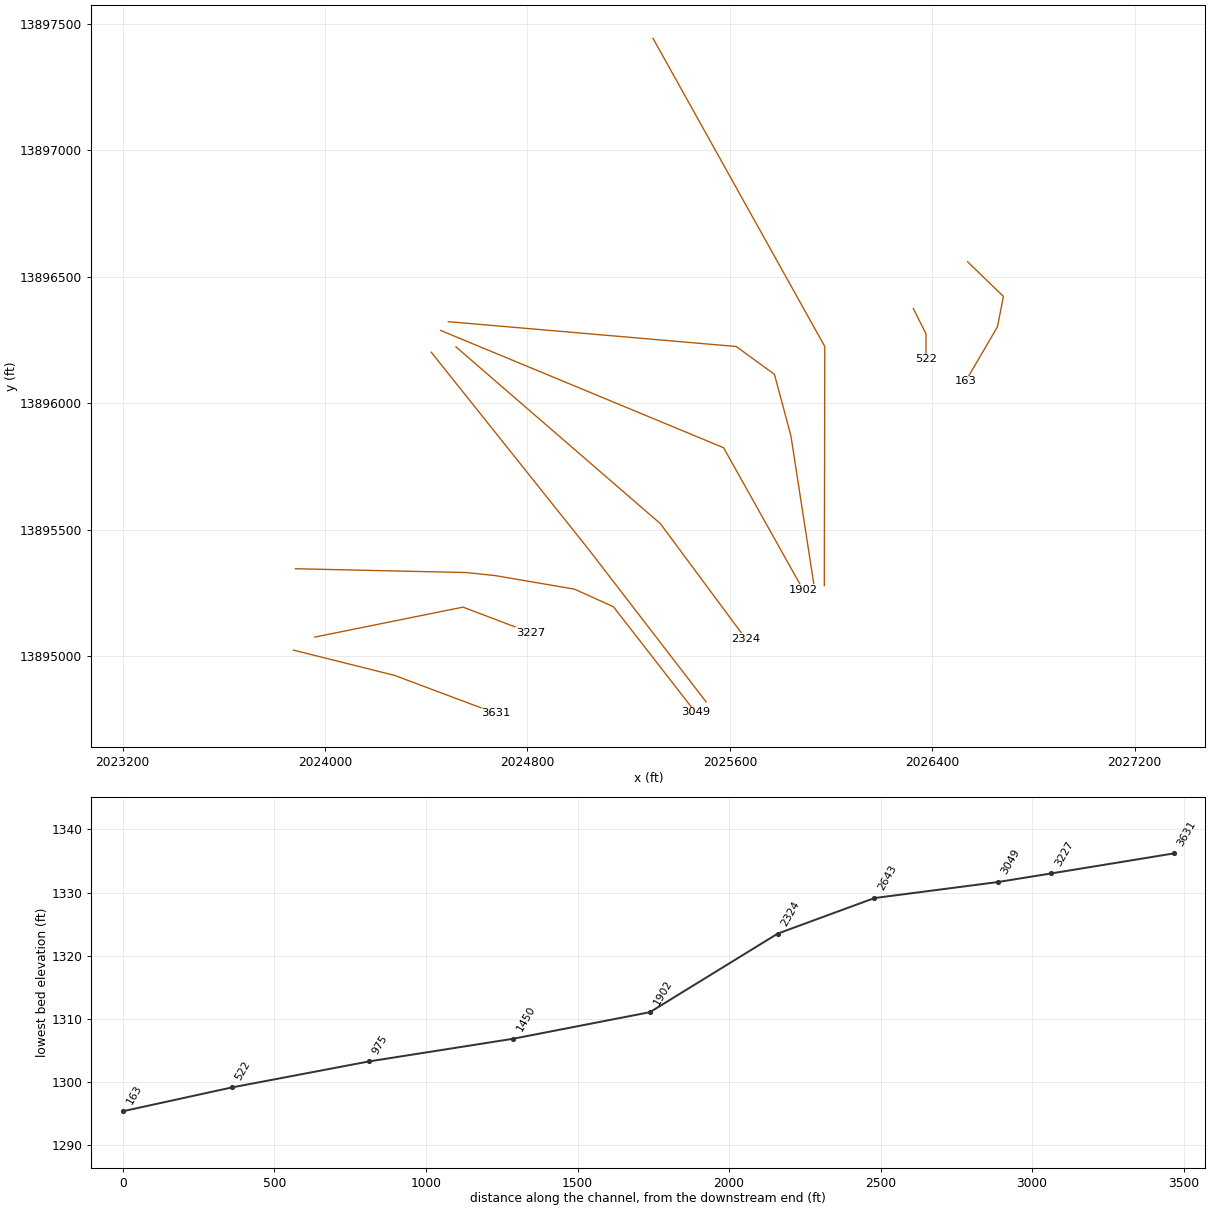
HEC-RAS study Stream0130_DS.prj: Stream0130_DS Base Level Engineering

--- Stream0130_DS.g01 (geometry) --- (continued)

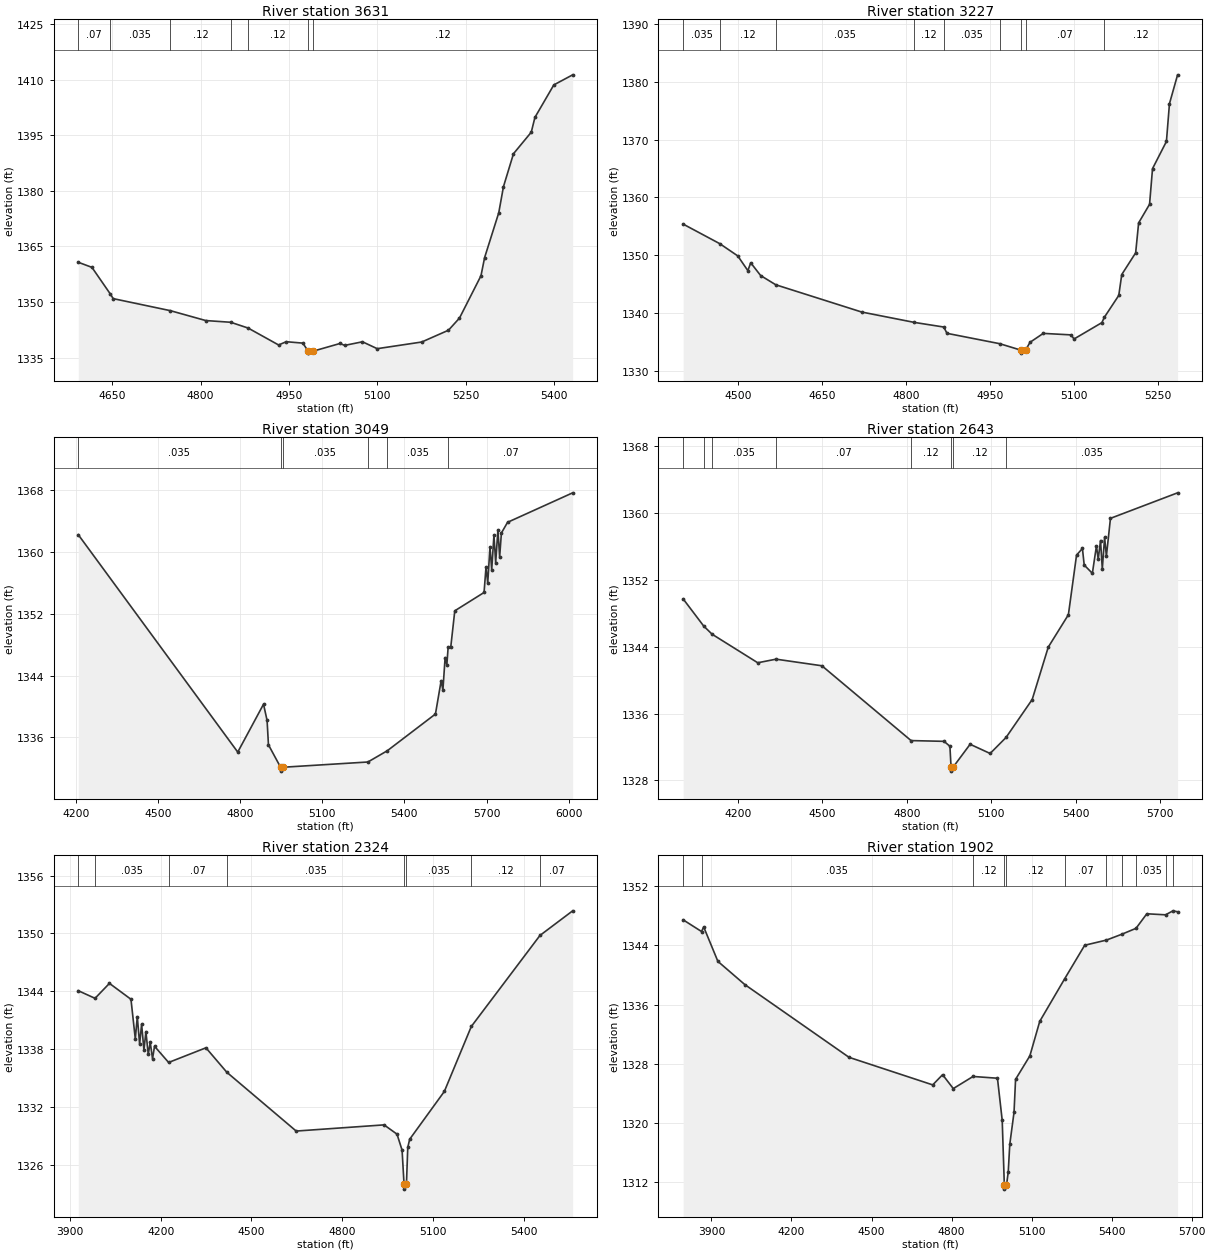
Type RM Length L Ch R = 1,3631,404,404,404
BEGIN DESCRIPTION:
Stream0130_DS 8.0
END DESCRIPTION:
XS GIS Cut Line= 3
      2023874.98     13895025.00      2024275.00     13894925.00
      2024674.97     13894775.01
#Sta/Elev= 30
  4592.3 1360.72  4615.5 1359.35  4646.3 1352.26  4651.6 1350.91  4748.7 1347.66
  4808.8 1344.99  4851.1 1344.53  4880.7 1342.97  4932.5 1338.40  4945.4 1339.28
  4973.7 1338.90  4982.7 1336.70  4983.2 1336.20  4990.5 1336.70  5036.7 1338.80
  5044.7 1338.29  5074.9 1339.26  5099.9 1337.40  5175.5 1339.20  5220.9 1342.38
  5239.6 1345.66  5276.1 1357.08  5282.3 1362.00  5306.3 1374.09  5314.3 1381.14
  5331.3 1390.02  5361.5 1395.83  5367.7 1399.82  5399.8 1408.59  5431.8 1411.31
#Mann=7,-1,0
  4592.3    0.07       0  4646.3   0.035       0  4748.7    0.12       0
  4851.1   0.035       0  4880.7    0.12       0  4982.7    0.05       0
  4990.5    0.12       0
Bank Sta=4982.7,4990.5
Exp/Cntr=0.3,0.1

Type RM Length L Ch R = 1,3227,178,178,178
BEGIN DESCRIPTION:
Stream0130_DS 7.0
END DESCRIPTION:
XS GIS Cut Line= 3
      2023959.57     13895076.57      2024545.03     13895194.93
      2024811.22     13895093.95
#Sta/Elev= 30
  4402.7 1355.38  4468.0 1351.99  4500.1 1349.87  4518.1 1347.32  4523.2 1348.68
  4540.9 1346.47  4567.9 1344.87  4721.1 1340.15  4815.2 1338.35  4867.6 1337.55
  4873.3 1336.46  4967.6 1334.66  5005.7 1333.53  5006.2 1333.03  5013.5 1333.53
  5021.4 1334.90  5045.1 1336.45  5094.7 1336.19  5100.0 1335.48  5149.6 1338.31
  5154.2 1339.26  5179.8 1343.03  5185.1 1346.64  5209.9 1350.40  5215.2 1355.59
  5234.7 1358.81  5240.0 1364.99  5264.8 1369.70  5270.2 1376.24  5284.7 1381.24
#Mann=9,-1,0
  4402.7   0.035       0  4468.0    0.12       0  4567.9   0.035       0
  4815.2    0.12       0  4867.6   0.035       0  4967.6    0.07       0
  5005.7    0.05       0  5013.5    0.07       0  5154.2    0.12       0
Bank Sta=5005.7,5013.5
Exp/Cntr=0.3,0.1

Type RM Length L Ch R = 1,3049,406,406,406
BEGIN DESCRIPTION:
Stream0130_DS 6.5
END DESCRIPTION:
XS GIS Cut Line= 6
      2023882.86     13895346.68      2024559.11     13895331.58
      2024672.55     13895319.53      2024985.91     13895265.92
      2025139.66     13895196.41      2025463.73     13894779.61
#Sta/Elev= 30
  4209.5 1362.21  4791.8 1334.11  4885.9 1340.30  4898.9 1338.20  4903.9 1335.05
  4948.2 1332.15  4948.7 1331.65  4956.1 1332.15  5267.0 1332.83  5337.6 1334.28
  5513.6 1339.03  5534.4 1343.34  5540.8 1342.12  5548.9 1346.33  5555.2 1345.38
  5559.9 1347.66  5569.7 1347.75  5584.2 1352.37  5691.1 1354.74  5698.2 1358.04
  5704.5 1355.97  5712.7 1360.65  5719.0 1357.69  5727.2 1362.17  5733.5 1358.60
  5741.7 1362.85  5748.0 1359.36  5754.4 1362.43  5776.9 1363.81  6014.6 1367.62
#Mann=6,-1,0
  4209.5   0.035       0  4948.2   0.035       0  4956.1   0.035       0
  5267.0    0.12       0  5337.6   0.035       0  5559.9    0.07       0
Bank Sta=4948.2,4956.1
Exp/Cntr=0.3,0.1

Type RM Length L Ch R = 1,2643,319,319,319
BEGIN DESCRIPTION:
Stream0130_DS 6.0
END DESCRIPTION:
XS GIS Cut Line= 3
      2024419.87     13896202.15      2025042.40     13895422.21
      2025505.47     13894820.99
#Sta/Elev= 30
  4005.5 1349.70  4078.4 1346.46  4108.4 1345.48  4270.5 1342.07  4335.5 1342.50
  4498.5 1341.71  4815.3 1332.77  4932.5 1332.68  4953.3 1332.09  4957.3 1329.62
  4957.8 1329.12  4965.2 1329.62  5025.1 1332.33  5096.2 1331.23  5152.7 1333.14
  5245.7 1337.68  5302.8 1343.94  5374.3 1347.81  5403.3 1354.94  5424.2 1355.73
  5430.5 1353.75  5459.5 1352.76  5474.0 1356.04  5480.3 1354.45  5488.5 1356.68
  5494.8 1353.29  5503.0 1357.06  5509.3 1354.82  5523.8 1359.33  5762.3 1362.38
#Mann=8,-1,0
  4005.5    0.12       0  4078.4    0.07       0  4108.4   0.035       0
  4335.5    0.07       0  4815.3    0.12       0  4957.3    0.05       0
  4965.2    0.12       0  5152.7   0.035       0
Bank Sta=4957.3,4965.2
Exp/Cntr=0.3,0.1

Type RM Length L Ch R = 1,2324,422,422,422
BEGIN DESCRIPTION:
Stream0130_DS 5.0
END DESCRIPTION:
XS GIS Cut Line= 3
      2024517.39     13896223.41      2025325.00     13895525.00
      2025662.85     13895069.41
#Sta/Elev= 30
  3927.5 1344.06  3983.0 1343.27  4030.6 1344.82  4101.8 1343.17  4116.1 1339.07
  4122.7 1341.37  4130.4 1338.53  4137.0 1340.59  4144.6 1337.92  4151.2 1339.82
  4158.9 1337.46  4165.5 1338.70  4173.1 1337.00  4179.7 1338.30  4226.3 1336.62
  4349.7 1338.14  4418.9 1335.60  4648.1 1329.51  4938.7 1330.15  4981.5 1329.19
  4998.3 1327.53  5004.8 1323.99  5005.3 1323.49  5012.7 1323.99  5017.1 1327.81
  5023.4 1328.66  5138.1 1333.62  5227.2 1340.35  5454.3 1349.79  5562.4 1352.34
#Mann=8,-1,0
  3927.5    0.12       0  3983.0   0.035       0  4226.3    0.07       0
  4418.9   0.035       0  5004.8   0.035       0  5012.7   0.035       0
  5227.2    0.12       0  5454.3    0.07       0
Bank Sta=5004.8,5012.7
Exp/Cntr=0.3,0.1

Type RM Length L Ch R = 1,1902,452,452,452
BEGIN DESCRIPTION:
Stream0130_DS 4.0
END DESCRIPTION:
XS GIS Cut Line= 3
      2024456.68     13896288.48      2025575.00     13895825.00
      2025888.96     13895264.16
#Sta/Elev= 30
  3794.0 1347.47  3862.8 1345.89  3870.9 1346.51  3924.1 1341.85  4025.0 1338.71
  4415.8 1328.86  4729.4 1325.13  4766.4 1326.51  4806.5 1324.63  4880.6 1326.27
  4972.1 1326.03  4989.9 1320.34  4997.9 1311.52  4998.4 1311.02  5005.9 1311.52
  5012.5 1313.34  5018.3 1317.09  5034.2 1321.41  5040.0 1325.88  5093.6 1329.06
  5130.6 1333.73  5223.7 1339.47  5299.1 1344.03  5380.6 1344.73  5437.5 1345.51
  5491.4 1346.32  5532.0 1348.29  5602.2 1348.15  5630.1 1348.69  5647.3 1348.56
#Mann=11,-1,0
  3794.0    0.12       0  3862.8   0.035       0  4880.6    0.12       0
  4997.9    0.05       0  5005.9    0.12       0  5223.7    0.07       0
  5380.6   0.035       0  5437.5    0.07       0  5491.4   0.035       0
  5602.2    0.07       0  5630.1   0.035       0
Bank Sta=4997.9,5005.9
Exp/Cntr=0.3,0.1

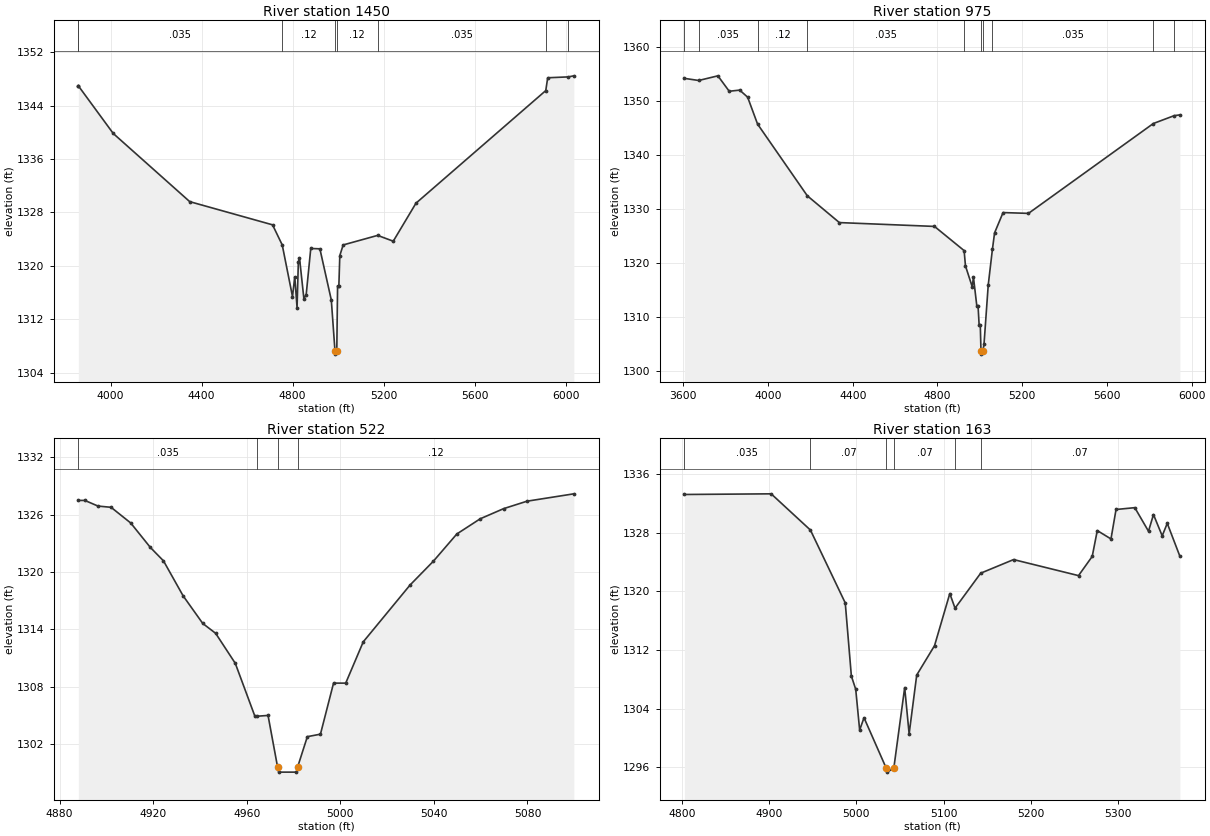
Type RM Length L Ch R = 1,1450,475,475,475
BEGIN DESCRIPTION:
Stream0130_DS 3.0
END DESCRIPTION:
XS GIS Cut Line= 5
      2024487.03     13896323.21      2025625.00     13896225.00
      2025776.10     13896114.88      2025841.20     13895871.83
      2025932.35     13895281.51
#Sta/Elev= 30
  3858.0 1346.97  3858.4 1346.94  4011.6 1339.82  4347.8 1329.62  4711.8 1326.15
  4754.4 1323.14  4799.5 1315.42  4809.5 1318.38  4819.5 1313.77  4825.2 1320.59
  4830.2 1321.23  4849.6 1315.08  4859.7 1315.71  4879.8 1322.61  4919.9 1322.56
  4970.1 1314.90  4986.2 1307.30  4986.7 1306.80  4994.2 1307.30  4997.7 1317.02
  5003.3 1317.02  5007.5 1321.55  5022.2 1323.14  5173.8 1324.57  5242.4 1323.70
  5342.3 1329.39  5912.8 1346.24  5921.3 1348.16  6011.9 1348.29  6036.1 1348.45
#Mann=8,-1,0
  3858.0    0.12       0  3858.4   0.035       0  4754.4    0.12       0
  4986.2    0.05       0  4994.2    0.12       0  5173.8   0.035       0
  5912.8    0.07       0  6011.9   0.035       0
Bank Sta=4986.2,4994.2
Exp/Cntr=0.3,0.1

Type RM Length L Ch R = 1,975,453,453,453
BEGIN DESCRIPTION:
Stream0130_DS 2.0
END DESCRIPTION:
XS GIS Cut Line= 3
      2025296.06     13897443.01      2025975.00     13896225.00
      2025973.15     13895279.86
#Sta/Elev= 30
  3605.1 1354.17  3672.5 1353.78  3763.1 1354.64  3816.6 1351.79  3866.1 1352.00
  3903.5 1350.70  3950.5 1345.72  4185.3 1332.47  4336.7 1327.52  4785.8 1326.81
  4925.8 1322.34  4932.1 1319.52  4964.1 1315.65  4969.8 1317.44  4985.8 1312.08
  4991.6 1312.07  4996.7 1308.56  5002.1 1308.56  5005.4 1303.71  5005.9 1303.21
  5013.8 1303.71  5019.6 1305.00  5039.6 1315.98  5059.5 1322.63  5069.6 1325.62
  5109.6 1329.37  5229.6 1329.22  5819.3 1345.83  5917.7 1347.28  5944.7 1347.42
#Mann=10,-1,0
  3605.1    0.07       0  3672.5   0.035       0  3950.5    0.12       0
  4185.3   0.035       0  4925.8    0.12       0  5005.4    0.05       0
  5013.8    0.12       0  5059.5   0.035       0  5819.3    0.07       0
  5917.7   0.035       0
Bank Sta=5005.4,5013.8
Exp/Cntr=0.3,0.1

Type RM Length L Ch R = 1,522,359,359,359
BEGIN DESCRIPTION:
Stream0130_DS 1.0
END DESCRIPTION:
XS GIS Cut Line= 3
      2026324.98     13896375.04      2026375.00     13896275.00
      2026375.00     13896175.05
#Sta/Elev= 30
  4888.0 1327.50  4890.8 1327.50  4896.4 1326.91  4902.0 1326.78  4910.4 1325.14
  4918.8 1322.58  4924.4 1321.18  4932.8 1317.52  4941.2 1314.63  4946.7 1313.60
  4955.1 1310.46  4963.5 1304.91  4964.5 1304.93  4969.1 1305.01  4973.2 1299.58
  4973.7 1299.08  4981.2 1299.08  4981.7 1299.58  4985.9 1302.79  4991.5 1303.05
  4997.1 1308.39  5002.3 1308.39  5009.8 1312.71  5029.8 1318.65  5039.8 1321.15
  5049.8 1323.99  5059.8 1325.58  5069.8 1326.64  5079.8 1327.42  5099.8 1328.19
#Mann=4,-1,0
  4888.0   0.035       0  4964.5    0.12       0  4973.2    0.05       0
  4981.7    0.12       0
Bank Sta=4973.2,4981.7
Exp/Cntr=0.3,0.1

Type RM Length L Ch R = 1,163,0,0,0
BEGIN DESCRIPTION:
Stream0130_DS 0.0
END DESCRIPTION:
XS GIS Cut Line= 4
      2026539.37     13896559.96      2026680.88     13896423.04
      2026657.57     13896303.05      2026532.13     13896088.34
#Sta/Elev= 30
  4803.1 1333.23  4902.5 1333.32  4947.5 1328.37  4987.4 1318.42  4994.4 1308.44
  4999.4 1306.62  5003.9 1301.06  5008.9 1302.74  5034.5 1295.81  5035.0 1295.31
  5043.0 1295.81  5055.5 1306.86  5060.6 1300.54  5069.3 1308.57  5089.7 1312.58
  5107.2 1319.70  5113.2 1317.70  5142.6 1322.48  5180.3 1324.34  5254.7 1322.15
  5270.4 1324.77  5276.2 1328.30  5291.9 1327.16  5297.7 1331.18  5319.2 1331.43
  5334.9 1328.21  5340.6 1330.49  5350.6 1327.58  5356.4 1329.29  5370.9 1324.78
#Mann=6,-1,0
  4803.1   0.035       0  4947.5    0.07       0  5034.5    0.05       0
  5043.0    0.07       0  5113.2    0.12       0  5142.6    0.07       0
Bank Sta=5034.5,5043
Exp/Cntr=0.3,0.1

Chan Stop Cuts=-1