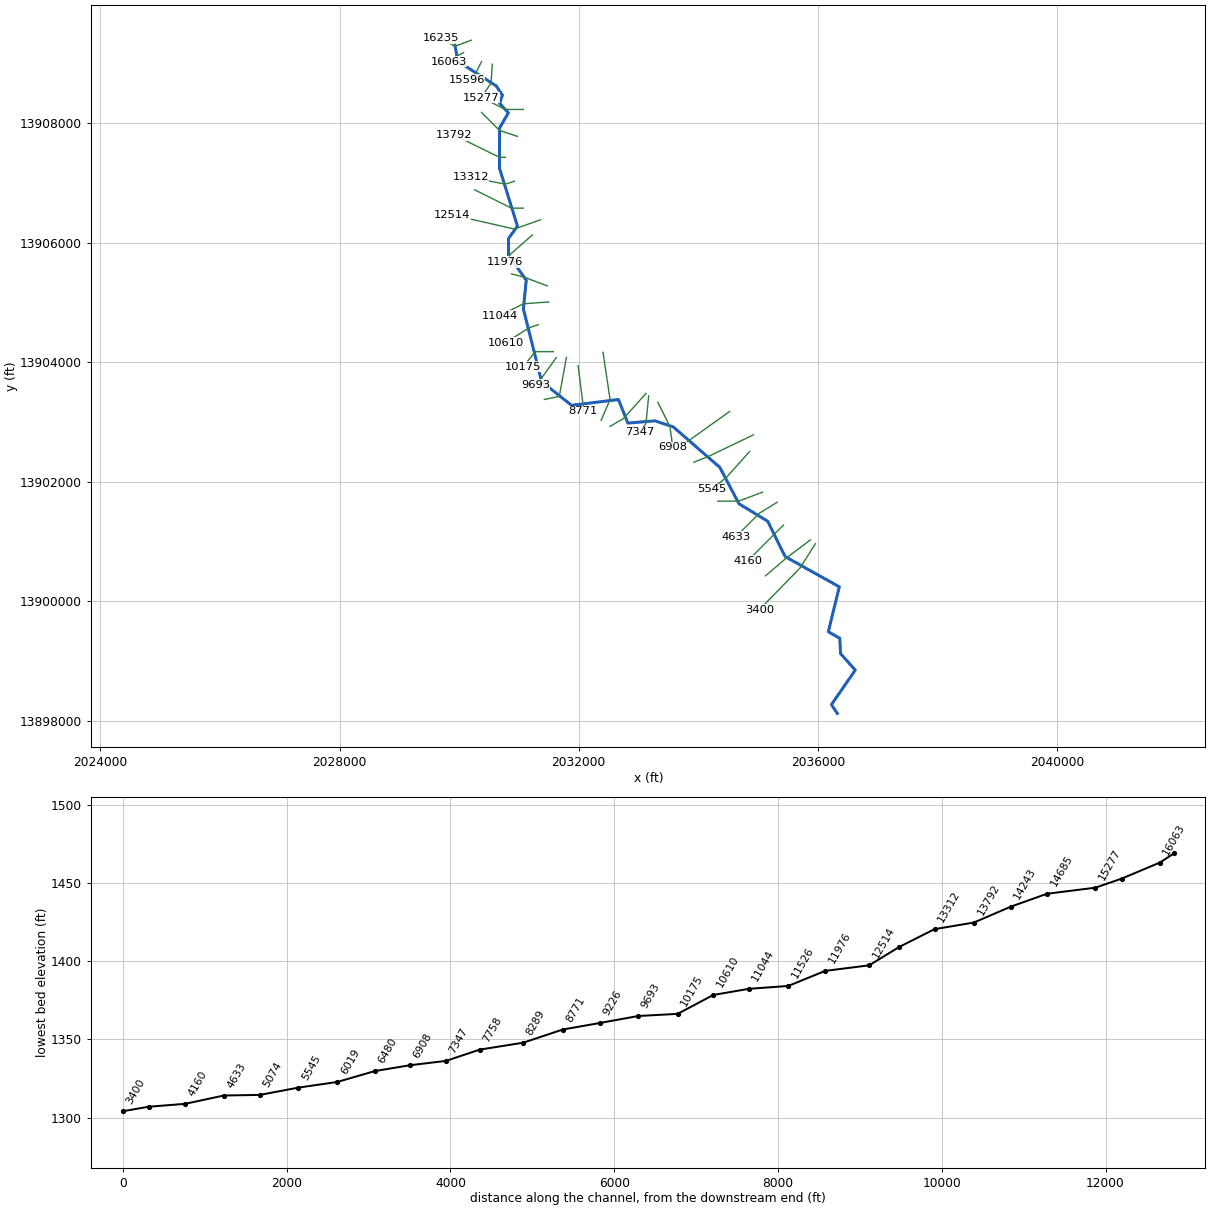
--- Stream0131_DS.prj (project) ---

Proj Title=Stream0131_DS Base Level Engineering
Current Plan=p01
Default Exp/Contr=0.3,0.1
English Units
Geom File=g01
Flow File=f01
Plan File=p01
Y Axis Title=Elevation
X Axis Title(PF)=Main Channel Distance
X Axis Title(XS)=Station
BEGIN DESCRIPTION:
Stream0131_DS
END DESCRIPTION:
DSS Export Rating Curves= 0
DSS Export Rating Curve Sorted= 0
DSS Export Volume Flow Curves= 0
DXF OffsetX= 0
DXF OffsetY= 0
DXF ScaleX= 1
DXF ScaleY= 10

--- Stream0131_DS.p01 (plan) ---

Plan Title=Multiple Run
Short Identifier=Multiple
Geom File=g01
Flow File=f01
Subcritical Flow
K Sum by GR= 0
Std Step Tol= 0.01
Critical Tol= 0.01
Num of Std Step Trials= 20
Max Error Tol= 0.3
Flow Tol Ratio= 0.001
Split Flow NTrial= 30
Split Flow Tol= 0.02
Split Flow Ratio= 0.02
Log Output Level= 0
Friction Slope Method= 1
Unsteady Friction Slope Method= 2
Unsteady Bridges Friction Slope Method= 1
Parabolic Critical Depth
Global Vel Dist=  1 , 1 , 1
Global Log Level= 0
CheckData=True
Encroach Param= -1, 0, 0, 0
BEGIN DESCRIPTION:
Multiple Run
END DESCRIPTION:

--- Stream0131_DS.f01 (steady flow) ---

Flow Title=Multiple
Number of Profiles=7
Profile Names=10-year,25-year,50-year,1pct_min,100-year,1pct_plu,500-year
River Rch & RM= Stream0131_DS,Reach-1,16235
     583     957    1303     863    1722    3436    2968
River Rch & RM= Stream0131_DS,Reach-1,14685
    1720    3032    4332    2999    5984   11940   11301
River Rch & RM= Stream0131_DS,Reach-1,11044
    2122    3769    5408    3756    7495   14955   14253
River Rch & RM= Stream0131_DS,Reach-1,6480
    3371    6102    8866    6223   12417   24776   24128
Boundary for River Rch & Prof#=Stream0131_DS,Reach-1,1
Up Type=0
Dn Type=3
Dn Slope=0.005
Boundary for River Rch & Prof#=Stream0131_DS,Reach-1,2
Up Type=0
Dn Type=3
Dn Slope=0.005
Boundary for River Rch & Prof#=Stream0131_DS,Reach-1,3
Up Type=0
Dn Type=3
Dn Slope=0.005
Boundary for River Rch & Prof#=Stream0131_DS,Reach-1,4
Up Type=0
Dn Type=3
Dn Slope=0.005
Boundary for River Rch & Prof#=Stream0131_DS,Reach-1,5
Up Type=0
Dn Type=3
Dn Slope=0.005
Boundary for River Rch & Prof#=Stream0131_DS,Reach-1,6
Up Type=0
Dn Type=3
Dn Slope=0.005
Boundary for River Rch & Prof#=Stream0131_DS,Reach-1,7
Up Type=0
Dn Type=3
Dn Slope=0.005

--- Stream0131_DS.g01 (geometry) ---

Geom Title=Existing Conditions
Program Version=4.10

River Reach=Stream0131_DS   ,Reach-1
Reach XY= 30
        2029925.       13909325.      2029980.18     13909030.44
      2030619.58     13908619.53      2030724.52     13908465.19
      2030678.13     13908326.63      2030823.58     13908168.57
      2030676.22      13907914.5      2030675.21     13907243.27
        2030976.     13906274.63      2030827.24     13906069.07
      2030825.51     13905790.21      2031122.65     13905369.48
      2031075.29     13904890.12      2031380.42     13903672.32
      2031880.45     13903277.18      2032664.57     13903373.96
      2032822.53     13902980.45        2033275.     13903017.44
      2033581.07     13902916.87      2034361.37     13902238.21
      2034680.62     13901630.62      2035161.38     13901338.22
      2035451.43     13900747.86       2036358.6     13900241.75
      2036175.42     13899490.64       2036367.2     13899381.21
      2036378.75     13899126.55       2036625.6     13898847.88
      2036228.09     13898273.36        2036325.       13898125.

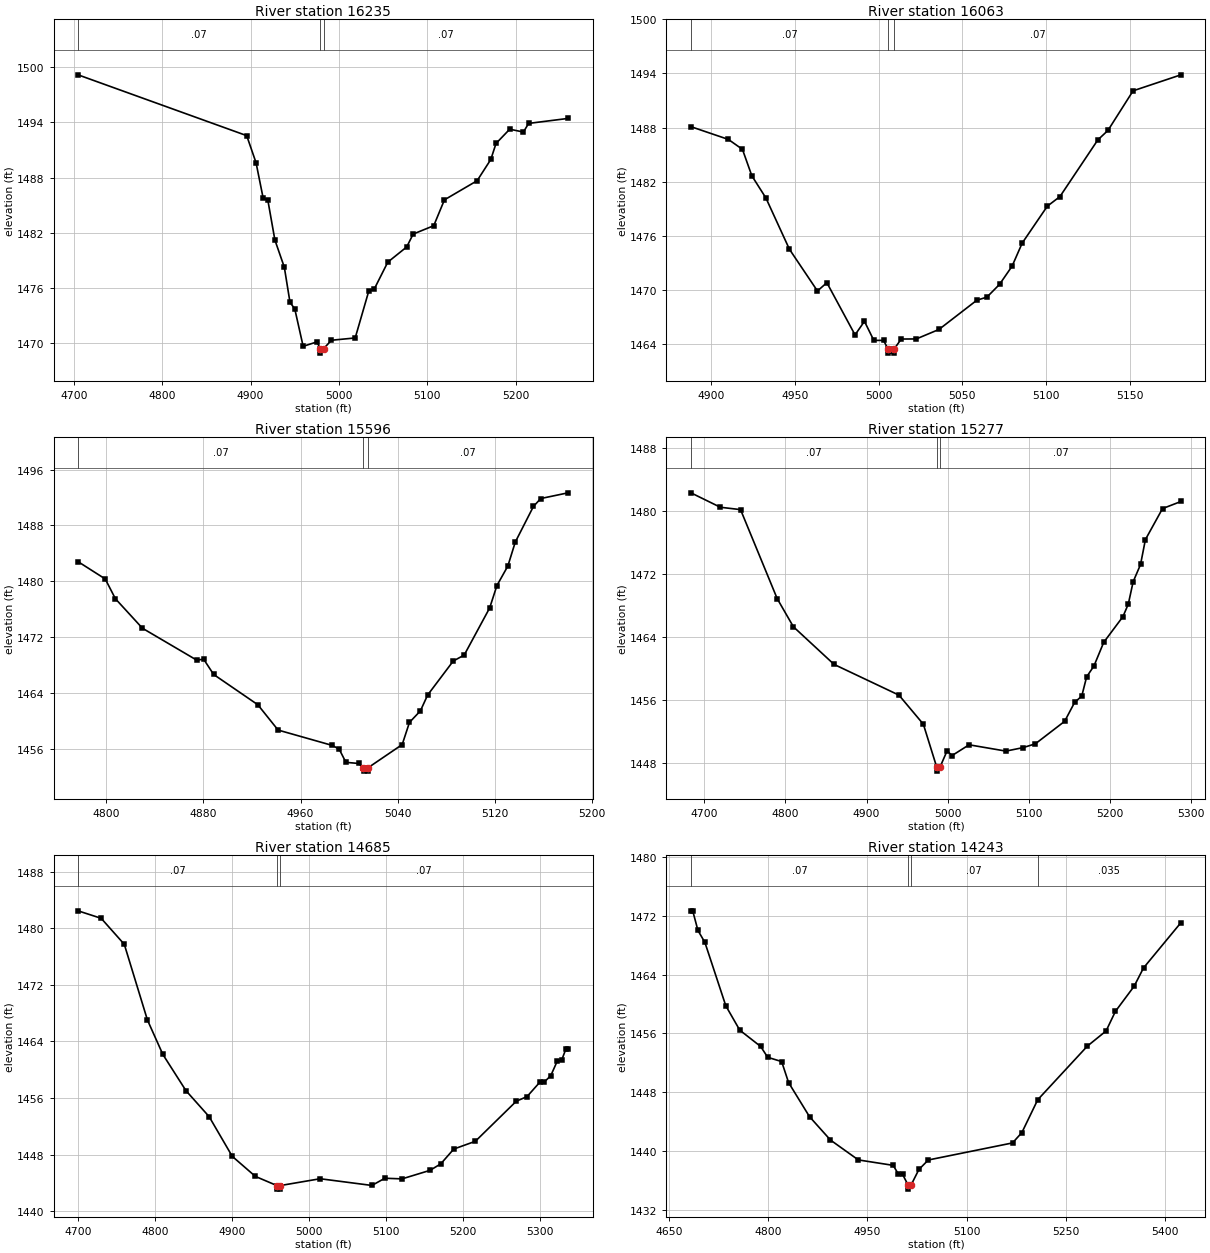
Type RM Length L Ch R = 1 ,16235   ,172,172,172
BEGIN DESCRIPTION:
Stream0131_DS 36.0
END DESCRIPTION:
XS GIS Cut Line= 3
      2030204.15     13909383.18      2029926.99     13909281.27
      2029704.66     13909414.72
#Sta/Elev= 30
  4704.7 1499.17  4895.6 1492.56  4906.2 1489.61  4914.2 1485.78  4919.5 1485.56
  4927.5 1481.22  4938.2 1478.25  4944.6 1474.44    4950 1473.73  4959.5 1469.66
  4975.1 1470.14  4978.8 1469.42  4979.1 1468.92  4982.8 1469.42  4991.5 1470.32
  5018.4 1470.57  5033.9 1475.71  5039.8 1475.85  5055.3 1478.81  5076.7 1480.46
    5084 1481.86  5107.3 1482.77  5119.4 1485.58  5156.4 1487.66  5171.9 1489.97
  5177.8 1491.71  5193.3 1493.26  5208.8 1492.95  5214.7 1493.89  5259.3 1494.43
#Mann= 3 ,-1 , 0
  4704.7     .07       0  4978.8     .05       0  4982.8     .07       0
Bank Sta=4978.8,4982.8
XS Rating Curve= 0 ,0
Exp/Cntr=0.3,0.1

Type RM Length L Ch R = 1 ,16063   ,467,467,467
BEGIN DESCRIPTION:
Stream0131_DS 35.0
END DESCRIPTION:
XS GIS Cut Line= 3
      2030074.97     13909174.98        2029975.       13909125.
      2029825.04     13909025.02
#Sta/Elev= 30
  4888.2  1488.1  4910.5 1486.69  4918.9 1485.59  4924.5 1482.66  4932.9  1480.2
  4946.9 1474.53  4963.6 1469.91  4969.2 1470.83    4986 1465.05  4991.6 1466.55
  4997.2 1464.44    5003 1464.44  5005.5 1463.53  5005.7 1463.03  5009.2 1463.03
  5009.5 1463.53  5013.5 1464.59  5022.5  1464.6    5036 1465.65  5058.6 1468.89
  5064.6 1469.23  5072.1 1470.64  5079.6 1472.66  5085.6 1475.21  5100.6  1479.3
  5108.1 1480.36  5130.7 1486.64  5136.7 1487.68  5151.7 1492.07  5180.2 1493.84
#Mann= 3 ,-1 , 0
  4888.2     .07       0  5005.5     .05       0  5009.5     .07       0
Bank Sta=5005.5,5009.5
XS Rating Curve= 0 ,0
Exp/Cntr=0.3,0.1

Type RM Length L Ch R = 1 ,15596   ,319,319,319
BEGIN DESCRIPTION:
Stream0131_DS 34.0
END DESCRIPTION:
XS GIS Cut Line= 3
      2030375.02     13909025.03        2030275.       13908825.
      2030125.02     13908725.01
#Sta/Elev= 30
  4776.6 1482.81    4799 1480.33  4807.4 1477.49  4829.7 1473.26  4874.5 1468.68
  4880.1 1468.83  4888.4 1466.63  4924.8 1462.29  4941.5 1458.66  4986.3 1456.45
  4991.9 1455.91  4997.4 1454.03  5007.8 1453.87  5011.8 1453.27    5012 1452.77
  5015.5 1452.77  5015.8 1453.27  5043.8 1456.58  5049.8 1459.76  5058.8 1461.41
  5064.8 1463.69  5085.9 1468.56  5094.9 1469.41  5115.9 1476.17  5121.9 1479.39
  5130.9 1482.18    5137 1485.61    5152 1490.73    5158 1491.86  5180.5 1492.68
#Mann= 3 ,-1 , 0
  4776.6     .07       0  5011.8     .05       0  5015.8     .07       0
Bank Sta=5011.8,5015.8
XS Rating Curve= 0 ,0
Exp/Cntr=0.3,0.1

Type RM Length L Ch R = 1 ,15277   ,592,592,592
BEGIN DESCRIPTION:
Stream0131_DS 33.0
END DESCRIPTION:
XS GIS Cut Line= 3
      2030553.44     13908981.23      2030536.08     13908673.11
      2030375.01     13908425.02
#Sta/Elev= 30
  4683.4  1482.3  4719.7 1480.47  4744.6 1480.17  4789.8 1468.88  4809.8 1465.31
  4859.9 1460.54    4940 1456.64  4970.1 1452.95  4986.6  1447.5  4986.8    1447
  4990.6  1447.5  4999.4 1449.58  5005.4 1448.97  5026.5 1450.34  5071.9 1449.54
    5093 1449.98  5108.2 1450.46  5144.4 1453.32  5156.7 1455.72  5165.5 1456.52
  5171.5 1458.96  5180.5 1460.33  5192.6 1463.34  5216.3  1466.6  5222.9 1468.19
  5228.9 1471.03    5238 1473.21    5244 1476.37  5265.1  1480.3  5287.8  1481.2
#Mann= 3 ,-1 , 0
  4683.4     .07       0  4986.6     .05       0  4990.6     .07       0
Bank Sta=4986.6,4990.6
XS Rating Curve= 0 ,0
Exp/Cntr=0.3,0.1

Type RM Length L Ch R = 1 ,14685   ,442,442,442
BEGIN DESCRIPTION:
Stream0131_DS 32.0
END DESCRIPTION:
XS GIS Cut Line= 3
      2031075.04       13908225.        2030775.       13908225.
      2030474.96     13908375.02
#Sta/Elev= 30
  4700.3 1482.49  4730.3 1481.43  4760.3 1477.75  4790.3 1467.04  4810.3 1462.17
  4840.3 1457.04  4870.3 1453.37  4900.3 1447.75  4930.3 1444.91  4958.3 1443.61
  4958.6 1443.11  4962.1 1443.11  4962.3 1443.61  5014.3 1444.58  5081.4 1443.63
  5098.2 1444.65  5120.5 1444.56  5156.9 1445.77  5170.8 1446.69  5187.6 1448.78
  5215.6 1449.88  5268.7 1455.55  5282.6  1456.2  5299.4 1458.26    5305 1458.27
  5313.4 1459.16  5321.8 1461.22  5327.4 1461.33    5333 1462.92  5335.8 1462.92
#Mann= 3 ,-1 , 0
  4700.3     .07       0  4958.3     .05       0  4962.3     .07       0
Bank Sta=4958.3,4962.3
XS Rating Curve= 0 ,0
Exp/Cntr=0.3,0.1

Type RM Length L Ch R = 1 ,14243   ,451,451,451
BEGIN DESCRIPTION:
Stream0131_DS 31.0
END DESCRIPTION:
XS GIS Cut Line= 3
      2030975.03     13907774.99        2030675.       13907875.
      2030375.02     13908174.98
#Sta/Elev= 30
  4683.2 1472.67  4685.9 1472.67  4693.8    1470  4704.3 1468.38  4735.9 1459.76
    4757 1456.45  4788.6 1454.23  4799.2 1452.76  4820.3 1452.18  4830.8 1449.32
  4862.4 1444.69  4894.1 1441.51  4936.2 1438.81  4988.9 1438.07  4996.8 1436.87
    5003 1436.87  5011.6 1435.34  5011.9 1434.84  5015.6 1435.34  5027.7 1437.51
  5041.9  1438.8  5169.2 1441.12  5183.3 1442.52  5207.3 1446.99  5282.3 1454.28
  5310.6 1456.34  5324.7    1459    5353 1462.42  5367.2 1464.91  5423.7 1471.06
#Mann= 4 ,-1 , 0
  4683.2     .07       0  5011.6     .05       0  5015.6     .07       0
  5207.3    .035       0
Bank Sta=5011.6,5015.6
XS Rating Curve= 0 ,0
Exp/Cntr=0.3,0.1

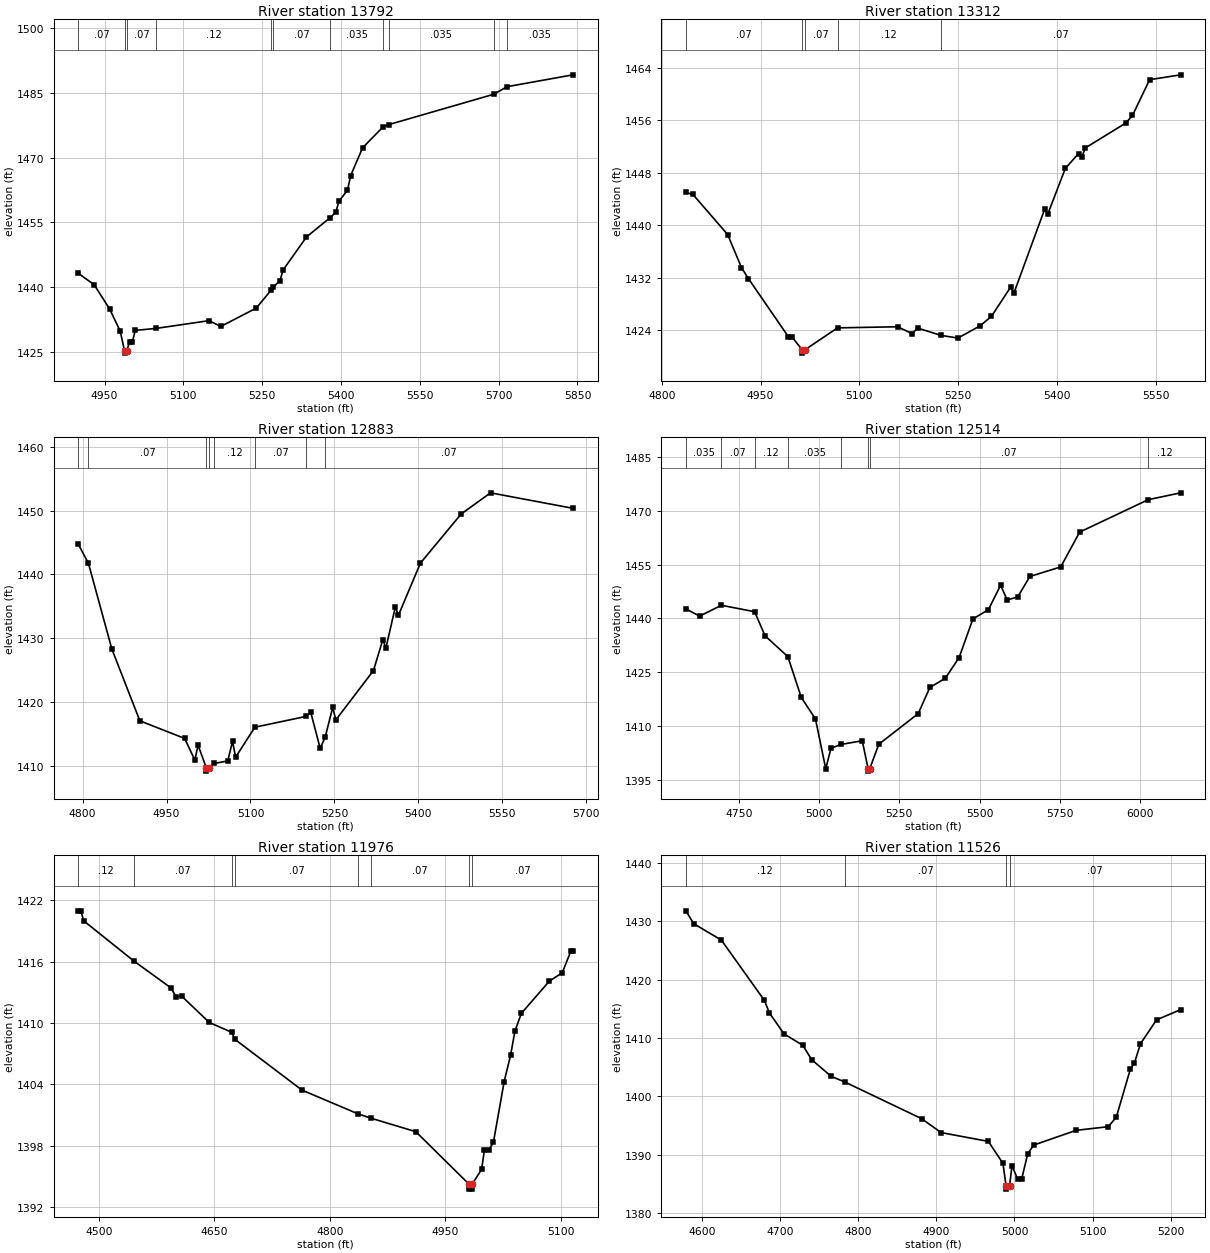
Type RM Length L Ch R = 1 ,13792   ,480,480,480
BEGIN DESCRIPTION:
Stream0131_DS 30.0
END DESCRIPTION:
XS GIS Cut Line= 3
      2030774.98       13907425.        2030675.       13907425.
      2029919.84     13907796.34
#Sta/Elev= 30
    4900 1443.17    4930 1440.57    4960 1434.84    4980 1429.72    4988 1425.19
  4988.2 1424.69    4992 1425.19  4997.5 1427.22  5002.8 1427.22  5008.4 1429.95
  5048.3 1430.42  5148.8 1432.21  5171.3 1430.87  5238.7 1435.12  5267.3 1439.32
  5271.1 1440.06  5283.7 1441.41  5289.7 1443.93  5334.3 1451.59  5378.9 1456.03
    5390 1457.29  5396.1 1459.88  5412.3 1462.42  5418.5 1465.83    5441 1472.24
  5480.8 1477.18  5490.4  1477.6  5690.4 1484.64  5715.9  1486.4  5841.5 1489.15
#Mann= 11 ,-1 , 0
    4900     .07       0    4988     .05       0    4992     .07       0
  5048.3     .12       0  5267.3    .035       0  5271.1     .07       0
  5378.9    .035       0  5480.8     .07       0  5490.4    .035       0
  5690.4     .07       0  5715.9    .035       0
Bank Sta=4988,4992
XS Rating Curve= 0 ,0
Exp/Cntr=0.3,0.1

Type RM Length L Ch R = 1 ,13312   ,429,429,429
BEGIN DESCRIPTION:
Stream0131_DS 29.0
END DESCRIPTION:
XS GIS Cut Line= 3
      2030925.02     13907025.01        2030775.       13906975.
      2030193.18     13907088.92
#Sta/Elev= 30
  4836.7 1444.97  4847.3 1444.66    4900 1438.55    4921 1433.51  4931.6 1431.82
  4992.2 1422.97  4997.4 1422.97  5013.2 1420.97  5013.5 1420.47  5017.2 1420.97
  5066.8 1424.32  5157.9 1424.49  5180.2 1423.44  5188.4 1424.29    5224 1423.17
  5249.6 1422.77  5283.2 1424.63  5300.5 1426.08  5329.6 1430.54  5334.7 1429.67
  5381.1 1442.38  5386.2 1441.73  5412.6 1448.63  5432.6 1450.89  5437.7 1450.41
  5443.2 1451.77  5504.3 1455.54  5514.5 1456.71  5540.6 1462.16  5587.7  1462.9
#Mann= 5 ,-1 , 0
  4836.7     .07       0  5013.2     .05       0  5017.2     .07       0
  5066.8     .12       0    5224     .07       0
Bank Sta=5013.2,5017.2
XS Rating Curve= 0 ,0
Exp/Cntr=0.3,0.1

Type RM Length L Ch R = 1 ,12883   ,369,369,369
BEGIN DESCRIPTION:
Stream0131_DS 28.0
END DESCRIPTION:
XS GIS Cut Line= 3
      2031074.95       13906575.        2030875.       13906575.
       2030263.2      13906880.3
#Sta/Elev= 30
  4792.4 1444.74  4810.6 1441.72  4852.4 1428.28  4902.4 1417.03  4982.4 1414.27
  5000.7 1410.86  5006.3 1413.24  5021.1 1409.64  5021.4 1409.14  5025.1 1409.64
  5035.4 1410.35  5059.4 1410.74  5067.9 1413.81  5073.5 1411.32  5107.8 1416.03
  5199.3 1417.72  5207.7 1418.34  5224.5 1412.71  5233.6 1414.52  5246.9 1419.15
  5252.4 1417.17  5319.6  1424.9  5336.4 1429.76  5341.9 1428.45  5358.7 1434.86
  5364.3 1433.59  5403.5 1441.76  5476.2 1449.46  5528.8 1452.79  5676.1 1450.36
#Mann= 8 ,-1 , 0
  4792.4     .12       0  4810.6     .07       0  5021.1     .05       0
  5025.1     .07       0  5035.4     .12       0  5107.8     .07       0
  5199.3     .12       0  5233.6     .07       0
Bank Sta=5021.1,5025.1
XS Rating Curve= 0 ,0
Exp/Cntr=0.3,0.1

Type RM Length L Ch R = 1 ,12514   ,538,538,538
BEGIN DESCRIPTION:
Stream0131_DS 27.0
END DESCRIPTION:
XS GIS Cut Line= 3
      2031365.11     13906381.46        2030925.       13906225.
      2029878.21     13906463.49
#Sta/Elev= 30
  4585.7 1442.61  4628.3 1440.61  4696.1 1443.63  4799.5 1441.84  4832.1  1435.1
    4903  1429.3  4944.8 1417.92  4989.1 1411.88    5021 1398.01  5037.4 1403.74
  5068.9  1404.8  5134.8 1405.81  5153.4 1397.84  5153.6 1397.34  5157.4 1397.84
  5186.1 1404.83  5309.2 1413.41  5345.2 1420.69  5393.4 1423.25  5436.4 1429.05
  5479.4 1439.82  5527.6  1442.4  5565.5 1449.22  5586.1 1445.13  5618.8 1445.95
  5656.7 1451.67  5752.9 1454.34  5811.8 1464.06  6025.4 1473.11  6126.4 1475.02
#Mann= 8 ,-1 , 0
  4585.7    .035       0  4696.1     .07       0  4799.5     .12       0
    4903    .035       0  5068.9     .07       0  5153.4    .035       0
  5157.4     .07       0  6025.4     .12       0
Bank Sta=5153.4,5157.4
XS Rating Curve= 0 ,0
Exp/Cntr=0.3,0.1

Type RM Length L Ch R = 1 ,11976   ,450,450,450
BEGIN DESCRIPTION:
Stream0131_DS 26.0
END DESCRIPTION:
XS GIS Cut Line= 3
      2031224.97     13906124.98        2030825.       13905775.
      2030774.99     13905674.98
#Sta/Elev= 30
  4472.9 1420.95  4476.2 1420.95    4480 1419.97  4544.8 1416.07  4592.9 1413.45
  4600.5 1412.53  4607.2 1412.63  4643.2 1410.05  4672.3 1409.09  4676.7 1408.39
  4763.8 1403.44  4836.7 1401.12  4853.4  1400.7  4911.8 1399.38  4980.8 1394.27
  4981.1 1393.77  4984.9 1393.77  4985.2 1394.27  4997.3 1395.69  5001.1 1397.63
  5007.2 1397.63  5012.8 1398.38  5026.7 1404.28  5035.1 1406.87  5040.7 1409.21
  5049.1 1410.94  5085.4 1414.08  5102.2  1414.9  5113.4 1417.01  5116.2 1417.01
#Mann= 8 ,-1 , 0
  4472.9     .12       0  4544.8     .07       0  4672.3    .035       0
  4676.7     .07       0  4836.7    .035       0  4853.4     .07       0
  4980.8     .05       0  4985.2     .07       0
Bank Sta=4980.8,4985.2
XS Rating Curve= 0 ,0
Exp/Cntr=0.3,0.1

Type RM Length L Ch R = 1 ,11526   ,482,482,482
BEGIN DESCRIPTION:
Stream0131_DS 25.0
END DESCRIPTION:
XS GIS Cut Line= 3
      2031474.98     13905275.01        2031075.       13905425.
      2030875.03     13905474.99
#Sta/Elev= 30
  4579.5 1431.78  4589.3 1429.59  4624.9 1426.76    4680 1416.43  4686.3 1414.31
    4705 1410.72    4729 1408.76  4740.6 1406.28  4765.5 1403.44  4782.7 1402.49
  4881.2  1396.2  4906.1 1393.82  4966.6 1392.31  4985.3 1388.55  4989.3 1384.64
  4989.6 1384.14  4993.7 1384.64  4996.9 1388.17    5004 1385.87  5009.3 1385.87
    5017  1390.2  5024.7 1391.68  5078.8  1394.2  5120.1 1394.83  5130.4 1396.46
  5148.4 1404.69  5153.6 1405.73  5161.3 1409.02  5181.9 1413.11  5212.8 1414.87
#Mann= 4 ,-1 , 0
  4579.5     .12       0  4782.7     .07       0  4989.3     .05       0
  4993.7     .07       0
Bank Sta=4989.3,4993.7
XS Rating Curve= 0 ,0
Exp/Cntr=0.3,0.1

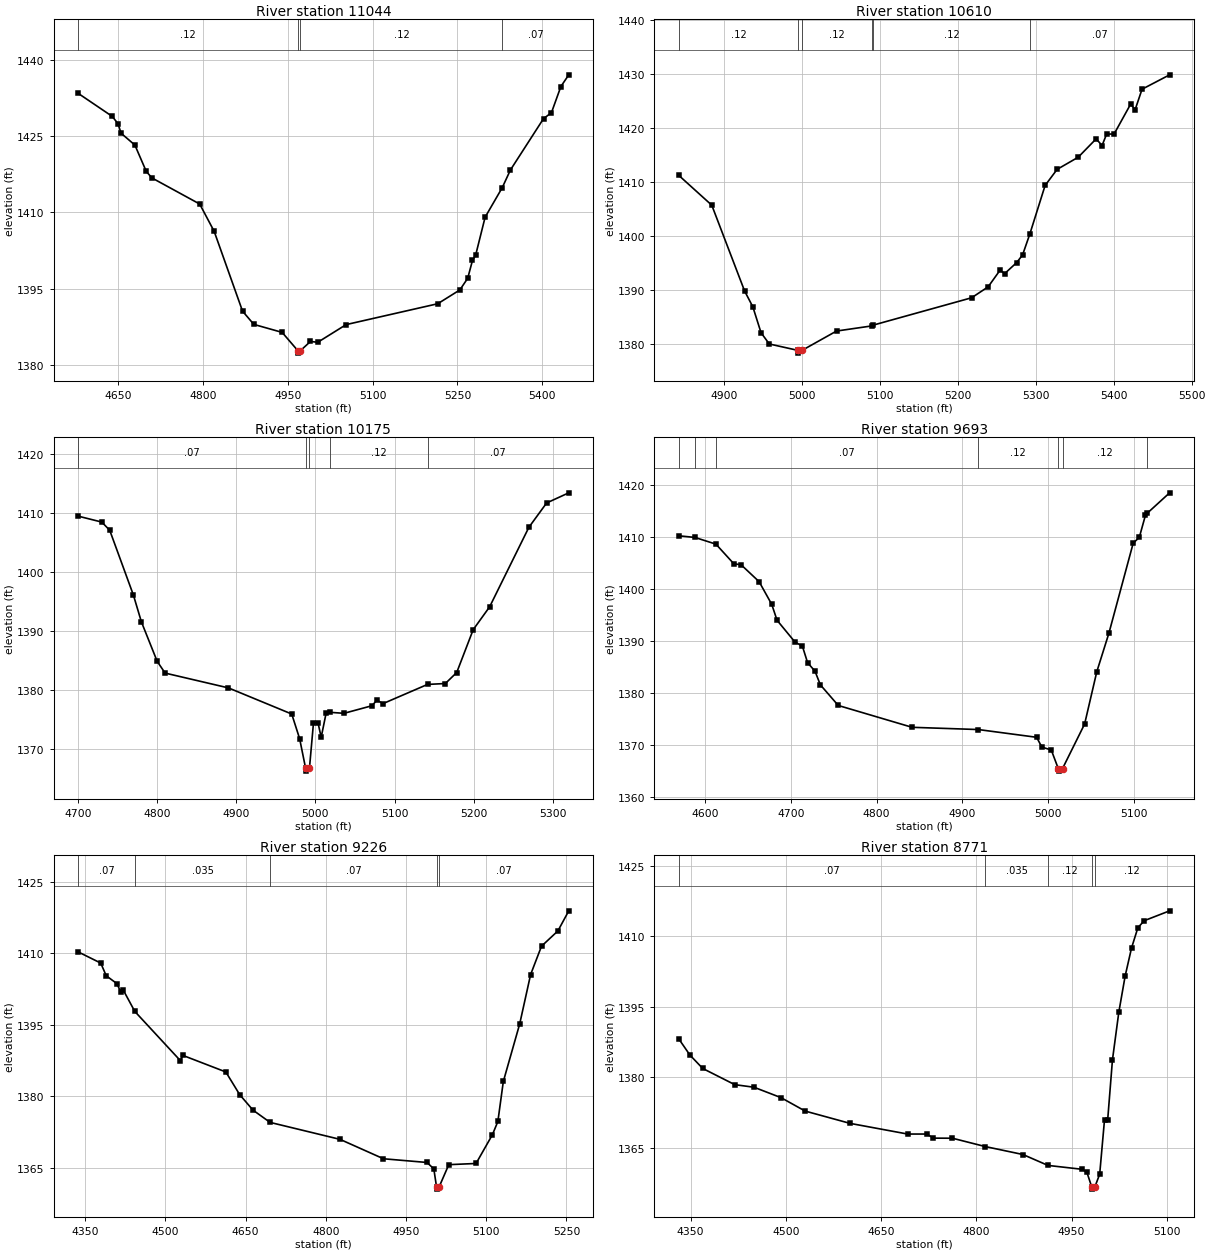
Type RM Length L Ch R = 1 ,11044   ,434,434,434
BEGIN DESCRIPTION:
Stream0131_DS 24.0
END DESCRIPTION:
XS GIS Cut Line= 3
      2031495.29     13905005.58        2031075.       13904975.
      2030675.01     13904775.01
#Sta/Elev= 30
  4578.6  1433.4    4639 1428.86  4649.1 1427.45  4654.8 1425.54  4679.2 1423.21
  4699.2 1418.06  4709.2 1416.76  4793.9 1411.62  4819.5 1406.25  4869.7 1390.56
  4889.7 1387.95  4939.8 1386.38  4967.5  1382.8  4967.9  1382.3  4972.3  1382.8
    4990  1384.6  5002.8 1384.43  5053.1 1387.91  5215.2 1392.01  5254.4 1394.73
  5268.3 1397.02  5276.7 1400.52  5282.3 1401.55  5299.1 1409.03  5329.5 1414.86
  5343.8  1418.3  5402.5 1428.42  5416.5 1429.58  5433.2 1434.73  5447.2 1437.03
#Mann= 4 ,-1 , 0
  4578.6     .12       0  4967.5     .05       0  4972.3     .12       0
  5329.5     .07       0
Bank Sta=4967.5,4972.3
XS Rating Curve= 0 ,0
Exp/Cntr=0.3,0.1

Type RM Length L Ch R = 1 ,10610   ,435,435,435
BEGIN DESCRIPTION:
Stream0131_DS 23.0
END DESCRIPTION:
XS GIS Cut Line= 3
        2031325.       13904625.        2031175.       13904575.
      2030775.02     13904325.01
#Sta/Elev= 30
  4841.9 1411.19  4884.1  1405.7  4926.2 1389.85  4936.8 1386.92  4947.3 1382.14
  4957.9 1380.06  4994.9 1378.87  4995.3 1378.37  4999.8 1378.87  5044.2 1382.45
  5089.1 1383.39  5091.4 1383.55  5217.6  1388.6  5238.8 1390.62  5254.1  1393.7
    5260 1393.06  5275.4  1395.1    5283 1396.52  5292.5 1400.47  5311.9 1409.35
  5327.3 1412.32  5354.4 1414.57  5377.4 1417.96    5385 1416.73  5390.9 1418.86
  5400.4 1418.84  5421.6 1424.36  5427.5 1423.37  5436.3 1427.13  5471.7 1429.79
#Mann= 6 ,-1 , 0
  4841.9     .12       0  4994.9     .05       0  4999.8     .12       0
  5089.1     .07       0  5091.4     .12       0  5292.5     .07       0
Bank Sta=4994.9,4999.8
XS Rating Curve= 0 ,0
Exp/Cntr=0.3,0.1

Type RM Length L Ch R = 1 ,10175   ,482,482,482
BEGIN DESCRIPTION:
Stream0131_DS 22.0
END DESCRIPTION:
XS GIS Cut Line= 3
      2031574.98       13904175.        2031275.       13904175.
      2031075.03     13903925.03
#Sta/Elev= 30
  4700.1 1409.52  4730.1 1408.51  4740.1 1407.12  4770.1  1396.1  4780.1  1391.6
  4800.1 1384.89  4810.1 1382.91  4890.1  1380.4  4970.1 1375.97  4980.1 1371.78
  4987.6 1366.79    4988 1366.29  4992.5 1366.79  4997.6  1374.5  5003.3  1374.5
  5007.3 1372.02  5013.7 1376.22  5018.5 1376.26  5036.1 1376.09  5071.3 1377.37
  5077.7  1378.3  5085.7 1377.75  5141.7 1380.99  5164.2 1381.14  5178.6 1383.01
  5199.4 1390.27  5220.2 1394.15  5269.8 1407.63  5292.2 1411.75  5320.2 1413.47
#Mann= 5 ,-1 , 0
  4700.1     .07       0  4987.6     .05       0  4992.5     .07       0
  5018.5     .12       0  5141.7     .07       0
Bank Sta=4987.6,4992.5
XS Rating Curve= 0 ,0
Exp/Cntr=0.3,0.1

Type RM Length L Ch R = 1 ,9693    ,467,467,467
BEGIN DESCRIPTION:
Stream0131_DS 21.0
END DESCRIPTION:
XS GIS Cut Line= 3
        2031625.       13904075.        2031375.       13903725.
      2031275.03     13903625.03
#Sta/Elev= 30
  4569.8 1410.18  4588.4 1409.87  4612.9 1408.58  4633.7 1404.81  4642.3  1404.6
  4663.2 1401.36  4677.9    1397  4684.1 1393.93    4705 1389.74  4713.6 1388.96
  4719.7 1385.76  4728.3 1384.14  4734.5 1381.52  4755.4 1377.54  4841.4 1373.34
  4918.4 1372.91  4986.4 1371.42  4992.5 1369.54  5003.5 1368.97  5011.6 1365.41
    5012 1364.91  5016.6 1365.41  5042.3 1373.97  5056.5 1384.04  5070.6 1391.45
  5098.9 1408.78    5106 1409.88  5113.1 1414.11  5115.4 1414.55  5141.3 1418.45
#Mann= 7 ,-1 , 0
  4569.8     .07       0  4588.4     .12       0  4612.9     .07       0
  4918.4     .12       0  5011.6     .05       0  5016.6     .12       0
  5115.4     .07       0
Bank Sta=5011.6,5016.6
XS Rating Curve= 0 ,0
Exp/Cntr=0.3,0.1

Type RM Length L Ch R = 1 ,9226    ,455,455,455
BEGIN DESCRIPTION:
Stream0131_DS 20.0
END DESCRIPTION:
XS GIS Cut Line= 3
      2031794.76     13904076.74        2031675.       13903425.
        2031425.       13903375.
#Sta/Elev= 30
  4336.8 1410.32  4379.2 1407.96  4389.4  1405.3  4409.7 1403.62  4416.6 1401.81
  4421.7  1402.2  4442.9  1397.8  4527.9 1387.48    4533 1388.55  4613.1 1385.08
  4639.1  1380.3  4663.9 1377.06  4695.9 1374.48  4826.6 1370.92  4907.9 1366.84
  4989.3 1366.06    5002 1364.72  5007.1 1360.96  5007.5 1360.46  5012.1 1360.96
    5030  1365.6    5081 1365.85  5111.6  1371.9  5121.8 1374.68    5132 1383.08
  5162.6 1395.17    5183 1405.54  5203.4 1411.51    5234 1414.71  5254.4 1418.94
#Mann= 5 ,-1 , 0
  4336.8     .07       0  4442.9    .035       0  4695.9     .07       0
  5007.1     .05       0  5012.1     .07       0
Bank Sta=5007.1,5012.1
XS Rating Curve= 0 ,0
Exp/Cntr=0.3,0.1

Type RM Length L Ch R = 1 ,8771    ,482,482,482
BEGIN DESCRIPTION:
Stream0131_DS 19.0
END DESCRIPTION:
XS GIS Cut Line= 3
      2031990.07     13903942.25        2032075.       13903275.
        2032075.     13903175.03
#Sta/Elev= 30
  4331.7 1388.16  4349.1 1384.75  4369.2 1381.91  4419.6 1378.47  4449.9 1377.92
  4492.4 1375.71  4530.5 1372.85  4601.1 1370.24  4691.8 1367.97  4722.1 1367.97
  4732.2  1367.1  4762.4 1367.08    4814 1365.31  4873.3 1363.62  4912.8  1361.3
  4966.9 1360.47  4974.1 1359.82  4981.6 1356.76    4982 1356.26  4986.7 1356.76
  4994.2 1359.44  5001.8 1371.01  5006.8 1371.01  5014.3 1383.74  5024.3 1393.86
  5034.3 1401.57  5044.3  1407.5  5054.3 1411.82  5064.3 1413.32  5104.3 1415.42
#Mann= 5 ,-1 , 0
  4331.7     .07       0    4814    .035       0  4912.8     .12       0
  4981.6     .05       0  4986.7     .12       0
Bank Sta=4981.6,4986.7
XS Rating Curve= 0 ,0
Exp/Cntr=0.3,0.1

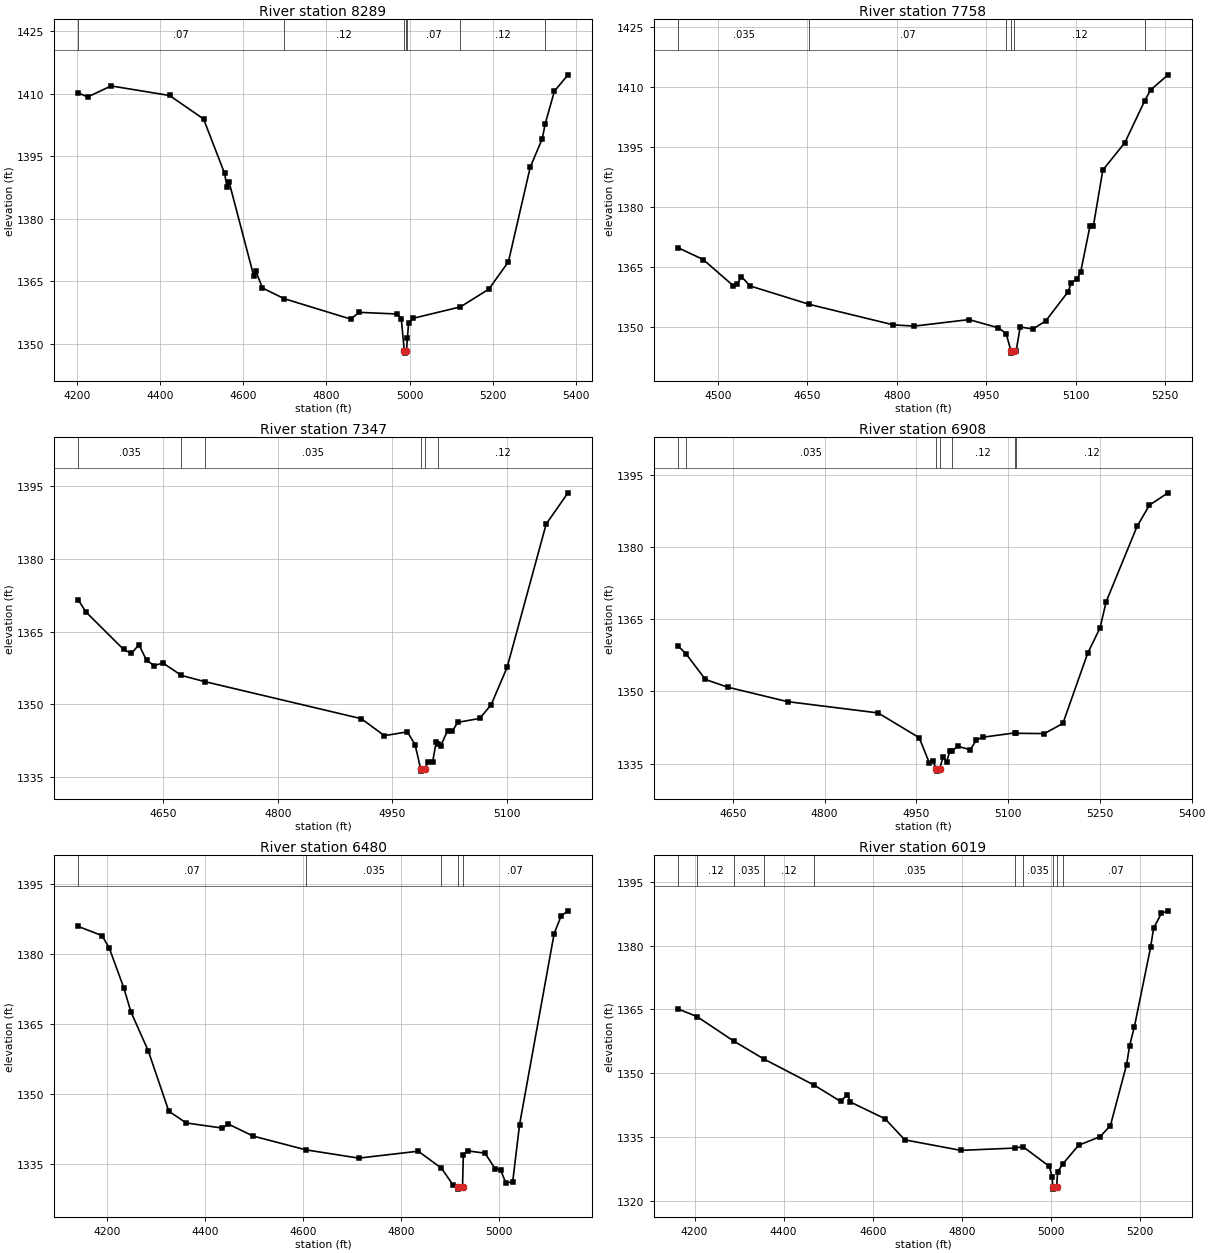
Type RM Length L Ch R = 1 ,8289    ,531,531,531
BEGIN DESCRIPTION:
Stream0131_DS 18.0
END DESCRIPTION:
XS GIS Cut Line= 3
      2032406.74     13904163.58        2032525.       13903375.
        2032375.     13903024.99
#Sta/Elev= 30
  4202.7 1410.23  4225.6  1409.2  4282.2 1411.85  4422.8 1409.56  4504.6 1403.93
  4555.2 1390.88    4561 1387.55  4566.1 1388.77  4625.1 1366.36  4630.1 1367.49
  4646.2 1363.45  4697.9  1360.9  4858.5 1355.99  4878.8 1357.61  4970.6 1357.21
  4979.9 1356.09  4987.4 1348.34  4987.8 1347.84  4992.5 1348.34  4994.9 1351.53
  4997.6 1355.12  5009.2  1356.2  5122.3 1358.92  5190.5 1363.16  5237.6 1369.71
  5290.2 1392.42  5319.2 1399.23  5325.9  1402.7  5348.2 1410.59  5380.9 1414.51
#Mann= 7 ,-1 , 0
  4202.7     .07       0  4697.9     .12       0  4987.4     .05       0
  4992.5     .12       0  4994.9     .07       0  5122.3     .12       0
  5325.9     .07       0
Bank Sta=4987.4,4992.5
XS Rating Curve= 0 ,0
Exp/Cntr=0.3,0.1

Type RM Length L Ch R = 1 ,7758    ,411,411,411
BEGIN DESCRIPTION:
Stream0131_DS 17.0
END DESCRIPTION:
XS GIS Cut Line= 3
        2033125.       13903475.      2032749.62     13903056.79
        2032525.       13902925.
#Sta/Elev= 30
  4432.8  1369.8    4475 1366.85  4525.1 1360.34  4531.8 1360.62  4539.3 1362.58
  4553.5 1360.25  4653.3 1355.62  4794.2  1350.5  4829.4 1350.19  4921.3 1351.82
  4970.6 1349.76  4983.4 1348.33  4991.8 1343.93  4992.2 1343.43  4997.2 1343.93
  5000.3 1343.93  5007.1 1349.97  5028.5 1349.47    5050 1351.48  5087.2 1358.72
    5093 1361.01  5102.8 1362.04  5108.6  1363.7  5124.3 1375.25  5130.1 1375.34
  5145.8 1389.22  5182.9  1396.1  5215.8 1406.47  5225.9 1409.25  5255.2 1413.05
#Mann= 6 ,-1 , 0
  4432.8    .035       0  4653.3     .07       0  4983.4     .12       0
  4991.8     .05       0  4997.2     .12       0  5215.8     .07       0
Bank Sta=4991.8,4997.2
XS Rating Curve= 0 ,0
Exp/Cntr=0.3,0.1

Type RM Length L Ch R = 1 ,7347    ,439,439,439
BEGIN DESCRIPTION:
Stream0131_DS 16.0
END DESCRIPTION:
XS GIS Cut Line= 3
      2033170.63     13903434.42        2033125.       13902975.
      2033024.98     13902824.97
#Sta/Elev= 30
  4538.2 1371.62  4548.6 1369.04  4597.9 1361.32    4608 1360.49    4618 1362.28
  4628.1 1359.04  4638.1    1358  4649.5 1358.52  4673.6 1355.96  4704.3 1354.68
  4909.4 1347.03  4939.6 1343.53  4969.7 1344.31  4979.8  1341.7  4987.1 1336.71
  4987.5 1336.21  4992.5 1336.71  4997.4 1338.18  5002.9 1338.18  5007.4 1342.14
  5010.2  1341.8  5013.4 1341.41  5022.4 1344.55  5028.4 1344.41  5035.9 1346.28
  5064.5 1347.08  5079.5  1349.9  5100.5 1357.66  5151.6 1387.19  5180.2 1393.64
#Mann= 6 ,-1 , 0
  4538.2    .035       0  4673.6     .07       0  4704.3    .035       0
  4987.1    .035       0  4992.5    .035       0  5010.2     .12       0
Bank Sta=4987.1,4992.5
XS Rating Curve= 0 ,0
Exp/Cntr=0.3,0.1

Type RM Length L Ch R = 1 ,6908    ,428,428,428
BEGIN DESCRIPTION:
Stream0131_DS 15.0
END DESCRIPTION:
XS GIS Cut Line= 3
      2033325.01     13903324.98        2033525.       13902925.
      2033574.99     13902575.04
#Sta/Elev= 30
  4560.6 1359.47  4574.4  1357.7  4605.3  1352.5  4641.6  1350.9  4739.5 1347.89
  4887.6 1345.54  4954.7 1340.39  4971.5 1335.08    4977  1335.5  4982.6 1333.94
  4983.1 1333.44  4988.2 1333.94  4993.8 1336.39  4999.4 1335.38    5005 1337.61
  5007.6 1337.61  5017.9 1338.62  5038.1 1337.87  5048.2 1339.92  5058.3 1340.48
  5111.3 1341.39  5112.5 1341.31  5159.3 1341.24  5189.6 1343.37    5230 1357.93
  5250.2  1363.2  5260.3 1368.67  5310.8 1384.33    5331 1388.74  5361.3  1391.3
#Mann= 7 ,-1 , 0
  4560.6     .07       0  4574.4    .035       0  4982.6    .035       0
  4988.2    .035       0  5007.6     .12       0  5111.3     .07       0
  5112.5     .12       0
Bank Sta=4982.6,4988.2
XS Rating Curve= 0 ,0
Exp/Cntr=0.3,0.1

Type RM Length L Ch R = 1 ,6480    ,461,461,461
BEGIN DESCRIPTION:
Stream0131_DS 14.0
END DESCRIPTION:
XS GIS Cut Line= 3
      2034524.97     13903174.98        2033825.       13902675.
      2033725.02     13902575.02
#Sta/Elev= 30
  4139.8 1385.86  4188.9 1383.87  4203.7  1381.2  4233.2 1372.76  4247.9  1367.6
  4283.5 1359.23  4325.3 1346.39    4361 1343.87  4434.7 1342.78    4447 1343.64
  4497.4 1341.08  4605.5 1338.13  4713.7 1336.36  4835.3 1337.84  4882.8  1334.2
  4906.6  1330.6    4917 1330.24  4917.5 1329.74  4925.8 1330.24  4927.5 1337.12
  4936.1 1337.91  4971.7 1337.42  4992.6 1334.09  5003.5 1333.88  5014.1 1331.12
  5028.3 1331.24  5042.4 1343.51  5113.1 1384.31  5127.3 1388.05  5141.4 1389.17
#Mann= 5 ,-1 , 0
  4139.8     .07       0  4605.5    .035       0  4882.8     .07       0
    4917     .05       0  4925.8     .07       0
Bank Sta=4917,4925.8
XS Rating Curve= 0 ,0
Exp/Cntr=0.3,0.1

Type RM Length L Ch R = 1 ,6019    ,474,474,474
BEGIN DESCRIPTION:
Stream0131_DS 13.0
END DESCRIPTION:
XS GIS Cut Line= 3
      2034924.08     13902783.35        2034175.       13902425.
      2033925.04     13902325.01
#Sta/Elev= 30
  4162.9  1365.1  4205.2 1363.31  4288.5  1357.5  4355.8 1353.31  4468.9 1347.15
  4527.7 1343.36  4542.9 1344.93  4549.9 1343.19  4627.5 1339.28  4671.8 1334.31
  4797.8 1331.84  4920.1 1332.39  4936.6 1332.75    4996 1328.09  5002.7 1325.57
  5003.7 1323.23  5004.2 1322.73  5012.5 1323.23  5014.8 1326.77  5026.8  1328.7
  5061.9 1333.04  5110.4 1335.08  5133.3 1337.68  5169.6 1352.01  5176.4 1356.46
  5187.1 1360.91  5223.5 1379.58  5230.2 1384.07  5247.7 1387.56  5262.5 1388.16
#Mann= 10 ,-1 , 0
  4162.9     .07       0  4205.2     .12       0  4288.5    .035       0
  4355.8     .12       0  4468.9    .035       0  4920.1     .07       0
  4936.6    .035       0  5003.7    .035       0  5012.5    .035       0
  5026.8     .07       0
Bank Sta=5003.7,5012.5
XS Rating Curve= 0 ,0
Exp/Cntr=0.3,0.1

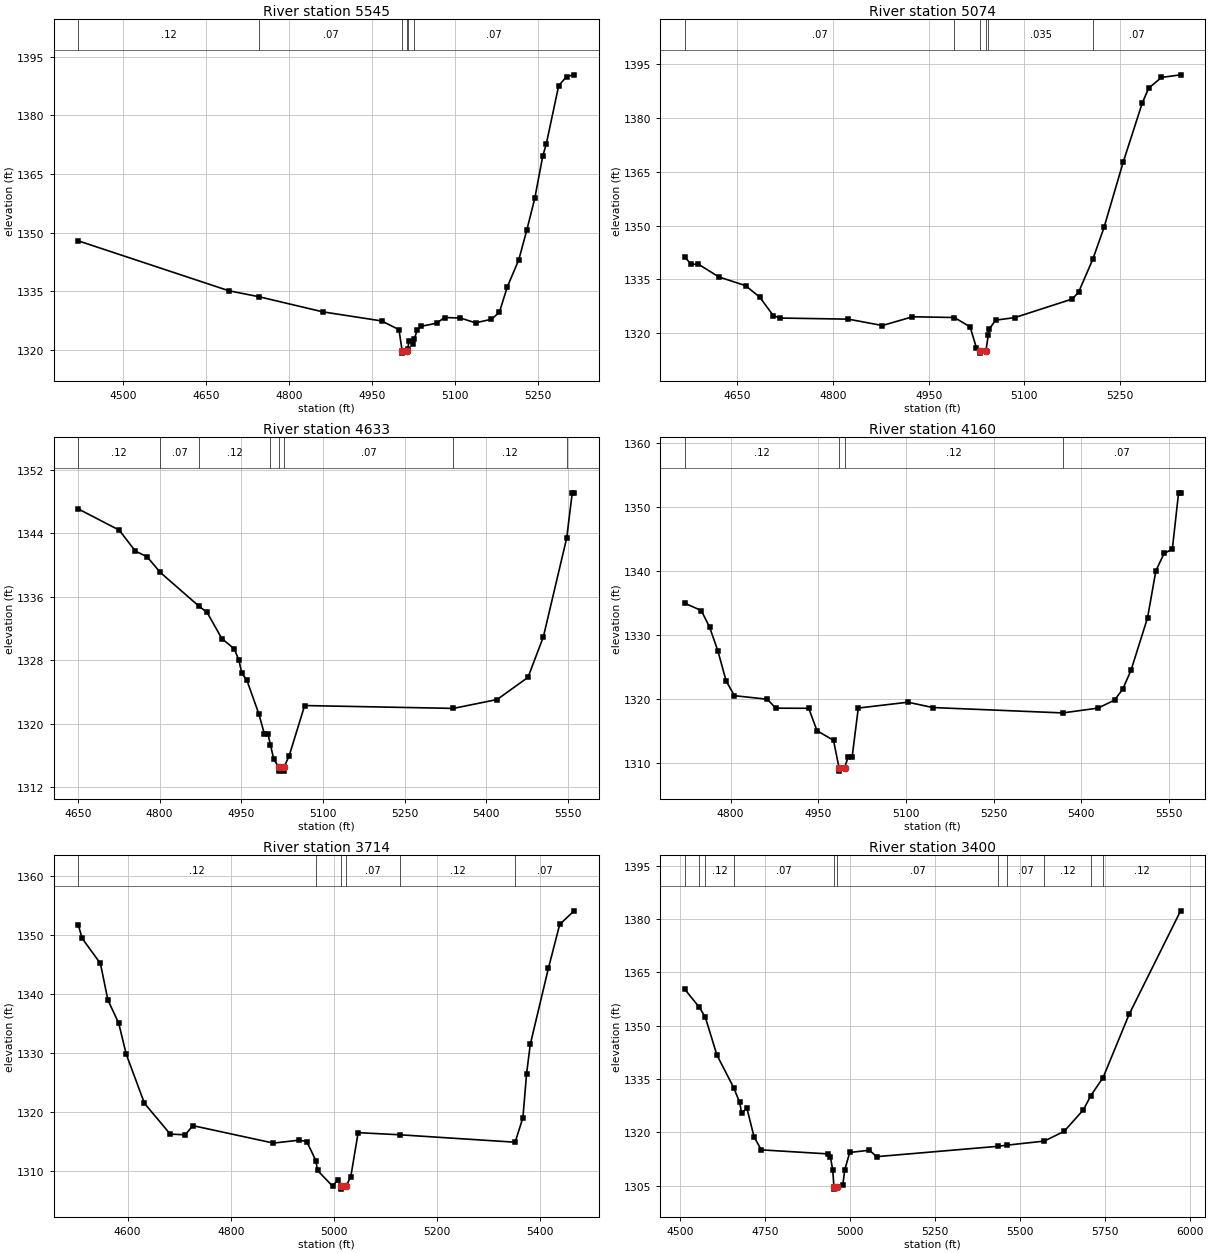
Type RM Length L Ch R = 1 ,5545    ,471,471,471
BEGIN DESCRIPTION:
Stream0131_DS 12.0
END DESCRIPTION:
XS GIS Cut Line= 3
        2034859.     13902505.58        2034475.       13902075.
      2034224.99     13901874.99
#Sta/Elev= 30
  4418.9 1347.88  4691.1 1335.11  4745.8 1333.57  4861.6 1329.69  4967.8 1327.37
    4999 1325.14  5004.9 1319.63  5005.4 1319.13    5014 1319.63  5014.6  1320.1
  5017.4 1322.31  5023.8 1321.42    5027 1322.83  5031.9    1325  5038.3 1325.99
  5067.1 1326.78  5081.5 1328.25  5110.3 1328.12  5137.5 1326.89  5166.3  1327.8
  5180.7  1329.6  5195.1  1336.1  5215.9 1343.08  5230.3 1350.62  5244.8 1358.82
  5259.2 1369.58  5265.6 1372.71    5288 1387.62  5302.4 1389.97    5316  1390.4
#Mann= 6 ,-1 , 0
  4418.9     .12       0  4745.8     .07       0  5004.9     .05       0
    5014     .07       0  5014.6    .035       0    5027     .07       0
Bank Sta=5004.9,5014
XS Rating Curve= 0 ,0
Exp/Cntr=0.3,0.1

Type RM Length L Ch R = 1 ,5074    ,441,441,441
BEGIN DESCRIPTION:
Stream0131_DS 11.0
END DESCRIPTION:
XS GIS Cut Line= 3
      2035075.01       13901825.        2034675.       13901675.
      2034325.01       13901675.
#Sta/Elev= 30
  4567.7 1341.29  4577.5 1339.23  4589.1 1339.23  4621.1  1335.7  4662.9 1333.27
  4685.2 1330.06  4706.6 1324.87  4717.2 1324.24    4824 1323.93  4877.4 1322.15
  4924.6 1324.59  4990.2 1324.39  5014.9 1321.79  5024.9 1315.87  5030.3 1314.96
  5030.8 1314.46  5039.5 1314.96  5043.4 1319.43  5044.9 1321.15  5054.9 1323.65
  5084.9 1324.36  5174.9 1329.54  5184.9 1331.42  5207.3 1340.66  5224.9 1349.52
  5254.9 1367.71  5284.9 1384.25  5294.9 1388.33  5314.9  1391.3  5344.9 1392.03
#Mann= 6 ,-1 , 0
  4567.7     .07       0  4990.2     .12       0  5030.3     .05       0
  5039.5     .12       0  5043.4    .035       0  5207.3     .07       0
Bank Sta=5030.3,5039.5
XS Rating Curve= 0 ,0
Exp/Cntr=0.3,0.1

Type RM Length L Ch R = 1 ,4633    ,473,473,473
BEGIN DESCRIPTION:
Stream0131_DS 10.0
END DESCRIPTION:
XS GIS Cut Line= 3
      2035319.08     13901654.89        2035025.       13901475.
      2034625.02     13901075.02
#Sta/Elev= 30
  4650.9 1347.08    4726 1344.41  4755.7 1341.76    4777 1341.07  4801.3 1339.09
  4872.8 1334.81  4887.3 1334.05  4914.4 1330.75    4937 1329.47  4945.3 1328.11
  4951.2 1326.39  4960.5 1325.48  4982.1 1321.31  4992.7 1318.71  4999.2 1318.71
  5003.6 1317.39  5009.8 1315.53  5019.3 1314.56  5019.8 1314.06  5028.1 1314.06
  5028.6 1314.56  5038.1    1316  5066.4 1322.32  5339.7 1321.96  5419.9 1323.08
  5476.5 1325.87  5504.8 1330.98  5547.6 1343.42  5557.8 1349.11  5561.3 1349.11
#Mann= 8 ,-1 , 0
  4650.9     .12       0  4801.3     .07       0  4872.8     .12       0
  5003.6     .07       0  5019.3     .05       0  5028.6     .07       0
  5339.7     .12       0  5547.6     .07       0
Bank Sta=5019.3,5028.6
XS Rating Curve= 0 ,0
Exp/Cntr=0.3,0.1

Type RM Length L Ch R = 1 ,4160    ,446,446,446
BEGIN DESCRIPTION:
Stream0131_DS 9.0
END DESCRIPTION:
XS GIS Cut Line= 3
      2035424.97     13901274.97        2035225.       13901075.
      2034824.99     13900674.99
#Sta/Elev= 30
  4721.7 1334.93  4749.9 1333.79  4764.1  1331.2  4778.2 1327.53  4792.4 1322.82
  4806.5 1320.51  4863.1 1319.95  4877.2 1318.56  4933.8 1318.54  4947.9 1315.05
  4976.2 1313.54  4985.7 1309.24  4986.2 1308.74    4995 1309.24    5001  1310.9
    5008  1310.9  5018.6 1318.58  5103.5 1319.49  5145.9 1318.66  5368.4 1317.82
  5428.8 1318.57  5457.1 1319.82  5471.2 1321.54  5485.3 1324.47  5513.6 1332.66
  5527.8 1339.97  5541.9 1342.71    5556 1343.35  5566.7 1352.15  5570.2 1352.15
#Mann= 4 ,-1 , 0
  4721.7     .12       0  4985.7     .05       0    4995     .12       0
  5368.4     .07       0
Bank Sta=4985.7,4995
XS Rating Curve= 0 ,0
Exp/Cntr=0.3,0.1

Type RM Length L Ch R = 1 ,3714    ,314,314,314
BEGIN DESCRIPTION:
Stream0131_DS 8.0
END DESCRIPTION:
XS GIS Cut Line= 3
      2035875.03     13901025.03        2035475.       13900725.
      2035125.02     13900425.01
#Sta/Elev= 30
  4504.7 1351.62    4512 1349.39  4547.5 1345.12    4562 1338.92  4582.9 1335.02
  4597.5 1329.75  4632.9 1321.41  4682.9  1316.2    4712 1316.09  4726.6 1317.64
  4882.9 1314.68  4932.9 1315.18  4947.5 1314.94    4965 1311.72  4968.3 1310.04
  4997.5 1307.39    5008 1308.47  5013.8 1307.38  5014.3 1306.88  5023.2 1307.38
  5032.7 1308.95    5047 1316.45  5127.5 1316.09  5351.3 1314.83  5366.4    1319
  5373.5 1326.47  5380.7 1331.43  5415.8 1344.31  5437.7 1351.74  5465.7 1354.04
#Mann= 6 ,-1 , 0
  4504.7     .12       0    4965     .07       0  5013.8     .05       0
  5023.2     .07       0  5127.5     .12       0  5351.3     .07       0
Bank Sta=5013.8,5023.2
XS Rating Curve= 0 ,0
Exp/Cntr=0.3,0.1

Type RM Length L Ch R = 1 ,3400    ,153,153,153
BEGIN DESCRIPTION:
Stream0131_DS 7.5
END DESCRIPTION:
XS GIS Cut Line= 3
      2035958.83     13900962.49      2035698.12     13900551.27
      2035018.62     13899856.94
#Sta/Elev= 30
  4513.1 1360.19  4555.4  1355.2  4573.4 1352.36  4607.5 1341.73  4656.9 1332.54
  4674.5 1328.38  4680.4 1325.37  4695.7  1326.8  4716.8 1318.71    4738 1315.05
  4935.5 1313.91  4941.4 1313.08  4948.2 1309.41  4951.9 1304.51  4952.4 1304.01
  4961.3 1304.51  4977.8 1305.19  4983.7 1309.48  4998.2 1314.32  5056.1 1314.94
  5077.4 1313.14  5434.2 1316.05  5459.5 1316.36  5570.7 1317.52  5628.9 1320.27
  5685.5  1326.3  5707.3  1330.3  5743.4 1335.37  5819.9 1353.14  5971.5 1382.27
#Mann= 11 ,-1 , 0
  4513.1     .12       0  4555.4     .07       0  4573.4     .12       0
  4656.9     .07       0  4951.9     .05       0  4961.3     .07       0
  5434.2     .12       0  5459.5     .07       0  5570.7     .12       0
  5707.3     .07       0  5743.4     .12       0
Bank Sta=4951.9,4961.3
XS Rating Curve= 0 ,0
Exp/Cntr=0.3,0.1