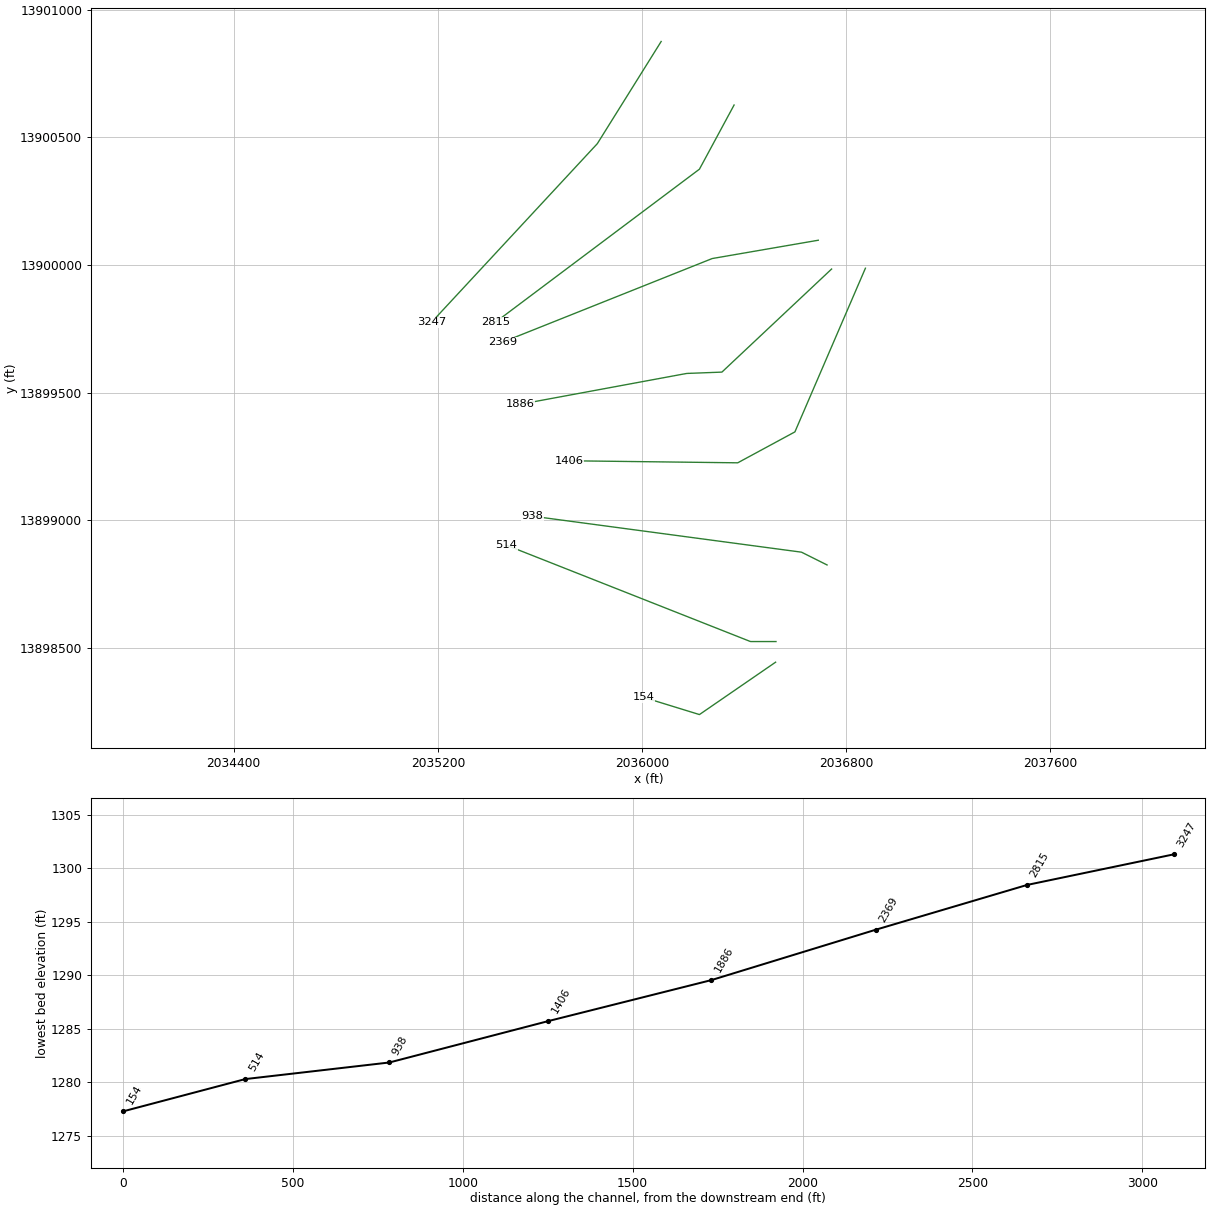
HEC-RAS study Stream0131_DS.prj: Stream0131_DS Base Level Engineering

--- Stream0131_DS.g01 (geometry) --- (continued)

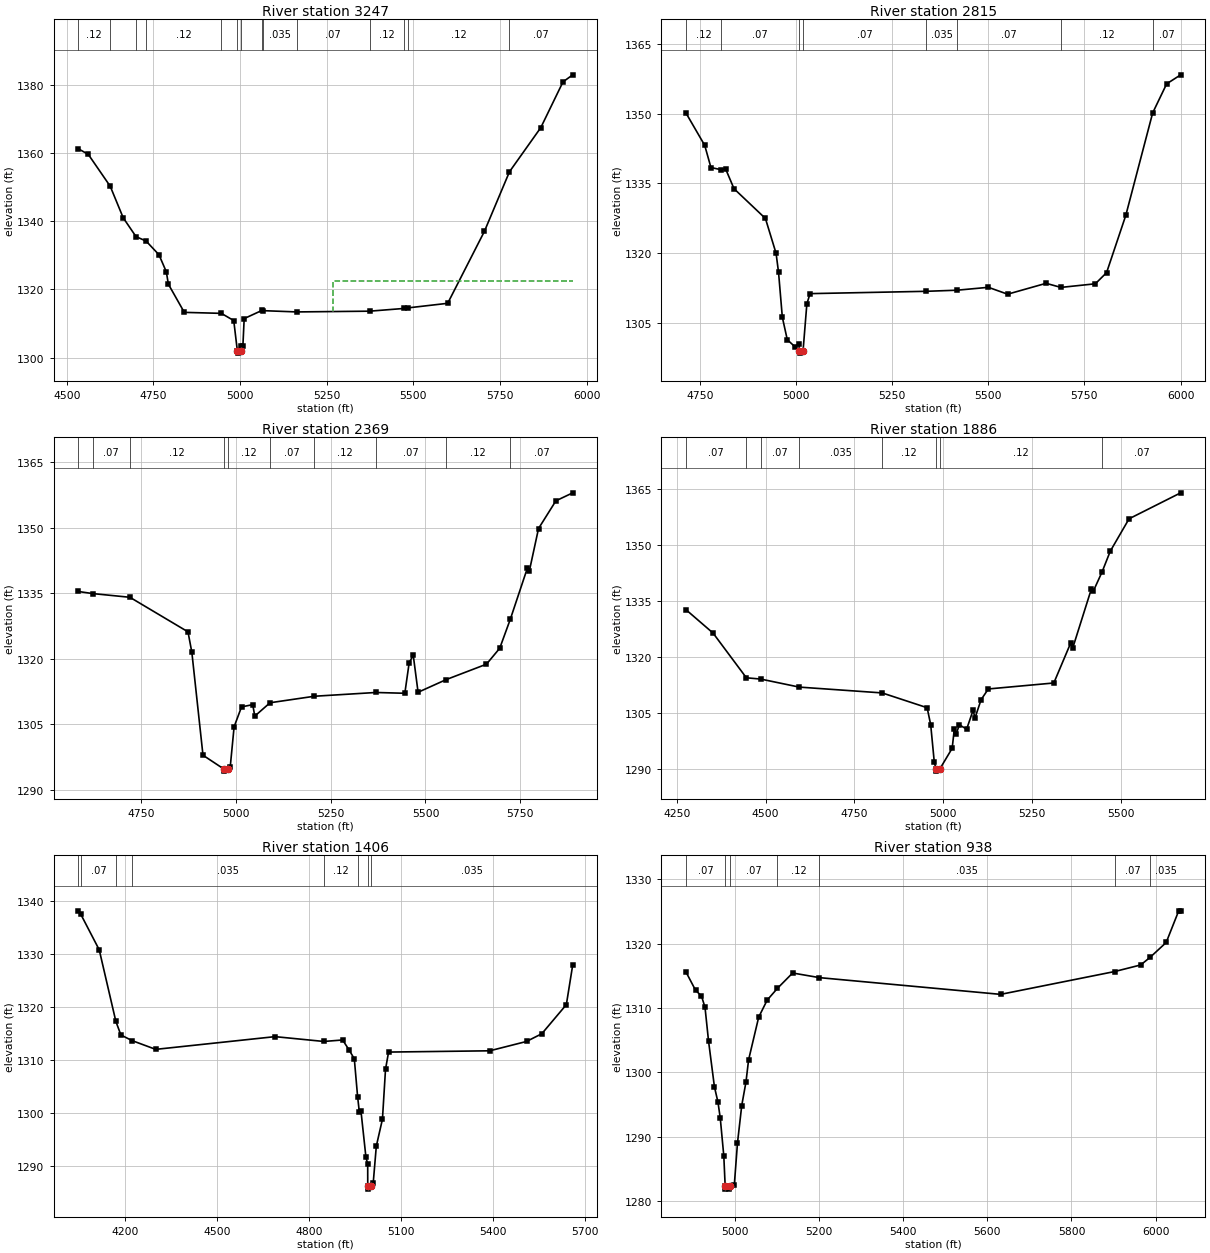
Type RM Length L Ch R = 1 ,3247    ,432,432,432
BEGIN DESCRIPTION:
Stream0131_DS 7.0
END DESCRIPTION:
XS GIS Cut Line= 3
      2036075.01     13900875.01        2035825.       13900475.
      2035174.97     13899774.97
#Sta/Elev= 30
  4532.9 1361.32  4561.8 1359.67  4625.1 1350.31  4662.6 1341.04  4699.6 1335.51
  4728.7 1334.21  4765.8 1330.19    4787 1325.18  4792.9 1321.55  4838.9 1313.27
  4945.8 1312.98  4981.6 1310.86  4992.2  1301.8  4992.7  1301.3  5001.6  1301.8
  5001.7 1303.49    5008 1303.49  5011.7 1311.44  5062.9 1313.84  5066.6 1313.77
  5163.6  1313.4  5373.6 1313.62  5473.9 1314.43  5483.8 1314.58    5599 1315.93
    5705 1337.07  5777.3 1354.57  5867.7 1367.53  5931.8 1380.97  5959.9 1383.03
#Mann= 14 ,-1 , 0
  4532.9     .12       0  4625.1     .07       0  4699.6    .035       0
  4728.7     .12       0  4945.8     .07       0  4992.2     .05       0
  5001.6     .07       0  5062.9     .12       0  5066.6    .035       0
  5163.6     .07       0  5373.6     .12       0  5473.9     .07       0
  5483.8     .12       0  5777.3     .07       0
#XS Ineff= 2 , 0
       0                    5268       0 1322.44
Permanent Ineff=
       F       F
Bank Sta=4992.2,5001.6
XS Rating Curve= 0 ,0
Exp/Cntr=0.3,0.1

Type RM Length L Ch R = 1 ,2815    ,446,446,446
BEGIN DESCRIPTION:
Stream0131_DS 6.0
END DESCRIPTION:
XS GIS Cut Line= 3
      2036360.74     13900626.25        2036225.       13900375.
      2035424.98     13899774.98
#Sta/Elev= 30
  4714.7 1350.05  4762.8 1343.18    4779  1338.4  4804.5 1337.95  4817.1 1338.12
    4839 1333.84  4920.7 1327.43  4948.4 1319.91  4954.8 1315.82  4964.6 1306.17
  4977.5 1301.33  4997.4 1299.81  5007.6 1300.45  5009.1 1298.94  5009.6 1298.44
  5018.5 1298.94  5028.4 1309.06  5036.7 1311.25  5338.9 1311.75  5419.2 1311.99
  5500.3 1312.61  5550.3 1311.13  5650.3 1313.47  5688.9 1312.59  5778.4 1313.37
  5807.6 1315.77  5857.6 1328.11  5927.4 1350.15  5963.8 1356.42  6000.3 1358.36
#Mann= 8 ,-1 , 0
  4714.7     .12       0  4804.5     .07       0  5009.1     .05       0
  5018.5     .07       0  5338.9    .035       0  5419.2     .07       0
  5688.9     .12       0  5927.4     .07       0
Bank Sta=5009.1,5018.5
XS Rating Curve= 0 ,0
Exp/Cntr=0.3,0.1

Type RM Length L Ch R = 1 ,2369    ,483,483,483
BEGIN DESCRIPTION:
Stream0131_DS 5.0
END DESCRIPTION:
XS GIS Cut Line= 3
      2036690.59     13900096.72        2036275.       13900025.
      2035453.65     13899697.43
#Sta/Elev= 30
    4583 1335.37    4621 1334.89  4719.4 1334.04  4872.8 1326.13    4883 1321.43
  4912.4 1297.89  4967.2 1294.75  4967.7 1294.25  4977.4 1294.75  4984.4 1295.24
  4994.6  1304.4  5014.2 1308.95  5043.8 1309.47  5049.2 1306.84  5089.5  1309.9
  5206.7 1311.39  5368.9 1312.25  5445.5 1312.07  5456.9 1319.03  5467.7 1320.79
  5480.5  1312.3  5554.7  1315.2  5661.1 1318.73  5696.1 1322.37  5724.3 1329.07
  5768.9 1340.65  5774.3 1340.04  5798.6 1349.78  5844.5 1356.12    5889 1357.95
#Mann= 10 ,-1 , 0
    4583     .12       0    4621     .07       0  4719.4     .12       0
  4967.2     .05       0  4977.4     .12       0  5089.5     .07       0
  5206.7     .12       0  5368.9     .07       0  5554.7     .12       0
  5724.3     .07       0
Bank Sta=4967.2,4977.4
XS Rating Curve= 0 ,0
Exp/Cntr=0.3,0.1

Type RM Length L Ch R = 1 ,1886    ,480,480,480
BEGIN DESCRIPTION:
Stream0131_DS 4.0
END DESCRIPTION:
XS GIS Cut Line= 4
       2036742.7      13899983.9      2036312.99     13899580.23
        2036175.       13899575.      2035523.04     13899454.36
#Sta/Elev= 30
  4276.9  1332.7  4352.4  1326.5  4446.1 1314.53  4486.8 1314.18  4594.7 1312.04
    4828 1310.48  4954.5 1306.52  4964.5 1301.97  4974.5 1292.06  4979.5 1290.05
    4980 1289.55  4989.7 1290.05  5024.9 1295.66    5031 1300.85  5036.1  1299.5
  5045.2 1301.94  5065.6 1300.78  5083.9 1305.88    5089 1303.75  5106.3 1308.68
  5126.6 1311.54  5310.8 1313.14  5358.6 1323.92  5363.7 1322.42  5416.6 1338.37
  5421.7 1337.68  5446.7 1342.91  5469.5  1348.4  5522.4 1357.08  5667.6 1364.03
#Mann= 8 ,-1 , 0
  4276.9     .07       0  4446.1    .035       0  4486.8     .07       0
  4594.7    .035       0    4828     .12       0  4979.5     .05       0
  4989.7     .12       0  5446.7     .07       0
Bank Sta=4979.5,4989.7
XS Rating Curve= 0 ,0
Exp/Cntr=0.3,0.1

Type RM Length L Ch R = 1 ,1406    ,468,468,468
BEGIN DESCRIPTION:
Stream0131_DS 3.0
END DESCRIPTION:
XS GIS Cut Line= 4
      2036875.22     13899987.09        2036599.     13899346.08
        2036375.       13899225.      2035714.07     13899233.01
#Sta/Elev= 30
  4047.3 1338.19  4055.8 1337.51  4115.7 1330.84  4169.9 1317.36  4186.3 1314.79
  4222.5 1313.73    4300 1312.07  4689.4 1314.47  4848.6 1313.56    4910 1313.84
  4931.9 1311.88  4948.1 1310.28  4958.8 1303.18  4964.3 1300.34  4969.9  1300.4
  4986.1 1291.69  4991.8 1290.48  4991.9 1286.22  4992.4 1285.72  5002.2 1286.22
  5009.9 1286.96  5019.9 1293.83  5039.9 1298.91  5049.9 1308.31  5059.9 1311.56
    5390  1311.8    5510 1313.56    5560 1315.02    5640  1320.5  5660.9 1328.03
#Mann= 8 ,-1 , 0
  4047.3     .12       0  4055.8     .07       0  4169.9     .12       0
  4222.5    .035       0  4848.6     .12       0  4958.8    .035       0
  4991.9    .035       0  5002.2    .035       0
Bank Sta=4991.9,5002.2
XS Rating Curve= 0 ,0
Exp/Cntr=0.3,0.1

Type RM Length L Ch R = 1 ,938     ,424,424,424
BEGIN DESCRIPTION:
Stream0131_DS 2.0
END DESCRIPTION:
XS GIS Cut Line= 3
      2036724.99     13898825.01        2036625.       13898875.
      2035570.78       13899016.
#Sta/Elev= 30
  4884.2 1315.52  4906.5 1312.74  4920.5 1311.85  4928.9  1310.1  4937.3 1304.85
  4951.3 1297.74  4959.7 1295.37  4965.2 1292.86  4973.6 1286.98  4976.8 1282.35
  4977.3 1281.85  4986.7 1281.85  4987.2 1282.35  4998.5 1282.45  5006.1 1289.03
  5016.2 1294.84  5026.3 1298.51  5032.5 1301.94  5056.5 1308.57  5076.7 1311.22
  5101.1 1313.05  5137.2 1315.43  5200.9 1314.71  5631.6 1312.11  5902.8 1315.66
  5964.5 1316.68  5987.2 1317.88  6025.1 1320.17  6054.9 1325.09  6059.6 1325.09
#Mann= 7 ,-1 , 0
  4884.2     .07       0  4976.8     .05       0  4987.2     .07       0
  5101.1     .12       0  5200.9    .035       0  5902.8     .07       0
  5987.2    .035       0
Bank Sta=4976.8,4987.2
XS Rating Curve= 0 ,0
Exp/Cntr=0.3,0.1

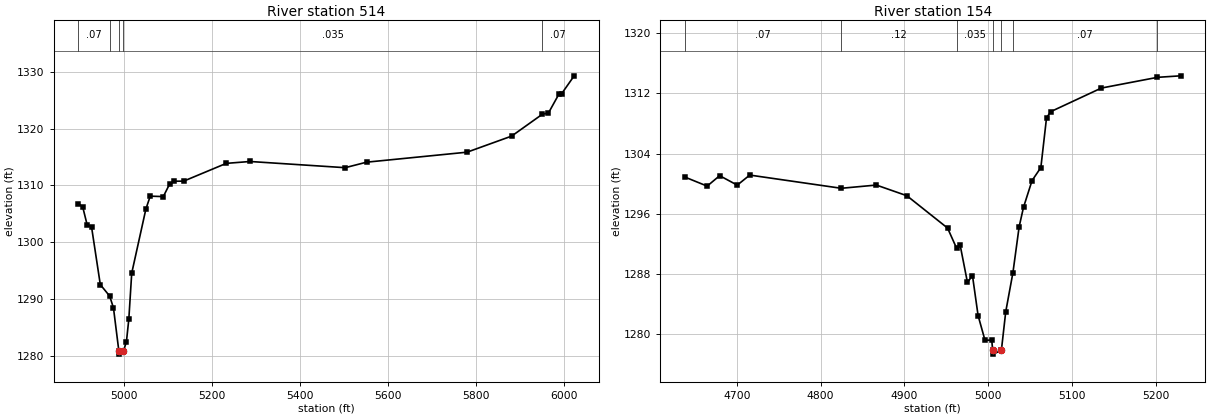
Type RM Length L Ch R = 1 ,514     ,360,360,360
BEGIN DESCRIPTION:
Stream0131_DS 1.0
END DESCRIPTION:
XS GIS Cut Line= 3
      2036524.99       13898525.        2036425.       13898525.
      2035468.28      13898902.5
#Sta/Elev= 30
  4895.5  1306.8  4905.5  1306.2  4915.5 1303.08  4925.5 1302.74  4945.5 1292.54
  4966.9 1290.51  4975.5 1288.42  4987.8  1280.8  4988.3  1280.3  4998.2  1280.8
    5005 1282.52  5010.4 1286.45    5017 1294.55  5049.2 1305.82  5059.1 1308.11
  5088.9 1308.03    5103  1310.2  5113.2 1310.74  5135.2 1310.75  5232.2 1313.88
  5286.3 1314.21  5502.8 1313.12  5551.6 1314.09  5780.3 1315.85  5881.7 1318.68
  5951.6 1322.53  5965.5 1322.75  5989.9 1326.15  5995.3 1326.12    6024 1329.29
#Mann= 5 ,-1 , 0
  4895.5     .07       0  4966.9    .035       0  4987.8    .035       0
  4998.2    .035       0  5951.6     .07       0
Bank Sta=4987.8,4998.2
XS Rating Curve= 0 ,0
Exp/Cntr=0.3,0.1

Type RM Length L Ch R = 1 ,154     ,0,0,0
BEGIN DESCRIPTION:
Stream0131_DS 0.0
END DESCRIPTION:
XS GIS Cut Line= 3
      2036523.38     13898444.21        2036225.     13898239.07
      2036005.56     13898306.61
#Sta/Elev= 30
  4637.9 1300.87  4664.6 1299.66  4679.5 1301.05  4700.5 1299.79  4715.4 1301.13
  4824.6 1299.37  4866.5  1299.8  4902.9 1298.38  4951.5 1294.07  4962.4 1291.35
  4966.4 1291.85  4975.2 1286.83  4981.2 1287.74  4987.9 1282.42  4996.1 1279.14
  5004.2 1279.14  5005.3 1277.78  5005.8 1277.28  5015.7 1277.78  5020.9 1282.93
  5029.5 1288.15  5036.9 1294.25  5042.1 1296.84  5052.3  1300.4  5062.8 1302.13
  5069.6 1308.78  5074.8 1309.59    5135 1312.72    5202 1314.15  5229.6 1314.35
#Mann= 7 ,-1 , 0
  4637.9     .07       0  4824.6     .12       0  4962.4    .035       0
  5005.3    .035       0  5015.7    .035       0  5029.5     .07       0
    5202    .035       0
Bank Sta=5005.3,5015.7
XS Rating Curve= 0 ,0
Exp/Cntr=0.3,0.1

Chan Stop Cuts=-1
Use User Specified Reach Order=0
Composite Channel Slope=5