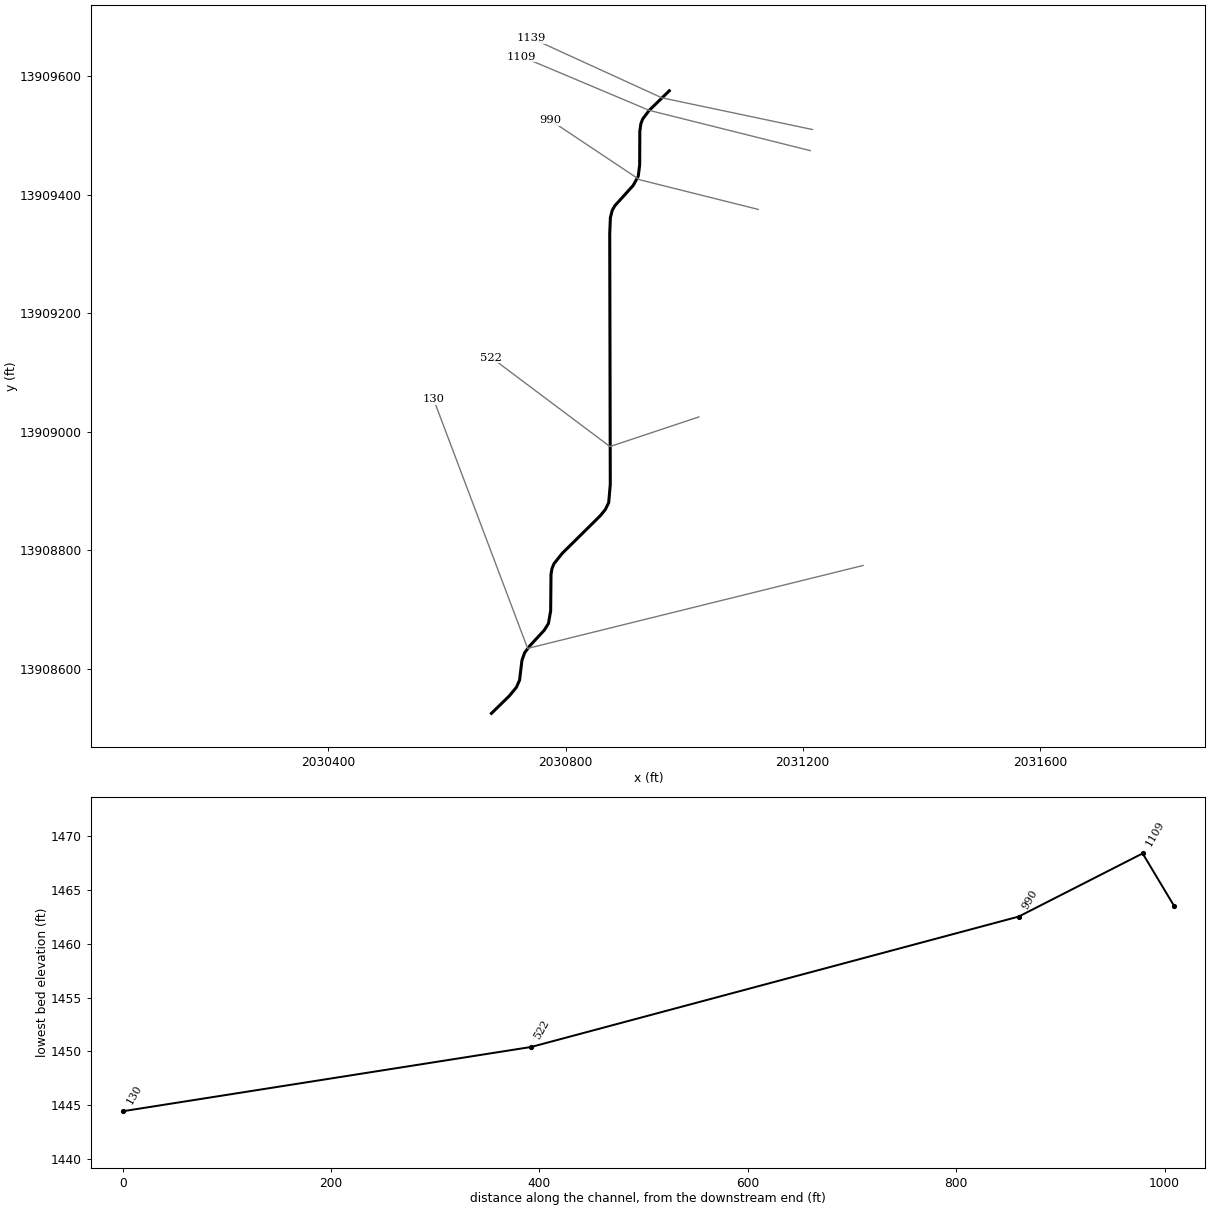
--- Stream0132_DS.prj (project) ---

Proj Title=Stream0132_DS Base Level Engineering
Current Plan=p01
Default Exp/Contr=0.3,0.1
English Units
Geom File=g01
Flow File=f01
Plan File=p01
BEGIN DESCRIPTION:
Stream0132_DS
END DESCRIPTION:

--- Stream0132_DS.p01 (plan) ---

Plan Title=Multiple Run
Short Identifier=Multiple
Geom File=g01
Flow File=f01
Subcritical Flow
K Sum by GR= 0
Std Step Tol= 0.01
Critical Tol= 0.01
Num of Std Step Trials= 20
Max Error Tol= 0.3
Flow Tol Ratio= 0.001
Split Flow NTrial= 30
Split Flow Tol= 0.02
Split Flow Ratio= 0.02
Log Output Level= 0
Friction Slope Method= 1
Unsteady Friction Slope Method= 2
Unsteady Bridges Friction Slope Method= 1
Parabolic Critical Depth
Global Vel Dist=  1 , 1 , 1
Global Log Level= 0
CheckData=True
Encroach Param= -1, 0, 0, 0
BEGIN DESCRIPTION:
Multiple Run
END DESCRIPTION:

--- Stream0132_DS.f01 (steady flow) ---

Flow Title=Multiple
Number of Profiles=7
Profile Names=10-year,25-year,50-year,1pct_min,100-year,1pct_plu,500-year
River Rch & RM= Stream0132_DS,Reach-1,1139
     759    1285    1788    1211    2416    4820    4365
Boundary for River Rch & Prof#=Stream0132_DS,Reach-1,1
Up Type=0
Dn Type=3
Dn Slope=0.005
Boundary for River Rch & Prof#=Stream0132_DS,Reach-1,2
Up Type=0
Dn Type=3
Dn Slope=0.005
Boundary for River Rch & Prof#=Stream0132_DS,Reach-1,3
Up Type=0
Dn Type=3
Dn Slope=0.005
Boundary for River Rch & Prof#=Stream0132_DS,Reach-1,4
Up Type=0
Dn Type=3
Dn Slope=0.005
Boundary for River Rch & Prof#=Stream0132_DS,Reach-1,5
Up Type=0
Dn Type=3
Dn Slope=0.005
Boundary for River Rch & Prof#=Stream0132_DS,Reach-1,6
Up Type=0
Dn Type=3
Dn Slope=0.005
Boundary for River Rch & Prof#=Stream0132_DS,Reach-1,7
Up Type=0
Dn Type=3
Dn Slope=0.005

--- Stream0132_DS.g01 (geometry) ---

Geom Title=Existing Conditions

River Reach=Stream0132_DS,Reach-1
Reach XY= 30
      2030975.00     13909575.00      2030941.12     13909542.05
      2030930.22     13909527.55      2030927.12     13909519.58
      2030925.29     13909506.70      2030925.06     13909449.97
      2030922.68     13909430.96      2030914.11     13909415.37
      2030883.14     13909381.06      2030878.78     13909373.44
      2030875.68     13909361.08      2030874.55     13909334.28
      2030875.50     13908911.16      2030872.82     13908880.45
      2030867.17     13908868.81      2030858.53     13908858.25
      2030794.67     13908795.14      2030780.54     13908777.42
      2030777.16     13908769.11      2030775.53     13908759.78
      2030774.91     13908697.76      2030771.18     13908676.58
      2030764.18     13908665.34      2030739.01     13908638.05
      2030731.03     13908627.22      2030726.51     13908614.37
      2030722.49     13908581.04      2030717.09     13908568.85
      2030704.86     13908554.08      2030675.00     13908525.00

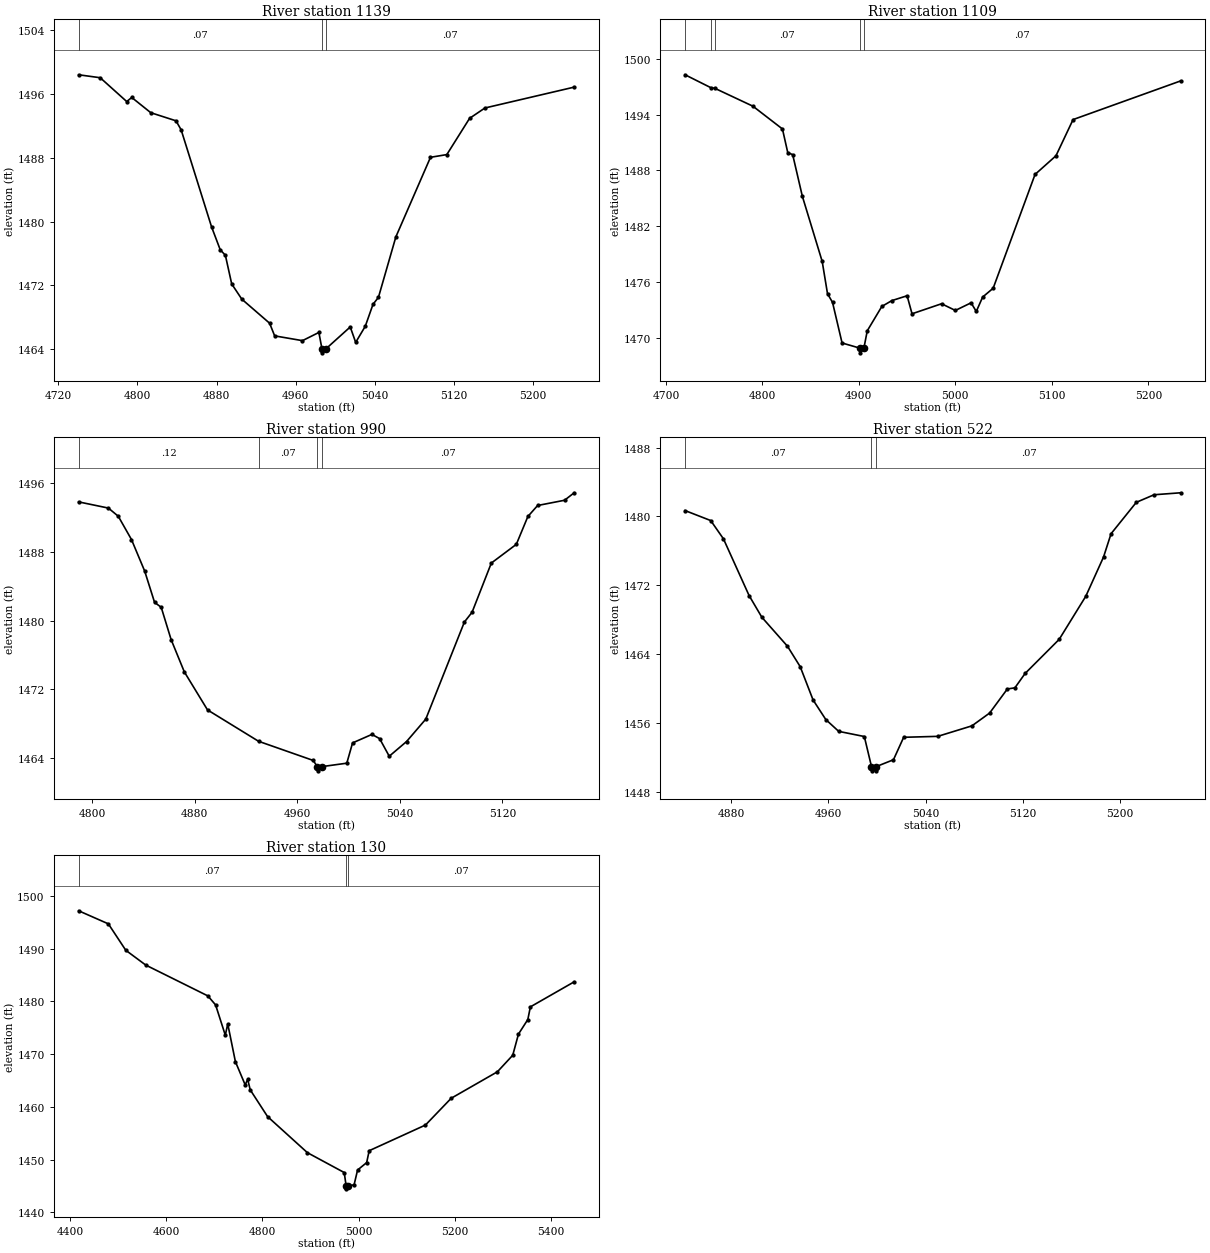
Type RM Length L Ch R = 1,1139,30,30,30
BEGIN DESCRIPTION:
Stream0132_DS 3.0
END DESCRIPTION:
XS GIS Cut Line= 3
      2031216.38     13909509.73      2030962.54     13909563.18
      2030742.98     13909663.50
#Sta/Elev= 30
  4740.6 1498.44  4762.4 1498.07  4789.2 1495.08  4794.3 1495.59  4813.5 1493.68
  4839.0 1492.66  4844.2 1491.53  4874.9 1479.36  4883.7 1476.47  4888.9 1475.78
  4895.3 1472.18  4905.5 1470.27  4933.6 1467.25  4938.7 1465.66  4966.8 1465.06
  4983.4 1466.09  4986.5 1464.03  4986.7 1463.53  4990.5 1464.03  5015.1 1466.78
  5020.6 1464.84  5030.3 1466.87  5038.1 1469.62  5043.6 1470.50  5061.2 1478.09
  5096.2 1488.08  5112.7 1488.42  5135.7 1492.97  5151.2 1494.27  5241.4 1496.89
#Mann=3,-1,0
  4740.6    0.07       0  4986.5    0.05       0  4990.5    0.07       0
Bank Sta=4986.5,4990.5
Exp/Cntr=0.3,0.1

Type RM Length L Ch R = 1,1109,119,119,119
BEGIN DESCRIPTION:
Stream0132_DS 4.0
END DESCRIPTION:
XS GIS Cut Line= 3
      2031212.86     13909474.11      2030941.12     13909542.05
      2030725.95     13909632.72
#Sta/Elev= 30
  4719.9 1498.28  4747.2 1496.86  4750.4 1496.84  4790.2 1494.90  4820.8 1492.45
  4826.3 1489.91  4831.4 1489.69  4841.4 1485.22  4862.0 1478.20  4867.5 1474.73
  4872.7 1473.80  4882.6 1469.43  4901.2 1468.87  4901.5 1468.37  4905.2 1468.87
  4908.7 1470.74  4923.8 1473.36  4934.2 1473.99  4950.0 1474.51  4955.1 1472.57
  4985.7 1473.65  5000.0 1472.93  5016.3 1473.75  5021.7 1472.82  5028.3 1474.37
  5039.2 1475.32  5082.6 1487.56  5104.3 1489.57  5122.0 1493.46  5233.5 1497.62
#Mann=5,-1,0
  4719.9    0.07       0  4747.2    0.12       0  4750.4    0.07       0
  4901.2    0.05       0  4905.2    0.07       0
Bank Sta=4901.2,4905.2
Exp/Cntr=0.3,0.1

Type RM Length L Ch R = 1,990,468,468,468
BEGIN DESCRIPTION:
Stream0132_DS 2.0
END DESCRIPTION:
XS GIS Cut Line= 3
      2031124.97     13909375.01      2030925.00     13909425.00
      2030775.00     13909525.00
#Sta/Elev= 30
  4789.6 1493.81  4812.8 1493.09  4820.5 1492.14  4830.8 1489.43  4841.1 1485.76
  4848.8 1482.12  4854.0 1481.54  4861.7 1477.79  4872.0 1474.03  4890.1 1469.60
  4929.9 1465.95  4972.5 1463.72  4975.7 1463.01  4975.9 1462.51  4979.7 1463.01
  4998.7 1463.40  5003.2 1465.76  5018.3 1466.75  5024.3 1466.26  5031.8 1464.21
  5045.3 1465.92  5060.3 1468.53  5090.4 1479.83  5096.4 1480.97  5111.4 1486.69
  5130.9 1488.87  5139.9 1492.11  5147.5 1493.39  5168.5 1494.00  5176.0 1494.87
#Mann=4,-1,0
  4789.6    0.12       0  4929.9    0.07       0  4975.7    0.05       0
  4979.7    0.07       0
Bank Sta=4975.7,4979.7
Exp/Cntr=0.3,0.1

Type RM Length L Ch R = 1,522,392,392,392
BEGIN DESCRIPTION:
Stream0132_DS 1.0
END DESCRIPTION:
XS GIS Cut Line= 3
      2031024.98     13909024.99      2030875.00     13908975.00
      2030674.99     13909125.00
#Sta/Elev= 30
  4842.0 1480.68  4863.1 1479.52  4873.6 1477.39  4894.7 1470.80  4905.2 1468.28
  4926.3 1464.91  4936.8 1462.53  4947.4 1458.66  4957.9 1456.38  4968.5 1455.01
  4989.6 1454.41  4995.5 1450.92  4995.7 1450.42  4999.2 1450.42  4999.5 1450.92
  5013.6 1451.71  5022.0 1454.32  5050.1 1454.43  5078.2 1455.65  5092.8 1457.14
  5107.4 1459.94  5113.6 1460.07  5122.0 1461.74  5150.1 1465.71  5172.0 1470.72
  5186.6 1475.28  5192.8 1477.99  5213.6 1481.64  5228.2 1482.52  5250.1 1482.75
#Mann=3,-1,0
  4842.0    0.07       0  4995.5    0.05       0  4999.5    0.07       0
Bank Sta=4995.5,4999.5
Exp/Cntr=0.3,0.1

Type RM Length L Ch R = 1,130,0,0,0
BEGIN DESCRIPTION:
Stream0132_DS 0.0
END DESCRIPTION:
XS GIS Cut Line= 3
      2031301.86     13908774.44      2030736.10     13908634.55
      2030577.55     13909054.62
#Sta/Elev= 30
  4417.2 1497.18  4479.1 1494.70  4515.4 1489.69  4556.9 1486.89  4686.3 1481.04
  4702.4 1479.33  4722.6 1473.59  4727.7 1475.73  4743.6 1468.58  4764.0 1464.17
  4769.2 1465.22  4774.5 1463.23  4810.6 1458.16  4893.5 1451.32  4970.2 1447.55
  4974.3 1444.96  4974.6 1444.46  4978.3 1444.96  4990.8 1445.24  4998.0 1448.03
  5016.9 1449.43  5022.2 1451.69  5139.4 1456.56  5192.9 1461.63  5289.1 1466.65
  5321.1 1469.79  5333.0 1473.80  5352.5 1476.56  5357.8 1478.96  5449.0 1483.71
#Mann=3,-1,0
  4417.2    0.07       0  4974.3    0.05       0  4978.3    0.07       0
Bank Sta=4974.3,4978.3
Exp/Cntr=0.3,0.1

Chan Stop Cuts=-1