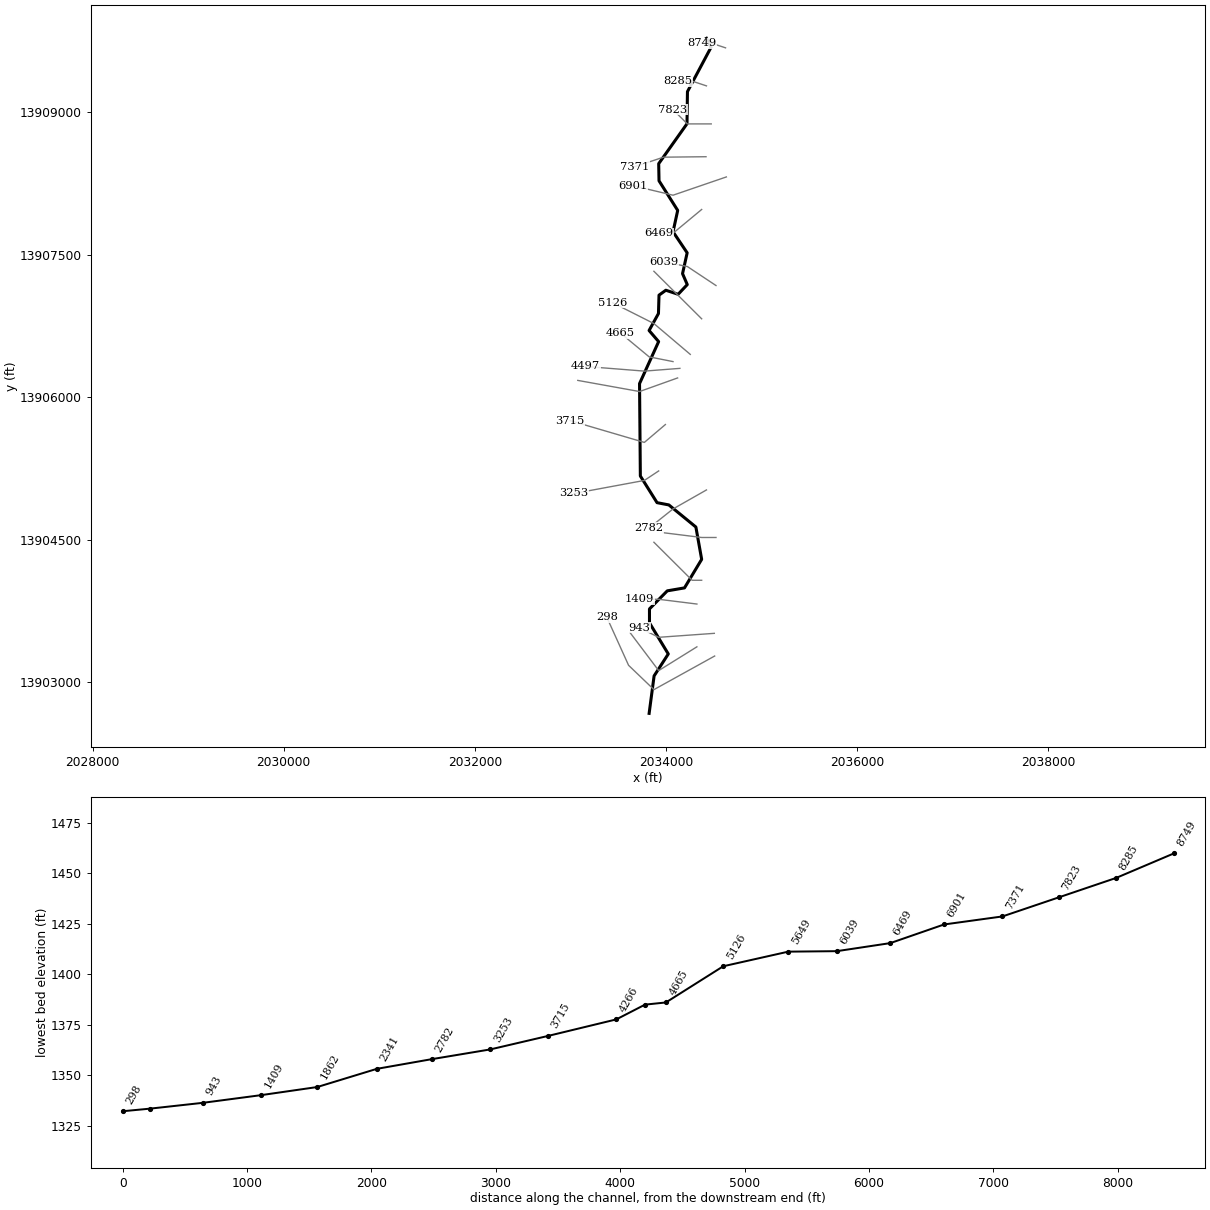
--- Stream0133_DS.prj (project) ---

Proj Title=Stream0133_DS Base Level Engineering
Current Plan=p01
Default Exp/Contr=0.3,0.1
English Units
Geom File=g01
Flow File=f01
Plan File=p01
BEGIN DESCRIPTION:
Stream0133_DS
END DESCRIPTION:

--- Stream0133_DS.p01 (plan) ---

Plan Title=Multiple Run
Short Identifier=Multiple
Geom File=g01
Flow File=f01
Subcritical Flow
K Sum by GR= 0
Std Step Tol= 0.01
Critical Tol= 0.01
Num of Std Step Trials= 20
Max Error Tol= 0.3
Flow Tol Ratio= 0.001
Split Flow NTrial= 30
Split Flow Tol= 0.02
Split Flow Ratio= 0.02
Log Output Level= 0
Friction Slope Method= 1
Unsteady Friction Slope Method= 2
Unsteady Bridges Friction Slope Method= 1
Parabolic Critical Depth
Global Vel Dist=  1 , 1 , 1
Global Log Level= 0
CheckData=True
Encroach Param= -1, 0, 0, 0
BEGIN DESCRIPTION:
Multiple Run
END DESCRIPTION:

--- Stream0133_DS.f01 (steady flow) ---

Flow Title=Multiple
Number of Profiles=7
Profile Names=10-year,25-year,50-year,1pct_min,100-year,1pct_plu,500-year
River Rch & RM= Stream0133_DS,Reach-1,8749
     659    1098    1510    1011    2018    4026    3555
River Rch & RM= Stream0133_DS,Reach-1,7371
    1354    2352    3326    2281    4551    9080    8427
River Rch & RM= Stream0133_DS,Reach-1,2782
    1677    2940    4184    2884    5754   11480   10771
Boundary for River Rch & Prof#=Stream0133_DS,Reach-1,1
Up Type=0
Dn Type=3
Dn Slope=0.005
Boundary for River Rch & Prof#=Stream0133_DS,Reach-1,2
Up Type=0
Dn Type=3
Dn Slope=0.005
Boundary for River Rch & Prof#=Stream0133_DS,Reach-1,3
Up Type=0
Dn Type=3
Dn Slope=0.005
Boundary for River Rch & Prof#=Stream0133_DS,Reach-1,4
Up Type=0
Dn Type=3
Dn Slope=0.005
Boundary for River Rch & Prof#=Stream0133_DS,Reach-1,5
Up Type=0
Dn Type=3
Dn Slope=0.005
Boundary for River Rch & Prof#=Stream0133_DS,Reach-1,6
Up Type=0
Dn Type=3
Dn Slope=0.005
Boundary for River Rch & Prof#=Stream0133_DS,Reach-1,7
Up Type=0
Dn Type=3
Dn Slope=0.005

--- Stream0133_DS.g01 (geometry) ---

Geom Title=Existing Conditions

River Reach=Stream0133_DS,Reach-1
Reach XY= 30
      2034425.00     13909775.00      2034473.26     13909681.05
      2034226.20     13909214.50      2034221.46     13908876.46
      2033925.15     13908456.75      2033928.54     13908276.46
      2034124.07     13907965.15      2034075.37     13907740.17
      2034223.05     13907519.28      2034174.69     13907300.03
      2034224.24     13907184.76      2034128.43     13907082.79
      2033999.87     13907125.53      2033928.44     13907073.78
      2033922.65     13906880.52      2033824.50     13906702.09
      2033924.44     13906585.18      2033724.61     13906143.34
      2033733.07     13905171.69      2033907.87     13904891.29
      2034031.32     13904867.50      2034314.37     13904635.00
      2034374.94     13904295.03      2034195.13     13903994.76
      2034015.00     13903963.76      2033828.53     13903773.53
      2033828.74     13903626.56      2034025.50     13903300.03
      2033877.07     13903069.14      2033825.00     13902675.00

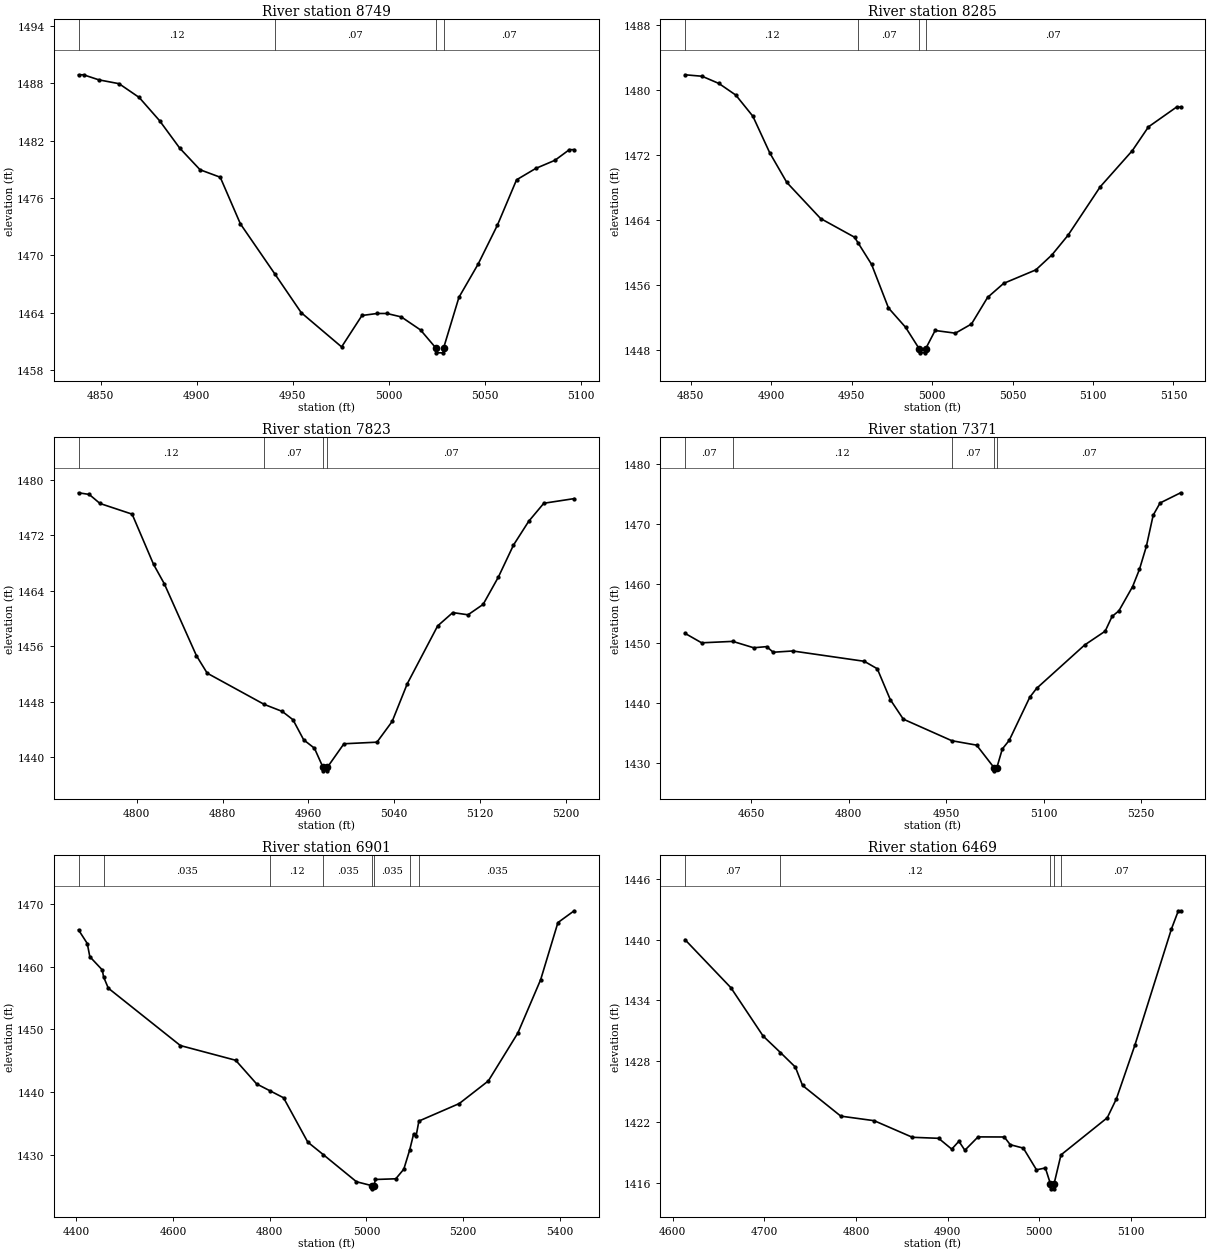
Type RM Length L Ch R = 1,8749,464,464,464
BEGIN DESCRIPTION:
Stream0133_DS 19.0
END DESCRIPTION:
XS GIS Cut Line= 3
      2034625.01     13909675.00      2034475.00     13909725.00
      2034375.03     13909725.00
#Sta/Elev= 30
  4838.4 1488.87  4841.0 1488.87  4849.0 1488.34  4859.5 1487.94  4870.0 1486.50
  4880.6 1484.08  4891.1 1481.21  4901.7 1478.95  4912.2 1478.17  4922.7 1473.30
  4940.7 1468.05  4954.4 1464.02  4975.4 1460.45  4986.0 1463.73  4993.9 1463.94
  4999.0 1463.94  5006.5 1463.58  5016.5 1462.22  5024.5 1460.33  5024.8 1459.83
  5028.3 1459.83  5028.5 1460.33  5036.5 1465.63  5046.5 1469.10  5056.5 1473.15
  5066.5 1477.90  5076.5 1479.09  5086.5 1479.94  5094.0 1481.05  5096.5 1481.05
#Mann=4,-1,0
  4838.4    0.12       0  4940.7    0.07       0  5024.5    0.05       0
  5028.5    0.07       0
Bank Sta=5024.5,5028.5
Exp/Cntr=0.3,0.1

Type RM Length L Ch R = 1,8285,462,462,462
BEGIN DESCRIPTION:
Stream0133_DS 18.0
END DESCRIPTION:
XS GIS Cut Line= 3
      2034425.02     13909274.99      2034275.00     13909325.00
      2034125.03     13909325.00
#Sta/Elev= 30
  4846.4 1481.91  4857.0 1481.73  4867.5 1480.84  4878.0 1479.41  4888.6 1476.81
  4899.1 1472.30  4909.7 1468.66  4930.7 1464.22  4951.8 1461.92  4954.2 1461.16
  4962.4 1458.57  4972.9 1453.21  4983.5 1450.84  4992.0 1448.19  4992.2 1447.69
  4995.7 1447.69  4996.0 1448.19  5001.9 1450.44  5014.5 1450.11  5024.5 1451.24
  5034.5 1454.51  5044.5 1456.24  5064.5 1457.90  5074.5 1459.74  5084.5 1462.16
  5104.5 1468.12  5124.5 1472.58  5134.5 1475.50  5152.0 1477.94  5154.5 1477.94
#Mann=4,-1,0
  4846.4    0.12       0  4954.2    0.07       0  4992.0    0.05       0
  4996.0    0.07       0
Bank Sta=4992,4996
Exp/Cntr=0.3,0.1

Type RM Length L Ch R = 1,7823,452,452,452
BEGIN DESCRIPTION:
Stream0133_DS 17.0
END DESCRIPTION:
XS GIS Cut Line= 3
      2034475.05     13908875.00      2034225.00     13908875.00
      2034074.99     13909025.01
#Sta/Elev= 30
  4745.7 1478.10  4755.7 1477.86  4765.7 1476.56  4795.7 1475.02  4815.7 1467.78
  4825.7 1464.99  4855.7 1454.62  4865.7 1452.11  4918.9 1447.61  4935.7 1446.60
  4945.7 1445.40  4955.7 1442.50  4965.7 1441.30  4973.7 1438.54  4974.0 1438.04
  4977.5 1438.04  4977.7 1438.54  4993.2 1441.94  5024.0 1442.17  5038.2 1445.16
  5052.3 1450.60  5080.6 1458.92  5094.7 1460.84  5108.9 1460.52  5123.0 1462.02
  5137.2 1465.95  5151.3 1470.56  5165.5 1473.99  5179.6 1476.59  5207.9 1477.26
#Mann=4,-1,0
  4745.7    0.12       0  4918.9    0.07       0  4973.7    0.05       0
  4977.7    0.07       0
Bank Sta=4973.7,4977.7
Exp/Cntr=0.3,0.1

Type RM Length L Ch R = 1,7371,470,470,470
BEGIN DESCRIPTION:
Stream0133_DS 16.0
END DESCRIPTION:
XS GIS Cut Line= 3
      2034420.62     13908529.88      2033975.00     13908525.00
      2033674.98     13908424.99
#Sta/Elev= 30
  4548.6 1451.67  4574.2 1450.08  4622.1 1450.32  4654.2 1449.25  4674.2 1449.44
  4684.2 1448.50  4714.2 1448.71  4824.2 1446.98  4844.2 1445.73  4864.2 1440.55
  4884.2 1437.28  4958.8 1433.66  4996.9 1432.92  5023.9 1429.11  5024.1 1428.61
  5027.9 1429.11  5036.4 1432.28  5047.0 1433.72  5078.6 1440.95  5089.1 1442.44
  5162.9 1449.71  5194.5 1452.03  5205.1 1454.50  5215.6 1455.44  5236.7 1459.51
  5247.2 1462.40  5257.8 1466.25  5268.3 1471.48  5278.9 1473.53  5310.5 1475.24
#Mann=5,-1,0
  4548.6    0.07       0  4622.1    0.12       0  4958.8    0.07       0
  5023.9    0.05       0  5027.9    0.07       0
Bank Sta=5023.9,5027.9
Exp/Cntr=0.3,0.1

Type RM Length L Ch R = 1,6901,432,432,432
BEGIN DESCRIPTION:
Stream0133_DS 15.0
END DESCRIPTION:
XS GIS Cut Line= 3
      2034633.29     13908317.21      2034075.00     13908125.00
      2033652.37     13908226.07
#Sta/Elev= 30
  4404.5 1465.85  4422.6 1463.68  4427.9 1461.58  4453.8 1459.46  4456.2 1458.39
  4466.1 1456.57  4615.2 1447.43  4729.5 1445.09  4772.9 1441.32  4800.2 1440.24
  4828.5 1439.12  4878.6 1432.06  4911.1 1430.04  4979.3 1425.75  5011.4 1425.12
  5011.7 1424.62  5015.4 1425.12  5018.5 1426.11  5060.6 1426.22  5077.2 1427.75
  5089.4 1430.82  5097.5 1433.36  5102.7 1433.06  5108.4 1435.41  5191.9 1438.20
  5252.0 1441.80  5313.0 1449.42  5360.2 1457.92  5395.9 1467.01  5429.5 1468.89
#Mann=8,-1,0
  4404.5    0.07       0  4456.2   0.035       0  4800.2    0.12       0
  4911.1   0.035       0  5011.4   0.035       0  5015.4   0.035       0
  5089.4    0.12       0  5108.4   0.035       0
Bank Sta=5011.4,5015.4
Exp/Cntr=0.3,0.1

Type RM Length L Ch R = 1,6469,430,430,430
BEGIN DESCRIPTION:
Stream0133_DS 14.0
END DESCRIPTION:
XS GIS Cut Line= 3
      2034374.99     13907974.99      2034075.00     13907725.00
      2033925.00     13907725.00
#Sta/Elev= 30
  4613.6 1440.00  4663.7 1435.25  4698.8 1430.48  4717.7 1428.85  4734.0 1427.41
  4741.8 1425.60  4783.5 1422.57  4819.9 1422.12  4861.6 1420.48  4890.2 1420.38
  4904.5 1419.31  4912.3 1420.09  4918.8 1419.20  4933.2 1420.52  4961.8 1420.51
  4968.3 1419.75  4982.6 1419.41  4996.9 1417.27  5006.6 1417.45  5012.1 1415.89
  5012.3 1415.39  5015.8 1415.39  5016.1 1415.89  5023.6 1418.74  5074.1 1422.41
  5084.1 1424.29  5104.1 1429.55  5144.1 1441.06  5151.6 1442.85  5154.1 1442.85
#Mann=5,-1,0
  4613.6    0.07       0  4717.7    0.12       0  5012.1    0.05       0
  5016.1    0.12       0  5023.6    0.07       0
Bank Sta=5012.1,5016.1
Exp/Cntr=0.3,0.1

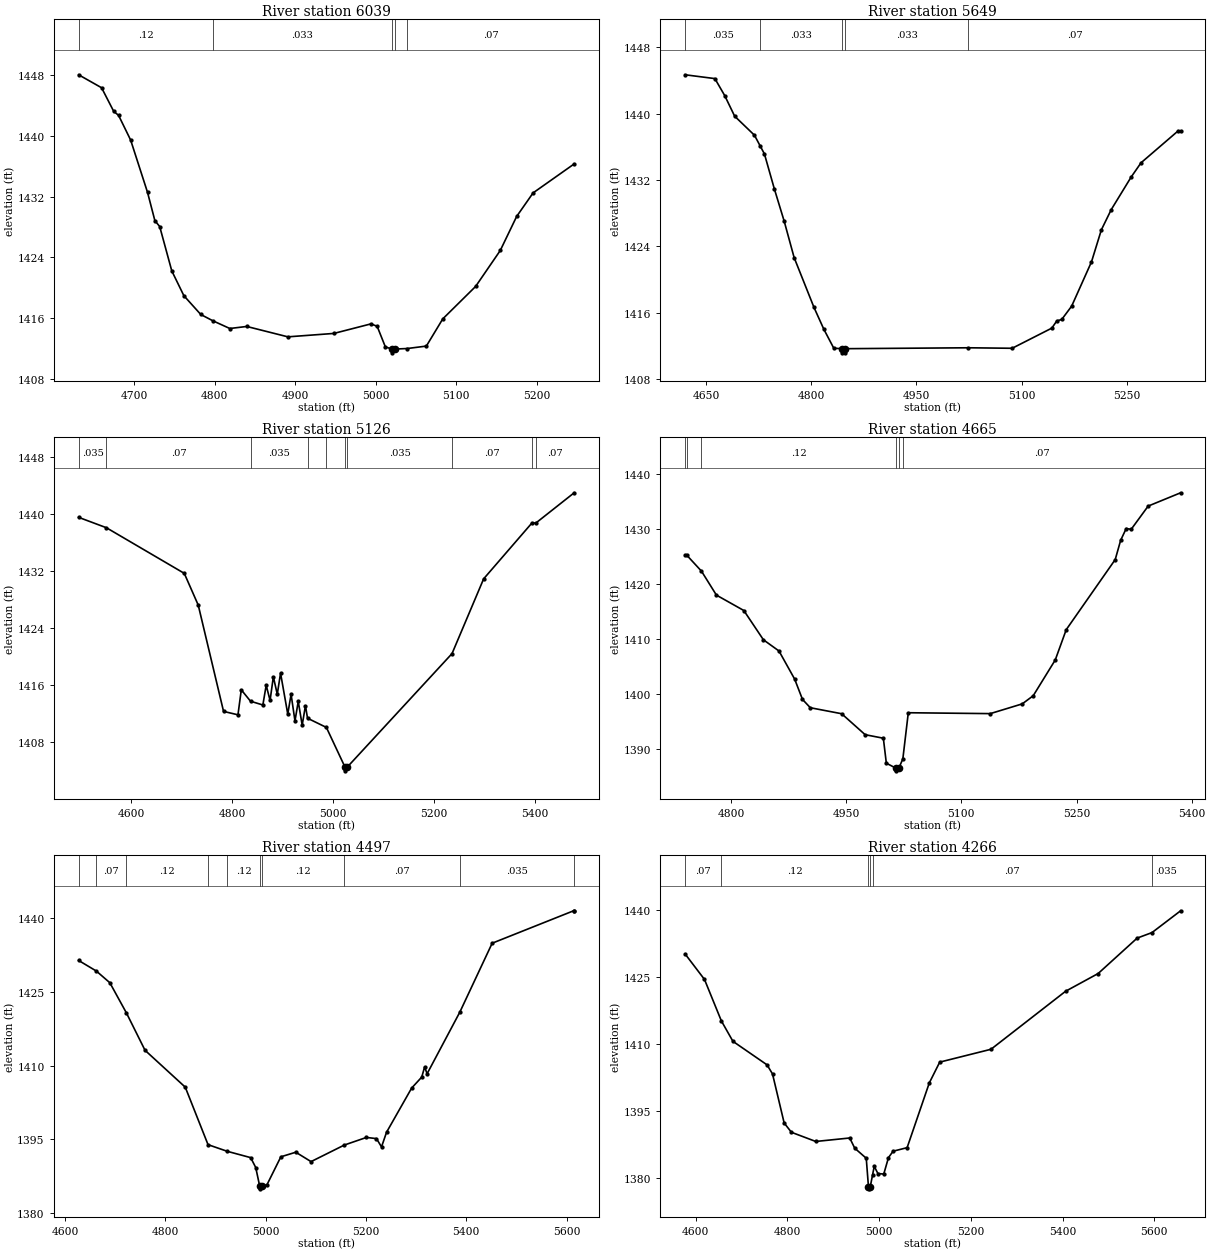
Type RM Length L Ch R = 1,6039,390,390,390
BEGIN DESCRIPTION:
Stream0133_DS 13.0
END DESCRIPTION:
XS GIS Cut Line= 3
      2034525.00     13907175.00      2034225.00     13907375.00
      2033975.01     13907425.00
#Sta/Elev= 30
  4631.2 1448.08  4659.7 1446.37  4674.8 1443.25  4680.8 1442.73  4695.8 1439.47
  4716.8 1432.56  4725.9 1428.84  4731.9 1428.06  4746.9 1422.21  4761.9 1418.94
  4782.9 1416.46  4797.7 1415.64  4819.0 1414.61  4840.0 1414.88  4891.1 1413.51
  4948.2 1413.96  4994.3 1415.22  5002.0 1414.90  5012.2 1412.18  5020.4 1411.90
  5020.6 1411.40  5024.4 1411.90  5039.4 1411.97  5063.1 1412.29  5083.5 1415.88
  5124.3 1420.16  5154.9 1424.90  5175.3 1429.40  5195.7 1432.50  5246.7 1436.32
#Mann=5,-1,0
  4631.2    0.12       0  4797.7   0.033       0  5020.4   0.033       0
  5024.4   0.033       0  5039.4    0.07       0
Bank Sta=5020.4,5024.4
Exp/Cntr=0.3,0.1

Type RM Length L Ch R = 1,5649,523,523,523
BEGIN DESCRIPTION:
Stream0133_DS 12.0
END DESCRIPTION:
XS GIS Cut Line= 3
      2034375.02     13906824.98      2034075.00     13907125.00
      2033875.02     13907324.98
#Sta/Elev= 30
  4619.9 1444.68  4662.4 1444.22  4676.5 1442.16  4690.6 1439.69  4718.9 1437.39
  4726.9 1436.12  4733.1 1435.14  4747.2 1430.94  4761.3 1427.03  4775.5 1422.64
  4803.8 1416.64  4817.9 1414.00  4832.1 1411.71  4844.2 1411.66  4844.4 1411.16
  4847.9 1411.16  4848.2 1411.66  5024.2 1411.77  5086.6 1411.71  5143.2 1414.14
  5150.3 1415.01  5157.3 1415.18  5171.5 1416.79  5199.8 1422.13  5213.9 1425.99
  5228.0 1428.43  5256.3 1432.34  5270.5 1434.07  5323.5 1437.92  5327.0 1437.92
#Mann=5,-1,0
  4619.9   0.035       0  4726.9   0.033       0  4844.2   0.033       0
  4848.2   0.033       0  5024.2    0.07       0
Bank Sta=4844.2,4848.2
Exp/Cntr=0.3,0.1

Type RM Length L Ch R = 1,5126,461,461,461
BEGIN DESCRIPTION:
Stream0133_DS 11.0
END DESCRIPTION:
XS GIS Cut Line= 3
      2034255.72     13906450.87      2033875.00     13906775.00
      2033444.10     13906993.41
#Sta/Elev= 30
  4495.4 1439.53  4550.5 1438.07  4705.0 1431.66  4732.7 1427.20  4782.9 1412.27
  4811.5 1411.79  4818.1 1415.30  4836.4 1413.70  4860.9 1413.17  4867.5 1415.94
  4875.2 1413.81  4881.7 1417.13  4889.5 1414.68  4896.0 1417.64  4910.3 1411.89
  4916.9 1414.67  4924.6 1410.93  4931.1 1413.67  4938.9 1410.34  4945.4 1413.07
  4949.5 1411.31  4986.9 1410.02  5024.0 1404.42  5024.3 1403.92  5028.0 1404.42
  5236.2 1420.39  5298.9 1430.89  5393.9 1438.67  5403.4 1438.78  5478.5 1442.98
#Mann=10,-1,0
  4495.4   0.035       0  4550.5    0.07       0  4836.4   0.035       0
  4949.5    0.07       0  4986.9   0.035       0  5024.0   0.035       0
  5028.0   0.035       0  5236.2    0.07       0  5393.9   0.035       0
  5403.4    0.07       0
Bank Sta=5024,5028
Exp/Cntr=0.3,0.1

Type RM Length L Ch R = 1,4665,168,168,168
BEGIN DESCRIPTION:
Stream0133_DS 10.0
END DESCRIPTION:
XS GIS Cut Line= 3
      2034074.97     13906375.01      2033825.00     13906425.00
      2033525.03     13906674.98
#Sta/Elev= 30
  4740.2 1425.15  4742.6 1425.15  4761.5 1422.29  4781.0 1417.93  4816.7 1415.13
  4842.2 1409.81  4862.5 1407.77  4882.9 1402.66  4893.1 1398.97  4903.3 1397.46
  4944.1 1396.37  4974.7 1392.56  4998.4 1391.92  5002.3 1387.38  5014.6 1386.49
  5014.9 1385.99  5018.6 1386.49  5023.8 1388.16  5030.9 1396.55  5137.7 1396.39
  5179.3 1398.16  5193.6 1399.64  5222.3 1406.14  5236.6 1411.65  5300.4 1424.39
  5307.5 1427.90  5314.7 1430.03  5321.2 1429.89  5343.3 1434.11  5385.6 1436.53
#Mann=6,-1,0
  4740.2    0.12       0  4742.6    0.07       0  4761.5    0.12       0
  5014.6    0.05       0  5018.6    0.12       0  5023.8    0.07       0
Bank Sta=5014.6,5018.6
Exp/Cntr=0.3,0.1

Type RM Length L Ch R = 1,4497,231,231,231
BEGIN DESCRIPTION:
Stream0133_DS 9.5
END DESCRIPTION:
XS GIS Cut Line= 3
      2034147.01     13906303.77      2033775.33     13906274.86
      2033162.06     13906323.55
#Sta/Elev= 30
  4627.2 1431.38  4662.6 1429.22  4689.4 1426.85  4722.6 1420.68  4759.6 1413.10
  4839.8 1405.60  4885.2 1393.90  4923.4 1392.55  4970.2 1391.26  4980.3 1389.25
  4988.3 1385.41  4988.6 1384.91  4992.3 1385.41  5002.7 1385.74  5030.4 1391.43
  5060.2 1392.36  5090.6 1390.45  5156.9 1393.82  5201.0 1395.37  5221.0 1395.13
  5231.1 1393.44  5241.1 1396.42  5291.2 1405.42  5311.3 1407.65  5317.0 1409.70
  5322.0 1408.33  5387.2 1420.86  5451.7 1434.89  5614.1 1441.49  5615.2 1441.49
#Mann=10,-1,0
  4627.2    0.12       0  4662.6    0.07       0  4722.6    0.12       0
  4885.2    0.07       0  4923.4    0.12       0  4988.3    0.05       0
  4992.3    0.12       0  5156.9    0.07       0  5387.2   0.035       0
  5614.1    0.07       0
Bank Sta=4988.3,4992.3
Exp/Cntr=0.3,0.1

Type RM Length L Ch R = 1,4266,551,551,551
BEGIN DESCRIPTION:
Stream0133_DS 9.0
END DESCRIPTION:
XS GIS Cut Line= 3
      2034123.14     13906203.09      2033724.96     13906060.02
      2033078.08     13906177.16
#Sta/Elev= 30
  4576.9 1430.20  4619.2 1424.49  4656.0 1415.20  4681.2 1410.63  4755.6 1405.36
  4767.5 1403.33  4792.9 1392.34  4808.7 1390.26  4861.8 1388.20  4935.9 1388.98
  4946.8 1386.69  4971.9 1384.44  4976.7 1378.09  4977.0 1377.59  4980.7 1378.09
  4985.6 1380.68  4989.3 1382.63  4997.3 1381.02  5010.1 1380.90  5020.3 1384.57
  5030.4 1386.02  5061.0 1386.81  5109.4 1401.32  5132.1 1405.97  5243.9 1408.85
  5406.5 1421.84  5477.6 1425.82  5562.6 1433.75  5595.0 1434.99  5657.4 1439.87
#Mann=6,-1,0
  4576.9    0.07       0  4656.0    0.12       0  4976.7    0.05       0
  4980.7    0.12       0  4985.6    0.07       0  5595.0   0.035       0
Bank Sta=4976.7,4980.7
Exp/Cntr=0.3,0.1

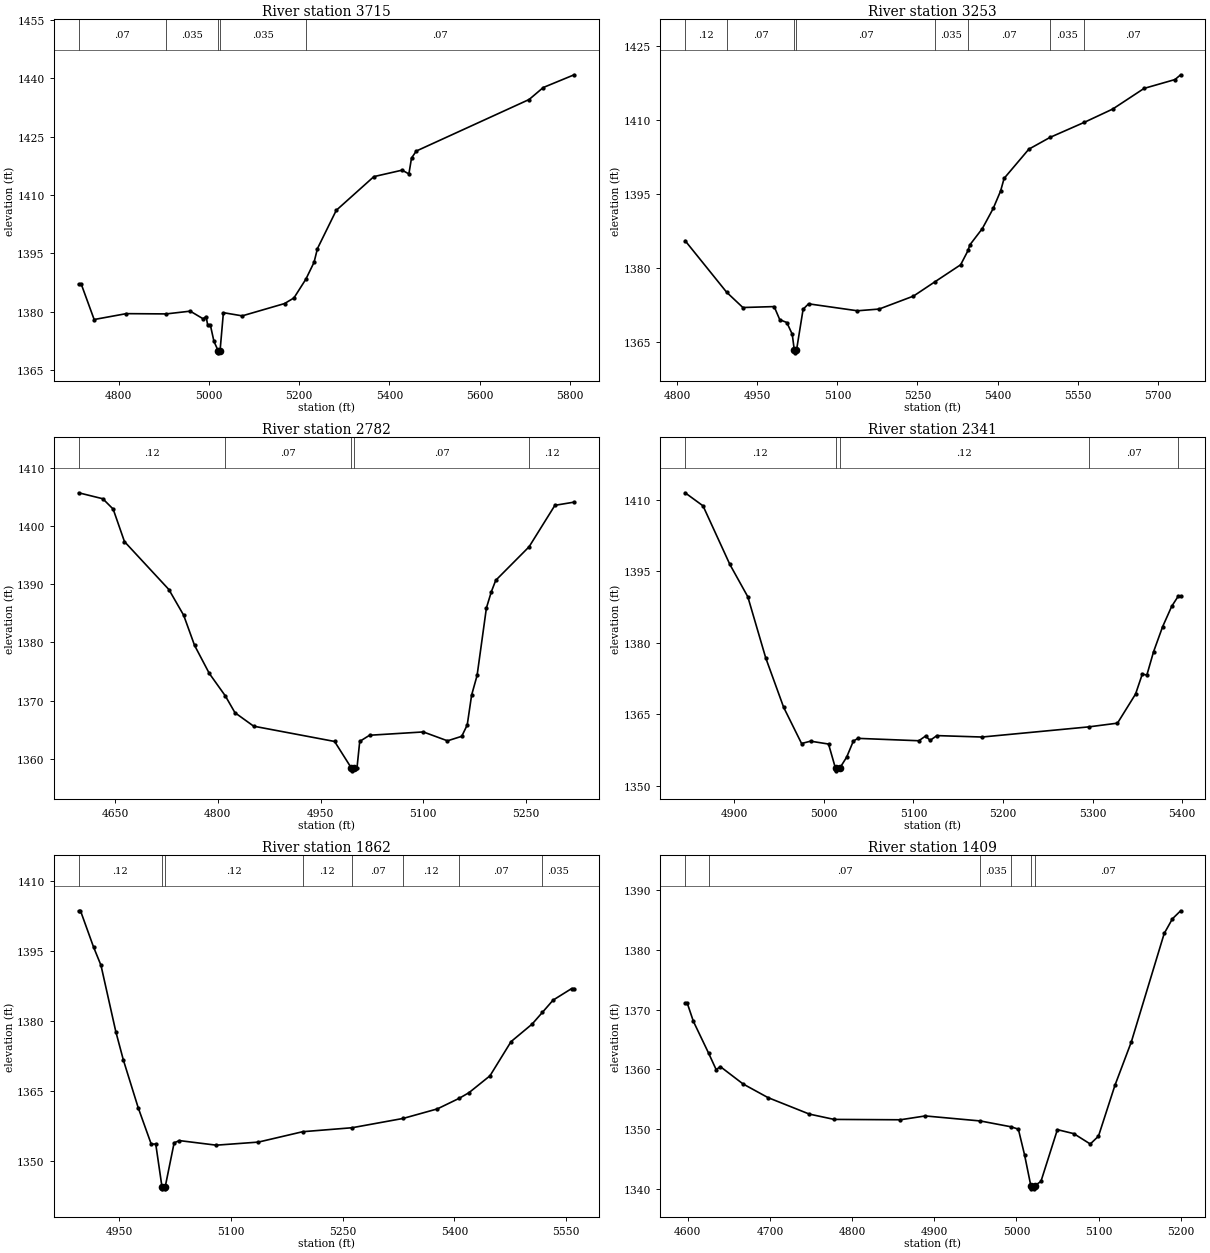
Type RM Length L Ch R = 1,3715,462,462,462
BEGIN DESCRIPTION:
Stream0133_DS 8.0
END DESCRIPTION:
XS GIS Cut Line= 3
      2033995.28     13905713.04      2033775.00     13905525.00
      2032999.17     13905753.85
#Sta/Elev= 30
  4711.0 1387.00  4716.8 1387.04  4745.4 1377.94  4816.6 1379.45  4905.2 1379.38
  4958.4 1380.09  4986.9 1378.13  4993.5 1378.71  4997.3 1376.41  5003.2 1376.41
  5011.0 1372.30  5020.5 1369.87  5020.7 1369.37  5024.5 1369.87  5031.9 1379.70
  5073.6 1378.88  5167.4 1382.04  5188.3 1383.49  5214.8 1388.33  5232.8 1392.63
  5240.4 1396.18  5282.1 1406.02  5365.5 1414.69  5428.1 1416.35  5443.1 1415.38
  5448.9 1419.45  5459.4 1421.26  5709.6 1434.52  5740.9 1437.60  5809.5 1440.88
#Mann=5,-1,0
  4711.0    0.07       0  4905.2   0.035       0  5020.5   0.035       0
  5024.5   0.035       0  5214.8    0.07       0
Bank Sta=5020.5,5024.5
Exp/Cntr=0.3,0.1

Type RM Length L Ch R = 1,3253,471,471,471
BEGIN DESCRIPTION:
Stream0133_DS 7.0
END DESCRIPTION:
XS GIS Cut Line= 3
      2033925.01     13905225.01      2033775.00     13905125.00
      2033039.95     13904987.99
#Sta/Elev= 30
  4814.8 1385.47  4892.7 1375.00  4923.0 1371.91  4981.6 1372.10  4992.1 1369.44
  5005.3 1368.87  5015.4 1366.51  5019.4 1363.22  5019.7 1362.72  5023.4 1363.22
  5035.8 1371.56  5046.0 1372.66  5137.5 1371.25  5178.2 1371.60  5242.5 1374.23
  5282.0 1377.08  5330.8 1380.58  5344.7 1383.48  5347.9 1384.59  5371.5 1387.93
  5391.8 1392.00  5405.7 1395.56  5412.2 1398.10  5458.5 1404.02  5498.2 1406.41
  5562.7 1409.48  5615.6 1412.16  5674.4 1416.35  5732.2 1418.14  5742.8 1419.11
#Mann=8,-1,0
  4814.8    0.12       0  4892.7    0.07       0  5019.4    0.05       0
  5023.4    0.07       0  5282.0   0.035       0  5344.7    0.07       0
  5498.2   0.035       0  5562.7    0.07       0
Bank Sta=5019.4,5023.4
Exp/Cntr=0.3,0.1

Type RM Length L Ch R = 1,2782,441,441,441
BEGIN DESCRIPTION:
Stream0133_DS 6.0
END DESCRIPTION:
XS GIS Cut Line= 3
      2034424.99     13905024.99      2034075.00     13904825.00
      2033824.97     13904624.97
#Sta/Elev= 30
  4596.9 1405.78  4632.2 1404.75  4647.3 1402.97  4663.8 1397.37  4728.6 1389.12
  4750.2 1384.69  4766.1 1379.50  4787.6 1374.67  4811.0 1370.80  4825.1 1367.90
  4852.4 1365.58  4970.5 1362.95  4994.9 1358.39  4995.2 1357.89  4999.3 1358.39
  5003.2 1358.39  5007.2 1362.96  5021.6 1364.02  5100.0 1364.59  5135.3 1363.06
  5156.1 1363.84  5164.1 1365.79  5170.5 1370.93  5178.5 1374.32  5192.1 1385.94
  5199.3 1388.74  5205.7 1390.70  5254.4 1396.48  5292.1 1403.62  5320.2 1404.17
#Mann=5,-1,0
  4596.9    0.12       0  4811.0    0.07       0  4994.9    0.05       0
  4999.3    0.07       0  5254.4    0.12       0
Bank Sta=4994.9,4999.3
Exp/Cntr=0.3,0.1

Type RM Length L Ch R = 1,2341,479,479,479
BEGIN DESCRIPTION:
Stream0133_DS 5.0
END DESCRIPTION:
XS GIS Cut Line= 3
      2034525.03     13904525.00      2034375.00     13904525.00
      2033975.04     13904574.99
#Sta/Elev= 30
  4845.1 1411.41  4865.1 1408.67  4895.1 1396.37  4915.1 1389.60  4935.1 1376.78
  4955.1 1366.42  4975.1 1358.83  4985.1 1359.32  5005.2 1358.72  5013.0 1353.60
  5013.3 1353.10  5017.5 1353.60  5025.4 1355.96  5032.9 1359.34  5038.0 1359.91
  5106.0 1359.41  5113.5 1360.40  5118.6 1359.48  5126.1 1360.49  5176.5 1360.19
  5295.7 1362.32  5327.7 1363.10  5347.9 1369.21  5355.4 1373.38  5360.5 1373.19
  5368.0 1378.09  5378.1 1383.33  5388.2 1387.59  5395.5 1389.72  5398.2 1389.78
#Mann=5,-1,0
  4845.1    0.12       0  5013.0    0.05       0  5017.5    0.12       0
  5295.7    0.07       0  5395.5   0.035       0
Bank Sta=5013,5017.5
Exp/Cntr=0.3,0.1

Type RM Length L Ch R = 1,1862,453,453,453
BEGIN DESCRIPTION:
Stream0133_DS 4.0
END DESCRIPTION:
XS GIS Cut Line= 3
      2034375.04     13904075.00      2034275.00     13904075.00
      2033875.02     13904474.98
#Sta/Elev= 30
  4895.2 1403.57  4897.7 1403.57  4915.2 1395.83  4925.2 1391.91  4945.2 1377.68
  4955.2 1371.70  4975.2 1361.45  4992.7 1353.67  4998.8 1353.67  5007.1 1344.59
  5007.4 1344.09  5011.3 1344.09  5011.6 1344.59  5023.5 1353.94  5030.6 1354.41
  5080.1 1353.43  5136.7 1354.09  5196.2 1356.31  5262.5 1357.16  5331.1 1359.15
  5377.1 1361.19  5406.4 1363.45  5419.5 1364.65  5447.8 1368.27  5476.1 1375.58
  5504.4 1379.33  5518.1 1381.82  5532.6 1384.46  5557.4 1386.92  5560.9 1386.92
#Mann=8,-1,0
  4895.2    0.12       0  5007.1    0.05       0  5011.6    0.12       0
  5196.2    0.12       0  5262.5    0.07       0  5331.1    0.12       0
  5406.4    0.07       0  5518.1   0.035       0
Bank Sta=5007.1,5011.6
Exp/Cntr=0.3,0.1

Type RM Length L Ch R = 1,1409,466,466,466
BEGIN DESCRIPTION:
Stream0133_DS 3.0
END DESCRIPTION:
XS GIS Cut Line= 3
      2034325.02     13903825.00      2033925.00     13903875.00
      2033725.04     13903875.00
#Sta/Elev= 30
  4596.8 1371.13  4599.3 1371.13  4606.9 1368.04  4625.3 1362.76  4634.6 1359.98
  4639.7 1360.48  4667.4 1357.58  4697.6 1355.31  4748.0 1352.55  4778.2 1351.66
  4858.8 1351.60  4889.1 1352.24  4956.2 1351.40  4993.7 1350.42  5002.4 1350.03
  5009.9 1345.76  5017.6 1340.56  5018.0 1340.06  5021.9 1340.06  5022.2 1340.56
  5029.9 1341.31  5049.9 1349.95  5069.9 1349.28  5089.9 1347.55  5099.9 1348.86
  5119.9 1357.34  5139.9 1364.62  5179.9 1382.73  5189.9 1385.18  5199.9 1386.52
#Mann=6,-1,0
  4596.8    0.12       0  4625.3    0.07       0  4956.2   0.035       0
  4993.7    0.07       0  5017.6    0.05       0  5022.2    0.07       0
Bank Sta=5017.6,5022.2
Exp/Cntr=0.3,0.1

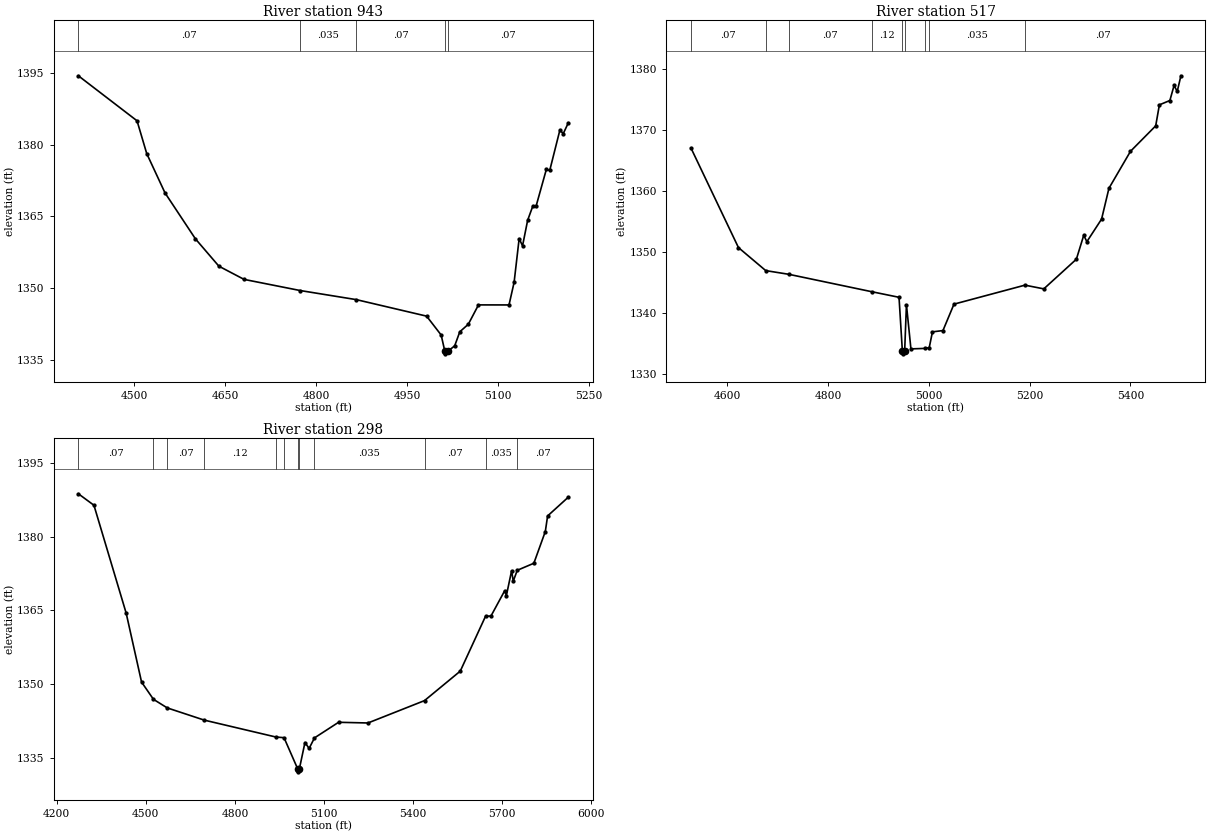
Type RM Length L Ch R = 1,943,426,426,426
BEGIN DESCRIPTION:
Stream0133_DS 2.0
END DESCRIPTION:
XS GIS Cut Line= 3
      2034507.39     13903516.86      2033925.00     13903475.00
      2033725.00     13903575.00
#Sta/Elev= 30
  4408.4 1394.39  4505.1 1384.98  4521.1 1378.12  4551.2 1369.91  4601.3 1360.31
  4640.0 1354.59  4681.5 1351.83  4774.0 1349.50  4866.5 1347.60  4982.3 1344.15
  5006.3 1340.20  5012.4 1336.77  5012.7 1336.27  5017.0 1336.77  5028.6 1337.95
  5037.0 1340.88  5051.0 1342.45  5067.8 1346.50  5118.1 1346.49  5126.5 1351.22
  5134.8 1360.35  5140.4 1358.85  5148.8 1364.19  5157.2 1367.11  5162.8 1367.18
  5179.6 1374.81  5185.2 1374.60  5201.9 1383.03  5207.5 1382.30  5215.9 1384.57
#Mann=5,-1,0
  4408.4    0.07       0  4774.0   0.035       0  4866.5    0.07       0
  5012.4    0.05       0  5017.0    0.07       0
Bank Sta=5012.4,5017
Exp/Cntr=0.3,0.1

Type RM Length L Ch R = 1,517,219,219,219
BEGIN DESCRIPTION:
Stream0133_DS 1.0
END DESCRIPTION:
XS GIS Cut Line= 3
      2034324.98     13903374.99      2033925.00     13903125.00
      2033624.98     13903525.02
#Sta/Elev= 30
  4528.3 1367.11  4622.6 1350.78  4676.7 1347.01  4722.2 1346.41  4886.6 1343.56
  4941.0 1342.64  4947.6 1333.88  4947.9 1333.38  4952.2 1333.88  4955.7 1341.43
  4964.6 1334.19  4992.7 1334.27  5000.9 1334.40  5007.3 1336.98  5028.1 1337.19
  5050.0 1341.52  5190.7 1344.63  5228.1 1344.02  5292.7 1348.88  5307.3 1352.80
  5313.5 1351.75  5342.7 1355.45  5357.3 1360.50  5400.0 1366.55  5450.0 1370.72
  5457.3 1374.16  5478.1 1374.87  5486.4 1377.33  5492.7 1376.36  5500.0 1378.92
#Mann=9,-1,0
  4528.3    0.07       0  4676.7   0.035       0  4722.2    0.07       0
  4886.6    0.12       0  4947.6    0.05       0  4952.2    0.12       0
  4992.7    0.07       0  5000.9   0.035       0  5190.7    0.07       0
Bank Sta=4947.6,4952.2
Exp/Cntr=0.3,0.1

Type RM Length L Ch R = 1,298,0,0,0
BEGIN DESCRIPTION:
Stream0133_DS 0.0
END DESCRIPTION:
XS GIS Cut Line= 4
      2034510.95     13903278.24      2033875.40     13902924.83
      2033609.88     13903180.53      2033382.18     13903685.77
#Sta/Elev= 30
  4272.8 1388.78  4325.3 1386.44  4433.8 1364.45  4485.6 1350.40  4525.7 1346.88
  4572.2 1345.13  4696.9 1342.64  4937.8 1339.20  4965.4 1339.06  5012.1 1332.60
  5012.4 1332.10  5016.7 1332.60  5035.8 1338.07  5049.9 1336.88  5067.9 1339.02
  5149.0 1342.20  5248.0 1342.06  5438.4 1346.62  5558.8 1352.63  5643.8 1363.80
  5662.3 1363.87  5708.6 1369.04  5714.0 1368.00  5731.7 1373.10  5737.2 1370.96
  5750.7 1373.18  5806.6 1374.62  5845.2 1381.09  5852.9 1384.26  5922.8 1388.10
#Mann=12,-1,0
  4272.8    0.07       0  4525.7   0.035       0  4572.2    0.07       0
  4696.9    0.12       0  4937.8   0.035       0  4965.4    0.07       0
  5012.1    0.05       0  5016.7    0.07       0  5067.9   0.035       0
  5438.4    0.07       0  5643.8   0.035       0  5750.7    0.07       0
Bank Sta=5012.1,5016.7
Exp/Cntr=0.3,0.1

Chan Stop Cuts=-1