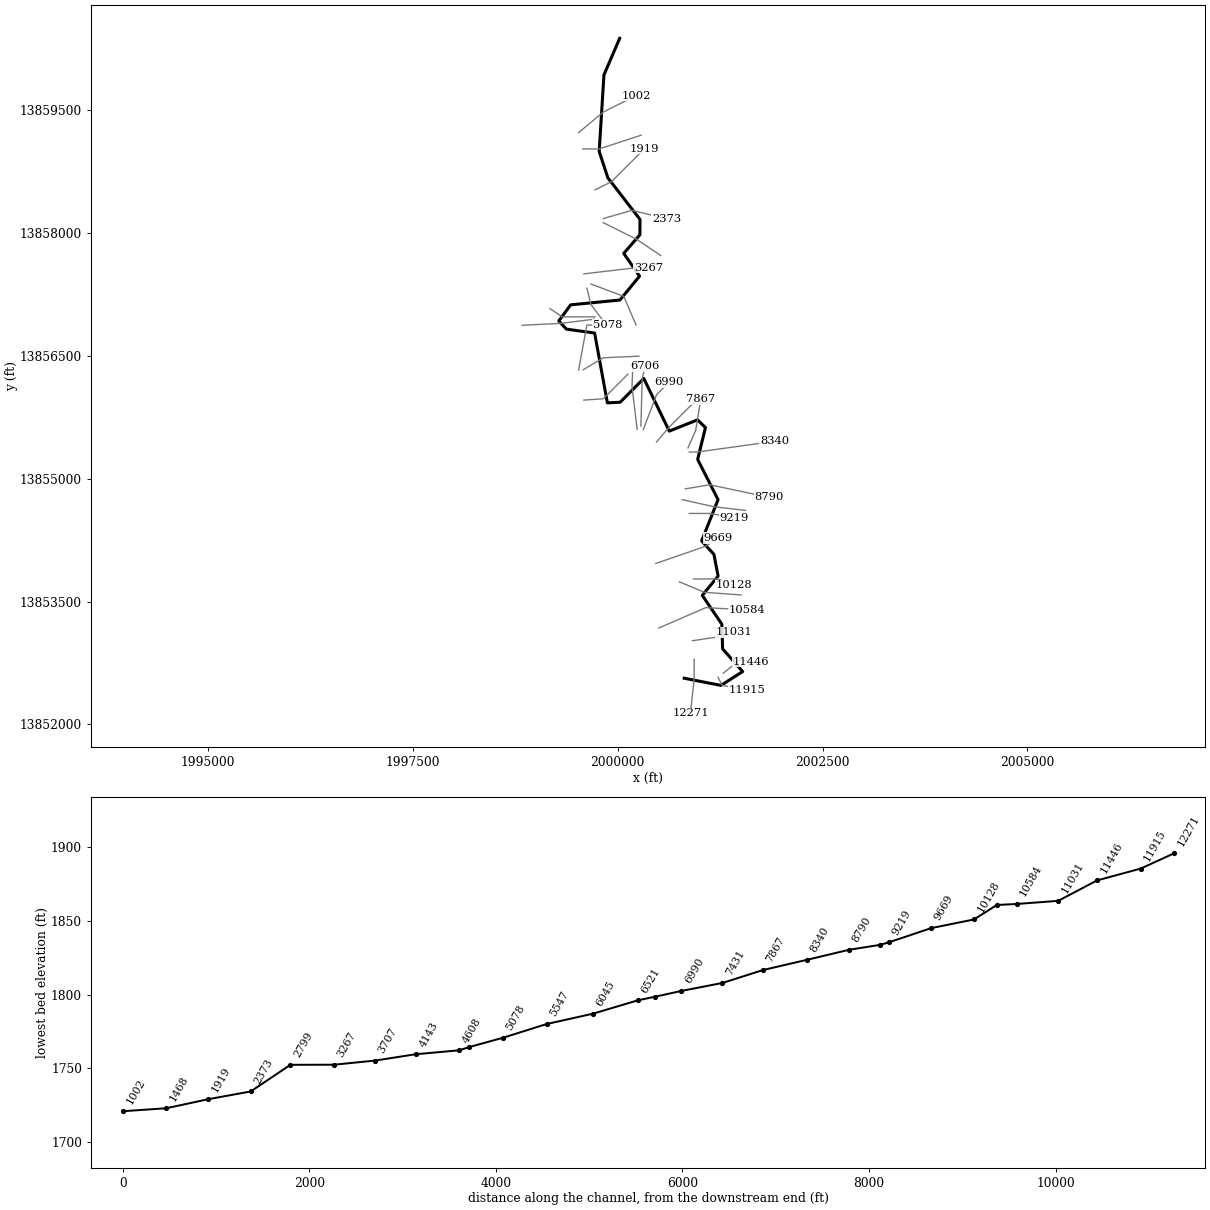
--- Stream0134_DS.prj (project) ---

Proj Title=Stream0134_DS Base Level Engineering
Current Plan=p01
Default Exp/Contr=0.3,0.1
English Units
Geom File=g01
Flow File=f01
Plan File=p01
Y Axis Title=Elevation
X Axis Title(PF)=Main Channel Distance
X Axis Title(XS)=Station
BEGIN DESCRIPTION:
Stream0134_DS
END DESCRIPTION:
DSS Export Rating Curves= 0
DSS Export Rating Curve Sorted= 0
DSS Export Volume Flow Curves= 0
DXF OffsetX= 0
DXF OffsetY= 0
DXF ScaleX= 1
DXF ScaleY= 10

--- Stream0134_DS.p01 (plan) ---

Plan Title=Multiple Run
Short Identifier=Multiple
Geom File=g01
Flow File=f01
Subcritical Flow
K Sum by GR= 0
Std Step Tol= 0.01
Critical Tol= 0.01
Num of Std Step Trials= 20
Max Error Tol= 0.3
Flow Tol Ratio= 0.001
Split Flow NTrial= 30
Split Flow Tol= 0.02
Split Flow Ratio= 0.02
Log Output Level= 0
Friction Slope Method= 1
Unsteady Friction Slope Method= 2
Unsteady Bridges Friction Slope Method= 1
Parabolic Critical Depth
Global Vel Dist=  1 , 1 , 1
Global Log Level= 0
CheckData=True
Encroach Param= -1, 0, 0, 0
BEGIN DESCRIPTION:
Multiple Run
END DESCRIPTION:

--- Stream0134_DS.f01 (steady flow) ---

Flow Title=Multiple
Number of Profiles=7
Profile Names=10-year,25-year,50-year,1pct_min,100-year,1pct_plu,500-year
River Rch & RM= Stream0134_DS,Reach-1,12271
     416     663     885     575    1147    2289    1900
River Rch & RM= Stream0134_DS,Reach-1,11915
     738    1222    1673    1112    2219    4427    3857
River Rch & RM= Stream0134_DS,Reach-1,9669
    1006    1697    2350    1578    3148    6280    5586
River Rch & RM= Stream0134_DS,Reach-1,6045
    1103    1869    2597    1749    3489    6962    6233
River Rch & RM= Stream0134_DS,Reach-1,4712
    1227    2091    2916    1970    3931    7843    7068
River Rch & RM= Stream0134_DS,Reach-1,3267
    1436    2469    3465    2353    4696    9369    8537
River Rch & RM= Stream0134_DS,Reach-1,1919
    1582    2733    3846    2619    5226   10426    9550
Boundary for River Rch & Prof#=Stream0134_DS,Reach-1,1
Up Type=0
Dn Type=3
Dn Slope=0.005
Boundary for River Rch & Prof#=Stream0134_DS,Reach-1,2
Up Type=0
Dn Type=3
Dn Slope=0.005
Boundary for River Rch & Prof#=Stream0134_DS,Reach-1,3
Up Type=0
Dn Type=3
Dn Slope=0.005
Boundary for River Rch & Prof#=Stream0134_DS,Reach-1,4
Up Type=0
Dn Type=3
Dn Slope=0.005
Boundary for River Rch & Prof#=Stream0134_DS,Reach-1,5
Up Type=0
Dn Type=3
Dn Slope=0.005
Boundary for River Rch & Prof#=Stream0134_DS,Reach-1,6
Up Type=0
Dn Type=3
Dn Slope=0.005
Boundary for River Rch & Prof#=Stream0134_DS,Reach-1,7
Up Type=0
Dn Type=3
Dn Slope=0.005

--- Stream0134_DS.g01 (geometry) ---

Geom Title=Existing Conditions
Program Version=4.10

River Reach=Stream0134_DS   ,Reach-1
Reach XY= 30
      2000812.56     13852563.25      2001261.11     13852475.61
      2001525.26     13852644.96      2001280.46     13852922.53
      2001271.25     13853223.45      2001032.51     13853575.04
       2001225.5      13853809.8        2001175.       13854075.
      2001024.95     13854240.34      2001225.22     13854743.69
      2000976.24      13855234.7      2001071.47     13855623.56
       2000975.1     13855717.72      2000630.11     13855579.96
      2000319.03     13856223.08      2000031.22     13855932.78
        1999875.       13855925.      1999719.17     13856777.31
        1999375.       13856825.      1999282.19     13856924.91
      1999426.48     13857121.39       2000027.7     13857180.36
      2000267.35     13857471.59      2000074.41       13857750.
      2000271.47     13857976.47      2000273.13     13858163.85
      1999880.52     13858672.57      1999775.07     13858995.03
      1999833.08      13859928.3        2000025.       13860375.

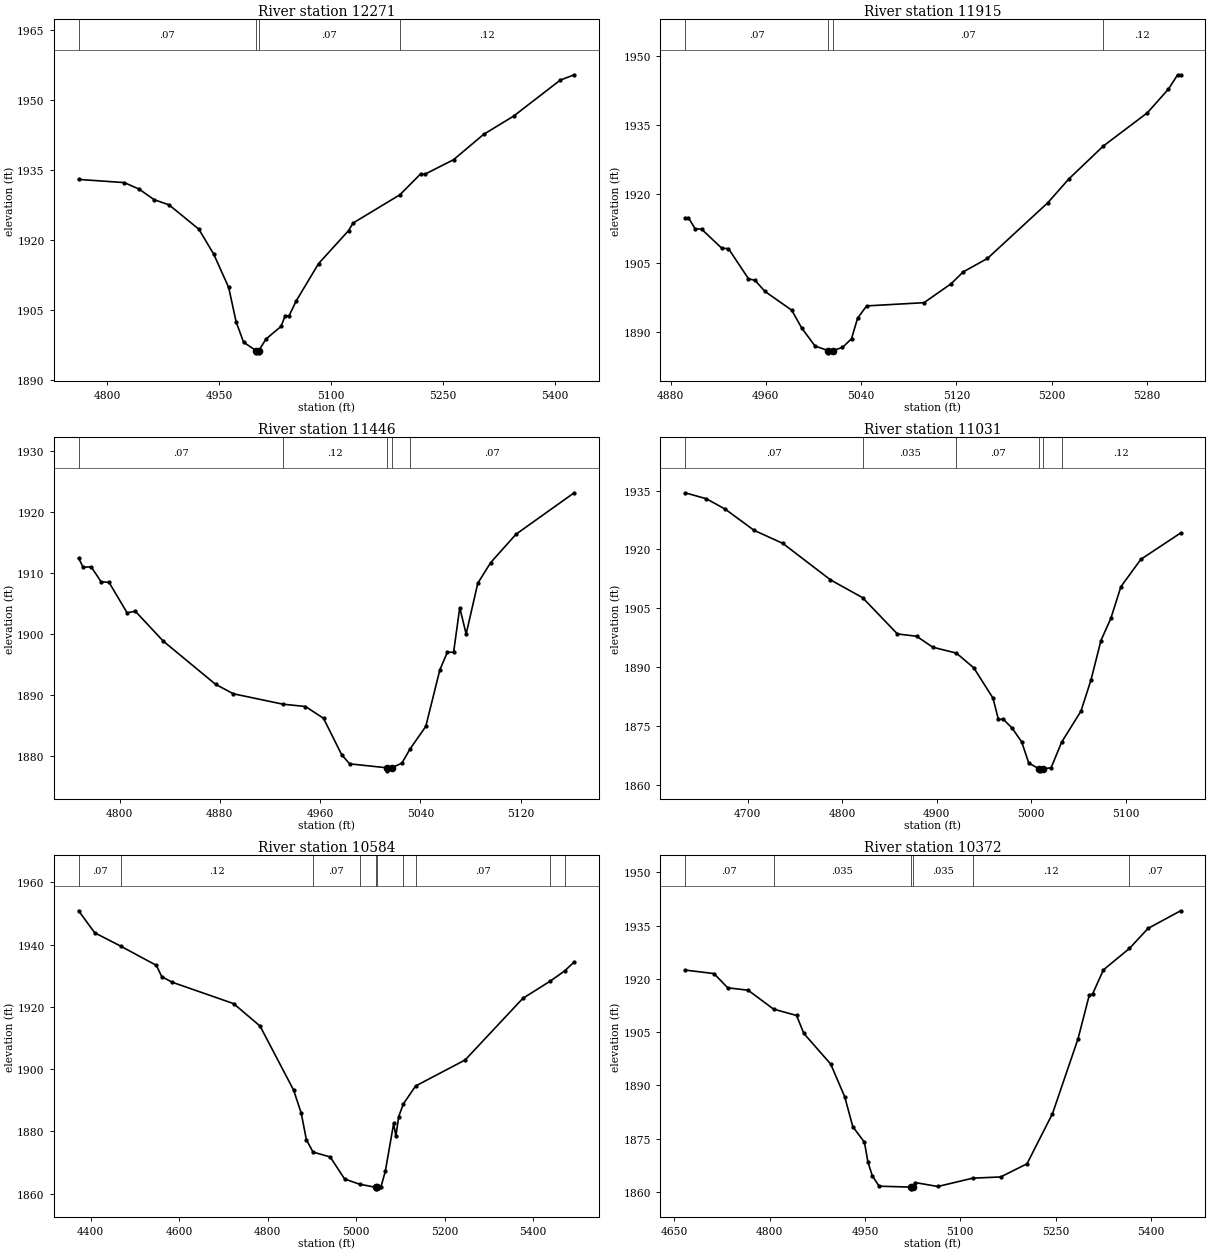
Type RM Length L Ch R = 1 ,12271   ,356,356,356
BEGIN DESCRIPTION:
Stream0134_DS 27.0
END DESCRIPTION:
XS GIS Cut Line= 3
      2000933.96     13852796.23      2000933.79      13852553.1
      2000887.64     13852134.26
#Sta/Elev= 30
  4761.4 1933.04  4822.6 1932.36  4842.6 1930.95  4862.6  1928.7  4882.6 1927.59
  4922.6 1922.37  4942.6    1917  4962.6 1909.89  4972.6 1902.51  4982.6 1898.14
  4999.1 1896.37  4999.3 1895.87  5002.8 1895.87  5003.1 1896.37  5012.7 1898.84
  5032.8 1901.53  5038.5 1903.87  5043.5 1903.76  5052.9 1906.93  5083.1 1914.99
  5123.3 1922.06  5129.4 1923.69  5192.3 1929.76  5220.3 1934.27  5225.4 1934.13
  5264.2 1937.27  5304.4 1942.69  5344.7 1946.61  5407.2 1954.32  5425.9 1955.47
#Mann= 4 ,-1 , 0
  4761.4     .07       0  4999.1     .05       0  5003.1     .07       0
  5192.3     .12       0
Bank Sta=4999.1,5003.1
XS Rating Curve= 0 ,0
Exp/Cntr=0.3,0.1

Type RM Length L Ch R = 1 ,11915   ,469,469,469
BEGIN DESCRIPTION:
Stream0134_DS 26.0
END DESCRIPTION:
XS GIS Cut Line= 3
      2001224.98     13852575.04        2001275.       13852475.
      2001575.01       13852425.
#Sta/Elev= 30
  4892.2 1914.88    4895 1914.88  4900.6 1912.52  4906.2 1912.38    4923 1908.27
  4928.6 1908.19  4945.4 1901.65  4950.9 1901.29  4959.3 1898.88  4981.7 1894.82
  4990.1 1890.95  5001.3 1887.03  5012.2 1886.06  5012.4 1885.56  5016.2 1886.06
  5024.3 1886.72  5031.9 1888.63    5037 1893.08  5044.6 1895.75  5092.8 1896.45
  5115.6 1900.58  5125.7 1903.14    5146 1906.05  5196.7 1918.15  5214.4 1923.33
  5243.3 1930.46  5280.3 1937.68    5298 1942.84  5305.7 1945.93  5308.2 1945.93
#Mann= 4 ,-1 , 0
  4892.2     .07       0  5012.2     .05       0  5016.2     .07       0
  5243.3     .12       0
Bank Sta=5012.2,5016.2
XS Rating Curve= 0 ,0
Exp/Cntr=0.3,0.1

Type RM Length L Ch R = 1 ,11446   ,415,415,415
BEGIN DESCRIPTION:
Stream0134_DS 25.0
END DESCRIPTION:
XS GIS Cut Line= 4
      2001289.97     13852625.59        2001475.       13852775.
      2001531.92     13852781.64      2001630.79     13852764.92
#Sta/Elev= 30
  4767.3 1912.46  4770.8 1910.96  4777.3 1911.01  4785.2 1908.57  4791.6 1908.45
    4806 1903.45  4812.5 1903.72  4834.8 1898.81  4876.6  1891.7  4890.8 1890.15
  4930.4 1888.44  4948.3 1888.06  4962.7 1886.12  4977.1 1880.17  4983.5 1878.64
  5013.2 1877.99  5013.4 1877.49  5017.2 1877.99  5025.3 1878.77  5031.6 1881.04
  5044.3 1884.79  5055.5 1894.07  5061.5 1896.98  5066.5 1896.98  5071.4  1904.3
  5076.5 1899.97  5085.8 1908.32    5096 1911.69  5116.3 1916.37  5162.7 1923.18
#Mann= 5 ,-1 , 0
  4767.3     .07       0  4930.4     .12       0  5013.2     .05       0
  5017.2     .12       0  5031.6     .07       0
Bank Sta=5013.2,5017.2
XS Rating Curve= 0 ,0
Exp/Cntr=0.3,0.1

Type RM Length L Ch R = 1 ,11031   ,447,447,447
BEGIN DESCRIPTION:
Stream0134_DS 24.0
END DESCRIPTION:
XS GIS Cut Line= 3
      2000912.87     13853021.21        2001275.       13853075.
      2001424.98     13853124.99
#Sta/Elev= 30
  4633.9 1934.42  4656.3 1932.91  4676.5 1930.23  4706.8 1924.87  4737.2 1921.55
  4787.7 1912.26  4821.7 1907.71  4858.5 1898.49  4878.7 1897.91  4895.9 1895.12
  4920.9 1893.61  4939.3 1889.86  4959.6 1882.16  4965.3 1876.73  4970.4  1876.8
  4979.8 1874.54  4989.9 1871.04  4997.5 1865.61  5008.5 1864.15  5008.8 1863.65
  5012.5 1864.15  5021.1 1864.44  5032.2 1870.94  5052.7 1878.87  5063.3 1886.81
  5073.8 1896.81  5084.3 1902.47  5094.9 1910.52    5116 1917.48  5158.1 1924.19
#Mann= 6 ,-1 , 0
  4633.9     .07       0  4821.7    .035       0  4920.9     .07       0
  5008.5     .05       0  5012.5     .07       0  5032.2     .12       0
Bank Sta=5008.5,5012.5
XS Rating Curve= 0 ,0
Exp/Cntr=0.3,0.1

Type RM Length L Ch R = 1 ,10584   ,212,212,212
BEGIN DESCRIPTION:
Stream0134_DS 23.0
END DESCRIPTION:
XS GIS Cut Line= 3
      2000503.96      13853176.8        2001075.       13853425.
      2001570.83      13853398.2
#Sta/Elev= 30
  4373.1  1950.9  4409.3 1943.83  4468.2 1939.53  4548.7 1933.35  4560.9 1929.71
  4584.3 1927.94  4723.2 1921.05  4782.8 1913.85  4858.6 1893.26  4875.8 1885.88
  4887.5 1877.29  4902.5 1873.34  4941.2 1871.77  4973.9 1864.68  5007.6 1863.01
  5043.8 1862.02  5044.1 1861.52  5047.8 1862.02  5055.8 1862.07  5065.8  1867.2
  5084.6 1882.53  5089.6 1878.45  5095.9 1884.72  5106.5 1888.82  5134.2 1894.58
  5246.1 1902.95  5376.3 1922.74  5438.2 1928.28  5470.9 1931.58  5492.3 1934.44
#Mann= 10 ,-1 , 0
  4373.1     .07       0  4468.2     .12       0  4902.5     .07       0
  5007.6    .035       0  5043.8     .05       0  5047.8    .035       0
  5106.5     .12       0  5134.2     .07       0  5438.2     .12       0
  5470.9     .07       0
Bank Sta=5043.8,5047.8
XS Rating Curve= 0 ,0
Exp/Cntr=0.3,0.1

Type RM Length L Ch R = 1 ,10372   ,244,244,244
BEGIN DESCRIPTION:
Stream0134_DS 22.5
END DESCRIPTION:
XS GIS Cut Line= 3
      2000753.05     13853740.04      2001060.46     13853612.03
       2001506.2     13853579.88
#Sta/Elev= 30
    4667 1922.49  4712.4  1921.5  4734.1 1917.49  4766.2 1916.81  4806.2 1911.49
  4842.4 1909.69  4853.9 1904.63  4896.2 1895.98  4918.3 1886.73  4930.9 1878.36
  4949.3 1873.95  4954.7 1868.42  4961.6 1864.52  4972.4 1861.57  5021.9 1861.33
  5022.1 1860.83  5025.9 1861.33  5028.9 1862.61  5064.7 1861.49  5119.6 1863.84
  5163.6 1864.18  5205.1 1867.89  5245.2 1882.02  5285.3 1903.05  5303.2 1915.48
  5308.3 1915.75  5325.4 1922.55  5366.4  1928.6  5395.6 1934.23  5446.9  1939.2
#Mann= 6 ,-1 , 0
    4667     .07       0  4806.2    .035       0  5021.9    .035       0
  5025.9    .035       0  5119.6     .12       0  5366.4     .07       0
Bank Sta=5021.9,5025.9
XS Rating Curve= 0 ,0
Exp/Cntr=0.3,0.1

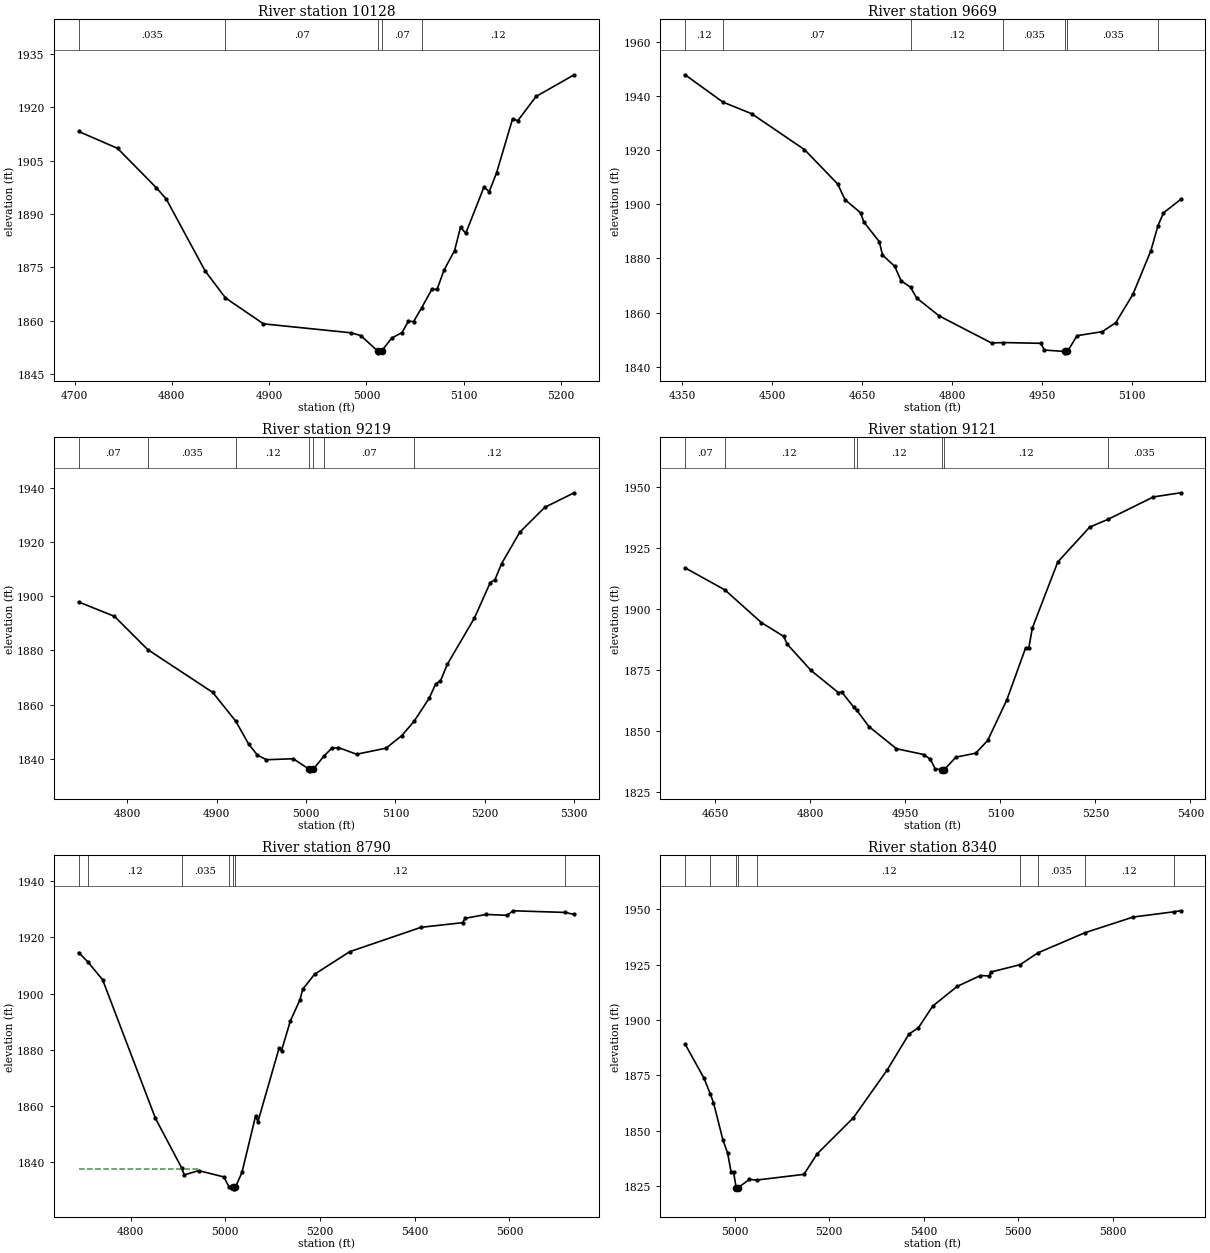
Type RM Length L Ch R = 1 ,10128   ,459,459,459
BEGIN DESCRIPTION:
Stream0134_DS 22.0
END DESCRIPTION:
XS GIS Cut Line= 3
      2000924.96       13853775.        2001225.       13853775.
      2001418.91     13853696.34
#Sta/Elev= 30
  4704.2  1913.2  4744.2 1908.45  4784.2 1897.35  4794.2 1894.24  4834.2 1874.03
  4855.1 1866.44  4894.2 1859.15  4984.2 1856.64  4994.2 1855.86  5011.6 1851.51
  5011.8 1851.01  5015.6 1851.51  5025.8 1855.12  5036.6 1856.72  5043.1 1859.87
  5048.5  1859.8  5056.6 1863.59  5067.2 1868.84  5072.6 1868.86  5079.8 1874.28
  5090.6 1879.75  5096.7 1886.28  5102.1 1884.59  5120.8 1897.59  5126.2 1896.28
  5133.7 1901.54  5150.2 1916.74  5155.6 1916.23  5174.3 1923.02  5213.5 1929.12
#Mann= 5 ,-1 , 0
  4704.2    .035       0  4855.1     .07       0  5011.6     .05       0
  5015.6     .07       0  5056.6     .12       0
Bank Sta=5011.6,5015.6
XS Rating Curve= 0 ,0
Exp/Cntr=0.3,0.1

Type RM Length L Ch R = 1 ,9669    ,450,450,450
BEGIN DESCRIPTION:
Stream0134_DS 21.0
END DESCRIPTION:
XS GIS Cut Line= 3
      2000464.88      13853963.9        2001075.       13854175.
      2001225.01     13854275.01
#Sta/Elev= 30
  4354.7 1947.83  4417.7 1937.74  4465.5 1933.46  4553.7 1920.19  4608.8 1907.54
  4621.3  1901.7  4647.2 1896.84  4652.5 1893.47  4678.4 1886.18  4683.7 1881.27
    4704 1877.09  4714.8 1871.71  4730.4 1869.36  4740.7 1865.38  4778.1 1858.78
  4865.4 1848.76  4884.9 1848.93  4947.4 1848.65  4953.6 1846.16    4988 1845.63
  4988.3 1845.13    4992 1845.63  5007.8 1851.46  5049.9 1852.95  5072.4 1856.25
    5101 1866.72    5131 1882.86  5142.9 1892.15    5152 1896.83  5180.6 1901.78
#Mann= 7 ,-1 , 0
  4354.7     .12       0  4417.7     .07       0  4730.4     .12       0
  4884.9    .035       0    4988     .05       0    4992    .035       0
  5142.9     .12       0
Bank Sta=4988,4992
XS Rating Curve= 0 ,0
Exp/Cntr=0.3,0.1

Type RM Length L Ch R = 1 ,9219    ,98,98,98
BEGIN DESCRIPTION:
Stream0134_DS 20.0
END DESCRIPTION:
XS GIS Cut Line= 3
      2000875.02       13854575.        2001125.       13854575.
      2001424.98       13854525.
#Sta/Elev= 30
  4745.7 1897.84  4785.7 1892.54  4822.9  1880.3  4895.7 1864.47  4921.4 1853.87
  4935.7 1845.49  4945.7 1841.33  4955.7 1839.66  4985.7 1840.02  5003.8 1836.06
  5004.1 1835.56  5007.8 1836.06  5020.4 1841.15  5028.6 1843.83  5036.2 1844.14
  5056.5 1841.68  5089.5 1843.93  5107.2 1848.59  5120.8 1853.84  5137.6 1862.29
  5145.2 1867.74  5150.3 1868.72  5157.9 1874.82  5188.3 1891.93    5206 1905.01
  5211.1 1905.98  5218.7    1912    5239 1923.57  5266.9 1932.73  5299.8  1938.1
#Mann= 7 ,-1 , 0
  4745.7     .07       0  4822.9    .035       0  4921.4     .12       0
  5003.8     .05       0  5007.8     .12       0  5020.4     .07       0
  5120.8     .12       0
Bank Sta=5003.8,5007.8
XS Rating Curve= 0 ,0
Exp/Cntr=0.3,0.1

Type RM Length L Ch R = 1 ,9121    ,331,331,331
BEGIN DESCRIPTION:
Stream0134_DS 19.5
END DESCRIPTION:
XS GIS Cut Line= 3
      2000787.32     13854743.92      2001175.62     13854656.59
      2001557.66     13854612.29
#Sta/Elev= 30
    4602 1916.81    4665 1907.75  4722.6 1894.38  4757.5 1888.81  4763.6 1885.48
  4800.8 1874.84  4844.1 1865.74  4849.2 1866.06  4868.4 1859.76    4873 1858.56
  4892.5 1851.82  4935.8 1842.79  4978.9 1840.43  4989.3  1838.5  4997.1 1834.49
  5007.4 1834.25  5007.7 1833.75  5011.4 1834.25  5029.6 1839.34    5061 1840.97
  5079.9  1846.2  5110.1 1862.78  5139.6 1883.93  5144.7 1883.88  5150.4 1892.18
  5190.6 1919.22    5241 1933.48  5269.4 1936.59  5341.7 1945.83  5384.6 1947.52
#Mann= 7 ,-1 , 0
    4602     .07       0    4665     .12       0  4868.4    .035       0
    4873     .12       0  5007.4     .05       0  5011.4     .12       0
  5269.4    .035       0
Bank Sta=5007.4,5011.4
XS Rating Curve= 0 ,0
Exp/Cntr=0.3,0.1

Type RM Length L Ch R = 1 ,8790    ,450,450,450
BEGIN DESCRIPTION:
Stream0134_DS 19.0
END DESCRIPTION:
XS GIS Cut Line= 3
      2000824.99       13854875.        2001125.       13854925.
      2001851.41     13854771.52
#Sta/Elev= 30
  4690.1 1914.58  4709.5 1911.28  4740.8 1904.88  4852.3 1855.56  4908.2 1837.73
  4913.1 1835.39  4943.6 1836.93  4996.8 1834.68  5007.9 1831.11  5017.1 1830.94
  5017.4 1830.44  5021.1 1830.94  5035.1 1836.33  5063.7 1856.29  5068.9 1854.41
  5113.5 1880.59  5118.6 1879.67  5137.3 1890.23  5157.8 1897.86  5163.2 1901.47
  5188.4 1906.86  5262.7  1914.9  5413.3 1923.57  5501.2 1925.23  5506.3 1926.78
  5550.9 1928.15  5595.6 1927.85  5607.5 1929.46  5717.6 1928.87  5736.7 1928.16
#Mann= 7 ,-1 , 0
  4690.1     .07       0  4709.5     .12       0  4908.2    .035       0
  5007.9     .12       0  5017.1    .035       0  5021.1     .12       0
  5717.6     .07       0
#XS Ineff= 2 , 0
       0 4943.77 1837.42               0
Permanent Ineff=
       F       F
Bank Sta=5017.1,5021.1
XS Rating Curve= 0 ,0
Exp/Cntr=0.3,0.1

Type RM Length L Ch R = 1 ,8340    ,473,473,473
BEGIN DESCRIPTION:
Stream0134_DS 18.0
END DESCRIPTION:
XS GIS Cut Line= 3
      2000874.97       13855325.        2000975.       13855325.
      2001914.56     13855455.45
#Sta/Elev= 30
  4895.4 1889.03  4935.4 1873.64    4949 1866.33  4955.4 1862.65  4975.4 1845.76
  4985.4 1839.79  4992.9  1831.1    4998  1831.1  5003.5 1824.14  5003.8 1823.64
  5007.5 1824.14  5031.3 1827.87  5047.8 1827.63  5146.9 1830.19  5174.7 1839.41
  5251.4 1855.73  5323.1 1877.36    5369 1893.53  5389.2 1896.45  5419.5 1906.24
  5471.5 1915.16  5520.4    1920  5538.2 1919.86  5543.2 1921.65  5604.3 1924.92
  5642.1 1930.27  5741.2 1939.34  5843.5 1946.45  5929.6 1948.82    5944 1949.28
#Mann= 9 ,-1 , 0
  4895.4     .12       0    4949    .035       0  5003.5    .035       0
  5007.5    .035       0  5047.8     .12       0  5604.3     .07       0
  5642.1    .035       0  5741.2     .12       0  5929.6     .07       0
Bank Sta=5003.5,5007.5
XS Rating Curve= 0 ,0
Exp/Cntr=0.3,0.1

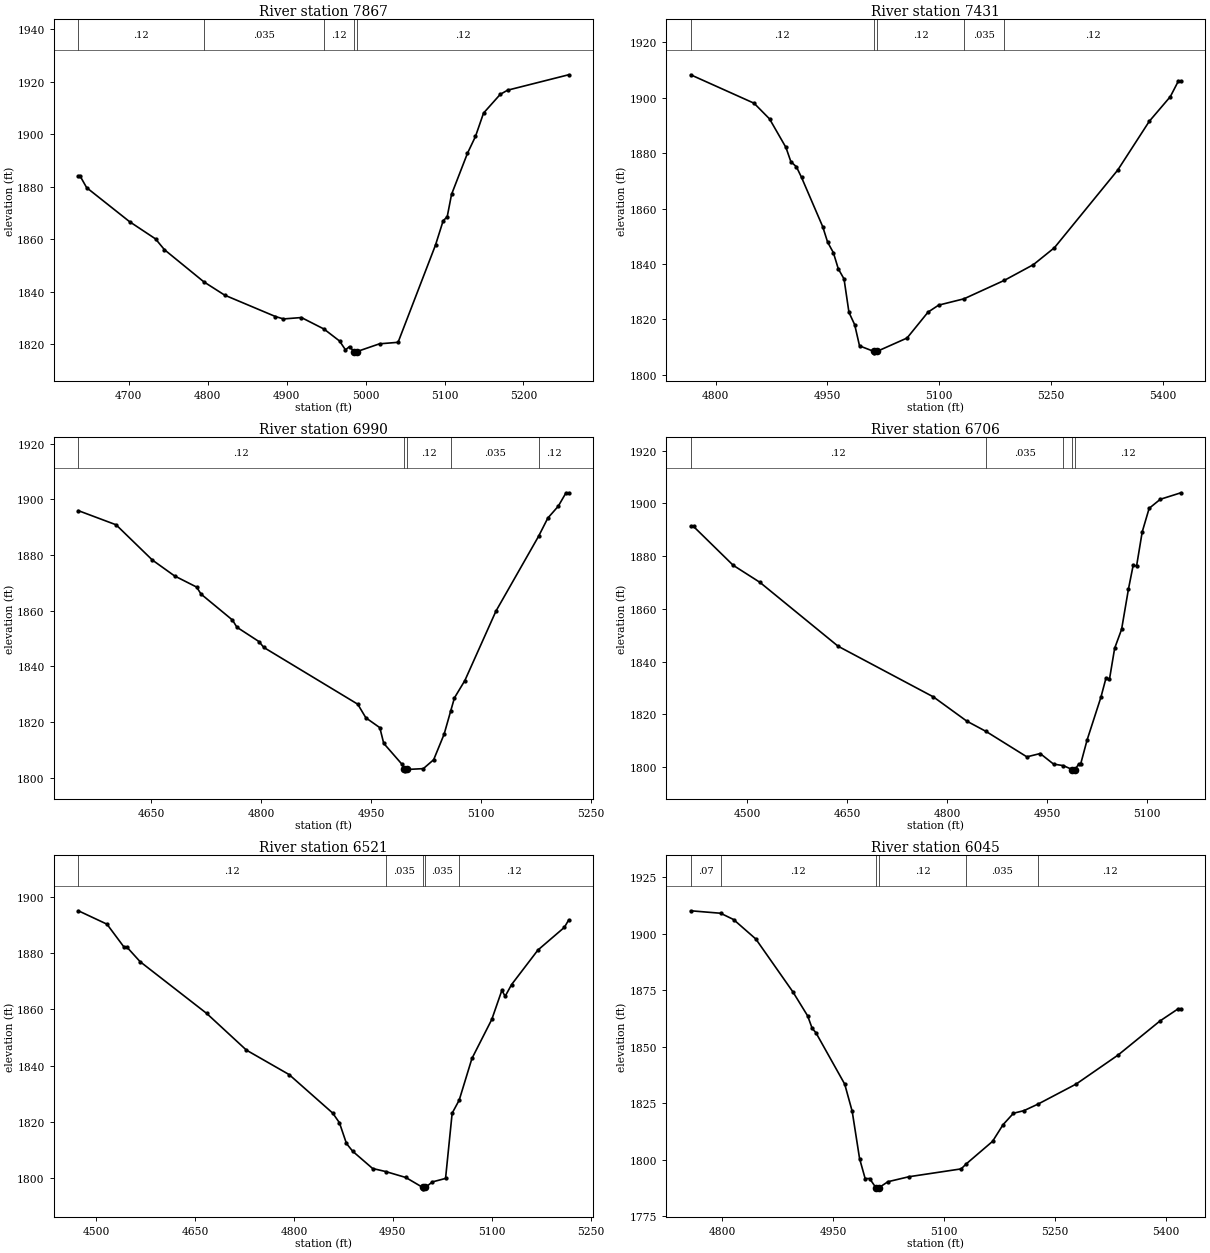
Type RM Length L Ch R = 1 ,7867    ,436,436,436
BEGIN DESCRIPTION:
Stream0134_DS 17.0
END DESCRIPTION:
XS GIS Cut Line= 4
      2000857.79     13855375.74      2000952.16     13855587.69
        2000975.       13855725.      2001014.27     13855971.38
#Sta/Elev= 30
  4636.4 1883.99  4638.7 1883.99  4646.9 1879.62  4701.3 1866.65  4734.1  1860.1
  4745.4 1855.98  4795.4 1843.71  4821.7 1838.66    4886 1830.51  4896.1  1829.6
  4918.8 1830.13  4947.4 1825.75  4967.1 1821.19  4974.6 1817.82  4979.7 1819.06
  4985.3 1817.18  4985.6 1816.68  4989.3 1817.18  5017.7 1820.12  5041.2 1820.69
  5088.6 1857.76  5098.3 1867.02  5103.4 1868.52  5108.9 1877.06  5129.1 1892.75
  5139.2 1899.14  5149.4 1908.03  5170.6 1915.19  5179.8 1916.76  5257.1 1922.64
#Mann= 5 ,-1 , 0
  4636.4     .12       0  4795.4    .035       0  4947.4     .12       0
  4985.3     .05       0  4989.3     .12       0
Bank Sta=4985.3,4989.3
XS Rating Curve= 0 ,0
Exp/Cntr=0.3,0.1

Type RM Length L Ch R = 1 ,7431    ,441,441,441
BEGIN DESCRIPTION:
Stream0134_DS 16.0
END DESCRIPTION:
XS GIS Cut Line= 3
      2000473.57     13855446.75        2000625.       13855625.
      2000925.03     13855925.03
#Sta/Elev= 30
  4766.4 1908.28  4851.5 1898.01  4872.3 1892.34  4894.3 1882.04  4900.9 1876.92
  4908.4 1875.04  4915.2 1871.25  4943.7 1853.42  4950.3 1847.83    4958 1844.05
  4964.6 1838.21  4972.3 1834.57  4978.9  1822.5  4986.6 1818.04  4993.1 1810.41
  5012.4 1808.39  5012.7 1807.89  5016.4 1808.39  5056.9 1813.24  5085.1 1822.59
  5099.3 1825.11  5133.4  1827.4  5187.7 1834.08  5226.6 1839.74  5254.8 1845.85
  5339.7 1873.84  5382.1 1891.47  5410.4 1900.39    5421 1905.91  5424.6 1905.91
#Mann= 5 ,-1 , 0
  4766.4     .12       0  5012.4     .05       0  5016.4     .12       0
  5133.4    .035       0  5187.7     .12       0
Bank Sta=5012.4,5016.4
XS Rating Curve= 0 ,0
Exp/Cntr=0.3,0.1

Type RM Length L Ch R = 1 ,6990    ,284,284,284
BEGIN DESCRIPTION:
Stream0134_DS 15.0
END DESCRIPTION:
XS GIS Cut Line= 3
      2000312.99     13855598.68        2000475.       13856025.
        2000625.       13856175.
#Sta/Elev= 30
  4551.1 1895.91  4602.5 1890.83    4652 1878.16  4682.2 1872.47  4712.3 1868.46
  4718.3 1865.94  4761.1 1856.63  4767.2 1854.04  4797.3 1848.88  4803.9 1846.77
  4931.9 1826.39    4943 1821.49    4962 1817.96  4967.3 1812.33  4992.1 1804.84
  4995.5 1802.95  4995.7 1802.45  4999.5 1802.95  5021.3 1803.24  5035.4 1806.45
  5049.6 1815.58  5058.5 1823.84  5063.7 1828.66  5077.9 1834.88  5120.3 1859.83
  5178.3 1886.66    5191 1893.25  5205.2  1897.5  5215.8 1902.33  5219.3 1902.33
#Mann= 5 ,-1 , 0
  4551.1     .12       0  4995.5     .05       0  4999.5     .12       0
  5058.5    .035       0  5178.3     .12       0
Bank Sta=4995.5,4999.5
XS Rating Curve= 0 ,0
Exp/Cntr=0.3,0.1

Type RM Length L Ch R = 1 ,6706    ,185,185,185
BEGIN DESCRIPTION:
Stream0134_DS 14.5
END DESCRIPTION:
XS GIS Cut Line= 3
      2000283.91      13855641.3      2000299.85     13856225.58
      2000337.43     13856371.11
#Sta/Elev= 30
  4415.5 1891.24  4419.8 1891.24  4479.2 1876.52  4519.2 1870.06  4636.5  1845.8
  4779.3 1826.58  4829.4 1817.38  4858.4 1813.45  4919.4 1803.83  4939.4 1805.08
  4959.4 1801.08    4974  1800.5  4987.4 1799.02  4987.7 1798.52  4991.4 1799.02
  4997.2 1801.07    5000 1801.07  5009.7 1810.24  5030.4 1826.44  5038.1 1833.81
  5043.2 1833.23    5051 1845.04  5061.4 1852.21  5071.7 1867.52  5078.7 1876.45
  5083.9  1876.3  5092.3 1889.18  5102.7 1898.13  5119.4 1901.56  5150.3 1904.03
#Mann= 5 ,-1 , 0
  4415.5     .12       0  4858.4    .035       0    4974     .12       0
  4987.4     .05       0  4991.4     .12       0
Bank Sta=4987.4,4991.4
XS Rating Curve= 0 ,0
Exp/Cntr=0.3,0.1

Type RM Length L Ch R = 1 ,6521    ,476,476,476
BEGIN DESCRIPTION:
Stream0134_DS 14.0
END DESCRIPTION:
XS GIS Cut Line= 3
      2000238.34     13855601.96        2000175.       13856125.
      2000184.36     13856341.44
#Sta/Elev= 30
  4473.1 1895.19  4516.5 1890.41    4542 1882.35  4547.1 1882.14  4566.8 1877.03
  4667.6 1858.61    4728  1845.5  4792.7 1836.79  4858.9 1823.04    4869 1819.63
  4879.7 1812.21  4889.2 1809.43  4919.4 1803.29    4939 1802.22  4969.7 1800.09
  4995.4 1796.54  4995.7 1796.04  4999.4 1796.54    5010 1798.51    5030 1799.75
    5040 1823.01  5050.7 1827.68    5070 1842.52  5100.1 1856.44  5115.4 1866.81
  5120.4  1864.7  5130.1 1868.87  5170.1 1881.19  5210.2 1889.28  5216.6 1891.84
#Mann= 5 ,-1 , 0
  4473.1     .12       0    4939    .035       0  4995.4    .035       0
  4999.4    .035       0  5050.7     .12       0
Bank Sta=4995.4,4999.4
XS Rating Curve= 0 ,0
Exp/Cntr=0.3,0.1

Type RM Length L Ch R = 1 ,6045    ,498,498,498
BEGIN DESCRIPTION:
Stream0134_DS 13.0
END DESCRIPTION:
XS GIS Cut Line= 3
      1999587.25      13855958.7        1999825.       13855975.
      2000125.02     13856275.02
#Sta/Elev= 30
  4757.7 1910.08  4798.1 1908.99  4815.6 1906.22  4845.7 1897.61  4895.8 1874.22
  4915.8 1863.57  4921.9 1858.06  4926.9 1856.17  4965.9 1833.38    4976 1821.36
    4986  1800.4  4993.5 1791.61  4999.5 1791.61  5008.1 1787.55  5008.4 1787.05
  5012.1 1787.55  5024.3  1790.2  5052.6  1792.4  5123.3 1795.88  5130.1 1798.07
  5165.7 1808.05  5179.9 1815.43    5194  1820.5  5208.1 1821.64  5227.4 1824.58
  5278.8 1833.43  5335.4 1846.25    5392 1861.32  5416.7 1866.73  5420.3 1866.73
#Mann= 6 ,-1 , 0
  4757.7     .07       0  4798.1     .12       0  5008.1     .05       0
  5012.1     .12       0  5130.1    .035       0  5227.4     .12       0
Bank Sta=5008.1,5012.1
XS Rating Curve= 0 ,0
Exp/Cntr=0.3,0.1

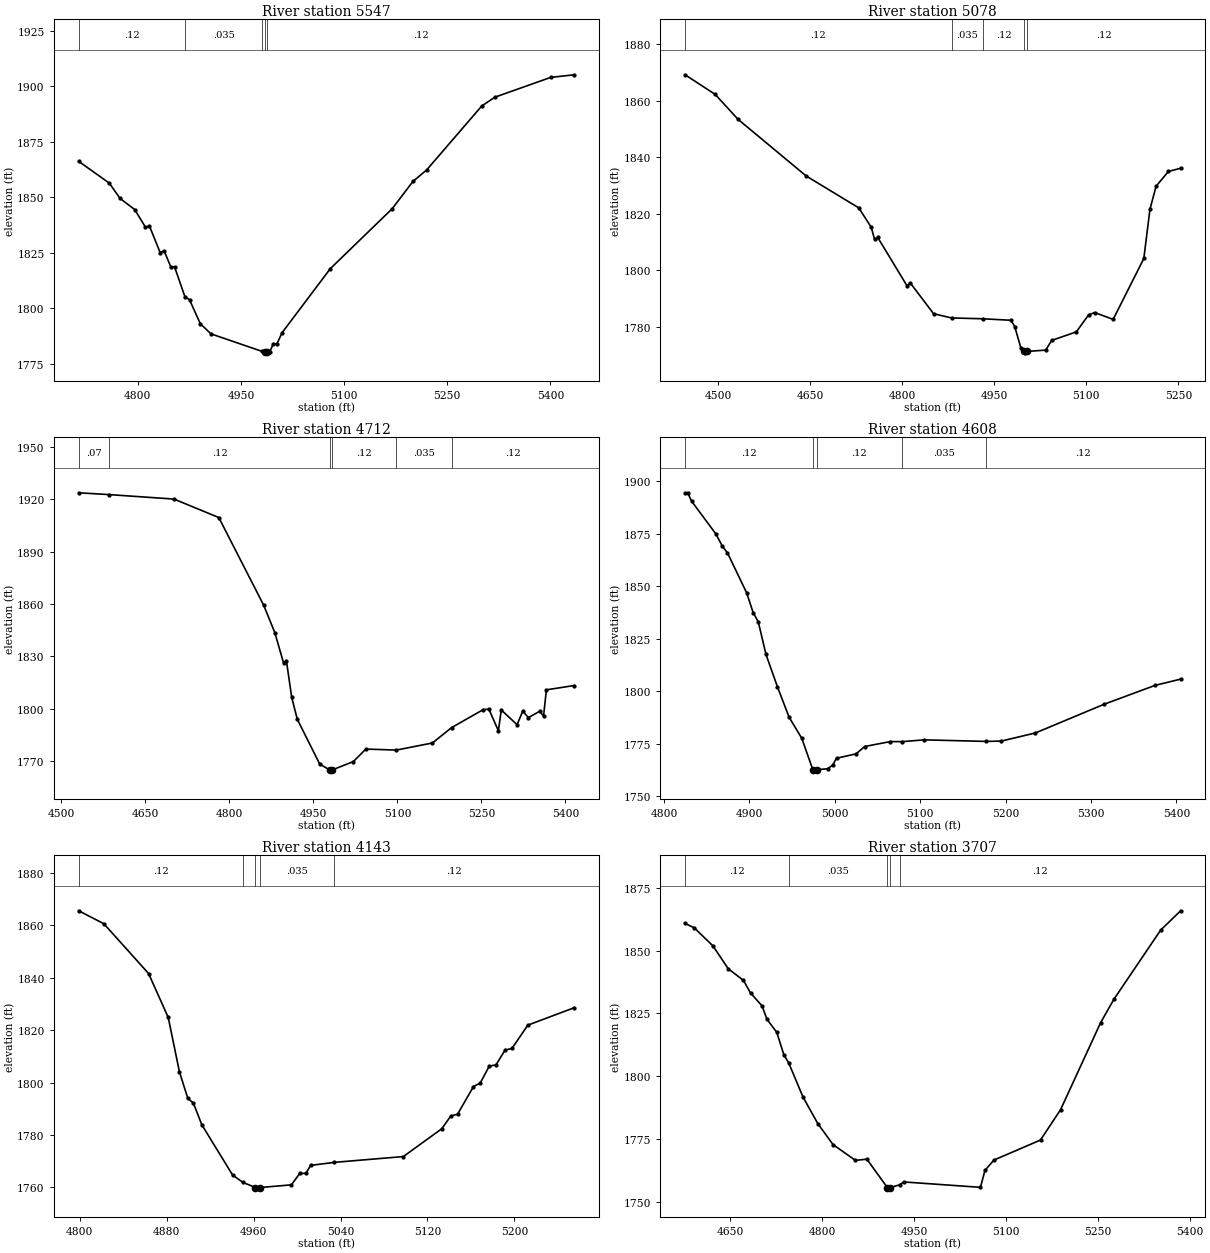
Type RM Length L Ch R = 1 ,5547    ,469,469,469
BEGIN DESCRIPTION:
Stream0134_DS 12.0
END DESCRIPTION:
XS GIS Cut Line= 3
      1999579.48     13856328.49        1999825.       13856475.
      2000259.22     13856495.16
#Sta/Elev= 30
    4714 1866.29  4758.6 1856.46  4774.2 1849.57  4795.6 1844.53  4811.1 1836.64
    4817 1837.13  4832.5 1825.18  4838.4 1825.96  4848.1 1818.64  4853.5 1818.73
  4868.5 1805.32  4875.3 1803.91  4890.9 1793.14  4906.5 1788.54  4981.1 1780.62
  4984.3  1780.5  4984.5    1780  4988.3  1780.5  4992.1 1780.51    4997 1784.08
  5002.4 1784.08  5009.9 1789.09    5080 1817.93  5170.1 1844.97  5200.1  1857.2
  5220.1  1862.4  5300.2 1891.21  5319.3 1895.17  5400.3 1904.08  5434.6 1905.27
#Mann= 5 ,-1 , 0
    4714     .12       0  4868.5    .035       0  4981.1     .12       0
  4984.3     .05       0  4988.3     .12       0
Bank Sta=4984.3,4988.3
XS Rating Curve= 0 ,0
Exp/Cntr=0.3,0.1

Type RM Length L Ch R = 1 ,5078    ,366,366,366
BEGIN DESCRIPTION:
Stream0134_DS 11.0
END DESCRIPTION:
XS GIS Cut Line= 3
      1999524.03     13856326.76        1999625.       13856875.
      1999875.04       13856875.
#Sta/Elev= 30
  4446.2  1869.2  4495.3 1862.24  4532.6 1853.39  4643.7 1833.31  4729.1 1822.06
  4749.5  1815.2  4754.9 1810.88    4760  1811.6  4807.9 1794.39    4813 1795.48
  4851.1 1784.54  4880.5 1783.03  4931.4 1782.74  4977.1 1782.21  4983.3    1780
  4993.5  1772.3  4999.1 1771.17  4999.4 1770.67  5003.1 1771.17  5033.7 1771.63
  5043.7 1775.08  5083.7  1778.1  5103.7 1784.11  5113.7 1784.95  5143.7 1782.52
  5193.7  1804.1  5203.7 1821.56  5213.7  1829.7  5233.7 1834.94  5253.7 1836.08
#Mann= 5 ,-1 , 0
  4446.2     .12       0  4880.5    .035       0  4931.4     .12       0
  4999.1     .05       0  5003.1     .12       0
Bank Sta=4999.1,5003.1
XS Rating Curve= 0 ,0
Exp/Cntr=0.3,0.1

Type RM Length L Ch R = 1 ,4712    ,104,104,104
BEGIN DESCRIPTION:
Stream0134_DS 10.5
END DESCRIPTION:
XS GIS Cut Line= 3
      1998834.99     13856872.23      1999303.84     13856894.98
      1999716.12     13856946.55
#Sta/Elev= 30
  4530.6 1923.79  4585.4 1922.74  4700.8 1920.18  4780.9 1909.59    4861 1859.31
    4881 1843.52  4896.6  1826.1  4901.6  1827.5  4911.1 1806.38  4921.1 1793.83
  4961.1 1768.17    4979 1764.78  4979.3 1764.28  4983.3 1764.78  5021.3 1769.62
  5043.5 1776.78  5097.7 1776.18  5162.4 1780.26  5196.6 1789.08  5253.1 1799.41
  5263.2 1799.65  5280.2 1787.26  5285.3 1799.19  5313.6 1790.76  5323.7 1798.61
  5333.7 1794.83  5353.9 1798.45  5360.8 1795.71  5365.9 1810.75  5415.5 1813.22
#Mann= 6 ,-1 , 0
  4530.6     .07       0  4585.4     .12       0    4979     .05       0
  4983.3     .12       0  5097.7    .035       0  5196.6     .12       0
Bank Sta=4979,4983.3
XS Rating Curve= 0 ,0
Exp/Cntr=0.3,0.1

Type RM Length L Ch R = 1 ,4608    ,465,465,465
BEGIN DESCRIPTION:
Stream0134_DS 10.0
END DESCRIPTION:
XS GIS Cut Line= 3
      1999174.97     13857075.02        1999325.       13856975.
      1999724.99       13856975.
#Sta/Elev= 30
  4824.6 1894.51  4827.6 1894.51  4832.1 1890.56  4860.7 1874.89  4868.2 1869.08
  4874.2 1865.91  4896.7 1846.85  4904.3 1837.47  4910.3 1833.08  4919.3 1817.57
  4932.8 1802.09  4946.3 1787.75  4961.3 1777.58  4974.2 1762.64  4974.5 1762.14
  4978.5 1762.64  4991.4 1763.14  4997.4 1764.86  5001.9 1768.13  5024.9 1770.24
  5034.9 1773.72  5064.9 1776.07  5078.6 1776.04  5104.9 1776.89  5177.1 1776.15
  5194.9 1776.31  5234.9 1780.18  5314.9 1793.78  5374.9 1802.82  5404.9  1805.8
#Mann= 5 ,-1 , 0
  4824.6     .12       0  4974.2     .05       0  4978.5     .12       0
  5078.6    .035       0  5177.1     .12       0
Bank Sta=4974.2,4978.5
XS Rating Curve= 0 ,0
Exp/Cntr=0.3,0.1

Type RM Length L Ch R = 1 ,4143    ,436,436,436
BEGIN DESCRIPTION:
Stream0134_DS 9.0
END DESCRIPTION:
XS GIS Cut Line= 3
        1999625.     13857325.01        1999675.       13857125.
      1999825.02     13856924.98
#Sta/Elev= 30
  4798.9 1865.53  4822.1  1860.6  4863.3  1841.6  4881.4 1824.84  4891.7 1804.09
  4899.4 1794.02  4904.6 1792.13  4912.3 1783.92  4940.6 1764.77  4950.2 1761.93
  4961.7 1759.98    4962 1759.48    4966 1759.98  4994.8 1761.01  5002.5 1765.37
  5008.2 1765.37  5012.4 1768.42  5034.3 1769.58  5097.8 1771.79  5133.2 1782.39
  5141.5 1787.24  5147.8 1787.97  5162.4  1798.5  5168.6 1799.81  5176.9 1806.26
  5183.2 1806.79  5191.5 1812.44  5197.8 1813.01  5212.4  1821.9  5255.1 1828.56
#Mann= 5 ,-1 , 0
  4798.9     .12       0  4950.2    .035       0  4961.7    .035       0
    4966    .035       0  5034.3     .12       0
Bank Sta=4961.7,4966
XS Rating Curve= 0 ,0
Exp/Cntr=0.3,0.1

Type RM Length L Ch R = 1 ,3707    ,440,440,440
BEGIN DESCRIPTION:
Stream0134_DS 8.0
END DESCRIPTION:
XS GIS Cut Line= 3
      1999674.99       13857375.        2000075.       13857225.
        2000225.       13856875.
#Sta/Elev= 30
  4576.9  1860.8    4592 1859.02  4622.3 1851.86  4647.2 1842.79  4672.1 1838.11
  4683.7  1833.1  4702.4 1827.98  4710.4 1822.65  4726.4 1817.46    4738 1808.47
  4745.8 1805.31  4769.1 1791.75  4793.2 1781.17  4818.1 1772.79  4854.6  1766.5
  4873.3 1766.98  4906.7 1755.67    4907 1755.17    4911 1755.67  4926.5 1756.75
  4933.8 1757.91  5058.5 1755.77  5065.8  1762.5  5080.3 1766.61  5156.4  1774.6
  5189.1 1786.66  5254.3 1821.25  5276.1 1830.63  5352.3 1858.15  5384.9 1865.84
#Mann= 5 ,-1 , 0
  4576.9     .12       0  4745.8    .035       0  4906.7     .05       0
    4911    .035       0  4926.5     .12       0
Bank Sta=4906.7,4911
XS Rating Curve= 0 ,0
Exp/Cntr=0.3,0.1

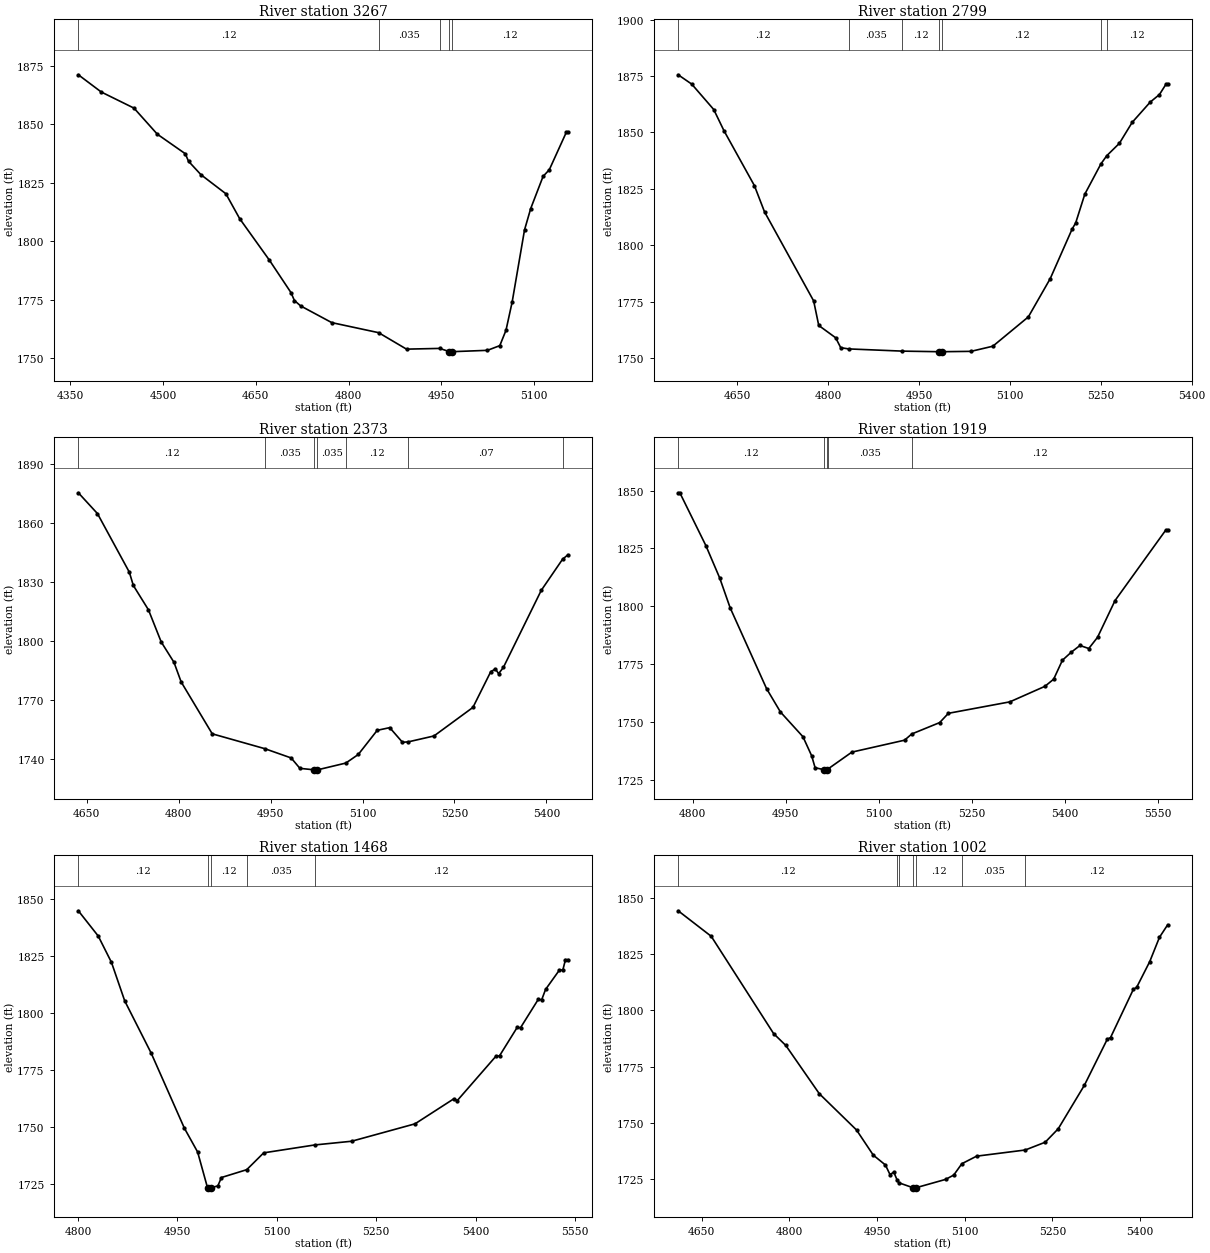
Type RM Length L Ch R = 1 ,3267    ,468,468,468
BEGIN DESCRIPTION:
Stream0134_DS 7.0
END DESCRIPTION:
XS GIS Cut Line= 3
      1999588.15     13857499.72        2000225.       13857575.
      2000375.02       13857575.
#Sta/Elev= 30
  4363.2 1871.08  4400.3 1863.72  4453.2 1856.84  4490.9 1845.71  4536.1 1837.37
  4541.3 1834.17  4561.4 1828.42  4601.7 1820.29    4624 1809.66  4672.2 1791.88
  4706.9  1778.1  4712.5  1774.7  4722.5 1772.41  4772.9 1765.26  4848.6 1760.97
  4893.7 1753.94  4947.4 1754.25  4963.2 1752.86  4963.5 1752.36  4967.9 1752.86
  5024.5 1753.43  5044.5 1755.43  5054.5 1761.97  5064.5 1774.07  5084.5 1804.87
  5094.5 1813.98  5114.5 1827.71  5124.5 1830.52    5152 1846.51  5154.5 1846.51
#Mann= 5 ,-1 , 0
  4363.2     .12       0  4848.6    .035       0  4947.4     .12       0
  4963.2     .05       0  4967.9     .12       0
Bank Sta=4963.2,4967.9
XS Rating Curve= 0 ,0
Exp/Cntr=0.3,0.1

Type RM Length L Ch R = 1 ,2799    ,426,426,426
BEGIN DESCRIPTION:
Stream0134_DS 6.0
END DESCRIPTION:
XS GIS Cut Line= 3
        1999825.       13858125.        2000225.       13857925.
      2000525.03     13857724.98
#Sta/Elev= 30
  4552.5 1875.58  4574.9 1871.44  4611.2 1860.18    4628 1850.83  4678.3 1826.44
    4695 1814.81  4776.1 1775.31  4784.5 1764.43  4812.4 1758.97  4820.8 1754.57
  4833.9 1754.03  4922.6 1753.05  4983.3 1752.79  4983.7 1752.29  4988.1 1752.79
  5035.8 1752.95  5071.8 1755.23  5130.4 1768.23  5166.5 1785.19  5202.5  1807.1
  5208.5  1809.9  5223.6 1822.67  5250.2 1836.09  5259.8  1839.7  5280.6 1845.18
  5301.7 1854.46  5331.7 1863.52  5346.7  1866.8  5357.3  1871.3  5360.3  1871.3
#Mann= 7 ,-1 , 0
  4552.5     .12       0  4833.9    .035       0  4922.6     .12       0
  4983.3     .05       0  4988.1     .12       0  5250.2     .07       0
  5259.8     .12       0
Bank Sta=4983.3,4988.1
XS Rating Curve= 0 ,0
Exp/Cntr=0.3,0.1

Type RM Length L Ch R = 1 ,2373    ,454,454,454
BEGIN DESCRIPTION:
Stream0134_DS 5.0
END DESCRIPTION:
XS GIS Cut Line= 3
      1999824.96     13858174.99        2000175.       13858275.
      2000597.16     13858172.79
#Sta/Elev= 30
  4636.5 1875.44  4667.7 1864.87  4719.7  1835.1  4726.2 1828.36  4750.9 1815.97
  4771.7 1799.65  4792.5 1789.33  4804.2 1779.37  4854.9    1753  4940.5 1745.47
  4983.6 1740.75  4997.9 1735.46  5021.6  1734.7    5022  1734.2  5026.5  1734.7
  5072.8 1738.15  5093.1 1742.51    5124 1754.78  5144.4 1756.14  5165.2  1748.7
  5174.9 1748.94  5216.6 1751.92  5280.1 1766.42  5309.2 1784.58  5316.8 1785.95
    5322 1783.56  5329.8 1786.75  5391.5 1825.85  5426.2 1841.64  5434.9 1843.92
#Mann= 7 ,-1 , 0
  4636.5     .12       0  4940.5    .035       0  5021.6    .035       0
  5026.5    .035       0  5072.8     .12       0  5174.9     .07       0
  5426.2     .12       0
Bank Sta=5021.6,5026.5
XS Rating Curve= 0 ,0
Exp/Cntr=0.3,0.1

Type RM Length L Ch R = 1 ,1919    ,451,451,451
BEGIN DESCRIPTION:
Stream0134_DS 4.0
END DESCRIPTION:
XS GIS Cut Line= 3
      1999725.04     13858525.02        1999925.       13858625.
      2000324.97     13859024.97
#Sta/Elev= 30
  4776.7 1849.04  4779.4 1849.04  4821.4 1826.21  4843.7 1812.22  4860.5 1799.37
  4919.2 1764.46  4941.6 1754.36  4977.9 1743.67  4991.9 1735.46  4997.5 1730.28
  5011.8 1729.44  5012.2 1728.94    5017 1729.44  5018.2 1729.73  5056.8 1737.03
  5141.7 1742.18  5153.3 1744.86  5198.3 1749.78  5212.4 1753.79  5311.4 1758.73
    5368 1765.44  5382.1 1768.53  5396.2 1776.71  5410.4 1780.16  5424.5 1783.08
  5438.7 1781.78  5452.8  1786.6  5481.1 1802.51  5562.4 1832.76  5565.9 1832.76
#Mann= 5 ,-1 , 0
  4776.7     .12       0  5011.8     .05       0    5017     .12       0
  5018.2    .035       0  5153.3     .12       0
Bank Sta=5011.8,5017
XS Rating Curve= 0 ,0
Exp/Cntr=0.3,0.1

Type RM Length L Ch R = 1 ,1468    ,466,466,466
BEGIN DESCRIPTION:
Stream0134_DS 3.0
END DESCRIPTION:
XS GIS Cut Line= 3
      1999575.02       13859025.        1999775.       13859025.
      2000286.94     13859192.42
#Sta/Elev= 30
  4800.4  1844.7  4830.4 1833.64  4850.4 1822.08  4870.4 1805.19  4910.4 1782.24
  4960.4 1749.39  4980.4 1738.94  4995.3 1723.29  4995.7 1722.79  5000.5 1723.29
  5010.9 1724.07  5016.3 1727.75  5054.5 1731.19  5080.1 1738.57  5157.1 1742.03
  5212.8 1743.66  5308.4 1751.29  5366.9 1762.25  5372.1 1761.46  5430.6 1780.97
  5435.9 1781.09  5462.5 1793.54  5467.7 1793.47  5494.3 1805.82  5499.6 1805.73
  5505.4 1810.22  5526.2 1818.67  5531.5 1818.76  5535.4 1823.27    5539 1823.27
#Mann= 5 ,-1 , 0
  4800.4     .12       0  4995.3     .05       0  5000.5     .12       0
  5054.5    .035       0  5157.1     .12       0
Bank Sta=4995.3,5000.5
XS Rating Curve= 0 ,0
Exp/Cntr=0.3,0.1

Type RM Length L Ch R = 1 ,1002    ,559,559,559
BEGIN DESCRIPTION:
Stream0134_DS 2.0
END DESCRIPTION:
XS GIS Cut Line= 3
      1999525.01     13859225.01        1999825.       13859475.
      2000224.99     13859674.99
#Sta/Elev= 30
  4609.6 1844.25  4666.2 1832.91    4773 1789.69  4793.8 1784.45  4851.1 1763.02
  4914.8 1746.91  4943.5 1735.73  4964.3 1731.35  4972.1  1727.1  4978.6 1728.17
  4984.6 1724.51  4987.3 1723.45  5011.4 1721.26  5011.9 1720.76  5016.7 1721.26
  5067.2 1724.95  5081.2 1726.88  5095.1 1731.92  5120.3 1735.27  5203.6 1738.01
  5237.7 1741.46    5260 1747.43  5304.8 1766.77  5343.9 1787.18  5349.5 1787.93
  5388.6 1809.37  5394.2 1810.23  5416.6 1821.67  5433.3 1832.49  5447.3 1838.03
#Mann= 7 ,-1 , 0
  4609.6     .12       0  4984.6    .035       0  4987.3     .12       0
  5011.4     .05       0  5016.7     .12       0  5095.1    .035       0
  5203.6     .12       0
Bank Sta=5011.4,5016.7
XS Rating Curve= 0 ,0
Exp/Cntr=0.3,0.1