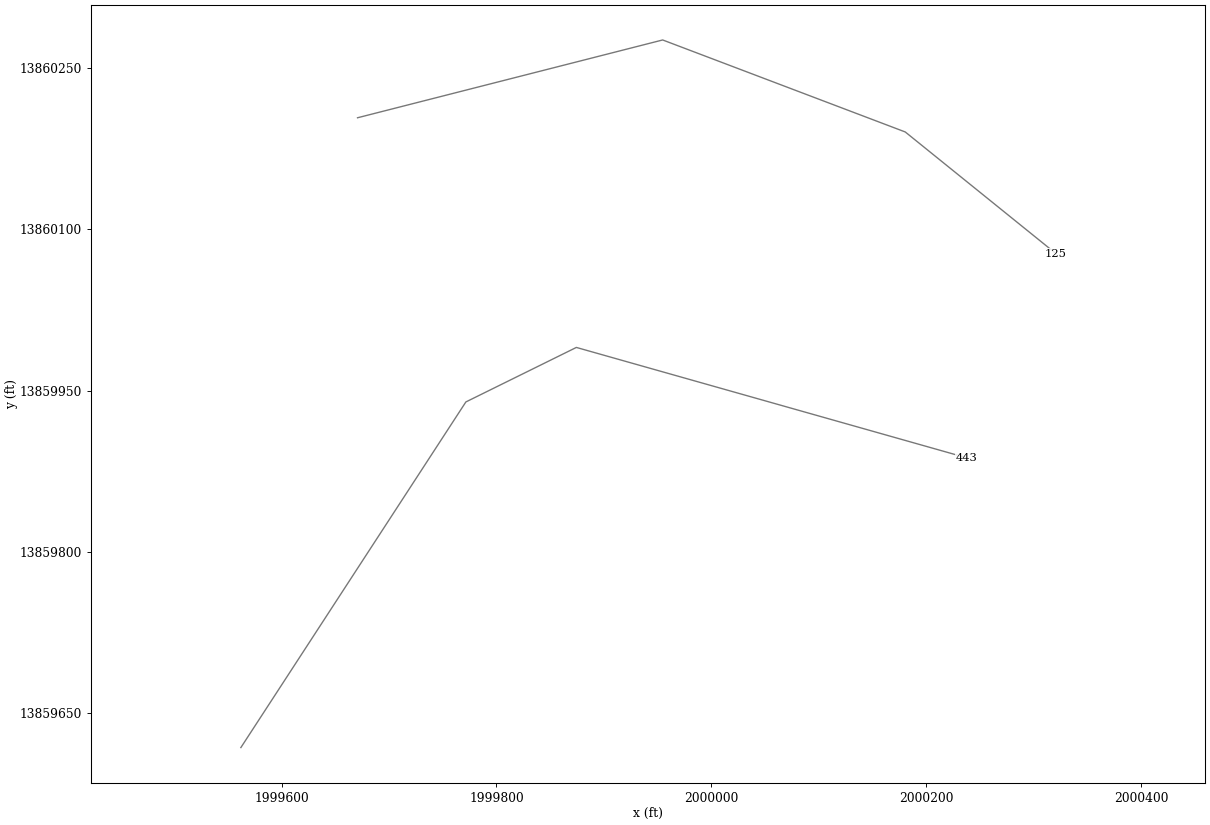
HEC-RAS study Stream0134_DS.prj: Stream0134_DS Base Level Engineering

--- Stream0134_DS.g01 (geometry) --- (continued)

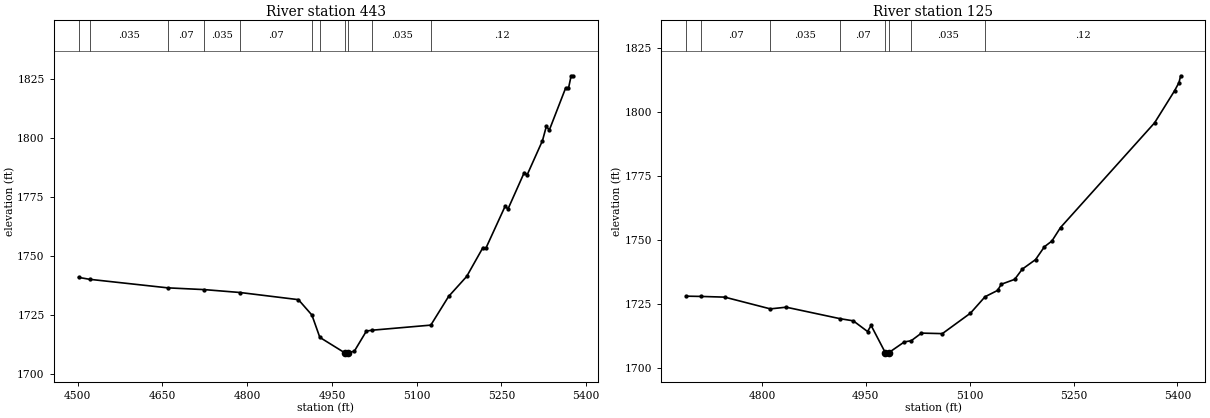
Type RM Length L Ch R = 1 ,443     ,318,318,318
BEGIN DESCRIPTION:
Stream0134_DS 1.0
END DESCRIPTION:
XS GIS Cut Line= 4
       1999562.1     13859617.75      1999771.51     13859939.42
      1999874.34     13859990.16       2000237.6     13859887.44
#Sta/Elev= 30
  4501.5 1740.88  4520.9 1740.07  4659.3 1736.45  4724.3  1735.7  4787.3 1734.48
  4890.7 1731.45  4914.6 1724.93  4928.6 1715.48  4972.3 1709.01  4972.7 1708.51
  4977.6 1709.01  4989.6 1709.59  5011.1 1718.16  5021.8 1718.53  5125.1 1720.67
  5156.6 1732.81  5188.6 1741.27  5217.4  1753.5  5222.6 1753.23  5256.6 1770.96
  5261.8 1769.86  5290.5 1785.25  5295.7  1784.3  5322.8 1798.77  5329.7 1804.87
  5334.9 1803.24  5363.6 1820.93  5368.8  1820.9  5373.6 1826.24  5377.5 1826.24
#Mann= 11 ,-1 , 0
  4501.5     .07       0  4520.9    .035       0  4659.3     .07       0
  4724.3    .035       0  4787.3     .07       0  4914.6     .12       0
  4928.6     .07       0  4972.3     .05       0  4977.6     .07       0
  5021.8    .035       0  5125.1     .12       0
Bank Sta=4972.3,4977.6
XS Rating Curve= 0 ,0
Exp/Cntr=0.3,0.1

Type RM Length L Ch R = 1 ,125     ,0,0,0
BEGIN DESCRIPTION:
Stream0134_DS 0.0
END DESCRIPTION:
XS GIS Cut Line= 4
      1999670.68     13860203.91      1999954.67     13860276.32
      2000180.43      13860190.7      2000320.71     13860077.48
#Sta/Elev= 30
    4690 1727.97  4711.2 1727.87  4746.1 1727.59    4812    1723  4834.9 1723.66
  4912.9 1719.16  4931.8 1718.33  4952.4 1714.16  4957.6 1716.51    4978 1705.93
  4978.4 1705.43  4983.3 1705.93  5005.5 1710.07  5015.6 1710.57  5030.3 1713.53
  5060.5 1713.33  5101.1 1721.33  5122.2 1727.75  5140.2  1730.2  5145.6 1732.62
    5165 1734.54  5175.9 1738.52  5195.1 1742.25    5208  1747.3  5218.7  1749.5
  5231.2 1754.79  5367.1 1795.71  5395.9 1808.21  5402.3 1811.42  5404.8  1814.1
#Mann= 8 ,-1 , 0
    4690    .035       0  4711.2     .07       0    4812    .035       0
  4912.9     .07       0    4978     .05       0  4983.3     .07       0
  5015.6    .035       0  5122.2     .12       0
Bank Sta=4978,4983.3
XS Rating Curve= 0 ,0
Exp/Cntr=0.3,0.1

Chan Stop Cuts=-1
Use User Specified Reach Order=0
Composite Channel Slope=5