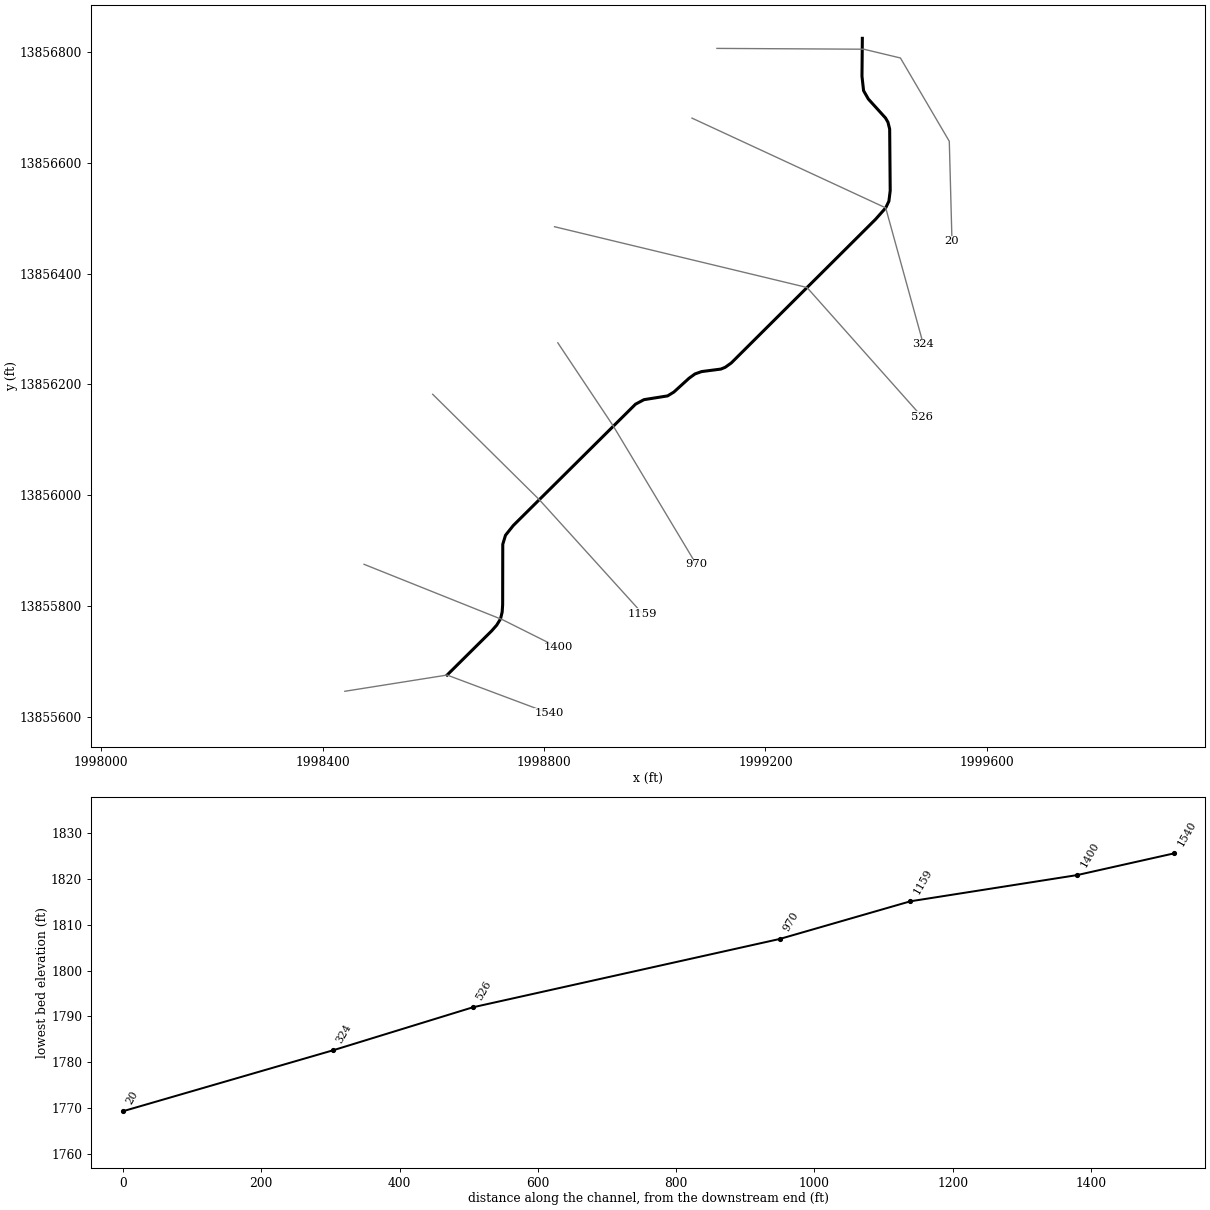
--- Stream0135_DS.prj (project) ---

Proj Title=Stream0135_DS Base Level Engineering
Current Plan=p01
Default Exp/Contr=0.3,0.1
English Units
Geom File=g01
Flow File=f01
Plan File=p01
Y Axis Title=Elevation
X Axis Title(PF)=Main Channel Distance
X Axis Title(XS)=Station
BEGIN DESCRIPTION:
Stream0135_DS
END DESCRIPTION:
DSS Export Rating Curves= 0
DSS Export Rating Curve Sorted= 0
DSS Export Volume Flow Curves= 0
DXF OffsetX= 0
DXF OffsetY= 0
DXF ScaleX= 1
DXF ScaleY= 10

--- Stream0135_DS.p01 (plan) ---

Plan Title=Multiple Run
Short Identifier=Multiple
Geom File=g01
Flow File=f01
Subcritical Flow
K Sum by GR= 0
Std Step Tol= 0.01
Critical Tol= 0.01
Num of Std Step Trials= 20
Max Error Tol= 0.3
Flow Tol Ratio= 0.001
Split Flow NTrial= 30
Split Flow Tol= 0.02
Split Flow Ratio= 0.02
Log Output Level= 0
Friction Slope Method= 1
Unsteady Friction Slope Method= 2
Unsteady Bridges Friction Slope Method= 1
Parabolic Critical Depth
Global Vel Dist=  1 , 1 , 1
Global Log Level= 0
CheckData=True
Encroach Param= -1, 0, 0, 0
BEGIN DESCRIPTION:
Multiple Run
END DESCRIPTION:

--- Stream0135_DS.f01 (steady flow) ---

Flow Title=Multiple
Number of Profiles=7
Profile Names=10-year,25-year,50-year,1pct_min,100-year,1pct_plu,500-year
River Rch & RM= Stream0135_DS,Reach-1,1540
     334     528     701     454     906    1808    1492
River Rch & RM= Stream0135_DS,Reach-1,20
    1227    2091    2916    1970    3931    7843    7068
Boundary for River Rch & Prof#=Stream0135_DS,Reach-1,1
Up Type=0
Dn Type=3
Dn Slope=0.005
Boundary for River Rch & Prof#=Stream0135_DS,Reach-1,2
Up Type=0
Dn Type=3
Dn Slope=0.005
Boundary for River Rch & Prof#=Stream0135_DS,Reach-1,3
Up Type=0
Dn Type=3
Dn Slope=0.005
Boundary for River Rch & Prof#=Stream0135_DS,Reach-1,4
Up Type=0
Dn Type=3
Dn Slope=0.005
Boundary for River Rch & Prof#=Stream0135_DS,Reach-1,5
Up Type=0
Dn Type=3
Dn Slope=0.005
Boundary for River Rch & Prof#=Stream0135_DS,Reach-1,6
Up Type=0
Dn Type=3
Dn Slope=0.005
Boundary for River Rch & Prof#=Stream0135_DS,Reach-1,7
Up Type=0
Dn Type=3
Dn Slope=0.005

--- Stream0135_DS.g01 (geometry) ---

Geom Title=Existing Conditions
Program Version=4.10

River Reach=Stream0135_DS   ,Reach-1
Reach XY= 30
        1998625.       13855675.       1998705.5     13855754.79
      1998714.61     13855765.16      1998721.51     13855776.45
      1998724.47     13855788.86      1998725.34     13855802.13
      1998725.55     13855911.14      1998730.47     13855927.45
      1998744.61     13855945.16      1998965.32     13856164.24
      1998980.63     13856172.39      1999023.26     13856179.19
      1999034.55      13856186.1      1999061.94     13856211.02
      1999072.81      13856218.9      1999084.86     13856223.14
      1999119.37     13856227.61       1999127.3     13856230.83
      1999138.21     13856238.62      1999398.84     13856498.13
      1999417.19     13856518.81      1999422.95     13856530.86
      1999425.32     13856549.89      1999424.35     13856661.08
      1999421.26     13856673.44      1999416.91     13856681.07
      1999385.86     13856715.35      1999377.22     13856730.47
      1999374.33     13856756.54        1999375.       13856825.

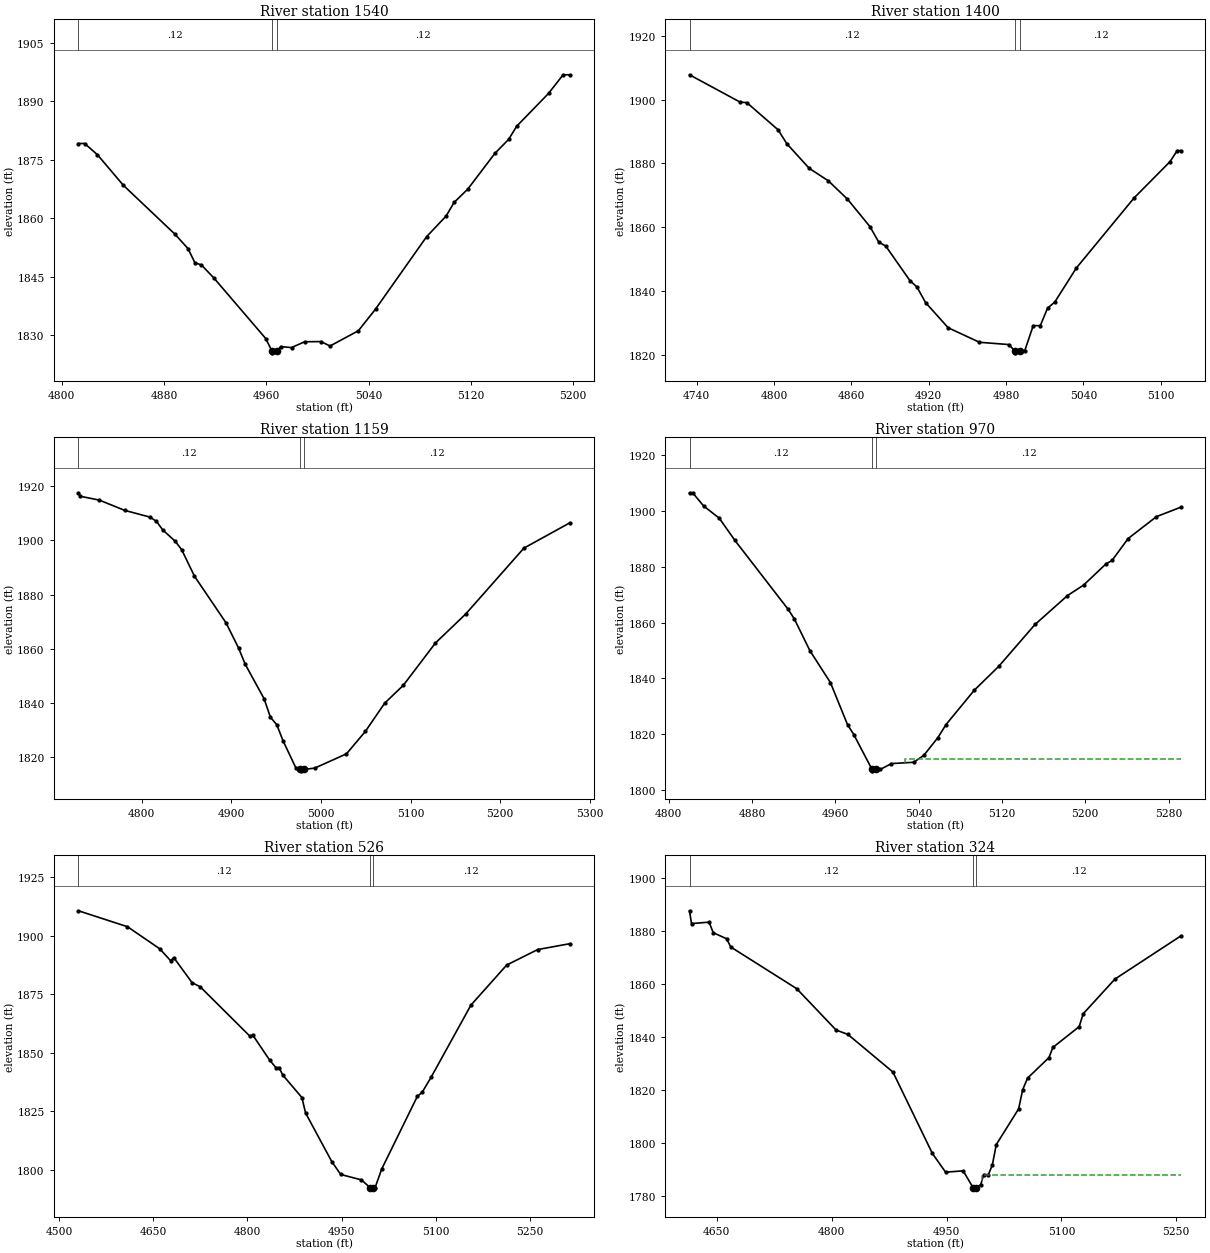
Type RM Length L Ch R = 1 ,1540    ,140,140,140
BEGIN DESCRIPTION:
Stream0135_DS 6.0
END DESCRIPTION:
XS GIS Cut Line= 3
      1998440.32     13855645.67        1998625.       13855675.
      1998809.75     13855605.77
#Sta/Elev= 30
    4813 1879.16  4817.9 1879.16  4827.9 1876.27  4848.1 1868.46  4888.6 1855.88
  4898.7 1852.22  4904.1  1848.6  4909.2 1848.02    4919 1844.66  4959.5 1829.16
  4964.3 1825.99  4964.6 1825.49  4968.3 1825.99  4971.4 1827.09  4979.7 1826.83
  4989.9 1828.33  5002.7 1828.38  5009.8 1827.24    5032 1831.16  5045.4 1836.71
  5085.4  1855.3  5100.6 1860.56  5106.8 1864.04  5117.5 1867.45  5138.8 1876.65
  5149.5 1880.22  5155.8 1883.59  5180.7    1892  5192.1 1896.78  5197.3 1896.78
#Mann= 3 ,-1 , 0
    4813     .12       0  4964.3     .05       0  4968.3     .12       0
Bank Sta=4964.3,4968.3
XS Rating Curve= 0 ,0
Exp/Cntr=0.3,0.1

Type RM Length L Ch R = 1 ,1400    ,241,241,241
BEGIN DESCRIPTION:
Stream0135_DS 5.0
END DESCRIPTION:
XS GIS Cut Line= 3
      1998474.98     13855875.01        1998725.       13855775.
      1998825.01     13855724.99
#Sta/Elev= 30
  4734.5 1907.74  4773.6 1899.22    4779 1899.01  4803.2 1890.53  4809.9 1886.21
  4827.4 1878.46  4842.2 1874.57    4857 1868.85  4874.5 1860.23  4881.3 1855.38
  4886.7 1854.18  4905.5 1843.34  4910.9 1841.38  4917.6 1836.49  4935.1 1828.62
  4959.4 1824.07  4982.2 1823.36    4987 1821.27  4987.2 1820.77    4991 1821.27
  4994.4 1821.29  5001.1 1829.28  5006.6 1829.28  5012.2 1834.74  5017.8 1836.64
  5034.5 1847.28  5079.3 1869.21  5107.2 1880.57  5112.8 1884.03  5115.6 1884.03
#Mann= 3 ,-1 , 0
  4734.5     .12       0    4987     .05       0    4991     .12       0
Bank Sta=4987,4991
XS Rating Curve= 0 ,0
Exp/Cntr=0.3,0.1

Type RM Length L Ch R = 1 ,1159    ,189,189,189
BEGIN DESCRIPTION:
Stream0135_DS 4.0
END DESCRIPTION:
XS GIS Cut Line= 3
      1998598.98     13856182.09      1998791.57     13855991.71
      1998977.92     13855785.96
#Sta/Elev= 30
  4729.2 1917.57  4731.4 1916.28  4752.6 1914.86  4780.9 1911.08  4809.1  1908.6
  4816.3 1907.04  4823.3 1903.88  4837.4 1899.65  4844.5 1896.56  4858.7 1886.83
    4894 1869.61  4908.1 1860.25  4915.3  1854.4  4936.4 1841.67  4943.5 1834.85
  4950.6 1832.06  4957.7 1826.06  4971.8 1816.24  4976.9 1815.57  4977.1 1815.07
  4980.9 1815.57    4993 1816.09  5028.4 1821.34  5049.5 1829.62    5071    1840
  5091.9 1846.63  5127.7  1862.2  5161.5 1872.89  5226.4 1897.16  5277.6 1906.48
#Mann= 3 ,-1 , 0
  4729.2     .12       0  4976.9     .05       0  4980.9     .12       0
Bank Sta=4976.9,4980.9
XS Rating Curve= 0 ,0
Exp/Cntr=0.3,0.1

Type RM Length L Ch R = 1 ,970     ,444,444,444
BEGIN DESCRIPTION:
Stream0135_DS 3.0
END DESCRIPTION:
XS GIS Cut Line= 3
      1998824.98     13856275.04        1998925.       13856125.
      1999075.02     13855874.97
#Sta/Elev= 30
  4819.9 1906.62  4822.9 1906.62  4833.5 1901.87  4848.5 1897.49  4863.5 1889.53
  4914.6 1864.83  4920.6 1861.35  4935.6 1849.92  4955.2 1838.56  4971.7  1823.4
  4977.7 1819.87  4995.2 1807.37  4995.5 1806.87  4999.2 1807.37  5003.1 1807.37
  5013.8 1809.47  5035.2 1809.94  5044.9 1812.41  5058.5 1818.82  5066.3 1823.49
  5093.5 1835.83  5116.8 1844.31  5151.8  1859.4  5182.9 1869.73  5198.5 1873.54
  5219.9 1881.11  5225.7 1882.34  5241.2 1890.21  5268.4 1898.07  5291.8 1901.45
#Mann= 3 ,-1 , 0
  4819.9     .12       0  4995.2     .05       0  4999.2     .12       0
#XS Ineff= 2 , 0
       0                 5027.05       0 1811.04
Permanent Ineff=
       F       F
Bank Sta=4995.2,4999.2
XS Rating Curve= 0 ,0
Exp/Cntr=0.3,0.1

Type RM Length L Ch R = 1 ,526     ,202,202,202
BEGIN DESCRIPTION:
Stream0135_DS 2.0
END DESCRIPTION:
XS GIS Cut Line= 3
      1998819.04     13856484.75        1999275.       13856375.
      1999483.16     13856140.96
#Sta/Elev= 30
    4531 1910.63  4609.1 1903.83  4660.6 1894.38  4677.7 1889.34  4682.9 1890.63
    4712 1879.93  4724.8 1878.22  4803.6 1857.23  4808.7 1857.54  4835.4 1846.93
  4845.5 1843.66  4850.6  1843.7    4856 1840.65  4886.8 1830.94  4892.6 1824.37
  4934.5 1803.55  4948.6 1798.12  4981.6 1795.81  4995.4 1792.49  4995.7 1791.99
  4999.4 1792.49  5003.3 1792.49  5013.8 1800.43  5070.6 1831.47  5078.2 1833.17
  5092.4 1839.57  5155.9 1870.39  5212.8 1887.48  5262.1 1894.08  5313.2 1896.58
#Mann= 3 ,-1 , 0
    4531     .12       0  4995.4     .05       0  4999.4     .12       0
Bank Sta=4995.4,4999.4
XS Rating Curve= 0 ,0
Exp/Cntr=0.3,0.1

Type RM Length L Ch R = 1 ,324     ,304,304,304
BEGIN DESCRIPTION:
Stream0135_DS 1.0
END DESCRIPTION:
XS GIS Cut Line= 3
      1999067.32      13856680.9      1999417.19     13856518.81
      1999485.28     13856272.03
#Sta/Elev= 30
  4614.4 1887.54    4617 1882.71  4639.9 1883.25  4645.4 1879.28  4662.8 1876.98
  4668.3 1873.87  4754.4 1858.15  4805.8 1842.55  4821.2  1840.9    4880 1826.71
  4931.5 1796.01  4948.8 1788.92  4971.7 1789.43  4984.6 1783.14  4984.8 1782.64
  4988.6 1783.14  4994.6 1784.17  4998.6 1787.97  5004.6 1787.97  5009.8 1791.58
    5015 1799.35  5044.2 1812.82  5049.4 1819.99  5055.8  1824.4  5083.8 1832.16
  5088.9 1835.99  5123.2 1843.82  5128.5 1848.68  5169.9 1861.77    5256 1878.05
#Mann= 3 ,-1 , 0
  4614.4     .12       0  4984.6     .05       0  4988.6     .12       0
#XS Ineff= 2 , 0
       0                 4996.03       0 1788.03
Permanent Ineff=
       F       F
Bank Sta=4984.6,4988.6
XS Rating Curve= 0 ,0
Exp/Cntr=0.3,0.1

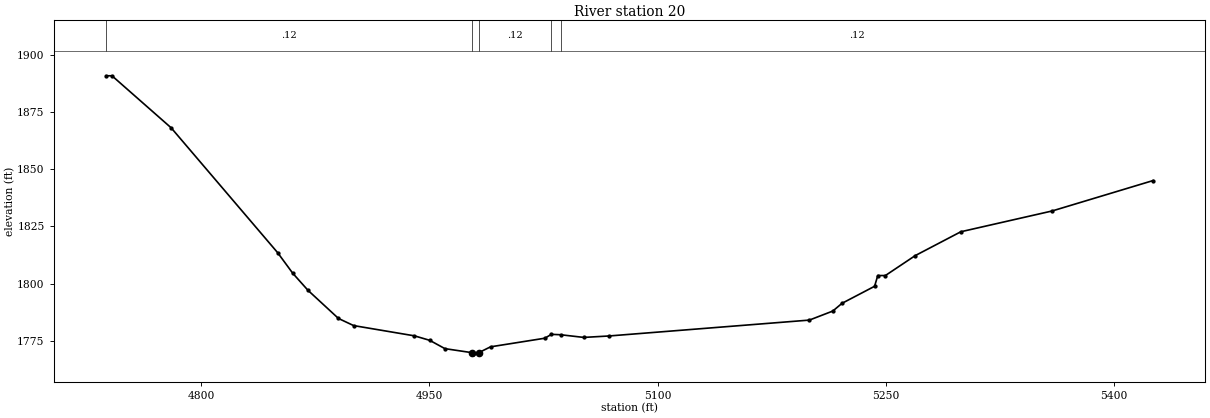
Type RM Length L Ch R = 1 ,20      ,0,0,0
BEGIN DESCRIPTION:
Stream0135_DS 0.0
END DESCRIPTION:
XS GIS Cut Line= 5
       1999112.3     13856806.82      1999377.68     13856805.36
      1999443.77     13856789.51      1999532.05     13856639.02
       1999536.9     13856458.61
#Sta/Elev= 30
  4737.5 1890.75  4741.3 1890.75  4780.2 1868.04  4850.2 1813.55  4860.2 1804.51
  4870.2 1797.08  4890.2 1784.82  4900.2  1781.7  4940.2 1777.22  4950.2 1775.27
  4960.2 1771.64  4978.1 1769.87  4978.4 1769.37  4982.4 1769.87  4990.2 1772.43
  5025.9 1776.19  5030.2 1777.88  5036.2 1777.71  5051.5 1776.54  5067.9 1777.16
  5199.8  1784.1  5215.2 1788.04  5221.3 1791.43  5242.7 1798.86  5244.8 1803.55
  5249.8 1803.55  5269.4 1812.24  5299.4 1822.66  5359.4 1831.73  5425.8 1845.01
#Mann= 5 ,-1 , 0
  4737.5     .12       0  4978.1     .05       0  4982.4     .12       0
  5030.2    .035       0  5036.2     .12       0
Bank Sta=4978.1,4982.4
XS Rating Curve= 0 ,0
Exp/Cntr=0.3,0.1

Chan Stop Cuts=-1
Use User Specified Reach Order=0
Composite Channel Slope=5