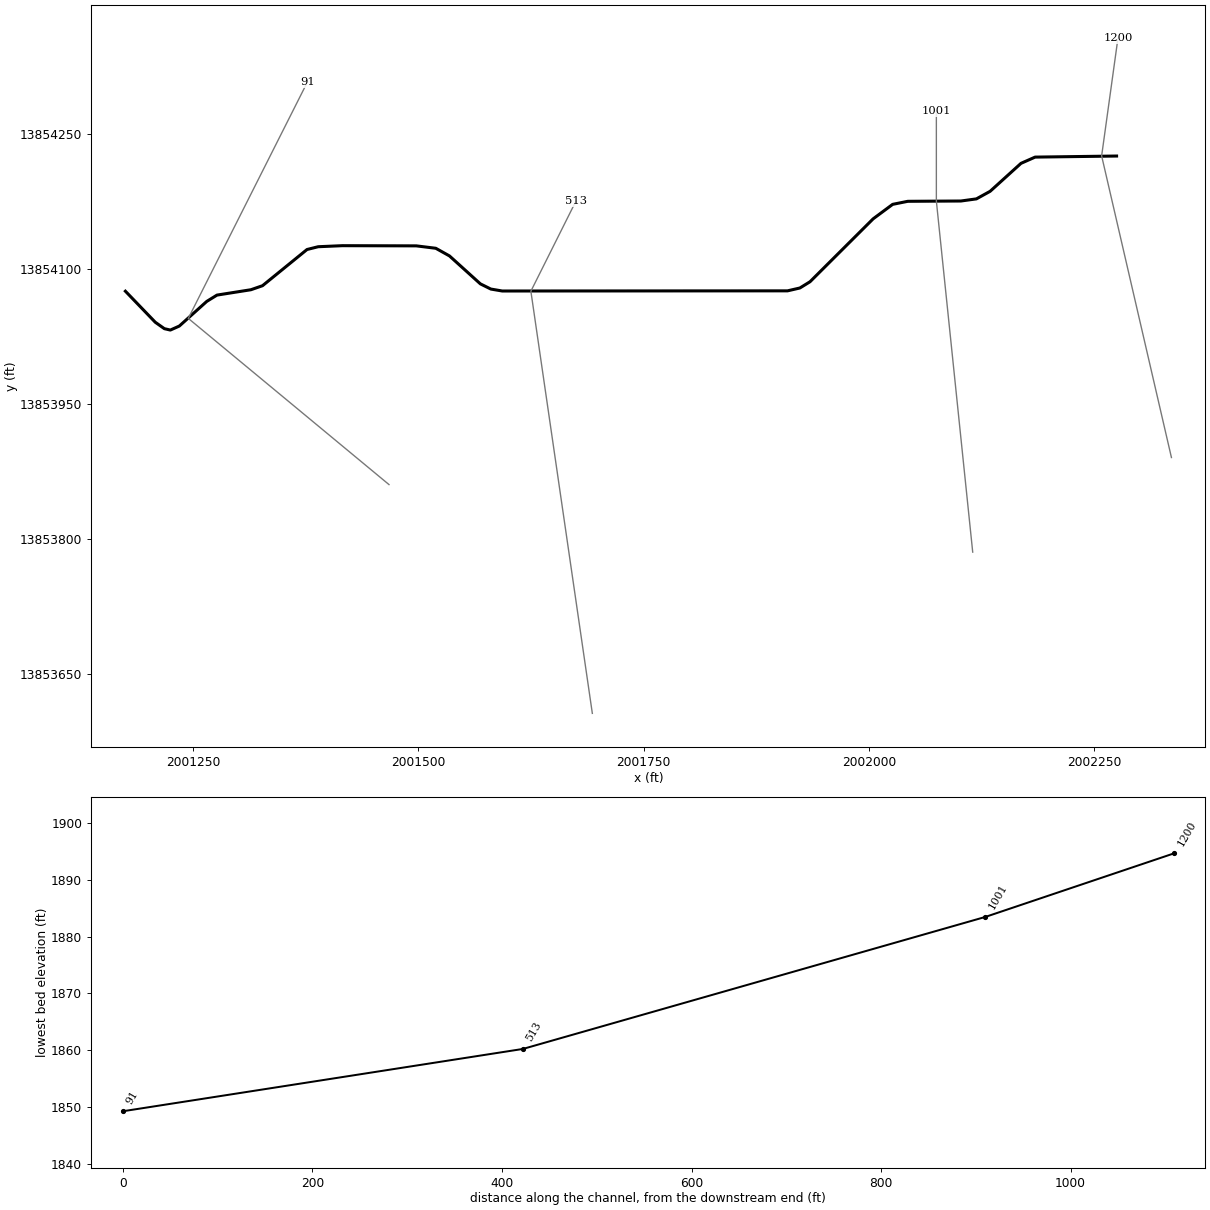
--- Stream0136_DS.prj (project) ---

Proj Title=Stream0136_DS Base Level Engineering
Current Plan=p01
Default Exp/Contr=0.3,0.1
English Units
Geom File=g01
Flow File=f01
Plan File=p01
Y Axis Title=Elevation
X Axis Title(PF)=Main Channel Distance
X Axis Title(XS)=Station
BEGIN DESCRIPTION:
Stream0136_DS
END DESCRIPTION:
DSS Export Rating Curves= 0
DSS Export Rating Curve Sorted= 0
DSS Export Volume Flow Curves= 0
DXF OffsetX= 0
DXF OffsetY= 0
DXF ScaleX= 1
DXF ScaleY= 10

--- Stream0136_DS.p01 (plan) ---

Plan Title=Multiple Run
Short Identifier=Multiple
Geom File=g01
Flow File=f01
Subcritical Flow
K Sum by GR= 0
Std Step Tol= 0.01
Critical Tol= 0.01
Num of Std Step Trials= 20
Max Error Tol= 0.3
Flow Tol Ratio= 0.001
Split Flow NTrial= 30
Split Flow Tol= 0.02
Split Flow Ratio= 0.02
Log Output Level= 0
Friction Slope Method= 1
Unsteady Friction Slope Method= 2
Unsteady Bridges Friction Slope Method= 1
Parabolic Critical Depth
Global Vel Dist=  1 , 1 , 1
Global Log Level= 0
CheckData=True
Encroach Param= -1, 0, 0, 0
BEGIN DESCRIPTION:
Multiple Run
END DESCRIPTION:

--- Stream0136_DS.f01 (steady flow) ---

Flow Title=Multiple
Number of Profiles=7
Profile Names=10-year,25-year,50-year,1pct_min,100-year,1pct_plu,500-year
River Rch & RM= Stream0136_DS,Reach-1,1200
     325     511     676     436     870    1736    1420
Boundary for River Rch & Prof#=Stream0136_DS,Reach-1,1
Up Type=0
Dn Type=3
Dn Slope=0.005
Boundary for River Rch & Prof#=Stream0136_DS,Reach-1,2
Up Type=0
Dn Type=3
Dn Slope=0.005
Boundary for River Rch & Prof#=Stream0136_DS,Reach-1,3
Up Type=0
Dn Type=3
Dn Slope=0.005
Boundary for River Rch & Prof#=Stream0136_DS,Reach-1,4
Up Type=0
Dn Type=3
Dn Slope=0.005
Boundary for River Rch & Prof#=Stream0136_DS,Reach-1,5
Up Type=0
Dn Type=3
Dn Slope=0.005
Boundary for River Rch & Prof#=Stream0136_DS,Reach-1,6
Up Type=0
Dn Type=3
Dn Slope=0.005
Boundary for River Rch & Prof#=Stream0136_DS,Reach-1,7
Up Type=0
Dn Type=3
Dn Slope=0.005

--- Stream0136_DS.g01 (geometry) ---

Geom Title=Existing Conditions
Program Version=4.10

River Reach=Stream0136_DS   ,Reach-1
Reach XY= 30
        2002275.       13854225.      2002184.58     13854223.81
      2002168.93     13854216.89      2002134.65     13854185.84
      2002119.44     13854177.45      2002102.23     13854175.09
      2002043.29     13854174.75       2002026.5     13854171.38
      2002004.86     13854155.33      2001934.79      13854085.5
      2001923.53     13854078.55      2001909.84     13854075.39
      2001593.27     13854075.21      2001580.53     13854077.38
      2001568.94     13854083.14      2001534.64     13854114.15
      2001519.47     13854122.63      2001497.83     13854125.31
      2001415.74     13854125.51      2001388.92     13854124.35
      2001376.56     13854121.26      2001327.17     13854081.09
      2001314.29     13854076.62      2001276.62     13854070.67
      2001265.29     13854063.67      2001234.83      13854036.3
      2001224.88     13854031.87      2001218.24     13854033.41
      2001208.17     13854040.53        2001175.       13854075.

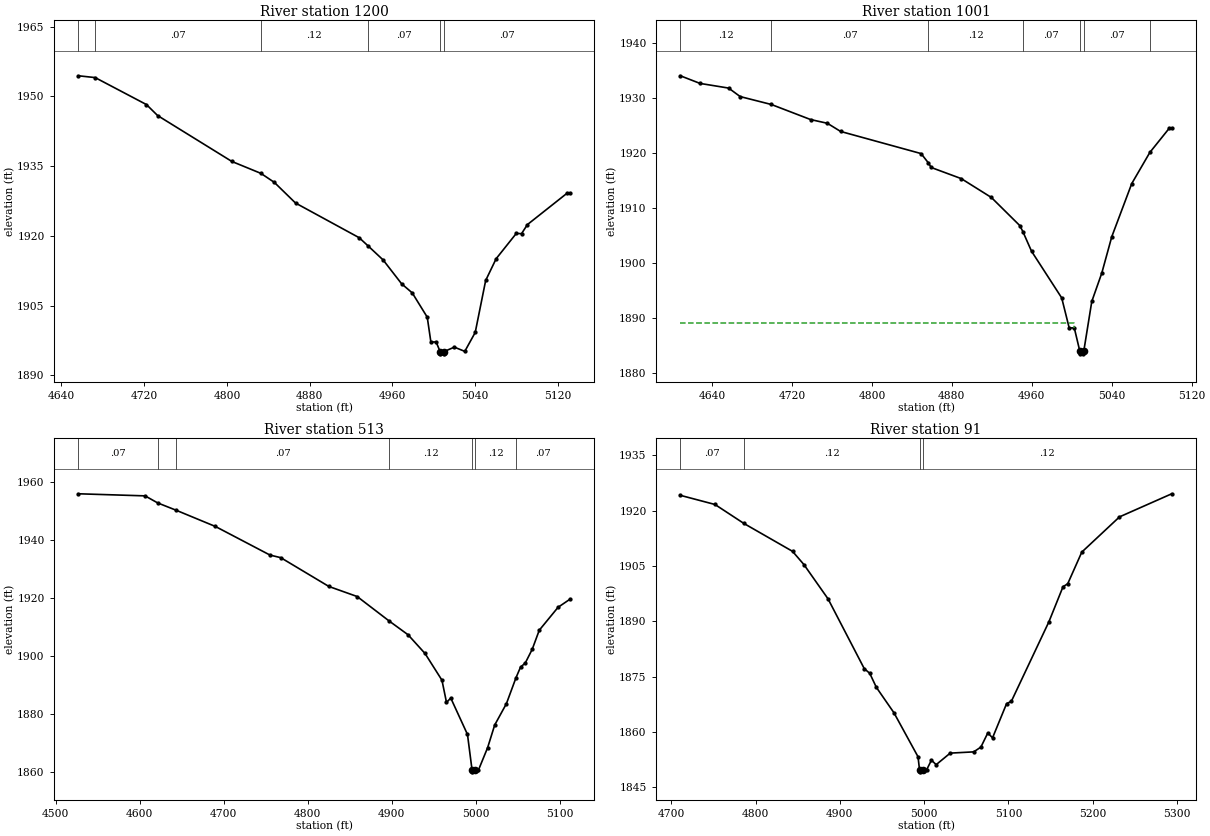
Type RM Length L Ch R = 1 ,1200    ,199,199,199
BEGIN DESCRIPTION:
Stream0136_DS 3.0
END DESCRIPTION:
XS GIS Cut Line= 3
      2002335.88     13853890.41      2002258.42     13854225.16
       2002276.5     13854355.62
#Sta/Elev= 30
  4656.4 1954.42  4672.6 1954.03  4722.2 1948.23    4733 1945.87  4804.8    1936
  4832.9 1933.44  4845.9  1931.5  4866.4 1927.06    4928  1919.6  4936.3  1917.9
  4951.1 1914.83    4969  1909.7  4979.3 1907.74  4993.8 1902.52  4997.3 1897.19
  5002.4 1897.19  5006.2 1895.14  5006.4 1894.64  5009.9 1894.64  5010.2 1895.14
    5020 1896.08  5030.1 1895.17  5040.2 1899.24  5050.3 1910.41  5060.4 1915.08
  5079.9 1920.52    5085 1920.48  5090.7 1922.43  5128.9 1929.15  5131.7 1929.15
#Mann= 6 ,-1 , 0
  4656.4     .12       0  4672.6     .07       0  4832.9     .12       0
  4936.3     .07       0  5006.2     .05       0  5010.2     .07       0
Bank Sta=5006.2,5010.2
XS Rating Curve= 0 ,0
Exp/Cntr=0.3,0.1

Type RM Length L Ch R = 1 ,1001    ,488,488,488
BEGIN DESCRIPTION:
Stream0136_DS 2.0
END DESCRIPTION:
XS GIS Cut Line= 3
      2002115.34     13853785.43        2002075.       13854175.
        2002075.     13854275.05
#Sta/Elev= 30
  4608.3 1934.09    4628  1932.7  4656.6 1931.85  4668.2  1930.3  4699.4 1928.86
  4738.6 1926.12  4755.4 1925.44  4768.7 1923.95  4849.2 1919.92  4856.6  1918.2
  4859.3 1917.39  4889.4 1915.36  4919.5 1911.93    4948  1906.8    4951 1905.73
  4959.7 1902.14  4989.9 1893.64  4997.4 1888.17  5002.5 1888.17    5008 1883.95
  5008.2 1883.45  5011.7 1883.45    5012 1883.95    5020 1892.99    5030 1898.15
    5040 1904.78    5060 1914.46  5078.1 1920.13  5097.5 1924.53    5100 1924.53
#Mann= 7 ,-1 , 0
  4608.3     .12       0  4699.4     .07       0  4856.6     .12       0
    4951     .07       0    5008     .05       0    5012     .07       0
  5078.1     .07       0
#XS Ineff= 2 , 0
       0  5002.5 1888.98               0
Permanent Ineff=
       F       F
Bank Sta=5008,5012
XS Rating Curve= 0 ,0
Exp/Cntr=0.3,0.1

Type RM Length L Ch R = 1 ,513     ,422,422,422
BEGIN DESCRIPTION:
Stream0136_DS 1.0
END DESCRIPTION:
XS GIS Cut Line= 3
       2001693.2     13853606.47        2001625.       13854075.
      2001675.01     13854175.03
#Sta/Elev= 30
  4526.9    1956  4606.3 1955.28  4621.3 1952.85  4643.7 1950.28  4690.1 1944.73
  4755.1 1934.88  4767.9 1933.99  4825.2 1924.07  4858.9  1920.6  4897.1 1912.15
  4919.5 1907.43  4939.7 1900.99  4959.9 1891.77  4965.3 1884.12  4970.4 1885.62
  4990.3 1873.08  4995.8  1860.7  4996.1  1860.2  4999.8  1860.7  5003.2  1860.7
  5014.3 1868.53  5022.7 1876.32  5036.7 1883.71  5048.1 1892.64  5053.5 1896.28
  5059.1 1897.68  5067.4 1902.41  5075.8 1908.99  5098.2 1916.89  5112.2 1919.64
#Mann= 7 ,-1 , 0
  4526.9     .07       0  4621.3     .12       0  4643.7     .07       0
  4897.1     .12       0  4995.8     .05       0  4999.8     .12       0
  5048.1     .07       0
Bank Sta=4995.8,4999.8
XS Rating Curve= 0 ,0
Exp/Cntr=0.3,0.1

Type RM Length L Ch R = 1 ,91      ,0,0,0
BEGIN DESCRIPTION:
Stream0136_DS 0.0
END DESCRIPTION:
XS GIS Cut Line= 3
      2001467.54     13853860.38       2001244.8     13854044.83
      2001377.02     13854307.19
#Sta/Elev= 30
  4710.8 1924.13  4751.9 1921.65  4786.3  1916.5  4843.9 1908.96  4857.4 1905.38
    4886  1896.1    4929 1877.19  4935.5 1875.92  4943.4  1872.1  4964.2 1865.24
  4992.8 1853.31  4994.6 1849.73  4994.9 1849.23  4998.6 1849.73  5002.9 1849.73
  5008.7  1852.4  5014.3 1851.17    5031  1854.3  5058.9 1854.64  5067.4 1855.94
  5075.6 1859.77  5081.2 1858.44  5097.9 1867.72  5103.5 1868.32  5148.1 1889.89
  5164.8 1899.37  5170.4 1900.18  5187.1 1908.75  5231.8 1918.29  5293.8 1924.55
#Mann= 4 ,-1 , 0
  4710.8     .07       0  4786.3     .12       0  4994.6     .05       0
  4998.6     .12       0
Bank Sta=4994.6,4998.6
XS Rating Curve= 0 ,0
Exp/Cntr=0.3,0.1

Chan Stop Cuts=-1
Use User Specified Reach Order=0
Composite Channel Slope=5