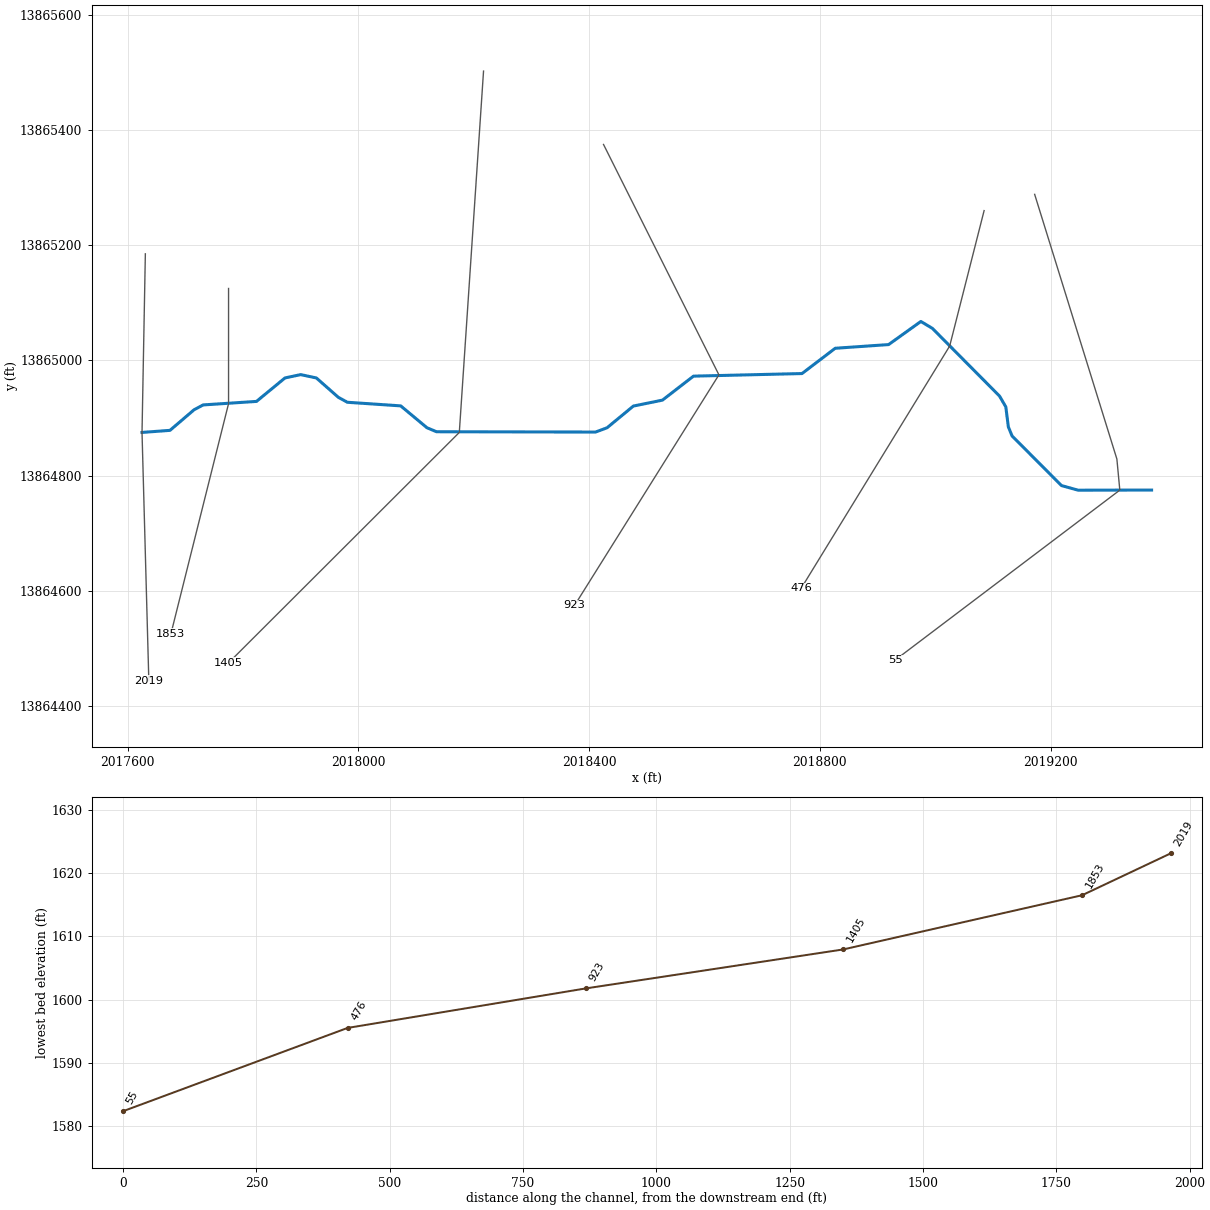
--- Stream0137_DS.prj (project) ---

Proj Title=Stream0137_DS Base Level Engineering
Current Plan=p01
Default Exp/Contr=0.3,0.1
English Units
Geom File=g01
Flow File=f01
Plan File=p01
BEGIN DESCRIPTION:
Stream0137_DS
END DESCRIPTION:

--- Stream0137_DS.p01 (plan) ---

Plan Title=Multiple Run
Short Identifier=Multiple
Geom File=g01
Flow File=f01
Subcritical Flow
K Sum by GR= 0
Std Step Tol= 0.01
Critical Tol= 0.01
Num of Std Step Trials= 20
Max Error Tol= 0.3
Flow Tol Ratio= 0.001
Split Flow NTrial= 30
Split Flow Tol= 0.02
Split Flow Ratio= 0.02
Log Output Level= 0
Friction Slope Method= 1
Unsteady Friction Slope Method= 2
Unsteady Bridges Friction Slope Method= 1
Parabolic Critical Depth
Global Vel Dist=  1 , 1 , 1
Global Log Level= 0
CheckData=True
Encroach Param= -1, 0, 0, 0
BEGIN DESCRIPTION:
Multiple Run
END DESCRIPTION:

--- Stream0137_DS.f01 (steady flow) ---

Flow Title=Multiple
Number of Profiles=7
Profile Names=10-year,25-year,50-year,1pct_min,100-year,1pct_plu,500-year
River Rch & RM= Stream0137_DS,Reach-1,2019
    1307    2254    3171    2163    4316    8611    7907
River Rch & RM= Stream0137_DS,Reach-1,1853
    1477    2564    3623    2480    4948    9872    9132
Boundary for River Rch & Prof#=Stream0137_DS,Reach-1,1
Up Type=0
Dn Type=3
Dn Slope=0.005
Boundary for River Rch & Prof#=Stream0137_DS,Reach-1,2
Up Type=0
Dn Type=3
Dn Slope=0.005
Boundary for River Rch & Prof#=Stream0137_DS,Reach-1,3
Up Type=0
Dn Type=3
Dn Slope=0.005
Boundary for River Rch & Prof#=Stream0137_DS,Reach-1,4
Up Type=0
Dn Type=3
Dn Slope=0.005
Boundary for River Rch & Prof#=Stream0137_DS,Reach-1,5
Up Type=0
Dn Type=3
Dn Slope=0.005
Boundary for River Rch & Prof#=Stream0137_DS,Reach-1,6
Up Type=0
Dn Type=3
Dn Slope=0.005
Boundary for River Rch & Prof#=Stream0137_DS,Reach-1,7
Up Type=0
Dn Type=3
Dn Slope=0.005

--- Stream0137_DS.g01 (geometry) ---

Geom Title=Existing Conditions

River Reach=Stream0137_DS,Reach-1
Reach XY= 30
      2017625.00     13864875.00      2017673.49     13864878.64
      2017715.25     13864914.39      2017730.92     13864922.78
      2017823.42     13864928.88      2017872.82     13864969.63
      2017900.00     13864975.40      2017927.18     13864969.63
      2017965.35     13864935.95      2017980.97     13864927.38
      2018073.40     13864921.14      2018118.94     13864883.14
      2018135.50     13864876.22      2018411.09     13864875.67
      2018431.08     13864883.09      2018476.74     13864920.81
      2018527.18     13864931.12      2018580.93     13864972.76
      2018769.06     13864977.26      2018826.60     13865021.15
      2018919.11     13865027.56      2018975.10     13865067.69
      2018995.04     13865055.71      2019111.37     13864938.21
      2019122.35     13864919.36      2019126.70     13864884.79
      2019133.15     13864868.93      2019218.78     13864782.78
      2019247.61     13864774.72      2019375.00     13864775.00

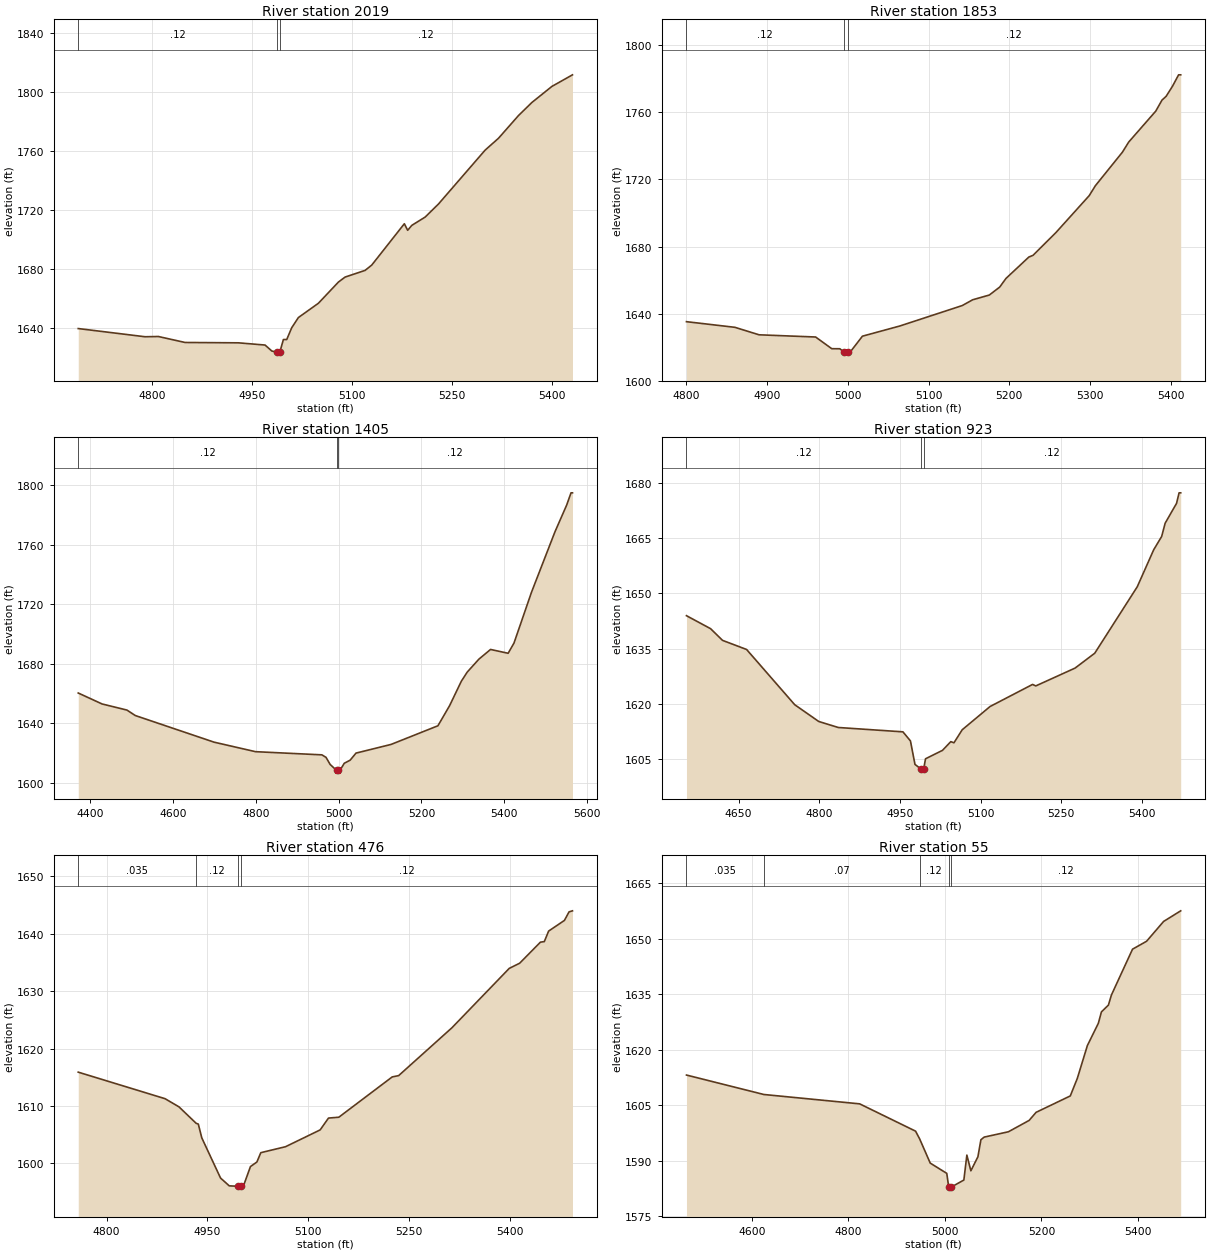
Type RM Length L Ch R = 1,2019,166,166,166
BEGIN DESCRIPTION:
Stream0137_DS 5.0
END DESCRIPTION:
XS GIS Cut Line= 3
      2017630.78     13865185.15      2017625.00     13864875.00
      2017636.80     13864444.06
#Sta/Elev= 30
  4689.8 1639.79  4790.0 1634.24  4810.0 1634.40  4850.0 1630.36  4930.0 1630.12
  4970.0 1628.62  4980.0 1624.61  4988.0 1623.64  4988.2 1623.14  4992.0 1623.64
  4997.5 1632.35  5002.5 1632.35  5010.0 1640.36  5020.0 1647.26  5050.0 1656.94
  5080.0 1671.29  5090.0 1674.68  5120.0 1679.21  5130.0 1682.81  5178.9 1710.84
  5183.9 1706.39  5190.1 1709.74  5210.1 1715.35  5230.1 1724.21  5300.1 1760.75
  5320.1 1768.76  5350.1 1784.16  5370.1 1792.98  5400.2 1803.91  5431.1 1811.77
#Mann=3,-1,0
  4689.8    0.12       0  4988.0    0.05       0  4992.0    0.12       0
Bank Sta=4988,4992
Exp/Cntr=0.3,0.1

Type RM Length L Ch R = 1,1853,448,448,448
BEGIN DESCRIPTION:
Stream0137_DS 4.0
END DESCRIPTION:
XS GIS Cut Line= 3
      2017775.00     13865124.98      2017775.00     13864925.00
      2017675.00     13864524.99
#Sta/Elev= 30
  4800.0 1635.25  4860.0 1631.89  4890.0 1627.43  4960.0 1626.12  4980.0 1619.16
  4990.0 1619.12  4995.5 1617.02  4995.7 1616.52  4999.5 1617.02  5002.6 1617.02
  5018.0 1626.61  5064.4 1632.69  5141.7 1644.86  5154.6 1648.30  5175.2 1651.12
  5188.1 1655.87  5195.8 1660.99  5224.2 1673.75  5229.3 1674.75  5257.7 1688.32
  5298.9 1710.29  5306.6 1716.23  5340.1 1736.21  5347.9 1742.24  5381.4 1760.65
  5389.1 1767.19  5394.3 1769.51  5402.0 1775.37  5409.7 1782.27  5412.3 1782.27
#Mann=3,-1,0
  4800.0    0.12       0  4995.5    0.05       0  4999.5    0.12       0
Bank Sta=4995.5,4999.5
Exp/Cntr=0.3,0.1

Type RM Length L Ch R = 1,1405,482,482,482
BEGIN DESCRIPTION:
Stream0137_DS 3.0
END DESCRIPTION:
XS GIS Cut Line= 3
      2018217.00     13865502.45      2018175.00     13864875.00
      2017775.03     13864475.03
#Sta/Elev= 30
  4370.6 1660.38  4428.2 1653.03  4488.3 1648.93  4508.4 1645.27  4698.8 1627.39
  4799.0 1621.00  4959.4 1618.87  4969.4 1617.19  4979.4 1612.43  4994.9 1608.44
  4995.2 1607.94  4998.9 1608.44  5003.0 1608.44  5013.6 1613.23  5027.7 1615.28
  5041.9 1620.04  5126.7 1625.87  5239.9 1638.39  5268.2 1651.94  5296.4 1668.26
  5310.6 1674.39  5338.9 1683.11  5367.1 1689.63  5409.6 1687.06  5423.7 1693.90
  5466.1 1728.08  5522.7 1768.58  5551.0 1786.53  5561.6 1794.78  5565.1 1794.78
#Mann=3,-1,0
  4370.6    0.12       0  4994.9    0.05       0  4998.9    0.12       0
Bank Sta=4994.9,4998.9
Exp/Cntr=0.3,0.1

Type RM Length L Ch R = 1,923,447,447,447
BEGIN DESCRIPTION:
Stream0137_DS 2.0
END DESCRIPTION:
XS GIS Cut Line= 3
      2018424.98     13865375.03      2018625.00     13864975.00
      2018374.97     13864574.96
#Sta/Elev= 30
  4553.2 1643.96  4598.0 1640.44  4620.3 1637.26  4665.0 1634.79  4754.5 1619.80
  4799.2 1615.25  4835.5 1613.62  4955.7 1612.44  4969.7 1609.97  4978.1 1603.61
  4989.9 1602.28  4990.2 1601.78  4994.2 1602.28  4997.7 1605.13  5029.3 1607.42
  5044.7 1609.78  5050.6 1609.47  5065.9 1613.00  5117.8 1619.32  5196.8 1625.31
  5202.7 1624.90  5275.8 1629.74  5312.4 1633.78  5391.4 1651.80  5422.0 1661.85
  5436.8 1665.46  5443.3 1669.06  5464.5 1674.45  5469.2 1677.30  5472.2 1677.30
#Mann=3,-1,0
  4553.2    0.12       0  4989.9    0.05       0  4994.2    0.12       0
Bank Sta=4989.9,4994.2
Exp/Cntr=0.3,0.1

Type RM Length L Ch R = 1,476,421,421,421
BEGIN DESCRIPTION:
Stream0137_DS 1.0
END DESCRIPTION:
XS GIS Cut Line= 3
      2019084.70     13865260.17      2019025.00     13865025.00
      2018767.85     13864604.76
#Sta/Elev= 30
  4757.8 1615.90  4886.9 1611.28  4907.6 1609.86  4933.3 1606.98  4936.4 1606.86
  4941.6 1604.45  4969.5 1597.45  4982.5 1596.09  4995.6 1596.02  4995.9 1595.52
  5000.0 1596.02  5003.4 1596.02  5014.0 1599.45  5023.6 1600.25  5029.4 1601.87
  5066.2 1602.91  5117.7 1605.84  5130.1 1607.90  5145.5 1608.05  5224.9 1615.07
  5234.5 1615.30  5313.8 1623.64  5399.0 1633.98  5414.5 1634.88  5445.4 1638.55
  5451.2 1638.65  5457.6 1640.48  5481.1 1642.34  5488.0 1643.83  5493.1 1644.01
#Mann=4,-1,0
  4757.8   0.035       0  4933.3    0.12       0  4995.6    0.05       0
  5000.0    0.12       0
Bank Sta=4995.6,5000
Exp/Cntr=0.3,0.1

Type RM Length L Ch R = 1,55,0,0,0
BEGIN DESCRIPTION:
Stream0137_DS 0.0
END DESCRIPTION:
XS GIS Cut Line= 4
      2019172.32     13865288.42      2019314.85     13864828.83
      2019319.94     13864774.86      2018930.45     13864479.69
#Sta/Elev= 30
  4464.6 1613.19  4625.0 1607.93  4823.5 1605.40  4939.3 1598.02  4947.8 1595.92
  4969.7 1589.38  5004.0 1586.60  5008.1 1582.84  5008.4 1582.34  5012.5 1582.84
  5039.4 1584.80  5045.6 1591.55  5053.9 1587.30  5068.5 1591.09  5074.7 1595.69
  5081.5 1596.41  5131.7 1597.85  5174.6 1600.92  5189.1 1603.11  5259.9 1607.54
  5274.5 1612.29  5295.3 1621.16  5318.1 1627.20  5324.4 1630.26  5338.9 1632.11
  5345.2 1634.85  5388.9 1647.23  5418.0 1649.37  5453.3 1654.73  5488.7 1657.60
#Mann=5,-1,0
  4464.6   0.035       0  4625.0    0.07       0  4947.8    0.12       0
  5008.1    0.05       0  5012.5    0.12       0
Bank Sta=5008.1,5012.5
Exp/Cntr=0.3,0.1

Chan Stop Cuts=-1