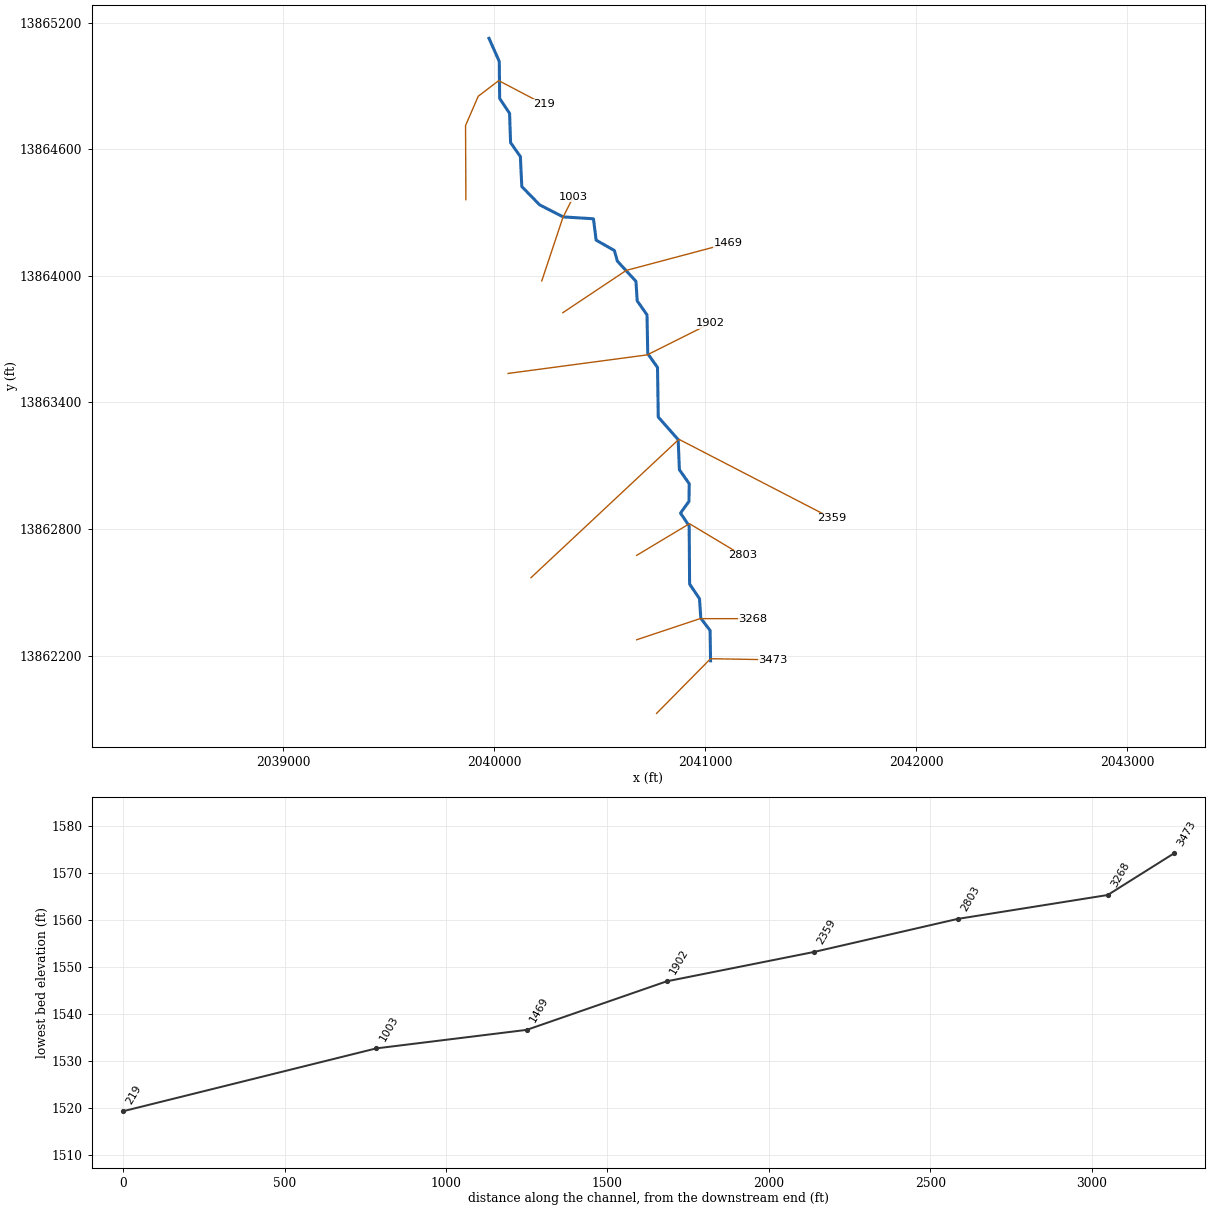
--- Stream0138_DS.prj (project) ---

Proj Title=Stream0138_DS Base Level Engineering
Current Plan=p01
Default Exp/Contr=0.3,0.1
English Units
Geom File=g01
Flow File=f01
Plan File=p01
BEGIN DESCRIPTION:
Stream0138_DS
END DESCRIPTION:

--- Stream0138_DS.p01 (plan) ---

Plan Title=Multiple Run
Short Identifier=Multiple
Geom File=g01
Flow File=f01
Subcritical Flow
K Sum by GR= 0
Std Step Tol= 0.01
Critical Tol= 0.01
Num of Std Step Trials= 20
Max Error Tol= 0.3
Flow Tol Ratio= 0.001
Split Flow NTrial= 30
Split Flow Tol= 0.02
Split Flow Ratio= 0.02
Log Output Level= 0
Friction Slope Method= 1
Unsteady Friction Slope Method= 2
Unsteady Bridges Friction Slope Method= 1
Parabolic Critical Depth
Global Vel Dist=  1 , 1 , 1
Global Log Level= 0
CheckData=True
Encroach Param= -1, 0, 0, 0
BEGIN DESCRIPTION:
Multiple Run
END DESCRIPTION:

--- Stream0138_DS.f01 (steady flow) ---

Flow Title=Multiple
Number of Profiles=7
Profile Names=10-year,25-year,50-year,1pct_min,100-year,1pct_plu,500-year
River Rch & RM= Stream0138_DS,Reach-1,3473
     647    1063    1449     961    1917    3826    3310
River Rch & RM= Stream0138_DS,Reach-1,3268
    1140    1938    2701    1827    3645    7273    6559
Boundary for River Rch & Prof#=Stream0138_DS,Reach-1,1
Up Type=0
Dn Type=3
Dn Slope=0.005
Boundary for River Rch & Prof#=Stream0138_DS,Reach-1,2
Up Type=0
Dn Type=3
Dn Slope=0.005
Boundary for River Rch & Prof#=Stream0138_DS,Reach-1,3
Up Type=0
Dn Type=3
Dn Slope=0.005
Boundary for River Rch & Prof#=Stream0138_DS,Reach-1,4
Up Type=0
Dn Type=3
Dn Slope=0.005
Boundary for River Rch & Prof#=Stream0138_DS,Reach-1,5
Up Type=0
Dn Type=3
Dn Slope=0.005
Boundary for River Rch & Prof#=Stream0138_DS,Reach-1,6
Up Type=0
Dn Type=3
Dn Slope=0.005
Boundary for River Rch & Prof#=Stream0138_DS,Reach-1,7
Up Type=0
Dn Type=3
Dn Slope=0.005

--- Stream0138_DS.g01 (geometry) ---

Geom Title=Existing Conditions

River Reach=Stream0138_DS,Reach-1
Reach XY= 30
      2041025.00     13862175.00      2041022.78     13862319.08
      2040978.85     13862376.60      2040972.53     13862469.43
      2040925.68     13862538.92      2040923.62     13862814.56
      2040882.56     13862875.00      2040922.64     13862930.89
      2040923.89     13863014.45      2040877.39     13863080.53
      2040871.44     13863223.53      2040777.18     13863330.45
      2040773.62     13863565.34      2040727.38     13863630.53
      2040723.78     13863814.50      2040677.36     13863880.98
      2040671.38     13863973.50      2040583.30     13864069.26
      2040569.35     13864119.37      2040482.81     13864168.62
      2040469.92     13864269.96      2040326.56     13864278.76
      2040215.29     13864335.75      2040130.46     13864422.54
      2040123.77     13864564.49      2040077.27     13864630.94
      2040072.61     13864769.47      2040025.52     13864840.22
      2040023.73     13865015.38      2039975.00     13865125.00

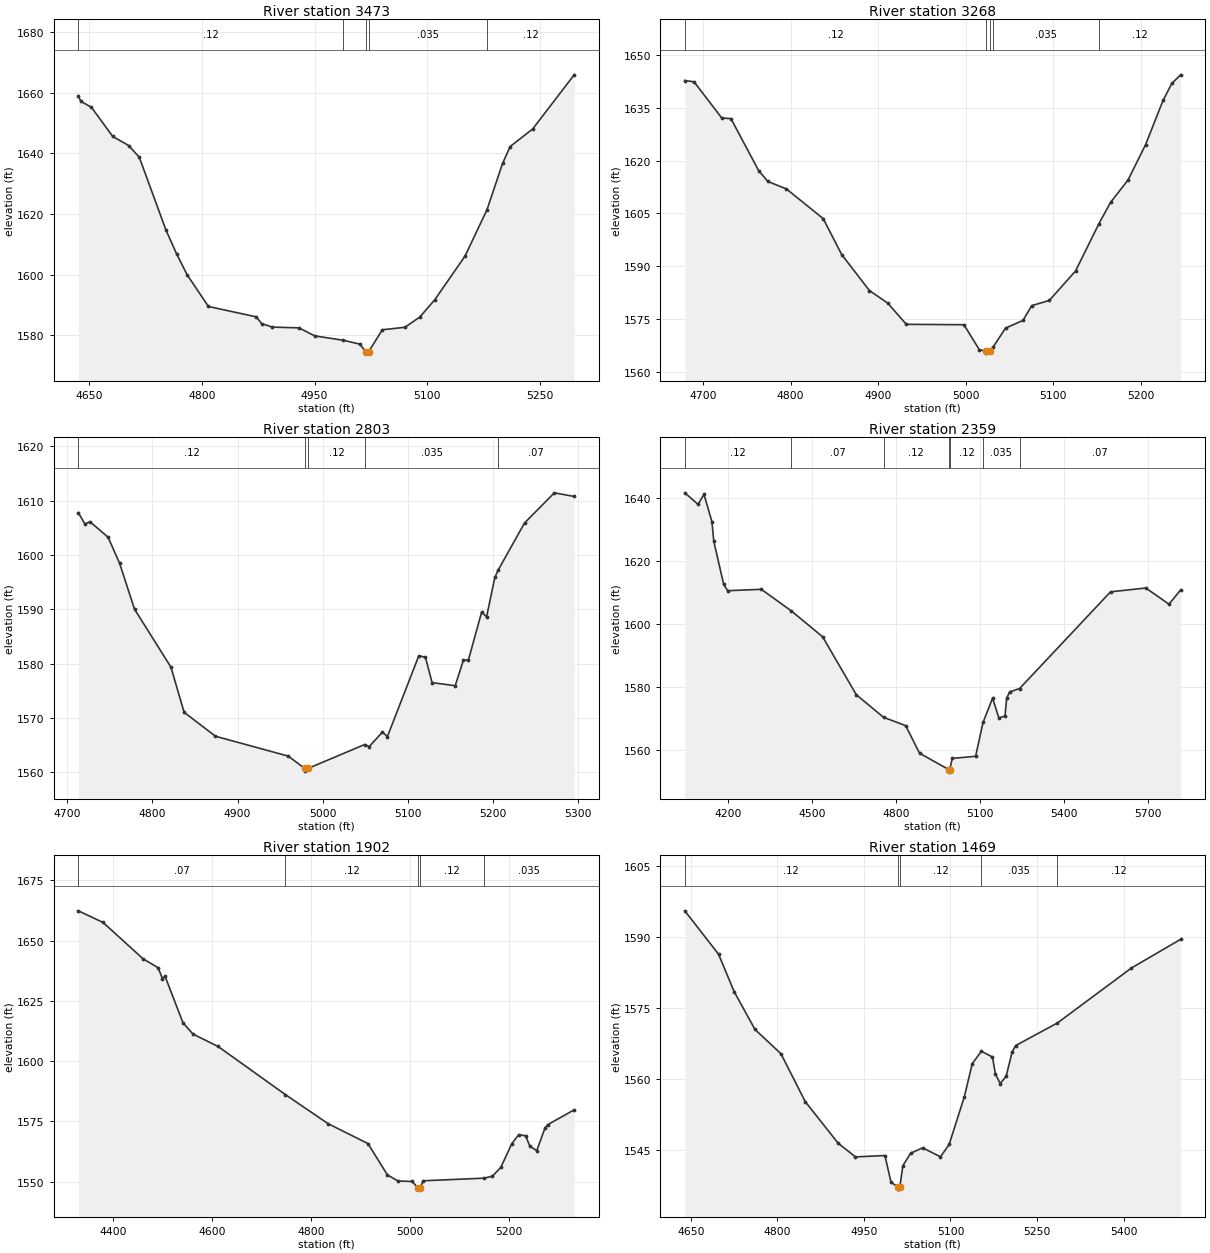
Type RM Length L Ch R = 1,3473,205,205,205
BEGIN DESCRIPTION:
Stream0138_DS 8.0
END DESCRIPTION:
XS GIS Cut Line= 3
      2040769.21     13861926.12      2041025.02     13862185.21
      2041320.08     13862180.00
#Sta/Elev= 30
  4635.9 1658.98  4639.2 1657.14  4653.3 1655.19  4681.6 1645.58  4702.9 1642.57
  4717.0 1638.68  4752.3 1614.79  4766.5 1606.90  4780.6 1599.96  4808.9 1589.53
  4872.6 1586.11  4879.6 1583.89  4893.8 1582.74  4929.2 1582.49  4950.3 1579.83
  4988.3 1578.40  5010.0 1577.13  5018.0 1574.66  5018.2 1574.16  5022.0 1574.66
  5040.0 1581.86  5070.0 1582.67  5090.0 1586.07  5110.0 1591.82  5150.0 1606.14
  5179.1 1621.36  5200.0 1636.72  5210.0 1642.24  5240.0 1648.05  5295.1 1665.88
#Mann=5,-1,0
  4635.9    0.12       0  4988.3   0.035       0  5018.0   0.035       0
  5022.0   0.035       0  5179.1    0.12       0
Bank Sta=5018,5022
Exp/Cntr=0.3,0.1

Type RM Length L Ch R = 1,3268,465,465,465
BEGIN DESCRIPTION:
Stream0138_DS 7.0
END DESCRIPTION:
XS GIS Cut Line= 3
      2040674.98     13862274.99      2040975.00     13862375.00
      2041225.05     13862375.00
#Sta/Elev= 30
  4679.1 1642.75  4689.7 1642.38  4721.3 1632.11  4731.8 1631.93  4763.4 1617.18
  4774.0 1614.07  4795.1 1611.96  4837.2 1603.52  4858.3 1593.31  4889.9 1583.10
  4911.0 1579.50  4932.1 1573.49  4997.9 1573.38  5015.4 1566.32  5023.4 1565.81
  5023.6 1565.31  5027.4 1565.81  5031.0 1566.96  5045.4 1572.40  5065.4 1574.62
  5075.4 1578.81  5095.4 1580.28  5125.4 1588.65  5152.1 1602.09  5165.4 1608.14
  5185.4 1614.51  5205.4 1624.55  5225.4 1637.13  5235.4 1641.93  5245.4 1644.37
#Mann=5,-1,0
  4679.1    0.12       0  5023.4    0.05       0  5027.4    0.12       0
  5031.0   0.035       0  5152.1    0.12       0
Bank Sta=5023.4,5027.4
Exp/Cntr=0.3,0.1

Type RM Length L Ch R = 1,2803,444,444,444
BEGIN DESCRIPTION:
Stream0138_DS 6.0
END DESCRIPTION:
XS GIS Cut Line= 3
      2040674.99     13862674.99      2040925.00     13862825.00
      2041174.99     13862675.00
#Sta/Elev= 30
  4712.8 1607.79  4720.6 1605.69  4726.4 1606.13  4747.8 1603.27  4761.4 1598.44
  4778.9 1590.02  4821.7 1579.36  4837.2 1571.05  4874.1 1566.64  4959.7 1562.98
  4979.0 1560.72  4979.3 1560.22  4983.0 1560.72  5049.6 1565.12  5054.9 1564.74
  5070.4 1567.40  5076.3 1566.59  5113.2 1581.44  5121.0 1581.19  5128.8 1576.51
  5156.0 1575.94  5165.7 1580.66  5171.5 1580.66  5187.1 1589.48  5192.9 1588.62
  5202.6 1595.86  5206.6 1597.24  5237.6 1605.90  5272.6 1611.44  5295.9 1610.77
#Mann=5,-1,0
  4712.8    0.12       0  4979.0    0.05       0  4983.0    0.12       0
  5049.6   0.035       0  5206.6    0.07       0
Bank Sta=4979,4983
Exp/Cntr=0.3,0.1

Type RM Length L Ch R = 1,2359,457,457,457
BEGIN DESCRIPTION:
Stream0138_DS 5.0
END DESCRIPTION:
XS GIS Cut Line= 3
      2040174.08     13862569.14      2040875.00     13863225.00
      2041597.68     13862851.30
#Sta/Elev= 30
  4044.3 1641.80  4091.5 1638.15  4113.0 1641.29  4141.3 1632.62  4148.1 1626.33
  4183.3 1612.70  4197.5 1610.64  4318.1 1611.08  4424.6 1604.26  4537.5 1595.95
  4657.6 1577.54  4755.2 1570.33  4834.5 1567.67  4883.8 1558.92  4988.3 1553.70
  4988.5 1553.20  4992.3 1553.70  5000.8 1557.25  5084.5 1557.92  5111.1 1568.72
  5145.3 1576.47  5167.5 1570.16  5189.6 1570.71  5195.6 1576.42  5206.1 1578.39
  5241.8 1579.50  5567.1 1610.28  5693.3 1611.50  5776.2 1606.35  5817.8 1610.89
#Mann=7,-1,0
  4044.3    0.12       0  4424.6    0.07       0  4755.2    0.12       0
  4988.3    0.05       0  4992.3    0.12       0  5111.1   0.035       0
  5241.8    0.07       0
Bank Sta=4988.3,4992.3
Exp/Cntr=0.3,0.1

Type RM Length L Ch R = 1,1902,433,433,433
BEGIN DESCRIPTION:
Stream0138_DS 4.0
END DESCRIPTION:
XS GIS Cut Line= 3
      2040065.56     13863537.04      2040725.00     13863625.00
      2041025.01     13863775.00
#Sta/Elev= 30
  4330.6 1662.35  4380.5 1657.53  4461.2 1642.46  4491.5 1638.76  4500.4 1634.22
  4505.4 1635.32  4541.9 1615.90  4562.1 1611.22  4612.5 1606.12  4748.7 1586.11
  4834.5 1574.10  4915.2 1565.82  4954.3 1552.86  4975.7 1550.31  5004.3 1550.11
  5016.2 1547.44  5016.5 1546.94  5020.2 1547.44  5026.6 1550.40  5149.6 1551.49
  5166.4 1552.31  5183.2 1555.93  5205.5 1565.80  5219.5 1569.54  5233.5 1569.06
  5241.8 1564.74  5255.8 1562.91  5272.6 1572.37  5278.2 1573.70  5331.3 1579.82
#Mann=5,-1,0
  4330.6    0.07       0  4748.7    0.12       0  5016.2    0.05       0
  5020.2    0.12       0  5149.6   0.035       0
Bank Sta=5016.2,5020.2
Exp/Cntr=0.3,0.1

Type RM Length L Ch R = 1,1469,466,466,466
BEGIN DESCRIPTION:
Stream0138_DS 3.0
END DESCRIPTION:
XS GIS Cut Line= 3
      2040325.04     13863825.02      2040625.00     13864025.00
      2041107.29     13864153.37
#Sta/Elev= 30
  4639.4 1595.60  4697.9 1586.41  4725.0 1578.47  4761.0 1570.47  4806.1 1565.31
  4848.2 1555.17  4905.3 1546.35  4935.3 1543.45  4986.4 1543.74  4996.9 1538.08
  5008.3 1537.12  5008.5 1536.62  5012.3 1537.12  5017.4 1541.58  5031.0 1544.22
  5051.7 1545.38  5082.7 1543.47  5097.7 1546.08  5124.1 1556.22  5137.8 1563.22
  5153.6 1565.84  5172.8 1564.62  5177.9 1561.02  5186.2 1558.99  5196.5 1560.53
  5206.9 1565.70  5212.9 1567.04  5285.4 1571.83  5413.8 1583.49  5499.0 1589.56
#Mann=5,-1,0
  4639.4    0.12       0  5008.3    0.05       0  5012.3    0.12       0
  5153.6   0.035       0  5285.4    0.12       0
Bank Sta=5008.3,5012.3
Exp/Cntr=0.3,0.1

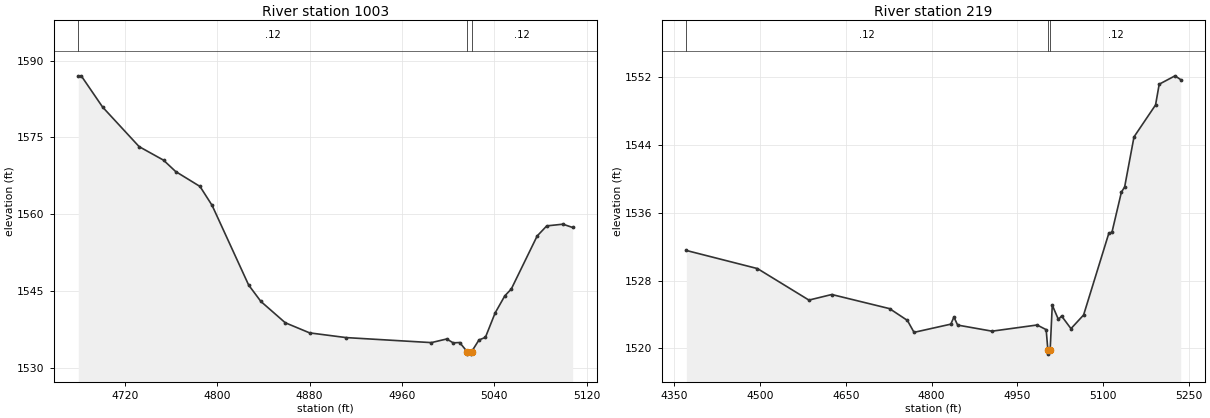
Type RM Length L Ch R = 1,1003,784,784,784
BEGIN DESCRIPTION:
Stream0138_DS 2.0
END DESCRIPTION:
XS GIS Cut Line= 3
      2040225.01     13863975.03      2040325.00     13864275.00
      2040375.00     13864375.00
#Sta/Elev= 30
  4679.7 1587.04  4682.3 1587.04  4700.8 1580.93  4732.4 1573.21  4753.5 1570.57
  4764.0 1568.35  4785.1 1565.43  4795.6 1561.72  4827.2 1546.18  4837.8 1542.97
  4858.9 1538.81  4880.0 1536.83  4911.6 1535.91  4985.4 1534.93  4998.7 1535.64
  5004.3 1534.88  5009.9 1534.95  5016.3 1533.18  5016.5 1532.68  5020.0 1532.68
  5020.3 1533.18  5026.6 1535.44  5032.2 1535.96  5040.6 1540.72  5049.0 1544.07
  5054.6 1545.40  5077.0 1555.76  5085.3 1557.73  5099.3 1558.06  5107.7 1557.42
#Mann=3,-1,0
  4679.7    0.12       0  5016.3    0.05       0  5020.3    0.12       0
Bank Sta=5016.3,5020.3
Exp/Cntr=0.3,0.1

Type RM Length L Ch R = 1,219,0,0,0
BEGIN DESCRIPTION:
Stream0138_DS 1.0
END DESCRIPTION:
XS GIS Cut Line= 5
      2039865.50     13864360.48      2039863.91     13864711.51
      2039923.95     13864850.47      2040021.13     13864924.59
      2040233.97     13864812.89
#Sta/Elev= 30
  4371.0 1531.55  4495.5 1529.41  4585.5 1525.69  4625.5 1526.35  4726.7 1524.68
  4757.8 1523.29  4769.4 1521.88  4833.8 1522.85  4839.2 1523.69  4845.7 1522.74
  4905.9 1522.02  4984.8 1522.75  5000.6 1522.20  5003.6 1519.81  5003.8 1519.31
  5007.6 1519.81  5011.3 1525.09  5022.0 1523.41  5027.6 1523.81  5044.0 1522.32
  5066.1 1523.93  5110.2 1533.57  5115.8 1533.72  5132.3 1538.45  5137.9 1539.04
  5154.3 1544.96  5192.0 1548.73  5198.4 1551.18  5226.1 1552.17  5236.0 1551.72
#Mann=3,-1,0
  4371.0    0.12       0  5003.6    0.05       0  5007.6    0.12       0
Bank Sta=5003.6,5007.6
Exp/Cntr=0.3,0.1

Chan Stop Cuts=-1