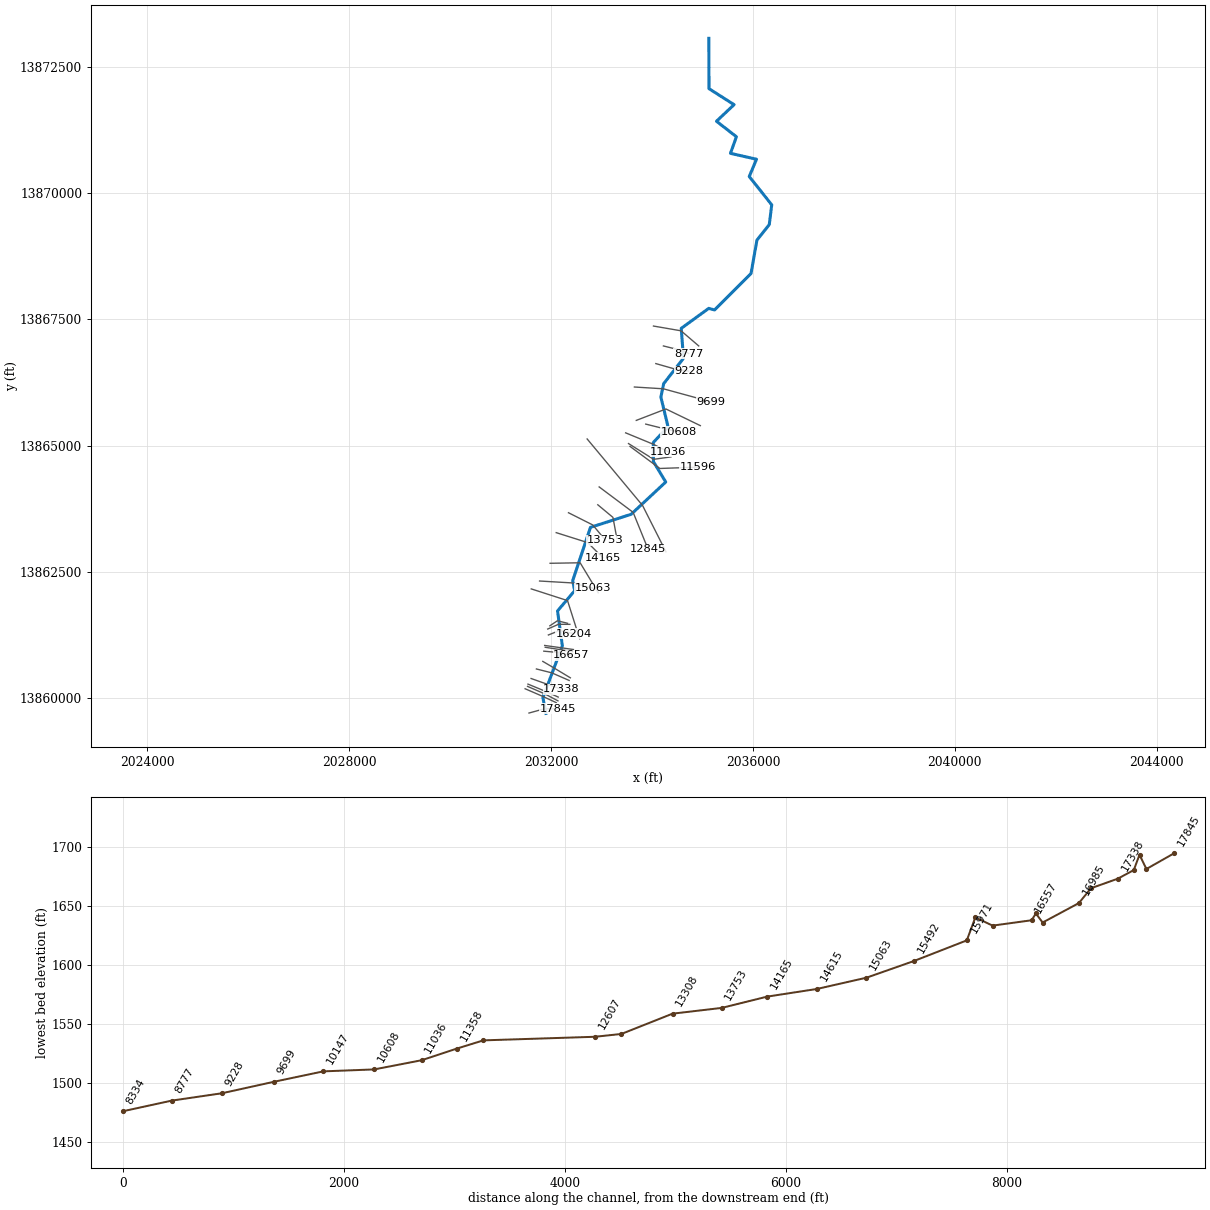
--- Stream0139_DS.prj (project) ---

Proj Title=Stream0139_DS Base Level Engineering
Current Plan=p01
Default Exp/Contr=0.3,0.1
English Units
Geom File=g01
Flow File=f01
Plan File=p01
Y Axis Title=Elevation
X Axis Title(PF)=Main Channel Distance
X Axis Title(XS)=Station
BEGIN DESCRIPTION:
Stream0139_DS
END DESCRIPTION:
DSS Export Rating Curves= 0
DSS Export Rating Curve Sorted= 0
DSS Export Volume Flow Curves= 0
DXF OffsetX= 0
DXF OffsetY= 0
DXF ScaleX= 1
DXF ScaleY= 10

--- Stream0139_DS.p01 (plan) ---

Plan Title=Multiple Run
Short Identifier=Multiple
Geom File=g01
Flow File=f01
Subcritical Flow
K Sum by GR= 0
Std Step Tol= 0.01
Critical Tol= 0.01
Num of Std Step Trials= 20
Max Error Tol= 0.3
Flow Tol Ratio= 0.001
Split Flow NTrial= 30
Split Flow Tol= 0.02
Split Flow Ratio= 0.02
Log Output Level= 0
Friction Slope Method= 1
Unsteady Friction Slope Method= 2
Unsteady Bridges Friction Slope Method= 1
Parabolic Critical Depth
Global Vel Dist=  1 , 1 , 1
Global Log Level= 0
CheckData=True
Encroach Param= -1, 0, 0, 0
BEGIN DESCRIPTION:
Multiple Run
END DESCRIPTION:

--- Stream0139_DS.f01 (steady flow) ---

Flow Title=Multiple
Number of Profiles=7
Profile Names=10-year,25-year,50-year,1pct_min,100-year,1pct_plu,500-year
River Rch & RM= Stream0139_DS,Reach-1,17845
     349     552     734     476     950    1895    1565
River Rch & RM= Stream0139_DS,Reach-1,16048
    1033    1761    2460    1669    3330    6645    6029
River Rch & RM= Stream0139_DS,Reach-1,13308
    1536    2677    3795    2608    5203   10381    9672
River Rch & RM= Stream0139_DS,Reach-1,11358
    1913    3361    4789    3304    6592   13153   12360
River Rch & RM= Stream0139_DS,Reach-1,6519
    2358    4170    5965    4126    8233   16428   15528
Boundary for River Rch & Prof#=Stream0139_DS,Reach-1,1
Up Type=0
Dn Type=3
Dn Slope=0.005
Boundary for River Rch & Prof#=Stream0139_DS,Reach-1,2
Up Type=0
Dn Type=3
Dn Slope=0.005
Boundary for River Rch & Prof#=Stream0139_DS,Reach-1,3
Up Type=0
Dn Type=3
Dn Slope=0.005
Boundary for River Rch & Prof#=Stream0139_DS,Reach-1,4
Up Type=0
Dn Type=3
Dn Slope=0.005
Boundary for River Rch & Prof#=Stream0139_DS,Reach-1,5
Up Type=0
Dn Type=3
Dn Slope=0.005
Boundary for River Rch & Prof#=Stream0139_DS,Reach-1,6
Up Type=0
Dn Type=3
Dn Slope=0.005
Boundary for River Rch & Prof#=Stream0139_DS,Reach-1,7
Up Type=0
Dn Type=3
Dn Slope=0.005

--- Stream0139_DS.g01 (geometry) ---

Geom Title=Existing Conditions
Program Version=4.10

River Reach=Stream0139_DS   ,Reach-1
Reach XY= 30
      2031897.16     13859688.42      2031837.23     13860000.19
      2032222.58     13861029.07      2032127.17     13861719.56
      2032467.19     13862121.59      2032427.34     13862319.48
      2032780.36      13863377.7      2033585.04     13863636.13
      2034271.54      13864276.5      2034027.08     13864680.48
      2034025.09     13865060.97      2034316.93     13865371.69
      2034175.24      13865960.9      2034230.47     13866227.45
      2034622.91     13866730.26       2034578.6     13867323.51
       2035122.7     13867719.89      2035238.38     13867688.54
       2035961.4     13868411.76      2036078.54     13869073.54
      2036322.76     13869380.93      2036371.47     13869773.53
      2035926.09     13870334.64      2036069.92     13870677.31
      2035554.24     13870794.44      2035671.91     13871123.37
      2035276.96     13871430.89      2035625.17     13871759.78
      2035128.54     13872076.46        2035125.       13873075.

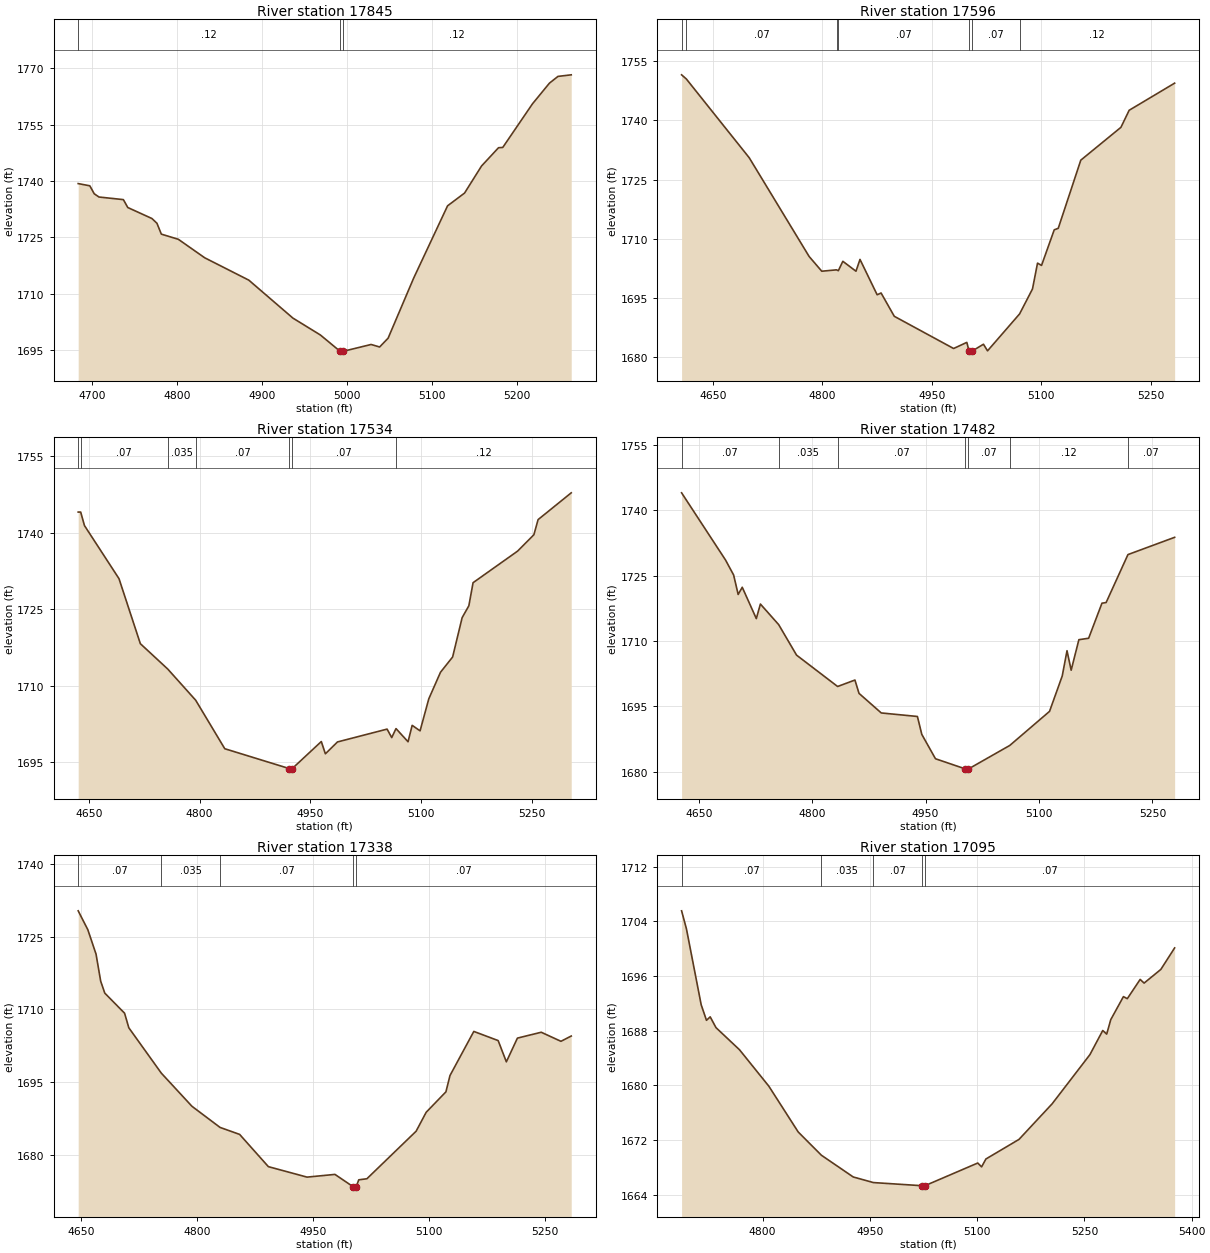
Type RM Length L Ch R = 1 ,17845   ,249,249,249
BEGIN DESCRIPTION:
Stream0139_DS 42.0
END DESCRIPTION:
XS GIS Cut Line= 3
      2031561.35     13859695.09      2031860.84     13859777.92
      2032130.59     13859780.89
#Sta/Elev= 30
  4683.6 1739.32  4697.3 1738.73  4702.5 1736.61  4708.1 1735.75  4736.8 1735.06
    4742 1732.96  4770.4 1730.04  4776.3 1728.78  4781.5 1725.89  4801.5 1724.52
  4832.6  1719.6  4884.5 1713.66  4936.4 1703.58  4968.7  1699.1  4991.9 1694.77
  4992.2 1694.27  4995.9 1694.77  5028.5 1696.57  5038.5  1695.9  5048.5 1698.24
  5078.5 1714.16  5118.5 1733.41  5138.5  1736.8  5158.5 1743.99  5178.5 1748.85
  5183.5 1748.93  5218.5 1760.52  5238.5 1766.02  5248.5  1767.8  5264.1 1768.22
#Mann= 3 ,-1 , 0
  4683.6     .12       0  4991.9     .05       0  4995.9     .12       0
Bank Sta=4991.9,4995.9
XS Rating Curve= 0 ,0
Exp/Cntr=0.3,0.1

Type RM Length L Ch R = 1 ,17596   ,62,62,62
BEGIN DESCRIPTION:
Stream0139_DS 41.0
END DESCRIPTION:
XS GIS Cut Line= 3
       2031484.6     13860176.65      2031849.34     13860018.83
      2032101.48     13859901.08
#Sta/Elev= 30
  4607.2  1751.5  4613.7 1750.45  4699.9 1730.51    4782 1705.52  4799.3 1701.79
  4819.5 1702.14    4822 1701.92  4828.2  1704.3  4846.2 1701.79  4851.7 1704.78
  4875.2 1695.83  4880.6 1696.28  4898.7 1690.38    4980 1682.23  4998.1 1683.78
  5001.2 1681.56  5001.4 1681.06  5005.2 1681.56  5020.9 1683.31  5026.5 1681.64
  5070.4 1690.98  5088.1  1697.3    5095 1703.84  5100.5 1703.26  5117.9 1712.27
  5123.4 1712.65  5154.3  1729.9  5209.3 1738.21  5220.6 1742.53  5282.9 1749.39
#Mann= 7 ,-1 , 0
  4607.2    .035       0  4613.7     .07       0  4819.5     .12       0
    4822     .07       0  5001.2     .05       0  5005.2     .07       0
  5070.4     .12       0
Bank Sta=5001.2,5005.2
XS Rating Curve= 0 ,0
Exp/Cntr=0.3,0.1

Type RM Length L Ch R = 1 ,17534   ,52,52,52
BEGIN DESCRIPTION:
Stream0139_DS 40.0
END DESCRIPTION:
XS GIS Cut Line= 3
       2031532.9     13860223.68      2031871.62     13860076.14
      2032135.73     13859936.94
#Sta/Elev= 30
  4635.4 1744.06  4638.8 1744.06  4643.9 1741.41  4690.7 1730.98  4719.6 1718.22
  4756.7 1713.24  4794.6 1707.11    4834 1697.59  4921.4 1693.69  4921.7 1693.19
  4925.4 1693.69  4964.8    1699  4970.3 1696.59  4986.7 1698.92  5053.9 1701.44
  5060.2 1699.78    5066 1701.54  5082.3 1698.96  5087.9 1702.18  5098.6  1701.1
  5110.4 1707.38  5126.3 1712.61  5142.7  1715.6  5155.6 1723.33  5164.7 1725.66
  5170.4 1730.19  5230.8  1736.4  5252.8 1739.61  5258.5 1742.58  5303.4 1747.84
#Mann= 7 ,-1 , 0
  4635.4    .035       0  4638.8     .07       0  4756.7    .035       0
  4794.6     .07       0  4921.4     .05       0  4925.4     .07       0
    5066     .12       0
Bank Sta=4921.4,4925.4
XS Rating Curve= 0 ,0
Exp/Cntr=0.3,0.1

Type RM Length L Ch R = 1 ,17482   ,144,144,144
BEGIN DESCRIPTION:
Stream0139_DS 39.0
END DESCRIPTION:
XS GIS Cut Line= 3
      2031541.41     13860268.77      2031890.46     13860124.77
      2032140.34     13860011.62
#Sta/Elev= 30
  4627.4 1744.03  4685.4 1728.64  4696.2 1725.18  4702.2 1720.71  4707.6 1722.36
  4726.2 1715.17  4731.6 1718.51  4755.8 1713.78  4779.4 1706.79  4833.7 1699.59
  4856.6 1701.07    4862 1698.01  4891.4 1693.52  4939.2 1692.71    4945  1688.6
  4963.1 1683.01  5002.7 1680.67    5003 1680.17  5006.7 1680.67  5061.3 1686.06
  5113.9 1693.88  5130.7 1702.01    5137  1707.8  5142.5 1703.33  5152.7 1710.33
  5165.6 1710.66  5183.2  1718.7  5188.7 1718.85  5217.6 1729.86  5279.3 1733.82
#Mann= 7 ,-1 , 0
  4627.4     .07       0  4755.8    .035       0  4833.7     .07       0
  5002.7     .05       0  5006.7     .07       0  5061.3     .12       0
  5217.6     .07       0
Bank Sta=5002.7,5006.7
XS Rating Curve= 0 ,0
Exp/Cntr=0.3,0.1

Type RM Length L Ch R = 1 ,17338   ,243,243,243
BEGIN DESCRIPTION:
Stream0139_DS 38.0
END DESCRIPTION:
XS GIS Cut Line= 2
      2031603.26     13860380.02        2032204.     13860166.09
#Sta/Elev= 30
  4646.7 1730.37  4659.2 1726.46  4669.8 1721.42  4675.8 1715.84  4681.1 1713.38
  4706.7 1709.23  4712.2 1706.22  4754.2 1696.86  4793.8 1690.02  4830.2 1685.65
  4855.5 1684.21  4892.7 1677.55  4942.7 1675.39  4978.8 1675.95  5002.3 1673.41
  5002.6 1672.91  5006.3 1673.41  5009.6 1674.83  5020.1 1675.05  5083.8 1684.87
  5096.8 1688.78  5122.3 1692.99  5127.6 1696.37  5158.4 1705.47  5189.9 1703.58
  5200.5 1699.19  5214.8 1704.09  5245.6  1705.3  5271.1 1703.43  5284.4 1704.52
#Mann= 5 ,-1 , 0
  4646.7     .07       0  4754.2    .035       0  4830.2     .07       0
  5002.3     .05       0  5006.3     .07       0
Bank Sta=5002.3,5006.3
XS Rating Curve= 0 ,0
Exp/Cntr=0.3,0.1

Type RM Length L Ch R = 1 ,17095   ,110,110,110
BEGIN DESCRIPTION:
Stream0139_DS 37.0
END DESCRIPTION:
XS GIS Cut Line= 3
      2031708.41     13860569.06      2032011.69     13860492.44
      2032356.89     13860341.91
#Sta/Elev= 30
  4686.8 1705.55  4693.6  1702.9  4714.2  1691.8  4721.6 1689.52  4726.8 1690.03
  4734.9 1688.45  4767.8 1685.21  4808.8 1679.88  4849.9 1673.17  4882.3 1669.77
  4926.8 1666.59    4955 1665.77    5023 1665.31  5023.3 1664.81    5027 1665.31
  5100.9 1668.63  5106.3 1668.07  5112.3 1669.22  5158.6 1672.09    5205 1677.31
  5257.7 1684.49  5275.7 1688.03  5281.2  1687.5  5286.9 1689.62  5304.6 1692.99
    5310 1692.69    5328 1695.51  5333.5 1694.97  5356.9 1696.97  5376.2 1700.12
#Mann= 5 ,-1 , 0
  4686.8     .07       0  4882.3    .035       0    4955     .07       0
    5023     .05       0    5027     .07       0
Bank Sta=5023,5027
XS Rating Curve= 0 ,0
Exp/Cntr=0.3,0.1

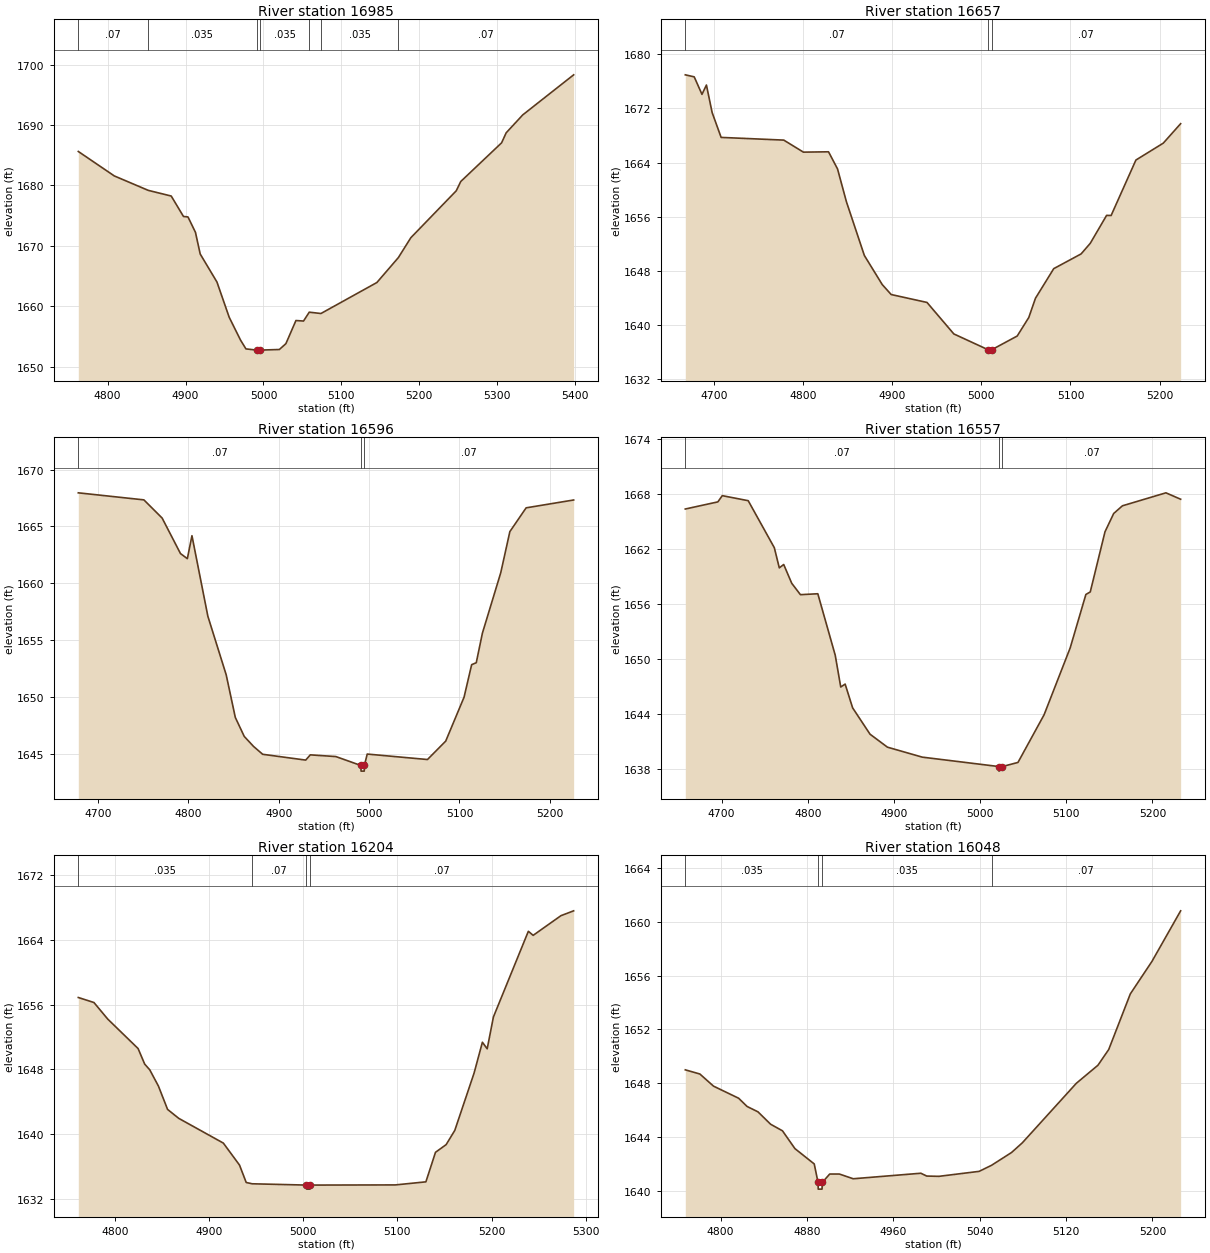
Type RM Length L Ch R = 1 ,16985   ,328,328,328
BEGIN DESCRIPTION:
Stream0139_DS 36.0
END DESCRIPTION:
XS GIS Cut Line= 3
      2031835.15     13860719.16      2032040.35     13860599.18
      2032381.34     13860393.54
#Sta/Elev= 30
  4762.3 1685.63  4808.5 1681.58  4852.1 1679.19  4881.6 1678.25  4897.3 1674.87
  4903.1 1674.79  4912.7 1672.24  4918.8 1668.65  4940.3 1664.01    4956 1658.18
  4970.6 1654.39  4977.5 1652.94  4991.2 1652.74  4991.4 1652.24  4995.2 1652.74
  5020.4 1652.84  5028.8 1653.81  5041.7 1657.64  5051.4 1657.55  5058.8 1659.02
  5073.8  1658.8  5145.6 1663.93  5173.2 1668.06  5189.2 1671.35  5247.5 1679.12
  5253.3 1680.66  5305.7 1687.06  5311.6 1688.72  5332.9 1691.69  5398.2 1698.32
#Mann= 7 ,-1 , 0
  4762.3     .07       0  4852.1    .035       0  4991.2    .035       0
  4995.2    .035       0  5058.8     .07       0  5073.8    .035       0
  5173.2     .07       0
Bank Sta=4991.2,4995.2
XS Rating Curve= 0 ,0
Exp/Cntr=0.3,0.1

Type RM Length L Ch R = 1 ,16657   ,61,61,61
BEGIN DESCRIPTION:
Stream0139_DS 35.0
END DESCRIPTION:
XS GIS Cut Line= 3
        2031855.     13860922.08      2032185.39     13860891.08
      2032404.05     13860842.67
#Sta/Elev= 30
  4667.8 1676.98  4677.8 1676.68  4686.5 1674.09  4691.5 1675.47  4697.9  1671.4
    4708 1667.72  4778.3 1667.32  4800.3 1665.54  4828.5 1665.59  4838.6 1663.06
  4848.6 1658.19  4868.7 1650.25  4888.8 1645.94  4898.8 1644.47    4939  1643.3
  4969.1 1638.64  5007.6  1636.3  5007.9  1635.8  5011.6  1636.3  5040.2 1638.33
  5053.2 1641.07  5060.7 1643.92  5081.2  1648.3  5111.9 1650.48  5122.2 1652.05
  5140.5 1656.18  5145.6 1656.17  5173.4 1664.37  5204.1 1666.87  5223.6 1669.75
#Mann= 3 ,-1 , 0
  4667.8     .07       0  5007.6     .05       0  5011.6     .07       0
Bank Sta=5007.6,5011.6
XS Rating Curve= 0 ,0
Exp/Cntr=0.3,0.1

Type RM Length L Ch R = 1 ,16596   ,39,39,39
BEGIN DESCRIPTION:
Stream0139_DS 34.0
END DESCRIPTION:
XS GIS Cut Line= 3
      2031883.27     13860998.91      2032200.73     13860949.66
      2032424.57     13860911.67
#Sta/Elev= 30
  4678.1 1667.95  4750.7 1667.33  4770.9 1665.73  4791.2 1662.61  4798.8 1662.16
  4803.9 1664.18  4821.5  1657.1  4841.8 1651.95  4851.9  1648.2  4861.8 1646.53
  4872.1 1645.65  4882.2 1644.96  4929.8 1644.45  4934.9 1644.91  4963.2 1644.76
  4990.8 1643.98  4991.1 1643.48  4994.6 1643.48  4994.8 1643.98  4997.9 1644.98
  5064.6  1644.5  5084.8 1646.12  5105.1 1649.98  5113.5 1652.84  5118.6 1653.01
  5125.4 1655.61  5145.7 1660.92  5155.8 1664.54  5173.8 1666.63  5226.4 1667.32
#Mann= 3 ,-1 , 0
  4678.1     .07       0  4990.8     .05       0  4994.8     .07       0
Bank Sta=4990.8,4994.8
XS Rating Curve= 0 ,0
Exp/Cntr=0.3,0.1

Type RM Length L Ch R = 1 ,16557   ,353,353,353
BEGIN DESCRIPTION:
Stream0139_DS 33.0
END DESCRIPTION:
XS GIS Cut Line= 3
      2031872.66     13861035.28      2032213.56     13860987.42
      2032441.92     13860954.94
#Sta/Elev= 30
  4657.8 1666.39  4695.6 1667.17  4700.7 1667.85  4730.8  1667.3  4761.1 1662.16
  4766.9 1659.95    4772 1660.32  4781.3 1658.27  4791.4 1657.02  4811.6 1657.12
  4831.8  1650.4  4838.2 1646.92  4843.3 1647.24    4852 1644.64  4872.2 1641.76
  4892.4 1640.34  4932.8 1639.25  5021.7 1638.22  5021.9 1637.72  5025.7 1638.22
  5043.9 1638.67  5074.2 1643.88  5104.5  1651.2  5122.7 1657.04  5127.8 1657.32
  5144.9  1663.9    5155  1665.9  5165.1 1666.74  5215.6 1668.16  5232.7 1667.46
#Mann= 3 ,-1 , 0
  4657.8     .07       0  5021.7     .05       0  5025.7     .07       0
Bank Sta=5021.7,5025.7
XS Rating Curve= 0 ,0
Exp/Cntr=0.3,0.1

Type RM Length L Ch R = 1 ,16204   ,156,156,156
BEGIN DESCRIPTION:
Stream0139_DS 32.0
END DESCRIPTION:
XS GIS Cut Line= 3
        2031946.     13861243.26      2032167.76     13861331.84
       2032448.2      13861269.9
#Sta/Elev= 30
  4761.2 1656.88  4777.8 1656.26  4792.4 1654.22  4824.7 1650.57  4831.7 1648.65
  4837.1 1647.94  4846.3 1645.93    4856 1643.05  4867.8 1641.95  4915.2 1638.89
  4932.4 1636.17  4939.5 1634.02  4945.8 1633.86  5003.4  1633.7  5003.7  1633.2
  5007.2  1633.2  5007.4  1633.7  5097.9 1633.72  5130.3  1634.1  5140.5 1637.75
  5151.8  1638.7    5161 1640.46  5181.5 1647.55  5190.3 1651.35  5195.4 1650.54
    5202 1654.47  5239.1 1665.06  5244.2 1664.56  5273.7 1666.99  5287.2 1667.59
#Mann= 4 ,-1 , 0
  4761.2    .035       0  4945.8     .07       0  5003.4     .05       0
  5007.4     .07       0
Bank Sta=5003.4,5007.4
XS Rating Curve= 0 ,0
Exp/Cntr=0.3,0.1

Type RM Length L Ch R = 1 ,16048   ,77,77,77
BEGIN DESCRIPTION:
Stream0139_DS 31.5
END DESCRIPTION:
XS GIS Cut Line= 3
      2031932.68     13861360.96       2032145.5     13861454.83
       2032371.6       13861454.
#Sta/Elev= 30
  4767.4    1649  4780.9 1648.69  4793.5 1647.79  4816.8 1646.89  4824.6 1646.28
  4834.7 1645.88  4846.4 1644.96  4857.4 1644.47  4868.9 1643.15  4886.8 1642.01
  4890.3 1640.64  4890.5 1640.14    4894 1640.14  4894.3 1640.64  4901.1 1641.26
  4910.1 1641.26  4922.9 1640.91  4985.5 1641.32    4991 1641.11  5002.3 1641.09
  5039.5 1641.46    5051 1641.91  5069.5 1642.86  5079.5 1643.58  5129.5    1648
  5149.5 1649.34  5159.5 1650.51  5179.5 1654.64  5199.5 1657.05  5226.1 1660.81
#Mann= 4 ,-1 , 0
  4767.4    .035       0  4890.3    .035       0  4894.3    .035       0
    5051     .07       0
Bank Sta=4890.3,4894.3
XS Rating Curve= 0 ,0
Exp/Cntr=0.3,0.1

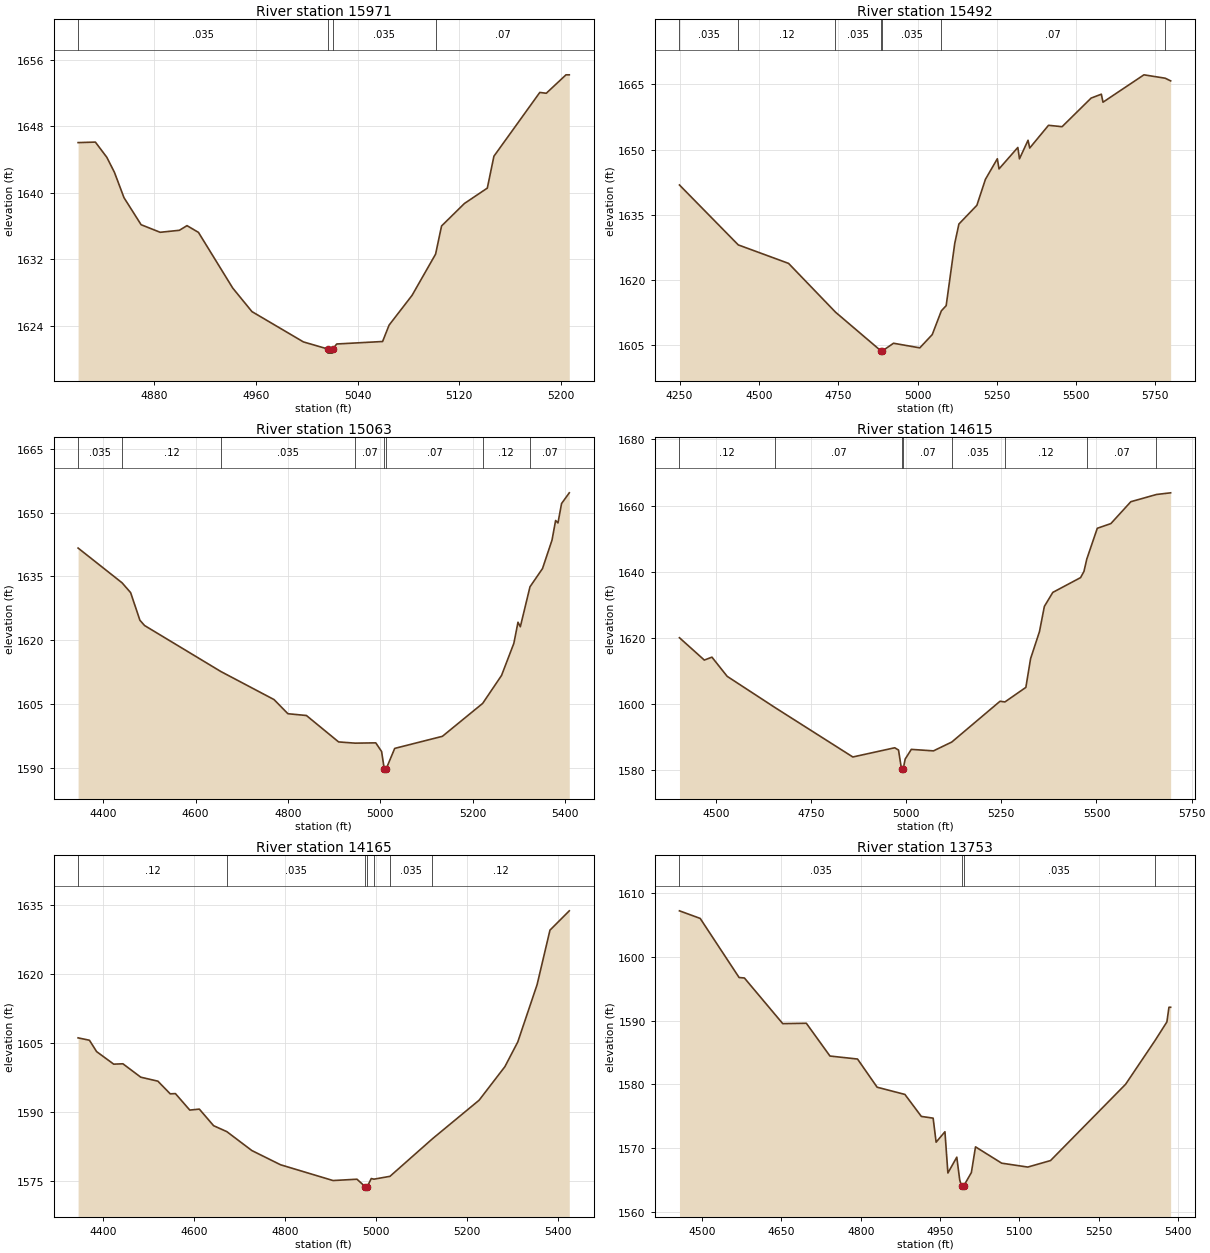
Type RM Length L Ch R = 1 ,15971   ,479,479,479
BEGIN DESCRIPTION:
Stream0139_DS 31.0
END DESCRIPTION:
XS GIS Cut Line= 3
      2031974.97     13861424.98        2032125.       13861525.
      2032325.03     13861474.99
#Sta/Elev= 30
  4820.1 1646.06  4833.7 1646.12  4842.7 1644.29  4848.7 1642.48  4856.2 1639.43
  4869.7 1636.17  4884.7 1635.26  4899.8  1635.5  4905.8 1636.06  4914.8 1635.25
  4941.8 1628.54  4956.9 1625.71  4997.4 1622.06  5016.5 1621.21  5016.7 1620.71
  5020.2 1620.71  5020.5 1621.21  5023.6 1621.81  5059.7 1622.11  5064.8 1624.08
  5082.9 1627.67  5101.4 1632.63  5106.1 1636.02  5124.1 1638.73  5142.1 1640.58
  5147.3 1644.42  5183.4  1652.1  5188.5    1652    5204 1654.22  5206.6 1654.22
#Mann= 4 ,-1 , 0
  4820.1    .035       0  5016.5    .035       0  5020.5    .035       0
  5101.4     .07       0
Bank Sta=5016.5,5020.5
XS Rating Curve= 0 ,0
Exp/Cntr=0.3,0.1

Type RM Length L Ch R = 1 ,15492   ,429,429,429
BEGIN DESCRIPTION:
Stream0139_DS 30.0
END DESCRIPTION:
XS GIS Cut Line= 3
      2031606.42     13862156.83        2032325.       13861925.
      2032565.15     13861168.66
#Sta/Elev= 30
  4249.5 1641.88  4434.9 1628.11  4593.5 1623.86  4741.4 1612.66  4885.1 1603.74
  4885.4 1603.24  4889.1 1603.74  4924.4 1605.51  5007.2 1604.45  5046.5  1607.5
  5075.2 1612.96  5090.4 1614.15  5117.5 1628.49  5130.5  1632.9  5187.2 1637.21
  5214.2 1643.19  5251.7  1647.9    5257 1645.57  5316.3  1650.5  5321.5 1647.89
  5348.5 1652.15  5353.8 1650.37    5413 1655.59  5455.8 1655.27  5547.3 1661.84
  5579.6 1662.74  5584.8  1660.9  5713.9 1667.19  5781.1 1666.41  5798.1  1665.8
#Mann= 7 ,-1 , 0
  4249.5    .035       0  4434.9     .12       0  4741.4    .035       0
  4885.1    .035       0  4889.1    .035       0  5075.2     .07       0
  5781.1     .12       0
Bank Sta=4885.1,4889.1
XS Rating Curve= 0 ,0
Exp/Cntr=0.3,0.1

Type RM Length L Ch R = 1 ,15063   ,448,448,448
BEGIN DESCRIPTION:
Stream0139_DS 29.0
END DESCRIPTION:
XS GIS Cut Line= 3
      2031771.35     13862313.09        2032425.       13862275.
      2032821.19     13862173.27
#Sta/Elev= 30
  4345.7 1641.69  4440.9 1633.51  4459.5 1631.19  4479.6 1624.68  4489.6 1623.45
  4654.9 1612.61  4770.1    1606  4800.1 1602.67  4840.2 1602.25  4909.9 1596.03
  4945.6 1595.74  4990.4 1595.81    5003 1593.77  5008.8 1589.65    5009 1589.15
  5012.8 1589.65  5031.4  1594.5  5134.7 1597.35  5221.9  1605.1  5262.8 1611.69
  5289.5 1619.27  5298.4 1624.22  5303.5 1623.16  5324.4 1632.57  5351.5 1636.86
  5372.1 1643.57  5379.9 1648.18    5385 1647.61  5392.8 1652.18  5409.5  1654.7
#Mann= 8 ,-1 , 0
  4345.7    .035       0  4440.9     .12       0  4654.9    .035       0
  4945.6     .07       0  5008.8     .05       0  5012.8     .07       0
  5221.9     .12       0  5324.4     .07       0
Bank Sta=5008.8,5012.8
XS Rating Curve= 0 ,0
Exp/Cntr=0.3,0.1

Type RM Length L Ch R = 1 ,14615   ,450,450,450
BEGIN DESCRIPTION:
Stream0139_DS 28.0
END DESCRIPTION:
XS GIS Cut Line= 3
      2031979.69     13862664.65        2032575.       13862675.
       2032933.7     13862079.95
#Sta/Elev= 30
  4404.6    1620  4469.9 1613.24  4489.9 1614.12  4529.9 1608.32  4656.2 1598.82
    4860 1583.91    4970  1586.7    4980 1586.01    4988 1580.13  4988.2 1579.63
    4992 1580.13  4997.5 1583.28  5013.6 1586.21  5071.8 1585.76    5120 1588.44
  5246.6 1600.77  5259.5 1600.57  5314.5 1604.97  5326.9 1613.66  5350.3 1621.87
  5363.1 1629.48  5385.3 1633.72  5458.2 1638.19  5467.1 1640.07  5474.5 1643.79
  5502.1 1653.12  5537.8 1654.54  5590.2 1661.16  5657.6 1663.35  5694.8 1663.85
#Mann= 8 ,-1 , 0
  4404.6     .12       0  4656.2     .07       0    4988     .05       0
    4992     .07       0    5120    .035       0  5259.5     .12       0
  5474.5     .07       0  5657.6    .035       0
Bank Sta=4988,4992
XS Rating Curve= 0 ,0
Exp/Cntr=0.3,0.1

Type RM Length L Ch R = 1 ,14165   ,412,412,412
BEGIN DESCRIPTION:
Stream0139_DS 27.0
END DESCRIPTION:
XS GIS Cut Line= 3
      2032101.23     13863272.28        2032725.       13863075.
      2033025.01     13862774.99
#Sta/Elev= 30
  4345.7 1606.13  4370.6 1605.61  4386.4 1603.13  4423.9  1600.4  4444.1 1600.48
  4483.3 1597.56  4520.9 1596.69    4548 1593.93  4559.4 1593.98  4590.9 1590.39
  4611.9  1590.6  4643.3 1586.98  4672.3 1585.69  4727.2 1581.57  4790.2 1578.47
  4905.5 1575.03    4958 1575.32  4976.5 1573.66  4976.8 1573.16  4980.5 1573.66
  4989.4 1575.47  4995.3 1575.33  5030.5 1575.95  5123.8 1584.14  5226.2 1592.54
  5282.8 1599.85  5311.1 1605.24  5353.5 1617.72  5381.8 1629.61  5424.2 1633.82
#Mann= 7 ,-1 , 0
  4345.7     .12       0  4672.3    .035       0  4976.5     .05       0
  4980.5    .035       0  4995.3     .07       0  5030.5    .035       0
  5123.8     .12       0
Bank Sta=4976.5,4980.5
XS Rating Curve= 0 ,0
Exp/Cntr=0.3,0.1

Type RM Length L Ch R = 1 ,13753   ,445,445,445
BEGIN DESCRIPTION:
Stream0139_DS 26.0
END DESCRIPTION:
XS GIS Cut Line= 3
      2032344.28     13863667.24        2032825.       13863425.
      2033074.99     13863125.02
#Sta/Elev= 30
  4457.3 1607.23  4496.5 1606.04  4570.1 1596.77  4580.1  1596.7  4652.6 1589.54
  4697.2  1589.6  4741.9 1584.46    4794 1583.99  4831.1 1579.57  4883.6 1578.44
  4914.7 1574.99    4937 1574.72  4942.6 1570.95  4959.3 1572.59  4964.9 1566.12
  4981.7  1568.6  4987.3    1565  4990.8 1564.09  4991.1 1563.59  4994.8 1564.09
  5009.3 1566.19  5017.1 1570.22  5066.6 1567.66    5116 1567.05    5159 1568.07
  5300.9 1580.03  5356.6 1586.89    5379 1589.81  5382.9 1592.11  5386.1 1592.11
#Mann= 4 ,-1 , 0
  4457.3    .035       0  4990.8    .035       0  4994.8    .035       0
  5356.6     .12       0
Bank Sta=4990.8,4994.8
XS Rating Curve= 0 ,0
Exp/Cntr=0.3,0.1

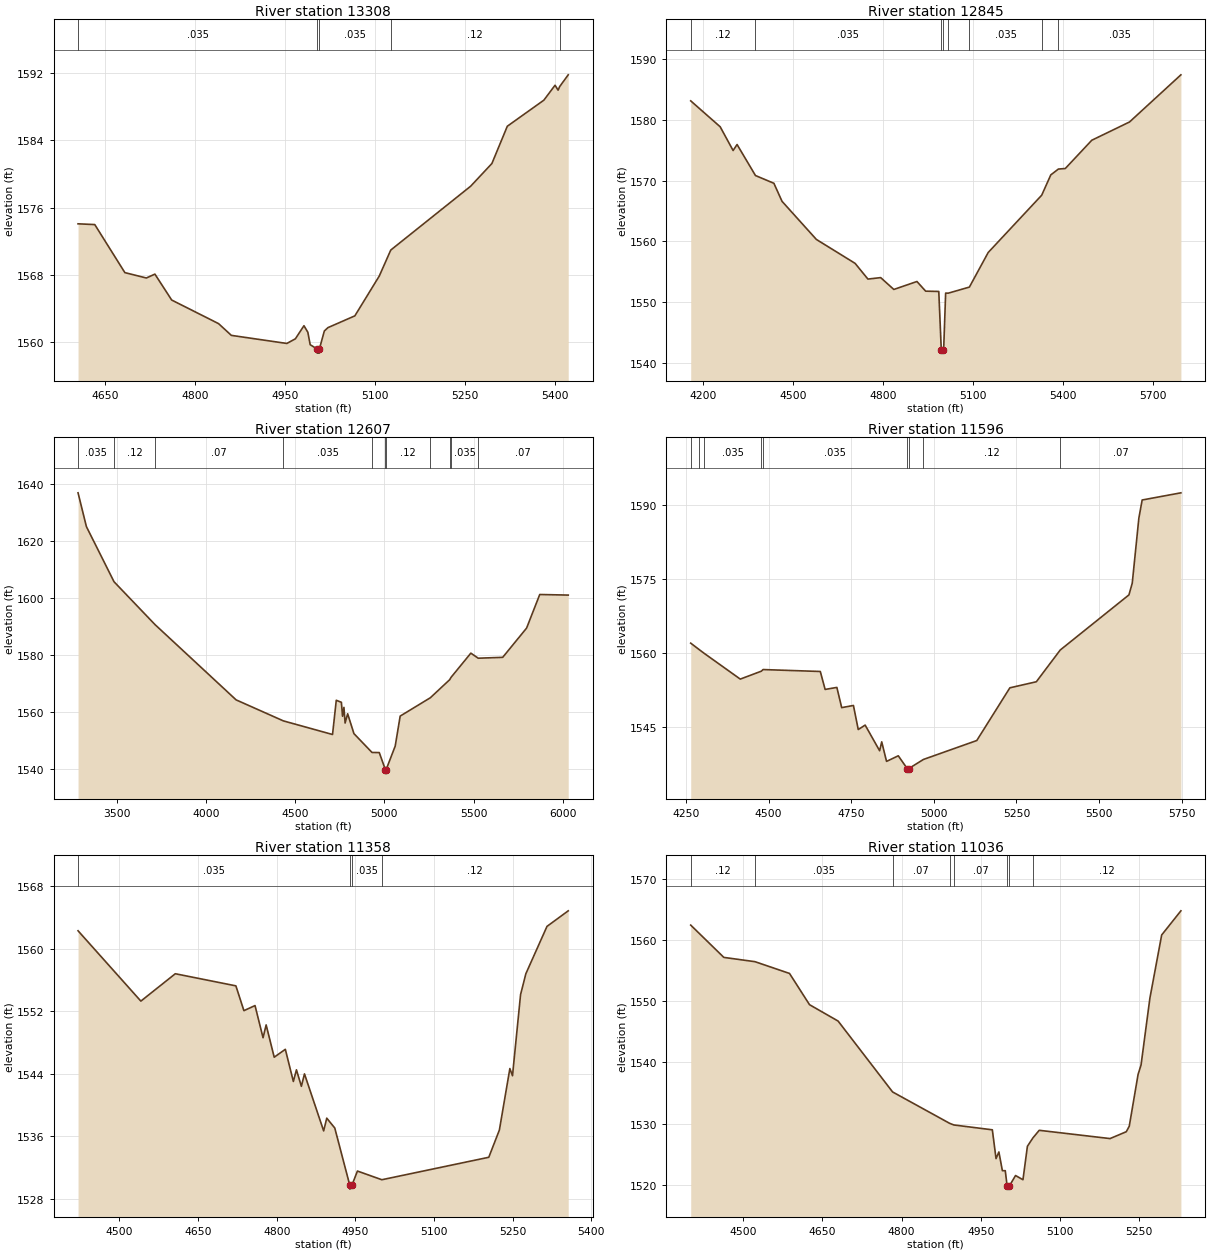
Type RM Length L Ch R = 1 ,13308   ,463,463,463
BEGIN DESCRIPTION:
Stream0139_DS 25.0
END DESCRIPTION:
XS GIS Cut Line= 3
      2032925.03     13863824.97        2033225.       13863575.
      2033303.44     13863155.14
#Sta/Elev= 30
  4605.2 1574.09  4633.1    1574  4683.3 1568.29  4719.1 1567.65  4733.4 1568.11
  4761.4 1565.03  4839.5 1562.23  4860.9 1560.83  4953.4 1559.87  4967.7 1560.42
    4982 1561.98  4988.5  1561.2  4992.4 1559.72  5003.8 1559.22  5004.1 1558.72
  5007.6 1558.72  5007.8 1559.22    5016 1561.35    5022 1561.75  5066.9 1563.15
  5107.6 1567.88  5126.8 1570.97  5260.2 1578.57  5295.5 1581.26  5321.2 1585.69
  5382.2 1588.79  5400.8 1590.56  5405.9 1589.98  5408.6 1590.41  5422.8  1591.8
#Mann= 5 ,-1 , 0
  4605.2    .035       0  5003.8    .035       0  5007.8    .035       0
  5126.8     .12       0  5408.6     .07       0
Bank Sta=5003.8,5007.8
XS Rating Curve= 0 ,0
Exp/Cntr=0.3,0.1

Type RM Length L Ch R = 1 ,12845   ,238,238,238
BEGIN DESCRIPTION:
Stream0139_DS 24.0
END DESCRIPTION:
XS GIS Cut Line= 3
      2032951.88     13864179.41        2033625.       13863675.
      2033923.71     13862939.06
#Sta/Elev= 30
  4158.7 1583.13    4257 1578.86  4300.1 1574.95  4313.3 1575.94  4374.7 1570.83
  4436.2 1569.55  4463.3 1566.58  4577.9  1560.3  4707.1 1556.36  4749.9 1553.77
  4792.5 1554.01  4836.3 1552.06  4913.4 1553.37  4942.5 1551.78  4986.3 1551.73
  4994.7 1542.07    4995 1541.57  4998.7 1542.07  5002.5 1542.07  5009.2 1551.46
    5018 1551.45  5088.4 1552.45  5151.2 1558.15  5329.7 1567.59  5360.1 1570.94
  5385.5  1571.9  5408.3 1571.98  5496.7 1576.64  5622.6 1579.65  5794.1 1587.42
#Mann= 8 ,-1 , 0
  4158.7     .12       0  4374.7    .035       0  4994.7    .035       0
  4998.7    .035       0    5018     .12       0  5088.4    .035       0
  5329.7     .07       0  5385.5    .035       0
Bank Sta=4994.7,4998.7
XS Rating Curve= 0 ,0
Exp/Cntr=0.3,0.1

Type RM Length L Ch R = 1 ,12607   ,1011,1011,1011
BEGIN DESCRIPTION:
Stream0139_DS 23.0
END DESCRIPTION:
XS GIS Cut Line= 3
      2032713.79     13865130.42      2033811.61     13863811.67
      2034275.52     13862892.62
#Sta/Elev= 30
  3284.1 1637.05  3330.9 1625.17  3485.5 1605.79  3714.7 1590.74  4169.3 1564.24
    4434 1556.85  4709.4 1552.06  4730.4  1564.1    4759 1563.38  4765.5 1558.48
  4773.3  1561.6  4779.8  1556.1  4794.1 1559.35  4829.3 1552.37  4930.4 1545.75
  4971.2  1545.7  5005.5 1539.68  5005.7 1539.18  5009.5 1539.68  5060.4 1547.98
  5088.3 1558.53  5257.2 1564.98  5365.7 1571.34  5373.1 1572.15  5484.1 1580.67
  5525.4 1578.89  5662.5  1579.2  5796.3 1589.48    5870 1601.29  6029.5 1601.09
#Mann= 11 ,-1 , 0
  3284.1    .035       0  3485.5     .12       0  3714.7     .07       0
    4434    .035       0  4930.4     .12       0  5005.5     .05       0
  5009.5     .12       0  5257.2    .035       0  5365.7     .07       0
  5373.1    .035       0  5525.4     .07       0
#XS Ineff= 2 , 0
       0 4728.23 1557.05               0
Permanent Ineff=
       F       F
Bank Sta=5005.5,5009.5
XS Rating Curve= 0 ,0
Exp/Cntr=0.3,0.1

Type RM Length L Ch R = 1 ,11596   ,238,238,238
BEGIN DESCRIPTION:
Stream0139_DS 22.0
END DESCRIPTION:
XS GIS Cut Line= 3
      2033563.85     13864982.37      2034155.07     13864545.03
      2034902.11     13864571.28
#Sta/Elev= 30
  4264.6 1562.02  4290.5  1560.7  4304.1 1560.02  4414.5 1554.75  4478.5 1556.36
  4483.4 1556.68  4656.6 1556.29  4671.2 1552.66  4706.7 1553.07  4721.3 1548.98
  4756.8 1549.42  4771.4 1544.55  4792.3 1545.45  4836.1 1540.26  4842.4 1542.06
    4857 1538.11  4892.5 1539.24  4919.7 1536.64  4919.9 1536.14  4923.8 1536.64
  4968.6  1538.5    5130 1542.33  5230.1 1552.99  5310.1 1554.21  5382.4 1560.63
  5590.3 1571.78  5600.3 1574.15  5620.3  1587.3  5630.3 1590.97  5747.5 1592.42
#Mann= 9 ,-1 , 0
  4264.6    .035       0  4290.5    .094       0  4304.1    .035       0
  4478.5    .094       0  4483.4    .035       0  4919.7     .05       0
  4923.8    .035       0  4968.6     .12       0  5382.4     .07       0
Bank Sta=4919.7,4923.8
XS Rating Curve= 0 ,0
Exp/Cntr=0.3,0.1

Type RM Length L Ch R = 1 ,11358   ,322,322,322
BEGIN DESCRIPTION:
Stream0139_DS 21.0
END DESCRIPTION:
XS GIS Cut Line= 3
      2033533.44     13865038.81      2034032.61     13864726.28
      2034375.02       13864775.
#Sta/Elev= 30
    4421 1562.27  4540.8 1553.28  4606.5 1556.78    4722 1555.23  4737.3 1552.06
  4758.5 1552.71  4773.8  1548.6  4779.7 1550.24  4795.1 1546.11  4816.3 1547.12
  4831.6 1543.01  4837.5  1544.5  4846.9 1542.39  4852.8 1543.98  4889.4 1536.69
  4895.3 1538.32  4910.6 1537.06  4939.2 1529.75  4939.4 1529.25  4943.3 1529.75
  4953.8 1531.56  5000.4 1530.45  5204.3 1533.32  5224.5  1536.8  5244.5 1544.66
  5249.5 1543.74  5264.9 1554.11    5275 1556.78  5315.3 1562.83  5355.8 1564.82
#Mann= 4 ,-1 , 0
    4421    .035       0  4939.2    .035       0  4943.3    .035       0
  5000.4     .12       0
Bank Sta=4939.2,4943.3
XS Rating Curve= 0 ,0
Exp/Cntr=0.3,0.1

Type RM Length L Ch R = 1 ,11036   ,428,428,428
BEGIN DESCRIPTION:
Stream0139_DS 20.0
END DESCRIPTION:
XS GIS Cut Line= 3
      2033477.08     13865251.44        2034025.       13865025.
      2034325.02     13864874.99
#Sta/Elev= 30
  4400.6  1562.4  4463.3 1557.13  4522.3 1556.43  4587.7 1554.51  4625.6 1549.41
  4679.7 1546.74  4782.9 1535.17  4890.9 1530.05    4899 1529.78  4971.8 1528.99
  4978.8 1524.29  4984.2 1525.38  4990.8 1522.32  4996.3 1522.32  4999.8 1519.81
  5000.1 1519.31  5003.9 1519.81  5015.8 1521.53  5029.8 1520.84  5038.2  1526.3
  5048.4 1527.64  5060.6 1528.91  5194.7 1527.56  5225.5 1528.68  5231.1 1529.58
  5247.8 1538.03  5253.4 1539.56  5270.2 1550.49  5292.5 1560.79  5328.9 1564.73
#Mann= 8 ,-1 , 0
  4400.6     .12       0  4522.3    .035       0  4782.9     .07       0
  4890.9    .035       0    4899     .07       0  4999.8     .05       0
  5003.9     .07       0  5048.4     .12       0
Bank Sta=4999.8,5003.9
XS Rating Curve= 0 ,0
Exp/Cntr=0.3,0.1

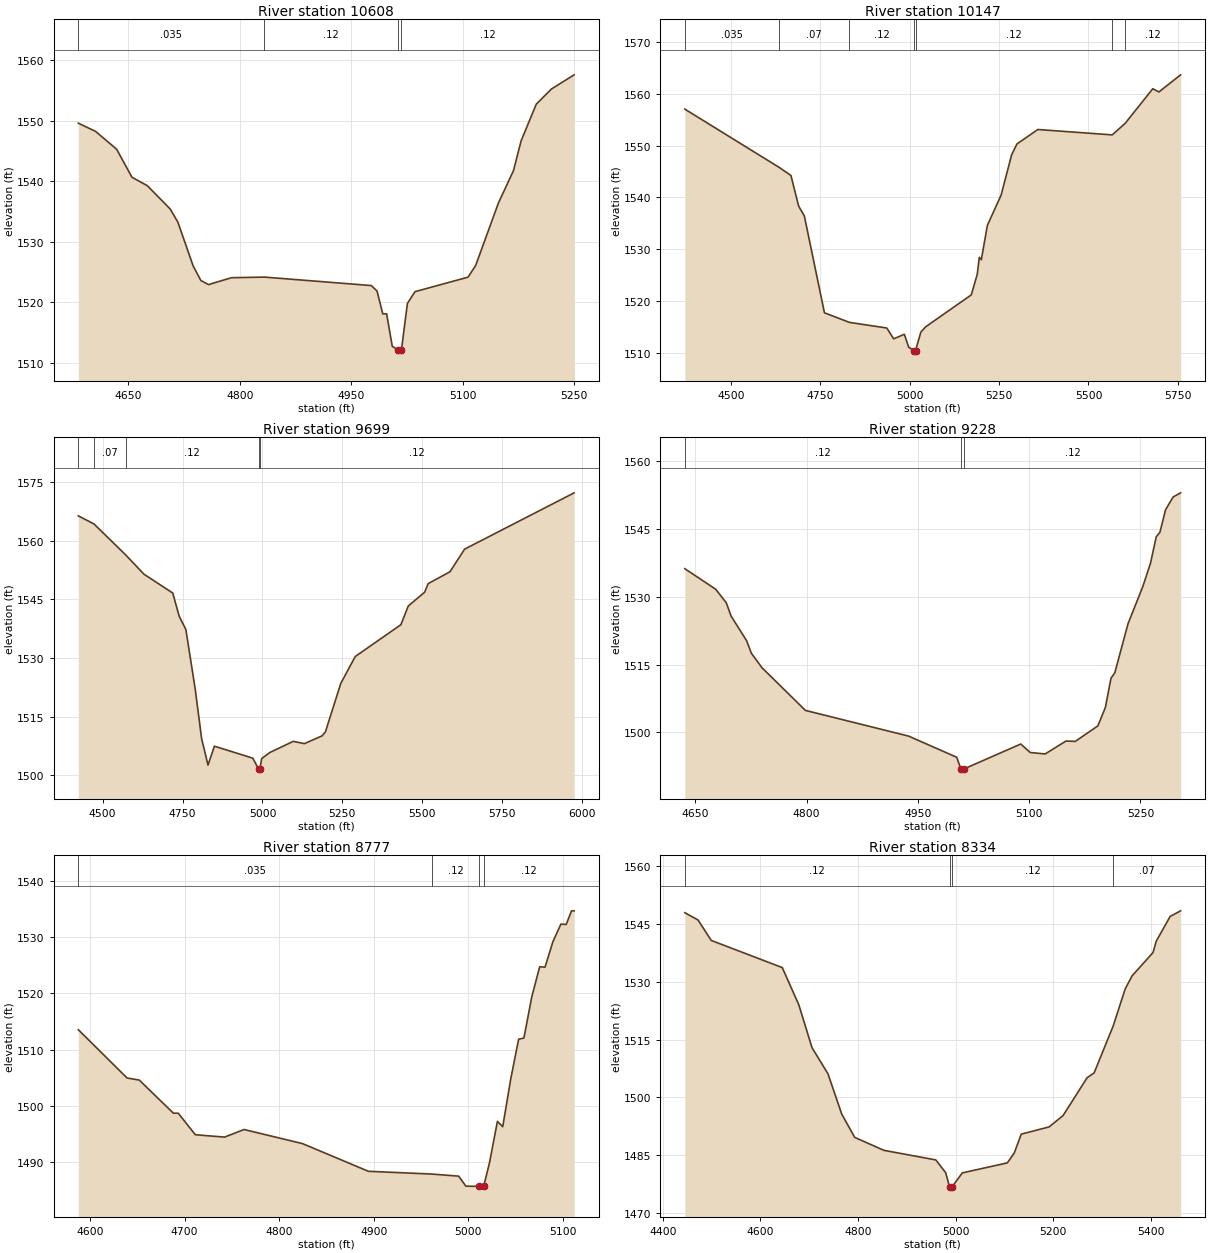
Type RM Length L Ch R = 1 ,10608   ,461,461,461
BEGIN DESCRIPTION:
Stream0139_DS 19.0
END DESCRIPTION:
XS GIS Cut Line= 3
        2033875.       13865425.        2034275.       13865325.
      2034525.04     13865274.99
#Sta/Elev= 30
  4582.8 1549.62    4606 1548.26  4634.3 1545.32    4655 1540.67  4675.6 1539.28
  4706.5 1535.41  4716.8 1533.23  4737.4 1525.98  4747.7 1523.59    4758 1522.91
    4789 1524.05  4833.2 1524.15  4977.1 1522.75  4984.8 1521.85  4992.5 1518.08
  4997.7 1518.08  5005.3  1512.7  5013.4 1512.07  5013.7 1511.57  5017.6 1512.07
  5025.7 1519.79  5035.9 1521.74  5107.3 1524.14  5117.5 1526.06  5148.1 1536.38
  5168.5 1541.79  5178.7 1546.69  5199.1 1552.76  5219.5 1555.27  5250.1 1557.62
#Mann= 4 ,-1 , 0
  4582.8    .035       0  4833.2     .12       0  5013.4     .05       0
  5017.6     .12       0
Bank Sta=5013.4,5017.6
XS Rating Curve= 0 ,0
Exp/Cntr=0.3,0.1

Type RM Length L Ch R = 1 ,10147   ,448,448,448
BEGIN DESCRIPTION:
Stream0139_DS 18.0
END DESCRIPTION:
XS GIS Cut Line= 3
      2033687.89     13865498.42        2034275.       13865725.
      2034957.11     13865394.67
#Sta/Elev= 30
  4370.7 1557.05  4634.1 1545.82  4667.7 1544.23  4689.2 1538.32  4705.2 1536.41
  4761.4 1517.71  4831.1 1515.86  4935.8 1514.77  4955.1 1512.68    4985 1513.56
  4997.3 1511.03    5012 1510.42  5012.2 1509.92  5016.2 1510.42  5031.1 1513.98
  5044.5    1515  5172.2 1521.17  5188.9 1525.13  5194.7 1528.42  5200.3 1527.96
  5217.3  1534.6  5255.6 1540.43  5285.1 1548.22    5300 1550.32  5358.4 1553.11
  5566.5 1552.07  5602.5 1554.28  5680.1 1560.99  5697.1 1560.36  5757.9 1563.67
#Mann= 7 ,-1 , 0
  4370.7    .035       0  4634.1     .07       0  4831.1     .12       0
    5012     .05       0  5016.2     .12       0  5566.5     .07       0
  5602.5     .12       0
Bank Sta=5012,5016.2
XS Rating Curve= 0 ,0
Exp/Cntr=0.3,0.1

Type RM Length L Ch R = 1 ,9699    ,471,471,471
BEGIN DESCRIPTION:
Stream0139_DS 17.0
END DESCRIPTION:
XS GIS Cut Line= 3
      2033650.18     13866160.45        2034225.       13866125.
      2035165.44     13865867.77
#Sta/Elev= 30
  4424.1 1566.36    4473 1564.29    4572 1556.39  4629.3 1551.45  4719.5 1546.62
  4739.5  1540.7  4760.5 1537.29  4789.6 1522.12  4809.7 1509.42  4829.7 1502.63
  4849.7 1507.46    4970 1504.39  4987.9 1501.58  4988.1 1501.08  4992.1 1501.58
  4997.5 1504.27  5022.5 1505.82  5096.6  1508.7  5131.1 1508.11  5186.6  1510.1
    5197 1511.13    5245  1523.5  5290.3 1530.39  5433.1 1538.53  5456.2 1543.32
  5507.3 1546.83  5518.4 1549.03  5586.6 1552.06  5632.4 1557.85    5975 1572.25
#Mann= 5 ,-1 , 0
  4424.1    .035       0    4473     .07       0    4572     .12       0
  4987.9     .05       0  4992.1     .12       0
Bank Sta=4987.9,4992.1
XS Rating Curve= 0 ,0
Exp/Cntr=0.3,0.1

Type RM Length L Ch R = 1 ,9228    ,451,451,451
BEGIN DESCRIPTION:
Stream0139_DS 16.0
END DESCRIPTION:
XS GIS Cut Line= 3
      2034075.02     13866624.99        2034425.       13866525.
      2034724.98       13866475.
#Sta/Elev= 30
    4636 1536.24  4677.6 1531.69  4691.9 1528.68  4698.4 1525.73  4719.2  1520.3
  4725.7  1517.5    4740 1514.29  4798.5 1504.83  4937.6 1499.13  5002.5 1494.43
  5007.9 1491.87  5008.2 1491.37  5012.4 1491.87  5088.7 1497.38  5101.4  1495.5
  5121.6 1495.17  5149.5 1498.03  5162.2 1497.96  5192.6  1501.4  5202.7 1505.47
  5210.3 1511.97  5215.4 1513.15  5233.2 1524.02  5253.4 1532.39  5263.6  1537.5
  5271.2 1543.29  5276.2  1544.3  5283.8  1549.3    5294 1552.13  5304.1 1553.05
#Mann= 3 ,-1 , 0
    4636     .12       0  5007.9     .05       0  5012.4     .12       0
Bank Sta=5007.9,5012.4
XS Rating Curve= 0 ,0
Exp/Cntr=0.3,0.1

Type RM Length L Ch R = 1 ,8777    ,443,443,443
BEGIN DESCRIPTION:
Stream0139_DS 15.0
END DESCRIPTION:
XS GIS Cut Line= 3
      2034225.04     13866974.99        2034625.       13866875.
      2034725.02     13866824.99
#Sta/Elev= 30
  4587.7 1513.55  4639.2 1504.97  4652.1  1504.6  4688.2 1498.71  4693.3 1498.71
  4711.4 1494.88  4742.3 1494.46  4762.9 1495.81  4824.7  1493.3  4894.3 1488.38
  4961.1 1487.89  4989.7 1487.52  4997.4 1485.73  5011.7 1485.71    5012 1485.21
  5016.2 1485.71  5022.3 1489.89  5030.7 1497.26  5036.3 1496.31  5044.7 1504.73
  5053.1 1511.86  5058.7 1512.08  5067.1 1519.47  5075.4 1524.75    5081 1524.67
  5089.4 1529.23  5097.8 1532.33  5103.4 1532.27    5109 1534.69  5111.8 1534.69
#Mann= 4 ,-1 , 0
  4587.7    .035       0  4961.1     .12       0  5011.7     .05       0
  5016.2     .12       0
Bank Sta=5011.7,5016.2
XS Rating Curve= 0 ,0
Exp/Cntr=0.3,0.1

Type RM Length L Ch R = 1 ,8334    ,437,437,437
BEGIN DESCRIPTION:
Stream0139_DS 14.0
END DESCRIPTION:
XS GIS Cut Line= 3
      2034028.25     13867369.51        2034575.       13867275.
      2034924.97     13866975.02
#Sta/Elev= 30
  4445.2 1547.89  4472.3 1546.01  4499.4  1540.7  4644.9 1533.66  4678.8 1524.01
  4705.8  1512.9  4738.6 1506.09  4766.7 1495.67  4793.3 1489.62  4853.1 1486.26
  4959.5 1483.77  4979.8 1480.44  4987.7  1476.7    4988  1476.2  4992.2  1476.7
  5013.8 1480.41    5106 1483.01  5120.2 1485.57  5134.5 1490.46  5191.6 1492.34
  5220.1 1495.27  5269.5  1505.1  5283.8 1506.34    5323 1518.56  5347.4 1528.12
  5361.7 1531.53  5404.5 1537.57  5411.1 1540.52  5439.6 1546.94    5461 1548.38
#Mann= 4 ,-1 , 0
  4445.2     .12       0  4987.7     .05       0  4992.2     .12       0
    5323     .07       0
Bank Sta=4987.7,4992.2
XS Rating Curve= 0 ,0
Exp/Cntr=0.3,0.1