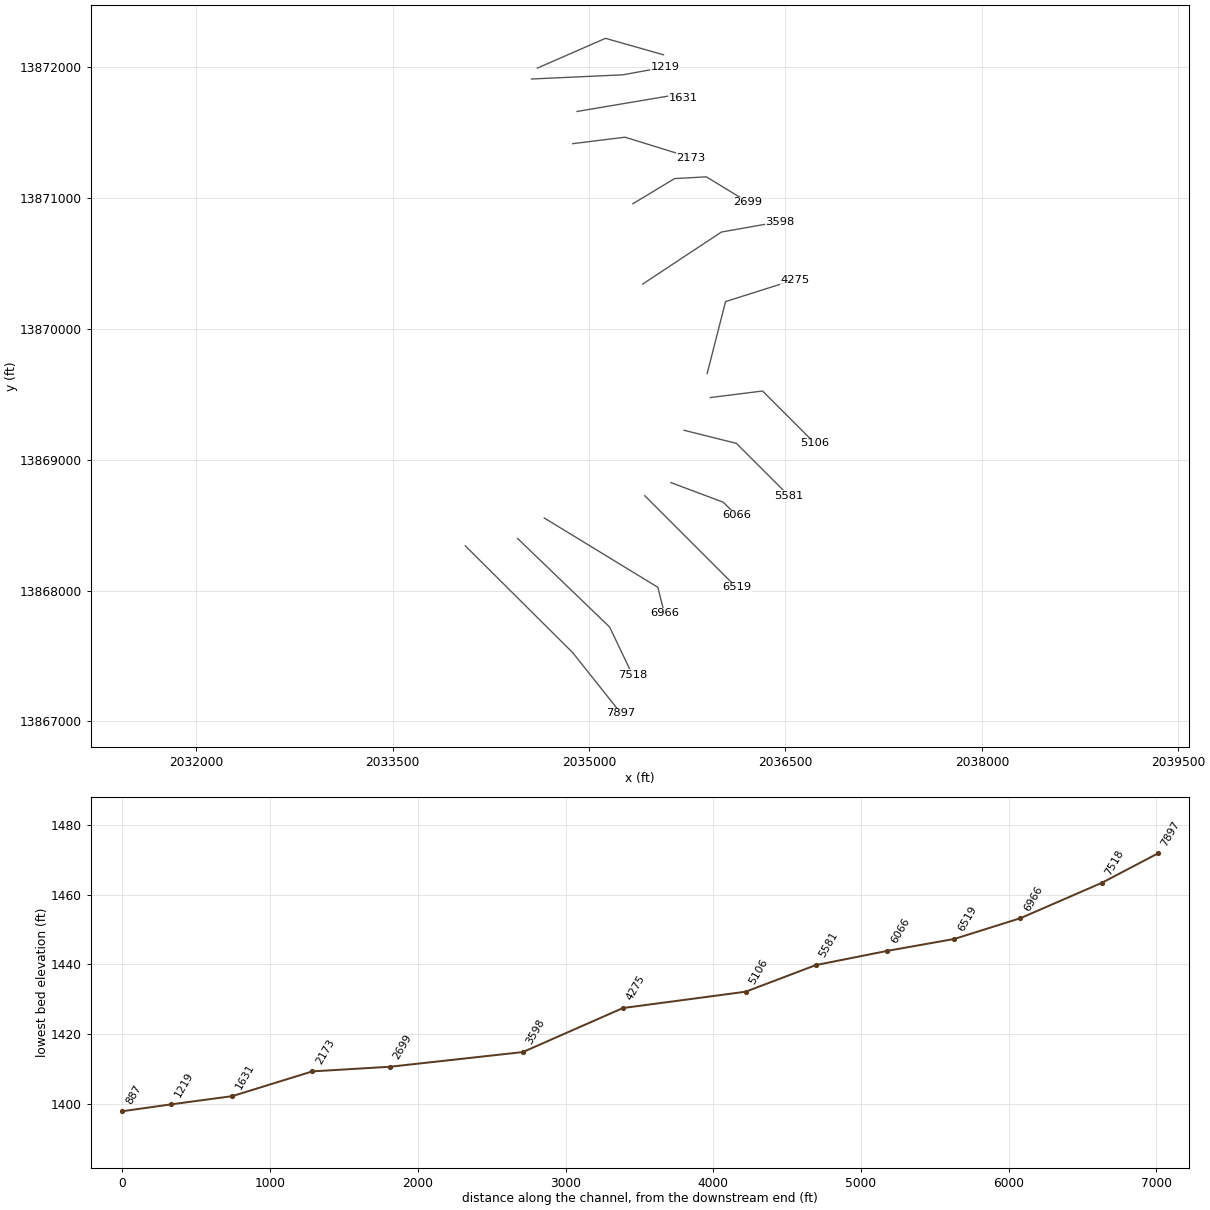
HEC-RAS study Stream0139_DS.prj: Stream0139_DS Base Level Engineering

--- Stream0139_DS.g01 (geometry) --- (continued)

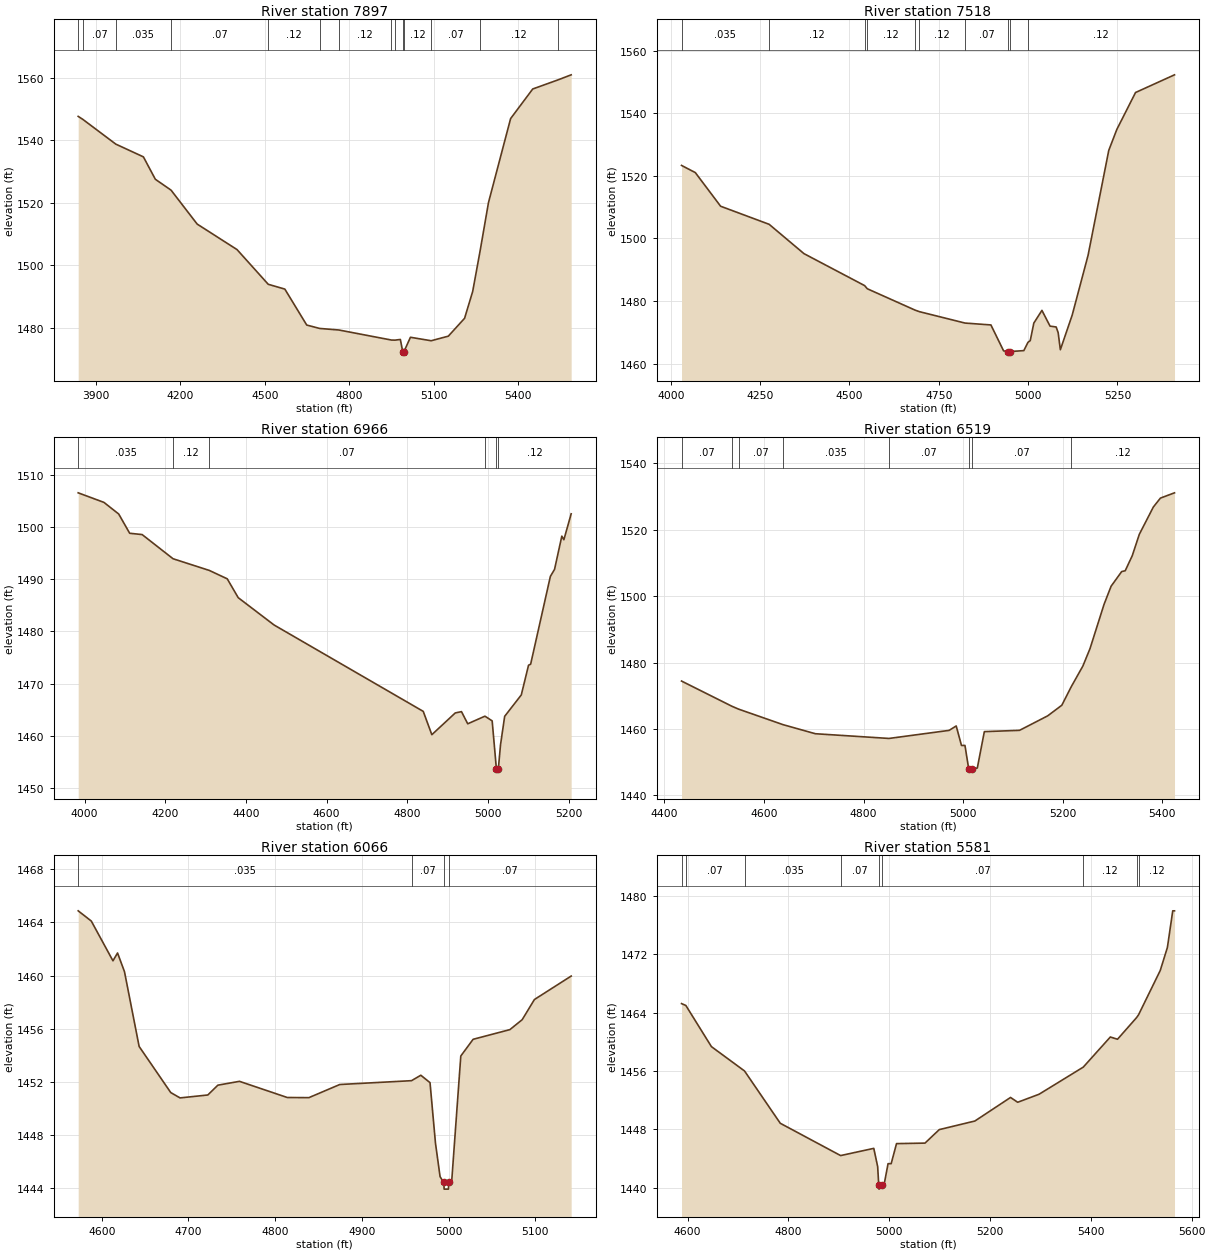
Type RM Length L Ch R = 1 ,7897    ,379,379,379
BEGIN DESCRIPTION:
Stream0139_DS 13.0
END DESCRIPTION:
XS GIS Cut Line= 3
      2034054.32     13868341.73        2034875.       13867525.
      2035243.54     13867061.36
#Sta/Elev= 30
  3837.8 1547.66    3855 1546.66  3971.3 1538.77  4069.3 1534.69  4111.7 1527.51
  4167.5 1524.02  4260.2 1513.15  4401.7 1504.97  4512.5 1493.85  4571.4 1492.31
  4649.1 1480.79    4695  1479.7  4763.4  1479.2    4950 1475.98  4962.3 1475.95
  4981.5 1476.17  4989.8 1472.29  4990.1 1471.79  4994.4 1472.29  5017.3 1476.87
  5090.9 1475.76  5151.8 1477.23  5209.5 1482.95  5238.3 1491.57  5264.8 1504.65
  5294.4 1520.06  5372.9 1546.95  5451.4 1556.44    5540 1559.32  5587.9 1560.98
#Mann= 14 ,-1 , 0
  3837.8     .12       0    3855     .07       0  3971.3    .035       0
  4167.5     .07       0  4512.5     .12       0    4695     .07       0
  4763.4     .12       0    4950     .07       0  4962.3     .12       0
  4989.8     .05       0  4994.4     .12       0  5090.9     .07       0
  5264.8     .12       0    5540     .07       0
Bank Sta=4989.8,4994.4
XS Rating Curve= 0 ,0
Exp/Cntr=0.3,0.1

Type RM Length L Ch R = 1 ,7518    ,552,552,552
BEGIN DESCRIPTION:
Stream0139_DS 12.0
END DESCRIPTION:
XS GIS Cut Line= 3
      2034453.61     13868398.16      2035156.74     13867721.07
      2035330.33     13867356.53
#Sta/Elev= 30
    4030 1523.32  4068.6 1521.03  4139.4 1510.29  4275.3 1504.51  4372.7 1495.15
  4542.4 1484.95  4550.1 1483.93  4683.4 1477.13  4695.8 1476.62  4823.5 1472.98
    4896 1472.38  4931.5  1464.1  4943.1 1463.88  4943.5 1463.38  4948.1 1463.88
  4988.1 1464.18  4999.7 1466.83  5006.1 1467.38  5016.1 1472.98  5038.8 1477.03
  5061.5    1472  5078.6 1471.73  5084.2 1469.93  5090.4 1464.47  5123.6 1475.56
  5167.9  1494.6  5225.9 1528.14  5248.6 1534.85  5300.8  1546.6  5409.9 1552.25
#Mann= 10 ,-1 , 0
    4030    .035       0  4275.3     .12       0  4542.4     .07       0
  4550.1     .12       0  4683.4     .07       0  4695.8     .12       0
  4823.5     .07       0  4943.1     .05       0  4948.1     .07       0
  4999.7     .12       0
Bank Sta=4943.1,4948.1
XS Rating Curve= 0 ,0
Exp/Cntr=0.3,0.1

Type RM Length L Ch R = 1 ,6966    ,447,447,447
BEGIN DESCRIPTION:
Stream0139_DS 11.0
END DESCRIPTION:
XS GIS Cut Line= 3
      2034657.57     13868554.43        2035525.       13868025.
        2035575.     13867824.99
#Sta/Elev= 30
    3984 1506.57  4047.8 1504.74  4084.5 1502.51  4111.7 1498.82  4142.6 1498.57
  4219.2 1493.94  4309.1  1491.7  4353.6 1490.09  4380.8 1486.48  4469.8 1481.24
  4839.6 1464.69  4860.9 1460.22    4919 1464.39  4934.4 1464.64  4949.9 1462.31
  4992.6 1463.77  5010.5 1462.87  5020.9 1453.74  5021.3 1453.24  5025.9 1453.74
  5031.2 1458.28  5041.5 1463.74  5082.7 1467.84  5100.7 1473.54  5105.9 1473.73
  5154.8 1490.55  5165.2 1491.91  5183.2 1498.27  5188.3 1497.58  5206.4 1502.55
#Mann= 6 ,-1 , 0
    3984    .035       0  4219.2     .12       0  4309.1     .07       0
  4992.6     .12       0  5020.9     .05       0  5025.9     .12       0
Bank Sta=5020.9,5025.9
XS Rating Curve= 0 ,0
Exp/Cntr=0.3,0.1

Type RM Length L Ch R = 1 ,6519    ,453,453,453
BEGIN DESCRIPTION:
Stream0139_DS 10.0
END DESCRIPTION:
XS GIS Cut Line= 3
      2035424.99     13868725.01        2035825.       13868325.
      2036125.03     13868024.97
#Sta/Elev= 30
  4434.3 1474.42  4534.9 1466.87  4548.8 1465.97    4638  1461.3    4703 1458.56
    4851 1457.14  4971.7 1459.57  4985.9  1460.9  4996.5 1455.03  5003.5 1455.03
  5011.2  1447.8  5011.7  1447.3    5017  1447.8  5028.3 1448.25  5042.4 1459.19
  5113.1 1459.58  5169.7 1463.95    5198 1467.14    5217 1472.73  5240.4 1478.98
  5254.6 1484.19  5282.8 1497.52    5297 1502.98  5318.2 1507.38  5325.3 1507.63
  5339.4 1512.14  5353.6 1518.59  5381.8 1526.82    5396  1529.5  5424.3 1531.09
#Mann= 8 ,-1 , 0
  4434.3     .07       0  4534.9    .035       0  4548.8     .07       0
    4638    .035       0    4851     .07       0  5011.2     .05       0
    5017     .07       0    5217     .12       0
Bank Sta=5011.2,5017
XS Rating Curve= 0 ,0
Exp/Cntr=0.3,0.1

Type RM Length L Ch R = 1 ,6066    ,485,485,485
BEGIN DESCRIPTION:
Stream0139_DS 9.0
END DESCRIPTION:
XS GIS Cut Line= 3
        2035625.       13868825.        2036025.       13868675.
      2036124.98     13868575.02
#Sta/Elev= 30
  4572.8 1464.88  4587.9 1464.11  4612.9 1461.11  4618.2  1461.7  4626.2 1460.29
  4643.1 1454.65  4679.6 1451.17  4690.3 1450.77  4722.3 1450.99  4733.9 1451.73
  4758.8 1452.02    4814  1450.8  4838.9 1450.79  4874.5 1451.78  4957.3 1452.07
    4968 1452.48  4978.6 1451.92  4984.9 1447.35  4990.2 1444.83  4994.4 1444.39
  4994.9 1443.89  4999.8 1443.89  5000.2 1444.39  5003.5 1444.39  5014.1 1453.93
  5028.3 1455.19  5070.7 1455.92  5084.9 1456.67    5099 1458.19  5141.4 1459.96
#Mann= 4 ,-1 , 0
  4572.8    .035       0  4957.3     .07       0  4994.4     .05       0
  5000.2     .07       0
Bank Sta=4994.4,5000.2
XS Rating Curve= 0 ,0
Exp/Cntr=0.3,0.1

Type RM Length L Ch R = 1 ,5581    ,475,475,475
BEGIN DESCRIPTION:
Stream0139_DS 8.0
END DESCRIPTION:
XS GIS Cut Line= 3
      2035724.99       13869225.        2036125.       13869125.
      2036524.99     13868725.01
#Sta/Elev= 30
    4588 1465.25  4596.6 1464.99  4647.3 1459.35    4713 1456.01  4783.9 1448.84
  4903.6 1444.41  4969.4  1445.4  4977.1  1442.9  4979.3 1440.31  4979.8 1439.81
  4985.2 1440.31    4990 1440.47  4997.7  1443.3  5003.9  1443.3  5014.5 1446.05
    5071 1446.12  5099.3 1447.97    5170 1449.15  5240.7 1452.38  5254.9 1451.72
  5297.3 1452.82    5385 1456.54  5438.7 1460.67  5452.9 1460.36  5490.9 1463.34
  5494.7 1463.72  5537.7 1469.79  5551.9 1472.95  5562.5 1477.97    5566 1477.97
#Mann= 9 ,-1 , 0
    4588    .035       0  4596.6     .07       0    4713    .035       0
  4903.6     .07       0  4979.3     .05       0  4985.2     .07       0
    5385     .12       0  5490.9     .07       0  5494.7     .12       0
Bank Sta=4979.3,4985.2
XS Rating Curve= 0 ,0
Exp/Cntr=0.3,0.1

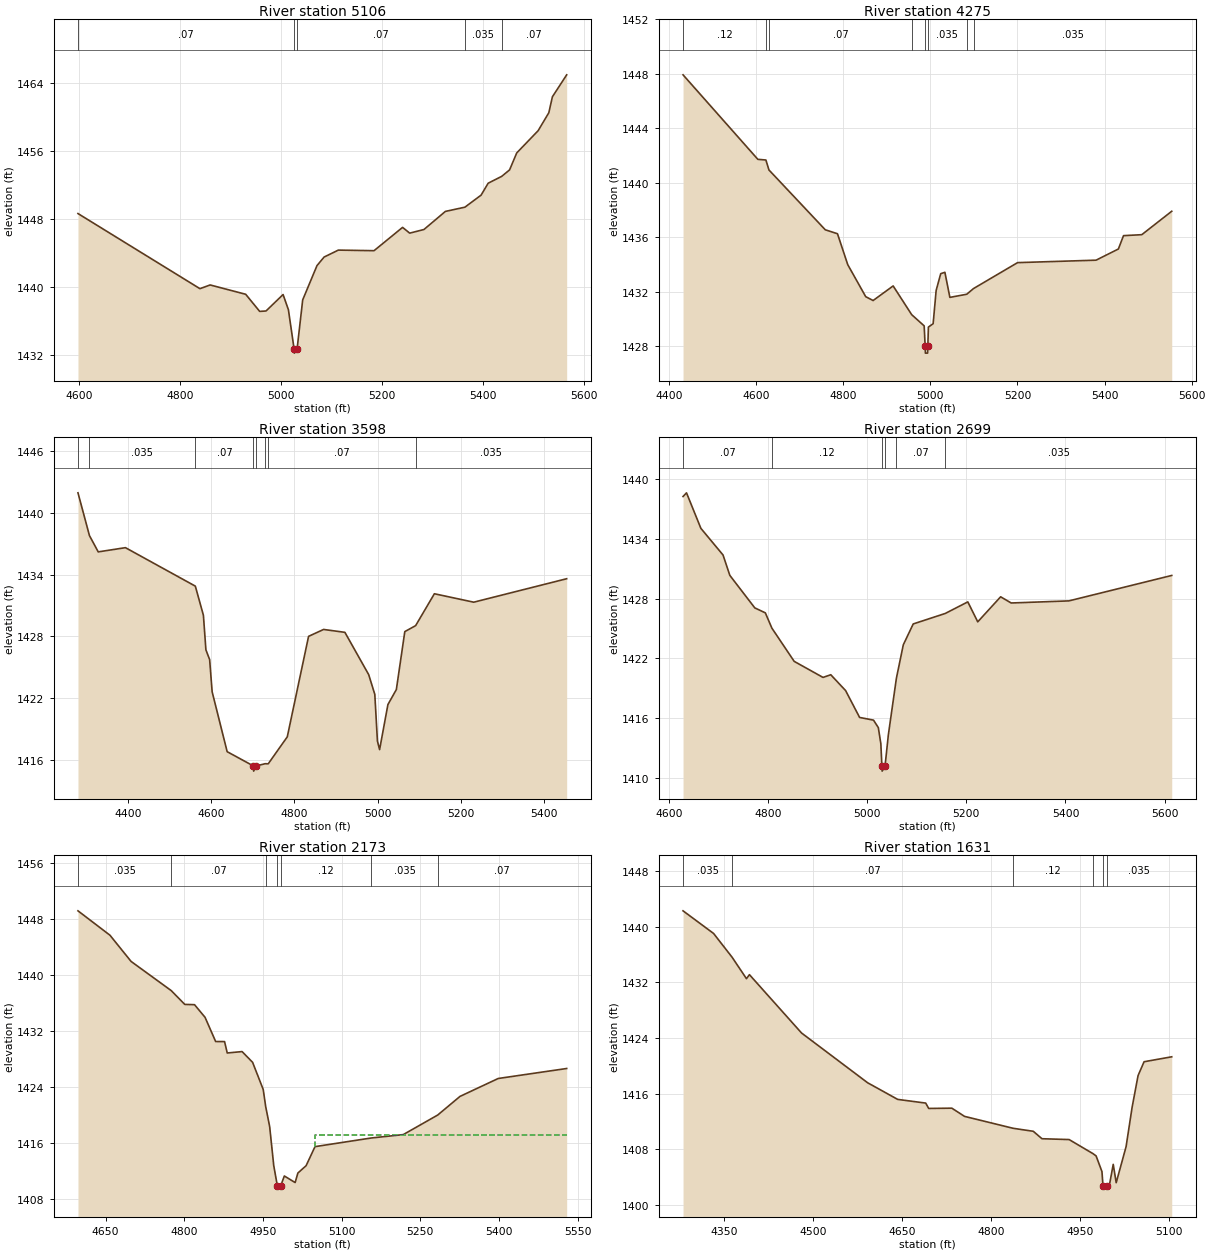
Type RM Length L Ch R = 1 ,5106    ,831,831,831
BEGIN DESCRIPTION:
Stream0139_DS 7.0
END DESCRIPTION:
XS GIS Cut Line= 3
      2035925.04     13869475.01        2036325.       13869525.
      2036725.03     13869124.97
#Sta/Elev= 30
  4597.3 1448.65  4839.1 1439.79  4859.3 1440.23  4929.8 1439.13  4957.5 1437.11
  4970.1 1437.16  5003.9  1439.1  5014.5  1437.3  5025.7 1432.69  5026.2 1432.19
  5031.7 1432.69  5042.8 1438.47  5071.1 1442.51  5085.2 1443.52  5113.5 1444.34
  5184.2 1444.27  5240.8 1447.02  5254.9 1446.34  5283.2 1446.77  5325.6  1448.9
  5364.3  1449.4  5396.4 1450.82  5410.5 1452.23  5437.4 1453.04  5452.9  1453.8
  5467.1  1455.8  5509.5 1458.42  5530.7 1460.54  5537.8 1462.42  5566.1 1465.01
#Mann= 5 ,-1 , 0
  4597.3     .07       0  5025.7     .05       0  5031.7     .07       0
  5364.3    .035       0  5437.4     .07       0
Bank Sta=5025.7,5031.7
XS Rating Curve= 0 ,0
Exp/Cntr=0.3,0.1

Type RM Length L Ch R = 1 ,4275    ,677,677,677
BEGIN DESCRIPTION:
Stream0139_DS 6.0
END DESCRIPTION:
XS GIS Cut Line= 3
      2035901.74     13869658.65      2036042.12     13870208.52
      2036570.58     13870375.79
#Sta/Elev= 30
  4432.5 1447.93  4604.2 1441.73  4622.7 1441.68  4629.7 1440.95    4759 1436.56
    4787 1436.27  4810.6    1434  4851.9 1431.65  4868.8 1431.37  4914.8 1432.44
  4957.4 1430.33    4986 1429.51  4988.3 1428.01  4988.8 1427.51  4993.9 1427.51
  4994.4 1428.01  4995.7 1429.42  5006.6 1429.67  5013.5 1432.11    5024 1433.34
  5033.6 1433.44    5045  1431.6  5083.7 1431.83  5099.4 1432.25  5200.4 1434.15
  5380.6 1434.33  5431.8 1435.15  5443.6 1436.13  5485.5  1436.2  5554.3 1437.92
#Mann= 8 ,-1 , 0
  4432.5     .12       0  4622.7    .035       0  4629.7     .07       0
  4957.4    .035       0  4988.3    .035       0  4994.4    .035       0
  5083.7     .07       0  5099.4    .035       0
Bank Sta=4988.3,4994.4
XS Rating Curve= 0 ,0
Exp/Cntr=0.3,0.1

Type RM Length L Ch R = 1 ,3598    ,899,899,899
BEGIN DESCRIPTION:
Stream0139_DS 5.0
END DESCRIPTION:
XS GIS Cut Line= 3
      2035409.77     13870342.94       2036010.7     13870740.07
      2036458.15     13870819.24
#Sta/Elev= 30
  4279.7 1441.96  4307.3  1437.8  4328.4 1436.22  4393.8 1436.63  4561.8 1432.89
  4581.2 1430.06  4587.2  1426.7  4596.2 1425.75  4602.2 1422.62  4638.3  1416.8
  4701.5 1415.41    4702 1414.91  4707.7 1415.41  4729.5 1415.63    4737 1415.62
  4782.8 1418.24    4834 1428.01  4870.1 1428.68  4921.3  1428.4  4978.5 1424.29
  4993.2 1422.37  4999.5 1417.83  5004.7    1417  5024.7 1421.38    5045 1422.84
  5065.3 1428.47  5091.3 1429.05  5136.4 1432.15    5231 1431.33  5454.4 1433.61
#Mann= 8 ,-1 , 0
  4279.7     .07       0  4307.3    .035       0  4561.8     .07       0
  4701.5     .05       0  4707.7     .07       0  4729.5     .12       0
    4737     .07       0  5091.3    .035       0
Bank Sta=4701.5,4707.7
XS Rating Curve= 0 ,0
Exp/Cntr=0.3,0.1

Type RM Length L Ch R = 1 ,2699    ,526,526,526
BEGIN DESCRIPTION:
Stream0139_DS 4.0
END DESCRIPTION:
XS GIS Cut Line= 4
      2035334.18      13870956.3      2035652.32     13871148.52
      2035895.41     13871161.77      2036212.36     13870968.85
#Sta/Elev= 30
  4628.3 1438.23  4635.3  1438.6  4664.3 1435.04    4709 1432.37  4722.7 1430.33
  4773.1 1427.07  4794.4 1426.57  4807.6 1425.04  4852.6 1421.71  4910.8  1420.1
  4926.4 1420.37  4956.4 1418.78  4984.6 1416.09  5012.7 1415.82  5022.4 1415.07
  5027.5 1413.44  5029.6 1411.21  5030.1 1410.71  5035.9 1411.21  5042.7 1414.38
  5058.9 1420.03  5072.8 1423.37  5092.8 1425.46  5157.4 1426.51    5203 1427.67
    5223 1425.67  5269.2 1428.18  5290.5 1427.56  5406.9 1427.77  5614.5 1430.32
#Mann= 6 ,-1 , 0
  4628.3     .07       0  4807.6     .12       0  5029.6     .05       0
  5035.9     .12       0  5058.9     .07       0  5157.4    .035       0
Bank Sta=5029.6,5035.9
XS Rating Curve= 0 ,0
Exp/Cntr=0.3,0.1

Type RM Length L Ch R = 1 ,2173    ,542,542,542
BEGIN DESCRIPTION:
Stream0139_DS 3.0
END DESCRIPTION:
XS GIS Cut Line= 3
      2034874.42     13871415.33      2035274.16     13871464.94
      2035779.81      13871308.5
#Sta/Elev= 30
  4597.2  1449.2  4658.2 1445.71  4698.5 1441.96    4775 1437.79  4800.9 1435.81
  4819.5 1435.77  4839.6 1433.96  4859.8  1430.5  4876.8 1430.49  4881.9 1428.86
  4910.2 1429.06  4930.3 1427.52  4950.5 1423.64  4955.2  1421.2  4962.8 1418.33
  4970.6 1412.75  4977.4 1409.88  4977.9 1409.38    4984 1409.88  4990.8 1411.26
  5011.4 1410.32  5016.6 1411.68  5032.3 1412.73  5049.3 1415.46  5156.9  1416.7
  5217.6 1417.18  5283.3 1419.98  5325.9 1422.65  5398.7 1425.21  5529.3 1426.64
#Mann= 7 ,-1 , 0
  4597.2    .035       0    4775     .07       0  4955.2     .12       0
  4977.4     .05       0    4984     .12       0  5156.9    .035       0
  5283.3     .07       0
#XS Ineff= 2 , 0
       0                 5049.95       0 1417.09
Permanent Ineff=
       F       F
Bank Sta=4977.4,4984
XS Rating Curve= 0 ,0
Exp/Cntr=0.3,0.1

Type RM Length L Ch R = 1 ,1631    ,412,412,412
BEGIN DESCRIPTION:
Stream0139_DS 2.0
END DESCRIPTION:
XS GIS Cut Line= 3
       2034907.9     13871661.64      2035617.67     13871781.37
      2035721.15     13871766.07
#Sta/Elev= 30
  4280.2 1442.27  4331.7 1439.02    4363  1435.6  4387.2 1432.52  4392.2  1433.1
  4480.1 1424.72  4591.6 1417.57  4642.3 1415.18  4689.6 1414.65  4694.6 1413.88
  4733.6 1413.92  4755.1 1412.74    4837 1411.03    4871  1410.6  4885.7 1409.53
  4931.5 1409.41  4971.7 1407.39    4977 1407.06  4986.9  1404.8  4988.6 1402.79
  4989.1 1402.29  4995.3 1402.79    5000 1403.13  5005.9 1405.85  5010.9 1403.21
  5027.6  1408.4  5037.7 1414.03  5047.8  1418.6  5057.9 1420.59  5104.6  1421.3
#Mann= 6 ,-1 , 0
  4280.2    .035       0    4363     .07       0    4837     .12       0
  4971.7    .035       0  4988.6    .035       0  4995.3    .035       0
Bank Sta=4988.6,4995.3
XS Rating Curve= 0 ,0
Exp/Cntr=0.3,0.1

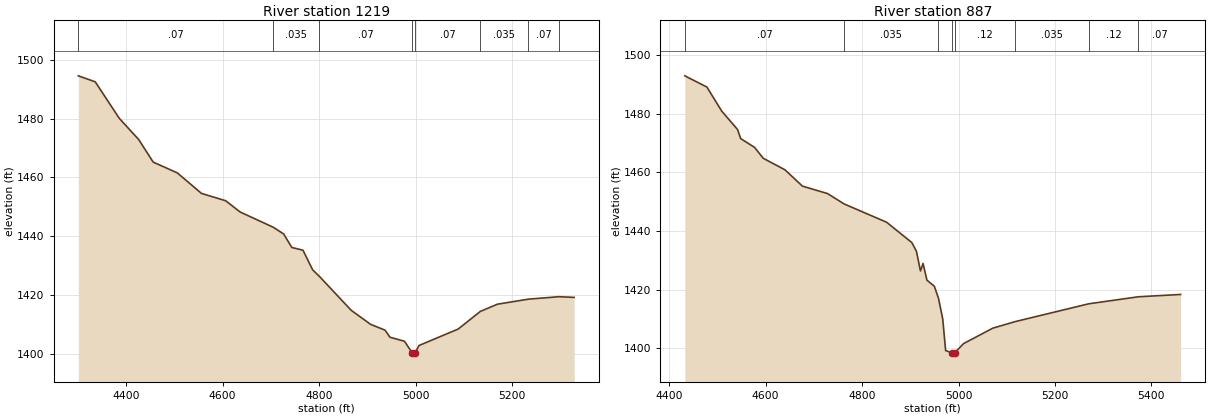
Type RM Length L Ch R = 1 ,1219    ,332,332,332
BEGIN DESCRIPTION:
Stream0139_DS 1.0
END DESCRIPTION:
XS GIS Cut Line= 3
      2034560.05      13871909.7      2035258.32     13871941.64
      2035581.25     13872000.81
#Sta/Elev= 30
    4301 1494.56    4336 1492.53    4386 1480.08  4426.1  1472.9  4456.1 1465.23
  4506.2 1461.55  4556.2 1454.58  4606.3  1452.1  4636.3 1448.26  4704.8 1443.09
  4726.4  1440.8  4743.3 1436.21  4766.4 1435.29  4786.5 1428.61  4800.3 1426.41
  4866.5 1414.83  4906.6 1410.07  4936.6 1408.09  4946.6  1405.7  4976.7 1404.33
  4992.5 1400.45    4993 1399.95  4999.2 1400.45  5006.8 1402.88  5088.1 1408.48
  5133.9 1414.47  5169.5 1416.93  5233.6 1418.64  5296.8 1419.47  5328.3 1419.24
#Mann= 8 ,-1 , 0
    4301     .07       0  4704.8    .035       0  4800.3     .07       0
  4992.5     .05       0  4999.2     .07       0  5133.9    .035       0
  5233.6     .07       0  5296.8     .12       0
Bank Sta=4992.5,4999.2
XS Rating Curve= 0 ,0
Exp/Cntr=0.3,0.1

Type RM Length L Ch R = 1 ,887     ,0,0,0
BEGIN DESCRIPTION:
Stream0139_DS 0.0
END DESCRIPTION:
XS GIS Cut Line= 3
      2034604.79     13871993.12      2035124.98     13872220.45
      2035568.16      13872094.6
#Sta/Elev= 30
  4432.3 1492.88  4478.1 1489.06  4508.9 1480.85  4541.7 1474.58  4548.2 1471.48
  4577.1 1468.47    4595 1464.76  4639.9 1460.85  4676.2 1455.28  4728.4 1452.72
    4763 1449.17  4850.9 1442.95  4903.1 1436.03  4912.7 1433.09  4921.1 1426.34
  4926.5 1428.88  4934.5 1423.21  4949.9 1421.12  4958.5 1417.02  4967.3 1409.96
  4973.3 1399.19  4985.8 1398.47  4986.3 1397.97  4992.5 1398.47  5010.4 1401.55
  5071.2 1406.83  5118.1 1409.08  5269.7 1415.12  5373.1 1417.53  5460.7 1418.32
#Mann= 8 ,-1 , 0
  4432.3     .07       0    4763    .035       0  4958.5     .12       0
  4985.8     .05       0  4992.5     .12       0  5118.1    .035       0
  5269.7     .12       0  5373.1     .07       0
Bank Sta=4985.8,4992.5
XS Rating Curve= 0 ,0
Exp/Cntr=0.3,0.1

Chan Stop Cuts=-1
Use User Specified Reach Order=0
Composite Channel Slope=5