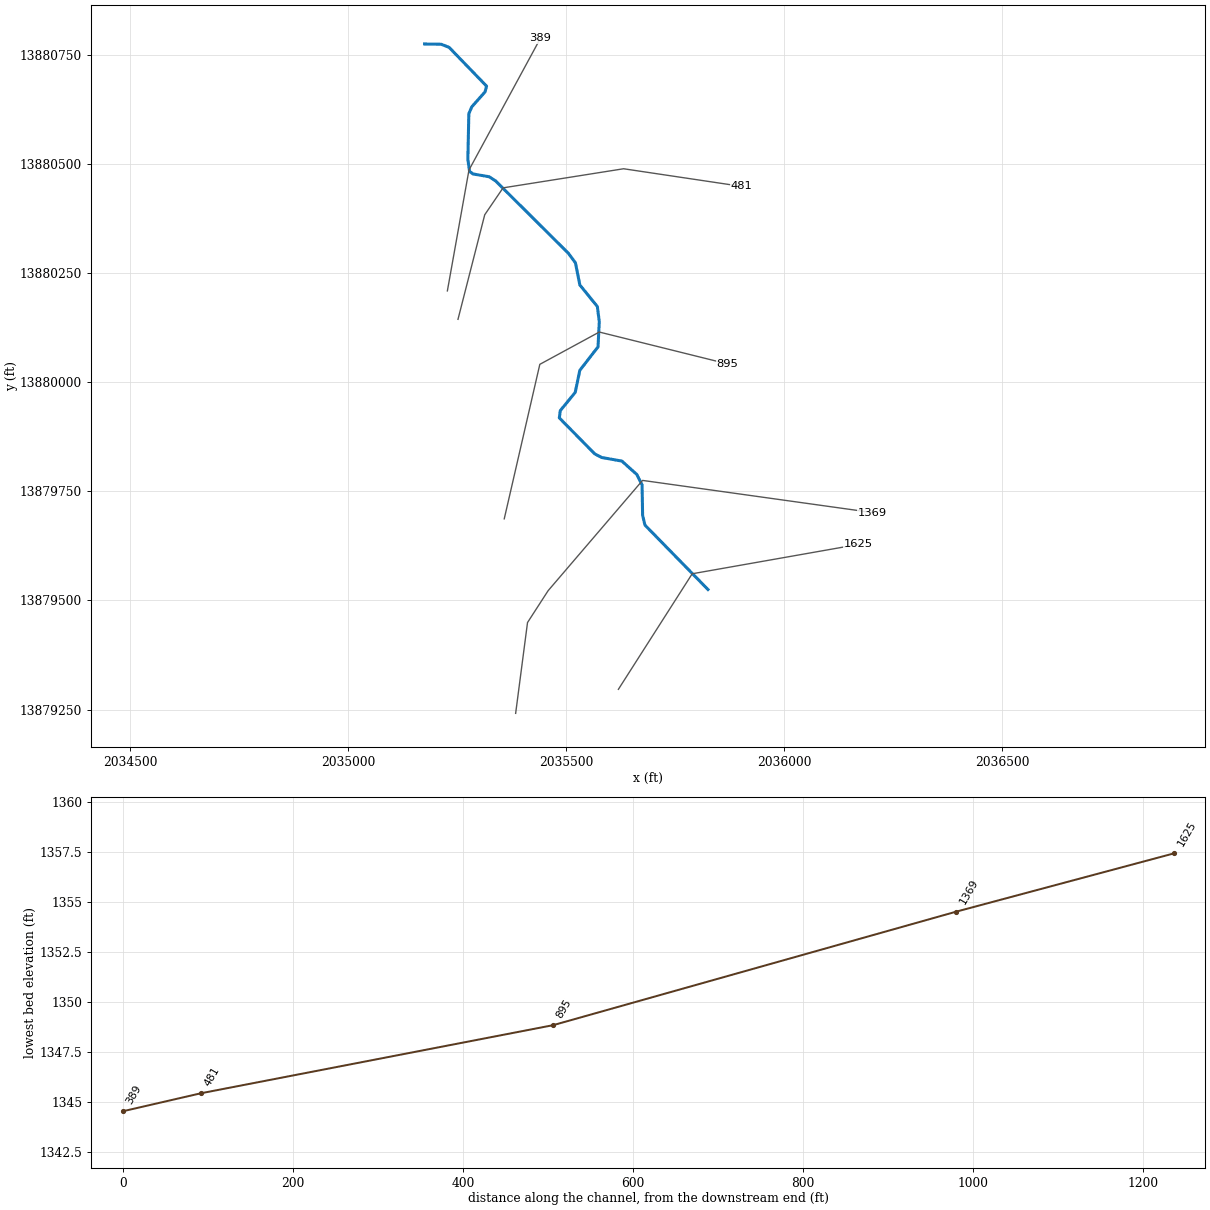
--- Stream0140_DS.prj (project) ---

Proj Title=Stream0140_DS Base Level Engineering
Current Plan=p01
Default Exp/Contr=0.3,0.1
English Units
Geom File=g01
Flow File=f01
Plan File=p01
Y Axis Title=Elevation
X Axis Title(PF)=Main Channel Distance
X Axis Title(XS)=Station
BEGIN DESCRIPTION:
Stream0140_DS
END DESCRIPTION:
DSS Export Rating Curves= 0
DSS Export Rating Curve Sorted= 0
DSS Export Volume Flow Curves= 0
DXF OffsetX= 0
DXF OffsetY= 0
DXF ScaleX= 1
DXF ScaleY= 10

--- Stream0140_DS.p01 (plan) ---

Plan Title=Multiple Run
Short Identifier=Multiple
Geom File=g01
Flow File=f01
Subcritical Flow
K Sum by GR= 0
Std Step Tol= 0.01
Critical Tol= 0.01
Num of Std Step Trials= 20
Max Error Tol= 0.3
Flow Tol Ratio= 0.001
Split Flow NTrial= 30
Split Flow Tol= 0.02
Split Flow Ratio= 0.02
Log Output Level= 0
Friction Slope Method= 1
Unsteady Friction Slope Method= 2
Unsteady Bridges Friction Slope Method= 1
Parabolic Critical Depth
Global Vel Dist=  1 , 1 , 1
Global Log Level= 0
CheckData=True
Encroach Param= -1, 0, 0, 0
BEGIN DESCRIPTION:
Multiple Run
END DESCRIPTION:

--- Stream0140_DS.f01 (steady flow) ---

Flow Title=Multiple
Number of Profiles=7
Profile Names=10-year,25-year,50-year,1pct_min,100-year,1pct_plu,500-year
River Rch & RM= Stream0140_DS,Reach-1,1625
    1283    2187    3051    2062    4115    8210    7403
Boundary for River Rch & Prof#=Stream0140_DS,Reach-1,1
Up Type=0
Dn Type=3
Dn Slope=0.005
Boundary for River Rch & Prof#=Stream0140_DS,Reach-1,2
Up Type=0
Dn Type=3
Dn Slope=0.005
Boundary for River Rch & Prof#=Stream0140_DS,Reach-1,3
Up Type=0
Dn Type=3
Dn Slope=0.005
Boundary for River Rch & Prof#=Stream0140_DS,Reach-1,4
Up Type=0
Dn Type=3
Dn Slope=0.005
Boundary for River Rch & Prof#=Stream0140_DS,Reach-1,5
Up Type=0
Dn Type=3
Dn Slope=0.005
Boundary for River Rch & Prof#=Stream0140_DS,Reach-1,6
Up Type=0
Dn Type=3
Dn Slope=0.005
Boundary for River Rch & Prof#=Stream0140_DS,Reach-1,7
Up Type=0
Dn Type=3
Dn Slope=0.005

--- Stream0140_DS.g01 (geometry) ---

Geom Title=Existing Conditions
Program Version=4.10

River Reach=Stream0140_DS   ,Reach-1
Reach XY= 30
        2035825.       13879525.      2035680.52     13879672.57
      2035675.14     13879695.06       2035673.9     13879764.67
      2035661.74     13879788.65      2035627.57     13879819.26
      2035581.07     13879827.55      2035565.29     13879835.79
       2035484.1     13879918.25      2035486.27     13879934.86
      2035520.57     13879976.63      2035531.09     13880027.17
      2035572.86     13880080.97      2035575.74      13880138.7
      2035571.33     13880173.42      2035531.15     13880222.83
      2035521.06     13880273.37      2035505.22     13880295.09
      2035337.95     13880461.26      2035322.91     13880470.84
      2035285.99      13880477.2      2035278.22     13880483.01
      2035274.31     13880510.82      2035276.54     13880615.39
      2035283.46     13880631.19      2035313.68     13880665.16
      2035317.23     13880678.43      2035231.27     13880767.24
      2035213.18     13880774.41        2035175.       13880775.

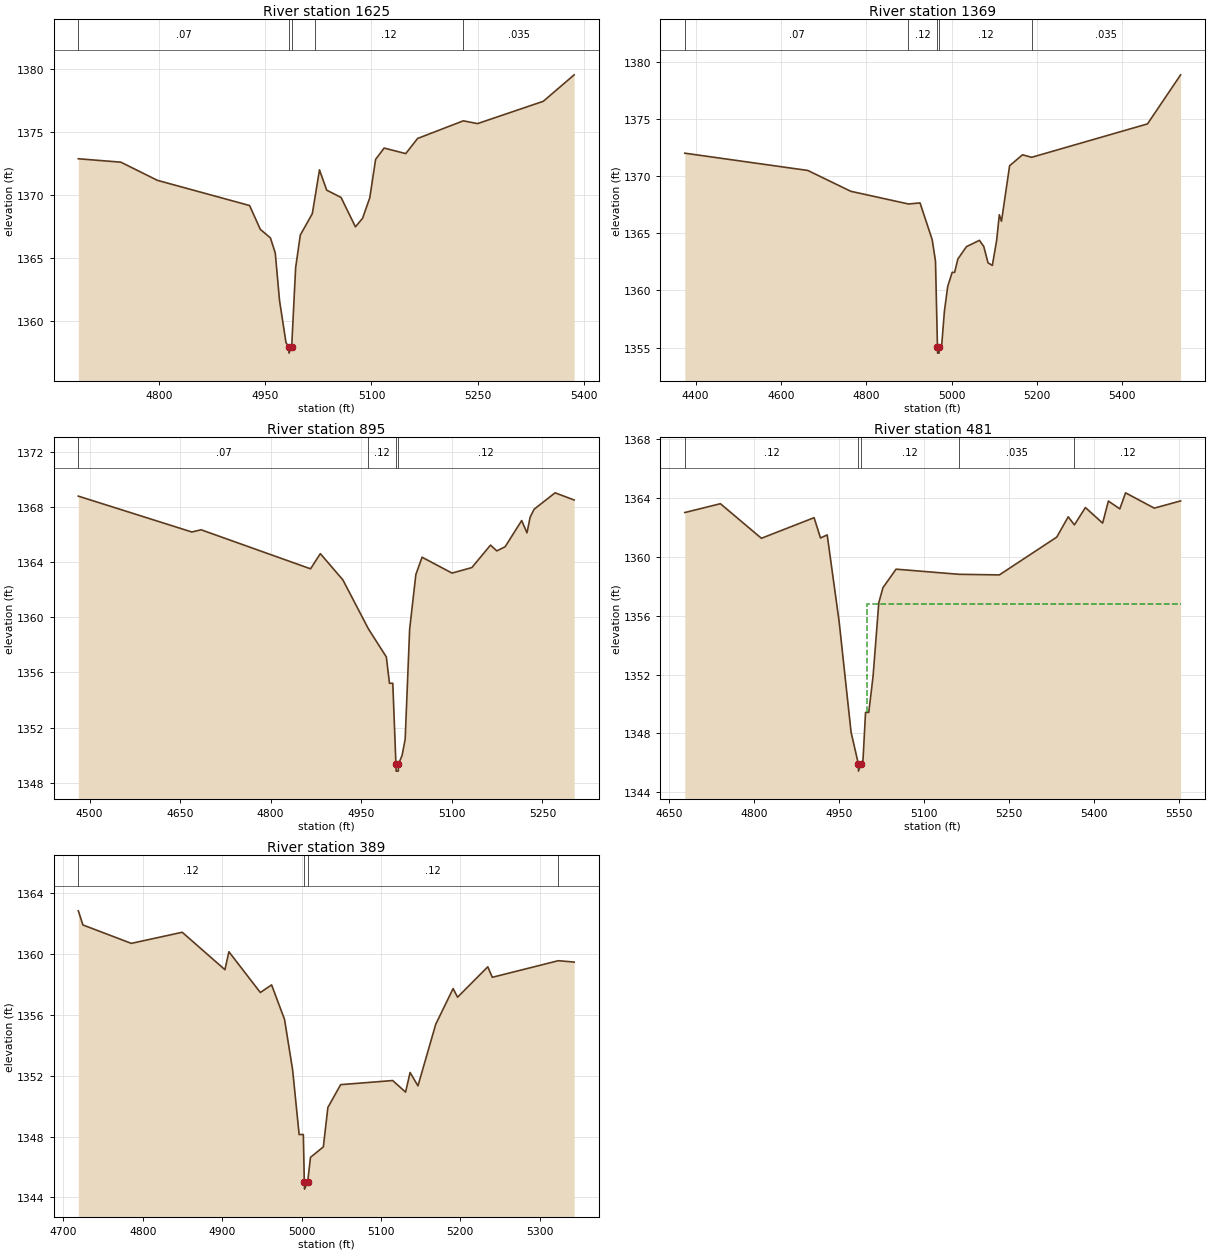
Type RM Length L Ch R = 1 ,1625    ,256,256,256
BEGIN DESCRIPTION:
Stream140_DS 3.0
END DESCRIPTION:
XS GIS Cut Line= 3
      2035619.57     13879296.28      2035788.88     13879561.07
      2036169.41      13879628.2
#Sta/Elev= 30
  4685.7 1372.84  4745.8 1372.57  4797.4 1371.13  4927.7 1369.13  4942.9 1367.24
  4957.2 1366.56    4964 1365.37    4970 1361.61  4979.2 1358.25  4983.2 1357.92
  4983.4 1357.42  4987.2 1357.92  4992.8  1364.2  4999.4 1366.79  5016.4 1368.49
  5019.8 1369.66  5026.5 1371.96  5036.7 1370.35    5057 1369.77  5077.3 1367.44
  5087.4 1368.12  5097.6 1369.75  5105.8 1372.79  5117.9 1373.69  5148.4 1373.25
  5165.1 1374.45  5229.8 1375.85  5249.9 1375.63  5342.8  1377.4  5386.4  1379.5
#Mann= 5 ,-1 , 0
  4685.7     .07       0  4983.2     .05       0  4987.2     .07       0
  5019.8     .12       0  5229.8    .035       0
Bank Sta=4983.2,4987.2
XS Rating Curve= 0 ,0
Exp/Cntr=0.3,0.1

Type RM Length L Ch R = 1 ,1369    ,474,474,474
BEGIN DESCRIPTION:
Stream140_DS 2.0
END DESCRIPTION:
XS GIS Cut Line= 5
      2035383.91     13879241.18      2035411.13     13879449.29
       2035458.4     13879522.31        2035675.       13879775.
       2036201.9     13879701.42
#Sta/Elev= 30
  4374.7 1371.99  4662.9 1370.48  4763.5 1368.66  4898.7 1367.55  4925.9 1367.64
  4954.4 1364.42  4962.1 1362.54  4966.7 1355.01    4967 1354.51  4970.5 1354.51
  4970.8 1355.01  4976.4  1355.1    4983 1358.19  4990.7 1360.34  5001.1 1361.57
  5006.9 1361.57  5014.5 1362.74  5034.7 1363.82    5065 1364.37  5075.1 1363.84
  5085.2  1362.4  5095.3 1362.18  5105.4 1364.38  5111.6 1366.61  5116.7 1366.04
  5135.7 1370.89  5165.9 1371.85  5187.4 1371.63  5458.8 1374.55  5536.4 1378.84
#Mann= 5 ,-1 , 0
  4374.7     .07       0  4898.7     .12       0  4966.7     .05       0
  4970.8     .12       0  5187.4    .035       0
Bank Sta=4966.7,4970.8
XS Rating Curve= 0 ,0
Exp/Cntr=0.3,0.1

Type RM Length L Ch R = 1 ,895     ,414,414,414
BEGIN DESCRIPTION:
Stream140_DS 1.0
END DESCRIPTION:
XS GIS Cut Line= 4
      2035357.76     13879686.92      2035439.36     13880040.94
      2035575.78     13880114.95      2035869.38     13880042.09
#Sta/Elev= 30
  4481.5 1368.78  4669.5 1366.18  4684.8 1366.34    4866 1363.51  4882.2 1364.61
  4919.5 1362.71  4961.9 1359.15  4991.5 1357.12  4996.7 1355.21  5002.2 1355.21
  5007.4 1349.34  5007.7 1348.84  5011.3 1348.84  5011.5 1349.34  5017.6 1349.98
  5022.7 1351.16  5030.1 1359.13  5040.4  1363.1  5050.7 1364.35  5100.3  1363.2
  5133.1  1363.6    5164 1365.23  5174.4 1364.81  5188.2 1365.11  5215.6 1367.01
  5224.4 1366.12  5229.6 1367.25  5236.2 1367.83  5270.9 1369.02  5302.5  1368.5
#Mann= 4 ,-1 , 0
  4481.5     .07       0  4961.9     .12       0  5007.4     .05       0
  5011.5     .12       0
Bank Sta=5007.4,5011.5
XS Rating Curve= 0 ,0
Exp/Cntr=0.3,0.1

Type RM Length L Ch R = 1 ,481     ,92,92,92
BEGIN DESCRIPTION:
Stream140_DS 0.1
END DESCRIPTION:
XS GIS Cut Line= 5
      2035251.67     13880144.14      2035312.98     13880383.63
      2035355.05     13880445.34      2035631.49      13880489.1
      2035901.03     13880448.89
#Sta/Elev= 30
  4678.1 1363.02  4740.9 1363.62  4813.2 1361.27  4906.1 1362.67  4917.4 1361.29
  4929.2  1361.5  4950.3 1355.59  4971.3 1348.09  4984.1 1345.94  4984.4 1345.44
  4988.4 1345.94  4992.3 1346.17  4996.8 1349.43  5002.5 1349.43  5010.1  1351.9
  5020.2 1356.89  5027.5 1357.91  5050.6 1359.17  5161.8 1358.82  5232.8 1358.78
    5334 1361.35  5354.2 1362.73  5365.1 1362.18  5384.5 1363.36  5414.9  1362.3
    5425  1363.8  5445.2 1363.27  5455.3 1364.36  5505.9 1363.32  5552.4 1363.81
#Mann= 5 ,-1 , 0
  4678.1     .12       0  4984.1     .05       0  4988.4     .12       0
  5161.8    .035       0  5365.1     .12       0
#XS Ineff= 2 , 0
       0                    5000       0 1356.81
Permanent Ineff=
       F       F
Bank Sta=4984.1,4988.4
XS Rating Curve= 0 ,0
Exp/Cntr=0.3,0.1

Type RM Length L Ch R = 1 ,389     ,0,0,0
BEGIN DESCRIPTION:
Stream140_DS 0.0
END DESCRIPTION:
XS GIS Cut Line= 3
      2035227.31     13880209.24      2035276.83     13880486.15
      2035440.67     13880787.95
#Sta/Elev= 30
  4718.7 1362.84  4724.5 1361.91  4785.5  1360.7  4849.6 1361.43  4903.4 1358.97
  4908.4 1360.15    4948 1357.47  4962.2 1357.97  4978.5  1355.7  4988.7 1352.38
  4996.9 1348.13  5002.2 1348.13  5003.4 1345.04  5003.7 1344.54  5007.7 1345.04
  5011.2 1346.63  5027.4 1347.32  5033.1 1349.91  5049.2 1351.41  5114.8 1351.68
    5131 1350.92  5136.7 1352.21  5146.6 1351.33    5169 1355.38  5190.9 1357.73
  5196.5 1357.16  5234.6 1359.16  5240.3 1358.47  5323.4 1359.56  5343.4 1359.47
#Mann= 4 ,-1 , 0
  4718.7     .12       0  5003.4     .05       0  5007.7     .12       0
  5323.4    .035       0
Bank Sta=5003.4,5007.7
XS Rating Curve= 0 ,0
Exp/Cntr=0.3,0.1

Chan Stop Cuts=-1
Use User Specified Reach Order=0
Composite Channel Slope=5