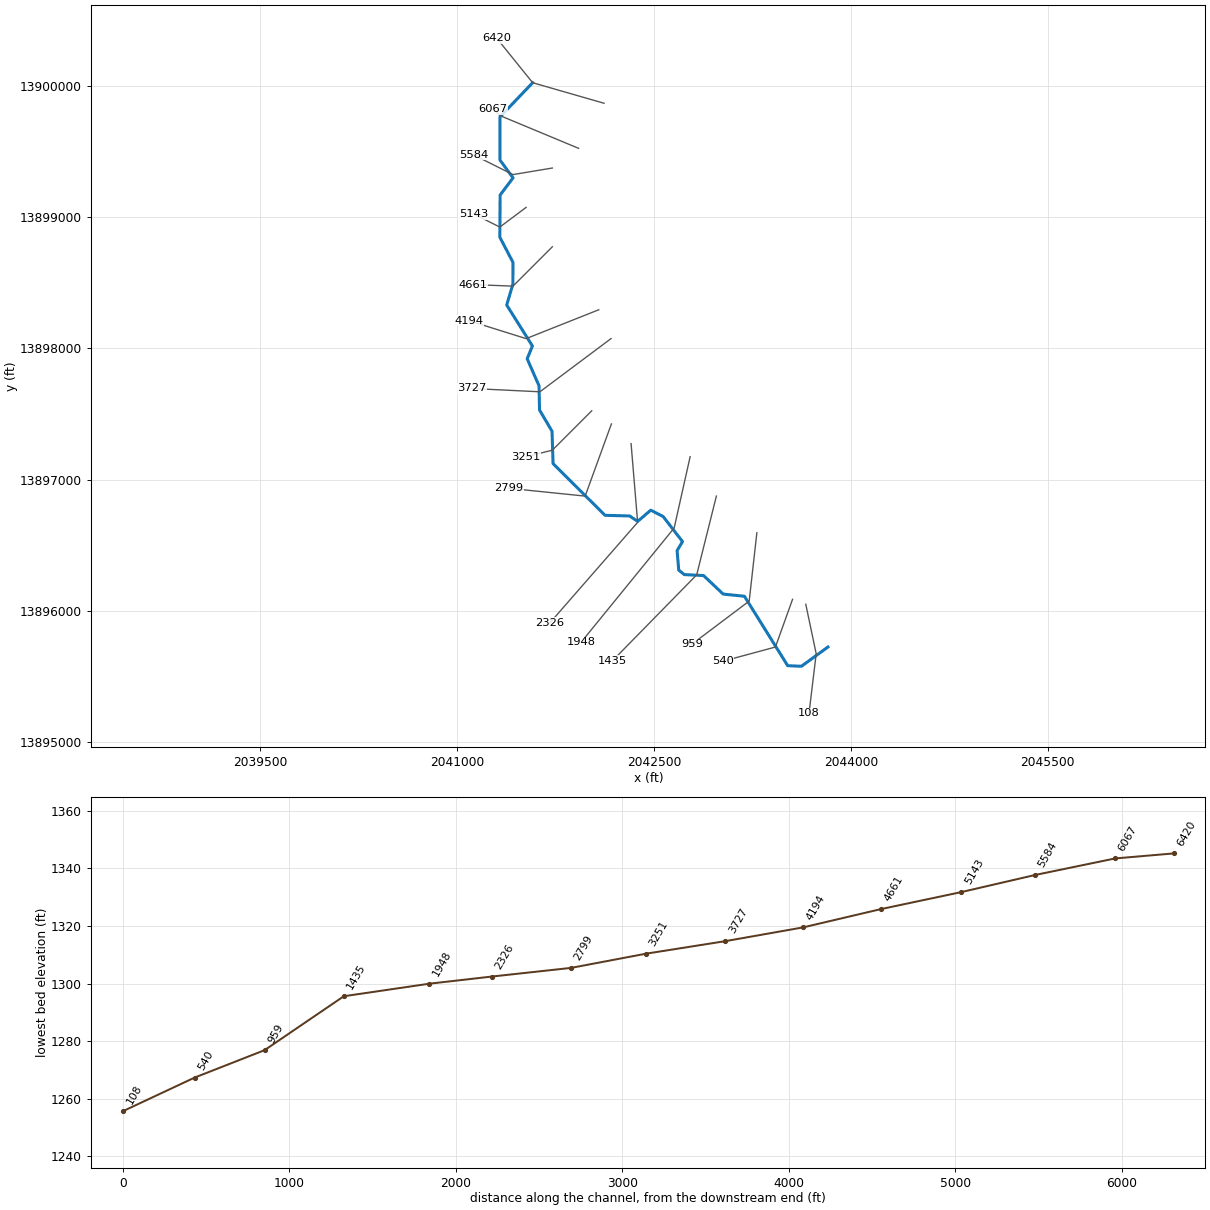
--- Stream0141_DS.prj (project) ---

Proj Title=Stream0141_DS Base Level Engineering
Current Plan=p01
Default Exp/Contr=0.3,0.1
English Units
Geom File=g01
Flow File=f01
Plan File=p01
BEGIN DESCRIPTION:
Stream0141_DS
END DESCRIPTION:

--- Stream0141_DS.p01 (plan) ---

Plan Title=Multiple Run
Short Identifier=Multiple
Geom File=g01
Flow File=f01
Subcritical Flow
K Sum by GR= 0
Std Step Tol= 0.01
Critical Tol= 0.01
Num of Std Step Trials= 20
Max Error Tol= 0.3
Flow Tol Ratio= 0.001
Split Flow NTrial= 30
Split Flow Tol= 0.02
Split Flow Ratio= 0.02
Log Output Level= 0
Friction Slope Method= 1
Unsteady Friction Slope Method= 2
Unsteady Bridges Friction Slope Method= 1
Parabolic Critical Depth
Global Vel Dist=  1 , 1 , 1
Global Log Level= 0
CheckData=True
Encroach Param= -1, 0, 0, 0
BEGIN DESCRIPTION:
Multiple Run
END DESCRIPTION:

--- Stream0141_DS.f01 (steady flow) ---

Flow Title=Multiple
Number of Profiles=7
Profile Names=10-year,25-year,50-year,1pct_min,100-year,1pct_plu,500-year
River Rch & RM= Stream0141_DS,Reach-1,6420
     927    1551    2139    1431    2856    5698    5029
River Rch & RM= Stream0141_DS,Reach-1,6067
    1348    2301    3215    2174    4338    8656    7816
Boundary for River Rch & Prof#=Stream0141_DS,Reach-1,1
Up Type=0
Dn Type=3
Dn Slope=0.005
Boundary for River Rch & Prof#=Stream0141_DS,Reach-1,2
Up Type=0
Dn Type=3
Dn Slope=0.005
Boundary for River Rch & Prof#=Stream0141_DS,Reach-1,3
Up Type=0
Dn Type=3
Dn Slope=0.005
Boundary for River Rch & Prof#=Stream0141_DS,Reach-1,4
Up Type=0
Dn Type=3
Dn Slope=0.005
Boundary for River Rch & Prof#=Stream0141_DS,Reach-1,5
Up Type=0
Dn Type=3
Dn Slope=0.005
Boundary for River Rch & Prof#=Stream0141_DS,Reach-1,6
Up Type=0
Dn Type=3
Dn Slope=0.005
Boundary for River Rch & Prof#=Stream0141_DS,Reach-1,7
Up Type=0
Dn Type=3
Dn Slope=0.005

--- Stream0141_DS.g01 (geometry) ---

Geom Title=Existing Conditions

River Reach=Stream0141_DS,Reach-1
Reach XY= 30
      2041575.00     13900025.00      2041326.05     13899764.57
      2041326.06     13899435.44      2041425.58     13899300.00
      2041327.07     13899169.14      2041324.89     13898847.68
      2041424.80     13898656.73      2041424.48     13898490.22
      2041377.14     13898330.97      2041573.16     13898018.88
      2041533.10     13897921.71      2041623.62     13897715.34
      2041627.24     13897530.93      2041722.65     13897369.48
      2041730.46     13897122.55      2042126.46     13896728.54
      2042314.57     13896723.61      2042375.10     13896682.34
      2042474.94     13896767.70      2042569.37     13896719.41
      2042716.97     13896528.35      2042675.64     13896459.83
      2042688.19     13896311.26      2042730.65     13896276.98
      2042877.45     13896269.53      2043026.47     13896128.54
      2043188.67     13896111.77      2043518.55     13895582.64
      2043623.50     13895578.47      2043825.00     13895725.00

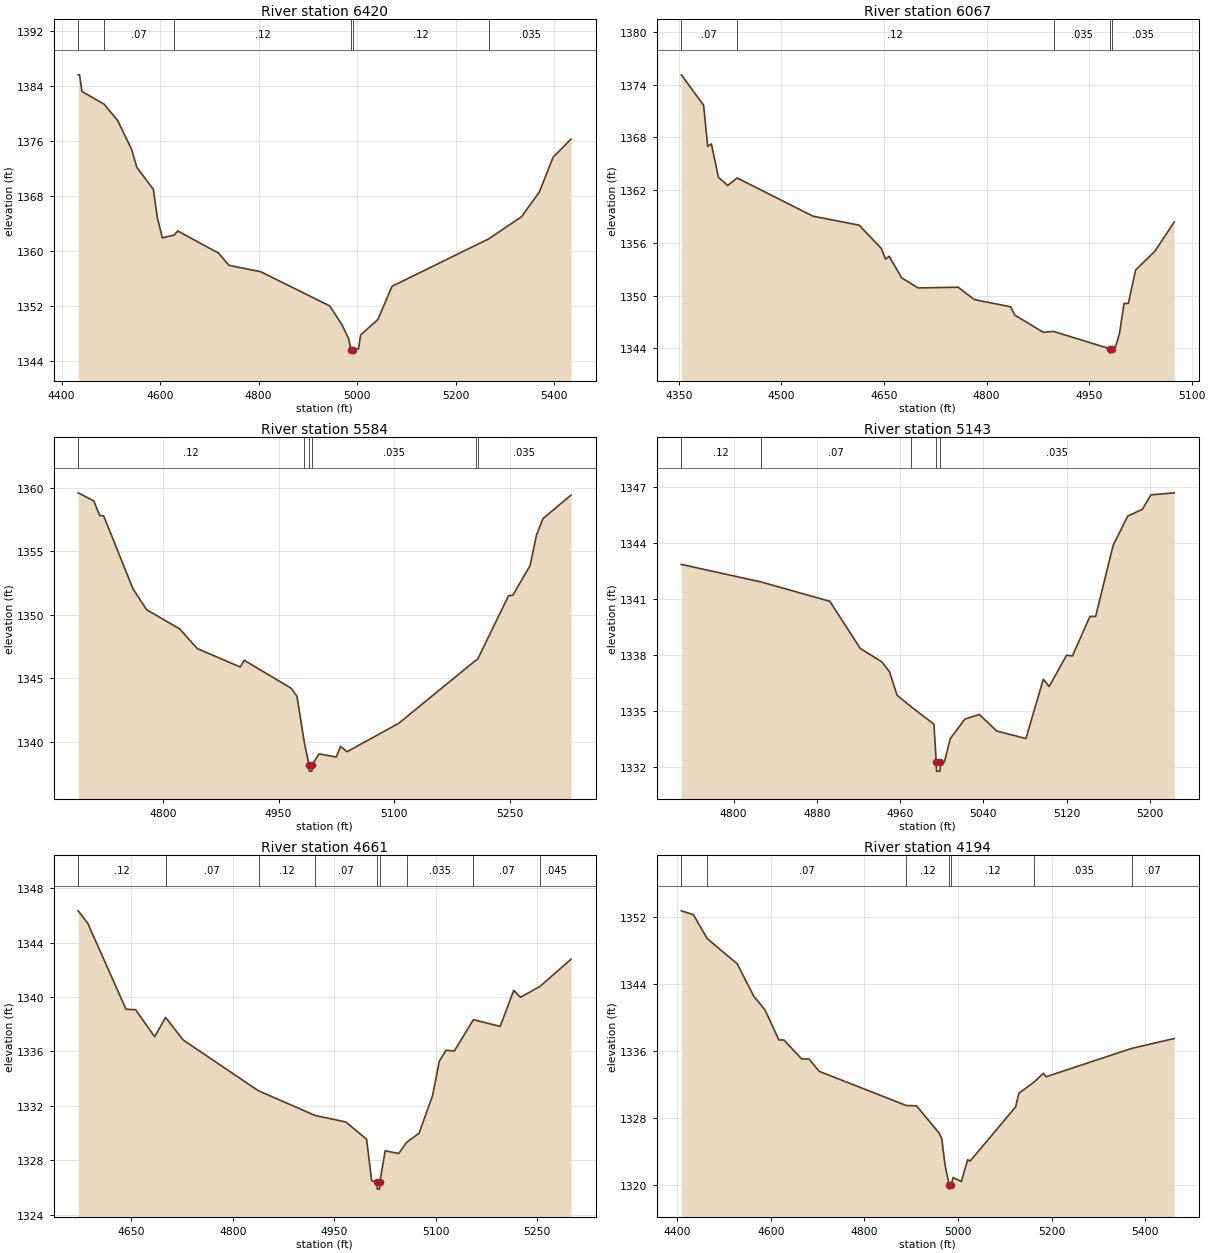
Type RM Length L Ch R = 1,6420,353,353,353
BEGIN DESCRIPTION:
Stream0141_DS 14.0
END DESCRIPTION:
XS GIS Cut Line= 3
      2042119.24     13899868.47      2041575.00     13900025.00
      2041302.11     13900363.24
#Sta/Elev= 30
  4433.7 1385.58  4436.5 1385.58  4441.3 1383.17  4486.7 1381.30  4513.9 1378.95
  4542.2 1374.77  4552.8 1372.16  4586.5 1368.96  4594.2 1364.95  4604.6 1361.93
  4628.8 1362.34  4635.8 1362.94  4719.1 1359.70  4739.9 1357.95  4804.3 1357.02
  4944.3 1352.07  4968.8 1349.40  4983.2 1347.28  4987.6 1345.71  4987.8 1345.21
  4991.6 1345.71  5003.2 1345.85  5007.2 1347.83  5042.4 1350.10  5071.2 1354.91
  5267.3 1361.78  5334.1 1365.00  5370.2 1368.57  5398.3 1373.64  5434.6 1376.26
#Mann=6,-1,0
  4433.7    0.12       0  4486.7    0.07       0  4628.8    0.12       0
  4987.6    0.05       0  4991.6    0.12       0  5267.3   0.035       0
Bank Sta=4987.6,4991.6
Exp/Cntr=0.3,0.1

Type RM Length L Ch R = 1,6067,483,483,483
BEGIN DESCRIPTION:
Stream0141_DS 13.0
END DESCRIPTION:
XS GIS Cut Line= 3
      2041925.03     13899524.99      2041325.00     13899775.00
      2041275.03     13899824.97
#Sta/Elev= 30
  4353.8 1375.13  4386.3 1371.67  4392.3 1366.99  4397.7 1367.27  4408.0 1363.47
  4421.5 1362.54  4435.4 1363.39  4546.1 1359.05  4613.8 1358.02  4646.3 1355.36
  4652.3 1354.16  4657.7 1354.47  4676.1 1352.02  4700.0 1350.88  4758.5 1350.96
  4782.3 1349.55  4835.4 1348.73  4841.3 1347.79  4883.0 1345.83  4898.0 1345.93
  4980.2 1343.96  4980.4 1343.46  4984.2 1343.96  4989.2 1344.27  4994.6 1345.75
  5001.1 1349.12  5007.4 1349.12  5018.0 1352.91  5046.3 1355.06  5074.5 1358.38
#Mann=5,-1,0
  4353.8    0.07       0  4435.4    0.12       0  4898.0   0.035       0
  4980.2   0.035       0  4984.2   0.035       0
Bank Sta=4980.2,4984.2
Exp/Cntr=0.3,0.1

Type RM Length L Ch R = 1,5584,441,441,441
BEGIN DESCRIPTION:
Stream0141_DS 12.0
END DESCRIPTION:
XS GIS Cut Line= 3
      2041725.01     13899375.00      2041425.00     13899325.00
      2041124.96     13899475.02
#Sta/Elev= 30
  4689.9 1359.62  4710.2 1358.98  4717.8 1357.83  4722.9 1357.81  4760.9 1352.07
  4778.6 1350.41  4821.7 1348.89  4844.5 1347.34  4900.3 1345.89  4905.3 1346.42
  4966.2 1344.22  4973.8 1343.59  4983.5 1339.89  4989.5 1338.18  4989.8 1337.68
  4993.3 1337.68  4993.5 1338.18  5002.4 1339.04  5024.8 1338.79  5030.4 1339.63
  5038.8 1339.21  5105.9 1341.45  5206.1 1346.43  5208.3 1346.50  5248.4 1351.51
  5254.0 1351.55  5276.4 1353.88  5284.7 1356.30  5293.1 1357.59  5329.5 1359.44
#Mann=6,-1,0
  4689.9    0.12       0  4983.5   0.035       0  4989.5   0.035       0
  4993.5   0.035       0  5206.1    0.07       0  5208.3   0.035       0
Bank Sta=4989.5,4993.5
Exp/Cntr=0.3,0.1

Type RM Length L Ch R = 1,5143,482,482,482
BEGIN DESCRIPTION:
Stream0141_DS 11.0
END DESCRIPTION:
XS GIS Cut Line= 3
      2041525.00     13899075.00      2041325.00     13898925.00
      2041125.01     13899025.00
#Sta/Elev= 30
  4749.9 1342.86  4826.3 1341.92  4892.6 1340.88  4921.8 1338.35  4942.6 1337.63
  4949.9 1337.10  4957.2 1335.84  4970.1 1335.25  4992.6 1334.29  4994.8 1332.27
  4995.0 1331.77  4998.5 1331.77  4998.8 1332.27  5002.7 1332.27  5008.3 1333.51
  5022.3 1334.56  5036.2 1334.81  5053.0 1333.92  5081.0 1333.52  5097.7 1336.70
  5103.3 1336.31  5120.1 1337.99  5125.7 1337.95  5142.5 1340.07  5148.0 1340.07
  5164.8 1343.88  5178.8 1345.45  5192.8 1345.81  5201.1 1346.59  5223.5 1346.70
#Mann=5,-1,0
  4749.9    0.12       0  4826.3    0.07       0  4970.1   0.035       0
  4994.8   0.035       0  4998.8   0.035       0
Bank Sta=4994.8,4998.8
Exp/Cntr=0.3,0.1

Type RM Length L Ch R = 1,4661,467,467,467
BEGIN DESCRIPTION:
Stream0141_DS 10.0
END DESCRIPTION:
XS GIS Cut Line= 3
      2041725.03     13898775.03      2041425.00     13898475.00
      2041120.24     13898486.79
#Sta/Elev= 30
  4571.2 1346.34  4585.4 1345.42  4642.0 1339.10  4656.1 1339.07  4684.4 1337.08
  4700.5 1338.50  4726.8 1336.83  4838.1 1333.10  4922.2 1331.28  4967.2 1330.81
  4998.0 1329.54  5005.5 1326.49  5013.5 1326.37  5013.8 1325.87  5017.3 1325.87
  5017.5 1326.37  5025.5 1328.69  5045.5 1328.49  5057.2 1329.31  5075.6 1329.98
  5095.6 1332.75  5105.6 1335.28  5115.6 1336.08  5127.8 1336.03  5156.0 1338.33
  5195.7 1337.84  5215.7 1340.49  5225.7 1339.98  5254.8 1340.79  5300.5 1342.78
#Mann=9,-1,0
  4571.2    0.12       0  4700.5    0.07       0  4838.1    0.12       0
  4922.2    0.07       0  5013.5    0.05       0  5017.5    0.07       0
  5057.2   0.035       0  5156.0    0.07       0  5254.8   0.045       0
Bank Sta=5013.5,5017.5
Exp/Cntr=0.3,0.1

Type RM Length L Ch R = 1,4194,467,467,467
BEGIN DESCRIPTION:
Stream0141_DS 9.0
END DESCRIPTION:
XS GIS Cut Line= 3
      2042078.72     13898294.93      2041525.00     13898075.00
      2041088.23     13898211.86
#Sta/Elev= 30
  4408.8 1352.76  4434.3 1352.31  4464.2 1349.43  4528.1 1346.44  4563.4 1342.58
  4587.5 1340.93  4617.2 1337.34  4628.0 1337.33  4665.8 1335.08  4681.8 1335.06
  4703.3 1333.59  4889.6 1329.51  4911.5 1329.47  4960.1 1326.19  4965.4 1325.53
  4972.3 1322.47  4981.1 1320.02  4981.3 1319.52  4985.1 1320.02  4989.8 1320.91
  5007.2 1320.42  5020.8 1323.04  5026.1 1322.87  5123.4 1329.35  5130.3 1330.98
  5162.4 1332.29  5182.7 1333.36  5188.3 1332.94  5371.0 1336.32  5462.3 1337.51
#Mann=7,-1,0
  4408.8    0.12       0  4464.2    0.07       0  4889.6    0.12       0
  4981.1    0.05       0  4985.1    0.12       0  5162.4   0.035       0
  5371.0    0.07       0
Bank Sta=4981.1,4985.1
Exp/Cntr=0.3,0.1

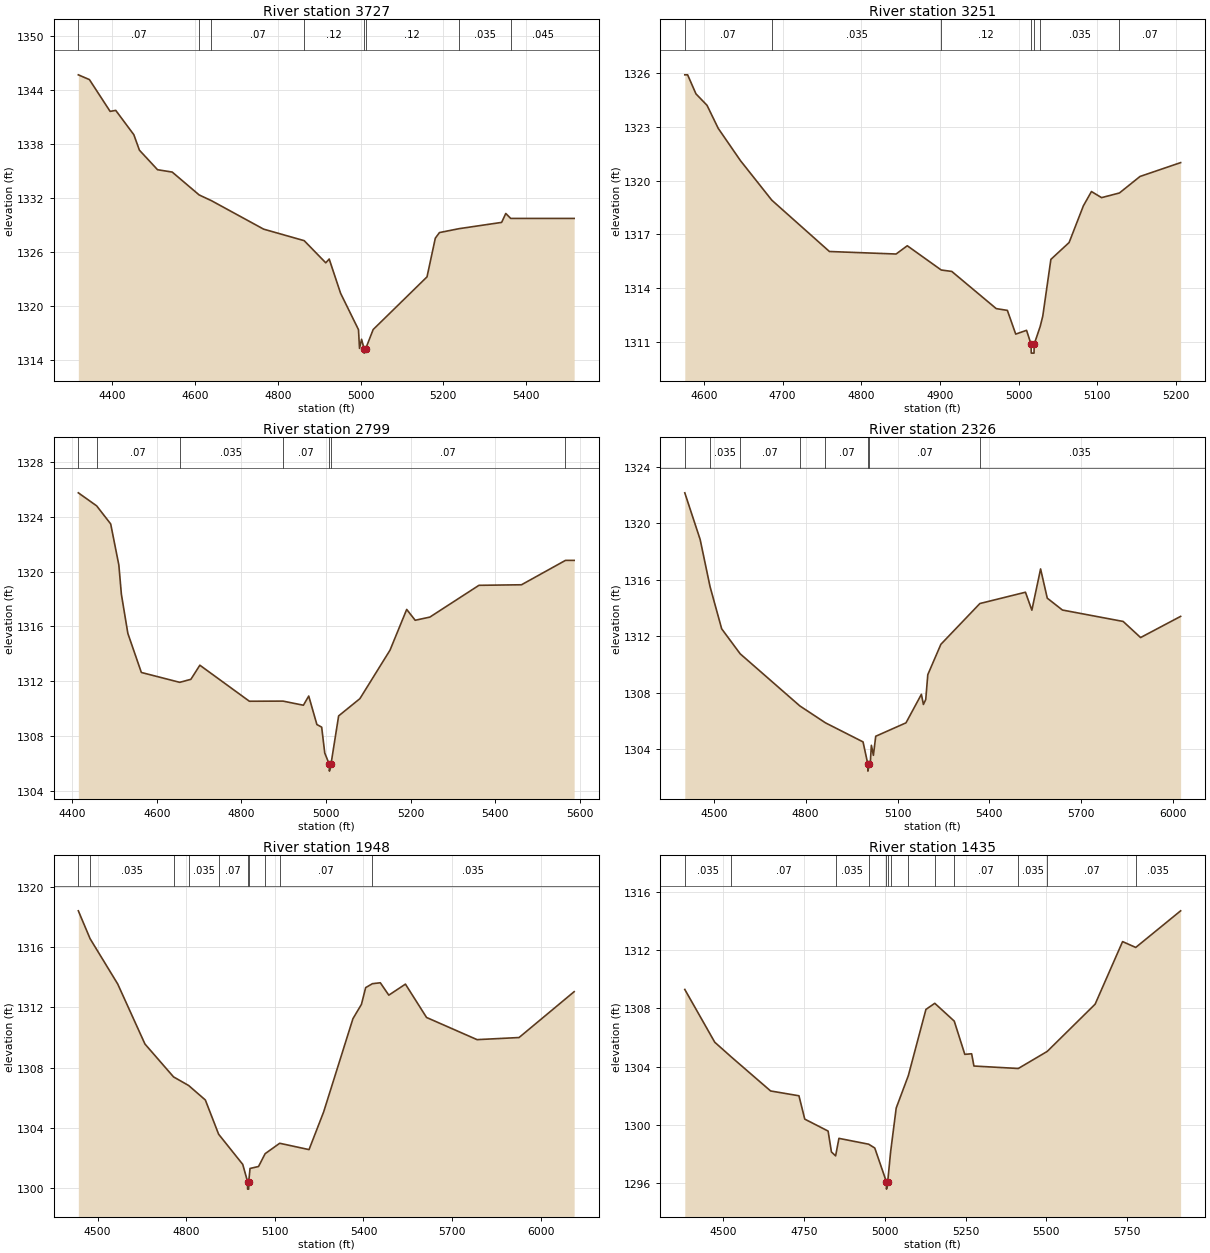
Type RM Length L Ch R = 1,3727,476,476,476
BEGIN DESCRIPTION:
Stream0141_DS 8.0
END DESCRIPTION:
XS GIS Cut Line= 3
      2042172.36     13898075.33      2041630.21     13897669.79
      2041109.97     13897695.11
#Sta/Elev= 30
  4318.1 1345.65  4344.9 1345.12  4394.9 1341.59  4408.5 1341.70  4452.2 1339.00
  4465.7 1337.28  4509.5 1335.11  4544.9 1334.85  4610.0 1332.31  4639.8 1331.67
  4765.8 1328.51  4863.8 1327.23  4915.9 1324.77  4924.2 1325.19  4951.7 1321.39
  4995.0 1317.34  4997.4 1315.27  5002.4 1316.28  5008.4 1315.24  5008.6 1314.74
  5012.4 1315.24  5030.4 1317.36  5160.5 1323.21  5180.6 1327.51  5190.6 1328.13
  5237.5 1328.56  5340.8 1329.26  5350.8 1330.25  5362.8 1329.70  5516.0 1329.70
#Mann=8,-1,0
  4318.1    0.07       0  4610.0    0.12       0  4639.8    0.07       0
  4863.8    0.12       0  5008.4    0.05       0  5012.4    0.12       0
  5237.5   0.035       0  5362.8   0.045       0
Bank Sta=5008.4,5012.4
Exp/Cntr=0.3,0.1

Type RM Length L Ch R = 1,3251,452,452,452
BEGIN DESCRIPTION:
Stream0141_DS 7.0
END DESCRIPTION:
XS GIS Cut Line= 3
      2042025.03     13897525.03      2041725.00     13897225.00
      2041524.96     13897174.99
#Sta/Elev= 30
  4575.6 1325.89  4579.2 1325.89  4589.8 1324.83  4603.9 1324.19  4618.1 1322.91
  4646.4 1321.11  4686.2 1318.91  4759.5 1316.05  4844.3 1315.91  4858.5 1316.37
  4901.7 1315.02  4915.1 1314.94  4971.6 1312.87  4985.8 1312.77  4996.4 1311.45
  5010.2 1311.66  5015.9 1310.89  5016.2 1310.39  5019.7 1310.39  5019.9 1310.89
  5027.5 1311.87  5030.8 1312.45  5041.1 1315.61  5064.3 1316.55  5082.4 1318.59
  5092.7 1319.39  5105.6 1319.05  5128.3 1319.31  5154.5 1320.23  5206.1 1321.00
#Mann=7,-1,0
  4575.6    0.07       0  4686.2   0.035       0  4901.7    0.12       0
  5015.9    0.05       0  5019.9    0.12       0  5027.5   0.035       0
  5128.3    0.07       0
Bank Sta=5015.9,5019.9
Exp/Cntr=0.3,0.1

Type RM Length L Ch R = 1,2799,473,473,473
BEGIN DESCRIPTION:
Stream0141_DS 6.0
END DESCRIPTION:
XS GIS Cut Line= 3
      2042175.01     13897425.03      2041975.00     13896875.00
      2041391.11     13896934.70
#Sta/Elev= 30
  4414.7 1325.75  4458.0 1324.80  4491.2 1323.48  4510.5 1320.48  4516.5 1318.34
  4531.8 1315.49  4563.7 1312.64  4654.4 1311.92  4680.8 1312.14  4702.0 1313.17
  4819.1 1310.54  4898.5 1310.55  4946.8 1310.25  4959.4 1310.92  4978.7 1308.84
  4990.0 1308.65  4997.3 1306.76  5008.0 1305.94  5008.3 1305.44  5012.0 1305.94
  5030.1 1309.47  5080.4 1310.73  5151.6 1314.27  5191.0 1317.24  5211.1 1316.45
  5245.7 1316.68  5361.8 1319.00  5462.4 1319.04  5566.4 1320.82  5586.9 1320.82
#Mann=7,-1,0
  4414.7   0.035       0  4458.0    0.07       0  4654.4   0.035       0
  4898.5    0.07       0  5008.0    0.05       0  5012.0    0.07       0
  5566.4   0.035       0
Bank Sta=5008,5012
Exp/Cntr=0.3,0.1

Type RM Length L Ch R = 1,2326,378,378,378
BEGIN DESCRIPTION:
Stream0141_DS 5.0
END DESCRIPTION:
XS GIS Cut Line= 3
      2042325.00     13897275.01      2042375.00     13896675.00
      2041706.27     13895909.03
#Sta/Elev= 30
  4405.4 1322.16  4455.6 1318.85  4487.8 1315.52  4525.8 1312.53  4586.2 1310.76
  4780.9 1307.07  4864.7 1305.87  4987.4 1304.52  5003.0 1302.95  5003.2 1302.45
  5007.0 1302.95  5010.8 1302.95  5014.6 1304.28  5021.2 1303.57  5028.8 1304.92
  5127.6 1305.87  5177.9 1307.89  5184.5 1307.17  5192.1 1307.52  5198.8 1309.28
  5241.5 1311.43  5368.9 1314.32  5517.7 1315.12  5538.6 1313.85  5567.1 1316.77
  5588.9 1314.70  5638.3 1313.86  5836.7 1313.05  5893.6 1311.91  6024.3 1313.41
#Mann=8,-1,0
  4405.4    0.07       0  4487.8   0.035       0  4586.2    0.07       0
  4780.9   0.035       0  4864.7    0.07       0  5003.0    0.05       0
  5007.0    0.07       0  5368.9   0.035       0
Bank Sta=5003,5007
Exp/Cntr=0.3,0.1

Type RM Length L Ch R = 1,1948,513,513,513
BEGIN DESCRIPTION:
Stream0141_DS 4.0
END DESCRIPTION:
XS GIS Cut Line= 3
      2042775.01     13897175.03      2042653.29     13896631.96
      2041944.93     13895762.14
#Sta/Elev= 30
  4434.8 1318.40  4474.7 1316.55  4568.1 1313.55  4660.3 1309.57  4757.1 1307.39
  4808.2 1306.82  4864.7 1305.86  4909.7 1303.59  4991.3 1301.59  5007.6 1300.45
  5007.8 1299.95  5011.3 1299.95  5011.6 1300.45  5016.0 1301.32  5044.8 1301.45
  5067.1 1302.30  5116.4 1302.99  5215.7 1302.57  5265.2 1305.07  5364.3 1311.25
  5393.1 1312.20  5407.4 1313.31  5430.3 1313.57  5457.0 1313.63  5485.7 1312.81
  5542.0 1313.54  5613.5 1311.33  5784.5 1309.86  5926.6 1310.00  6113.1 1313.04
#Mann=10,-1,0
  4434.8    0.07       0  4474.7   0.035       0  4757.1    0.07       0
  4808.2   0.035       0  4909.7    0.07       0  5007.6    0.05       0
  5011.6    0.07       0  5067.1   0.035       0  5116.4    0.07       0
  5430.3   0.035       0
Bank Sta=5007.6,5011.6
Exp/Cntr=0.3,0.1

Type RM Length L Ch R = 1,1435,476,476,476
BEGIN DESCRIPTION:
Stream0141_DS 3.0
END DESCRIPTION:
XS GIS Cut Line= 3
      2042974.99     13896874.96      2042825.00     13896275.00
      2042184.55     13895621.55
#Sta/Elev= 30
  4381.9 1309.29  4474.6 1305.67  4525.8 1304.66  4647.3 1302.33  4734.9 1302.00
  4752.9 1300.40  4825.1 1299.58  4835.4 1298.15  4848.3 1297.88  4858.6 1299.08
  4950.5 1298.68  4969.4 1298.42  5005.4 1296.10  5005.7 1295.60  5009.4 1296.10
  5018.5 1298.17  5035.7 1301.16  5073.2 1303.38  5127.6 1307.92  5155.0 1308.34
  5215.2 1307.12  5247.9 1304.84  5269.0 1304.88  5276.1 1304.04  5413.2 1303.87
  5502.7 1305.04  5650.9 1308.28  5735.8 1312.57  5776.5 1312.17  5915.3 1314.68
#Mann=13,-1,0
  4381.9   0.035       0  4525.8    0.07       0  4848.3   0.035       0
  4950.5    0.07       0  5005.4    0.05       0  5009.4    0.07       0
  5018.5    0.12       0  5073.2    0.07       0  5155.0   0.035       0
  5215.2    0.07       0  5413.2   0.035       0  5502.7    0.07       0
  5776.5   0.035       0
Bank Sta=5005.4,5009.4
Exp/Cntr=0.3,0.1

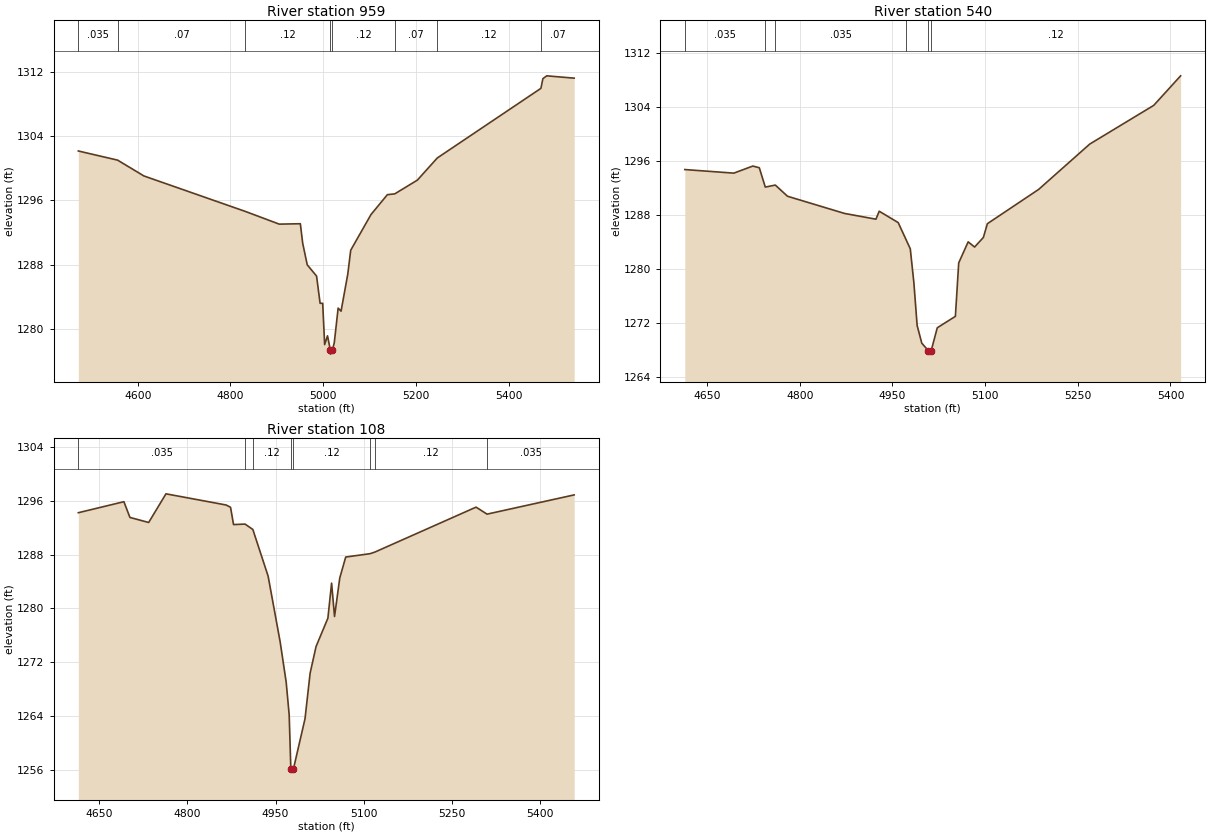
Type RM Length L Ch R = 1,959,419,419,419
BEGIN DESCRIPTION:
Stream0141_DS 2.0
END DESCRIPTION:
XS GIS Cut Line= 3
      2043283.49     13896595.50      2043225.00     13896075.00
      2042789.33     13895747.02
#Sta/Elev= 30
  4471.9 1302.16  4556.6 1301.02  4613.3 1299.05  4832.1 1294.63  4905.1 1293.05
  4950.6 1293.10  4955.7 1290.66  4965.5 1287.98  4985.6 1286.58  4993.2 1283.19
  4998.8 1283.19  5003.0 1278.05  5009.2 1279.14  5015.3 1277.36  5015.6 1276.86
  5019.7 1277.36  5023.8 1278.29  5032.1 1282.59  5038.4 1282.21  5052.9 1286.83
  5059.2 1289.80  5102.9 1294.24  5138.3 1296.72  5154.2 1296.82  5202.9 1298.53
  5245.9 1301.29  5469.3 1309.96  5473.6 1311.17  5481.9 1311.52  5541.0 1311.23
#Mann=8,-1,0
  4471.9   0.035       0  4556.6    0.07       0  4832.1    0.12       0
  5015.3    0.05       0  5019.7    0.12       0  5154.2    0.07       0
  5245.9    0.12       0  5469.3    0.07       0
Bank Sta=5015.3,5019.7
Exp/Cntr=0.3,0.1

Type RM Length L Ch R = 1,540,432,432,432
BEGIN DESCRIPTION:
Stream0141_DS 1.0
END DESCRIPTION:
XS GIS Cut Line= 3
      2043555.43     13896088.52      2043425.00     13895725.00
      2043023.04     13895616.33
#Sta/Elev= 30
  4613.8 1294.74  4693.2 1294.21  4723.9 1295.26  4734.4 1295.01  4744.1 1292.14
  4760.3 1292.44  4780.1 1290.78  4872.5 1288.23  4923.2 1287.38  4928.5 1288.56
  4959.2 1286.88  4971.7 1284.40  4978.8 1282.99  4984.6 1277.98  4989.9 1271.62
  4997.4 1269.00  5008.1 1267.87  5008.4 1267.37  5012.6 1267.87  5022.5 1271.28
  5051.8 1272.97  5057.2 1280.90  5072.5 1284.02  5082.9 1283.25  5097.1 1284.67
  5103.6 1286.71  5186.5 1291.79  5269.3 1298.52  5372.9 1304.26  5416.4 1308.64
#Mann=6,-1,0
  4613.8   0.035       0  4744.1    0.07       0  4760.3   0.035       0
  4971.7    0.12       0  5008.1    0.05       0  5012.6    0.12       0
Bank Sta=5008.1,5012.6
Exp/Cntr=0.3,0.1

Type RM Length L Ch R = 1,108,0,0,0
BEGIN DESCRIPTION:
Stream0141_DS 0.0
END DESCRIPTION:
XS GIS Cut Line= 3
      2043656.16     13896050.80      2043735.55     13895673.67
      2043680.80     13895219.35
#Sta/Elev= 30
  4614.6 1294.23  4692.1 1295.87  4702.3 1293.53  4734.2 1292.78  4763.6 1297.04
  4865.8 1295.38  4873.4 1295.04  4878.5 1292.47  4898.1 1292.54  4911.3 1291.74
  4937.3 1284.80  4957.8 1275.00  4968.0 1269.03  4973.1 1264.16  4975.9 1256.16
  4976.2 1255.66  4980.4 1256.16  5000.0 1263.59  5008.7 1270.38  5018.8 1274.34
  5038.9 1278.55  5045.2 1283.76  5050.2 1278.80  5059.1 1284.53  5069.2 1287.64
  5110.6 1288.14  5118.8 1288.38  5290.8 1295.06  5309.5 1294.02  5457.6 1296.88
#Mann=8,-1,0
  4614.6   0.035       0  4898.1    0.07       0  4911.3    0.12       0
  4975.9    0.05       0  4980.4    0.12       0  5110.6    0.07       0
  5118.8    0.12       0  5309.5   0.035       0
Bank Sta=4975.9,4980.4
Exp/Cntr=0.3,0.1

Chan Stop Cuts=-1