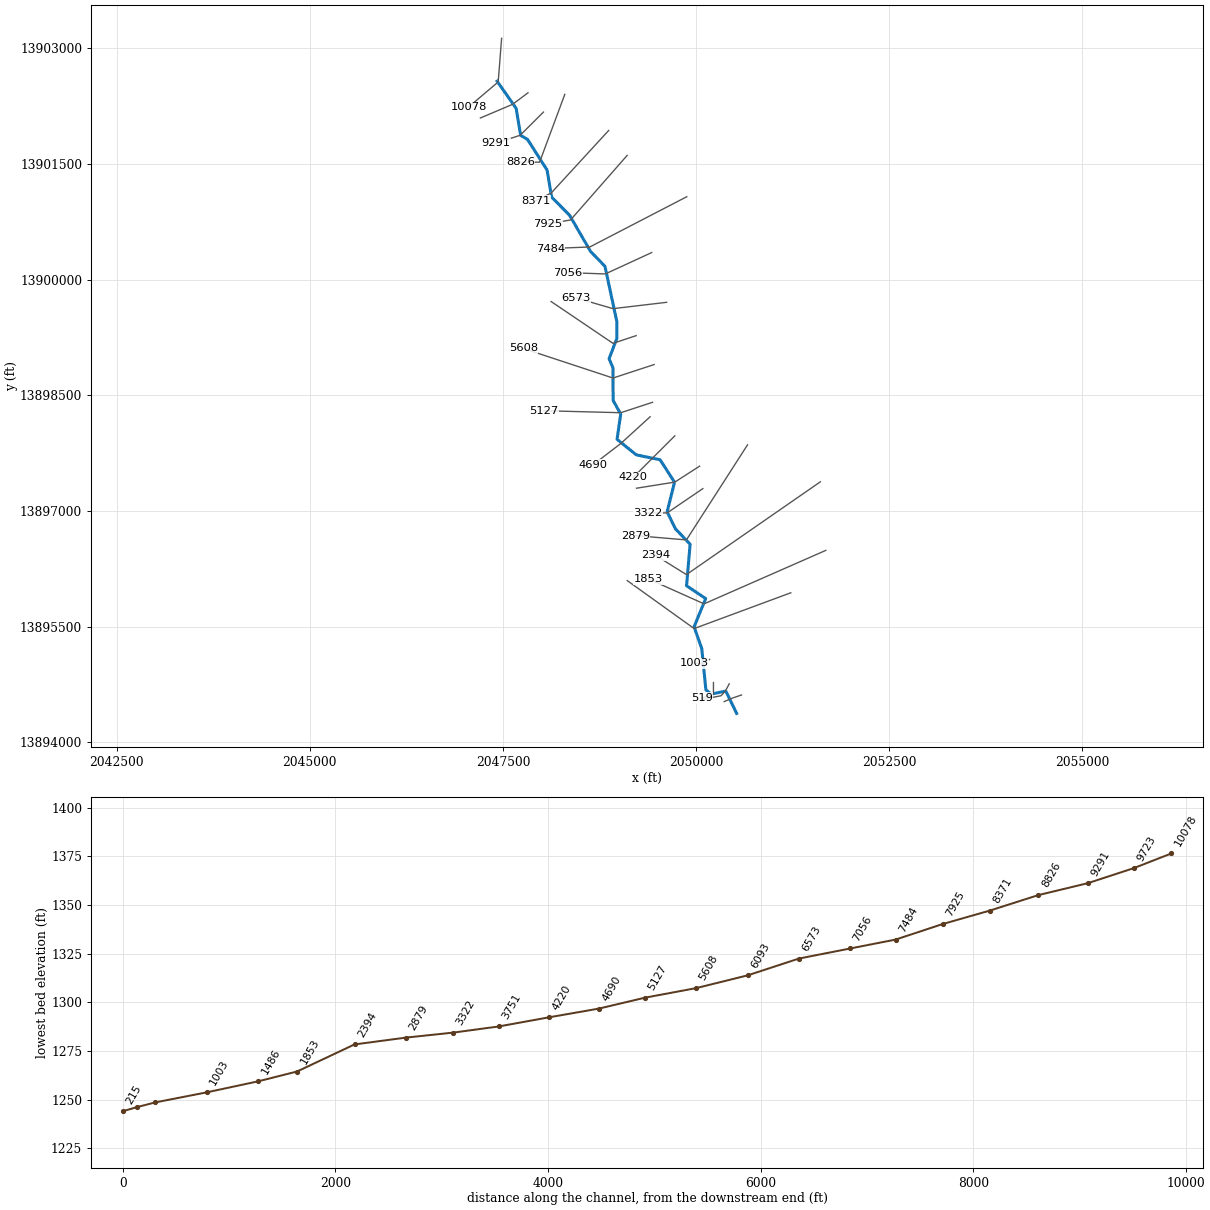
--- Stream0142_DS.prj (project) ---

Proj Title=Stream0142_DS Base Level Engineering
Current Plan=p01
Default Exp/Contr=0.3,0.1
English Units
Geom File=g01
Flow File=f01
Plan File=p01
BEGIN DESCRIPTION:
Stream0142_DS
END DESCRIPTION:

--- Stream0142_DS.p01 (plan) ---

Plan Title=Multiple Run
Short Identifier=Multiple
Geom File=g01
Flow File=f01
Subcritical Flow
K Sum by GR= 0
Std Step Tol= 0.01
Critical Tol= 0.01
Num of Std Step Trials= 20
Max Error Tol= 0.3
Flow Tol Ratio= 0.001
Split Flow NTrial= 30
Split Flow Tol= 0.02
Split Flow Ratio= 0.02
Log Output Level= 0
Friction Slope Method= 1
Unsteady Friction Slope Method= 2
Unsteady Bridges Friction Slope Method= 1
Parabolic Critical Depth
Global Vel Dist=  1 , 1 , 1
Global Log Level= 0
CheckData=True
Encroach Param= -1, 0, 0, 0
BEGIN DESCRIPTION:
Multiple Run
END DESCRIPTION:

--- Stream0142_DS.f01 (steady flow) ---

Flow Title=Multiple
Number of Profiles=7
Profile Names=10-year,25-year,50-year,1pct_min,100-year,1pct_plu,500-year
River Rch & RM= Stream0142_DS,Reach-1,10078
     490     786    1055     688    1373    2739    2295
River Rch & RM= Stream0142_DS,Reach-1,9723
     851    1413    1937    1289    2572    5132    4479
River Rch & RM= Stream0142_DS,Reach-1,5127
    1324    2253    3140    2119    4228    8436    7583
River Rch & RM= Stream0142_DS,Reach-1,2394
    1382    2356    3287    2220    4429    8837    7956
Boundary for River Rch & Prof#=Stream0142_DS,Reach-1,1
Up Type=0
Dn Type=3
Dn Slope=0.005
Boundary for River Rch & Prof#=Stream0142_DS,Reach-1,2
Up Type=0
Dn Type=3
Dn Slope=0.005
Boundary for River Rch & Prof#=Stream0142_DS,Reach-1,3
Up Type=0
Dn Type=3
Dn Slope=0.005
Boundary for River Rch & Prof#=Stream0142_DS,Reach-1,4
Up Type=0
Dn Type=3
Dn Slope=0.005
Boundary for River Rch & Prof#=Stream0142_DS,Reach-1,5
Up Type=0
Dn Type=3
Dn Slope=0.005
Boundary for River Rch & Prof#=Stream0142_DS,Reach-1,6
Up Type=0
Dn Type=3
Dn Slope=0.005
Boundary for River Rch & Prof#=Stream0142_DS,Reach-1,7
Up Type=0
Dn Type=3
Dn Slope=0.005

--- Stream0142_DS.g01 (geometry) ---

Geom Title=Existing Conditions

River Reach=Stream0142_DS,Reach-1
Reach XY= 30
      2047425.00     13902575.00      2047671.45     13902223.53
      2047730.46     13901872.34      2047819.38     13901819.38
      2048071.46     13901423.53      2048130.47     13901072.55
      2048364.22     13900834.68      2048633.14     13900368.94
      2048821.39     13900173.50      2048974.93     13899454.97
      2048973.78     13899235.50      2048874.18     13898975.00
      2048924.79     13898856.73      2048926.36     13898434.65
      2049024.96     13898256.67      2048977.09     13897930.26
      2049226.50     13897728.61      2049534.82     13897664.53
      2049721.33     13897373.42      2049625.65     13896988.92
      2049733.14     13896768.94      2049922.83     13896569.56
      2049877.05     13896030.84      2050124.52     13895864.53
      2049974.62     13895497.81      2050073.78     13895214.50
      2050126.98     13894680.62      2050195.01     13894624.55
      2050384.81     13894664.58      2050525.00     13894375.00

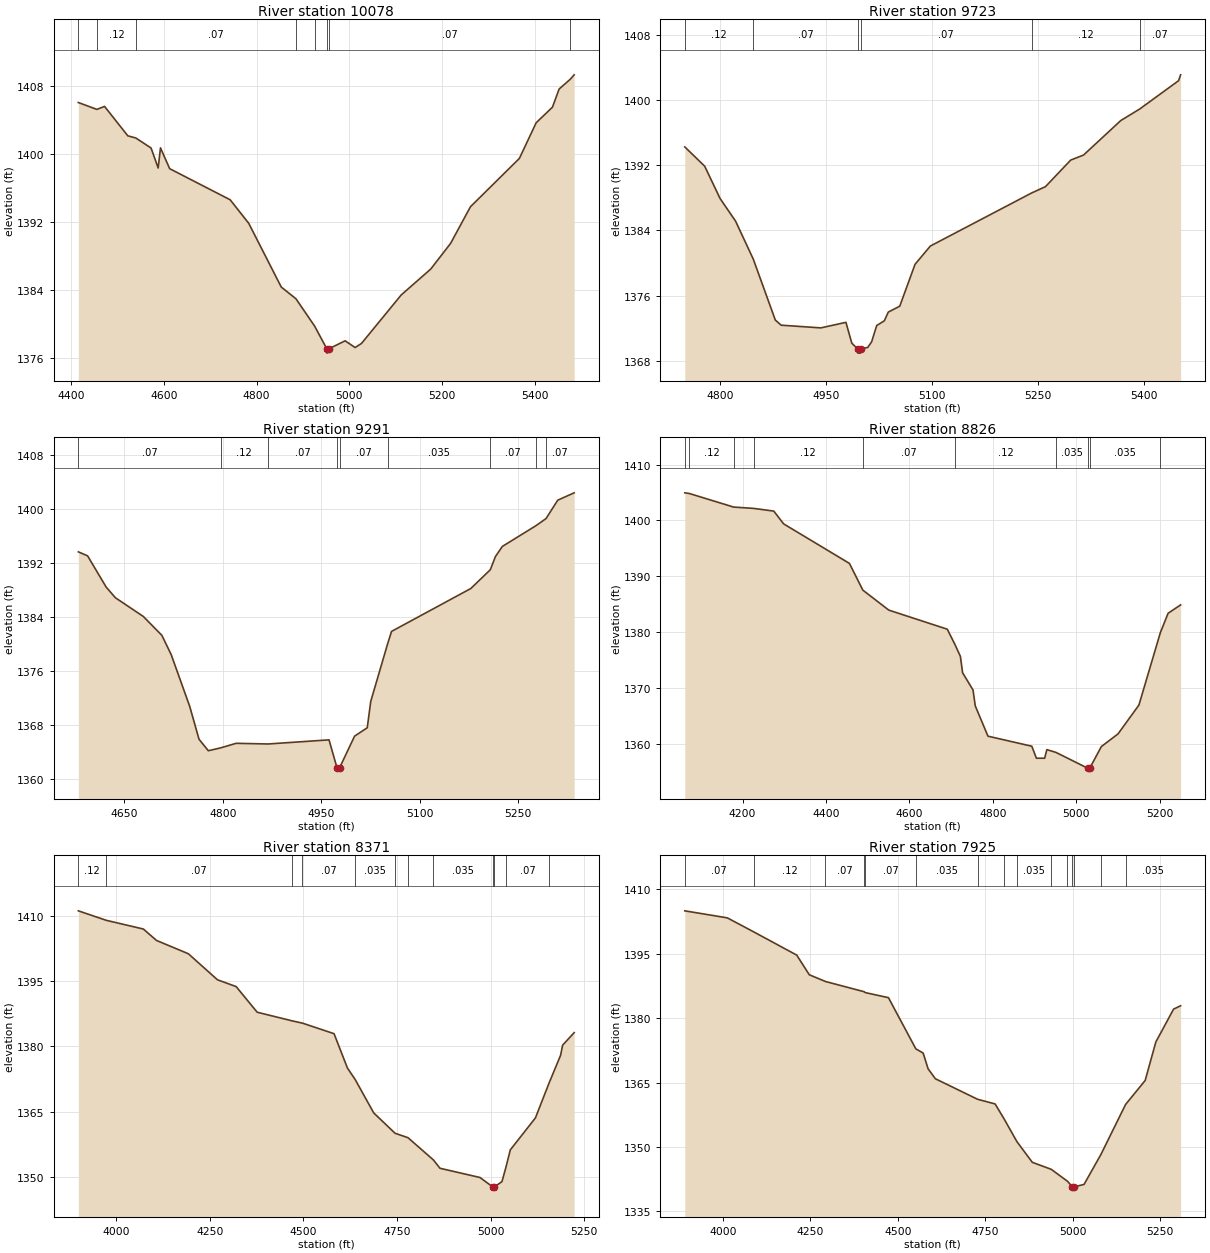
Type RM Length L Ch R = 1,10078,355,355,355
BEGIN DESCRIPTION:
Stream0142_DS 22.0
END DESCRIPTION:
XS GIS Cut Line= 4
      2047483.44     13903131.40      2047440.15     13902577.61
      2047424.52     13902553.16      2047055.02     13902239.15
#Sta/Elev= 30
  4415.5 1406.03  4455.5 1405.22  4472.1 1405.57  4522.2 1402.11  4539.6 1401.85
  4572.4 1400.67  4587.7 1398.32  4592.7 1400.69  4612.5 1398.24  4742.9 1394.58
  4783.0 1391.81  4853.2 1384.30  4884.9 1382.92  4925.3 1379.69  4951.5 1377.02
  4951.8 1376.52  4955.5 1377.02  4990.9 1377.97  5012.5 1377.18  5026.2 1377.66
  5111.9 1383.37  5175.6 1386.42  5218.5 1389.45  5261.3 1393.76  5366.8 1399.45
  5403.0 1403.65  5438.1 1405.48  5452.4 1407.61  5476.7 1408.78  5484.9 1409.29
#Mann=8,-1,0
  4415.5    0.07       0  4455.5    0.12       0  4539.6    0.07       0
  4884.9    0.12       0  4925.3    0.07       0  4951.5    0.05       0
  4955.5    0.07       0  5476.7   0.035       0
Bank Sta=4951.5,4955.5
Exp/Cntr=0.3,0.1

Type RM Length L Ch R = 1,9723,432,432,432
BEGIN DESCRIPTION:
Stream0142_DS 21.0
END DESCRIPTION:
XS GIS Cut Line= 3
      2047825.02     13902425.02      2047625.00     13902275.00
      2047208.81     13902098.23
#Sta/Elev= 30
  4750.0 1394.25  4778.2 1391.88  4800.0 1387.91  4821.9 1385.14  4847.0 1380.47
  4878.2 1372.99  4886.5 1372.36  4942.7 1372.03  4978.2 1372.71  4986.5 1370.16
  4994.9 1369.43  4995.2 1368.93  4998.7 1368.93  4998.9 1369.43  5009.1 1369.63
  5014.6 1370.32  5021.8 1372.32  5032.6 1372.90  5038.2 1373.97  5054.4 1374.69
  5076.1 1379.84  5097.8 1382.08  5241.1 1388.59  5260.8 1389.37  5296.5 1392.63
  5314.7 1393.25  5367.5 1397.49  5394.2 1398.90  5449.3 1402.38  5452.2 1403.10
#Mann=6,-1,0
  4750.0    0.12       0  4847.0    0.07       0  4994.9    0.05       0
  4998.9    0.07       0  5241.1    0.12       0  5394.2    0.07       0
Bank Sta=4994.9,4998.9
Exp/Cntr=0.3,0.1

Type RM Length L Ch R = 1,9291,465,465,465
BEGIN DESCRIPTION:
Stream0142_DS 20.0
END DESCRIPTION:
XS GIS Cut Line= 3
      2048024.98     13902174.98      2047725.00     13901875.00
      2047411.31     13901769.78
#Sta/Elev= 30
  4580.0 1393.68  4594.1 1393.09  4622.4 1388.46  4636.5 1386.88  4679.0 1384.11
  4707.2 1381.32  4721.4 1378.47  4749.7 1370.78  4763.8 1365.93  4778.0 1364.23
  4796.6 1364.65  4820.4 1365.33  4869.0 1365.23  4961.8 1365.84  4973.9 1361.71
  4974.2 1361.21  4977.9 1361.71  5000.7 1366.39  5020.0 1367.63  5025.3 1371.53
  5051.0 1380.05  5057.0 1381.90  5177.7 1388.25  5207.4 1391.03  5215.2 1392.98
  5225.7 1394.48  5276.4 1397.52  5292.3 1398.61  5310.1 1401.33  5335.1 1402.42
#Mann=9,-1,0
  4580.0    0.07       0  4796.6    0.12       0  4869.0    0.07       0
  4973.9    0.05       0  4977.9    0.07       0  5051.0   0.035       0
  5207.4    0.07       0  5276.4   0.035       0  5292.3    0.07       0
Bank Sta=4973.9,4977.9
Exp/Cntr=0.3,0.1

Type RM Length L Ch R = 1,8826,455,455,455
BEGIN DESCRIPTION:
Stream0142_DS 19.0
END DESCRIPTION:
XS GIS Cut Line= 3
      2048301.30     13902404.95      2047975.00     13901525.00
      2047725.00     13901525.00
#Sta/Elev= 30
  4061.5 1404.94  4072.4 1404.82  4178.5 1402.39  4226.7 1402.15  4274.8 1401.67
  4298.4 1399.38  4456.1 1392.30  4488.3 1387.51  4550.5 1383.93  4690.7 1380.51
  4709.1 1377.77  4722.1 1375.64  4727.4 1372.71  4752.4 1369.62  4757.8 1366.77
  4788.2 1361.35  4893.3 1359.55  4904.3 1357.40  4924.1 1357.40  4929.4 1358.94
  4951.0 1358.45  5028.0 1355.59  5028.3 1355.09  5032.0 1355.59  5060.0 1359.49
  5100.0 1361.76  5150.0 1366.92  5201.4 1379.89  5220.0 1383.37  5250.0 1384.87
#Mann=10,-1,0
  4061.5    0.07       0  4072.4    0.12       0  4178.5    0.07       0
  4226.7    0.12       0  4488.3    0.07       0  4709.1    0.12       0
  4951.0   0.035       0  5028.0   0.035       0  5032.0   0.035       0
  5201.4    0.07       0
Bank Sta=5028,5032
Exp/Cntr=0.3,0.1

Type RM Length L Ch R = 1,8371,446,446,446
BEGIN DESCRIPTION:
Stream0142_DS 18.0
END DESCRIPTION:
XS GIS Cut Line= 3
      2048869.00     13901936.22      2048125.00     13901125.00
      2047925.04     13901025.02
#Sta/Elev= 30
  3898.9 1411.21  3973.7 1409.02  4072.6 1407.02  4107.7 1404.39  4192.8 1401.33
  4270.5 1395.34  4320.4 1393.77  4376.6 1387.87  4470.1 1385.88  4497.4 1385.36
  4581.9 1382.93  4617.6 1375.03  4638.4 1372.37  4687.9 1364.69  4744.9 1360.01
  4779.4 1358.99  4847.4 1353.86  4864.9 1351.95  4971.6 1349.83  5006.0 1347.65
  5006.3 1347.15  5010.0 1347.65  5030.4 1348.88  5041.0 1352.19  5052.7 1356.19
  5119.8 1363.55  5155.7 1371.46  5186.9 1377.94  5192.5 1380.30  5223.2 1383.17
#Mann=12,-1,0
  3898.9    0.12       0  3973.7    0.07       0  4470.1    0.12       0
  4497.4    0.07       0  4638.4   0.035       0  4744.9    0.07       0
  4779.4    0.12       0  4847.4   0.035       0  5006.0   0.035       0
  5010.0   0.035       0  5041.0    0.07       0  5155.7    0.12       0
Bank Sta=5006,5010
Exp/Cntr=0.3,0.1

Type RM Length L Ch R = 1,7925,441,441,441
BEGIN DESCRIPTION:
Stream0142_DS 17.0
END DESCRIPTION:
XS GIS Cut Line= 3
      2049108.61     13901613.32      2048375.00     13900775.00
      2048075.03     13900725.00
#Sta/Elev= 30
  3891.0 1404.96  4012.7 1403.32  4087.7 1400.08  4211.1 1394.66  4247.1 1390.08
  4293.2 1388.52  4403.8 1386.14  4407.3 1385.93  4473.5 1384.75  4551.8 1372.84
  4572.7 1371.87  4586.9 1368.19  4607.8 1365.88  4728.4 1361.11  4778.6 1360.02
  4804.6 1356.49  4840.9 1351.25  4884.9 1346.44  4939.0 1344.81  4985.4 1342.04
  4999.7 1340.70  4999.9 1340.20  5003.7 1340.70  5032.9 1341.30  5081.0 1348.24
  5151.7 1359.90  5207.7 1365.48  5238.2 1374.44  5288.9 1382.08  5309.1 1382.87
#Mann=15,-1,0
  3891.0    0.07       0  4087.7    0.12       0  4293.2    0.07       0
  4403.8    0.12       0  4407.3    0.07       0  4551.8   0.035       0
  4728.4    0.07       0  4804.6    0.12       0  4840.9   0.035       0
  4939.0    0.12       0  4985.4   0.035       0  4999.7   0.035       0
  5003.7   0.035       0  5081.0    0.07       0  5151.7   0.035       0
Bank Sta=4999.7,5003.7
Exp/Cntr=0.3,0.1

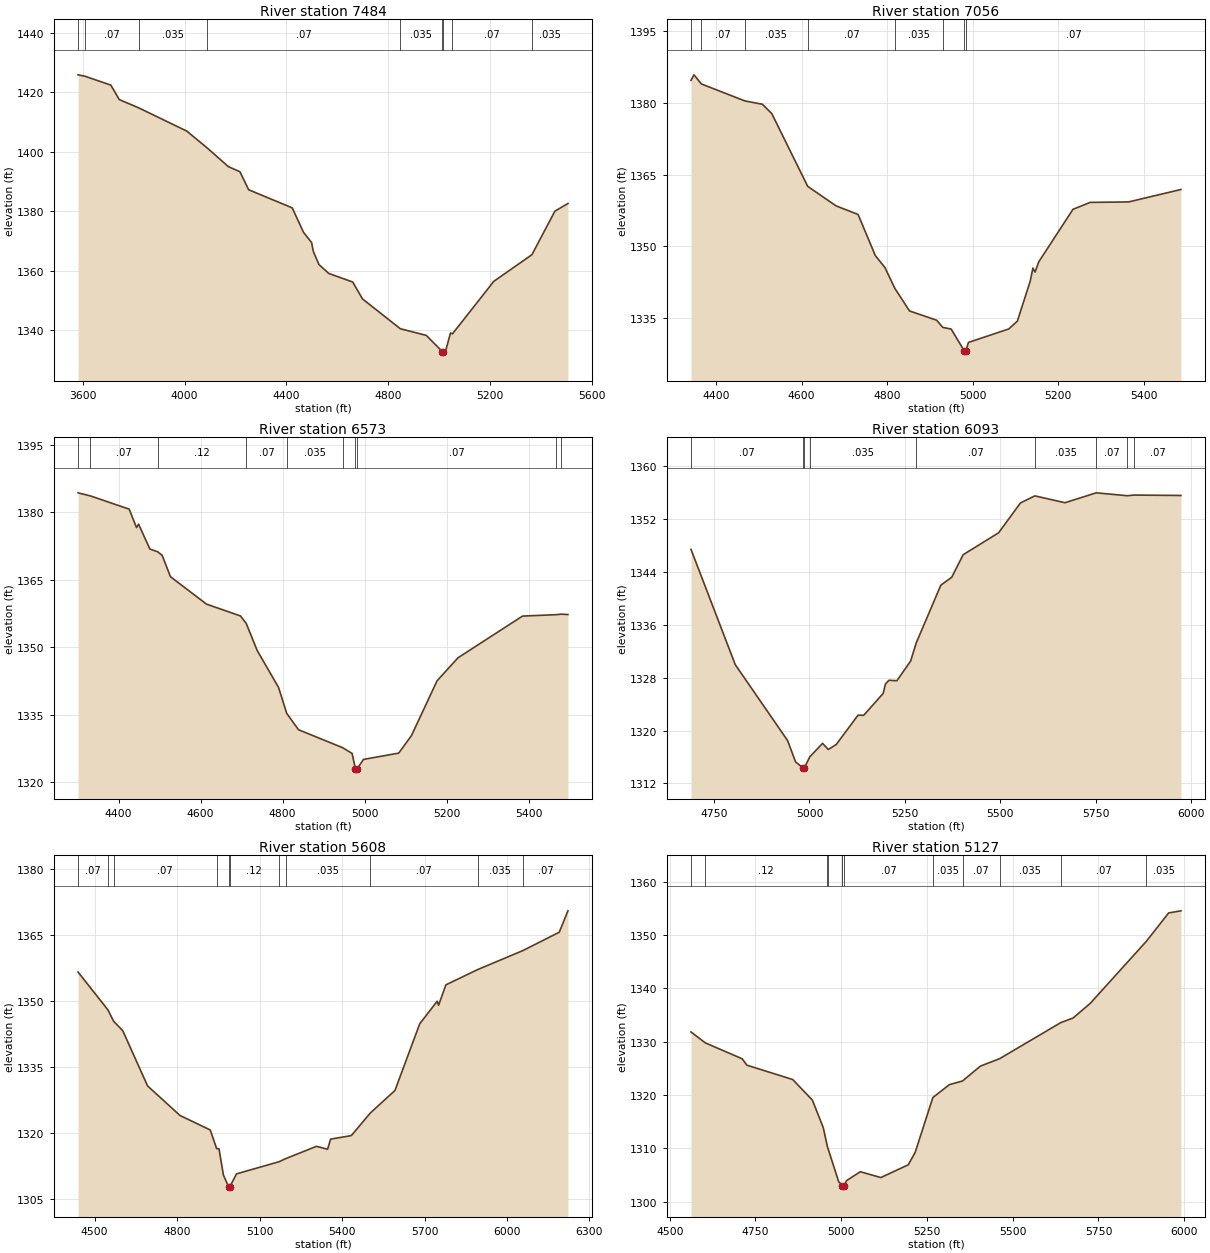
Type RM Length L Ch R = 1,7484,428,428,428
BEGIN DESCRIPTION:
Stream0142_DS 16.0
END DESCRIPTION:
XS GIS Cut Line= 3
      2049879.49     13901076.89      2048625.00     13900425.00
      2048113.85     13900405.00
#Sta/Elev= 30
  3581.3 1425.95  3607.6 1425.50  3710.3 1422.49  3743.3 1417.62  3820.4 1414.80
  4008.6 1407.01  4089.4 1401.29  4172.4 1395.02  4217.5 1393.32  4251.9 1387.25
  4423.1 1381.15  4467.4 1372.92  4499.2 1369.47  4506.0 1366.49  4528.1 1362.07
  4566.7 1359.07  4660.8 1356.18  4699.3 1350.49  4847.9 1340.45  4950.0 1338.21
  5013.1 1332.74  5013.3 1332.24  5017.1 1332.74  5025.1 1332.74  5045.1 1339.03
  5052.6 1338.72  5215.2 1356.41  5365.0 1365.38  5455.4 1380.05  5506.6 1382.62
#Mann=9,-1,0
  3581.3   0.035       0  3607.6    0.07       0  3820.4   0.035       0
  4089.4    0.07       0  4847.9   0.035       0  5013.1   0.035       0
  5017.1   0.035       0  5052.6    0.07       0  5365.0   0.035       0
Bank Sta=5013.1,5017.1
Exp/Cntr=0.3,0.1

Type RM Length L Ch R = 1,7056,483,483,483
BEGIN DESCRIPTION:
Stream0142_DS 15.0
END DESCRIPTION:
XS GIS Cut Line= 3
      2049426.28     13900352.89      2048825.00     13900075.00
      2048343.01     13900092.49
#Sta/Elev= 30
  4341.8 1384.76  4348.7 1385.92  4366.1 1384.01  4467.4 1380.46  4508.5 1379.76
  4530.5 1377.81  4614.5 1362.56  4680.8 1358.48  4732.2 1356.68  4772.5 1348.06
  4794.9 1345.57  4818.2 1341.19  4852.4 1336.48  4915.7 1334.54  4930.1 1333.04
  4949.6 1332.69  4980.2 1328.15  4980.4 1327.65  4984.2 1328.15  4990.0 1329.89
  5084.2 1332.71  5104.3 1334.34  5134.3 1342.69  5140.7 1345.46  5145.7 1344.61
  5154.3 1346.76  5234.3 1357.76  5274.4 1359.21  5364.4 1359.31  5486.5 1361.91
#Mann=8,-1,0
  4341.8   0.035       0  4366.1    0.07       0  4467.4   0.035       0
  4614.5    0.07       0  4818.2   0.035       0  4930.1    0.07       0
  4980.2    0.05       0  4984.2    0.07       0
Bank Sta=4980.2,4984.2
Exp/Cntr=0.3,0.1

Type RM Length L Ch R = 1,6573,480,480,480
BEGIN DESCRIPTION:
Stream0142_DS 14.0
END DESCRIPTION:
XS GIS Cut Line= 3
      2049618.98     13899707.07      2048925.00     13899625.00
      2048448.57     13899763.96
#Sta/Elev= 30
  4301.1 1384.32  4331.1 1383.64  4425.9 1380.69  4443.8 1376.59  4448.8 1377.36
  4476.3 1371.83  4495.5 1371.21  4506.5 1370.40  4526.6 1365.67  4614.5 1359.58
  4697.4 1356.95  4711.3 1355.32  4738.1 1349.28  4790.3 1341.05  4810.2 1335.30
  4838.8 1331.67  4946.5 1327.67  4969.7 1326.39  4977.8 1322.96  4978.0 1322.46
  4981.8 1322.96  4997.4 1325.06  5083.3 1326.46  5114.5 1330.36  5177.0 1342.55
  5228.0 1347.65  5385.3 1356.92  5468.0 1357.24  5479.7 1357.35  5496.2 1357.27
#Mann=10,-1,0
  4301.1    0.12       0  4331.1    0.07       0  4495.5    0.12       0
  4711.3    0.07       0  4810.2   0.035       0  4946.5    0.07       0
  4977.8    0.05       0  4981.8    0.07       0  5468.0   0.035       0
  5479.7    0.07       0
Bank Sta=4977.8,4981.8
Exp/Cntr=0.3,0.1

Type RM Length L Ch R = 1,6093,485,485,485
BEGIN DESCRIPTION:
Stream0142_DS 13.0
END DESCRIPTION:
XS GIS Cut Line= 3
      2049224.96     13899274.99      2048925.00     13899175.00
      2048124.25     13899717.49
#Sta/Elev= 30
  4689.7 1347.44  4805.6 1329.99  4942.6 1318.50  4963.7 1315.26  4982.8 1314.36
  4983.1 1313.86  4986.8 1314.36  5000.7 1316.01  5034.4 1318.07  5049.3 1317.13
  5070.3 1317.90  5127.2 1322.33  5142.2 1322.32  5193.1 1325.63  5199.1 1327.06
  5208.1 1327.62  5229.0 1327.55  5265.0 1330.53  5279.6 1333.26  5344.1 1342.02
  5372.8 1343.23  5402.7 1346.64  5495.6 1349.96  5552.6 1354.47  5590.5 1355.55
  5669.3 1354.51  5751.3 1356.01  5832.8 1355.57  5849.8 1355.67  5973.1 1355.61
#Mann=9,-1,0
  4689.7    0.07       0  4982.8    0.05       0  4986.8    0.07       0
  5000.7   0.035       0  5279.6    0.07       0  5590.5   0.035       0
  5751.3    0.07       0  5832.8   0.035       0  5849.8    0.07       0
Bank Sta=4982.8,4986.8
Exp/Cntr=0.3,0.1

Type RM Length L Ch R = 1,5608,481,481,481
BEGIN DESCRIPTION:
Stream0142_DS 12.0
END DESCRIPTION:
XS GIS Cut Line= 3
      2049457.59     13898899.79      2048925.00     13898725.00
      2047764.87     13899108.12
#Sta/Elev= 30
  4439.5 1356.56  4548.3 1347.96  4568.7 1345.41  4602.3 1343.23  4692.5 1330.71
  4810.6 1324.00  4920.5 1320.71  4943.8 1316.48  4952.3 1316.44  4968.5 1310.47
  4987.5 1307.79  4987.8 1307.29  4991.5 1307.79  5015.9 1310.75  5170.1 1313.49
  5196.0 1314.23  5306.9 1317.00  5347.6 1316.34  5358.1 1318.63  5433.8 1319.44
  5503.1 1324.58  5592.5 1329.68  5682.5 1344.79  5746.0 1349.92  5751.2 1349.00
  5777.7 1353.64  5894.2 1357.13  6058.0 1361.42  6190.1 1365.58  6221.8 1370.44
#Mann=11,-1,0
  4439.5    0.07       0  4548.3    0.12       0  4568.7    0.07       0
  4943.8    0.12       0  4987.5    0.05       0  4991.5    0.12       0
  5170.1    0.07       0  5196.0   0.035       0  5503.1    0.07       0
  5894.2   0.035       0  6058.0    0.07       0
Bank Sta=4987.5,4991.5
Exp/Cntr=0.3,0.1

Type RM Length L Ch R = 1,5127,437,437,437
BEGIN DESCRIPTION:
Stream0142_DS 11.0
END DESCRIPTION:
XS GIS Cut Line= 3
      2049436.73     13898410.20      2049025.00     13898275.00
      2048030.50     13898300.83
#Sta/Elev= 30
  4562.1 1331.84  4603.8 1329.79  4711.3 1326.81  4725.0 1325.61  4858.6 1322.92
  4915.9 1319.07  4947.7 1313.90  4959.7 1310.35  4962.0 1309.89  4992.8 1303.74
  5001.0 1303.27  5003.5 1302.88  5003.7 1302.38  5007.5 1302.88  5015.5 1303.97
  5055.5 1305.64  5115.5 1304.55  5195.5 1306.94  5215.5 1309.25  5267.2 1319.55
  5315.6 1321.97  5353.7 1322.65  5405.6 1325.43  5462.4 1326.85  5639.8 1333.58
  5675.7 1334.44  5725.7 1337.18  5889.7 1348.84  5954.6 1354.15  5990.3 1354.54
#Mann=12,-1,0
  4562.1    0.07       0  4603.8    0.12       0  4959.7    0.07       0
  4962.0    0.12       0  5001.0    0.07       0  5003.5    0.05       0
  5007.5    0.07       0  5267.2   0.035       0  5353.7    0.07       0
  5462.4   0.035       0  5639.8    0.07       0  5889.7   0.035       0
Bank Sta=5003.5,5007.5
Exp/Cntr=0.3,0.1

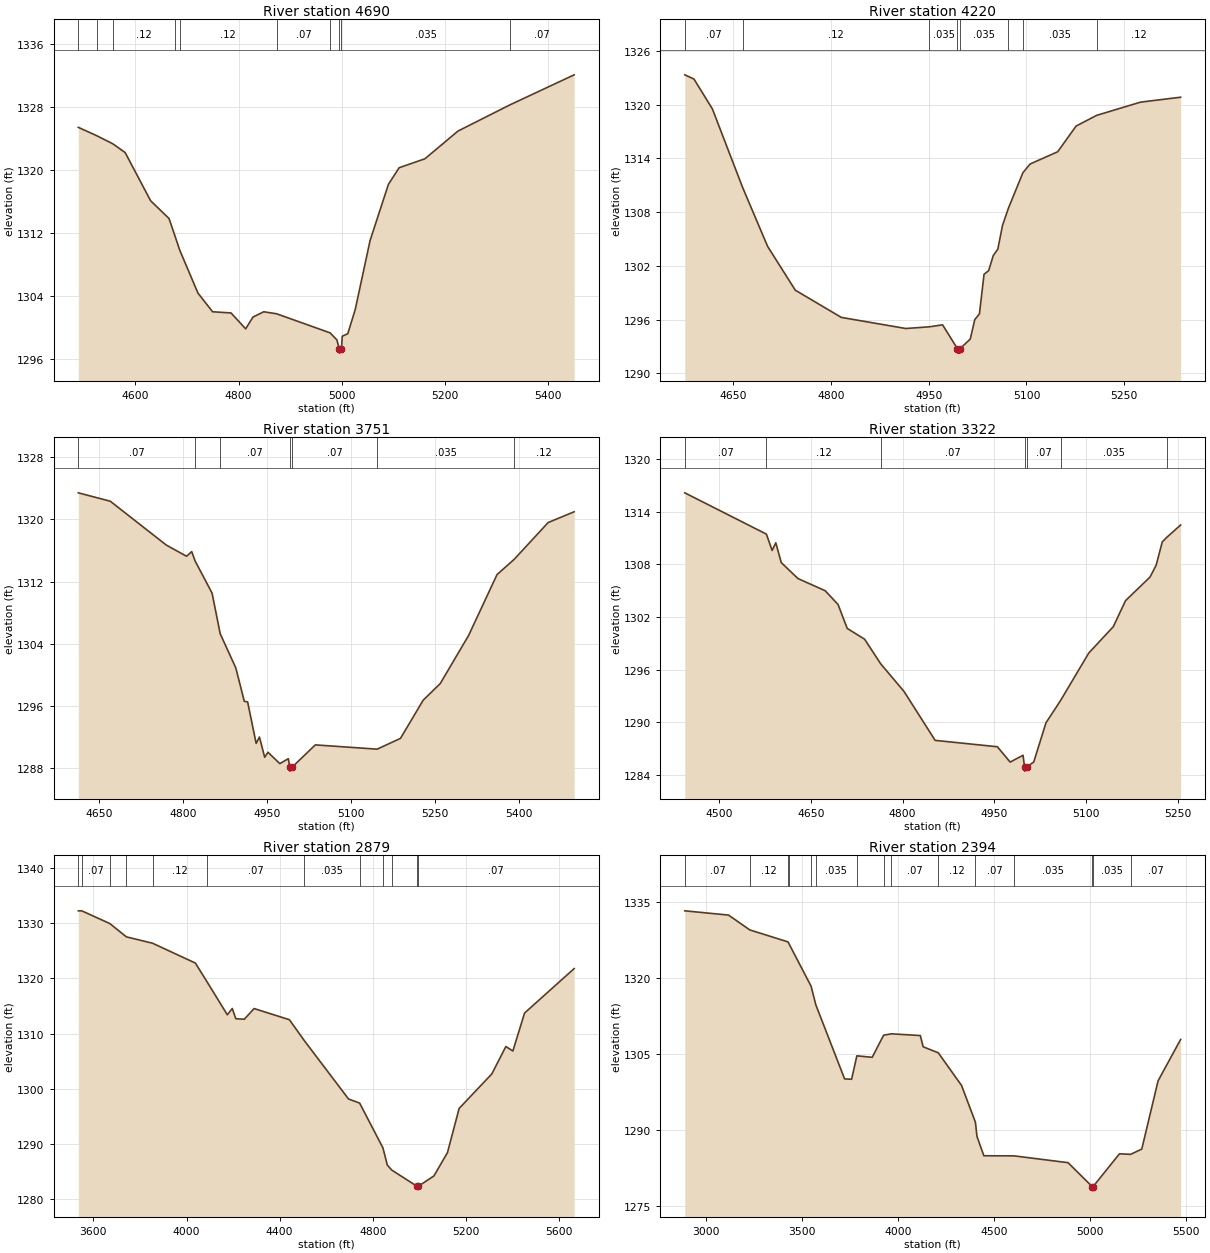
Type RM Length L Ch R = 1,4690,470,470,470
BEGIN DESCRIPTION:
Stream0142_DS 10.0
END DESCRIPTION:
XS GIS Cut Line= 3
      2049405.49     13898222.70      2049025.00     13897875.00
      2048671.13     13897602.93
#Sta/Elev= 30
  4489.3 1325.44  4525.0 1324.38  4555.9 1323.36  4580.1 1322.24  4629.5 1316.11
  4665.2 1313.85  4676.0 1311.78  4685.8 1309.86  4721.3 1304.37  4749.7 1301.99
  4785.5 1301.84  4813.9 1299.82  4828.1 1301.32  4849.0 1301.99  4874.1 1301.73
  4977.9 1299.30  4990.9 1298.41  4995.6 1297.23  4995.9 1296.73  4999.6 1297.23
  5001.3 1298.88  5012.0 1299.20  5026.5 1302.29  5055.2 1311.04  5090.8 1318.19
  5111.7 1320.31  5161.5 1321.44  5225.8 1324.97  5325.9 1328.28  5451.1 1332.12
#Mann=10,-1,0
  4489.3    0.12       0  4525.0    0.07       0  4555.9    0.12       0
  4676.0    0.07       0  4685.8    0.12       0  4874.1    0.07       0
  4977.9   0.035       0  4995.6   0.035       0  4999.6   0.035       0
  5325.9    0.07       0
Bank Sta=4995.6,4999.6
Exp/Cntr=0.3,0.1

Type RM Length L Ch R = 1,4220,469,469,469
BEGIN DESCRIPTION:
Stream0142_DS 9.0
END DESCRIPTION:
XS GIS Cut Line= 3
      2049724.98     13897974.98      2049425.00     13897675.00
      2049186.76     13897436.27
#Sta/Elev= 30
  4575.3 1323.33  4589.4 1322.86  4617.7 1319.52  4664.0 1310.77  4702.5 1304.17
  4745.0 1299.28  4815.7 1296.24  4914.7 1295.00  4951.1 1295.19  4971.2 1295.41
  4994.0 1292.75  4994.2 1292.25  4997.7 1292.25  4998.0 1292.75  5013.7 1293.82
  5020.7 1296.00  5027.8 1296.63  5034.9 1301.06  5042.0 1301.46  5049.0 1303.14
  5056.1 1303.87  5063.2 1306.50  5072.4 1308.45  5094.6 1312.40  5105.6 1313.37
  5148.0 1314.74  5176.3 1317.61  5207.7 1318.80  5275.3 1320.28  5336.8 1320.83
#Mann=8,-1,0
  4575.3    0.07       0  4664.0    0.12       0  4951.1   0.035       0
  4994.0   0.035       0  4998.0   0.035       0  5072.4    0.07       0
  5094.6   0.035       0  5207.7    0.12       0
Bank Sta=4994,4998
Exp/Cntr=0.3,0.1

Type RM Length L Ch R = 1,3751,429,429,429
BEGIN DESCRIPTION:
Stream0142_DS 8.0
END DESCRIPTION:
XS GIS Cut Line= 3
      2050046.13     13897582.09      2049725.00     13897375.00
      2049229.20     13897295.75
#Sta/Elev= 30
  4613.7 1323.43  4670.7 1322.35  4770.4 1316.71  4806.7 1315.26  4815.9 1315.86
  4821.9 1314.66  4852.2 1310.51  4866.7 1305.28  4894.5 1300.88  4909.7 1296.57
  4915.6 1296.50  4930.8 1291.15  4936.7 1291.97  4946.0 1289.37  4951.9 1290.01
  4973.0 1288.55  4988.2 1289.18  4990.8 1288.08  4991.1 1287.58  4994.8 1288.08
  5036.3 1290.96  5146.5 1290.41  5188.2 1291.80  5228.7 1296.72  5259.1 1298.86
  5309.7 1305.06  5360.4 1312.90  5391.2 1314.88  5451.5 1319.60  5497.9 1320.99
#Mann=7,-1,0
  4613.7    0.07       0  4821.9    0.12       0  4866.7    0.07       0
  4990.8    0.05       0  4994.8    0.07       0  5146.5   0.035       0
  5391.2    0.12       0
Bank Sta=4990.8,4994.8
Exp/Cntr=0.3,0.1

Type RM Length L Ch R = 1,3322,443,443,443
BEGIN DESCRIPTION:
Stream0142_DS 7.0
END DESCRIPTION:
XS GIS Cut Line= 3
      2050087.81     13897290.44      2049625.00     13896975.00
      2049374.99     13896975.00
#Sta/Elev= 30
  4444.1 1316.17  4577.4 1311.46  4586.8 1309.60  4592.8 1310.47  4601.7 1308.21
  4629.0 1306.39  4673.5 1305.00  4694.5 1303.43  4709.5 1300.70  4737.9 1299.47
  4764.2 1296.66  4802.3 1293.51  4853.1 1287.93  4954.8 1287.20  4975.7 1285.45
  4996.7 1286.23  4999.2 1284.92  4999.4 1284.42  5003.2 1284.92  5014.2 1285.46
  5034.2 1289.93  5058.0 1292.47  5104.2 1297.90  5144.2 1300.90  5164.2 1303.87
  5204.2 1306.56  5214.2 1307.91  5224.2 1310.57  5231.4 1311.08  5254.2 1312.50
#Mann=7,-1,0
  4444.1    0.07       0  4577.4    0.12       0  4764.2    0.07       0
  4999.2    0.05       0  5003.2    0.07       0  5058.0   0.035       0
  5231.4    0.07       0
Bank Sta=4999.2,5003.2
Exp/Cntr=0.3,0.1

Type RM Length L Ch R = 1,2879,485,485,485
BEGIN DESCRIPTION:
Stream0142_DS 6.0
END DESCRIPTION:
XS GIS Cut Line= 3
      2050665.91     13897858.14      2049875.00     13896625.00
      2049212.75     13896681.04
#Sta/Elev= 30
  3535.3 1332.21  3551.2 1332.19  3670.4 1329.91  3741.8 1327.50  3853.9 1326.35
  4038.0 1322.76  4086.6 1319.47  4175.3 1313.40  4196.5 1314.54  4211.7 1312.69
  4248.0 1312.59  4290.3 1314.53  4441.9 1312.51  4505.0 1308.78  4696.0 1298.16
  4743.5 1297.43  4843.5 1289.33  4862.5 1286.21  4881.8 1285.30  4990.7 1282.36
  4990.9 1281.86  4994.7 1282.36  5062.5 1284.24  5120.7 1288.46  5170.9 1296.46
  5311.4 1302.71  5371.6 1307.66  5401.7 1306.85  5451.9 1313.72  5664.9 1321.76
#Mann=12,-1,0
  3535.3   0.035       0  3551.2    0.07       0  3670.4   0.035       0
  3741.8    0.07       0  3853.9    0.12       0  4086.6    0.07       0
  4505.0   0.035       0  4743.5    0.07       0  4843.5   0.035       0
  4881.8    0.07       0  4990.7    0.05       0  4994.7    0.07       0
Bank Sta=4990.7,4994.7
Exp/Cntr=0.3,0.1

Type RM Length L Ch R = 1,2394,541,541,541
BEGIN DESCRIPTION:
Stream0142_DS 5.0
END DESCRIPTION:
XS GIS Cut Line= 3
      2051608.62     13897378.96      2049875.00     13896175.00
      2049474.98     13896425.01
#Sta/Elev= 30
  2889.3 1333.23  3117.2 1332.39  3228.1 1329.46  3426.4 1327.11  3429.5 1326.91
  3547.0 1318.37  3571.9 1314.67  3721.6 1300.08  3758.0 1300.01  3785.5 1304.63
  3865.4 1304.34  3924.9 1308.70  3965.6 1308.97  4116.0 1308.63  4130.8 1306.41
  4209.5 1305.23  4330.7 1298.79  4402.9 1291.54  4411.1 1288.73  4446.9 1284.92
  4604.1 1284.90  4885.2 1283.56  5011.2 1278.84  5011.6 1278.34  5015.8 1278.84
  5153.3 1285.31  5211.2 1285.20  5269.4 1286.24  5354.3 1299.70  5471.7 1307.86
#Mann=15,-1,0
  2889.3    0.07       0  3228.1    0.12       0  3426.4    0.07       0
  3429.5    0.12       0  3547.0    0.07       0  3571.9   0.035       0
  3785.5    0.07       0  3924.9   0.035       0  3965.6    0.07       0
  4209.5    0.12       0  4402.9    0.07       0  4604.1   0.035       0
  5011.2   0.035       0  5015.8   0.035       0  5211.2    0.07       0
Bank Sta=5011.2,5015.8
Exp/Cntr=0.3,0.1

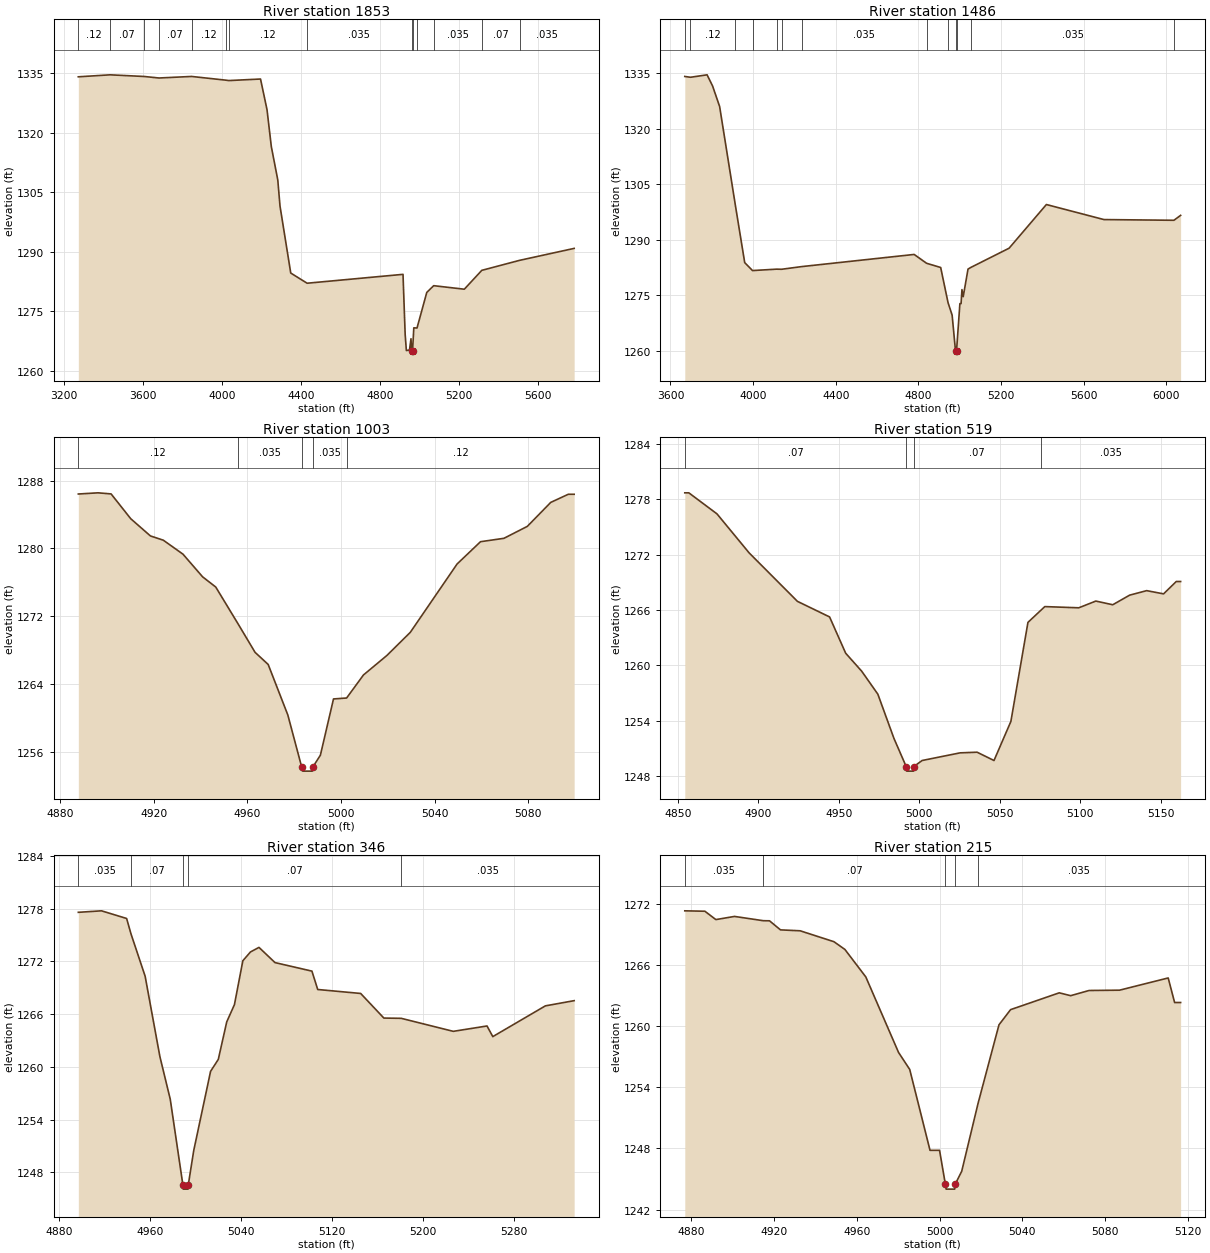
Type RM Length L Ch R = 1,1853,367,367,367
BEGIN DESCRIPTION:
Stream0142_DS 4.0
END DESCRIPTION:
XS GIS Cut Line= 3
      2051678.95     13896489.30      2050103.40     13895795.62
      2049384.61     13896118.56
#Sta/Elev= 30
  3273.1 1334.15  3434.0 1334.65  3607.0 1334.23  3680.9 1333.85  3846.2 1334.24
  4020.2 1333.30  4034.2 1333.20  4195.2 1333.59  4228.0 1325.89  4249.9 1316.54
  4282.6 1308.12  4293.9 1301.51  4348.2 1284.63  4431.0 1282.06  4916.4 1284.30
  4927.3 1269.12  4933.4 1265.07  4949.1 1265.22  4956.8 1268.05  4959.9 1264.92
  4960.2 1264.42  4964.6 1264.92  4971.0 1270.80  4987.3 1270.76  5036.7 1279.74
  5071.6 1281.44  5226.7 1280.55  5315.1 1285.31  5506.1 1287.83  5782.6 1290.85
#Mann=14,-1,0
  3273.1    0.12       0  3434.0    0.07       0  3607.0   0.035       0
  3680.9    0.07       0  3846.2    0.12       0  4020.2    0.07       0
  4034.2    0.12       0  4431.0   0.035       0  4959.9    0.05       0
  4964.6   0.035       0  4987.3    0.07       0  5071.6   0.035       0
  5315.1    0.07       0  5506.1   0.035       0
Bank Sta=4959.9,4964.6
Exp/Cntr=0.3,0.1

Type RM Length L Ch R = 1,1486,483,483,483
BEGIN DESCRIPTION:
Stream0142_DS 3.0
END DESCRIPTION:
XS GIS Cut Line= 3
      2051226.11     13895939.39      2049975.00     13895475.00
      2049109.32     13896097.19
#Sta/Elev= 30
  3669.3 1334.19  3696.7 1333.97  3777.2 1334.63  3803.8 1331.62  3837.9 1326.07
  3914.4 1299.27  3959.4 1283.84  3997.2 1281.69  4113.3 1282.07  4138.1 1282.04
  4234.9 1282.76  4779.8 1286.05  4840.0 1283.66  4908.2 1282.52  4943.9 1273.00
  4963.6 1269.65  4980.1 1259.86  4980.5 1259.36  4984.8 1259.86  5001.2 1272.75
  5006.9 1272.75  5011.2 1276.54  5017.3 1274.64  5040.6 1282.10  5056.4 1282.60
  5239.5 1287.74  5420.0 1299.55  5698.7 1295.48  6037.5 1295.29  6069.9 1296.62
#Mann=13,-1,0
  3669.3    0.07       0  3696.7    0.12       0  3914.4   0.035       0
  3997.2    0.12       0  4113.3   0.035       0  4138.1    0.12       0
  4234.9   0.035       0  4840.0    0.07       0  4943.9    0.12       0
  4980.1    0.05       0  4984.8    0.12       0  5056.4   0.035       0
  6037.5    0.07       0
Bank Sta=4980.1,4984.8
Exp/Cntr=0.3,0.1

Type RM Length L Ch R = 1,1003,484,484,484
BEGIN DESCRIPTION:
Stream0142_DS 2.0
END DESCRIPTION:
XS GIS Cut Line= 3
      2050175.01     13895075.01      2050075.00     13895025.00
      2049975.02     13895025.00
#Sta/Elev= 30
  4887.8 1286.42  4896.2 1286.56  4901.8 1286.43  4910.2 1283.50  4918.6 1281.47
  4924.1 1280.97  4932.5 1279.32  4940.9 1276.64  4946.5 1275.44  4956.0 1271.11
  4963.3 1267.73  4968.9 1266.30  4977.3 1260.33  4983.2 1254.21  4983.6 1253.71
  4987.7 1253.71  4988.0 1254.21  4991.2 1255.59  4996.8 1262.23  5002.4 1262.34
  5009.6 1265.06  5019.6 1267.36  5029.6 1270.09  5049.6 1278.16  5059.6 1280.79
  5069.6 1281.19  5079.6 1282.60  5089.6 1285.43  5097.1 1286.39  5099.6 1286.39
#Mann=5,-1,0
  4887.8    0.12       0  4956.0   0.035       0  4983.2   0.035       0
  4988.0   0.035       0  5002.4    0.12       0
Bank Sta=4983.2,4988
Exp/Cntr=0.3,0.1

Type RM Length L Ch R = 1,519,173,173,173
BEGIN DESCRIPTION:
Stream0142_DS 1.0
END DESCRIPTION:
XS GIS Cut Line= 3
      2050225.00     13894775.04      2050225.00     13894625.00
      2050074.96     13894574.99
#Sta/Elev= 30
  4854.2 1278.70  4856.7 1278.70  4874.2 1276.42  4894.2 1272.19  4924.2 1266.94
  4944.2 1265.25  4954.2 1261.32  4964.2 1259.36  4974.2 1256.88  4984.2 1252.09
  4991.8 1249.04  4992.2 1248.54  4996.3 1248.54  4996.6 1249.04  5001.7 1249.69
  5025.3 1250.52  5035.9 1250.59  5046.4 1249.69  5056.9 1253.93  5067.5 1264.66
  5075.4 1265.95  5078.0 1266.37  5099.1 1266.24  5109.7 1266.97  5120.2 1266.57
  5130.7 1267.61  5141.3 1268.10  5151.8 1267.75  5159.7 1269.09  5162.4 1269.09
#Mann=4,-1,0
  4854.2    0.07       0  4991.8    0.05       0  4996.6    0.07       0
  5075.4   0.035       0
Bank Sta=4991.8,4996.6
Exp/Cntr=0.3,0.1

Type RM Length L Ch R = 1,346,131,131,131
BEGIN DESCRIPTION:
Stream0142_DS 0.5
END DESCRIPTION:
XS GIS Cut Line= 4
      2050429.23     13894758.59      2050381.19     13894667.25
      2050323.11     13894603.70      2050080.65     13894556.02
#Sta/Elev= 30
  4896.8 1277.59  4917.2 1277.76  4939.3 1276.89  4943.1 1275.16  4955.6 1270.32
  4968.6 1261.17  4977.7 1256.33  4988.8 1246.60  4989.2 1246.10  4993.3 1246.10
  4993.6 1246.60  4998.4 1250.51  5013.2 1259.50  5020.0 1260.86  5027.4 1265.12
  5034.2 1267.09  5041.6 1272.08  5048.3 1273.08  5055.8 1273.60  5069.9 1271.87
  5102.4 1270.90  5107.5 1268.81  5145.3 1268.36  5165.7 1265.56  5181.0 1265.53
  5226.8 1264.05  5256.5 1264.66  5261.6 1263.45  5307.9 1266.95  5333.2 1267.54
#Mann=5,-1,0
  4896.8   0.035       0  4943.1    0.07       0  4988.8    0.05       0
  4993.6    0.07       0  5181.0   0.035       0
Bank Sta=4988.8,4993.6
Exp/Cntr=0.3,0.1

Type RM Length L Ch R = 1,215,0,0,0
BEGIN DESCRIPTION:
Stream0142_DS 0.0
END DESCRIPTION:
XS GIS Cut Line= 3
      2050587.66     13894613.68      2050471.40     13894573.52
      2050364.39     13894527.72
#Sta/Elev= 30
  4877.0 1271.33  4886.7 1271.29  4892.0 1270.47  4901.0 1270.78  4914.9 1270.36
  4917.9 1270.35  4923.2 1269.46  4932.7 1269.37  4949.0 1268.30  4954.3 1267.54
  4964.4 1264.84  4980.2 1257.43  4985.6 1255.76  4995.4 1247.82  5000.0 1247.82
  5002.8 1244.51  5003.2 1244.01  5007.3 1244.01  5007.6 1244.51  5010.7 1245.76
  5018.6 1252.43  5028.7 1260.14  5034.3 1261.63  5057.8 1263.28  5063.3 1263.00
  5072.2 1263.51  5086.9 1263.54  5110.4 1264.74  5113.5 1262.33  5116.4 1262.33
#Mann=5,-1,0
  4877.0   0.035       0  4914.9    0.07       0  5002.8    0.05       0
  5007.6    0.07       0  5018.6   0.035       0
Bank Sta=5002.8,5007.6
Exp/Cntr=0.3,0.1

Chan Stop Cuts=-1