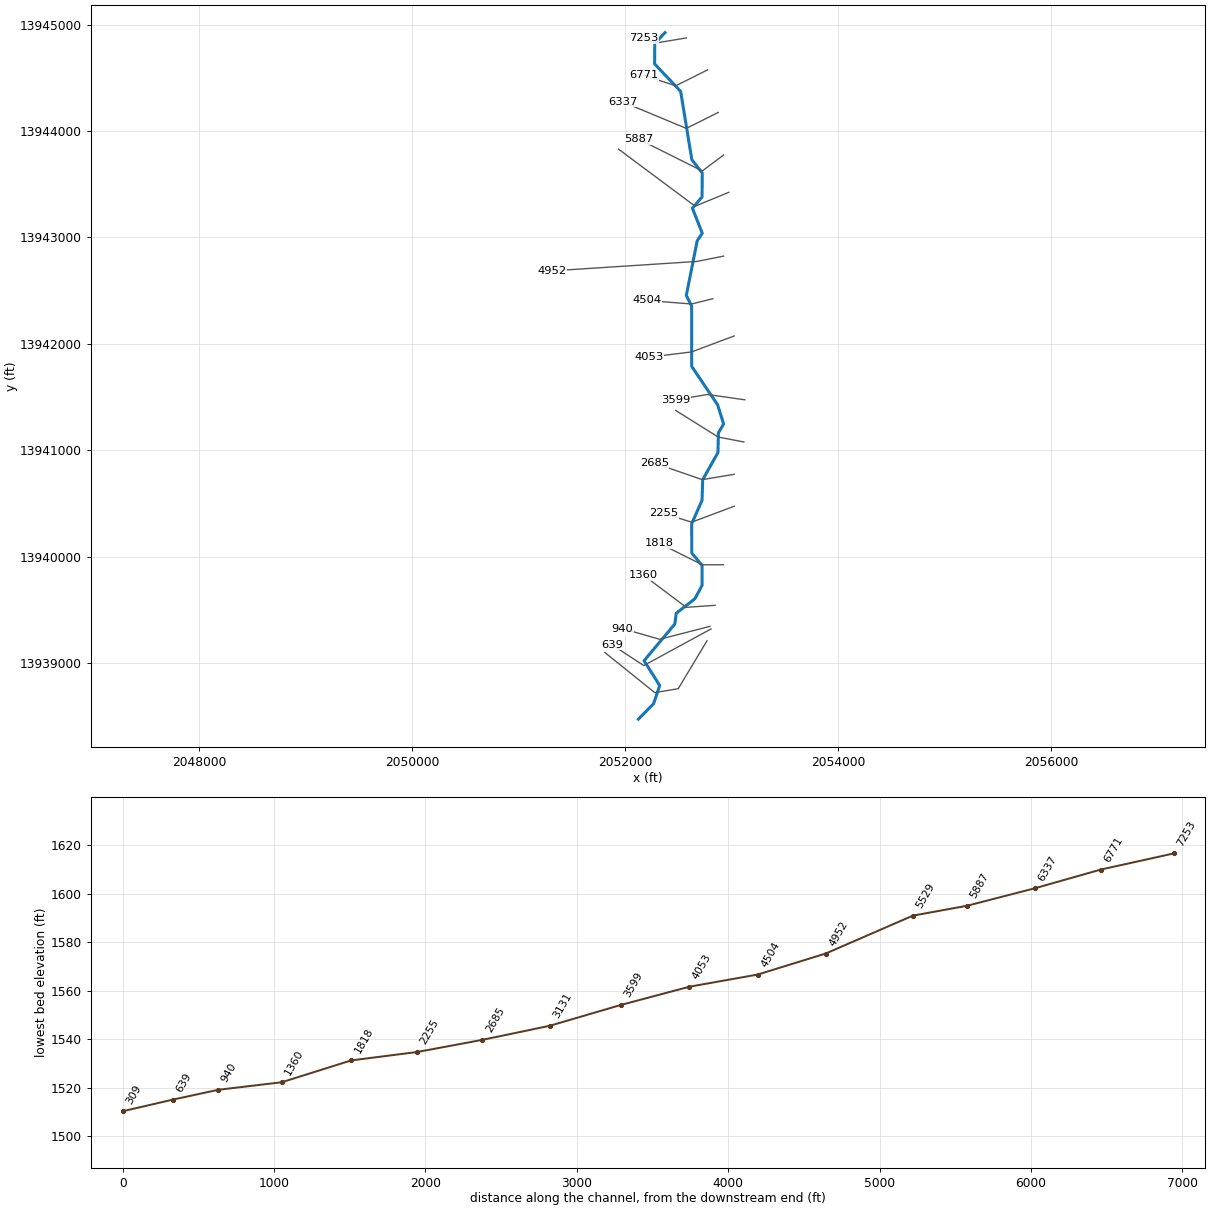
--- Stream0143_DS.prj (project) ---

Proj Title=Stream0143_DS Base Level Engineering
Current Plan=p01
Default Exp/Contr=0.3,0.1
English Units
Geom File=g01
Flow File=f01
Plan File=p01
BEGIN DESCRIPTION:
Stream0143_DS
END DESCRIPTION:

--- Stream0143_DS.p01 (plan) ---

Plan Title=Multiple Run
Short Identifier=Multiple
Geom File=g01
Flow File=f01
Subcritical Flow
K Sum by GR= 0
Std Step Tol= 0.01
Critical Tol= 0.01
Num of Std Step Trials= 20
Max Error Tol= 0.3
Flow Tol Ratio= 0.001
Split Flow NTrial= 30
Split Flow Tol= 0.02
Split Flow Ratio= 0.02
Log Output Level= 0
Friction Slope Method= 1
Unsteady Friction Slope Method= 2
Unsteady Bridges Friction Slope Method= 1
Parabolic Critical Depth
Global Vel Dist=  1 , 1 , 1
Global Log Level= 0
CheckData=True
Encroach Param= -1, 0, 0, 0
BEGIN DESCRIPTION:
Multiple Run
END DESCRIPTION:

--- Stream0143_DS.f01 (steady flow) ---

Flow Title=Multiple
Number of Profiles=7
Profile Names=10-year,25-year,50-year,1pct_min,100-year,1pct_plu,500-year
River Rch & RM= Stream0143_DS,Reach-1,7253
    1134    1975    2796    1923    3836    7654    7161
River Rch & RM= Stream0143_DS,Reach-1,4952
    1785    3174    4558    3172    6328   12626   12106
Boundary for River Rch & Prof#=Stream0143_DS,Reach-1,1
Up Type=0
Dn Type=3
Dn Slope=0.005
Boundary for River Rch & Prof#=Stream0143_DS,Reach-1,2
Up Type=0
Dn Type=3
Dn Slope=0.005
Boundary for River Rch & Prof#=Stream0143_DS,Reach-1,3
Up Type=0
Dn Type=3
Dn Slope=0.005
Boundary for River Rch & Prof#=Stream0143_DS,Reach-1,4
Up Type=0
Dn Type=3
Dn Slope=0.005
Boundary for River Rch & Prof#=Stream0143_DS,Reach-1,5
Up Type=0
Dn Type=3
Dn Slope=0.005
Boundary for River Rch & Prof#=Stream0143_DS,Reach-1,6
Up Type=0
Dn Type=3
Dn Slope=0.005
Boundary for River Rch & Prof#=Stream0143_DS,Reach-1,7
Up Type=0
Dn Type=3
Dn Slope=0.005

--- Stream0143_DS.g01 (geometry) ---

Geom Title=Existing Conditions

River Reach=Stream0143_DS,Reach-1
Reach XY= 30
      2052375.00     13944925.00      2052278.48     13944823.56
      2052277.06     13944630.85      2052521.39     13944373.50
      2052627.07     13943730.86      2052724.91     13943606.78
      2052722.93     13943380.85      2052632.30     13943275.08
      2052724.62     13943040.27      2052677.38     13942969.47
      2052574.72     13942454.82      2052624.77     13942356.74
      2052625.54     13941788.86      2052869.46     13941427.42
      2052925.38     13941247.81      2052876.24     13941164.50
      2052872.65     13940980.52      2052728.75     13940723.45
      2052722.74     13940530.94      2052625.68     13940311.08
      2052626.06     13940035.44      2052722.82     13939919.55
      2052722.76     13939730.93      2052655.22     13939604.91
      2052480.26     13939469.53      2052467.12     13939368.88
      2052178.31     13939023.26      2052324.97     13938790.42
      2052267.14     13938618.83      2052125.00     13938475.00

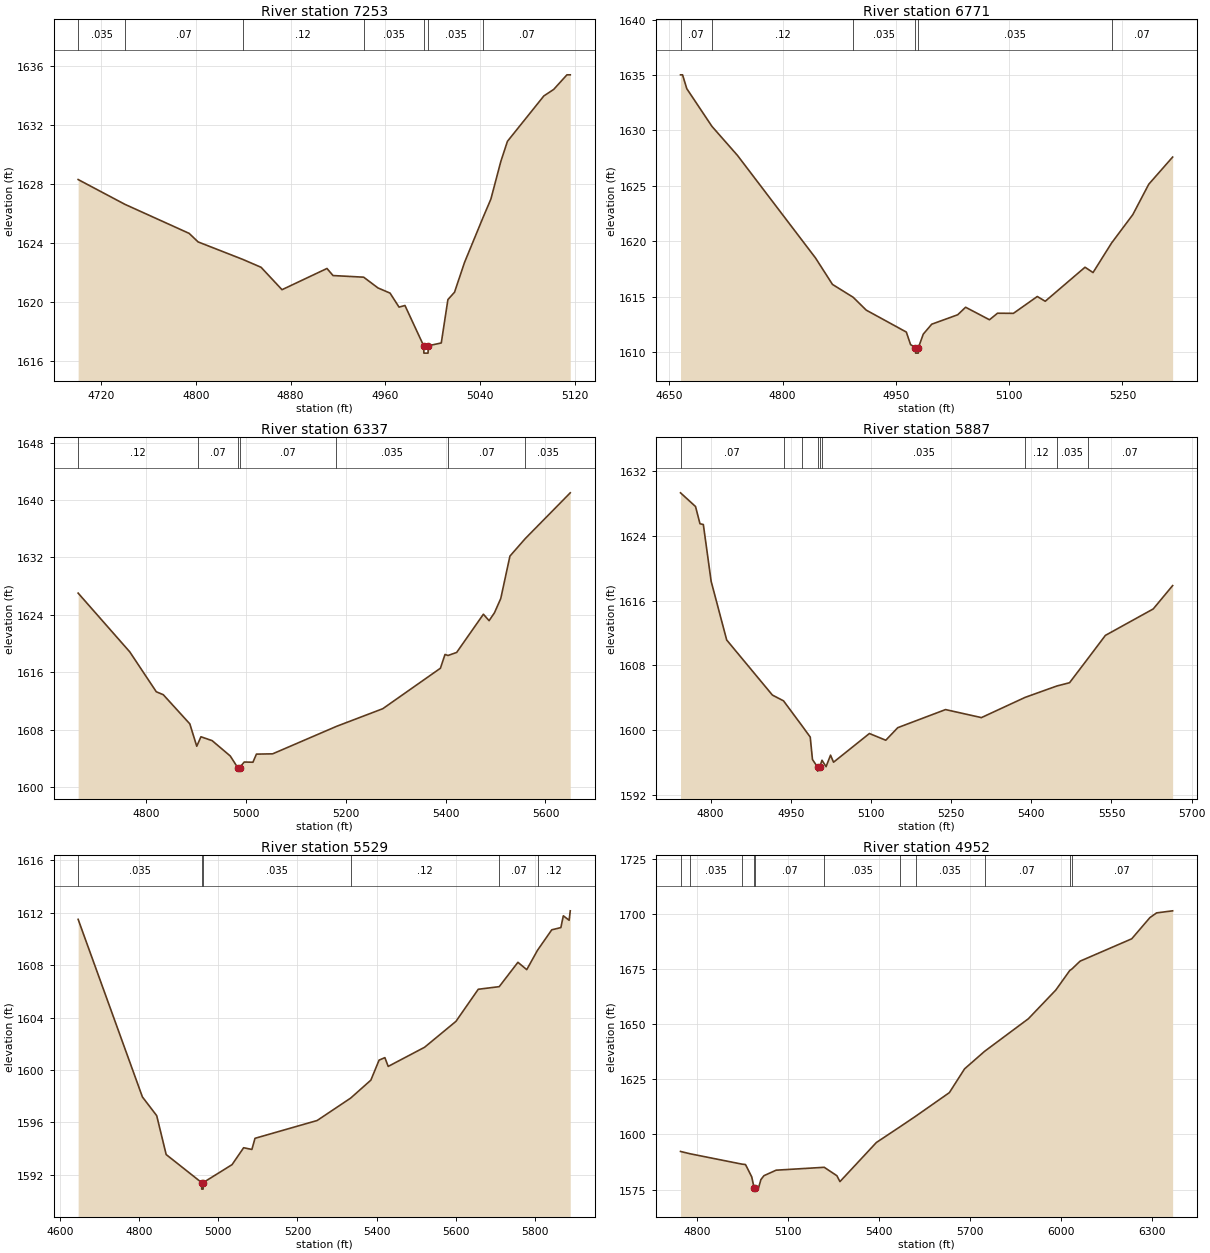
Type RM Length L Ch R = 1,7253,482,482,482
BEGIN DESCRIPTION:
Stream0143_DS 16.0
END DESCRIPTION:
XS GIS Cut Line= 3
      2052574.98     13944875.00      2052275.00     13944825.00
      2052175.02     13944874.99
#Sta/Elev= 30
  4700.5 1628.32  4740.0 1626.64  4794.3 1624.67  4801.9 1624.09  4839.5 1622.91
  4855.1 1622.37  4872.8 1620.85  4910.8 1622.29  4915.9 1621.81  4941.8 1621.70
  4953.9 1620.97  4964.1 1620.62  4971.7 1619.67  4976.7 1619.78  4992.5 1617.05
  4992.7 1616.55  4996.2 1616.55  4996.5 1617.05  5007.4 1617.24  5013.0 1620.18
  5018.6 1620.68  5027.0 1622.69  5042.6 1625.73  5049.3 1626.99  5057.7 1629.54
  5063.3 1630.91  5094.1 1633.99  5102.4 1634.43  5113.6 1635.42  5116.4 1635.42
#Mann=7,-1,0
  4700.5   0.035       0  4740.0    0.07       0  4839.5    0.12       0
  4941.8   0.035       0  4992.5   0.035       0  4996.5   0.035       0
  5042.6    0.07       0
Bank Sta=4992.5,4996.5
Exp/Cntr=0.3,0.1

Type RM Length L Ch R = 1,6771,434,434,434
BEGIN DESCRIPTION:
Stream0143_DS 15.0
END DESCRIPTION:
XS GIS Cut Line= 3
      2052774.96     13944574.98      2052475.00     13944425.00
      2052174.99     13944525.00
#Sta/Elev= 30
  4664.9 1635.01  4667.6 1635.01  4673.2 1633.76  4706.5 1630.36  4740.3 1627.74
  4843.7 1618.48  4866.1 1616.10  4893.5 1614.94  4910.8 1613.78  4963.9 1611.80
  4969.5 1610.67  4975.9 1610.40  4976.2 1609.90  4979.7 1609.90  4979.9 1610.40
  4986.3 1611.61  4997.5 1612.51  5031.9 1613.36  5042.4 1614.04  5074.0 1612.91
  5084.6 1613.50  5105.7 1613.49  5137.3 1615.01  5147.8 1614.58  5200.5 1617.65
  5211.1 1617.17  5235.6 1619.83  5263.8 1622.40  5284.9 1625.14  5316.5 1627.59
#Mann=6,-1,0
  4664.9    0.07       0  4706.5    0.12       0  4893.5   0.035       0
  4975.9   0.035       0  4979.9   0.035       0  5235.6    0.07       0
Bank Sta=4975.9,4979.9
Exp/Cntr=0.3,0.1

Type RM Length L Ch R = 1,6337,450,450,450
BEGIN DESCRIPTION:
Stream0143_DS 14.0
END DESCRIPTION:
XS GIS Cut Line= 3
      2052874.96     13944174.98      2052575.00     13944025.00
      2051974.97     13944275.01
#Sta/Elev= 30
  4664.2 1627.03  4767.6 1618.84  4820.7 1613.28  4834.7 1612.87  4887.8 1608.81
  4901.7 1605.69  4905.1 1606.22  4910.1 1607.01  4932.5 1606.47  4968.8 1604.33
  4983.6 1602.72  4983.8 1602.22  4987.6 1602.72  4996.8 1603.49  5014.2 1603.46
  5021.2 1604.59  5053.7 1604.63  5181.5 1608.46  5274.2 1610.92  5389.6 1616.56
  5398.8 1618.48  5404.8 1618.34  5422.1 1618.76  5475.7 1624.09  5487.1 1623.19
  5497.9 1624.30  5510.4 1626.27  5528.8 1632.19  5559.5 1634.63  5649.6 1641.01
#Mann=7,-1,0
  4664.2    0.12       0  4905.1    0.07       0  4983.6    0.05       0
  4987.6    0.07       0  5181.5   0.035       0  5404.8    0.07       0
  5559.5   0.035       0
Bank Sta=4983.6,4987.6
Exp/Cntr=0.3,0.1

Type RM Length L Ch R = 1,5887,358,358,358
BEGIN DESCRIPTION:
Stream0143_DS 13.0
END DESCRIPTION:
XS GIS Cut Line= 3
      2052924.98     13943774.99      2052725.00     13943625.00
      2052125.00     13943925.00
#Sta/Elev= 30
  4743.6 1629.29  4771.7 1627.60  4780.0 1625.48  4786.3 1625.38  4800.9 1618.38
  4830.0 1611.14  4915.5 1604.35  4936.3 1603.64  4970.3 1600.62  4986.3 1599.17
  4990.5 1596.40  5000.0 1595.47  5000.2 1594.97  5004.0 1595.47  5008.3 1596.31
  5015.9 1595.52  5024.3 1596.94  5029.9 1596.07  5097.0 1599.61  5127.7 1598.78
  5150.1 1600.33  5239.5 1602.56  5306.6 1601.57  5388.2 1604.06  5447.8 1605.47
  5471.5 1605.87  5505.5 1608.82  5538.6 1611.71  5628.1 1614.97  5664.4 1617.85
#Mann=9,-1,0
  4743.6    0.07       0  4936.3   0.035       0  4970.3    0.07       0
  5000.0    0.05       0  5004.0    0.07       0  5008.3   0.035       0
  5388.2    0.12       0  5447.8   0.035       0  5505.5    0.07       0
Bank Sta=5000,5004
Exp/Cntr=0.3,0.1

Type RM Length L Ch R = 1,5529,577,577,577
BEGIN DESCRIPTION:
Stream0143_DS 12.0
END DESCRIPTION:
XS GIS Cut Line= 3
      2052974.97     13943424.99      2052657.70     13943294.03
      2051936.95     13943831.13
#Sta/Elev= 30
  4646.4 1611.50  4808.6 1597.94  4844.7 1596.51  4868.6 1593.54  4958.1 1591.40
  4958.3 1590.90  4961.8 1590.90  4962.1 1591.40  5034.9 1592.77  5064.1 1594.06
  5084.9 1593.93  5092.8 1594.78  5249.7 1596.14  5334.2 1597.85  5385.2 1599.22
  5406.0 1600.75  5420.6 1600.94  5429.0 1600.27  5520.7 1601.73  5600.0 1603.71
  5656.3 1606.16  5709.2 1606.36  5756.4 1608.22  5778.7 1607.66  5806.1 1609.15
  5841.8 1610.70  5864.8 1610.87  5871.0 1611.77  5885.7 1611.43  5888.5 1612.15
#Mann=6,-1,0
  4646.4   0.035       0  4958.1   0.035       0  4962.1   0.035       0
  5334.2    0.12       0  5709.2    0.07       0  5806.1    0.12       0
Bank Sta=4958.1,4962.1
Exp/Cntr=0.3,0.1

Type RM Length L Ch R = 1,4952,448,448,448
BEGIN DESCRIPTION:
Stream0143_DS 11.0
END DESCRIPTION:
XS GIS Cut Line= 3
      2052925.04     13942825.01      2052675.00     13942775.00
      2051310.46     13942686.39
#Sta/Elev= 30
  4745.4 1592.32  4775.9 1591.30  4947.8 1586.58  4959.6 1586.39  4980.0 1580.86
  4988.2 1575.75  4988.4 1575.25  4992.2 1575.75  5002.9 1575.97  5010.4 1579.56
  5020.4 1581.34  5060.5 1583.83  5219.2 1585.14  5260.9 1581.33  5271.0 1578.65
  5391.2 1596.39  5468.6 1603.45  5520.7 1608.28  5631.7 1618.96  5681.8 1629.73
  5747.9 1637.68  5892.3 1652.45  5982.5 1665.42  6028.8 1674.32  6035.7 1674.97
  6062.6 1678.52  6233.0 1688.66  6293.1 1698.29  6315.1 1700.40  6367.8 1701.33
#Mann=11,-1,0
  4745.4    0.07       0  4775.9   0.035       0  4947.8    0.07       0
  4988.2    0.05       0  4992.2    0.07       0  5219.2   0.035       0
  5468.6    0.07       0  5520.7   0.035       0  5747.9    0.07       0
  6028.8   0.035       0  6035.7    0.07       0
Bank Sta=4988.2,4992.2
Exp/Cntr=0.3,0.1

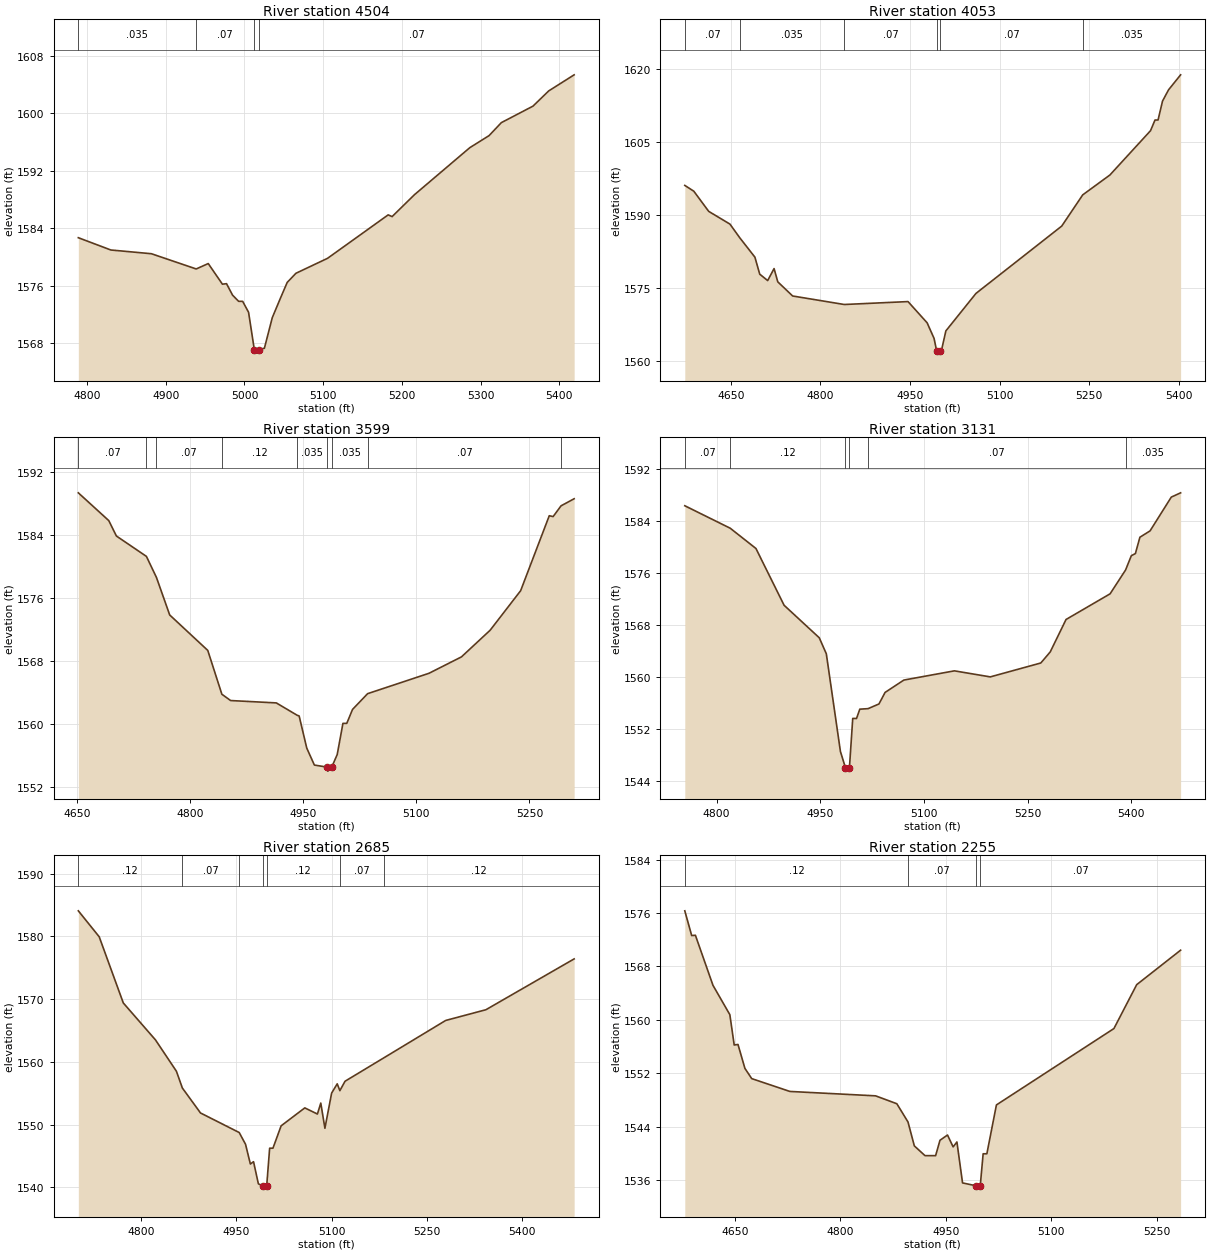
Type RM Length L Ch R = 1,4504,451,451,451
BEGIN DESCRIPTION:
Stream0143_DS 10.0
END DESCRIPTION:
XS GIS Cut Line= 3
      2052825.04     13942425.01      2052625.00     13942375.00
      2052202.83     13942408.61
#Sta/Elev= 30
  4789.0 1582.68  4830.3 1580.97  4881.8 1580.45  4938.7 1578.33  4954.0 1579.08
  4972.0 1576.21  4977.2 1576.28  4984.9 1574.68  4992.6 1573.82  4997.7 1573.82
  5005.2 1572.30  5012.5 1567.11  5013.0 1566.61  5017.6 1566.61  5018.0 1567.11
  5025.3 1567.29  5035.3 1571.54  5045.4 1574.19  5054.3 1576.46  5065.4 1577.73
  5105.5 1579.81  5182.5 1585.86  5187.5 1585.62  5215.9 1588.67  5286.1 1595.21
  5310.7 1596.90  5326.2 1598.70  5366.4 1601.00  5386.4 1603.12  5418.7 1605.36
#Mann=4,-1,0
  4789.0   0.035       0  4938.7    0.07       0  5012.5    0.05       0
  5018.0    0.07       0
Bank Sta=5012.5,5018
Exp/Cntr=0.3,0.1

Type RM Length L Ch R = 1,4053,454,454,454
BEGIN DESCRIPTION:
Stream0143_DS 9.0
END DESCRIPTION:
XS GIS Cut Line= 3
      2053024.96     13942074.99      2052625.00     13941925.00
      2052224.98     13941875.00
#Sta/Elev= 30
  4572.8 1596.06  4587.9 1594.87  4612.8 1590.73  4648.4 1588.11  4665.1 1585.26
  4690.2 1581.32  4698.3 1577.82  4711.6 1576.51  4722.3 1578.97  4728.5 1576.25
  4753.4 1573.34  4839.9 1571.59  4946.6 1572.19  4978.6 1567.83  4990.2 1564.63
  4994.5 1562.10  4994.9 1561.60  5000.0 1562.10  5002.5 1562.10  5010.0 1566.17
  5060.4 1573.87  5204.0 1587.70  5239.2 1594.12  5284.7 1598.20  5352.7 1607.30
  5360.2 1609.49  5365.3 1609.50  5372.8 1613.38  5382.9 1615.70  5403.1 1618.78
#Mann=6,-1,0
  4572.8    0.07       0  4665.1   0.035       0  4839.9    0.07       0
  4994.5    0.05       0  5000.0    0.07       0  5239.2   0.035       0
Bank Sta=4994.5,5000
Exp/Cntr=0.3,0.1

Type RM Length L Ch R = 1,3599,468,468,468
BEGIN DESCRIPTION:
Stream0143_DS 8.0
END DESCRIPTION:
XS GIS Cut Line= 3
      2053124.99     13941475.00      2052775.00     13941525.00
      2052474.99     13941475.00
#Sta/Elev= 30
  4651.6 1589.31  4692.0 1585.79  4702.1 1583.84  4741.9 1581.26  4755.2 1578.60
  4772.8 1573.84  4823.3 1569.35  4842.0 1563.80  4853.6 1563.00  4914.2 1562.70
  4942.0 1561.13  4944.5 1561.05  4954.6 1556.98  4964.7 1554.83  4982.1 1554.56
  4982.6 1554.06  4987.7 1554.56  4995.0 1556.16  5002.6 1560.11  5007.7 1560.11
  5015.3 1561.87  5035.3 1563.87  5116.7 1566.45  5159.8 1568.53  5197.8 1571.90
  5238.3 1576.91  5276.3 1586.41  5281.4 1586.30  5291.9 1587.66  5309.3 1588.56
#Mann=9,-1,0
  4651.6    0.07       0  4741.9    0.12       0  4755.2    0.07       0
  4842.0    0.12       0  4942.0   0.035       0  4982.1   0.035       0
  4987.7   0.035       0  5035.3    0.07       0  5291.9   0.035       0
Bank Sta=4982.1,4987.7
Exp/Cntr=0.3,0.1

Type RM Length L Ch R = 1,3131,446,446,446
BEGIN DESCRIPTION:
Stream0143_DS 7.0
END DESCRIPTION:
XS GIS Cut Line= 3
      2053116.03     13941078.75      2052875.00     13941125.00
      2052475.03     13941374.98
#Sta/Elev= 30
  4754.1 1586.36  4819.8 1582.90  4857.0 1579.78  4897.7 1571.04  4948.6 1566.03
  4958.8 1563.56  4979.2 1548.52  4986.5 1546.00  4986.9 1545.50  4992.2 1546.00
  4997.0 1553.61  5002.5 1553.61  5007.2 1555.04  5019.2 1555.12  5034.9 1555.84
  5043.8 1557.62  5070.9 1559.52  5144.0 1560.94  5195.9 1560.01  5269.0 1562.15
  5282.6 1563.85  5305.5 1568.85  5369.2 1572.80  5391.6 1576.47  5399.9 1578.67
  5405.8 1579.00  5412.3 1581.51  5427.0 1582.49  5457.7 1587.69  5471.2 1588.35
#Mann=6,-1,0
  4754.1    0.07       0  4819.8    0.12       0  4986.5    0.05       0
  4992.2    0.12       0  5019.2    0.07       0  5391.6   0.035       0
Bank Sta=4986.5,4992.2
Exp/Cntr=0.3,0.1

Type RM Length L Ch R = 1,2685,430,430,430
BEGIN DESCRIPTION:
Stream0143_DS 6.0
END DESCRIPTION:
XS GIS Cut Line= 3
      2053024.97     13940775.00      2052725.00     13940725.00
      2052273.51     13940880.41
#Sta/Elev= 30
  4700.9 1584.09  4733.8 1579.95  4771.8 1569.39  4822.5 1563.50  4855.5 1558.50
  4864.9 1555.82  4893.5 1551.84  4954.5 1548.72  4964.5 1546.84  4972.1 1543.69
  4977.1 1544.07  4984.7 1540.54  4991.9 1540.19  4992.4 1539.69  4997.8 1540.19
  5002.5 1546.22  5007.7 1546.22  5020.6 1549.79  5057.9 1552.65  5077.8 1551.67
  5083.1 1553.42  5089.6 1549.40  5100.2 1555.01  5109.0 1556.49  5113.2 1555.40
  5121.3 1556.90  5182.9 1560.66  5280.0 1566.60  5343.4 1568.31  5482.5 1576.42
#Mann=7,-1,0
  4700.9    0.12       0  4864.9    0.07       0  4954.5    0.12       0
  4991.9    0.05       0  4997.8    0.12       0  5113.2    0.07       0
  5182.9    0.12       0
Bank Sta=4991.9,4997.8
Exp/Cntr=0.3,0.1

Type RM Length L Ch R = 1,2255,437,437,437
BEGIN DESCRIPTION:
Stream0143_DS 5.0
END DESCRIPTION:
XS GIS Cut Line= 3
      2053025.01     13940475.00      2052625.00     13940325.00
      2052359.53     13940408.47
#Sta/Elev= 30
  4578.8 1576.33  4588.6 1572.63  4593.9 1572.67  4618.9 1565.18  4642.9 1560.79
  4649.1 1556.25  4654.5 1556.33  4664.3 1552.76  4674.0 1551.22  4728.3 1549.30
  4850.3 1548.64  4880.5 1547.46  4896.4 1544.73  4905.4 1541.15  4920.6 1539.69
  4935.7 1539.69  4941.9 1541.99  4952.6 1542.78  4960.6 1541.00  4966.0 1541.74
  4974.0 1535.61  4993.3 1535.18  4993.8 1534.68  4999.2 1535.18  5003.3 1539.97
  5008.6 1539.97  5022.2 1547.28  5189.4 1558.71  5221.8 1565.28  5284.3 1570.44
#Mann=4,-1,0
  4578.8    0.12       0  4896.4    0.07       0  4993.3    0.05       0
  4999.2    0.07       0
Bank Sta=4993.3,4999.2
Exp/Cntr=0.3,0.1

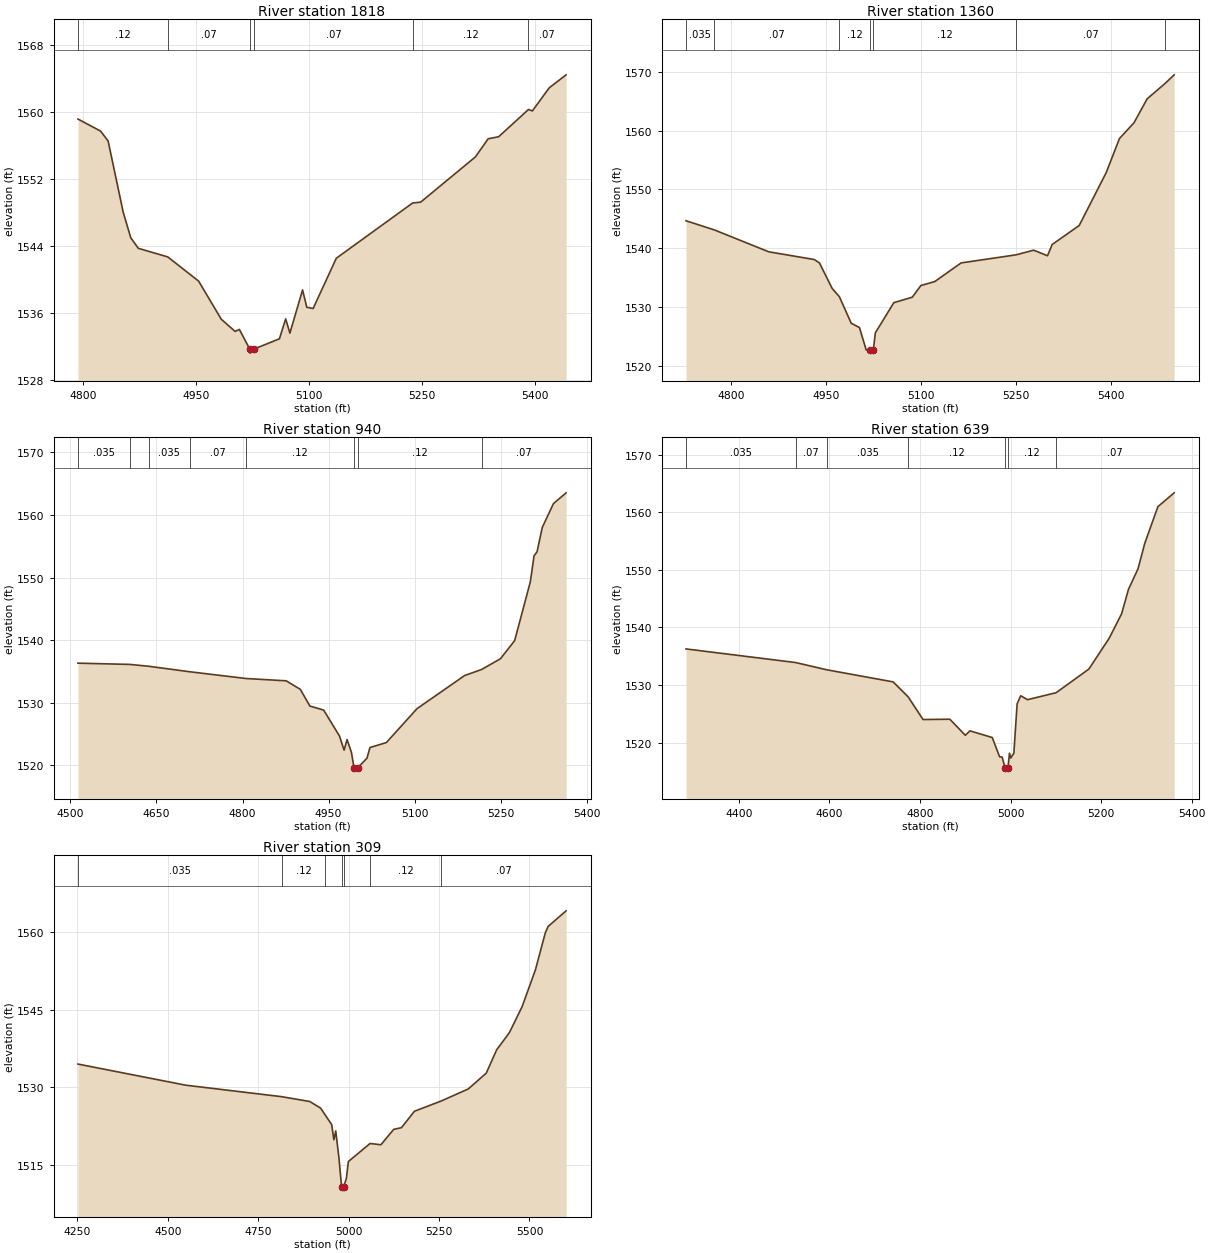
Type RM Length L Ch R = 1,1818,458,458,458
BEGIN DESCRIPTION:
Stream0143_DS 4.0
END DESCRIPTION:
XS GIS Cut Line= 3
      2052924.98     13939925.00      2052725.00     13939925.00
      2052324.99     13940125.00
#Sta/Elev= 30
  4793.6 1559.17  4823.6 1557.73  4833.6 1556.55  4853.6 1548.04  4863.6 1544.99
  4873.6 1543.73  4912.7 1542.70  4953.6 1539.81  4983.6 1535.26  5002.0 1533.80
  5007.6 1534.04  5021.3 1531.71  5021.8 1531.21  5027.3 1531.71  5060.7 1532.92
  5069.0 1535.30  5074.6 1533.60  5091.4 1538.76  5097.0 1536.69  5105.4 1536.54
  5136.1 1542.54  5237.3 1549.14  5247.9 1549.24  5320.6 1554.65  5337.4 1556.81
  5351.4 1557.06  5390.9 1560.31  5396.1 1560.14  5418.4 1562.90  5440.8 1564.45
#Mann=6,-1,0
  4793.6    0.12       0  4912.7    0.07       0  5021.3    0.05       0
  5027.3    0.07       0  5237.3    0.12       0  5390.9    0.07       0
Bank Sta=5021.3,5027.3
Exp/Cntr=0.3,0.1

Type RM Length L Ch R = 1,1360,420,420,420
BEGIN DESCRIPTION:
Stream0143_DS 3.0
END DESCRIPTION:
XS GIS Cut Line= 3
      2052845.24     13939544.03      2052575.00     13939525.00
      2052175.01     13939824.99
#Sta/Elev= 30
  4729.4 1544.69  4774.3 1543.13  4860.0 1539.42  4932.1 1538.10  4940.2 1537.52
  4960.2 1533.20  4971.6 1531.79  4990.3 1527.29  5003.4 1526.54  5013.9 1522.76
  5019.2 1522.71  5019.7 1522.21  5025.2 1522.71  5028.4 1525.65  5057.6 1530.78
  5086.8 1531.71  5100.3 1533.69  5122.2 1534.36  5163.9 1537.53  5250.6 1538.90
  5278.4 1539.69  5300.3 1538.75  5307.6 1540.65  5350.3 1543.88  5393.0 1552.87
  5413.9 1558.65  5436.8 1561.32  5457.6 1565.39  5486.1 1568.02  5500.3 1569.47
#Mann=7,-1,0
  4729.4   0.035       0  4774.3    0.07       0  4971.6    0.12       0
  5019.2    0.05       0  5025.2    0.12       0  5250.6    0.07       0
  5486.1    0.12       0
Bank Sta=5019.2,5025.2
Exp/Cntr=0.3,0.1

Type RM Length L Ch R = 1,940,301,301,301
BEGIN DESCRIPTION:
Stream0143_DS 2.0
END DESCRIPTION:
XS GIS Cut Line= 3
      2052796.57     13939346.11      2052325.00     13939225.00
      2051974.98     13939325.00
#Sta/Elev= 30
  4513.1 1536.34  4603.9 1536.14  4636.7 1535.84  4707.8 1534.97  4805.9 1533.89
  4876.1 1533.52  4900.7 1532.16  4917.4 1529.49  4941.4 1528.85  4969.0 1524.70
  4977.0 1522.45  4982.2 1524.14  4989.7 1522.13  4994.4 1519.60  4994.9 1519.10
  5000.4 1519.60  5016.9 1521.17  5022.1 1522.87  5050.7 1523.66  5104.0 1529.07
  5187.2 1534.37  5216.7 1535.33  5249.6 1537.05  5274.3 1539.94  5301.6 1549.32
  5308.1 1553.48  5313.3 1554.11  5322.4 1558.00  5341.9 1561.82  5364.0 1563.54
#Mann=8,-1,0
  4513.1   0.035       0  4603.9    0.07       0  4636.7   0.035       0
  4707.8    0.07       0  4805.9    0.12       0  4994.4    0.05       0
  5000.4    0.12       0  5216.7    0.07       0
Bank Sta=4994.4,5000.4
Exp/Cntr=0.3,0.1

Type RM Length L Ch R = 1,639,330,330,330
BEGIN DESCRIPTION:
Stream0143_DS 1.0
END DESCRIPTION:
XS GIS Cut Line= 3
      2052806.99     13939321.80      2052175.06     13938978.06
      2051874.99     13939175.01
#Sta/Elev= 30
  4283.1 1536.27  4525.4 1533.90  4594.2 1532.64  4740.7 1530.54  4773.9 1527.93
  4806.7 1524.00  4865.9 1524.05  4900.1 1521.26  4910.2 1522.03  4959.6 1520.87
  4975.8 1517.53  4981.5 1517.46  4988.1 1515.53  4988.6 1515.03  4994.2 1515.53
  4997.6 1518.15  5000.4 1517.31  5007.3 1518.15  5014.5 1526.72  5022.4 1528.13
  5037.5 1527.45  5100.7 1528.66  5173.0 1532.77  5217.9 1538.13  5245.3 1542.38
  5260.4 1546.61  5281.5 1550.19  5296.6 1554.66  5325.5 1561.00  5361.4 1563.40
#Mann=7,-1,0
  4283.1   0.035       0  4525.4    0.07       0  4594.2   0.035       0
  4773.9    0.12       0  4988.1    0.05       0  4994.2    0.12       0
  5100.7    0.07       0
Bank Sta=4988.1,4994.2
Exp/Cntr=0.3,0.1

Type RM Length L Ch R = 1,309,0,0,0
BEGIN DESCRIPTION:
Stream0143_DS 0.0
END DESCRIPTION:
XS GIS Cut Line= 4
      2052769.41     13939210.52      2052499.18     13938760.65
      2052278.89     13938723.41      2051810.11     13939100.15
#Sta/Elev= 30
  4251.8 1534.46  4549.9 1530.37  4814.7 1528.15  4892.4 1527.22  4922.8 1525.93
  4936.0 1524.54  4953.2 1522.76  4959.4 1519.81  4964.5 1521.53  4973.5 1516.20
  4980.6 1510.76  4981.1 1510.26  4986.7 1510.76  4993.8 1512.33  4999.4 1515.60
  5059.4 1519.09  5089.4 1518.85  5124.6 1521.82  5146.1 1522.15  5182.1 1525.33
  5256.4 1527.32  5331.0 1529.65  5380.6 1532.70  5409.4 1537.22  5444.6 1540.54
  5479.8 1545.58  5516.5 1552.68  5543.8 1559.84  5551.7 1561.10  5601.4 1564.11
#Mann=7,-1,0
  4251.8   0.035       0  4814.7    0.12       0  4936.0    0.07       0
  4980.6    0.05       0  4986.7    0.07       0  5059.4    0.12       0
  5256.4    0.07       0
Bank Sta=4980.6,4986.7
Exp/Cntr=0.3,0.1

Chan Stop Cuts=-1