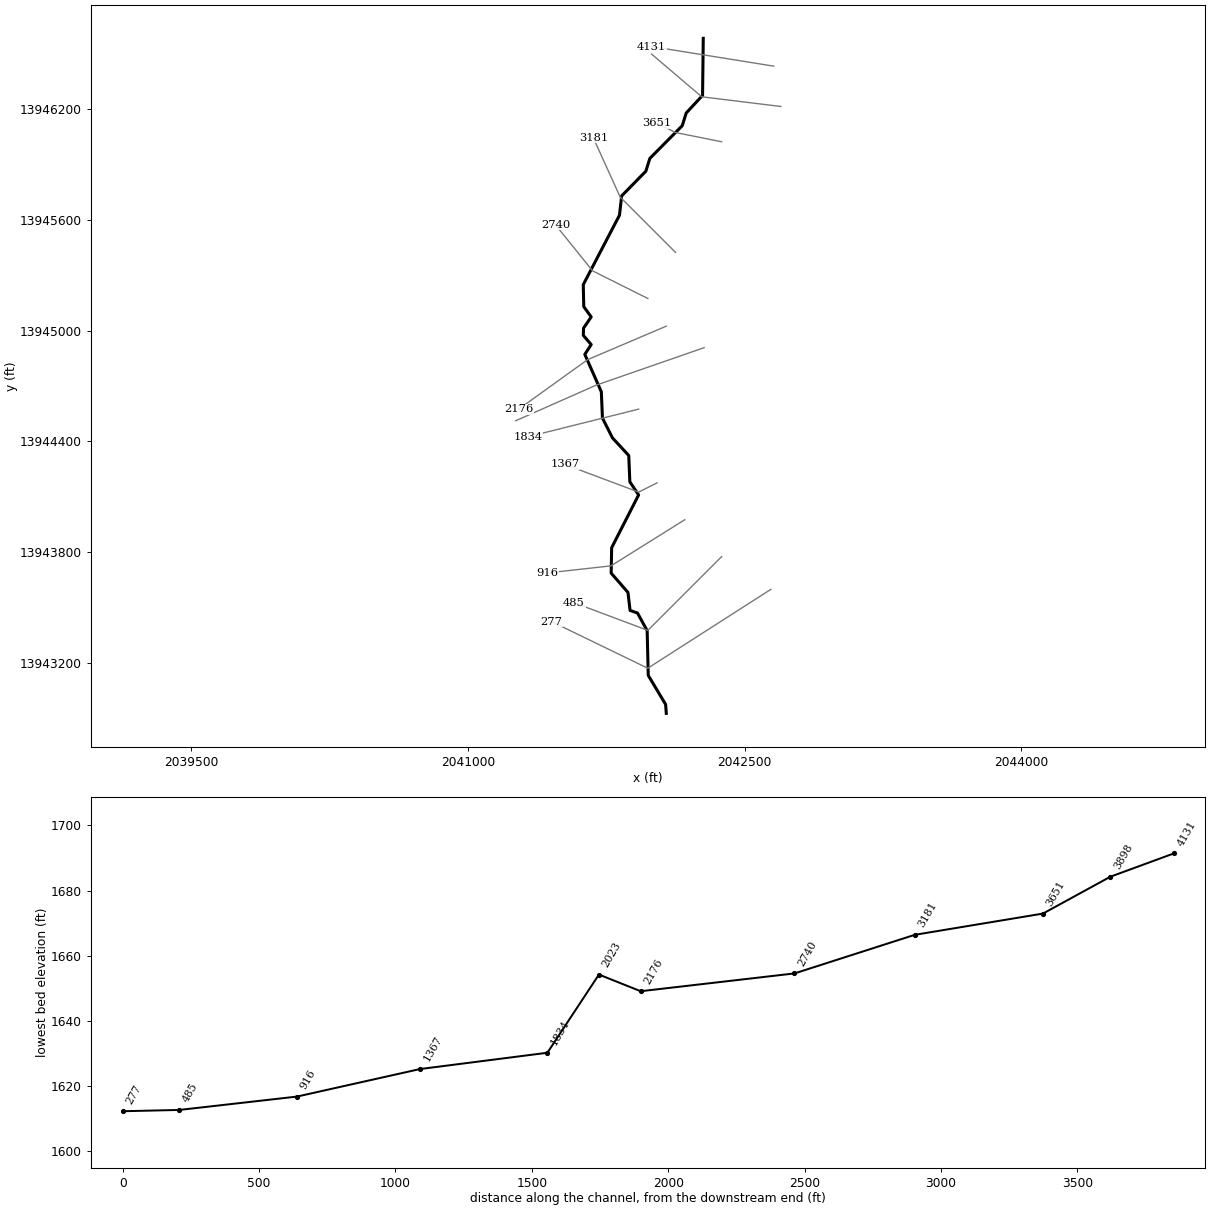
--- Stream0144_DS.prj (project) ---

Proj Title=Stream0144_DS Base Level Engineering
Current Plan=p01
Default Exp/Contr=0.3,0.1
English Units
Geom File=g01
Flow File=f01
Plan File=p01
BEGIN DESCRIPTION:
Stream0144_DS
END DESCRIPTION:

--- Stream0144_DS.p01 (plan) ---

Plan Title=Multiple Run
Short Identifier=Multiple
Geom File=g01
Flow File=f01
Subcritical Flow
K Sum by GR= 0
Std Step Tol= 0.01
Critical Tol= 0.01
Num of Std Step Trials= 20
Max Error Tol= 0.3
Flow Tol Ratio= 0.001
Split Flow NTrial= 30
Split Flow Tol= 0.02
Split Flow Ratio= 0.02
Log Output Level= 0
Friction Slope Method= 1
Unsteady Friction Slope Method= 2
Unsteady Bridges Friction Slope Method= 1
Parabolic Critical Depth
Global Vel Dist=  1 , 1 , 1
Global Log Level= 0
CheckData=True
Encroach Param= -1, 0, 0, 0
BEGIN DESCRIPTION:
Multiple Run
END DESCRIPTION:

--- Stream0144_DS.f01 (steady flow) ---

Flow Title=Multiple
Number of Profiles=7
Profile Names=10-year,25-year,50-year,1pct_min,100-year,1pct_plu,500-year
River Rch & RM= Stream0144_DS,Reach-1,4131
     574     959    1322     887    1770    3531    3142
River Rch & RM= Stream0144_DS,Reach-1,2176
    1198    2086    2954    2030    4051    8082    7556
Boundary for River Rch & Prof#=Stream0144_DS,Reach-1,1
Up Type=0
Dn Type=3
Dn Slope=0.005
Boundary for River Rch & Prof#=Stream0144_DS,Reach-1,2
Up Type=0
Dn Type=3
Dn Slope=0.005
Boundary for River Rch & Prof#=Stream0144_DS,Reach-1,3
Up Type=0
Dn Type=3
Dn Slope=0.005
Boundary for River Rch & Prof#=Stream0144_DS,Reach-1,4
Up Type=0
Dn Type=3
Dn Slope=0.005
Boundary for River Rch & Prof#=Stream0144_DS,Reach-1,5
Up Type=0
Dn Type=3
Dn Slope=0.005
Boundary for River Rch & Prof#=Stream0144_DS,Reach-1,6
Up Type=0
Dn Type=3
Dn Slope=0.005
Boundary for River Rch & Prof#=Stream0144_DS,Reach-1,7
Up Type=0
Dn Type=3
Dn Slope=0.005

--- Stream0144_DS.g01 (geometry) ---

Geom Title=Existing Conditions

River Reach=Stream0144_DS,Reach-1
Reach XY= 30
      2042275.48     13946585.83      2042271.71     13946276.36
      2042183.16     13946181.05      2042161.37     13946111.79
      2041985.78     13945934.68      2041964.22     13945865.32
      2041832.86     13945731.17      2041821.17     13945626.59
      2041624.76     13945250.08      2041627.44     13945130.86
      2041667.69     13945074.96      2041626.27     13945014.24
      2041625.00     13944975.00      2041667.77     13944925.01
      2041633.15     13944871.79      2041722.73     13944669.06
      2041728.76     13944526.56      2041783.16     13944418.95
      2041871.45     13944323.53      2041877.30     13944180.93
      2041924.91     13944109.60      2041778.74     13943823.44
      2041776.04     13943685.44      2041867.10     13943581.12
      2041878.66     13943483.19      2041918.98     13943469.21
      2041971.26     13943373.47      2041977.24     13943130.93
      2042071.40     13942973.51      2042075.00     13942925.00

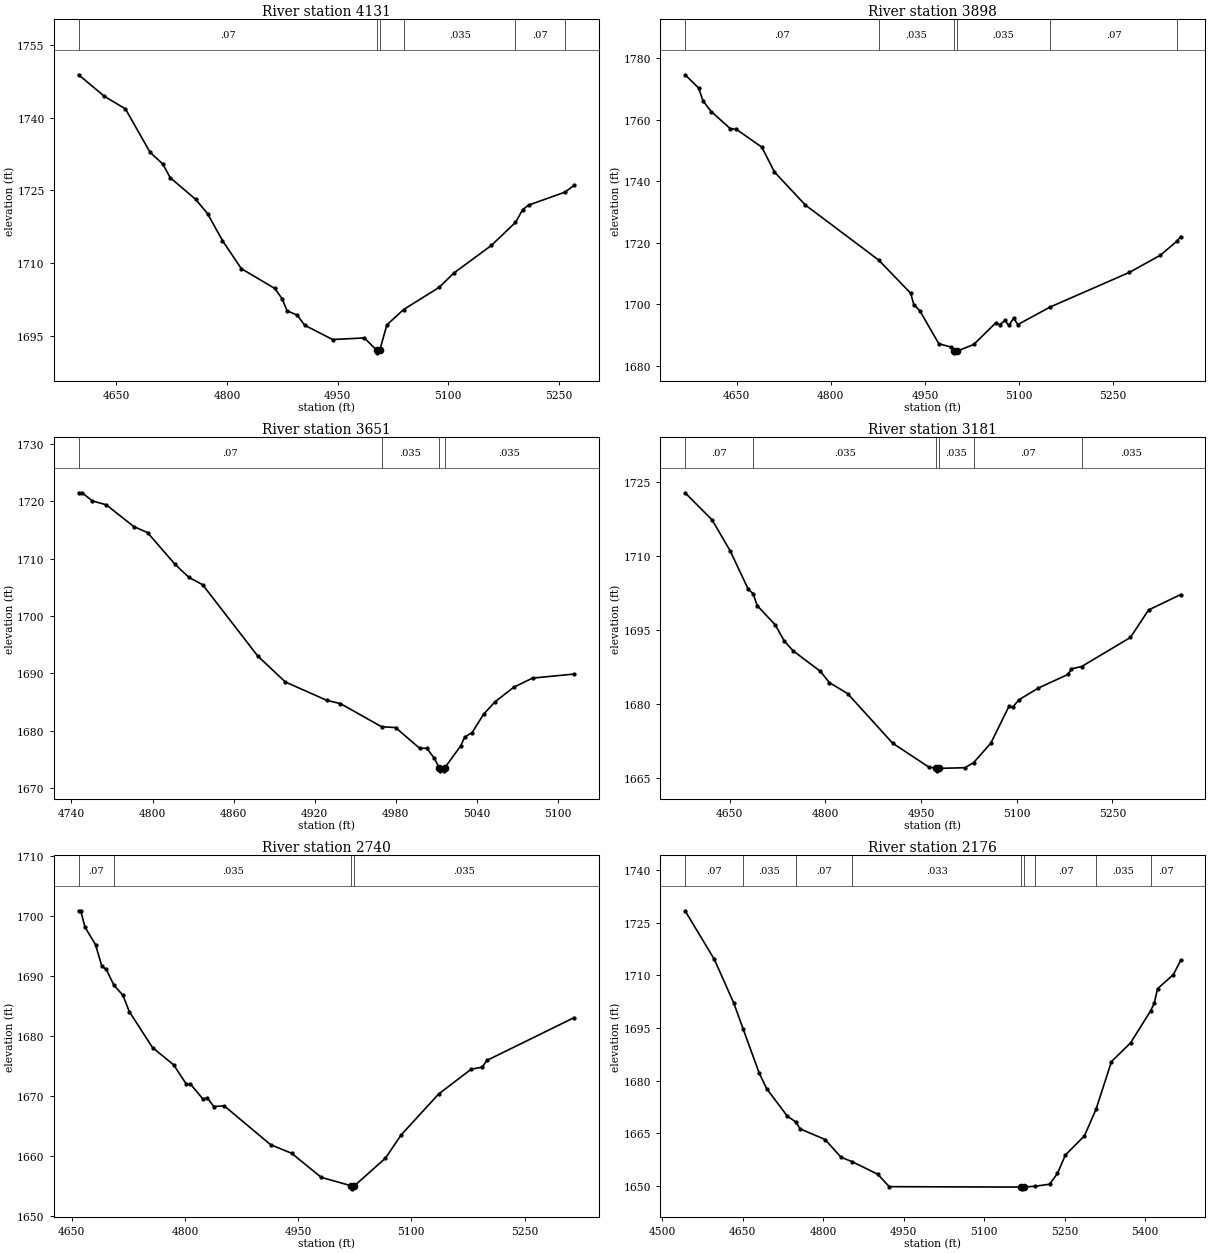
Type RM Length L Ch R = 1,4131,233,233,233
BEGIN DESCRIPTION:
Stream0144_DS 10.0
END DESCRIPTION:
XS GIS Cut Line= 2
      2042657.67     13946434.97      2041994.08     13946541.55
#Sta/Elev= 30
  4598.7 1748.88  4633.6 1744.43  4662.2 1741.83  4695.6 1732.86  4712.8 1730.45
  4722.9 1727.62  4757.5 1723.13  4773.6 1720.18  4793.8 1714.62  4819.4 1708.82
  4864.7 1704.74  4874.9 1702.56  4881.3 1700.13  4895.1 1699.22  4905.3 1697.13
  4943.2 1694.18  4986.3 1694.51  5003.1 1691.93  5003.4 1691.43  5007.1 1691.93
  5016.7 1697.20  5039.5 1700.38  5087.6 1704.95  5107.8 1707.94  5158.5 1713.62
  5191.2 1718.37  5201.0 1721.03  5209.1 1721.96  5258.3 1724.63  5270.8 1726.05
#Mann=6,-1,0
  4598.7    0.07       0  5003.1    0.05       0  5007.1    0.07       0
  5039.5   0.035       0  5191.2    0.07       0  5258.3   0.035       0
Bank Sta=5003.1,5007.1
Exp/Cntr=0.3,0.1

Type RM Length L Ch R = 1,3898,247,247,247
BEGIN DESCRIPTION:
Stream0144_DS 9.0
END DESCRIPTION:
XS GIS Cut Line= 3
      2042696.31     13946216.27      2042267.21     13946268.80
      2041995.06     13946500.47
#Sta/Elev= 30
  4567.7 1774.53  4589.2 1770.26  4596.3 1766.03  4609.3 1762.61  4639.5 1757.07
  4649.6 1756.79  4689.9 1751.06  4710.1 1742.98  4759.2 1732.28  4876.0 1714.42
  4927.1 1703.64  4932.2 1699.93  4941.8 1697.92  4972.0 1687.23  4992.2 1686.10
  4996.6 1684.77  4996.8 1684.27  5000.6 1684.77  5027.7 1686.99  5062.8 1694.01
  5069.4 1693.38  5077.1 1694.78  5083.6 1693.17  5091.3 1695.52  5097.9 1693.44
  5149.3 1699.13  5275.8 1710.39  5325.2 1715.97  5351.4 1720.50  5357.4 1722.00
#Mann=6,-1,0
  4567.7    0.07       0  4876.0   0.035       0  4996.6   0.035       0
  5000.6   0.035       0  5149.3    0.07       0  5351.4   0.035       0
Bank Sta=4996.6,5000.6
Exp/Cntr=0.3,0.1

Type RM Length L Ch R = 1,3651,470,470,470
BEGIN DESCRIPTION:
Stream0144_DS 8.0
END DESCRIPTION:
XS GIS Cut Line= 3
      2042375.00     13946025.00      2042125.00     13946075.00
      2042024.96     13946125.02
#Sta/Elev= 30
  4745.3 1721.52  4747.9 1721.52  4755.5 1720.09  4765.7 1719.43  4786.1 1715.62
  4796.3 1714.57  4816.7 1709.02  4826.9 1706.75  4837.1 1705.46  4877.9 1693.01
  4898.3 1688.48  4928.9 1685.28  4939.1 1684.70  4969.5 1680.67  4979.9 1680.52
  4997.7 1676.90  5003.0 1676.90  5008.6 1675.15  5012.2 1673.46  5012.5 1672.96
  5016.0 1672.96  5016.2 1673.46  5028.2 1677.34  5031.0 1678.85  5036.6 1679.65
  5045.0 1682.83  5053.4 1684.99  5067.3 1687.55  5081.3 1689.16  5112.1 1689.86
#Mann=4,-1,0
  4745.3    0.07       0  4969.5   0.035       0  5012.2   0.035       0
  5016.2   0.035       0
Bank Sta=5012.2,5016.2
Exp/Cntr=0.3,0.1

Type RM Length L Ch R = 1,3181,441,441,441
BEGIN DESCRIPTION:
Stream0144_DS 7.0
END DESCRIPTION:
XS GIS Cut Line= 3
      2042125.00     13945425.00      2041825.00     13945725.00
      2041679.26     13946045.89
#Sta/Elev= 30
  4580.1 1722.76  4622.5 1717.25  4650.8 1710.98  4679.1 1703.21  4686.7 1702.34
  4693.2 1699.89  4721.5 1695.99  4735.7 1692.71  4749.8 1690.71  4792.2 1686.59
  4806.4 1684.30  4834.7 1682.10  4905.4 1672.04  4961.9 1667.22  4974.1 1666.94
  4974.3 1666.44  4978.1 1666.94  5018.6 1667.07  5032.3 1668.09  5059.3 1672.05
  5087.9 1679.55  5093.4 1679.29  5103.2 1680.82  5134.0 1683.22  5180.1 1685.96
  5185.7 1687.10  5201.7 1687.57  5278.0 1693.45  5306.5 1699.02  5356.8 1702.14
#Mann=6,-1,0
  4580.1    0.07       0  4686.7   0.035       0  4974.1   0.035       0
  4978.1   0.035       0  5032.3    0.07       0  5201.7   0.035       0
Bank Sta=4974.1,4978.1
Exp/Cntr=0.3,0.1

Type RM Length L Ch R = 1,2740,564,564,564
BEGIN DESCRIPTION:
Stream0144_DS 6.0
END DESCRIPTION:
XS GIS Cut Line= 3
      2041975.02     13945174.99      2041675.00     13945325.00
      2041473.70     13945575.25
#Sta/Elev= 30
  4659.2 1700.90  4662.0 1700.90  4667.6 1698.17  4681.6 1695.25  4690.0 1691.64
  4695.6 1691.17  4706.1 1688.48  4717.9 1686.83  4726.3 1684.11  4757.1 1678.12
  4785.0 1675.25  4801.8 1672.05  4807.4 1672.04  4824.1 1669.52  4829.7 1669.78
  4838.1 1668.30  4852.1 1668.41  4913.6 1661.94  4941.5 1660.51  4980.7 1656.50
  5020.6 1655.09  5020.9 1654.59  5024.6 1655.09  5065.8 1659.71  5086.6 1663.58
  5136.2 1670.38  5179.4 1674.52  5193.8 1674.85  5200.2 1675.98  5315.8 1683.11
#Mann=4,-1,0
  4659.2    0.07       0  4706.1   0.035       0  5020.6   0.035       0
  5024.6   0.035       0
Bank Sta=5020.6,5024.6
Exp/Cntr=0.3,0.1

Type RM Length L Ch R = 1,2176,153,153,153
BEGIN DESCRIPTION:
Stream0144_DS 5.0
END DESCRIPTION:
XS GIS Cut Line= 3
      2042075.02     13945025.01      2041647.28     13944842.64
      2041274.99     13944575.00
#Sta/Elev= 30
  4542.4 1728.46  4596.8 1714.62  4633.2 1702.10  4650.9 1694.60  4680.5 1682.16
  4694.6 1677.66  4733.2 1669.82  4748.3 1668.27  4756.8 1666.24  4803.3 1663.20
  4833.1 1658.13  4854.0 1656.86  4901.2 1653.31  4922.9 1649.75  5169.2 1649.63
  5169.5 1649.13  5173.3 1649.63  5195.3 1649.89  5221.6 1650.44  5236.3 1653.51
  5251.1 1658.78  5286.7 1664.26  5308.3 1671.86  5337.0 1685.44  5372.6 1690.77
  5409.9 1699.89  5416.6 1702.04  5422.9 1706.22  5452.4 1710.27  5465.9 1714.29
#Mann=9,-1,0
  4542.4    0.07       0  4650.9   0.035       0  4748.3    0.07       0
  4854.0   0.033       0  5169.2   0.033       0  5173.3   0.033       0
  5195.3    0.07       0  5308.3   0.035       0  5409.9    0.07       0
Bank Sta=5169.2,5173.3
Exp/Cntr=0.3,0.1

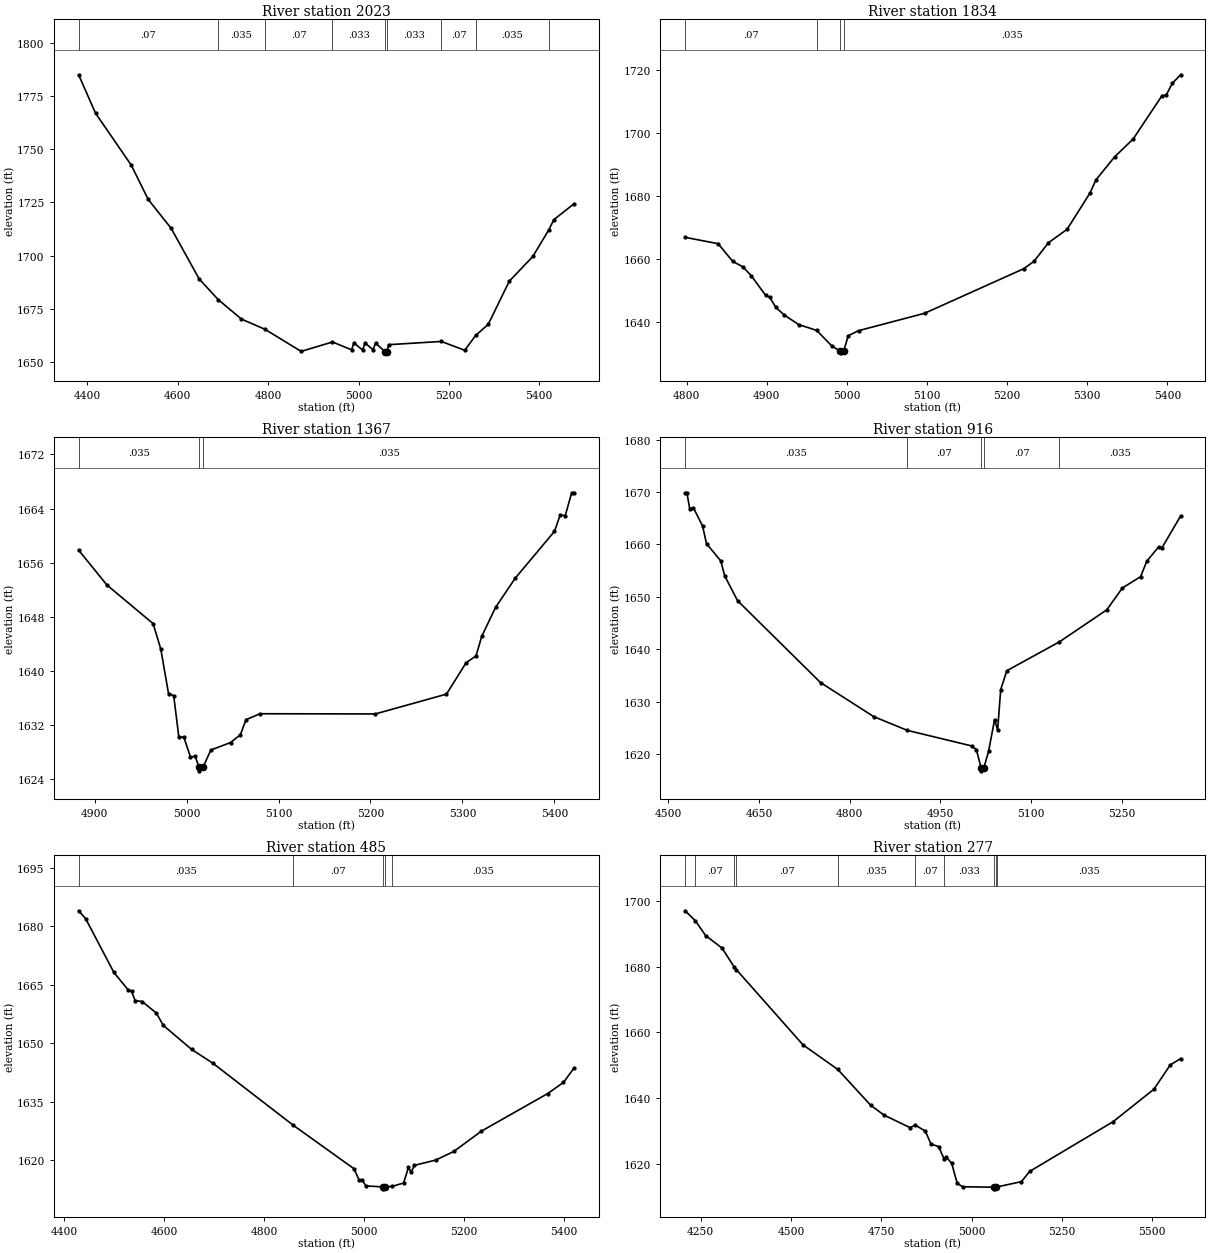
Type RM Length L Ch R = 1,2023,189,189,189
BEGIN DESCRIPTION:
Stream0144_DS 4.5
END DESCRIPTION:
XS GIS Cut Line= 3
      2042280.33     13944908.28      2041695.12     13944705.05
      2041258.48     13944512.02
#Sta/Elev= 30
  4380.5 1785.09  4417.9 1767.01  4497.2 1742.50  4534.3 1726.50  4585.3 1712.82
  4647.5 1688.96  4689.4 1679.31  4740.9 1670.12  4792.6 1665.35  4873.1 1654.92
  4942.4 1659.35  4984.6 1655.66  4989.9 1658.87  5009.0 1655.57  5014.5 1658.86
  5032.3 1655.70  5037.8 1658.80  5059.0 1654.74  5059.3 1654.24  5063.2 1654.74
  5066.6 1658.08  5183.3 1659.60  5235.1 1655.45  5259.4 1662.44  5287.2 1667.65
  5333.8 1687.96  5385.9 1699.58  5421.5 1712.22  5432.5 1716.92  5477.4 1724.45
#Mann=9,-1,0
  4380.5    0.07       0  4689.4   0.035       0  4792.6    0.07       0
  4942.4   0.033       0  5059.0   0.033       0  5063.2   0.033       0
  5183.3    0.07       0  5259.4   0.035       0  5421.5    0.07       0
Bank Sta=5059,5063.2
Exp/Cntr=0.3,0.1

Type RM Length L Ch R = 1,1834,467,467,467
BEGIN DESCRIPTION:
Stream0144_DS 4.0
END DESCRIPTION:
XS GIS Cut Line= 3
      2041925.00     13944575.00      2041725.00     13944525.00
      2041324.97     13944424.99
#Sta/Elev= 30
  4798.0 1666.92  4839.2 1664.91  4857.3 1659.33  4870.2 1657.53  4880.5 1654.77
  4898.5 1648.50  4903.7 1647.85  4911.4 1644.64  4921.7 1642.27  4939.7 1639.23
  4962.3 1637.35  4981.0 1632.46  4991.7 1630.74  4992.0 1630.24  4995.9 1630.74
  5001.6 1635.68  5014.5 1637.28  5096.9 1642.80  5220.6 1656.95  5233.5 1659.30
  5251.5 1665.21  5274.7 1669.45  5303.1 1680.88  5310.8 1685.17  5334.0 1692.46
  5357.2 1698.14  5393.3 1711.95  5398.4 1712.09  5406.2 1715.87  5416.5 1718.55
#Mann=4,-1,0
  4798.0    0.07       0  4962.3   0.035       0  4991.7   0.035       0
  4995.9   0.035       0
Bank Sta=4991.7,4995.9
Exp/Cntr=0.3,0.1

Type RM Length L Ch R = 1,1367,451,451,451
BEGIN DESCRIPTION:
Stream0144_DS 3.0
END DESCRIPTION:
XS GIS Cut Line= 3
      2042024.97     13944174.99      2041925.00     13944125.00
      2041524.97     13944275.01
#Sta/Elev= 30
  4882.6 1657.86  4913.3 1652.72  4963.6 1647.00  4972.0 1643.22  4980.4 1636.64
  4986.0 1636.36  4991.6 1630.23  4997.0 1630.23  5004.2 1627.31  5009.5 1627.37
  5013.6 1625.74  5013.9 1625.24  5017.8 1625.74  5026.4 1628.32  5047.8 1629.42
  5058.5 1630.57  5064.7 1632.80  5079.8 1633.68  5205.3 1633.65  5282.7 1636.58
  5304.1 1641.23  5314.8 1642.21  5321.0 1645.10  5336.1 1649.40  5357.5 1653.72
  5400.2 1660.64  5406.4 1663.07  5411.8 1662.93  5418.9 1666.34  5421.6 1666.34
#Mann=3,-1,0
  4882.6   0.035       0  5013.6   0.035       0  5017.8   0.035       0
Bank Sta=5013.6,5017.8
Exp/Cntr=0.3,0.1

Type RM Length L Ch R = 1,916,431,431,431
BEGIN DESCRIPTION:
Stream0144_DS 2.0
END DESCRIPTION:
XS GIS Cut Line= 3
      2042175.01     13943975.01      2041775.00     13943725.00
      2041429.25     13943686.47
#Sta/Elev= 30
  4527.8 1669.87  4530.8 1669.87  4535.5 1666.78  4541.4 1667.04  4556.7 1663.53
  4563.2 1660.16  4586.8 1656.86  4593.3 1654.02  4614.5 1649.28  4751.9 1633.63
  4839.7 1627.15  4895.4 1624.51  5002.0 1621.54  5009.6 1620.83  5017.5 1617.29
  5017.8 1616.79  5021.8 1617.29  5029.7 1620.51  5039.7 1626.58  5044.7 1624.56
  5049.8 1632.30  5059.9 1635.90  5147.0 1641.42  5225.2 1647.52  5251.1 1651.70
  5281.2 1653.86  5291.3 1656.78  5311.0 1659.55  5316.0 1659.27  5347.4 1665.45
#Mann=5,-1,0
  4527.8   0.035       0  4895.4    0.07       0  5017.5    0.05       0
  5021.8    0.07       0  5147.0   0.035       0
Bank Sta=5017.5,5021.8
Exp/Cntr=0.3,0.1

Type RM Length L Ch R = 1,485,208,208,208
BEGIN DESCRIPTION:
Stream0144_DS 1.0
END DESCRIPTION:
XS GIS Cut Line= 3
      2042375.00     13943775.00      2041975.00     13943375.00
      2041574.98     13943525.01
#Sta/Elev= 30
  4428.4 1683.93  4442.5 1681.90  4499.1 1668.12  4527.4 1663.69  4534.5 1663.28
  4541.5 1660.94  4555.7 1660.68  4584.0 1657.74  4598.1 1654.56  4654.7 1648.42
  4697.1 1644.90  4857.0 1629.12  4979.9 1617.86  4990.5 1614.95  4996.7 1614.95
  5003.9 1613.44  5037.3 1613.19  5037.6 1612.69  5041.6 1613.19  5057.1 1613.33
  5079.5 1614.19  5089.3 1618.17  5094.6 1616.91  5100.9 1618.70  5143.6 1620.05
  5180.1 1622.26  5235.3 1627.46  5367.9 1637.07  5399.9 1639.96  5421.3 1643.68
#Mann=5,-1,0
  4428.4   0.035       0  4857.0    0.07       0  5037.3    0.05       0
  5041.6    0.07       0  5057.1   0.035       0
Bank Sta=5037.3,5041.6
Exp/Cntr=0.3,0.1

Type RM Length L Ch R = 1,277,0,0,0
BEGIN DESCRIPTION:
Stream0144_DS 0.0
END DESCRIPTION:
XS GIS Cut Line= 3
      2042642.33     13943597.71      2041974.56     13943169.82
      2041453.65     13943422.36
#Sta/Elev= 30
  4206.9 1697.07  4235.5 1694.01  4263.7 1689.52  4309.3 1685.69  4342.6 1679.98
  4348.8 1679.12  4533.3 1656.20  4629.7 1648.69  4721.0 1637.74  4757.4 1634.80
  4830.1 1630.92  4843.7 1631.76  4872.3 1629.86  4887.5 1625.96  4908.7 1625.17
  4924.3 1621.33  4929.8 1621.98  4945.0 1620.10  4960.2 1613.96  4975.5 1612.92
  5062.8 1612.79  5063.1 1612.29  5067.1 1612.79  5069.4 1612.84  5138.2 1614.49
  5160.8 1617.60  5392.1 1632.78  5504.9 1642.66  5550.1 1650.06  5578.9 1652.00
#Mann=10,-1,0
  4206.9   0.035       0  4235.5    0.07       0  4342.6   0.035       0
  4348.8    0.07       0  4629.7   0.035       0  4843.7    0.07       0
  4924.3   0.033       0  5062.8   0.033       0  5067.1   0.033       0
  5069.4   0.035       0
Bank Sta=5062.8,5067.1
Exp/Cntr=0.3,0.1

Chan Stop Cuts=-1