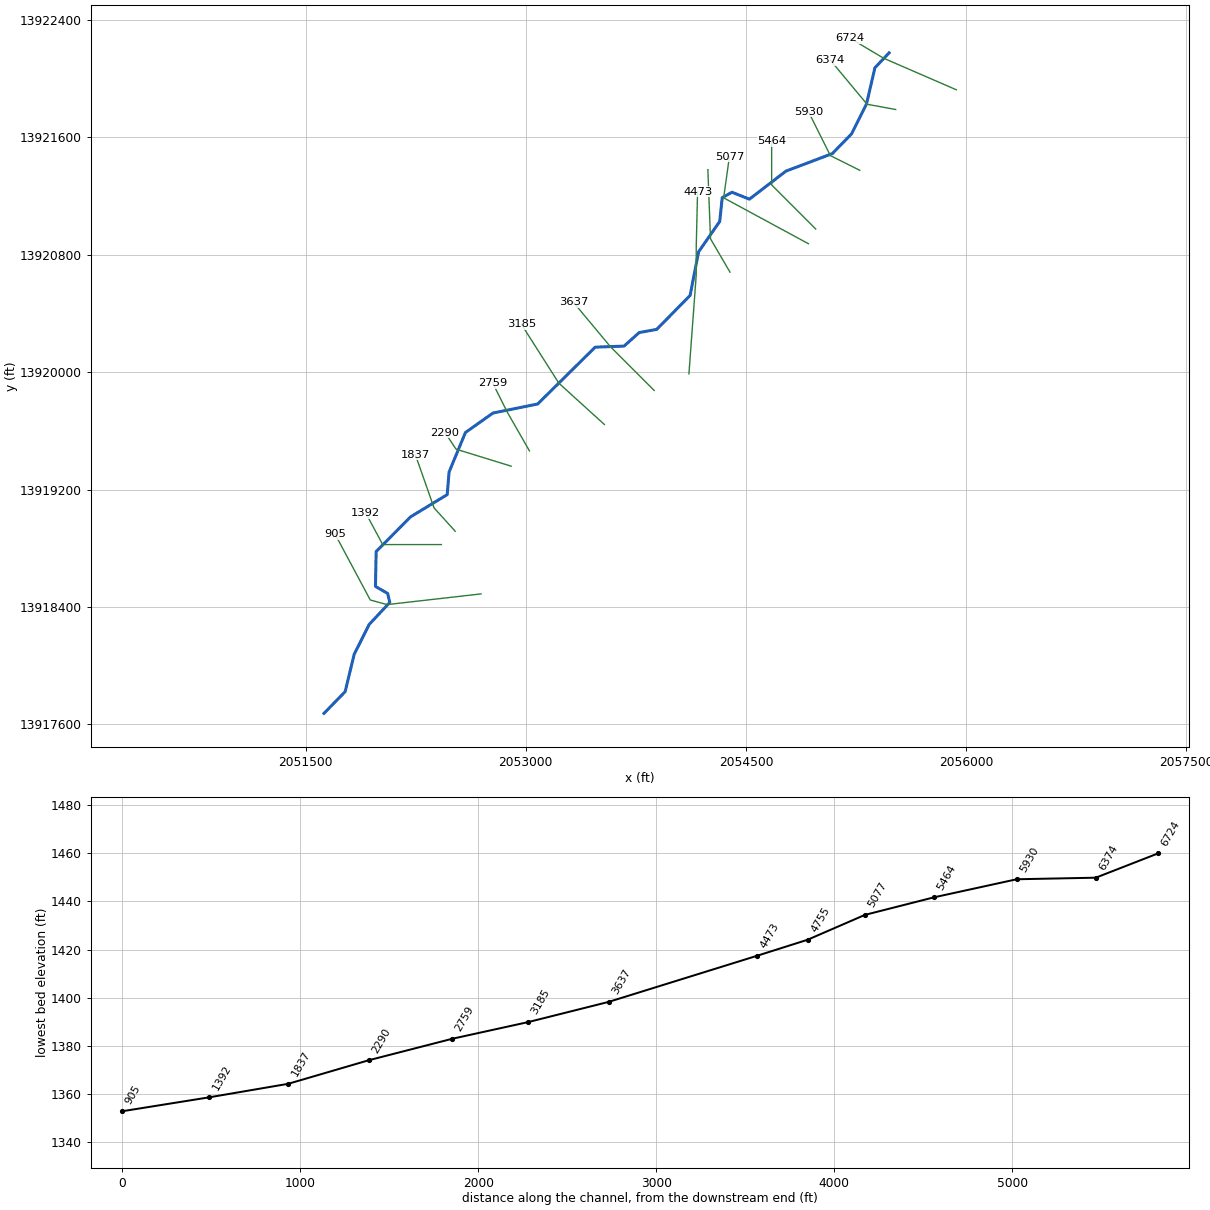
--- Stream0145_DS.prj (project) ---

Proj Title=Stream0145_DS Base Level Engineering
Current Plan=p01
Default Exp/Contr=0.3,0.1
English Units
Geom File=g01
Flow File=f01
Plan File=p01
BEGIN DESCRIPTION:
Stream0145_DS
END DESCRIPTION:

--- Stream0145_DS.p01 (plan) ---

Plan Title=Multiple Run
Short Identifier=Multiple
Geom File=g01
Flow File=f01
Subcritical Flow
K Sum by GR= 0
Std Step Tol= 0.01
Critical Tol= 0.01
Num of Std Step Trials= 20
Max Error Tol= 0.3
Flow Tol Ratio= 0.001
Split Flow NTrial= 30
Split Flow Tol= 0.02
Split Flow Ratio= 0.02
Log Output Level= 0
Friction Slope Method= 1
Unsteady Friction Slope Method= 2
Unsteady Bridges Friction Slope Method= 1
Parabolic Critical Depth
Global Vel Dist=  1 , 1 , 1
Global Log Level= 0
CheckData=True
Encroach Param= -1, 0, 0, 0
BEGIN DESCRIPTION:
Multiple Run
END DESCRIPTION:

--- Stream0145_DS.f01 (steady flow) ---

Flow Title=Multiple
Number of Profiles=7
Profile Names=10-year,25-year,50-year,1pct_min,100-year,1pct_plu,500-year
River Rch & RM= Stream0145_DS,Reach-1,6724
     575     950    1298     864    1725    3441    3010
River Rch & RM= Stream0145_DS,Reach-1,3637
     972    1661    2323    1579    3151    6286    5740
River Rch & RM= Stream0145_DS,Reach-1,3185
    1208    2084    2933    2004    3998    7977    7361
Boundary for River Rch & Prof#=Stream0145_DS,Reach-1,1
Up Type=0
Dn Type=3
Dn Slope=0.005
Boundary for River Rch & Prof#=Stream0145_DS,Reach-1,2
Up Type=0
Dn Type=3
Dn Slope=0.005
Boundary for River Rch & Prof#=Stream0145_DS,Reach-1,3
Up Type=0
Dn Type=3
Dn Slope=0.005
Boundary for River Rch & Prof#=Stream0145_DS,Reach-1,4
Up Type=0
Dn Type=3
Dn Slope=0.005
Boundary for River Rch & Prof#=Stream0145_DS,Reach-1,5
Up Type=0
Dn Type=3
Dn Slope=0.005
Boundary for River Rch & Prof#=Stream0145_DS,Reach-1,6
Up Type=0
Dn Type=3
Dn Slope=0.005
Boundary for River Rch & Prof#=Stream0145_DS,Reach-1,7
Up Type=0
Dn Type=3
Dn Slope=0.005

--- Stream0145_DS.g01 (geometry) ---

Geom Title=Existing Conditions

River Reach=Stream0145_DS,Reach-1
Reach XY= 30
      2055475.00     13922175.00      2055378.56     13922073.52
      2055321.17     13921826.58      2055219.17     13921622.70
      2055088.22     13921488.62      2054772.58     13921369.46
      2054523.36     13921178.14      2054404.72     13921225.38
      2054338.23     13921188.81      2054321.24     13921026.56
      2054177.19     13920819.55      2054119.48     13920522.57
      2053892.05     13920291.13      2053772.57     13920269.48
      2053669.55     13920177.18      2053472.41     13920169.86
      2053081.17     13919782.86      2052776.56     13919721.24
      2052588.61     13919588.24      2052477.27     13919319.06
      2052464.53     13919165.18      2052215.32     13919014.24
      2051980.46     13918777.45      2051975.90     13918539.71
      2052058.86     13918492.01      2052073.32     13918430.67
      2051933.14     13918281.06      2051830.71     13918077.35
      2051769.17     13917822.70      2051625.00     13917675.00

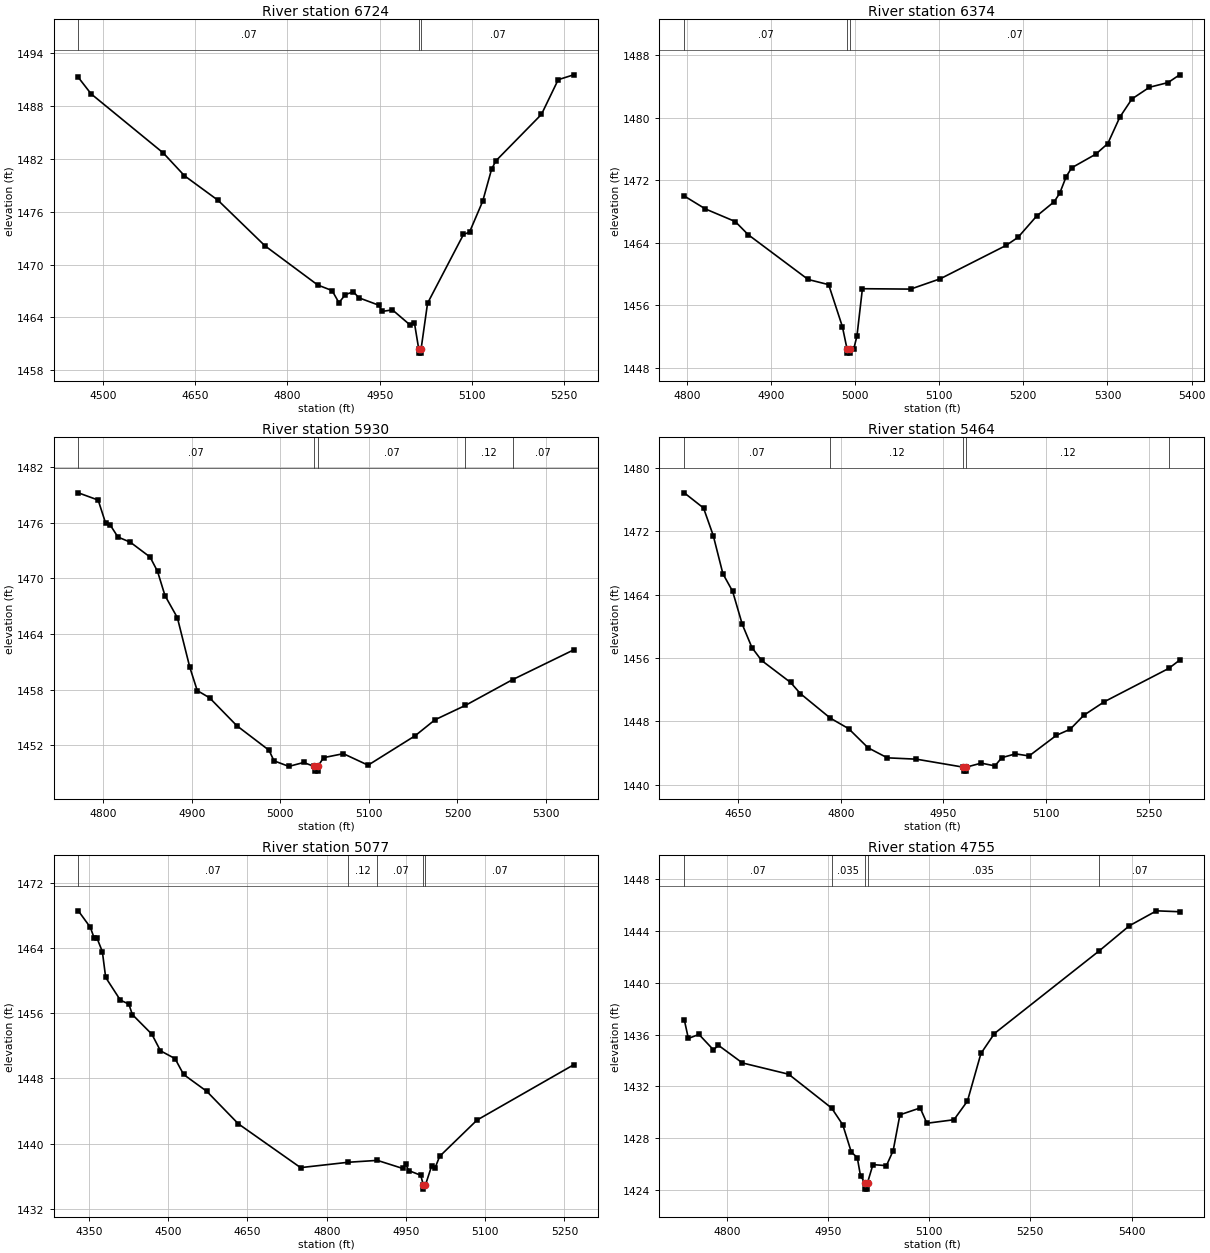
Type RM Length L Ch R = 1,6724,350,350,350
BEGIN DESCRIPTION:
Stream0145_DS 15.0
END DESCRIPTION:
XS GIS Cut Line= 3
      2055933.22     13921923.51      2055438.15     13922138.41
      2055210.34     13922273.98
#Sta/Elev= 30
  4460.3 1491.21  4481.1 1489.34  4598.4 1482.64  4632.8 1480.06  4687.3 1477.28
  4763.6 1472.12  4849.3 1467.68  4872.6 1467.05  4883.7 1465.68  4894.4 1466.60
  4907.2 1466.91  4916.2 1466.23  4948.6 1465.39  4954.1 1464.69  4970.7 1464.86
  4999.0 1463.17  5006.3 1463.43  5013.3 1460.46  5013.6 1459.96  5017.1 1459.96
  5017.3 1460.46  5027.7 1465.61  5086.1 1473.41  5095.9 1473.67  5117.3 1477.17
  5131.7 1480.79  5138.7 1481.75  5212.8 1487.02  5240.0 1490.95  5265.1 1491.50
#Mann=3,-1,0
  4460.3    0.07       0  5013.3    0.05       0  5017.3    0.07       0
Bank Sta=5013.3,5017.3
Exp/Cntr=0.3,0.1

Type RM Length L Ch R = 1,6374,444,444,444
BEGIN DESCRIPTION:
Stream0145_DS 14.0
END DESCRIPTION:
XS GIS Cut Line= 3
      2055519.78     13921789.01      2055325.00     13921825.00
      2055074.99     13922125.01
#Sta/Elev= 30
  4797.1 1469.97  4822.3 1468.31  4857.7 1466.70  4873.1 1465.02  4944.3 1459.29
  4968.7 1458.63  4985.0 1453.26  4990.6 1450.37  4990.9 1449.87  4994.4 1449.87
  4994.6 1450.37  4998.4 1450.37  5002.3 1452.05  5008.8 1458.11  5066.1 1458.06
  5101.3 1459.38  5179.4 1463.64  5193.7 1464.68  5215.8 1467.40  5236.6 1469.23
  5243.2 1470.31  5251.0 1472.46  5257.5 1473.58  5286.1 1475.32  5300.4 1476.68
  5314.7 1480.06  5329.1 1482.39  5349.9 1483.88  5372.0 1484.48  5385.7 1485.47
#Mann=3,-1,0
  4797.1    0.07       0  4990.6    0.05       0  4994.6    0.07       0
Bank Sta=4990.6,4994.6
Exp/Cntr=0.3,0.1

Type RM Length L Ch R = 1,5930,466,466,466
BEGIN DESCRIPTION:
Stream0145_DS 13.0
END DESCRIPTION:
XS GIS Cut Line= 3
      2055274.99     13921375.00      2055075.00     13921475.00
      2054925.00     13921774.99
#Sta/Elev= 30
  4772.1 1479.20  4794.5 1478.42  4802.8 1475.97  4808.4 1475.69  4816.8 1474.44
  4830.8 1473.88  4853.1 1472.28  4861.5 1470.74  4869.9 1468.13  4883.9 1465.75
  4897.9 1460.41  4906.3 1457.90  4920.2 1457.12  4951.0 1454.11  4987.3 1451.47
  4992.9 1450.33  5009.7 1449.73  5026.4 1450.15  5038.4 1449.72  5038.7 1449.22
  5042.2 1449.22  5042.4 1449.72  5048.8 1450.67  5071.2 1451.10  5099.1 1449.86
  5152.2 1453.03  5174.6 1454.75  5208.9 1456.30  5262.1 1459.07  5331.1 1462.28
#Mann=5,-1,0
  4772.1    0.07       0  5038.4    0.05       0  5042.4    0.07       0
  5208.9    0.12       0  5262.1    0.07       0
Bank Sta=5038.4,5042.4
Exp/Cntr=0.3,0.1

Type RM Length L Ch R = 1,5464,387,387,387
BEGIN DESCRIPTION:
Stream0145_DS 12.0
END DESCRIPTION:
XS GIS Cut Line= 3
      2054974.97     13920975.03      2054675.00     13921275.00
      2054675.00     13921574.98
#Sta/Elev= 30
  4571.0 1476.85  4599.2 1474.93  4613.4 1471.45  4627.5 1466.63  4641.7 1464.41
  4655.8 1460.24  4670.0 1457.29  4684.1 1455.67  4726.5 1452.89  4740.7 1451.49
  4784.5 1448.39  4811.4 1447.05  4839.7 1444.64  4867.9 1443.37  4910.4 1443.20
  4979.1 1442.19  4979.3 1441.69  4982.8 1441.69  4983.1 1442.19  5005.2 1442.70
  5025.2 1442.35  5035.2 1443.39  5055.2 1443.87  5075.2 1443.61  5115.2 1446.22
  5135.2 1446.98  5155.2 1448.75  5185.2 1450.46  5279.4 1454.67  5295.2 1455.71
#Mann=5,-1,0
  4571.0    0.07       0  4784.5    0.12       0  4979.1    0.05       0
  4983.1    0.12       0  5279.4    0.07       0
Bank Sta=4979.1,4983.1
Exp/Cntr=0.3,0.1

Type RM Length L Ch R = 1,5077,322,322,322
BEGIN DESCRIPTION:
Stream0145_DS 11.0
END DESCRIPTION:
XS GIS Cut Line= 3
      2054924.99     13920875.00      2054347.93     13921187.44
      2054386.99     13921466.10
#Sta/Elev= 30
  4329.8 1468.59  4352.5 1466.57  4359.8 1465.25  4365.4 1465.20  4375.3 1463.58
  4381.6 1460.41  4409.4 1457.62  4425.4 1457.14  4432.1 1455.85  4469.1 1453.43
  4485.3 1451.40  4512.9 1450.44  4529.1 1448.49  4572.8 1446.43  4632.7 1442.43
  4750.5 1437.05  4840.8 1437.71  4895.9 1437.94  4943.8 1436.95  4949.5 1437.47
  4955.2 1436.69  4978.0 1436.11  4982.8 1434.91  4983.1 1434.41  4986.8 1434.91
  4998.7 1437.28  5004.9 1436.99  5013.8 1438.44  5084.5 1442.89  5267.4 1449.68
#Mann=5,-1,0
  4329.8    0.07       0  4840.8    0.12       0  4895.9    0.07       0
  4982.8    0.05       0  4986.8    0.07       0
Bank Sta=4982.8,4986.8
Exp/Cntr=0.3,0.1

Type RM Length L Ch R = 1,4755,282,282,282
BEGIN DESCRIPTION:
Stream0145_DS 10.5
END DESCRIPTION:
XS GIS Cut Line= 3
      2054391.02     13920681.27      2054258.32     13920908.34
      2054240.50     13921379.30
#Sta/Elev= 30
  4737.0 1437.15  4743.1 1435.70  4758.8 1436.01  4780.3 1434.82  4787.7 1435.17
  4823.2 1433.81  4891.8 1432.94  4955.5 1430.33  4972.0 1429.04  4984.6 1426.94
  4993.5 1426.51  4998.3 1425.10  5004.7 1424.58  5004.9 1424.08  5008.4 1424.08
  5008.7 1424.58  5016.7 1425.97  5036.7 1425.89  5046.7 1427.05  5056.7 1429.81
  5086.7 1430.34  5096.7 1429.16  5136.8 1429.43  5156.8 1430.87  5176.8 1434.54
  5196.8 1436.08  5352.3 1442.46  5396.9 1444.39  5437.0 1445.54  5471.3 1445.47
#Mann=5,-1,0
  4737.0    0.07       0  4955.5   0.035       0  5004.7   0.035       0
  5008.7   0.035       0  5352.3    0.07       0
Bank Sta=5004.7,5008.7
Exp/Cntr=0.3,0.1

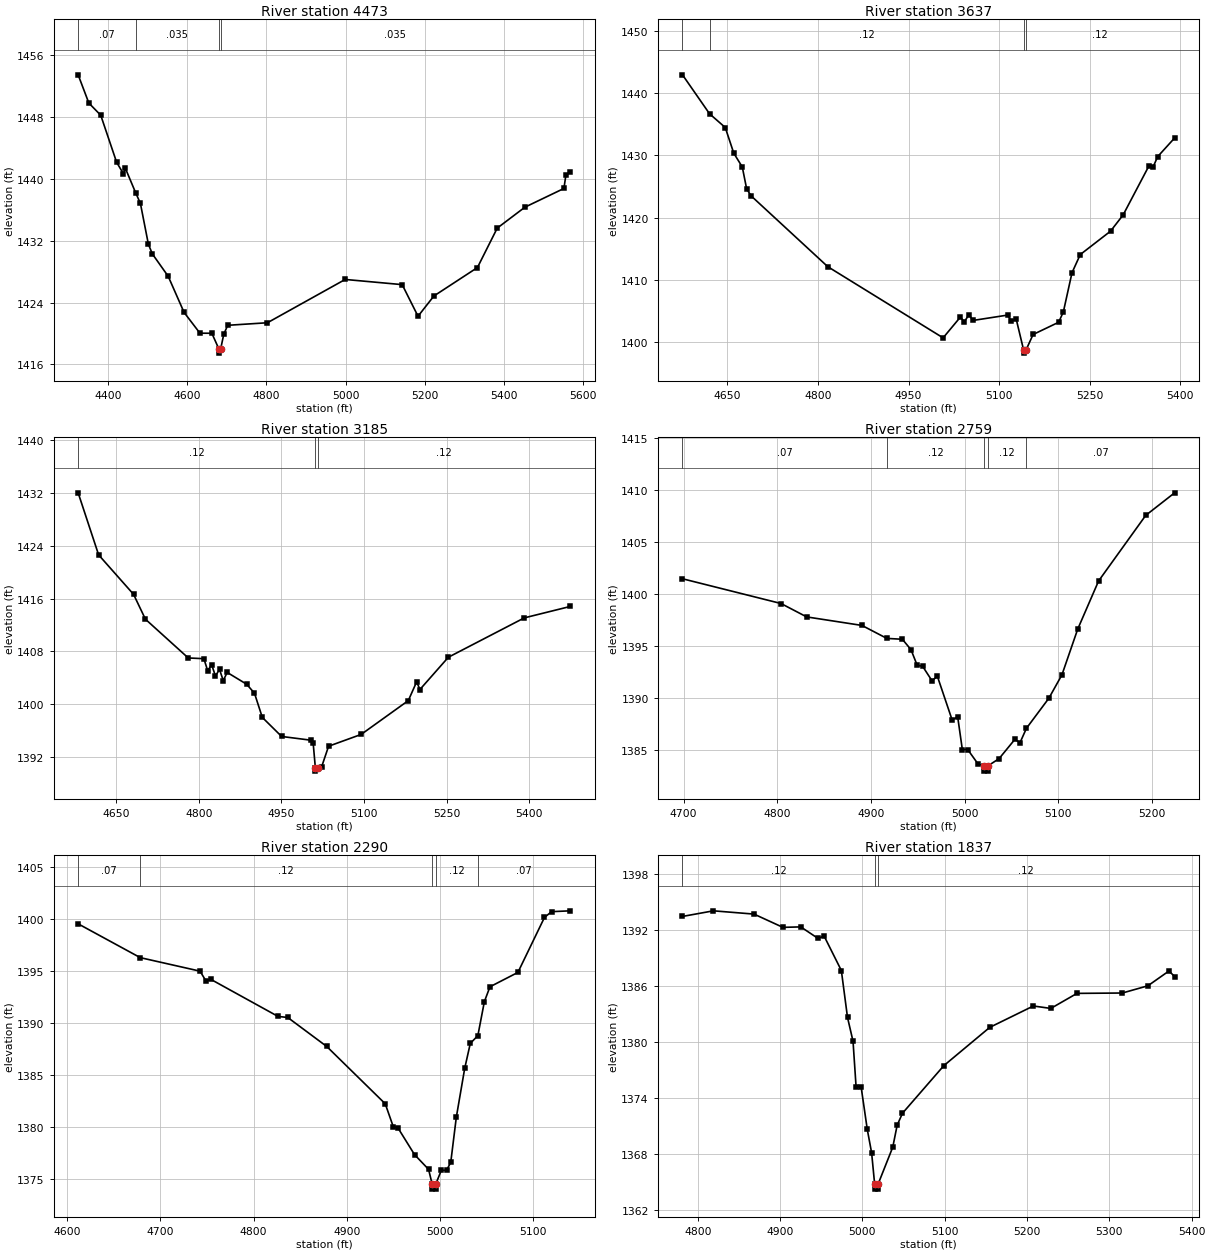
Type RM Length L Ch R = 1,4473,836,836,836
BEGIN DESCRIPTION:
Stream0145_DS 10.0
END DESCRIPTION:
XS GIS Cut Line= 4
      2054111.41     13919988.09      2054161.21     13920661.86
      2054161.17     13920851.23      2054170.30     13921229.45
#Sta/Elev= 30
  4324.4 1453.47  4351.4 1449.82  4381.5 1448.24  4421.6 1442.16  4438.8 1440.67
  4443.8 1441.37  4469.7 1438.21  4481.7 1436.84  4501.8 1431.57  4511.8 1430.31
  4551.9 1427.41  4592.0 1422.74  4632.1 1420.05  4662.2 1420.04  4680.3 1417.97
  4680.5 1417.47  4684.3 1417.97  4692.3 1419.91  4702.3 1421.07  4802.6 1421.40
  4999.1 1427.00  5143.1 1426.33  5183.1 1422.24  5223.2 1424.86  5333.2 1428.54
  5383.2 1433.64  5453.2 1436.35  5551.7 1438.77  5556.7 1440.51  5567.7 1440.88
#Mann=4,-1,0
  4324.4    0.07       0  4469.7   0.035       0  4680.3   0.035       0
  4684.3   0.035       0
Bank Sta=4680.3,4684.3
Exp/Cntr=0.3,0.1

Type RM Length L Ch R = 1,3637,452,452,452
BEGIN DESCRIPTION:
Stream0145_DS 8.0
END DESCRIPTION:
XS GIS Cut Line= 3
      2053875.03     13919874.97      2053575.00     13920175.00
      2053325.01     13920474.99
#Sta/Elev= 30
  4575.7 1442.90  4620.5 1436.65  4646.5 1434.45  4660.6 1430.33  4674.7 1428.12
  4681.8 1424.66  4688.9 1423.52  4816.2 1412.13  5007.2 1400.71  5035.8 1404.04
  5042.3 1403.28  5050.1 1404.44  5056.6 1403.50  5113.9 1404.36  5120.4 1403.38
  5128.2 1403.73  5140.5 1398.76  5140.8 1398.26  5144.5 1398.76  5156.2 1401.25
  5198.5 1403.21  5206.3 1404.87  5220.6 1411.15  5234.3 1414.07  5284.4 1417.82
  5305.3 1420.43  5348.2 1428.33  5354.7 1428.08  5362.5 1429.78  5390.5 1432.77
#Mann=4,-1,0
  4575.7   0.035       0  4620.5    0.12       0  5140.5    0.05       0
  5144.5    0.12       0
Bank Sta=5140.5,5144.5
Exp/Cntr=0.3,0.1

Type RM Length L Ch R = 1,3185,426,426,426
BEGIN DESCRIPTION:
Stream0145_DS 7.0
END DESCRIPTION:
XS GIS Cut Line= 3
      2053535.46     13919643.14      2053225.00     13919925.00
      2052970.32     13920325.46
#Sta/Elev= 30
  4580.7 1432.02  4617.9 1422.62  4681.4 1416.64  4702.9 1412.88  4780.7 1407.01
  4809.1 1406.90  4815.9 1405.10  4823.3 1405.96  4830.1 1404.28  4837.5 1405.27
  4844.3 1403.58  4851.4 1404.82  4886.8 1403.03  4901.0 1401.67  4915.2 1398.01
  4950.3 1395.12  5003.0 1394.56  5007.6 1394.12  5011.6 1390.37  5011.8 1389.87
  5015.6 1390.37  5022.9 1390.50  5035.6 1393.64  5094.8 1395.43  5180.4 1400.55
  5195.6 1403.40  5201.5 1402.23  5253.2 1407.12  5391.1 1413.08  5474.6 1414.81
#Mann=3,-1,0
  4580.7    0.12       0  5011.6    0.05       0  5015.6    0.12       0
Bank Sta=5011.6,5015.6
Exp/Cntr=0.3,0.1

Type RM Length L Ch R = 1,2759,469,469,469
BEGIN DESCRIPTION:
Stream0145_DS 6.0
END DESCRIPTION:
XS GIS Cut Line= 3
      2053025.01     13919463.49      2052875.00     13919725.00
      2052775.00     13919925.01
#Sta/Elev= 30
  4698.9 1401.46  4804.0 1399.08  4831.4 1397.79  4890.4 1396.97  4917.0 1395.72
  4933.5 1395.64  4942.7 1394.64  4949.3 1393.14  4955.1 1393.04  4965.1 1391.65
  4970.9 1392.07  4986.7 1387.85  4992.5 1388.20  4997.5 1385.03  5003.2 1385.03
  5014.4 1383.62  5020.7 1383.45  5021.0 1382.95  5024.5 1382.95  5024.7 1383.45
  5036.7 1384.15  5053.5 1386.00  5059.1 1385.70  5065.9 1387.07  5089.8 1389.96
  5103.8 1392.22  5120.6 1396.61  5142.9 1401.25  5193.2 1407.56  5224.0 1409.73
#Mann=5,-1,0
  4698.9    0.07       0  4917.0    0.12       0  5020.7    0.05       0
  5024.7    0.12       0  5065.9    0.07       0
Bank Sta=5020.7,5024.7
Exp/Cntr=0.3,0.1

Type RM Length L Ch R = 1,2290,453,453,453
BEGIN DESCRIPTION:
Stream0145_DS 5.0
END DESCRIPTION:
XS GIS Cut Line= 3
      2052900.05     13919359.31      2052525.00     13919475.00
      2052449.76     13919588.07
#Sta/Elev= 30
  4611.7 1399.53  4678.4 1396.28  4742.6 1394.98  4748.8 1394.05  4754.0 1394.20
  4826.3 1390.63  4836.7 1390.53  4878.6 1387.74  4941.4 1382.23  4950.0 1380.03
  4955.2 1379.89  4972.8 1377.35  4987.9 1375.93  4991.7 1374.53  4992.0 1374.03
  4995.5 1374.03  4995.7 1374.53  5001.6 1375.84  5007.2 1375.84  5011.7 1376.60
  5017.7 1380.95  5026.7 1385.64  5032.7 1388.04  5040.8 1388.78  5047.8 1392.05
  5053.8 1393.48  5083.8 1394.86  5112.3 1400.14  5119.9 1400.70  5140.0 1400.78
#Mann=5,-1,0
  4611.7    0.07       0  4678.4    0.12       0  4991.7    0.05       0
  4995.7    0.12       0  5040.8    0.07       0
Bank Sta=4991.7,4995.7
Exp/Cntr=0.3,0.1

Type RM Length L Ch R = 1,1837,445,445,445
BEGIN DESCRIPTION:
Stream0145_DS 4.0
END DESCRIPTION:
XS GIS Cut Line= 3
      2052518.78     13918916.07      2052375.00     13919075.00
      2052247.93     13919436.92
#Sta/Elev= 30
  4781.4 1393.43  4819.0 1394.03  4868.3 1393.68  4903.4 1392.26  4925.1 1392.31
  4946.0 1391.08  4953.5 1391.32  4974.4 1387.64  4981.9 1382.61  4988.6 1380.06
  4992.3 1375.19  4998.4 1375.19  5005.9 1370.63  5011.2 1368.11  5014.9 1364.73
  5015.2 1364.23  5018.7 1364.23  5018.9 1364.73  5036.9 1368.73  5042.2 1371.07
  5048.7 1372.36  5098.9 1377.45  5154.7 1381.55  5207.7 1383.84  5228.9 1383.58
  5260.7 1385.19  5315.8 1385.23  5346.8 1386.00  5372.5 1387.59  5379.3 1386.99
#Mann=3,-1,0
  4781.4    0.12       0  5014.9    0.05       0  5018.9    0.12       0
Bank Sta=5014.9,5018.9
Exp/Cntr=0.3,0.1

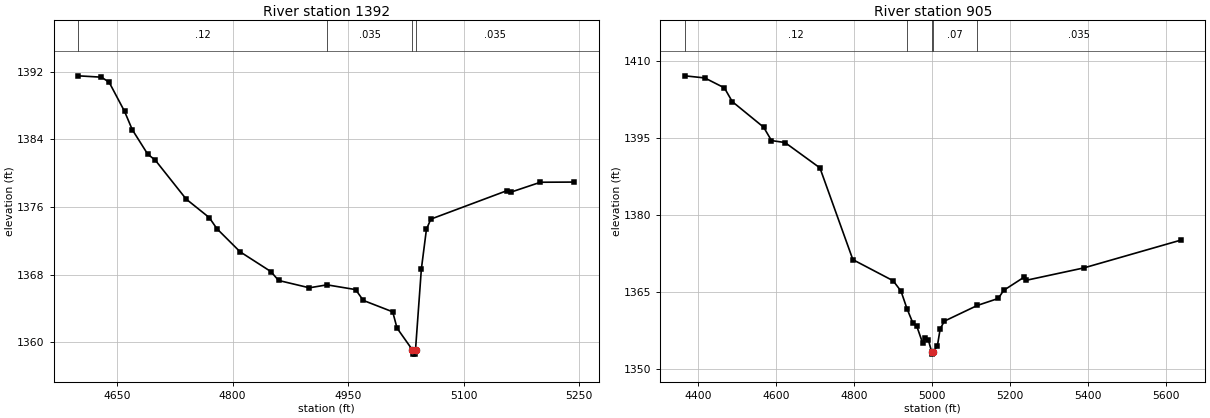
Type RM Length L Ch R = 1,1392,487,487,487
BEGIN DESCRIPTION:
Stream0145_DS 3.0
END DESCRIPTION:
XS GIS Cut Line= 3
      2052425.03     13918825.00      2052025.00     13918825.00
      2051910.00     13919039.94
#Sta/Elev= 30
  4599.7 1391.50  4629.7 1391.34  4639.7 1390.74  4659.7 1387.30  4669.7 1385.14
  4689.7 1382.25  4699.7 1381.52  4739.7 1376.93  4769.7 1374.74  4779.7 1373.42
  4809.7 1370.70  4849.7 1368.36  4859.7 1367.31  4899.7 1366.44  4922.6 1366.79
  4959.7 1366.23  4969.7 1364.95  5007.9 1363.60  5013.5 1361.68  5033.5 1359.10
  5033.7 1358.60  5037.2 1358.60  5037.5 1359.10  5045.1 1368.66  5051.7 1373.36
  5057.4 1374.56  5155.8 1377.91  5161.4 1377.75  5199.7 1378.92  5243.5 1378.94
#Mann=4,-1,0
  4599.7    0.12       0  4922.6   0.035       0  5033.5   0.035       0
  5037.5   0.035       0
Bank Sta=5033.5,5037.5
Exp/Cntr=0.3,0.1

Type RM Length L Ch R = 1,905,0,0,0
BEGIN DESCRIPTION:
Stream0145_DS 2.0
END DESCRIPTION:
XS GIS Cut Line= 4
      2052695.87     13918489.01      2052055.22     13918416.09
      2051940.63     13918447.34      2051701.06     13918895.23
#Sta/Elev= 30
  4366.4 1407.16  4417.6 1406.75  4467.9 1404.81  4488.1 1402.13  4568.6 1397.13
  4588.7 1394.52  4623.4 1394.14  4712.9 1389.19  4797.4 1371.28  4900.7 1367.16
  4920.8 1365.14  4936.1 1361.73  4951.0 1358.96  4961.1 1358.33  4976.4 1354.99
  4981.4 1355.90  4991.3 1355.53  4999.2 1353.34  4999.5 1352.84  5003.4 1353.34
  5013.9 1354.34  5021.3 1357.77  5032.1 1359.28  5116.8 1362.35  5170.4 1363.71
  5184.0 1365.28  5236.2 1367.85  5241.9 1367.25  5389.8 1369.67  5637.9 1375.08
#Mann=5,-1,0
  4366.4    0.12       0  4936.1    0.07       0  4999.2    0.05       0
  5003.4    0.07       0  5116.8   0.035       0
Bank Sta=4999.2,5003.4
Exp/Cntr=0.3,0.1

Chan Stop Cuts=-1