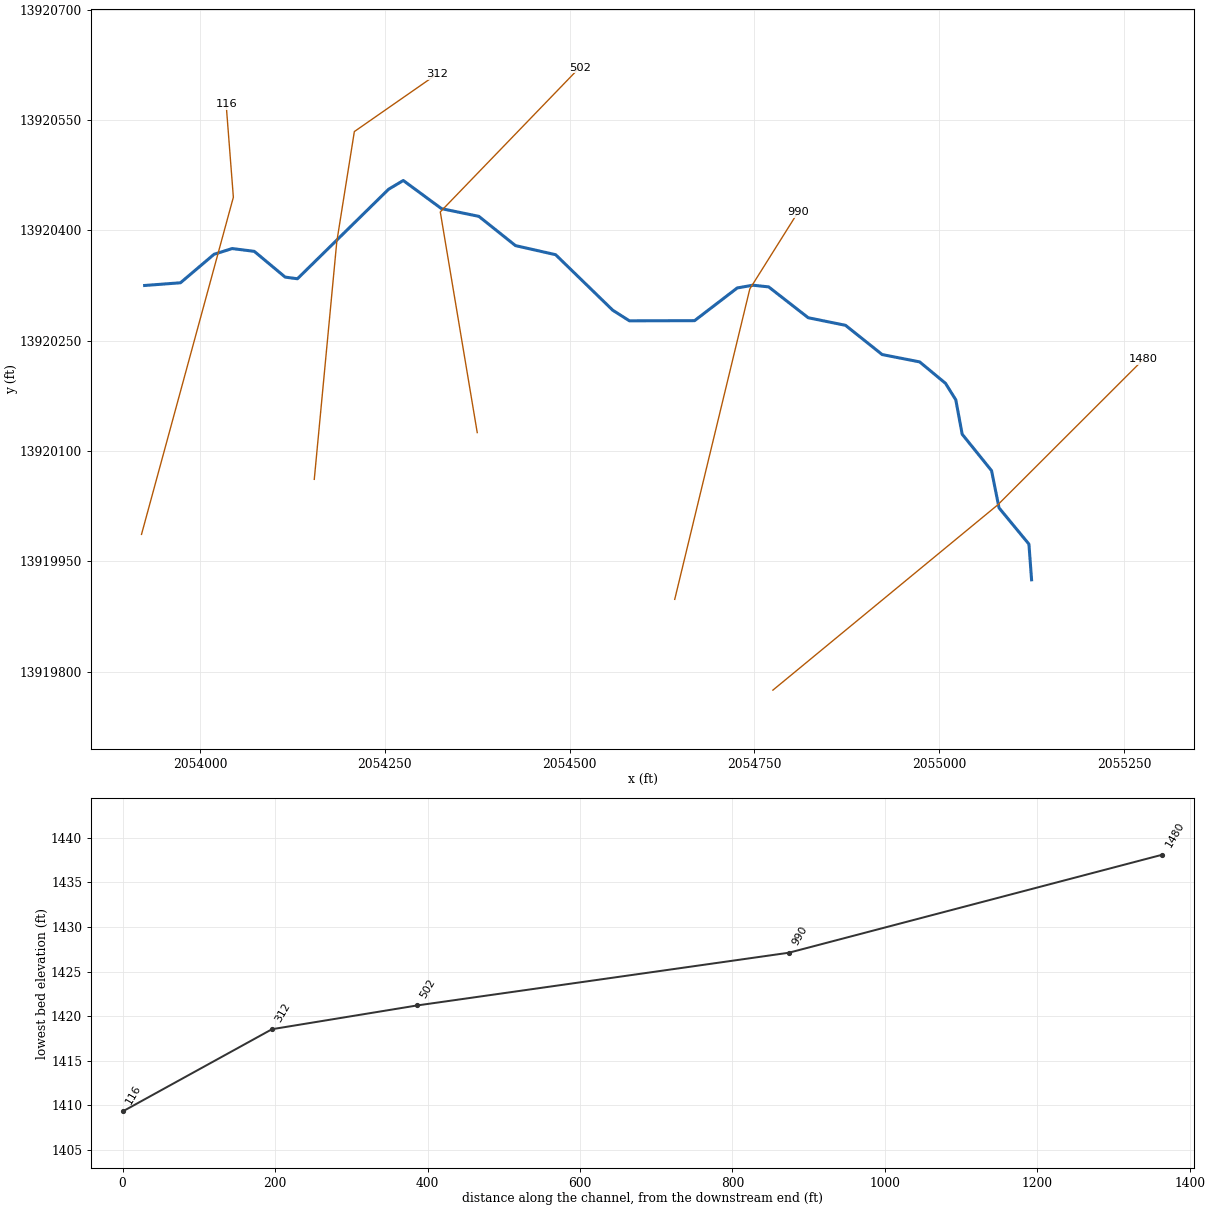
--- Stream0146_DS.prj (project) ---

Proj Title=Stream0146_DS Base Level Engineering
Current Plan=p01
Default Exp/Contr=0.3,0.1
English Units
Geom File=g01
Flow File=f01
Plan File=p01
BEGIN DESCRIPTION:
Stream0146_DS
END DESCRIPTION:

--- Stream0146_DS.p01 (plan) ---

Plan Title=Multiple Run
Short Identifier=Multiple
Geom File=g01
Flow File=f01
Subcritical Flow
K Sum by GR= 0
Std Step Tol= 0.01
Critical Tol= 0.01
Num of Std Step Trials= 20
Max Error Tol= 0.3
Flow Tol Ratio= 0.001
Split Flow NTrial= 30
Split Flow Tol= 0.02
Split Flow Ratio= 0.02
Log Output Level= 0
Friction Slope Method= 1
Unsteady Friction Slope Method= 2
Unsteady Bridges Friction Slope Method= 1
Parabolic Critical Depth
Global Vel Dist=  1 , 1 , 1
Global Log Level= 0
CheckData=True
Encroach Param= -1, 0, 0, 0
BEGIN DESCRIPTION:
Multiple Run
END DESCRIPTION:

--- Stream0146_DS.f01 (steady flow) ---

Flow Title=Multiple
Number of Profiles=7
Profile Names=10-year,25-year,50-year,1pct_min,100-year,1pct_plu,500-year
River Rch & RM= Stream0146_DS,Reach-1,1480
     518     848    1153     763    1523    3038    2628
Boundary for River Rch & Prof#=Stream0146_DS,Reach-1,1
Up Type=0
Dn Type=3
Dn Slope=0.005
Boundary for River Rch & Prof#=Stream0146_DS,Reach-1,2
Up Type=0
Dn Type=3
Dn Slope=0.005
Boundary for River Rch & Prof#=Stream0146_DS,Reach-1,3
Up Type=0
Dn Type=3
Dn Slope=0.005
Boundary for River Rch & Prof#=Stream0146_DS,Reach-1,4
Up Type=0
Dn Type=3
Dn Slope=0.005
Boundary for River Rch & Prof#=Stream0146_DS,Reach-1,5
Up Type=0
Dn Type=3
Dn Slope=0.005
Boundary for River Rch & Prof#=Stream0146_DS,Reach-1,6
Up Type=0
Dn Type=3
Dn Slope=0.005
Boundary for River Rch & Prof#=Stream0146_DS,Reach-1,7
Up Type=0
Dn Type=3
Dn Slope=0.005

--- Stream0146_DS.g01 (geometry) ---

Geom Title=Existing Conditions

River Reach=Stream0146_DS,Reach-1
Reach XY= 30
      2055125.00     13919925.00      2055121.40     13919973.51
      2055080.95     13920022.75      2055070.86     13920073.29
      2055031.11     13920122.84      2055022.47     13920169.56
      2055008.51     13920192.05      2054973.58     13920221.14
      2054922.84     13920231.11      2054873.28     13920270.85
      2054822.80     13920281.16      2054769.30     13920323.08
      2054747.81     13920325.39      2054726.74     13920321.63
      2054669.03     13920277.19      2054580.89     13920276.97
      2054558.26     13920291.44      2054481.05     13920366.84
      2054426.73     13920379.19      2054377.19     13920418.95
      2054326.63     13920429.44      2054274.91     13920467.71
      2054254.97     13920455.72      2054131.73     13920334.15
      2054115.13     13920336.38      2054073.37     13920371.39
      2054043.46     13920375.20      2054019.00     13920367.46
      2053973.51     13920328.69      2053925.00     13920325.00

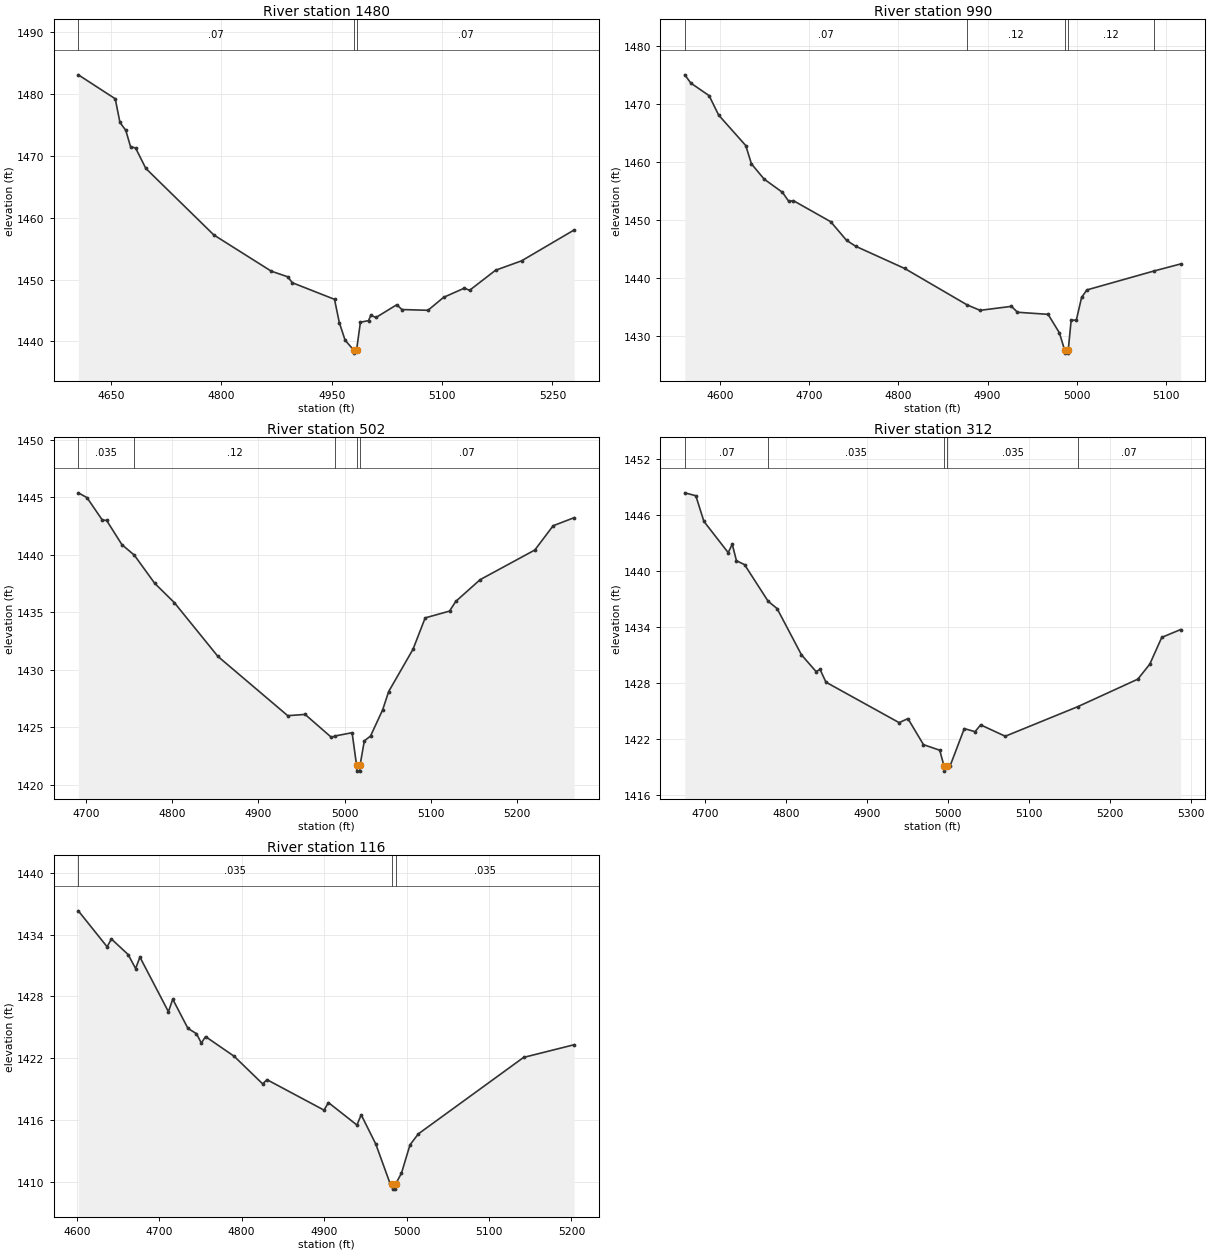
Type RM Length L Ch R = 1,1480,490,490,490
BEGIN DESCRIPTION:
Stream0146_DS 3.0
END DESCRIPTION:
XS GIS Cut Line= 3
      2054775.01     13919775.01      2055079.06     13920026.68
      2055276.43     13920224.73
#Sta/Elev= 30
  4605.3 1483.07  4655.5 1479.20  4661.9 1475.37  4669.8 1474.11  4676.3 1471.47
  4683.2 1471.24  4697.1 1467.95  4789.6 1457.20  4867.7 1451.35  4889.9 1450.45
  4896.4 1449.48  4953.7 1446.80  4960.2 1443.05  4968.1 1440.20  4979.7 1438.61
  4980.0 1438.11  4983.7 1438.61  4988.9 1443.10  5000.0 1443.36  5003.0 1444.22
  5010.1 1443.87  5038.4 1445.93  5045.4 1445.15  5080.8 1445.03  5102.0 1447.12
  5130.3 1448.61  5137.4 1448.26  5172.7 1451.50  5208.1 1453.02  5279.6 1458.01
#Mann=3,-1,0
  4605.3    0.07       0  4979.7    0.05       0  4983.7    0.07       0
Bank Sta=4979.7,4983.7
Exp/Cntr=0.3,0.1

Type RM Length L Ch R = 1,990,488,488,488
BEGIN DESCRIPTION:
Stream0146_DS 2.0
END DESCRIPTION:
XS GIS Cut Line= 3
      2054642.20     13919898.41      2054743.76     13920320.26
      2054808.84     13920424.39
#Sta/Elev= 30
  4560.1 1475.11  4566.9 1473.68  4587.4 1471.52  4598.1 1468.17  4628.6 1462.90
  4634.9 1459.76  4649.2 1457.12  4669.7 1454.85  4676.9 1453.27  4682.0 1453.41
  4723.9 1449.78  4741.7 1446.57  4752.0 1445.54  4807.0 1441.71  4877.3 1435.41
  4891.7 1434.49  4926.9 1435.18  4933.6 1434.16  4968.0 1433.80  4980.7 1430.61
  4986.6 1427.61  4986.8 1427.11  4990.3 1427.11  4990.6 1427.61  4993.9 1432.80
  4999.7 1432.80  5005.6 1436.71  5011.5 1438.01  5087.2 1441.29  5116.8 1442.49
#Mann=5,-1,0
  4560.1    0.07       0  4877.3    0.12       0  4986.6    0.05       0
  4990.6    0.12       0  5087.2    0.07       0
Bank Sta=4986.6,4990.6
Exp/Cntr=0.3,0.1

Type RM Length L Ch R = 1,502,190,190,190
BEGIN DESCRIPTION:
Stream0146_DS 1.0
END DESCRIPTION:
XS GIS Cut Line= 3
      2054374.99     13920125.04      2054325.00     13920425.00
      2054513.45     13920621.15
#Sta/Elev= 30
  4690.7 1445.38  4700.8 1444.96  4718.5 1443.02  4723.6 1442.98  4741.3 1440.88
  4755.8 1439.96  4779.4 1437.52  4802.2 1435.84  4852.9 1431.16  4934.0 1426.01
  4954.2 1426.12  4984.7 1424.13  4989.3 1424.25  5008.8 1424.53  5014.0 1421.69
  5014.3 1421.19  5017.8 1421.19  5018.0 1421.69  5023.0 1423.82  5030.2 1424.24
  5044.3 1426.52  5051.3 1428.11  5079.6 1431.79  5093.7 1434.51  5122.0 1435.10
  5129.2 1435.94  5157.5 1437.83  5221.1 1440.41  5242.4 1442.52  5266.8 1443.22
#Mann=5,-1,0
  4690.7   0.035       0  4755.8    0.12       0  4989.3    0.07       0
  5014.0    0.05       0  5018.0    0.07       0
Bank Sta=5014,5018
Exp/Cntr=0.3,0.1

Type RM Length L Ch R = 1,312,196,196,196
BEGIN DESCRIPTION:
Stream0146_DS 0.1
END DESCRIPTION:
XS GIS Cut Line= 4
      2054154.51     13920061.50      2054185.00     13920384.76
      2054208.73     13920534.20      2054320.51     13920612.34
#Sta/Elev= 30
  4675.3 1448.37  4688.9 1448.06  4698.9 1445.31  4728.9 1441.96  4733.9 1442.86
  4739.1 1441.09  4749.1 1440.67  4778.2 1436.75  4789.3 1435.96  4819.4 1431.00
  4837.4 1429.21  4842.4 1429.43  4849.6 1428.07  4940.0 1423.73  4950.9 1424.16
  4970.1 1421.37  4990.2 1420.77  4995.6 1419.03  4995.9 1418.53  4999.6 1419.03
  5002.7 1419.03  5020.5 1423.09  5033.8 1422.76  5040.7 1423.49  5071.1 1422.27
  5160.6 1425.44  5234.8 1428.39  5249.6 1430.00  5264.4 1432.87  5287.7 1433.71
#Mann=5,-1,0
  4675.3    0.07       0  4778.2   0.035       0  4995.6   0.035       0
  4999.6   0.035       0  5160.6    0.07       0
Bank Sta=4995.6,4999.6
Exp/Cntr=0.3,0.1

Type RM Length L Ch R = 1,116,0,0,0
BEGIN DESCRIPTION:
Stream0146_DS 0.0
END DESCRIPTION:
XS GIS Cut Line= 3
      2053920.77     13919986.73      2054045.04     13920444.98
      2054035.27     13920571.20
#Sta/Elev= 30
  4601.9 1436.30  4636.8 1432.81  4642.0 1433.57  4662.3 1432.06  4671.4 1430.70
  4676.6 1431.81  4711.2 1426.51  4716.4 1427.73  4734.8 1424.90  4745.2 1424.38
  4751.1 1423.47  4756.2 1424.10  4790.9 1422.19  4825.5 1419.51  4830.7 1419.92
  4900.0 1416.96  4905.2 1417.70  4939.8 1415.52  4945.0 1416.51  4962.7 1413.67
  4979.7 1409.92  4982.8 1409.80  4983.1 1409.30  4986.6 1409.30  4986.8 1409.80
  4993.8 1410.84  5004.2 1413.60  5014.3 1414.66  5142.0 1422.08  5203.3 1423.31
#Mann=3,-1,0
  4601.9   0.035       0  4982.8   0.035       0  4986.8   0.035       0
Bank Sta=4982.8,4986.8
Exp/Cntr=0.3,0.1

Chan Stop Cuts=-1