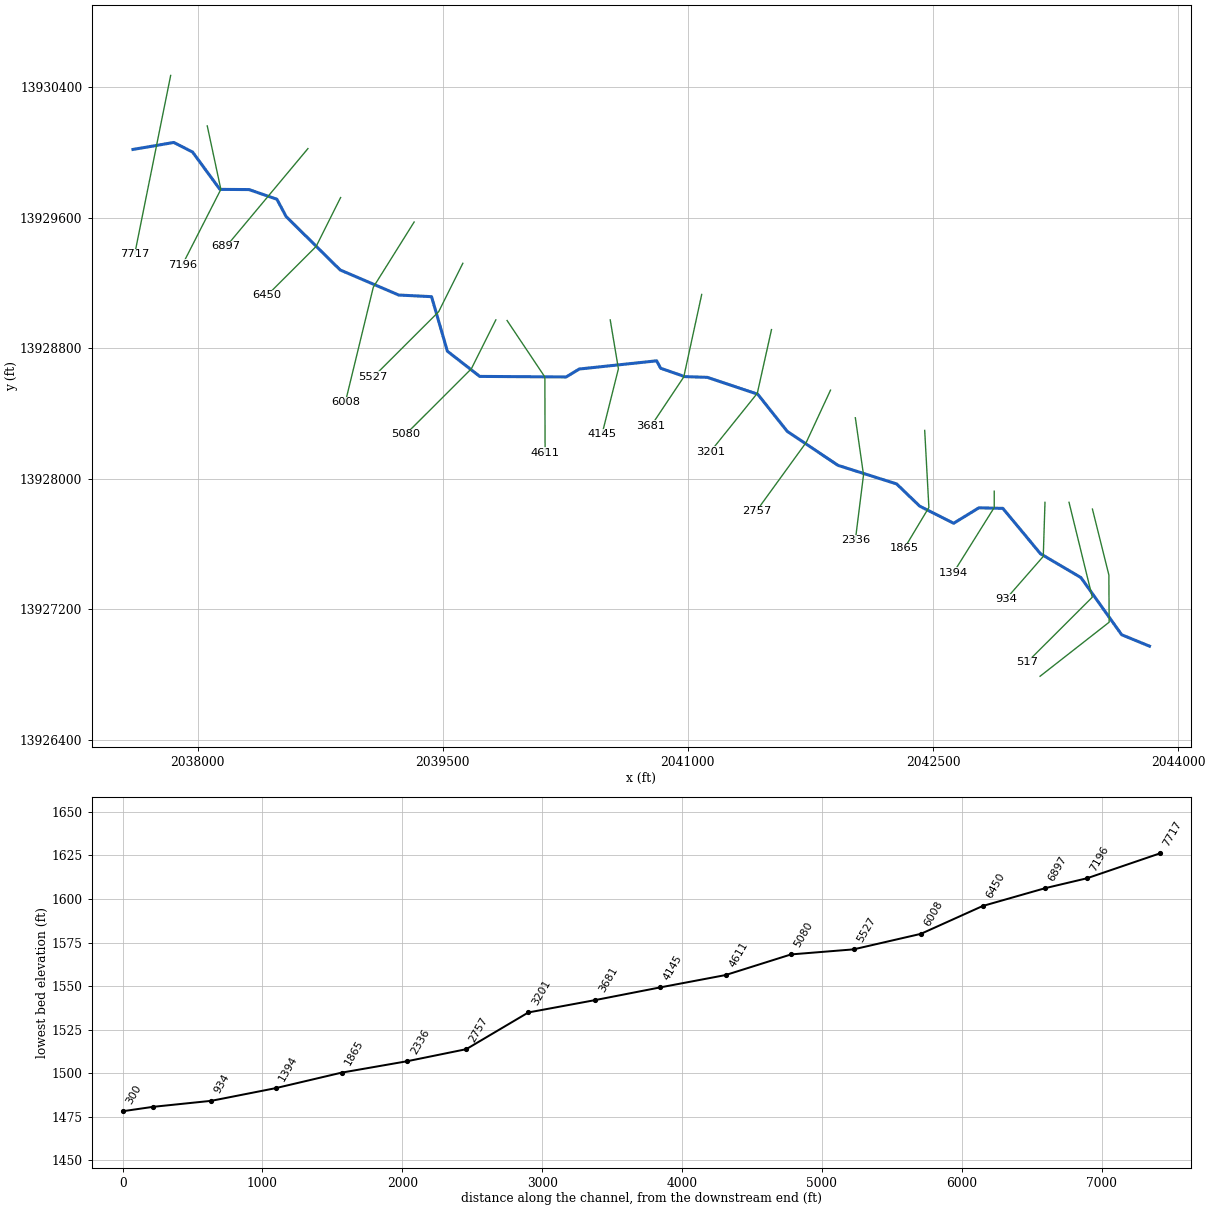
--- Stream0147_DS.prj (project) ---

Proj Title=Stream0147_DS Base Level Engineering
Current Plan=p01
Default Exp/Contr=0.3,0.1
English Units
Geom File=g01
Flow File=f01
Plan File=p01
BEGIN DESCRIPTION:
Stream0147_DS
END DESCRIPTION:

--- Stream0147_DS.p01 (plan) ---

Plan Title=Multiple Run
Short Identifier=Multiple
Geom File=g01
Flow File=f01
Subcritical Flow
K Sum by GR= 0
Std Step Tol= 0.01
Critical Tol= 0.01
Num of Std Step Trials= 20
Max Error Tol= 0.3
Flow Tol Ratio= 0.001
Split Flow NTrial= 30
Split Flow Tol= 0.02
Split Flow Ratio= 0.02
Log Output Level= 0
Friction Slope Method= 1
Unsteady Friction Slope Method= 2
Unsteady Bridges Friction Slope Method= 1
Parabolic Critical Depth
Global Vel Dist=  1 , 1 , 1
Global Log Level= 0
CheckData=True
Encroach Param= -1, 0, 0, 0
BEGIN DESCRIPTION:
Multiple Run
END DESCRIPTION:

--- Stream0147_DS.f01 (steady flow) ---

Flow Title=Multiple
Number of Profiles=7
Profile Names=10-year,25-year,50-year,1pct_min,100-year,1pct_plu,500-year
River Rch & RM= Stream0147_DS,Reach-1,7717
    1282    2246    3196    2208    4405    8790    8301
River Rch & RM= Stream0147_DS,Reach-1,6008
    1513    2659    3790    2619    5226   10428    9860
Boundary for River Rch & Prof#=Stream0147_DS,Reach-1,1
Up Type=0
Dn Type=3
Dn Slope=0.005
Boundary for River Rch & Prof#=Stream0147_DS,Reach-1,2
Up Type=0
Dn Type=3
Dn Slope=0.005
Boundary for River Rch & Prof#=Stream0147_DS,Reach-1,3
Up Type=0
Dn Type=3
Dn Slope=0.005
Boundary for River Rch & Prof#=Stream0147_DS,Reach-1,4
Up Type=0
Dn Type=3
Dn Slope=0.005
Boundary for River Rch & Prof#=Stream0147_DS,Reach-1,5
Up Type=0
Dn Type=3
Dn Slope=0.005
Boundary for River Rch & Prof#=Stream0147_DS,Reach-1,6
Up Type=0
Dn Type=3
Dn Slope=0.005
Boundary for River Rch & Prof#=Stream0147_DS,Reach-1,7
Up Type=0
Dn Type=3
Dn Slope=0.005

--- Stream0147_DS.g01 (geometry) ---

Geom Title=Existing Conditions

River Reach=Stream0147_DS,Reach-1
Reach XY= 30
      2037604.67     13930019.79      2037854.16     13930062.54
      2037968.87     13930004.11      2038136.37     13929775.01
      2038314.50     13929773.79      2038485.10     13929714.61
      2038541.66     13929608.34      2038872.70     13929280.83
      2039230.53     13929127.38      2039431.52     13929117.33
      2039528.32     13928783.05      2039726.46     13928628.54
      2040254.97     13928625.07      2040335.50     13928673.78
      2040809.04     13928724.05      2040833.50     13928678.56
      2040980.94     13928627.27      2041119.06     13928622.73
      2041427.44     13928519.48      2041608.29     13928291.64
      2041918.95     13928083.16      2042277.43     13927969.48
      2042418.94     13927833.14      2042626.74     13927728.31
      2042780.86     13927822.94      2042927.68     13927819.61
      2043157.95     13927541.50      2043405.37     13927395.46
      2043654.91     13927044.78      2043825.00     13926975.00

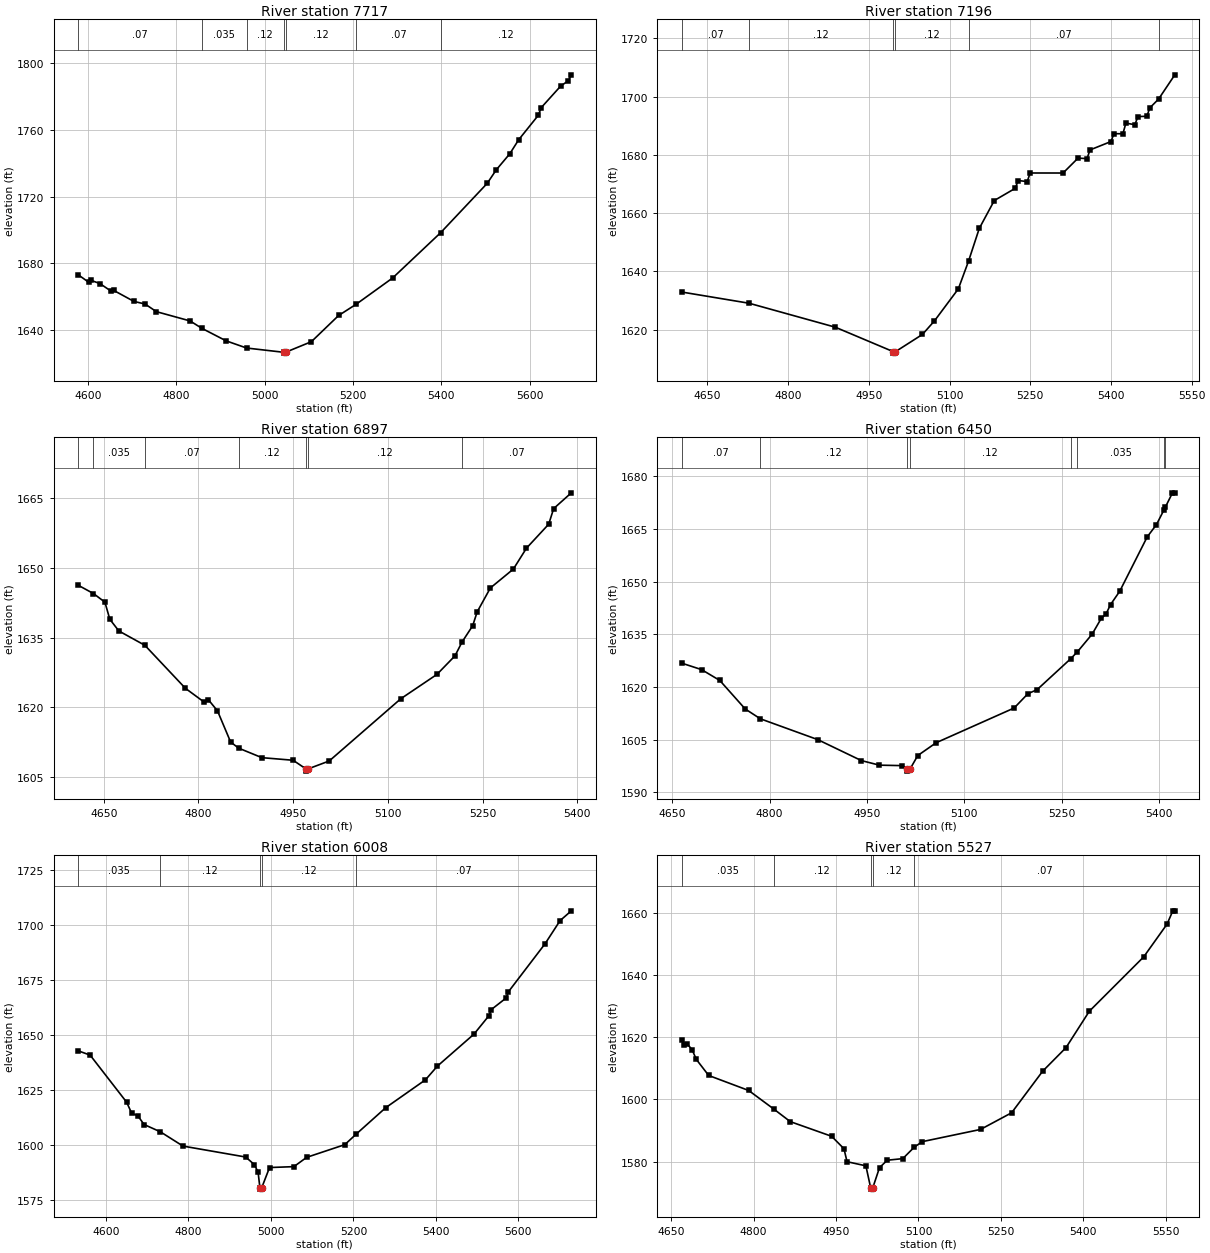
Type RM Length L Ch R = 1,7717,521,521,521
BEGIN DESCRIPTION:
Stream0147_DS 17.0
END DESCRIPTION:
XS GIS Cut Line= 2
      2037834.96     13930473.39      2037614.88     13929378.28
#Sta/Elev= 30
  4577.6 1673.16  4602.1 1668.53  4607.2 1669.76  4627.0 1667.85  4653.0 1663.16
  4658.1 1663.77  4703.9 1657.17  4729.0 1655.63  4754.7 1651.04  4831.0 1645.48
  4858.0 1641.01  4912.6 1633.55  4959.0 1629.24  5043.2 1626.68  5043.4 1626.18
  5047.2 1626.68  5105.8 1633.04  5167.5 1648.74  5207.2 1655.47  5289.9 1671.24
  5398.7 1698.40  5504.1 1727.96  5524.5 1736.03  5555.1 1745.64  5575.5 1754.14
  5619.7 1768.72  5626.5 1773.37  5670.5 1786.27  5687.7 1789.45  5694.6 1793.01
#Mann=7,-1,0
  4577.6    0.07       0  4858.0   0.035       0  4959.0    0.12       0
  5043.2    0.05       0  5047.2    0.12       0  5207.2    0.07       0
  5398.7    0.12       0
Bank Sta=5043.2,5047.2
Exp/Cntr=0.3,0.1

Type RM Length L Ch R = 1,7196,299,299,299
BEGIN DESCRIPTION:
Stream0147_DS 16.0
END DESCRIPTION:
XS GIS Cut Line= 3
      2038059.03     13930164.02      2038142.21     13929775.01
      2037906.85     13929312.78
#Sta/Elev= 30
  4602.2 1632.90  4727.4 1629.05  4887.5 1620.83  4995.5 1612.41  4995.7 1611.91
  4999.5 1612.41  5049.7 1618.34  5072.0 1622.99  5116.4 1634.00  5135.4 1643.55
  5155.3 1654.76  5183.2 1664.33  5222.0 1668.51  5227.7 1671.20  5244.3 1670.84
  5249.9 1673.79  5311.0 1673.78  5338.9 1678.91  5355.5 1678.72  5361.1 1681.71
  5400.0 1684.59  5405.6 1687.29  5422.2 1687.27  5427.8 1690.92  5444.5 1690.38
  5450.1 1693.17  5466.7 1693.27  5472.3 1696.17  5488.5 1699.17  5518.7 1707.51
#Mann=6,-1,0
  4602.2    0.07       0  4727.4    0.12       0  4995.5    0.05       0
  4999.5    0.12       0  5135.4    0.07       0  5488.5    0.12       0
Bank Sta=4995.5,4999.5
Exp/Cntr=0.3,0.1

Type RM Length L Ch R = 1,6897,447,447,447
BEGIN DESCRIPTION:
Stream0147_DS 15.0
END DESCRIPTION:
XS GIS Cut Line= 3
      2038674.98     13930024.97      2038425.00     13929725.00
      2038174.99     13929424.99
#Sta/Elev= 30
  4609.6 1646.25  4633.7 1644.47  4651.9 1642.61  4659.7 1638.92  4674.0 1636.41
  4715.2 1633.32  4779.4 1624.06  4808.1 1621.19  4815.9 1621.58  4830.2 1619.21
  4851.0 1612.50  4863.7 1611.18  4900.5 1609.13  4950.0 1608.57  4970.1 1606.73
  4970.3 1606.23  4974.1 1606.73  5007.2 1608.42  5120.5 1621.81  5177.8 1627.06
  5206.4 1631.06  5217.5 1634.02  5234.4 1637.54  5241.5 1640.52  5262.4 1645.67
  5298.8 1649.73  5319.6 1654.24  5354.8 1659.40  5362.6 1662.75  5390.6 1666.15
#Mann=7,-1,0
  4609.6    0.07       0  4633.7   0.035       0  4715.2    0.07       0
  4863.7    0.12       0  4970.1    0.05       0  4974.1    0.12       0
  5217.5    0.07       0
Bank Sta=4970.1,4974.1
Exp/Cntr=0.3,0.1

Type RM Length L Ch R = 1,6450,442,442,442
BEGIN DESCRIPTION:
Stream0147_DS 14.0
END DESCRIPTION:
XS GIS Cut Line= 3
      2038874.99     13929724.98      2038725.00     13929425.00
      2038424.96     13929124.96
#Sta/Elev= 30
  4664.6 1626.76  4695.3 1624.91  4723.3 1621.83  4762.4 1613.71  4785.8 1610.90
  4874.2 1604.97  4941.3 1599.00  4969.2 1597.69  5003.5 1597.56  5012.1 1596.49
  5012.4 1595.99  5016.1 1596.49  5028.3 1600.43  5056.6 1604.08  5176.8 1613.98
  5198.0 1618.05  5212.1 1619.20  5263.7 1627.98  5274.3 1630.00  5297.0 1635.04
  5311.1 1639.56  5318.2 1640.72  5325.3 1643.45  5339.4 1647.23  5381.8 1662.74
  5396.0 1666.22  5407.2 1670.29  5409.5 1671.13  5420.7 1675.29  5424.3 1675.29
#Mann=8,-1,0
  4664.6    0.07       0  4785.8    0.12       0  5012.1    0.05       0
  5016.1    0.12       0  5263.7    0.07       0  5274.3   0.035       0
  5407.2    0.07       0  5409.5   0.035       0
Bank Sta=5012.1,5016.1
Exp/Cntr=0.3,0.1

Type RM Length L Ch R = 1,6008,481,481,481
BEGIN DESCRIPTION:
Stream0147_DS 13.0
END DESCRIPTION:
XS GIS Cut Line= 3
      2039325.02     13929575.04      2039075.00     13929175.00
      2038904.22     13928471.07
#Sta/Elev= 30
  4532.5 1642.86  4561.4 1640.92  4649.9 1619.53  4662.3 1614.47  4677.0 1613.36
  4692.3 1609.37  4731.9 1606.04  4786.7 1599.56  4938.8 1594.59  4960.0 1591.11
  4968.9 1587.64  4973.3 1580.50  4973.6 1580.00  4977.4 1580.50  4996.6 1589.81
  5055.7 1590.22  5086.6 1594.44  5179.2 1600.22  5206.9 1605.02  5278.4 1617.01
  5374.7 1629.67  5403.8 1635.92  5492.5 1650.45  5529.0 1658.87  5534.3 1661.58
  5570.2 1666.83  5576.1 1669.72  5664.8 1691.49  5701.4 1702.05  5728.6 1706.49
#Mann=5,-1,0
  4532.5   0.035       0  4731.9    0.12       0  4973.3    0.05       0
  4977.4    0.12       0  5206.9    0.07       0
Bank Sta=4973.3,4977.4
Exp/Cntr=0.3,0.1

Type RM Length L Ch R = 1,5527,447,447,447
BEGIN DESCRIPTION:
Stream0147_DS 12.0
END DESCRIPTION:
XS GIS Cut Line= 3
      2039622.99     13929321.83      2039475.00     13929025.00
      2039074.97     13928624.97
#Sta/Elev= 30
  4669.1 1619.25  4673.5 1617.47  4679.1 1617.91  4687.9 1616.09  4695.8 1612.90
  4718.2 1607.74  4791.0 1602.90  4837.0 1596.87  4866.7 1592.86  4942.0 1588.13
  4964.4 1584.12  4970.0 1579.94  5004.3 1578.61  5012.9 1571.60  5013.1 1571.10
  5017.0 1571.60  5029.1 1578.03  5043.2 1580.42  5071.5 1580.93  5091.8 1584.54
  5106.8 1586.40  5212.9 1590.34  5269.5 1595.71  5326.0 1609.11  5368.5 1616.71
  5410.9 1628.44  5509.9 1645.97  5552.3 1656.51  5562.9 1660.81  5566.5 1660.81
#Mann=5,-1,0
  4669.1   0.035       0  4837.0    0.12       0  5012.9    0.05       0
  5017.0    0.12       0  5091.8    0.07       0
Bank Sta=5012.9,5017
Exp/Cntr=0.3,0.1

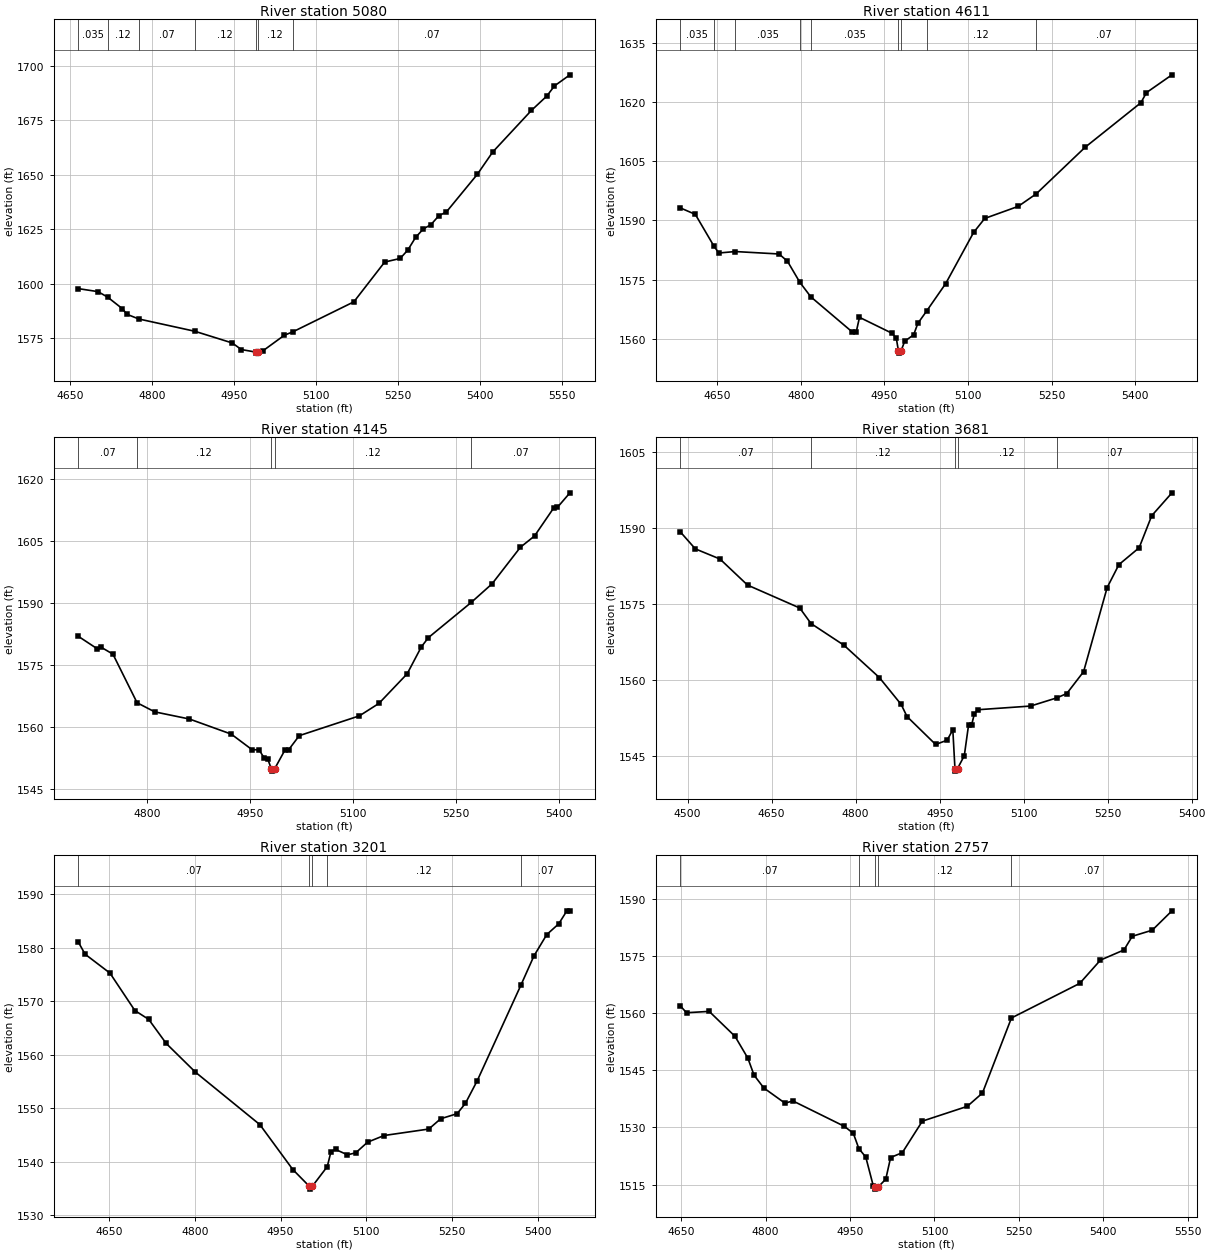
Type RM Length L Ch R = 1,5080,469,469,469
BEGIN DESCRIPTION:
Stream0147_DS 11.0
END DESCRIPTION:
XS GIS Cut Line= 3
      2039825.02     13928975.03      2039675.00     13928675.00
      2039275.02     13928275.02
#Sta/Elev= 30
  4664.3 1597.80  4700.7 1596.41  4718.3 1593.90  4745.4 1588.57  4753.8 1586.01
  4775.4 1583.87  4878.1 1578.23  4946.6 1572.87  4963.4 1569.84  4989.3 1568.70
  4989.6 1568.20  4993.4 1568.70  5003.3 1569.33  5042.2 1576.42  5057.6 1577.95
  5169.5 1591.73  5226.0 1609.98  5254.3 1611.62  5268.4 1615.49  5282.6 1621.29
  5296.7 1625.13  5310.9 1627.18  5325.0 1631.17  5339.2 1633.01  5395.7 1650.22
  5424.0 1660.48  5494.7 1679.51  5523.0 1686.12  5537.1 1690.79  5565.4 1695.87
#Mann=7,-1,0
  4664.3   0.035       0  4718.3    0.12       0  4775.4    0.07       0
  4878.1    0.12       0  4989.3    0.05       0  4993.4    0.12       0
  5057.6    0.07       0
Bank Sta=4989.3,4993.4
Exp/Cntr=0.3,0.1

Type RM Length L Ch R = 1,4611,466,466,466
BEGIN DESCRIPTION:
Stream0147_DS 10.0
END DESCRIPTION:
XS GIS Cut Line= 3
      2039893.84     13928971.07      2040125.00     13928625.00
      2040126.45     13928159.28
#Sta/Elev= 30
  4583.8 1593.20  4611.0 1591.54  4644.3 1583.50  4653.1 1581.74  4682.6 1582.11
  4761.2 1581.49  4776.2 1579.65  4798.4 1574.31  4818.1 1570.62  4891.7 1561.79
  4899.4 1561.63  4905.4 1565.42  4963.9 1561.37  4971.4 1560.12  4975.3 1556.84
  4975.6 1556.34  4979.7 1556.84  4986.5 1559.36  5002.5 1560.99  5010.0 1563.88
  5025.6 1566.98  5060.0 1573.99  5110.0 1586.95  5130.0 1590.51  5190.0 1593.57
  5222.3 1596.74  5310.0 1608.56  5410.0 1619.86  5420.0 1622.43  5465.7 1626.94
#Mann=9,-1,0
  4583.8   0.035       0  4644.3    0.07       0  4682.6   0.035       0
  4798.4    0.07       0  4818.1   0.035       0  4975.3   0.035       0
  4979.7   0.035       0  5025.6    0.12       0  5222.3    0.07       0
Bank Sta=4975.3,4979.7
Exp/Cntr=0.3,0.1

Type RM Length L Ch R = 1,4145,464,464,464
BEGIN DESCRIPTION:
Stream0147_DS 9.0
END DESCRIPTION:
XS GIS Cut Line= 3
      2040524.99     13928975.04      2040575.00     13928675.00
      2040475.00     13928274.99
#Sta/Elev= 30
  4700.1 1581.91  4728.0 1578.86  4733.1 1579.29  4750.8 1577.57  4786.0 1565.81
  4811.7 1563.61  4862.3 1561.88  4923.2 1558.23  4953.6 1554.45  4963.7 1554.44
  4971.3 1552.42  4976.4 1552.18  4981.7 1549.78  4982.1 1549.28  4986.2 1549.78
  5001.7 1554.47  5006.9 1554.47  5022.3 1557.86  5109.9 1562.65  5138.3 1565.65
  5179.5 1572.82  5200.1 1579.32  5210.4 1581.56  5272.7 1590.06  5303.2 1594.58
  5344.4 1603.41  5365.0 1606.14  5393.4 1613.03  5398.5 1613.09  5416.6 1616.58
#Mann=5,-1,0
  4700.1    0.07       0  4786.0    0.12       0  4981.7    0.05       0
  4986.2    0.12       0  5272.7    0.07       0
Bank Sta=4981.7,4986.2
Exp/Cntr=0.3,0.1

Type RM Length L Ch R = 1,3681,480,480,480
BEGIN DESCRIPTION:
Stream0147_DS 8.0
END DESCRIPTION:
XS GIS Cut Line= 3
      2041084.78     13929130.84      2040975.00     13928625.00
      2040774.99     13928324.98
#Sta/Elev= 30
  4486.6 1589.25  4513.7 1585.86  4557.7 1583.86  4606.9 1578.72  4700.1 1574.20
  4720.3 1571.13  4779.1 1566.85  4842.4 1560.46  4881.3 1555.16  4891.7 1552.78
  4942.8 1547.27  4963.3 1548.11  4973.5 1550.16  4977.3 1542.51  4977.6 1542.01
  4981.9 1542.51  4994.0 1545.06  5001.7 1551.19  5007.2 1551.19  5011.7 1553.20
  5017.7 1554.12  5112.4 1554.85  5159.6 1556.48  5177.0 1557.32  5207.0 1561.63
  5249.1 1578.23  5270.1 1582.76  5306.2 1586.08  5328.7 1592.41  5364.8 1596.92
#Mann=5,-1,0
  4486.6    0.07       0  4720.3    0.12       0  4977.3    0.05       0
  4981.9    0.12       0  5159.6    0.07       0
Bank Sta=4977.3,4981.9
Exp/Cntr=0.3,0.1

Type RM Length L Ch R = 1,3201,444,444,444
BEGIN DESCRIPTION:
Stream0147_DS 7.0
END DESCRIPTION:
XS GIS Cut Line= 3
      2041511.86     13928915.51      2041425.00     13928525.00
      2041136.88     13928165.58
#Sta/Elev= 30
  4595.8 1581.08  4608.0 1578.75  4651.5 1575.22  4695.1 1568.23  4719.3 1566.58
  4750.0 1562.08  4801.2 1556.71  4913.9 1546.92  4971.5 1538.54  5000.7 1535.38
  5001.1 1534.88  5005.4 1535.38  5031.8 1539.08  5038.3 1541.87  5046.3 1542.29
  5067.1 1541.29  5081.5 1541.65  5102.3 1543.64  5131.1 1544.89  5209.5 1546.10
  5230.3 1548.02  5259.1 1548.97  5273.5 1550.88  5294.3 1555.13  5370.7 1572.97
  5393.6 1578.44  5416.0 1582.42  5436.8 1584.41  5451.2 1586.85  5456.5 1586.85
#Mann=5,-1,0
  4595.8    0.07       0  5000.7    0.05       0  5005.4    0.07       0
  5031.8    0.12       0  5370.7    0.07       0
Bank Sta=5000.7,5005.4
Exp/Cntr=0.3,0.1

Type RM Length L Ch R = 1,2757,421,421,421
BEGIN DESCRIPTION:
Stream0147_DS 6.0
END DESCRIPTION:
XS GIS Cut Line= 3
      2041872.99     13928544.05      2041725.00     13928225.00
      2041419.07     13927802.29
#Sta/Elev= 30
  4648.3 1562.00  4659.6 1560.16  4699.9 1560.51  4745.7 1553.96  4768.5 1548.23
  4779.6 1543.74  4797.0 1540.37  4834.6 1536.38  4848.4 1536.99  4940.0 1530.30
  4955.9 1528.45  4965.7 1524.45  4978.0 1522.22  4991.3 1514.67  4994.9 1514.30
  4995.2 1513.80  4999.6 1514.30  5013.5 1516.42  5022.1 1522.11  5042.9 1523.39
  5078.5 1531.67  5158.2 1535.55  5185.2 1539.05  5236.7 1558.78  5358.0 1567.87
  5394.8 1573.99  5436.6 1576.66  5451.3 1580.25  5486.8 1581.85  5521.8 1586.94
#Mann=5,-1,0
  4648.3    0.07       0  4965.7    0.12       0  4994.9    0.05       0
  4999.6    0.12       0  5236.7    0.07       0
Bank Sta=4994.9,4999.6
Exp/Cntr=0.3,0.1

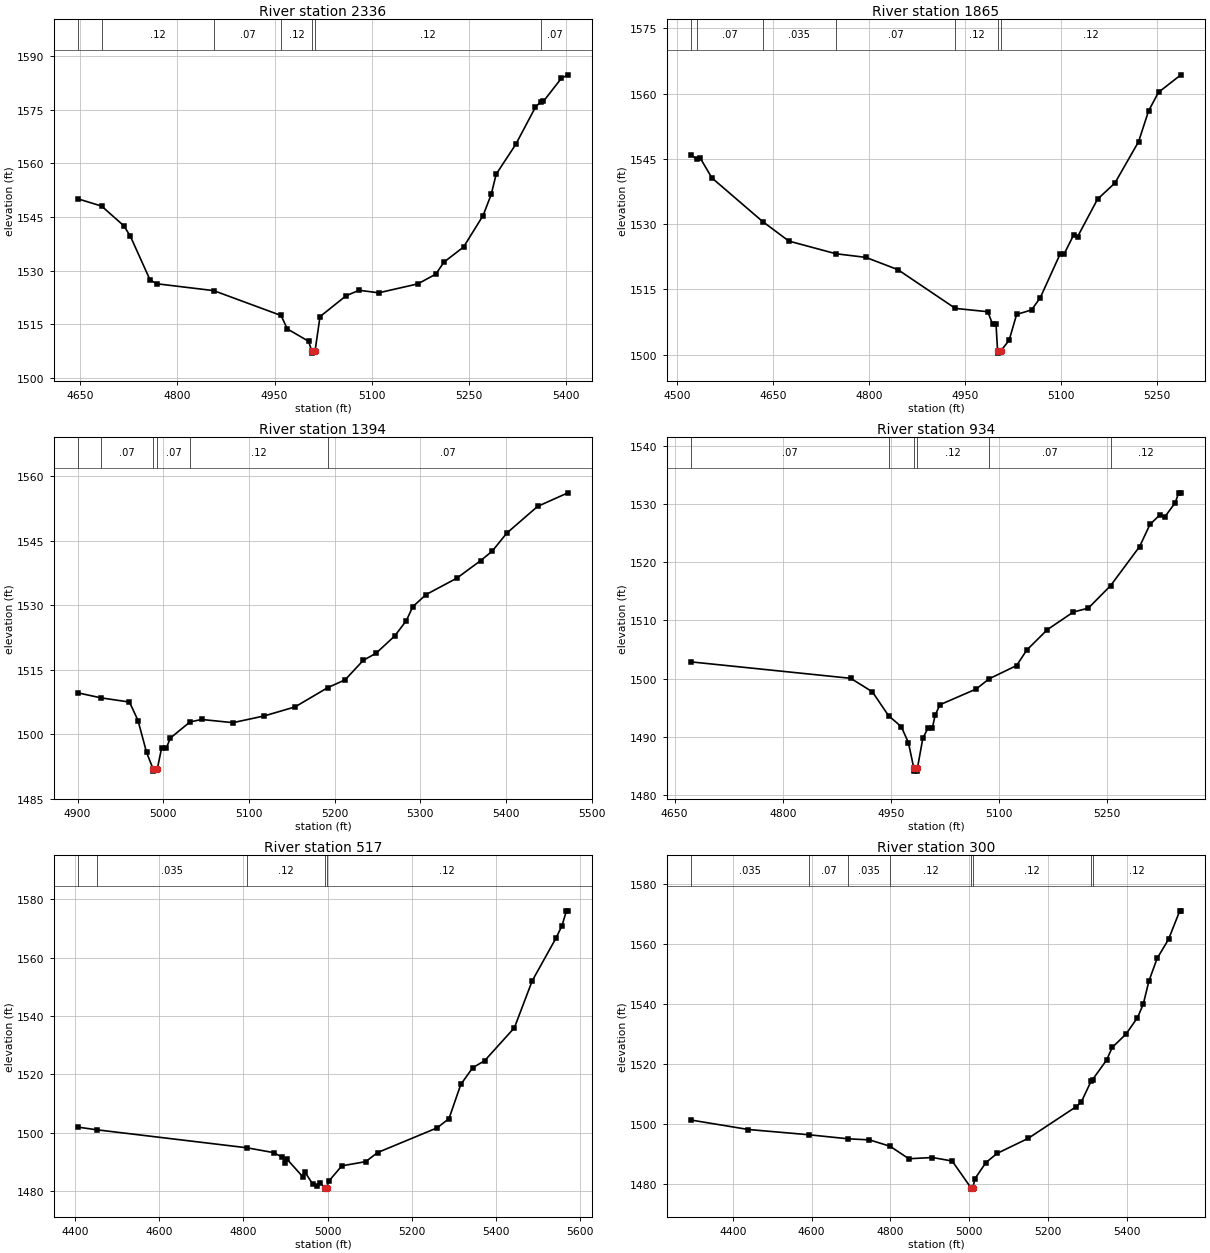
Type RM Length L Ch R = 1,2336,471,471,471
BEGIN DESCRIPTION:
Stream0147_DS 5.0
END DESCRIPTION:
XS GIS Cut Line= 3
      2042025.01     13928374.96      2042075.00     13928025.00
      2042025.00     13927625.03
#Sta/Elev= 30
  4646.5 1550.07  4682.8 1548.07  4717.2 1542.55  4727.3 1539.63  4757.6 1527.44
  4767.7 1526.33  4856.0 1524.40  4960.1 1517.44  4969.7 1513.69  5002.5 1510.23
  5007.7 1507.41  5008.0 1506.91  5012.5 1507.41  5020.2 1517.12  5060.5 1522.96
  5080.6 1524.50  5110.9 1523.79  5171.3 1526.29  5199.1 1529.02  5211.6 1532.37
  5241.9 1536.60  5272.1 1545.42  5284.7 1551.36  5292.3 1556.98  5322.5 1565.32
  5352.7 1575.66  5361.1 1577.26  5365.3 1577.37  5393.0 1583.82  5403.1 1584.79
#Mann=7,-1,0
  4646.5    0.07       0  4682.8    0.12       0  4856.0    0.07       0
  4960.1    0.12       0  5007.7    0.05       0  5012.5    0.12       0
  5361.1    0.07       0
Bank Sta=5007.7,5012.5
Exp/Cntr=0.3,0.1

Type RM Length L Ch R = 1,1865,471,471,471
BEGIN DESCRIPTION:
Stream0147_DS 4.0
END DESCRIPTION:
XS GIS Cut Line= 3
      2042449.37     13928297.47      2042475.00     13927825.00
      2042325.01     13927575.01
#Sta/Elev= 30
  4522.2 1545.92  4531.3 1544.86  4536.8 1545.10  4554.7 1540.61  4633.9 1530.58
  4674.9 1526.08  4748.2 1523.17  4795.1 1522.33  4845.1 1519.51  4934.8 1510.60
  4985.4 1509.84  4992.9 1506.98  4998.3 1506.98  5000.7 1500.82  5001.0 1500.32
  5005.6 1500.82  5018.7 1503.26  5030.4 1509.21  5053.7 1510.25  5067.3 1513.05
  5098.4 1523.13  5104.2 1523.00  5119.8 1527.59  5125.6 1527.09  5156.7 1535.70
  5183.9 1539.43  5220.8 1548.93  5236.4 1556.00  5251.9 1560.28  5286.9 1564.30
#Mann=7,-1,0
  4522.2    0.12       0  4531.3    0.07       0  4633.9   0.035       0
  4748.2    0.07       0  4934.8    0.12       0  5000.7    0.05       0
  5005.6    0.12       0
Bank Sta=5000.7,5005.6
Exp/Cntr=0.3,0.1

Type RM Length L Ch R = 1,1394,460,460,460
BEGIN DESCRIPTION:
Stream0147_DS 3.0
END DESCRIPTION:
XS GIS Cut Line= 3
      2042875.00     13927925.02      2042875.00     13927825.00
      2042625.01     13927425.02
#Sta/Elev= 30
  4900.5 1509.64  4927.6 1508.47  4960.5 1507.51  4970.5 1503.21  4980.5 1495.78
  4988.1 1491.93  4988.4 1491.43  4993.0 1491.93  4998.0 1496.78  5003.5 1496.78
  5008.2 1499.12  5031.1 1502.87  5044.7 1503.45  5081.3 1502.71  5117.9 1504.28
  5153.8 1506.38  5191.7 1510.84  5212.2 1512.68  5233.4 1517.22  5248.2 1518.85
  5270.0 1522.87  5283.5 1526.41  5291.2 1529.70  5306.5 1532.50  5342.5 1536.33
  5370.2 1540.40  5383.8 1542.61  5400.9 1546.83  5436.8 1553.04  5472.2 1556.20
#Mann=6,-1,0
  4900.5   0.035       0  4927.6    0.07       0  4988.1    0.05       0
  4993.0    0.07       0  5031.1    0.12       0  5191.7    0.07       0
Bank Sta=4988.1,4993
Exp/Cntr=0.3,0.1

Type RM Length L Ch R = 1,934,417,417,417
BEGIN DESCRIPTION:
Stream0147_DS 2.0
END DESCRIPTION:
XS GIS Cut Line= 3
      2043185.48     13927856.53      2043175.00     13927525.00
      2042945.90     13927262.78
#Sta/Elev= 30
  4672.8 1502.90  4894.4 1500.08  4924.5 1497.76  4946.9 1493.67  4964.5 1491.80
  4974.5 1489.05  4982.0 1484.66  4982.4 1484.16  4986.6 1484.16  4987.0 1484.66
  4994.5 1489.80  5002.0 1491.62  5007.8 1491.62  5011.6 1493.77  5018.3 1495.55
  5068.6 1498.25  5086.6 1500.00  5124.6 1502.27  5138.8 1504.93  5167.3 1508.43
  5203.4 1511.45  5224.2 1512.12  5255.1 1515.98  5295.4 1522.69  5309.7 1526.47
  5323.2 1528.08  5330.6 1527.82  5344.8 1530.20  5349.6 1531.90  5352.7 1531.90
#Mann=6,-1,0
  4672.8    0.07       0  4946.9    0.12       0  4982.0    0.05       0
  4987.0    0.12       0  5086.6    0.07       0  5255.1    0.12       0
Bank Sta=4982,4987
Exp/Cntr=0.3,0.1

Type RM Length L Ch R = 1,517,217,217,217
BEGIN DESCRIPTION:
Stream0147_DS 1.0
END DESCRIPTION:
XS GIS Cut Line= 3
      2043332.58     13927856.84      2043475.00     13927275.00
      2043075.00     13926875.00
#Sta/Elev= 30
  4406.7 1501.93  4450.7 1501.03  4808.2 1494.86  4871.9 1493.20  4892.5 1491.61
  4899.1 1489.68  4904.2 1490.85  4940.7 1484.99  4945.9 1486.62  4964.5 1482.44
  4974.8 1481.61  4982.3 1482.86  4992.9 1481.20  4993.3 1480.70  4997.9 1481.20
  5003.1 1483.48  5034.0 1488.68  5090.6 1490.11  5118.9 1493.22  5260.3 1501.67
  5288.6 1504.84  5316.8 1516.57  5345.1 1522.28  5373.4 1524.68  5444.1 1535.95
  5486.5 1552.03  5543.1 1566.68  5557.3 1570.94  5567.9 1576.01  5571.4 1576.01
#Mann=5,-1,0
  4406.7    0.07       0  4450.7   0.035       0  4808.2    0.12       0
  4992.9    0.05       0  4997.9    0.12       0
Bank Sta=4992.9,4997.9
Exp/Cntr=0.3,0.1

Type RM Length L Ch R = 1,300,0,0,0
BEGIN DESCRIPTION:
Stream0147_DS 0.0
END DESCRIPTION:
XS GIS Cut Line= 4
      2043475.82     13927815.31      2043576.49     13927411.31
      2043578.12     13927121.57      2043155.39     13926790.42
#Sta/Elev= 30
  4293.9 1501.26  4439.5 1498.10  4592.6 1496.35  4693.2 1494.98  4746.6 1494.64
  4799.0 1492.50  4846.6 1488.33  4906.6 1488.74  4956.6 1487.57  5003.9 1478.68
  5004.3 1478.18  5008.9 1478.68  5014.5 1481.70  5042.1 1487.05  5070.6 1490.12
  5149.3 1495.13  5270.7 1505.68  5284.0 1507.24  5309.2 1514.29  5312.9 1514.79
  5348.2 1521.27  5362.6 1525.50  5397.9 1530.02  5426.8 1535.48  5441.3 1539.92
  5455.8 1547.69  5476.6 1555.27  5505.5 1561.61  5534.1 1571.16  5537.0 1571.16
#Mann=8,-1,0
  4293.9   0.035       0  4592.6    0.07       0  4693.2   0.035       0
  4799.0    0.12       0  5003.9    0.05       0  5008.9    0.12       0
  5309.2    0.07       0  5312.9    0.12       0
Bank Sta=5003.9,5008.9
Exp/Cntr=0.3,0.1

Chan Stop Cuts=-1