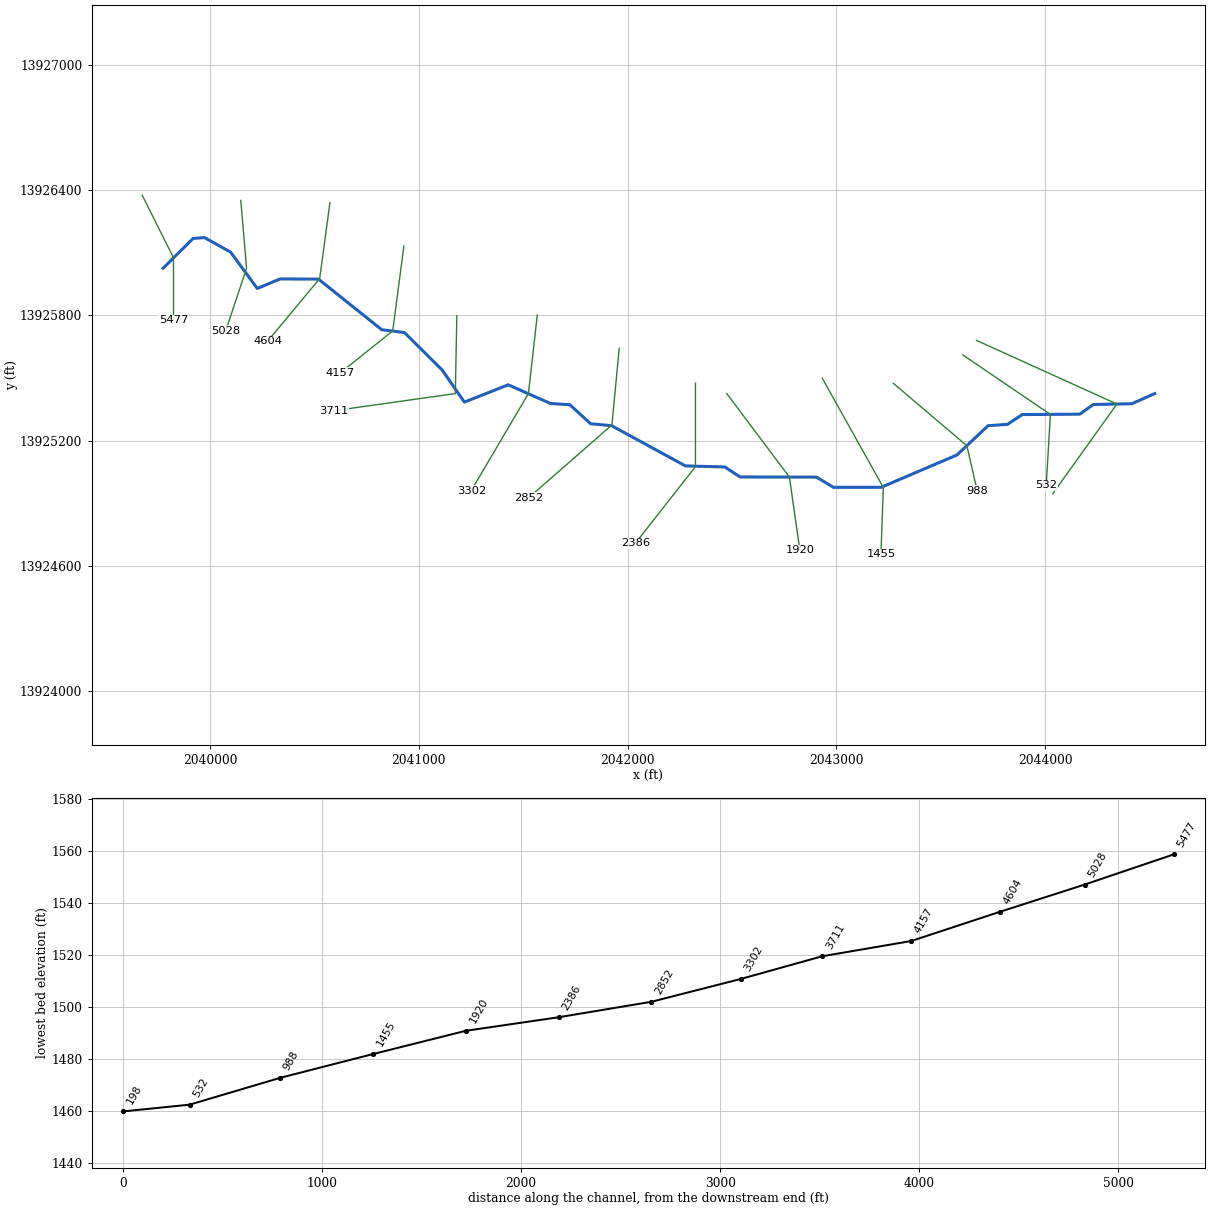
--- Stream0148_DS.prj (project) ---

Proj Title=Stream0148_DS Base Level Engineering
Current Plan=p01
Default Exp/Contr=0.3,0.1
English Units
Geom File=g01
Flow File=f01
Plan File=p01
BEGIN DESCRIPTION:
Stream0148_DS
END DESCRIPTION:

--- Stream0148_DS.p01 (plan) ---

Plan Title=Multiple Run
Short Identifier=Multiple
Geom File=g01
Flow File=f01
Subcritical Flow
K Sum by GR= 0
Std Step Tol= 0.01
Critical Tol= 0.01
Num of Std Step Trials= 20
Max Error Tol= 0.3
Flow Tol Ratio= 0.001
Split Flow NTrial= 30
Split Flow Tol= 0.02
Split Flow Ratio= 0.02
Log Output Level= 0
Friction Slope Method= 1
Unsteady Friction Slope Method= 2
Unsteady Bridges Friction Slope Method= 1
Parabolic Critical Depth
Global Vel Dist=  1 , 1 , 1
Global Log Level= 0
CheckData=True
Encroach Param= -1, 0, 0, 0
BEGIN DESCRIPTION:
Multiple Run
END DESCRIPTION:

--- Stream0148_DS.f01 (steady flow) ---

Flow Title=Multiple
Number of Profiles=7
Profile Names=10-year,25-year,50-year,1pct_min,100-year,1pct_plu,500-year
River Rch & RM= Stream0148_DS,Reach-1,5477
    1051    1817    2561    1755    3501    6985    6482
River Rch & RM= Stream0148_DS,Reach-1,5028
    1216    2118    3001    2064    4119    8218    7693
River Rch & RM= Stream0148_DS,Reach-1,3302
    1367    2380    3371    2317    4623    9224    8619
Boundary for River Rch & Prof#=Stream0148_DS,Reach-1,1
Up Type=0
Dn Type=3
Dn Slope=0.005
Boundary for River Rch & Prof#=Stream0148_DS,Reach-1,2
Up Type=0
Dn Type=3
Dn Slope=0.005
Boundary for River Rch & Prof#=Stream0148_DS,Reach-1,3
Up Type=0
Dn Type=3
Dn Slope=0.005
Boundary for River Rch & Prof#=Stream0148_DS,Reach-1,4
Up Type=0
Dn Type=3
Dn Slope=0.005
Boundary for River Rch & Prof#=Stream0148_DS,Reach-1,5
Up Type=0
Dn Type=3
Dn Slope=0.005
Boundary for River Rch & Prof#=Stream0148_DS,Reach-1,6
Up Type=0
Dn Type=3
Dn Slope=0.005
Boundary for River Rch & Prof#=Stream0148_DS,Reach-1,7
Up Type=0
Dn Type=3
Dn Slope=0.005

--- Stream0148_DS.g01 (geometry) ---

Geom Title=Existing Conditions

River Reach=Stream0148_DS,Reach-1
Reach XY= 30
      2039775.00     13926025.00      2039918.94     13926167.53
      2039973.27     13926171.69      2040098.52     13926102.01
      2040226.42     13925928.04      2040335.50     13925973.76
      2040519.56     13925972.83      2040822.58     13925730.54
      2040931.17     13925717.14      2041111.37     13925538.21
      2041218.24     13925384.12      2041428.30     13925466.92
      2041630.57     13925377.47      2041723.50     13925371.38
      2041822.58     13925280.54      2041923.41     13925271.17
      2042276.55     13925078.75      2042465.34     13925073.62
      2042538.92     13925025.68      2042904.97     13925024.93
      2042985.50     13924976.22      2043214.50     13924976.22
      2043577.30     13925130.83      2043726.50     13925271.39
      2043819.02     13925277.36      2043890.22     13925324.48
      2044165.34     13925326.38      2044230.53     13925372.62
      2044415.38     13925376.27      2044525.00     13925425.00

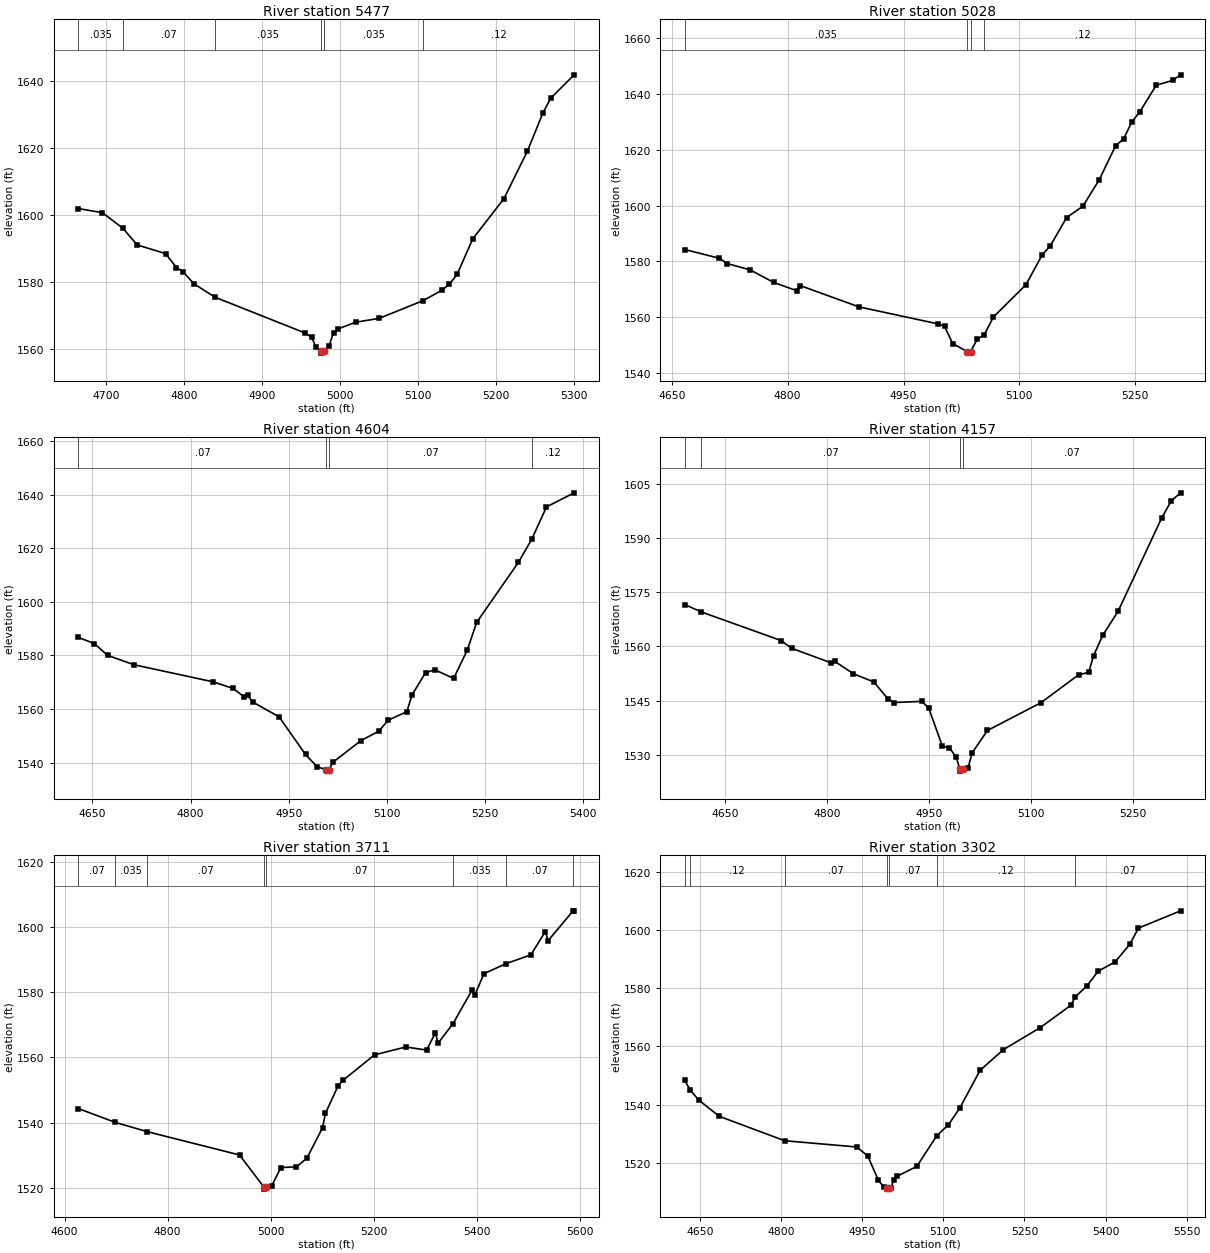
Type RM Length L Ch R = 1,5477,449,449,449
BEGIN DESCRIPTION:
Stream0148_DS 12.0
END DESCRIPTION:
XS GIS Cut Line= 3
      2039674.98     13926375.04      2039825.00     13926075.00
      2039825.00     13925774.95
#Sta/Elev= 30
  4664.6 1602.03  4695.4 1600.81  4721.6 1596.18  4740.1 1591.17  4776.4 1588.59
  4790.4 1584.43  4798.8 1583.19  4812.8 1579.56  4840.1 1575.54  4955.3 1564.89
  4963.7 1563.65  4969.3 1560.57  4975.7 1559.38  4975.9 1558.88  4979.7 1559.38
  4986.1 1561.13  4991.7 1565.03  4997.3 1566.09  5020.1 1568.11  5050.1 1569.25
  5106.7 1574.57  5130.1 1577.60  5140.1 1579.42  5150.1 1582.41  5170.1 1592.98
  5210.1 1605.00  5240.1 1619.15  5260.1 1630.60  5270.1 1634.99  5300.1 1641.96
#Mann=6,-1,0
  4664.6   0.035       0  4721.6    0.07       0  4840.1   0.035       0
  4975.7   0.035       0  4979.7   0.035       0  5106.7    0.12       0
Bank Sta=4975.7,4979.7
Exp/Cntr=0.3,0.1

Type RM Length L Ch R = 1,5028,424,424,424
BEGIN DESCRIPTION:
Stream0148_DS 11.0
END DESCRIPTION:
XS GIS Cut Line= 3
      2040147.28     13926349.61      2040175.00     13926025.00
      2040075.00     13925725.01
#Sta/Elev= 30
  4666.8 1584.27  4711.6 1581.14  4721.6 1579.27  4751.7 1576.96  4781.8 1572.52
  4811.6 1569.57  4816.6 1571.34  4892.2 1563.78  4995.2 1557.66  5003.1 1556.79
  5013.7 1550.66  5032.8 1547.74  5033.0 1547.24  5036.8 1547.74  5045.3 1552.14
  5054.5 1553.76  5066.4 1560.16  5108.5 1571.66  5129.6 1582.39  5140.2 1585.66
  5161.2 1595.71  5182.3 1599.75  5203.4 1609.20  5224.5 1621.30  5235.0 1623.83
  5245.6 1629.89  5256.1 1633.54  5277.2 1642.99  5298.3 1644.72  5308.8 1646.71
#Mann=4,-1,0
  4666.8   0.035       0  5032.8   0.035       0  5036.8   0.035       0
  5054.5    0.12       0
Bank Sta=5032.8,5036.8
Exp/Cntr=0.3,0.1

Type RM Length L Ch R = 1,4604,447,447,447
BEGIN DESCRIPTION:
Stream0148_DS 10.0
END DESCRIPTION:
XS GIS Cut Line= 3
      2040574.37     13926339.18      2040525.00     13925975.00
      2040275.02     13925675.02
#Sta/Elev= 30
  4628.4 1586.73  4652.8 1584.45  4673.0 1580.04  4713.4 1576.53  4834.4 1570.14
  4864.7 1567.70  4882.1 1564.52  4887.1 1565.08  4895.0 1562.60  4935.4 1557.05
  4975.7 1543.01  4993.4 1538.44  5007.6 1537.30  5007.8 1536.80  5011.6 1537.30
  5017.4 1540.06  5060.3 1548.19  5087.7 1551.69  5102.0 1555.80  5130.6 1559.01
  5138.5 1565.24  5159.3 1573.62  5173.6 1574.61  5202.2 1571.41  5223.1 1582.05
  5237.4 1592.37  5301.2 1614.76  5321.9 1623.55  5344.1 1635.47  5386.4 1640.72
#Mann=4,-1,0
  4628.4    0.07       0  5007.6    0.05       0  5011.6    0.07       0
  5321.9    0.12       0
Bank Sta=5007.6,5011.6
Exp/Cntr=0.3,0.1

Type RM Length L Ch R = 1,4157,446,446,446
BEGIN DESCRIPTION:
Stream0148_DS 9.0
END DESCRIPTION:
XS GIS Cut Line= 3
      2040928.53     13926130.78      2040875.00     13925725.00
      2040624.97     13925524.97
#Sta/Elev= 30
  4590.7 1571.57  4614.4 1569.57  4732.5 1561.61  4747.8 1559.49  4806.1 1555.45
  4811.1 1555.90  4838.6 1552.46  4868.9 1550.17  4889.7 1545.47  4899.1 1544.49
  4939.5 1544.81  4949.6 1542.93  4969.7 1532.41  4979.8 1532.01  4989.9 1529.41
  4995.5 1526.03  4995.7 1525.53  4999.5 1526.03  5007.2 1526.29  5013.6 1530.61
  5036.0 1536.77  5114.5 1544.42  5170.5 1552.21  5184.9 1552.80  5192.1 1557.42
  5205.7 1563.10  5228.1 1569.68  5292.1 1595.40  5306.5 1600.26  5320.2 1602.45
#Mann=4,-1,0
  4590.7    0.12       0  4614.4    0.07       0  4995.5    0.05       0
  4999.5    0.07       0
Bank Sta=4995.5,4999.5
Exp/Cntr=0.3,0.1

Type RM Length L Ch R = 1,3711,409,409,409
BEGIN DESCRIPTION:
Stream0148_DS 8.0
END DESCRIPTION:
XS GIS Cut Line= 3
      2041182.01     13925797.54      2041175.00     13925425.00
      2040591.69     13925342.63
#Sta/Elev= 30
  4626.7 1544.36  4698.3 1540.13  4760.6 1537.27  4939.3 1530.15  4987.3 1520.19
  4987.5 1519.69  4991.4 1520.19  5001.8 1520.69  5019.5 1526.28  5049.8 1526.52
  5070.0 1529.17  5100.3 1538.45  5106.0 1542.91  5130.6 1551.33  5140.7 1553.09
  5201.3 1560.81  5261.9 1563.21  5302.3 1562.27  5319.3 1567.60  5324.3 1564.34
  5353.6 1570.40  5390.4 1580.66  5395.5 1579.02  5413.4 1585.66  5456.8 1588.76
  5504.3 1591.40  5532.6 1598.57  5537.7 1595.73  5586.4 1604.90  5588.4 1604.90
#Mann=8,-1,0
  4626.7    0.07       0  4698.3   0.035       0  4760.6    0.07       0
  4987.3    0.05       0  4991.4    0.07       0  5353.6   0.035       0
  5456.8    0.07       0  5586.4   0.035       0
Bank Sta=4987.3,4991.4
Exp/Cntr=0.3,0.1

Type RM Length L Ch R = 1,3302,450,450,450
BEGIN DESCRIPTION:
Stream0148_DS 7.0
END DESCRIPTION:
XS GIS Cut Line= 3
      2041567.42     13925800.97      2041525.00     13925425.00
      2041251.47     13924960.74
#Sta/Elev= 30
  4621.7 1548.29  4631.6 1545.03  4647.8 1541.50  4685.5 1535.97  4806.2 1527.60
  4939.7 1525.44  4960.1 1522.35  4979.9 1513.98  4990.0 1511.61  4995.5 1511.46
  4995.7 1510.96  4999.6 1511.46  5003.0 1511.46  5007.9 1513.94  5013.7 1515.31
  5050.8 1518.74  5087.7 1529.27  5109.4 1533.07  5130.8 1538.95  5167.9 1551.77
  5210.8 1558.86  5278.6 1566.39  5336.6 1574.22  5343.2 1576.90  5365.1 1580.71
  5386.5 1585.85  5417.8 1589.05  5445.1 1595.12  5460.8 1600.64  5538.9 1606.58
#Mann=7,-1,0
  4621.7    0.07       0  4631.6    0.12       0  4806.2    0.07       0
  4995.5    0.05       0  4999.6    0.07       0  5087.7    0.12       0
  5343.2    0.07       0
Bank Sta=4995.5,4999.6
Exp/Cntr=0.3,0.1

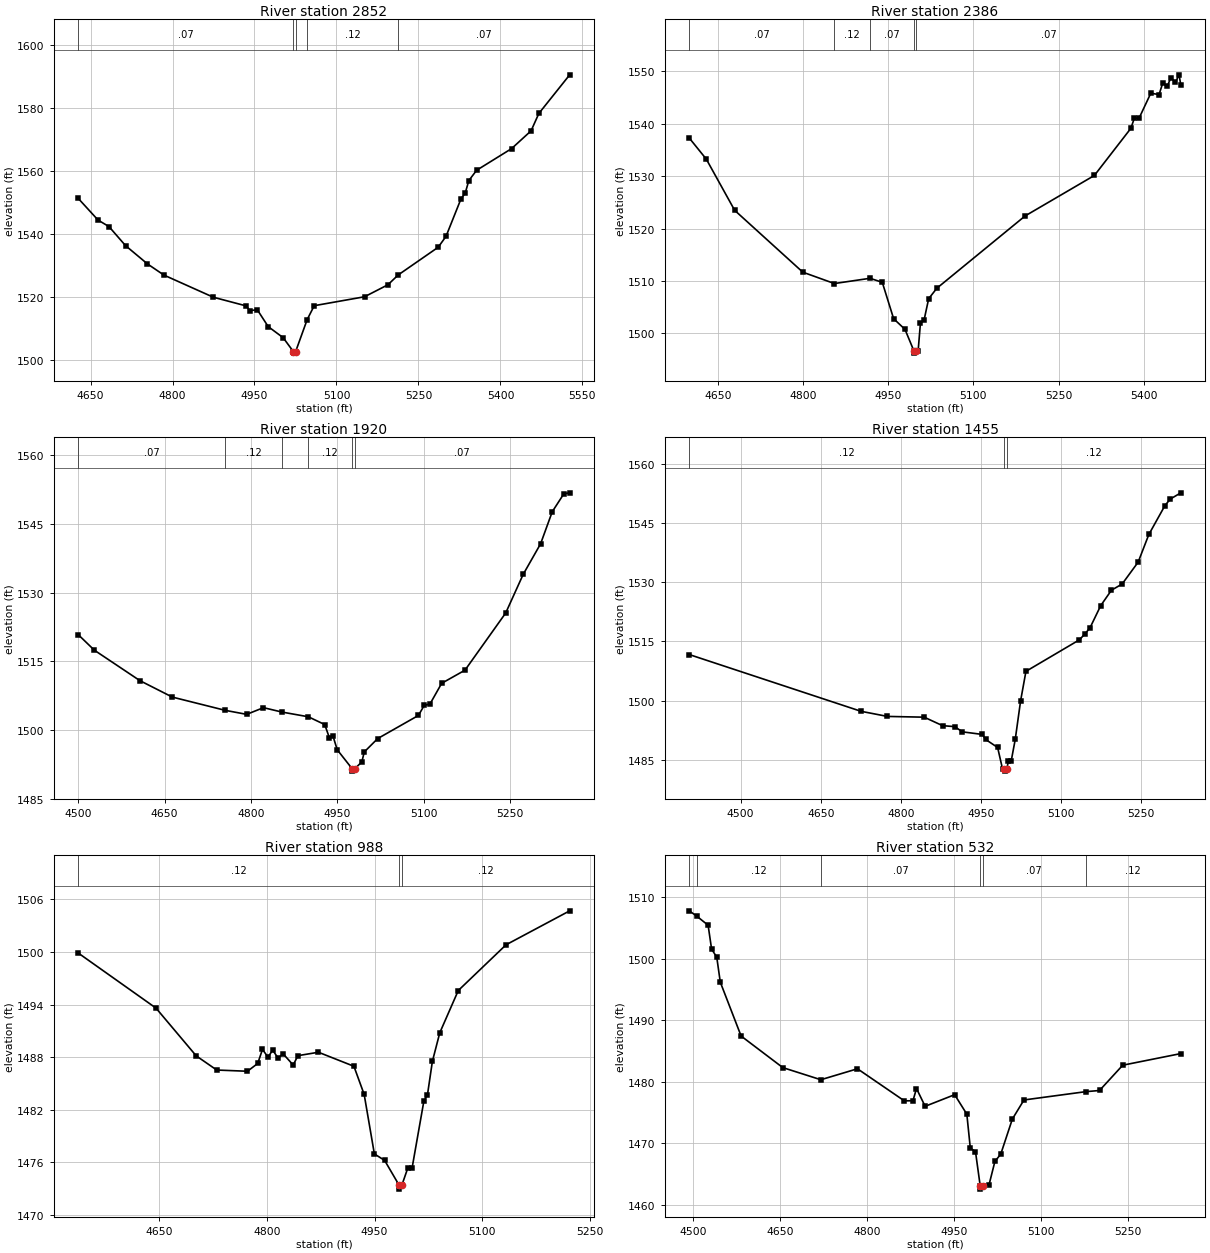
Type RM Length L Ch R = 1,2852,466,466,466
BEGIN DESCRIPTION:
Stream0148_DS 6.0
END DESCRIPTION:
XS GIS Cut Line= 3
      2041959.79     13925641.29      2041925.00     13925275.00
      2041525.03     13924925.03
#Sta/Elev= 30
  4627.3 1551.25  4663.8 1544.34  4683.8 1542.27  4714.0 1536.25  4754.2 1530.44
  4784.3 1526.90  4874.7 1519.88  4935.0 1517.12  4941.2 1515.64  4955.1 1515.91
  4975.1 1510.57  5002.4 1507.06  5021.1 1502.66  5021.4 1502.16  5025.3 1502.66
  5046.4 1512.80  5059.3 1517.20  5151.4 1520.03  5194.1 1523.83  5212.9 1526.94
  5286.1 1535.73  5300.4 1539.17  5327.9 1551.11  5335.5 1552.85  5342.1 1556.85
  5356.4 1560.13  5420.4 1567.00  5456.0 1572.63  5470.3 1578.15  5526.7 1590.39
#Mann=5,-1,0
  4627.3    0.07       0  5021.1    0.05       0  5025.3    0.07       0
  5046.4    0.12       0  5212.9    0.07       0
Bank Sta=5021.1,5025.3
Exp/Cntr=0.3,0.1

Type RM Length L Ch R = 1,2386,466,466,466
BEGIN DESCRIPTION:
Stream0148_DS 5.0
END DESCRIPTION:
XS GIS Cut Line= 3
      2042325.00     13925474.99      2042325.00     13925075.00
      2042037.24     13924708.58
#Sta/Elev= 30
  4599.5 1537.29  4629.5 1533.26  4679.5 1523.48  4799.5 1511.67  4855.1 1509.50
  4917.9 1510.50  4939.5 1509.73  4959.5 1502.78  4979.5 1500.75  4994.9 1496.71
  4995.1 1496.21  4999.1 1496.71  5002.7 1496.71  5006.7 1501.94  5013.1 1502.52
  5021.2 1506.60  5035.6 1508.60  5191.1 1522.41  5313.1 1530.14  5377.3 1539.13
  5383.6 1541.10  5391.7 1541.05  5412.5 1545.85  5427.0 1545.59  5433.4 1547.73
  5441.5 1547.15  5447.8 1548.83  5455.9 1547.94  5462.3 1549.36  5465.4 1547.37
#Mann=5,-1,0
  4599.5    0.07       0  4855.1    0.12       0  4917.9    0.07       0
  4994.9    0.05       0  4999.1    0.07       0
Bank Sta=4994.9,4999.1
Exp/Cntr=0.3,0.1

Type RM Length L Ch R = 1,1920,465,465,465
BEGIN DESCRIPTION:
Stream0148_DS 4.0
END DESCRIPTION:
XS GIS Cut Line= 3
      2042474.98     13925425.02      2042775.00     13925025.00
      2042825.00     13924674.98
#Sta/Elev= 30
  4500.0 1520.83  4528.2 1517.41  4607.3 1510.76  4663.6 1507.17  4755.6 1504.27
  4792.7 1503.40  4821.9 1504.86  4853.9 1503.90  4899.8 1502.87  4928.2 1501.17
  4936.5 1498.22  4942.7 1498.60  4950.0 1495.65  4976.0 1491.50  4976.3 1491.00
  4980.3 1491.50  4992.7 1493.03  4996.9 1495.19  5020.2 1498.11  5090.9 1503.16
  5101.0 1505.35  5111.1 1505.68  5131.3 1510.18  5171.8 1513.05  5242.5 1525.54
  5272.8 1533.96  5303.1 1540.66  5323.3 1547.65  5343.5 1551.58  5353.6 1551.78
#Mann=6,-1,0
  4500.0    0.07       0  4755.6    0.12       0  4853.9    0.07       0
  4899.8    0.12       0  4976.0    0.05       0  4980.3    0.07       0
Bank Sta=4976,4980.3
Exp/Cntr=0.3,0.1

Type RM Length L Ch R = 1,1455,467,467,467
BEGIN DESCRIPTION:
Stream0148_DS 3.0
END DESCRIPTION:
XS GIS Cut Line= 3
      2042932.01     13925498.88      2043225.00     13924975.00
      2043213.26     13924655.16
#Sta/Elev= 30
  4403.9 1511.66  4725.5 1497.26  4775.0 1495.96  4843.7 1495.77  4878.1 1493.62
  4901.0 1493.37  4915.1 1492.05  4952.8 1491.39  4958.5 1490.14  4981.2 1488.08
  4990.4 1482.62  4994.0 1482.58  4994.3 1482.08  4998.4 1482.58  5001.3 1484.64
  5006.6 1484.64  5014.2 1490.14  5024.2 1499.91  5034.2 1507.40  5134.2 1515.39
  5144.8 1516.92  5154.2 1518.46  5174.3 1524.10  5194.3 1527.99  5214.3 1529.56
  5244.3 1535.12  5264.3 1542.13  5294.3 1549.43  5304.3 1551.11  5324.2 1552.70
#Mann=3,-1,0
  4403.9    0.12       0  4994.0    0.05       0  4998.4    0.12       0
Bank Sta=4994,4998.4
Exp/Cntr=0.3,0.1

Type RM Length L Ch R = 1,988,456,456,456
BEGIN DESCRIPTION:
Stream0148_DS 2.0
END DESCRIPTION:
XS GIS Cut Line= 3
      2043272.32     13925474.55      2043625.00     13925175.00
      2043674.75     13924958.57
#Sta/Elev= 30
  4537.0 1499.89  4645.5 1493.59  4701.5 1488.14  4730.1 1486.52  4772.9 1486.38
  4787.2 1487.27  4793.8 1488.87  4801.5 1488.00  4808.1 1488.79  4815.8 1487.85
  4822.3 1488.40  4836.6 1487.09  4843.2 1488.16  4871.8 1488.55  4921.2 1486.95
  4935.5 1483.73  4949.7 1476.94  4964.0 1476.20  4983.8 1473.42  4984.1 1472.92
  4988.2 1473.42  4996.4 1475.36  5002.3 1475.36  5018.6 1482.95  5023.7 1483.71
  5030.5 1487.50  5040.8 1490.77  5066.6 1495.60  5133.1 1500.82  5221.8 1504.70
#Mann=3,-1,0
  4537.0    0.12       0  4983.8    0.05       0  4988.2    0.12       0
Bank Sta=4983.8,4988.2
Exp/Cntr=0.3,0.1

Type RM Length L Ch R = 1,532,334,334,334
BEGIN DESCRIPTION:
Stream0148_DS 1.0
END DESCRIPTION:
XS GIS Cut Line= 3
      2043605.66     13925609.97      2044025.00     13925325.00
      2044004.92     13924985.00
#Sta/Elev= 30
  4493.0 1507.81  4506.0 1506.94  4525.5 1505.47  4531.5 1501.59  4540.4 1500.28
  4546.5 1496.22  4582.4 1487.46  4654.3 1482.33  4719.9 1480.36  4783.0 1482.14
  4863.8 1476.93  4878.7 1476.94  4884.8 1478.93  4899.7 1476.04  4950.6 1477.93
  4971.6 1474.76  4977.6 1469.24  4986.5 1468.69  4994.7 1463.08  4995.0 1462.58
  4999.2 1463.08  5010.0 1463.33  5020.0 1467.08  5030.1 1468.27  5050.1 1473.97
  5070.1 1477.07  5176.7 1478.42  5200.4 1478.61  5240.4 1482.72  5340.6 1484.61
#Mann=6,-1,0
  4493.0    0.07       0  4506.0    0.12       0  4719.9    0.07       0
  4994.7    0.05       0  4999.2    0.07       0  5176.7    0.12       0
Bank Sta=4994.7,4999.2
Exp/Cntr=0.3,0.1

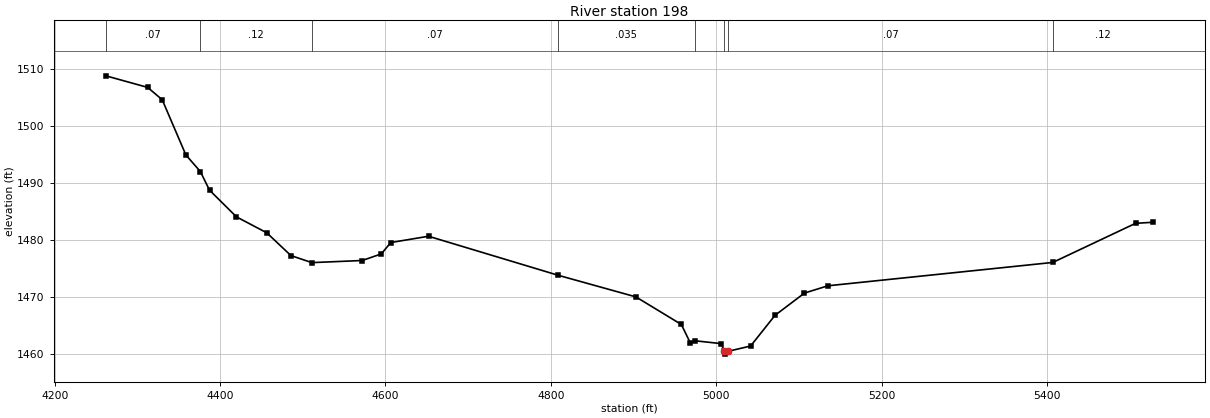
Type RM Length L Ch R = 1,198,0,0,0
BEGIN DESCRIPTION:
Stream0148_DS 0.0
END DESCRIPTION:
XS GIS Cut Line= 3
      2043671.20     13925679.59      2044343.46     13925374.85
      2044036.04     13924945.20
#Sta/Elev= 30
  4261.9 1508.77  4312.4 1506.74  4330.0 1504.58  4358.6 1494.91  4376.1 1492.00
  4387.2 1488.73  4419.8 1484.05  4456.4 1481.26  4485.7 1477.26  4511.0 1476.03
  4571.9 1476.40  4595.0 1477.56  4606.4 1479.55  4652.1 1480.65  4808.9 1473.81
  4902.9 1470.02  4957.8 1465.19  4968.8 1461.92  4973.9 1462.34  5006.0 1461.83
  5009.9 1460.49  5010.2 1459.99  5014.4 1460.49  5041.6 1461.41  5071.1 1466.79
  5106.7 1470.69  5135.1 1471.97  5407.0 1476.06  5507.2 1482.92  5528.3 1483.10
#Mann=8,-1,0
  4261.9    0.07       0  4376.1    0.12       0  4511.0    0.07       0
  4808.9   0.035       0  4973.9    0.07       0  5009.9    0.05       0
  5014.4    0.07       0  5407.0    0.12       0
Bank Sta=5009.9,5014.4
Exp/Cntr=0.3,0.1

Chan Stop Cuts=-1