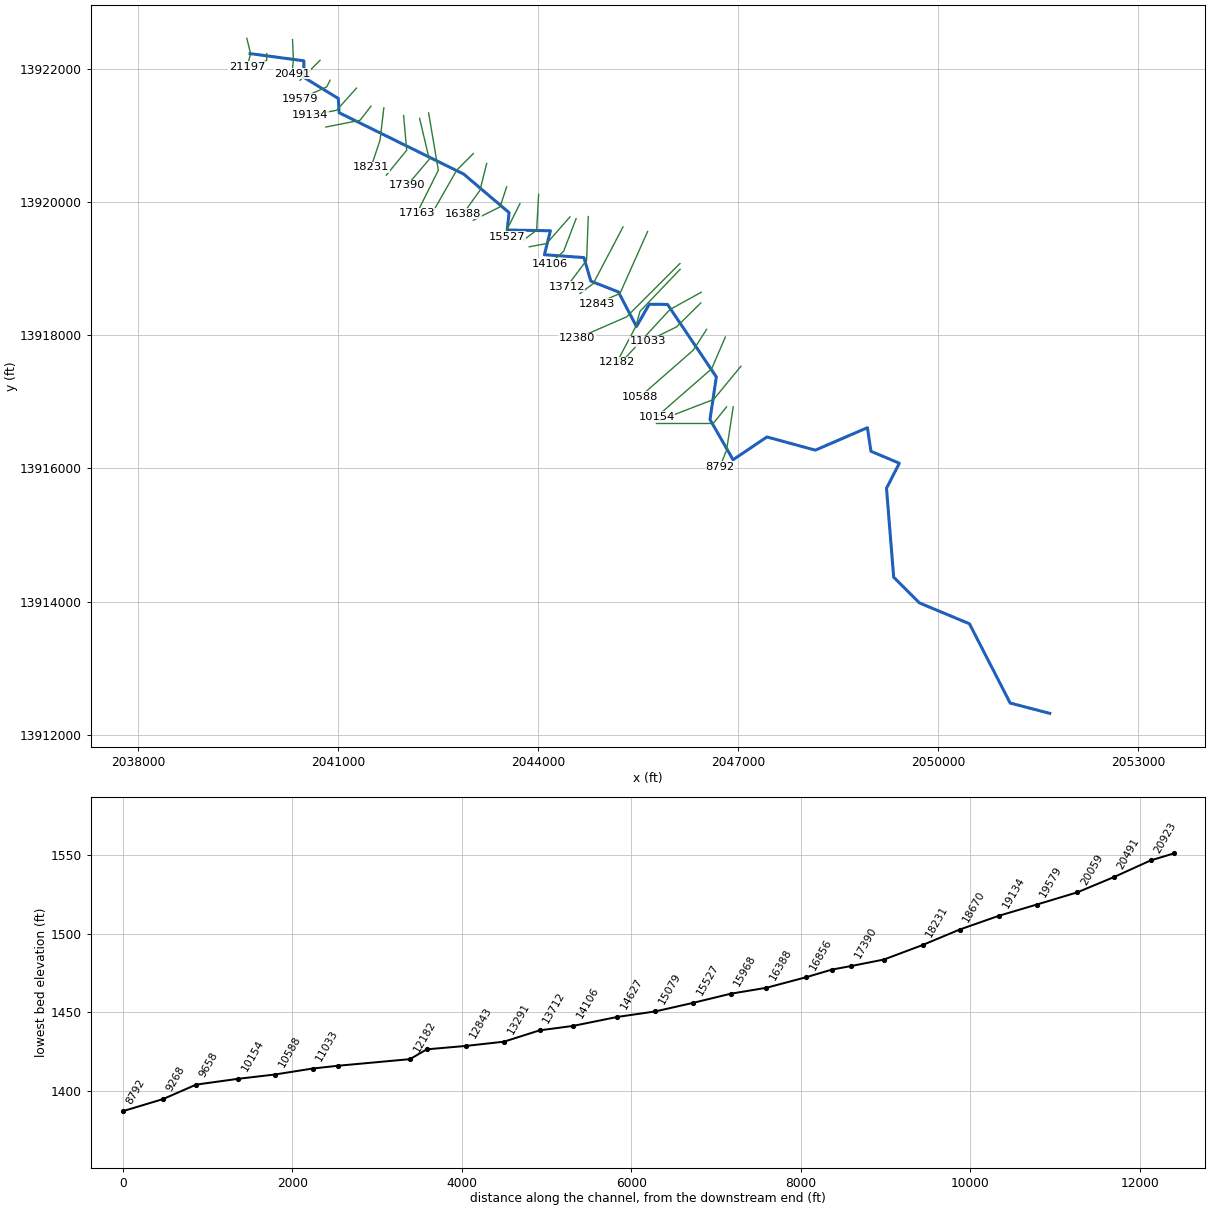
--- Stream0149_DS.prj (project) ---

Proj Title=Stream0149_DS Base Level Engineering
Current Plan=p01
Default Exp/Contr=0.3,0.1
English Units
Geom File=g01
Flow File=f01
Plan File=p01
Y Axis Title=Elevation
X Axis Title(PF)=Main Channel Distance
X Axis Title(XS)=Station
BEGIN DESCRIPTION:
Stream0149_DS
END DESCRIPTION:
DSS Export Rating Curves= 0
DSS Export Rating Curve Sorted= 0
DSS Export Volume Flow Curves= 0
DXF OffsetX= 0
DXF OffsetY= 0
DXF ScaleX= 1
DXF ScaleY= 10

--- Stream0149_DS.p01 (plan) ---

Plan Title=Multiple Run
Short Identifier=Multiple
Geom File=g01
Flow File=f01
Subcritical Flow
K Sum by GR= 0
Std Step Tol= 0.01
Critical Tol= 0.01
Num of Std Step Trials= 20
Max Error Tol= 0.3
Flow Tol Ratio= 0.001
Split Flow NTrial= 30
Split Flow Tol= 0.02
Split Flow Ratio= 0.02
Log Output Level= 0
Friction Slope Method= 1
Unsteady Friction Slope Method= 2
Unsteady Bridges Friction Slope Method= 1
Parabolic Critical Depth
Global Vel Dist=  1 , 1 , 1
Global Log Level= 0
CheckData=True
Encroach Param= -1, 0, 0, 0
BEGIN DESCRIPTION:
Multiple Run
END DESCRIPTION:

--- Stream0149_DS.f01 (steady flow) ---

Flow Title=Multiple
Program Version=4.10
Number of Profiles= 7
Profile Names=10-year,25-year,50-year,1pct_min,100-year,1pct_plu,500-year
River Rch & RM=Stream0149_DS,Reach-1         ,21197
     499     824    1127     753    1502    2997    2635
River Rch & RM=Stream0149_DS,Reach-1         ,20923
     674    1132    1565    1054    2103    4196    3756
River Rch & RM=Stream0149_DS,Reach-1         ,18231
    1484    2605    3711    2565    5118   10212    9652
River Rch & RM=Stream0149_DS,Reach-1         ,13291
    1959    3476    4988    3468    6920   13807   13208
River Rch & RM=Stream0149_DS,Reach-1         ,8792
    2388    4267    6147    4287    8554   17067   16433
River Rch & RM=Stream0149_DS,Reach-1         ,3580
    2639    4709    6779    4722    9422   18800   18052
Boundary for River Rch & Prof#=Stream0149_DS,Reach-1         , 1
Up Type= 0
Dn Type= 3
Dn Slope=0.005
Boundary for River Rch & Prof#=Stream0149_DS,Reach-1         , 2
Up Type= 0
Dn Type= 3
Dn Slope=0.005
Boundary for River Rch & Prof#=Stream0149_DS,Reach-1         , 3
Up Type= 0
Dn Type= 3
Dn Slope=0.005
Boundary for River Rch & Prof#=Stream0149_DS,Reach-1         , 4
Up Type= 0
Dn Type= 3
Dn Slope=0.005
Boundary for River Rch & Prof#=Stream0149_DS,Reach-1         , 5
Up Type= 0
Dn Type= 3
Dn Slope=0.005
Boundary for River Rch & Prof#=Stream0149_DS,Reach-1         , 6
Up Type= 0
Dn Type= 3
Dn Slope=0.005
Boundary for River Rch & Prof#=Stream0149_DS,Reach-1         , 7
Up Type= 0
Dn Type= 3
Dn Slope=0.005
DSS Import GetInterval= 0
DSS Import GetPeak= 0
DSS Import FillOption= 0

--- Stream0149_DS.g01 (geometry) ---

Geom Title=Existing Conditions
Program Version=4.10

River Reach=Stream0149_DS   ,Reach-1
Reach XY= 30
        2039675.       13922225.      2040481.57      13922117.3
      2040482.76     13921868.83      2040998.96     13921551.82
      2041011.19     13921338.22      2042881.06     13920416.86
      2043561.62     13919838.73      2043532.61     13919578.07
      2044181.86     13919567.19      2044091.39     13919207.35
      2044684.84     13919164.61      2044788.38     13918811.26
      2045201.88     13918648.83      2045472.71     13918130.06
      2045664.94     13918464.39      2045938.63     13918461.56
      2046671.45     13917373.53      2046576.36     13916734.65
      2046922.54     13916130.45      2047430.45     13916472.84
      2048156.72     13916275.19      2048938.74     13916611.81
      2048991.41      13916258.2      2049417.24     13916078.42
       2049224.9     13915702.31      2049332.81     13914368.81
      2049718.55     13913982.74      2050469.74     13913669.53
      2051080.47     13912480.26        2051675.       13912325.

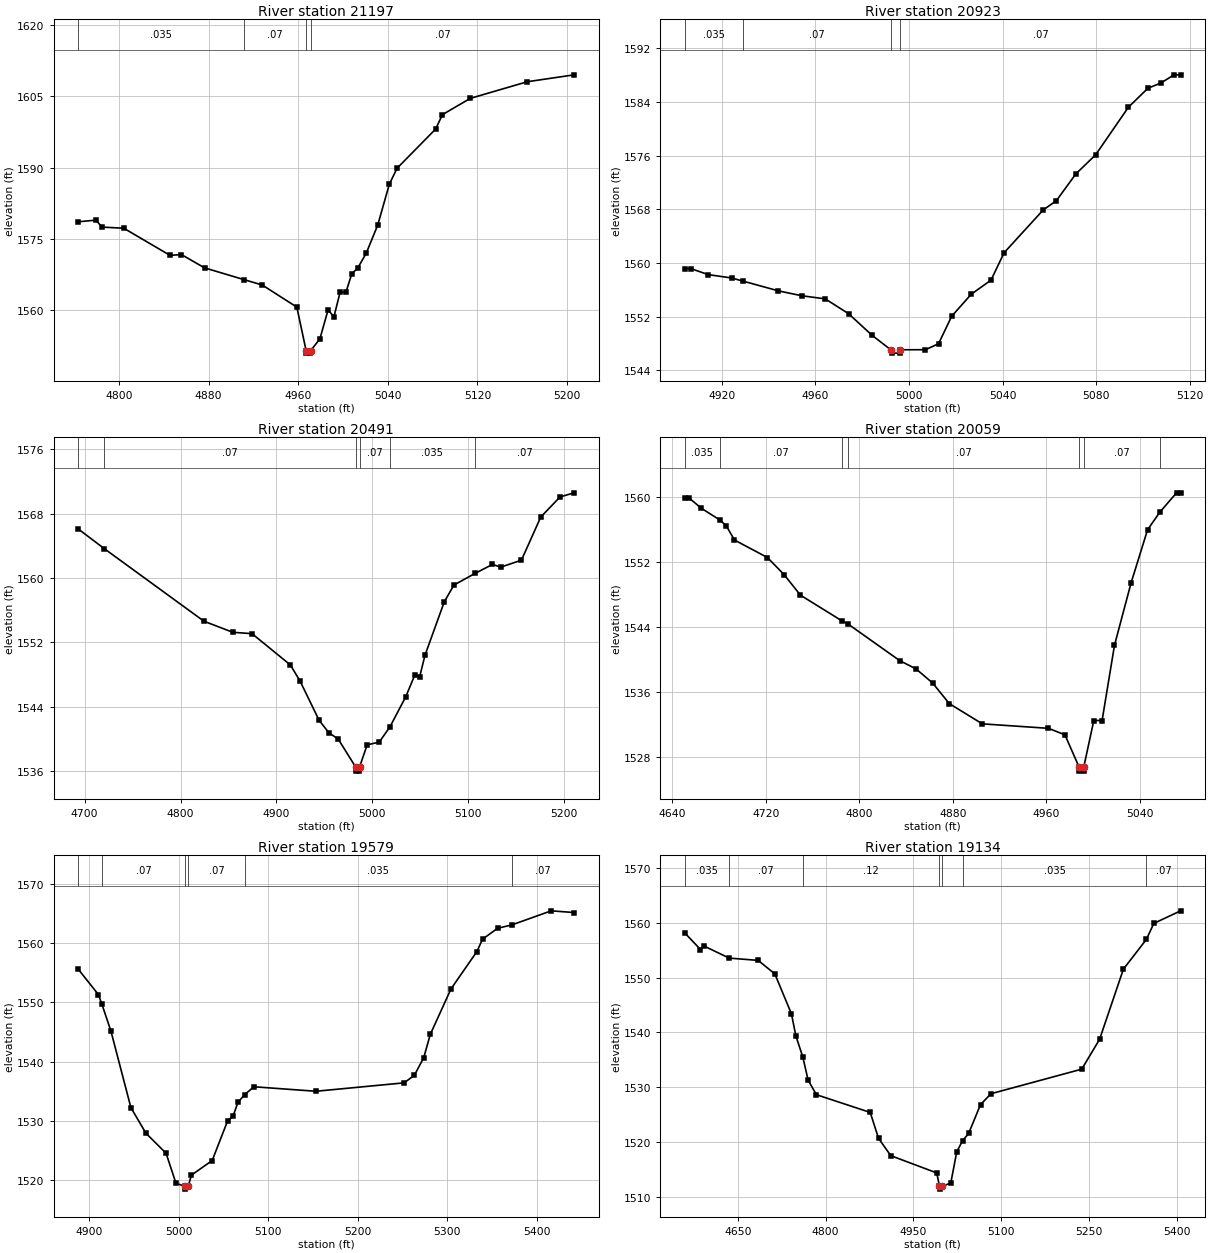
Type RM Length L Ch R = 1 ,21197   ,274,274,274
BEGIN DESCRIPTION:
Stream0149_DS 45.0
END DESCRIPTION:
XS GIS Cut Line= 3
      2039625.96     13922454.44      2039682.67     13922225.04
      2039630.52     13922025.34
#Sta/Elev= 30
  4763.7 1578.63  4779.5 1578.97  4784.7 1577.51  4804.3 1577.27  4845.5 1571.58
  4855.8 1571.73  4876.4 1568.95  4911.4 1566.49  4927.9 1565.35  4958.8  1560.7
  4967.1 1551.54  4967.4 1551.04  4970.9 1551.04  4971.1 1551.54  4979.4 1554.05
  4986.7 1560.14  4991.9 1558.66  4997.4 1563.82  5002.6 1563.82  5007.9 1567.73
    5013 1568.85  5020.7    1572    5031 1577.92  5041.4 1586.54  5048.3 1589.87
  5082.7  1598.1  5088.8 1601.13  5113.7 1604.55  5164.6 1608.04  5206.4 1609.49
#Mann= 4 ,-1 , 0
  4763.7    .035       0  4911.4     .07       0  4967.1     .05       0
  4971.1     .07       0
Bank Sta=4967.1,4971.1
XS Rating Curve= 0 ,0
Exp/Cntr=0.3,0.1

Type RM Length L Ch R = 1 ,20923   ,432,432,432
BEGIN DESCRIPTION:
Stream0149_DS 44.0
END DESCRIPTION:
XS GIS Cut Line= 3
        2039925.     13922225.02        2039925.       13922125.
      2039825.02     13922075.01
#Sta/Elev= 29
  4904.2 1559.18  4906.7 1559.18  4914.2 1558.27  4924.2 1557.77    4929 1557.31
  4944.2 1555.85  4954.2 1555.12  4964.2 1554.66  4974.2 1552.44  4984.2 1549.23
  4992.2 1547.08  4992.5 1546.58    4996 1546.58  4996.2 1547.08    5007 1547.09
  5012.6 1547.98  5018.2 1552.07  5026.6 1555.36    5035 1557.45  5040.6 1561.53
  5057.3  1567.9  5062.9 1569.27  5071.3 1573.29  5079.7 1576.11  5093.7  1583.2
    5102 1586.01  5107.6 1586.81  5113.2 1588.02    5116 1588.02
#Mann= 4 ,-1 , 0
  4904.2    .035       0    4929     .07       0  4992.2     .05       0
  4996.2     .07       0
Bank Sta=4992.2,4996.2
XS Rating Curve= 0 ,0
Exp/Cntr=0.3,0.1

Type RM Length L Ch R = 1 ,20491   ,432,432,432
BEGIN DESCRIPTION:
Stream0149_DS 43.0
END DESCRIPTION:
XS GIS Cut Line= 3
      2040312.21     13922436.02        2040325.       13922125.
      2040301.79     13921920.39
#Sta/Elev= 30
  4693.4 1566.08  4720.5 1563.64  4824.5 1554.62  4854.6 1553.25  4874.6 1553.08
  4914.6 1549.19  4924.6 1547.21  4944.6 1542.31  4954.6 1540.79  4964.6 1539.96
  4982.7  1536.5  4982.9    1536  4986.4    1536  4986.7  1536.5  4994.7 1539.27
  5007.2  1539.6  5018.3 1541.47  5034.9 1545.23  5044.5 1547.98  5049.5 1547.75
    5055  1550.4  5075.1 1557.03  5085.2 1559.12  5107.1 1560.56  5125.4 1561.68
  5134.1 1561.35  5155.6 1562.21  5175.8 1567.58  5195.9 1570.07  5210.6 1570.58
#Mann= 6 ,-1 , 0
  4693.4    .035       0  4720.5     .07       0  4982.7     .05       0
  4986.7     .07       0  5018.3    .035       0  5107.1     .07       0
Bank Sta=4982.7,4986.7
XS Rating Curve= 0 ,0
Exp/Cntr=0.3,0.1

Type RM Length L Ch R = 1 ,20059   ,480,480,480
BEGIN DESCRIPTION:
Stream0149_DS 42.0
END DESCRIPTION:
XS GIS Cut Line= 3
      2040725.02     13922125.02        2040475.       13921875.
      2040424.99     13921824.99
#Sta/Elev= 30
  4650.6 1559.84  4654.2 1559.84  4664.8 1558.57  4680.4 1557.15    4686 1556.44
  4693.1 1554.67  4721.3 1552.52  4735.5 1550.43  4749.6 1547.89  4784.9 1544.75
    4790 1544.38  4834.5 1539.85  4848.6 1538.82  4862.8 1537.08  4876.9 1534.57
  4905.2 1532.08  4961.8 1531.53  4975.9 1530.73    4988 1526.77  4988.3 1526.27
  4991.8 1526.27    4992 1526.77  5000.6 1532.49  5007.7 1532.49  5018.3 1541.73
  5032.5  1549.4  5046.6 1555.93  5057.1 1558.09  5071.4 1560.47  5074.9 1560.47
#Mann= 7 ,-1 , 0
  4650.6    .035       0  4680.4     .07       0  4784.9    .035       0
    4790     .07       0    4988     .05       0    4992     .07       0
  5057.1    .035       0
Bank Sta=4988,4992
XS Rating Curve= 0 ,0
Exp/Cntr=0.3,0.1

Type RM Length L Ch R = 1 ,19579   ,445,445,445
BEGIN DESCRIPTION:
Stream0149_DS 41.0
END DESCRIPTION:
XS GIS Cut Line= 3
      2040875.02     13921825.03        2040825.       13921725.
      2040421.61     13921545.42
#Sta/Elev= 30
  4888.2 1555.57  4910.6  1551.3  4914.6 1549.63  4924.6 1545.13  4946.9  1532.2
  4963.7 1527.89  4986.1 1524.52  4997.2 1519.44  5006.9 1518.96  5007.2 1518.46
  5010.9 1518.96  5014.4 1520.82  5037.6 1523.29  5054.8 1529.98  5060.9 1530.78
  5066.4 1533.13  5073.7 1534.38  5084.1 1535.74  5153.3 1534.98  5251.8  1536.4
  5263.2 1537.67  5273.7 1540.64    5281 1544.57  5304.2 1552.28  5332.9 1558.53
  5339.4 1560.66  5356.2  1562.5  5371.8 1563.05    5416 1565.44  5441.6 1565.15
#Mann= 6 ,-1 , 0
  4888.2    .035       0  4914.6     .07       0  5006.9     .05       0
  5010.9     .07       0  5073.7    .035       0  5371.8     .07       0
Bank Sta=5006.9,5010.9
XS Rating Curve= 0 ,0
Exp/Cntr=0.3,0.1

Type RM Length L Ch R = 1 ,19134   ,464,464,464
BEGIN DESCRIPTION:
Stream0149_DS 40.0
END DESCRIPTION:
XS GIS Cut Line= 3
      2041270.55     13921706.88        2040975.       13921375.
      2040578.89     13921300.82
#Sta/Elev= 30
  4559.4 1558.18  4586.2 1555.15  4592.8 1555.76  4635.2 1553.58  4684.8 1553.16
  4713.3 1550.69  4741.7 1543.38  4749.2 1539.37  4761.1  1535.5  4770.1 1531.29
  4784.3 1528.61  4876.3 1525.37  4890.5 1520.64  4911.4 1517.47    4990 1514.31
  4994.7 1511.85  4994.9 1511.35  4998.7 1511.85    5014 1512.47  5024.2 1518.18
  5034.2 1520.22  5044.5 1521.52  5064.8  1526.8  5082.7 1528.79  5237.8 1533.28
  5268.3 1538.73    5309 1551.56  5348.3    1557    5361 1559.92  5406.8 1562.22
#Mann= 7 ,-1 , 0
  4559.4    .035       0  4635.2     .07       0  4761.1     .12       0
  4994.7     .05       0  4998.7     .12       0  5034.2    .035       0
  5348.3     .07       0
Bank Sta=4994.7,4998.7
XS Rating Curve= 0 ,0
Exp/Cntr=0.3,0.1

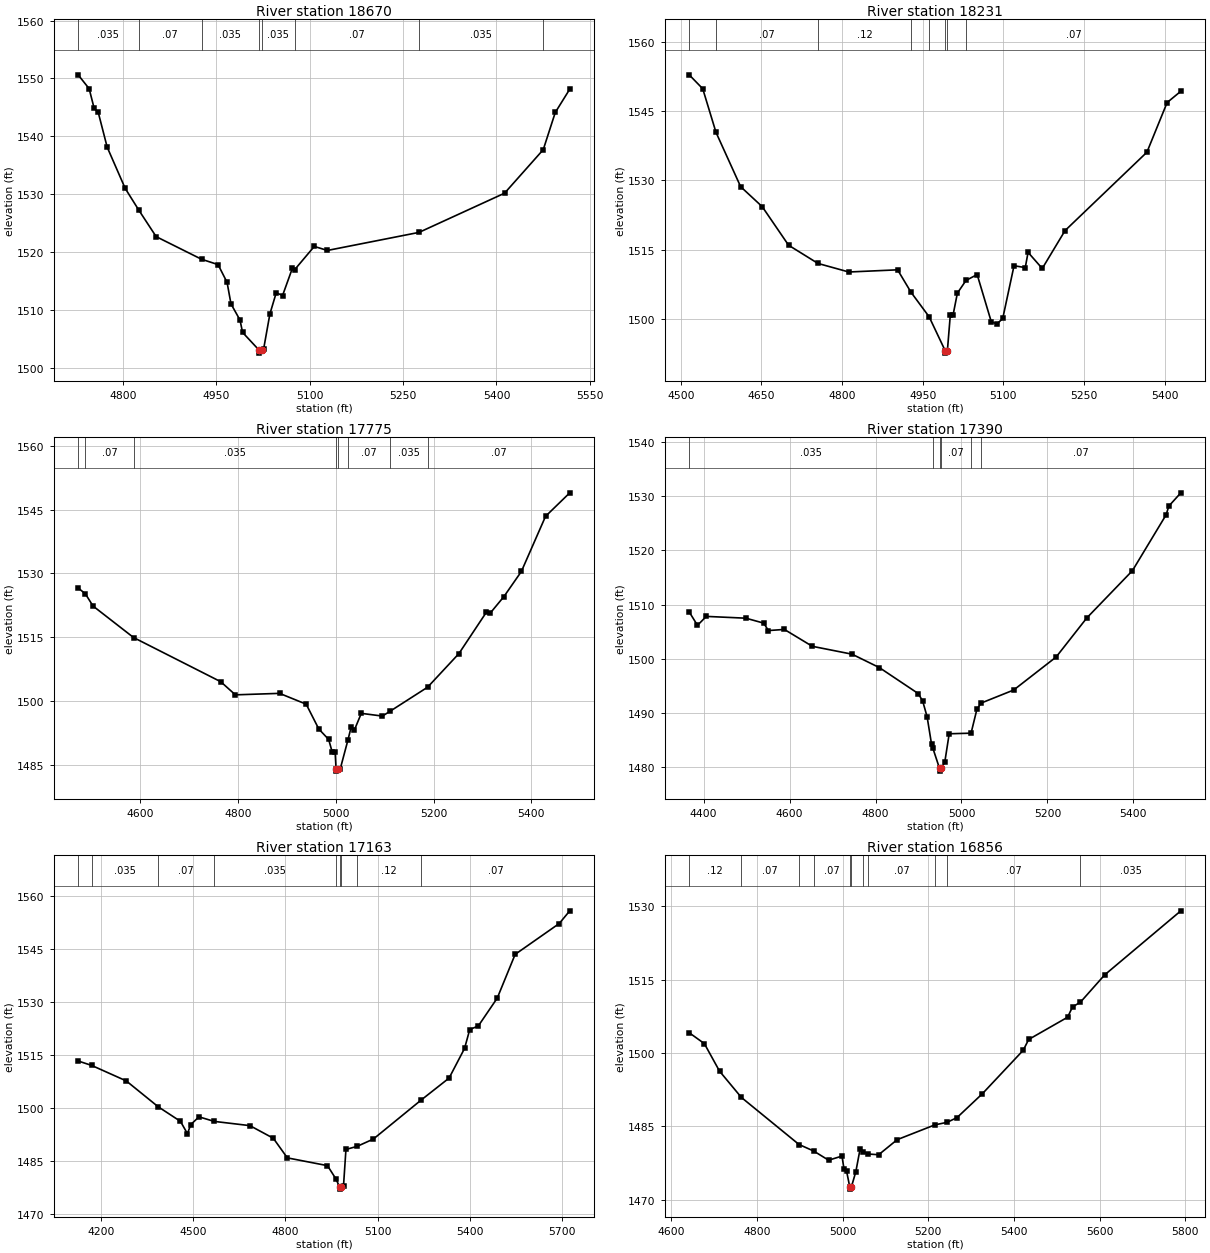
Type RM Length L Ch R = 1 ,18670   ,439,439,439
BEGIN DESCRIPTION:
Stream0149_DS 39.0
END DESCRIPTION:
XS GIS Cut Line= 3
      2041489.28     13921436.02        2041325.       13921225.
      2040812.17     13921123.53
#Sta/Elev= 30
  4727.6 1550.62  4745.3 1548.23  4753.4 1544.82  4759.8 1544.19  4774.3 1538.13
  4803.2 1531.02  4824.8 1527.31    4853 1522.68    4926 1518.77  4952.5 1517.85
    4967 1514.78  4973.3 1511.06  4987.8 1508.27  4991.9 1506.14  5018.6 1503.06
  5018.9 1502.56  5022.6 1503.06  5025.7 1503.24  5035.8 1509.31    5046 1512.99
  5056.2 1512.51  5071.9  1517.2  5075.7 1516.98  5107.2 1520.99  5128.2 1520.29
  5275.5 1523.41    5413 1530.18  5475.2  1537.7  5494.5 1544.12  5517.8 1548.15
#Mann= 8 ,-1 , 0
  4727.6    .035       0  4824.8     .07       0    4926    .035       0
  5018.6    .035       0  5022.6    .035       0  5075.7     .07       0
  5275.5    .035       0  5475.2     .07       0
Bank Sta=5018.6,5022.6
XS Rating Curve= 0 ,0
Exp/Cntr=0.3,0.1

Type RM Length L Ch R = 1 ,18231   ,456,456,456
BEGIN DESCRIPTION:
Stream0149_DS 38.0
END DESCRIPTION:
XS GIS Cut Line= 3
      2041682.01     13921410.01        2041625.       13920925.
      2041489.76     13920520.77
#Sta/Elev= 30
  4515.7 1552.84  4540.9 1549.83  4565.5 1540.42  4611.4 1528.66  4651.6 1524.33
  4700.6    1516  4755.3 1512.06  4812.7 1510.21  4903.4 1510.68  4928.3 1505.84
  4962.1 1500.52    4992 1493.17  4992.2 1492.67    4996 1493.17  5001.5 1500.98
  5006.7 1500.98  5014.6 1505.64  5030.6 1508.38  5051.4 1509.66  5077.7 1499.44
  5088.4 1498.99    5099 1500.17    5120 1511.57  5140.9 1511.16  5146.1 1514.46
  5172.5 1510.97  5214.9 1519.16  5367.2 1536.11  5404.8 1546.85  5430.3 1549.29
#Mann= 8 ,-1 , 0
  4515.7    .035       0  4565.5     .07       0  4755.3     .12       0
  4928.3     .07       0  4962.1    .035       0    4992    .035       0
    4996    .035       0  5030.6     .07       0
Bank Sta=4992,4996
XS Rating Curve= 0 ,0
Exp/Cntr=0.3,0.1

Type RM Length L Ch R = 1 ,17775   ,385,385,385
BEGIN DESCRIPTION:
Stream0149_DS 37.0
END DESCRIPTION:
XS GIS Cut Line= 3
      2041978.88     13921295.41        2042025.       13920775.
      2041719.42     13920400.76
#Sta/Elev= 30
  4472.9  1526.6  4487.9 1525.18  4503.4 1522.33  4586.3 1514.91  4764.5 1504.51
  4794.6 1501.41  4884.9 1501.76  4939.4 1499.21  4965.2 1493.36  4985.3 1490.91
  4992.8 1487.86  4998.6 1487.86  5000.5 1483.94  5000.8 1483.44  5004.5 1483.94
    5009 1483.94  5024.9 1490.83  5031.3  1493.8  5037.7 1493.05  5052.1 1497.05
  5095.2 1496.41  5110.5 1497.51  5187.8 1503.22  5251.7 1511.12  5307.7 1520.83
  5315.6 1520.63  5343.9 1524.57  5379.5 1530.47    5429 1543.47  5478.5    1549
#Mann= 8 ,-1 , 0
  4472.9    .035       0  4487.9     .07       0  4586.3    .035       0
  5000.5    .035       0  5004.5    .035       0  5024.9     .07       0
  5110.5    .035       0  5187.8     .07       0
Bank Sta=5000.5,5004.5
XS Rating Curve= 0 ,0
Exp/Cntr=0.3,0.1

Type RM Length L Ch R = 1 ,17390   ,227,227,227
BEGIN DESCRIPTION:
Stream0149_DS 36.0
END DESCRIPTION:
XS GIS Cut Line= 3
      2042218.46     13921253.76       2042364.3     13920639.17
      2042031.59     13920249.28
#Sta/Elev= 30
  4366.4 1508.65  4385.7 1506.17  4406.2 1507.82  4498.3 1507.49  4539.8 1506.58
  4550.8 1505.21  4587.9 1505.42  4652.9 1502.31  4745.4 1500.86  4809.2 1498.38
  4899.6  1493.6  4909.8 1492.22  4920.1 1489.33  4930.4 1484.29  4933.7  1483.5
    4949 1479.82  4949.2 1479.32    4953 1479.82  4961.2 1480.96  4971.5  1486.2
  5022.4 1486.31  5035.9 1490.68  5045.6 1491.85  5121.6 1494.26  5220.4 1500.34
  5291.8 1507.54  5397.9 1516.24  5476.2 1526.51  5482.8 1528.15  5510.6 1530.58
#Mann= 6 ,-1 , 0
  4366.4    .035       0  4933.7     .07       0    4949     .05       0
    4953     .07       0  5022.4     .12       0  5045.6     .07       0
Bank Sta=4949,4953
XS Rating Curve= 0 ,0
Exp/Cntr=0.3,0.1

Type RM Length L Ch R = 1 ,17163   ,307,307,307
BEGIN DESCRIPTION:
Stream0149_DS 35.5
END DESCRIPTION:
XS GIS Cut Line= 3
      2042354.08     13921335.42      2042499.88     13920474.48
      2042176.24     13919826.17
#Sta/Elev= 30
  4126.8 1513.36  4170.5 1512.11  4283.2 1507.72  4386.9  1500.4  4459.3 1496.27
  4482.2 1492.75  4492.4 1495.31  4519.6 1497.54  4569.1 1496.25  4685.1 1495.05
  4761.1 1491.48  4806.8 1485.92  4937.2 1483.72  4964.4 1479.99  4977.2 1477.57
  4977.4 1477.07  4981.2 1477.57  4989.3    1478  4997.2 1488.31  5033.5 1489.18
  5086.3 1491.25  5242.2 1502.34  5332.4 1508.52  5382.7 1516.92  5399.5 1522.26
  5427.4 1523.28  5488.9 1531.16  5547.1 1543.55  5690.3 1552.28  5724.6 1555.88
#Mann= 9 ,-1 , 0
  4126.8     .07       0  4170.5    .035       0  4386.9     .07       0
  4569.1    .035       0  4964.4     .07       0  4977.2     .05       0
  4981.2     .07       0  5033.5     .12       0  5242.2     .07       0
Bank Sta=4977.2,4981.2
XS Rating Curve= 0 ,0
Exp/Cntr=0.3,0.1

Type RM Length L Ch R = 1 ,16856   ,468,468,468
BEGIN DESCRIPTION:
Stream0149_DS 35.0
END DESCRIPTION:
XS GIS Cut Line= 3
      2043025.03     13920725.03        2042775.       13920475.
      2042381.88     13919785.49
#Sta/Elev= 30
  4642.2 1504.16  4677.6 1501.93    4713  1496.3    4764 1490.92  4898.5 1481.29
  4932.6 1479.96  4967.5 1478.08  4998.7 1478.92  5003.7 1476.18  5009.5 1475.83
  5016.8 1472.66    5017 1472.16  5020.9 1472.66  5031.1 1475.74  5041.2 1480.46
  5048.7 1479.84  5060.3 1479.34  5084.4  1479.2  5127.6 1482.28  5215.3  1485.3
  5244.2 1485.83  5267.3  1486.8  5326.4 1491.68  5421.7 1500.57  5434.4 1502.78
  5525.2 1507.33  5536.8 1509.45  5555.1  1510.4  5611.6 1515.98  5789.5  1529.1
#Mann= 11 ,-1 , 0
  4642.2     .12       0    4764     .07       0  4898.5     .12       0
  4932.6     .07       0  5016.8     .05       0  5020.9     .07       0
  5048.7    .035       0  5060.3     .07       0  5215.3     .12       0
  5244.2     .07       0  5555.1    .035       0
Bank Sta=5016.8,5020.9
XS Rating Curve= 0 ,0
Exp/Cntr=0.3,0.1

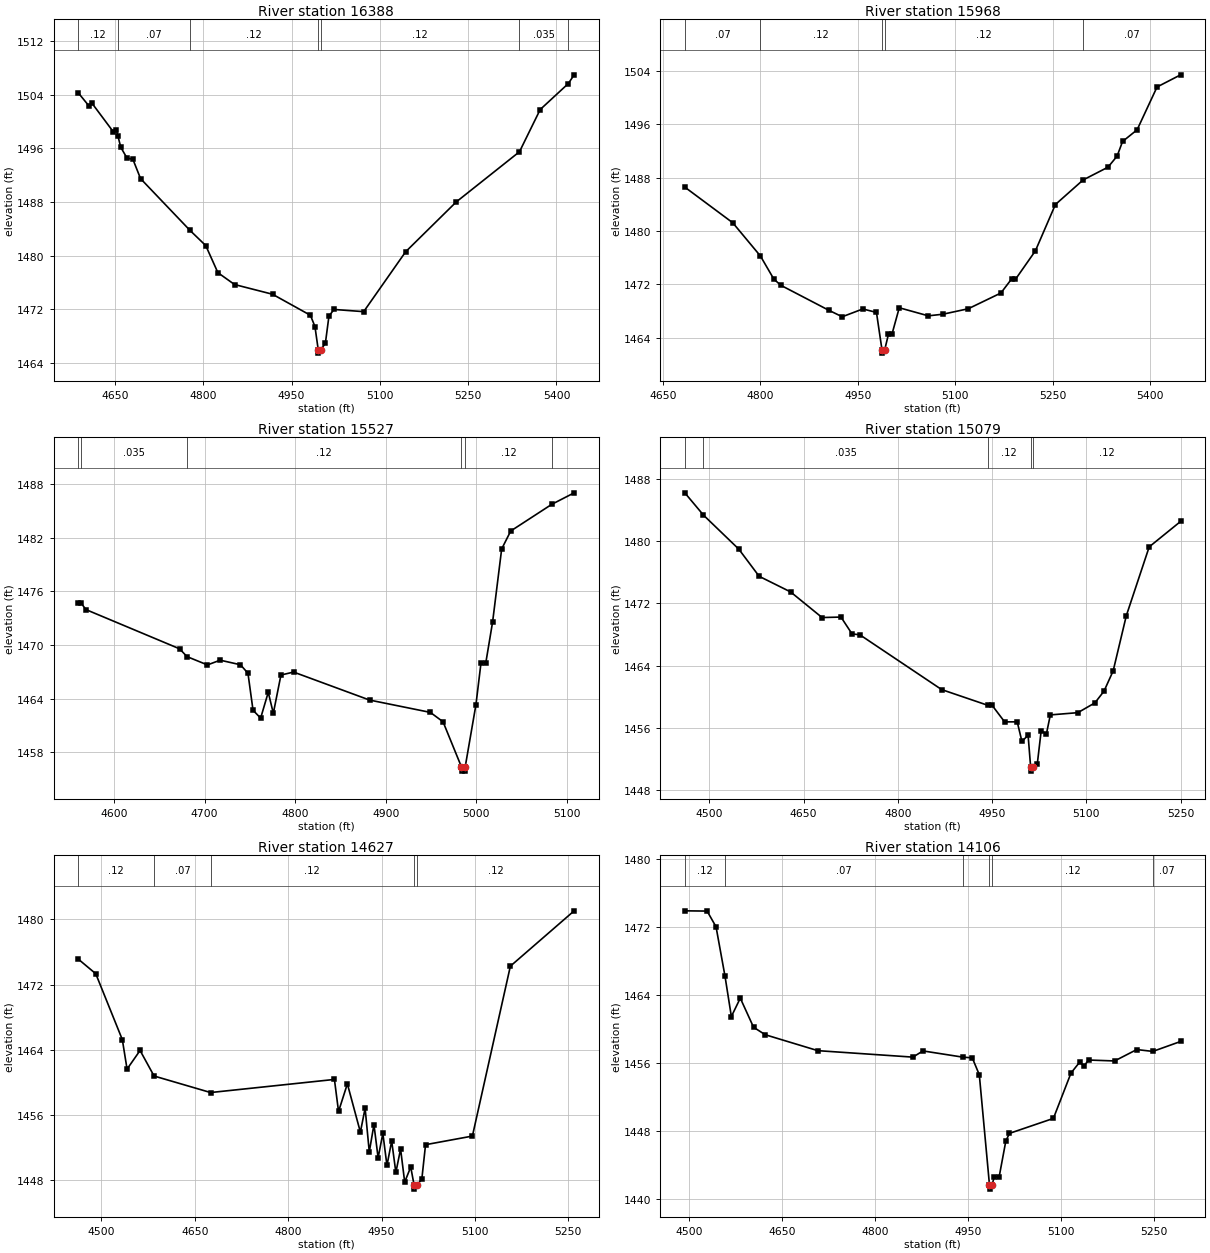
Type RM Length L Ch R = 1 ,16388   ,420,420,420
BEGIN DESCRIPTION:
Stream0149_DS 34.0
END DESCRIPTION:
XS GIS Cut Line= 3
        2043225.     13920575.01        2043125.       13920175.
      2042875.02     13919825.03
#Sta/Elev= 30
  4587.7 1504.29  4605.7 1502.35  4610.9 1502.75    4647  1498.5  4652.1 1498.82
    4655 1497.83  4659.9 1496.16  4670.2 1494.59  4680.5 1494.36  4693.4  1491.5
  4777.3 1483.78  4804.2  1481.5  4824.8 1477.46  4853.1 1475.69  4917.6 1474.24
    4982  1471.1  4989.7 1469.42  4995.3 1465.95  4995.6 1465.45  4999.5 1465.95
  5007.4 1466.91  5013.5 1470.98  5022.1 1471.97  5072.5 1471.64  5143.8 1480.58
  5229.8 1488.02  5337.2 1495.51  5372.4 1501.81  5420.1 1505.68  5430.1 1506.99
#Mann= 7 ,-1 , 0
  4587.7     .12       0    4655     .07       0  4777.3     .12       0
  4995.3     .05       0  4999.5     .12       0  5337.2    .035       0
  5420.1     .07       0
Bank Sta=4995.3,4999.5
XS Rating Curve= 0 ,0
Exp/Cntr=0.3,0.1

Type RM Length L Ch R = 1 ,15968   ,441,441,441
BEGIN DESCRIPTION:
Stream0149_DS 33.0
END DESCRIPTION:
XS GIS Cut Line= 3
        2043525.       13920225.        2043425.       13919925.
      2043025.03     13919725.02
#Sta/Elev= 30
  4683.8 1486.56  4757.6 1481.22  4800.2 1476.24  4820.8 1472.79  4831.4 1471.86
  4905.2 1468.12  4926.2 1467.13  4957.9  1468.3  4978.9 1467.78  4987.4 1462.18
  4987.6 1461.68  4991.6 1462.18  4997.4 1464.53  5002.8 1464.53    5014 1468.48
  5058.7 1467.27  5081.1 1467.51  5120.2 1468.33  5170.5 1470.69  5187.3 1472.84
  5192.9 1472.74  5223.6 1477.01  5254.4 1483.95    5297 1487.63  5335.4 1489.55
  5349.4 1491.21  5357.8  1493.4  5380.2 1495.15  5410.9 1501.57  5447.2 1503.39
#Mann= 5 ,-1 , 0
  4683.8     .07       0  4800.2     .12       0  4987.4     .05       0
  4991.6     .12       0    5297     .07       0
Bank Sta=4987.4,4991.6
XS Rating Curve= 0 ,0
Exp/Cntr=0.3,0.1

Type RM Length L Ch R = 1 ,15527   ,448,448,448
BEGIN DESCRIPTION:
Stream0149_DS 32.0
END DESCRIPTION:
XS GIS Cut Line= 3
      2043724.99     13919974.97        2043525.       13919575.
        2043525.     13919474.98
#Sta/Elev= 30
  4560.7 1474.73  4563.5 1474.73  4569.1 1473.97  4672.5 1469.58  4680.6 1468.71
  4703.2 1467.78  4717.2 1468.31  4739.6  1467.8  4747.9 1466.85  4753.5 1462.71
  4761.9 1461.83  4770.3 1464.72  4775.9 1462.37  4784.3 1466.65  4798.3 1466.98
  4882.1 1463.85  4949.2 1462.47  4963.2 1461.42  4983.4  1456.4  4983.7  1455.9
  4987.4  1455.9  4987.7  1456.4  4999.5 1463.33  5005.1 1468.02  5010.4 1468.02
  5017.9 1472.59  5027.9 1480.75  5037.9 1482.76  5083.3 1485.75  5107.9 1487.03
#Mann= 6 ,-1 , 0
  4560.7     .07       0  4563.5    .035       0  4680.6     .12       0
  4983.4     .05       0  4987.7     .12       0  5083.3     .07       0
Bank Sta=4983.4,4987.7
XS Rating Curve= 0 ,0
Exp/Cntr=0.3,0.1

Type RM Length L Ch R = 1 ,15079   ,452,452,452
BEGIN DESCRIPTION:
Stream0149_DS 31.0
END DESCRIPTION:
XS GIS Cut Line= 3
      2044004.92     13920113.08        2043975.       13919575.
      2043775.01     13919425.01
#Sta/Elev= 30
  4461.1 1486.25  4490.8 1483.38    4547    1479  4579.4  1475.5  4629.4 1473.49
  4679.5 1470.19  4709.6 1470.25  4727.2 1468.08  4739.6 1467.97  4869.8 1460.91
  4943.1 1458.89  4949.9  1458.9    4970 1456.75    4990 1456.76  4997.5 1454.23
  5007.3 1455.04  5011.4 1450.91  5011.7 1450.41  5015.7 1450.91  5021.9  1451.3
  5028.1 1455.59  5036.5 1455.22  5042.7 1457.65  5086.5 1457.94  5113.6  1459.2
  5128.1 1460.71  5142.7 1463.33  5163.6 1470.43    5200 1479.29    5250 1482.57
#Mann= 5 ,-1 , 0
  4461.1     .07       0  4490.8    .035       0  4943.1     .12       0
  5011.4     .05       0  5015.7     .12       0
Bank Sta=5011.4,5015.7
XS Rating Curve= 0 ,0
Exp/Cntr=0.3,0.1

Type RM Length L Ch R = 1 ,14627   ,521,521,521
BEGIN DESCRIPTION:
Stream0149_DS 30.0
END DESCRIPTION:
XS GIS Cut Line= 3
      2044475.01     13919775.01        2044125.       13919375.
      2043864.26     13919326.66
#Sta/Elev= 30
  4462.8 1475.12  4490.8 1473.33  4533.5 1465.23  4541.1 1461.61    4562  1463.9
  4584.5 1460.76  4675.3 1458.73  4874.3 1460.34  4880.9  1456.4  4895.1  1459.8
    4916 1453.86  4923.6  1456.8  4930.3 1451.43  4937.8 1454.79  4944.5 1450.71
  4952.1  1453.7  4958.7 1449.77  4966.3 1452.77    4973 1448.91  4980.6 1451.79
  4987.2 1447.72  4996.9 1449.58  5002.3 1447.36  5002.6 1446.86  5006.6 1447.36
  5014.7 1448.06  5020.7 1452.32    5096 1453.38    5157 1474.26  5259.5 1481.06
#Mann= 5 ,-1 , 0
  4462.8     .12       0  4584.5     .07       0  4675.3     .12       0
  5002.3     .05       0  5006.6     .12       0
Bank Sta=5002.3,5006.6
XS Rating Curve= 0 ,0
Exp/Cntr=0.3,0.1

Type RM Length L Ch R = 1 ,14106   ,394,394,394
BEGIN DESCRIPTION:
Stream0149_DS 29.0
END DESCRIPTION:
XS GIS Cut Line= 3
      2044567.44     13919748.58      2044379.92     13919258.96
      2044174.99     13919074.99
#Sta/Elev= 30
  4493.7 1473.86  4529.7 1473.83  4544.1 1471.98  4558.5  1466.2  4568.8 1461.44
  4583.2  1463.6  4604.6 1460.18  4623.5  1459.3  4708.3 1457.43  4861.6 1456.67
  4877.8  1457.4  4942.8 1456.66  4957.3 1456.59  4968.7  1454.6  4985.1 1441.66
  4985.4 1441.16  4989.5 1441.66  4992.6 1442.58  5000.8 1442.64  5011.5 1446.82
  5017.3 1447.71  5088.2 1449.47  5116.6  1454.8  5130.8  1456.1  5137.5 1455.63
    5145 1456.33  5186.9 1456.22  5222.7 1457.56  5248.5 1457.34  5293.4 1458.51
#Mann= 6 ,-1 , 0
  4493.7     .12       0  4558.5     .07       0  4942.8     .12       0
  4985.1     .05       0  4989.5     .12       0  5248.5     .07       0
Bank Sta=4985.1,4989.5
XS Rating Curve= 0 ,0
Exp/Cntr=0.3,0.1

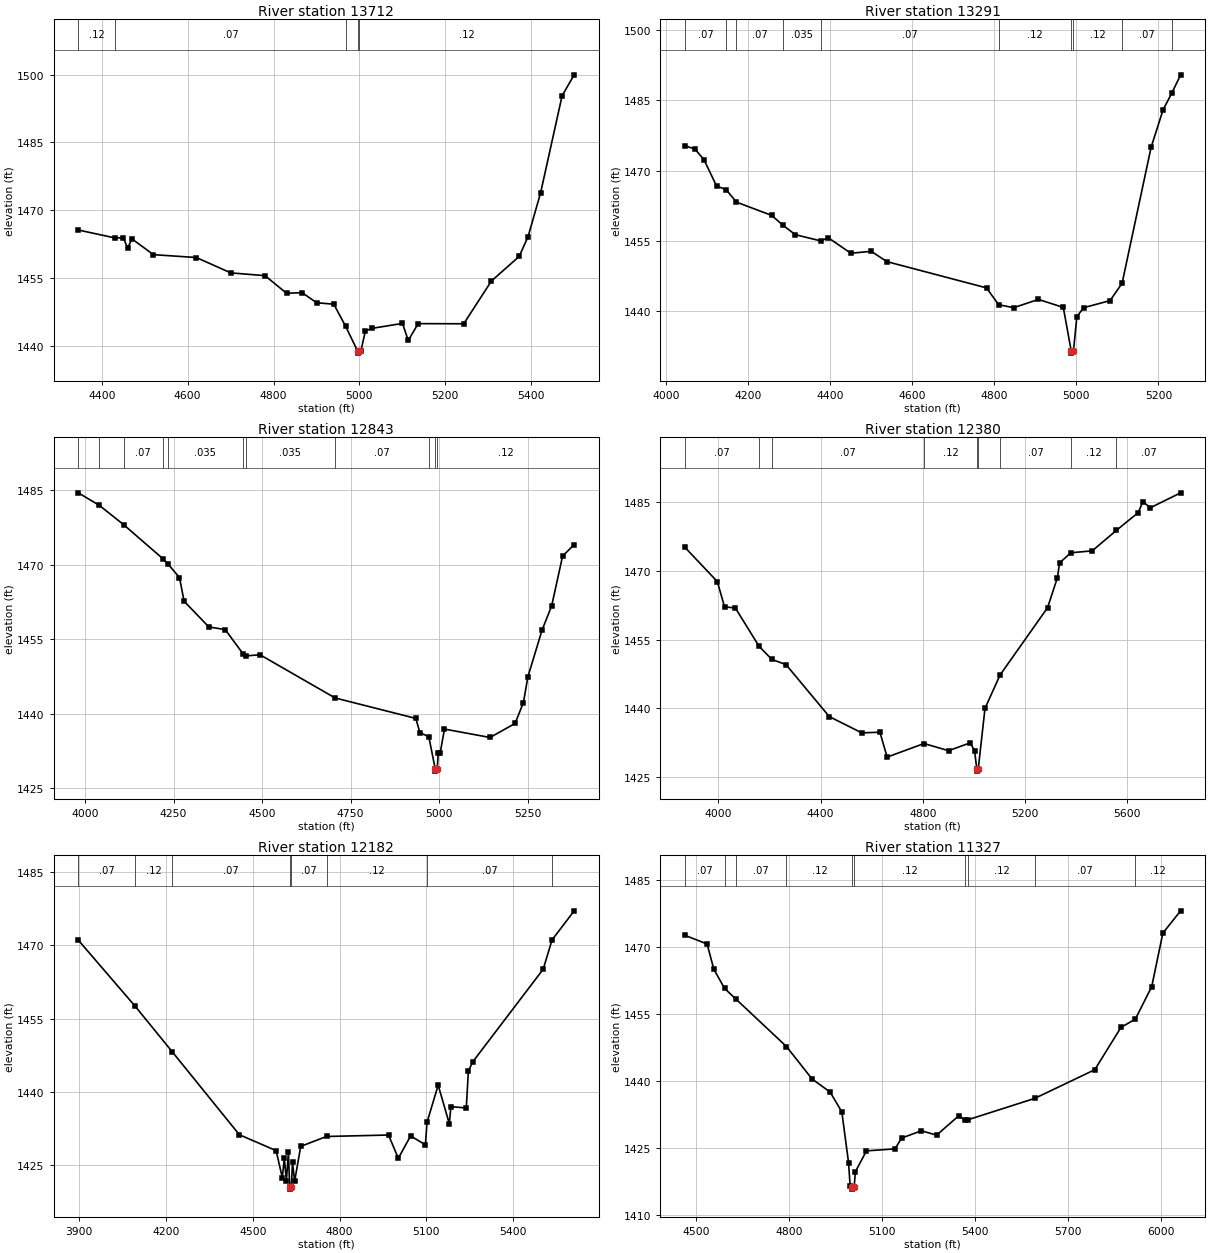
Type RM Length L Ch R = 1 ,13712   ,421,421,421
BEGIN DESCRIPTION:
Stream0149_DS 28.0
END DESCRIPTION:
XS GIS Cut Line= 3
      2044749.71     13919779.83        2044725.       13919125.
        2044425.       13918725.
#Sta/Elev= 30
  4345.2  1465.6  4430.8 1463.84  4450.1 1463.88  4460.1 1461.59  4470.1 1463.64
  4520.2 1460.14  4620.2 1459.51  4700.3 1456.11  4780.3 1455.49  4830.4 1451.59
  4866.7 1451.73  4900.4  1449.5  4940.5 1449.17  4968.2 1444.24  4995.7 1438.84
    4996 1438.34  5000.3 1438.84  5003.6 1438.84    5014 1443.23  5028.6 1443.81
  5100.5 1444.92    5114 1441.14    5137 1444.87  5243.2 1444.84  5307.8 1454.32
  5372.4 1459.75  5393.2 1464.16  5422.4 1473.87  5472.4 1495.32  5500.5 1499.96
#Mann= 5 ,-1 , 0
  4345.2     .12       0  4430.8     .07       0  4968.2     .12       0
  4995.7     .05       0  5000.3     .12       0
Bank Sta=4995.7,5000.3
XS Rating Curve= 0 ,0
Exp/Cntr=0.3,0.1

Type RM Length L Ch R = 1 ,13291   ,448,448,448
BEGIN DESCRIPTION:
Stream0149_DS 27.0
END DESCRIPTION:
XS GIS Cut Line= 3
      2045270.53     13919623.51        2044825.       13918775.
      2044624.97     13918624.98
#Sta/Elev= 30
  4045.8 1475.34  4070.4 1474.63  4092.4 1472.38  4123.2 1466.75  4146.7 1465.96
  4171.7 1463.31  4257.6 1460.48  4284.6 1458.41  4315.2 1456.37  4376.6 1455.06
  4395.5 1455.72  4450.4 1452.42  4500.1 1452.82  4538.6 1450.62  4781.1 1445.03
  4810.7 1441.44  4847.3 1440.81  4907.8 1442.57  4968.3 1440.86  4987.5 1431.62
    4988 1431.12  4993.1 1431.62  5001.3 1438.89  5017.7  1440.8  5082.3 1442.32
  5111.6 1446.03  5182.3 1475.02  5211.5 1483.01  5232.5 1486.52  5254.2 1490.45
#Mann= 10 ,-1 , 0
  4045.8     .07       0  4146.7     .12       0  4171.7     .07       0
  4284.6    .035       0  4376.6     .07       0  4810.7     .12       0
  4987.5     .05       0  4993.1     .12       0  5111.6     .07       0
  5232.5     .12       0
Bank Sta=4987.5,4993.1
XS Rating Curve= 0 ,0
Exp/Cntr=0.3,0.1

Type RM Length L Ch R = 1 ,12843   ,463,463,463
BEGIN DESCRIPTION:
Stream0149_DS 26.0
END DESCRIPTION:
XS GIS Cut Line= 3
      2045640.34     13919555.83        2045225.       13918625.
      2044874.98     13918474.99
#Sta/Elev= 30
    3981 1484.51  4040.3 1481.98    4109 1478.09  4219.9 1471.22  4233.3 1470.23
  4266.6 1467.44  4279.7 1462.66  4349.3 1457.49  4395.8 1456.94    4446 1452.08
  4453.5 1451.64  4494.1 1451.87    4706 1443.17    4934 1439.04  4945.5 1436.17
  4970.7 1435.36  4988.6 1428.92  4989.1 1428.42  4994.3 1428.92  4997.6 1432.15
    5003 1432.15  5014.8  1436.9  5143.5  1435.2  5214.3 1438.03  5237.8 1442.25
  5250.5 1447.45  5290.4 1456.83  5317.6 1461.73  5348.4 1471.75  5381.1 1474.08
#Mann= 11 ,-1 , 0
    3981     .07       0  4040.3     .12       0    4109     .07       0
  4219.9     .12       0  4233.3    .035       0    4446     .07       0
  4453.5    .035       0    4706     .07       0  4970.7     .12       0
  4988.6     .05       0  4994.3     .12       0
Bank Sta=4988.6,4994.3
XS Rating Curve= 0 ,0
Exp/Cntr=0.3,0.1

Type RM Length L Ch R = 1 ,12380   ,198,198,198
BEGIN DESCRIPTION:
Stream0149_DS 25.0
END DESCRIPTION:
XS GIS Cut Line= 3
      2046124.99     13919074.99        2045325.       13918275.
      2044583.05     13917951.67
#Sta/Elev= 30
  3868.6 1475.17  3995.9 1467.66  4024.1 1462.15  4066.6 1461.88  4159.3 1453.52
  4209.5 1450.64  4264.6 1449.53  4434.3 1438.16  4561.5 1434.61  4632.3 1434.75
  4660.5 1429.31  4804.8 1432.28    4901 1430.72  4985.8 1432.43  5002.7 1430.73
  5011.5 1426.75    5012 1426.25  5017.2 1426.75  5043.6 1439.96  5102.5 1447.25
  5288.4 1461.95  5327.2 1468.55  5335.3 1471.74  5379.7 1473.96  5463.3 1474.37
  5557.7 1478.84  5643.6 1482.74  5661.6 1485.13  5690.5 1483.78  5809.3 1487.05
#Mann= 9 ,-1 , 0
  3868.6     .07       0  4159.3     .12       0  4209.5     .07       0
  4804.8     .12       0  5011.5     .05       0  5017.2     .12       0
  5102.5     .07       0  5379.7     .12       0  5557.7     .07       0
Bank Sta=5011.5,5017.2
XS Rating Curve= 0 ,0
Exp/Cntr=0.3,0.1

Type RM Length L Ch R = 1 ,12182   ,855,855,855
BEGIN DESCRIPTION:
Stream0149_DS 24.5
END DESCRIPTION:
XS GIS Cut Line= 4
      2046128.01     13918988.42      2045524.91     13918356.33
      2045465.32     13918135.17      2045179.93     13917595.49
#Sta/Elev= 30
  3897.3 1471.08  4092.7 1457.59  4221.1 1448.23  4453.7 1431.16  4580.7  1427.9
  4602.1 1422.36    4609 1426.32  4616.3 1421.72  4623.2 1427.69  4627.5  1420.5
    4628    1420  4633.4  1420.5  4637.3 1425.53  4644.6 1421.61  4665.7 1428.77
  4754.8  1430.8  4969.1  1431.1  5002.9 1426.33  5045.4 1430.92  5096.6 1429.08
  5101.9 1433.68  5140.7 1441.34    5179 1433.43  5184.7 1436.92  5237.8 1436.65
    5245 1444.24  5260.4 1446.14  5503.5 1465.12  5534.1 1471.13  5610.5  1477.1
#Mann= 8 ,-1 , 0
  3897.3     .07       0  4092.7     .12       0  4221.1     .07       0
  4627.5     .05       0  4633.4     .07       0  4754.8     .12       0
  5101.9     .07       0  5534.1     .12       0
Bank Sta=4627.5,4633.4
XS Rating Curve= 0 ,0
Exp/Cntr=0.3,0.1

Type RM Length L Ch R = 1 ,11327   ,294,294,294
BEGIN DESCRIPTION:
Stream0149_DS 24.0
END DESCRIPTION:
XS GIS Cut Line= 3
      2046444.29     13918643.98      2045975.18     13918385.11
      2045255.21     13917603.46
#Sta/Elev= 30
  4464.2 1472.54  4536.1 1470.59  4557.8 1464.94  4592.5 1460.65  4628.7 1458.29
  4791.9 1447.66  4874.6 1440.39  4932.6 1437.48  4970.4 1433.05  4992.2 1421.67
  4997.2 1416.51  5004.3 1416.26  5004.8 1415.76  5010.3 1416.26  5014.1 1419.64
  5049.8 1424.32  5141.7 1424.76  5163.3 1427.18  5226.8 1428.81  5276.1 1427.84
    5347 1432.14    5369  1431.2  5377.7 1431.29  5592.1 1436.05  5785.9 1442.47
  5870.4 1451.94  5916.7 1453.78  5969.6 1461.07  6005.4 1473.03  6062.7 1478.01
#Mann= 10 ,-1 , 0
  4464.2     .07       0  4592.5     .12       0  4628.7     .07       0
  4791.9     .12       0  5004.3     .05       0  5010.3     .12       0
    5369    .035       0  5377.7     .12       0  5592.1     .07       0
  5916.7     .12       0
Bank Sta=5004.3,5010.3
XS Rating Curve= 0 ,0
Exp/Cntr=0.3,0.1

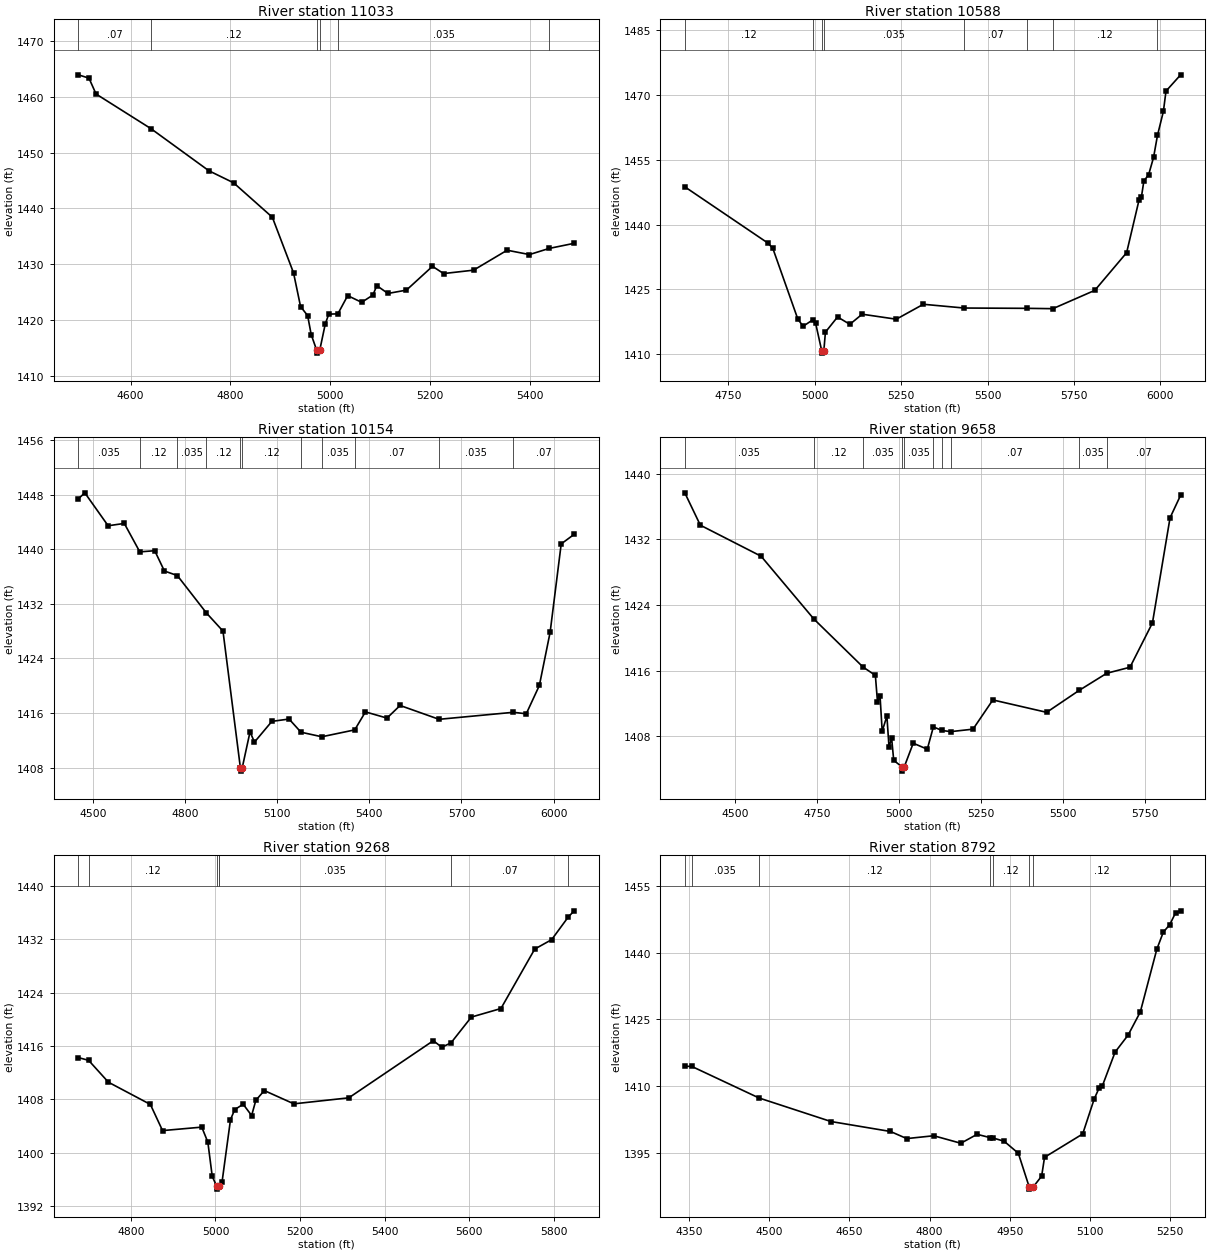
Type RM Length L Ch R = 1 ,11033   ,445,445,445
BEGIN DESCRIPTION:
Stream0149_DS 23.0
END DESCRIPTION:
XS GIS Cut Line= 3
      2046437.24     13918482.94        2046075.       13918125.
      2045640.32     13917909.99
#Sta/Elev= 30
  4495.1 1463.97  4516.4 1463.38  4530.6 1460.53  4640.7 1454.31  4756.9 1446.75
  4806.4 1444.59  4884.1 1438.41  4926.6 1428.43  4940.7 1422.38  4954.9 1420.75
    4962 1417.36  4973.1 1414.52  4973.6 1414.02  4979.1 1414.52  4990.3 1419.28
  4997.3 1421.02  5015.5 1421.07  5035.2 1424.34  5063.2 1423.14  5085.7 1424.44
  5093.6 1426.13  5115.9 1424.73    5153 1425.33  5205.2  1429.6  5227.5  1428.3
  5287.6 1428.91  5354.9 1432.49  5399.7 1431.71  5439.1 1432.81  5489.3 1433.73
#Mann= 6 ,-1 , 0
  4495.1     .07       0  4640.7     .12       0  4973.1     .05       0
  4979.1     .12       0  5015.5    .035       0  5439.1     .07       0
#XS Ineff= 2 , 0
       0                  5093.9       0 1426.07
Permanent Ineff=
       F       F
Bank Sta=4973.1,4979.1
XS Rating Curve= 0 ,0
Exp/Cntr=0.3,0.1

Type RM Length L Ch R = 1 ,10588   ,434,434,434
BEGIN DESCRIPTION:
Stream0149_DS 22.0
END DESCRIPTION:
XS GIS Cut Line= 3
      2046525.74     13918087.07        2046325.       13917775.
      2045524.98     13917074.98
#Sta/Elev= 30
  4624.3 1448.75  4864.6 1435.72  4878.8 1434.51  4951.4 1418.06  4966.6 1416.44
  4993.9 1417.89  5002.5 1417.21  5020.4 1410.71  5020.9 1410.21  5026.4 1410.71
    5031 1415.07  5066.1 1418.59  5101.7 1416.89  5137.3 1419.23    5236 1418.07
  5314.3 1421.53    5432 1420.66  5612.9 1420.59  5688.9 1420.51  5810.2 1424.76
  5902.2 1433.48  5938.3 1445.75    5945  1446.4  5952.1 1450.11  5965.8 1451.54
  5980.1 1455.56  5991.4 1460.65  6008.5 1466.21  6016.1 1470.93  6058.4  1474.7
#Mann= 8 ,-1 , 0
  4624.3     .12       0  4993.9    .035       0  5020.4    .035       0
  5026.4    .035       0    5432     .07       0  5612.9    .035       0
  5688.9     .12       0  5991.4     .07       0
Bank Sta=5020.4,5026.4
XS Rating Curve= 0 ,0
Exp/Cntr=0.3,0.1

Type RM Length L Ch R = 1 ,10154   ,496,496,496
BEGIN DESCRIPTION:
Stream0149_DS 21.0
END DESCRIPTION:
XS GIS Cut Line= 3
      2046807.01     13917972.52      2046601.04     13917495.83
      2045775.01     13916775.01
#Sta/Elev= 30
  4451.5 1447.42  4472.6  1448.3  4548.6 1443.47  4601.3 1443.81  4651.8 1439.64
  4700.4 1439.81    4732 1436.83    4774 1436.17    4869 1430.67  4922.8 1428.02
  4979.5 1407.98    4980 1407.48  4985.6 1407.98    5011 1413.25  5025.3 1411.73
  5082.2 1414.78  5138.2 1415.12  5176.9 1413.19  5244.8 1412.52  5352.1 1413.53
    5387 1416.17  5457.2 1415.26  5499.9 1417.11  5626.9 1415.08    5869 1416.11
    5911 1415.89  5953.7 1420.04  5988.8 1427.85  6024.9 1440.81  6067.1 1442.21
#Mann= 11 ,-1 , 0
  4451.5    .035       0  4651.8     .12       0    4774    .035       0
    4869     .12       0  4979.5     .05       0  4985.6     .12       0
  5176.9     .07       0  5244.8    .035       0  5352.1     .07       0
  5626.9    .035       0    5869     .07       0
Bank Sta=4979.5,4985.6
XS Rating Curve= 0 ,0
Exp/Cntr=0.3,0.1

Type RM Length L Ch R = 1 ,9658    ,390,390,390
BEGIN DESCRIPTION:
Stream0149_DS 20.0
END DESCRIPTION:
XS GIS Cut Line= 3
      2047041.37     13917534.98      2046629.92       13917035.
      2045824.97     13916724.99
#Sta/Elev= 30
  4347.1 1437.66  4394.4 1433.72  4579.5 1429.94  4740.3 1422.29  4889.8 1416.45
  4927.5 1415.43  4933.9 1412.23  4941.8 1412.87  4948.3 1408.63  4962.6 1410.47
  4969.1 1406.69    4977  1407.8  4983.4 1405.08  5009.2 1404.27  5009.7 1403.77
  5015.3 1404.27  5042.8 1407.17  5085.6 1406.44  5104.2 1409.16  5130.2 1408.72
    5157 1408.58  5224.9 1408.88  5285.3 1412.44  5449.2 1410.93  5547.7 1413.59
  5632.3 1415.69    5703 1416.42  5771.4 1421.82    5825 1434.62  5857.2 1437.37
#Mann= 10 ,-1 , 0
  4347.1    .035       0  4740.3     .12       0  4889.8    .035       0
  5009.2    .035       0  5015.3    .035       0  5104.2     .07       0
  5130.2    .035       0    5157     .07       0  5547.7    .035       0
  5632.3     .07       0
Bank Sta=5009.2,5015.3
XS Rating Curve= 0 ,0
Exp/Cntr=0.3,0.1

Type RM Length L Ch R = 1 ,9268    ,476,476,476
BEGIN DESCRIPTION:
Stream0149_DS 19.0
END DESCRIPTION:
XS GIS Cut Line= 3
      2046824.99     13916924.99        2046625.       13916675.
      2045771.75     13916674.76
#Sta/Elev= 30
  4675.4 1414.27  4699.7 1413.86  4746.6 1410.58  4845.9 1407.25  4874.7 1403.33
  4967.5 1403.85  4981.9  1401.6  4992.3 1396.47  5002.4 1395.06  5002.9 1394.56
  5008.6 1395.06  5008.8 1395.08  5015.5 1395.62  5035.5 1404.97  5045.5 1406.48
  5065.5 1407.28  5085.5 1405.59  5095.5 1407.87  5115.5 1409.33  5185.5 1407.34
  5315.5 1408.24  5515.5  1416.8  5535.5 1415.82  5557.3 1416.47  5605.5 1420.34
  5675.5 1421.62  5755.5 1430.53  5795.5 1431.94  5834.8 1435.33  5848.8 1436.26
#Mann= 7 ,-1 , 0
  4675.4     .07       0  4699.7     .12       0  5002.4     .05       0
  5008.6     .12       0  5008.8    .035       0  5557.3     .07       0
  5834.8     .12       0
Bank Sta=5002.4,5008.6
XS Rating Curve= 0 ,0
Exp/Cntr=0.3,0.1

Type RM Length L Ch R = 1 ,8792    ,454,454,454
BEGIN DESCRIPTION:
Stream0149_DS 18.0
END DESCRIPTION:
XS GIS Cut Line= 3
        2046925.     13916925.03        2046825.       13916275.
      2046725.01     13916025.03
#Sta/Elev= 30
  4342.3 1414.45  4355.1 1414.44    4481 1407.33  4615.5 1402.03  4726.8 1399.79
  4757.2 1398.19  4807.7 1398.83  4858.3 1397.14  4888.7 1399.15  4913.3  1398.4
  4918.8 1398.32  4939.3 1397.59  4965.8 1394.89  4986.1 1387.32  4986.6 1386.82
  4993.7 1387.32  5009.4 1389.75  5014.8 1393.98  5086.1 1399.23  5107.7 1407.12
  5117.1 1409.64  5122.5 1409.92  5146.7 1417.65    5171 1421.47  5193.8 1426.67
  5224.8 1440.83  5236.9 1444.65  5248.7 1446.29  5259.8 1448.99  5269.2 1449.43
#Mann= 8 ,-1 , 0
  4342.3     .07       0  4355.1    .035       0    4481     .12       0
  4913.3     .07       0  4918.8     .12       0  4986.1     .05       0
  4993.7     .12       0  5248.7     .07       0
Bank Sta=4986.1,4993.7
XS Rating Curve= 0 ,0
Exp/Cntr=0.3,0.1