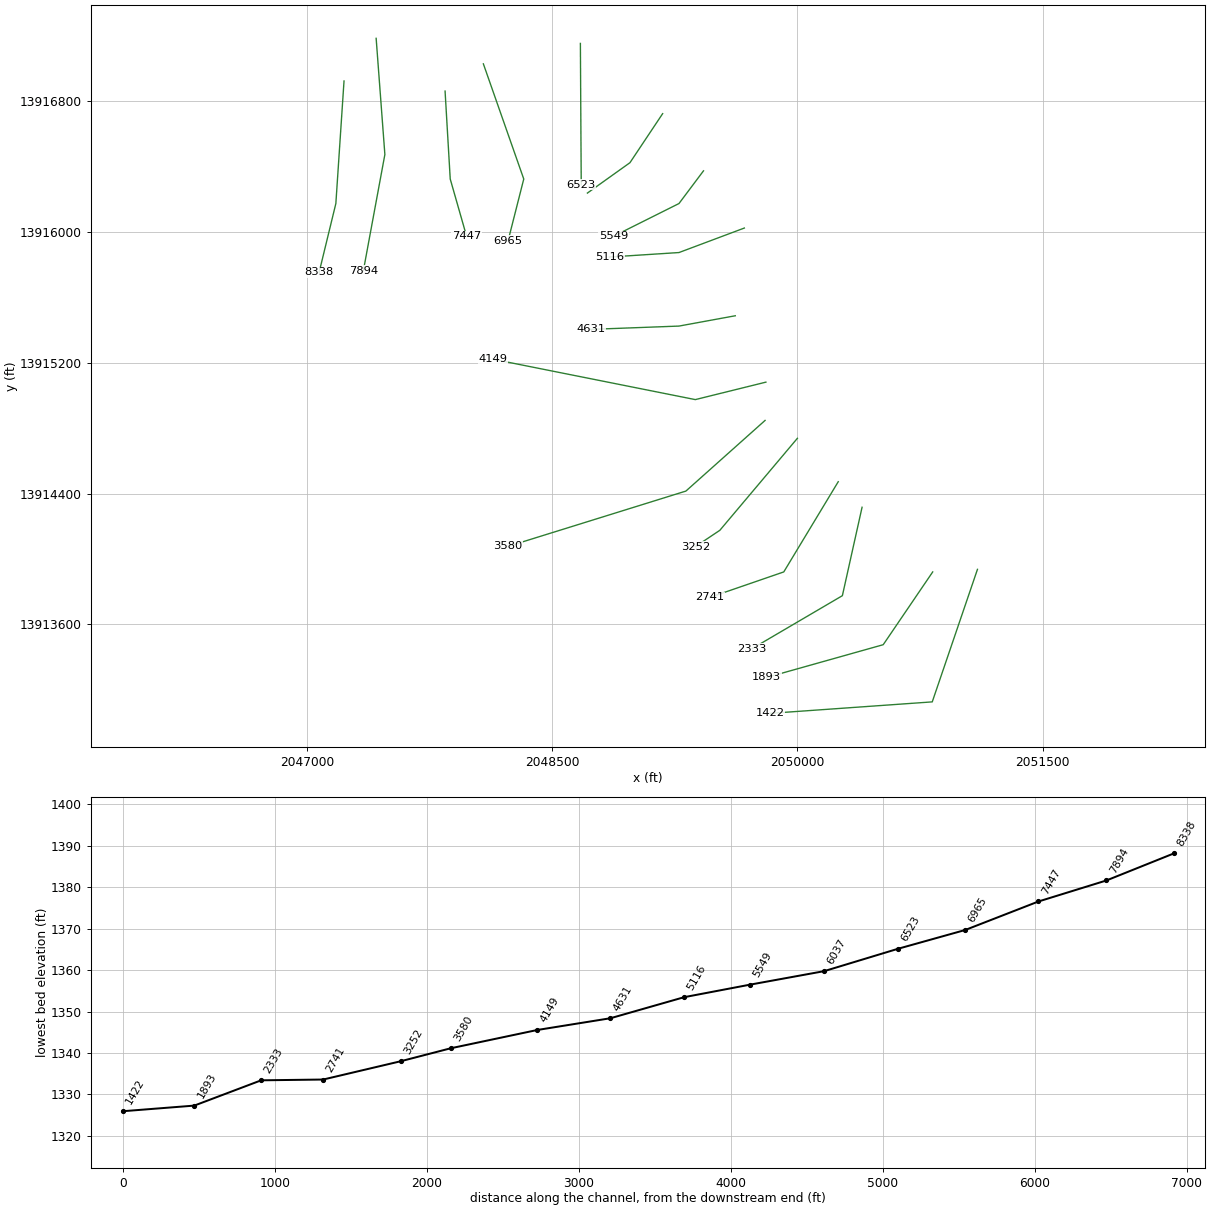
HEC-RAS study Stream0149_DS.prj: Stream0149_DS Base Level Engineering

--- Stream0149_DS.g01 (geometry) --- (continued)

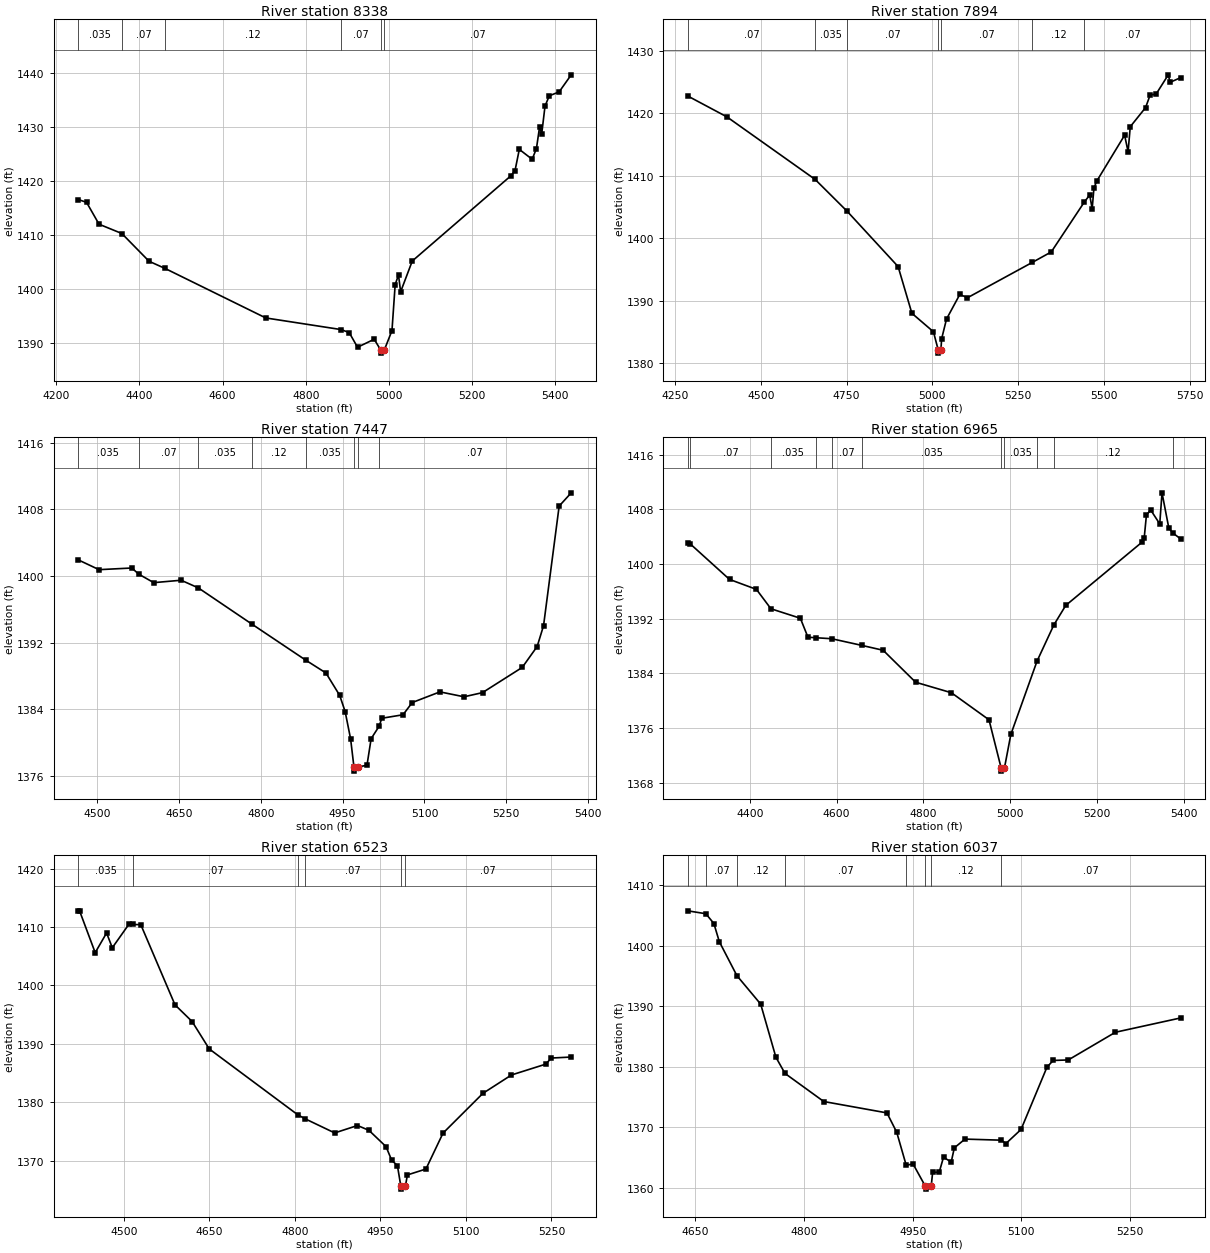
Type RM Length L Ch R = 1 ,8338    ,444,444,444
BEGIN DESCRIPTION:
Stream0149_DS 17.0
END DESCRIPTION:
XS GIS Cut Line= 3
        2047225.     13916925.02        2047175.       13916175.
      2047072.63     13915753.74
#Sta/Elev= 30
    4253 1416.58  4273.1 1416.06  4303.1 1412.01  4357.9 1410.29  4423.4 1405.15
  4461.4 1403.84    4704 1394.66    4885 1392.51  4904.5 1391.95  4924.5 1389.24
  4964.6 1390.72  4980.8 1388.65  4981.3 1388.15  4988.5 1388.65  5007.3 1392.32
    5015 1400.84    5023 1402.61  5028.1  1399.5  5056.1  1405.2  5292.8 1420.95
  5303.1 1421.93  5313.4 1425.86  5344.3 1424.03  5354.6 1426.02  5362.2 1430.05
  5367.3 1428.76  5375.2 1433.87  5385.5 1435.78  5409.1  1436.5  5438.2 1439.66
#Mann= 6 ,-1 , 0
    4253    .035       0  4357.9     .07       0  4461.4     .12       0
    4885     .07       0  4980.8     .05       0  4988.5     .07       0
Bank Sta=4980.8,4988.5
XS Rating Curve= 0 ,0
Exp/Cntr=0.3,0.1

Type RM Length L Ch R = 1 ,7894    ,447,447,447
BEGIN DESCRIPTION:
Stream0149_DS 16.0
END DESCRIPTION:
XS GIS Cut Line= 3
      2047421.59     13917186.01        2047475.       13916475.
      2047343.47     13915764.18
#Sta/Elev= 30
  4287.5  1422.8  4401.8 1419.45  4658.5 1409.44  4751.9 1404.33  4900.2 1395.48
  4940.3    1388  5003.1 1385.04    5017 1382.12  5017.5 1381.62  5024.8 1382.12
    5027 1383.93  5041.2 1387.08  5079.9 1391.02  5102.2 1390.49  5291.4 1396.16
  5346.3 1397.83  5442.7 1405.83  5458.2 1406.94  5465.4 1404.74  5470.5 1408.04
  5478.5 1409.15  5559.9 1416.52    5570 1413.87  5576.3 1417.88  5620.9 1420.94
  5634.3 1422.97  5651.4 1423.09    5687 1426.19  5692.3 1424.99  5723.4 1425.75
#Mann= 7 ,-1 , 0
  4287.5     .07       0  4658.5    .035       0  4751.9     .07       0
    5017     .05       0  5024.8     .07       0  5291.4     .12       0
  5442.7     .07       0
Bank Sta=5017,5024.8
XS Rating Curve= 0 ,0
Exp/Cntr=0.3,0.1

Type RM Length L Ch R = 1 ,7447    ,482,482,482
BEGIN DESCRIPTION:
Stream0149_DS 15.0
END DESCRIPTION:
XS GIS Cut Line= 3
      2047843.46     13916863.14        2047875.       13916325.
      2047975.01     13915974.97
#Sta/Elev= 30
  4465.7 1401.93  4503.9 1400.75    4564 1400.95  4576.4 1400.22  4604.1 1399.19
  4654.2 1399.48  4685.8 1398.56  4784.1  1394.2  4882.5 1389.88  4919.5 1388.34
  4944.7 1385.65  4954.7  1383.7  4964.7 1380.42  4970.8 1377.05  4971.3 1376.55
  4978.7 1377.05  4994.7 1377.26  5002.3 1380.45  5017.2 1381.97  5021.7  1382.9
  5060.7 1383.32  5077.6 1384.79  5128.3 1386.07  5172.5 1385.48  5206.3 1385.98
  5279.1 1389.01  5306.4 1391.52  5318.1 1394.02  5346.7 1408.39  5368.8 1409.98
#Mann= 8 ,-1 , 0
  4465.7    .035       0  4576.4     .07       0  4685.8    .035       0
  4784.1     .12       0  4882.5    .035       0  4970.8    .035       0
  4978.7    .035       0  5017.2     .07       0
Bank Sta=4970.8,4978.7
XS Rating Curve= 0 ,0
Exp/Cntr=0.3,0.1

Type RM Length L Ch R = 1 ,6965    ,442,442,442
BEGIN DESCRIPTION:
Stream0149_DS 14.0
END DESCRIPTION:
XS GIS Cut Line= 3
      2048077.84     13917029.78        2048325.       13916325.
      2048229.33     13915948.22
#Sta/Elev= 30
  4257.3  1403.1  4263.6 1402.92  4353.5 1397.75  4415.5 1396.29  4448.9 1393.45
  4516.7 1392.06  4534.2 1389.28    4552 1389.21    4589 1389.06  4659.3 1388.07
  4707.4 1387.37  4782.2 1382.69  4864.6 1381.15  4951.2 1377.19    4979 1370.17
  4979.5 1369.67  4986.9 1370.17  5001.5 1375.04  5061.9 1385.79  5100.5 1391.07
    5128 1393.94  5303.4 1403.19  5308.7 1403.83  5313.9 1407.23    5324 1407.88
  5344.5 1405.88  5349.7 1410.43  5365.3  1405.3  5373.9 1404.58  5392.9 1403.67
#Mann= 11 ,-1 , 0
  4257.3    .035       0  4263.6     .07       0  4448.9    .035       0
    4552     .12       0    4589     .07       0  4659.3    .035       0
    4979    .035       0  4986.9    .035       0  5061.9     .07       0
  5100.5     .12       0  5373.9    .035       0
Bank Sta=4979,4986.9
XS Rating Curve= 0 ,0
Exp/Cntr=0.3,0.1

Type RM Length L Ch R = 1 ,6523    ,486,486,486
BEGIN DESCRIPTION:
Stream0149_DS 13.0
END DESCRIPTION:
XS GIS Cut Line= 3
      2048671.59     13917154.83        2048675.       13916575.
       2048676.8     13916290.25
#Sta/Elev= 30
  4420.2 1412.78  4422.6 1412.78    4450 1405.62    4470 1408.99    4480 1406.46
    4510  1410.6  4516.6 1410.44    4530 1410.41    4590 1396.68    4620 1393.83
    4650 1389.14  4805.2 1377.87  4817.5 1377.21    4870 1374.76    4910 1376.03
    4930 1375.21    4960 1372.42    4970 1370.08    4980 1369.17    4986 1365.64
  4986.5 1365.14    4994 1365.64  4997.5 1367.57    5030 1368.58    5060 1374.73
    5130 1381.54    5180 1384.68    5240 1386.53    5250 1387.58  5284.8 1387.75
#Mann= 6 ,-1 , 0
  4420.2    .035       0  4516.6     .07       0  4805.2    .035       0
  4817.5     .07       0    4986     .05       0    4994     .07       0
Bank Sta=4986,4994
XS Rating Curve= 0 ,0
Exp/Cntr=0.3,0.1

Type RM Length L Ch R = 1 ,6037    ,488,488,488
BEGIN DESCRIPTION:
Stream0149_DS 12.0
END DESCRIPTION:
XS GIS Cut Line= 3
      2049175.02     13916725.03        2048975.       13916425.
      2048714.56     13916239.05
#Sta/Elev= 30
  4639.4 1405.74  4664.4 1405.26  4675.5 1403.64    4683 1400.64  4707.3 1395.02
  4740.1 1390.32  4761.1 1381.54  4773.7 1378.86  4827.2 1374.22  4914.4 1372.34
  4927.9 1369.14    4941 1363.68  4950.4 1363.91  4967.3 1360.24  4967.8 1359.74
  4975.5 1360.24  4977.5 1362.52  4986.5 1362.52  4992.5 1365.02  5003.1 1364.21
  5007.4 1366.56  5022.1 1368.01  5072.4 1367.83  5078.6 1367.27  5099.5  1369.6
  5135.2 1379.87  5143.8 1381.01  5164.7 1381.09  5229.8 1385.67    5320 1388.04
#Mann= 8 ,-1 , 0
  4639.4    .035       0  4664.4     .07       0  4707.3     .12       0
  4773.7     .07       0    4941     .12       0  4967.3     .05       0
  4975.5     .12       0  5072.4     .07       0
Bank Sta=4967.3,4975.5
XS Rating Curve= 0 ,0
Exp/Cntr=0.3,0.1

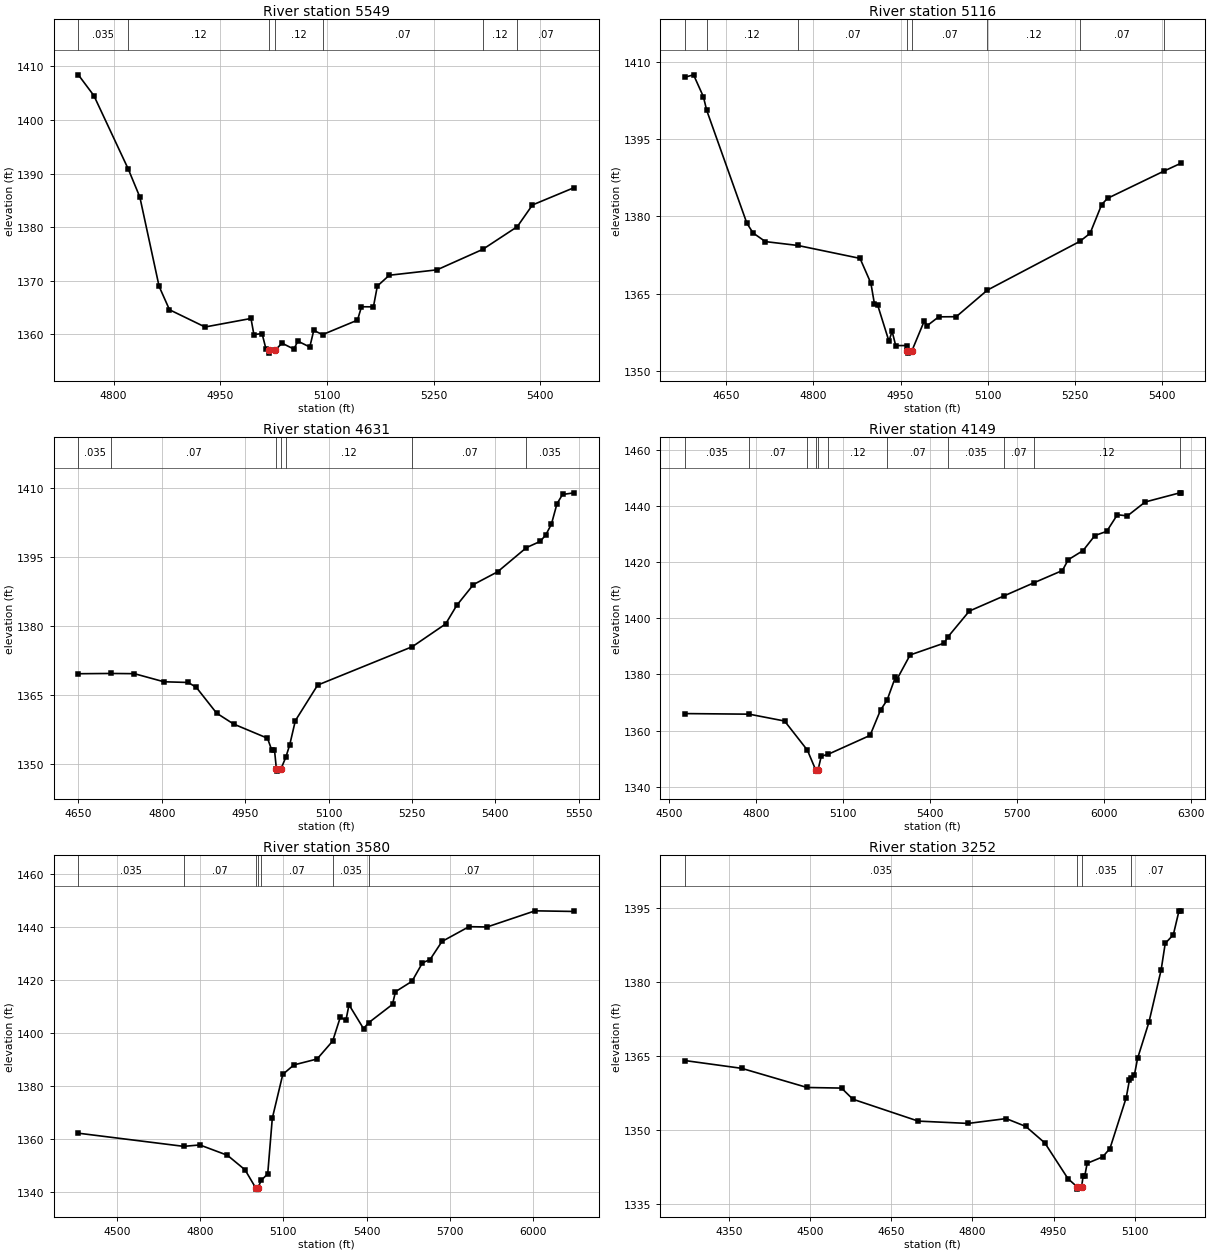
Type RM Length L Ch R = 1 ,5549    ,433,433,433
BEGIN DESCRIPTION:
Stream0149_DS 11.0
END DESCRIPTION:
XS GIS Cut Line= 3
      2049425.03     13916375.04        2049275.       13916175.
      2048874.96     13915974.98
#Sta/Elev= 30
  4750.5 1408.44  4772.4 1404.55  4820.7 1390.85    4837 1385.62  4864.1 1368.94
  4878.7 1364.58  4928.7 1361.36  4993.3 1362.95  4997.4 1359.95  5008.9 1360.12
  5014.5  1357.2  5018.8 1356.98  5019.3 1356.48    5027 1356.98  5036.9 1358.34
  5053.7 1357.23  5059.2 1358.72    5076 1357.62  5081.6 1360.73  5093.9 1359.93
  5143.1 1362.64  5148.7 1365.14  5165.5 1365.12    5171    1369  5187.8 1371.02
  5254.9 1372.03  5319.2 1375.85  5367.8 1380.09  5389.1 1384.14  5447.8 1387.38
#Mann= 7 ,-1 , 0
  4750.5    .035       0  4820.7     .12       0  5018.8     .05       0
    5027     .12       0  5093.9     .07       0  5319.2     .12       0
  5367.8     .07       0
Bank Sta=5018.8,5027
XS Rating Curve= 0 ,0
Exp/Cntr=0.3,0.1

Type RM Length L Ch R = 1 ,5116    ,485,485,485
BEGIN DESCRIPTION:
Stream0149_DS 10.0
END DESCRIPTION:
XS GIS Cut Line= 3
      2049674.99       13916025.        2049275.       13915875.
      2048849.38     13915847.55
#Sta/Elev= 30
  4578.5 1407.04  4593.6 1407.51  4610.5 1403.26  4616.2 1400.62  4685.3 1378.71
    4696  1376.8  4717.3 1375.12  4773.1 1374.37  4880.2 1371.86  4898.9 1367.04
  4905.1 1362.97  4910.5 1362.81    4930 1355.78  4935.4 1357.73  4941.6 1354.93
  4960.3 1354.93  4961.5 1353.96    4962 1353.46  4969.7 1353.96  4990.6 1359.64
  4995.9  1358.8  5015.7 1360.51  5045.8 1360.53  5099.5  1365.7  5258.5 1375.15
  5276.3 1376.72  5296.3 1382.32  5306.3 1383.52  5403.8 1388.83  5432.2 1390.31
#Mann= 8 ,-1 , 0
  4578.5    .035       0  4616.2     .12       0  4773.1     .07       0
  4961.5     .05       0  4969.7     .07       0  5099.5     .12       0
  5258.5     .07       0  5403.8    .035       0
Bank Sta=4961.5,4969.7
XS Rating Curve= 0 ,0
Exp/Cntr=0.3,0.1

Type RM Length L Ch R = 1 ,4631    ,482,482,482
BEGIN DESCRIPTION:
Stream0149_DS 9.0
END DESCRIPTION:
XS GIS Cut Line= 3
      2049619.48     13915488.12        2049275.       13915425.
       2048734.1     13915404.79
#Sta/Elev= 30
  4650.1 1369.57  4708.8 1369.63  4750.9 1369.58  4804.1 1367.82  4847.8 1367.67
  4862.3 1366.59  4898.7    1361  4929.2 1358.63  4990.2 1355.54  4997.8 1352.98
  5002.8 1352.98  5006.2 1348.88  5006.7 1348.38  5014.5 1348.88  5023.3 1351.44
  5030.3 1354.16  5040.3 1359.36  5080.4  1367.1  5250.7 1375.46  5310.5  1380.4
  5330.5 1384.45  5360.6 1388.98  5403.9 1391.74  5455.8 1397.01  5480.7 1398.37
  5490.7  1399.8  5500.7 1402.11  5510.7 1406.55  5520.7 1408.57  5541.6 1408.93
#Mann= 7 ,-1 , 0
  4650.1    .035       0  4708.8     .07       0  5006.2     .05       0
  5014.5     .07       0  5023.3     .12       0  5250.7     .07       0
  5455.8    .035       0
Bank Sta=5006.2,5014.5
XS Rating Curve= 0 ,0
Exp/Cntr=0.3,0.1

Type RM Length L Ch R = 1 ,4149    ,569,569,569
BEGIN DESCRIPTION:
Stream0149_DS 8.0
END DESCRIPTION:
XS GIS Cut Line= 3
      2049806.97     13915081.87        2049375.       13914975.
      2048135.15      13915222.5
#Sta/Elev= 30
  4555.1 1366.03  4777.1 1365.82  4899.1 1363.38  4977.7    1353  5006.1 1346.04
  5006.6 1345.54  5014.5 1346.04  5025.6 1350.86  5050.2 1351.58  5193.8 1358.26
  5229.8 1367.27  5252.5 1370.82  5280.8 1378.92  5285.9 1378.13  5331.8  1386.9
  5448.8  1391.1  5462.5 1393.37    5536 1402.53  5657.1    1408  5758.2 1412.58
  5856.7 1416.96  5877.1 1420.82    5928 1424.06  5968.8 1429.42  6009.6 1430.91
  6046.3 1436.83    6081 1436.42  6142.2 1441.37  6261.5 1444.62  6264.4 1444.63
#Mann= 11 ,-1 , 0
  4555.1    .035       0  4777.1     .07       0  4977.7    .035       0
  5006.1    .035       0  5014.5    .035       0  5050.2     .12       0
  5252.5     .07       0  5462.5    .035       0  5657.1     .07       0
  5758.2     .12       0  6261.5     .07       0
Bank Sta=5006.1,5014.5
XS Rating Curve= 0 ,0
Exp/Cntr=0.3,0.1

Type RM Length L Ch R = 1 ,3580    ,328,328,328
BEGIN DESCRIPTION:
Stream0149_DS 7.0
END DESCRIPTION:
XS GIS Cut Line= 3
      2049801.82     13914847.52      2049317.42     13914415.21
      2048229.48     13914076.85
#Sta/Elev= 30
  4360.2 1362.21  4740.3 1357.25  4798.5 1357.78    4898 1353.89  4961.5 1348.41
  4999.8 1341.63  5000.3 1341.13  5008.5 1341.63  5019.6 1344.41  5043.4  1346.9
  5059.9 1367.83  5097.7 1384.37  5137.7 1387.94  5221.4 1390.17  5277.7 1396.94
  5305.2 1405.91  5325.5 1404.78  5336.6 1410.61    5389 1401.62  5407.5 1403.85
  5493.5 1410.76  5504.2 1415.54  5563.8 1419.46  5601.6 1426.42  5628.9 1427.64
  5671.9 1434.46  5769.5 1440.05  5834.6 1439.93  6007.8 1446.02  6148.8 1445.78
#Mann= 7 ,-1 , 0
  4360.2    .035       0  4740.3     .07       0  4999.8     .05       0
  5008.5     .07       0  5019.6     .07       0  5277.7    .035       0
  5407.5     .07       0
Bank Sta=4999.8,5008.5
XS Rating Curve= 0 ,0
Exp/Cntr=0.3,0.1

Type RM Length L Ch R = 1 ,3252    ,511,511,511
BEGIN DESCRIPTION:
Stream0149_DS 6.0
END DESCRIPTION:
XS GIS Cut Line= 3
      2049999.72     13914738.13        2049525.       13914175.
      2049375.01       13914075.
#Sta/Elev= 30
  4268.1 1364.06  4373.3 1362.48  4494.2  1358.6  4557.9 1358.48  4578.8 1356.23
  4699.7 1351.79    4792 1351.32  4862.3  1352.3  4898.6 1350.71  4933.8 1347.37
  4976.6 1340.13  4993.1 1338.51  4993.6 1338.01  5001.9 1338.51  5004.6 1340.67
  5007.6 1340.67  5012.1 1343.24  5040.7 1344.54  5054.2 1346.23  5084.3 1356.54
  5090.3 1360.14  5093.4 1360.46  5099.3 1361.07  5105.3 1364.49  5126.3 1371.83
  5148.9 1382.43  5156.4 1387.79  5171.4 1389.54  5181.9 1394.39  5184.9 1394.39
#Mann= 4 ,-1 , 0
  4268.1    .035       0  4993.1    .035       0  5001.9    .035       0
  5093.4     .07       0
Bank Sta=4993.1,5001.9
XS Rating Curve= 0 ,0
Exp/Cntr=0.3,0.1

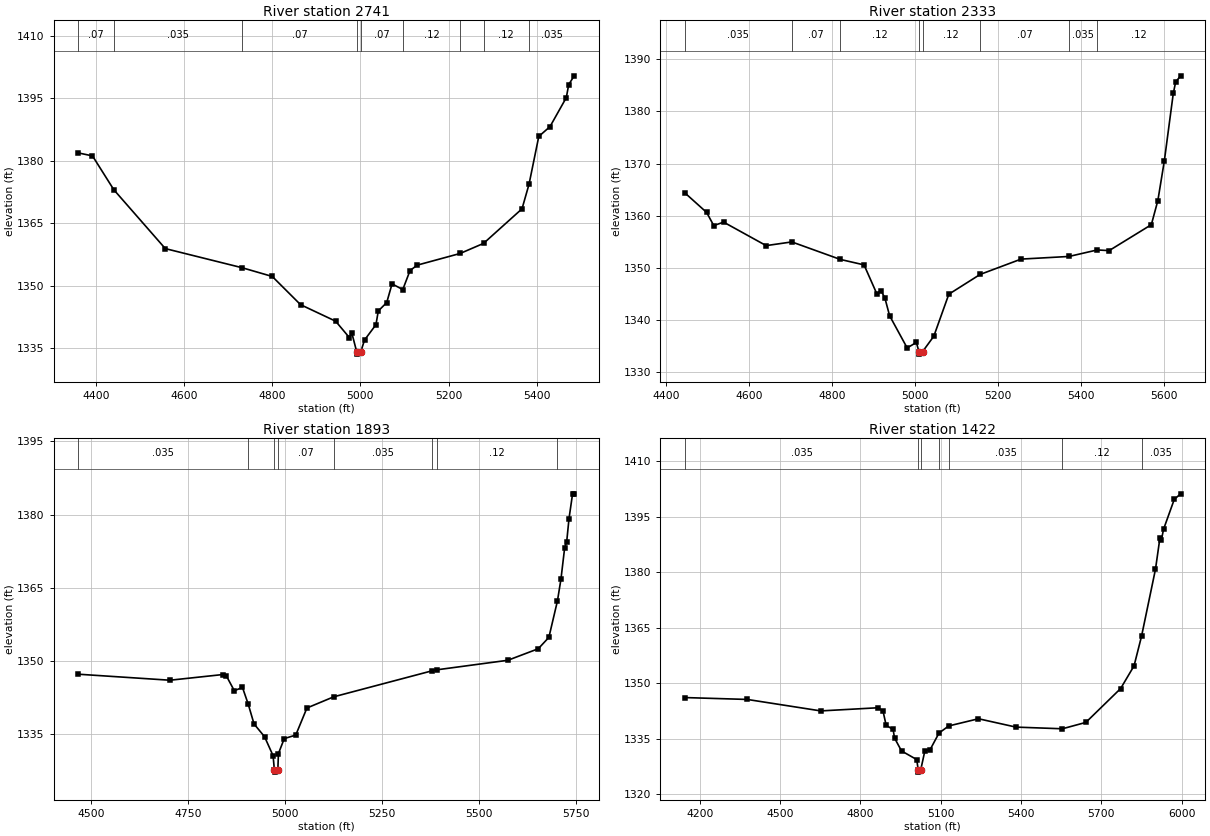
Type RM Length L Ch R = 1 ,2741    ,408,408,408
BEGIN DESCRIPTION:
Stream0149_DS 5.0
END DESCRIPTION:
XS GIS Cut Line= 3
       2050249.7     13914472.47      2049916.38     13913920.42
      2049463.24     13913764.16
#Sta/Elev= 30
  4360.4 1381.91  4392.5 1381.19  4440.9 1373.06  4557.6 1358.93    4732 1354.33
  4800.1 1352.24  4864.2 1345.47  4943.8  1341.5  4974.8 1337.58  4980.7 1338.58
  4991.7 1334.09  4992.2 1333.59  5000.6 1334.09  5009.3 1336.98  5035.2 1340.66
  5040.5 1343.96  5059.6 1345.97  5071.7 1350.47    5096 1349.09  5112.5 1353.66
  5128.8 1354.96    5226 1357.76  5279.1 1360.18  5366.4 1368.49  5382.3  1374.4
  5404.4 1385.87  5429.8 1388.22  5466.8 1395.19  5472.2  1398.3  5484.6 1400.42
#Mann= 9 ,-1 , 0
  4360.4     .07       0  4440.9    .035       0    4732     .07       0
  4991.7     .05       0  5000.6     .07       0    5096     .12       0
    5226    .035       0  5279.1     .12       0  5382.3    .035       0
Bank Sta=4991.7,5000.6
XS Rating Curve= 0 ,0
Exp/Cntr=0.3,0.1

Type RM Length L Ch R = 1 ,2333    ,440,440,440
BEGIN DESCRIPTION:
Stream0149_DS 4.0
END DESCRIPTION:
XS GIS Cut Line= 3
      2050395.54     13914316.22        2050275.       13913775.
      2049723.69     13913451.68
#Sta/Elev= 30
  4445.5 1364.38    4498 1360.62  4515.2 1358.09    4539 1358.75  4641.4 1354.24
  4703.1 1354.95  4819.8 1351.59    4877 1350.54  4907.8 1344.98    4918 1345.56
  4927.1  1344.2  4938.5 1340.78  4980.8 1334.59  5002.9 1335.64  5009.1  1333.9
  5009.6  1333.4  5018.1  1333.9    5045 1336.85  5081.1 1344.91  5156.3  1348.7
    5255 1351.65  5370.5 1352.16  5438.4 1353.41    5467 1353.28  5568.6 1358.26
  5584.3  1362.9  5599.9 1370.52  5621.4 1383.46  5627.2 1385.68  5639.1 1386.85
#Mann= 8 ,-1 , 0
  4445.5    .035       0  4703.1     .07       0  4819.8     .12       0
  5009.1     .05       0  5018.1     .12       0  5156.3     .07       0
  5370.5    .035       0  5438.4     .12       0
Bank Sta=5009.1,5018.1
XS Rating Curve= 0 ,0
Exp/Cntr=0.3,0.1

Type RM Length L Ch R = 1 ,1893    ,471,471,471
BEGIN DESCRIPTION:
Stream0149_DS 3.0
END DESCRIPTION:
XS GIS Cut Line= 3
      2050827.86     13913920.45        2050525.       13913475.
      2049812.19     13913274.58
#Sta/Elev= 30
  4466.7 1347.33    4703  1346.1  4839.2 1347.26  4848.1 1347.06  4869.1 1343.95
  4890.1 1344.63  4904.8 1341.25    4920 1337.15    4947 1334.56  4969.1 1330.66
  4972.4  1327.8  4972.9  1327.3  4981.4  1327.8  4982.9 1331.09  4997.9 1334.16
  5027.6 1334.88  5056.4 1340.42  5125.7 1342.71  5378.9 1348.02  5391.5 1348.23
  5574.7 1350.18  5653.2 1352.54  5680.6 1354.87  5702.6  1362.3  5711.7 1366.75
  5721.3  1373.2  5726.5 1374.39  5732.5 1379.15  5741.7 1384.23  5745.8 1384.23
#Mann= 8 ,-1 , 0
  4466.7    .035       0  4904.8     .07       0  4972.4     .05       0
  4981.4     .07       0  5125.7    .035       0  5378.9     .07       0
  5391.5     .12       0  5702.6    .035       0
Bank Sta=4972.4,4981.4
XS Rating Curve= 0 ,0
Exp/Cntr=0.3,0.1

Type RM Length L Ch R = 1 ,1422    ,0,0,0
BEGIN DESCRIPTION:
Stream0149_DS 2.0
END DESCRIPTION:
XS GIS Cut Line= 3
       2051101.7     13913935.97        2050825.       13913125.
      2049831.36     13913054.66
#Sta/Elev= 30
  4143.4  1346.1  4376.9 1345.59  4651.6 1342.49  4864.6 1343.34    4884  1342.5
  4895.9  1338.6  4921.9 1337.47  4927.2 1335.16  4953.3 1331.67  5010.3 1329.33
  5015.8 1326.44  5016.3 1325.94  5024.8 1326.44  5040.4 1331.64  5060.4 1332.05
  5093.4  1336.5  5129.5 1338.42  5240.9 1340.37  5381.2 1338.11  5554.5 1337.66
  5642.2 1339.38  5772.2 1348.54  5822.3 1354.67  5850.3 1362.67  5902.5 1380.82
  5919.2 1389.35  5924.2  1388.6  5932.6  1391.6  5972.7 1399.69  5996.4 1401.18
#Mann= 7 ,-1 , 0
  4143.4    .035       0  5015.8    .035       0  5024.8    .035       0
  5093.4     .07       0  5129.5    .035       0  5554.5     .12       0
  5850.3    .035       0
Bank Sta=5015.8,5024.8
XS Rating Curve= 0 ,0
Exp/Cntr=0.3,0.1

Chan Stop Cuts=-1
Use User Specified Reach Order=0
Composite Channel Slope=5