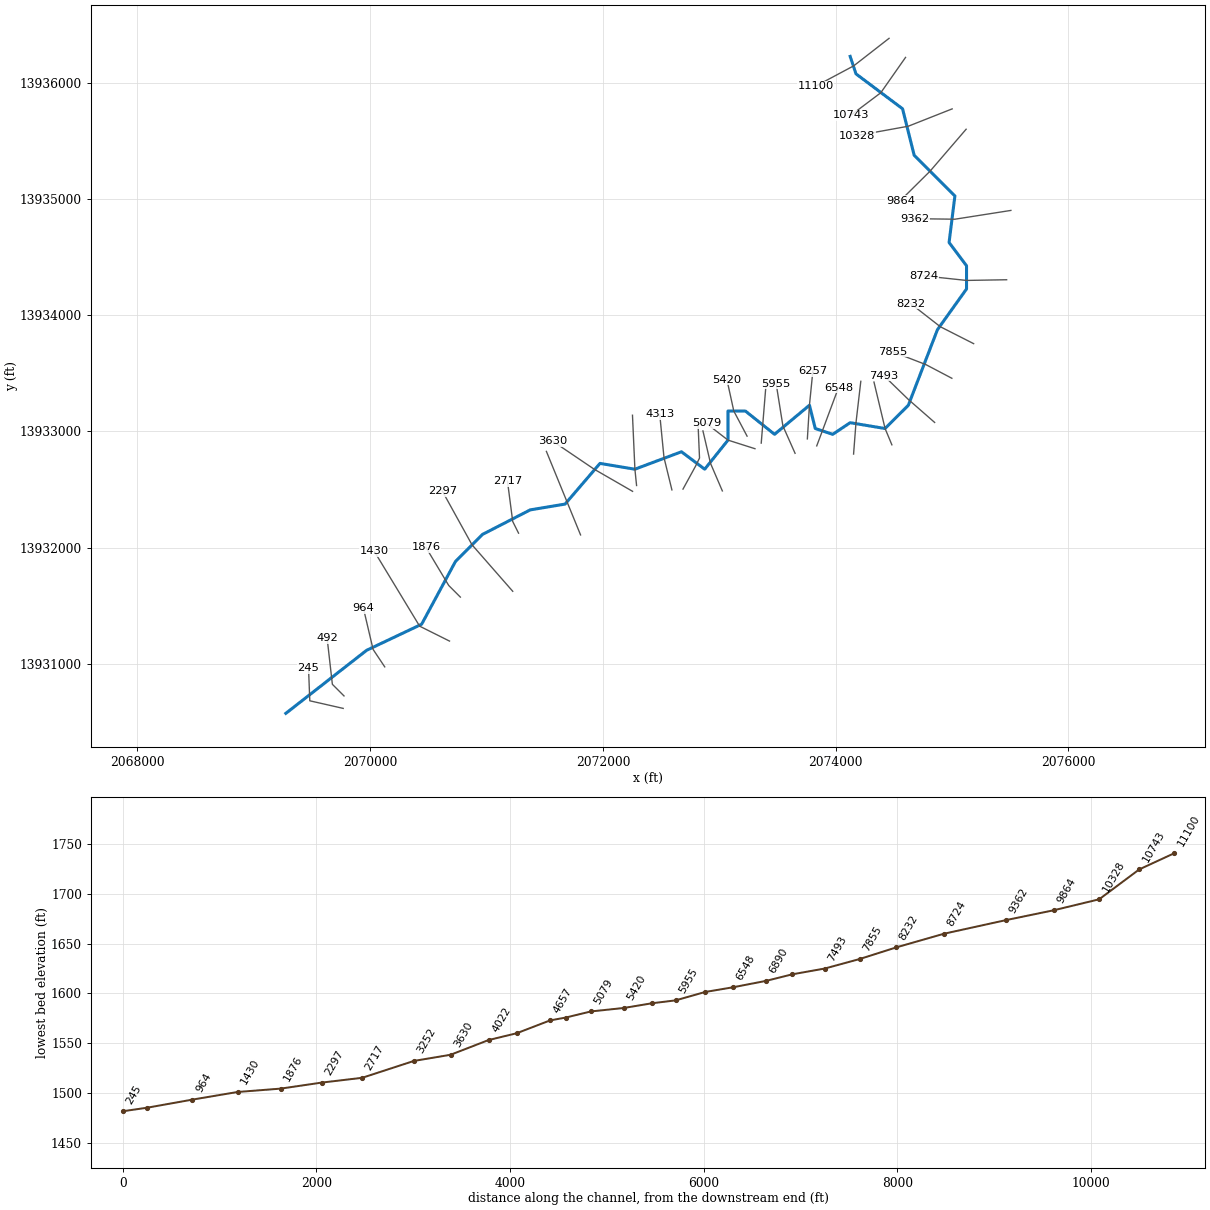
--- Stream0150_DS.prj (project) ---

Proj Title=Stream0150_DS Base Level Engineering
Current Plan=p01
Default Exp/Contr=0.3,0.1
English Units
Geom File=g01
Flow File=f01
Plan File=p01
BEGIN DESCRIPTION:
Stream0150_DS
END DESCRIPTION:

--- Stream0150_DS.p01 (plan) ---

Plan Title=Multiple Run
Short Identifier=Multiple
Geom File=g01
Flow File=f01
Subcritical Flow
K Sum by GR= 0
Std Step Tol= 0.01
Critical Tol= 0.01
Num of Std Step Trials= 20
Max Error Tol= 0.3
Flow Tol Ratio= 0.001
Split Flow NTrial= 30
Split Flow Tol= 0.02
Split Flow Ratio= 0.02
Log Output Level= 0
Friction Slope Method= 1
Unsteady Friction Slope Method= 2
Unsteady Bridges Friction Slope Method= 1
Parabolic Critical Depth
Global Vel Dist=  1 , 1 , 1
Global Log Level= 0
CheckData=True
Encroach Param= -1, 0, 0, 0
BEGIN DESCRIPTION:
Multiple Run
END DESCRIPTION:

--- Stream0150_DS.f01 (steady flow) ---

Flow Title=Multiple
Number of Profiles=7
Profile Names=10-year,25-year,50-year,1pct_min,100-year,1pct_plu,500-year
River Rch & RM= Stream0150_DS,Reach-1,11100
    1604    2830    4045    2806    5599   11171   10631
River Rch & RM= Stream0150_DS,Reach-1,2717
    1671    2946    4209    2916    5818   11608   11025
Boundary for River Rch & Prof#=Stream0150_DS,Reach-1,1
Up Type=0
Dn Type=3
Dn Slope=0.005
Boundary for River Rch & Prof#=Stream0150_DS,Reach-1,2
Up Type=0
Dn Type=3
Dn Slope=0.005
Boundary for River Rch & Prof#=Stream0150_DS,Reach-1,3
Up Type=0
Dn Type=3
Dn Slope=0.005
Boundary for River Rch & Prof#=Stream0150_DS,Reach-1,4
Up Type=0
Dn Type=3
Dn Slope=0.005
Boundary for River Rch & Prof#=Stream0150_DS,Reach-1,5
Up Type=0
Dn Type=3
Dn Slope=0.005
Boundary for River Rch & Prof#=Stream0150_DS,Reach-1,6
Up Type=0
Dn Type=3
Dn Slope=0.005
Boundary for River Rch & Prof#=Stream0150_DS,Reach-1,7
Up Type=0
Dn Type=3
Dn Slope=0.005

--- Stream0150_DS.g01 (geometry) ---

Geom Title=Existing Conditions

River Reach=Stream0150_DS,Reach-1
Reach XY= 30
      2074125.00     13936225.00      2074175.00     13936075.00
      2074575.00     13935775.00      2074675.00     13935375.00
      2075025.00     13935025.00      2074975.00     13934625.00
      2075125.00     13934425.00      2075125.00     13934225.00
      2074875.00     13933875.00      2074625.00     13933225.00
      2074425.00     13933025.00      2074125.00     13933075.00
      2073975.00     13932975.00      2073825.00     13933025.00
      2073775.00     13933225.00      2073475.00     13932975.00
      2073225.00     13933175.00      2073075.00     13933175.00
      2073075.00     13932925.00      2072875.00     13932675.00
      2072675.00     13932825.00      2072275.00     13932675.00
      2071975.00     13932725.00      2071675.00     13932375.00
      2071375.00     13932325.00      2070965.32     13932114.24
      2070732.86     13931881.17      2070442.05     13931341.50
      2069968.83     13931117.14      2069275.00     13930575.00

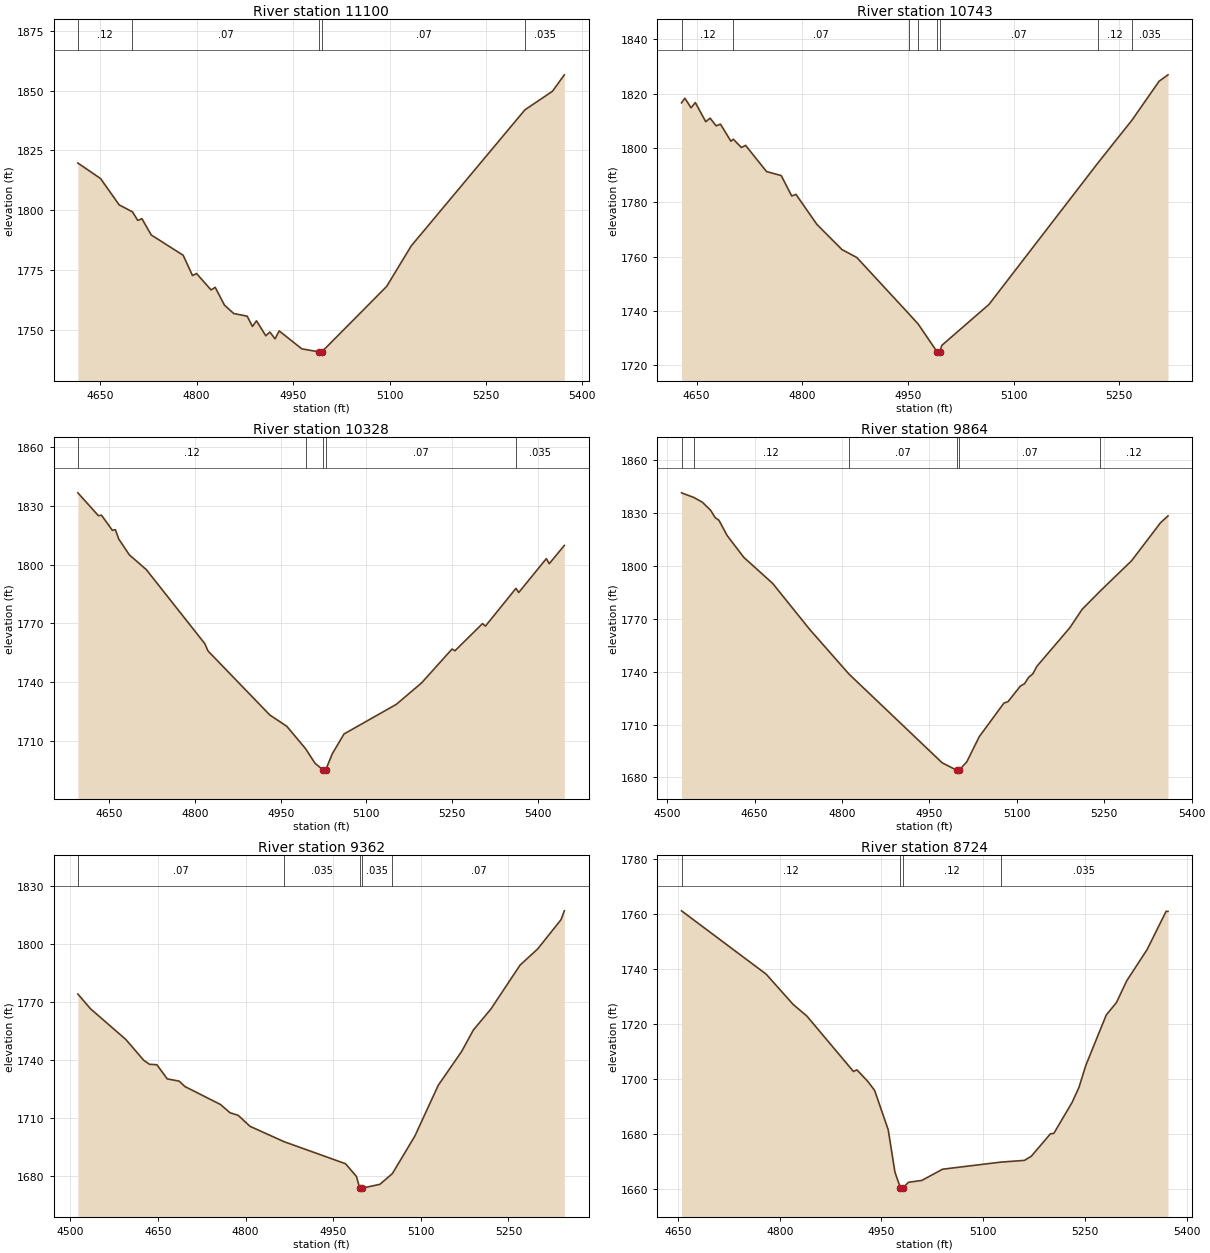
Type RM Length L Ch R = 1,11100,357,357,357
BEGIN DESCRIPTION:
Stream0150_DS 29.0
END DESCRIPTION:
XS GIS Cut Line= 3
      2074459.25     13936380.66      2074155.80     13936144.20
      2073827.70     13935969.10
#Sta/Elev= 30
  4615.3 1819.77  4650.6 1813.31  4679.6 1802.32  4700.2 1799.44  4708.5 1795.85
  4714.9 1796.59  4729.4 1789.80  4779.1 1781.33  4793.6 1772.87  4799.9 1773.72
  4822.5 1766.88  4828.9 1767.98  4843.3 1760.55  4857.8 1757.03  4878.6 1755.96
  4886.8 1751.66  4893.1 1754.01  4907.6 1747.78  4913.9 1749.33  4922.0 1746.50
  4928.4 1749.79  4963.7 1742.32  4990.6 1741.04  4990.9 1740.54  4994.6 1741.04
  5095.6 1768.36  5133.8 1785.24  5310.6 1841.95  5353.4 1849.68  5371.9 1856.54
#Mann=5,-1,0
  4615.3    0.12       0  4700.2    0.07       0  4990.6    0.05       0
  4994.6    0.07       0  5310.6   0.035       0
Bank Sta=4990.6,4994.6
Exp/Cntr=0.3,0.1

Type RM Length L Ch R = 1,10743,415,415,415
BEGIN DESCRIPTION:
Stream0150_DS 28.0
END DESCRIPTION:
XS GIS Cut Line= 3
      2074600.84     13936216.56      2074387.76     13935912.24
      2074132.71     13935720.31
#Sta/Elev= 30
  4628.5 1816.65  4633.2 1818.37  4642.0 1814.83  4648.1 1816.76  4662.9 1809.70
  4669.0 1811.03  4677.7 1808.18  4683.8 1808.81  4698.6 1802.53  4702.0 1803.28
  4713.4 1800.22  4719.5 1800.99  4749.2 1791.36  4770.1 1789.87  4784.9 1782.37
  4791.0 1782.95  4820.7 1771.90  4856.4 1762.62  4877.4 1759.71  4951.5 1738.92
  4964.5 1735.22  4991.3 1725.01  4991.6 1724.51  4995.3 1725.01  4998.0 1727.35
  5065.0 1742.44  5219.8 1794.56  5268.1 1810.31  5306.6 1824.62  5319.2 1826.97
#Mann=8,-1,0
  4628.5    0.12       0  4702.0    0.07       0  4951.5    0.12       0
  4964.5    0.07       0  4991.3    0.05       0  4995.3    0.07       0
  5219.8    0.12       0  5268.1   0.035       0
Bank Sta=4991.3,4995.3
Exp/Cntr=0.3,0.1

Type RM Length L Ch R = 1,10328,464,464,464
BEGIN DESCRIPTION:
Stream0150_DS 27.0
END DESCRIPTION:
XS GIS Cut Line= 3
      2075001.59     13935774.00      2074625.00     13935625.00
      2074185.53     13935544.98
#Sta/Elev= 30
  4595.0 1836.68  4631.0 1825.00  4636.4 1825.25  4655.4 1817.53  4660.7 1817.83
  4666.6 1813.08  4685.1 1804.99  4714.8 1797.45  4817.2 1759.62  4822.9 1755.85
  4931.1 1723.13  4960.8 1717.35  4993.7 1705.91  5010.2 1698.47  5024.7 1694.94
  5024.9 1694.44  5028.7 1694.94  5040.7 1703.45  5061.0 1713.42  5152.5 1728.57
  5196.8 1739.54  5250.1 1756.85  5255.2 1755.95  5303.4 1769.82  5308.5 1768.54
  5362.0 1787.85  5366.9 1785.74  5415.2 1803.06  5420.3 1800.47  5446.7 1809.81
#Mann=5,-1,0
  4595.0    0.12       0  4993.7    0.07       0  5024.7    0.05       0
  5028.7    0.07       0  5362.0   0.035       0
Bank Sta=5024.7,5028.7
Exp/Cntr=0.3,0.1

Type RM Length L Ch R = 1,9864,502,502,502
BEGIN DESCRIPTION:
Stream0150_DS 26.0
END DESCRIPTION:
XS GIS Cut Line= 3
      2075121.58     13935598.96      2074811.69     13935238.31
      2074556.46     13934985.27
#Sta/Elev= 30
  4524.5 1841.50  4545.3 1838.90  4560.1 1836.21  4574.4 1831.62  4582.1 1827.47
  4588.7 1825.92  4602.9 1817.20  4631.5 1804.83  4680.9 1790.10  4744.5 1763.96
  4811.7 1738.69  4971.7 1688.30  4996.9 1684.04  4997.1 1683.54  5000.9 1684.04
  5014.1 1688.83  5035.4 1703.08  5077.8 1722.16  5084.8 1722.98  5106.1 1731.84
  5113.1 1733.13  5120.2 1736.80  5127.3 1738.72  5134.4 1743.05  5190.9 1764.93
  5212.1 1775.42  5243.0 1785.73  5297.0 1802.99  5346.5 1824.50  5359.4 1828.40
#Mann=6,-1,0
  4524.5   0.035       0  4545.3    0.12       0  4811.7    0.07       0
  4996.9    0.05       0  5000.9    0.07       0  5243.0    0.12       0
Bank Sta=4996.9,5000.9
Exp/Cntr=0.3,0.1

Type RM Length L Ch R = 1,9362,638,638,638
BEGIN DESCRIPTION:
Stream0150_DS 25.0
END DESCRIPTION:
XS GIS Cut Line= 3
      2075506.19     13934900.62      2075025.00     13934825.00
      2074679.23     13934829.74
#Sta/Elev= 30
  4512.9 1774.18  4534.4 1766.60  4595.1 1750.70  4625.5 1740.02  4635.6 1737.90
  4648.2 1737.67  4666.0 1730.35  4686.2 1729.24  4696.3 1726.41  4757.1 1717.15
  4773.4 1712.89  4787.4 1711.56  4807.7 1705.88  4866.0 1697.95  4971.2 1686.58
  4989.9 1680.00  4995.5 1673.97  4995.7 1673.47  4999.5 1673.97  5030.0 1675.95
  5051.4 1681.49  5090.0 1700.92  5130.0 1727.10  5170.0 1744.53  5190.0 1755.58
  5220.0 1766.39  5270.0 1789.09  5300.0 1797.39  5340.0 1812.48  5345.8 1817.11
#Mann=5,-1,0
  4512.9    0.07       0  4866.0   0.035       0  4995.5   0.035       0
  4999.5   0.035       0  5051.4    0.07       0
Bank Sta=4995.5,4999.5
Exp/Cntr=0.3,0.1

Type RM Length L Ch R = 1,8724,492,492,492
BEGIN DESCRIPTION:
Stream0150_DS 24.0
END DESCRIPTION:
XS GIS Cut Line= 3
      2075469.75     13934304.41      2075125.00     13934298.50
      2074754.41     13934338.08
#Sta/Elev= 30
  4655.2 1761.28  4780.0 1738.20  4820.0 1727.12  4840.0 1722.94  4908.8 1702.72
  4913.8 1703.33  4930.0 1699.10  4940.0 1695.81  4960.0 1681.51  4970.0 1665.97
  4978.0 1660.34  4978.2 1659.84  4982.0 1660.34  4990.0 1662.34  5009.6 1663.01
  5040.2 1667.10  5125.8 1669.68  5160.9 1670.32  5171.0 1671.81  5199.3 1680.00
  5204.3 1680.16  5231.3 1691.48  5241.4 1696.96  5251.4 1704.89  5281.6 1723.31
  5296.6 1727.83  5311.8 1735.77  5341.9 1747.18  5369.9 1761.09  5372.7 1761.09
#Mann=4,-1,0
  4655.2    0.12       0  4978.0    0.05       0  4982.0    0.12       0
  5125.8   0.035       0
Bank Sta=4978,4982
Exp/Cntr=0.3,0.1

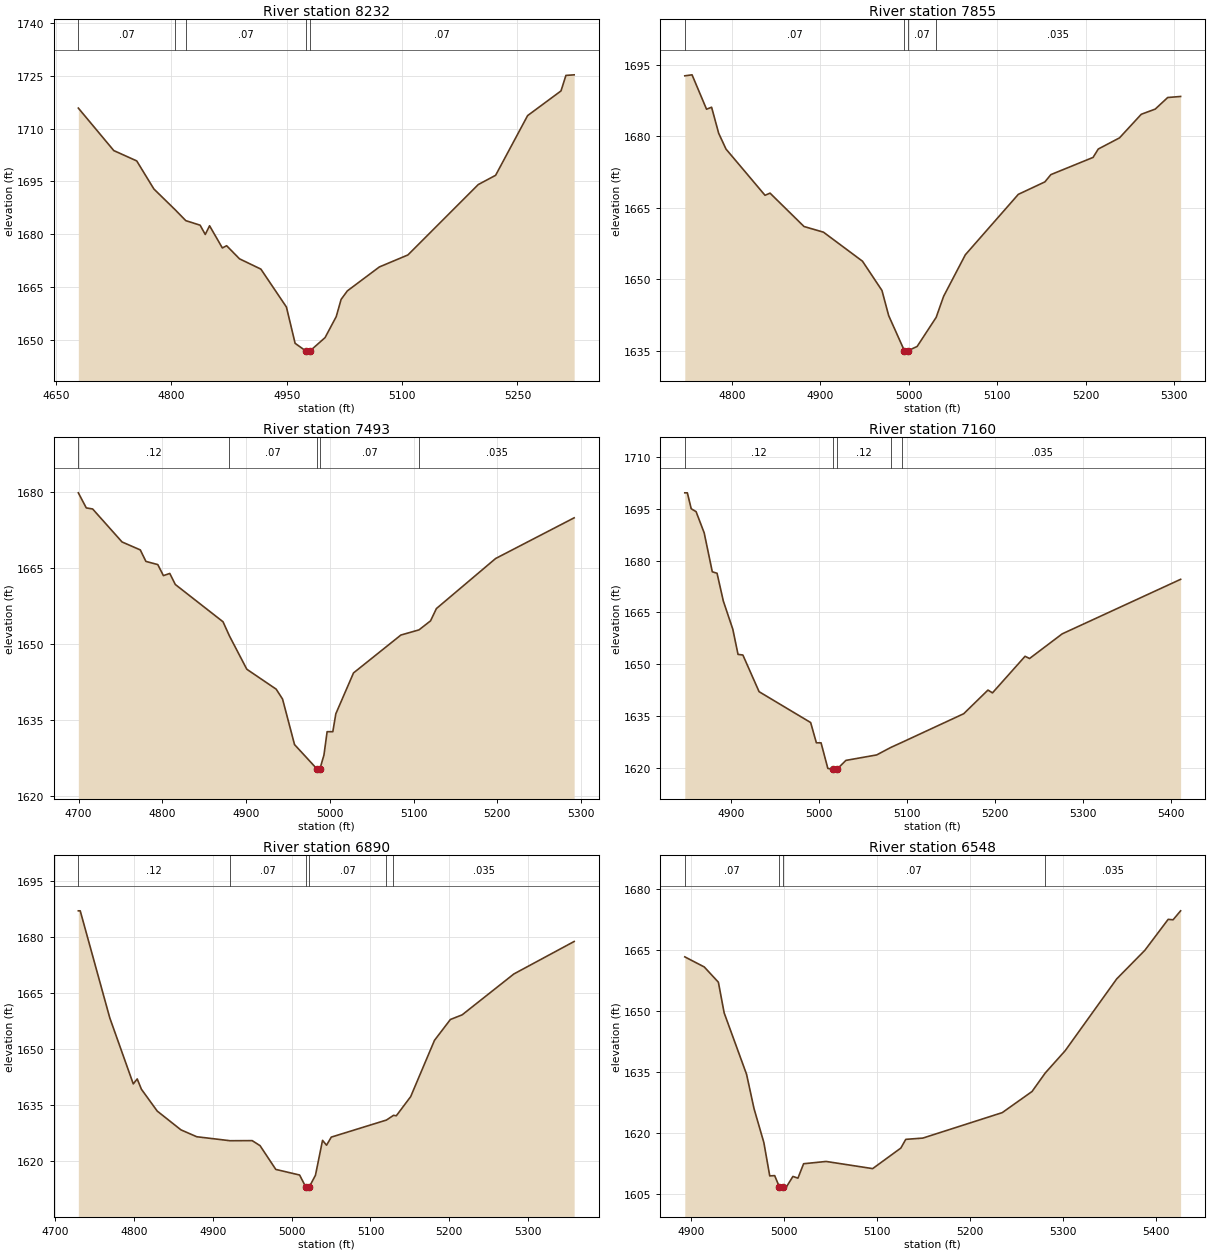
Type RM Length L Ch R = 1,8232,377,377,377
BEGIN DESCRIPTION:
Stream0150_DS 23.0
END DESCRIPTION:
XS GIS Cut Line= 3
      2075186.12     13933754.80      2074900.13     13933900.13
      2074644.88     13934099.21
#Sta/Elev= 30
  4679.2 1715.90  4725.3 1703.80  4755.1 1700.86  4777.4 1692.87  4805.2 1686.92
  4818.9 1683.85  4837.5 1682.56  4844.2 1679.92  4849.8 1682.39  4866.4 1676.08
  4872.0 1676.71  4888.7 1672.98  4916.5 1670.05  4949.7 1659.25  4961.0 1648.92
  4975.7 1646.63  4975.9 1646.13  4979.7 1646.63  4999.9 1650.54  5014.4 1656.51
  5020.8 1661.44  5028.9 1663.85  5070.5 1670.67  5107.6 1674.08  5199.0 1694.12
  5221.6 1696.76  5263.2 1713.76  5306.6 1720.79  5313.0 1725.20  5323.7 1725.37
#Mann=5,-1,0
  4679.2    0.07       0  4805.2    0.12       0  4818.9    0.07       0
  4975.7    0.05       0  4979.7    0.07       0
Bank Sta=4975.7,4979.7
Exp/Cntr=0.3,0.1

Type RM Length L Ch R = 1,7855,362,362,362
BEGIN DESCRIPTION:
Stream0150_DS 22.0
END DESCRIPTION:
XS GIS Cut Line= 3
      2074998.92     13933457.01      2074775.00     13933575.00
      2074488.22     13933685.95
#Sta/Elev= 30
  4746.9 1692.67  4755.1 1692.88  4771.5 1685.66  4777.2 1686.08  4785.2 1680.62
  4793.5 1677.30  4837.6 1667.60  4843.3 1668.05  4881.7 1661.05  4903.7 1659.86
  4947.8 1653.77  4969.8 1647.64  4977.4 1642.36  4995.2 1634.98  4995.4 1634.48
  4999.2 1634.98  5009.6 1635.88  5031.1 1641.98  5039.5 1646.39  5064.1 1655.12
  5124.0 1667.80  5154.0 1670.41  5160.8 1671.94  5208.5 1675.55  5214.4 1677.31
  5238.4 1679.65  5263.0 1684.60  5278.8 1685.69  5292.9 1688.12  5307.5 1688.34
#Mann=4,-1,0
  4746.9    0.07       0  4995.2    0.05       0  4999.2    0.07       0
  5031.1   0.035       0
Bank Sta=4995.2,4999.2
Exp/Cntr=0.3,0.1

Type RM Length L Ch R = 1,7493,333,333,333
BEGIN DESCRIPTION:
Stream0150_DS 21.0
END DESCRIPTION:
XS GIS Cut Line= 3
      2074851.00     13933077.10      2074625.00     13933275.00
      2074415.78     13933478.26
#Sta/Elev= 30
  4699.6 1679.89  4709.1 1676.91  4716.7 1676.70  4751.8 1670.18  4773.6 1668.61
  4780.3 1666.34  4794.5 1665.71  4801.2 1663.53  4808.8 1663.96  4815.4 1661.78
  4872.4 1654.41  4880.0 1651.63  4900.8 1645.03  4935.9 1641.09  4943.5 1639.13
  4957.8 1630.14  4984.2 1625.40  4984.5 1624.90  4988.2 1625.40  4992.9 1628.07
  4996.7 1632.69  5003.5 1632.69  5007.1 1636.23  5028.2 1644.30  5084.8 1651.79
  5106.4 1652.81  5120.2 1654.59  5127.2 1657.02  5197.9 1666.91  5291.7 1674.95
#Mann=5,-1,0
  4699.6    0.12       0  4880.0    0.07       0  4984.2    0.05       0
  4988.2    0.07       0  5106.4   0.035       0
Bank Sta=4984.2,4988.2
Exp/Cntr=0.3,0.1

Type RM Length L Ch R = 1,7160,270,270,270
BEGIN DESCRIPTION:
Stream0150_DS 20.0
END DESCRIPTION:
XS GIS Cut Line= 3
      2074483.43     13932884.68      2074425.00     13933025.00
      2074329.65     13933424.38
#Sta/Elev= 30
  4848.0 1699.56  4850.9 1699.56  4855.3 1694.95  4860.8 1694.13  4870.0 1687.99
  4879.2 1676.75  4884.6 1676.32  4891.7 1668.31  4902.5 1660.13  4908.4 1652.88
  4913.9 1652.70  4932.3 1642.10  4990.8 1633.19  4997.3 1627.33  5002.6 1627.33
  5010.3 1619.94  5016.5 1619.65  5016.7 1619.15  5020.5 1619.65  5030.8 1622.25
  5065.7 1623.83  5081.9 1626.01  5094.9 1627.52  5164.5 1635.74  5192.0 1642.57
  5197.1 1641.76  5234.1 1652.33  5239.2 1651.69  5276.2 1658.81  5410.6 1674.57
#Mann=5,-1,0
  4848.0    0.12       0  5016.5    0.05       0  5020.5    0.12       0
  5081.9    0.07       0  5094.9   0.035       0
Bank Sta=5016.5,5020.5
Exp/Cntr=0.3,0.1

Type RM Length L Ch R = 1,6890,342,342,342
BEGIN DESCRIPTION:
Stream0150_DS 19.0
END DESCRIPTION:
XS GIS Cut Line= 3
      2074154.31     13932805.19      2074175.00     13933075.00
      2074216.45     13933430.99
#Sta/Elev= 30
  4729.4 1687.10  4731.8 1687.10  4769.3 1658.43  4799.1 1640.75  4804.1 1642.08
  4809.4 1639.33  4829.5 1633.47  4859.6 1628.44  4879.6 1626.60  4922.0 1625.53
  4949.9 1625.56  4959.9 1624.22  4979.9 1617.85  5010.1 1616.35  5018.1 1613.07
  5018.4 1612.57  5022.1 1613.07  5030.2 1616.27  5039.2 1625.63  5044.3 1624.34
  5050.3 1626.50  5120.3 1631.07  5129.2 1632.33  5132.8 1632.22  5151.0 1637.34
  5181.2 1652.41  5201.4 1658.00  5216.3 1659.24  5281.9 1670.19  5358.4 1678.89
#Mann=6,-1,0
  4729.4    0.12       0  4922.0    0.07       0  5018.1    0.05       0
  5022.1    0.07       0  5120.3    0.07       0  5129.2   0.035       0
Bank Sta=5018.1,5022.1
Exp/Cntr=0.3,0.1

Type RM Length L Ch R = 1,6548,291,291,291
BEGIN DESCRIPTION:
Stream0150_DS 18.0
END DESCRIPTION:
XS GIS Cut Line= 3
      2073837.58     13932875.40      2073875.00     13932975.00
      2074023.90     13933374.66
#Sta/Elev= 30
  4893.6 1663.21  4914.5 1660.73  4929.7 1656.98  4935.9 1649.45  4960.0 1634.34
  4968.0 1625.92  4978.6 1617.55  4984.9 1609.38  4990.2 1609.45  4995.3 1606.63
  4995.6 1606.13  4999.3 1606.63  5002.7 1606.63  5009.8 1609.25  5015.2 1608.83
  5021.3 1612.37  5045.5 1612.93  5095.5 1611.17  5125.8 1616.22  5131.1 1618.36
  5149.4 1618.67  5234.8 1624.93  5266.8 1630.12  5281.0 1634.67  5302.4 1640.14
  5357.8 1657.79  5388.1 1664.83  5413.1 1672.42  5418.4 1672.32  5426.5 1674.52
#Mann=4,-1,0
  4893.6    0.07       0  4995.3    0.05       0  4999.3    0.07       0
  5281.0   0.035       0
Bank Sta=4995.3,4999.3
Exp/Cntr=0.3,0.1

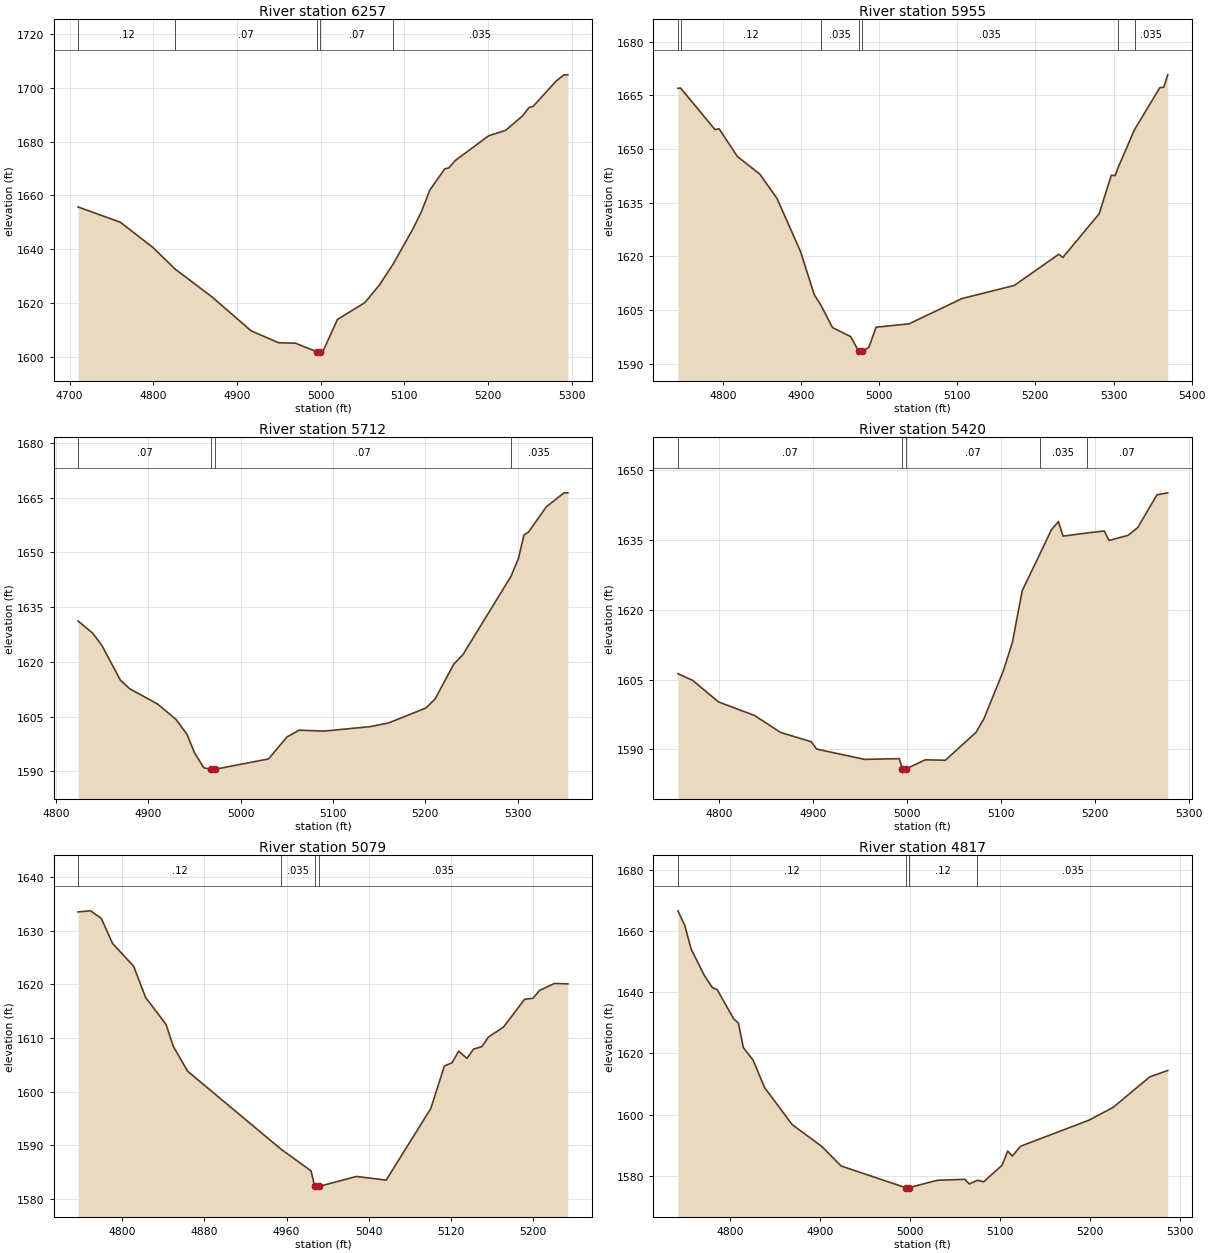
Type RM Length L Ch R = 1,6257,302,302,302
BEGIN DESCRIPTION:
Stream0150_DS 17.0
END DESCRIPTION:
XS GIS Cut Line= 3
      2073757.10     13932935.65      2073775.00     13933225.00
      2073804.36     13933518.94
#Sta/Elev= 30
  4710.1 1655.74  4760.8 1650.01  4799.6 1640.64  4826.0 1632.64  4869.8 1622.35
  4916.9 1609.63  4949.9 1605.19  4969.9 1605.03  4995.5 1601.83  4995.7 1601.33
  4999.5 1601.83  5002.5 1601.83  5020.1 1613.87  5052.8 1620.12  5070.3 1626.72
  5086.4 1634.37  5110.5 1647.69  5120.6 1654.10  5130.6 1662.11  5148.3 1669.92
  5153.3 1670.27  5160.8 1673.02  5201.0 1682.25  5221.1 1684.25  5241.2 1689.59
  5248.9 1692.74  5253.9 1693.16  5281.4 1702.60  5290.9 1704.90  5295.4 1704.90
#Mann=5,-1,0
  4710.1    0.12       0  4826.0    0.07       0  4995.5    0.05       0
  4999.5    0.07       0  5086.4   0.035       0
Bank Sta=4995.5,4999.5
Exp/Cntr=0.3,0.1

Type RM Length L Ch R = 1,5955,243,243,243
BEGIN DESCRIPTION:
Stream0150_DS 16.0
END DESCRIPTION:
XS GIS Cut Line= 3
      2073651.44     13932811.70      2073546.94     13933046.94
      2073488.67     13933411.72
#Sta/Elev= 30
  4742.6 1667.01  4746.0 1667.08  4790.0 1655.47  4795.4 1655.67  4818.7 1647.95
  4847.4 1643.01  4869.3 1636.27  4899.4 1621.43  4917.2 1609.26  4925.6 1606.37
  4940.4 1600.13  4963.7 1597.60  4974.0 1593.48  4974.2 1592.98  4978.0 1593.48
  4986.9 1594.57  4996.2 1600.23  5038.5 1601.17  5105.9 1608.22  5173.0 1611.90
  5230.0 1620.62  5235.1 1619.72  5281.6 1631.92  5297.2 1642.71  5302.2 1642.63
  5305.3 1644.56  5326.9 1655.46  5359.3 1667.19  5364.3 1667.29  5369.4 1670.77
#Mann=7,-1,0
  4742.6    0.07       0  4746.0    0.12       0  4925.6   0.035       0
  4974.0   0.035       0  4978.0   0.035       0  5305.3    0.07       0
  5326.9   0.035       0
Bank Sta=4974,4978
Exp/Cntr=0.3,0.1

Type RM Length L Ch R = 1,5712,292,292,292
BEGIN DESCRIPTION:
Stream0150_DS 15.0
END DESCRIPTION:
XS GIS Cut Line= 3
      2073360.63     13932899.29      2073375.00     13933075.00
      2073403.80     13933428.33
#Sta/Elev= 30
  4823.7 1631.23  4839.5 1627.92  4849.5 1624.54  4869.6 1615.01  4879.6 1612.67
  4909.7 1608.51  4929.8 1604.28  4941.7 1600.19  4949.8 1595.20  4959.9 1591.01
  4967.9 1590.58  4968.1 1590.08  4971.9 1590.58  5030.1 1593.42  5050.2 1599.46
  5063.4 1601.30  5090.3 1601.05  5140.5 1602.28  5160.5 1603.31  5200.7 1607.39
  5210.7 1609.89  5230.8 1619.37  5240.8 1622.02  5292.8 1643.44  5301.0 1648.42
  5306.9 1654.79  5311.9 1655.61  5331.1 1662.50  5350.3 1666.35  5354.5 1666.35
#Mann=4,-1,0
  4823.7    0.07       0  4967.9    0.05       0  4971.9    0.07       0
  5292.8   0.035       0
Bank Sta=4967.9,4971.9
Exp/Cntr=0.3,0.1

Type RM Length L Ch R = 1,5420,341,341,341
BEGIN DESCRIPTION:
Stream0150_DS 14.0
END DESCRIPTION:
XS GIS Cut Line= 3
      2073239.00     13932959.38      2073125.00     13933175.00
      2073065.60     13933446.27
#Sta/Elev= 30
  4756.1 1606.29  4771.7 1604.85  4799.4 1600.20  4837.8 1597.29  4865.4 1593.65
  4898.1 1591.65  4903.8 1590.07  4954.8 1587.86  4991.8 1588.01  4995.2 1585.83
  4995.4 1585.33  4999.2 1585.83  5019.4 1587.76  5040.9 1587.67  5073.5 1593.66
  5081.9 1596.57  5102.4 1606.76  5112.2 1612.96  5122.8 1624.16  5141.7 1632.07
  5153.6 1637.13  5161.2 1638.97  5166.3 1635.84  5191.4 1636.51  5210.1 1636.96
  5215.2 1634.91  5235.4 1636.01  5245.7 1637.67  5266.2 1644.72  5277.7 1645.15
#Mann=5,-1,0
  4756.1    0.07       0  4995.2    0.05       0  4999.2    0.07       0
  5141.7   0.035       0  5191.4    0.07       0
Bank Sta=4995.2,4999.2
Exp/Cntr=0.3,0.1

Type RM Length L Ch R = 1,5079,262,262,262
BEGIN DESCRIPTION:
Stream0150_DS 13.0
END DESCRIPTION:
XS GIS Cut Line= 3
      2073306.67     13932851.32      2073075.00     13932925.00
      2072889.80     13933068.19
#Sta/Elev= 30
  4756.9 1633.51  4769.1 1633.71  4779.6 1632.29  4790.5 1627.64  4811.1 1623.38
  4822.7 1617.57  4842.6 1612.55  4849.7 1608.45  4863.6 1603.82  4954.9 1589.24
  4983.9 1585.24  4987.5 1582.33  4987.8 1581.83  4991.5 1582.33  5028.1 1584.19
  5057.1 1583.51  5100.5 1596.84  5113.8 1604.79  5121.3 1605.39  5127.7 1607.56
  5135.8 1606.21  5142.2 1607.93  5150.3 1608.39  5156.7 1610.18  5171.2 1612.01
  5192.0 1617.23  5200.1 1617.41  5206.5 1618.87  5221.0 1620.17  5234.1 1620.10
#Mann=4,-1,0
  4756.9    0.12       0  4954.9   0.035       0  4987.5   0.035       0
  4991.5   0.035       0
Bank Sta=4987.5,4991.5
Exp/Cntr=0.3,0.1

Type RM Length L Ch R = 1,4817,160,160,160
BEGIN DESCRIPTION:
Stream0150_DS 12.0
END DESCRIPTION:
XS GIS Cut Line= 3
      2073026.50     13932488.13      2072925.00     13932725.00
      2072859.75     13933004.28
#Sta/Elev= 30
  4742.3 1666.52  4749.8 1661.85  4757.0 1654.04  4771.5 1645.50  4780.6 1641.47
  4786.0 1640.77  4804.2 1631.30  4809.6 1629.86  4815.0 1621.86  4825.9 1617.78
  4838.6 1608.83  4869.4 1596.70  4902.1 1589.63  4923.8 1583.20  4995.3 1576.16
  4995.5 1575.66  4999.3 1576.16  5030.8 1578.55  5061.2 1578.86  5066.3 1577.34
  5075.3 1578.56  5082.2 1578.05  5102.7 1583.48  5108.9 1588.10  5114.0 1586.45
  5123.2 1589.66  5199.0 1598.15  5225.9 1602.31  5267.0 1612.35  5286.8 1614.40
#Mann=4,-1,0
  4742.3    0.12       0  4995.3    0.05       0  4999.3    0.12       0
  5075.3   0.035       0
Bank Sta=4995.3,4999.3
Exp/Cntr=0.3,0.1

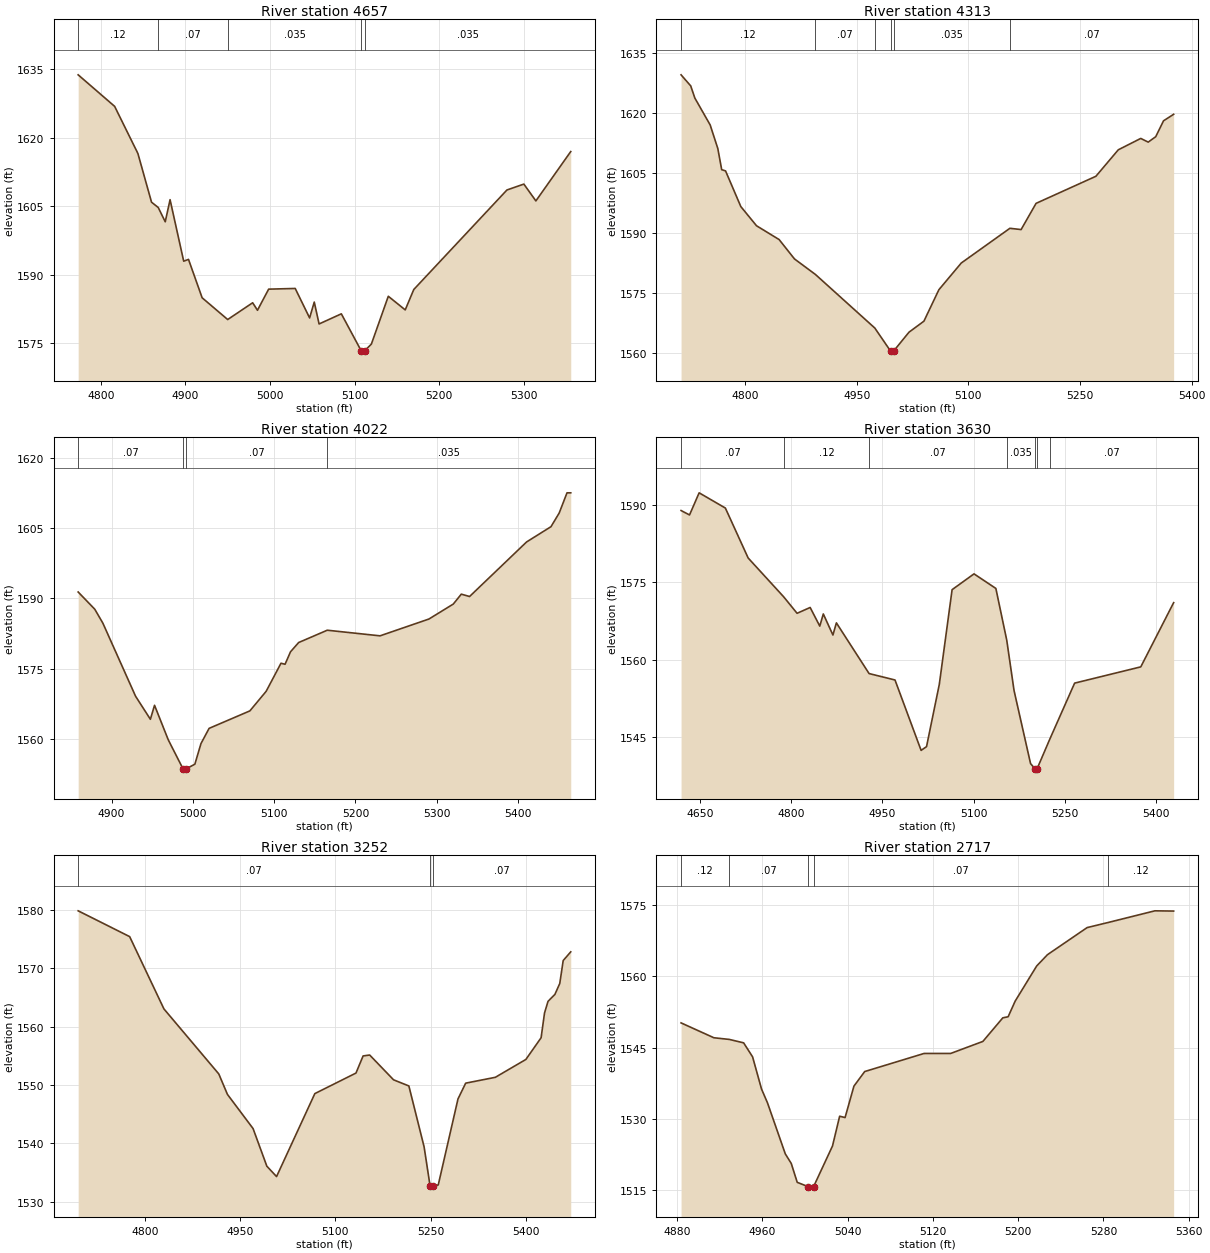
Type RM Length L Ch R = 1,4657,344,344,344
BEGIN DESCRIPTION:
Stream0150_DS 11.0
END DESCRIPTION:
XS GIS Cut Line= 4
      2072688.34     13932503.99      2072797.11     13932702.89
      2072830.34     13932771.17      2072818.17     13933050.37
#Sta/Elev= 30
  4773.3 1633.72  4816.4 1626.82  4843.9 1616.50  4860.0 1605.85  4867.9 1604.69
  4876.2 1601.56  4881.9 1606.40  4898.0 1592.94  4903.7 1593.33  4919.8 1584.93
  4950.0 1580.17  4979.5 1583.84  4985.2 1582.20  4998.4 1586.82  5029.8 1586.97
  5046.8 1580.52  5052.3 1583.99  5058.0 1579.20  5084.3 1581.42  5107.8 1573.32
  5108.0 1572.82  5111.8 1573.32  5119.8 1574.80  5139.8 1585.26  5159.8 1582.28
  5169.9 1586.74  5280.0 1608.52  5300.0 1609.81  5314.2 1606.13  5355.4 1616.93
#Mann=5,-1,0
  4773.3    0.12       0  4867.9    0.07       0  4950.0   0.035       0
  5107.8   0.035       0  5111.8   0.035       0
Bank Sta=5107.8,5111.8
Exp/Cntr=0.3,0.1

Type RM Length L Ch R = 1,4313,291,291,291
BEGIN DESCRIPTION:
Stream0150_DS 10.0
END DESCRIPTION:
XS GIS Cut Line= 3
      2072593.00     13932496.99      2072525.00     13932775.00
      2072488.22     13933149.00
#Sta/Elev= 30
  4713.8 1629.43  4726.8 1626.66  4732.3 1623.64  4752.9 1616.92  4763.2 1611.02
  4768.4 1605.75  4773.6 1605.44  4794.1 1596.54  4815.2 1591.75  4845.6 1588.30
  4866.2 1583.47  4894.3 1579.60  4974.2 1566.21  4995.4 1560.45  4995.7 1559.95
  4999.4 1560.45  5020.1 1565.17  5040.2 1567.93  5060.3 1575.78  5090.4 1582.45
  5155.7 1591.11  5170.8 1590.80  5190.9 1597.34  5271.3 1604.10  5301.4 1610.71
  5331.6 1613.55  5341.6 1612.63  5351.7 1613.98  5362.2 1617.95  5375.8 1619.58
#Mann=6,-1,0
  4713.8    0.12       0  4894.3    0.07       0  4974.2   0.035       0
  4995.4   0.035       0  4999.4   0.035       0  5155.7    0.07       0
Bank Sta=4995.4,4999.4
Exp/Cntr=0.3,0.1

Type RM Length L Ch R = 1,4022,392,392,392
BEGIN DESCRIPTION:
Stream0150_DS 9.0
END DESCRIPTION:
XS GIS Cut Line= 3
      2072289.38     13932534.74      2072275.00     13932675.00
      2072254.19     13933139.23
#Sta/Elev= 30
  4859.0 1591.35  4879.4 1587.68  4889.4 1584.69  4929.6 1569.09  4947.8 1564.17
  4952.9 1567.16  4969.8 1559.78  4987.9 1553.60  4988.2 1553.10  4991.9 1553.60
  5002.5 1554.58  5010.0 1558.98  5020.0 1562.23  5070.1 1565.96  5090.1 1570.13
  5108.4 1576.14  5113.4 1575.92  5120.1 1578.58  5130.1 1580.56  5165.3 1583.19
  5230.2 1581.99  5290.3 1585.58  5320.3 1588.78  5330.1 1590.89  5340.3 1590.39
  5410.4 1602.04  5440.4 1605.30  5450.5 1608.22  5460.1 1612.53  5464.7 1612.53
#Mann=4,-1,0
  4859.0    0.07       0  4987.9    0.05       0  4991.9    0.07       0
  5165.3   0.035       0
Bank Sta=4987.9,4991.9
Exp/Cntr=0.3,0.1

Type RM Length L Ch R = 1,3630,378,378,378
BEGIN DESCRIPTION:
Stream0150_DS 8.0
END DESCRIPTION:
XS GIS Cut Line= 3
      2072254.95     13932484.69      2071925.00     13932675.00
      2071570.25     13932915.16
#Sta/Elev= 30
  4619.1 1588.97  4633.0 1588.11  4648.8 1592.41  4691.9 1589.45  4729.3 1579.75
  4787.7 1572.20  4809.7 1569.00  4831.2 1570.13  4847.0 1566.51  4852.8 1568.87
  4868.6 1564.78  4874.3 1567.14  4928.0 1557.29  4970.6 1556.04  5013.5 1542.36
  5022.4 1543.09  5043.4 1555.20  5064.4 1573.59  5100.4 1576.66  5136.3 1573.83
  5154.2 1563.77  5166.2 1553.98  5193.3 1539.80  5200.2 1538.83  5200.4 1538.33
  5204.2 1538.83  5224.5 1544.43  5265.7 1555.43  5374.4 1558.59  5428.4 1571.07
#Mann=7,-1,0
  4619.1    0.07       0  4787.7    0.12       0  4928.0    0.07       0
  5154.2   0.035       0  5200.2    0.05       0  5204.2   0.035       0
  5224.5    0.07       0
Bank Sta=5200.2,5204.2
Exp/Cntr=0.3,0.1

Type RM Length L Ch R = 1,3252,535,535,535
BEGIN DESCRIPTION:
Stream0150_DS 7.0
END DESCRIPTION:
XS GIS Cut Line= 2
      2071807.93     13932109.94      2071514.34     13932828.15
#Sta/Elev= 30
  4694.8 1579.85  4775.9 1575.43  4829.9 1563.04  4916.3 1551.90  4929.9 1548.40
  4970.3 1542.54  4992.0 1536.09  5007.3 1534.31  5067.6 1548.53  5132.4 1552.05
  5143.6 1554.98  5154.0 1555.14  5191.6 1550.89  5215.7 1549.84  5239.7 1539.41
  5249.2 1532.66  5249.5 1532.16  5253.2 1532.66  5262.0 1532.88  5293.1 1547.62
  5305.2 1550.32  5351.9 1551.32  5400.0 1554.38  5424.0 1558.10  5429.4 1562.34
  5434.9 1564.34  5445.7 1565.52  5453.4 1567.40  5458.8 1571.33  5470.7 1572.82
#Mann=3,-1,0
  4694.8    0.07       0  5249.2    0.05       0  5253.2    0.07       0
Bank Sta=5249.2,5253.2
Exp/Cntr=0.3,0.1

Type RM Length L Ch R = 1,2717,420,420,420
BEGIN DESCRIPTION:
Stream0150_DS 6.0
END DESCRIPTION:
XS GIS Cut Line= 3
      2071275.00     13932124.99      2071225.00     13932225.00
      2071179.76     13932572.46
#Sta/Elev= 30
  4883.7 1550.18  4914.5 1547.05  4929.0 1546.70  4942.4 1545.98  4950.8 1543.04
  4959.2 1536.26  4964.8 1533.35  4981.5 1522.62  4987.1 1520.60  4992.7 1516.63
  5003.2 1515.70  5003.5 1515.20  5008.0 1515.70  5025.8 1524.28  5032.5 1530.54
  5037.6 1530.26  5045.9 1536.87  5056.0 1539.94  5111.6 1543.74  5136.7 1543.75
  5166.9 1546.28  5185.6 1551.24  5190.6 1551.47  5197.2 1554.76  5217.4 1562.16
  5227.5 1564.53  5264.7 1570.23  5284.7 1571.32  5328.3 1573.76  5345.9 1573.71
#Mann=5,-1,0
  4883.7    0.12       0  4929.0    0.07       0  5003.2    0.05       0
  5008.0    0.07       0  5284.7    0.12       0
Bank Sta=5003.2,5008
Exp/Cntr=0.3,0.1

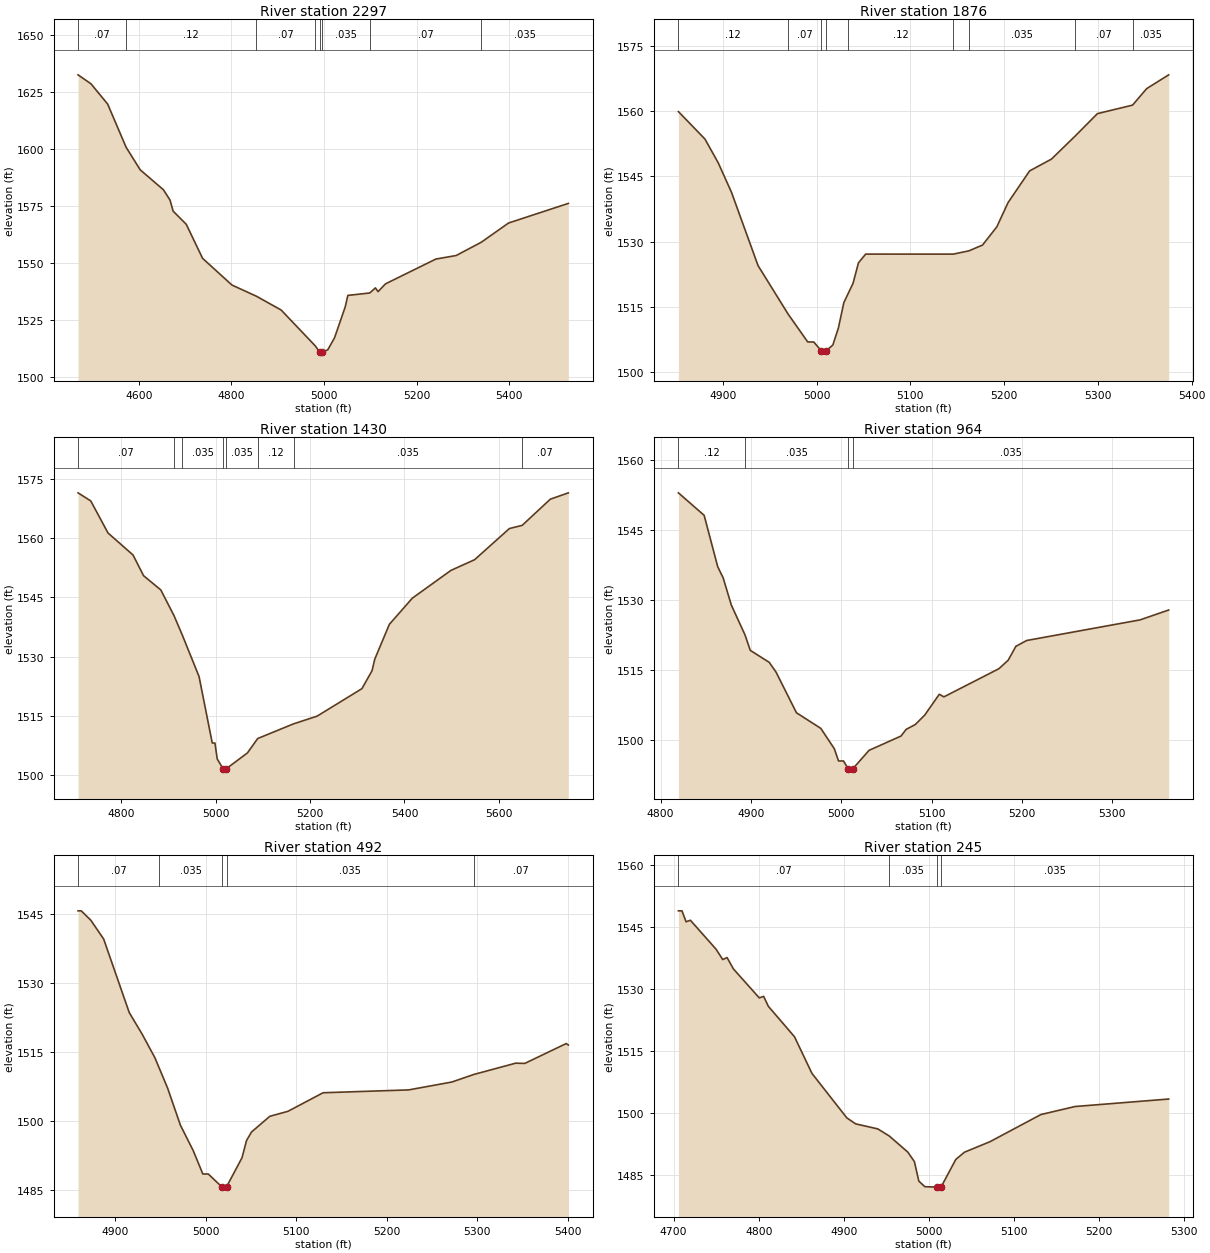
Type RM Length L Ch R = 1,2297,421,421,421
BEGIN DESCRIPTION:
Stream0150_DS 5.0
END DESCRIPTION:
XS GIS Cut Line= 3
      2071224.99     13931625.01      2070875.00     13932025.00
      2070619.80     13932487.13
#Sta/Elev= 30
  4468.5 1632.62  4496.5 1628.66  4532.5 1619.77  4572.3 1600.83  4602.8 1590.89
  4653.1 1582.11  4667.3 1577.57  4674.0 1572.73  4702.4 1566.94  4737.6 1552.01
  4801.1 1540.27  4853.8 1535.38  4907.4 1529.30  4981.1 1513.55  4990.4 1510.87
  4990.8 1510.37  4995.3 1510.87  5008.0 1511.79  5022.8 1517.15  5045.7 1530.62
  5051.5 1535.72  5098.7 1536.79  5111.1 1539.02  5116.8 1537.38  5132.9 1540.81
  5241.7 1551.69  5285.6 1553.25  5339.9 1559.09  5398.7 1567.52  5527.9 1576.14
#Mann=8,-1,0
  4468.5    0.07       0  4572.3    0.12       0  4853.8    0.07       0
  4981.1   0.035       0  4990.4   0.035       0  4995.3   0.035       0
  5098.7    0.07       0  5339.9   0.035       0
Bank Sta=4990.4,4995.3
Exp/Cntr=0.3,0.1

Type RM Length L Ch R = 1,1876,446,446,446
BEGIN DESCRIPTION:
Stream0150_DS 4.0
END DESCRIPTION:
XS GIS Cut Line= 3
      2070775.00     13931575.00      2070675.00     13931675.00
      2070479.27     13932002.32
#Sta/Elev= 30
  4852.7 1559.93  4881.0 1553.61  4895.1 1548.17  4909.3 1541.36  4937.6 1524.50
  4969.7 1513.33  4990.6 1506.92  4997.0 1506.92  5005.2 1504.85  5005.6 1504.35
  5010.2 1504.85  5017.4 1506.23  5023.3 1510.14  5029.1 1515.97  5033.2 1517.83
  5038.9 1520.41  5044.7 1525.13  5052.4 1527.14  5145.7 1527.13  5162.4 1527.88
  5177.0 1529.22  5192.2 1533.40  5204.2 1538.98  5227.2 1546.28  5250.5 1549.00
  5275.9 1554.33  5299.5 1559.46  5337.0 1561.42  5352.0 1565.21  5375.5 1568.39
#Mann=9,-1,0
  4852.7    0.12       0  4969.7    0.07       0  5005.2    0.05       0
  5010.2    0.07       0  5033.2    0.12       0  5145.7    0.07       0
  5162.4   0.035       0  5275.9    0.07       0  5337.0   0.035       0
Bank Sta=5005.2,5010.2
Exp/Cntr=0.3,0.1

Type RM Length L Ch R = 1,1430,466,466,466
BEGIN DESCRIPTION:
Stream0150_DS 3.0
END DESCRIPTION:
XS GIS Cut Line= 3
      2070681.71     13931196.78      2070425.00     13931325.00
      2070035.87     13931967.61
#Sta/Elev= 30
  4708.8 1571.55  4735.7 1569.50  4772.2 1561.37  4825.2 1555.78  4847.6 1550.52
  4884.0 1546.92  4911.9 1540.42  4929.4 1535.51  4965.0 1524.96  4993.0 1508.08
  4998.7 1508.08  5003.5 1504.04  5016.4 1501.45  5016.8 1500.95  5021.5 1501.45
  5067.5 1505.57  5089.2 1509.22  5165.1 1512.94  5214.9 1514.89  5309.9 1521.87
  5331.3 1526.41  5337.1 1529.35  5368.1 1538.20  5416.6 1544.82  5498.4 1551.87
  5548.5 1554.58  5622.2 1562.49  5649.3 1563.30  5708.9 1569.94  5747.0 1571.54
#Mann=8,-1,0
  4708.8    0.07       0  4911.9    0.12       0  4929.4   0.035       0
  5016.4   0.035       0  5021.5   0.035       0  5089.2    0.12       0
  5165.1   0.035       0  5649.3    0.07       0
Bank Sta=5016.4,5021.5
Exp/Cntr=0.3,0.1

Type RM Length L Ch R = 1,964,472,472,472
BEGIN DESCRIPTION:
Stream0150_DS 2.0
END DESCRIPTION:
XS GIS Cut Line= 3
      2070124.99     13930975.02      2070025.00     13931125.00
      2069942.11     13931478.04
#Sta/Elev= 30
  4819.7 1553.04  4848.2 1548.21  4863.2 1537.20  4869.3 1534.76  4878.3 1528.95
  4893.5 1522.52  4899.3 1519.23  4920.3 1516.65  4927.8 1514.57  4950.4 1505.84
  4977.4 1502.48  4992.4 1498.10  4997.0 1495.49  5002.5 1495.49  5007.7 1493.81
  5008.1 1493.31  5012.8 1493.81  5030.8 1497.77  5066.2 1500.84  5071.9 1502.27
  5082.1 1503.33  5092.4 1505.32  5108.6 1509.81  5113.7 1509.25  5174.6 1515.29
  5184.9 1517.12  5193.4 1520.10  5205.4 1521.35  5330.9 1525.77  5362.6 1527.89
#Mann=4,-1,0
  4819.7    0.12       0  4893.5   0.035       0  5007.7   0.035       0
  5012.8   0.035       0
Bank Sta=5007.7,5012.8
Exp/Cntr=0.3,0.1

Type RM Length L Ch R = 1,492,247,247,247
BEGIN DESCRIPTION:
Stream0150_DS 1.0
END DESCRIPTION:
XS GIS Cut Line= 3
      2069775.00     13930725.00      2069675.00     13930825.00
      2069629.81     13931222.82
#Sta/Elev= 30
  4858.8 1545.59  4862.3 1545.59  4872.9 1543.55  4887.1 1539.46  4915.4 1523.46
  4929.5 1518.83  4943.6 1513.70  4948.3 1511.50  4957.8 1507.04  4971.9 1499.00
  4986.1 1493.45  4996.7 1488.38  5002.7 1488.38  5017.7 1485.59  5018.1 1485.09
  5022.5 1485.09  5022.9 1485.59  5040.0 1491.92  5045.0 1495.67  5050.5 1497.51
  5070.7 1500.92  5090.8 1502.01  5129.6 1506.04  5224.2 1506.66  5272.0 1508.38
  5296.4 1510.03  5342.4 1512.47  5352.5 1512.42  5398.3 1516.74  5400.6 1516.42
#Mann=5,-1,0
  4858.8    0.07       0  4948.3   0.035       0  5017.7   0.035       0
  5022.9   0.035       0  5296.4    0.07       0
Bank Sta=5017.7,5022.9
Exp/Cntr=0.3,0.1

Type RM Length L Ch R = 1,245,0,0,0
BEGIN DESCRIPTION:
Stream0150_DS 0.0
END DESCRIPTION:
XS GIS Cut Line= 3
      2069768.10     13930617.84      2069481.04     13930683.18
      2069470.06     13930965.06
#Sta/Elev= 30
  4705.6 1548.97  4709.8 1548.97  4714.6 1546.32  4719.7 1546.69  4749.8 1539.70
  4757.7 1537.18  4762.8 1537.66  4770.3 1534.91  4800.7 1527.90  4805.8 1528.28
  4811.3 1525.88  4842.1 1518.50  4862.6 1509.64  4903.6 1498.88  4913.9 1497.43
  4940.1 1496.20  4953.5 1494.49  4975.4 1490.58  4983.1 1488.28  4988.3 1483.56
  4995.4 1482.22  5009.2 1482.13  5009.6 1481.63  5014.4 1482.13  5031.8 1488.82
  5041.9 1490.56  5071.9 1493.10  5131.9 1499.68  5172.0 1501.62  5282.1 1503.43
#Mann=4,-1,0
  4705.6    0.07       0  4953.5   0.035       0  5009.2   0.035       0
  5014.4   0.035       0
Bank Sta=5009.2,5014.4
Exp/Cntr=0.3,0.1

Chan Stop Cuts=-1