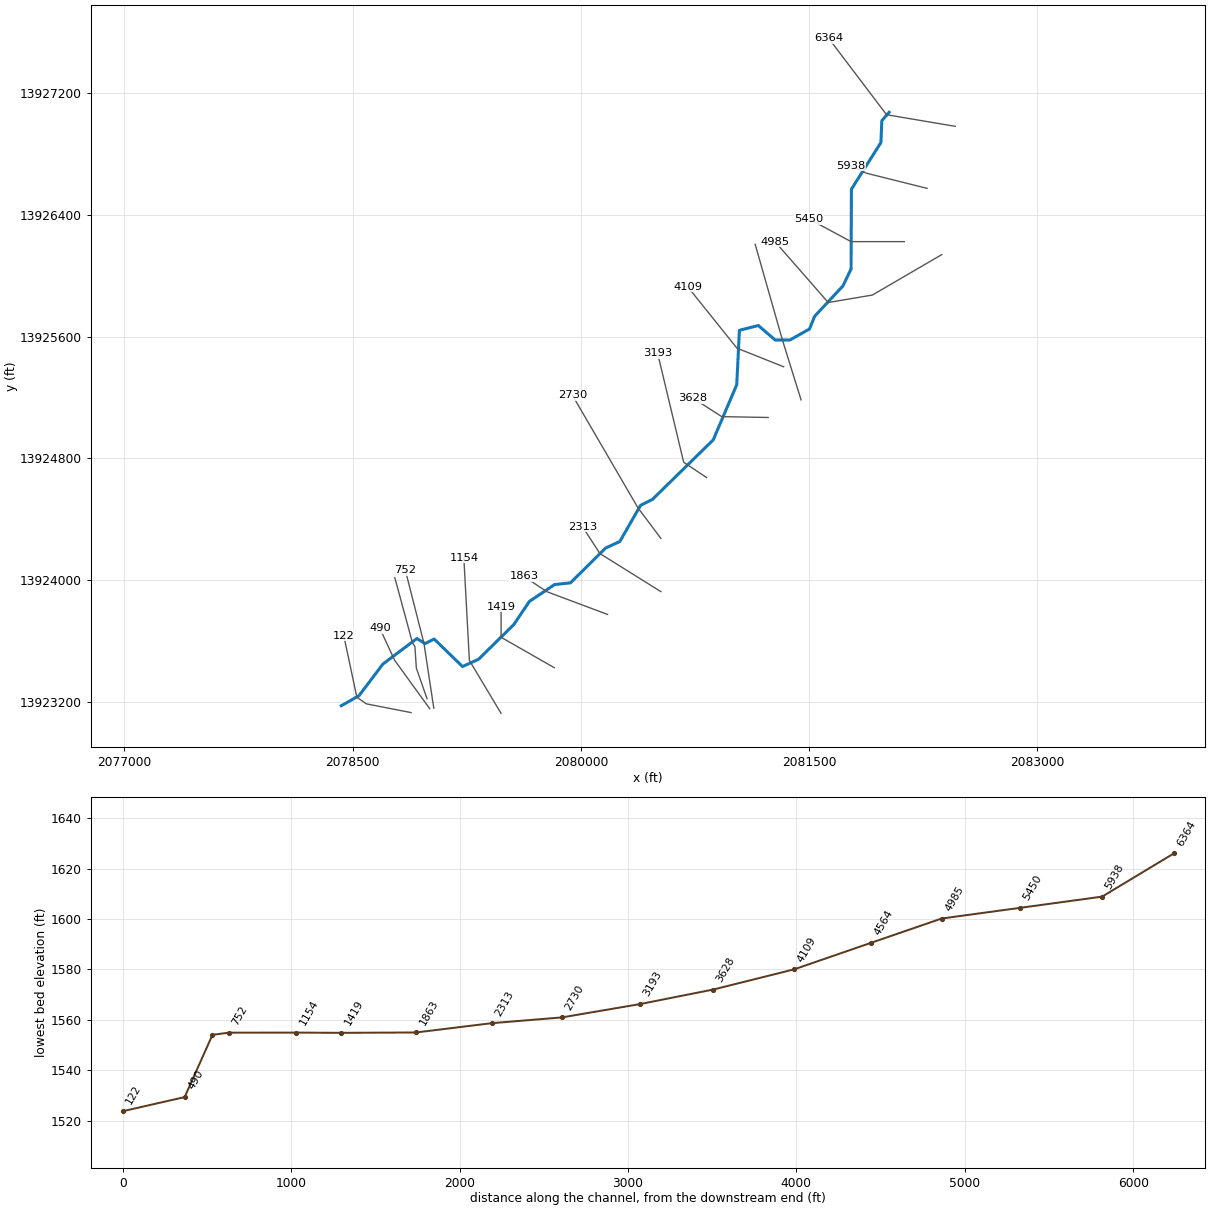
--- Stream0151_DS.prj (project) ---

Proj Title=Stream0151_DS Base Level Engineering
Current Plan=p01
Default Exp/Contr=0.3,0.1
English Units
Geom File=g01
Flow File=f01
Plan File=p01
BEGIN DESCRIPTION:
Stream0151_DS
END DESCRIPTION:

--- Stream0151_DS.p01 (plan) ---

Plan Title=Multiple Run
Short Identifier=Multiple
Geom File=g01
Flow File=f01
Subcritical Flow
K Sum by GR= 0
Std Step Tol= 0.01
Critical Tol= 0.01
Num of Std Step Trials= 20
Max Error Tol= 0.3
Flow Tol Ratio= 0.001
Split Flow NTrial= 30
Split Flow Tol= 0.02
Split Flow Ratio= 0.02
Log Output Level= 0
Friction Slope Method= 1
Unsteady Friction Slope Method= 2
Unsteady Bridges Friction Slope Method= 1
Parabolic Critical Depth
Global Vel Dist=  1 , 1 , 1
Global Log Level= 0
CheckData=True
Encroach Param= -1, 0, 0, 0
BEGIN DESCRIPTION:
Multiple Run
END DESCRIPTION:

--- Stream0151_DS.f01 (steady flow) ---

Flow Title=Multiple
Number of Profiles=7
Profile Names=10-year,25-year,50-year,1pct_min,100-year,1pct_plu,500-year
River Rch & RM= Stream0151_DS,Reach-1,6364
    1209    2095    2960    2030    4050    8081    7514
River Rch & RM= Stream0151_DS,Reach-1,5938
    1635    2866    4078    2812    5611   11196   10537
Boundary for River Rch & Prof#=Stream0151_DS,Reach-1,1
Up Type=0
Dn Type=3
Dn Slope=0.005
Boundary for River Rch & Prof#=Stream0151_DS,Reach-1,2
Up Type=0
Dn Type=3
Dn Slope=0.005
Boundary for River Rch & Prof#=Stream0151_DS,Reach-1,3
Up Type=0
Dn Type=3
Dn Slope=0.005
Boundary for River Rch & Prof#=Stream0151_DS,Reach-1,4
Up Type=0
Dn Type=3
Dn Slope=0.005
Boundary for River Rch & Prof#=Stream0151_DS,Reach-1,5
Up Type=0
Dn Type=3
Dn Slope=0.005
Boundary for River Rch & Prof#=Stream0151_DS,Reach-1,6
Up Type=0
Dn Type=3
Dn Slope=0.005
Boundary for River Rch & Prof#=Stream0151_DS,Reach-1,7
Up Type=0
Dn Type=3
Dn Slope=0.005

--- Stream0151_DS.g01 (geometry) ---

Geom Title=Existing Conditions

River Reach=Stream0151_DS,Reach-1
Reach XY= 30
      2082025.00     13927075.00      2081976.91     13927019.21
      2081971.25     13926876.56      2081777.18     13926569.55
      2081774.94     13926045.01      2081721.16     13925933.62
      2081535.79     13925734.66      2081502.14     13925651.16
      2081373.42     13925578.67      2081276.50     13925578.47
      2081165.36     13925673.91      2081041.24     13925642.24
      2081023.62     13925284.66      2080869.23     13924922.47
      2080469.34     13924530.66      2080391.58     13924492.02
      2080255.37     13924254.53      2080161.80     13924211.36
      2079931.17     13923982.86      2079826.50     13923971.37
      2079661.76     13923861.38      2079558.35     13923708.33
      2079327.29     13923480.80      2079221.59     13923432.77
      2079035.00     13923613.77      2078975.00     13923583.05
      2078921.67     13923617.02      2078698.12     13923448.73
      2078541.72     13923241.60      2078425.00     13923175.00

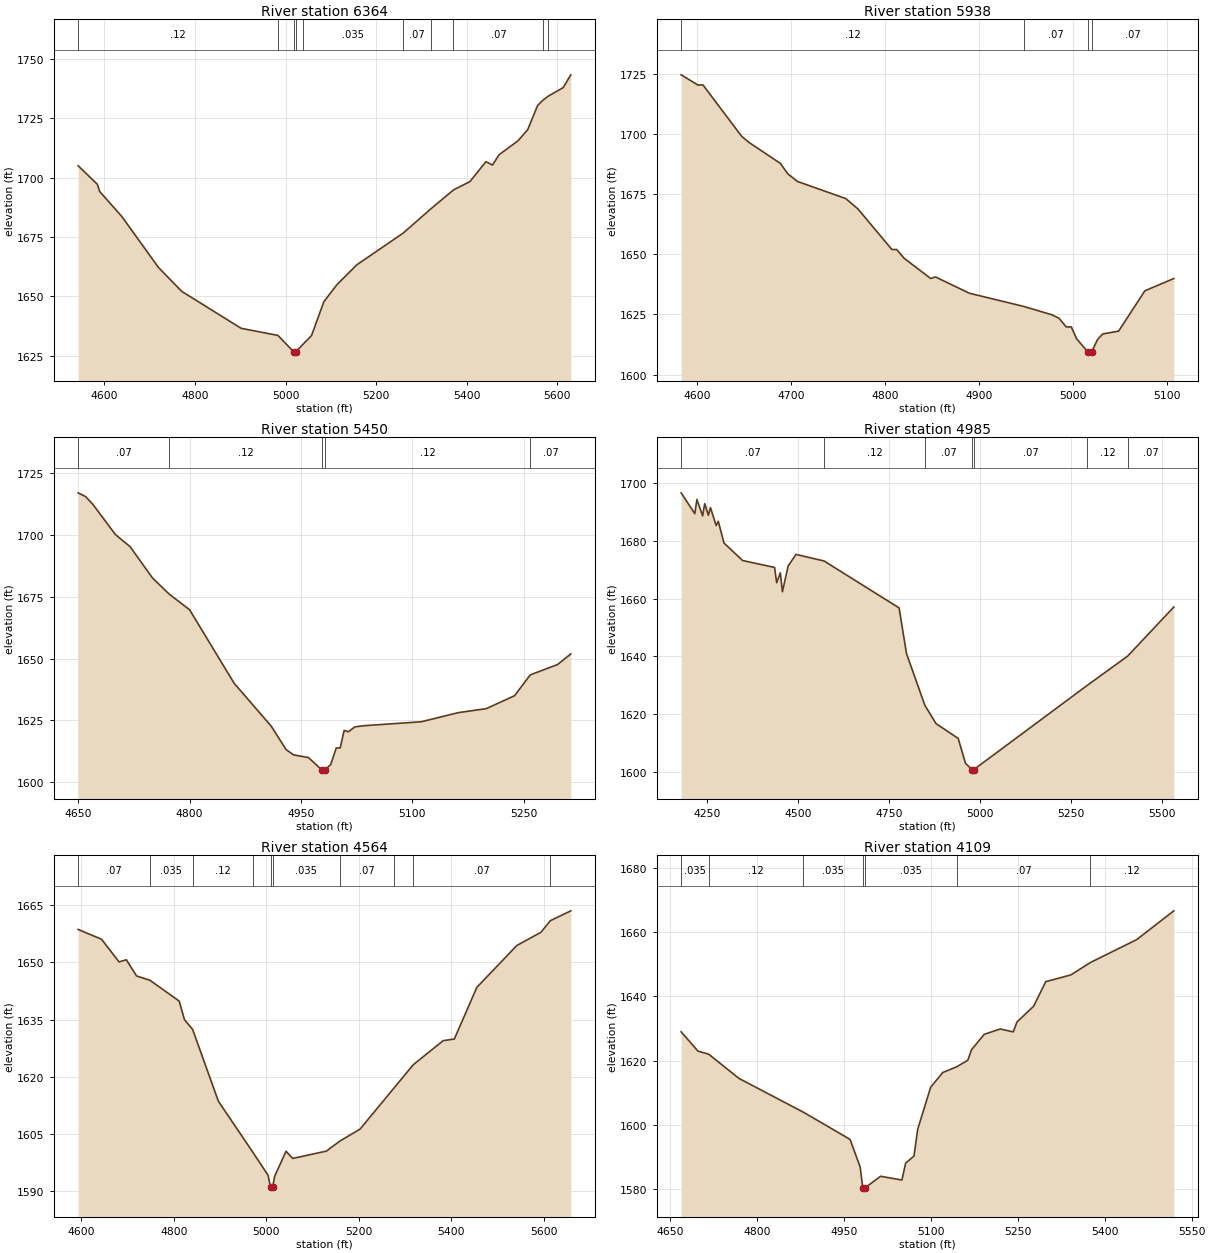
Type RM Length L Ch R = 1,6364,426,426,426
BEGIN DESCRIPTION:
Stream0151_DS 14.0
END DESCRIPTION:
XS GIS Cut Line= 3
      2082459.83     13926982.61      2082008.15     13927059.03
      2081627.94     13927560.99
#Sta/Elev= 30
  4541.9 1704.98  4584.3 1697.18  4589.3 1694.17  4638.1 1683.66  4719.2 1662.15
  4770.5 1652.09  4901.8 1636.51  4983.0 1633.52  5018.0 1626.56  5018.3 1626.06
  5022.0 1626.56  5038.1 1629.72  5057.3 1633.52  5084.4 1647.74  5113.5 1654.95
  5157.2 1663.27  5259.7 1676.65  5320.1 1686.75  5370.6 1694.82  5406.8 1698.31
  5442.2 1706.71  5456.8 1705.31  5471.3 1709.65  5513.0 1715.50  5534.4 1720.16
  5556.6 1730.48  5568.8 1732.71  5579.9 1734.31  5612.8 1737.92  5629.7 1743.30
#Mann=10,-1,0
  4541.9    0.12       0  4983.0    0.07       0  5018.0    0.05       0
  5022.0    0.07       0  5038.1   0.035       0  5259.7    0.07       0
  5320.1   0.035       0  5370.6    0.07       0  5568.8   0.035       0
  5579.9    0.12       0
Bank Sta=5018,5022
Exp/Cntr=0.3,0.1

Type RM Length L Ch R = 1,5938,488,488,488
BEGIN DESCRIPTION:
Stream0151_DS 13.0
END DESCRIPTION:
XS GIS Cut Line= 3
      2082274.97     13926575.01      2081875.00     13926675.00
      2081774.99     13926725.01
#Sta/Elev= 30
  4583.4 1724.63  4601.4 1720.36  4606.6 1720.44  4647.8 1699.06  4655.5 1696.55
  4689.0 1687.78  4696.8 1683.48  4707.1 1680.30  4758.6 1673.16  4771.5 1668.86
  4807.6 1652.00  4812.7 1652.00  4820.5 1648.39  4848.8 1639.95  4854.0 1640.58
  4890.0 1633.82  4948.0 1628.31  4977.6 1624.88  4985.4 1623.41  4993.1 1619.80
  4998.5 1619.80  5004.1 1614.89  5016.0 1609.41  5016.2 1608.91  5020.1 1609.41
  5026.4 1614.58  5032.0 1616.90  5048.8 1618.05  5076.7 1634.82  5107.5 1639.93
#Mann=4,-1,0
  4583.4    0.12       0  4948.0    0.07       0  5016.0    0.05       0
  5020.1    0.07       0
Bank Sta=5016,5020.1
Exp/Cntr=0.3,0.1

Type RM Length L Ch R = 1,5450,465,465,465
BEGIN DESCRIPTION:
Stream0151_DS 12.0
END DESCRIPTION:
XS GIS Cut Line= 3
      2082125.01     13926225.00      2081775.00     13926225.00
      2081499.25     13926373.70
#Sta/Elev= 30
  4650.0 1717.13  4660.0 1715.60  4670.0 1712.39  4700.0 1700.29  4720.0 1695.30
  4750.0 1682.67  4772.5 1676.14  4800.0 1669.80  4860.0 1640.02  4910.0 1622.63
  4930.0 1613.16  4940.0 1611.02  4960.0 1609.95  4978.0 1604.95  4978.2 1604.45
  4982.1 1604.95  4990.0 1607.10  4997.5 1613.84  5002.8 1613.84  5008.1 1620.94
  5013.8 1620.39  5022.7 1622.39  5035.7 1622.86  5111.9 1624.43  5161.4 1628.11
  5199.5 1629.75  5237.6 1635.00  5258.7 1643.42  5295.4 1647.60  5313.3 1651.91
#Mann=5,-1,0
  4650.0    0.07       0  4772.5    0.12       0  4978.0    0.05       0
  4982.1    0.12       0  5258.7    0.07       0
Bank Sta=4978,4982.1
Exp/Cntr=0.3,0.1

Type RM Length L Ch R = 1,4985,421,421,421
BEGIN DESCRIPTION:
Stream0151_DS 11.0
END DESCRIPTION:
XS GIS Cut Line= 4
      2082370.92     13926139.71      2081915.20     13925874.09
      2081625.00     13925825.00      2081275.01     13926224.99
#Sta/Elev= 30
  4178.5 1696.67  4216.0 1689.44  4221.8 1694.36  4237.5 1688.70  4243.3 1692.92
  4253.2 1688.91  4259.0 1691.57  4274.7 1685.34  4280.5 1686.82  4296.2 1679.27
  4347.4 1673.21  4435.2 1670.81  4440.9 1665.50  4450.9 1668.95  4456.7 1662.39
  4472.4 1671.31  4493.9 1675.33  4571.1 1673.05  4777.2 1656.79  4797.5 1640.99
  4847.7 1623.12  4878.6 1616.69  4939.5 1611.56  4959.7 1602.90  4977.9 1600.72
  4978.2 1600.22  4982.1 1600.72  5293.6 1629.90  5405.1 1640.09  5531.8 1657.09
#Mann=7,-1,0
  4178.5    0.07       0  4571.1    0.12       0  4847.7    0.07       0
  4977.9    0.05       0  4982.1    0.07       0  5293.6    0.12       0
  5405.1    0.07       0
Bank Sta=4977.9,4982.1
Exp/Cntr=0.3,0.1

Type RM Length L Ch R = 1,4564,455,455,455
BEGIN DESCRIPTION:
Stream0151_DS 10.0
END DESCRIPTION:
XS GIS Cut Line= 3
      2081446.26     13925185.55      2081325.00     13925575.00
      2081144.82     13926207.24
#Sta/Elev= 30
  4593.0 1658.67  4643.6 1656.09  4681.4 1650.15  4697.2 1650.71  4719.2 1646.47
  4748.5 1645.31  4811.5 1639.86  4822.8 1635.01  4840.4 1632.46  4896.2 1613.60
  4971.3 1600.11  5003.5 1594.20  5009.0 1591.04  5009.3 1590.54  5013.5 1591.04
  5017.8 1593.90  5042.5 1600.48  5056.8 1598.59  5129.7 1600.51  5159.5 1603.20
  5202.6 1606.29  5275.6 1617.02  5317.5 1623.17  5382.2 1629.48  5406.4 1629.92
  5455.1 1643.48  5541.6 1654.46  5593.6 1657.92  5614.1 1660.97  5658.3 1663.55
#Mann=10,-1,0
  4593.0    0.07       0  4748.5   0.035       0  4840.4    0.12       0
  4971.3   0.035       0  5009.0   0.035       0  5013.5   0.035       0
  5159.5    0.07       0  5275.6   0.035       0  5317.5    0.07       0
  5614.1    0.12       0
Bank Sta=5009,5013.5
Exp/Cntr=0.3,0.1

Type RM Length L Ch R = 1,4109,481,481,481
BEGIN DESCRIPTION:
Stream0151_DS 9.0
END DESCRIPTION:
XS GIS Cut Line= 3
      2081331.91     13925402.72      2081025.00     13925525.00
      2080700.07     13925930.12
#Sta/Elev= 30
  4669.5 1629.00  4698.5 1623.00  4717.0 1622.03  4769.3 1614.49  4880.3 1603.99
  4960.8 1595.53  4978.3 1586.92  4982.7 1580.55  4983.1 1580.05  4987.3 1580.55
  5013.5 1584.05  5050.3 1582.88  5056.7 1588.14  5071.1 1590.35  5077.5 1598.69
  5099.9 1611.77  5120.7 1616.33  5145.3 1618.16  5163.9 1620.15  5170.3 1623.40
  5192.2 1628.21  5219.9 1629.88  5242.3 1628.97  5248.7 1632.05  5277.5 1636.97
  5298.3 1644.60  5341.5 1646.69  5375.5 1650.57  5455.2 1657.68  5519.2 1666.64
#Mann=7,-1,0
  4669.5   0.035       0  4717.0    0.12       0  4880.3   0.035       0
  4982.7   0.035       0  4987.3   0.035       0  5145.3    0.07       0
  5375.5    0.12       0
Bank Sta=4982.7,4987.3
Exp/Cntr=0.3,0.1

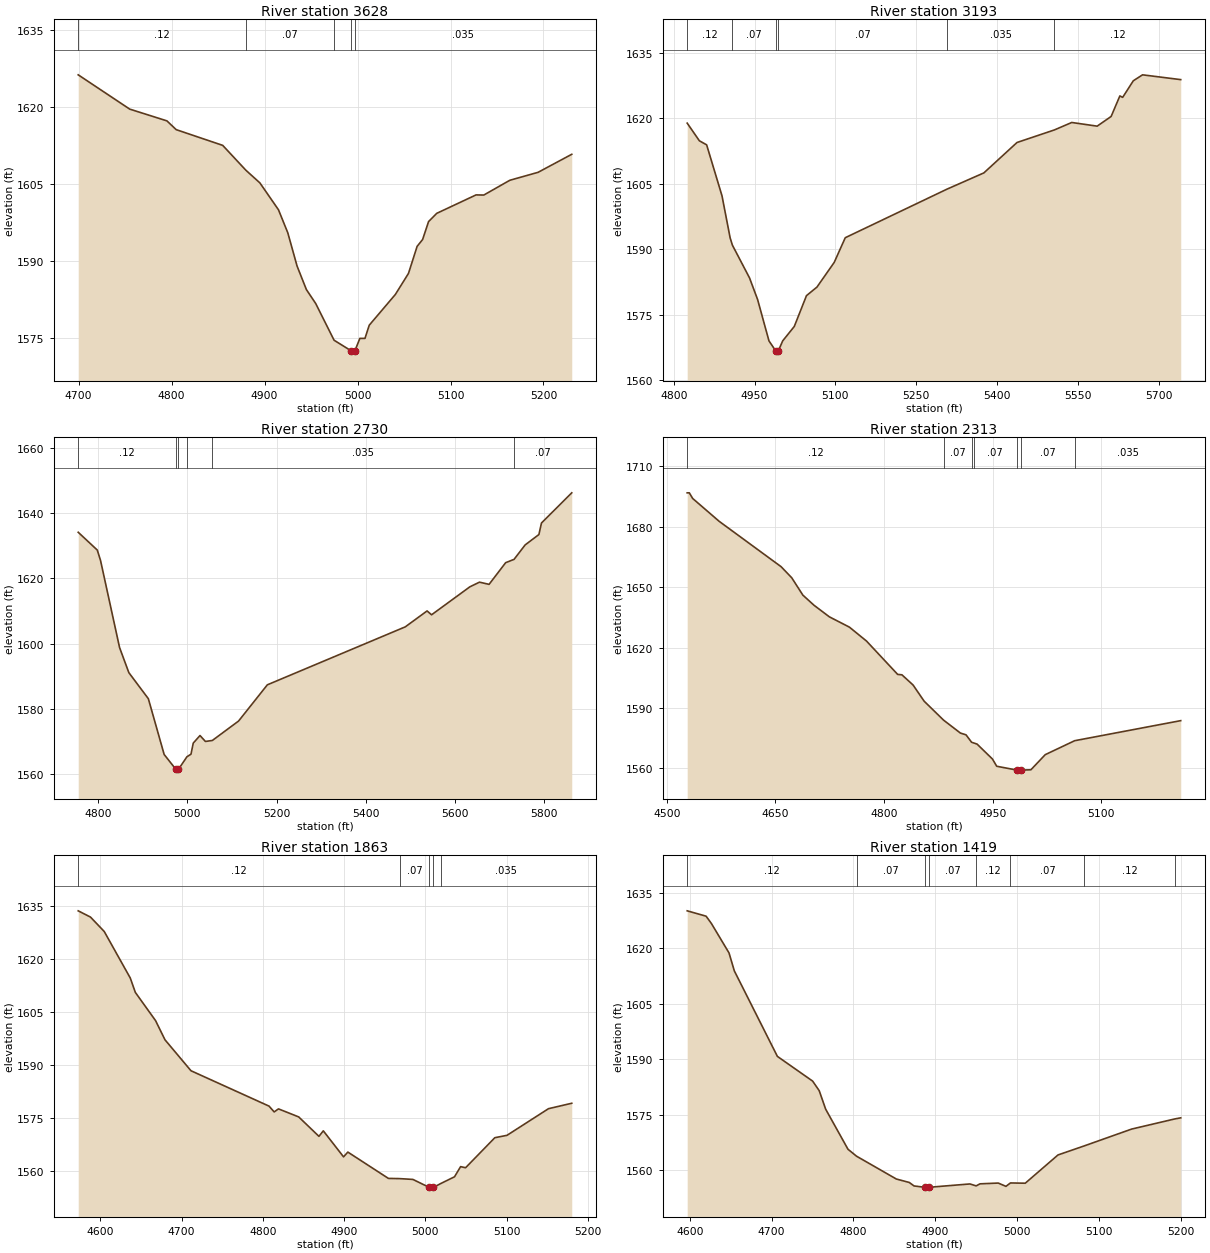
Type RM Length L Ch R = 1,3628,435,435,435
BEGIN DESCRIPTION:
Stream0151_DS 8.0
END DESCRIPTION:
XS GIS Cut Line= 3
      2081230.35     13925069.40      2080925.00     13925075.00
      2080735.49     13925197.02
#Sta/Elev= 30
  4699.6 1626.24  4755.0 1619.56  4795.0 1617.27  4805.0 1615.56  4855.0 1612.50
  4879.9 1607.66  4895.0 1605.19  4915.0 1599.95  4925.0 1595.47  4935.0 1588.98
  4945.0 1584.41  4955.0 1581.70  4974.8 1574.54  4992.7 1572.53  4993.0 1572.03
  4997.3 1572.53  5002.5 1574.90  5008.0 1574.90  5012.6 1577.47  5040.7 1583.46
  5054.8 1587.56  5064.1 1592.83  5070.0 1594.16  5076.4 1597.65  5085.2 1599.26
  5127.5 1602.85  5135.8 1602.82  5163.8 1605.70  5194.2 1607.25  5230.4 1610.76
#Mann=5,-1,0
  4699.6    0.12       0  4879.9    0.07       0  4974.8   0.035       0
  4992.7   0.035       0  4997.3   0.035       0
Bank Sta=4992.7,4997.3
Exp/Cntr=0.3,0.1

Type RM Length L Ch R = 1,3193,463,463,463
BEGIN DESCRIPTION:
Stream0151_DS 7.0
END DESCRIPTION:
XS GIS Cut Line= 3
      2080825.03     13924674.98      2080675.00     13924775.00
      2080503.90     13925490.62
#Sta/Elev= 30
  4825.0 1618.91  4847.6 1614.87  4861.1 1613.94  4889.6 1602.27  4904.7 1592.65
  4908.9 1590.98  4940.7 1583.48  4955.7 1578.53  4976.8 1569.06  4989.4 1566.76
  4989.8 1566.26  4994.1 1566.76  5002.3 1569.07  5023.8 1572.37  5046.4 1579.42
  5065.8 1581.37  5097.9 1587.03  5118.4 1592.68  5306.9 1603.78  5375.7 1607.52
  5437.2 1614.48  5506.7 1617.36  5538.8 1619.06  5586.0 1618.22  5611.9 1620.44
  5628.1 1625.14  5633.3 1624.81  5653.1 1628.61  5670.2 1629.97  5741.1 1628.87
#Mann=6,-1,0
  4825.0    0.12       0  4908.9    0.07       0  4989.4    0.05       0
  4994.1    0.07       0  5306.9   0.035       0  5506.7    0.12       0
Bank Sta=4989.4,4994.1
Exp/Cntr=0.3,0.1

Type RM Length L Ch R = 1,2730,417,417,417
BEGIN DESCRIPTION:
Stream0151_DS 6.0
END DESCRIPTION:
XS GIS Cut Line= 3
      2080525.00     13924275.00      2080375.00     13924475.00
      2079943.82     13925215.28
#Sta/Elev= 30
  4755.1 1634.13  4797.8 1628.69  4805.1 1625.53  4847.8 1598.84  4868.6 1591.15
  4912.4 1583.15  4947.8 1566.08  4974.4 1561.48  4974.8 1560.98  4979.6 1561.48
  4998.9 1565.38  5008.0 1566.17  5013.0 1569.55  5028.2 1571.88  5040.3 1570.07
  5055.9 1570.37  5114.7 1576.32  5179.2 1587.41  5488.6 1605.17  5537.4 1610.04
  5547.4 1608.85  5633.4 1617.43  5654.9 1618.85  5676.4 1618.18  5713.6 1624.82
  5732.4 1625.83  5757.3 1630.26  5788.1 1633.43  5793.9 1636.97  5861.8 1646.21
#Mann=6,-1,0
  4755.1    0.12       0  4974.4    0.05       0  4979.6    0.12       0
  4998.9    0.07       0  5055.9   0.035       0  5732.4    0.07       0
Bank Sta=4974.4,4979.6
Exp/Cntr=0.3,0.1

Type RM Length L Ch R = 1,2313,450,450,450
BEGIN DESCRIPTION:
Stream0151_DS 5.0
END DESCRIPTION:
XS GIS Cut Line= 3
      2080524.96     13923925.02      2080125.00     13924175.00
      2080010.51     13924350.86
#Sta/Elev= 30
  4528.1 1696.78  4531.0 1696.78  4535.7 1693.97  4572.3 1682.63  4657.8 1660.12
  4672.5 1654.61  4687.8 1646.03  4703.2 1641.00  4724.4 1635.25  4752.1 1630.13
  4775.7 1623.23  4818.7 1606.69  4824.6 1606.48  4840.0 1601.42  4855.3 1593.39
  4882.1 1584.00  4905.4 1577.57  4913.1 1576.70  4920.8 1573.02  4923.5 1572.69
  4928.4 1572.10  4949.6 1564.70  4955.5 1561.11  4983.6 1559.19  4984.0 1558.69
  4988.8 1559.19  5002.7 1559.36  5022.5 1566.86  5063.1 1573.78  5209.6 1583.74
#Mann=7,-1,0
  4528.1    0.12       0  4882.1    0.07       0  4920.8    0.12       0
  4923.5    0.07       0  4983.6    0.05       0  4988.8    0.07       0
  5063.1   0.035       0
Bank Sta=4983.6,4988.8
Exp/Cntr=0.3,0.1

Type RM Length L Ch R = 1,1863,444,444,444
BEGIN DESCRIPTION:
Stream0151_DS 4.0
END DESCRIPTION:
XS GIS Cut Line= 3
      2080174.98     13923775.01      2079775.00     13923925.00
      2079624.96     13924025.03
#Sta/Elev= 30
  4572.8 1633.66  4587.9 1631.89  4604.8 1627.83  4636.9 1614.66  4643.1 1610.61
  4668.0 1602.63  4679.6 1597.21  4711.6 1588.46  4807.7 1578.46  4814.0 1576.82
  4819.3 1577.68  4844.2 1575.41  4869.1 1569.92  4874.5 1571.47  4899.4 1564.12
  4904.7 1565.47  4954.6 1558.03  4968.5 1557.97  4984.8 1557.74  5004.8 1555.50
  5005.2 1555.00  5010.1 1555.50  5018.9 1556.56  5036.0 1558.49  5043.5 1561.36
  5049.6 1561.04  5085.6 1569.53  5100.6 1570.21  5151.7 1577.74  5180.3 1579.27
#Mann=5,-1,0
  4572.8    0.12       0  4968.5    0.07       0  5004.8    0.05       0
  5010.1    0.07       0  5018.9   0.035       0
Bank Sta=5004.8,5010.1
Exp/Cntr=0.3,0.1

Type RM Length L Ch R = 1,1419,265,265,265
BEGIN DESCRIPTION:
Stream0151_DS 3.0
END DESCRIPTION:
XS GIS Cut Line= 3
      2079825.02     13923424.99      2079475.00     13923625.00
      2079475.00     13923824.96
#Sta/Elev= 30
  4596.9 1630.12  4620.0 1628.67  4626.4 1626.72  4648.0 1618.74  4654.5 1613.88
  4707.1 1590.76  4750.2 1584.07  4758.2 1581.49  4766.1 1576.48  4793.4 1565.64
  4803.8 1563.77  4852.5 1557.59  4868.3 1556.66  4874.1 1555.72  4887.2 1555.36
  4887.6 1554.86  4892.1 1554.86  4892.5 1555.36  4942.4 1556.26  4950.0 1555.74
  4954.7 1556.29  4977.0 1556.50  4986.4 1555.61  4991.9 1556.53  5010.0 1556.46
  5050.0 1564.10  5082.1 1566.55  5140.0 1571.10  5192.5 1573.83  5200.0 1574.14
#Mann=8,-1,0
  4596.9    0.12       0  4803.8    0.07       0  4887.2    0.05       0
  4892.5    0.07       0  4950.0    0.12       0  4991.9    0.07       0
  5082.1    0.12       0  5192.5    0.07       0
Bank Sta=4887.2,4892.5
Exp/Cntr=0.3,0.1

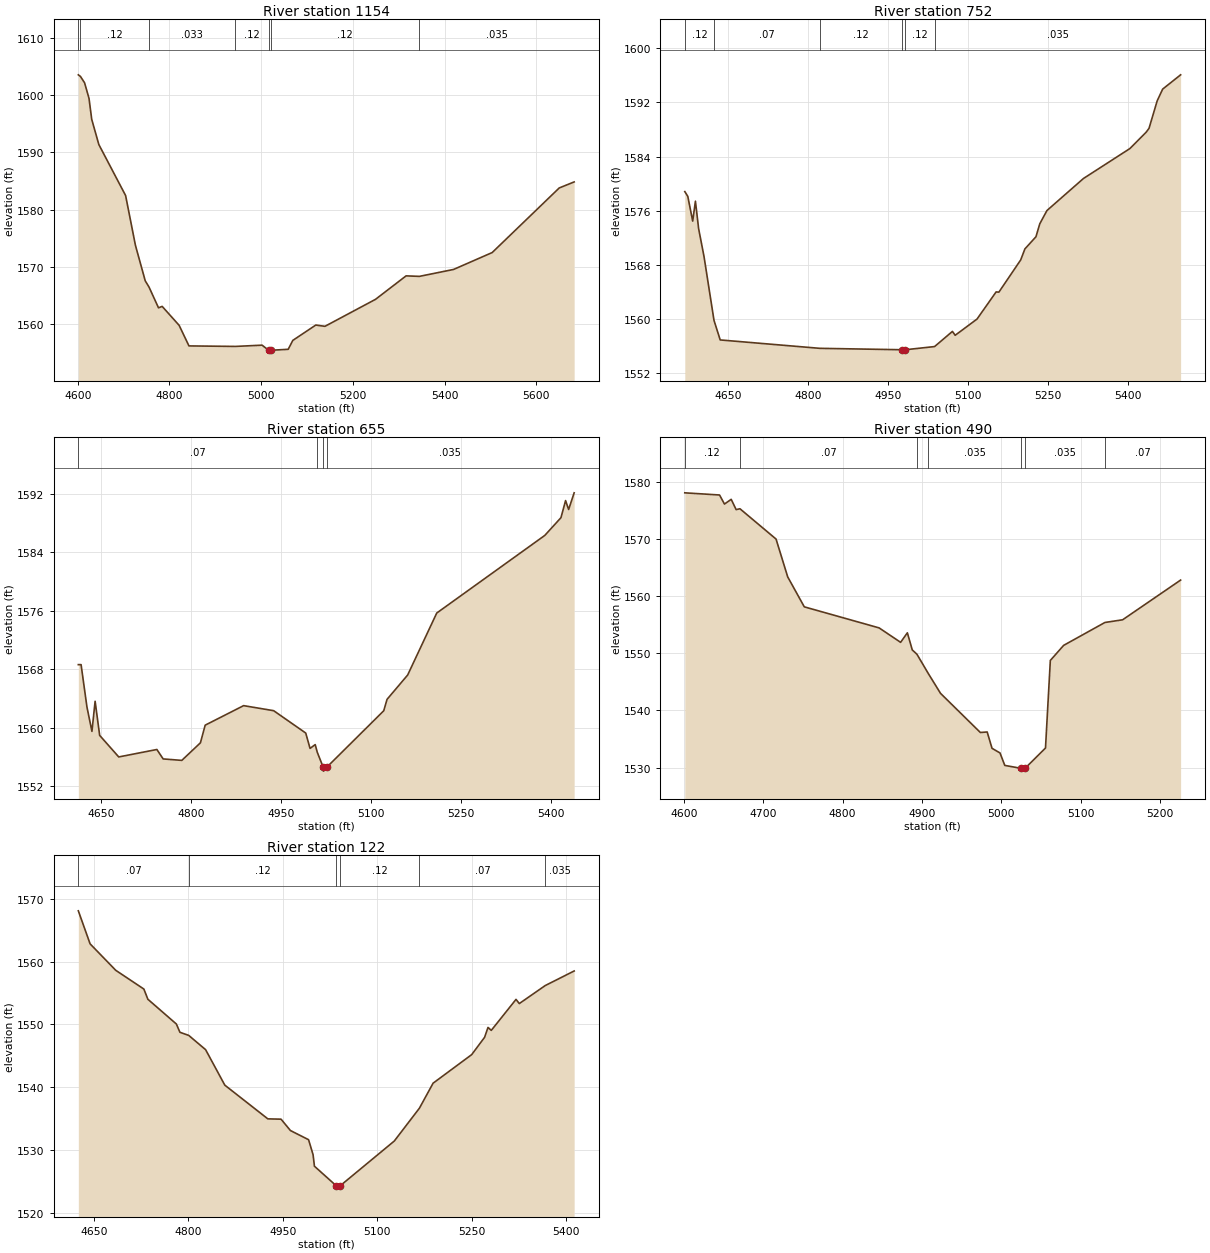
Type RM Length L Ch R = 1,1154,402,402,402
BEGIN DESCRIPTION:
Stream0151_DS 2.0
END DESCRIPTION:
XS GIS Cut Line= 3
      2079474.99     13923125.01      2079266.76     13923473.05
      2079230.31     13924147.49
#Sta/Elev= 30
  4601.4 1603.54  4606.0 1603.26  4615.0 1602.15  4624.7 1599.42  4630.6 1595.77
  4646.1 1591.37  4704.5 1582.46  4725.9 1573.77  4747.3 1567.57  4755.5 1566.49
  4776.2 1562.86  4784.2 1563.11  4821.2 1559.80  4842.6 1556.21  4943.6 1556.12
  5002.0 1556.34  5016.3 1555.45  5016.7 1554.95  5021.6 1555.45  5059.0 1555.62
  5069.0 1557.17  5119.1 1559.85  5139.1 1559.63  5249.3 1564.34  5316.0 1568.44
  5344.9 1568.35  5419.5 1569.56  5503.7 1572.51  5649.9 1583.79  5682.4 1584.84
#Mann=7,-1,0
  4601.4   0.035       0  4606.0    0.12       0  4755.5   0.033       0
  4943.6    0.12       0  5016.3    0.05       0  5021.6    0.12       0
  5344.9   0.035       0
Bank Sta=5016.3,5021.6
Exp/Cntr=0.3,0.1

Type RM Length L Ch R = 1,752,97,97,97
BEGIN DESCRIPTION:
Stream0151_DS 1.5
END DESCRIPTION:
XS GIS Cut Line= 3
      2079032.84     13923159.43      2078968.33     13923584.97
      2078845.47     13924067.57
#Sta/Elev= 30
  4569.6 1578.81  4575.2 1578.11  4584.4 1574.45  4589.5 1577.39  4595.5 1573.33
  4605.6 1569.20  4624.3 1559.76  4635.9 1556.87  4822.3 1555.63  4977.1 1555.42
  4977.5 1554.92  4982.5 1555.42  5037.3 1555.89  5070.7 1558.13  5075.9 1557.56
  5116.8 1559.96  5152.5 1563.97  5157.7 1563.94  5198.6 1568.71  5206.4 1570.33
  5227.1 1572.13  5234.3 1574.05  5247.7 1576.01  5316.1 1580.75  5403.1 1585.18
  5433.4 1587.59  5438.8 1588.16  5454.1 1592.23  5464.4 1593.97  5498.0 1596.08
#Mann=6,-1,0
  4569.6    0.12       0  4624.3    0.07       0  4822.3    0.12       0
  4977.1    0.05       0  4982.5    0.12       0  5037.3   0.035       0
Bank Sta=4977.1,4982.5
Exp/Cntr=0.3,0.1

Type RM Length L Ch R = 1,655,165,165,165
BEGIN DESCRIPTION:
Stream0151_DS 1.1
END DESCRIPTION:
XS GIS Cut Line= 5
      2078988.47     13923221.38      2078918.23     13923422.20
      2078908.94     13923562.60      2078891.67     13923592.52
      2078776.90     13924016.25
#Sta/Elev= 30
  4612.0 1568.64  4616.6 1568.64  4626.4 1562.83  4634.7 1559.51  4640.0 1563.63
  4647.6 1558.96  4679.4 1556.01  4743.0 1557.03  4753.5 1555.74  4784.6 1555.54
  4815.6 1557.94  4823.6 1560.36  4887.7 1563.03  4937.8 1562.34  4991.3 1559.28
  4998.5 1557.18  5007.1 1557.70  5010.5 1556.66  5020.6 1554.57  5021.0 1554.07
  5026.0 1554.57  5121.4 1562.33  5126.9 1563.89  5161.3 1567.22  5209.8 1575.70
  5390.0 1586.32  5417.0 1588.75  5424.7 1591.09  5429.8 1589.87  5439.0 1592.15
#Mann=4,-1,0
  4612.0    0.07       0  5010.5   0.035       0  5020.6    0.05       0
  5026.0   0.035       0
Bank Sta=5020.6,5026
Exp/Cntr=0.3,0.1

Type RM Length L Ch R = 1,490,368,368,368
BEGIN DESCRIPTION:
Stream0151_DS 1.0
END DESCRIPTION:
XS GIS Cut Line= 3
      2079006.34     13923155.35      2078775.00     13923475.00
      2078678.21     13923684.00
#Sta/Elev= 30
  4601.1 1578.14  4644.9 1577.76  4651.1 1576.17  4659.6 1577.00  4665.8 1575.20
  4670.6 1575.35  4716.1 1570.04  4730.8 1563.41  4751.7 1558.16  4846.0 1554.47
  4873.1 1551.94  4881.6 1553.61  4887.8 1550.61  4893.7 1549.85  4908.1 1546.45
  4923.4 1543.00  4973.6 1536.14  4982.2 1536.23  4988.3 1533.37  4998.4 1532.55
  5004.4 1530.37  5024.6 1529.87  5025.0 1529.37  5030.0 1529.87  5055.7 1533.42
  5061.8 1548.77  5078.6 1551.41  5130.6 1555.42  5152.9 1555.89  5226.0 1562.85
#Mann=7,-1,0
  4601.1    0.12       0  4670.6    0.07       0  4893.7    0.12       0
  4908.1   0.035       0  5024.6   0.035       0  5030.0   0.035       0
  5130.6    0.07       0
Bank Sta=5024.6,5030
Exp/Cntr=0.3,0.1

Type RM Length L Ch R = 1,122,0,0,0
BEGIN DESCRIPTION:
Stream0151_DS 0.0
END DESCRIPTION:
XS GIS Cut Line= 4
      2078883.33     13923130.25      2078590.44     13923187.48
      2078527.36     13923230.71      2078441.65     13923634.11
#Sta/Elev= 30
  4625.1 1568.07  4643.8 1562.81  4684.5 1558.60  4729.2 1555.61  4735.5 1553.99
  4780.8 1550.04  4786.4 1548.73  4800.4 1548.23  4827.2 1545.96  4857.7 1540.31
  4926.0 1534.94  4947.0 1534.89  4961.9 1533.08  4990.7 1531.62  4997.8 1529.25
  5000.0 1527.40  5035.0 1524.25  5035.5 1523.75  5040.5 1524.25  5126.8 1531.41
  5166.7 1536.64  5188.4 1540.62  5249.7 1545.17  5270.2 1547.93  5275.6 1549.50
  5280.8 1549.03  5320.1 1553.97  5325.3 1553.30  5366.5 1556.17  5412.4 1558.49
#Mann=6,-1,0
  4625.1    0.07       0  4800.4    0.12       0  5035.0    0.05       0
  5040.5    0.12       0  5166.7    0.07       0  5366.5   0.035       0
Bank Sta=5035,5040.5
Exp/Cntr=0.3,0.1

Chan Stop Cuts=-1