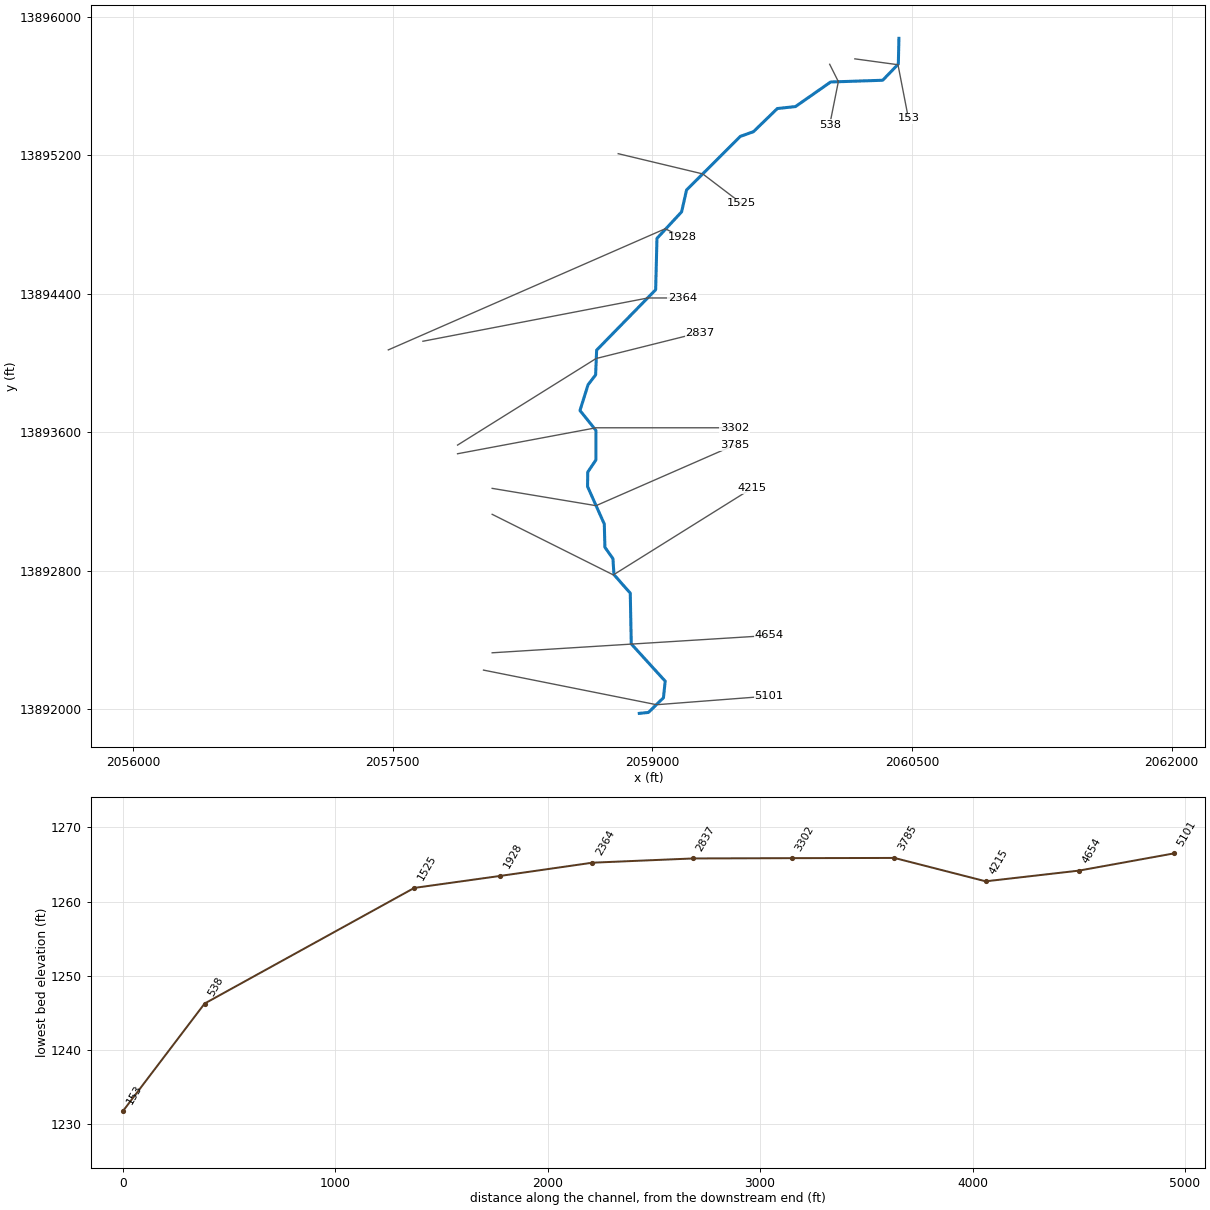
--- Stream0152_DS.prj (project) ---

Proj Title=Stream0152_DS Base Level Engineering
Current Plan=p01
Default Exp/Contr=0.3,0.1
English Units
Geom File=g01
Flow File=f01
Plan File=p01
BEGIN DESCRIPTION:
Stream0152_DS
END DESCRIPTION:

--- Stream0152_DS.p01 (plan) ---

Plan Title=Multiple Run
Short Identifier=Multiple
Geom File=g01
Flow File=f01
Subcritical Flow
K Sum by GR= 0
Std Step Tol= 0.01
Critical Tol= 0.01
Num of Std Step Trials= 20
Max Error Tol= 0.3
Flow Tol Ratio= 0.001
Split Flow NTrial= 30
Split Flow Tol= 0.02
Split Flow Ratio= 0.02
Log Output Level= 0
Friction Slope Method= 1
Unsteady Friction Slope Method= 2
Unsteady Bridges Friction Slope Method= 1
Parabolic Critical Depth
Global Vel Dist=  1 , 1 , 1
Global Log Level= 0
CheckData=True
Encroach Param= -1, 0, 0, 0
BEGIN DESCRIPTION:
Multiple Run
END DESCRIPTION:

--- Stream0152_DS.f01 (steady flow) ---

Flow Title=Multiple
Number of Profiles=7
Profile Names=10-year,25-year,50-year,1pct_min,100-year,1pct_plu,500-year
River Rch & RM= Stream0152_DS,Reach-1,5101
    1542    2637    3685    2491    4970    9917    8947
Boundary for River Rch & Prof#=Stream0152_DS,Reach-1,1
Up Type=0
Dn Type=3
Dn Slope=0.005
Boundary for River Rch & Prof#=Stream0152_DS,Reach-1,2
Up Type=0
Dn Type=3
Dn Slope=0.005
Boundary for River Rch & Prof#=Stream0152_DS,Reach-1,3
Up Type=0
Dn Type=3
Dn Slope=0.005
Boundary for River Rch & Prof#=Stream0152_DS,Reach-1,4
Up Type=0
Dn Type=3
Dn Slope=0.005
Boundary for River Rch & Prof#=Stream0152_DS,Reach-1,5
Up Type=0
Dn Type=3
Dn Slope=0.005
Boundary for River Rch & Prof#=Stream0152_DS,Reach-1,6
Up Type=0
Dn Type=3
Dn Slope=0.005
Boundary for River Rch & Prof#=Stream0152_DS,Reach-1,7
Up Type=0
Dn Type=3
Dn Slope=0.005

--- Stream0152_DS.g01 (geometry) ---

Geom Title=Existing Conditions

River Reach=Stream0152_DS,Reach-1
Reach XY= 30
      2058925.00     13891975.00      2058977.54     13891980.30
      2059064.59     13892065.19      2059074.60     13892161.09
      2058878.54     13892376.46      2058872.82     13892669.55
      2058778.62     13892776.50      2058772.64     13892869.02
      2058726.39     13892934.67      2058722.73     13893069.06
      2058626.10     13893285.55      2058627.17     13893369.02
      2058674.32     13893438.92      2058674.61     13893609.84
      2058582.33     13893724.90      2058628.85     13893873.40
      2058672.61     13893930.53      2058678.54     13894073.53
      2059019.54     13894422.55      2059027.06     13894719.15
      2059169.48     13894872.57      2059197.88     13894998.52
      2059508.33     13895308.35      2059584.68     13895335.78
      2059722.57     13895469.48      2059827.32     13895480.77
      2060030.45     13895622.82      2060331.21     13895632.80
      2060421.51     13895726.44      2060425.00     13895875.00

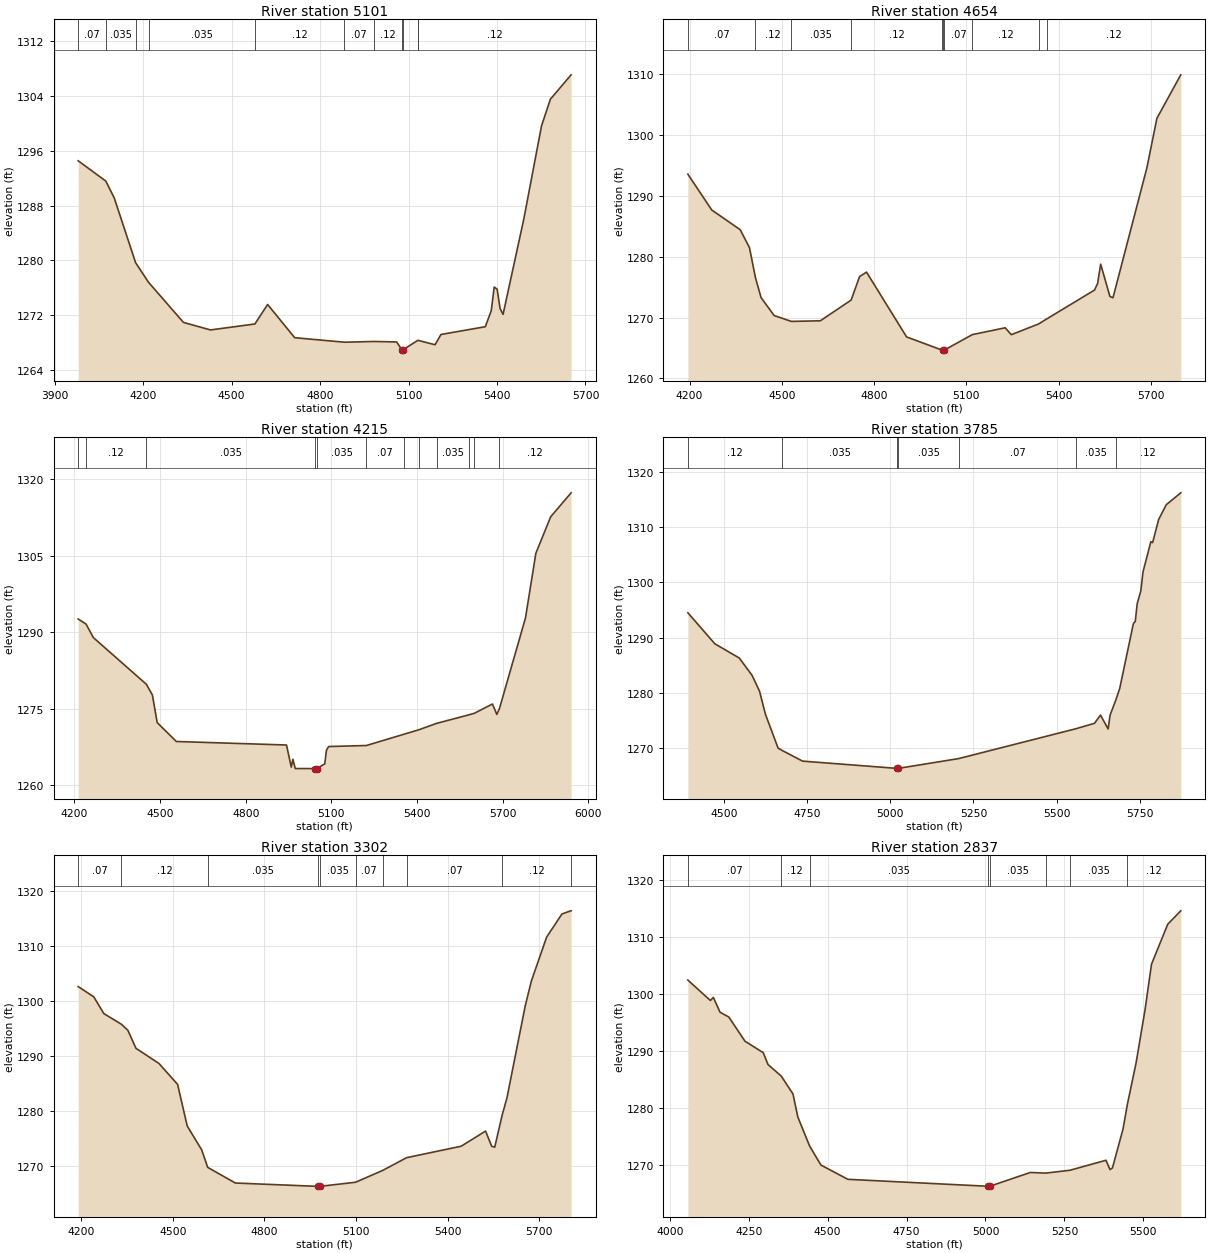
Type RM Length L Ch R = 1,5101,447,447,447
BEGIN DESCRIPTION:
Stream0152_DS 9.0
END DESCRIPTION:
XS GIS Cut Line= 3
      2058024.97     13892225.01      2059025.00     13892025.00
      2059675.05     13892075.00
#Sta/Elev= 30
  3979.5 1294.52  4073.2 1291.56  4101.9 1289.09  4174.3 1279.66  4218.0 1276.81
  4336.5 1270.96  4428.2 1269.86  4578.9 1270.73  4622.0 1273.57  4713.8 1268.73
  4882.3 1268.07  4983.5 1268.18  5059.5 1268.11  5077.5 1266.98  5077.8 1266.48
  5081.6 1266.98  5131.1 1268.33  5132.5 1268.34  5189.9 1267.70  5210.0 1269.20
  5360.4 1270.33  5380.5 1272.67  5390.5 1276.11  5400.5 1275.80  5410.5 1272.97
  5420.6 1272.13  5490.8 1286.00  5551.0 1299.60  5581.0 1303.49  5651.3 1307.05
#Mann=11,-1,0
  3979.5    0.07       0  4073.2   0.035       0  4174.3    0.12       0
  4218.0   0.035       0  4578.9    0.12       0  4882.3    0.07       0
  4983.5    0.12       0  5077.5    0.05       0  5081.6    0.12       0
  5131.1   0.035       0  5132.5    0.12       0
Bank Sta=5077.5,5081.6
Exp/Cntr=0.3,0.1

Type RM Length L Ch R = 1,4654,439,439,439
BEGIN DESCRIPTION:
Stream0152_DS 8.0
END DESCRIPTION:
XS GIS Cut Line= 3
      2058075.00     13892325.00      2058875.00     13892375.00
      2059674.98     13892425.00
#Sta/Elev= 30
  4194.3 1293.55  4272.0 1287.67  4364.6 1284.43  4394.7 1281.48  4413.9 1276.61
  4432.3 1273.29  4474.8 1270.34  4530.9 1269.37  4625.1 1269.47  4725.3 1272.87
  4752.9 1276.74  4775.4 1277.46  4905.7 1266.82  5021.0 1264.66  5023.4 1264.66
  5023.8 1264.16  5028.4 1264.66  5119.5 1267.20  5226.3 1268.32  5246.4 1267.19
  5335.5 1268.96  5361.2 1269.77  5516.9 1274.52  5526.9 1275.60  5536.9 1278.77
  5567.0 1273.47  5577.0 1273.26  5687.2 1294.59  5719.8 1302.73  5797.4 1309.87
#Mann=10,-1,0
  4194.3    0.07       0  4413.9    0.12       0  4530.9   0.035       0
  4725.3    0.12       0  5021.0    0.07       0  5023.4    0.05       0
  5028.4    0.07       0  5119.5    0.12       0  5335.5    0.07       0
  5361.2    0.12       0
Bank Sta=5023.4,5028.4
Exp/Cntr=0.3,0.1

Type RM Length L Ch R = 1,4215,430,430,430
BEGIN DESCRIPTION:
Stream0152_DS 7.0
END DESCRIPTION:
XS GIS Cut Line= 3
      2058075.04     13893124.98      2058775.00     13892775.00
      2059575.02     13893275.01
#Sta/Elev= 30
  4213.4 1292.59  4240.9 1291.61  4266.5 1288.95  4452.3 1279.77  4473.3 1277.66
  4490.1 1272.25  4557.1 1268.54  4942.9 1267.85  4959.6 1263.51  4965.2 1265.05
  4973.6 1263.23  5043.6 1263.22  5043.9 1262.72  5048.6 1263.22  5076.8 1264.14
  5082.7 1266.81  5090.3 1267.55  5222.7 1267.75  5354.3 1269.97  5405.2 1270.82
  5468.4 1272.10  5582.4 1273.79  5600.5 1274.08  5664.0 1275.90  5679.3 1273.86
  5688.3 1274.96  5779.6 1292.78  5816.1 1305.52  5868.0 1312.68  5939.4 1317.38
#Mann=12,-1,0
  4213.4    0.07       0  4240.9    0.12       0  4452.3   0.035       0
  5043.6   0.035       0  5048.6   0.035       0  5222.7    0.07       0
  5354.3   0.035       0  5405.2    0.07       0  5468.4   0.035       0
  5582.4    0.12       0  5600.5   0.035       0  5688.3    0.12       0
Bank Sta=5043.6,5048.6
Exp/Cntr=0.3,0.1

Type RM Length L Ch R = 1,3785,483,483,483
BEGIN DESCRIPTION:
Stream0152_DS 6.0
END DESCRIPTION:
XS GIS Cut Line= 3
      2058074.96     13893275.01      2058675.00     13893175.00
      2059474.97     13893524.99
#Sta/Elev= 30
  4391.7 1294.51  4472.8 1288.90  4546.3 1286.32  4584.4 1283.22  4607.2 1280.32
  4624.9 1276.15  4662.9 1270.03  4675.5 1269.60  4736.4 1267.68  5019.3 1266.37
  5019.6 1265.87  5024.4 1266.37  5205.8 1268.14  5558.9 1273.55  5614.0 1274.52
  5631.9 1276.01  5654.9 1273.50  5660.8 1276.01  5677.6 1278.67  5689.6 1280.79
  5730.9 1292.59  5736.4 1292.92  5742.2 1296.13  5753.2 1298.50  5759.8 1301.93
  5783.2 1307.35  5788.6 1307.19  5806.6 1311.36  5829.6 1314.05  5873.2 1316.20
#Mann=7,-1,0
  4391.7    0.12       0  4675.5   0.035       0  5019.3   0.035       0
  5024.4   0.035       0  5205.8    0.07       0  5558.9   0.035       0
  5677.6    0.12       0
Bank Sta=5019.3,5024.4
Exp/Cntr=0.3,0.1

Type RM Length L Ch R = 1,3302,465,465,465
BEGIN DESCRIPTION:
Stream0152_DS 5.0
END DESCRIPTION:
XS GIS Cut Line= 3
      2057874.95     13893474.99      2058675.00     13893625.00
      2059475.01     13893625.00
#Sta/Elev= 30
  4190.0 1302.67  4240.9 1300.81  4274.0 1297.76  4331.4 1295.82  4352.8 1294.71
  4379.1 1291.45  4454.6 1288.68  4515.6 1284.88  4547.0 1277.32  4594.5 1272.97
  4614.0 1269.80  4704.7 1266.95  4975.1 1266.34  4975.5 1265.84  4980.3 1266.34
  5098.2 1267.09  5187.1 1269.24  5265.6 1271.56  5444.0 1273.64  5524.0 1276.40
  5544.0 1273.63  5554.0 1273.47  5578.3 1279.30  5594.0 1282.43  5654.0 1299.20
  5674.0 1303.69  5724.0 1311.67  5774.0 1315.86  5802.4 1316.44  5804.0 1316.44
#Mann=10,-1,0
  4190.0    0.07       0  4331.4    0.12       0  4614.0   0.035       0
  4975.1   0.035       0  4980.3   0.035       0  5098.2    0.07       0
  5187.1   0.035       0  5265.6    0.07       0  5578.3    0.12       0
  5802.4    0.07       0
Bank Sta=4975.1,4980.3
Exp/Cntr=0.3,0.1

Type RM Length L Ch R = 1,2837,473,473,473
BEGIN DESCRIPTION:
Stream0152_DS 4.0
END DESCRIPTION:
XS GIS Cut Line= 3
      2057875.01     13893525.01      2058675.00     13894025.00
      2059274.95     13894174.99
#Sta/Elev= 30
  4057.0 1302.46  4128.3 1298.88  4137.8 1299.42  4159.0 1296.82  4186.7 1295.98
  4238.0 1291.74  4295.8 1289.73  4311.1 1287.64  4352.6 1285.64  4390.1 1282.49
  4405.5 1278.43  4442.7 1273.37  4478.6 1270.02  4564.1 1267.52  5008.0 1266.30
  5008.4 1265.80  5013.3 1266.30  5142.1 1268.72  5191.3 1268.61  5267.7 1269.11
  5381.8 1270.86  5394.7 1269.22  5402.4 1269.52  5435.9 1276.35  5449.9 1280.73
  5477.1 1287.90  5505.5 1297.22  5526.1 1305.24  5577.6 1312.26  5618.8 1314.60
#Mann=8,-1,0
  4057.0    0.07       0  4352.6    0.12       0  4442.7   0.035       0
  5008.0   0.035       0  5013.3   0.035       0  5191.3    0.07       0
  5267.7   0.035       0  5449.9    0.12       0
Bank Sta=5008,5013.3
Exp/Cntr=0.3,0.1

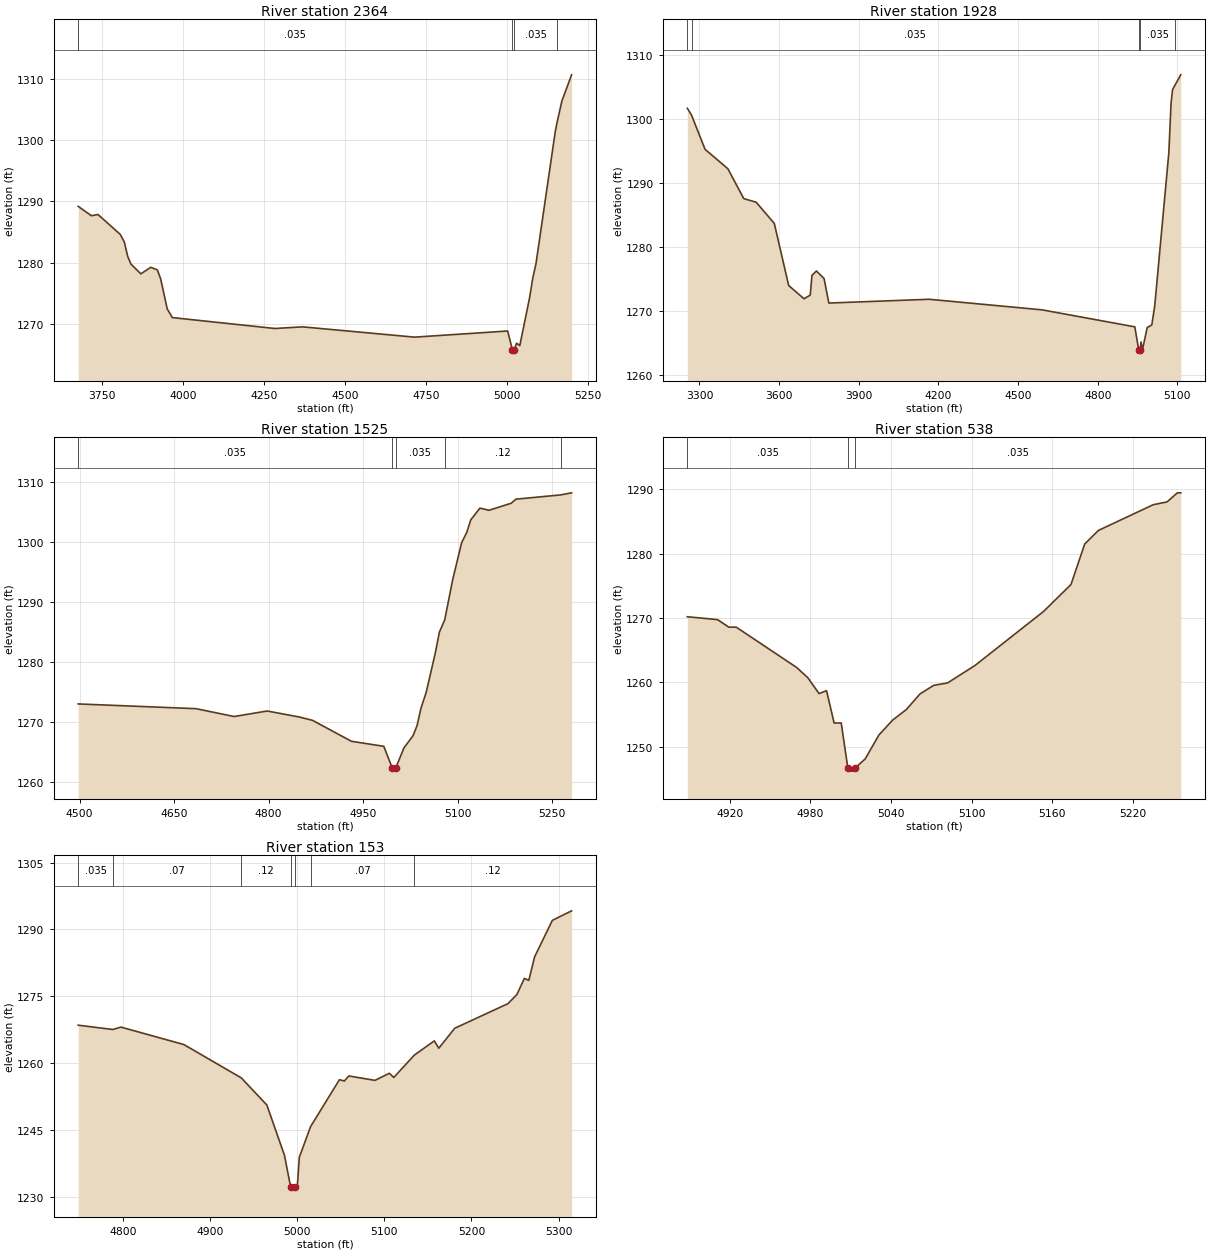
Type RM Length L Ch R = 1,2364,436,436,436
BEGIN DESCRIPTION:
Stream0152_DS 3.0
END DESCRIPTION:
XS GIS Cut Line= 3
      2057674.97     13894124.99      2058975.00     13894375.00
      2059174.95     13894375.00
#Sta/Elev= 30
  3675.8 1289.19  3716.6 1287.66  3736.9 1287.86  3805.7 1284.61  3818.4 1283.35
  3828.6 1281.04  3838.8 1279.76  3869.3 1278.17  3899.9 1279.24  3920.2 1278.81
  3930.4 1277.36  3950.8 1272.44  3966.6 1271.03  4283.3 1269.25  4368.3 1269.52
  4714.5 1267.84  5002.1 1268.84  5017.0 1265.73  5017.4 1265.23  5021.9 1265.23
  5022.3 1265.73  5029.6 1266.85  5039.6 1266.46  5069.6 1274.20  5079.6 1277.46
  5089.6 1279.83  5149.6 1301.55  5154.4 1302.80  5169.6 1306.39  5199.6 1310.66
#Mann=4,-1,0
  3675.8   0.035       0  5017.0   0.035       0  5022.3   0.035       0
  5154.4    0.12       0
Bank Sta=5017,5022.3
Exp/Cntr=0.3,0.1

Type RM Length L Ch R = 1,1928,403,403,403
BEGIN DESCRIPTION:
Stream0152_DS 2.0
END DESCRIPTION:
XS GIS Cut Line= 3
      2057474.97     13894074.99      2059075.00     13894775.00
      2059175.03     13894724.98
#Sta/Elev= 30
  3254.3 1301.63  3270.4 1300.53  3321.0 1295.23  3407.1 1292.19  3466.8 1287.54
  3513.6 1286.98  3581.8 1283.67  3636.0 1273.98  3693.7 1271.92  3717.1 1272.49
  3723.7 1275.58  3740.5 1276.25  3769.3 1275.07  3787.2 1271.25  4165.4 1271.84
  4590.3 1270.19  4939.6 1267.54  4954.4 1263.94  4954.9 1263.44  4959.8 1263.94
  4962.9 1265.18  4968.4 1263.96  4986.3 1267.43  5003.6 1267.84  5014.7 1270.82
  5067.8 1294.73  5076.2 1302.47  5081.8 1304.55  5092.7 1305.37  5112.6 1306.85
#Mann=5,-1,0
  3254.3    0.12       0  3270.4   0.035       0  4954.4   0.035       0
  4959.8   0.035       0  5092.7    0.12       0
Bank Sta=4954.4,4959.8
Exp/Cntr=0.3,0.1

Type RM Length L Ch R = 1,1525,987,987,987
BEGIN DESCRIPTION:
Stream0152_DS 1.5
END DESCRIPTION:
XS GIS Cut Line= 3
      2058803.16     13895208.59      2059291.66     13895091.67
      2059515.31     13894921.38
#Sta/Elev= 30
  4497.7 1273.04  4684.7 1272.25  4745.3 1270.94  4797.8 1271.86  4849.2 1270.85
  4869.8 1270.30  4931.5 1266.81  4982.9 1265.97  4996.4 1262.33  4996.8 1261.83
  5001.4 1261.83  5001.8 1262.33  5014.9 1265.71  5029.3 1267.73  5035.7 1269.41
  5042.0 1272.35  5050.2 1274.96  5064.8 1281.59  5071.1 1284.99  5079.7 1287.08
  5092.2 1293.73  5106.4 1299.91  5114.7 1301.68  5121.0 1303.75  5135.5 1305.71
  5150.0 1305.35  5185.4 1306.53  5192.7 1307.20  5263.5 1307.91  5281.1 1308.26
#Mann=5,-1,0
  4497.7   0.035       0  4996.4   0.035       0  5001.8   0.035       0
  5079.7    0.12       0  5263.5    0.07       0
Bank Sta=4996.4,5001.8
Exp/Cntr=0.3,0.1

Type RM Length L Ch R = 1,538,385,385,385
BEGIN DESCRIPTION:
Stream0152_DS 1.0
END DESCRIPTION:
XS GIS Cut Line= 3
      2060024.98     13895725.04      2060075.00     13895625.00
      2060025.00     13895375.00
#Sta/Elev= 30
  4888.6 1270.19  4911.0 1269.75  4919.4 1268.58  4925.0 1268.57  4969.7 1262.35
  4978.1 1260.75  4986.5 1258.28  4992.1 1258.72  4997.7 1253.72  5003.0 1253.72
  5007.9 1246.75  5008.3 1246.25  5012.9 1246.25  5013.4 1246.75  5020.8 1248.14
  5031.0 1251.85  5041.2 1254.16  5051.4 1255.80  5061.6 1258.23  5071.8 1259.56
  5082.0 1259.92  5102.4 1262.63  5153.4 1271.01  5173.8 1275.19  5184.0 1281.47
  5194.2 1283.58  5235.0 1287.57  5245.2 1288.00  5252.9 1289.41  5255.4 1289.41
#Mann=3,-1,0
  4888.6   0.035       0  5007.9   0.035       0  5013.4   0.035       0
Bank Sta=5007.9,5013.4
Exp/Cntr=0.3,0.1

Type RM Length L Ch R = 1,153,0,0,0
BEGIN DESCRIPTION:
Stream0152_DS 0.0
END DESCRIPTION:
XS GIS Cut Line= 3
      2060170.38     13895756.49      2060419.58     13895722.52
      2060479.67     13895413.30
#Sta/Elev= 30
  4748.5 1268.52  4788.2 1267.56  4797.6 1268.09  4869.9 1264.17  4935.8 1256.69
  4965.1 1250.61  4985.3 1239.34  4992.4 1232.24  4992.9 1231.74  4997.9 1232.24
  5000.0 1232.24  5002.4 1238.89  5015.3 1245.76  5048.4 1256.29  5054.1 1256.00
  5059.2 1257.13  5089.2 1256.14  5105.8 1257.73  5110.8 1256.79  5134.5 1261.82
  5157.4 1265.00  5162.5 1263.35  5180.8 1267.83  5242.0 1273.36  5252.2 1275.42
  5260.8 1279.02  5265.9 1278.58  5272.5 1283.85  5292.9 1292.04  5315.0 1294.18
#Mann=7,-1,0
  4748.5   0.035       0  4788.2    0.07       0  4935.8    0.12       0
  4992.4    0.05       0  4997.9    0.12       0  5015.3    0.07       0
  5134.5    0.12       0
Bank Sta=4992.4,4997.9
Exp/Cntr=0.3,0.1

Chan Stop Cuts=-1