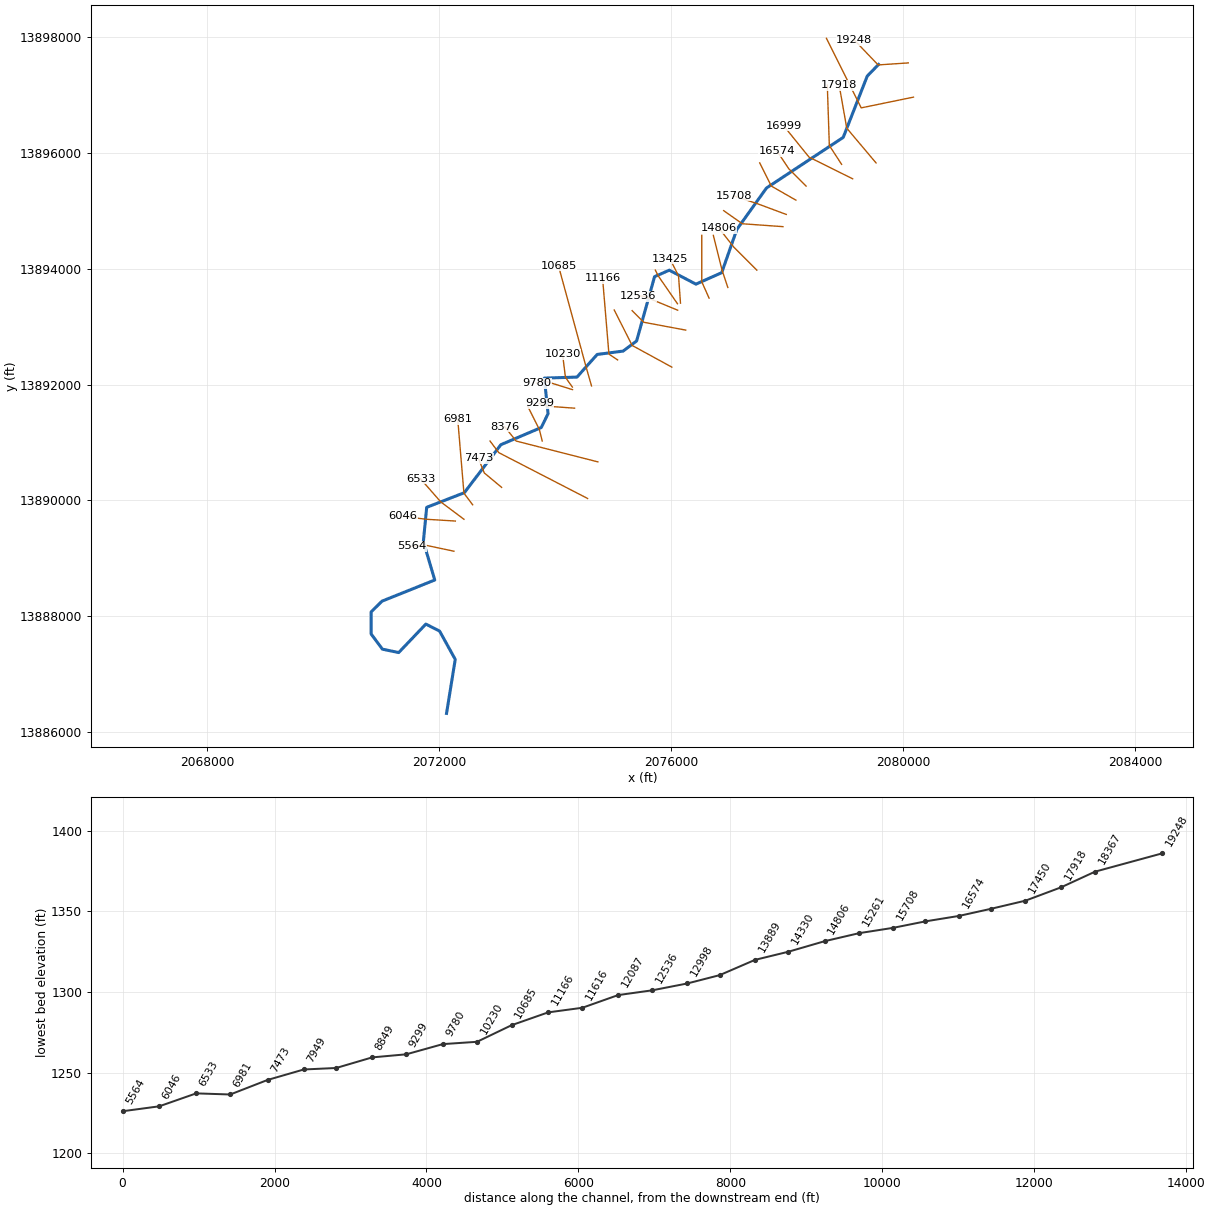
--- Stream0153_DS.prj (project) ---

Proj Title=Stream0153_DS Base Level Engineering
Current Plan=p01
Default Exp/Contr=0.3,0.1
English Units
Geom File=g01
Flow File=f01
Plan File=p01
BEGIN DESCRIPTION:
Stream0153_DS
END DESCRIPTION:

--- Stream0153_DS.p01 (plan) ---

Plan Title=Multiple Run
Short Identifier=Multiple
Geom File=g01
Flow File=f01
Subcritical Flow
K Sum by GR= 0
Std Step Tol= 0.01
Critical Tol= 0.01
Num of Std Step Trials= 20
Max Error Tol= 0.3
Flow Tol Ratio= 0.001
Split Flow NTrial= 30
Split Flow Tol= 0.02
Split Flow Ratio= 0.02
Log Output Level= 0
Friction Slope Method= 1
Unsteady Friction Slope Method= 2
Unsteady Bridges Friction Slope Method= 1
Parabolic Critical Depth
Global Vel Dist=  1 , 1 , 1
Global Log Level= 0
CheckData=True
Encroach Param= -1, 0, 0, 0
BEGIN DESCRIPTION:
Multiple Run
END DESCRIPTION:

--- Stream0153_DS.f01 (steady flow) ---

Flow Title=Multiple
Program Version=4.10
Number of Profiles= 7
Profile Names=10-year,25-year,50-year,1pct_min,100-year,1pct_plu,500-year
River Rch & RM=Stream0153_DS,Reach-1         ,19248
    1224    2084    2907    1965    3921    7824    7053
River Rch & RM=Stream0153_DS,Reach-1         ,18367
    1441    2475    3471    2357    4703    9385    8545
River Rch & RM=Stream0153_DS,Reach-1         ,16999
    1893    3292    4657    3186    6357   12683   11723
River Rch & RM=Stream0153_DS,Reach-1         ,11616
    2468    4342    6188    4261    8502   16963   15886
River Rch & RM=Stream0153_DS,Reach-1         ,4193
    2459    4318    6145    4225    8430   16819   15705
Boundary for River Rch & Prof#=Stream0153_DS,Reach-1         , 1
Up Type= 0
Dn Type= 3
Dn Slope=0.005
Boundary for River Rch & Prof#=Stream0153_DS,Reach-1         , 2
Up Type= 0
Dn Type= 3
Dn Slope=0.005
Boundary for River Rch & Prof#=Stream0153_DS,Reach-1         , 3
Up Type= 0
Dn Type= 3
Dn Slope=0.005
Boundary for River Rch & Prof#=Stream0153_DS,Reach-1         , 4
Up Type= 0
Dn Type= 3
Dn Slope=0.005
Boundary for River Rch & Prof#=Stream0153_DS,Reach-1         , 5
Up Type= 0
Dn Type= 3
Dn Slope=0.005
Boundary for River Rch & Prof#=Stream0153_DS,Reach-1         , 6
Up Type= 0
Dn Type= 3
Dn Slope=0.005
Boundary for River Rch & Prof#=Stream0153_DS,Reach-1         , 7
Up Type= 0
Dn Type= 3
Dn Slope=0.005
DSS Import GetInterval= 0
DSS Import GetPeak= 0
DSS Import FillOption= 0

--- Stream0153_DS.g01 (geometry) ---

Geom Title=Existing Conditions

River Reach=Stream0153_DS,Reach-1
Reach XY= 30
      2079575.00     13897525.00      2079378.54     13897323.53
      2078964.24     13896265.32      2077641.50     13895392.05
      2077130.46     13894677.45      2076869.41     13893930.61
      2076425.00     13893732.56      2075965.36     13893973.91
      2075711.44     13893861.52      2075401.99     13892751.53
      2075169.07     13892577.24      2074722.55     13892519.54
      2074373.55     13892128.53      2073811.36     13892111.56
      2073875.11     13891497.68      2073758.36     13891258.32
      2073061.28     13890961.77      2072431.06     13890133.14
      2071782.80     13889881.21      2071725.51     13889290.22
      2071921.88     13888626.62      2071011.79     13888261.37
      2070825.00     13888075.00      2070824.90     13887695.10
      2071018.94     13887433.14      2071300.12     13887374.70
      2071768.26     13887865.87      2072005.23     13887745.13
      2072274.96     13887256.67      2072125.00     13886325.00

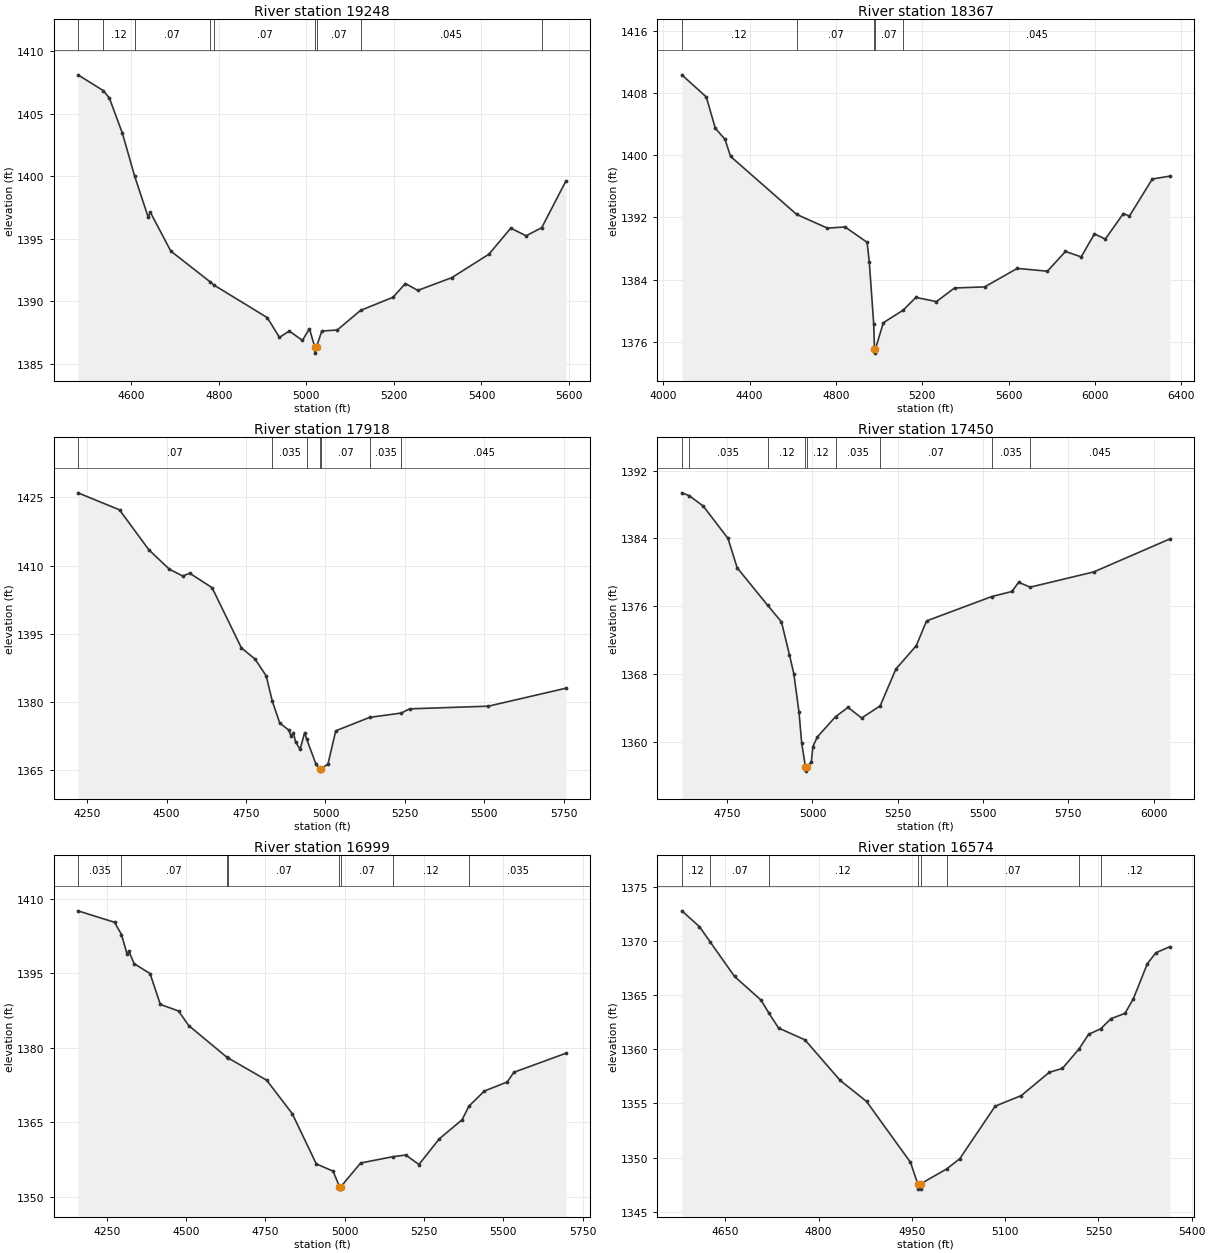
Type RM Length L Ch R = 1,19248,881,881,881
BEGIN DESCRIPTION:
Stream0153_DS 41.0
END DESCRIPTION:
XS GIS Cut Line= 3
      2080086.51     13897550.95      2079566.08     13897516.09
      2079156.35     13897944.77
#Sta/Elev= 30
  4478.4 1408.11  4536.1 1406.85  4550.1 1406.26  4580.1 1403.42  4608.0 1399.99
  4638.8 1396.73  4643.8 1397.11  4690.4 1394.01  4779.4 1391.57  4789.0 1391.29
  4910.9 1388.68  4938.7 1387.10  4961.0 1387.61  4991.1 1386.86  5007.1 1387.79
  5019.3 1386.34  5019.5 1385.84  5023.3 1386.34  5035.4 1387.61  5070.6 1387.69
  5123.9 1389.26  5198.0 1390.31  5226.3 1391.41  5254.6 1390.86  5332.3 1391.88
  5417.2 1393.76  5466.9 1395.84  5502.1 1395.23  5537.7 1395.88  5593.0 1399.62
#Mann=9,-1,0
  4478.4    0.07       0  4536.1    0.12       0  4608.0    0.07       0
  4779.4    0.12       0  4789.0    0.07       0  5019.3    0.05       0
  5023.3    0.07       0  5123.9   0.045       0  5537.7    0.07       0
Bank Sta=5019.3,5023.3
Exp/Cntr=0.3,0.1

Type RM Length L Ch R = 1,18367,449,449,449
BEGIN DESCRIPTION:
Stream0153_DS 40.0
END DESCRIPTION:
XS GIS Cut Line= 3
      2080176.04     13896960.41      2079275.00     13896775.00
      2078674.98     13897975.04
#Sta/Elev= 30
  4085.8 1410.34  4199.2 1407.49  4240.9 1403.48  4286.1 1402.03  4311.5 1399.85
  4618.1 1392.38  4760.7 1390.62  4842.4 1390.77  4944.5 1388.79  4954.7 1386.22
  4975.1 1378.29  4978.5 1375.04  4978.8 1374.54  4982.6 1375.04  5019.7 1378.45
  5111.6 1380.07  5170.6 1381.71  5265.7 1381.17  5349.5 1382.92  5489.3 1383.06
  5640.2 1385.44  5780.0 1385.08  5863.8 1387.62  5936.5 1386.92  5998.0 1389.88
  6048.3 1389.21  6132.1 1392.50  6160.1 1392.17  6266.3 1396.94  6347.4 1397.31
#Mann=5,-1,0
  4085.8    0.12       0  4618.1    0.07       0  4978.5    0.05       0
  4982.6    0.07       0  5111.6   0.045       0
Bank Sta=4978.5,4982.6
Exp/Cntr=0.3,0.1

Type RM Length L Ch R = 1,17918,468,468,468
BEGIN DESCRIPTION:
Stream0153_DS 39.0
END DESCRIPTION:
XS GIS Cut Line= 3
      2079530.19     13895825.02      2079025.00     13896425.00
      2078894.80     13897165.30
#Sta/Elev= 30
  4220.9 1425.98  4351.8 1422.24  4444.1 1413.45  4508.5 1409.20  4550.7 1407.69
  4572.8 1408.30  4643.1 1405.13  4735.4 1391.89  4778.3 1389.44  4813.4 1385.74
  4832.7 1380.16  4856.3 1375.35  4884.9 1373.81  4891.5 1372.44  4899.2 1373.27
  4905.8 1371.21  4920.1 1369.60  4934.4 1373.26  4941.1 1371.79  4969.5 1366.44
  4981.6 1365.30  4981.9 1364.80  4985.9 1365.30  5007.8 1366.34  5032.4 1373.67
  5139.4 1376.62  5238.8 1377.57  5264.6 1378.49  5512.9 1379.08  5756.9 1383.03
#Mann=7,-1,0
  4220.9    0.07       0  4832.7   0.035       0  4941.1    0.07       0
  4981.6    0.05       0  4985.9    0.07       0  5139.4   0.035       0
  5238.8   0.045       0
Bank Sta=4981.6,4985.9
Exp/Cntr=0.3,0.1

Type RM Length L Ch R = 1,17450,451,451,451
BEGIN DESCRIPTION:
Stream0153_DS 38.0
END DESCRIPTION:
XS GIS Cut Line= 3
      2078936.47     13895800.69      2078725.00     13896125.00
      2078689.97     13897167.84
#Sta/Elev= 30
  4617.1 1389.38  4638.4 1389.05  4679.9 1387.82  4752.4 1384.00  4779.4 1380.53
  4868.8 1376.11  4909.2 1374.15  4932.6 1370.27  4945.4 1368.04  4960.5 1363.54
  4968.5 1359.87  4979.4 1357.05  4979.7 1356.55  4983.8 1357.05  4996.7 1357.64
  5001.3 1359.45  5014.3 1360.58  5067.6 1362.97  5104.3 1364.07  5144.3 1362.82
  5198.6 1364.25  5244.4 1368.58  5304.4 1371.35  5334.5 1374.27  5526.0 1377.15
  5584.6 1377.74  5604.6 1378.83  5638.1 1378.25  5824.7 1380.05  6047.7 1383.94
#Mann=9,-1,0
  4617.1    0.07       0  4638.4   0.035       0  4868.8    0.12       0
  4979.4    0.05       0  4983.8    0.12       0  5067.6   0.035       0
  5198.6    0.07       0  5526.0   0.035       0  5638.1   0.045       0
Bank Sta=4979.4,4983.8
Exp/Cntr=0.3,0.1

Type RM Length L Ch R = 1,16999,425,425,425
BEGIN DESCRIPTION:
Stream0153_DS 37.0
END DESCRIPTION:
XS GIS Cut Line= 3
      2079127.45     13895550.68      2078375.00     13895925.00
      2077936.46     13896467.37
#Sta/Elev= 30
  4159.6 1407.58  4275.0 1405.27  4296.8 1402.81  4314.2 1398.90  4319.8 1399.48
  4336.6 1396.95  4386.9 1394.94  4419.2 1388.73  4476.5 1387.41  4508.6 1384.48
  4628.3 1378.13  4632.2 1377.97  4754.3 1373.47  4834.8 1366.75  4910.7 1356.62
  4963.6 1355.15  4983.8 1352.03  4984.1 1351.53  4988.3 1352.03  5050.4 1356.79
  5151.2 1358.05  5192.7 1358.40  5234.3 1356.49  5298.2 1361.65  5370.2 1365.50
  5391.8 1368.25  5440.5 1371.29  5512.5 1373.11  5533.3 1375.06  5697.5 1378.90
#Mann=8,-1,0
  4159.6   0.035       0  4296.8    0.07       0  4628.3   0.035       0
  4632.2    0.07       0  4983.8    0.05       0  4988.3    0.07       0
  5151.2    0.12       0  5391.8   0.035       0
Bank Sta=4983.8,4988.3
Exp/Cntr=0.3,0.1

Type RM Length L Ch R = 1,16574,444,444,444
BEGIN DESCRIPTION:
Stream0153_DS 36.0
END DESCRIPTION:
XS GIS Cut Line= 3
      2078324.98     13895425.02      2078025.00     13895725.00
      2077825.00     13896025.00
#Sta/Elev= 30
  4580.1 1372.81  4608.4 1371.35  4625.5 1369.95  4664.9 1366.74  4707.4 1364.56
  4720.0 1363.37  4735.6 1361.98  4778.1 1360.88  4834.6 1357.14  4877.1 1355.19
  4947.8 1349.56  4959.4 1347.58  4959.8 1347.08  4964.1 1347.08  4964.5 1347.58
  5005.8 1348.94  5026.9 1349.88  5084.0 1354.75  5126.0 1355.73  5171.1 1357.88
  5192.1 1358.24  5218.9 1360.04  5234.2 1361.39  5253.8 1361.91  5270.3 1362.84
  5292.8 1363.33  5306.3 1364.69  5328.8 1367.93  5342.4 1368.93  5364.9 1369.50
#Mann=8,-1,0
  4580.1    0.12       0  4625.5    0.07       0  4720.0    0.12       0
  4959.4    0.05       0  4964.5    0.12       0  5005.8    0.07       0
  5218.9   0.035       0  5253.8    0.12       0
Bank Sta=4959.4,4964.5
Exp/Cntr=0.3,0.1

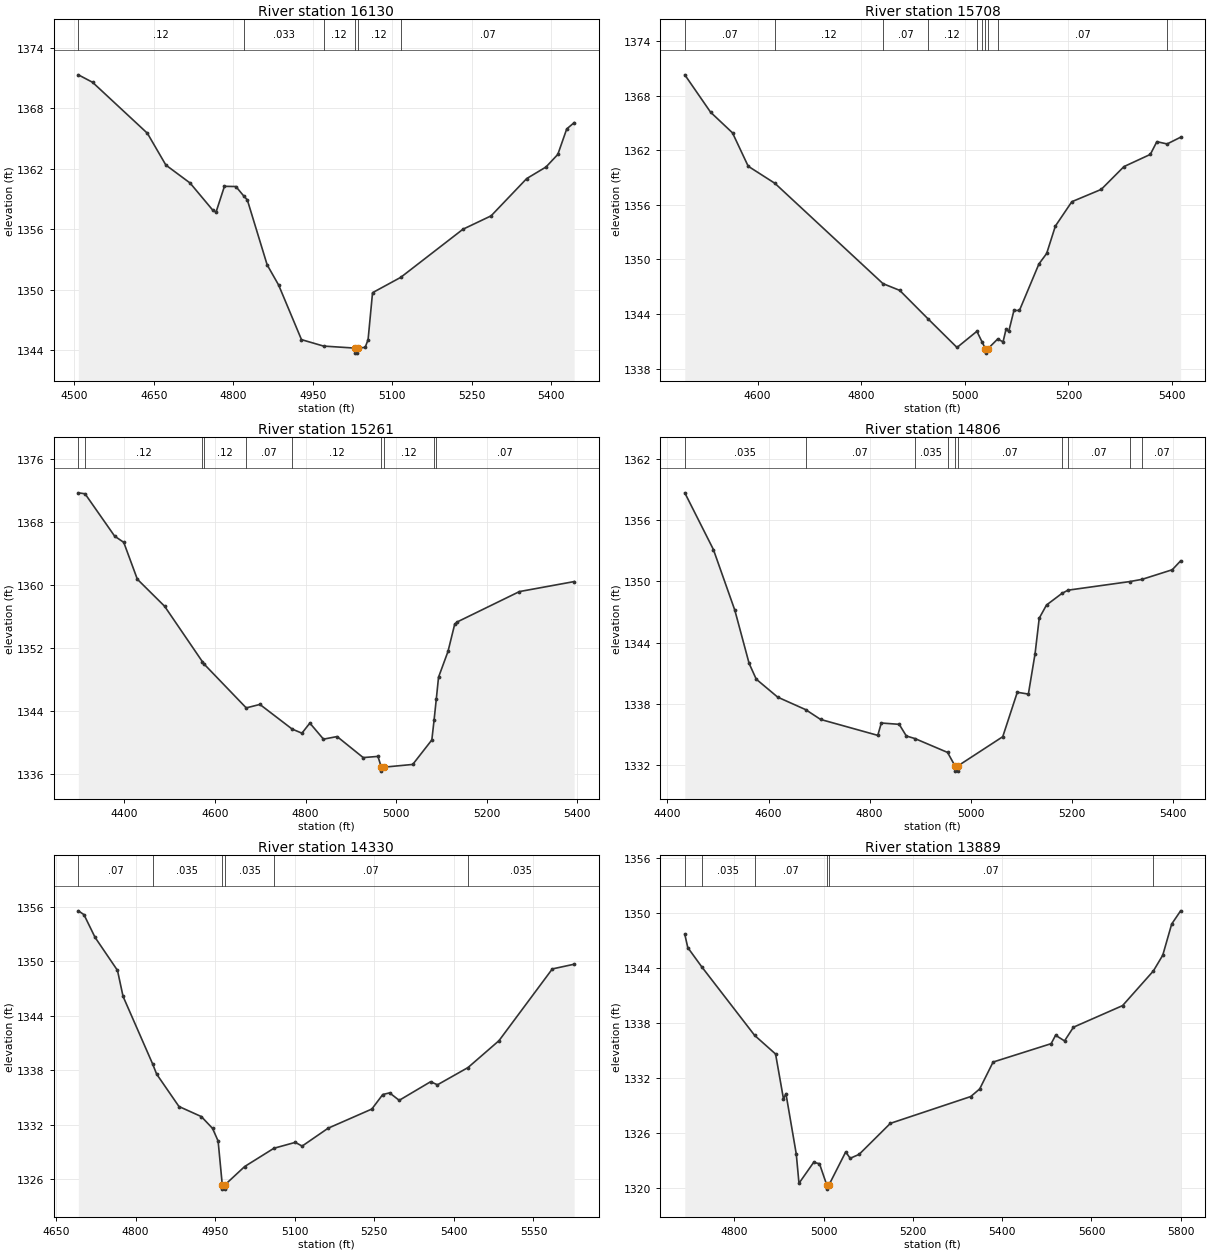
Type RM Length L Ch R = 1,16130,422,422,422
BEGIN DESCRIPTION:
Stream0153_DS 35.0
END DESCRIPTION:
XS GIS Cut Line= 3
      2078148.27     13895182.63      2077725.00     13895425.00
      2077524.98     13895825.03
#Sta/Elev= 30
  4507.9 1371.32  4534.7 1370.58  4638.1 1365.52  4673.0 1362.36  4718.6 1360.58
  4761.8 1357.86  4767.6 1357.69  4783.4 1360.25  4805.0 1360.23  4820.2 1359.27
  4826.6 1358.90  4864.0 1352.45  4885.6 1350.45  4928.7 1345.03  4970.3 1344.39
  5029.4 1344.19  5029.8 1343.69  5034.1 1343.69  5034.5 1344.19  5048.8 1344.26
  5054.3 1345.03  5062.7 1349.69  5115.8 1351.21  5233.2 1355.99  5286.3 1357.32
  5353.4 1361.02  5389.8 1362.17  5412.1 1363.42  5428.9 1365.95  5442.9 1366.57
#Mann=6,-1,0
  4507.9    0.12       0  4820.2   0.033       0  4970.3    0.12       0
  5029.4    0.05       0  5034.5    0.12       0  5115.8    0.07       0
Bank Sta=5029.4,5034.5
Exp/Cntr=0.3,0.1

Type RM Length L Ch R = 1,15708,447,447,447
BEGIN DESCRIPTION:
Stream0153_DS 34.0
END DESCRIPTION:
XS GIS Cut Line= 3
      2077981.62     13894936.10      2077475.00     13895125.00
      2077079.41     13895255.36
#Sta/Elev= 30
  4459.3 1370.30  4509.1 1366.19  4551.4 1363.92  4581.7 1360.25  4633.3 1358.37
  4841.9 1347.34  4874.2 1346.60  4928.5 1343.49  4984.8 1340.32  5023.2 1342.10
  5033.0 1340.95  5039.5 1340.20  5039.9 1339.70  5044.8 1340.20  5063.3 1341.25
  5073.7 1340.94  5079.4 1342.31  5084.7 1342.09  5094.7 1344.39  5105.3 1344.39
  5142.9 1349.50  5157.9 1350.66  5174.7 1353.67  5206.5 1356.35  5263.2 1357.70
  5307.1 1360.21  5358.0 1361.55  5370.6 1362.95  5390.4 1362.70  5416.5 1363.44
#Mann=10,-1,0
  4459.3    0.07       0  4633.3    0.12       0  4841.9    0.07       0
  4928.5    0.12       0  5023.2    0.07       0  5033.0    0.12       0
  5039.5    0.05       0  5044.8    0.12       0  5063.3    0.07       0
  5390.4   0.035       0
Bank Sta=5039.5,5044.8
Exp/Cntr=0.3,0.1

Type RM Length L Ch R = 1,15261,455,455,455
BEGIN DESCRIPTION:
Stream0153_DS 33.0
END DESCRIPTION:
XS GIS Cut Line= 3
      2077925.01     13894725.00      2077225.00     13894775.00
      2076903.25     13895001.02
#Sta/Elev= 30
  4298.2 1371.75  4313.0 1371.63  4378.4 1366.25  4398.5 1365.46  4428.5 1360.78
  4488.7 1357.35  4572.3 1350.30  4576.0 1350.00  4669.0 1344.44  4699.2 1344.88
  4770.4 1341.75  4792.0 1341.23  4809.5 1342.51  4839.6 1340.47  4869.7 1340.80
  4927.3 1338.13  4959.9 1338.28  4967.3 1336.91  4967.7 1336.41  4972.6 1336.91
  5036.7 1337.26  5078.9 1340.37  5083.9 1342.92  5088.7 1345.53  5093.7 1348.34
  5114.6 1351.61  5129.4 1355.07  5135.5 1355.37  5272.3 1359.21  5393.2 1360.48
#Mann=10,-1,0
  4298.2    0.07       0  4313.0    0.12       0  4572.3    0.07       0
  4576.0    0.12       0  4669.0    0.07       0  4770.4    0.12       0
  4967.3    0.05       0  4972.6    0.12       0  5083.9   0.035       0
  5088.7    0.07       0
Bank Sta=4967.3,4972.6
Exp/Cntr=0.3,0.1

Type RM Length L Ch R = 1,14806,476,476,476
BEGIN DESCRIPTION:
Stream0153_DS 32.0
END DESCRIPTION:
XS GIS Cut Line= 3
      2077475.01     13893974.99      2077075.00     13894375.00
      2076819.22     13894702.43
#Sta/Elev= 30
  4434.3 1358.66  4490.9 1353.11  4533.3 1347.17  4561.6 1341.96  4575.7 1340.42
  4618.2 1338.66  4673.4 1337.44  4703.0 1336.48  4816.2 1334.92  4823.2 1336.13
  4858.6 1336.00  4872.7 1334.86  4889.6 1334.61  4954.3 1333.25  4969.1 1331.92
  4969.5 1331.42  4974.0 1331.42  4974.4 1331.92  5063.5 1334.79  5092.3 1339.14
  5114.2 1338.96  5127.5 1342.93  5135.7 1346.39  5150.1 1347.68  5180.5 1348.81
  5192.5 1349.13  5314.4 1349.97  5339.1 1350.19  5398.9 1351.13  5415.5 1352.00
#Mann=10,-1,0
  4434.3   0.035       0  4673.4    0.07       0  4889.6   0.035       0
  4954.3    0.07       0  4969.1    0.05       0  4974.4    0.07       0
  5180.5   0.035       0  5192.5    0.07       0  5314.4   0.035       0
  5339.1    0.07       0
Bank Sta=4969.1,4974.4
Exp/Cntr=0.3,0.1

Type RM Length L Ch R = 1,14330,441,441,441
BEGIN DESCRIPTION:
Stream0153_DS 31.0
END DESCRIPTION:
XS GIS Cut Line= 3
      2076975.00     13893674.99      2076875.00     13893975.00
      2076725.00     13894574.99
#Sta/Elev= 30
  4692.0 1355.55  4702.6 1355.13  4723.6 1352.62  4765.8 1348.99  4776.3 1346.13
  4831.9 1338.71  4839.6 1337.57  4881.7 1334.00  4923.9 1332.89  4945.0 1331.59
  4955.5 1330.20  4963.3 1325.40  4963.7 1324.90  4968.4 1324.90  4968.9 1325.40
  5005.6 1327.39  5060.7 1329.40  5101.0 1330.05  5113.9 1329.64  5162.9 1331.61
  5245.3 1333.72  5265.9 1335.32  5278.8 1335.50  5296.9 1334.68  5356.1 1336.73
  5369.0 1336.39  5426.6 1338.29  5485.0 1341.25  5585.5 1349.15  5626.7 1349.67
#Mann=6,-1,0
  4692.0    0.07       0  4831.9   0.035       0  4963.3   0.035       0
  4968.9   0.035       0  5060.7    0.07       0  5426.6   0.035       0
Bank Sta=4963.3,4968.9
Exp/Cntr=0.3,0.1

Type RM Length L Ch R = 1,13889,464,464,464
BEGIN DESCRIPTION:
Stream0153_DS 30.0
END DESCRIPTION:
XS GIS Cut Line= 3
      2076651.76     13893491.63      2076525.00     13893775.00
      2076525.00     13894574.97
#Sta/Elev= 30
  4689.2 1347.69  4695.9 1346.24  4726.7 1344.17  4845.7 1336.64  4892.5 1334.61
  4910.2 1329.70  4915.7 1330.28  4938.9 1323.66  4944.9 1320.48  4977.7 1322.76
  4990.8 1322.62  5006.8 1320.34  5007.2 1319.84  5012.5 1320.34  5049.6 1323.91
  5059.6 1323.21  5079.6 1323.64  5149.6 1327.03  5329.6 1329.96  5349.6 1330.79
  5379.6 1333.73  5509.6 1335.74  5519.6 1336.66  5539.6 1336.04  5559.6 1337.54
  5669.6 1339.90  5738.6 1343.69  5759.6 1345.41  5779.6 1348.82  5799.6 1350.26
#Mann=6,-1,0
  4689.2    0.07       0  4726.7   0.035       0  4845.7    0.07       0
  5006.8    0.05       0  5012.5    0.07       0  5738.6   0.035       0
Bank Sta=5006.8,5012.5
Exp/Cntr=0.3,0.1

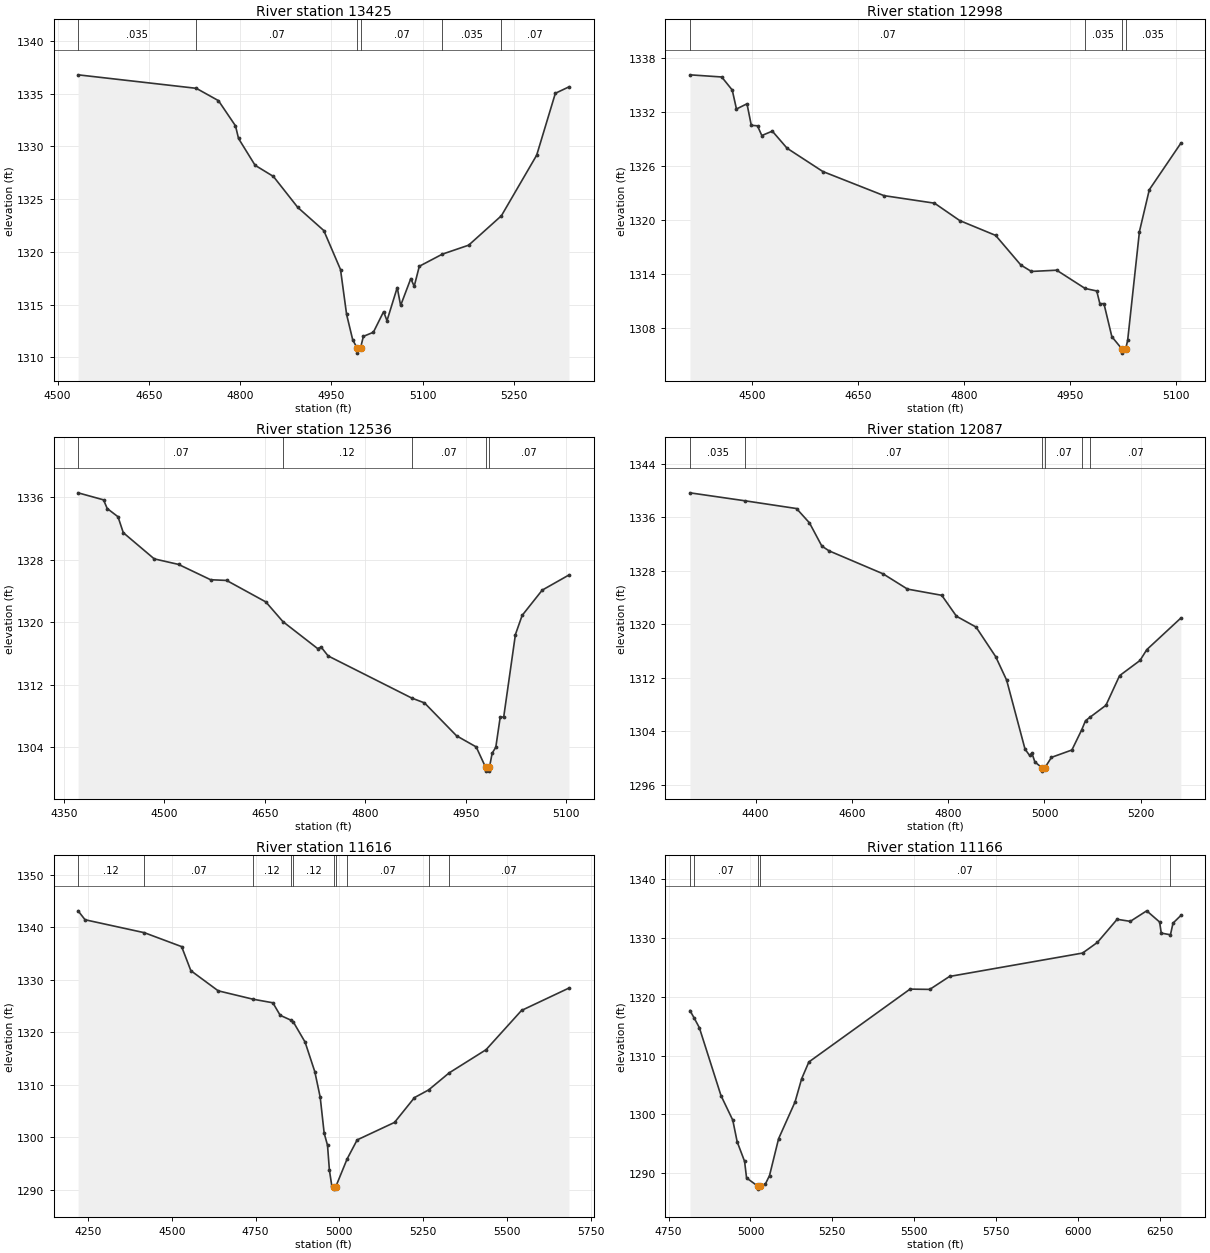
Type RM Length L Ch R = 1,13425,427,427,427
BEGIN DESCRIPTION:
Stream0153_DS 29.0
END DESCRIPTION:
XS GIS Cut Line= 3
      2076158.69     13893404.85      2076125.00     13893875.00
      2075974.99     13894175.03
#Sta/Elev= 30
  4533.6 1336.79  4727.9 1335.51  4764.3 1334.34  4792.3 1331.95  4797.3 1330.75
  4824.5 1328.21  4854.6 1327.15  4894.7 1324.21  4937.4 1322.02  4964.9 1318.32
  4974.9 1314.06  4984.9 1311.66  4992.0 1310.89  4992.5 1310.39  4997.8 1310.89
  5002.5 1311.98  5018.9 1312.37  5035.7 1314.32  5041.3 1313.47  5058.1 1316.61
  5063.7 1314.91  5080.4 1317.46  5086.0 1316.73  5094.4 1318.63  5132.3 1319.78
  5175.5 1320.63  5229.3 1323.42  5287.3 1329.17  5318.0 1335.04  5340.4 1335.65
#Mann=6,-1,0
  4533.6   0.035       0  4727.9    0.07       0  4992.0    0.05       0
  4997.8    0.07       0  5132.3   0.035       0  5229.3    0.07       0
Bank Sta=4992,4997.8
Exp/Cntr=0.3,0.1

Type RM Length L Ch R = 1,12998,462,462,462
BEGIN DESCRIPTION:
Stream0153_DS 28.0
END DESCRIPTION:
XS GIS Cut Line= 3
      2076106.58     13893394.47      2075775.00     13893875.00
      2075725.01     13893974.97
#Sta/Elev= 30
  4411.8 1336.16  4456.8 1335.92  4471.7 1334.47  4477.7 1332.36  4492.6 1332.94
  4498.7 1330.55  4507.5 1330.49  4513.6 1329.41  4528.5 1329.90  4549.4 1328.00
  4600.1 1325.41  4686.7 1322.73  4758.3 1321.89  4794.2 1319.95  4844.9 1318.31
  4880.7 1315.01  4895.6 1314.30  4931.4 1314.44  4971.7 1312.41  4988.2 1312.13
  4992.6 1310.72  4998.4 1310.72  5009.6 1307.05  5023.5 1305.72  5023.9 1305.22
  5029.3 1305.72  5032.0 1306.64  5048.7 1318.74  5062.7 1323.39  5107.4 1328.56
#Mann=4,-1,0
  4411.8    0.07       0  4971.7   0.035       0  5023.5   0.035       0
  5029.3   0.035       0
Bank Sta=5023.5,5029.3
Exp/Cntr=0.3,0.1

Type RM Length L Ch R = 1,12536,449,449,449
BEGIN DESCRIPTION:
Stream0153_DS 27.0
END DESCRIPTION:
XS GIS Cut Line= 3
      2076110.11     13893283.32      2075525.00     13893525.00
      2075424.96     13893525.00
#Sta/Elev= 30
  4371.0 1336.58  4409.0 1335.68  4414.5 1334.57  4430.6 1333.52  4438.5 1331.48
  4484.7 1328.13  4521.0 1327.42  4568.9 1325.46  4592.8 1325.37  4651.4 1322.62
  4676.9 1320.10  4728.6 1316.66  4734.0 1316.84  4744.4 1315.71  4869.3 1310.32
  4888.3 1309.70  4936.2 1305.49  4965.5 1304.07  4979.5 1301.47  4980.0 1300.97
  4984.9 1300.97  4985.3 1301.47  4989.4 1303.27  4994.8 1304.03  5001.4 1307.89
  5006.6 1307.89  5024.1 1318.45  5034.1 1320.89  5064.1 1324.13  5104.1 1326.07
#Mann=5,-1,0
  4371.0    0.07       0  4676.9    0.12       0  4869.3    0.07       0
  4979.5    0.05       0  4985.3    0.07       0
Bank Sta=4979.5,4985.3
Exp/Cntr=0.3,0.1

Type RM Length L Ch R = 1,12087,471,471,471
BEGIN DESCRIPTION:
Stream0153_DS 26.0
END DESCRIPTION:
XS GIS Cut Line= 3
      2076248.95     13892939.58      2075525.00     13893075.00
      2075324.97     13893275.03
#Sta/Elev= 30
  4263.9 1339.64  4379.0 1338.44  4485.2 1337.29  4512.1 1335.14  4537.8 1331.67
  4552.8 1330.96  4664.7 1327.53  4715.6 1325.24  4786.8 1324.31  4817.3 1321.18
  4858.0 1319.56  4898.7 1315.14  4921.5 1311.62  4959.7 1301.29  4969.0 1300.38
  4974.1 1300.68  4980.1 1299.39  4994.9 1298.51  4995.4 1298.01  5000.8 1298.51
  5014.6 1300.07  5057.0 1301.17  5077.6 1304.22  5085.3 1305.56  5094.8 1306.08
  5127.7 1307.86  5156.0 1312.29  5198.4 1314.56  5212.5 1316.18  5283.3 1320.91
#Mann=6,-1,0
  4263.9   0.035       0  4379.0    0.07       0  4994.9    0.05       0
  5000.8    0.07       0  5077.6   0.035       0  5094.8    0.07       0
Bank Sta=4994.9,5000.8
Exp/Cntr=0.3,0.1

Type RM Length L Ch R = 1,11616,450,450,450
BEGIN DESCRIPTION:
Stream0153_DS 25.0
END DESCRIPTION:
XS GIS Cut Line= 3
      2076009.40     13892300.68      2075325.00     13892675.00
      2075016.34     13893286.77
#Sta/Elev= 30
  4220.2 1343.17  4241.0 1341.47  4418.2 1339.00  4529.3 1336.35  4556.8 1331.77
  4638.4 1327.93  4742.5 1326.33  4801.6 1325.65  4823.4 1323.27  4856.8 1322.30
  4862.9 1321.97  4897.7 1318.17  4926.8 1312.52  4942.9 1307.66  4954.7 1300.82
  4964.7 1298.51  4970.4 1293.74  4977.5 1290.78  4983.4 1290.65  4983.9 1290.15
  4989.6 1290.65  5023.3 1295.91  5053.2 1299.53  5164.7 1302.86  5224.3 1307.59
  5266.5 1309.05  5327.9 1312.30  5437.9 1316.71  5543.8 1324.19  5685.5 1328.46
#Mann=10,-1,0
  4220.2    0.12       0  4418.2    0.07       0  4742.5    0.12       0
  4856.8    0.07       0  4862.9    0.12       0  4983.4    0.05       0
  4989.6    0.12       0  5023.3    0.07       0  5266.5   0.035       0
  5327.9    0.07       0
Bank Sta=4983.4,4989.6
Exp/Cntr=0.3,0.1

Type RM Length L Ch R = 1,11166,481,481,481
BEGIN DESCRIPTION:
Stream0153_DS 24.0
END DESCRIPTION:
XS GIS Cut Line= 3
      2075075.02     13892424.99      2074925.00     13892525.00
      2074814.94     13893838.90
#Sta/Elev= 30
  4815.3 1317.67  4828.1 1316.40  4843.9 1314.76  4910.0 1303.21  4946.0 1299.03
  4959.5 1295.34  4982.1 1292.02  4988.1 1289.20  5022.6 1287.80  5023.1 1287.30
  5028.8 1287.80  5045.8 1288.19  5058.2 1289.61  5085.9 1295.87  5136.1 1302.12
  5156.2 1306.05  5178.3 1308.92  5487.3 1321.31  5547.5 1321.26  5607.7 1323.46
  6014.0 1327.44  6059.3 1329.25  6119.5 1333.18  6159.7 1332.83  6209.8 1334.62
  6249.2 1332.72  6254.2 1330.83  6282.3 1330.55  6290.1 1332.53  6314.1 1333.83
#Mann=5,-1,0
  4815.3    0.12       0  4828.1    0.07       0  5022.6    0.05       0
  5028.8    0.07       0  6282.3   0.035       0
Bank Sta=5022.6,5028.8
Exp/Cntr=0.3,0.1

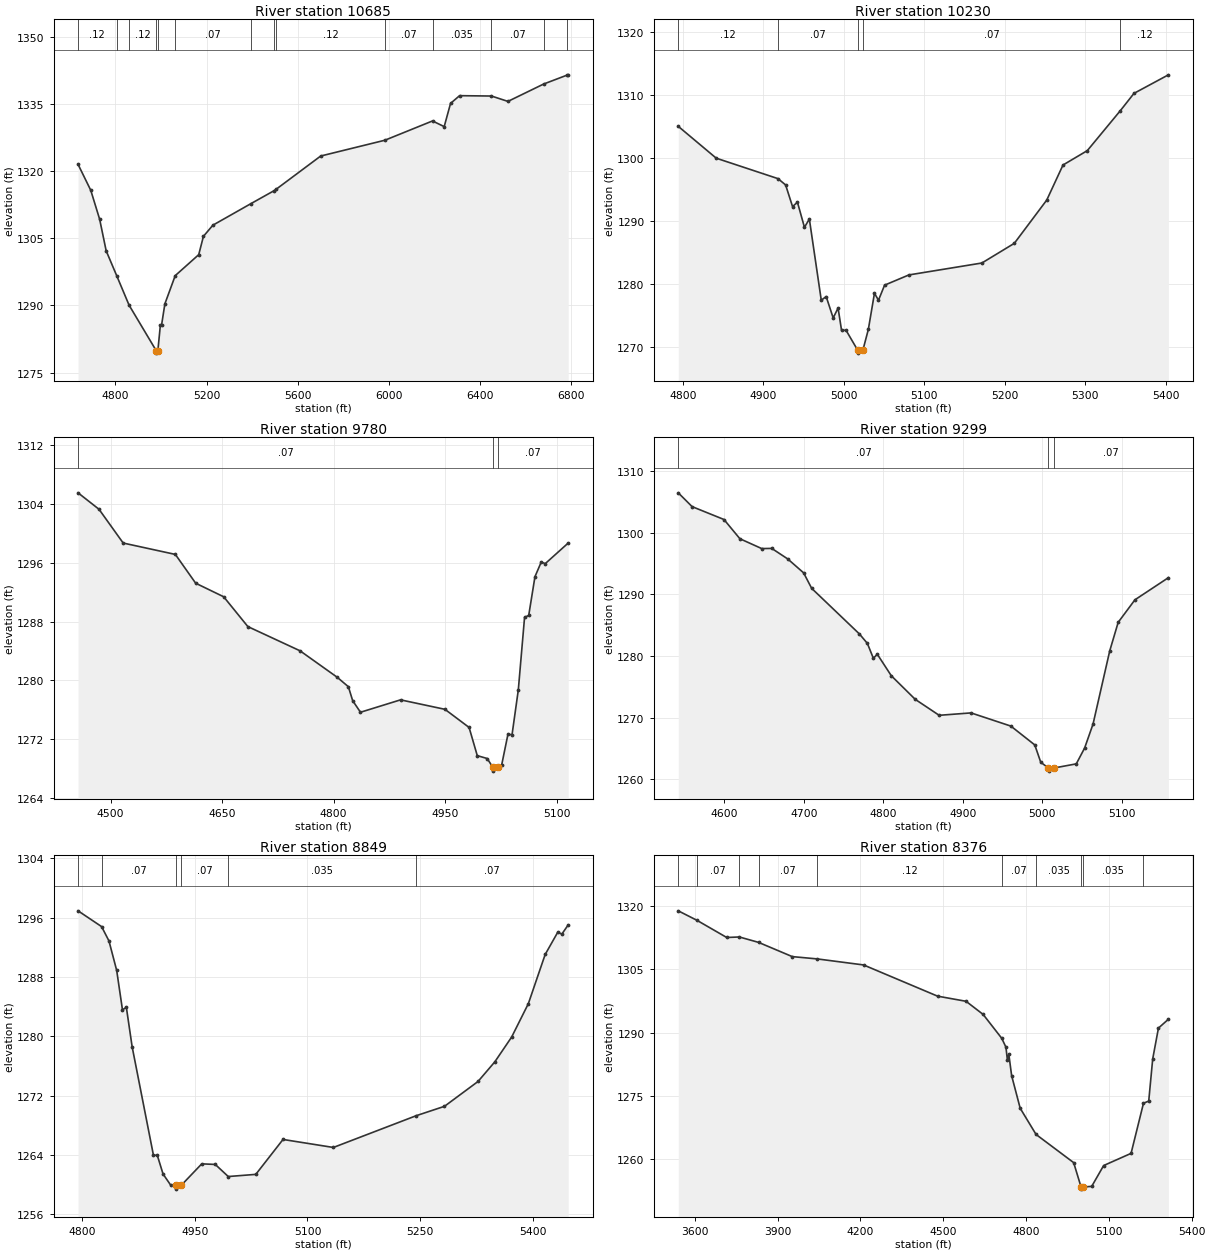
Type RM Length L Ch R = 1,10685,455,455,455
BEGIN DESCRIPTION:
Stream0153_DS 23.0
END DESCRIPTION:
XS GIS Cut Line= 3
      2074625.01     13891974.98      2074525.00     13892325.00
      2074054.63     13894050.30
#Sta/Elev= 30
  4635.7 1321.55  4691.6 1315.74  4730.6 1309.26  4759.2 1302.22  4805.4 1296.66
  4859.8 1290.07  4979.5 1279.85  4980.0 1279.35  4986.1 1279.85  4997.1 1285.57
  5002.3 1285.57  5017.0 1290.37  5062.4 1296.67  5165.6 1301.36  5186.3 1305.46
  5227.8 1307.95  5393.9 1312.74  5497.5 1315.69  5505.3 1315.97  5701.2 1323.41
  5983.0 1326.94  6192.2 1331.25  6243.5 1329.98  6271.4 1335.17  6311.1 1336.90
  6451.0 1336.82  6523.4 1335.62  6680.1 1339.50  6781.2 1341.46  6788.0 1341.56
#Mann=14,-1,0
  4635.7    0.12       0  4805.4    0.07       0  4859.8    0.12       0
  4979.5    0.05       0  4986.1    0.12       0  5062.4    0.07       0
  5393.9    0.12       0  5497.5    0.07       0  5505.3    0.12       0
  5983.0    0.07       0  6192.2   0.035       0  6451.0    0.07       0
  6680.1   0.035       0  6781.2    0.07       0
Bank Sta=4979.5,4986.1
Exp/Cntr=0.3,0.1

Type RM Length L Ch R = 1,10230,450,450,450
BEGIN DESCRIPTION:
Stream0153_DS 22.0
END DESCRIPTION:
XS GIS Cut Line= 3
      2074294.11     13891956.94      2074175.00     13892125.00
      2074125.00     13892525.00
#Sta/Elev= 30
  4794.5 1305.02  4841.7 1299.97  4918.4 1296.73  4927.9 1295.73  4936.5 1292.30
  4942.6 1292.99  4951.3 1289.01  4957.4 1290.32  4972.2 1277.45  4978.3 1278.03
  4987.0 1274.64  4993.1 1276.21  4997.4 1272.68  5003.0 1272.68  5017.3 1269.56
  5017.8 1269.06  5024.0 1269.56  5030.7 1272.82  5038.3 1278.55  5043.3 1277.45
  5050.9 1279.84  5081.1 1281.46  5171.8 1283.35  5212.1 1286.47  5252.4 1293.33
  5272.6 1298.89  5302.8 1301.17  5344.0 1307.53  5360.8 1310.25  5403.6 1313.19
#Mann=5,-1,0
  4794.5    0.12       0  4918.4    0.07       0  5017.3    0.05       0
  5024.0    0.07       0  5344.0    0.12       0
Bank Sta=5017.3,5024
Exp/Cntr=0.3,0.1

Type RM Length L Ch R = 1,9780,481,481,481
BEGIN DESCRIPTION:
Stream0153_DS 21.0
END DESCRIPTION:
XS GIS Cut Line= 3
      2074297.60     13891911.80      2073775.00     13892075.00
      2073674.99     13892025.00
#Sta/Elev= 30
  4456.2 1305.54  4484.4 1303.30  4516.9 1298.70  4587.1 1297.15  4614.4 1293.23
  4652.1 1291.38  4684.6 1287.32  4754.8 1284.02  4804.6 1280.43  4819.8 1279.13
  4825.6 1277.23  4836.1 1275.65  4890.0 1277.34  4949.7 1276.05  4982.2 1273.58
  4993.2 1269.74  5006.5 1269.35  5014.3 1268.13  5014.8 1267.63  5021.0 1268.13
  5026.0 1268.46  5034.4 1272.62  5040.0 1272.61  5048.4 1278.69  5056.8 1288.57
  5062.4 1288.84  5070.8 1294.12  5079.2 1296.10  5084.7 1295.90  5115.5 1298.70
#Mann=3,-1,0
  4456.2    0.07       0  5014.3    0.05       0  5021.0    0.07       0
Bank Sta=5014.3,5021
Exp/Cntr=0.3,0.1

Type RM Length L Ch R = 1,9299,450,450,450
BEGIN DESCRIPTION:
Stream0153_DS 20.0
END DESCRIPTION:
XS GIS Cut Line= 3
      2074332.35     13891592.35      2073875.00     13891625.00
      2073725.02     13891674.99
#Sta/Elev= 30
  4541.9 1306.48  4559.3 1304.24  4599.4 1302.15  4619.4 1299.03  4646.9 1297.43
  4659.5 1297.46  4679.6 1295.75  4699.6 1293.49  4709.7 1290.98  4769.8 1283.57
  4779.8 1282.04  4787.3 1279.63  4792.3 1280.28  4809.9 1276.79  4840.0 1272.96
  4870.1 1270.37  4910.2 1270.76  4960.3 1268.62  4990.4 1265.56  4997.9 1262.75
  5007.6 1261.81  5008.1 1261.31  5014.3 1261.81  5042.6 1262.49  5053.1 1265.06
  5063.7 1268.96  5084.7 1280.84  5095.3 1285.46  5116.4 1289.12  5158.5 1292.71
#Mann=3,-1,0
  4541.9    0.07       0  5007.6    0.05       0  5014.3    0.07       0
Bank Sta=5007.6,5014.3
Exp/Cntr=0.3,0.1

Type RM Length L Ch R = 1,8849,473,473,473
BEGIN DESCRIPTION:
Stream0153_DS 19.0
END DESCRIPTION:
XS GIS Cut Line= 3
      2073774.99     13891025.05      2073725.00     13891225.00
      2073525.01     13891624.98
#Sta/Elev= 30
  4794.2 1296.93  4825.6 1294.80  4835.4 1292.87  4845.7 1288.89  4853.4 1283.58
  4858.6 1283.91  4866.3 1278.59  4894.7 1263.96  4899.8 1263.96  4907.5 1261.43
  4917.8 1259.91  4924.8 1259.89  4925.3 1259.39  4931.6 1259.89  4959.1 1262.80
  4977.1 1262.72  4994.4 1261.09  5031.1 1261.38  5067.4 1266.09  5134.5 1265.01
  5244.8 1269.29  5282.6 1270.56  5327.3 1273.91  5349.7 1276.56  5372.1 1279.90
  5394.4 1284.41  5416.8 1291.04  5433.5 1294.03  5439.1 1293.80  5447.5 1295.03
#Mann=6,-1,0
  4794.2    0.12       0  4825.6    0.07       0  4924.8   0.035       0
  4931.6    0.07       0  4994.4   0.035       0  5244.8    0.07       0
Bank Sta=4924.8,4931.6
Exp/Cntr=0.3,0.1

Type RM Length L Ch R = 1,8376,427,427,427
BEGIN DESCRIPTION:
Stream0153_DS 18.0
END DESCRIPTION:
XS GIS Cut Line= 3
      2074735.05     13890665.28      2073325.00     13891025.00
      2073124.98     13891275.03
#Sta/Elev= 30
  3540.4 1318.91  3608.0 1316.66  3715.9 1312.58  3761.7 1312.70  3831.2 1311.42
  3953.3 1308.04  4044.1 1307.49  4211.6 1306.06  4479.6 1298.65  4582.8 1297.43
  4644.7 1294.31  4712.1 1288.64  4727.3 1286.53  4732.5 1283.47  4737.7 1284.86
  4747.9 1279.77  4778.9 1272.03  4836.4 1265.81  4972.6 1259.12  4999.4 1253.33
  4999.9 1252.83  5006.3 1253.33  5038.0 1253.49  5081.2 1258.43  5180.5 1261.32
  5225.5 1273.23  5244.5 1273.74  5258.9 1283.76  5279.7 1291.07  5315.8 1293.17
#Mann=10,-1,0
  3540.4    0.12       0  3608.0    0.07       0  3761.7    0.12       0
  3831.2    0.07       0  4044.1    0.12       0  4712.1    0.07       0
  4836.4   0.035       0  4999.4   0.035       0  5006.3   0.035       0
  5225.5    0.07       0
Bank Sta=4999.4,5006.3
Exp/Cntr=0.3,0.1

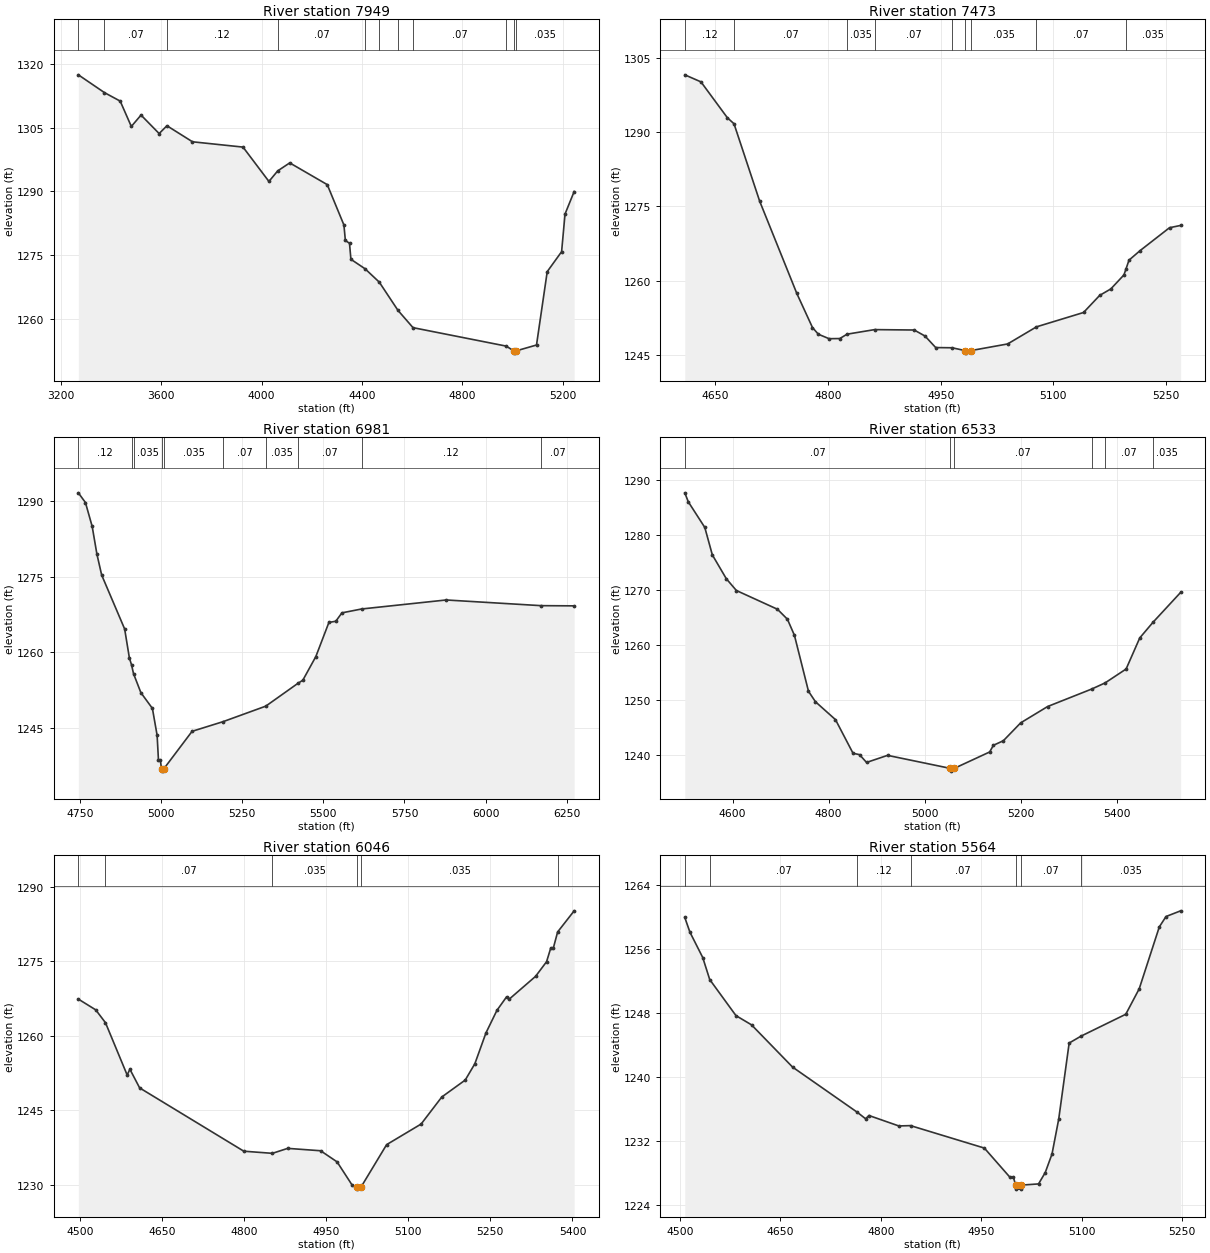
Type RM Length L Ch R = 1,7949,476,476,476
BEGIN DESCRIPTION:
Stream0153_DS 17.0
END DESCRIPTION:
XS GIS Cut Line= 3
      2074557.97     13890033.34      2073025.00     13890825.00
      2072875.01     13891024.99
#Sta/Elev= 30
  3270.1 1317.44  3374.2 1313.25  3436.9 1311.25  3481.2 1305.28  3519.9 1307.96
  3592.0 1303.61  3623.1 1305.45  3724.9 1301.67  3926.2 1300.42  4029.4 1292.33
  4064.4 1294.82  4112.3 1296.70  4261.8 1291.58  4328.2 1282.07  4333.9 1278.43
  4350.4 1277.77  4356.0 1274.00  4412.2 1271.77  4469.0 1268.62  4543.5 1261.97
  4603.4 1257.90  4974.9 1253.55  5005.5 1252.40  5006.0 1251.90  5012.4 1252.40
  5095.4 1253.81  5138.1 1271.09  5195.4 1275.79  5209.0 1284.65  5245.4 1289.96
#Mann=11,-1,0
  3270.1    0.12       0  3374.2    0.07       0  3623.1    0.12       0
  4064.4    0.07       0  4412.2    0.12       0  4469.0    0.07       0
  4543.5    0.12       0  4603.4    0.07       0  4974.9   0.035       0
  5005.5   0.035       0  5012.4   0.035       0
Bank Sta=5005.5,5012.4
Exp/Cntr=0.3,0.1

Type RM Length L Ch R = 1,7473,492,492,492
BEGIN DESCRIPTION:
Stream0153_DS 16.0
END DESCRIPTION:
XS GIS Cut Line= 3
      2073075.02     13890224.98      2072775.00     13890475.00
      2072675.00     13890725.01
#Sta/Elev= 30
  4609.5 1301.52  4631.0 1300.10  4666.1 1292.88  4675.0 1291.65  4709.1 1276.06
  4758.6 1257.44  4779.4 1250.58  4787.2 1249.23  4801.5 1248.33  4815.8 1248.36
  4825.4 1249.24  4862.1 1250.16  4914.8 1250.08  4929.1 1248.87  4943.4 1246.54
  4965.2 1246.50  4982.9 1245.92  4983.4 1245.42  4989.8 1245.92  5039.1 1247.27
  5077.5 1250.72  5140.1 1253.61  5161.6 1257.06  5176.4 1258.36  5193.9 1261.19
  5196.5 1262.34  5200.6 1264.16  5215.4 1266.09  5254.5 1270.70  5269.3 1271.16
#Mann=9,-1,0
  4609.5    0.12       0  4675.0    0.07       0  4825.4   0.035       0
  4862.1    0.07       0  4965.2   0.035       0  4982.9   0.035       0
  4989.8   0.035       0  5077.5    0.07       0  5196.5   0.035       0
Bank Sta=4982.9,4989.8
Exp/Cntr=0.3,0.1

Type RM Length L Ch R = 1,6981,448,448,448
BEGIN DESCRIPTION:
Stream0153_DS 15.0
END DESCRIPTION:
XS GIS Cut Line= 3
      2072575.02     13889924.97      2072425.00     13890125.00
      2072318.41     13891397.91
#Sta/Elev= 30
  4745.4 1291.70  4767.3 1289.77  4788.1 1285.01  4802.7 1279.49  4817.3 1275.36
  4888.1 1264.64  4902.7 1258.88  4909.3 1257.51  4915.5 1255.75  4938.1 1251.99
  4973.6 1248.86  4988.1 1243.52  4992.3 1238.52  4997.9 1238.52  5001.8 1236.90
  5002.3 1236.40  5009.2 1236.90  5095.8 1244.31  5191.3 1246.23  5322.8 1249.31
  5421.3 1253.82  5437.0 1254.47  5477.1 1259.17  5517.3 1265.95  5538.5 1266.18
  5557.4 1267.85  5618.2 1268.62  5878.5 1270.41  6170.7 1269.28  6272.8 1269.24
#Mann=10,-1,0
  4745.4    0.12       0  4909.3    0.07       0  4915.5   0.035       0
  5001.8   0.035       0  5009.2   0.035       0  5191.3    0.07       0
  5322.8   0.035       0  5421.3    0.07       0  5618.2    0.12       0
  6170.7    0.07       0
Bank Sta=5001.8,5009.2
Exp/Cntr=0.3,0.1

Type RM Length L Ch R = 1,6533,487,487,487
BEGIN DESCRIPTION:
Stream0153_DS 14.0
END DESCRIPTION:
XS GIS Cut Line= 3
      2072424.98     13889675.02      2072025.00     13889975.00
      2071674.99     13890375.01
#Sta/Elev= 30
  4500.7 1287.75  4508.0 1286.11  4542.3 1281.45  4558.0 1276.45  4587.1 1272.11
  4608.0 1269.97  4693.4 1266.56  4714.2 1264.74  4728.8 1261.81  4758.0 1251.63
  4772.5 1249.72  4814.2 1246.46  4850.7 1240.34  4864.2 1240.09  4878.8 1238.67
  4922.5 1239.96  5053.1 1237.59  5053.6 1237.09  5061.2 1237.59  5135.0 1240.58
  5142.6 1241.79  5163.4 1242.62  5199.5 1245.88  5255.5 1248.85  5347.4 1252.04
  5375.1 1253.15  5418.8 1255.68  5447.2 1261.34  5474.7 1264.18  5532.2 1269.62
#Mann=6,-1,0
  4500.7    0.07       0  5053.1    0.05       0  5061.2    0.07       0
  5347.4   0.035       0  5375.1    0.07       0  5474.7   0.035       0
Bank Sta=5053.1,5061.2
Exp/Cntr=0.3,0.1

Type RM Length L Ch R = 1,6046,482,482,482
BEGIN DESCRIPTION:
Stream0153_DS 13.0
END DESCRIPTION:
XS GIS Cut Line= 3
      2072276.78     13889644.44      2071775.00     13889675.00
      2071375.02     13889725.00
#Sta/Elev= 30
  4497.3 1267.35  4529.1 1265.18  4546.9 1262.59  4586.5 1252.06  4591.5 1253.22
  4609.3 1249.46  4799.6 1236.71  4851.8 1236.28  4879.8 1237.28  4939.9 1236.80
  4970.0 1234.56  4997.5 1229.88  5006.0 1229.57  5006.5 1229.07  5014.2 1229.57
  5060.5 1238.03  5123.5 1242.18  5161.3 1247.63  5204.1 1251.04  5221.7 1254.33
  5241.9 1260.52  5262.0 1265.08  5279.7 1267.81  5284.7 1267.36  5332.6 1271.93
  5352.7 1274.88  5360.3 1277.62  5365.3 1277.73  5372.9 1280.87  5403.1 1285.13
#Mann=6,-1,0
  4497.3    0.12       0  4546.9    0.07       0  4851.8   0.035       0
  5006.0   0.035       0  5014.2   0.035       0  5372.9    0.07       0
Bank Sta=5006,5014.2
Exp/Cntr=0.3,0.1

Type RM Length L Ch R = 1,5564,425,425,425
BEGIN DESCRIPTION:
Stream0153_DS 12.0
END DESCRIPTION:
XS GIS Cut Line= 3
      2072252.40     13889123.61      2071775.00     13889225.00
      2071523.27     13889210.41
#Sta/Elev= 30
  4507.5 1259.90  4515.1 1258.08  4534.3 1254.90  4544.7 1252.16  4583.9 1247.66
  4607.1 1246.51  4668.4 1241.24  4765.1 1235.60  4777.3 1234.80  4782.5 1235.20
  4827.0 1233.90  4844.5 1233.94  4954.7 1231.14  4993.0 1227.49  4998.1 1227.49
  5001.4 1226.52  5001.9 1226.02  5009.2 1226.02  5009.7 1226.52  5035.6 1226.67
  5045.6 1228.09  5055.7 1230.40  5065.7 1234.75  5081.3 1244.24  5099.0 1245.10
  5165.8 1247.83  5185.9 1251.01  5215.9 1258.73  5225.9 1260.02  5247.7 1260.73
#Mann=7,-1,0
  4507.5    0.12       0  4544.7    0.07       0  4765.1    0.12       0
  4844.5    0.07       0  5001.4    0.05       0  5009.7    0.07       0
  5099.0   0.035       0
Bank Sta=5001.4,5009.7
Exp/Cntr=0.3,0.1