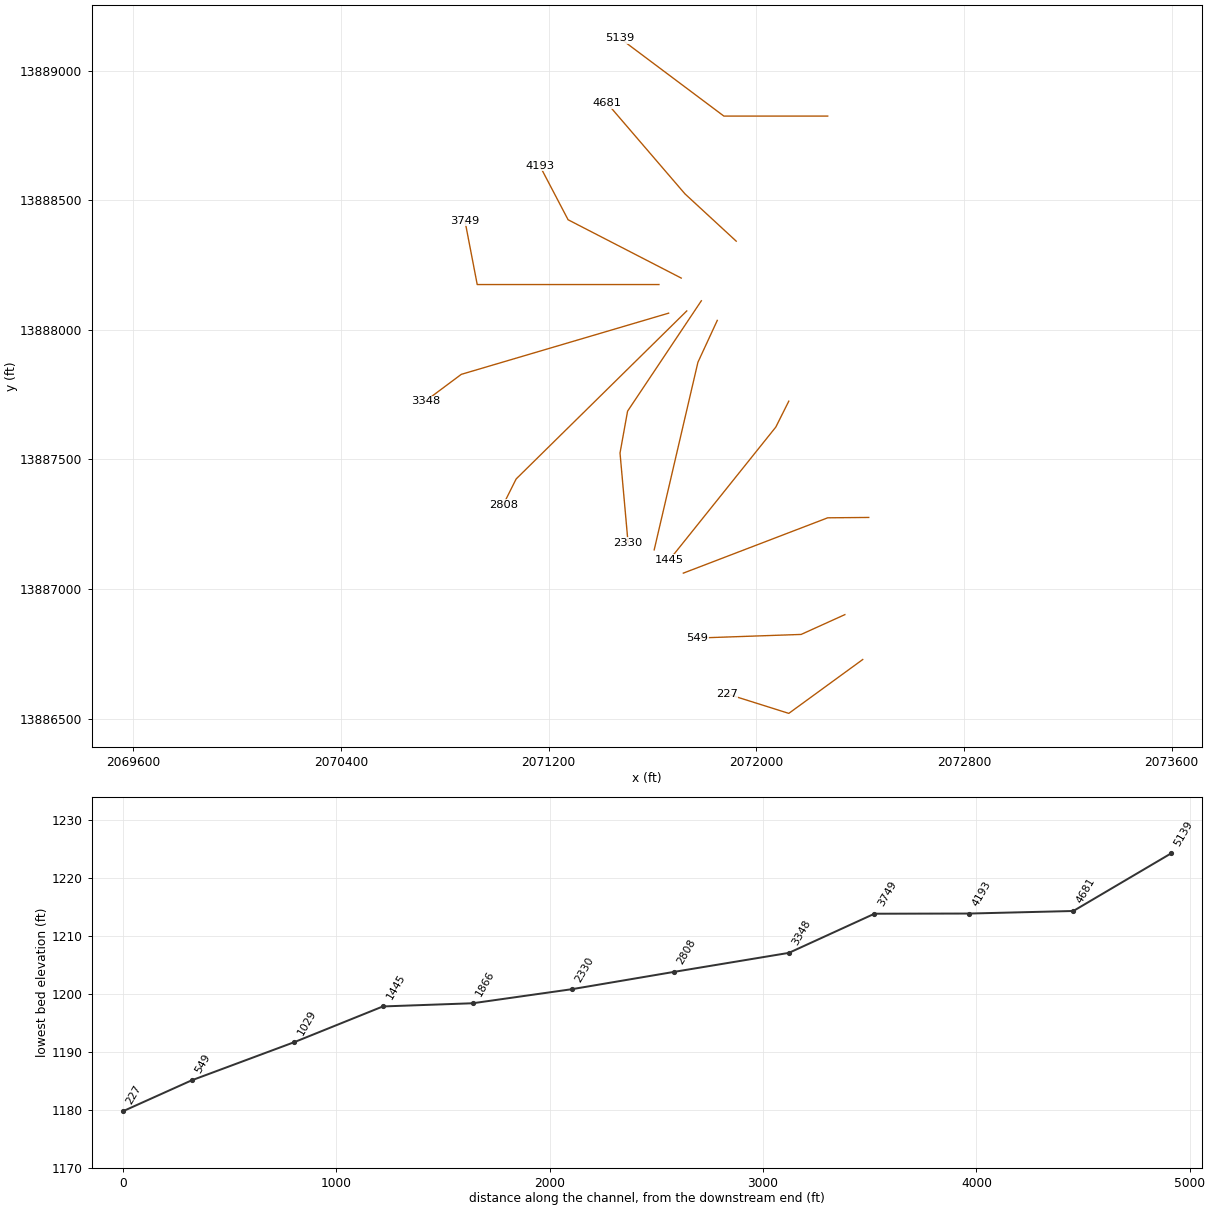
HEC-RAS study Stream0153_DS.prj: Stream0153_DS Base Level Engineering

--- Stream0153_DS.g01 (geometry) --- (continued)

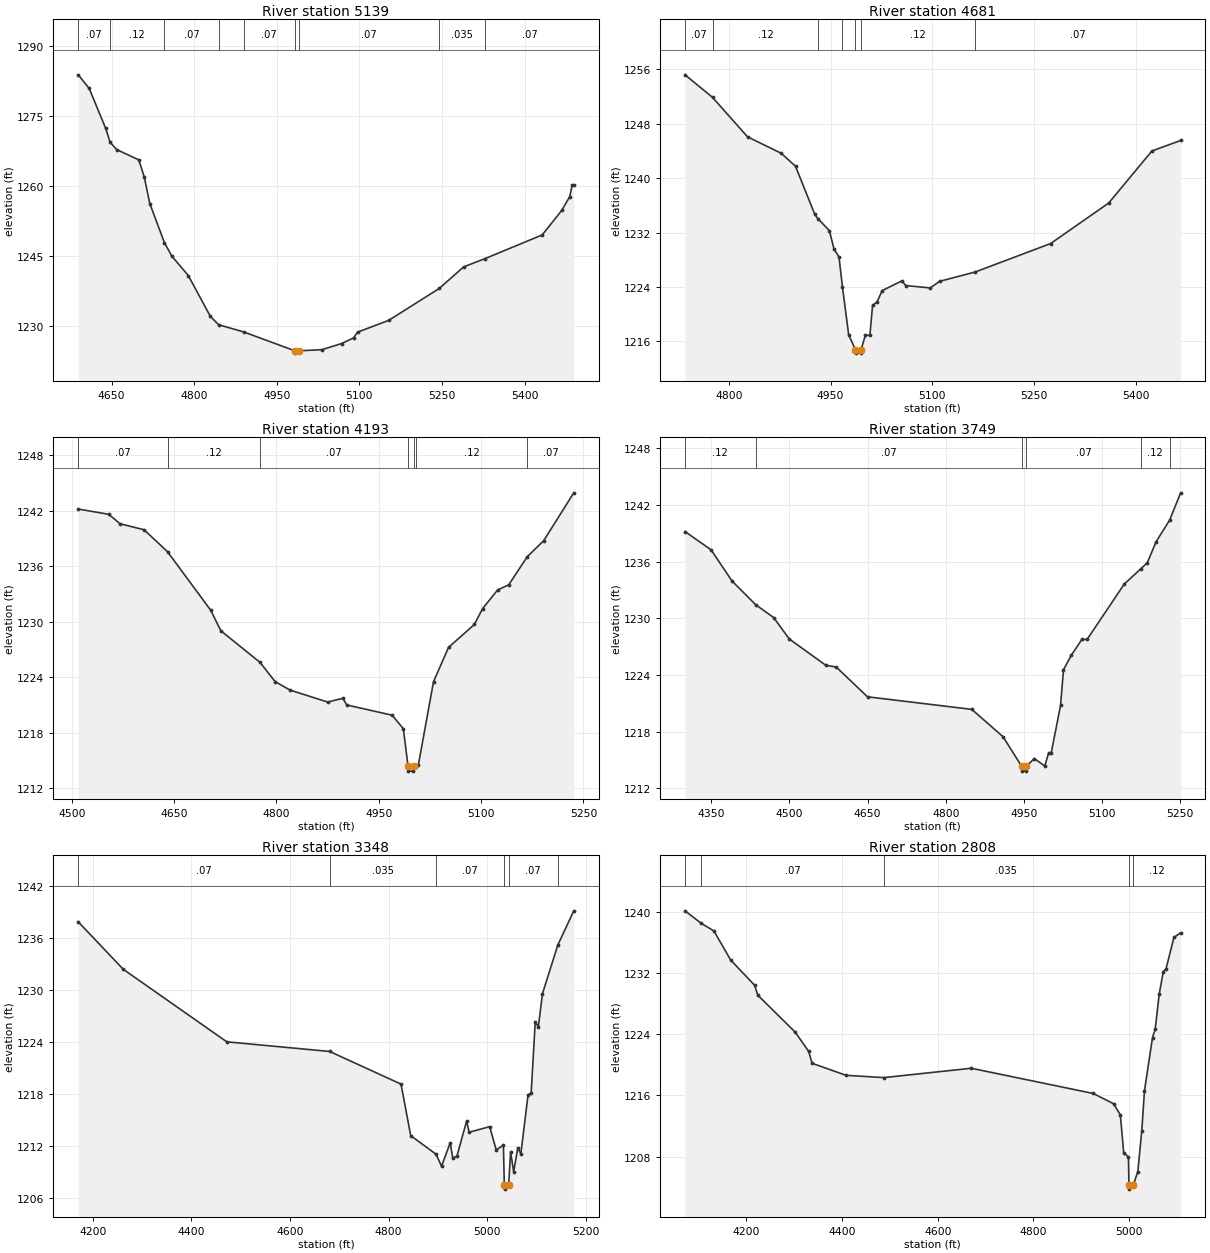
Type RM Length L Ch R = 1,5139,458,458,458
BEGIN DESCRIPTION:
Stream0153_DS 11.0
END DESCRIPTION:
XS GIS Cut Line= 3
      2072275.04     13888825.00      2071875.00     13888825.00
      2071475.03     13889124.98
#Sta/Elev= 30
  4589.5 1283.76  4609.5 1280.85  4639.5 1272.29  4647.5 1269.32  4659.5 1267.76
  4699.5 1265.57  4709.5 1261.92  4719.5 1256.23  4746.0 1247.87  4759.5 1244.99
  4789.5 1240.81  4829.5 1232.09  4844.6 1230.29  4890.2 1228.75  4982.9 1224.72
  4983.4 1224.22  4991.2 1224.72  5032.2 1224.96  5067.7 1226.27  5089.5 1227.47
  5096.8 1228.71  5153.1 1231.21  5245.1 1238.05  5289.5 1242.67  5328.5 1244.45
  5432.2 1249.51  5467.7 1254.76  5482.2 1257.72  5486.4 1260.13  5489.5 1260.13
#Mann=9,-1,0
  4589.5    0.07       0  4647.5    0.12       0  4746.0    0.07       0
  4844.6    0.12       0  4890.2    0.07       0  4982.9    0.05       0
  4991.2    0.07       0  5245.1   0.035       0  5328.5    0.07       0
Bank Sta=4982.9,4991.2
Exp/Cntr=0.3,0.1

Type RM Length L Ch R = 1,4681,488,488,488
BEGIN DESCRIPTION:
Stream0153_DS 10.0
END DESCRIPTION:
XS GIS Cut Line= 3
      2071922.55     13888342.38      2071725.00     13888525.00
      2071425.00     13888875.00
#Sta/Elev= 30
  4735.7 1255.15  4776.2 1251.84  4827.7 1246.05  4877.4 1243.63  4898.4 1241.73
  4926.8 1234.66  4931.9 1233.98  4948.3 1232.28  4955.1 1229.59  4962.5 1228.38
  4967.6 1223.97  4976.7 1217.01  4986.6 1214.79  4987.1 1214.29  4994.5 1214.29
  4995.0 1214.79  5001.3 1216.91  5008.0 1216.91  5011.9 1221.31  5018.4 1221.78
  5026.1 1223.47  5054.7 1224.88  5061.2 1224.21  5096.9 1223.86  5110.6 1224.83
  5163.3 1226.21  5274.2 1230.38  5359.8 1236.33  5423.4 1243.97  5465.7 1245.51
#Mann=7,-1,0
  4735.7    0.07       0  4776.2    0.12       0  4931.9    0.07       0
  4967.6    0.12       0  4986.6    0.05       0  4995.0    0.12       0
  5163.3    0.07       0
Bank Sta=4986.6,4995
Exp/Cntr=0.3,0.1

Type RM Length L Ch R = 1,4193,444,444,444
BEGIN DESCRIPTION:
Stream0153_DS 9.0
END DESCRIPTION:
XS GIS Cut Line= 3
      2071710.80     13888199.98      2071275.00     13888425.00
      2071165.62     13888634.05
#Sta/Elev= 30
  4509.5 1242.16  4554.3 1241.59  4570.8 1240.57  4606.1 1239.92  4640.4 1237.55
  4703.7 1231.23  4718.6 1229.01  4776.1 1225.59  4798.0 1223.53  4820.1 1222.60
  4875.3 1221.31  4897.5 1221.72  4903.1 1221.00  4969.6 1219.89  4986.1 1218.43
  4993.0 1214.35  4993.5 1213.85  5000.9 1213.85  5001.4 1214.35  5004.2 1214.40
  5008.2 1214.56  5030.3 1223.51  5052.3 1227.21  5090.3 1229.70  5102.1 1231.39
  5124.2 1233.41  5140.6 1233.98  5167.8 1237.02  5191.8 1238.74  5235.9 1243.91
#Mann=7,-1,0
  4509.5    0.07       0  4640.4    0.12       0  4776.1    0.07       0
  4993.0    0.05       0  5001.4    0.07       0  5004.2    0.12       0
  5167.8    0.07       0
Bank Sta=4993,5001.4
Exp/Cntr=0.3,0.1

Type RM Length L Ch R = 1,3749,401,401,401
BEGIN DESCRIPTION:
Stream0153_DS 8.0
END DESCRIPTION:
XS GIS Cut Line= 3
      2071624.97     13888175.00      2070925.00     13888175.00
      2070877.65     13888421.12
#Sta/Elev= 30
  4300.0 1239.19  4350.0 1237.25  4390.0 1233.96  4435.5 1231.44  4470.0 1230.08
  4500.0 1227.81  4570.0 1225.03  4590.0 1224.84  4650.0 1221.69  4850.0 1220.36
  4910.0 1217.46  4945.8 1214.32  4946.3 1213.82  4953.7 1213.82  4954.2 1214.32
  4970.0 1215.15  4990.0 1214.36  4997.5 1215.77  5002.5 1215.77  5020.3 1220.80
  5025.9 1224.55  5040.7 1226.07  5061.1 1227.76  5071.2 1227.77  5142.5 1233.63
  5173.9 1235.23  5186.8 1235.90  5203.6 1238.12  5229.4 1240.39  5250.6 1243.29
#Mann=6,-1,0
  4300.0    0.12       0  4435.5    0.07       0  4945.8    0.05       0
  4954.2    0.07       0  5173.9    0.12       0  5229.4    0.07       0
Bank Sta=4945.8,4954.2
Exp/Cntr=0.3,0.1

Type RM Length L Ch R = 1,3348,540,540,540
BEGIN DESCRIPTION:
Stream0153_DS 7.0
END DESCRIPTION:
XS GIS Cut Line= 3
      2071662.14     13888064.57      2070863.55     13887828.47
      2070724.99     13887724.99
#Sta/Elev= 30
  4170.3 1237.85  4261.7 1232.38  4471.8 1224.03  4680.5 1222.92  4825.4 1219.16
  4845.1 1213.23  4896.5 1211.09  4907.7 1209.70  4925.2 1212.41  4930.4 1210.62
  4939.0 1210.89  4958.5 1214.91  4963.7 1213.62  5005.3 1214.26  5018.6 1211.58
  5033.2 1212.13  5035.0 1207.57  5035.5 1207.07  5043.9 1207.57  5047.8 1211.38
  5054.0 1209.06  5062.4 1211.82  5068.6 1211.13  5083.2 1217.93  5089.5 1218.12
  5097.8 1226.34  5104.1 1225.74  5112.4 1229.56  5143.6 1235.17  5176.0 1239.11
#Mann=6,-1,0
  4170.3    0.07       0  4680.5   0.035       0  4896.5    0.07       0
  5035.0    0.05       0  5043.9    0.07       0  5143.6   0.035       0
Bank Sta=5035,5043.9
Exp/Cntr=0.3,0.1

Type RM Length L Ch R = 1,2808,478,478,478
BEGIN DESCRIPTION:
Stream0153_DS 6.0
END DESCRIPTION:
XS GIS Cut Line= 3
      2071732.02     13888073.12      2071075.00     13887425.00
      2071025.00     13887325.00
#Sta/Elev= 30
  4072.5 1240.09  4105.8 1238.48  4132.7 1237.47  4168.0 1233.65  4217.6 1230.39
  4224.6 1229.07  4302.4 1224.27  4330.7 1221.74  4337.7 1220.20  4408.5 1218.63
  4487.5 1218.33  4670.2 1219.55  4924.7 1216.26  4967.2 1214.92  4981.3 1213.47
  4988.3 1208.54  4998.2 1207.98  4999.3 1204.28  4999.8 1203.78  5008.2 1204.28
  5017.8 1206.07  5026.1 1211.39  5031.7 1216.63  5048.5 1223.56  5054.1 1224.65
  5062.5 1229.23  5070.9 1232.12  5076.5 1232.48  5093.2 1236.61  5107.2 1237.23
#Mann=5,-1,0
  4072.5    0.12       0  4105.8    0.07       0  4487.5   0.035       0
  4999.3   0.035       0  5008.2    0.12       0
Bank Sta=4999.3,5008.2
Exp/Cntr=0.3,0.1

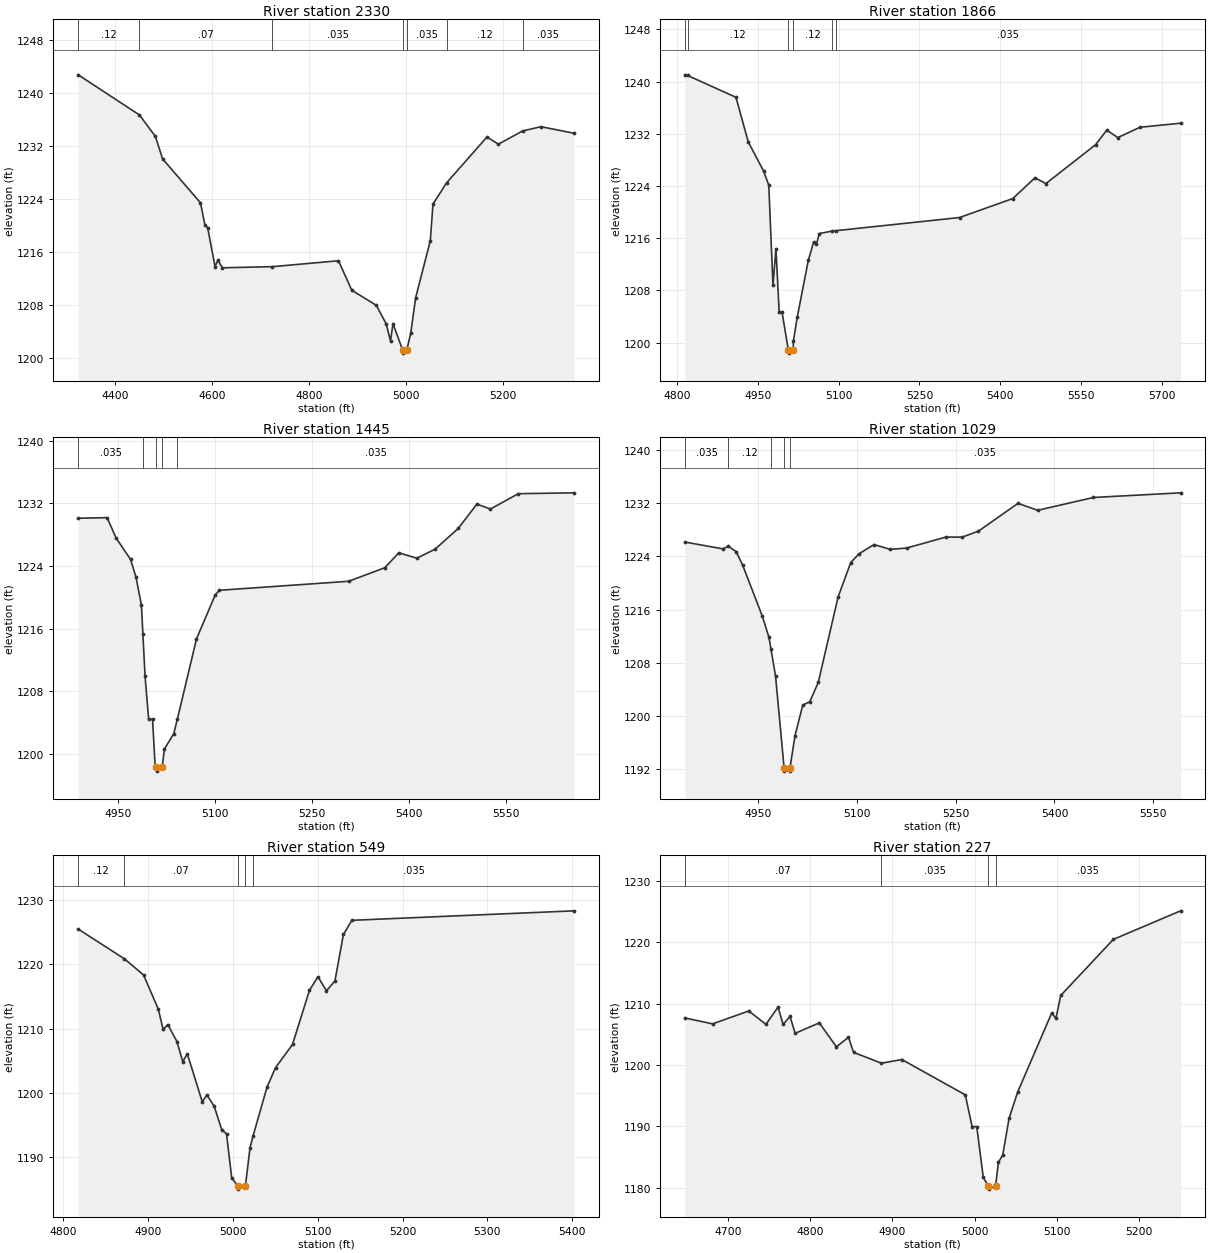
Type RM Length L Ch R = 1,2330,464,464,464
BEGIN DESCRIPTION:
Stream0153_DS 5.0
END DESCRIPTION:
XS GIS Cut Line= 4
      2071788.21     13888112.39      2071504.06     13887686.40
      2071475.00     13887525.00      2071505.88     13887179.54
#Sta/Elev= 30
  4323.9 1242.71  4450.3 1236.66  4483.0 1233.44  4498.0 1230.05  4576.1 1223.44
  4585.1 1220.16  4591.1 1219.64  4606.1 1213.84  4612.1 1214.79  4621.1 1213.65
  4724.5 1213.82  4860.8 1214.71  4888.2 1210.27  4939.0 1207.99  4959.3 1205.19
  4968.1 1202.64  4973.2 1205.23  4993.0 1201.30  4993.5 1200.80  5001.9 1201.30
  5010.0 1203.88  5020.0 1209.15  5050.2 1217.72  5055.7 1223.23  5083.8 1226.45
  5167.0 1233.34  5190.7 1232.27  5240.4 1234.25  5278.4 1234.90  5346.8 1233.91
#Mann=7,-1,0
  4323.9    0.12       0  4450.3    0.07       0  4724.5   0.035       0
  4993.0   0.035       0  5001.9   0.035       0  5083.8    0.12       0
  5240.4   0.035       0
Bank Sta=4993,5001.9
Exp/Cntr=0.3,0.1

Type RM Length L Ch R = 1,1866,421,421,421
BEGIN DESCRIPTION:
Stream0153_DS 4.0
END DESCRIPTION:
XS GIS Cut Line= 3
      2071849.64     13888036.76      2071775.00     13887875.00
      2071606.61     13887151.38
#Sta/Elev= 30
  4814.1 1241.03  4819.4 1240.93  4909.2 1237.59  4932.1 1230.75  4960.6 1226.28
  4970.2 1224.12  4978.0 1208.76  4983.5 1214.39  4989.5 1204.68  4994.8 1204.68
  5006.5 1198.88  5007.0 1198.38  5015.5 1198.88  5016.1 1200.31  5023.0 1203.85
  5043.6 1212.58  5053.6 1215.42  5058.7 1215.04  5064.1 1216.71  5087.8 1217.08
  5094.4 1217.14  5324.5 1219.16  5423.5 1222.07  5464.5 1225.24  5485.1 1224.37
  5577.5 1230.34  5598.0 1232.56  5618.5 1231.41  5659.6 1232.99  5735.2 1233.62
#Mann=6,-1,0
  4814.1   0.035       0  4819.4    0.12       0  5006.5    0.05       0
  5015.5    0.12       0  5087.8    0.07       0  5094.4   0.035       0
Bank Sta=5006.5,5015.5
Exp/Cntr=0.3,0.1

Type RM Length L Ch R = 1,1445,416,416,416
BEGIN DESCRIPTION:
Stream0153_DS 3.0
END DESCRIPTION:
XS GIS Cut Line= 3
      2072124.99     13887724.99      2072075.00     13887625.00
      2071665.62     13887113.17
#Sta/Elev= 30
  4888.2 1230.11  4932.9 1230.18  4946.9 1227.57  4969.2 1224.85  4977.6 1222.59
  4986.0 1219.03  4988.3 1215.30  4991.6 1209.96  4997.2 1204.45  5003.2 1204.45
  5007.2 1198.51  5009.1 1198.33  5009.6 1197.83  5018.1 1198.33  5021.6 1200.66
  5036.0 1202.60  5041.8 1204.53  5071.2 1214.70  5100.0 1220.29  5106.4 1220.91
  5306.5 1222.06  5362.6 1223.79  5384.1 1225.69  5412.2 1225.01  5440.3 1226.15
  5476.2 1228.81  5505.0 1231.91  5525.9 1231.28  5569.1 1233.24  5655.4 1233.35
#Mann=5,-1,0
  4888.2   0.035       0  4988.3    0.07       0  5009.1    0.05       0
  5018.1    0.07       0  5041.8   0.035       0
Bank Sta=5009.1,5018.1
Exp/Cntr=0.3,0.1

Type RM Length L Ch R = 1,1029,480,480,480
BEGIN DESCRIPTION:
Stream0153_DS 2.0
END DESCRIPTION:
XS GIS Cut Line= 3
      2072432.98     13887276.38      2072275.00     13887275.00
      2071718.84     13887061.54
#Sta/Elev= 30
  4838.0 1226.17  4896.0 1225.14  4904.2 1225.53  4916.0 1224.74  4926.0 1222.69
  4956.0 1214.98  4966.0 1211.81  4968.9 1210.13  4976.0 1206.00  4989.0 1192.16
  4989.5 1191.66  4997.5 1191.66  4998.0 1192.16  5005.6 1197.00  5017.4 1201.61
  5028.1 1202.12  5041.0 1205.04  5071.0 1217.86  5090.3 1223.08  5103.1 1224.41
  5125.7 1225.79  5150.4 1225.06  5175.1 1225.26  5235.1 1226.92  5259.8 1226.91
  5284.4 1227.81  5344.5 1231.99  5374.5 1230.95  5459.2 1232.88  5591.7 1233.58
#Mann=5,-1,0
  4838.0   0.035       0  4904.2    0.12       0  4968.9   0.035       0
  4989.0   0.035       0  4998.0   0.035       0
Bank Sta=4989,4998
Exp/Cntr=0.3,0.1

Type RM Length L Ch R = 1,549,322,322,322
BEGIN DESCRIPTION:
Stream0153_DS 1.0
END DESCRIPTION:
XS GIS Cut Line= 3
      2072341.00     13886901.40      2072172.58     13886825.00
      2071773.27     13886811.11
#Sta/Elev= 30
  4817.7 1225.43  4872.2 1220.81  4894.7 1218.32  4912.1 1213.01  4917.8 1209.86
  4923.3 1210.62  4934.1 1207.98  4940.9 1204.86  4946.3 1206.09  4963.9 1198.64
  4969.4 1199.70  4978.0 1197.94  4987.0 1194.27  4992.5 1193.68  4998.6 1186.86
  5005.7 1185.59  5006.2 1185.09  5014.8 1185.59  5020.2 1191.49  5023.8 1193.33
  5040.2 1200.89  5050.3 1203.94  5070.3 1207.53  5090.3 1215.94  5100.3 1218.04
  5110.3 1215.84  5120.3 1217.39  5130.3 1224.59  5140.3 1226.79  5402.2 1228.26
#Mann=5,-1,0
  4817.7    0.12       0  4872.2    0.07       0  5005.7    0.05       0
  5014.8    0.07       0  5023.8   0.035       0
Bank Sta=5005.7,5014.8
Exp/Cntr=0.3,0.1

Type RM Length L Ch R = 1,227,0,0,0
BEGIN DESCRIPTION:
Stream0153_DS 0.0
END DESCRIPTION:
XS GIS Cut Line= 3
      2072409.82     13886728.22      2072125.08     13886520.42
      2071886.01     13886595.87
#Sta/Elev= 30
  4647.5 1207.66  4681.4 1206.69  4725.4 1208.79  4746.3 1206.61  4761.0 1209.42
  4767.1 1206.59  4775.6 1207.90  4781.8 1205.15  4811.2 1206.85  4832.0 1202.95
  4846.7 1204.50  4852.9 1202.04  4886.8 1200.28  4911.6 1200.88  4988.8 1195.12
  4997.0 1189.95  5002.7 1189.95  5010.6 1181.72  5016.5 1180.26  5017.0 1179.76
  5025.6 1180.26  5029.1 1184.15  5034.3 1185.31  5042.0 1191.27  5052.5 1195.59
  5093.8 1208.44  5099.0 1207.59  5104.9 1211.32  5168.9 1220.46  5250.7 1225.11
#Mann=4,-1,0
  4647.5    0.07       0  4886.8   0.035       0  5016.5   0.035       0
  5025.6   0.035       0
Bank Sta=5016.5,5025.6
Exp/Cntr=0.3,0.1

Chan Stop Cuts=-1