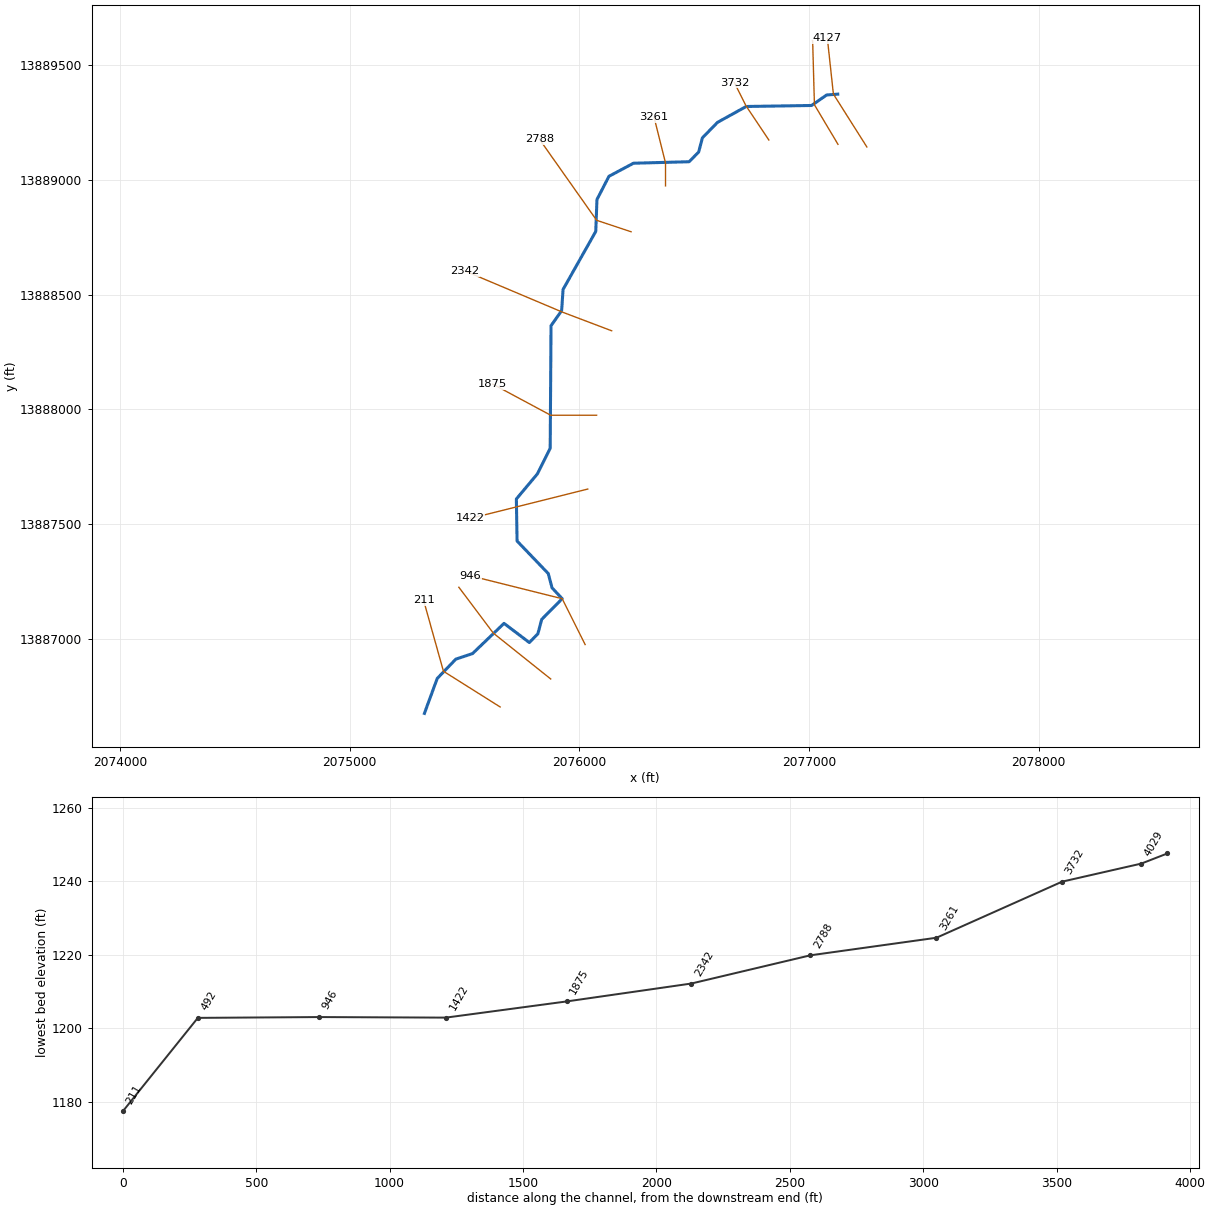
--- Stream0154_DS.prj (project) ---

Proj Title=Stream0154_DS Base Level Engineering
Current Plan=p01
Default Exp/Contr=0.3,0.1
English Units
Geom File=g01
Flow File=f01
Plan File=p01
BEGIN DESCRIPTION:
Stream0154_DS
END DESCRIPTION:

--- Stream0154_DS.p01 (plan) ---

Plan Title=Multiple Run
Short Identifier=Multiple
Geom File=g01
Flow File=f01
Subcritical Flow
K Sum by GR= 0
Std Step Tol= 0.01
Critical Tol= 0.01
Num of Std Step Trials= 20
Max Error Tol= 0.3
Flow Tol Ratio= 0.001
Split Flow NTrial= 30
Split Flow Tol= 0.02
Split Flow Ratio= 0.02
Log Output Level= 0
Friction Slope Method= 1
Unsteady Friction Slope Method= 2
Unsteady Bridges Friction Slope Method= 1
Parabolic Critical Depth
Global Vel Dist=  1 , 1 , 1
Global Log Level= 0
CheckData=True
Encroach Param= -1, 0, 0, 0
BEGIN DESCRIPTION:
Multiple Run
END DESCRIPTION:

--- Stream0154_DS.f01 (steady flow) ---

Flow Title=Multiple
Number of Profiles=7
Profile Names=10-year,25-year,50-year,1pct_min,100-year,1pct_plu,500-year
River Rch & RM= Stream0154_DS,Reach-1,4127
     952    1592    2193    1464    2922    5830    5128
River Rch & RM= Stream0154_DS,Reach-1,3732
    1127    1900    2633    1767    3526    7036    6255
River Rch & RM= Stream0154_DS,Reach-1,946
    1416    2423    3390    2296    4581    9141    8278
Boundary for River Rch & Prof#=Stream0154_DS,Reach-1,1
Up Type=0
Dn Type=3
Dn Slope=0.005
Boundary for River Rch & Prof#=Stream0154_DS,Reach-1,2
Up Type=0
Dn Type=3
Dn Slope=0.005
Boundary for River Rch & Prof#=Stream0154_DS,Reach-1,3
Up Type=0
Dn Type=3
Dn Slope=0.005
Boundary for River Rch & Prof#=Stream0154_DS,Reach-1,4
Up Type=0
Dn Type=3
Dn Slope=0.005
Boundary for River Rch & Prof#=Stream0154_DS,Reach-1,5
Up Type=0
Dn Type=3
Dn Slope=0.005
Boundary for River Rch & Prof#=Stream0154_DS,Reach-1,6
Up Type=0
Dn Type=3
Dn Slope=0.005
Boundary for River Rch & Prof#=Stream0154_DS,Reach-1,7
Up Type=0
Dn Type=3
Dn Slope=0.005

--- Stream0154_DS.g01 (geometry) ---

Geom Title=Existing Conditions

River Reach=Stream0154_DS,Reach-1
Reach XY= 30
      2077125.00     13889375.00      2077076.51     13889371.35
      2077011.11     13889325.60      2076726.55     13889321.25
      2076601.48     13889252.01      2076535.78     13889184.68
      2076519.26     13889122.43      2076477.70     13889080.36
      2076235.48     13889073.81      2076128.66     13889016.83
      2076076.36     13888915.36      2076071.24     13888776.56
      2075928.83     13888523.42      2075922.53     13888430.57
      2075876.38     13888365.34      2075872.76     13887830.93
      2075816.84     13887718.95      2075725.38     13887609.84
      2075728.54     13887426.46      2075864.30     13887284.71
      2075880.71     13887222.65      2075925.00     13887175.00
      2075835.72     13887084.67      2075819.15     13887022.13
      2075781.95     13886983.85      2075671.67     13887067.39
      2075534.68     13886935.78      2075461.76     13886911.38
      2075380.81     13886827.32      2075325.00     13886675.00

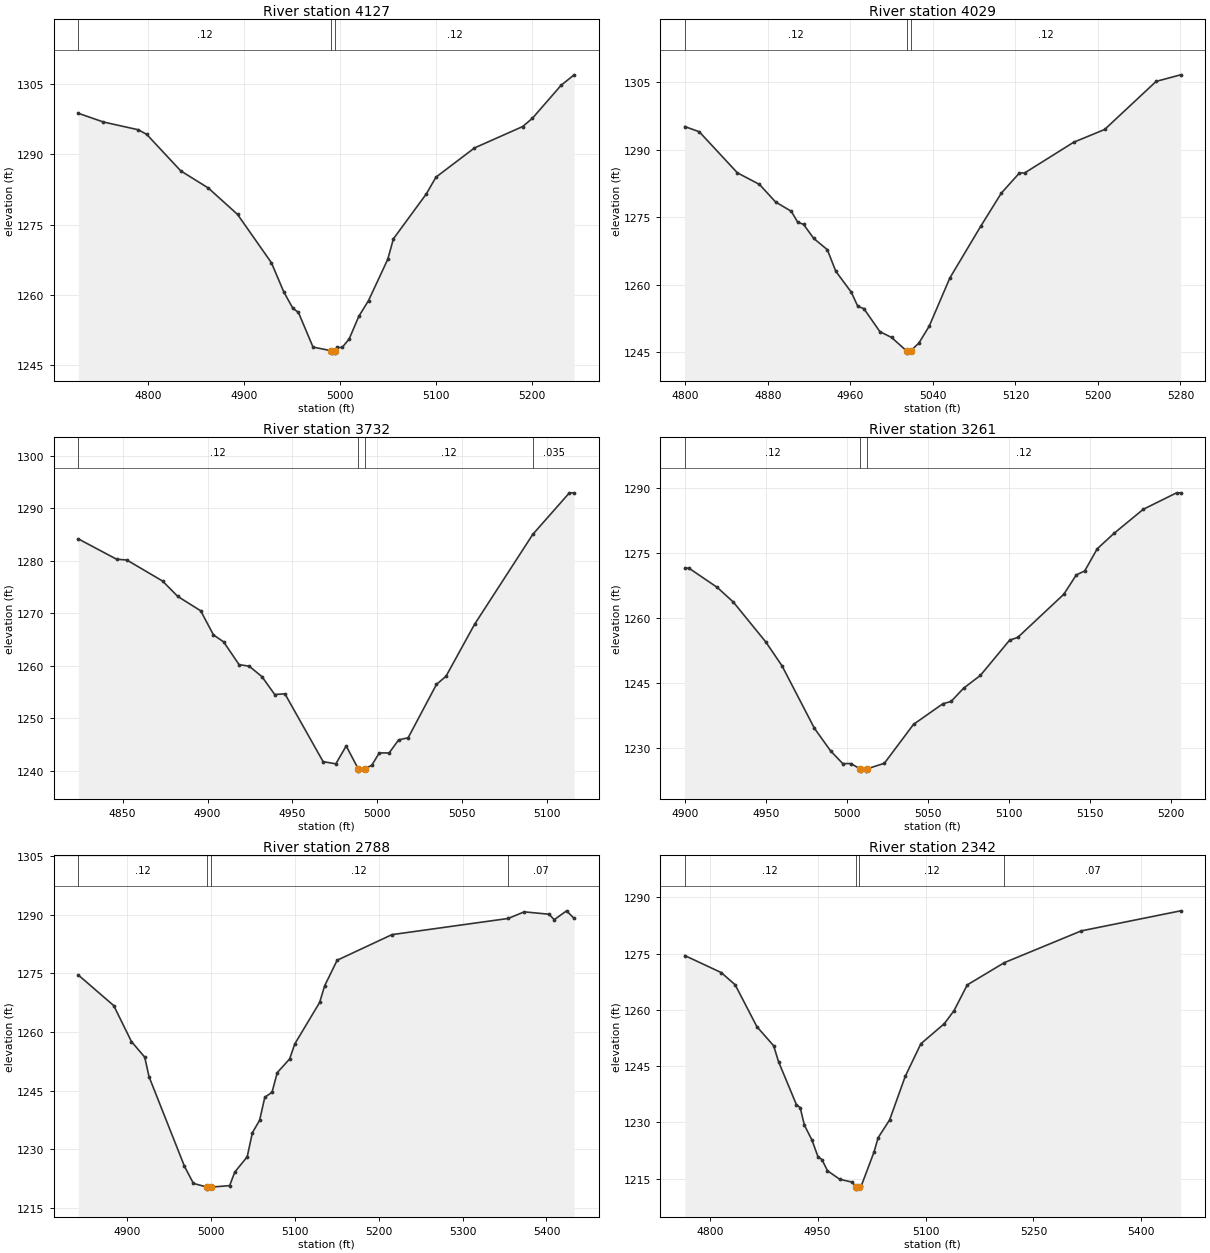
Type RM Length L Ch R = 1,4127,98,98,98
BEGIN DESCRIPTION:
Stream0154_DS 10.0
END DESCRIPTION:
XS GIS Cut Line= 3
      2077251.91     13889144.62      2077106.08     13889375.41
      2077079.83     13889618.39
#Sta/Elev= 30
  4727.0 1298.70  4753.2 1296.84  4789.6 1295.19  4798.4 1294.20  4833.9 1286.43
  4862.6 1282.79  4893.1 1277.17  4928.5 1266.87  4941.4 1260.65  4950.8 1257.19
  4956.7 1256.28  4971.9 1248.91  4991.1 1248.12  4991.4 1247.62  4994.9 1247.62
  4995.1 1248.12  4996.8 1248.82  5002.3 1248.82  5009.6 1250.64  5019.7 1255.46
  5029.8 1258.81  5049.9 1267.61  5055.8 1271.97  5090.1 1281.52  5100.2 1285.10
  5140.4 1291.32  5190.7 1295.88  5200.8 1297.63  5230.9 1304.69  5244.4 1306.89
#Mann=3,-1,0
  4727.0    0.12       0  4991.1    0.05       0  4995.1    0.12       0
Bank Sta=4991.1,4995.1
Exp/Cntr=0.3,0.1

Type RM Length L Ch R = 1,4029,297,297,297
BEGIN DESCRIPTION:
Stream0154_DS 9.0
END DESCRIPTION:
XS GIS Cut Line= 3
      2077126.09     13889156.22      2077023.51     13889328.60
      2077015.73     13889608.70
#Sta/Elev= 30
  4799.4 1295.13  4813.4 1293.98  4850.4 1284.86  4871.8 1282.29  4887.4 1278.40
  4902.7 1276.32  4908.8 1273.94  4914.6 1273.41  4924.4 1270.31  4937.6 1267.81
  4945.8 1263.03  4960.9 1258.35  4967.2 1255.21  4973.0 1254.74  4988.6 1249.61
  5000.0 1248.32  5014.4 1245.35  5014.7 1244.85  5018.4 1245.35  5026.4 1247.09
  5036.4 1250.83  5056.4 1261.52  5086.4 1273.02  5106.4 1280.38  5123.9 1284.83
  5128.9 1284.83  5176.5 1291.65  5206.5 1294.48  5256.5 1305.16  5280.2 1306.61
#Mann=3,-1,0
  4799.4    0.12       0  5014.4    0.05       0  5018.4    0.12       0
Bank Sta=5014.4,5018.4
Exp/Cntr=0.3,0.1

Type RM Length L Ch R = 1,3732,471,471,471
BEGIN DESCRIPTION:
Stream0154_DS 8.0
END DESCRIPTION:
XS GIS Cut Line= 3
      2076825.00     13889174.99      2076725.00     13889325.00
      2076675.00     13889425.01
#Sta/Elev= 30
  4823.9 1284.20  4846.4 1280.33  4852.5 1280.17  4873.5 1276.17  4882.5 1273.23
  4896.0 1270.49  4903.5 1265.90  4909.5 1264.57  4918.6 1260.23  4924.6 1259.93
  4932.1 1257.93  4939.6 1254.53  4945.6 1254.67  4968.1 1241.74  4975.6 1241.32
  4981.7 1244.73  4988.7 1240.43  4988.9 1239.93  4992.7 1240.43  4996.7 1241.01
  5001.2 1243.40  5007.0 1243.40  5012.6 1245.89  5018.2 1246.29  5034.9 1256.47
  5040.5 1258.01  5057.3 1267.90  5091.6 1285.05  5113.2 1292.98  5116.0 1292.98
#Mann=4,-1,0
  4823.9    0.12       0  4988.7    0.05       0  4992.7    0.12       0
  5091.6   0.035       0
Bank Sta=4988.7,4992.7
Exp/Cntr=0.3,0.1

Type RM Length L Ch R = 1,3261,473,473,473
BEGIN DESCRIPTION:
Stream0154_DS 7.0
END DESCRIPTION:
XS GIS Cut Line= 3
      2076375.00     13888975.01      2076375.00     13889075.00
      2076325.01     13889274.96
#Sta/Elev= 30
  4900.1 1271.51  4902.6 1271.51  4920.1 1267.07  4930.1 1263.66  4950.1 1254.47
  4960.1 1248.97  4980.1 1234.56  4990.1 1229.34  4997.6 1226.40  5002.7 1226.40
  5008.4 1225.16  5008.6 1224.66  5012.1 1224.66  5012.4 1225.16  5023.3 1226.47
  5041.3 1235.45  5059.4 1240.20  5064.5 1240.74  5072.2 1243.79  5082.6 1246.75
  5100.6 1254.87  5105.7 1255.53  5134.1 1265.48  5141.8 1269.94  5147.0 1270.86
  5154.7 1275.96  5165.0 1279.50  5183.1 1285.07  5203.7 1288.88  5206.2 1288.88
#Mann=3,-1,0
  4900.1    0.12       0  5008.4    0.05       0  5012.4    0.12       0
Bank Sta=5008.4,5012.4
Exp/Cntr=0.3,0.1

Type RM Length L Ch R = 1,2788,446,446,446
BEGIN DESCRIPTION:
Stream0154_DS 6.0
END DESCRIPTION:
XS GIS Cut Line= 3
      2076225.02     13888774.99      2076075.00     13888825.00
      2075825.81     13889178.70
#Sta/Elev= 30
  4842.2 1274.56  4884.4 1266.75  4905.5 1257.56  4921.3 1253.59  4926.5 1248.55
  4968.7 1225.69  4979.3 1221.34  4995.7 1220.37  4995.9 1219.87  4999.7 1220.37
  5022.5 1220.77  5028.6 1224.22  5043.4 1228.12  5049.6 1234.29  5058.2 1237.45
  5064.4 1243.34  5073.0 1244.62  5079.2 1249.62  5094.0 1253.13  5100.1 1256.96
  5129.7 1267.55  5135.8 1271.86  5150.6 1278.34  5215.9 1284.88  5354.4 1289.01
  5373.5 1290.70  5403.1 1290.09  5409.2 1288.69  5424.0 1290.96  5433.0 1289.01
#Mann=4,-1,0
  4842.2    0.12       0  4995.7    0.05       0  4999.7    0.12       0
  5354.4    0.07       0
Bank Sta=4995.7,4999.7
Exp/Cntr=0.3,0.1

Type RM Length L Ch R = 1,2342,467,467,467
BEGIN DESCRIPTION:
Stream0154_DS 5.0
END DESCRIPTION:
XS GIS Cut Line= 3
      2076140.43     13888343.24      2075925.00     13888425.00
      2075502.43     13888603.64
#Sta/Elev= 30
  4765.4 1274.51  4816.0 1269.97  4835.4 1266.71  4865.6 1255.54  4888.9 1250.44
  4895.7 1246.19  4920.5 1234.76  4925.8 1233.92  4931.6 1229.28  4942.3 1225.22
  4950.6 1220.78  4956.0 1220.09  4963.7 1217.10  4980.8 1214.81  4998.5 1214.04
  5003.0 1212.69  5003.2 1212.19  5007.0 1212.69  5010.4 1212.90  5028.4 1222.08
  5034.1 1225.89  5050.1 1230.66  5071.8 1242.27  5093.5 1250.97  5126.1 1256.33
  5139.7 1259.83  5158.0 1266.68  5209.6 1272.62  5316.5 1281.09  5454.6 1286.44
#Mann=4,-1,0
  4765.4    0.12       0  5003.0    0.05       0  5007.0    0.12       0
  5209.6    0.07       0
Bank Sta=5003,5007
Exp/Cntr=0.3,0.1

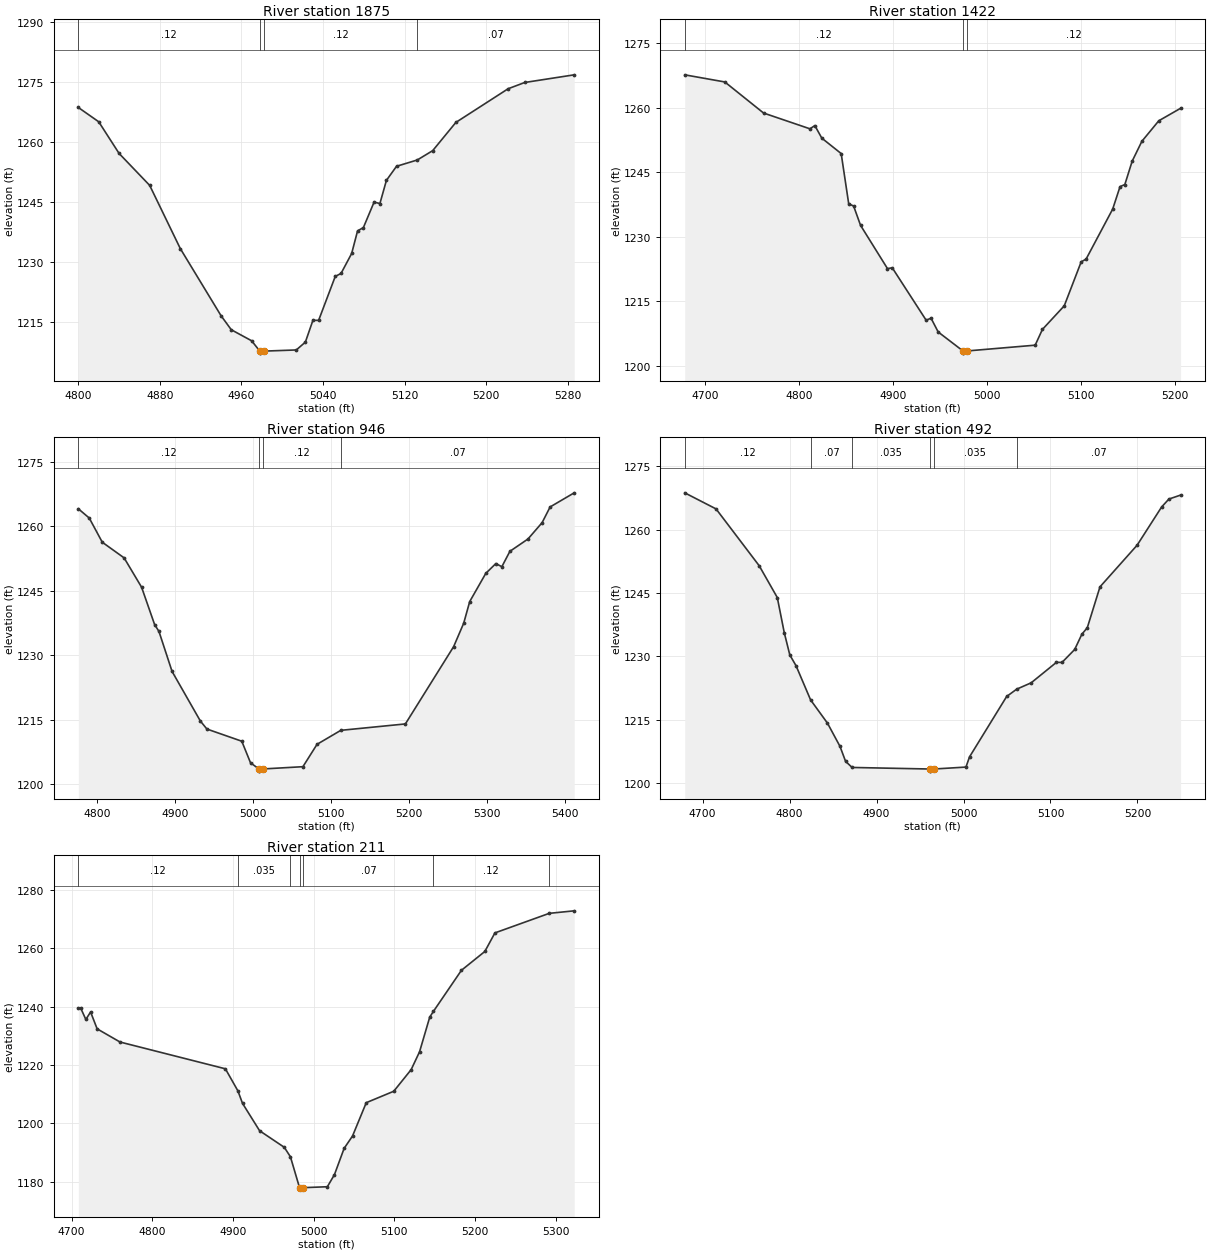
Type RM Length L Ch R = 1,1875,453,453,453
BEGIN DESCRIPTION:
Stream0154_DS 4.0
END DESCRIPTION:
XS GIS Cut Line= 3
      2076075.02     13887975.00      2075875.00     13887975.00
      2075622.72     13888110.52
#Sta/Elev= 30
  4800.0 1268.63  4820.0 1265.06  4840.0 1257.15  4870.0 1249.18  4900.0 1233.42
  4940.0 1216.65  4950.0 1213.16  4970.0 1210.40  4978.0 1207.82  4978.3 1207.32
  4982.0 1207.82  5013.8 1208.11  5022.7 1210.07  5030.1 1215.51  5035.7 1215.50
  5052.0 1226.46  5057.7 1227.22  5068.1 1232.19  5073.9 1237.84  5079.6 1238.65
  5090.1 1245.02  5095.8 1244.65  5102.2 1250.44  5112.1 1253.95  5132.5 1255.53
  5147.6 1257.86  5170.3 1264.90  5221.6 1273.31  5237.9 1274.87  5286.4 1276.78
#Mann=4,-1,0
  4800.0    0.12       0  4978.0    0.05       0  4982.0    0.12       0
  5132.5    0.07       0
Bank Sta=4978,4982
Exp/Cntr=0.3,0.1

Type RM Length L Ch R = 1,1422,476,476,476
BEGIN DESCRIPTION:
Stream0154_DS 3.0
END DESCRIPTION:
XS GIS Cut Line= 3
      2076036.29     13887653.12      2075725.00     13887575.00
      2075525.00     13887525.00
#Sta/Elev= 30
  4678.6 1267.66  4721.2 1266.00  4762.4 1258.77  4811.7 1255.10  4816.9 1255.85
  4824.3 1252.93  4844.9 1249.34  4852.9 1237.64  4858.1 1237.14  4865.5 1232.63
  4894.1 1222.58  4899.2 1222.76  4935.2 1210.57  4940.4 1211.04  4948.0 1207.83
  4974.4 1203.41  4974.6 1202.91  4978.4 1203.41  5051.1 1204.76  5058.8 1208.43
  5082.0 1213.91  5100.0 1224.15  5105.2 1224.78  5133.5 1236.43  5141.3 1241.65
  5146.4 1242.13  5154.2 1247.57  5164.5 1252.19  5182.5 1256.97  5205.7 1259.88
#Mann=3,-1,0
  4678.6    0.12       0  4974.4    0.05       0  4978.4    0.12       0
Bank Sta=4974.4,4978.4
Exp/Cntr=0.3,0.1

Type RM Length L Ch R = 1,946,454,454,454
BEGIN DESCRIPTION:
Stream0154_DS 2.0
END DESCRIPTION:
XS GIS Cut Line= 3
      2076025.00     13886975.01      2075925.00     13887175.00
      2075525.01     13887275.00
#Sta/Elev= 30
  4776.4 1264.03  4790.4 1261.88  4807.1 1256.26  4835.1 1252.62  4857.5 1245.81
  4874.2 1237.13  4879.8 1235.52  4896.6 1226.23  4932.9 1214.70  4941.3 1212.84
  4986.0 1210.01  4997.2 1205.00  5008.0 1203.56  5008.3 1203.06  5012.7 1203.56
  5064.4 1204.09  5082.5 1209.29  5113.0 1212.54  5195.8 1214.03  5257.7 1232.00
  5270.6 1237.45  5278.3 1242.47  5298.9 1249.02  5311.8 1251.30  5319.5 1250.57
  5329.8 1254.14  5353.0 1257.01  5371.1 1260.80  5381.4 1264.46  5412.3 1267.74
#Mann=4,-1,0
  4776.4    0.12       0  5008.0    0.05       0  5012.7    0.12       0
  5113.0    0.07       0
Bank Sta=5008,5012.7
Exp/Cntr=0.3,0.1

Type RM Length L Ch R = 1,492,281,281,281
BEGIN DESCRIPTION:
Stream0154_DS 1.0
END DESCRIPTION:
XS GIS Cut Line= 3
      2075874.98     13886825.01      2075625.00     13887025.00
      2075475.02     13887224.97
#Sta/Elev= 30
  4679.5 1268.76  4715.5 1264.95  4765.1 1251.49  4785.9 1243.96  4793.9 1235.66
  4800.3 1230.36  4807.5 1227.79  4824.2 1219.71  4843.6 1214.20  4858.0 1208.70
  4864.4 1205.16  4871.9 1203.71  4961.3 1203.34  4961.6 1202.84  4966.0 1203.34
  5002.8 1203.80  5006.9 1206.21  5049.6 1220.52  5061.1 1222.25  5077.8 1223.76
  5106.9 1228.62  5113.2 1228.58  5127.8 1231.65  5136.1 1235.28  5142.3 1236.80
  5156.9 1246.49  5199.6 1256.36  5227.8 1265.42  5236.1 1267.28  5249.6 1268.23
#Mann=6,-1,0
  4679.5    0.12       0  4824.2    0.07       0  4871.9   0.035       0
  4961.3   0.035       0  4966.0   0.035       0  5061.1    0.07       0
Bank Sta=4961.3,4966
Exp/Cntr=0.3,0.1

Type RM Length L Ch R = 1,211,0,0,0
BEGIN DESCRIPTION:
Stream0154_DS 0.0
END DESCRIPTION:
XS GIS Cut Line= 3
      2075654.68     13886703.03      2075407.92     13886858.58
      2075321.02     13887169.67
#Sta/Elev= 30
  4708.3 1239.57  4711.1 1239.57  4717.6 1235.60  4723.5 1238.16  4731.6 1232.38
  4760.0 1227.86  4890.6 1218.68  4906.1 1211.11  4911.8 1206.84  4933.0 1197.44
  4963.6 1191.76  4971.2 1188.52  4982.5 1177.92  4982.8 1177.42  4987.2 1177.92
  5017.0 1178.24  5025.8 1182.40  5037.8 1191.41  5048.2 1195.64  5065.2 1207.06
  5099.3 1210.98  5120.9 1218.41  5131.3 1224.53  5143.9 1236.40  5148.5 1238.38
  5183.2 1252.46  5212.2 1258.91  5224.7 1265.28  5292.1 1271.99  5323.0 1272.85
#Mann=7,-1,0
  4708.3    0.12       0  4906.1   0.035       0  4971.2    0.07       0
  4982.5    0.05       0  4987.2    0.07       0  5148.5    0.12       0
  5292.1    0.07       0
Bank Sta=4982.5,4987.2
Exp/Cntr=0.3,0.1

Chan Stop Cuts=-1