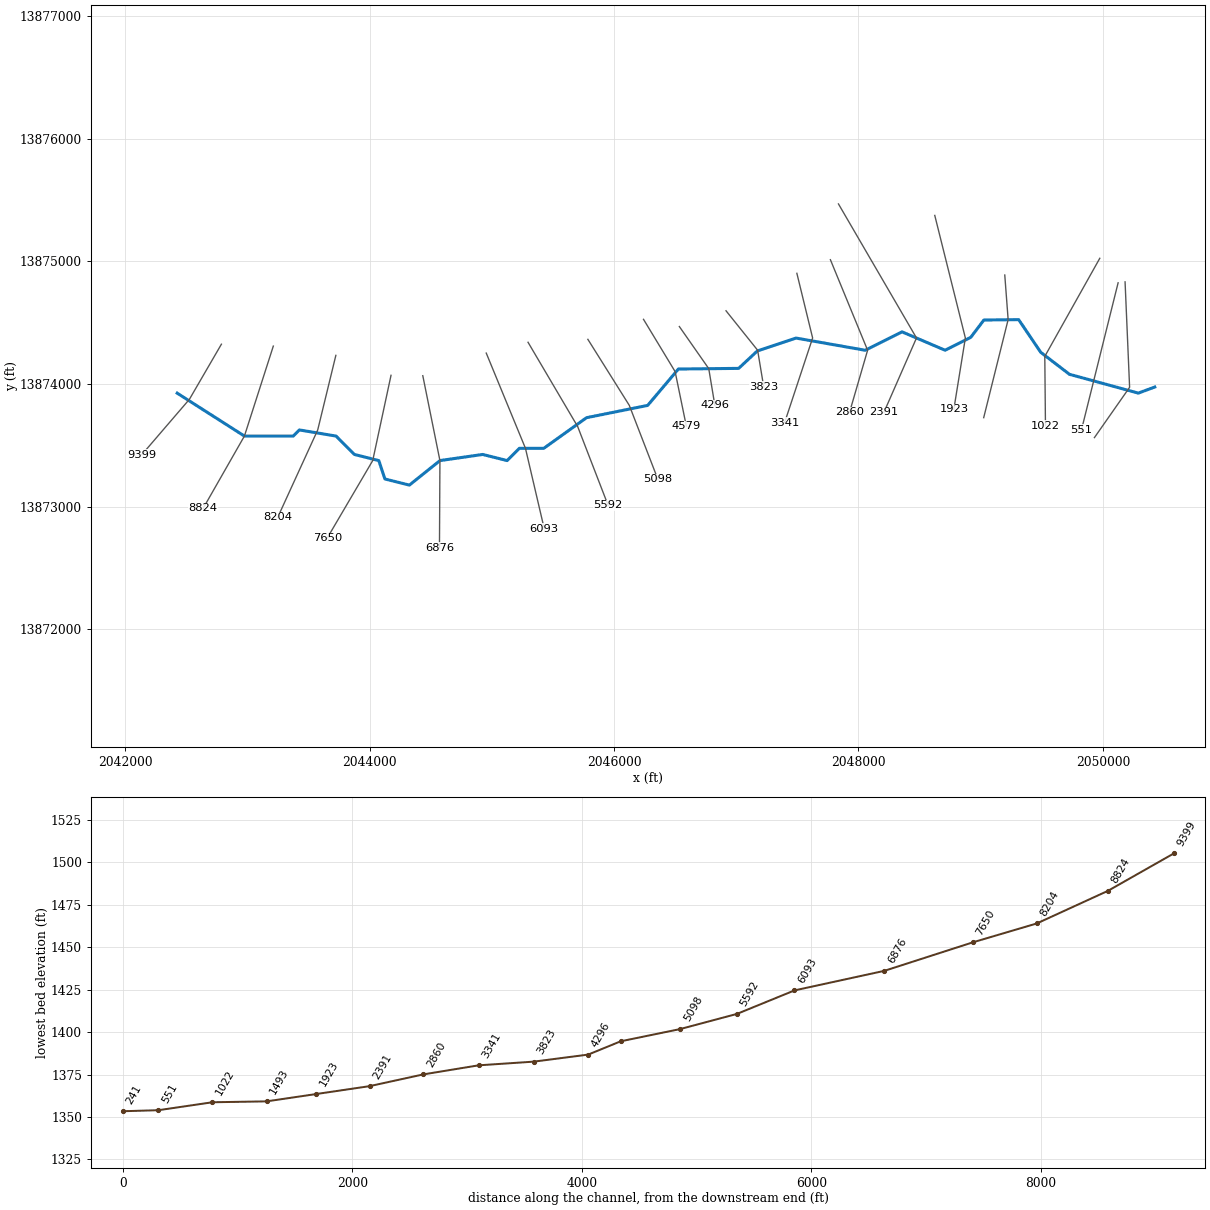
--- Stream0155_DS.prj (project) ---

Proj Title=Stream0155_DS Base Level Engineering
Current Plan=p01
Default Exp/Contr=0.3,0.1
English Units
Geom File=g01
Flow File=f01
Plan File=p01
Y Axis Title=Elevation
X Axis Title(PF)=Main Channel Distance
X Axis Title(XS)=Station
BEGIN DESCRIPTION:
Stream0155_DS
END DESCRIPTION:
DSS Export Rating Curves= 0
DSS Export Rating Curve Sorted= 0
DSS Export Volume Flow Curves= 0
DXF OffsetX= 0
DXF OffsetY= 0
DXF ScaleX= 1
DXF ScaleY= 10

--- Stream0155_DS.p01 (plan) ---

Plan Title=Multiple Run
Short Identifier=Multiple
Geom File=g01
Flow File=f01
Subcritical Flow
K Sum by GR= 0
Std Step Tol= 0.01
Critical Tol= 0.01
Num of Std Step Trials= 20
Max Error Tol= 0.3
Flow Tol Ratio= 0.001
Split Flow NTrial= 30
Split Flow Tol= 0.02
Split Flow Ratio= 0.02
Log Output Level= 0
Friction Slope Method= 1
Unsteady Friction Slope Method= 2
Unsteady Bridges Friction Slope Method= 1
Parabolic Critical Depth
Global Vel Dist=  1 , 1 , 1
Global Log Level= 0
CheckData=True
Encroach Param= -1, 0, 0, 0
BEGIN DESCRIPTION:
Multiple Run
END DESCRIPTION:

--- Stream0155_DS.f01 (steady flow) ---

Flow Title=Multiple
Number of Profiles=7
Profile Names=10-year,25-year,50-year,1pct_min,100-year,1pct_plu,500-year
River Rch & RM= Stream0155_DS,Reach-1,9399
     250     384     500     318     635    1267    1006
River Rch & RM= Stream0155_DS,Reach-1,8824
     763    1267    1740    1160    2315    4619    4048
River Rch & RM= Stream0155_DS,Reach-1,5098
    1558    2697    3804    2599    5185   10346    9529
River Rch & RM= Stream0155_DS,Reach-1,1493
    1690    2922    4119    2811    5609   11191   10284
Boundary for River Rch & Prof#=Stream0155_DS,Reach-1,1
Up Type=0
Dn Type=3
Dn Slope=0.005
Boundary for River Rch & Prof#=Stream0155_DS,Reach-1,2
Up Type=0
Dn Type=3
Dn Slope=0.005
Boundary for River Rch & Prof#=Stream0155_DS,Reach-1,3
Up Type=0
Dn Type=3
Dn Slope=0.005
Boundary for River Rch & Prof#=Stream0155_DS,Reach-1,4
Up Type=0
Dn Type=3
Dn Slope=0.005
Boundary for River Rch & Prof#=Stream0155_DS,Reach-1,5
Up Type=0
Dn Type=3
Dn Slope=0.005
Boundary for River Rch & Prof#=Stream0155_DS,Reach-1,6
Up Type=0
Dn Type=3
Dn Slope=0.005
Boundary for River Rch & Prof#=Stream0155_DS,Reach-1,7
Up Type=0
Dn Type=3
Dn Slope=0.005

--- Stream0155_DS.g01 (geometry) ---

Geom Title=Existing Conditions
Program Version=4.10

River Reach=Stream0155_DS   ,Reach-1
Reach XY= 30
        2042425.       13873925.        2042975.       13873575.
        2043375.       13873575.        2043425.       13873625.
        2043725.       13873575.        2043875.       13873425.
        2044075.       13873375.        2044125.       13873225.
        2044325.       13873175.        2044575.       13873375.
        2044925.       13873425.        2045125.       13873375.
        2045225.       13873475.        2045425.       13873475.
        2045775.       13873725.        2046275.       13873825.
      2046526.36     13874121.71      2047019.73     13874127.12
      2047172.64     13874269.25      2047488.92     13874374.32
      2048055.02     13874274.96      2048356.66     13874424.94
      2048709.59     13874275.02      2048919.39     13874380.59
      2049026.45     13874521.47      2049311.27     13874524.52
      2049491.65     13874258.33      2049726.58     13874078.82
      2050290.25     13873925.37        2050425.       13873975.

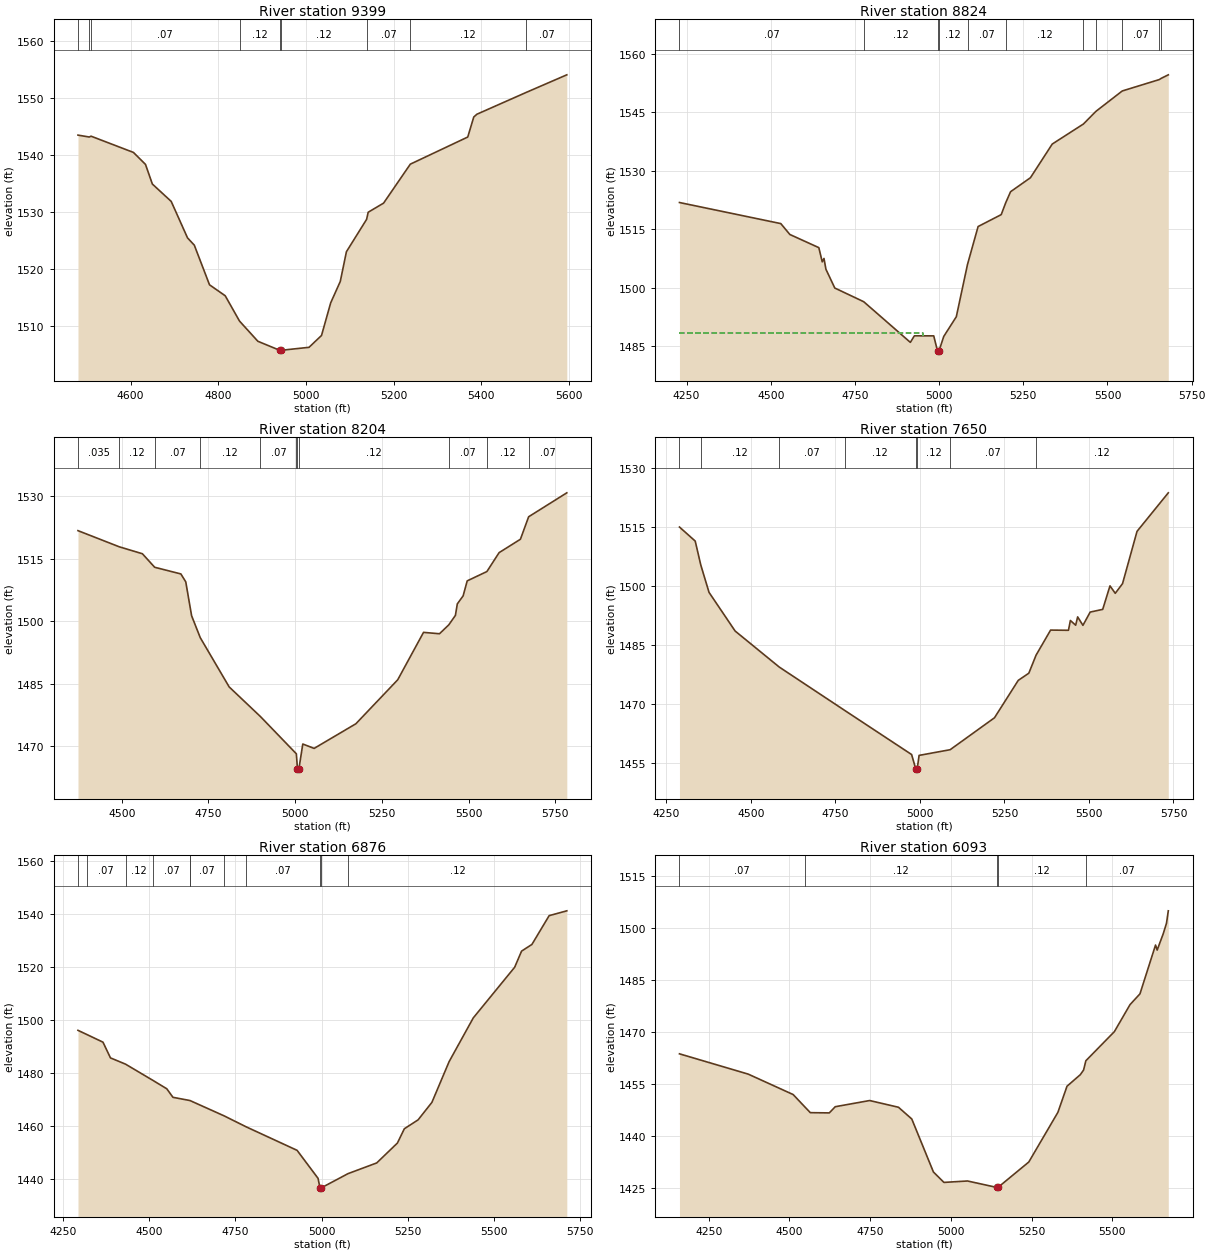
Type RM Length L Ch R = 1 ,9399    ,575,575,575
BEGIN DESCRIPTION:
Stream0155_DS 18.0
END DESCRIPTION:
XS GIS Cut Line= 3
      2042786.76     13874324.31        2042525.       13873875.
      2042136.38     13873424.19
#Sta/Elev= 30
    4480 1543.57  4505.8 1543.23  4509.8 1543.38  4606.5 1540.53    4634 1538.43
  4649.7 1534.98  4692.7 1531.93  4729.9 1525.53  4745.4 1524.25  4780.1 1517.29
  4815.9 1515.37  4848.5 1510.93  4890.4 1507.38  4940.1  1505.8  4940.4  1505.3
  4944.1  1505.8  5007.1 1506.32  5035.6  1508.4  5056.5 1514.12  5078.4 1517.88
  5092.4  1523.1  5138.4 1528.77  5142.1 1530.03  5177.2 1531.63  5238.2 1538.47
  5369.2 1543.23  5382.9 1546.74    5390 1547.23  5501.9 1551.04  5595.2 1554.15
#Mann= 9 ,-1 , 0
    4480     .07       0  4505.8    .035       0  4509.8     .07       0
  4848.5     .12       0  4940.1     .05       0  4944.1     .12       0
  5138.4     .07       0  5238.2     .12       0  5501.9     .07       0
Bank Sta=4940.1,4944.1
XS Rating Curve= 0 ,0
Exp/Cntr=0.3,0.1

Type RM Length L Ch R = 1 ,8824    ,620,620,620
BEGIN DESCRIPTION:
Stream0155_DS 17.0
END DESCRIPTION:
XS GIS Cut Line= 3
      2043211.56     13874308.92        2042975.       13873575.
      2042636.79     13872984.38
#Sta/Elev= 30
  4228.9 1521.87  4529.9 1516.46  4556.7 1513.67  4642.8 1510.29  4652.9 1506.65
  4658.1 1507.52  4663.8 1504.76  4690.2 1499.93  4776.1 1496.42  4914.6 1485.99
  4926.5 1487.67    4984 1487.66  4995.4 1483.73  4995.6 1483.23  4999.4 1483.73
  5013.7  1487.5  5051.1 1492.57  5084.3 1505.99  5115.8 1515.71  5184.4 1518.76
  5197.7 1521.79  5212.2 1524.64  5271.2 1528.23    5336 1536.87  5428.5 1542.01
  5465.7 1545.26  5543.9 1550.49  5653.8 1553.41  5659.4 1553.72  5680.6 1554.63
#Mann= 11 ,-1 , 0
  4228.9     .07       0  4776.1     .12       0  4995.4     .05       0
  4999.4     .12       0  5084.3     .07       0  5197.7     .12       0
  5428.5     .07       0  5465.7     .12       0  5543.9     .07       0
  5653.8     .12       0  5659.4     .07       0
#XS Ineff= 2 , 0
       0  4953.3 1488.43               0
Permanent Ineff=
       F       F
Bank Sta=4995.4,4999.4
XS Rating Curve= 0 ,0
Exp/Cntr=0.3,0.1

Type RM Length L Ch R = 1 ,8204    ,554,554,554
BEGIN DESCRIPTION:
Stream0155_DS 16.0
END DESCRIPTION:
XS GIS Cut Line= 3
      2043723.31     13874233.18        2043575.       13873625.
       2043248.2     13872913.46
#Sta/Elev= 30
    4374 1521.68    4493 1517.81  4559.7 1516.14  4595.1  1512.9  4670.6  1511.3
  4684.7  1509.4  4701.5 1501.28  4726.4 1496.03  4809.8 1484.21    4900  1477.1
  5003.4 1468.18  5006.7 1464.52    5007 1464.02  5010.7 1464.52    5022 1470.52
  5054.7 1469.47  5175.1 1475.38  5295.6 1485.92    5370 1497.29    5416 1496.96
  5442.8 1499.09  5461.9 1501.36  5467.4 1504.12  5484.2 1506.05  5495.9 1509.64
  5552.6 1511.87  5587.9 1516.41  5649.3 1519.62    5673 1525.01    5783 1530.75
#Mann= 11 ,-1 , 0
    4374    .035       0    4493     .12       0  4595.1     .07       0
  4726.4     .12       0    4900     .07       0  5003.4     .12       0
  5006.7     .05       0  5010.7     .12       0  5442.8     .07       0
  5552.6     .12       0    5673     .07       0
Bank Sta=5006.7,5010.7
XS Rating Curve= 0 ,0
Exp/Cntr=0.3,0.1

Type RM Length L Ch R = 1 ,7650    ,774,774,774
BEGIN DESCRIPTION:
Stream0155_DS 15.0
END DESCRIPTION:
XS GIS Cut Line= 3
      2044174.79     13874070.55        2044025.       13873375.
      2043652.07     13872741.99
#Sta/Elev= 30
  4288.5 1515.05  4335.1 1511.48  4351.6 1505.39    4376 1498.43  4453.2  1488.6
  4583.7 1479.44  4777.7 1468.39  4975.3 1457.19  4987.8 1453.47    4988 1452.97
  4991.8 1453.47  4997.4 1456.97  5089.4 1458.42  5220.5 1466.54  5290.8 1476.05
  5322.1 1477.88  5343.5 1482.46  5386.5 1488.84  5439.3 1488.79  5445.1 1491.28
  5460.7 1490.08  5466.5  1492.2  5482.2 1490.05  5503.6 1493.42  5540.7 1494.11
  5562.2 1500.09  5577.8 1498.19  5599.3 1500.65  5642.2 1513.95  5734.7 1523.75
#Mann= 8 ,-1 , 0
  4288.5     .07       0  4351.6     .12       0  4583.7     .07       0
  4777.7     .12       0  4987.8     .05       0  4991.8     .12       0
  5089.4     .07       0  5343.5     .12       0
Bank Sta=4987.8,4991.8
XS Rating Curve= 0 ,0
Exp/Cntr=0.3,0.1

Type RM Length L Ch R = 1 ,6876    ,783,783,783
BEGIN DESCRIPTION:
Stream0155_DS 14.0
END DESCRIPTION:
XS GIS Cut Line= 3
      2044434.85     13874067.36        2044575.       13873375.
      2044571.22     13872663.81
#Sta/Elev= 30
  4293.6 1496.03  4319.2 1494.46  4366.1 1491.57  4387.8 1485.63  4431.4 1483.28
  4511.5  1477.1  4551.1 1473.98    4569 1470.76  4618.4 1469.54  4619.1  1469.5
  4718.2 1463.71  4780.8 1459.65    4929 1450.75  4989.8 1440.18  4995.4 1436.61
  4995.7 1436.11  4999.4 1436.61  5076.5 1441.94    5160    1446    5220 1453.51
    5240 1458.88    5280 1462.26    5320 1468.85    5370 1484.25    5440 1500.73
    5560 1519.84    5580 1525.92    5610 1528.45    5660 1539.31  5711.2 1541.13
#Mann= 11 ,-1 , 0
  4293.6     .12       0  4319.2     .07       0  4431.4     .12       0
  4511.5     .07       0  4618.4     .12       0  4619.1     .07       0
  4718.2     .12       0  4780.8     .07       0  4995.4     .05       0
  4999.4     .07       0  5076.5     .12       0
Bank Sta=4995.4,4999.4
XS Rating Curve= 0 ,0
Exp/Cntr=0.3,0.1

Type RM Length L Ch R = 1 ,6093    ,501,501,501
BEGIN DESCRIPTION:
Stream0155_DS 13.0
END DESCRIPTION:
XS GIS Cut Line= 3
      2044954.11     13874251.72        2045275.       13873475.
      2045428.58     13872819.65
#Sta/Elev= 30
  4159.6 1463.65  4372.5 1457.79  4511.6 1451.89  4547.9 1448.31  4564.8 1446.66
  4623.5 1446.59    4642 1448.38  4748.5 1450.16  4837.7 1448.22  4878.9 1444.83
  4945.9 1429.53  4978.4 1426.52  5051.4 1426.93  5141.8 1425.08    5142 1424.58
  5145.8 1425.08  5241.2 1432.41  5331.3 1446.75  5359.5 1454.29  5400.6 1457.62
  5410.8 1458.96  5417.9 1461.65  5506.2 1470.06  5554.6 1477.85  5585.4 1480.97
  5633.6 1495.06  5638.7 1493.61  5657.3 1498.28  5667.6 1501.38  5673.1 1504.94
#Mann= 5 ,-1 , 0
  4159.6     .07       0  4547.9     .12       0  5141.8     .05       0
  5145.8     .12       0  5417.9     .07       0
Bank Sta=5141.8,5145.8
XS Rating Curve= 0 ,0
Exp/Cntr=0.3,0.1

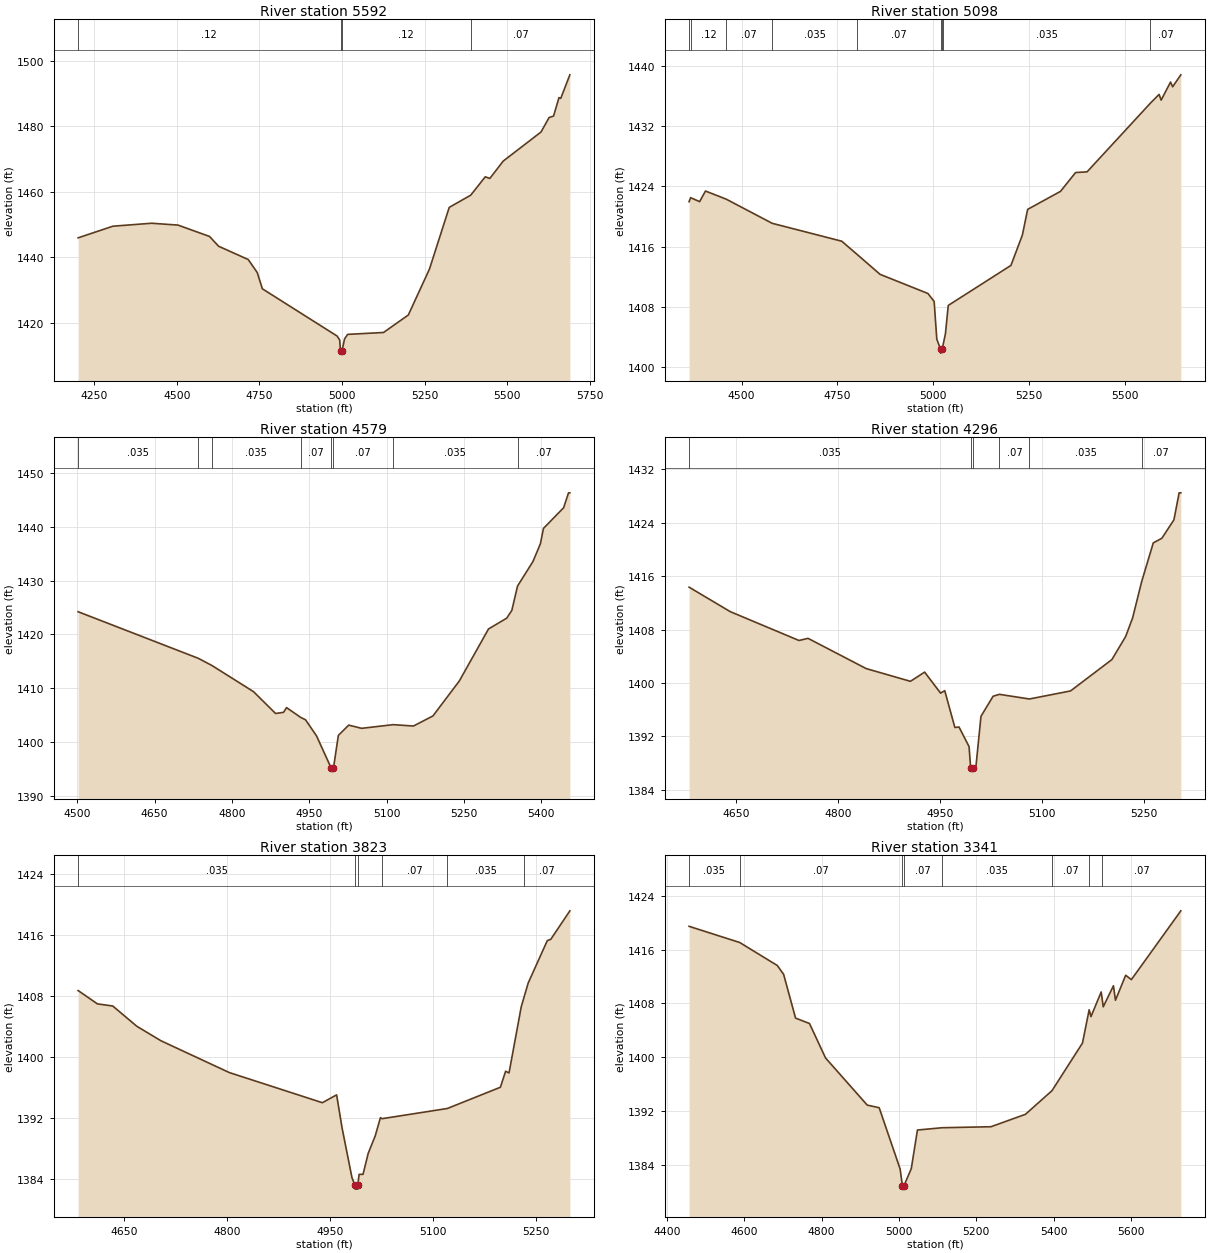
Type RM Length L Ch R = 1 ,5592    ,494,494,494
BEGIN DESCRIPTION:
Stream0155_DS 12.0
END DESCRIPTION:
XS GIS Cut Line= 3
      2045296.07     13874340.01      2045702.39     13873652.39
      2045951.83     13873009.05
#Sta/Elev= 30
  4201.3 1445.93  4306.6 1449.48  4423.6 1450.38  4503.6 1449.82  4599.2 1446.35
  4626.5 1443.37  4716.2 1439.31  4743.5 1435.36  4759.1 1430.38  4985.4 1415.96
  4993.2 1414.74  4995.7 1411.25  4995.9 1410.75  4999.7 1411.25  5007.9 1415.07
  5017.2 1416.47  5125.9 1417.05    5201 1422.39    5265 1436.41  5324.8 1455.22
    5390 1458.96  5433.8 1464.55  5447.7 1464.05  5488.3 1469.36  5602.6 1478.22
  5627.1 1482.63  5640.7  1483.1    5657 1488.71  5662.4 1488.49    5690 1495.67
#Mann= 4 ,-1 , 0
  4201.3     .12       0  4995.7     .05       0  4999.7     .12       0
    5390     .07       0
Bank Sta=4995.7,4999.7
XS Rating Curve= 0 ,0
Exp/Cntr=0.3,0.1

Type RM Length L Ch R = 1 ,5098    ,519,519,519
BEGIN DESCRIPTION:
Stream0155_DS 11.0
END DESCRIPTION:
XS GIS Cut Line= 3
      2045785.71     13874363.89        2046125.       13873825.
      2046358.63      13873222.3
#Sta/Elev= 30
  4363.2 1421.96  4367.2  1422.5  4390.7 1421.97    4406 1423.38  4460.1  1422.3
    4580 1419.09  4761.6 1416.71  4801.5 1414.96  4861.7  1412.3  4986.4 1409.76
  5002.7  1408.7  5009.6 1403.69  5019.5 1402.33  5019.7 1401.83  5023.5 1402.33
    5027 1403.17  5032.2 1404.43  5039.5 1408.17    5203 1413.49  5232.9 1417.52
  5246.7 1420.94  5332.5 1423.34  5371.8 1425.84  5401.7 1425.93  5566.4 1435.03
  5589.7 1436.23    5595 1435.47  5619.6 1437.87    5625 1437.24  5646.4 1438.83
#Mann= 9 ,-1 , 0
  4363.2     .07       0  4367.2     .12       0  4460.1     .07       0
    4580    .035       0  4801.5     .07       0  5019.5     .05       0
  5023.5     .07       0    5027    .035       0  5566.4     .07       0
Bank Sta=5019.5,5023.5
XS Rating Curve= 0 ,0
Exp/Cntr=0.3,0.1

Type RM Length L Ch R = 1 ,4579    ,283,283,283
BEGIN DESCRIPTION:
Stream0155_DS 10.0
END DESCRIPTION:
XS GIS Cut Line= 3
      2046241.09     13874527.05      2046499.71     13874100.89
      2046591.76     13873654.89
#Sta/Elev= 30
  4501.5 1424.22  4734.5 1415.57  4761.1 1414.23  4841.8 1409.37  4884.5 1405.32
    4900 1405.53  4905.8 1406.41  4933.4 1404.58  4942.6 1404.15    4964 1401.15
  4992.7 1395.11  4992.9 1394.61  4996.7 1395.11  5006.3 1401.24  5026.4 1403.16
  5051.4 1402.56  5112.7 1403.24    5152 1402.99  5189.8 1404.86  5240.9 1411.35
  5297.6 1421.02  5332.8 1423.02  5342.8 1424.46  5353.9 1428.99  5383.8 1433.55
  5398.2 1436.84  5404.2  1439.7  5443.3 1443.54  5452.8 1446.31  5455.4 1446.31
#Mann= 8 ,-1 , 0
  4501.5    .035       0  4734.5     .07       0  4761.1    .035       0
  4933.4     .07       0  4992.7     .05       0  4996.7     .07       0
  5112.7    .035       0  5353.9     .07       0
Bank Sta=4992.7,4996.7
XS Rating Curve= 0 ,0
Exp/Cntr=0.3,0.1

Type RM Length L Ch R = 1 ,4296    ,473,473,473
BEGIN DESCRIPTION:
Stream0155_DS 9.0
END DESCRIPTION:
XS GIS Cut Line= 3
      2046534.31     13874468.33        2046775.       13874125.
        2046825.     13873825.03
#Sta/Elev= 30
  4580.7 1414.35  4641.3 1410.68  4742.4 1406.36  4755.7 1406.68  4841.2 1402.15
  4906.3 1400.24  4927.2 1401.62  4950.7 1398.47  4956.8 1398.84  4971.7 1393.32
  4977.8 1393.39  4992.6 1390.45  4994.9 1387.28  4995.2 1386.78  4998.9 1387.28
  5002.5 1387.28  5010.1 1394.99  5027.9    1398  5037.2 1398.29  5081.3 1397.59
  5141.9  1398.8  5202.7  1403.5    5223 1406.97  5233.2 1409.75  5246.4 1415.15
  5263.6 1420.99  5276.2 1421.68    5294 1424.45  5301.6 1428.49  5304.1 1428.49
#Mann= 6 ,-1 , 0
  4580.7    .035       0  4994.9    .035       0  4998.9    .035       0
  5037.2     .07       0  5081.3    .035       0  5246.4     .07       0
Bank Sta=4994.9,4998.9
XS Rating Curve= 0 ,0
Exp/Cntr=0.3,0.1

Type RM Length L Ch R = 1 ,3823    ,482,482,482
BEGIN DESCRIPTION:
Stream0155_DS 8.0
END DESCRIPTION:
XS GIS Cut Line= 3
      2046916.27     13874596.79        2047175.       13874275.
      2047224.99     13873975.04
#Sta/Elev= 30
  4582.8 1408.72  4610.9 1406.97  4633.3 1406.69  4668.5 1404.02  4703.7 1402.12
  4803.2 1397.95  4938.9 1393.99  4959.7 1395.02  4967.7 1390.66  4982.1 1384.14
  4986.5 1383.14  4986.8 1382.64  4990.3 1382.64  4990.5 1383.14  4992.5 1384.58
  4998.2 1384.58  5005.8 1387.35    5016 1389.63  5023.6 1392.03  5025.9 1391.89
  5121.1 1393.23  5198.5 1396.02  5206.1 1398.12  5211.1  1397.9  5228.9 1406.59
  5232.7 1407.76    5239  1409.7  5266.9 1415.28    5272 1415.45  5299.8 1419.19
#Mann= 6 ,-1 , 0
  4582.8    .035       0  4986.5    .035       0  4990.5    .035       0
  5025.9     .07       0  5121.1    .035       0  5232.7     .07       0
Bank Sta=4986.5,4990.5
XS Rating Curve= 0 ,0
Exp/Cntr=0.3,0.1

Type RM Length L Ch R = 1 ,3341    ,481,481,481
BEGIN DESCRIPTION:
Stream0155_DS 7.0
END DESCRIPTION:
XS GIS Cut Line= 3
       2047496.1      13874902.4        2047625.       13874375.
      2047395.41     13873683.65
#Sta/Elev= 30
  4457.5 1419.45  4588.4 1417.05  4685.5 1413.64  4701.9 1412.33  4732.8 1405.83
  4768.8 1405.03  4810.4 1399.91  4918.1 1392.92    4949 1392.53  5003.1 1383.45
    5009 1380.95  5009.2 1380.45    5013 1380.95    5032 1383.49  5047.9 1389.22
  5111.3 1389.56    5238 1389.71  5327.1 1391.55  5395.8 1395.06  5474.6 1402.12
  5491.9 1407.07  5496.6 1406.05    5523 1409.71  5525.7 1408.59  5528.3 1407.51
  5554.7 1410.63  5559.9 1408.48  5586.3 1412.19    5601 1411.54  5728.9 1421.75
#Mann= 8 ,-1 , 0
  4457.5    .035       0  4588.4     .07       0    5009     .05       0
    5013     .07       0  5111.3    .035       0  5395.8     .07       0
  5491.9     .12       0  5525.7     .07       0
Bank Sta=5009,5013
XS Rating Curve= 0 ,0
Exp/Cntr=0.3,0.1

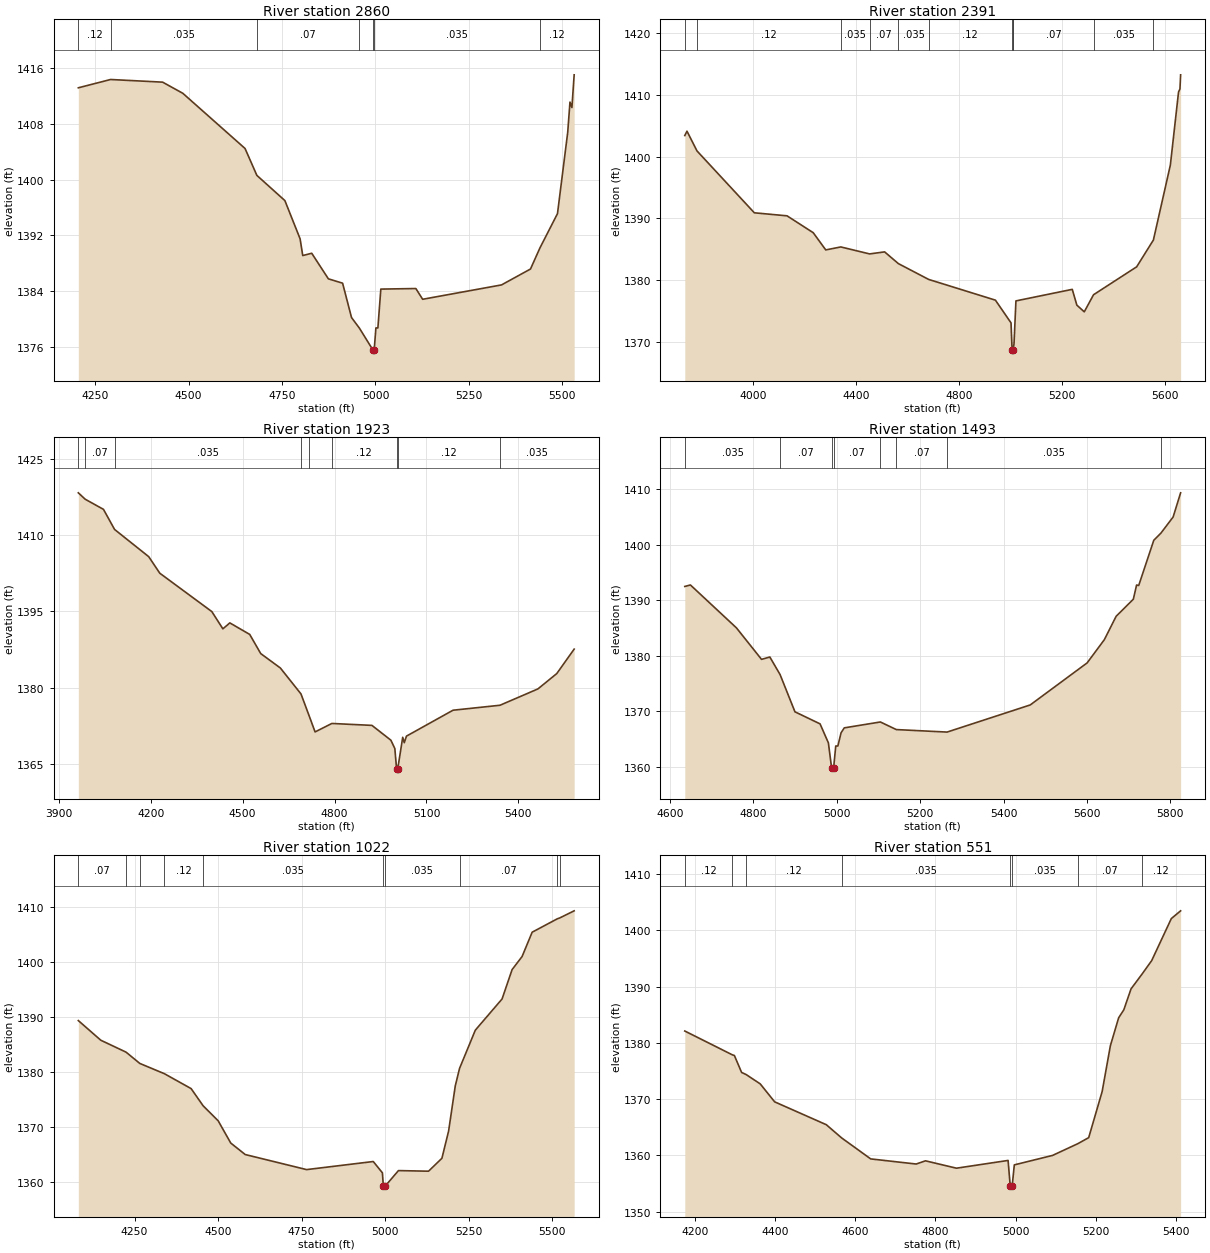
Type RM Length L Ch R = 1 ,2860    ,469,469,469
BEGIN DESCRIPTION:
Stream0155_DS 6.0
END DESCRIPTION:
XS GIS Cut Line= 3
      2047770.41     13875013.49        2048075.       13874275.
       2047927.1     13873768.49
#Sta/Elev= 30
    4205 1413.16  4291.3 1414.35  4430.5 1413.97  4484.6 1412.37    4651 1404.46
  4682.7  1400.6  4757.6 1396.99  4798.3 1391.51  4805.4 1389.11  4829.4 1389.44
    4874 1385.77    4912 1385.15  4935.9 1380.22    4957  1378.7  4992.6 1375.62
  4992.8 1375.12  4996.6 1375.62  5001.1 1378.73  5006.4 1378.73  5014.3  1384.3
    5108 1384.38  5126.2 1382.84  5337.2  1384.9  5414.7 1387.18  5440.1 1390.22
  5486.9 1395.12  5514.3 1406.79  5520.3 1411.11  5525.5 1410.33  5531.5 1415.02
#Mann= 7 ,-1 , 0
    4205     .12       0  4291.3    .035       0  4682.7     .07       0
    4957    .035       0  4992.6    .035       0  4996.6    .035       0
  5440.1     .12       0
Bank Sta=4992.6,4996.6
XS Rating Curve= 0 ,0
Exp/Cntr=0.3,0.1

Type RM Length L Ch R = 1 ,2391    ,468,468,468
BEGIN DESCRIPTION:
Stream0155_DS 5.0
END DESCRIPTION:
XS GIS Cut Line= 3
      2047836.36     13875468.39        2048475.       13874375.
      2048208.57     13873768.48
#Sta/Elev= 30
  3733.4 1403.43  3741.9 1404.14  3780.9 1400.94  4003.9 1390.92  4131.1 1390.43
  4232.9  1387.7  4281.7 1384.91  4340.4 1385.39  4452.3 1384.26  4510.7 1384.59
  4564.2 1382.69  4681.9 1380.13  4941.7 1376.77  5002.4 1373.09  5006.6 1368.69
  5006.8 1368.19  5010.6 1368.69  5011.5 1368.96    5014  1369.7  5021.5 1376.65
  5240.6 1378.52  5258.5 1375.96  5287.3 1374.88  5323.4 1377.65  5491.1 1382.17
  5556.2 1386.51  5622.2 1398.66    5654 1410.49  5659.5 1410.98  5662.1 1413.27
#Mann= 11 ,-1 , 0
  3733.4    .035       0  3780.9     .12       0  4340.4    .035       0
  4452.3     .07       0  4564.2    .035       0  4681.9     .12       0
  5006.6     .05       0  5010.6     .12       0  5011.5     .07       0
  5323.4    .035       0  5556.2     .12       0
Bank Sta=5006.6,5010.6
XS Rating Curve= 0 ,0
Exp/Cntr=0.3,0.1

Type RM Length L Ch R = 1 ,1923    ,430,430,430
BEGIN DESCRIPTION:
Stream0155_DS 4.0
END DESCRIPTION:
XS GIS Cut Line= 3
      2048624.57     13875374.63        2048875.       13874375.
      2048780.82     13873794.71
#Sta/Elev= 30
  3963.6 1418.39    3986 1417.13  4045.7 1415.13  4081.9 1411.17  4193.4  1405.8
  4229.5 1402.54  4399.4 1394.97  4435.4 1391.57  4458.1 1392.74    4523 1390.47
    4559 1386.69    4623 1383.85  4690.4 1378.73  4717.1  1374.4  4736.4 1371.24
  4791.1 1372.91    4922 1372.53  4983.8 1369.61  4996.7 1367.96  5002.3 1364.01
  5002.5 1363.51  5006.3 1364.01  5022.4 1370.18  5027.5 1369.12  5034.6 1370.41
  5186.6 1375.52  5339.9  1376.5  5463.7 1379.72  5525.3 1382.75    5582 1387.57
#Mann= 9 ,-1 , 0
  3963.6    .035       0    3986     .07       0  4081.9    .035       0
  4690.4     .12       0  4717.1    .035       0  4791.1     .12       0
  5002.3     .05       0  5006.3     .12       0  5339.9    .035       0
Bank Sta=5002.3,5006.3
XS Rating Curve= 0 ,0
Exp/Cntr=0.3,0.1

Type RM Length L Ch R = 1 ,1493    ,471,471,471
BEGIN DESCRIPTION:
Stream0155_DS 3.0
END DESCRIPTION:
XS GIS Cut Line= 3
      2049197.49     13874888.46        2049225.       13874525.
      2049025.01     13873725.02
#Sta/Elev= 30
  4635.6 1392.51  4649.1 1392.78  4759.4 1385.05  4819.6 1379.37  4839.6 1379.79
  4864.1 1376.63  4899.8 1369.91    4960 1367.74    4980 1364.31  4987.8 1359.72
  4988.1 1359.22  4992.4 1359.72  4997.6 1363.75  5002.7 1363.75  5010.4 1366.13
  5018.1 1367.02  5104.6 1368.08  5142.9 1366.71  5264.6 1366.26    5464 1371.15
  5600.5 1378.73  5641.8 1382.92  5670.1 1387.14  5711.3 1390.21  5719.1 1392.77
  5724.2 1392.69  5760.3 1400.83  5777.6 1402.14  5806.7 1405.03  5824.7 1409.39
#Mann= 8 ,-1 , 0
  4635.6    .035       0  4864.1     .07       0  4987.8     .05       0
  4992.4     .07       0  5104.6    .035       0  5142.9     .07       0
  5264.6    .035       0  5777.6     .07       0
Bank Sta=4987.8,4992.4
XS Rating Curve= 0 ,0
Exp/Cntr=0.3,0.1

Type RM Length L Ch R = 1 ,1022    ,471,471,471
BEGIN DESCRIPTION:
Stream0155_DS 2.0
END DESCRIPTION:
XS GIS Cut Line= 3
        2049975.       13875025.        2049525.       13874225.
      2049530.47      13873659.3
#Sta/Elev= 30
  4081.8 1389.35    4149 1385.78  4224.6 1383.61  4265.7 1381.56  4339.4 1379.69
  4419.3 1376.98  4455.3 1373.85  4500.3 1371.12  4537.9 1367.08  4581.2 1364.99
  4764.8 1362.25  4964.3 1363.72  4991.7 1361.66  4994.5  1359.2  4994.8  1358.7
  4999.2  1359.2  5039.7 1362.07  5129.7 1361.96  5169.7 1364.31  5189.7 1369.25
  5209.7 1377.48  5222.5 1380.66  5269.7 1387.61  5349.7 1393.28  5379.7 1398.62
  5409.7 1401.01  5439.7 1405.42  5514.4 1407.84  5522.7 1408.03  5565.4 1409.31
#Mann= 10 ,-1 , 0
  4081.8     .07       0  4224.6     .12       0  4265.7     .07       0
  4339.4     .12       0  4455.3    .035       0  4994.5    .035       0
  4999.2    .035       0  5222.5     .07       0  5514.4    .035       0
  5522.7     .07       0
Bank Sta=4994.5,4999.2
XS Rating Curve= 0 ,0
Exp/Cntr=0.3,0.1

Type RM Length L Ch R = 1 ,551     ,310,310,310
BEGIN DESCRIPTION:
Stream0155_DS 1.0
END DESCRIPTION:
XS GIS Cut Line= 3
      2050124.99     13874824.97        2049925.       13874025.
        2049825.       13873625.
#Sta/Elev= 30
    4175 1382.12  4293.8 1377.88  4298.7 1377.77  4316.7 1374.76  4328.3 1374.37
  4363.1 1372.73  4399.2 1369.53    4528 1365.47  4566.3 1363.12  4638.8 1359.39
  4752.2 1358.48  4775.4 1359.05  4852.7 1357.74  4981.5 1359.12  4986.9 1354.52
  4987.3 1354.02  4991.6 1354.52    4997 1358.33  5092.4 1360.01  5155.3 1362.09
  5182.6 1363.17  5216.1 1371.35  5236.7 1379.52  5257.3 1384.47  5270.2 1385.89
  5288.2 1389.61  5315.8 1392.25  5339.7 1394.63  5388.7  1402.1  5411.9 1403.48
#Mann= 8 ,-1 , 0
    4175     .12       0  4293.8     .07       0  4328.3     .12       0
  4566.3    .035       0  4986.9    .035       0  4991.6    .035       0
  5155.3     .07       0  5315.8     .12       0
Bank Sta=4986.9,4991.6
XS Rating Curve= 0 ,0
Exp/Cntr=0.3,0.1

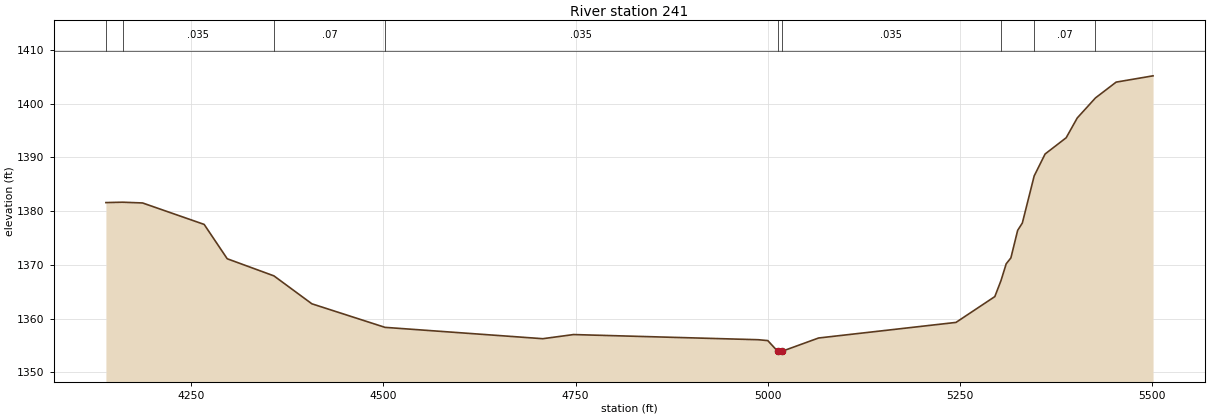
Type RM Length L Ch R = 1 ,241     ,0,0,0
BEGIN DESCRIPTION:
Stream0155_DS 0.0
END DESCRIPTION:
XS GIS Cut Line= 3
      2050181.96     13874832.65      2050219.03     13873972.64
      2049931.14      13873562.5
#Sta/Elev= 30
  4139.2  1381.6    4161 1381.67  4186.9 1381.53    4267 1377.54    4297 1371.15
  4357.7 1367.97  4407.1 1362.77  4502.2 1358.39  4707.4 1356.28  4747.4 1357.05
  4987.6 1356.09    5000 1355.93  5013.1 1353.91  5013.5 1353.41    5018 1353.91
  5066.1 1356.41  5244.8 1359.31  5295.3 1364.11  5303.3 1367.08  5310.1 1370.21
  5316.2 1371.31    5325 1376.43  5331.1  1377.8  5346.5 1386.56  5360.7 1390.64
  5388.1 1393.66  5402.5 1397.34  5426.2 1401.07  5453.1 1404.01  5501.1 1405.18
#Mann= 9 ,-1 , 0
  4139.2     .12       0    4161    .035       0  4357.7     .07       0
  4502.2    .035       0  5013.1    .035       0    5018    .035       0
  5303.3     .12       0  5346.5     .07       0  5426.2    .035       0
Bank Sta=5013.1,5018
XS Rating Curve= 0 ,0
Exp/Cntr=0.3,0.1

Chan Stop Cuts=-1
Use User Specified Reach Order=0
Composite Channel Slope=5