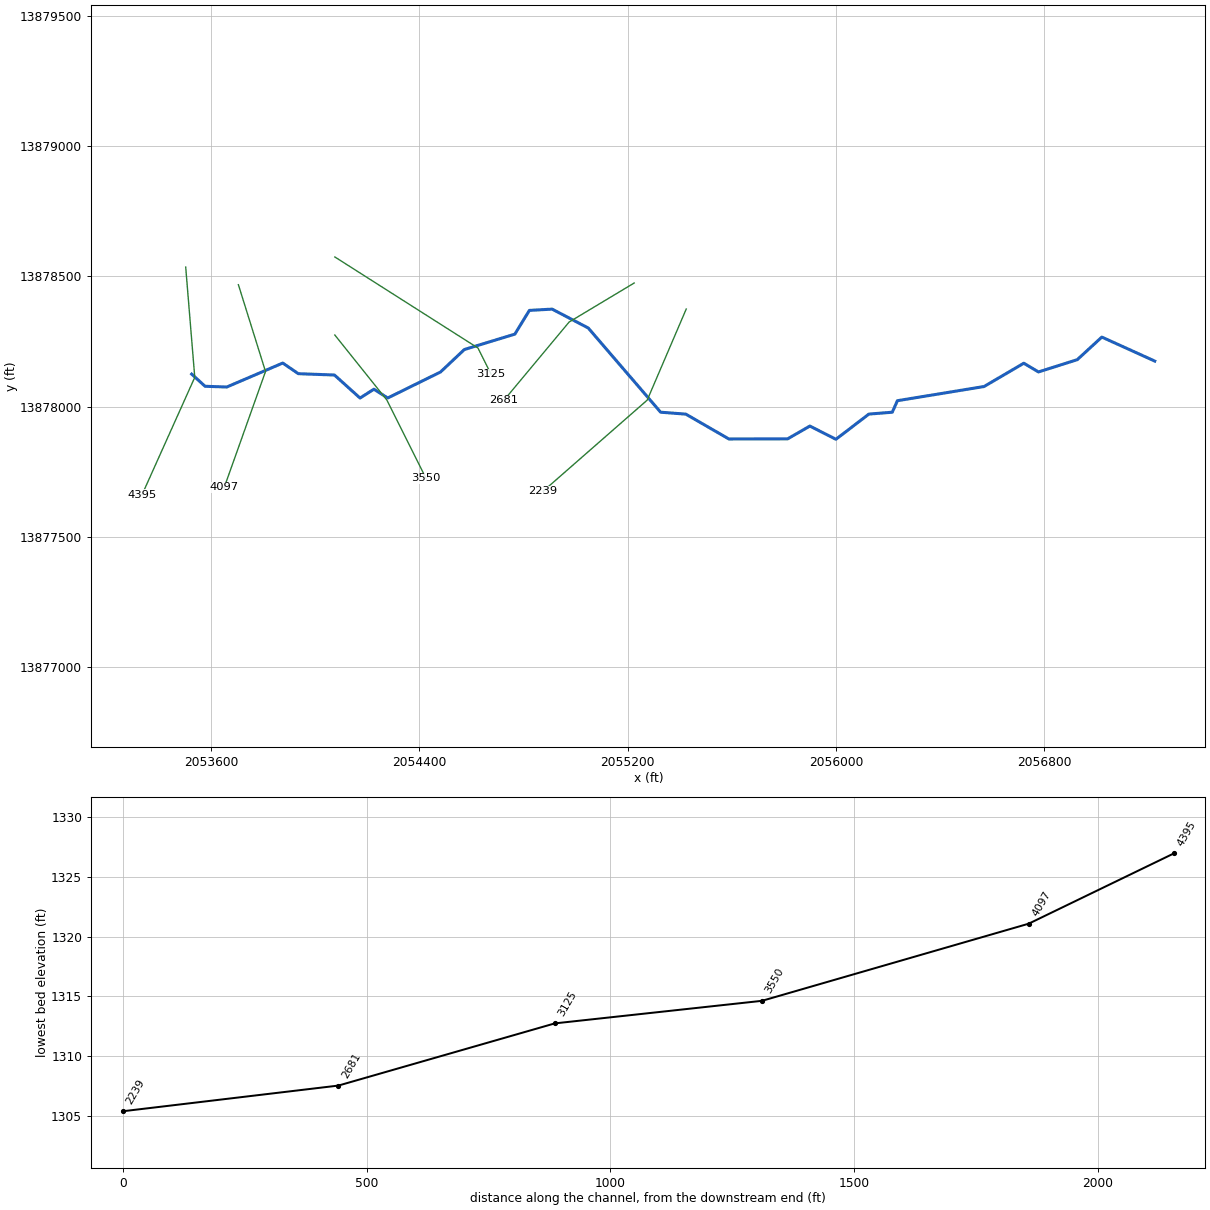
--- Stream0156_DS.prj (project) ---

Proj Title=Stream0156_DS Base Level Engineering
Current Plan=p01
Default Exp/Contr=0.3,0.1
English Units
Geom File=g01
Flow File=f01
Plan File=p01
BEGIN DESCRIPTION:
Stream0156_DS
END DESCRIPTION:

--- Stream0156_DS.p01 (plan) ---

Plan Title=Multiple Run
Short Identifier=Multiple
Geom File=g01
Flow File=f01
Subcritical Flow
K Sum by GR= 0
Std Step Tol= 0.01
Critical Tol= 0.01
Num of Std Step Trials= 20
Max Error Tol= 0.3
Flow Tol Ratio= 0.001
Split Flow NTrial= 30
Split Flow Tol= 0.02
Split Flow Ratio= 0.02
Log Output Level= 0
Friction Slope Method= 1
Unsteady Friction Slope Method= 2
Unsteady Bridges Friction Slope Method= 1
Parabolic Critical Depth
Global Vel Dist=  1 , 1 , 1
Global Log Level= 0
CheckData=True
Encroach Param= -1, 0, 0, 0
BEGIN DESCRIPTION:
Multiple Run
END DESCRIPTION:

--- Stream0156_DS.f01 (steady flow) ---

Flow Title=Multiple
Number of Profiles=7
Profile Names=10-year,25-year,50-year,1pct_min,100-year,1pct_plu,500-year
River Rch & RM= Stream0156_DS,Reach-1,4395
     910    1517    2085    1390    2773    5532    4847
River Rch & RM= Stream0156_DS,Reach-1,3125
     971    1617    2221    1479    2952    5890    5152
River Rch & RM= Stream0156_DS,Reach-1,2239
    1929    3336    4701    3203    6391   12751   11684
Boundary for River Rch & Prof#=Stream0156_DS,Reach-1,1
Up Type=0
Dn Type=3
Dn Slope=0.005
Boundary for River Rch & Prof#=Stream0156_DS,Reach-1,2
Up Type=0
Dn Type=3
Dn Slope=0.005
Boundary for River Rch & Prof#=Stream0156_DS,Reach-1,3
Up Type=0
Dn Type=3
Dn Slope=0.005
Boundary for River Rch & Prof#=Stream0156_DS,Reach-1,4
Up Type=0
Dn Type=3
Dn Slope=0.005
Boundary for River Rch & Prof#=Stream0156_DS,Reach-1,5
Up Type=0
Dn Type=3
Dn Slope=0.005
Boundary for River Rch & Prof#=Stream0156_DS,Reach-1,6
Up Type=0
Dn Type=3
Dn Slope=0.005
Boundary for River Rch & Prof#=Stream0156_DS,Reach-1,7
Up Type=0
Dn Type=3
Dn Slope=0.005

--- Stream0156_DS.g01 (geometry) ---

Geom Title=Existing Conditions

River Reach=Stream0156_DS,Reach-1
Reach XY= 30
      2053525.00     13878125.00      2053576.40     13878078.19
      2053659.75     13878075.37      2053875.00     13878167.44
      2053934.60     13878126.56      2054073.53     13878121.43
      2054171.67     13878033.00      2054225.00     13878066.96
      2054278.23     13878033.23      2054481.05     13878133.16
      2054572.58     13878219.46      2054766.51     13878278.54
      2054822.34     13878369.67      2054909.72     13878374.64
      2055048.51     13878302.08      2055326.48     13877978.61
      2055423.41     13877971.17      2055588.91     13877875.67
      2055814.50     13877876.24      2055900.00     13877925.39
      2056000.03     13877874.52      2056126.57     13877971.35
      2056216.50     13877978.56      2056236.29     13878022.79
      2056569.07     13878077.25      2056721.77     13878166.76
      2056778.22     13878133.28      2056927.43     13878180.55
      2057021.60     13878267.22      2057225.00     13878175.00

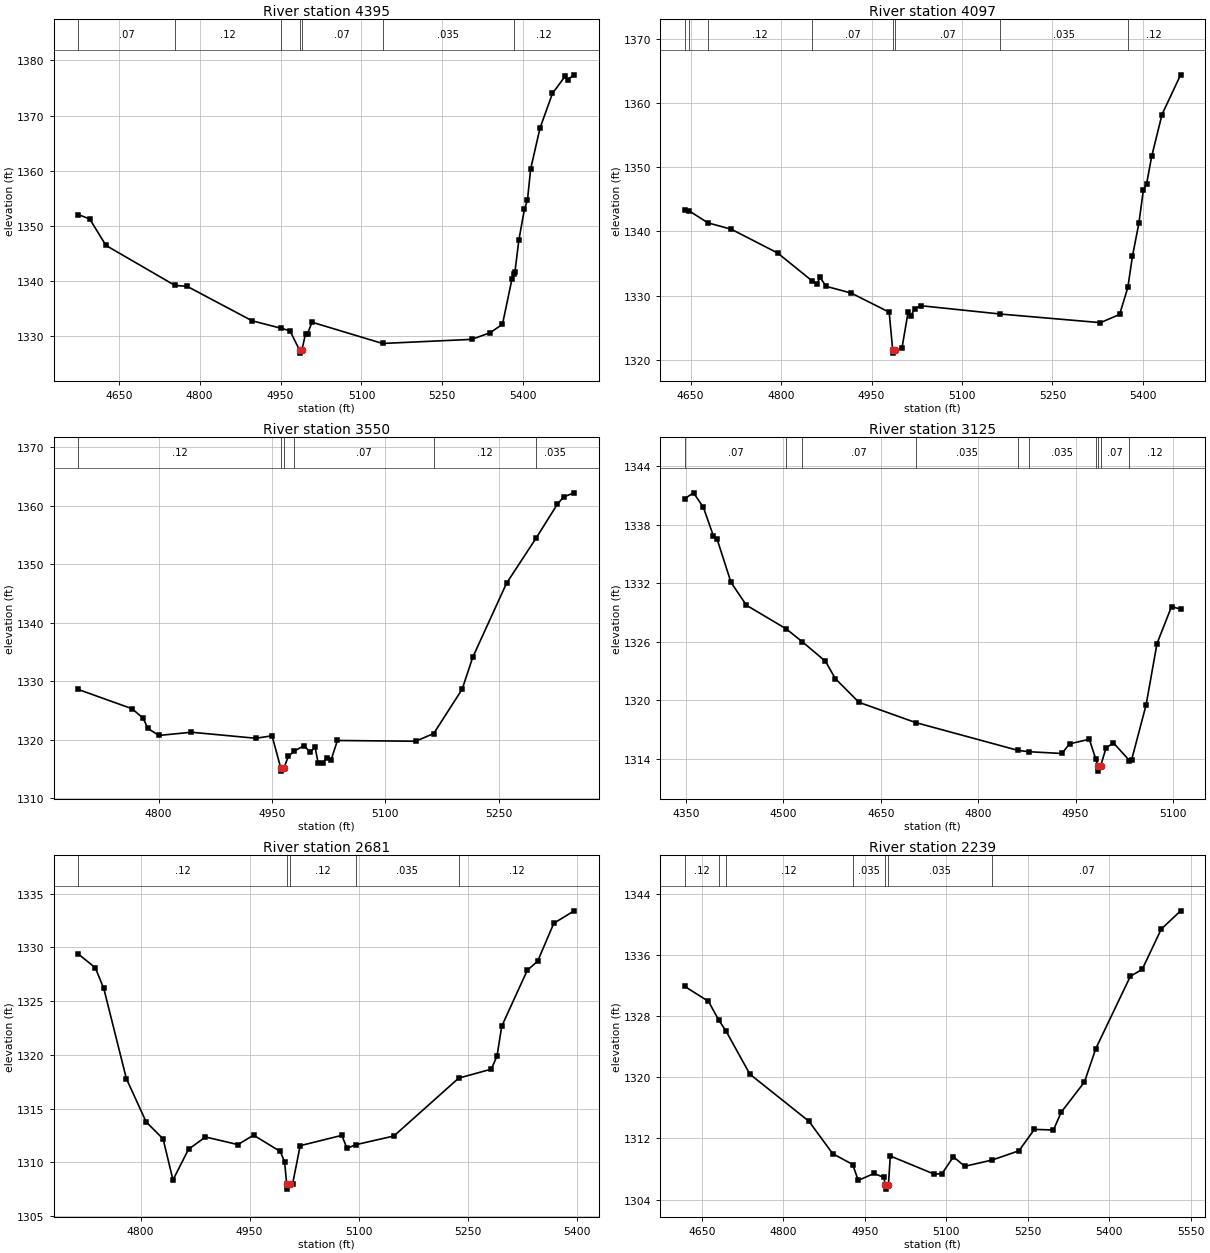
Type RM Length L Ch R = 1,4395,298,298,298
BEGIN DESCRIPTION:
Stream0156_DS 6.0
END DESCRIPTION:
XS GIS Cut Line= 3
      2053501.98     13878536.00      2053536.82     13878112.53
      2053334.29     13877661.52
#Sta/Elev= 30
  4575.1 1352.06  4596.2 1351.27  4626.3 1346.48  4754.3 1339.23  4776.8 1339.07
  4897.2 1332.83  4951.2 1331.47  4967.4 1331.02  4985.5 1327.47  4985.7 1326.97
  4989.5 1327.47  4996.3 1330.47  5000.0 1330.47  5008.3 1332.57  5139.1 1328.72
  5304.2 1329.46  5338.3 1330.65  5361.5 1332.19  5379.2 1340.43  5383.2 1341.36
  5384.6 1341.68  5391.9 1347.47  5402.3 1353.10  5407.8 1354.66  5413.8 1360.36
  5431.0 1367.70  5454.1 1374.00  5477.3 1377.08  5482.8 1376.53  5494.4 1377.38
#Mann=7,-1,0
  4575.1    0.07       0  4754.3    0.12       0  4951.2    0.07       0
  4985.5    0.05       0  4989.5    0.07       0  5139.1   0.035       0
  5383.2    0.12       0
Bank Sta=4985.5,4989.5
Exp/Cntr=0.3,0.1

Type RM Length L Ch R = 1,4097,547,547,547
BEGIN DESCRIPTION:
Stream0156_DS 5.0
END DESCRIPTION:
XS GIS Cut Line= 3
      2053704.43     13878468.38      2053808.60     13878135.02
      2053650.05     13877689.76
#Sta/Elev= 30
  4640.5 1343.33  4647.5 1343.22  4678.9 1341.34  4717.4 1340.36  4794.6 1336.64
  4851.7 1332.30  4859.6 1331.87  4864.8 1332.86  4874.5 1331.48  4916.4 1330.42
  4979.3 1327.45  4985.1 1321.58  4985.4 1321.08  4989.1 1321.58  5000.4 1321.81
  5010.6 1327.42  5015.4 1326.88  5021.6 1328.02  5032.2 1328.45  5163.7 1327.16
  5329.5 1325.82  5361.3 1327.10  5374.9 1331.30  5382.5 1336.14  5393.2 1341.28
  5400.7 1346.49  5406.0 1347.41  5414.4 1351.67  5431.5 1358.19  5462.4 1364.37
#Mann=8,-1,0
  4640.5   0.035       0  4647.5    0.07       0  4678.9    0.12       0
  4851.7    0.07       0  4985.1    0.05       0  4989.1    0.07       0
  5163.7   0.035       0  5374.9    0.12       0
Bank Sta=4985.1,4989.1
Exp/Cntr=0.3,0.1

Type RM Length L Ch R = 1,3550,425,425,425
BEGIN DESCRIPTION:
Stream0156_DS 4.0
END DESCRIPTION:
XS GIS Cut Line= 3
      2054075.02     13878274.97      2054275.00     13878025.00
      2054424.99     13877725.03
#Sta/Elev= 30
  4694.0 1328.58  4765.2 1325.28  4779.6 1323.67  4786.0 1321.93  4800.4 1320.72
  4843.6 1321.27  4928.5 1320.24  4950.1 1320.66  4961.7 1315.12  4961.9 1314.62
  4965.7 1315.12  4971.7 1317.16  4979.5 1318.04  4992.5 1319.00  5000.5 1317.81
  5006.9 1318.79  5010.9 1316.09  5016.9 1316.09  5022.5 1316.89  5028.1 1316.50
  5036.5 1319.86  5139.9 1319.73  5163.8 1321.05  5201.4 1328.62  5215.4 1334.08
  5260.1 1346.75  5299.3 1354.49  5327.2 1360.24  5335.6 1361.51  5349.5 1362.21
#Mann=6,-1,0
  4694.0    0.12       0  4961.7    0.05       0  4965.7    0.12       0
  4979.5    0.07       0  5163.8    0.12       0  5299.3   0.035       0
Bank Sta=4961.7,4965.7
Exp/Cntr=0.3,0.1

Type RM Length L Ch R = 1,3125,444,444,444
BEGIN DESCRIPTION:
Stream0156_DS 3.0
END DESCRIPTION:
XS GIS Cut Line= 3
      2054075.04     13878574.98      2054625.00     13878225.00
      2054675.01     13878124.98
#Sta/Elev= 30
  4348.2 1340.70  4361.7 1341.29  4376.9 1339.79  4392.2 1336.87  4398.1 1336.51
  4419.3 1332.11  4443.0 1329.76  4504.4 1327.33  4529.1 1326.01  4564.9 1324.00
  4580.1 1322.22  4616.5 1319.79  4703.9 1317.71  4861.9 1314.85  4878.6 1314.72
  4929.0 1314.54  4940.8 1315.53  4971.3 1316.00  4981.0 1314.01  4984.5 1313.23
  4984.8 1312.73  4988.5 1313.23  4997.1 1315.12  5008.5 1315.62  5033.1 1313.82
  5036.4 1313.88  5058.8 1319.55  5075.5 1325.82  5097.9 1329.62  5111.9 1329.35
#Mann=10,-1,0
  4348.2    0.07       0  4504.4   0.035       0  4529.1    0.07       0
  4703.9   0.035       0  4861.9    0.07       0  4878.6   0.035       0
  4981.0    0.07       0  4984.5    0.05       0  4988.5    0.07       0
  5033.1    0.12       0
Bank Sta=4984.5,4988.5
Exp/Cntr=0.3,0.1

Type RM Length L Ch R = 1,2681,442,442,442
BEGIN DESCRIPTION:
Stream0156_DS 2.0
END DESCRIPTION:
XS GIS Cut Line= 3
      2055225.00     13878475.00      2054975.00     13878325.00
      2054724.97     13878024.97
#Sta/Elev= 30
  4714.4 1329.38  4737.7 1328.11  4749.4 1326.18  4780.5 1317.79  4807.7 1313.77
  4831.0 1312.19  4844.6 1308.37  4866.0 1311.23  4889.3 1312.37  4934.0 1311.66
  4955.4 1312.54  4992.3 1311.02  4998.2 1310.03  5001.0 1308.02  5001.3 1307.52
  5005.0 1308.02  5009.2 1308.02  5019.6 1311.56  5076.9 1312.52  5084.0 1311.31
  5095.9 1311.65  5148.5 1312.46  5237.6 1317.84  5282.6 1318.68  5290.4 1319.91
  5296.9 1322.67  5332.0 1327.87  5346.3 1328.72  5368.5 1332.24  5396.5 1333.40
#Mann=5,-1,0
  4714.4    0.12       0  5001.0    0.05       0  5005.0    0.12       0
  5095.9   0.035       0  5237.6    0.12       0
Bank Sta=5001,5005
Exp/Cntr=0.3,0.1

Type RM Length L Ch R = 1,2239,0,0,0
BEGIN DESCRIPTION:
Stream0156_DS 1.0
END DESCRIPTION:
XS GIS Cut Line= 3
      2055425.00     13878375.01      2055275.00     13878025.00
      2054875.00     13877675.00
#Sta/Elev= 30
  4618.7 1331.90  4662.2 1329.95  4681.4 1327.47  4694.5 1326.07  4738.4 1320.42
  4847.2 1314.25  4890.7 1310.02  4927.7 1308.59  4937.8 1306.51  4966.9 1307.42
  4985.0 1306.90  4987.6 1305.87  4988.1 1305.37  4993.3 1305.87  4996.8 1309.71
  5077.8 1307.33  5092.0 1307.40  5112.9 1309.60  5133.8 1308.36  5184.3 1309.18
  5233.5 1310.39  5261.9 1313.19  5297.0 1313.11  5311.3 1315.44  5354.0 1319.39
  5374.9 1323.76  5438.5 1333.23  5460.3 1334.14  5495.4 1339.41  5531.0 1341.80
#Mann=7,-1,0
  4618.7    0.12       0  4681.4    0.07       0  4694.5    0.12       0
  4927.7   0.035       0  4987.6   0.035       0  4993.3   0.035       0
  5184.3    0.07       0
Bank Sta=4987.6,4993.3
Exp/Cntr=0.3,0.1

Chan Stop Cuts=-1