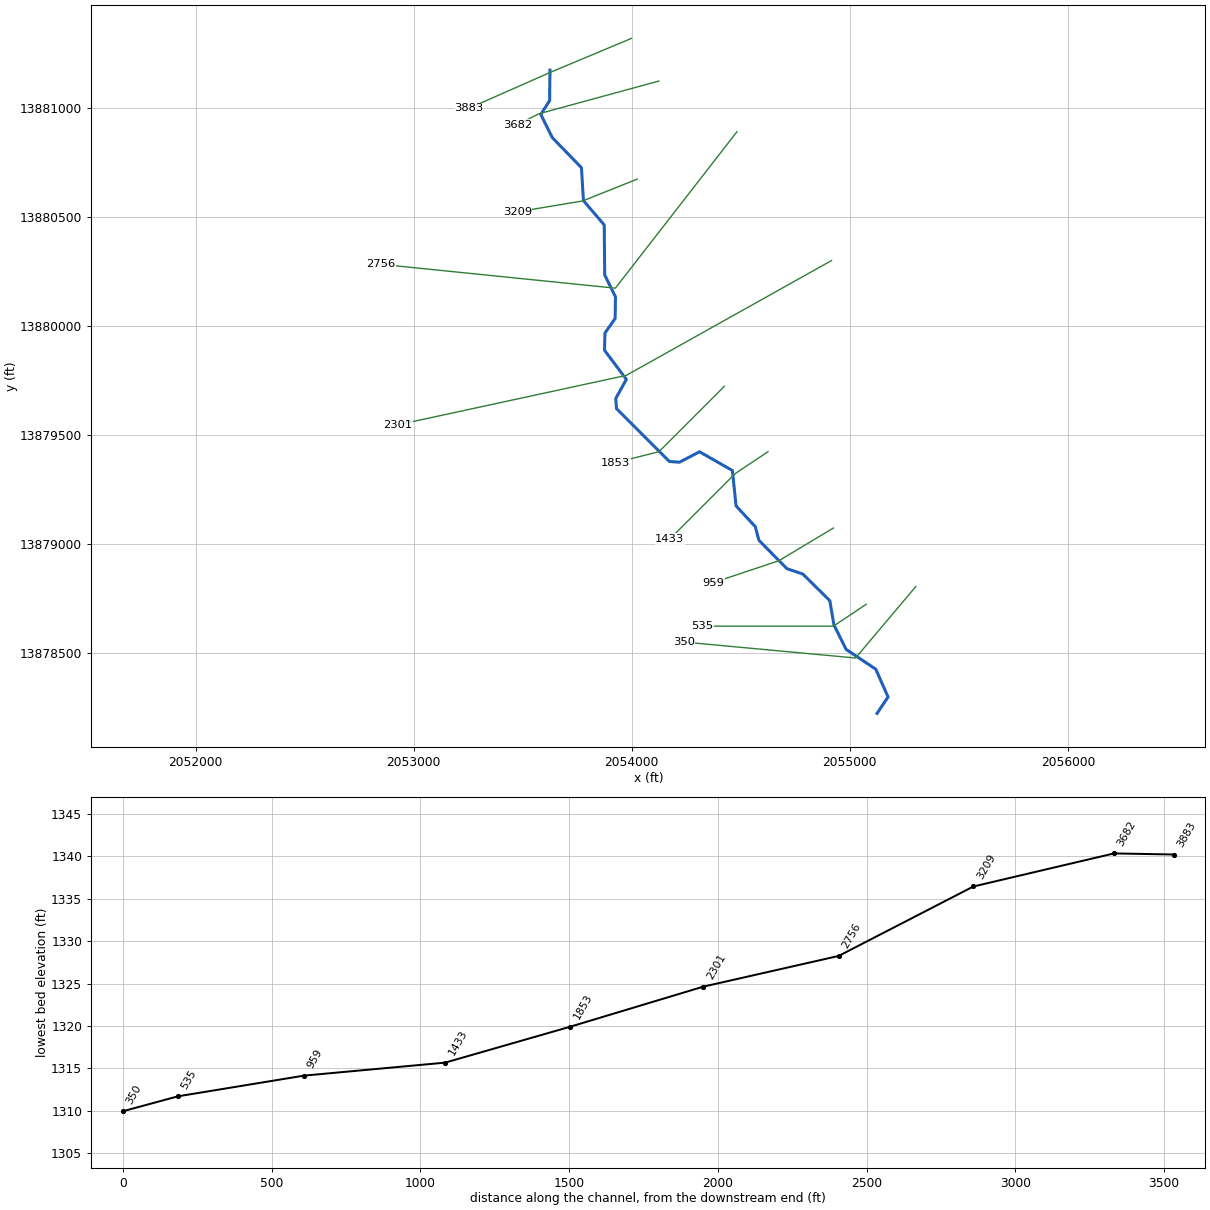
--- Stream0157_DS.prj (project) ---

Proj Title=Stream0157_DS Base Level Engineering
Current Plan=p01
Default Exp/Contr=0.3,0.1
English Units
Geom File=g01
Flow File=f01
Plan File=p01
BEGIN DESCRIPTION:
Stream0157_DS
END DESCRIPTION:

--- Stream0157_DS.p01 (plan) ---

Plan Title=Multiple Run
Short Identifier=Multiple
Geom File=g01
Flow File=f01
Subcritical Flow
K Sum by GR= 0
Std Step Tol= 0.01
Critical Tol= 0.01
Num of Std Step Trials= 20
Max Error Tol= 0.3
Flow Tol Ratio= 0.001
Split Flow NTrial= 30
Split Flow Tol= 0.02
Split Flow Ratio= 0.02
Log Output Level= 0
Friction Slope Method= 1
Unsteady Friction Slope Method= 2
Unsteady Bridges Friction Slope Method= 1
Parabolic Critical Depth
Global Vel Dist=  1 , 1 , 1
Global Log Level= 0
CheckData=True
Encroach Param= -1, 0, 0, 0
BEGIN DESCRIPTION:
Multiple Run
END DESCRIPTION:

--- Stream0157_DS.f01 (steady flow) ---

Flow Title=Multiple
Number of Profiles=7
Profile Names=10-year,25-year,50-year,1pct_min,100-year,1pct_plu,500-year
River Rch & RM= Stream0157_DS,Reach-1,3883
     746    1230    1679    1112    2218    4426    3828
River Rch & RM= Stream0157_DS,Reach-1,3682
    1068    1792    2475    1656    3304    6593    5823
Boundary for River Rch & Prof#=Stream0157_DS,Reach-1,1
Up Type=0
Dn Type=3
Dn Slope=0.005
Boundary for River Rch & Prof#=Stream0157_DS,Reach-1,2
Up Type=0
Dn Type=3
Dn Slope=0.005
Boundary for River Rch & Prof#=Stream0157_DS,Reach-1,3
Up Type=0
Dn Type=3
Dn Slope=0.005
Boundary for River Rch & Prof#=Stream0157_DS,Reach-1,4
Up Type=0
Dn Type=3
Dn Slope=0.005
Boundary for River Rch & Prof#=Stream0157_DS,Reach-1,5
Up Type=0
Dn Type=3
Dn Slope=0.005
Boundary for River Rch & Prof#=Stream0157_DS,Reach-1,6
Up Type=0
Dn Type=3
Dn Slope=0.005
Boundary for River Rch & Prof#=Stream0157_DS,Reach-1,7
Up Type=0
Dn Type=3
Dn Slope=0.005

--- Stream0157_DS.g01 (geometry) ---

Geom Title=Existing Conditions

River Reach=Stream0157_DS,Reach-1
Reach XY= 30
      2053625.00     13881175.00      2053623.66     13881035.41
      2053583.04     13880971.68      2053635.75     13880865.32
      2053769.53     13880727.45      2053778.56     13880576.47
      2053873.79     13880465.41      2053876.22     13880235.50
      2053925.50     13880135.17      2053923.79     13880035.51
      2053877.28     13879969.43      2053875.25     13879890.22
      2053975.29     13879756.61      2053926.81     13879668.88
      2053930.09     13879622.70      2054172.70     13879380.09
      2054219.28     13879376.93      2054310.90     13879424.77
      2054461.77     13879338.67      2054478.55     13879176.47
      2054566.82     13879081.04      2054583.16     13879018.95
      2054711.79     13878888.63      2054784.68     13878864.22
      2054908.54     13878741.75      2054927.33     13878630.97
      2054983.02     13878518.66      2055119.27     13878427.55
      2055175.62     13878300.06      2055125.00     13878225.00

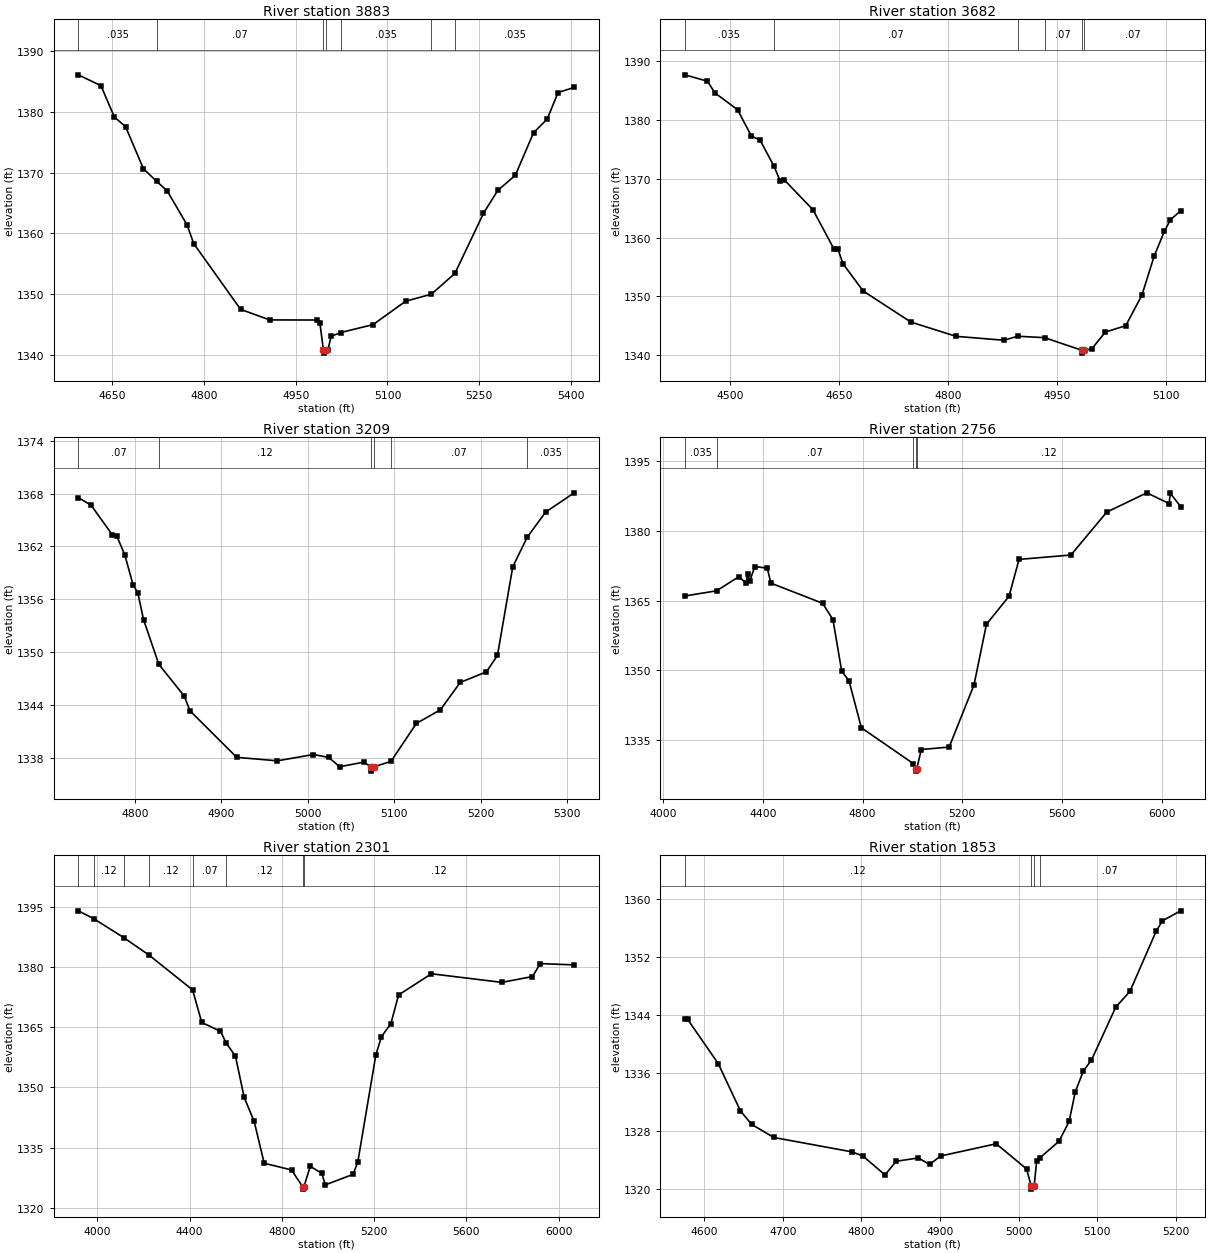
Type RM Length L Ch R = 1,3883,201,201,201
BEGIN DESCRIPTION:
Stream0157_DS 9.0
END DESCRIPTION:
XS GIS Cut Line= 3
      2053999.13     13881320.74      2053625.02     13881164.04
      2053254.24     13881000.13
#Sta/Elev= 30
  4594.4 1386.14  4631.4 1384.35  4653.3 1379.19  4671.7 1377.58  4700.9 1370.63
  4722.6 1368.57  4739.8 1366.98  4772.2 1361.39  4783.2 1358.29  4859.8 1347.45
  4907.4 1345.71  4984.2 1345.69  4989.6 1345.13  4995.3 1340.73  4995.6 1340.23
  4999.3 1340.73  5002.7 1340.73  5007.7 1343.00  5023.8 1343.63  5076.6 1344.94
  5129.7 1348.79  5171.9 1349.95  5210.4 1353.39  5257.1 1363.30  5280.4 1367.06
  5309.2 1369.57  5339.0 1376.60  5361.3 1378.84  5379.1 1383.22  5405.4 1384.06
#Mann=7,-1,0
  4594.4   0.035       0  4722.6    0.07       0  4995.3    0.05       0
  4999.3    0.07       0  5023.8   0.035       0  5171.9    0.07       0
  5210.4   0.035       0
Bank Sta=4995.3,4999.3
Exp/Cntr=0.3,0.1

Type RM Length L Ch R = 1,3682,473,473,473
BEGIN DESCRIPTION:
Stream0157_DS 8.0
END DESCRIPTION:
XS GIS Cut Line= 3
      2054124.97     13881124.99      2053575.00     13880975.00
      2053474.96     13880924.98
#Sta/Elev= 30
  4438.1 1387.65  4469.2 1386.57  4479.5 1384.58  4510.6 1381.73  4529.6 1377.27
  4541.7 1376.53  4560.6 1372.17  4569.4 1369.58  4574.5 1369.85  4614.3 1364.73
  4643.6 1357.97  4648.8 1357.98  4655.7 1355.54  4683.4 1350.92  4749.0 1345.64
  4811.2 1343.21  4876.9 1342.55  4896.0 1343.23  4932.9 1342.99  4983.7 1340.86
  4983.9 1340.36  4987.7 1340.86  4997.8 1341.08  5016.5 1343.94  5044.5 1345.02
  5066.8 1350.23  5083.6 1356.84  5097.6 1361.04  5106.0 1363.03  5120.0 1364.53
#Mann=6,-1,0
  4438.1   0.035       0  4560.6    0.07       0  4896.0   0.035       0
  4932.9    0.07       0  4983.7    0.05       0  4987.7    0.07       0
Bank Sta=4983.7,4987.7
Exp/Cntr=0.3,0.1

Type RM Length L Ch R = 1,3209,453,453,453
BEGIN DESCRIPTION:
Stream0157_DS 7.0
END DESCRIPTION:
XS GIS Cut Line= 3
      2054024.99     13880675.00      2053775.00     13880575.00
      2053474.99     13880525.00
#Sta/Elev= 30
  4734.6 1367.56  4749.4 1366.69  4773.6 1363.36  4779.0 1363.21  4788.4 1361.02
  4797.9 1357.64  4803.3 1356.76  4810.0 1353.69  4827.7 1348.60  4857.1 1344.99
  4863.8 1343.31  4917.7 1338.03  4964.8 1337.63  5006.4 1338.35  5024.1 1338.02
  5036.8 1336.96  5064.7 1337.48  5072.8 1336.96  5073.1 1336.46  5076.8 1336.96
  5096.2 1337.57  5125.5 1341.88  5153.4 1343.44  5176.2 1346.54  5206.6 1347.75
  5219.3 1349.62  5237.0 1359.69  5253.7 1363.05  5275.0 1365.91  5308.0 1368.10
#Mann=6,-1,0
  4734.6    0.07       0  4827.7    0.12       0  5072.8    0.05       0
  5076.8    0.12       0  5096.2    0.07       0  5253.7   0.035       0
Bank Sta=5072.8,5076.8
Exp/Cntr=0.3,0.1

Type RM Length L Ch R = 1,2756,455,455,455
BEGIN DESCRIPTION:
Stream0157_DS 6.0
END DESCRIPTION:
XS GIS Cut Line= 3
      2054482.23     13880891.99      2053925.00     13880175.00
      2052850.31     13880284.32
#Sta/Elev= 30
  4087.1 1365.97  4214.6 1367.09  4303.8 1370.12  4332.7 1368.75  4339.0 1370.78
  4347.2 1369.15  4368.0 1372.32  4417.8 1371.96  4432.3 1368.74  4639.5 1364.41
  4681.1 1360.91  4716.5 1349.73  4745.4 1347.75  4795.2 1337.60  5003.2 1329.90
  5013.3 1328.77  5013.5 1328.27  5017.3 1328.77  5035.4 1332.92  5147.2 1333.45
  5246.8 1346.83  5296.7 1359.89  5387.2 1365.91  5427.4 1373.85  5635.4 1374.79
  5779.2 1384.03  5940.0 1388.18  6029.1 1385.88  6034.1 1388.08  6075.4 1385.22
#Mann=5,-1,0
  4087.1   0.035       0  4214.6    0.07       0  5003.2    0.12       0
  5013.3    0.05       0  5017.3    0.12       0
Bank Sta=5013.3,5017.3
Exp/Cntr=0.3,0.1

Type RM Length L Ch R = 1,2301,448,448,448
BEGIN DESCRIPTION:
Stream0157_DS 5.0
END DESCRIPTION:
XS GIS Cut Line= 3
      2054916.21     13880301.67      2053975.00     13879775.00
      2052928.35     13879548.58
#Sta/Elev= 30
  3917.8 1393.97  3986.6 1391.94  4114.2 1387.31  4225.3 1382.90  4413.1 1374.27
  4452.8 1366.17  4533.9 1363.96  4558.3 1361.11  4599.0 1357.74  4636.7 1347.52
  4680.1 1341.50  4723.5 1331.10  4842.2 1329.42  4891.2 1325.15  4891.5 1324.65
  4895.2 1325.15  4923.3 1330.34  4973.4 1328.56  4988.4 1325.71  5108.9 1328.33
  5129.3 1331.41  5207.6 1358.10  5231.7 1362.61  5272.6 1365.86  5306.1 1373.02
  5448.6 1378.29  5753.5 1376.15  5886.5 1377.60  5920.4 1380.83  6067.2 1380.50
#Mann=8,-1,0
  3917.8    0.07       0  3986.6    0.12       0  4114.2    0.07       0
  4225.3    0.12       0  4413.1    0.07       0  4558.3    0.12       0
  4891.2    0.05       0  4895.2    0.12       0
Bank Sta=4891.2,4895.2
Exp/Cntr=0.3,0.1

Type RM Length L Ch R = 1,1853,420,420,420
BEGIN DESCRIPTION:
Stream0157_DS 4.0
END DESCRIPTION:
XS GIS Cut Line= 3
      2054425.02     13879725.02      2054125.00     13879425.00
      2053924.95     13879374.99
#Sta/Elev= 30
  4575.4 1343.39  4579.0 1343.39  4617.9 1337.28  4646.1 1330.75  4660.3 1328.88
  4688.6 1327.06  4787.6 1325.08  4801.7 1324.52  4830.0 1321.88  4844.1 1323.77
  4872.4 1324.23  4886.6 1323.33  4900.7 1324.50  4971.4 1326.19  5010.0 1322.71
  5015.7 1320.42  5016.0 1319.92  5019.7 1320.42  5022.9 1323.87  5026.5 1324.21
  5051.2 1326.53  5064.1 1329.28  5071.9 1333.35  5082.2 1336.26  5092.5 1337.76
  5123.4 1345.08  5141.4 1347.26  5174.9 1355.61  5182.7 1357.02  5205.9 1358.40
#Mann=4,-1,0
  4575.4    0.12       0  5015.7    0.05       0  5019.7    0.12       0
  5026.5    0.07       0
Bank Sta=5015.7,5019.7
Exp/Cntr=0.3,0.1

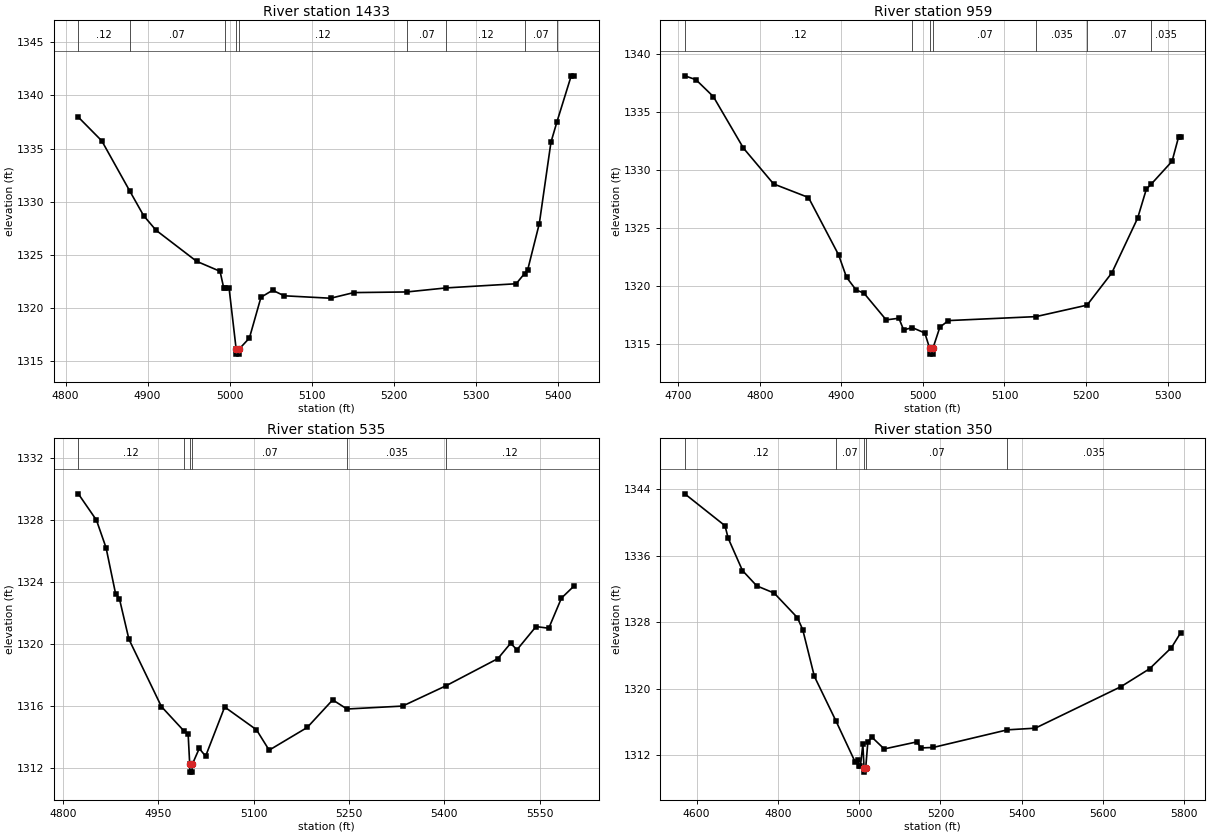
Type RM Length L Ch R = 1,1433,474,474,474
BEGIN DESCRIPTION:
Stream0157_DS 3.0
END DESCRIPTION:
XS GIS Cut Line= 3
      2054625.02     13879425.01      2054475.00     13879325.00
      2054174.97     13879024.97
#Sta/Elev= 30
  4815.6 1337.95  4844.2 1335.72  4878.1 1331.04  4895.2 1328.70  4910.3 1327.33
  4959.8 1324.41  4988.4 1323.47  4992.9 1321.90  4994.1 1321.90  4999.4 1321.90
  5008.0 1316.19  5008.3 1315.69  5011.8 1315.69  5012.0 1316.19  5024.2 1317.20
  5038.3 1321.03  5052.5 1321.69  5066.6 1321.17  5123.2 1320.94  5151.5 1321.47
  5216.1 1321.53  5264.2 1321.91  5349.5 1322.30  5359.7 1323.26  5363.6 1323.63
  5377.7 1327.95  5391.9 1335.59  5399.3 1337.53  5416.6 1341.83  5420.2 1341.83
#Mann=9,-1,0
  4815.6    0.12       0  4878.1    0.07       0  4994.1    0.12       0
  5008.0    0.05       0  5012.0    0.12       0  5216.1    0.07       0
  5264.2    0.12       0  5359.7    0.07       0  5399.3   0.035       0
Bank Sta=5008,5012
Exp/Cntr=0.3,0.1

Type RM Length L Ch R = 1,959,424,424,424
BEGIN DESCRIPTION:
Stream0157_DS 2.0
END DESCRIPTION:
XS GIS Cut Line= 3
      2054924.98     13879074.99      2054675.00     13878925.00
      2054375.05     13878825.02
#Sta/Elev= 30
  4708.2 1338.13  4721.8 1337.80  4743.2 1336.34  4780.1 1331.90  4817.0 1328.82
  4859.8 1327.65  4896.7 1322.71  4906.4 1320.78  4918.1 1319.69  4927.8 1319.41
  4955.0 1317.11  4970.6 1317.25  4976.4 1316.25  4987.1 1316.44  5002.4 1315.98
  5008.3 1314.66  5008.5 1314.16  5012.0 1314.16  5012.3 1314.66  5020.8 1316.48
  5031.3 1317.05  5138.5 1317.39  5201.2 1318.38  5231.6 1321.16  5263.2 1325.87
  5273.8 1328.35  5280.1 1328.82  5305.4 1330.77  5313.3 1332.84  5315.9 1332.84
#Mann=7,-1,0
  4708.2    0.12       0  4987.1    0.07       0  5008.3    0.05       0
  5012.3    0.07       0  5138.5   0.035       0  5201.2    0.07       0
  5280.1   0.035       0
Bank Sta=5008.3,5012.3
Exp/Cntr=0.3,0.1

Type RM Length L Ch R = 1,535,185,185,185
BEGIN DESCRIPTION:
Stream0157_DS 1.0
END DESCRIPTION:
XS GIS Cut Line= 3
      2055075.00     13878725.00      2054925.00     13878625.00
      2054324.98     13878625.00
#Sta/Elev= 30
  4824.0 1329.71  4852.5 1328.01  4867.6 1326.23  4882.6 1323.26  4888.6 1322.94
  4903.6 1320.31  4954.7 1315.96  4989.8 1314.40  4996.8 1314.19  4999.3 1312.22
  4999.5 1311.72  5003.0 1311.72  5003.3 1312.22  5014.3 1313.25  5024.3 1312.75
  5054.3 1315.93  5104.3 1314.46  5124.3 1313.14  5184.3 1314.61  5224.3 1316.39
  5246.8 1315.80  5334.3 1315.99  5403.0 1317.31  5484.3 1319.06  5504.3 1320.05
  5514.3 1319.63  5544.3 1321.13  5564.3 1321.02  5584.3 1322.97  5604.3 1323.76
#Mann=6,-1,0
  4824.0    0.12       0  4989.8    0.07       0  4999.3    0.05       0
  5003.3    0.07       0  5246.8   0.035       0  5403.0    0.12       0
Bank Sta=4999.3,5003.3
Exp/Cntr=0.3,0.1

Type RM Length L Ch R = 1,350,0,0,0
BEGIN DESCRIPTION:
Stream0157_DS 0.0
END DESCRIPTION:
XS GIS Cut Line= 3
      2055302.86     13878806.73      2055026.46     13878478.90
      2054238.97     13878552.22
#Sta/Elev= 30
  4571.2 1343.46  4670.1 1339.62  4677.9 1338.12  4713.0 1334.23  4748.2 1332.38
  4791.1 1331.51  4848.1 1328.56  4861.3 1327.11  4889.9 1321.49  4943.6 1316.06
  4990.0 1311.21  4996.5 1311.46  4999.3 1310.69  5003.2 1310.69  5009.2 1313.29
  5012.2 1310.46  5012.5 1309.96  5016.2 1310.46  5021.6 1313.64  5031.6 1314.16
  5061.7 1312.75  5142.1 1313.60  5152.1 1312.87  5182.2 1312.93  5364.6 1315.05
  5433.3 1315.25  5644.2 1320.25  5714.5 1322.40  5768.4 1324.95  5790.9 1326.73
#Mann=5,-1,0
  4571.2    0.12       0  4943.6    0.07       0  5012.2    0.05       0
  5016.2    0.07       0  5364.6   0.035       0
Bank Sta=5012.2,5016.2
Exp/Cntr=0.3,0.1

Chan Stop Cuts=-1