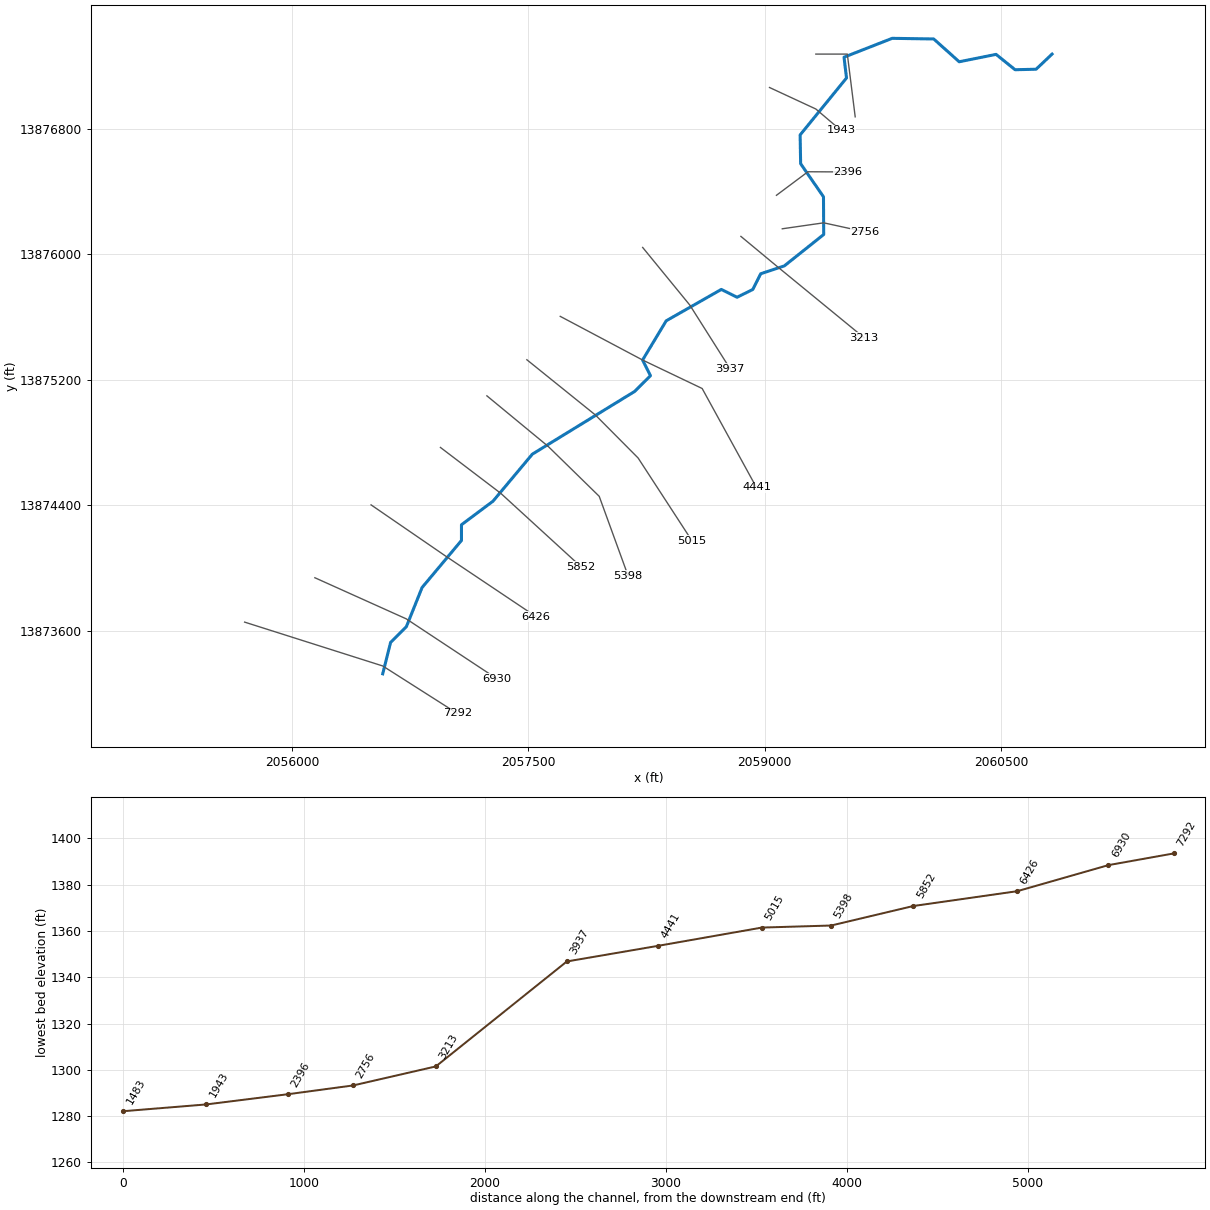
--- Stream0158_DS.prj (project) ---

Proj Title=Stream0158_DS Base Level Engineering
Current Plan=p01
Default Exp/Contr=0.3,0.1
English Units
Geom File=g01
Flow File=f01
Plan File=p01
BEGIN DESCRIPTION:
Stream0158_DS
END DESCRIPTION:

--- Stream0158_DS.p01 (plan) ---

Plan Title=Multiple Run
Short Identifier=Multiple
Geom File=g01
Flow File=f01
Subcritical Flow
K Sum by GR= 0
Std Step Tol= 0.01
Critical Tol= 0.01
Num of Std Step Trials= 20
Max Error Tol= 0.3
Flow Tol Ratio= 0.001
Split Flow NTrial= 30
Split Flow Tol= 0.02
Split Flow Ratio= 0.02
Log Output Level= 0
Friction Slope Method= 1
Unsteady Friction Slope Method= 2
Unsteady Bridges Friction Slope Method= 1
Parabolic Critical Depth
Global Vel Dist=  1 , 1 , 1
Global Log Level= 0
CheckData=True
Encroach Param= -1, 0, 0, 0
BEGIN DESCRIPTION:
Multiple Run
END DESCRIPTION:

--- Stream0158_DS.f01 (steady flow) ---

Flow Title=Multiple
Number of Profiles=7
Profile Names=10-year,25-year,50-year,1pct_min,100-year,1pct_plu,500-year
River Rch & RM= Stream0158_DS,Reach-1,7292
     622    1013    1374     905    1806    3604    3080
River Rch & RM= Stream0158_DS,Reach-1,6930
    1374    2346    3279    2221    4431    8841    7998
Boundary for River Rch & Prof#=Stream0158_DS,Reach-1,1
Up Type=0
Dn Type=3
Dn Slope=0.005
Boundary for River Rch & Prof#=Stream0158_DS,Reach-1,2
Up Type=0
Dn Type=3
Dn Slope=0.005
Boundary for River Rch & Prof#=Stream0158_DS,Reach-1,3
Up Type=0
Dn Type=3
Dn Slope=0.005
Boundary for River Rch & Prof#=Stream0158_DS,Reach-1,4
Up Type=0
Dn Type=3
Dn Slope=0.005
Boundary for River Rch & Prof#=Stream0158_DS,Reach-1,5
Up Type=0
Dn Type=3
Dn Slope=0.005
Boundary for River Rch & Prof#=Stream0158_DS,Reach-1,6
Up Type=0
Dn Type=3
Dn Slope=0.005
Boundary for River Rch & Prof#=Stream0158_DS,Reach-1,7
Up Type=0
Dn Type=3
Dn Slope=0.005

--- Stream0158_DS.g01 (geometry) ---

Geom Title=Existing Conditions

River Reach=Stream0158_DS,Reach-1
Reach XY= 30
      2056575.00     13873325.00      2056625.00     13873525.00
      2056725.00     13873625.00      2056825.00     13873875.00
      2057075.00     13874175.00      2057075.00     13874275.00
      2057275.00     13874425.00      2057525.00     13874725.00
      2058175.00     13875125.00      2058275.00     13875225.00
      2058225.00     13875325.00      2058375.00     13875575.00
      2058725.00     13875775.00      2058825.00     13875725.00
      2058925.00     13875775.00      2058975.00     13875875.00
      2059125.00     13875925.00      2059375.00     13876125.00
      2059373.64     13876365.35      2059228.55     13876576.47
      2059225.38     13876759.84      2059519.88     13877122.71
      2059503.97     13877255.23      2059809.82     13877375.43
      2060073.54     13877371.46      2060235.44     13877226.04
      2060469.37     13877273.26      2060590.17     13877175.37
      2060723.55     13877178.48      2060825.00     13877275.00

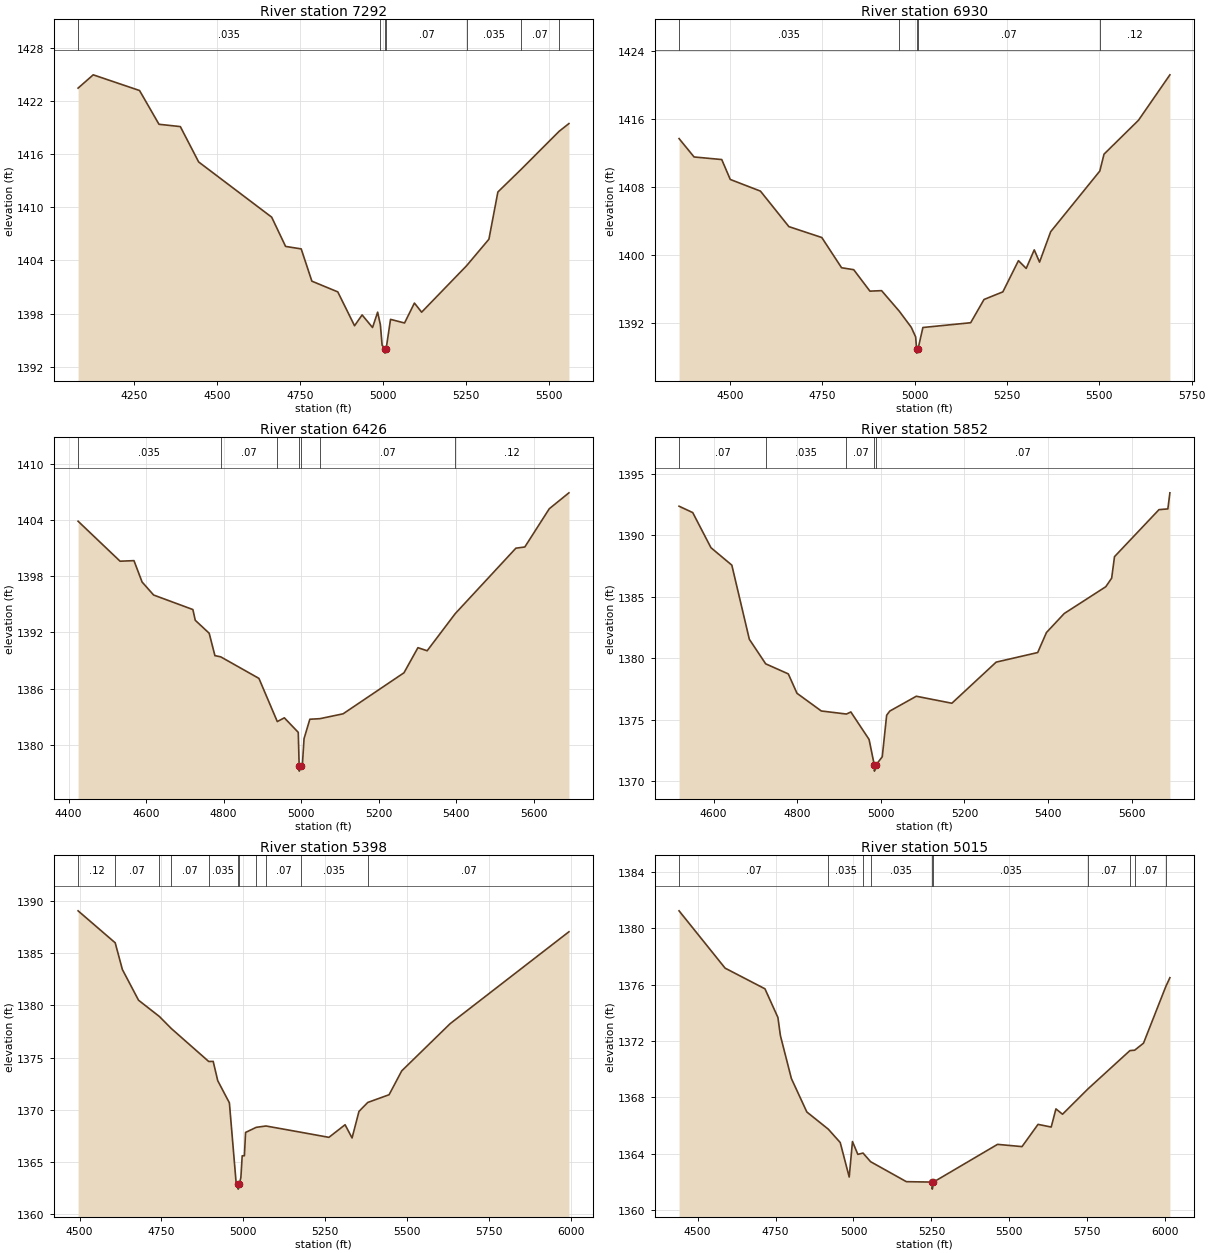
Type RM Length L Ch R = 1,7292,362,362,362
BEGIN DESCRIPTION:
Stream0158_DS 13.0
END DESCRIPTION:
XS GIS Cut Line= 3
      2055698.25     13873654.44      2056575.00     13873375.00
      2057047.88     13873072.79
#Sta/Elev= 30
  4079.8 1423.44  4125.5 1424.94  4265.3 1423.17  4324.0 1419.36  4388.4 1419.10
  4443.7 1415.11  4664.1 1408.88  4706.1 1405.58  4753.2 1405.30  4785.4 1401.66
  4863.6 1400.45  4914.2 1396.63  4937.0 1397.85  4968.5 1396.43  4983.9 1398.16
  4992.2 1396.74  4997.4 1394.44  5005.6 1394.04  5005.9 1393.54  5009.6 1394.04
  5022.8 1397.35  5065.1 1396.94  5094.9 1399.19  5116.7 1398.16  5252.3 1403.40
  5319.7 1406.39  5346.8 1411.72  5416.6 1414.26  5531.4 1418.56  5561.2 1419.44
#Mann=7,-1,0
  4079.8   0.035       0  4992.2    0.07       0  5005.6    0.05       0
  5009.6    0.07       0  5252.3   0.035       0  5416.6    0.07       0
  5531.4    0.12       0
Bank Sta=5005.6,5009.6
Exp/Cntr=0.3,0.1

Type RM Length L Ch R = 1,6930,504,504,504
BEGIN DESCRIPTION:
Stream0158_DS 12.0
END DESCRIPTION:
XS GIS Cut Line= 3
      2056144.19     13873937.31      2056725.00     13873675.00
      2057300.88     13873292.93
#Sta/Elev= 30
  4362.7 1413.67  4403.4 1411.51  4478.2 1411.21  4501.3 1408.87  4583.0 1407.50
  4659.9 1403.33  4749.0 1402.05  4802.5 1398.50  4835.4 1398.27  4879.3 1395.75
  4910.8 1395.81  4959.0 1393.38  4991.2 1391.50  5003.0 1390.38  5005.5 1388.97
  5005.8 1388.47  5009.5 1388.97  5022.6 1391.48  5151.9 1392.04  5188.0 1394.77
  5239.1 1395.67  5281.2 1399.33  5302.2 1398.42  5324.0 1400.60  5338.3 1399.16
  5368.4 1402.73  5501.4 1409.86  5512.8 1411.84  5606.0 1415.82  5691.1 1421.16
#Mann=5,-1,0
  4362.7   0.035       0  4959.0    0.07       0  5005.5    0.05       0
  5009.5    0.07       0  5501.4    0.12       0
Bank Sta=5005.5,5009.5
Exp/Cntr=0.3,0.1

Type RM Length L Ch R = 1,6426,574,574,574
BEGIN DESCRIPTION:
Stream0158_DS 11.0
END DESCRIPTION:
XS GIS Cut Line= 3
      2056501.02     13874401.76      2056975.00     13874075.00
      2057548.64     13873689.39
#Sta/Elev= 30
  4424.3 1403.88  4532.7 1399.61  4568.6 1399.67  4589.5 1397.39  4619.3 1396.00
  4720.6 1394.45  4726.8 1393.30  4762.7 1391.92  4777.5 1389.53  4792.5 1389.40
  4891.1 1387.10  4938.5 1382.49  4956.7 1382.89  4992.6 1381.34  4995.0 1377.70
  4995.2 1377.20  4999.0 1377.70  5003.0 1377.70  5007.5 1380.66  5022.5 1382.74
  5048.6 1382.80  5108.4 1383.32  5265.5 1387.70  5301.5 1390.38  5325.3 1390.05
  5397.7 1394.01  5554.3 1401.00  5577.4 1401.13  5640.5 1405.21  5691.2 1406.91
#Mann=7,-1,0
  4424.3   0.035       0  4792.5    0.07       0  4938.5    0.12       0
  4995.0    0.05       0  4999.0    0.12       0  5048.6    0.07       0
  5397.7    0.12       0
Bank Sta=4995,4999
Exp/Cntr=0.3,0.1

Type RM Length L Ch R = 1,5852,454,454,454
BEGIN DESCRIPTION:
Stream0158_DS 10.0
END DESCRIPTION:
XS GIS Cut Line= 3
      2056941.39     13874767.83      2057325.00     13874475.00
      2057834.19     13874007.28
#Sta/Elev= 30
  4517.4 1392.38  4550.1 1391.86  4593.7 1389.00  4643.6 1387.58  4685.5 1381.54
  4724.6 1379.54  4778.7 1378.72  4799.5 1377.14  4857.6 1375.70  4917.8 1375.45
  4928.3 1375.62  4971.9 1373.38  4984.4 1371.30  4984.7 1370.80  4988.4 1371.30
  5003.4 1371.97  5013.9 1375.35  5021.3 1375.69  5084.8 1376.90  5169.9 1376.33
  5275.9 1379.68  5375.2 1380.46  5396.1 1382.09  5438.7 1383.64  5538.0 1385.82
  5552.1 1386.52  5558.9 1388.27  5665.3 1392.10  5686.5 1392.16  5691.4 1393.47
#Mann=5,-1,0
  4517.4    0.07       0  4724.6   0.035       0  4917.8    0.07       0
  4984.4    0.05       0  4988.4    0.07       0
Bank Sta=4984.4,4988.4
Exp/Cntr=0.3,0.1

Type RM Length L Ch R = 1,5398,383,383,383
BEGIN DESCRIPTION:
Stream0158_DS 9.0
END DESCRIPTION:
XS GIS Cut Line= 4
      2057236.42     13875096.76      2057625.00     13874775.00
      2057949.63     13874456.32      2058133.48     13873948.70
#Sta/Elev= 30
  4495.5 1389.08  4608.9 1386.01  4630.8 1383.45  4680.2 1380.50  4743.8 1378.94
  4780.4 1377.78  4894.6 1374.62  4908.2 1374.63  4922.1 1372.78  4957.7 1370.65
  4978.5 1362.89  4984.3 1362.87  4984.6 1362.37  4988.3 1362.87  4992.8 1363.50
  4996.8 1365.57  5003.5 1365.57  5007.1 1367.81  5039.6 1368.30  5069.4 1368.43
  5175.8 1367.83  5261.7 1367.34  5311.1 1368.55  5332.4 1367.28  5353.5 1369.83
  5380.4 1370.69  5445.5 1371.43  5484.1 1373.72  5632.0 1378.25  5994.8 1387.07
#Mann=11,-1,0
  4495.5    0.12       0  4608.9    0.07       0  4743.8   0.035       0
  4780.4    0.07       0  4894.6   0.035       0  4984.3   0.035       0
  4988.3   0.035       0  5039.6    0.12       0  5069.4    0.07       0
  5175.8   0.035       0  5380.4    0.07       0
Bank Sta=4984.3,4988.3
Exp/Cntr=0.3,0.1

Type RM Length L Ch R = 1,5015,574,574,574
BEGIN DESCRIPTION:
Stream0158_DS 8.0
END DESCRIPTION:
XS GIS Cut Line= 4
      2057490.18     13875326.78      2057925.00     13874975.00
      2058196.74     13874700.41      2058538.57     13874172.90
#Sta/Elev= 30
  4440.7 1381.25  4588.3 1377.18  4716.2 1375.71  4757.8 1373.67  4765.7 1372.39
  4800.9 1369.34  4850.5 1366.96  4919.3 1365.74  4957.6 1364.79  4986.4 1362.34
  4996.8 1364.86  5014.1 1363.95  5030.8 1364.04  5054.9 1363.43  5169.7 1362.01
  5252.5 1361.98  5252.8 1361.48  5256.5 1361.98  5462.1 1364.66  5540.6 1364.50
  5592.0 1366.08  5634.2 1365.89  5649.4 1367.18  5670.5 1366.80  5752.1 1368.60
  5886.6 1371.32  5901.9 1371.35  5930.3 1371.85  6001.5 1375.86  6014.9 1376.50
#Mann=10,-1,0
  4440.7    0.07       0  4919.3   0.035       0  5030.8    0.07       0
  5054.9   0.035       0  5252.5   0.035       0  5256.5   0.035       0
  5752.1    0.07       0  5886.6   0.035       0  5901.9    0.07       0
  6001.5   0.035       0
Bank Sta=5252.5,5256.5
Exp/Cntr=0.3,0.1

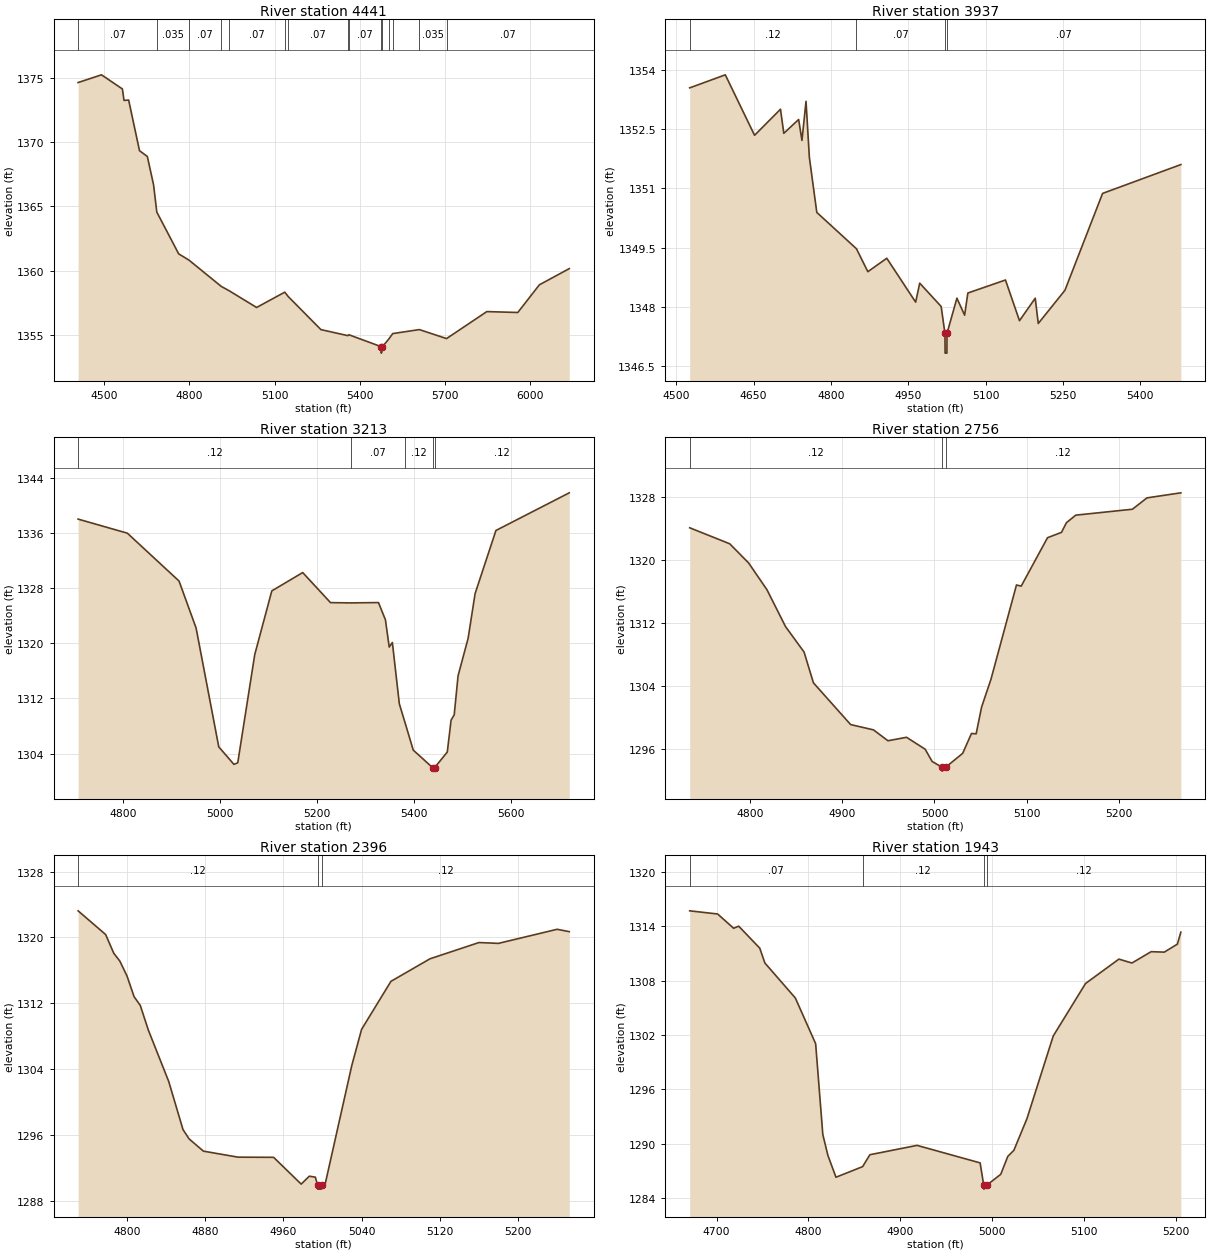
Type RM Length L Ch R = 1,4441,504,504,504
BEGIN DESCRIPTION:
Stream0158_DS 7.0
END DESCRIPTION:
XS GIS Cut Line= 4
      2057702.19     13875603.36      2058225.00     13875325.00
      2058603.30     13875143.49      2058947.92     13874512.79
#Sta/Elev= 30
  4407.7 1374.62  4490.2 1375.22  4563.8 1374.12  4569.5 1373.23  4585.8 1373.26
  4624.1 1369.32  4651.7 1368.87  4673.7 1366.66  4685.0 1364.55  4762.1 1361.30
  4798.5 1360.81  4912.0 1358.77  4939.2 1358.44  5036.7 1357.13  5135.9 1358.32
  5148.0 1357.98  5263.2 1355.41  5357.9 1354.94  5361.6 1355.01  5475.9 1354.08
  5476.2 1353.58  5479.9 1354.08  5502.6 1354.68  5516.3 1355.10  5610.2 1355.41
  5705.9 1354.71  5847.9 1356.81  5957.0 1356.74  6032.9 1358.89  6138.3 1360.15
#Mann=15,-1,0
  4407.7    0.07       0  4685.0   0.035       0  4798.5    0.07       0
  4912.0   0.035       0  4939.2    0.07       0  5135.9   0.035       0
  5148.0    0.07       0  5357.9   0.035       0  5361.6    0.07       0
  5475.9    0.05       0  5479.9    0.07       0  5502.6   0.035       0
  5516.3    0.07       0  5610.2   0.035       0  5705.9    0.07       0
Bank Sta=5475.9,5479.9
Exp/Cntr=0.3,0.1

Type RM Length L Ch R = 1,3937,724,724,724
BEGIN DESCRIPTION:
Stream0158_DS 6.0
END DESCRIPTION:
XS GIS Cut Line= 3
      2058225.54     13876042.55      2058525.00     13875675.00
      2058780.15     13875270.32
#Sta/Elev= 30
  4525.9 1353.54  4595.0 1353.87  4651.7 1352.34  4702.0 1353.00  4708.4 1352.39
  4737.2 1352.74  4743.6 1352.21  4751.5 1353.20  4758.0 1351.78  4772.4 1350.39
  4849.3 1349.47  4871.4 1348.89  4908.1 1349.23  4964.1 1348.12  4972.0 1348.60
  5013.6 1348.01  5020.9 1347.33  5021.2 1346.83  5024.7 1346.83  5024.9 1347.33
  5044.1 1348.22  5059.1 1347.79  5065.3 1348.35  5138.3 1348.68  5165.5 1347.65
  5196.0 1348.22  5201.9 1347.58  5253.6 1348.42  5326.6 1350.87  5478.4 1351.60
#Mann=4,-1,0
  4525.9    0.12       0  4849.3    0.07       0  5020.9    0.05       0
  5024.9    0.07       0
Bank Sta=5020.9,5024.9
Exp/Cntr=0.3,0.1

Type RM Length L Ch R = 1,3213,457,457,457
BEGIN DESCRIPTION:
Stream0158_DS 5.0
END DESCRIPTION:
XS GIS Cut Line= 3
      2058849.33     13876112.96      2059075.00     13875925.00
      2059631.20     13875467.32
#Sta/Elev= 30
  4706.3 1338.00  4808.0 1335.96  4914.7 1329.02  4949.9 1322.21  4996.7 1304.98
  5028.0 1302.44  5035.9 1302.67  5071.0 1318.36  5106.2 1327.59  5170.0 1330.25
  5227.4 1325.89  5269.3 1325.85  5326.4 1325.90  5340.8 1323.40  5348.6 1319.45
  5355.1 1320.11  5369.5 1311.21  5381.9 1308.34  5398.2 1304.51  5438.3 1301.96
  5438.6 1301.46  5442.3 1301.96  5468.5 1304.23  5476.3 1308.85  5482.8 1309.63
  5490.7 1315.27  5511.5 1320.72  5525.9 1327.20  5568.9 1336.35  5720.3 1341.81
#Mann=5,-1,0
  4706.3    0.12       0  5269.3    0.07       0  5381.9    0.12       0
  5438.3    0.05       0  5442.3    0.12       0
Bank Sta=5438.3,5442.3
Exp/Cntr=0.3,0.1

Type RM Length L Ch R = 1,2756,360,360,360
BEGIN DESCRIPTION:
Stream0158_DS 4.0
END DESCRIPTION:
XS GIS Cut Line= 3
      2059111.96     13876161.54      2059375.03     13876199.53
      2059636.42     13876142.23
#Sta/Elev= 30
  4734.2 1324.09  4777.7 1322.06  4798.2 1319.63  4818.1 1316.24  4838.3 1311.56
  4858.4 1308.34  4868.6 1304.43  4909.0 1299.14  4933.8 1298.47  4949.5 1297.09
  4969.7 1297.53  4989.9 1296.02  4997.5 1294.46  5008.2 1293.74  5008.4 1293.24
  5012.3 1293.74  5030.7 1295.50  5040.2 1298.01  5045.3 1297.97  5051.2 1301.36
  5061.4 1304.89  5089.1 1316.84  5094.2 1316.69  5122.8 1322.83  5138.0 1323.51
  5143.3 1324.73  5153.5 1325.69  5215.0 1326.44  5230.8 1327.88  5267.6 1328.52
#Mann=3,-1,0
  4734.2    0.12       0  5008.2    0.05       0  5012.3    0.12       0
Bank Sta=5008.2,5012.3
Exp/Cntr=0.3,0.1

Type RM Length L Ch R = 1,2396,453,453,453
BEGIN DESCRIPTION:
Stream0158_DS 3.0
END DESCRIPTION:
XS GIS Cut Line= 3
      2059074.98     13876374.98      2059275.00     13876525.00
      2059527.37     13876523.91
#Sta/Elev= 30
  4750.0 1323.23  4778.2 1320.35  4786.5 1318.08  4792.7 1317.13  4800.0 1315.33
  4807.3 1312.80  4813.6 1311.75  4821.9 1308.74  4842.7 1302.52  4857.3 1296.68
  4863.6 1295.54  4878.2 1294.06  4913.6 1293.33  4950.0 1293.31  4978.2 1290.06
  4986.5 1291.02  4992.7 1290.90  4994.9 1289.95  4995.1 1289.45  4998.7 1289.45
  4999.0 1289.95  5002.5 1289.95  5030.0 1304.48  5040.0 1308.85  5070.0 1314.67
  5110.0 1317.41  5160.0 1319.38  5180.0 1319.28  5240.0 1320.99  5252.4 1320.70
#Mann=3,-1,0
  4750.0    0.12       0  4994.9    0.05       0  4999.0    0.12       0
Bank Sta=4994.9,4999
Exp/Cntr=0.3,0.1

Type RM Length L Ch R = 1,1943,460,460,460
BEGIN DESCRIPTION:
Stream0158_DS 2.0
END DESCRIPTION:
XS GIS Cut Line= 3
      2059030.81     13877062.11      2059325.00     13876925.00
      2059484.42     13876788.88
#Sta/Elev= 30
  4670.8 1315.68  4701.2 1315.33  4718.6 1313.76  4724.1 1313.99  4747.0 1311.57
  4752.6 1309.93  4785.7 1306.08  4807.8 1301.04  4815.6 1291.03  4821.1 1288.74
  4829.9 1286.33  4858.9 1287.50  4866.8 1288.81  4918.1 1289.84  4986.7 1287.91
  4990.5 1285.52  4990.8 1285.02  4994.7 1285.52  5009.1 1286.65  5016.8 1288.63
  5023.4 1289.30  5037.6 1292.78  5066.2 1301.89  5101.3 1307.67  5137.6 1310.36
  5151.8 1309.93  5172.7 1311.18  5187.0 1311.13  5201.2 1312.01  5205.0 1313.33
#Mann=4,-1,0
  4670.8    0.07       0  4858.9    0.12       0  4990.5    0.05       0
  4994.7    0.12       0
Bank Sta=4990.5,4994.7
Exp/Cntr=0.3,0.1

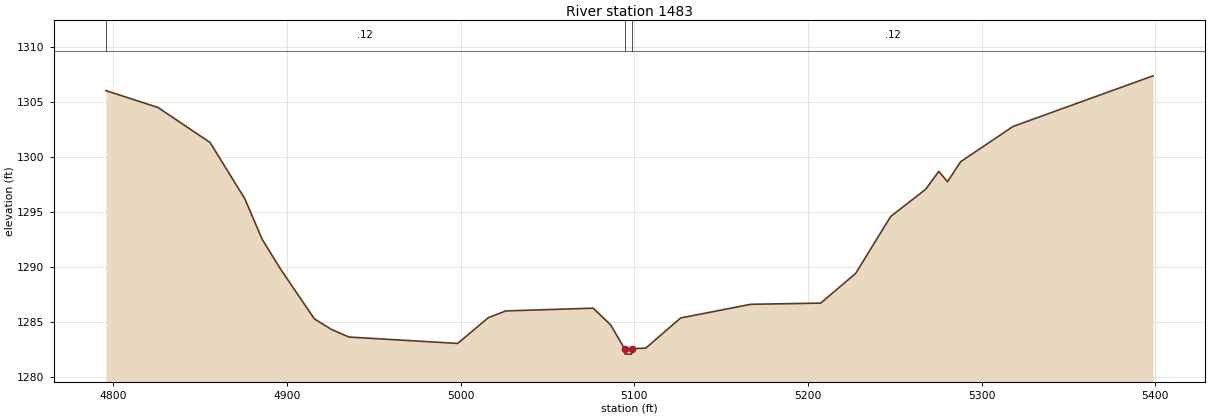
Type RM Length L Ch R = 1,1483,0,0,0
BEGIN DESCRIPTION:
Stream0158_DS 1.0
END DESCRIPTION:
XS GIS Cut Line= 3
      2059324.97     13877275.00      2059525.00     13877275.00
      2059574.99     13876875.05
#Sta/Elev= 30
  4795.7 1306.00  4825.7 1304.47  4855.7 1301.29  4875.7 1296.19  4885.7 1292.51
  4895.7 1289.95  4915.7 1285.30  4925.7 1284.32  4935.7 1283.64  4998.3 1283.06
  5015.9 1285.39  5026.0 1286.01  5076.4 1286.26  5086.4 1284.74  5094.4 1282.59
  5094.7 1282.09  5098.4 1282.09  5098.6 1282.59  5106.6 1282.63  5126.7 1285.37
  5167.1 1286.61  5207.4 1286.72  5227.5 1289.41  5247.7 1294.58  5267.8 1297.04
  5275.4 1298.67  5280.4 1297.73  5288.0 1299.55  5318.2 1302.75  5398.8 1307.34
#Mann=3,-1,0
  4795.7    0.12       0  5094.4    0.05       0  5098.6    0.12       0
Bank Sta=5094.4,5098.6
Exp/Cntr=0.3,0.1

Chan Stop Cuts=-1