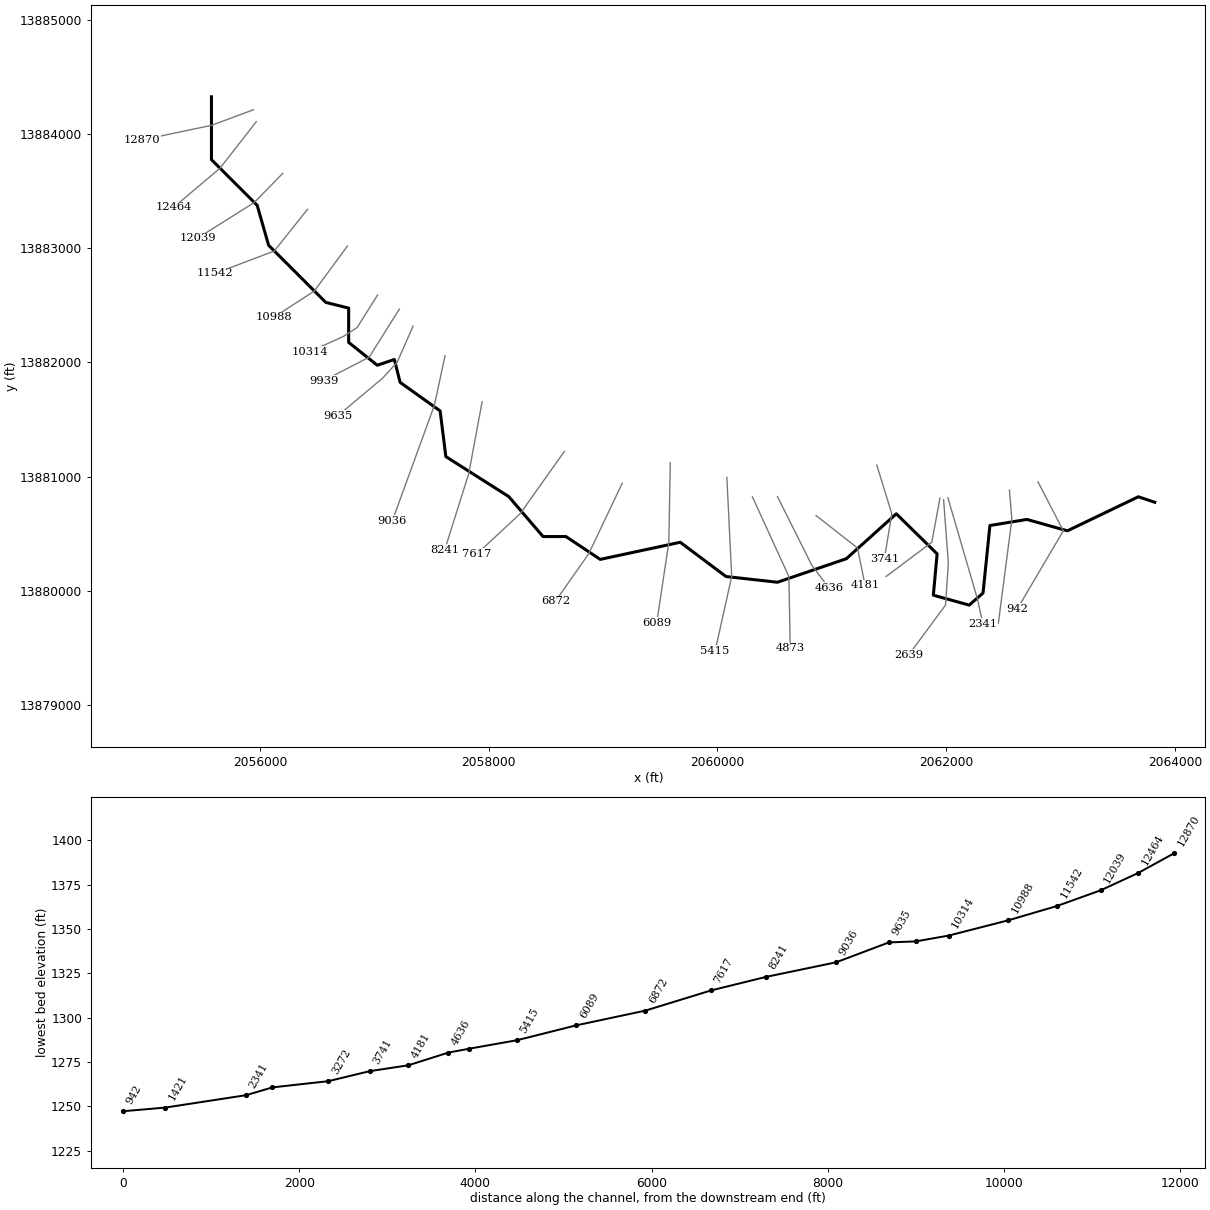
--- Stream0159_DS.prj (project) ---

Proj Title=Stream0159_DS Base Level Engineering
Current Plan=p01
Default Exp/Contr=0.3,0.1
English Units
Geom File=g01
Flow File=f01
Plan File=p01
BEGIN DESCRIPTION:
Stream0159_DS
END DESCRIPTION:

--- Stream0159_DS.p01 (plan) ---

Plan Title=Multiple Run
Short Identifier=Multiple
Geom File=g01
Flow File=f01
Subcritical Flow
K Sum by GR= 0
Std Step Tol= 0.01
Critical Tol= 0.01
Num of Std Step Trials= 20
Max Error Tol= 0.3
Flow Tol Ratio= 0.001
Split Flow NTrial= 30
Split Flow Tol= 0.02
Split Flow Ratio= 0.02
Log Output Level= 0
Friction Slope Method= 1
Unsteady Friction Slope Method= 2
Unsteady Bridges Friction Slope Method= 1
Parabolic Critical Depth
Global Vel Dist=  1 , 1 , 1
Global Log Level= 0
CheckData=True
Encroach Param= -1, 0, 0, 0
BEGIN DESCRIPTION:
Multiple Run
END DESCRIPTION:

--- Stream0159_DS.f01 (steady flow) ---

Flow Title=Multiple
Number of Profiles=7
Profile Names=10-year,25-year,50-year,1pct_min,100-year,1pct_plu,500-year
River Rch & RM= Stream0159_DS,Reach-1,12870
     259     397     517     328     654    1305    1030
River Rch & RM= Stream0159_DS,Reach-1,12039
     694    1136    1543    1017    2030    4050    3469
River Rch & RM= Stream0159_DS,Reach-1,7617
    1217    2050    2838    1903    3797    7576    6720
River Rch & RM= Stream0159_DS,Reach-1,3272
    1289    2172    3009    2017    4024    8030    7120
Boundary for River Rch & Prof#=Stream0159_DS,Reach-1,1
Up Type=0
Dn Type=3
Dn Slope=0.005
Boundary for River Rch & Prof#=Stream0159_DS,Reach-1,2
Up Type=0
Dn Type=3
Dn Slope=0.005
Boundary for River Rch & Prof#=Stream0159_DS,Reach-1,3
Up Type=0
Dn Type=3
Dn Slope=0.005
Boundary for River Rch & Prof#=Stream0159_DS,Reach-1,4
Up Type=0
Dn Type=3
Dn Slope=0.005
Boundary for River Rch & Prof#=Stream0159_DS,Reach-1,5
Up Type=0
Dn Type=3
Dn Slope=0.005
Boundary for River Rch & Prof#=Stream0159_DS,Reach-1,6
Up Type=0
Dn Type=3
Dn Slope=0.005
Boundary for River Rch & Prof#=Stream0159_DS,Reach-1,7
Up Type=0
Dn Type=3
Dn Slope=0.005

--- Stream0159_DS.g01 (geometry) ---

Geom Title=Existing Conditions

River Reach=Stream0159_DS,Reach-1
Reach XY= 30
      2055575.00     13884325.00      2055575.00     13883775.00
      2055975.00     13883375.00      2056075.00     13883025.00
      2056575.00     13882525.00      2056775.00     13882475.00
      2056775.00     13882175.00      2057025.00     13881975.00
      2057175.00     13882025.00      2057225.00     13881825.00
      2057575.00     13881575.00      2057625.00     13881175.00
      2058175.00     13880825.00      2058475.00     13880475.00
      2058675.00     13880475.00      2058975.00     13880275.00
      2059675.00     13880425.00      2060075.00     13880125.00
      2060525.00     13880075.00      2061127.30     13880280.83
      2061564.31     13880674.24      2061921.25     13880323.45
      2061888.52     13879961.59      2062202.36     13879874.80
      2062322.84     13879980.44      2062383.15     13880571.63
      2062706.73     13880624.79      2063060.90     13880525.24
      2063681.10     13880823.23      2063825.00     13880775.00

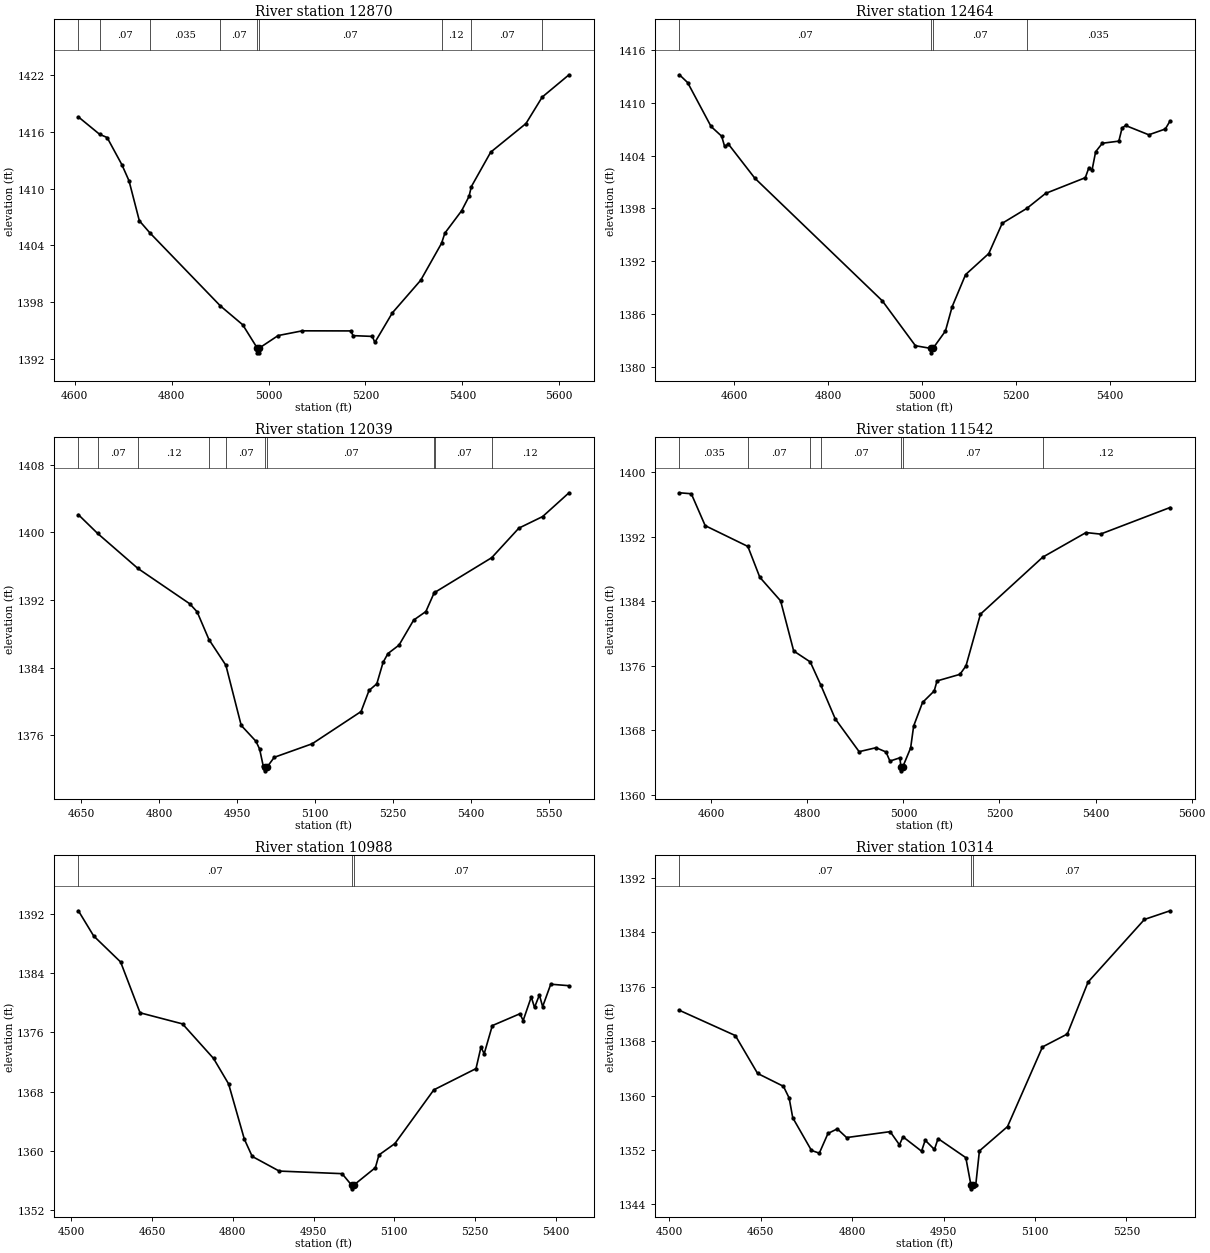
Type RM Length L Ch R = 1,12870,406,406,406
BEGIN DESCRIPTION:
Stream0159_DS 22.0
END DESCRIPTION:
XS GIS Cut Line= 3
      2055942.94     13884211.66      2055575.00     13884075.00
      2054968.13     13883947.59
#Sta/Elev= 30
  4607.5 1417.58  4651.3 1415.74  4666.8 1415.40  4697.2 1412.53  4712.0 1410.82
  4733.3 1406.59  4755.2 1405.30  4900.7 1397.57  4946.7 1395.58  4976.7 1393.11
  4976.9 1392.61  4980.4 1392.61  4980.7 1393.11  5019.8 1394.44  5069.7 1394.94
  5169.5 1394.93  5174.6 1394.43  5214.2 1394.35  5219.4 1393.71  5255.5 1396.84
  5314.0 1400.29  5357.0 1404.20  5363.9 1405.28  5398.5 1407.65  5413.8 1409.17
  5418.5 1410.20  5458.5 1413.85  5531.3 1416.88  5564.8 1419.68  5620.1 1422.04
#Mann=9,-1,0
  4607.5   0.035       0  4651.3    0.07       0  4755.2   0.035       0
  4900.7    0.07       0  4976.7    0.05       0  4980.7    0.07       0
  5357.0    0.12       0  5418.5    0.07       0  5564.8    0.12       0
Bank Sta=4976.7,4980.7
Exp/Cntr=0.3,0.1

Type RM Length L Ch R = 1,12464,425,425,425
BEGIN DESCRIPTION:
Stream0159_DS 21.0
END DESCRIPTION:
XS GIS Cut Line= 3
      2055967.67     13884107.76      2055650.00     13883700.00
      2055246.95     13883359.54
#Sta/Elev= 30
  4483.1 1413.20  4500.6 1412.31  4550.4 1407.32  4573.0 1406.21  4579.3 1405.05
  4587.4 1405.31  4643.5 1401.44  4915.0 1387.48  4985.5 1382.37  5018.8 1382.06
  5019.1 1381.56  5022.8 1382.06  5049.4 1384.04  5063.7 1386.81  5092.3 1390.46
  5141.7 1392.86  5170.3 1396.30  5222.8 1398.00  5262.6 1399.70  5347.2 1401.49
  5354.9 1402.64  5361.5 1402.34  5369.2 1404.44  5383.5 1405.41  5418.6 1405.65
  5425.4 1407.13  5432.9 1407.43  5482.4 1406.37  5517.5 1407.03  5527.6 1407.94
#Mann=4,-1,0
  4483.1    0.07       0  5018.8    0.05       0  5022.8    0.07       0
  5222.8   0.035       0
Bank Sta=5018.8,5022.8
Exp/Cntr=0.3,0.1

Type RM Length L Ch R = 1,12039,497,497,497
BEGIN DESCRIPTION:
Stream0159_DS 20.0
END DESCRIPTION:
XS GIS Cut Line= 3
      2056198.56     13883654.59      2055949.85     13883400.15
      2055452.18     13883086.05
#Sta/Elev= 30
  4644.2 1402.09  4681.3 1399.87  4758.9 1395.73  4858.5 1391.56  4872.7 1390.61
  4895.5 1387.33  4928.1 1384.29  4957.6 1377.18  4985.9 1375.31  4993.0 1374.39
  4999.9 1372.40  5004.0 1372.31  5004.2 1371.81  5008.0 1372.31  5021.2 1373.41
  5094.2 1375.01  5188.3 1378.82  5203.6 1381.31  5218.6 1382.10  5230.7 1384.64
  5240.1 1385.68  5261.3 1386.67  5289.5 1389.63  5313.0 1390.64  5328.8 1392.83
  5330.9 1392.93  5439.8 1397.01  5492.0 1400.50  5537.8 1401.87  5588.5 1404.68
#Mann=10,-1,0
  4644.2   0.035       0  4681.3    0.07       0  4758.9    0.12       0
  4895.5   0.035       0  4928.1    0.07       0  5004.0    0.05       0
  5008.0    0.07       0  5328.8   0.035       0  5330.9    0.07       0
  5439.8    0.12       0
Bank Sta=5004,5008
Exp/Cntr=0.3,0.1

Type RM Length L Ch R = 1,11542,554,554,554
BEGIN DESCRIPTION:
Stream0159_DS 19.0
END DESCRIPTION:
XS GIS Cut Line= 3
      2056414.90     13883339.98      2056125.00     13882975.00
      2055606.09     13882778.13
#Sta/Elev= 30
  4533.9 1397.47  4558.6 1397.35  4587.5 1393.39  4676.3 1390.81  4701.2 1386.98
  4744.5 1384.05  4771.7 1377.83  4806.2 1376.47  4828.4 1373.56  4858.2 1369.40
  4907.9 1365.33  4943.1 1365.82  4963.9 1365.29  4972.0 1364.16  4992.8 1364.57
  4994.8 1363.45  4995.1 1362.95  4998.8 1363.45  5015.1 1365.79  5021.4 1368.52
  5039.9 1371.44  5064.2 1372.87  5070.0 1374.11  5117.7 1374.93  5130.3 1375.98
  5160.4 1382.40  5290.1 1389.48  5380.1 1392.53  5410.3 1392.34  5555.0 1395.64
#Mann=7,-1,0
  4533.9   0.035       0  4676.3    0.07       0  4806.2   0.035       0
  4828.4    0.07       0  4994.8    0.05       0  4998.8    0.07       0
  5290.1    0.12       0
Bank Sta=4994.8,4998.8
Exp/Cntr=0.3,0.1

Type RM Length L Ch R = 1,10988,674,674,674
BEGIN DESCRIPTION:
Stream0159_DS 18.0
END DESCRIPTION:
XS GIS Cut Line= 3
      2056763.51     13883017.34      2056475.00     13882625.00
      2056119.22     13882393.07
#Sta/Elev= 30
  4513.0 1392.43  4541.4 1389.03  4591.5 1385.51  4627.6 1378.65  4706.5 1377.15
  4764.2 1372.48  4792.1 1369.05  4821.4 1361.58  4836.0 1359.25  4886.2 1357.27
  5003.0 1356.92  5020.7 1355.37  5020.9 1354.87  5024.7 1355.37  5064.9 1357.73
  5071.6 1359.45  5101.1 1360.98  5173.5 1368.24  5251.9 1371.11  5261.1 1374.01
  5267.1 1373.12  5282.2 1376.92  5333.5 1378.52  5339.5 1377.60  5354.6 1380.79
  5360.6 1379.37  5369.7 1381.06  5375.7 1379.48  5390.8 1382.51  5424.7 1382.31
#Mann=3,-1,0
  4513.0    0.07       0  5020.7    0.05       0  5024.7    0.07       0
Bank Sta=5020.7,5024.7
Exp/Cntr=0.3,0.1

Type RM Length L Ch R = 1,10314,375,375,375
BEGIN DESCRIPTION:
Stream0159_DS 17.0
END DESCRIPTION:
XS GIS Cut Line= 4
      2057027.67     13882589.49      2056849.08     13882304.79
      2056725.00     13882225.00      2056431.76     13882092.70
#Sta/Elev= 30
  4516.4 1372.52  4608.2 1368.81  4644.7 1363.25  4687.1 1361.36  4696.5 1359.64
  4702.4 1356.74  4733.1 1351.94  4746.0 1351.54  4760.2 1354.43  4775.5 1355.11
  4790.8 1353.83  4862.3 1354.70  4877.5 1352.77  4883.4 1353.94  4913.8 1351.83
  4919.8 1353.44  4935.0 1352.08  4940.9 1353.68  4986.5 1350.88  4995.0 1346.80
  4995.3 1346.30  4999.0 1346.80  5002.7 1346.80  5008.8 1351.87  5054.9 1355.44
  5112.3 1367.14  5153.1 1369.04  5187.2 1376.68  5279.7 1385.87  5321.7 1387.14
#Mann=3,-1,0
  4516.4    0.07       0  4995.0    0.05       0  4999.0    0.07       0
Bank Sta=4995,4999
Exp/Cntr=0.3,0.1

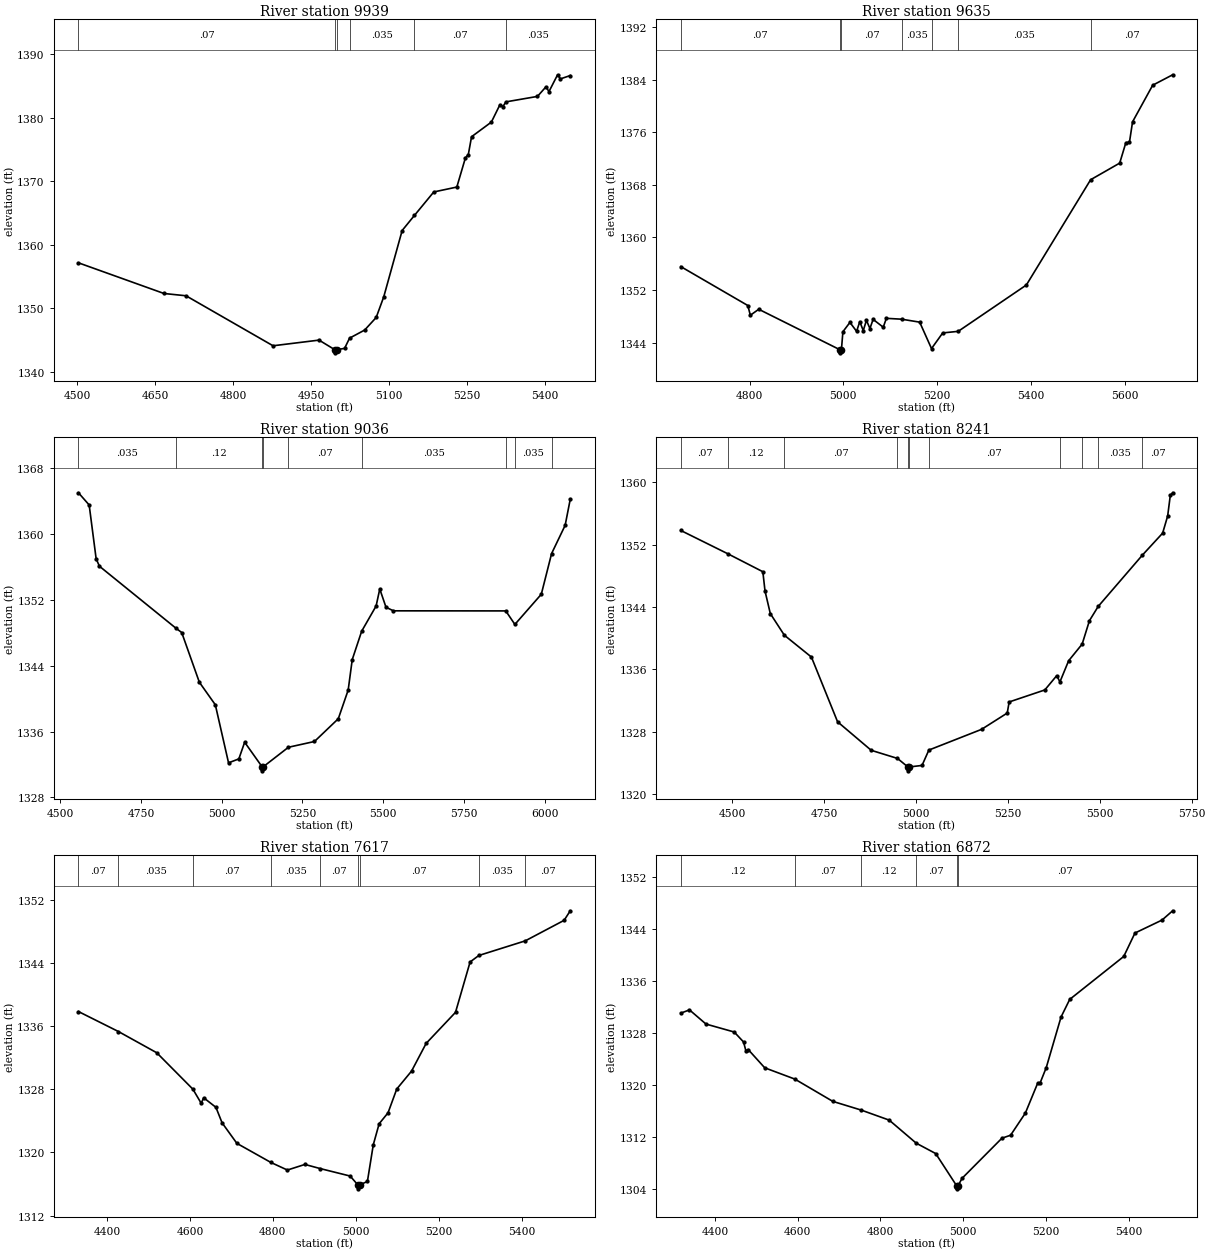
Type RM Length L Ch R = 1,9939,304,304,304
BEGIN DESCRIPTION:
Stream0159_DS 16.0
END DESCRIPTION:
XS GIS Cut Line= 3
      2057218.91     13882466.80      2056954.49     13882045.51
      2056556.44     13881839.72
#Sta/Elev= 30
  4502.6 1357.17  4667.0 1352.35  4709.4 1351.99  4876.7 1344.13  4965.1 1345.02
  4995.3 1343.52  4995.6 1343.02  4999.3 1343.52  5014.2 1343.72  5023.8 1345.33
  5052.8 1346.60  5075.0 1348.58  5089.5 1351.82  5124.9 1362.25  5148.6 1364.63
  5185.7 1368.31  5230.0 1369.08  5246.5 1373.67  5252.1 1374.19  5258.3 1376.99
  5296.4 1379.29  5312.9 1382.03  5318.6 1381.73  5324.3 1382.47  5385.0 1383.33
  5401.5 1384.85  5407.1 1384.08  5423.7 1386.73  5429.3 1386.09  5448.1 1386.61
#Mann=6,-1,0
  4502.6    0.07       0  4995.3    0.05       0  4999.3    0.07       0
  5023.8   0.035       0  5148.6    0.07       0  5324.3   0.035       0
Bank Sta=4995.3,4999.3
Exp/Cntr=0.3,0.1

Type RM Length L Ch R = 1,9635,599,599,599
BEGIN DESCRIPTION:
Stream0159_DS 15.0
END DESCRIPTION:
XS GIS Cut Line= 4
      2057338.77     13882317.81      2057199.26     13882000.74
      2057072.11     13881861.55      2056678.52     13881531.63
#Sta/Elev= 30
  4653.6 1355.56  4796.4 1349.64  4801.8 1348.16  4819.7 1349.07  4992.0 1342.94
  4992.3 1342.44  4996.0 1342.94  4999.1 1345.65  5014.1 1347.07  5028.3 1345.71
  5035.1 1347.19  5042.5 1345.82  5049.3 1347.39  5056.7 1346.14  5063.5 1347.53
  5085.1 1346.34  5091.8 1347.69  5124.2 1347.56  5162.8 1347.11  5188.0 1343.09
  5211.9 1345.47  5244.9 1345.71  5390.2 1352.76  5527.2 1368.78  5589.2 1371.31
  5602.3 1374.42  5610.0 1374.49  5616.6 1377.59  5659.5 1383.16  5702.1 1384.75
#Mann=7,-1,0
  4653.6    0.07       0  4992.0    0.05       0  4996.0    0.07       0
  5124.2   0.035       0  5188.0    0.07       0  5244.9   0.035       0
  5527.2    0.07       0
Bank Sta=4992,4996
Exp/Cntr=0.3,0.1

Type RM Length L Ch R = 1,9036,795,795,795
BEGIN DESCRIPTION:
Stream0159_DS 14.0
END DESCRIPTION:
XS GIS Cut Line= 3
      2057617.76     13882058.59      2057525.00     13881625.00
      2057156.18     13880610.67
#Sta/Elev= 30
  4556.6 1364.96  4589.8 1363.48  4611.4 1356.95  4621.6 1356.05  4859.4 1348.50
  4876.3 1348.01  4930.9 1341.98  4980.4 1339.24  5021.3 1332.20  5053.2 1332.68
  5071.2 1334.70  5125.0 1331.73  5125.3 1331.23  5129.0 1331.73  5206.7 1334.09
  5287.3 1334.79  5361.1 1337.55  5391.7 1341.03  5404.3 1344.73  5433.5 1348.17
  5478.2 1351.23  5489.5 1353.29  5508.8 1351.07  5532.0 1350.64  5879.6 1350.63
  5907.8 1348.99  5989.6 1352.65  6021.5 1357.59  6063.4 1361.01  6079.3 1364.19
#Mann=9,-1,0
  4556.6   0.035       0  4859.4    0.12       0  5125.0    0.05       0
  5129.0    0.12       0  5206.7    0.07       0  5433.5   0.035       0
  5879.6    0.07       0  5907.8   0.035       0  6021.5    0.07       0
Bank Sta=5125,5129
Exp/Cntr=0.3,0.1

Type RM Length L Ch R = 1,8241,624,624,624
BEGIN DESCRIPTION:
Stream0159_DS 13.0
END DESCRIPTION:
XS GIS Cut Line= 3
      2057942.04     13881654.41      2057825.00     13881025.00
      2057615.32     13880358.92
#Sta/Elev= 30
  4359.8 1353.80  4488.9 1350.79  4583.0 1348.52  4588.9 1346.05  4603.3 1343.16
  4641.5 1340.39  4715.2 1337.59  4786.4 1329.30  4877.9 1325.65  4949.4 1324.61
  4977.7 1323.52  4977.9 1323.02  4981.7 1323.52  5016.2 1323.71  5034.8 1325.68
  5178.1 1328.33  5248.1 1330.42  5253.3 1331.84  5350.4 1333.38  5382.8 1335.21
  5391.5 1334.41  5415.2 1337.12  5452.0 1339.25  5471.8 1342.25  5495.7 1344.08
  5616.0 1350.65  5671.0 1353.46  5684.7 1355.66  5691.9 1358.31  5698.3 1358.63
#Mann=11,-1,0
  4359.8    0.07       0  4488.9    0.12       0  4641.5    0.07       0
  4949.4   0.035       0  4977.7   0.035       0  4981.7   0.035       0
  5034.8    0.07       0  5391.5   0.035       0  5452.0    0.07       0
  5495.7   0.035       0  5616.0    0.07       0
Bank Sta=4977.7,4981.7
Exp/Cntr=0.3,0.1

Type RM Length L Ch R = 1,7617,745,745,745
BEGIN DESCRIPTION:
Stream0159_DS 12.0
END DESCRIPTION:
XS GIS Cut Line= 3
      2058661.68     13881220.69      2058275.00     13880675.00
      2057896.02     13880322.75
#Sta/Elev= 30
  4331.2 1337.84  4427.6 1335.31  4520.1 1332.62  4607.2 1328.01  4627.2 1326.23
  4633.3 1326.92  4662.8 1325.71  4677.6 1323.75  4713.3 1321.15  4795.4 1318.73
  4835.1 1317.77  4877.4 1318.48  4914.7 1317.95  4986.5 1317.01  5005.1 1315.89
  5005.3 1315.39  5009.1 1315.89  5028.1 1316.32  5042.3 1320.97  5056.4 1323.63
  5077.9 1325.02  5098.9 1328.03  5134.6 1330.30  5169.8 1333.81  5240.6 1337.74
  5275.8 1344.12  5296.9 1344.94  5408.8 1346.79  5502.5 1349.39  5517.4 1350.60
#Mann=9,-1,0
  4331.2    0.07       0  4427.6   0.035       0  4607.2    0.07       0
  4795.4   0.035       0  4914.7    0.07       0  5005.1    0.05       0
  5009.1    0.07       0  5296.9   0.035       0  5408.8    0.07       0
Bank Sta=5005.1,5009.1
Exp/Cntr=0.3,0.1

Type RM Length L Ch R = 1,6872,783,783,783
BEGIN DESCRIPTION:
Stream0159_DS 11.0
END DESCRIPTION:
XS GIS Cut Line= 3
      2059167.44     13880942.12      2058875.00     13880325.00
      2058584.46     13879909.87
#Sta/Elev= 30
  4317.1 1331.02  4338.0 1331.52  4378.0 1329.34  4446.2 1328.12  4468.8 1326.59
  4474.5 1325.22  4480.0 1325.43  4520.0 1322.62  4592.7 1320.89  4684.7 1317.46
  4753.5 1316.12  4821.1 1314.58  4886.4 1311.04  4933.6 1309.44  4983.9 1304.52
  4984.1 1304.02  4987.9 1304.52  4997.2 1305.63  5093.7 1311.80  5114.7 1312.26
  5150.4 1315.66  5180.1 1320.24  5186.2 1320.31  5201.0 1322.66  5236.7 1330.42
  5257.7 1333.13  5388.4 1339.73  5415.5 1343.33  5480.9 1345.32  5506.7 1346.75
#Mann=6,-1,0
  4317.1    0.12       0  4592.7    0.07       0  4753.5    0.12       0
  4886.4    0.07       0  4983.9    0.05       0  4987.9    0.07       0
Bank Sta=4983.9,4987.9
Exp/Cntr=0.3,0.1

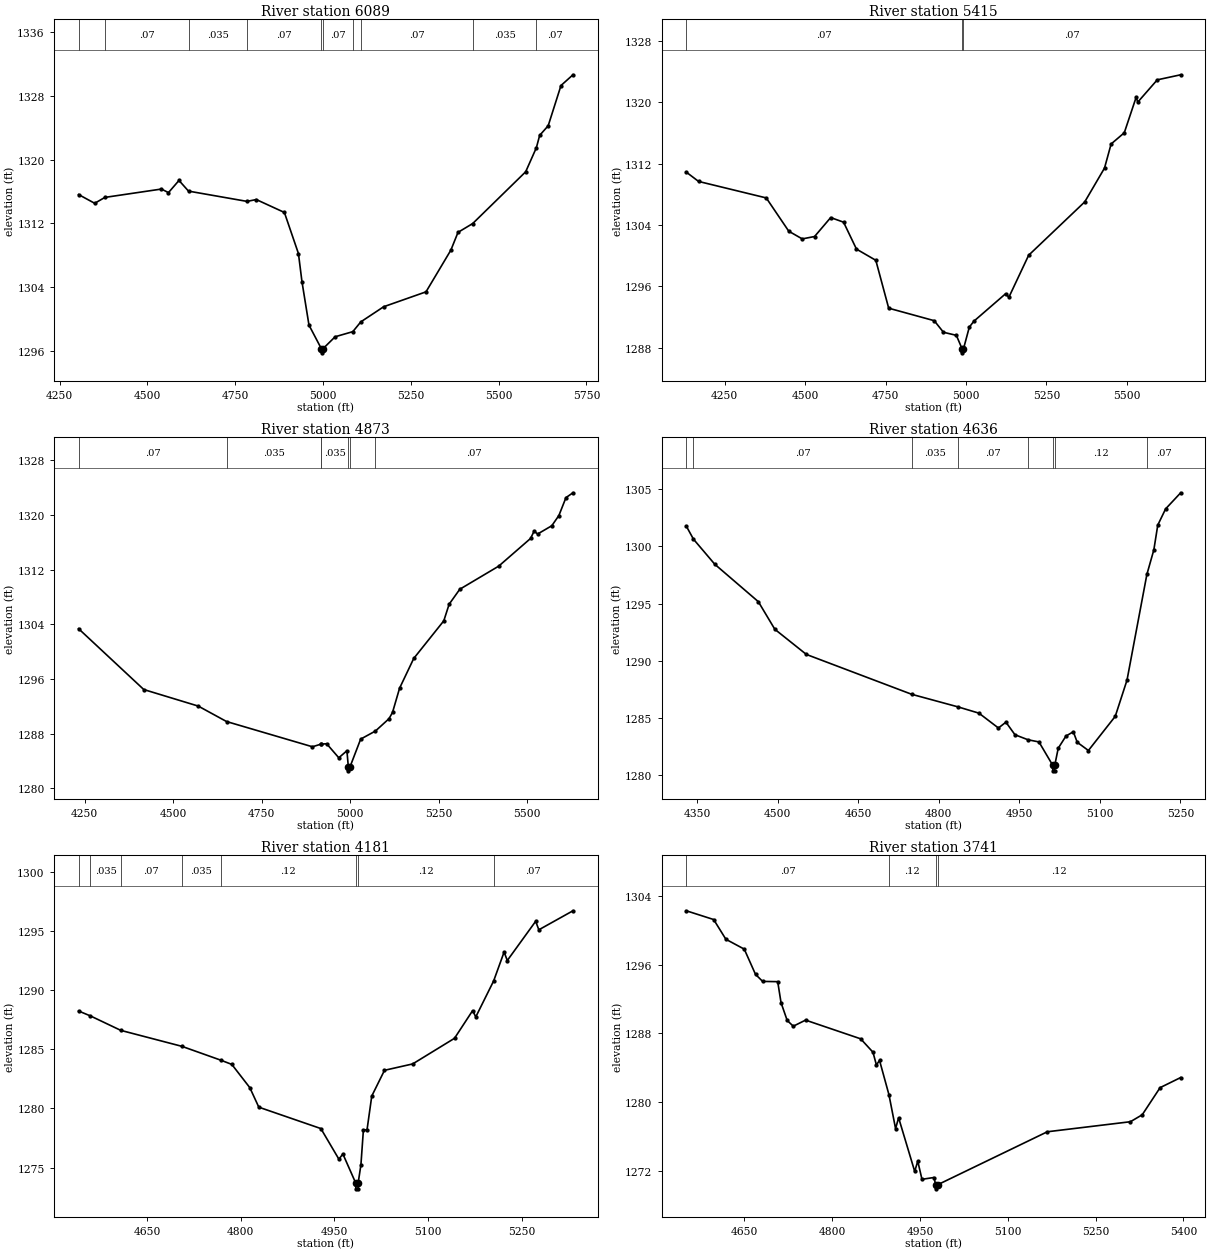
Type RM Length L Ch R = 1,6089,674,674,674
BEGIN DESCRIPTION:
Stream0159_DS 10.0
END DESCRIPTION:
XS GIS Cut Line= 3
      2059587.92     13881120.88      2059575.00     13880425.00
      2059469.37     13879721.28
#Sta/Elev= 30
  4304.0 1315.61  4349.9 1314.51  4378.9 1315.25  4539.9 1316.30  4559.9 1315.85
  4589.9 1317.38  4617.0 1316.04  4783.5 1314.75  4810.0 1314.98  4890.0 1313.36
  4930.0 1308.20  4940.0 1304.68  4960.0 1299.21  4995.5 1296.23  4995.7 1295.73
  4999.5 1296.23  5034.5 1297.75  5084.8 1298.39  5107.6 1299.62  5172.7 1301.52
  5293.2 1303.39  5364.0 1308.63  5384.3 1310.86  5426.2 1311.97  5577.0 1318.47
  5607.5 1321.50  5616.8 1323.04  5641.1 1324.25  5677.5 1329.30  5711.6 1330.65
#Mann=10,-1,0
  4304.0   0.035       0  4378.9    0.07       0  4617.0   0.035       0
  4783.5    0.07       0  4995.5    0.05       0  4999.5    0.07       0
  5084.8   0.035       0  5107.6    0.07       0  5426.2   0.035       0
  5607.5    0.07       0
Bank Sta=4995.5,4999.5
Exp/Cntr=0.3,0.1

Type RM Length L Ch R = 1,5415,542,542,542
BEGIN DESCRIPTION:
Stream0159_DS 9.0
END DESCRIPTION:
XS GIS Cut Line= 3
      2060082.58     13880993.06      2060125.00     13880125.00
      2059980.17     13879473.91
#Sta/Elev= 30
  4130.9 1310.89  4169.0 1309.68  4379.3 1307.53  4449.3 1303.19  4491.1 1302.19
  4529.4 1302.50  4579.5 1304.97  4619.5 1304.37  4659.6 1300.86  4719.7 1299.40
  4759.7 1293.16  4901.2 1291.53  4929.9 1290.02  4970.0 1289.62  4988.0 1287.84
  4988.2 1287.34  4992.0 1287.84  5010.2 1290.69  5024.3 1291.46  5122.9 1295.04
  5133.2 1294.59  5194.6 1300.06  5368.8 1307.01  5430.3 1311.42  5450.8 1314.56
  5491.7 1316.02  5528.6 1320.65  5533.7 1320.02  5594.2 1322.92  5667.0 1323.58
#Mann=3,-1,0
  4130.9    0.07       0  4988.0    0.05       0  4992.0    0.07       0
Bank Sta=4988,4992
Exp/Cntr=0.3,0.1

Type RM Length L Ch R = 1,4873,237,237,237
BEGIN DESCRIPTION:
Stream0159_DS 8.0
END DESCRIPTION:
XS GIS Cut Line= 3
      2060305.89     13880822.57      2060625.00     13880125.00
      2060636.90     13879495.21
#Sta/Elev= 30
  4232.9 1303.35  4417.2 1294.45  4571.1 1292.03  4651.1 1289.77  4893.7 1286.08
  4917.6 1286.46  4917.9 1286.47  4934.0 1286.52  4968.2 1284.47  4991.2 1285.50
  4995.3 1283.06  4995.5 1282.56  4999.3 1283.06  5030.0 1287.20  5071.7 1288.38
  5110.0 1290.18  5120.0 1291.10  5140.0 1294.65  5180.0 1299.00  5264.9 1304.50
  5280.0 1306.93  5310.1 1309.12  5420.1 1312.50  5510.1 1316.55  5520.1 1317.62
  5530.1 1317.20  5570.1 1318.41  5590.1 1319.90  5610.1 1322.52  5629.9 1323.23
#Mann=7,-1,0
  4232.9    0.07       0  4651.1   0.035       0  4917.6    0.07       0
  4917.9   0.035       0  4995.3   0.035       0  4999.3   0.035       0
  5071.7    0.07       0
Bank Sta=4995.3,4999.3
Exp/Cntr=0.3,0.1

Type RM Length L Ch R = 1,4636,455,455,455
BEGIN DESCRIPTION:
Stream0159_DS 7.0
END DESCRIPTION:
XS GIS Cut Line= 3
      2060525.01     13880824.97      2060825.00     13880225.00
      2060975.01     13880024.99
#Sta/Elev= 30
  4329.7 1301.78  4343.0 1300.64  4382.8 1298.44  4463.8 1295.17  4494.6 1292.75
  4553.3 1290.55  4749.5 1287.06  4835.6 1285.96  4874.7 1285.41  4911.0 1284.11
  4925.0 1284.62  4941.8 1283.52  4966.1 1283.08  4986.5 1282.89  5012.0 1280.86
  5012.3 1280.36  5015.8 1280.36  5016.0 1280.86  5022.4 1282.34  5036.9 1283.41
  5050.5 1283.78  5057.8 1282.86  5078.6 1282.14  5128.6 1285.13  5150.5 1288.30
  5187.5 1297.55  5200.5 1299.71  5207.8 1301.87  5222.4 1303.29  5250.5 1304.70
#Mann=8,-1,0
  4329.7   0.035       0  4343.0    0.07       0  4749.5   0.035       0
  4835.6    0.07       0  4966.1    0.12       0  5012.0    0.05       0
  5016.0    0.12       0  5187.5    0.07       0
Bank Sta=5012,5016
Exp/Cntr=0.3,0.1

Type RM Length L Ch R = 1,4181,440,440,440
BEGIN DESCRIPTION:
Stream0159_DS 6.0
END DESCRIPTION:
XS GIS Cut Line= 3
      2060862.97     13880658.64      2061225.00     13880375.00
      2061291.45     13880048.91
#Sta/Elev= 30
  4539.8 1288.25  4558.9 1287.83  4607.5 1286.61  4705.4 1285.26  4767.7 1284.09
  4785.5 1283.73  4814.4 1281.76  4828.8 1280.11  4928.3 1278.30  4957.2 1275.71
  4963.6 1276.15  4984.1 1273.70  4984.4 1273.20  4987.9 1273.20  4988.1 1273.70
  4992.5 1275.22  4996.5 1278.19  5002.3 1278.19  5009.9 1281.05  5030.3 1283.23
  5075.5 1283.77  5142.6 1285.94  5171.6 1288.28  5176.7 1287.75  5205.3 1290.79
  5222.1 1293.24  5227.2 1292.52  5272.7 1295.84  5277.8 1295.12  5332.5 1296.73
#Mann=8,-1,0
  4539.8    0.07       0  4558.9   0.035       0  4607.5    0.07       0
  4705.4   0.035       0  4767.7    0.12       0  4984.1    0.05       0
  4988.1    0.12       0  5205.3    0.07       0
Bank Sta=4984.1,4988.1
Exp/Cntr=0.3,0.1

Type RM Length L Ch R = 1,3741,469,469,469
BEGIN DESCRIPTION:
Stream0159_DS 5.0
END DESCRIPTION:
XS GIS Cut Line= 3
      2061394.19     13881099.64      2061525.00     13880675.00
      2061460.17     13880280.22
#Sta/Elev= 30
  4551.0 1302.28  4597.7 1301.26  4618.6 1298.96  4650.0 1297.81  4669.2 1294.87
  4681.4 1294.05  4707.1 1294.02  4712.8 1291.57  4723.3 1289.50  4733.7 1288.83
  4754.7 1289.54  4848.8 1287.36  4869.8 1285.80  4875.7 1284.31  4881.0 1284.85
  4897.1 1280.85  4908.4 1276.90  4913.6 1278.16  4941.1 1271.91  4946.3 1273.11
  4953.5 1270.99  4973.8 1271.20  4977.0 1270.38  4977.2 1269.88  4981.0 1270.38
  5167.6 1276.53  5309.5 1277.70  5329.7 1278.51  5360.2 1281.67  5395.4 1282.85
#Mann=4,-1,0
  4551.0    0.07       0  4897.1    0.12       0  4977.0    0.05       0
  4981.0    0.12       0
Bank Sta=4977,4981
Exp/Cntr=0.3,0.1

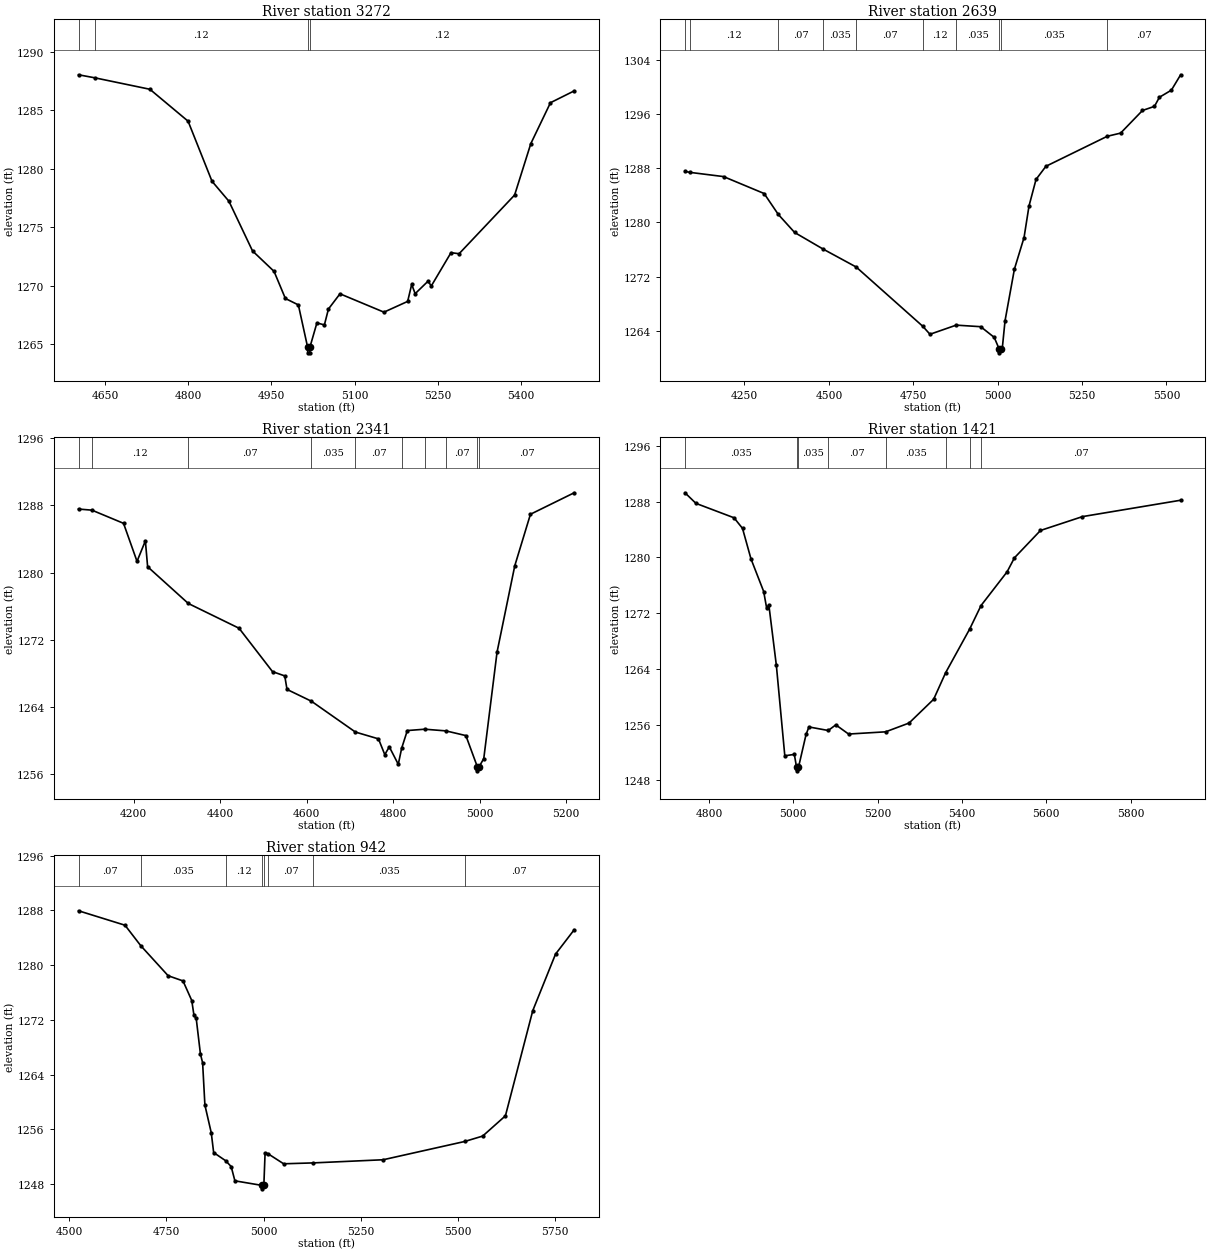
Type RM Length L Ch R = 1,3272,633,633,633
BEGIN DESCRIPTION:
Stream0159_DS 4.0
END DESCRIPTION:
XS GIS Cut Line= 3
      2061946.28     13880811.49      2061875.00     13880425.00
      2061475.01     13880125.00
#Sta/Elev= 30
  4602.5 1288.03  4631.9 1287.77  4731.1 1286.79  4799.9 1284.06  4843.0 1278.92
  4873.5 1277.21  4916.0 1272.96  4954.8 1271.21  4975.2 1268.89  4998.6 1268.34
  5015.2 1264.74  5015.5 1264.24  5019.2 1264.24  5019.5 1264.74  5032.0 1266.80
  5045.5 1266.63  5052.8 1267.99  5073.6 1269.29  5152.8 1267.72  5195.5 1268.64
  5202.8 1270.10  5209.0 1269.30  5232.0 1270.36  5238.2 1269.97  5273.6 1272.81
  5288.2 1272.72  5388.2 1277.74  5417.4 1282.14  5452.8 1285.64  5495.5 1286.65
#Mann=4,-1,0
  4602.5    0.07       0  4631.9    0.12       0  5015.2    0.05       0
  5019.5    0.12       0
Bank Sta=5015.2,5019.5
Exp/Cntr=0.3,0.1

Type RM Length L Ch R = 1,2639,298,298,298
BEGIN DESCRIPTION:
Stream0159_DS 3.5
END DESCRIPTION:
XS GIS Cut Line= 4
      2061978.10     13880798.89      2062019.60     13880242.53
      2061994.97     13879874.96      2061673.11     13879438.75
#Sta/Elev= 30
  4073.7 1287.54  4088.8 1287.39  4187.9 1286.77  4308.2 1284.27  4350.2 1281.18
  4398.5 1278.52  4482.5 1276.08  4580.9 1273.42  4778.4 1264.66  4799.5 1263.49
  4877.2 1264.84  4949.8 1264.61  4989.9 1263.03  5005.1 1261.25  5005.4 1260.75
  5009.5 1261.25  5013.5 1261.29  5021.9 1265.49  5049.7 1273.12  5078.2 1277.77
  5092.9 1282.43  5113.7 1286.35  5143.0 1288.29  5324.7 1292.72  5364.3 1293.19
  5429.1 1296.53  5464.6 1297.14  5479.2 1298.48  5514.7 1299.53  5542.1 1301.80
#Mann=10,-1,0
  4073.7    0.07       0  4088.8    0.12       0  4350.2    0.07       0
  4482.5   0.035       0  4580.9    0.07       0  4778.4    0.12       0
  4877.2   0.035       0  5005.1   0.035       0  5009.5   0.035       0
  5324.7    0.07       0
Bank Sta=5005.1,5009.5
Exp/Cntr=0.3,0.1

Type RM Length L Ch R = 1,2341,920,920,920
BEGIN DESCRIPTION:
Stream0159_DS 3.0
END DESCRIPTION:
XS GIS Cut Line= 3
      2062015.72     13880814.91      2062275.00     13879925.00
      2062321.27     13879710.76
#Sta/Elev= 30
  4072.5 1287.56  4103.5 1287.43  4176.6 1285.86  4207.8 1281.33  4227.1 1283.77
  4232.3 1280.69  4326.4 1276.31  4443.7 1273.36  4521.1 1268.19  4549.4 1267.68
  4554.6 1266.07  4611.2 1264.66  4712.8 1260.99  4766.1 1260.18  4780.7 1258.30
  4791.1 1259.23  4811.9 1257.15  4819.7 1259.06  4832.8 1261.17  4873.1 1261.33
  4922.1 1261.13  4968.2 1260.57  4994.6 1256.87  4994.9 1256.37  4999.0 1256.87
  5009.6 1257.84  5040.3 1270.52  5081.3 1280.81  5117.5 1286.94  5218.6 1289.50
#Mann=10,-1,0
  4072.5    0.07       0  4103.5    0.12       0  4326.4    0.07       0
  4611.2   0.035       0  4712.8    0.07       0  4819.7   0.035       0
  4873.1    0.12       0  4922.1    0.07       0  4994.6    0.05       0
  4999.0    0.07       0
Bank Sta=4994.6,4999
Exp/Cntr=0.3,0.1

Type RM Length L Ch R = 1,1421,479,479,479
BEGIN DESCRIPTION:
Stream0159_DS 2.0
END DESCRIPTION:
XS GIS Cut Line= 3
      2062553.91     13880880.93      2062575.00     13880625.00
      2062456.70     13879714.25
#Sta/Elev= 30
  4743.3 1289.27  4769.3 1287.75  4859.6 1285.68  4879.7 1284.16  4899.8 1279.78
  4929.9 1275.10  4937.0 1272.70  4942.1 1273.20  4960.0 1264.48  4980.0 1251.52
  5002.6 1251.72  5007.9 1249.86  5008.2 1249.36  5012.4 1249.86  5030.4 1254.58
  5037.2 1255.66  5083.0 1255.15  5100.9 1255.96  5131.2 1254.64  5219.1 1254.96
  5274.6 1256.22  5332.9 1259.63  5361.2 1263.43  5418.3 1269.71  5445.3 1273.09
  5507.0 1277.92  5524.5 1279.94  5586.2 1283.86  5685.8 1285.85  5918.5 1288.20
#Mann=8,-1,0
  4743.3   0.035       0  5007.9   0.035       0  5012.4   0.035       0
  5083.0    0.07       0  5219.1   0.035       0  5361.2    0.07       0
  5418.3    0.12       0  5445.3    0.07       0
Bank Sta=5007.9,5012.4
Exp/Cntr=0.3,0.1

Type RM Length L Ch R = 1,942,0,0,0
BEGIN DESCRIPTION:
Stream0159_DS 1.0
END DESCRIPTION:
XS GIS Cut Line= 3
      2062803.93     13880953.77      2063025.00     13880525.00
      2062623.38     13879842.73
#Sta/Elev= 30
  4524.3 1287.94  4643.8 1285.83  4684.3 1282.84  4754.7 1278.45  4792.9 1277.69
  4815.4 1274.83  4821.1 1272.65  4826.8 1272.24  4837.7 1267.01  4843.3 1265.73
  4849.2 1259.54  4865.5 1255.51  4871.7 1252.61  4902.2 1251.43  4916.7 1250.57
  4926.3 1248.48  4996.2 1247.81  4996.5 1247.31  5000.7 1247.81  5003.9 1252.56
  5011.4 1252.44  5051.6 1250.97  5127.7 1251.10  5307.4 1251.56  5517.0 1254.23
  5563.2 1255.02  5621.7 1257.98  5692.0 1273.35  5750.5 1281.61  5798.4 1285.16
#Mann=8,-1,0
  4524.3    0.07       0  4684.3   0.035       0  4902.2    0.12       0
  4996.2    0.05       0  5000.7    0.12       0  5011.4    0.07       0
  5127.7   0.035       0  5517.0    0.07       0
Bank Sta=4996.2,5000.7
Exp/Cntr=0.3,0.1

Chan Stop Cuts=-1