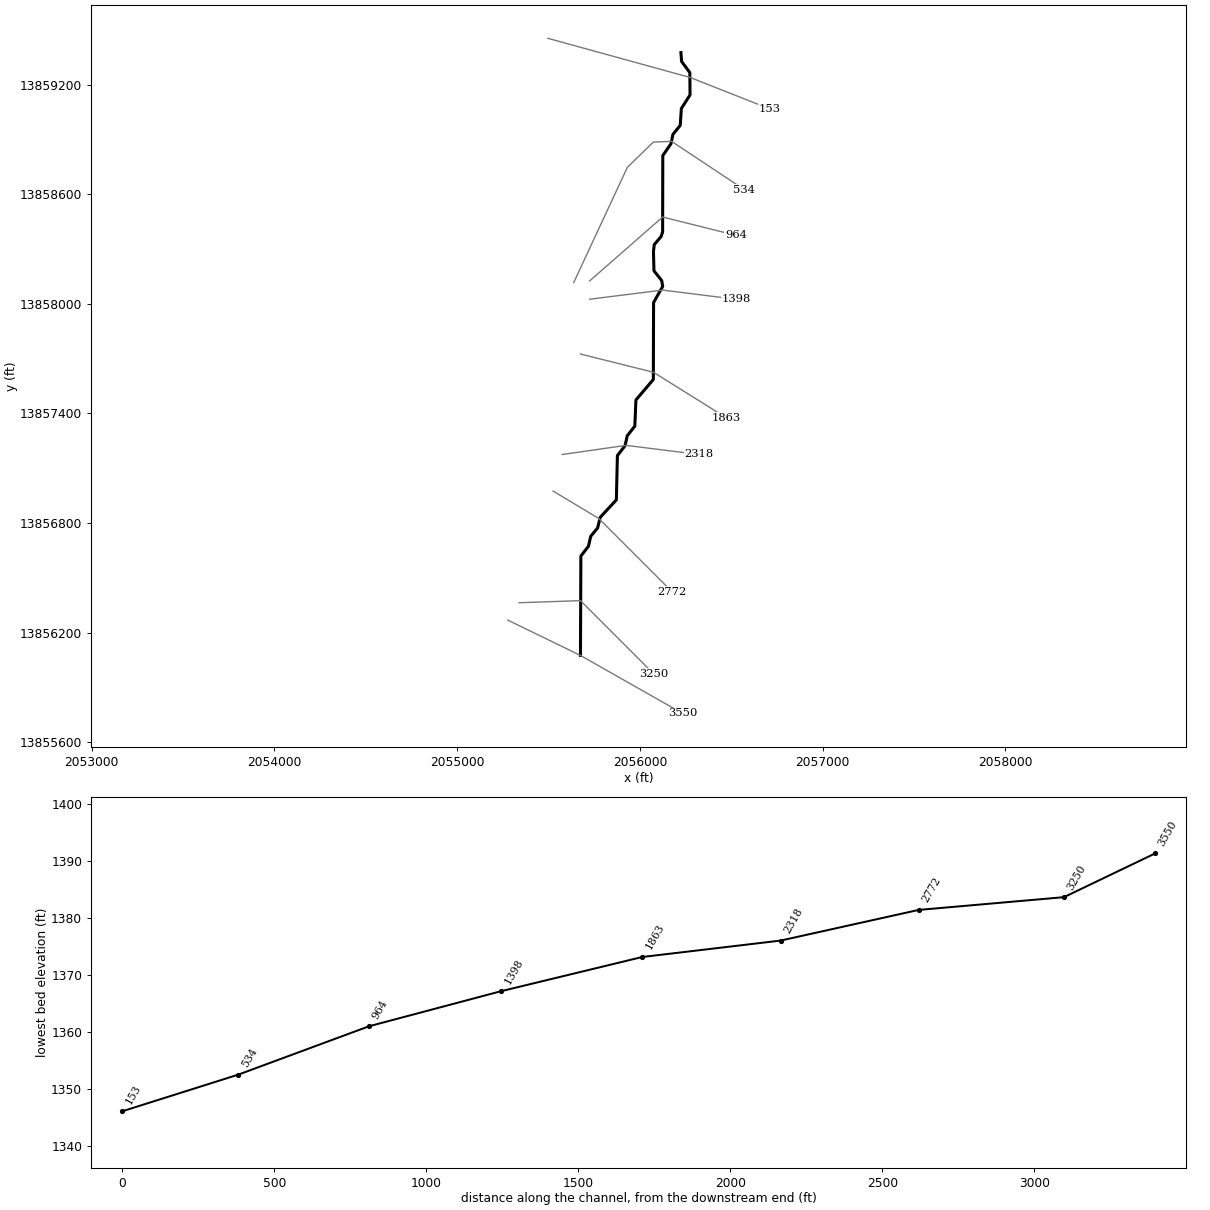
--- Stream0160_DS.prj (project) ---

Proj Title=Stream0160_DS Base Level Engineering
Current Plan=p01
Default Exp/Contr=0.3,0.1
English Units
Geom File=g01
Flow File=f01
Plan File=p01
Y Axis Title=Elevation
X Axis Title(PF)=Main Channel Distance
X Axis Title(XS)=Station
BEGIN DESCRIPTION:
Stream0160_DS
END DESCRIPTION:
DSS Export Rating Curves= 0
DSS Export Rating Curve Sorted= 0
DSS Export Volume Flow Curves= 0
DXF OffsetX= 0
DXF OffsetY= 0
DXF ScaleX= 1
DXF ScaleY= 10

--- Stream0160_DS.p01 (plan) ---

Plan Title=Multiple Run
Short Identifier=Multiple
Geom File=g01
Flow File=f01
Subcritical Flow
K Sum by GR= 0
Std Step Tol= 0.01
Critical Tol= 0.01
Num of Std Step Trials= 20
Max Error Tol= 0.3
Flow Tol Ratio= 0.001
Split Flow NTrial= 30
Split Flow Tol= 0.02
Split Flow Ratio= 0.02
Log Output Level= 0
Friction Slope Method= 1
Unsteady Friction Slope Method= 2
Unsteady Bridges Friction Slope Method= 1
Parabolic Critical Depth
Global Vel Dist=  1 , 1 , 1
Global Log Level= 0
CheckData=True
Encroach Param= -1, 0, 0, 0
BEGIN DESCRIPTION:
Multiple Run
END DESCRIPTION:

--- Stream0160_DS.f01 (steady flow) ---

Flow Title=Multiple
Number of Profiles=7
Profile Names=10-year,25-year,50-year,1pct_min,100-year,1pct_plu,500-year
River Rch & RM= Stream0160_DS,Reach-1,3550
    1455    2511    3536    2414    4816    9610    8833
River Rch & RM= Stream0160_DS,Reach-1,3250
    2119    3711    5278    3634    7250   14466   13527
Boundary for River Rch & Prof#=Stream0160_DS,Reach-1,1
Up Type=0
Dn Type=3
Dn Slope=0.005
Boundary for River Rch & Prof#=Stream0160_DS,Reach-1,2
Up Type=0
Dn Type=3
Dn Slope=0.005
Boundary for River Rch & Prof#=Stream0160_DS,Reach-1,3
Up Type=0
Dn Type=3
Dn Slope=0.005
Boundary for River Rch & Prof#=Stream0160_DS,Reach-1,4
Up Type=0
Dn Type=3
Dn Slope=0.005
Boundary for River Rch & Prof#=Stream0160_DS,Reach-1,5
Up Type=0
Dn Type=3
Dn Slope=0.005
Boundary for River Rch & Prof#=Stream0160_DS,Reach-1,6
Up Type=0
Dn Type=3
Dn Slope=0.005
Boundary for River Rch & Prof#=Stream0160_DS,Reach-1,7
Up Type=0
Dn Type=3
Dn Slope=0.005

--- Stream0160_DS.g01 (geometry) ---

Geom Title=Existing Conditions
Program Version=4.10

River Reach=Stream0160_DS   ,Reach-1
Reach XY= 30
        2055675.       13856075.      2055677.24     13856619.07
      2055718.88     13856672.82      2055731.08      13856727.2
       2055768.9     13856772.81      2055783.16     13856831.05
      2055871.45     13856926.47      2055877.24     13857169.07
      2055918.88     13857222.82      2055931.12     13857277.18
      2055972.64     13857330.52      2055978.56     13857473.53
      2056073.94     13857585.44      2056075.23     13858006.74
      2056125.28     13858095.18      2056119.62     13858127.18
      2056077.39     13858180.52       2056074.5     13858285.17
      2056078.77     13858323.43      2056116.86     13858368.94
      2056124.79     13858393.27      2056125.67     13858811.09
      2056170.81     13858876.74      2056181.11     13858927.18
      2056221.17     13858976.58      2056227.36     13859069.02
      2056274.81     13859143.28      2056273.74     13859265.38
      2056228.65     13859326.51        2056225.       13859375.

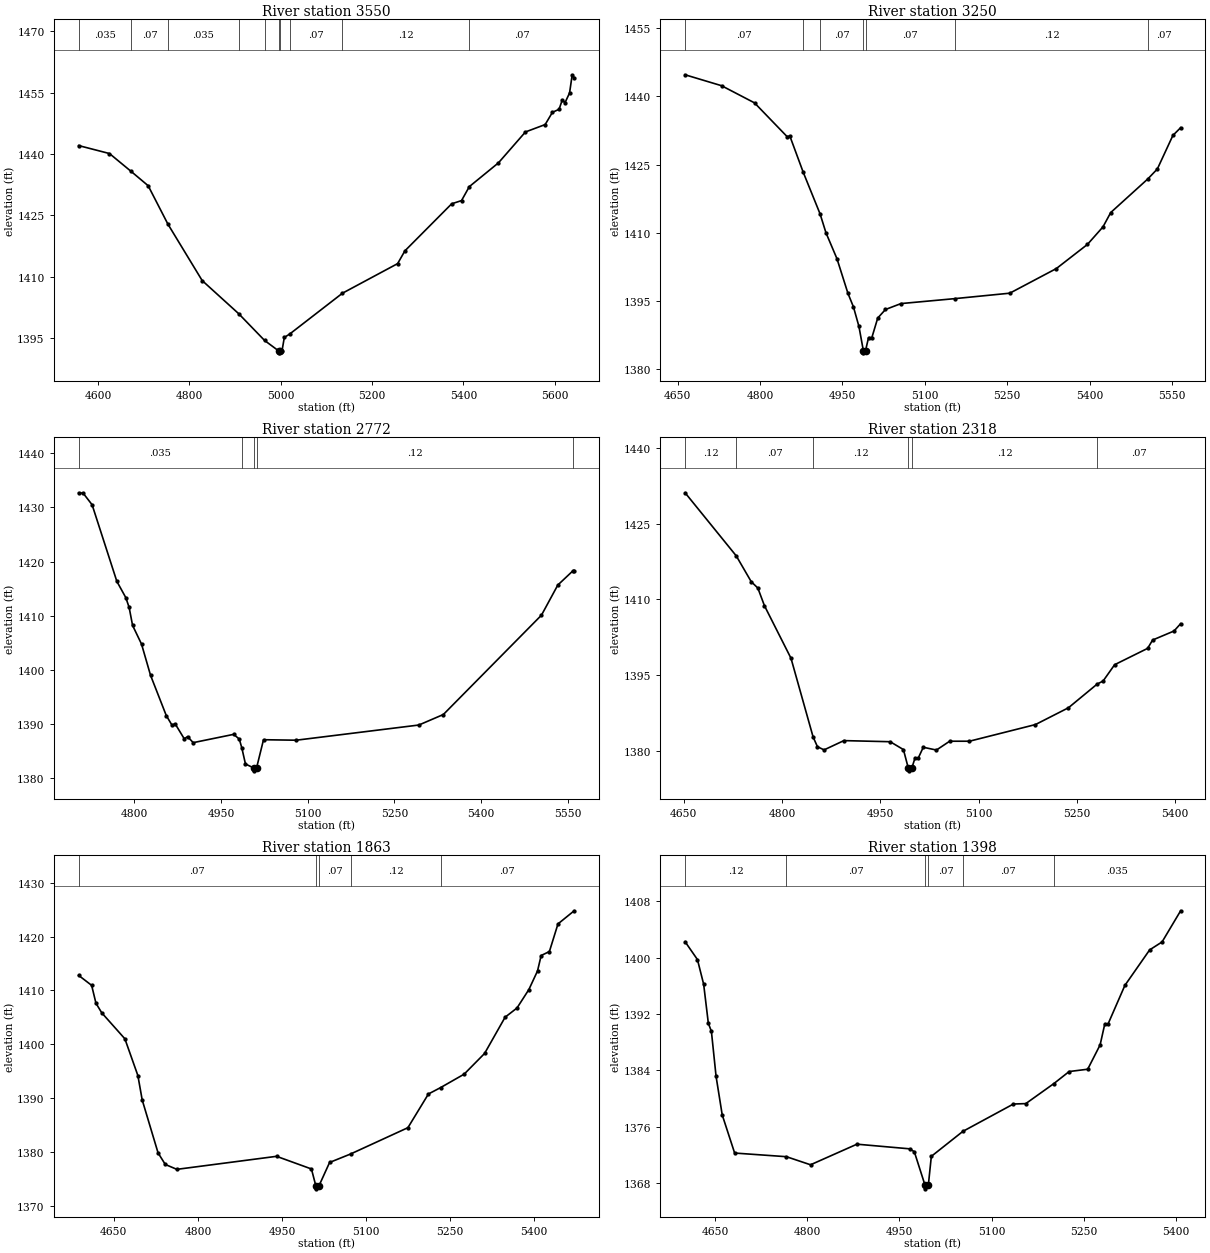
Type RM Length L Ch R = 1 ,3550    ,300,300,300
BEGIN DESCRIPTION:
Stream0160_DS 7.0
END DESCRIPTION:
XS GIS Cut Line= 3
      2055277.15     13856268.48        2055675.       13856075.
      2056233.79     13855757.89
#Sta/Elev= 30
  4557.6 1442.04  4625.1 1440.09  4672.3 1435.74  4709.8 1432.22  4753.2 1422.79
  4828.1 1409.01  4907.9 1400.92  4964.7 1394.36  4995.2 1391.83  4995.5 1391.33
  4999.2 1391.83  5002.9 1391.83  5007.9 1395.09  5019.9 1395.95  5135.2 1405.92
    5256 1413.16  5271.9 1416.28  5374.3 1427.79  5395.9 1428.58  5412.9 1431.99
  5476.7 1437.81  5535.8 1445.37    5579 1447.18  5594.9 1450.18  5609.4 1450.91
  5616.6 1453.25  5622.3 1452.49  5632.4 1454.91  5638.2 1459.36  5642.5 1458.61
#Mann= 10 ,-1 , 0
  4557.6    .035       0  4672.3     .07       0  4753.2    .035       0
  4907.9     .07       0  4964.7    .035       0  4995.2    .035       0
  4999.2    .035       0  5019.9     .07       0  5135.2     .12       0
  5412.9     .07       0
Bank Sta=4995.2,4999.2
XS Rating Curve= 0 ,0
Exp/Cntr=0.3,0.1

Type RM Length L Ch R = 1 ,3250    ,478,478,478
BEGIN DESCRIPTION:
Stream0160_DS 6.0
END DESCRIPTION:
XS GIS Cut Line= 3
      2055338.68     13856363.52        2055675.       13856375.
        2056075.       13855975.
#Sta/Elev= 30
  4663.5 1444.72  4729.9 1442.32  4789.9 1438.55  4849.2 1431.14  4854.2 1431.27
  4878.5 1423.33  4909.2 1414.18    4920 1410.01    4940 1404.32    4960 1396.71
    4970 1393.74    4980 1389.45    4988 1384.15  4988.3 1383.65    4992 1384.15
  4997.5 1386.99  5003.5 1386.99  5014.2 1391.29  5028.3 1393.17  5056.6 1394.47
    5155 1395.56  5254.6 1396.75  5339.4 1402.16    5396 1407.46  5424.3 1411.31
  5438.4 1414.46    5506 1421.85  5523.3 1424.03  5551.6  1431.4  5565.7  1433.1
#Mann= 7 ,-1 , 0
  4663.5     .07       0  4878.5    .035       0  4909.2     .07       0
    4988     .05       0    4992     .07       0    5155     .12       0
    5506     .07       0
Bank Sta=4988,4992
XS Rating Curve= 0 ,0
Exp/Cntr=0.3,0.1

Type RM Length L Ch R = 1 ,2772    ,454,454,454
BEGIN DESCRIPTION:
Stream0160_DS 5.0
END DESCRIPTION:
XS GIS Cut Line= 3
      2055525.02     13856974.99        2055775.       13856825.
      2056174.99     13856425.01
#Sta/Elev= 30
  4703.7  1432.7  4711.5 1432.63    4727 1430.49  4769.8 1416.36  4785.3 1413.36
  4791.1 1411.54    4797 1408.24  4812.5 1404.79  4828.1 1399.03  4855.3 1391.61
    4865 1389.87  4870.8 1390.06  4886.4 1387.32  4892.2 1387.72  4901.9 1386.61
  4971.9 1388.14  4981.6 1387.27    4986 1385.64  4992.3 1382.67  5007.3 1381.91
  5007.6 1381.41  5011.4 1381.91  5023.5 1387.15  5080.1 1387.06  5292.2 1389.86
  5334.6  1391.8  5504.3 1410.12  5532.6 1415.68  5559.1 1418.34  5560.9 1418.34
#Mann= 5 ,-1 , 0
  4703.7    .035       0    4986     .12       0  5007.3     .05       0
  5011.4     .12       0  5559.1     .07       0
Bank Sta=5007.3,5011.4
XS Rating Curve= 0 ,0
Exp/Cntr=0.3,0.1

Type RM Length L Ch R = 1 ,2318    ,455,455,455
BEGIN DESCRIPTION:
Stream0160_DS 4.0
END DESCRIPTION:
XS GIS Cut Line= 3
      2055574.97       13857175.        2055925.       13857225.
      2056325.01       13857175.
#Sta/Elev= 30
  4651.9 1431.13    4730 1418.63  4752.9 1413.51    4763 1412.25  4773.1 1408.74
  4813.6 1398.34  4847.4 1382.73    4854 1380.81  4864.1 1380.18  4894.4 1382.02
  4965.1  1381.8  4985.3 1380.24  4992.8 1376.53  4993.2 1376.03    4998 1376.53
    5003 1378.58    5008 1378.58  5015.6  1380.7  5035.7 1380.15  5055.9  1381.9
  5086.1  1381.9  5186.9  1385.2  5237.3 1388.53  5281.1 1393.22  5290.2 1393.83
  5307.8 1397.06  5358.2  1400.3  5365.8 1401.95  5398.5 1403.74  5408.6 1405.19
#Mann= 6 ,-1 , 0
  4651.9     .12       0    4730     .07       0  4847.4     .12       0
  4992.8     .05       0    4998     .12       0  5281.1     .07       0
Bank Sta=4992.8,4998
XS Rating Curve= 0 ,0
Exp/Cntr=0.3,0.1

Type RM Length L Ch R = 1 ,1863    ,465,465,465
BEGIN DESCRIPTION:
Stream0160_DS 3.0
END DESCRIPTION:
XS GIS Cut Line= 3
      2055674.98       13857725.        2056075.       13857625.
      2056474.98     13857375.01
#Sta/Elev= 30
  4587.2  1412.8  4610.4 1410.95  4618.1 1407.63  4628.4 1405.85  4669.7 1401.02
  4692.9 1394.19  4700.6 1389.66  4728.9 1379.83  4741.8 1377.68  4762.4 1376.77
  4940.3 1379.19  5002.5 1376.84  5010.5 1373.65  5010.9 1373.15  5015.7 1373.65
  5034.9 1378.05  5072.3 1379.62  5174.6 1384.51  5211.2 1390.77  5232.8 1391.95
  5274.9 1394.45  5311.4  1398.3    5348 1405.03  5369.2 1406.74  5390.4 1410.17
  5405.8 1413.62  5412.3 1416.49    5427 1417.23  5442.3 1422.36  5471.2  1424.8
#Mann= 5 ,-1 , 0
  4587.2     .07       0  5010.5     .05       0  5015.7     .07       0
  5072.3     .12       0  5232.8     .07       0
Bank Sta=5010.5,5015.7
XS Rating Curve= 0 ,0
Exp/Cntr=0.3,0.1

Type RM Length L Ch R = 1 ,1398    ,434,434,434
BEGIN DESCRIPTION:
Stream0160_DS 2.0
END DESCRIPTION:
XS GIS Cut Line= 3
      2055725.03       13858025.        2056125.       13858075.
        2056525.       13858025.
#Sta/Elev= 30
  4601.5 1402.28  4621.6 1399.74  4631.7 1396.23  4639.3 1390.69  4644.3 1389.53
  4651.9 1383.13  4661.9 1377.65  4682.1 1372.23  4766.4 1371.71  4805.6 1370.56
  4881.1 1373.49  4966.8 1372.83  4974.4 1372.42  4991.9 1367.64  4992.3 1367.14
  4997.2 1367.64  5002.1 1371.76  5053.4 1375.31  5135.6  1379.2  5155.8 1379.26
  5201.5 1382.11  5226.3 1383.82  5256.5 1384.15  5276.7 1387.61  5284.2 1390.55
  5289.3 1390.52    5317 1396.07  5357.3 1401.12  5377.5 1402.25  5407.7 1406.68
#Mann= 6 ,-1 , 0
  4601.5     .12       0  4766.4     .07       0  4991.9     .05       0
  4997.2     .07       0  5053.4     .07       0  5201.5    .035       0
Bank Sta=4991.9,4997.2
XS Rating Curve= 0 ,0
Exp/Cntr=0.3,0.1

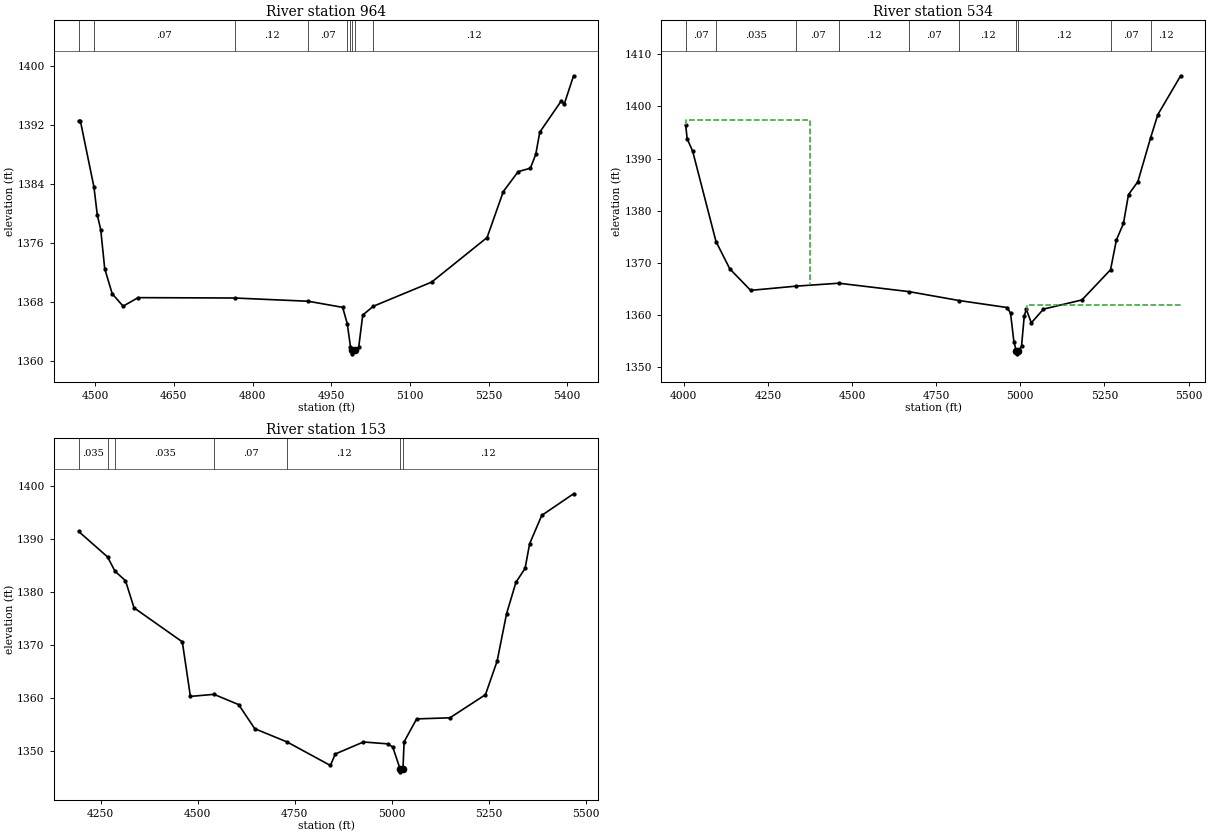
Type RM Length L Ch R = 1 ,964     ,430,430,430
BEGIN DESCRIPTION:
Stream0160_DS 1.0
END DESCRIPTION:
XS GIS Cut Line= 3
        2055725.       13858125.        2056125.       13858475.
      2056524.98       13858375.
#Sta/Elev= 30
  4468.4 1392.64  4471.7 1392.64  4497.7 1383.62    4504 1379.86  4510.6 1377.85
  4518.2 1372.55  4532.5 1369.14  4553.3 1367.46  4581.8 1368.62  4765.9 1368.57
  4906.3 1368.13  4971.9  1367.3  4980.6  1365.1  4986.8 1361.96  4990.1 1361.49
  4990.5 1360.99  4995.4 1361.49  5002.5 1361.89  5010.2 1366.26  5030.4 1367.45
  5141.6 1370.73  5247.3 1376.78  5278.2 1383.02  5306.6 1385.73  5329.8 1386.19
  5340.1 1388.07  5347.8 1391.09    5389 1395.35  5394.2 1394.85  5412.2 1398.74
#Mann= 9 ,-1 , 0
  4468.4     .12       0  4497.7     .07       0  4765.9     .12       0
  4906.3     .07       0  4980.6     .12       0  4986.8     .07       0
  4990.1     .05       0  4995.4     .07       0  5030.4     .12       0
Bank Sta=4990.1,4995.4
XS Rating Curve= 0 ,0
Exp/Cntr=0.3,0.1

Type RM Length L Ch R = 1 ,534     ,381,381,381
BEGIN DESCRIPTION:
Stream0160_DS 0.1
END DESCRIPTION:
XS GIS Cut Line= 5
      2055638.08     13858116.26      2055931.69     13858746.88
      2056074.09     13858885.34      2056173.88      13858889.1
      2056570.98     13858625.56
#Sta/Elev= 30
  4005.9 1396.38  4010.2 1393.81  4026.6 1391.41  4095.9 1374.07  4136.9 1368.82
  4198.8 1364.69  4334.5  1365.5  4460.8 1366.06    4670 1364.44  4817.8 1362.74
  4961.1 1361.39  4971.1 1360.31  4981.1 1354.79  4988.4    1353  4988.9  1352.5
  4993.8    1353  5003.7 1353.94  5011.9  1359.8  5017.9 1361.04  5032.9 1358.45
    5069 1361.09  5183.3 1362.85  5268.3 1368.65  5285.6 1374.36  5306.6 1377.54
  5321.6 1383.08  5349.4 1385.55  5387.2 1393.97  5408.9 1398.45  5476.6 1405.89
#Mann= 10 ,-1 , 0
  4005.9     .07       0  4095.9    .035       0  4334.5     .07       0
  4460.8     .12       0    4670     .07       0  4817.8     .12       0
  4988.4     .05       0  4993.8     .12       0  5268.3     .07       0
  5387.2     .12       0
#XS Ineff= 2 , 0
       0 4376.65 1397.44 5019.71       0 1361.93
Permanent Ineff=
       F       F
Bank Sta=4988.4,4993.8
XS Rating Curve= 0 ,0
Exp/Cntr=0.3,0.1

Type RM Length L Ch R = 1 ,153     ,0,0,0
BEGIN DESCRIPTION:
Stream0160_DS 0.0
END DESCRIPTION:
XS GIS Cut Line= 3
      2055497.26     13859453.11      2056275.49     13859238.81
      2056711.29     13859066.83
#Sta/Elev= 30
  4192.8  1391.5  4267.3 1386.69  4286.7 1383.97  4313.6 1382.19  4335.7 1377.06
  4460.1 1370.64  4480.9 1360.33  4541.7 1360.72  4605.3 1358.78  4646.8 1354.23
  4730.3 1351.72  4841.8 1347.28  4854.3 1349.45  4926.9 1351.72  4989.1 1351.37
  5002.4 1350.78  5021.6 1346.58  5022.1 1346.08  5028.8 1346.58  5031.7 1351.75
    5064 1356.08    5150 1356.29  5241.4 1360.66  5271.4 1366.98  5295.8 1375.96
  5320.1 1381.91  5343.5 1384.51  5355.3 1389.18  5386.5 1394.53  5468.5 1398.61
#Mann= 7 ,-1 , 0
  4192.8    .035       0  4267.3     .07       0  4286.7    .035       0
  4541.7     .07       0  4730.3     .12       0  5021.6     .05       0
  5028.8     .12       0
Bank Sta=5021.6,5028.8
XS Rating Curve= 0 ,0
Exp/Cntr=0.3,0.1

Chan Stop Cuts=-1
Use User Specified Reach Order=0
Composite Channel Slope=5