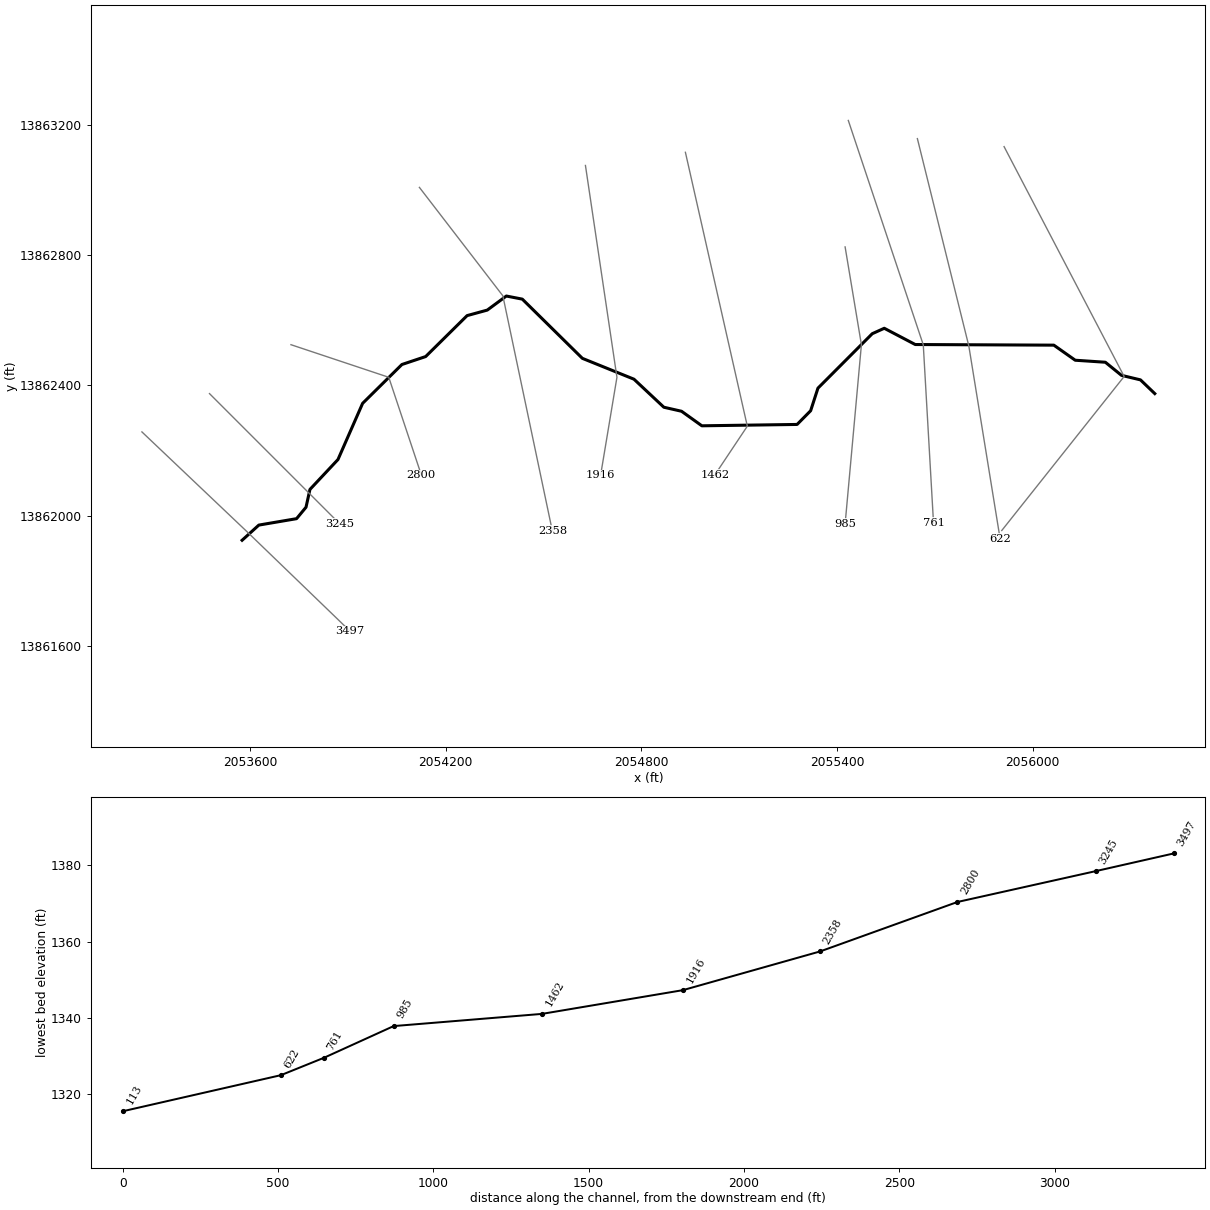
--- Stream0161_DS.prj (project) ---

Proj Title=Stream0161_DS Base Level Engineering
Current Plan=p01
Default Exp/Contr=0.3,0.1
English Units
Geom File=g01
Flow File=f01
Plan File=p01
BEGIN DESCRIPTION:
Stream0161_DS
END DESCRIPTION:

--- Stream0161_DS.p01 (plan) ---

Plan Title=Multiple Run
Short Identifier=Multiple
Geom File=g01
Flow File=f01
Subcritical Flow
K Sum by GR= 0
Std Step Tol= 0.01
Critical Tol= 0.01
Num of Std Step Trials= 20
Max Error Tol= 0.3
Flow Tol Ratio= 0.001
Split Flow NTrial= 30
Split Flow Tol= 0.02
Split Flow Ratio= 0.02
Log Output Level= 0
Friction Slope Method= 1
Unsteady Friction Slope Method= 2
Unsteady Bridges Friction Slope Method= 1
Parabolic Critical Depth
Global Vel Dist=  1 , 1 , 1
Global Log Level= 0
CheckData=True
Encroach Param= -1, 0, 0, 0
BEGIN DESCRIPTION:
Multiple Run
END DESCRIPTION:

--- Stream0161_DS.f01 (steady flow) ---

Flow Title=Multiple
Number of Profiles=7
Profile Names=10-year,25-year,50-year,1pct_min,100-year,1pct_plu,500-year
River Rch & RM= Stream0161_DS,Reach-1,3497
     802    1347    1863    1255    2504    4996    4459
River Rch & RM= Stream0161_DS,Reach-1,3245
    1791    3155    4507    3123    6231   12432   11771
Boundary for River Rch & Prof#=Stream0161_DS,Reach-1,1
Up Type=0
Dn Type=3
Dn Slope=0.005
Boundary for River Rch & Prof#=Stream0161_DS,Reach-1,2
Up Type=0
Dn Type=3
Dn Slope=0.005
Boundary for River Rch & Prof#=Stream0161_DS,Reach-1,3
Up Type=0
Dn Type=3
Dn Slope=0.005
Boundary for River Rch & Prof#=Stream0161_DS,Reach-1,4
Up Type=0
Dn Type=3
Dn Slope=0.005
Boundary for River Rch & Prof#=Stream0161_DS,Reach-1,5
Up Type=0
Dn Type=3
Dn Slope=0.005
Boundary for River Rch & Prof#=Stream0161_DS,Reach-1,6
Up Type=0
Dn Type=3
Dn Slope=0.005
Boundary for River Rch & Prof#=Stream0161_DS,Reach-1,7
Up Type=0
Dn Type=3
Dn Slope=0.005

--- Stream0161_DS.g01 (geometry) ---

Geom Title=Existing Conditions

River Reach=Stream0161_DS,Reach-1
Reach XY= 30
      2053575.00     13861925.00      2053626.41     13861971.61
      2053742.13     13861991.29      2053771.13     13862026.40
      2053783.19     13862081.02      2053869.15     13862172.71
      2053944.78     13862345.09      2054065.32     13862464.22
      2054138.21     13862488.63      2054265.32     13862614.24
      2054327.19     13862631.18      2054385.70     13862674.30
      2054434.68     13862664.81      2054618.94     13862483.14
      2054777.29     13862419.15      2054868.95     13862333.16
      2054923.25     13862320.78      2054985.50     13862276.20
      2055277.70     13862280.36      2055319.26     13862322.42
      2055341.66     13862391.66      2055508.32     13862558.78
      2055545.13     13862575.40      2055640.21     13862525.54
      2056065.34     13862523.62      2056130.98     13862477.36
      2056223.42     13862471.18      2056272.78     13862431.03
      2056331.15     13862417.09      2056375.00     13862375.00

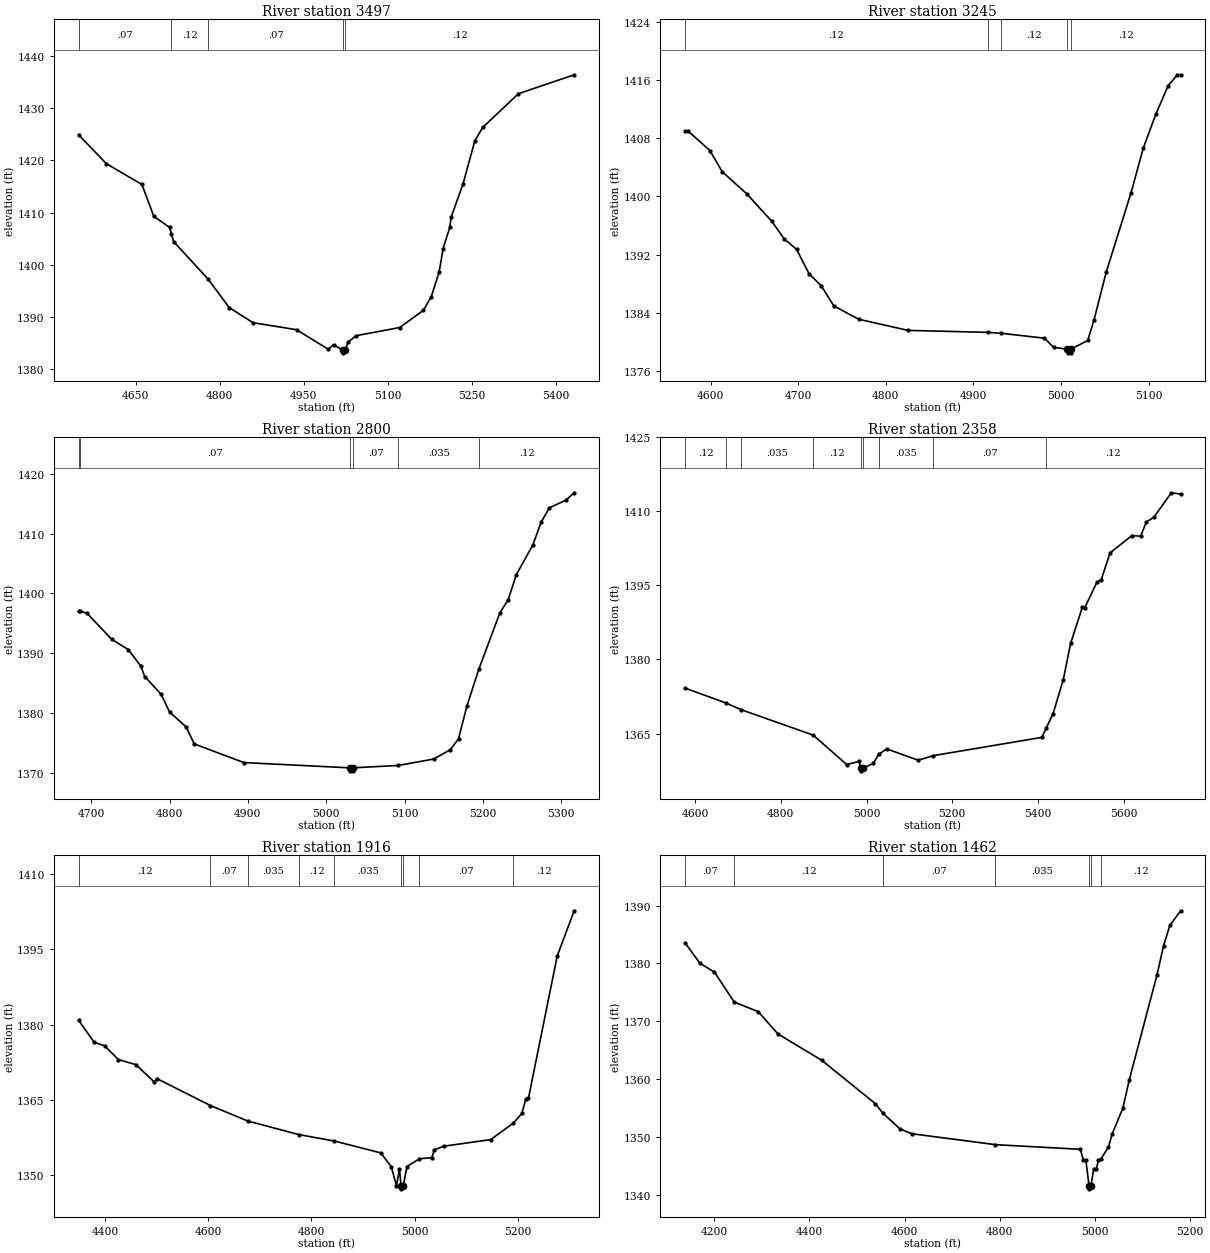
Type RM Length L Ch R = 1,3497,252,252,252
BEGIN DESCRIPTION:
Stream0161_DS 8.0
END DESCRIPTION:
XS GIS Cut Line= 3
      2053267.76     13862257.39      2053595.33     13861946.37
      2053906.55     13861645.90
#Sta/Elev= 30
  4548.3 1424.89  4597.7 1419.37  4661.2 1415.37  4682.4 1409.28  4710.6 1407.14
  4713.7 1405.97  4717.8 1404.43  4779.5 1397.23  4816.9 1391.80  4859.4 1388.90
  4937.1 1387.55  4993.7 1383.81  5003.2 1384.67  5020.0 1383.62  5020.2 1383.12
  5024.0 1383.62  5028.9 1385.13  5043.1 1386.40  5121.0 1387.96  5163.5 1391.26
  5177.6 1393.88  5191.8 1398.70  5198.7 1403.10  5210.7 1407.18  5212.9 1409.05
  5234.2 1415.46  5255.3 1423.73  5269.5 1426.32  5333.1 1432.76  5432.6 1436.39
#Mann=5,-1,0
  4548.3    0.07       0  4713.7    0.12       0  4779.5    0.07       0
  5020.0    0.05       0  5024.0    0.12       0
Bank Sta=5020,5024
Exp/Cntr=0.3,0.1

Type RM Length L Ch R = 1,3245,445,445,445
BEGIN DESCRIPTION:
Stream0161_DS 7.0
END DESCRIPTION:
XS GIS Cut Line= 3
      2053475.01     13862374.99      2053775.00     13862075.00
      2053875.02     13861974.98
#Sta/Elev= 30
  4570.9 1409.00  4574.4 1409.00  4599.2 1406.32  4613.3 1403.40  4641.6 1400.32
  4669.9 1396.57  4684.0 1394.15  4698.2 1392.72  4712.3 1389.38  4726.4 1387.69
  4740.6 1384.94  4768.9 1383.10  4825.4 1381.56  4916.2 1381.29  4932.0 1381.16
  4981.0 1380.49  4991.6 1379.22  5007.3 1378.97  5007.5 1378.47  5011.0 1378.47
  5011.3 1378.97  5030.5 1380.17  5037.6 1382.95  5051.7 1389.61  5080.0 1400.51
  5094.1 1406.71  5108.3 1411.33  5122.4 1415.27  5133.0 1416.75  5136.6 1416.75
#Mann=5,-1,0
  4570.9    0.12       0  4916.2    0.07       0  4932.0    0.12       0
  5007.3    0.05       0  5011.3    0.12       0
Bank Sta=5007.3,5011.3
Exp/Cntr=0.3,0.1

Type RM Length L Ch R = 1,2800,442,442,442
BEGIN DESCRIPTION:
Stream0161_DS 6.0
END DESCRIPTION:
XS GIS Cut Line= 3
      2053724.97     13862525.01      2054025.00     13862425.00
      2054125.00     13862124.99
#Sta/Elev= 30
  4684.0 1397.06  4685.4 1397.06  4694.6 1396.71  4726.2 1392.35  4747.3 1390.64
  4763.1 1387.93  4768.4 1386.13  4789.4 1383.16  4800.0 1380.22  4821.1 1377.74
  4831.6 1374.88  4894.9 1371.77  5029.9 1370.89  5030.1 1370.39  5033.6 1370.39
  5033.9 1370.89  5092.0 1371.29  5137.3 1372.36  5158.4 1373.92  5168.9 1375.74
  5179.5 1381.17  5194.7 1387.32  5221.6 1396.75  5232.2 1398.93  5242.7 1403.14
  5263.8 1408.11  5274.3 1411.90  5284.9 1414.30  5305.9 1415.58  5316.5 1416.81
#Mann=6,-1,0
  4684.0   0.035       0  4685.4    0.07       0  5029.9    0.05       0
  5033.9    0.07       0  5092.0   0.035       0  5194.7    0.12       0
Bank Sta=5029.9,5033.9
Exp/Cntr=0.3,0.1

Type RM Length L Ch R = 1,2358,442,442,442
BEGIN DESCRIPTION:
Stream0161_DS 5.0
END DESCRIPTION:
XS GIS Cut Line= 3
      2054118.99     13863007.61      2054375.00     13862675.00
      2054526.82     13861953.63
#Sta/Elev= 30
  4576.4 1374.20  4671.7 1371.19  4707.1 1369.83  4875.4 1364.68  4953.6 1358.72
  4982.6 1359.34  4986.9 1357.94  4987.1 1357.44  4990.9 1357.94  5015.9 1358.96
  5028.6 1360.80  5047.2 1361.88  5120.7 1359.59  5155.1 1360.51  5409.4 1364.22
  5419.2 1366.03  5435.5 1369.04  5459.3 1375.89  5476.4 1383.25  5504.0 1390.64
  5509.1 1390.42  5537.7 1395.64  5548.0 1396.17  5568.4 1401.58  5619.5 1405.10
  5639.9 1404.98  5653.4 1407.87  5670.6 1408.79  5711.5 1413.77  5733.3 1413.50
#Mann=9,-1,0
  4576.4    0.12       0  4671.7    0.07       0  4707.1   0.035       0
  4875.4    0.12       0  4986.9    0.05       0  4990.9    0.12       0
  5028.6   0.035       0  5155.1    0.07       0  5419.2    0.12       0
Bank Sta=4986.9,4990.9
Exp/Cntr=0.3,0.1

Type RM Length L Ch R = 1,1916,454,454,454
BEGIN DESCRIPTION:
Stream0161_DS 4.0
END DESCRIPTION:
XS GIS Cut Line= 3
      2054628.39     13863074.85      2054725.00     13862425.00
      2054675.00     13862125.03
#Sta/Elev= 30
  4348.5 1380.86  4378.7 1376.49  4398.9 1375.78  4425.8 1373.04  4459.6 1372.04
  4495.2 1368.56  4500.3 1369.26  4604.1 1363.89  4676.1 1360.82  4775.1 1358.11
  4844.6 1356.81  4934.7 1354.45  4954.9 1351.68  4965.0 1347.89  4970.8 1351.24
  4973.9 1347.79  4974.1 1347.29  4977.9 1347.79  4985.3 1351.74  5009.5 1353.28
  5033.4 1353.50  5038.4 1355.05  5056.2 1355.78  5147.4 1357.09  5191.5 1360.37
  5208.2 1362.32  5215.9 1365.20  5220.9 1365.32  5276.7 1393.68  5309.6 1402.69
#Mann=9,-1,0
  4348.5    0.12       0  4604.1    0.07       0  4676.1   0.035       0
  4775.1    0.12       0  4844.6   0.035       0  4973.9    0.05       0
  4977.9   0.035       0  5009.5    0.07       0  5191.5    0.12       0
Bank Sta=4973.9,4977.9
Exp/Cntr=0.3,0.1

Type RM Length L Ch R = 1,1462,477,477,477
BEGIN DESCRIPTION:
Stream0161_DS 3.0
END DESCRIPTION:
XS GIS Cut Line= 3
      2054935.04     13863115.27      2055125.00     13862275.00
      2055025.03     13862125.04
#Sta/Elev= 30
  4138.5 1383.57  4169.5 1380.05  4200.3 1378.49  4241.9 1373.32  4292.2 1371.68
  4333.6 1367.83  4425.8 1363.27  4538.6 1355.77  4554.2 1354.15  4589.9 1351.44
  4615.0 1350.59  4790.9 1348.70  4969.2 1347.90  4975.8 1346.04  4980.9 1346.09
  4987.7 1341.57  4988.0 1341.07  4991.7 1341.57  4997.4 1344.52  5003.0 1344.52
  5007.5 1346.05  5012.2 1346.19  5028.5 1348.27  5036.0 1350.50  5058.6 1354.96
  5072.1 1359.85  5130.7 1378.08  5144.2 1383.04  5157.7 1386.61  5180.2 1389.10
#Mann=7,-1,0
  4138.5    0.07       0  4241.9    0.12       0  4554.2    0.07       0
  4790.9   0.035       0  4987.7   0.035       0  4991.7   0.035       0
  5012.2    0.12       0
Bank Sta=4987.7,4991.7
Exp/Cntr=0.3,0.1

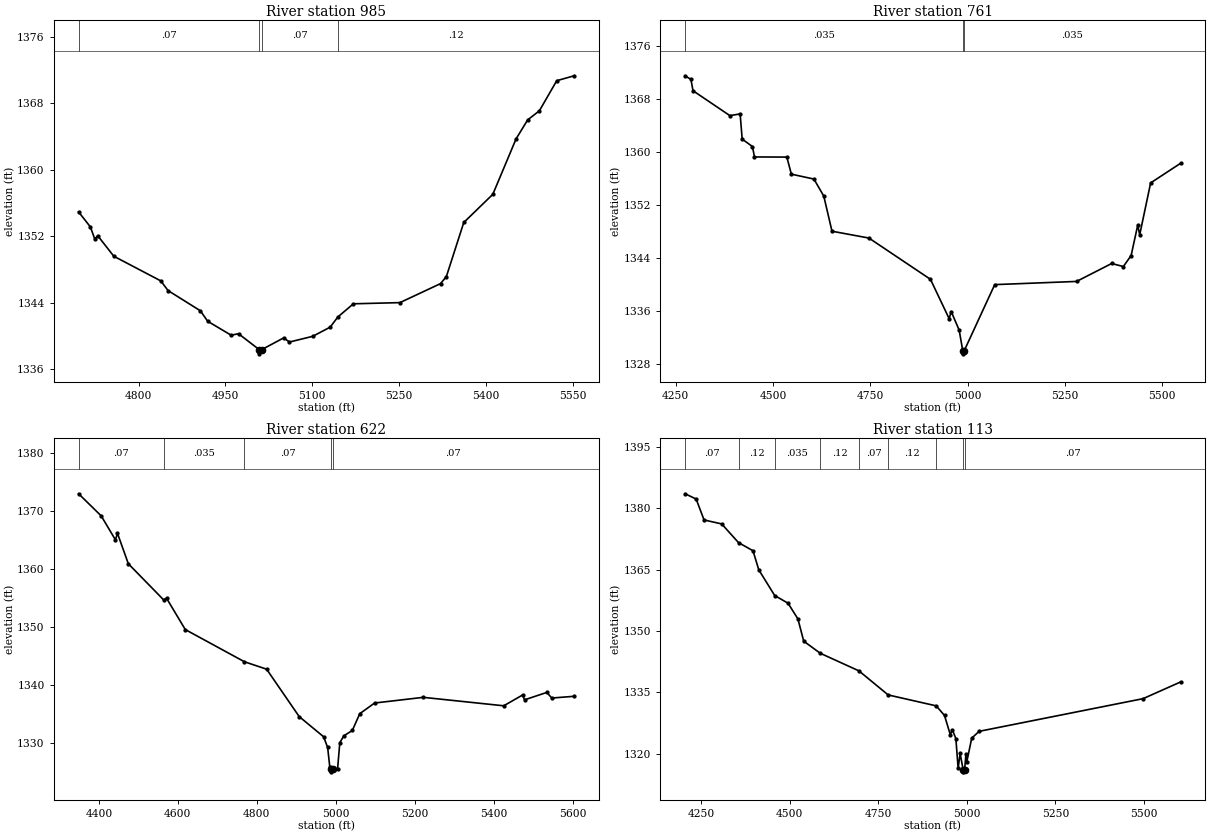
Type RM Length L Ch R = 1,985,224,224,224
BEGIN DESCRIPTION:
Stream0161_DS 2.0
END DESCRIPTION:
XS GIS Cut Line= 3
      2055425.00     13862825.01      2055475.00     13862525.00
      2055425.00     13861975.02
#Sta/Elev= 30
  4696.2 1354.95  4716.5 1353.15  4724.1 1351.69  4729.2 1352.09  4757.0 1349.62
  4838.1 1346.66  4850.8 1345.49  4906.6 1343.06  4919.2 1341.80  4959.8 1340.12
  4972.5 1340.30  5008.4 1338.38  5008.6 1337.88  5012.4 1338.38  5050.6 1339.80
  5060.6 1339.30  5100.8 1339.99  5130.9 1341.09  5144.3 1342.32  5171.0 1343.90
  5251.4 1344.04  5321.7 1346.33  5331.7 1347.17  5361.8 1353.68  5412.0 1357.07
  5452.2 1363.74  5472.3 1366.03  5492.4 1367.11  5522.5 1370.74  5552.6 1371.33
#Mann=4,-1,0
  4696.2    0.07       0  5008.4    0.05       0  5012.4    0.07       0
  5144.3    0.12       0
Bank Sta=5008.4,5012.4
Exp/Cntr=0.3,0.1

Type RM Length L Ch R = 1,761,139,139,139
BEGIN DESCRIPTION:
Stream0161_DS 1.0
END DESCRIPTION:
XS GIS Cut Line= 3
      2055434.80     13863212.94      2055664.81     13862524.55
      2055696.21     13861978.06
#Sta/Elev= 30
  4274.2 1371.45  4289.2 1370.90  4294.5 1369.20  4389.3 1365.45  4415.6 1365.71
  4420.9 1361.91  4447.2 1360.80  4452.5 1359.23  4535.6 1359.21  4547.2 1356.64
  4605.2 1355.90  4630.5 1353.34  4651.6 1348.05  4746.5 1347.02  4904.6 1340.81
  4952.7 1334.88  4957.9 1335.96  4978.4 1333.16  4987.5 1330.09  4987.8 1329.59
  4991.6 1330.09  5069.7 1340.01  5280.0 1340.49  5370.2 1343.19  5400.2 1342.73
  5420.2 1344.39  5437.2 1348.98  5442.2 1347.50  5470.3 1355.32  5547.4 1358.28
#Mann=3,-1,0
  4274.2   0.035       0  4987.5   0.035       0  4991.6   0.035       0
Bank Sta=4987.5,4991.6
Exp/Cntr=0.3,0.1

Type RM Length L Ch R = 1,622,509,509,509
BEGIN DESCRIPTION:
Stream0161_DS 0.5
END DESCRIPTION:
XS GIS Cut Line= 3
      2055646.72     13863157.22      2055804.62     13862520.56
      2055900.63     13861928.95
#Sta/Elev= 30
  4348.6 1373.02  4405.7 1369.21  4441.9 1365.06  4447.0 1366.19  4474.5 1360.94
  4564.0 1354.70  4571.2 1355.00  4618.8 1349.58  4768.7 1344.02  4824.8 1342.74
  4907.3 1334.56  4969.1 1331.08  4979.4 1329.23  4984.9 1325.82  4988.0 1325.52
  4988.3 1325.02  4992.1 1325.52  5004.6 1325.56  5010.2 1330.05  5020.3 1331.23
  5041.9 1332.16  5060.8 1335.06  5098.4 1336.90  5221.7 1337.88  5425.5 1336.42
  5473.1 1338.28  5478.2 1337.45  5534.7 1338.73  5547.1 1337.76  5603.9 1338.06
#Mann=5,-1,0
  4348.6    0.07       0  4564.0   0.035       0  4768.7    0.07       0
  4988.0    0.05       0  4992.1    0.07       0
Bank Sta=4988,4992.1
Exp/Cntr=0.3,0.1

Type RM Length L Ch R = 1,113,0,0,0
BEGIN DESCRIPTION:
Stream0161_DS 0.0
END DESCRIPTION:
XS GIS Cut Line= 3
      2055912.69     13863132.63      2056281.06     13862427.56
      2055905.59     13861954.96
#Sta/Elev= 30
  4204.5 1383.55  4235.7 1382.27  4258.0 1377.15  4307.8 1376.18  4355.3 1371.61
  4396.2 1369.62  4412.6 1364.95  4457.5 1358.67  4495.2 1356.79  4523.0 1352.96
  4539.4 1347.52  4585.9 1344.57  4695.2 1340.26  4777.9 1334.37  4913.6 1331.70
  4936.9 1329.35  4953.3 1324.65  4959.0 1325.86  4969.0 1323.70  4975.4 1316.42
  4981.0 1320.06  4989.6 1316.07  4989.8 1315.57  4993.7 1316.07  4997.5 1319.94
  5000.0 1318.08  5013.7 1323.79  5034.5 1325.47  5497.5 1333.46  5603.6 1337.55
#Mann=9,-1,0
  4204.5    0.07       0  4355.3    0.12       0  4457.5   0.035       0
  4585.9    0.12       0  4695.2    0.07       0  4777.9    0.12       0
  4913.6    0.07       0  4989.6    0.05       0  4993.7    0.07       0
Bank Sta=4989.6,4993.7
Exp/Cntr=0.3,0.1

Chan Stop Cuts=-1