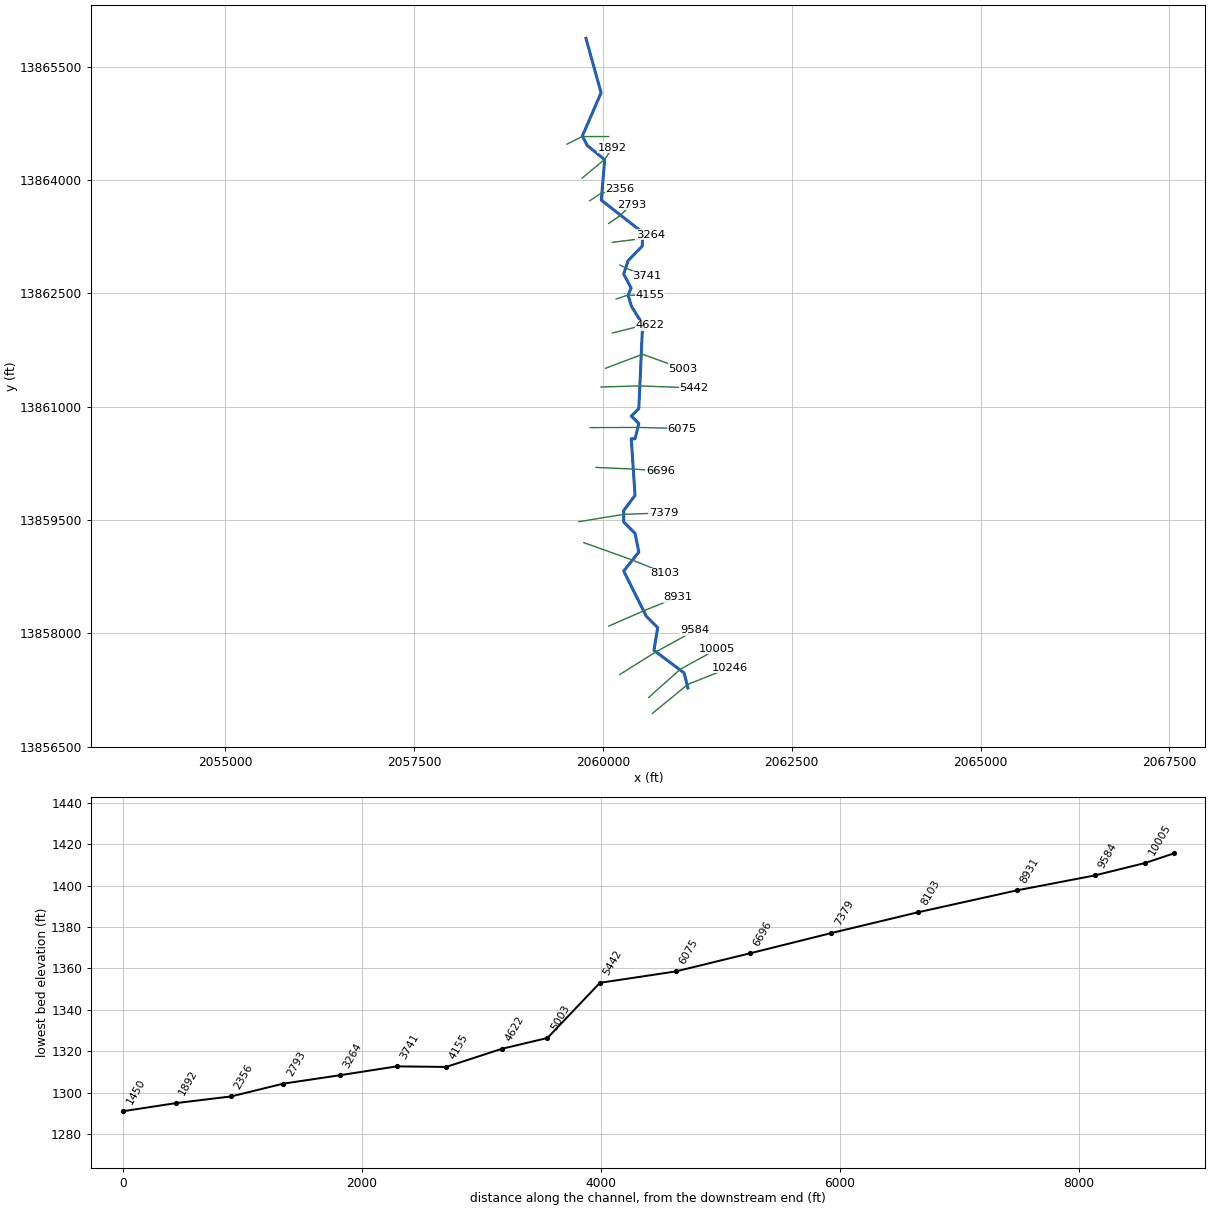
--- Stream0162_DS.prj (project) ---

Proj Title=Stream0162_DS Base Level Engineering
Current Plan=p01
Default Exp/Contr=0.3,0.1
English Units
Geom File=g01
Flow File=f01
Plan File=p01
BEGIN DESCRIPTION:
Stream0162_DS
END DESCRIPTION:

--- Stream0162_DS.p01 (plan) ---

Plan Title=Multiple Run
Short Identifier=Multiple
Geom File=g01
Flow File=f01
Subcritical Flow
K Sum by GR= 0
Std Step Tol= 0.01
Critical Tol= 0.01
Num of Std Step Trials= 20
Max Error Tol= 0.3
Flow Tol Ratio= 0.001
Split Flow NTrial= 30
Split Flow Tol= 0.02
Split Flow Ratio= 0.02
Log Output Level= 0
Friction Slope Method= 1
Unsteady Friction Slope Method= 2
Unsteady Bridges Friction Slope Method= 1
Parabolic Critical Depth
Global Vel Dist=  1 , 1 , 1
Global Log Level= 0
CheckData=True
Encroach Param= -1, 0, 0, 0
BEGIN DESCRIPTION:
Multiple Run
END DESCRIPTION:

--- Stream0162_DS.f01 (steady flow) ---

Flow Title=Multiple
Number of Profiles=7
Profile Names=10-year,25-year,50-year,1pct_min,100-year,1pct_plu,500-year
River Rch & RM= Stream0162_DS,Reach-1,10246
     704    1153    1568    1036    2067    4124    3544
River Rch & RM= Stream0162_DS,Reach-1,9584
    1450    2487    3485    2366    4721    9420    8565
River Rch & RM= Stream0162_DS,Reach-1,4622
    1616    2776    3894    2644    5276   10526    9577
Boundary for River Rch & Prof#=Stream0162_DS,Reach-1,1
Up Type=0
Dn Type=3
Dn Slope=0.005
Boundary for River Rch & Prof#=Stream0162_DS,Reach-1,2
Up Type=0
Dn Type=3
Dn Slope=0.005
Boundary for River Rch & Prof#=Stream0162_DS,Reach-1,3
Up Type=0
Dn Type=3
Dn Slope=0.005
Boundary for River Rch & Prof#=Stream0162_DS,Reach-1,4
Up Type=0
Dn Type=3
Dn Slope=0.005
Boundary for River Rch & Prof#=Stream0162_DS,Reach-1,5
Up Type=0
Dn Type=3
Dn Slope=0.005
Boundary for River Rch & Prof#=Stream0162_DS,Reach-1,6
Up Type=0
Dn Type=3
Dn Slope=0.005
Boundary for River Rch & Prof#=Stream0162_DS,Reach-1,7
Up Type=0
Dn Type=3
Dn Slope=0.005

--- Stream0162_DS.g01 (geometry) ---

Geom Title=Existing Conditions

River Reach=Stream0162_DS,Reach-1
Reach XY= 30
      2061125.00     13857275.00      2061075.00     13857475.00
      2060675.00     13857775.00      2060725.00     13858075.00
      2060575.00     13858225.00      2060275.00     13858825.00
      2060475.00     13859075.00      2060425.00     13859325.00
      2060275.00     13859475.00      2060275.00     13859625.00
      2060425.00     13859825.00      2060375.00     13860575.00
      2060425.00     13860575.00      2060475.00     13860775.00
      2060375.00     13860875.00      2060475.00     13860975.00
      2060525.44     13862090.18      2060378.62     13862326.50
      2060332.59     13862475.01      2060373.05     13862569.28
      2060274.71     13862754.82      2060332.86     13862931.17
      2060521.47     13863126.46      2060524.92     13863306.79
      2059978.40     13863733.44      2060022.94     13864269.15
      2059794.62     13864454.53      2059726.88     13864580.72
      2059975.60     13865154.95      2059775.00     13865875.00

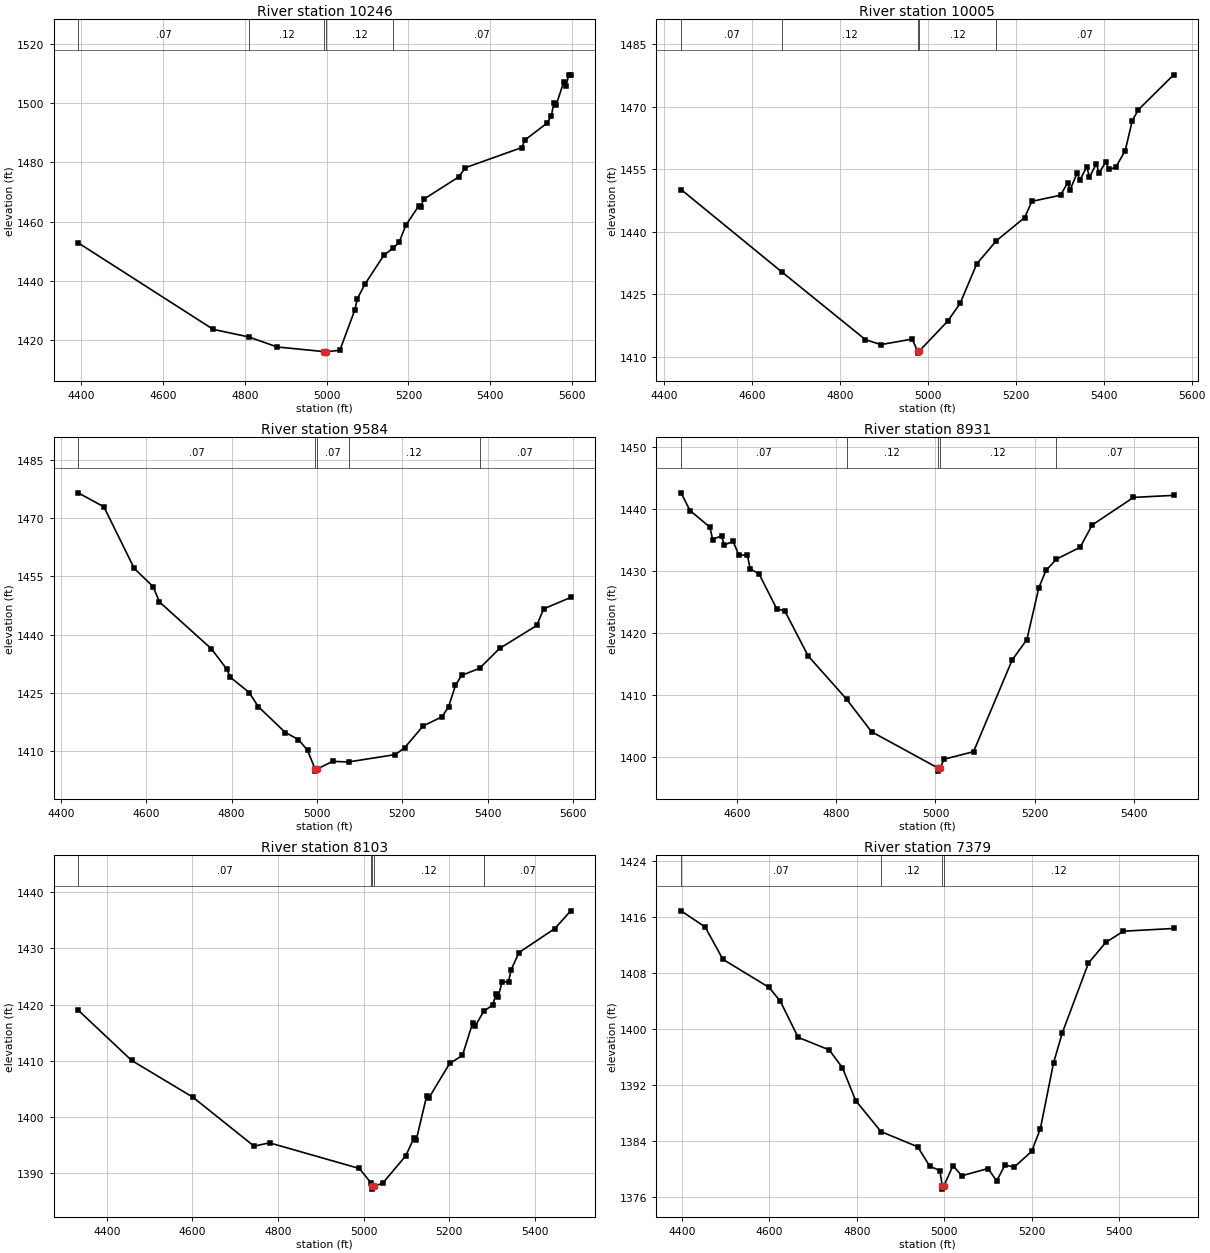
Type RM Length L Ch R = 1,10246,241,241,241
BEGIN DESCRIPTION:
Stream0162_DS 18.0
END DESCRIPTION:
XS GIS Cut Line= 3
      2060655.76     13856940.42      2061125.00     13857325.00
      2061679.31     13857544.81
#Sta/Elev= 30
  4393.3 1452.83  4723.0 1423.58  4809.8 1421.01  4879.4 1417.62  4994.8 1416.04
  4995.0 1415.54  4998.8 1416.04  5032.3 1416.48  5068.9 1430.11  5075.3 1433.99
  5093.2 1438.76  5139.8 1448.62  5161.9 1451.00  5176.9 1452.96  5193.6 1458.80
  5225.6 1465.42  5230.9 1465.05  5236.7 1467.52  5322.7 1475.12  5339.0 1478.24
  5476.7 1485.05  5484.1 1487.58  5537.9 1493.25  5548.6 1495.59  5555.1 1500.19
  5560.4 1499.32  5579.4 1507.34  5584.8 1505.85  5591.3 1509.64  5596.3 1509.64
#Mann=5,-1,0
  4393.3    0.07       0  4809.8    0.12       0  4994.8    0.05       0
  4998.8    0.12       0  5161.9    0.07       0
Bank Sta=4994.8,4998.8
Exp/Cntr=0.3,0.1

Type RM Length L Ch R = 1,10005,421,421,421
BEGIN DESCRIPTION:
Stream0162_DS 17.0
END DESCRIPTION:
XS GIS Cut Line= 3
      2060606.26     13857151.67      2061025.00     13857525.00
      2061515.29     13857793.72
#Sta/Elev= 30
  4439.0 1450.14  4668.7 1430.33  4858.3 1414.13  4893.4 1412.96  4964.5 1414.27
  4976.7 1411.41  4976.9 1410.91  4980.7 1411.41  5045.6 1418.62  5073.5 1422.84
  5111.4 1432.32  5155.8 1437.85  5220.4 1443.43  5236.5 1447.30  5301.9 1448.78
  5318.0 1451.79  5323.7 1450.09  5339.8 1454.16  5345.6 1452.36  5361.7 1455.63
  5367.4 1453.09  5383.5 1456.34  5389.2 1454.12  5405.3 1456.78  5411.0 1455.01
  5427.1 1455.43  5448.9 1459.47  5465.0 1466.67  5478.9 1469.29  5559.1 1477.65
#Mann=5,-1,0
  4439.0    0.07       0  4668.7    0.12       0  4976.7    0.05       0
  4980.7    0.12       0  5155.8    0.07       0
Bank Sta=4976.7,4980.7
Exp/Cntr=0.3,0.1

Type RM Length L Ch R = 1,9584,653,653,653
BEGIN DESCRIPTION:
Stream0162_DS 16.0
END DESCRIPTION:
XS GIS Cut Line= 3
      2060223.56     13857455.08      2060697.72     13857752.28
      2061219.45     13858038.54
#Sta/Elev= 30
  4440.4 1476.46  4500.7 1472.86  4571.9 1457.02  4616.2 1452.32  4630.9 1448.41
  4752.9 1436.33  4789.4 1431.05  4796.2 1429.13  4841.3 1425.12  4862.5 1421.50
  4926.1 1414.83  4956.8 1413.03  4978.0 1410.27  4995.9 1405.41  4996.1 1404.91
  4999.9 1405.41  5036.8 1407.42  5074.1 1407.27  5183.7 1409.16  5205.5 1410.91
  5249.1 1416.52  5293.5 1418.90  5308.8 1421.51  5324.9 1426.96  5339.1 1429.52
  5381.2 1431.33  5428.2 1436.44  5515.4 1442.36  5531.5 1446.62  5595.1 1449.57
#Mann=5,-1,0
  4440.4    0.07       0  4995.9    0.05       0  4999.9    0.07       0
  5074.1    0.12       0  5381.2    0.07       0
Bank Sta=4995.9,4999.9
Exp/Cntr=0.3,0.1

Type RM Length L Ch R = 1,8931,828,828,828
BEGIN DESCRIPTION:
Stream0162_DS 15.0
END DESCRIPTION:
XS GIS Cut Line= 3
      2060078.57     13858095.85      2060548.39     13858301.61
      2060993.96     13858480.67
#Sta/Elev= 30
  4487.1 1442.64  4505.0 1439.78  4545.3 1437.09  4550.7 1435.10  4568.6 1435.71
  4574.1 1434.21  4592.0 1434.80  4603.3 1432.63  4620.9 1432.53  4626.3 1430.38
  4644.3 1429.54  4679.7 1423.95  4696.5 1423.52  4743.2 1416.31  4820.6 1409.32
  4871.1 1404.05  5005.1 1398.19  5005.4 1397.69  5009.1 1398.19  5017.5 1399.62
  5076.7 1400.83  5154.6 1415.64  5184.2 1418.93  5208.4 1427.32  5222.7 1430.10
  5243.9 1431.93  5291.7 1433.85  5315.9 1437.45  5399.2 1441.90  5480.2 1442.23
#Mann=5,-1,0
  4487.1    0.07       0  4820.6    0.12       0  5005.1    0.05       0
  5009.1    0.12       0  5243.9    0.07       0
Bank Sta=5005.1,5009.1
Exp/Cntr=0.3,0.1

Type RM Length L Ch R = 1,8103,724,724,724
BEGIN DESCRIPTION:
Stream0162_DS 14.0
END DESCRIPTION:
XS GIS Cut Line= 3
      2059747.65     13859200.36      2060375.00     13858975.00
      2060824.28     13858796.06
#Sta/Elev= 30
  4333.4 1419.01  4458.1 1410.05  4601.1 1403.50  4744.1 1394.77  4780.2 1395.36
  4989.9 1390.79  5016.7 1388.27  5019.5 1387.61  5019.8 1387.11  5023.5 1387.61
  5044.5 1388.17  5098.4 1393.06  5117.3 1396.20  5122.7 1395.83  5147.0 1403.68
  5152.4 1403.38  5200.9 1409.52  5230.6 1410.93  5254.8 1416.77  5260.2 1416.15
  5280.7 1418.86  5301.4 1419.90  5308.8 1421.85  5314.2 1421.39  5322.9 1423.98
  5338.4 1424.10  5344.4 1426.22  5362.7 1429.28  5446.3 1433.54  5483.6 1436.71
#Mann=5,-1,0
  4333.4    0.07       0  5016.7    0.12       0  5019.5    0.05       0
  5023.5    0.12       0  5280.7    0.07       0
Bank Sta=5019.5,5023.5
Exp/Cntr=0.3,0.1

Type RM Length L Ch R = 1,7379,683,683,683
BEGIN DESCRIPTION:
Stream0162_DS 13.0
END DESCRIPTION:
XS GIS Cut Line= 3
      2059680.56     13859477.41      2060275.00     13859575.00
      2060799.88     13859593.37
#Sta/Elev= 30
  4397.6 1416.87  4452.8 1414.55  4493.3 1409.94  4599.2 1405.92  4625.0 1403.92
  4665.6 1398.79  4736.5 1397.00  4766.9 1394.46  4797.3 1389.75  4855.2 1385.32
  4939.2 1383.15  4966.8 1380.38  4989.9 1379.75  4995.5 1377.60  4995.7 1377.10
  4999.5 1377.60  5020.0 1380.46  5040.0 1379.01  5100.1 1380.04  5120.1 1378.27
  5139.0 1380.55  5160.1 1380.24  5200.1 1382.49  5220.1 1385.74  5250.2 1395.14
  5270.2 1399.42  5330.2 1409.41  5370.2 1412.38  5410.3 1413.96  5525.2 1414.35
#Mann=4,-1,0
  4397.6    0.07       0  4855.2    0.12       0  4995.5    0.05       0
  4999.5    0.12       0
Bank Sta=4995.5,4999.5
Exp/Cntr=0.3,0.1

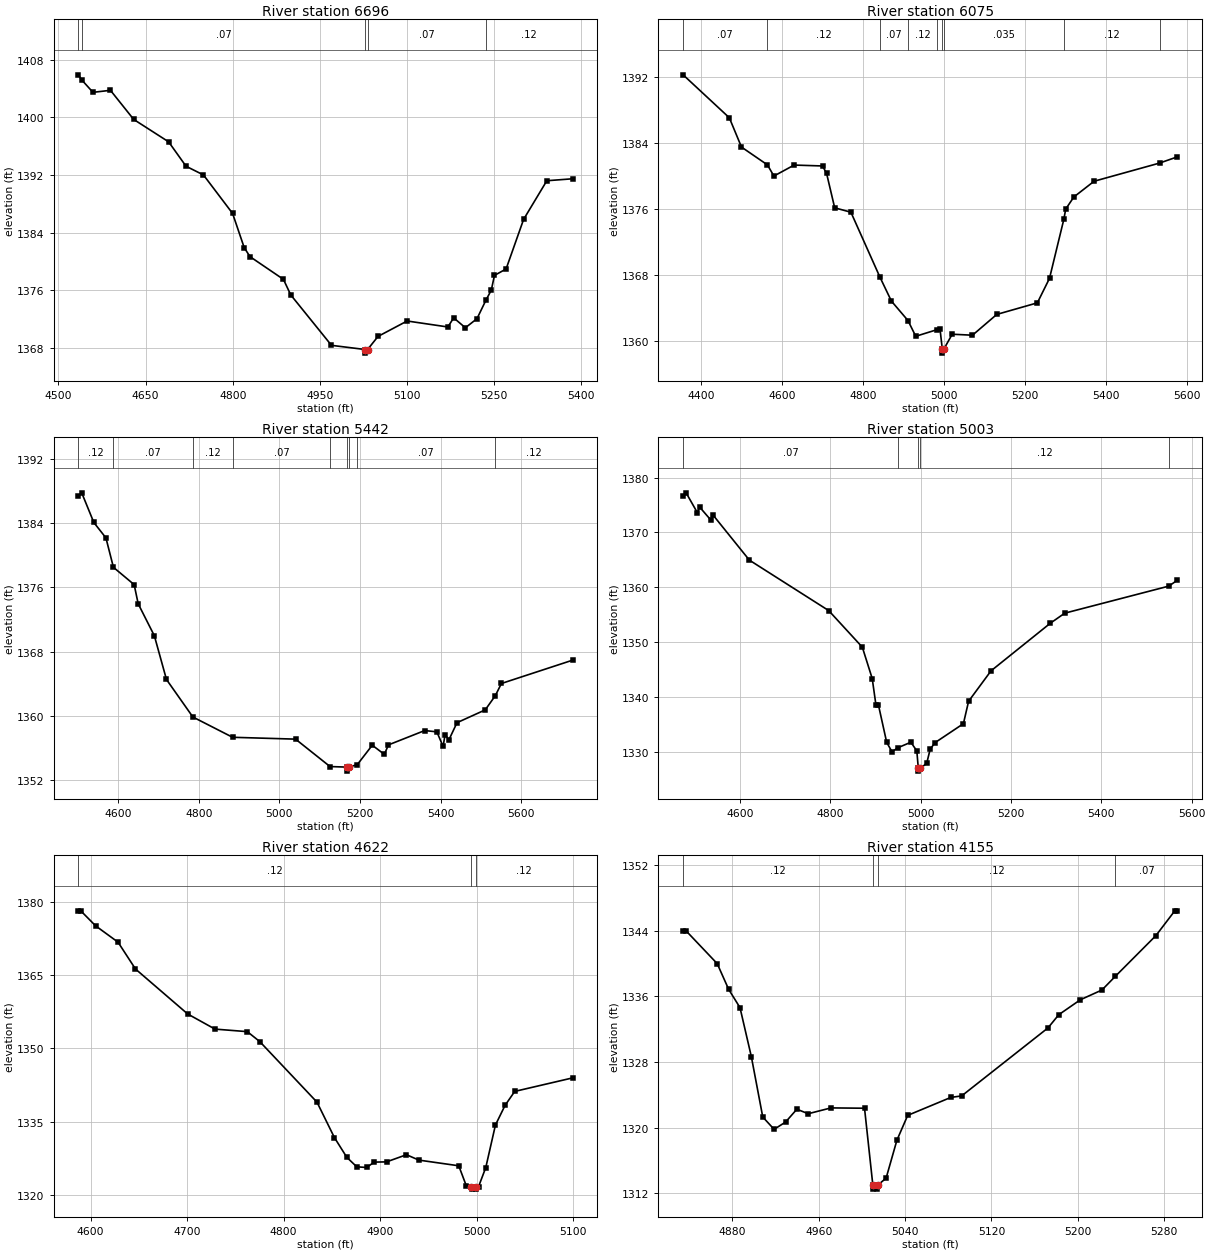
Type RM Length L Ch R = 1,6696,621,621,621
BEGIN DESCRIPTION:
Stream0162_DS 12.0
END DESCRIPTION:
XS GIS Cut Line= 3
      2059909.68     13860196.12      2060375.00     13860175.00
      2060759.28     13860151.39
#Sta/Elev= 30
  4534.2 1405.92  4540.9 1405.15  4559.5 1403.49  4589.6 1403.77  4629.6 1399.73
  4689.7 1396.62  4719.7 1393.23  4749.7 1392.02  4799.8 1386.68  4819.8 1381.93
  4829.8 1380.68  4887.3 1377.53  4899.9 1375.37  4970.0 1368.37  5028.1 1367.79
  5028.3 1367.29  5032.1 1367.79  5050.1 1369.61  5100.2 1371.75  5170.3 1370.92
  5180.3 1372.19  5200.4 1370.81  5220.4 1372.07  5235.8 1374.64  5245.0 1376.03
  5250.5 1378.08  5270.5 1378.97  5300.6 1385.85  5340.6 1391.22  5385.0 1391.49
#Mann=5,-1,0
  4534.2    0.12       0  4540.9    0.07       0  5028.1    0.05       0
  5032.1    0.07       0  5235.8    0.12       0
Bank Sta=5028.1,5032.1
Exp/Cntr=0.3,0.1

Type RM Length L Ch R = 1,6075,633,633,633
BEGIN DESCRIPTION:
Stream0162_DS 11.0
END DESCRIPTION:
XS GIS Cut Line= 3
      2059831.00     13860722.76      2060475.00     13860725.00
      2061050.73     13860710.91
#Sta/Elev= 30
  4356.0 1392.27  4470.0 1387.07  4500.0 1383.52  4564.1 1381.36  4580.0 1380.01
  4630.0 1381.34  4700.0 1381.23  4710.0 1380.33  4730.0 1376.16  4770.0 1375.63
  4841.5 1367.78  4870.0 1364.86  4910.8 1362.51  4930.0 1360.60  4982.4 1361.40
  4990.0 1361.45  4995.5 1359.06  4995.7 1358.56  4999.5 1359.06  5020.0 1360.85
  5070.0 1360.73  5130.0 1363.25  5230.1 1364.65  5260.1 1367.62  5295.4 1374.76
  5300.1 1376.01  5320.1 1377.47  5370.1 1379.38  5531.6 1381.58  5575.9 1382.34
#Mann=9,-1,0
  4356.0    0.07       0  4564.1    0.12       0  4841.5    0.07       0
  4910.8    0.12       0  4982.4   0.035       0  4995.5   0.035       0
  4999.5   0.035       0  5295.4    0.12       0  5531.6    0.07       0
Bank Sta=4995.5,4999.5
Exp/Cntr=0.3,0.1

Type RM Length L Ch R = 1,5442,439,439,439
BEGIN DESCRIPTION:
Stream0162_DS 10.0
END DESCRIPTION:
XS GIS Cut Line= 3
      2059976.43     13861259.95      2060475.00     13861275.00
      2061201.50     13861248.15
#Sta/Elev= 30
  4501.2 1387.37  4509.8 1387.79  4539.8 1384.09  4569.8 1382.17  4588.4 1378.50
  4639.8 1376.34  4649.8 1373.95  4689.9 1369.96  4719.9 1364.51  4785.4 1359.83
  4883.9 1357.30  5040.0 1357.07  5125.5 1353.65  5168.1 1353.58  5168.4 1353.08
  5172.1 1353.58  5193.0 1353.89  5230.2 1356.31  5260.2 1355.17  5270.2 1356.35
  5360.2 1358.14  5390.3 1357.98  5405.8 1356.16  5410.8 1357.63  5420.3 1356.99
  5440.3 1359.12  5510.3 1360.72  5535.2 1362.48  5550.4 1364.01  5727.0 1366.92
#Mann=9,-1,0
  4501.2    0.12       0  4588.4    0.07       0  4785.4    0.12       0
  4883.9    0.07       0  5125.5    0.12       0  5168.1    0.05       0
  5172.1    0.12       0  5193.0    0.07       0  5535.2    0.12       0
Bank Sta=5168.1,5172.1
Exp/Cntr=0.3,0.1

Type RM Length L Ch R = 1,5003,381,381,381
BEGIN DESCRIPTION:
Stream0162_DS 9.0
END DESCRIPTION:
XS GIS Cut Line= 3
      2060033.69     13861507.74      2060525.00     13861693.91
      2061059.55     13861499.81
#Sta/Elev= 30
  4474.6 1376.72  4481.2 1377.21  4506.0 1373.61  4511.3 1374.60  4536.1 1372.23
  4541.5 1373.09  4621.2 1364.94  4796.8 1355.74  4871.2 1349.07  4893.1 1343.35
  4901.4 1338.49  4906.7 1338.59  4925.1 1331.72  4936.9 1329.99  4949.8 1330.73
  4978.6 1331.74  4991.8 1330.16  4995.1 1326.97  4995.4 1326.47  4999.5 1326.97
  5013.7 1327.90  5021.3 1330.45  5031.9 1331.65  5094.9 1335.12  5106.4 1339.21
  5156.1 1344.76  5287.2 1353.43  5319.2 1355.27  5549.4 1360.20  5568.7 1361.29
#Mann=5,-1,0
  4474.6    0.07       0  4949.8    0.12       0  4995.1    0.05       0
  4999.5    0.12       0  5549.4    0.07       0
Bank Sta=4995.1,4999.5
Exp/Cntr=0.3,0.1

Type RM Length L Ch R = 1,4622,467,467,467
BEGIN DESCRIPTION:
Stream0162_DS 8.0
END DESCRIPTION:
XS GIS Cut Line= 3
      2060125.02     13861975.00      2060525.00     13862075.00
      2060625.01     13862075.00
#Sta/Elev= 30
  4587.3 1378.12  4589.9 1378.12  4605.3 1375.05  4628.5 1371.72  4646.6 1366.23
  4700.7 1357.04  4729.0 1353.95  4762.5 1353.43  4775.4 1351.40  4834.7 1339.02
  4852.7 1331.80  4865.6 1327.75  4875.9 1325.81  4886.2 1325.67  4893.9 1326.77
  4906.8 1326.82  4927.4 1328.28  4940.3 1327.18  4981.6 1326.02  4989.3 1321.99
  4994.7 1321.75  4995.0 1321.25  4999.0 1321.25  4999.3 1321.75  5002.1 1321.75
  5009.6 1325.66  5019.6 1334.34  5029.6 1338.37  5039.6 1341.22  5099.6 1343.98
#Mann=3,-1,0
  4587.3    0.12       0  4994.7    0.05       0  4999.3    0.12       0
Bank Sta=4994.7,4999.3
Exp/Cntr=0.3,0.1

Type RM Length L Ch R = 1,4155,414,414,414
BEGIN DESCRIPTION:
Stream0162_DS 7.0
END DESCRIPTION:
XS GIS Cut Line= 3
      2060175.00     13862425.00      2060325.00     13862475.00
      2060624.99     13862475.00
#Sta/Elev= 30
  4834.3 1343.99  4836.9 1343.99  4865.9 1339.97  4876.5 1336.84  4887.0 1334.61
  4897.5 1328.65  4908.1 1321.28  4918.6 1319.78  4929.2 1320.66  4939.7 1322.23
  4950.2 1321.68  4971.3 1322.39  5002.4 1322.35  5010.1 1312.99  5010.4 1312.49
  5014.4 1312.49  5014.8 1312.99  5022.4 1313.83  5032.4 1318.45  5042.4 1321.48
  5082.4 1323.67  5092.4 1323.85  5172.4 1332.14  5182.4 1333.75  5202.4 1335.57
  5222.4 1336.76  5234.9 1338.44  5272.4 1343.39  5289.9 1346.41  5292.4 1346.41
#Mann=4,-1,0
  4834.3    0.12       0  5010.1    0.05       0  5014.8    0.12       0
  5234.9    0.07       0
Bank Sta=5010.1,5014.8
Exp/Cntr=0.3,0.1

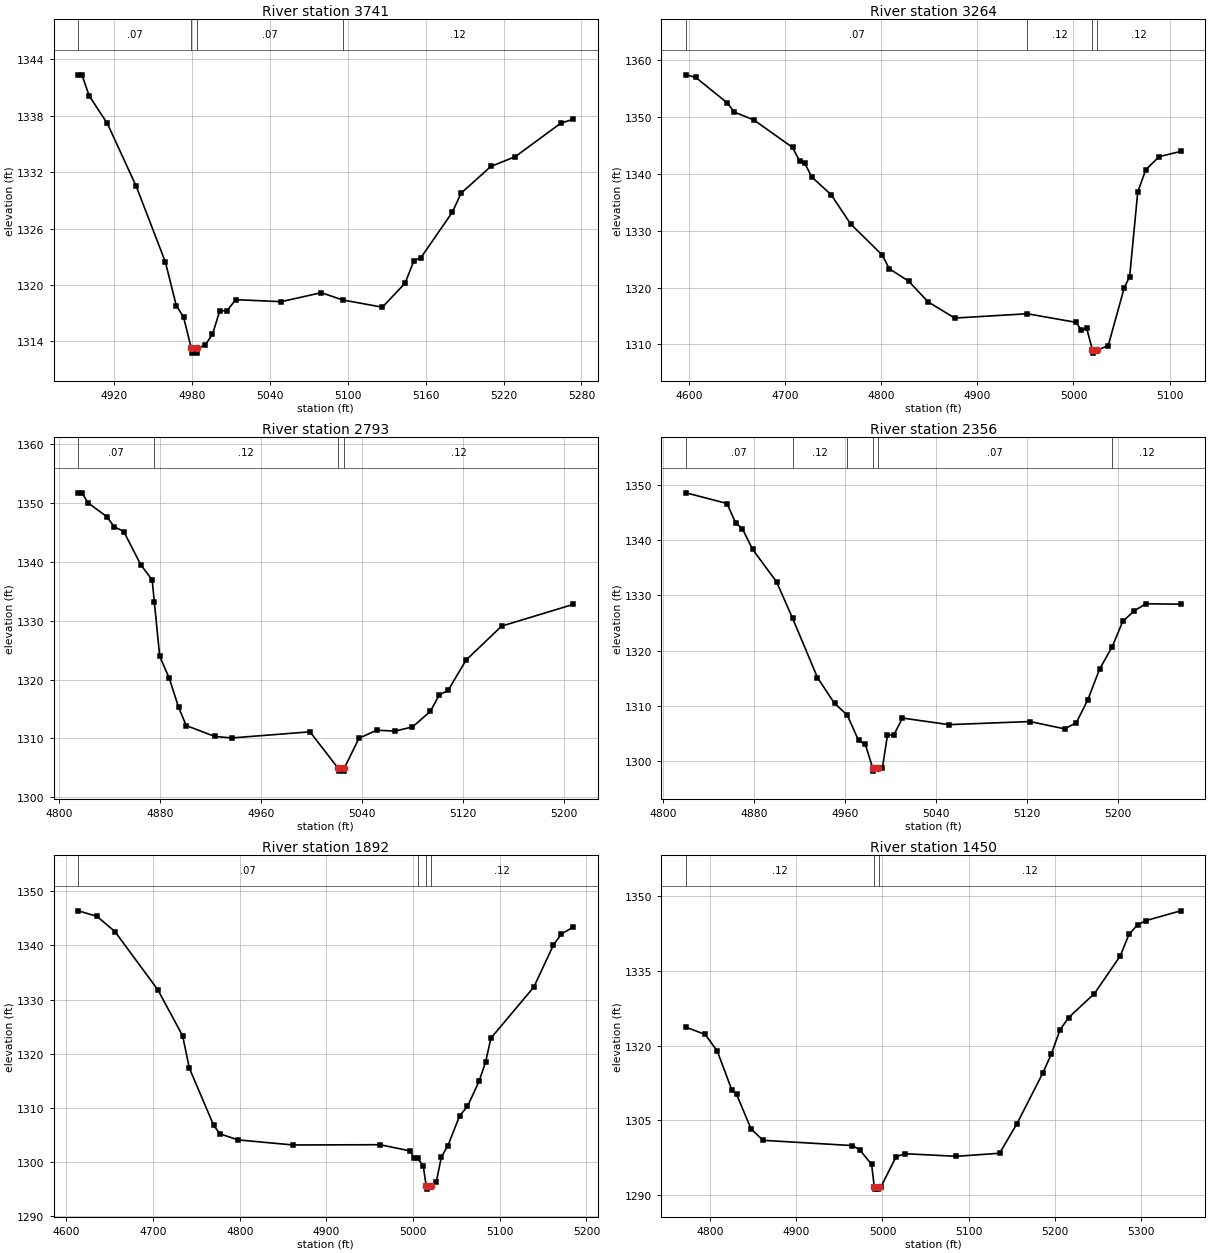
Type RM Length L Ch R = 1,3741,477,477,477
BEGIN DESCRIPTION:
Stream0162_DS 6.0
END DESCRIPTION:
XS GIS Cut Line= 3
      2060224.97     13862875.01      2060325.00     13862825.00
      2060575.01     13862725.00
#Sta/Elev= 30
  4892.4 1342.33  4895.2 1342.33  4900.8 1340.10  4914.8 1337.16  4937.1 1330.47
  4959.5 1322.44  4967.9 1317.81  4973.5 1316.59  4979.5 1313.26  4979.8 1312.76
  4983.9 1312.76  4984.2 1313.26  4990.3 1313.64  4995.8 1314.76  5001.4 1317.26
  5006.9 1317.26  5013.7 1318.44  5048.7 1318.23  5079.6 1319.18  5096.1 1318.41
  5126.7 1317.64  5144.2 1320.20  5151.0 1322.58  5156.4 1322.91  5180.6 1327.74
  5187.3 1329.75  5210.2 1332.59  5229.1 1333.64  5264.1 1337.19  5273.5 1337.60
#Mann=4,-1,0
  4892.4    0.07       0  4979.5    0.05       0  4984.2    0.07       0
  5096.1    0.12       0
Bank Sta=4979.5,4984.2
Exp/Cntr=0.3,0.1

Type RM Length L Ch R = 1,3264,471,471,471
BEGIN DESCRIPTION:
Stream0162_DS 5.0
END DESCRIPTION:
XS GIS Cut Line= 3
      2060124.99     13863175.00      2060525.00     13863225.00
      2060624.98     13863274.99
#Sta/Elev= 30
  4596.7 1357.45  4606.8 1357.00  4639.5 1352.53  4647.1 1350.88  4667.3 1349.51
  4707.6 1344.67  4715.1 1342.23  4720.2 1341.91  4727.7 1339.46  4747.9 1336.33
  4768.0 1331.21  4800.8 1325.76  4808.3 1323.32  4828.5 1321.13  4848.7 1317.49
  4876.4 1314.64  4951.9 1315.40  5002.6 1313.89  5008.2 1312.52  5013.8 1312.82
  5019.8 1308.97  5020.1 1308.47  5024.6 1308.97  5036.2 1309.80  5052.9 1320.00
  5058.5 1321.95  5066.9 1336.81  5075.3 1340.76  5089.3 1343.05  5111.6 1343.97
#Mann=4,-1,0
  4596.7    0.07       0  4951.9    0.12       0  5019.8    0.05       0
  5024.6    0.12       0
Bank Sta=5019.8,5024.6
Exp/Cntr=0.3,0.1

Type RM Length L Ch R = 1,2793,437,437,437
BEGIN DESCRIPTION:
Stream0162_DS 4.0
END DESCRIPTION:
XS GIS Cut Line= 3
      2060075.00     13863425.00      2060225.00     13863525.00
      2060374.99     13863674.99
#Sta/Elev= 30
  4814.9 1351.74  4817.9 1351.74  4822.4 1350.08  4837.4 1347.71  4843.4 1345.99
  4851.0 1345.15  4864.5 1339.50  4873.5 1336.93  4875.2 1333.25  4879.5 1323.95
  4887.0 1320.25  4894.5 1315.27  4900.5 1312.18  4923.1 1310.33  4936.6 1310.07
  4998.7 1311.11  5021.0 1304.93  5021.4 1304.43  5025.5 1304.43  5025.9 1304.93
  5037.6 1310.03  5051.7 1311.39  5065.9 1311.23  5080.0 1311.94  5094.2 1314.59
  5101.2 1317.37  5108.3 1318.17  5122.5 1323.31  5150.7 1329.08  5207.3 1332.76
#Mann=4,-1,0
  4814.9    0.07       0  4875.2    0.12       0  5021.0    0.05       0
  5025.9    0.12       0
Bank Sta=5021,5025.9
Exp/Cntr=0.3,0.1

Type RM Length L Ch R = 1,2356,464,464,464
BEGIN DESCRIPTION:
Stream0162_DS 3.0
END DESCRIPTION:
XS GIS Cut Line= 3
      2059824.96     13863724.98      2059975.00     13863825.00
      2060225.03     13863875.01
#Sta/Elev= 30
  4819.8 1348.55  4855.9 1346.62  4863.4 1343.15  4869.4 1342.07  4878.4 1338.34
  4899.5 1332.46  4913.6 1325.89  4935.5 1315.16  4950.5 1310.50  4961.7 1308.40
  4971.6 1303.81  4977.6 1303.08  4984.2 1298.76  4984.5 1298.26  4989.1 1298.76
  4992.6 1298.78  4997.1 1304.81  5002.7 1304.81  5010.3 1307.85  5051.1 1306.66
  5122.5 1307.22  5153.1 1305.89  5163.3 1307.03  5173.5 1311.20  5183.7 1316.68
  5194.8 1320.72  5204.1 1325.30  5214.3 1327.24  5224.5 1328.50  5255.1 1328.43
#Mann=6,-1,0
  4819.8    0.07       0  4913.6    0.12       0  4961.7    0.07       0
  4984.2    0.05       0  4989.1    0.07       0  5194.8    0.12       0
Bank Sta=4984.2,4989.1
Exp/Cntr=0.3,0.1

Type RM Length L Ch R = 1,1892,442,442,442
BEGIN DESCRIPTION:
Stream0162_DS 2.0
END DESCRIPTION:
XS GIS Cut Line= 3
      2059725.01     13864025.01      2060025.00     13864275.00
      2060125.02     13864425.02
#Sta/Elev= 30
  4613.6 1346.40  4635.1 1345.39  4655.9 1342.57  4705.4 1331.82  4734.0 1323.33
  4741.8 1317.34  4769.8 1306.81  4776.9 1305.24  4797.8 1304.11  4861.6 1303.17
  4961.8 1303.22  4996.9 1302.06  5000.8 1300.71  5005.1 1300.71  5011.6 1299.34
  5015.1 1295.52  5015.5 1295.02  5020.1 1295.52  5026.6 1296.29  5032.6 1300.98
  5040.1 1303.06  5053.7 1308.56  5062.7 1310.30  5076.2 1314.99  5083.7 1318.55
  5089.7 1322.89  5139.3 1332.34  5161.8 1340.07  5170.9 1342.11  5184.4 1343.37
#Mann=4,-1,0
  4613.6    0.07       0  5005.1    0.12       0  5015.1    0.05       0
  5020.1    0.12       0
Bank Sta=5015.1,5020.1
Exp/Cntr=0.3,0.1

Type RM Length L Ch R = 1,1450,0,0,0
BEGIN DESCRIPTION:
Stream0162_DS 1.0
END DESCRIPTION:
XS GIS Cut Line= 3
      2059525.00     13864475.00      2059725.00     13864575.00
      2060074.99     13864575.00
#Sta/Elev= 30
  4772.2 1323.68  4794.6 1322.22  4808.5 1318.87  4825.3 1311.08  4830.9 1310.15
  4847.7 1303.20  4861.6 1300.93  4965.1 1299.87  4973.4 1299.06  4987.4 1296.11
  4990.5 1291.61  4990.9 1291.11  4995.1 1291.11  4995.5 1291.61  4998.3 1291.61
  5015.8 1297.61  5025.8 1298.24  5085.8 1297.71  5135.8 1298.33  5155.8 1304.22
  5185.8 1314.41  5195.8 1318.27  5205.8 1323.14  5215.8 1325.61  5245.8 1330.46
  5275.8 1338.04  5285.8 1342.35  5295.8 1344.28  5305.8 1345.15  5345.8 1347.10
#Mann=3,-1,0
  4772.2    0.12       0  4990.5    0.05       0  4995.5    0.12       0
Bank Sta=4990.5,4995.5
Exp/Cntr=0.3,0.1

Chan Stop Cuts=-1