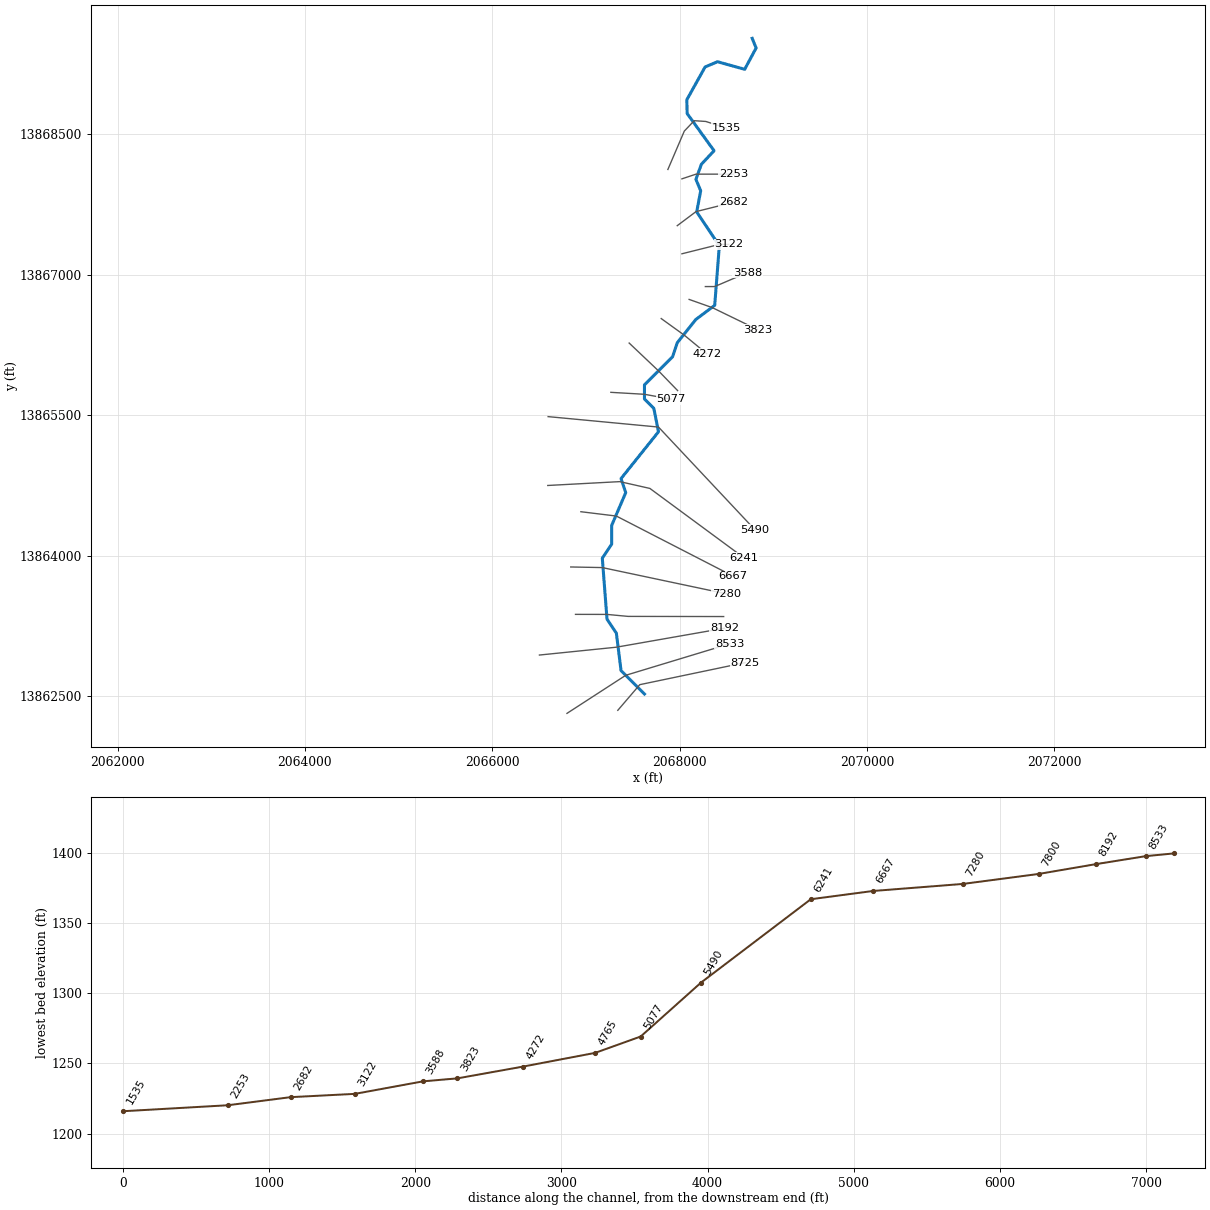
--- Stream0163_DS.prj (project) ---

Proj Title=Stream0163_DS Base Level Engineering
Current Plan=p01
Default Exp/Contr=0.3,0.1
English Units
Geom File=g01
Flow File=f01
Plan File=p01
BEGIN DESCRIPTION:
Stream0163_DS
END DESCRIPTION:

--- Stream0163_DS.p01 (plan) ---

Plan Title=Multiple Run
Short Identifier=Multiple
Geom File=g01
Flow File=f01
Subcritical Flow
K Sum by GR= 0
Std Step Tol= 0.01
Critical Tol= 0.01
Num of Std Step Trials= 20
Max Error Tol= 0.3
Flow Tol Ratio= 0.001
Split Flow NTrial= 30
Split Flow Tol= 0.02
Split Flow Ratio= 0.02
Log Output Level= 0
Friction Slope Method= 1
Unsteady Friction Slope Method= 2
Unsteady Bridges Friction Slope Method= 1
Parabolic Critical Depth
Global Vel Dist=  1 , 1 , 1
Global Log Level= 0
CheckData=True
Encroach Param= -1, 0, 0, 0
BEGIN DESCRIPTION:
Multiple Run
END DESCRIPTION:

--- Stream0163_DS.f01 (steady flow) ---

Flow Title=Multiple
Number of Profiles=7
Profile Names=10-year,25-year,50-year,1pct_min,100-year,1pct_plu,500-year
River Rch & RM= Stream0163_DS,Reach-1,8725
     569     924    1250     823    1642    3277    2794
River Rch & RM= Stream0163_DS,Reach-1,8192
    1724    3010    4272    2939    5863   11699   10921
River Rch & RM= Stream0163_DS,Reach-1,3588
    1793    3124    4426    3037    6060   12092   11236
Boundary for River Rch & Prof#=Stream0163_DS,Reach-1,1
Up Type=0
Dn Type=3
Dn Slope=0.005
Boundary for River Rch & Prof#=Stream0163_DS,Reach-1,2
Up Type=0
Dn Type=3
Dn Slope=0.005
Boundary for River Rch & Prof#=Stream0163_DS,Reach-1,3
Up Type=0
Dn Type=3
Dn Slope=0.005
Boundary for River Rch & Prof#=Stream0163_DS,Reach-1,4
Up Type=0
Dn Type=3
Dn Slope=0.005
Boundary for River Rch & Prof#=Stream0163_DS,Reach-1,5
Up Type=0
Dn Type=3
Dn Slope=0.005
Boundary for River Rch & Prof#=Stream0163_DS,Reach-1,6
Up Type=0
Dn Type=3
Dn Slope=0.005
Boundary for River Rch & Prof#=Stream0163_DS,Reach-1,7
Up Type=0
Dn Type=3
Dn Slope=0.005

--- Stream0163_DS.g01 (geometry) ---

Geom Title=Existing Conditions

River Reach=Stream0163_DS,Reach-1
Reach XY= 30
      2067625.00     13862525.00      2067375.00     13862775.00
      2067325.00     13863175.00      2067225.00     13863325.00
      2067175.00     13863975.00      2067275.00     13864125.00
      2067275.00     13864325.00      2067425.00     13864675.00
      2067375.00     13864825.00      2067775.00     13865325.00
      2067725.00     13865575.00      2067625.00     13865675.00
      2067625.00     13865825.00      2067925.00     13866125.00
      2067975.00     13866275.00      2068175.00     13866525.00
      2068375.00     13866675.00      2068424.33     13867311.09
      2068182.81     13867671.59      2068225.29     13867897.84
      2068174.19     13868019.97      2068233.14     13868181.06
      2068367.92     13868325.00      2068080.45     13868722.55
      2068077.34     13868869.48      2068272.45     13869219.28
      2068404.82     13869275.29      2068695.08     13869194.27
      2068817.11     13869421.74      2068775.00     13869525.00

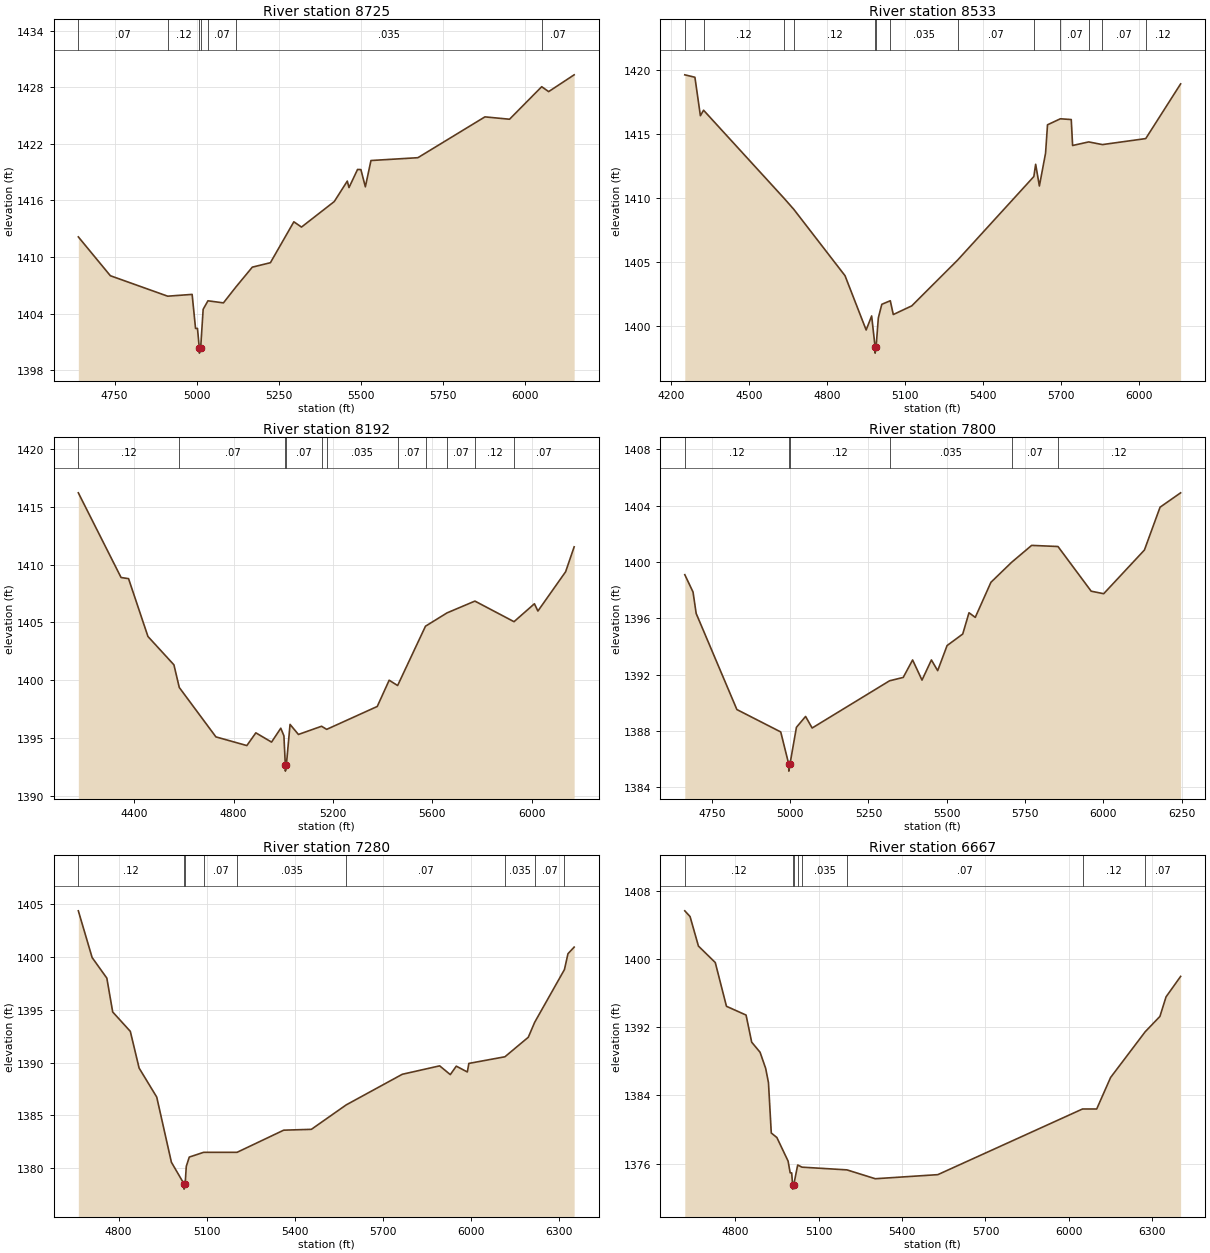
Type RM Length L Ch R = 1,8725,192,192,192
BEGIN DESCRIPTION:
Stream0163_DS 17.0
END DESCRIPTION:
XS GIS Cut Line= 3
      2067340.51     13862351.19      2067575.00     13862625.00
      2068701.10     13862860.69
#Sta/Elev= 30
  4639.5 1412.13  4737.1 1408.01  4911.8 1405.84  4986.3 1406.03  4996.7 1402.42
  5002.6 1402.42  5008.2 1400.30  5008.5 1399.80  5012.2 1400.30  5019.9 1404.45
  5034.5 1405.35  5081.7 1405.13  5119.8 1406.82  5169.7 1408.92  5224.8 1409.39
  5296.3 1413.73  5319.6 1413.17  5419.5 1415.88  5459.2 1418.05  5464.3 1417.36
  5490.4 1419.28  5500.6 1419.27  5514.2 1417.44  5531.3 1420.23  5674.3 1420.53
  5878.6 1424.86  5953.6 1424.61  6051.6 1428.06  6072.8 1427.54  6150.5 1429.32
#Mann=7,-1,0
  4639.5    0.07       0  4911.8    0.12       0  5008.2    0.05       0
  5012.2    0.12       0  5034.5    0.07       0  5119.8   0.035       0
  6051.6    0.07       0
Bank Sta=5008.2,5012.2
Exp/Cntr=0.3,0.1

Type RM Length L Ch R = 1,8533,341,341,341
BEGIN DESCRIPTION:
Stream0163_DS 16.0
END DESCRIPTION:
XS GIS Cut Line= 3
      2066797.79     13862318.53      2067425.00     13862725.00
      2068534.97     13863061.29
#Sta/Elev= 30
  4252.6 1419.63  4291.5 1419.44  4312.6 1416.43  4324.8 1416.86  4635.7 1409.94
  4672.0 1409.10  4868.9 1403.91  4950.2 1399.66  4971.3 1400.76  4984.5 1398.35
  4984.7 1397.85  4988.5 1398.35  4997.0 1400.60  5010.4 1401.67  5043.0 1401.95
  5054.6 1400.87  5125.7 1401.55  5302.4 1405.14  5595.2 1411.67  5602.2 1412.63
  5616.5 1410.93  5640.3 1413.50  5647.8 1415.72  5697.2 1416.19  5739.1 1416.13
  5744.3 1414.10  5806.3 1414.38  5859.0 1414.17  6025.6 1414.64  6159.8 1418.92
#Mann=13,-1,0
  4252.6   0.035       0  4324.8    0.12       0  4635.7   0.035       0
  4672.0    0.12       0  4984.5    0.05       0  4988.5    0.12       0
  5043.0   0.035       0  5302.4    0.07       0  5595.2   0.035       0
  5697.2    0.07       0  5806.3   0.035       0  5859.0    0.07       0
  6025.6    0.12       0
Bank Sta=4984.5,4988.5
Exp/Cntr=0.3,0.1

Type RM Length L Ch R = 1,8192,392,392,392
BEGIN DESCRIPTION:
Stream0163_DS 15.0
END DESCRIPTION:
XS GIS Cut Line= 3
      2066503.76     13862941.28      2067325.00     13863025.00
      2068478.77     13863227.46
#Sta/Elev= 30
  4174.5 1416.21  4346.6 1408.89  4376.8 1408.79  4454.9 1403.79  4559.5 1401.34
  4581.1 1399.38  4728.6 1395.11  4853.2 1394.36  4889.4 1395.46  4952.7 1394.66
  4989.9 1395.86  5002.5 1395.20  5008.2 1392.65  5008.4 1392.15  5012.2 1392.65
  5027.2 1396.19  5060.9 1395.32  5154.1 1396.03  5174.7 1395.76  5378.4 1397.74
  5426.4 1400.01  5460.4 1399.55  5572.7 1404.68  5659.4 1405.83  5771.7 1406.85
  5929.2 1405.07  6011.4 1406.62  6025.4 1405.99  6137.1 1409.39  6171.4 1411.54
#Mann=11,-1,0
  4174.5    0.12       0  4581.1    0.07       0  5008.2    0.05       0
  5012.2    0.07       0  5154.1    0.12       0  5174.7   0.035       0
  5460.4    0.07       0  5572.7   0.035       0  5659.4    0.07       0
  5771.7    0.12       0  5929.2    0.07       0
Bank Sta=5008.2,5012.2
Exp/Cntr=0.3,0.1

Type RM Length L Ch R = 1,7800,520,520,520
BEGIN DESCRIPTION:
Stream0163_DS 14.0
END DESCRIPTION:
XS GIS Cut Line= 4
      2066888.70     13863375.47      2067225.00     13863375.00
      2067450.46     13863353.83      2068470.61     13863352.24
#Sta/Elev= 30
  4663.7 1399.09  4690.0 1397.86  4700.0 1396.34  4830.0 1389.52  4970.0 1387.93
  4995.5 1385.65  4995.8 1385.15  4999.5 1385.65  5020.1 1388.26  5049.3 1389.03
  5070.3 1388.21  5317.3 1391.56  5361.0 1391.80  5391.0 1393.04  5421.0 1391.61
  5451.0 1393.04  5471.0 1392.28  5501.0 1394.06  5551.0 1394.88  5571.0 1396.39
  5591.0 1396.06  5641.0 1398.55  5707.1 1399.97  5771.0 1401.17  5855.1 1401.09
  5961.0 1397.92  6001.0 1397.74  6131.0 1400.84  6181.0 1403.88  6246.6 1404.90
#Mann=6,-1,0
  4663.7    0.12       0  4995.5    0.05       0  4999.5    0.12       0
  5317.3   0.035       0  5707.1    0.07       0  5855.1    0.12       0
Bank Sta=4995.5,4999.5
Exp/Cntr=0.3,0.1

Type RM Length L Ch R = 1,7280,613,613,613
BEGIN DESCRIPTION:
Stream0163_DS 13.0
END DESCRIPTION:
XS GIS Cut Line= 3
      2066837.96     13863881.44      2067175.00     13863875.00
      2068497.90     13863595.05
#Sta/Elev= 30
  4662.9 1404.40  4709.9 1399.97  4760.0 1398.02  4780.0 1394.81  4840.0 1392.97
  4870.0 1389.49  4930.0 1386.74  4980.0 1380.56  5022.9 1378.51  5023.1 1378.01
  5026.9 1378.51  5030.7 1380.17  5040.9 1381.05  5089.7 1381.50  5203.7 1381.50
  5362.6 1383.60  5456.9 1383.68  5575.7 1386.00  5766.6 1388.90  5894.0 1389.70
  5930.2 1388.87  5950.6 1389.67  5988.3 1389.12  5993.4 1389.93  6116.3 1390.56
  6195.9 1392.41  6217.7 1393.83  6319.1 1398.83  6331.1 1400.33  6352.2 1400.96
#Mann=9,-1,0
  4662.9    0.12       0  5022.9    0.05       0  5026.9    0.12       0
  5089.7    0.07       0  5203.7   0.035       0  5575.7    0.07       0
  6116.3   0.035       0  6217.7    0.07       0  6319.1    0.12       0
Bank Sta=5022.9,5026.9
Exp/Cntr=0.3,0.1

Type RM Length L Ch R = 1,6667,426,426,426
BEGIN DESCRIPTION:
Stream0163_DS 12.0
END DESCRIPTION:
XS GIS Cut Line= 3
      2066946.22     13864471.34      2067325.00     13864425.00
      2068571.62     13863783.49
#Sta/Elev= 30
  4618.4 1405.68  4637.3 1405.01  4667.5 1401.54  4728.0 1399.61  4768.3 1394.47
  4838.8 1393.44  4859.0 1390.26  4889.2 1389.07  4909.3 1387.18  4919.4 1385.50
  4929.5 1379.59  4949.6 1379.06  4989.9 1376.30  4997.5 1374.91  5002.8 1374.91
  5006.3 1373.50  5006.5 1373.00  5010.3 1373.50  5024.5 1375.83  5040.0 1375.58
  5201.7 1375.26  5303.7 1374.22  5528.6 1374.70  6049.1 1382.41  6100.1 1382.41
  6150.1 1386.11  6274.3 1391.47  6327.5 1393.28  6349.6 1395.58  6402.0 1397.98
#Mann=8,-1,0
  4618.4    0.12       0  5006.3    0.05       0  5010.3    0.12       0
  5024.5    0.07       0  5040.0   0.035       0  5201.7    0.07       0
  6049.1    0.12       0  6274.3    0.07       0
Bank Sta=5006.3,5010.3
Exp/Cntr=0.3,0.1

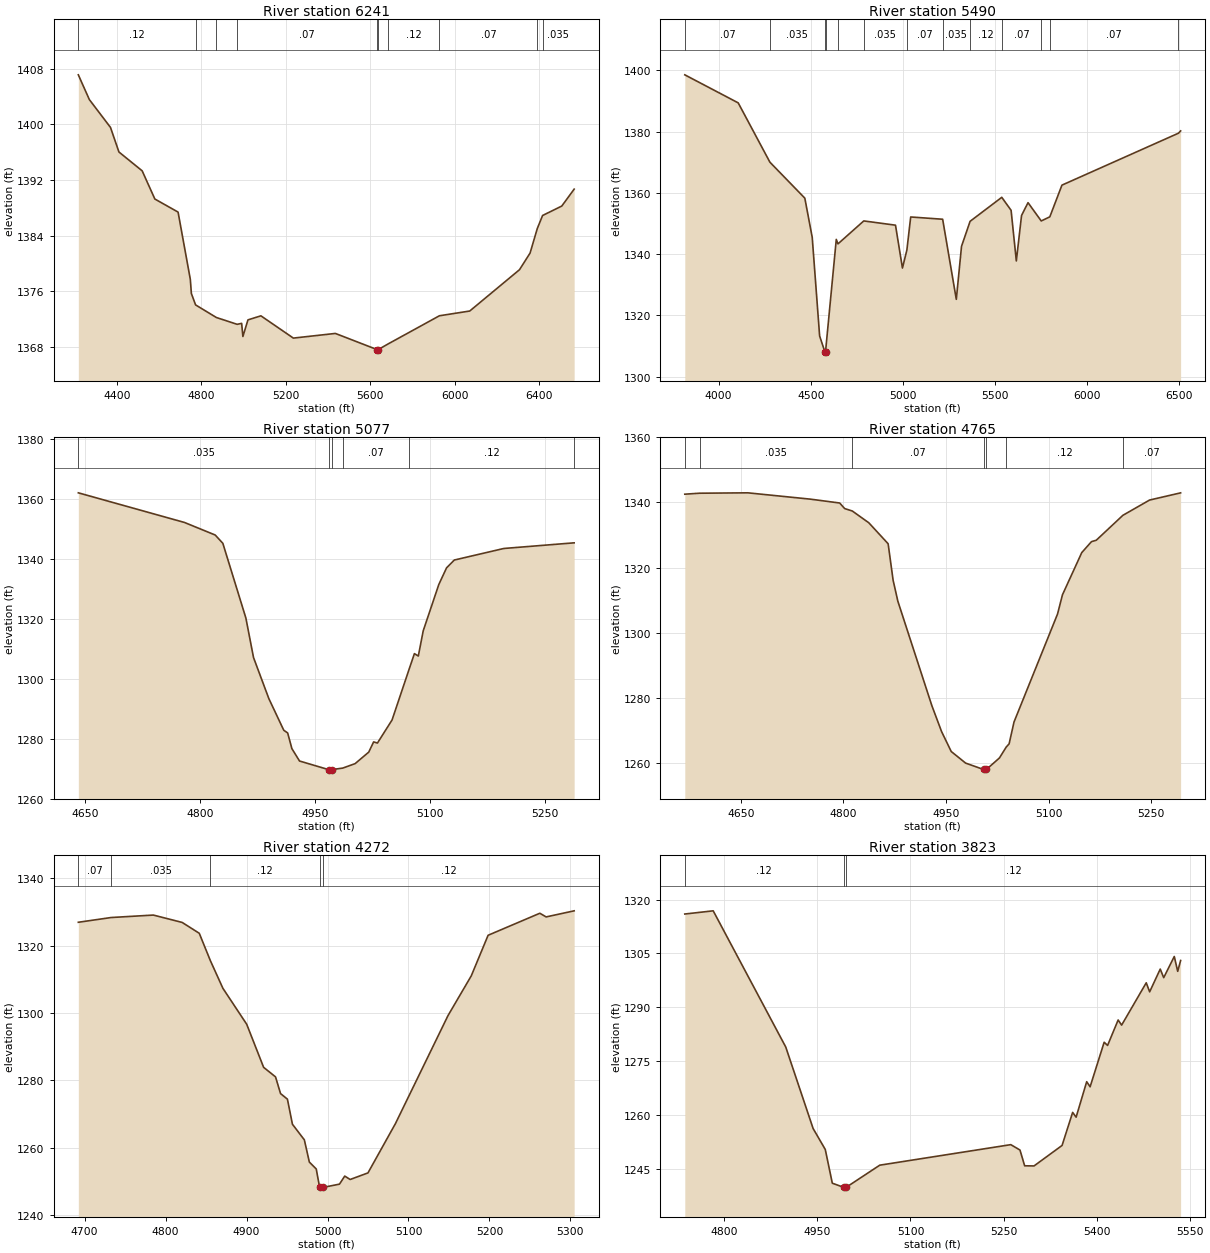
Type RM Length L Ch R = 1,6241,751,751,751
BEGIN DESCRIPTION:
Stream0163_DS 11.0
END DESCRIPTION:
XS GIS Cut Line= 4
      2066592.73     13864751.51      2067361.73     13864792.59
      2067683.20     13864719.92      2068690.18     13863977.42
#Sta/Elev= 30
  4216.3 1407.12  4268.6 1403.56  4368.8 1399.56  4408.8 1396.03  4519.0 1393.32
  4579.1 1389.27  4689.2 1387.39  4747.3 1377.72  4752.3 1375.68  4772.3 1374.05
  4870.8 1372.24  4969.3 1371.26  4990.6 1371.40  4996.5 1369.51  5020.5 1371.90
  5082.0 1372.48  5235.8 1369.28  5435.0 1369.95  5633.5 1367.62  5633.8 1367.12
  5637.5 1367.62  5685.0 1368.44  5928.3 1372.49  6072.0 1373.17  6308.0 1379.11
  6358.1 1381.50  6392.0 1385.00  6417.4 1386.90  6508.5 1388.26  6567.1 1390.69
#Mann=10,-1,0
  4216.3    0.12       0  4772.3    0.07       0  4870.8   0.035       0
  4969.3    0.07       0  5633.5    0.05       0  5637.5    0.07       0
  5685.0    0.12       0  5928.3    0.07       0  6392.0    0.12       0
  6417.4   0.035       0
Bank Sta=5633.5,5637.5
Exp/Cntr=0.3,0.1

Type RM Length L Ch R = 1,5490,413,413,413
BEGIN DESCRIPTION:
Stream0163_DS 10.0
END DESCRIPTION:
XS GIS Cut Line= 3
      2066596.37     13865486.56      2067775.00     13865375.00
      2068806.88     13864276.01
#Sta/Elev= 30
  3816.1 1398.58  4106.0 1389.42  4278.2 1370.03  4467.6 1358.29  4507.8 1345.48
  4548.0 1313.26  4576.1 1308.16  4576.4 1307.66  4580.1 1308.16  4638.4 1344.82
  4647.5 1343.35  4787.6 1350.85  4959.8 1349.46  4997.5 1335.46  5021.6 1341.34
  5042.3 1352.14  5215.8 1351.40  5289.9 1325.23  5318.2 1342.55  5364.7 1350.72
  5536.7 1358.56  5587.3 1354.31  5615.7 1337.78  5644.0 1352.62  5679.2 1356.82
  5750.9 1350.84  5797.5 1352.19  5863.3 1362.54  6495.8 1379.51  6507.5 1380.25
#Mann=13,-1,0
  3816.1    0.07       0  4278.2   0.035       0  4576.1   0.035       0
  4580.1   0.035       0  4647.5    0.12       0  4787.6   0.035       0
  5021.6    0.07       0  5215.8   0.035       0  5364.7    0.12       0
  5536.7    0.07       0  5750.9    0.12       0  5797.5    0.07       0
  6495.8    0.12       0
Bank Sta=4576.1,4580.1
Exp/Cntr=0.3,0.1

Type RM Length L Ch R = 1,5077,312,312,312
BEGIN DESCRIPTION:
Stream0163_DS 9.0
END DESCRIPTION:
XS GIS Cut Line= 3
      2067266.51     13865745.84      2067625.00     13865725.00
      2067909.03     13865673.31
#Sta/Elev= 30
  4640.9 1362.15  4779.6 1352.25  4819.7 1348.06  4829.7 1345.29  4859.8 1320.33
  4869.8 1307.13  4889.8 1293.42  4909.3 1282.85  4914.4 1281.94  4919.9 1276.71
  4929.9 1272.57  4967.9 1269.69  4968.2 1269.19  4971.9 1269.69  4986.3 1270.20
  5002.5 1271.69  5020.3 1275.53  5026.7 1278.95  5031.7 1278.57  5050.8 1286.28
  5073.5 1303.55  5080.0 1308.44  5085.1 1307.63  5091.5 1316.06  5111.8 1331.48
  5122.0 1337.09  5132.1 1339.70  5196.8 1343.56  5288.3 1345.44  5288.7 1345.44
#Mann=6,-1,0
  4640.9   0.035       0  4967.9    0.05       0  4971.9   0.035       0
  4986.3    0.07       0  5073.5    0.12       0  5288.3    0.07       0
Bank Sta=4967.9,4971.9
Exp/Cntr=0.3,0.1

Type RM Length L Ch R = 1,4765,493,493,493
BEGIN DESCRIPTION:
Stream0163_DS 8.0
END DESCRIPTION:
XS GIS Cut Line= 3
      2067461.72     13866272.02      2067775.00     13865975.00
      2067978.91     13865764.59
#Sta/Elev= 30
  4568.3 1342.55  4589.8 1342.85  4660.4 1342.97  4752.2 1341.02  4794.7 1339.84
  4802.0 1338.13  4813.1 1337.39  4837.2 1333.78  4865.5 1327.33  4872.8 1316.10
  4879.7 1309.69  4929.4 1277.62  4943.6 1269.66  4957.7 1263.54  4978.8 1259.97
  5005.1 1258.01  5005.3 1257.51  5009.1 1258.01  5028.2 1261.56  5038.2 1264.93
  5042.3 1265.87  5049.5 1272.60  5113.1 1305.75  5120.3 1311.66  5148.5 1324.61
  5162.7 1327.98  5169.7 1328.41  5208.6 1336.06  5247.6 1340.75  5293.0 1342.96
#Mann=7,-1,0
  4568.3    0.07       0  4589.8   0.035       0  4813.1    0.07       0
  5005.1    0.05       0  5009.1    0.07       0  5038.2    0.12       0
  5208.6    0.07       0
Bank Sta=5005.1,5009.1
Exp/Cntr=0.3,0.1

Type RM Length L Ch R = 1,4272,449,449,449
BEGIN DESCRIPTION:
Stream0163_DS 7.0
END DESCRIPTION:
XS GIS Cut Line= 3
      2067803.83     13866533.54      2068053.44     13866353.44
      2068288.33     13866159.35
#Sta/Elev= 30
  4692.2 1326.97  4732.7 1328.38  4784.9 1329.11  4820.5 1326.92  4841.6 1323.70
  4855.3 1315.58  4870.8 1307.36  4900.2 1296.69  4921.1 1283.90  4935.8 1281.07
  4942.0 1276.11  4950.5 1274.45  4956.7 1267.00  4971.4 1262.37  4977.6 1255.76
  4986.1 1253.72  4990.3 1248.24  4990.5 1247.74  4994.3 1248.24  5014.8 1249.22
  5021.3 1251.61  5028.0 1250.60  5050.0 1252.56  5083.9 1267.18  5148.9 1299.28
  5177.6 1311.06  5198.4 1323.11  5262.3 1329.65  5270.1 1328.56  5304.7 1330.37
#Mann=5,-1,0
  4692.2    0.07       0  4732.7   0.035       0  4855.3    0.12       0
  4990.3    0.05       0  4994.3    0.12       0
Bank Sta=4990.3,4994.3
Exp/Cntr=0.3,0.1

Type RM Length L Ch R = 1,3823,235,235,235
BEGIN DESCRIPTION:
Stream0163_DS 6.0
END DESCRIPTION:
XS GIS Cut Line= 3
      2068101.96     13866737.70      2068349.85     13866649.85
      2068830.73     13866416.28
#Sta/Elev= 30
  4737.0 1315.98  4782.7 1316.87  4899.4 1278.93  4943.4 1256.23  4963.0 1250.38
  4974.3 1240.99  4992.6 1239.84  4992.8 1239.34  4996.6 1239.84  5050.6 1246.01
  5261.4 1251.73  5276.2 1250.23  5283.7 1245.84  5298.8 1245.80  5343.9 1251.51
  5360.9 1260.71  5366.5 1259.39  5383.5 1269.27  5389.0 1267.85  5411.6 1280.26
  5417.1 1279.37  5434.1 1286.46  5439.7 1285.03  5479.3 1296.82  5484.8 1294.30
  5501.8 1300.64  5507.4 1298.25  5524.4 1304.15  5529.9 1300.01  5534.6 1303.03
#Mann=3,-1,0
  4737.0    0.12       0  4992.6    0.05       0  4996.6    0.12       0
Bank Sta=4992.6,4996.6
Exp/Cntr=0.3,0.1

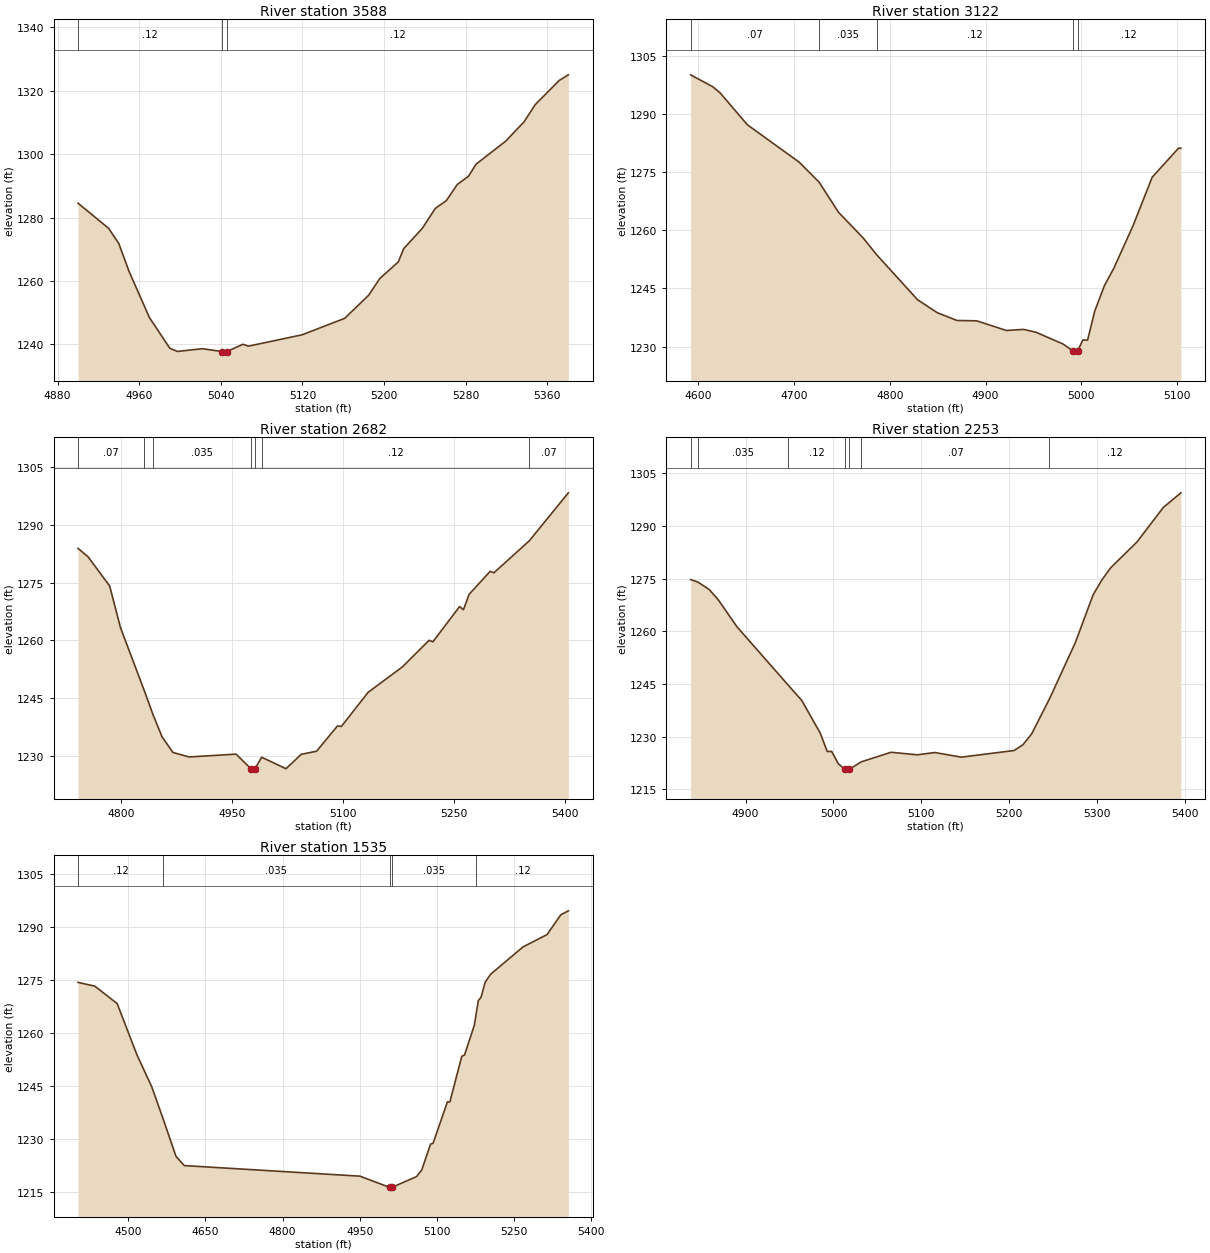
Type RM Length L Ch R = 1,3588,466,466,466
BEGIN DESCRIPTION:
Stream0163_DS 5.0
END DESCRIPTION:
XS GIS Cut Line= 3
      2068274.96     13866875.00      2068375.00     13866875.00
      2068724.98     13867024.99
#Sta/Elev= 30
  4900.0 1284.52  4930.0 1276.59  4940.0 1271.78  4950.0 1263.02  4970.0 1248.43
  4990.0 1238.76  4997.5 1237.75  5021.8 1238.62  5041.4 1237.72  5041.7 1237.22
  5045.8 1237.72  5061.7 1240.01  5067.1 1239.42  5119.7 1243.00  5161.4 1248.18
  5185.0 1255.49  5195.9 1260.76  5214.0 1265.97  5219.4 1270.21  5237.6 1276.59
  5250.3 1282.87  5261.2 1285.34  5272.0 1290.47  5282.9 1293.03  5290.2 1296.81
  5319.2 1304.05  5337.3 1310.16  5348.2 1315.57  5371.8 1323.24  5380.8 1325.02
#Mann=3,-1,0
  4900.0    0.12       0  5041.4    0.05       0  5045.8    0.12       0
Bank Sta=5041.4,5045.8
Exp/Cntr=0.3,0.1

Type RM Length L Ch R = 1,3122,440,440,440
BEGIN DESCRIPTION:
Stream0163_DS 4.0
END DESCRIPTION:
XS GIS Cut Line= 3
      2068024.96     13867224.99      2068425.00     13867325.00
      2068524.95     13867325.00
#Sta/Elev= 30
  4591.8 1300.24  4615.0 1297.15  4622.8 1295.53  4651.1 1287.33  4705.2 1277.67
  4726.0 1272.51  4746.5 1264.66  4772.2 1258.04  4786.3 1253.70  4828.9 1242.10
  4849.5 1238.75  4870.1 1236.73  4890.8 1236.64  4921.7 1234.15  4939.7 1234.42
  4952.6 1233.70  4981.0 1230.64  4991.6 1228.79  4991.9 1228.29  4995.8 1228.29
  4996.1 1228.79  5001.6 1231.67  5006.6 1231.67  5014.1 1239.17  5024.1 1245.70
  5034.1 1250.28  5054.1 1261.23  5074.1 1273.77  5101.6 1281.27  5104.1 1281.27
#Mann=5,-1,0
  4591.8    0.07       0  4726.0   0.035       0  4786.3    0.12       0
  4991.6    0.05       0  4996.1    0.12       0
Bank Sta=4991.6,4996.1
Exp/Cntr=0.3,0.1

Type RM Length L Ch R = 1,2682,429,429,429
BEGIN DESCRIPTION:
Stream0163_DS 3.0
END DESCRIPTION:
XS GIS Cut Line= 3
      2067975.00     13867525.00      2068175.00     13867675.00
      2068574.99     13867775.00
#Sta/Elev= 30
  4742.1 1283.91  4755.6 1281.74  4784.8 1274.13  4799.4 1263.31  4831.6 1246.88
  4843.5 1240.57  4855.6 1234.87  4870.2 1230.81  4892.1 1229.63  4955.6 1230.36
  4976.3 1226.44  4976.6 1225.94  4980.8 1226.44  4990.1 1229.56  5023.0 1226.57
  5043.6 1230.32  5064.3 1231.12  5092.6 1237.72  5097.8 1237.57  5133.8 1246.43
  5180.2 1253.07  5216.3 1260.00  5221.4 1259.60  5257.5 1268.78  5262.7 1267.95
  5270.4 1271.98  5298.8 1277.94  5303.9 1277.57  5351.5 1285.86  5404.4 1298.38
#Mann=7,-1,0
  4742.1    0.07       0  4831.6    0.12       0  4843.5   0.035       0
  4976.3    0.05       0  4980.8   0.035       0  4990.1    0.12       0
  5351.5    0.07       0
Bank Sta=4976.3,4980.8
Exp/Cntr=0.3,0.1

Type RM Length L Ch R = 1,2253,718,718,718
BEGIN DESCRIPTION:
Stream0163_DS 2.0
END DESCRIPTION:
XS GIS Cut Line= 3
      2068024.99     13868025.00      2068175.00     13868075.00
      2068574.97     13868075.00
#Sta/Elev= 30
  4837.4 1274.76  4845.5 1274.07  4858.5 1271.95  4869.0 1268.96  4890.1 1261.33
  4948.3 1244.73  4963.9 1240.33  4985.0 1230.99  4992.9 1225.78  4998.0 1225.78
  5005.5 1222.27  5013.2 1220.67  5013.6 1220.17  5017.8 1220.67  5031.8 1222.83
  5065.5 1225.54  5095.5 1224.82  5115.5 1225.47  5145.5 1224.15  5205.5 1226.04
  5215.5 1227.65  5225.5 1230.73  5245.9 1240.76  5275.5 1256.89  5295.5 1270.38
  5305.5 1274.64  5315.5 1278.10  5345.5 1285.48  5375.5 1295.32  5395.5 1299.48
#Mann=7,-1,0
  4837.4    0.07       0  4845.5   0.035       0  4948.3    0.12       0
  5013.2    0.05       0  5017.8    0.12       0  5031.8    0.07       0
  5245.9    0.12       0
Bank Sta=5013.2,5017.8
Exp/Cntr=0.3,0.1

Type RM Length L Ch R = 1,1535,0,0,0
BEGIN DESCRIPTION:
Stream0163_DS 1.0
END DESCRIPTION:
XS GIS Cut Line= 5
      2067875.01     13868125.03      2068050.44     13868534.80
      2068156.13     13868645.79      2068279.68     13868637.67
      2068498.89     13868567.13
#Sta/Elev= 30
  4402.3 1274.30  4434.9 1273.24  4478.4 1268.31  4516.5 1253.93  4545.6 1244.80
  4567.9 1235.64  4592.7 1225.15  4608.9 1222.55  4950.4 1219.56  5007.9 1216.40
  5008.2 1215.90  5012.5 1216.40  5060.3 1219.44  5070.3 1221.26  5087.5 1228.60
  5092.5 1228.88  5120.3 1240.54  5125.1 1240.54  5148.3 1253.44  5153.6 1253.79
  5172.7 1262.22  5176.8 1265.93  5180.4 1269.18  5185.6 1270.05  5193.7 1274.35
  5204.2 1276.59  5267.3 1284.33  5314.0 1287.81  5340.8 1293.41  5355.4 1294.52
#Mann=5,-1,0
  4402.3    0.12       0  4567.9   0.035       0  5007.9   0.035       0
  5012.5   0.035       0  5176.8    0.12       0
Bank Sta=5007.9,5012.5
Exp/Cntr=0.3,0.1

Chan Stop Cuts=-1