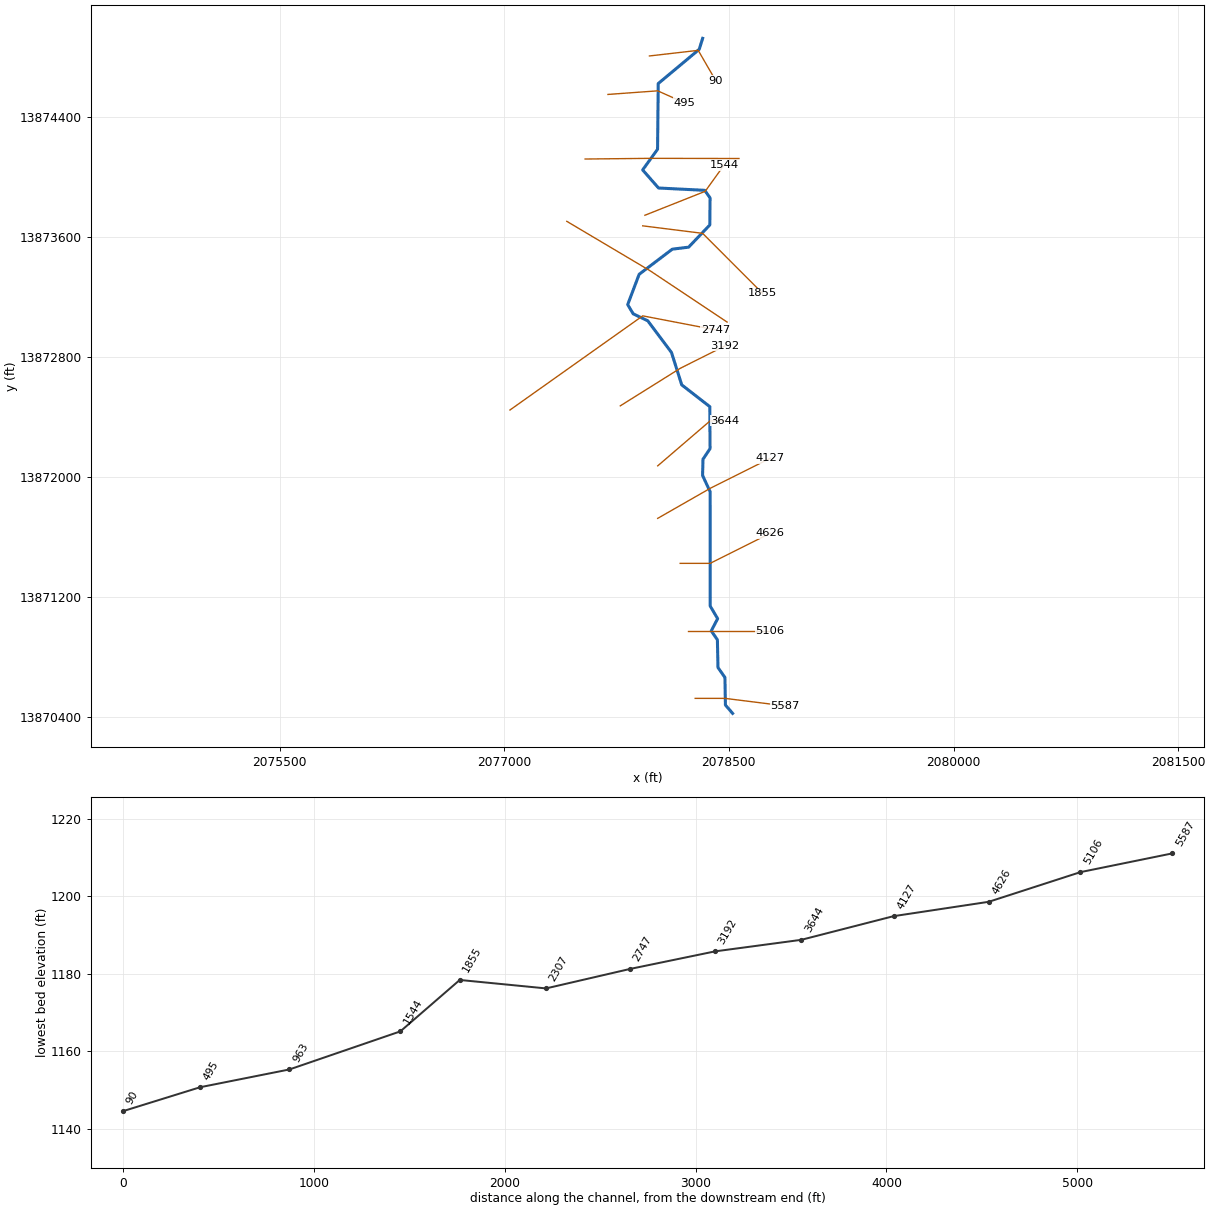
--- Stream0164_DS.prj (project) ---

Proj Title=Stream0164_DS Base Level Engineering
Current Plan=p01
Default Exp/Contr=0.3,0.1
English Units
Geom File=g01
Flow File=f01
Plan File=p01
BEGIN DESCRIPTION:
Stream0164_DS
END DESCRIPTION:

--- Stream0164_DS.p01 (plan) ---

Plan Title=Multiple Run
Short Identifier=Multiple
Geom File=g01
Flow File=f01
Subcritical Flow
K Sum by GR= 0
Std Step Tol= 0.01
Critical Tol= 0.01
Num of Std Step Trials= 20
Max Error Tol= 0.3
Flow Tol Ratio= 0.001
Split Flow NTrial= 30
Split Flow Tol= 0.02
Split Flow Ratio= 0.02
Log Output Level= 0
Friction Slope Method= 1
Unsteady Friction Slope Method= 2
Unsteady Bridges Friction Slope Method= 1
Parabolic Critical Depth
Global Vel Dist=  1 , 1 , 1
Global Log Level= 0
CheckData=True
Encroach Param= -1, 0, 0, 0
BEGIN DESCRIPTION:
Multiple Run
END DESCRIPTION:

--- Stream0164_DS.f01 (steady flow) ---

Flow Title=Multiple
Number of Profiles=7
Profile Names=10-year,25-year,50-year,1pct_min,100-year,1pct_plu,500-year
River Rch & RM= Stream0164_DS,Reach-1,5587
    1510    2587    3622    2456    4899    9776    8866
Boundary for River Rch & Prof#=Stream0164_DS,Reach-1,1
Up Type=0
Dn Type=3
Dn Slope=0.005
Boundary for River Rch & Prof#=Stream0164_DS,Reach-1,2
Up Type=0
Dn Type=3
Dn Slope=0.005
Boundary for River Rch & Prof#=Stream0164_DS,Reach-1,3
Up Type=0
Dn Type=3
Dn Slope=0.005
Boundary for River Rch & Prof#=Stream0164_DS,Reach-1,4
Up Type=0
Dn Type=3
Dn Slope=0.005
Boundary for River Rch & Prof#=Stream0164_DS,Reach-1,5
Up Type=0
Dn Type=3
Dn Slope=0.005
Boundary for River Rch & Prof#=Stream0164_DS,Reach-1,6
Up Type=0
Dn Type=3
Dn Slope=0.005
Boundary for River Rch & Prof#=Stream0164_DS,Reach-1,7
Up Type=0
Dn Type=3
Dn Slope=0.005

--- Stream0164_DS.g01 (geometry) ---

Geom Title=Existing Conditions

River Reach=Stream0164_DS,Reach-1
Reach XY= 30
      2078525.00     13870425.00      2078477.00     13870480.37
      2078473.78     13870664.49      2078427.38     13870730.53
      2078423.45     13870915.41      2078382.59     13870975.01
      2078425.11     13871056.54      2078375.54     13871140.21
      2078375.09     13871902.31      2078324.52     13872011.20
      2078327.25     13872119.06      2078374.48     13872190.22
      2078372.83     13872469.57      2078185.39     13872614.90
      2078116.86     13872831.06      2077958.50     13873042.05
      2077861.37     13873088.46      2077824.47     13873149.88
      2077901.16     13873352.14      2078122.57     13873519.48
      2078231.17     13873532.86      2078372.94     13873680.85
      2078374.53     13873861.29      2078338.74     13873911.80
      2078030.43     13873927.17      2077924.43     13874047.79
      2078023.94     13874185.44      2078028.53     13874623.55
      2078301.96     13874851.54      2078325.00     13874925.00

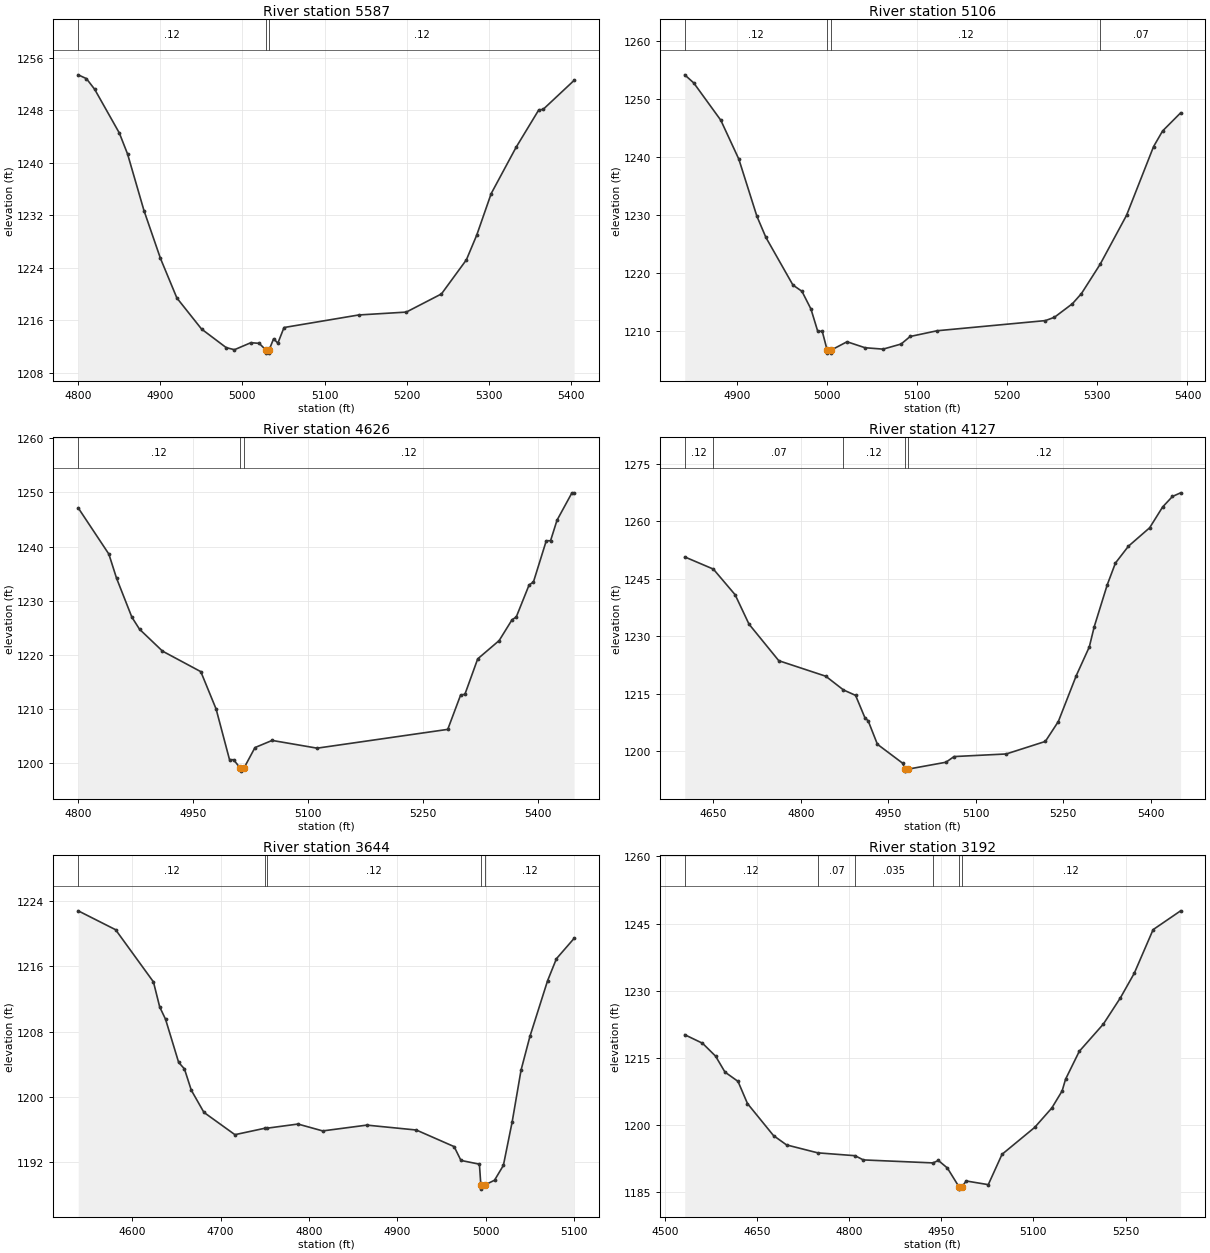
Type RM Length L Ch R = 1,5587,481,481,481
BEGIN DESCRIPTION:
Stream0164_DS 12.0
END DESCRIPTION:
XS GIS Cut Line= 3
      2078275.05     13870525.00      2078475.00     13870525.00
      2078875.03     13870475.00
#Sta/Elev= 30
  4800.4 1253.40  4810.4 1252.82  4820.4 1251.20  4850.4 1244.54  4860.4 1241.35
  4880.4 1232.72  4900.4 1225.45  4920.4 1219.41  4950.4 1214.68  4980.4 1211.85
  4990.4 1211.53  5010.4 1212.60  5020.5 1212.50  5028.5 1211.51  5028.8 1211.01
  5032.4 1211.01  5032.6 1211.51  5038.1 1213.21  5043.2 1212.52  5050.7 1214.91
  5141.4 1216.82  5199.4 1217.26  5242.2 1220.03  5272.5 1225.22  5285.1 1228.99
  5302.7 1235.32  5332.9 1242.35  5360.6 1248.07  5365.7 1248.12  5403.5 1252.55
#Mann=3,-1,0
  4800.4    0.12       0  5028.5    0.05       0  5032.6    0.12       0
Bank Sta=5028.5,5032.6
Exp/Cntr=0.3,0.1

Type RM Length L Ch R = 1,5106,480,480,480
BEGIN DESCRIPTION:
Stream0164_DS 11.0
END DESCRIPTION:
XS GIS Cut Line= 3
      2078224.99     13870975.00      2078375.00     13870975.00
      2078774.99     13870975.00
#Sta/Elev= 30
  4842.4 1254.17  4852.4 1252.77  4882.4 1246.34  4902.4 1239.63  4922.4 1229.80
  4932.4 1226.14  4962.4 1217.92  4972.4 1216.84  4982.4 1213.78  4989.9 1209.95
  4994.9 1209.95  5000.4 1206.68  5000.6 1206.18  5004.2 1206.18  5004.5 1206.68
  5022.4 1208.14  5042.4 1207.11  5062.4 1206.87  5082.4 1207.75  5092.4 1209.05
  5122.4 1210.04  5242.4 1211.79  5252.4 1212.36  5272.4 1214.70  5282.4 1216.45
  5303.1 1221.49  5332.4 1229.94  5362.4 1241.80  5372.4 1244.49  5392.4 1247.61
#Mann=4,-1,0
  4842.4    0.12       0  5000.4    0.05       0  5004.5    0.12       0
  5303.1    0.07       0
Bank Sta=5000.4,5004.5
Exp/Cntr=0.3,0.1

Type RM Length L Ch R = 1,4626,499,499,499
BEGIN DESCRIPTION:
Stream0164_DS 10.0
END DESCRIPTION:
XS GIS Cut Line= 3
      2078175.00     13871425.00      2078375.00     13871425.00
      2078774.99     13871624.99
#Sta/Elev= 30
  4800.0 1247.14  4840.0 1238.61  4850.0 1234.17  4870.0 1226.97  4880.0 1224.74
  4910.0 1220.69  4960.0 1216.90  4980.0 1209.99  4997.5 1200.64  5002.8 1200.64
  5011.8 1199.03  5012.1 1198.53  5016.1 1199.03  5030.7 1202.88  5053.1 1204.20
  5111.8 1202.77  5282.3 1206.24  5299.1 1212.58  5304.7 1212.72  5321.4 1219.26
  5349.4 1222.64  5366.2 1226.48  5371.7 1226.99  5388.5 1232.92  5394.1 1233.44
  5410.9 1241.07  5416.5 1241.08  5424.9 1244.86  5444.4 1249.92  5447.2 1249.92
#Mann=3,-1,0
  4800.0    0.12       0  5011.8    0.05       0  5016.1    0.12       0
Bank Sta=5011.8,5016.1
Exp/Cntr=0.3,0.1

Type RM Length L Ch R = 1,4127,483,483,483
BEGIN DESCRIPTION:
Stream0164_DS 9.0
END DESCRIPTION:
XS GIS Cut Line= 3
      2078024.96     13871724.98      2078375.00     13871925.00
      2078775.03     13872125.01
#Sta/Elev= 30
  4601.0 1250.73  4650.1 1247.55  4687.4 1240.86  4711.2 1233.19  4762.3 1223.64
  4842.9 1219.59  4873.1 1216.02  4894.0 1214.59  4909.9 1208.78  4915.6 1207.94
  4931.4 1201.83  4974.6 1196.90  4979.0 1195.32  4979.3 1194.82  4983.3 1195.32
  5048.9 1197.14  5062.9 1198.62  5152.3 1199.30  5219.4 1202.57  5241.7 1207.77
  5272.5 1219.77  5294.8 1227.24  5303.2 1232.49  5325.6 1243.47  5339.6 1249.13
  5361.9 1253.53  5398.3 1258.34  5420.6 1263.78  5437.4 1266.51  5451.4 1267.46
#Mann=5,-1,0
  4601.0    0.12       0  4650.1    0.07       0  4873.1    0.12       0
  4979.0    0.05       0  4983.3    0.12       0
Bank Sta=4979,4983.3
Exp/Cntr=0.3,0.1

Type RM Length L Ch R = 1,3644,452,452,452
BEGIN DESCRIPTION:
Stream0164_DS 8.0
END DESCRIPTION:
XS GIS Cut Line= 3
      2078024.98     13872074.99      2078375.00     13872375.00
      2078475.00     13872375.00
#Sta/Elev= 30
  4538.9 1222.76  4581.2 1220.45  4624.0 1214.07  4631.1 1211.00  4637.7 1209.50
  4652.5 1204.23  4659.1 1203.42  4666.8 1200.83  4681.1 1198.11  4716.2 1195.38
  4750.2 1196.17  4753.0 1196.18  4787.5 1196.68  4815.5 1195.84  4865.4 1196.55
  4921.4 1195.95  4964.2 1193.92  4971.9 1192.23  4992.8 1191.77  4994.4 1189.22
  4994.7 1188.72  4998.8 1189.22  5009.9 1189.81  5019.9 1191.62  5029.9 1196.98
  5039.9 1203.28  5049.9 1207.39  5069.9 1214.21  5079.9 1216.90  5099.9 1219.39
#Mann=5,-1,0
  4538.9    0.12       0  4750.2    0.07       0  4753.0    0.12       0
  4994.4    0.05       0  4998.8    0.12       0
Bank Sta=4994.4,4998.8
Exp/Cntr=0.3,0.1

Type RM Length L Ch R = 1,3192,445,445,445
BEGIN DESCRIPTION:
Stream0164_DS 7.0
END DESCRIPTION:
XS GIS Cut Line= 3
      2077774.96     13872474.97      2078175.00     13872725.00
      2078475.04     13872875.02
#Sta/Elev= 30
  4532.5 1220.20  4561.4 1218.30  4582.7 1215.42  4598.0 1211.86  4619.2 1209.79
  4634.6 1204.84  4677.0 1197.69  4698.2 1195.61  4748.9 1193.84  4809.7 1193.20
  4823.2 1192.26  4936.7 1191.59  4945.3 1192.14  4960.0 1190.46  4979.0 1186.24
  4979.3 1185.74  4983.5 1186.24  4990.7 1187.56  5026.6 1186.74  5049.0 1193.51
  5102.1 1199.51  5130.0 1203.84  5146.8 1207.65  5152.4 1210.27  5174.7 1216.49
  5213.9 1222.57  5241.8 1228.46  5264.2 1233.91  5294.9 1243.65  5339.7 1247.85
#Mann=6,-1,0
  4532.5    0.12       0  4748.9    0.07       0  4809.7   0.035       0
  4936.7    0.12       0  4979.0    0.05       0  4983.5    0.12       0
Bank Sta=4979,4983.5
Exp/Cntr=0.3,0.1

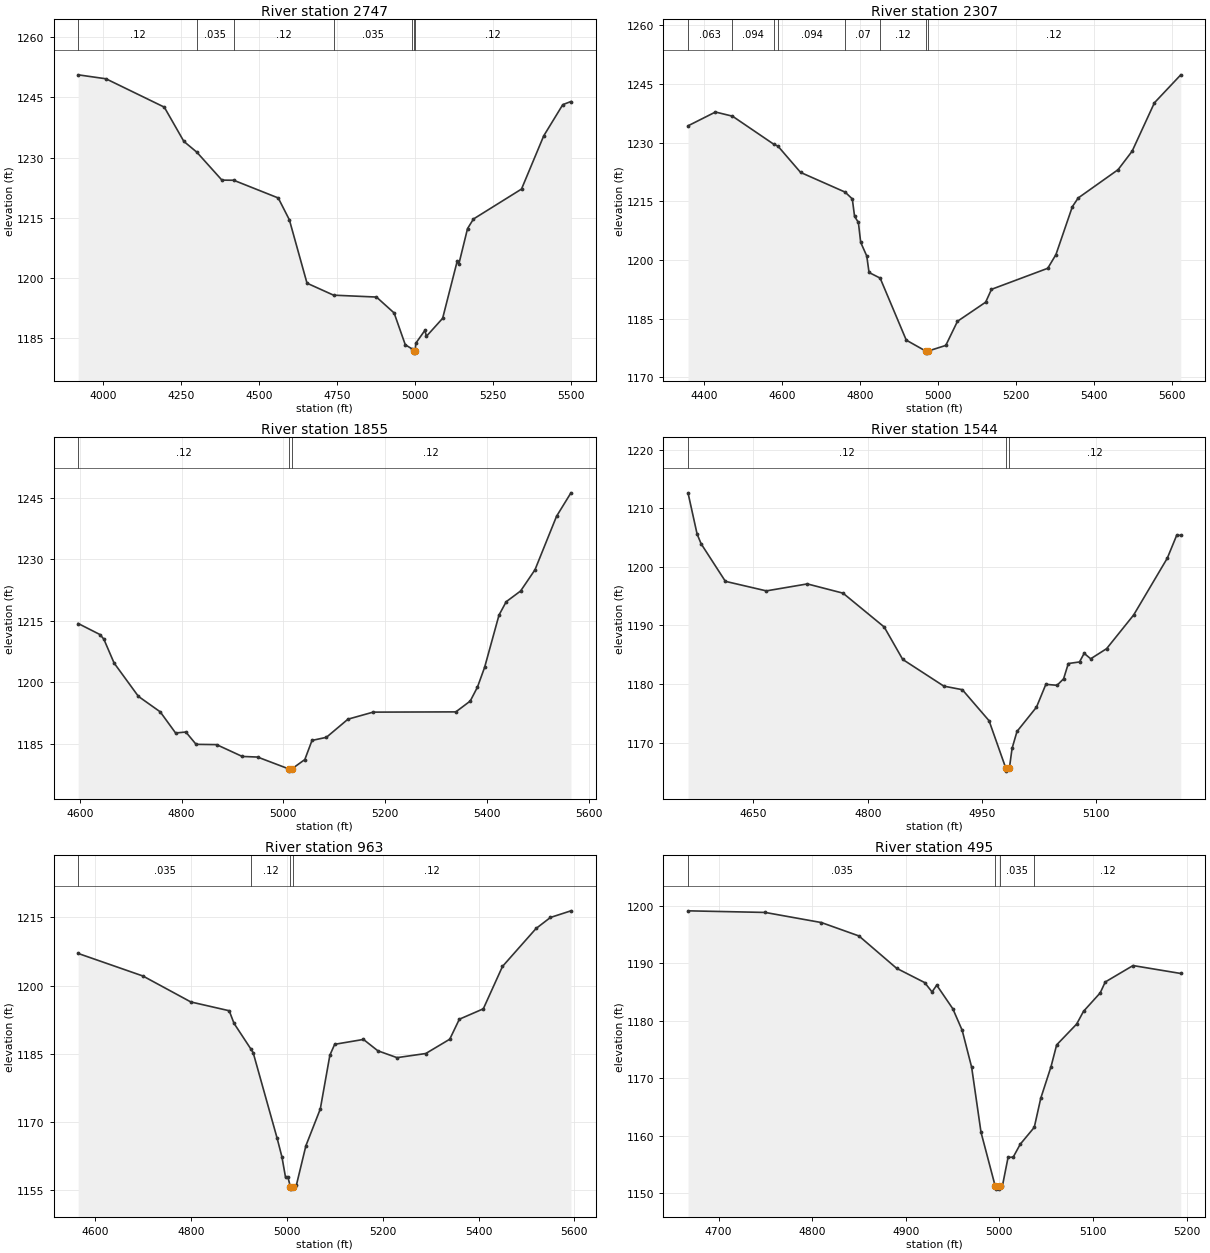
Type RM Length L Ch R = 1,2747,440,440,440
BEGIN DESCRIPTION:
Stream0164_DS 6.0
END DESCRIPTION:
XS GIS Cut Line= 3
      2077038.71     13872447.42      2077925.00     13873075.00
      2078410.74     13872981.73
#Sta/Elev= 30
  3919.2 1250.64  4008.4 1249.65  4195.4 1242.58  4258.2 1234.03  4299.8 1231.34
  4380.3 1224.37  4418.0 1224.34  4560.9 1219.92  4596.6 1214.47  4653.2 1198.66
  4738.4 1195.67  4876.0 1195.20  4932.6 1191.23  4968.4 1183.30  4988.7 1182.33
  4995.5 1181.71  4995.8 1181.21  5000.0 1181.71  5002.1 1183.67  5031.2 1186.88
  5036.3 1185.41  5088.2 1189.89  5135.1 1204.19  5140.2 1203.43  5168.1 1212.28
  5187.1 1214.67  5341.2 1222.14  5412.5 1235.42  5473.6 1243.20  5499.8 1243.98
#Mann=7,-1,0
  3919.2    0.12       0  4299.8   0.035       0  4418.0    0.12       0
  4738.4   0.035       0  4988.7    0.12       0  4995.5    0.05       0
  5000.0    0.12       0
Bank Sta=4995.5,5000
Exp/Cntr=0.3,0.1

Type RM Length L Ch R = 1,2307,452,452,452
BEGIN DESCRIPTION:
Stream0164_DS 5.0
END DESCRIPTION:
XS GIS Cut Line= 3
      2077418.02     13873705.08      2077975.00     13873375.00
      2078487.97     13873033.65
#Sta/Elev= 30
  4358.3 1234.30  4428.7 1237.83  4472.3 1236.77  4577.7 1229.63  4589.0 1229.10
  4647.0 1222.39  4761.1 1217.36  4779.6 1215.62  4785.4 1211.16  4795.2 1209.60
  4801.1 1204.52  4816.7 1201.01  4822.5 1196.81  4851.0 1195.37  4918.0 1179.51
  4968.4 1176.69  4968.7 1176.19  4973.0 1176.69  5019.3 1178.16  5049.3 1184.33
  5121.5 1189.21  5136.5 1192.50  5280.8 1197.88  5301.8 1201.39  5343.9 1213.64
  5358.9 1215.86  5461.1 1223.09  5497.2 1227.82  5554.3 1240.19  5621.9 1247.34
#Mann=8,-1,0
  4358.3   0.063       0  4472.3   0.094       0  4577.7   0.063       0
  4589.0   0.094       0  4761.1    0.07       0  4851.0    0.12       0
  4968.4    0.05       0  4973.0    0.12       0
Bank Sta=4968.4,4973
Exp/Cntr=0.3,0.1

Type RM Length L Ch R = 1,1855,311,311,311
BEGIN DESCRIPTION:
Stream0164_DS 4.0
END DESCRIPTION:
XS GIS Cut Line= 3
      2077924.98     13873675.00      2078325.00     13873625.00
      2078724.99     13873225.01
#Sta/Elev= 30
  4596.6 1214.35  4639.4 1211.66  4647.0 1210.55  4667.2 1204.72  4715.0 1196.59
  4757.9 1192.82  4788.1 1187.67  4808.3 1187.90  4828.4 1184.90  4868.7 1184.83
  4919.1 1181.95  4949.3 1181.80  5011.5 1178.87  5011.9 1178.37  5016.2 1178.87
  5042.2 1181.19  5056.3 1185.85  5084.6 1186.61  5127.0 1191.03  5176.5 1192.75
  5339.1 1192.81  5367.4 1195.45  5381.6 1198.85  5395.7 1203.68  5424.0 1216.42
  5438.1 1219.66  5466.4 1222.27  5494.7 1227.45  5537.1 1240.49  5565.4 1246.20
#Mann=3,-1,0
  4596.6    0.12       0  5011.5    0.05       0  5016.2    0.12       0
Bank Sta=5011.5,5016.2
Exp/Cntr=0.3,0.1

Type RM Length L Ch R = 1,1544,581,581,581
BEGIN DESCRIPTION:
Stream0164_DS 3.0
END DESCRIPTION:
XS GIS Cut Line= 3
      2077939.35     13873745.47      2078342.11     13873905.19
      2078467.11     13874078.80
#Sta/Elev= 30
  4564.0 1212.65  4575.9 1205.63  4581.2 1203.95  4613.1 1197.53  4666.9 1195.90
  4720.7 1197.09  4767.6 1195.51  4821.7 1189.73  4846.0 1184.19  4900.0 1179.63
  4924.3 1179.02  4959.4 1173.72  4981.4 1165.61  4981.7 1165.11  4986.1 1165.61
  4989.6 1168.98  4996.1 1171.89  5021.7 1176.04  5034.0 1179.94  5048.7 1179.77
  5057.3 1180.88  5063.5 1183.49  5078.2 1183.76  5084.3 1185.23  5092.9 1184.30
  5113.8 1186.03  5149.4 1191.80  5193.5 1201.49  5205.8 1205.39  5211.2 1205.39
#Mann=3,-1,0
  4564.0    0.12       0  4981.4    0.05       0  4986.1    0.12       0
Bank Sta=4981.4,4986.1
Exp/Cntr=0.3,0.1

Type RM Length L Ch R = 1,963,468,468,468
BEGIN DESCRIPTION:
Stream0164_DS 2.0
END DESCRIPTION:
XS GIS Cut Line= 3
      2077540.01     13874120.47      2077975.00     13874125.00
      2078567.78     13874123.94
#Sta/Elev= 30
  4565.0 1207.04  4700.0 1202.09  4800.0 1196.39  4880.0 1194.46  4890.0 1191.70
  4925.3 1186.04  4930.0 1185.25  4980.0 1166.45  4990.0 1162.35  4997.5 1157.88
  5002.5 1157.88  5007.7 1155.79  5008.0 1155.29  5012.4 1155.79  5020.0 1156.11
  5040.0 1164.83  5070.0 1172.89  5090.0 1184.71  5100.0 1187.09  5160.0 1188.16
  5190.0 1185.67  5230.0 1184.16  5290.0 1185.07  5340.0 1188.21  5360.0 1192.60
  5410.0 1194.88  5450.0 1204.19  5520.0 1212.52  5550.0 1214.94  5592.8 1216.40
#Mann=4,-1,0
  4565.0   0.035       0  4925.3    0.12       0  5007.7    0.05       0
  5012.4    0.12       0
Bank Sta=5007.7,5012.4
Exp/Cntr=0.3,0.1

Type RM Length L Ch R = 1,495,405,405,405
BEGIN DESCRIPTION:
Stream0164_DS 1.0
END DESCRIPTION:
XS GIS Cut Line= 3
      2077692.83     13874551.02      2078025.00     13874575.00
      2078201.58     13874496.20
#Sta/Elev= 30
  4667.4 1199.11  4749.8 1198.83  4809.9 1197.07  4850.0 1194.74  4890.2 1189.12
  4920.2 1186.63  4928.1 1185.00  4933.1 1186.18  4950.3 1182.07  4960.3 1178.32
  4970.4 1171.90  4980.4 1160.59  4995.6 1151.20  4995.9 1150.70  4999.9 1150.70
  5000.3 1151.20  5003.2 1151.20  5009.3 1156.22  5014.8 1156.27  5022.3 1158.51
  5037.3 1161.45  5044.2 1166.49  5055.2 1172.01  5061.2 1175.79  5082.6 1179.42
  5089.9 1181.63  5107.7 1184.83  5113.1 1186.73  5142.8 1189.59  5193.8 1188.21
#Mann=4,-1,0
  4667.4   0.035       0  4995.6   0.035       0  5000.3   0.035       0
  5037.3    0.12       0
Bank Sta=4995.6,5000.3
Exp/Cntr=0.3,0.1

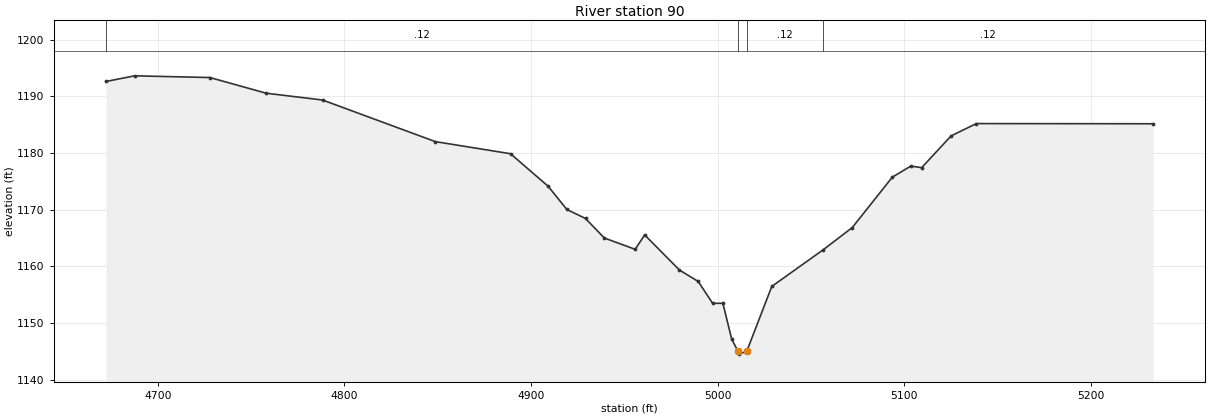
Type RM Length L Ch R = 1,90,0,0,0
BEGIN DESCRIPTION:
Stream0164_DS 0.0
END DESCRIPTION:
XS GIS Cut Line= 3
      2077969.65     13874807.52      2078295.32     13874844.87
      2078412.39     13874643.07
#Sta/Elev= 30
  4672.2 1192.63  4687.6 1193.63  4727.9 1193.33  4758.1 1190.56  4788.3 1189.36
  4848.7 1182.02  4889.0 1179.88  4909.1 1174.16  4919.2 1170.04  4929.2 1168.45
  4939.3 1165.00  4955.8 1163.01  4960.9 1165.55  4979.5 1159.36  4989.6 1157.33
  4997.3 1153.48  5002.8 1153.48  5007.5 1147.18  5010.9 1145.01  5011.2 1144.51
  5015.6 1145.01  5029.0 1156.46  5056.6 1162.94  5072.1 1166.84  5093.6 1175.75
  5103.5 1177.70  5109.3 1177.42  5125.1 1183.03  5138.6 1185.20  5233.3 1185.17
#Mann=4,-1,0
  4672.2    0.12       0  5010.9    0.05       0  5015.6    0.12       0
  5056.6    0.12       0
Bank Sta=5010.9,5015.6
Exp/Cntr=0.3,0.1

Chan Stop Cuts=-1