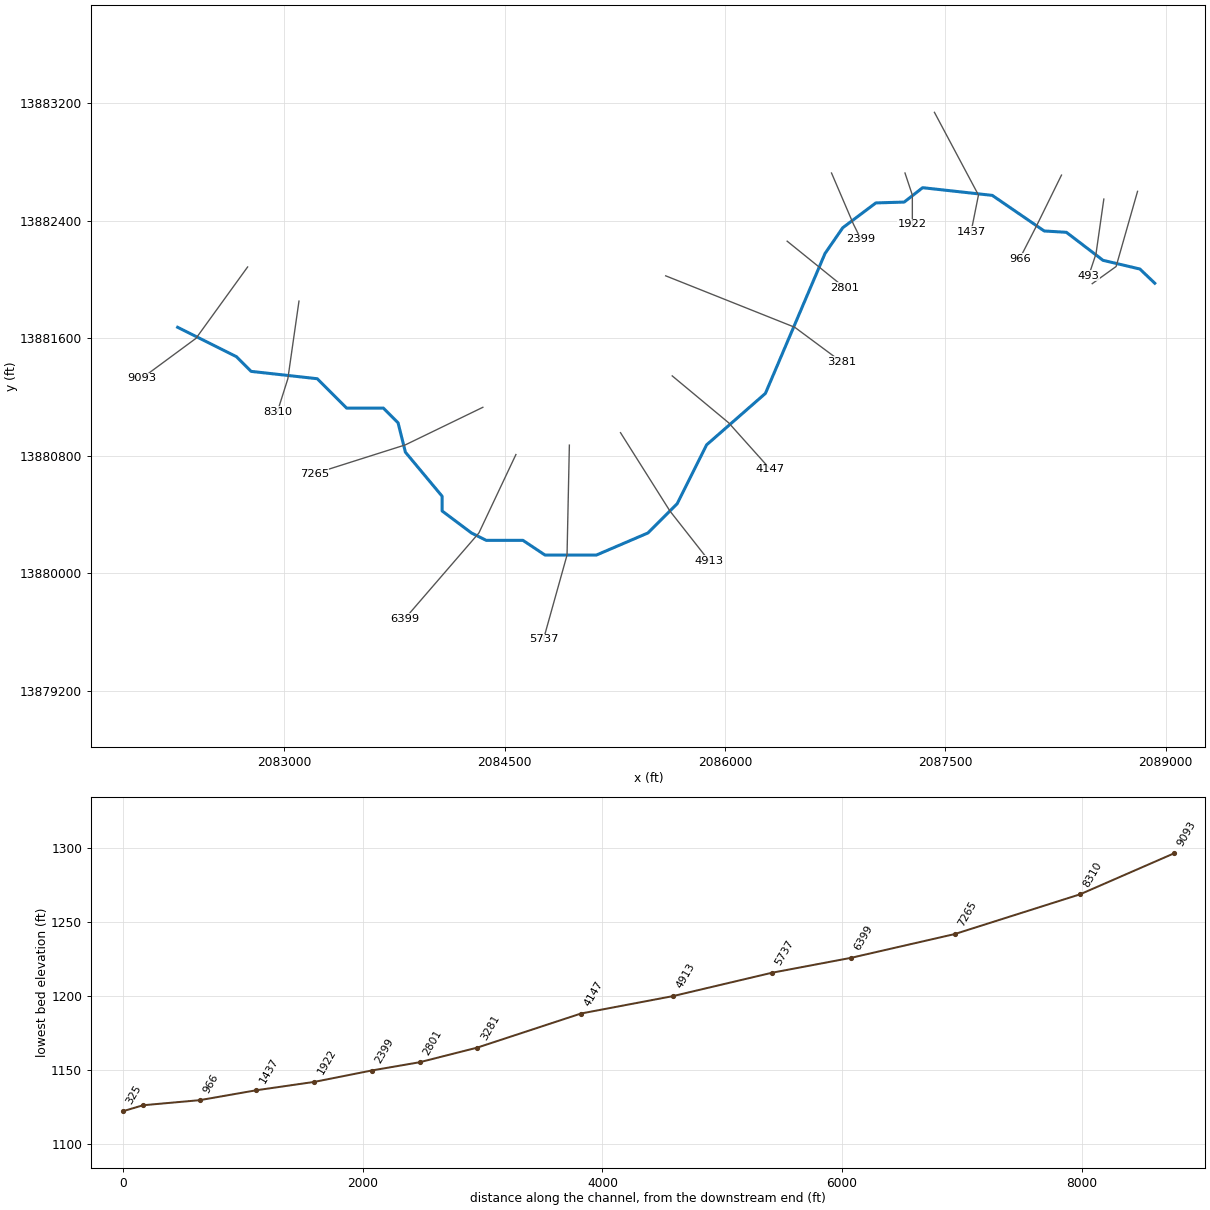
--- Stream0165_DS.prj (project) ---

Proj Title=Stream0165_DS Base Level Engineering
Current Plan=p01
Default Exp/Contr=0.3,0.1
English Units
Geom File=g01
Flow File=f01
Plan File=p01
BEGIN DESCRIPTION:
Stream0165_DS
END DESCRIPTION:

--- Stream0165_DS.p01 (plan) ---

Plan Title=Multiple Run
Short Identifier=Multiple
Geom File=g01
Flow File=f01
Subcritical Flow
K Sum by GR= 0
Std Step Tol= 0.01
Critical Tol= 0.01
Num of Std Step Trials= 20
Max Error Tol= 0.3
Flow Tol Ratio= 0.001
Split Flow NTrial= 30
Split Flow Tol= 0.02
Split Flow Ratio= 0.02
Log Output Level= 0
Friction Slope Method= 1
Unsteady Friction Slope Method= 2
Unsteady Bridges Friction Slope Method= 1
Parabolic Critical Depth
Global Vel Dist=  1 , 1 , 1
Global Log Level= 0
CheckData=True
Encroach Param= -1, 0, 0, 0
BEGIN DESCRIPTION:
Multiple Run
END DESCRIPTION:

--- Stream0165_DS.f01 (steady flow) ---

Flow Title=Multiple
Number of Profiles=7
Profile Names=10-year,25-year,50-year,1pct_min,100-year,1pct_plu,500-year
River Rch & RM= Stream0165_DS,Reach-1,9093
    1256    2138    2980    2012    4015    8012    7211
River Rch & RM= Stream0165_DS,Reach-1,2399
    1408    2408    3369    2281    4552    9082    8222
Boundary for River Rch & Prof#=Stream0165_DS,Reach-1,1
Up Type=0
Dn Type=3
Dn Slope=0.005
Boundary for River Rch & Prof#=Stream0165_DS,Reach-1,2
Up Type=0
Dn Type=3
Dn Slope=0.005
Boundary for River Rch & Prof#=Stream0165_DS,Reach-1,3
Up Type=0
Dn Type=3
Dn Slope=0.005
Boundary for River Rch & Prof#=Stream0165_DS,Reach-1,4
Up Type=0
Dn Type=3
Dn Slope=0.005
Boundary for River Rch & Prof#=Stream0165_DS,Reach-1,5
Up Type=0
Dn Type=3
Dn Slope=0.005
Boundary for River Rch & Prof#=Stream0165_DS,Reach-1,6
Up Type=0
Dn Type=3
Dn Slope=0.005
Boundary for River Rch & Prof#=Stream0165_DS,Reach-1,7
Up Type=0
Dn Type=3
Dn Slope=0.005

--- Stream0165_DS.g01 (geometry) ---

Geom Title=Existing Conditions

River Reach=Stream0165_DS,Reach-1
Reach XY= 30
      2082275.00     13881675.00      2082675.00     13881475.00
      2082775.00     13881375.00      2083225.00     13881325.00
      2083425.00     13881125.00      2083675.00     13881125.00
      2083775.00     13881025.00      2083825.00     13880825.00
      2084075.00     13880525.00      2084075.00     13880425.00
      2084275.00     13880275.00      2084375.00     13880225.00
      2084625.00     13880225.00      2084775.00     13880125.00
      2085125.00     13880125.00      2085475.00     13880275.00
      2085675.00     13880475.00      2085875.00     13880875.00
      2086275.00     13881225.00      2086680.74     13882177.34
      2086801.16     13882352.14      2087026.46     13882521.46
      2087219.55     13882527.18      2087344.99     13882625.04
      2087819.07     13882572.76      2088172.55     13882330.47
      2088323.53     13882321.45      2088572.71     13882130.84
      2088823.74     13882071.54      2088925.00     13881975.00

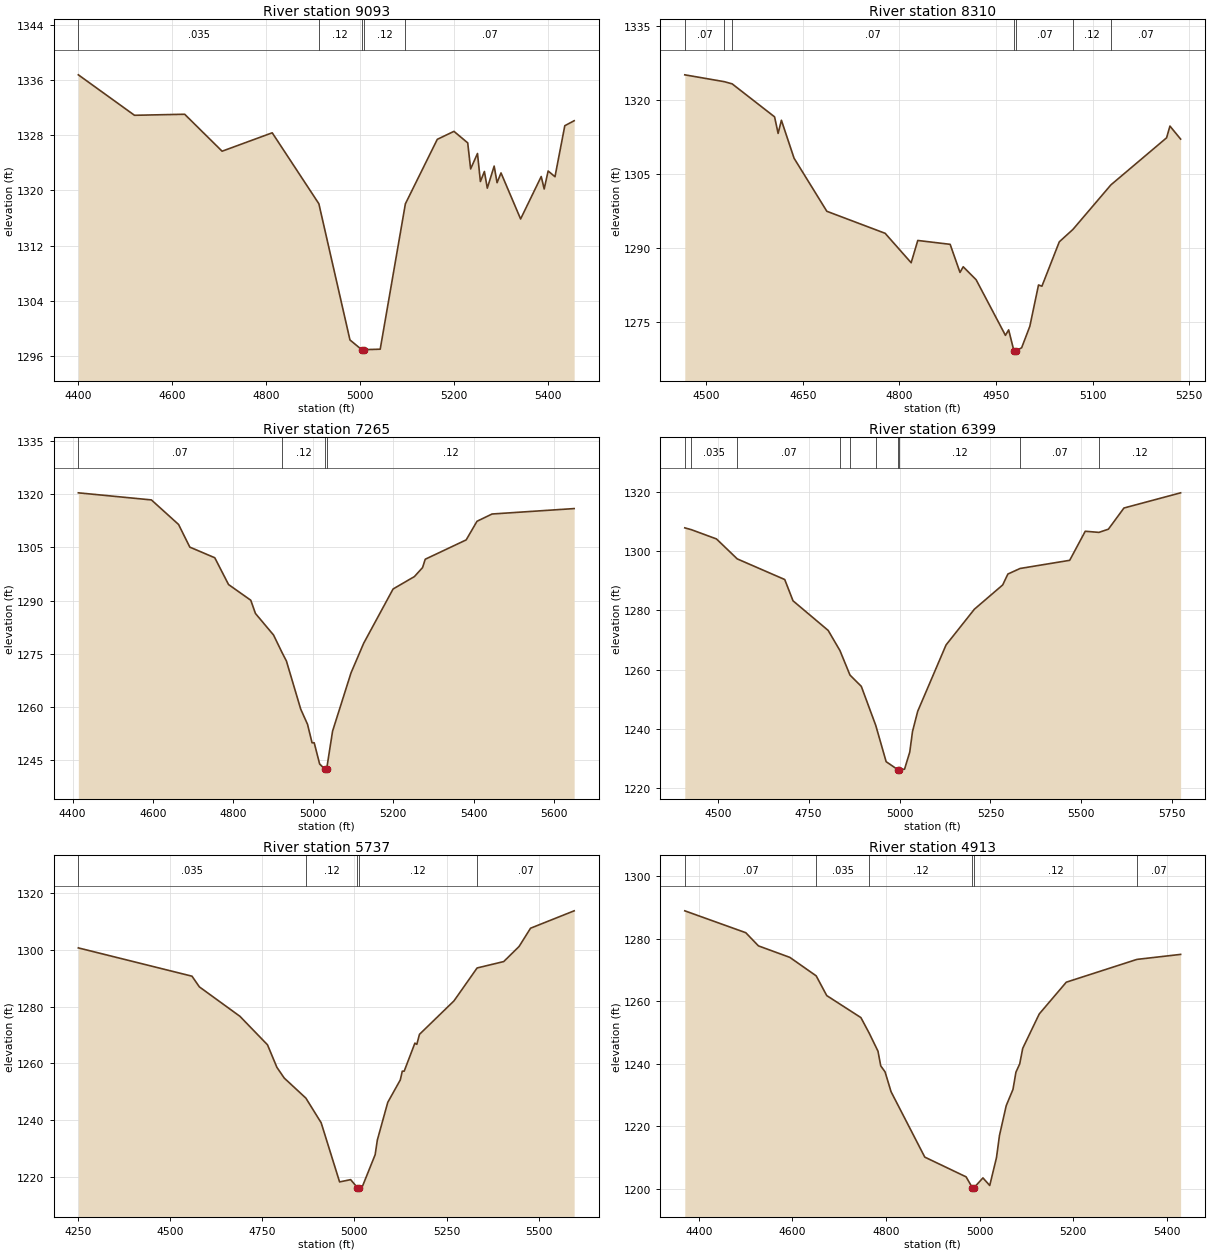
Type RM Length L Ch R = 1,9093,783,783,783
BEGIN DESCRIPTION:
Stream0165_DS 14.0
END DESCRIPTION:
XS GIS Cut Line= 3
      2082751.11     13882085.55      2082400.00     13881600.00
      2082032.69     13881329.11
#Sta/Elev= 30
  4400.8 1336.77  4520.4 1330.90  4627.2 1331.05  4706.9 1325.69  4813.6 1328.36
  4912.9 1318.07  4979.1 1298.31  5004.2 1296.90  5004.5 1296.40  5008.2 1296.90
  5043.5 1296.97  5097.1 1318.06  5165.0 1327.41  5200.5 1328.57  5229.8 1326.90
  5236.0 1323.12  5250.6 1325.36  5256.8 1321.29  5265.3 1322.75  5271.5 1320.33
  5286.1 1323.53  5292.3 1321.12  5300.7 1322.54  5342.4 1315.86  5386.3 1322.02
  5392.6 1320.21  5401.0 1322.82  5415.6 1321.99  5436.5 1329.39  5456.4 1330.11
#Mann=5,-1,0
  4400.8   0.035       0  4912.9    0.12       0  5004.2    0.05       0
  5008.2    0.12       0  5097.1    0.07       0
Bank Sta=5004.2,5008.2
Exp/Cntr=0.3,0.1

Type RM Length L Ch R = 1,8310,1045,1045,1045
BEGIN DESCRIPTION:
Stream0165_DS 13.0
END DESCRIPTION:
XS GIS Cut Line= 3
      2083100.62     13881853.11      2083025.00     13881325.00
      2082953.40     13881099.18
#Sta/Elev= 30
  4466.5 1325.10  4528.0 1323.71  4540.1 1323.27  4606.0 1316.59  4611.5 1313.24
  4616.6 1315.90  4636.3 1308.21  4687.2 1297.47  4777.8 1293.01  4818.2 1287.05
  4828.5 1291.56  4878.8 1290.78  4894.1 1285.09  4899.1 1286.24  4919.2 1283.60
  4964.7 1272.35  4969.7 1273.46  4977.8 1269.25  4978.0 1268.75  4981.8 1269.25
  4989.9 1269.84  5002.6 1274.18  5016.1 1282.55  5021.4 1282.30  5048.4 1291.29
  5069.6 1293.80  5128.6 1302.82  5215.1 1312.35  5220.3 1314.72  5236.9 1312.09
#Mann=7,-1,0
  4466.5    0.07       0  4528.0   0.035       0  4540.1    0.07       0
  4977.8    0.05       0  4981.8    0.07       0  5069.6    0.12       0
  5128.6    0.07       0
Bank Sta=4977.8,4981.8
Exp/Cntr=0.3,0.1

Type RM Length L Ch R = 1,7265,866,866,866
BEGIN DESCRIPTION:
Stream0165_DS 12.0
END DESCRIPTION:
XS GIS Cut Line= 3
      2084352.05     13881130.46      2083825.00     13880875.00
      2083204.59     13880678.11
#Sta/Elev= 30
  4414.3 1320.36  4596.6 1318.36  4664.3 1311.44  4692.4 1305.05  4754.6 1302.06
  4788.9 1294.51  4844.4 1290.08  4856.0 1286.36  4901.2 1280.27  4922.9 1275.22
  4933.3 1272.94  4968.9 1259.40  4985.9 1255.11  4997.2 1249.90  5002.6 1249.90
  5016.1 1243.94  5029.5 1242.41  5029.7 1241.91  5033.5 1242.41  5048.4 1253.19
  5094.4 1269.61  5125.9 1277.94  5199.3 1293.25  5252.5 1296.75  5272.8 1299.28
  5279.5 1301.64  5381.6 1307.09  5408.6 1312.34  5446.1 1314.39  5650.9 1315.92
#Mann=4,-1,0
  4414.3    0.07       0  4922.9    0.12       0  5029.5    0.05       0
  5033.5    0.12       0
Bank Sta=5029.5,5033.5
Exp/Cntr=0.3,0.1

Type RM Length L Ch R = 1,6399,662,662,662
BEGIN DESCRIPTION:
Stream0165_DS 11.0
END DESCRIPTION:
XS GIS Cut Line= 3
      2084577.09     13880808.99      2084325.00     13880275.00
      2083819.84     13879690.16
#Sta/Elev= 30
  4409.5 1307.87  4427.6 1307.25  4496.6 1304.13  4553.7 1297.40  4684.3 1290.44
  4707.1 1283.26  4803.7 1273.28  4836.2 1266.46  4863.7 1258.22  4894.8 1254.42
  4934.6 1241.23  4963.1 1229.01  4995.2 1226.33  4995.5 1225.83  4999.2 1226.33
  5013.7 1226.48  5028.0 1232.24  5035.6 1239.19  5049.9 1246.01  5127.8 1268.37
  5205.7 1280.43  5283.6 1288.62  5297.8 1292.29  5331.4 1294.17  5467.8 1296.92
  5510.6 1306.72  5548.2 1306.34  5574.2 1307.42  5617.0 1314.56  5772.8 1319.68
#Mann=10,-1,0
  4409.5    0.07       0  4427.6   0.035       0  4553.7    0.07       0
  4836.2    0.12       0  4863.7    0.07       0  4934.6    0.12       0
  4995.2    0.05       0  4999.2    0.12       0  5331.4    0.07       0
  5548.2    0.12       0
Bank Sta=4995.2,4999.2
Exp/Cntr=0.3,0.1

Type RM Length L Ch R = 1,5737,824,824,824
BEGIN DESCRIPTION:
Stream0165_DS 10.0
END DESCRIPTION:
XS GIS Cut Line= 3
      2084940.87     13880873.03      2084925.00     13880125.00
      2084764.65     13879551.18
#Sta/Elev= 30
  4251.8 1300.63  4559.9 1290.67  4579.9 1286.91  4689.9 1276.54  4764.6 1266.51
  4790.0 1258.59  4810.0 1254.80  4868.6 1247.75  4910.0 1239.08  4960.0 1218.25
  4990.0 1219.05  5008.4 1216.21  5008.6 1215.71  5012.4 1216.21  5022.3 1216.81
  5056.4 1227.84  5062.3 1232.99  5090.6 1246.27  5124.6 1254.17  5129.9 1257.23
  5135.1 1257.24  5164.1 1267.10  5169.3 1266.67  5176.5 1270.19  5270.0 1281.97
  5332.7 1293.56  5404.9 1295.82  5446.5 1301.13  5477.6 1307.56  5595.8 1313.68
#Mann=5,-1,0
  4251.8   0.035       0  4868.6    0.12       0  5008.4    0.05       0
  5012.4    0.12       0  5332.7    0.07       0
Bank Sta=5008.4,5012.4
Exp/Cntr=0.3,0.1

Type RM Length L Ch R = 1,4913,766,766,766
BEGIN DESCRIPTION:
Stream0165_DS 9.0
END DESCRIPTION:
XS GIS Cut Line= 3
      2085288.94     13880957.77      2085625.00     13880425.00
      2085890.44     13880087.22
#Sta/Elev= 30
  4370.1 1288.88  4500.4 1281.89  4527.5 1277.68  4594.6 1274.00  4650.9 1268.10
  4673.4 1261.80  4746.4 1254.77  4764.1 1249.81  4782.9 1244.04  4788.8 1239.36
  4798.1 1237.40  4810.8 1231.10  4882.9 1210.19  4971.2 1203.88  4984.4 1200.46
  4984.7 1199.96  4988.4 1200.46  5007.2 1203.55  5021.7 1201.12  5036.1 1210.01
  5042.5 1217.08  5056.9 1226.62  5071.4 1231.83  5077.7 1237.33  5085.8 1240.00
  5092.2 1244.94  5127.5 1255.93  5185.3 1266.08  5336.2 1273.36  5429.6 1274.96
#Mann=6,-1,0
  4370.1    0.07       0  4650.9   0.035       0  4764.1    0.12       0
  4984.4    0.05       0  4988.4    0.12       0  5336.2    0.07       0
Bank Sta=4984.4,4988.4
Exp/Cntr=0.3,0.1

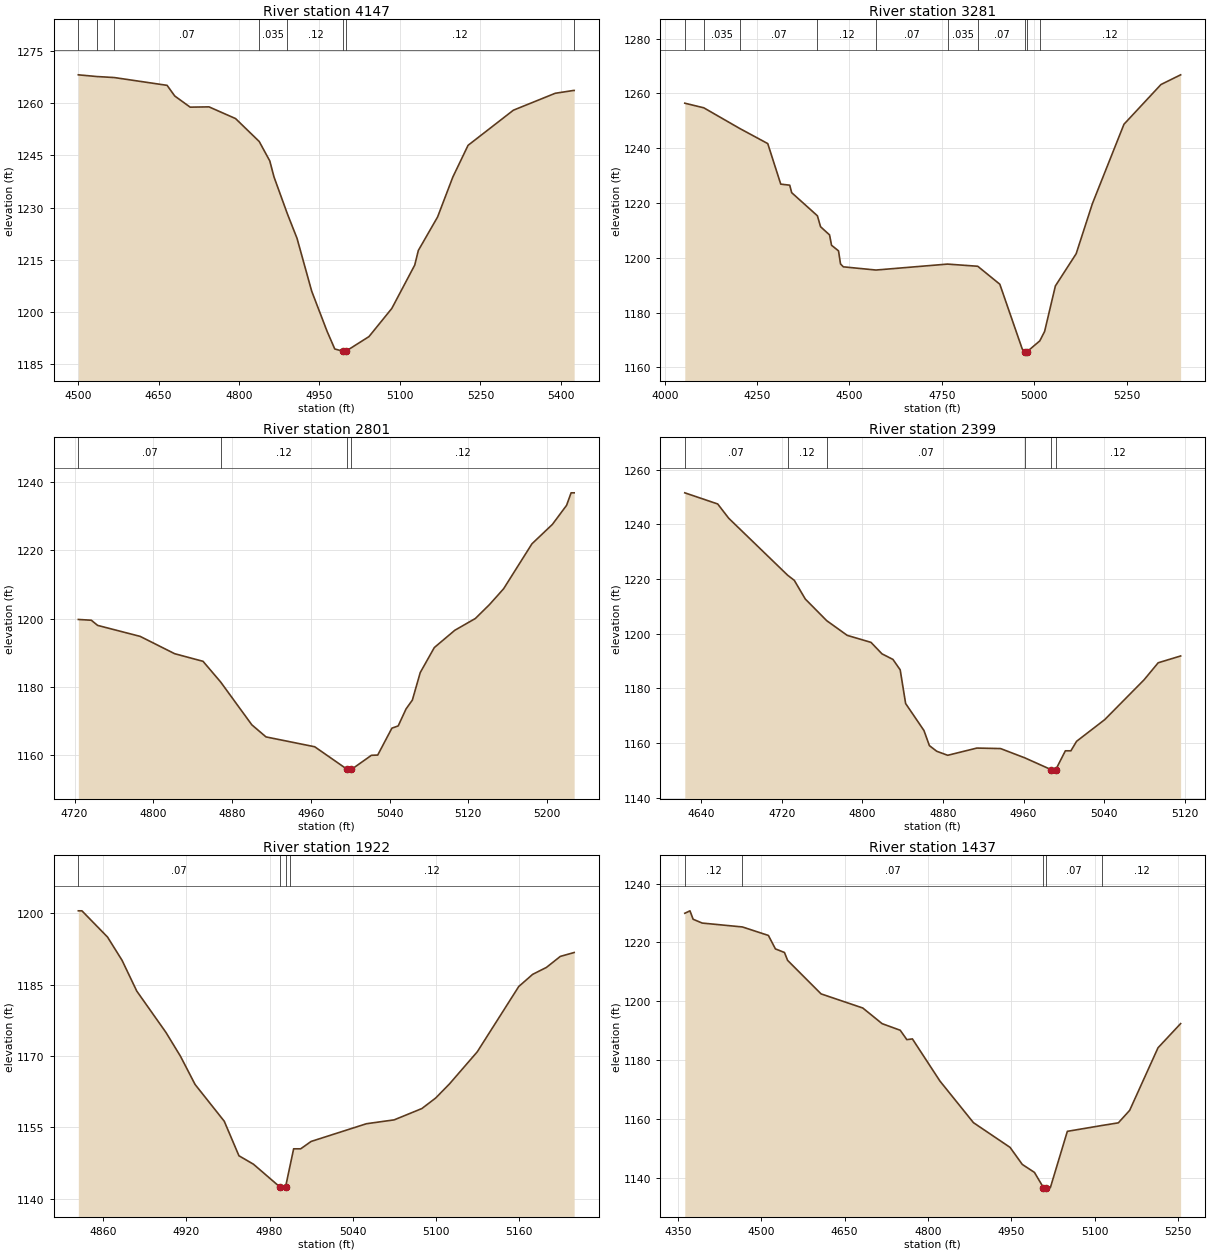
Type RM Length L Ch R = 1,4147,866,866,866
BEGIN DESCRIPTION:
Stream0165_DS 8.0
END DESCRIPTION:
XS GIS Cut Line= 3
      2085640.91     13881344.18      2086025.00     13881025.00
      2086308.27     13880708.70
#Sta/Elev= 30
  4500.6 1268.12  4535.1 1267.63  4567.5 1267.34  4666.0 1265.10  4680.3 1262.04
  4709.0 1258.84  4744.1 1258.92  4793.6 1255.56  4837.7 1248.98  4857.4 1243.40
  4865.2 1238.82  4890.2 1228.20  4908.2 1221.16  4935.5 1206.00  4964.2 1194.47
  4978.5 1189.41  4994.7 1188.72  4995.0 1188.22  4998.7 1188.72  5042.2 1192.96
  5084.8 1201.05  5127.5 1213.50  5134.2 1217.69  5170.1 1227.31  5198.5 1238.77
  5226.9 1247.88  5311.4 1257.97  5389.3 1262.82  5424.2 1263.65  5424.6 1263.64
#Mann=8,-1,0
  4500.6    0.07       0  4535.1   0.035       0  4567.5    0.07       0
  4837.7   0.035       0  4890.2    0.12       0  4994.7    0.05       0
  4998.7    0.12       0  5424.2    0.07       0
Bank Sta=4994.7,4998.7
Exp/Cntr=0.3,0.1

Type RM Length L Ch R = 1,3281,480,480,480
BEGIN DESCRIPTION:
Stream0165_DS 7.0
END DESCRIPTION:
XS GIS Cut Line= 3
      2085596.35     13882025.28      2086475.00     13881675.00
      2086793.51     13881438.85
#Sta/Elev= 30
  4054.1 1256.43  4105.5 1254.75  4202.3 1247.24  4278.7 1241.68  4313.9 1226.88
  4338.2 1226.49  4343.5 1223.76  4413.1 1215.32  4421.7 1211.32  4446.0 1208.34
  4451.4 1204.56  4470.3 1202.51  4475.7 1197.74  4483.3 1196.68  4571.7 1195.51
  4765.4 1197.68  4847.2 1196.89  4907.0 1190.33  4967.7 1166.68  4976.5 1165.67
  4976.7 1165.17  4980.5 1165.67  5015.2 1169.64  5028.2 1173.06  5057.4 1189.69
  5113.7 1201.47  5157.6 1219.74  5243.1 1248.74  5343.3 1263.25  5396.5 1266.79
#Mann=10,-1,0
  4054.1    0.07       0  4105.5   0.035       0  4202.3    0.07       0
  4413.1    0.12       0  4571.7    0.07       0  4765.4   0.035       0
  4847.2    0.07       0  4976.5    0.05       0  4980.5    0.07       0
  5015.2    0.12       0
Bank Sta=4976.5,4980.5
Exp/Cntr=0.3,0.1

Type RM Length L Ch R = 1,2801,402,402,402
BEGIN DESCRIPTION:
Stream0165_DS 6.0
END DESCRIPTION:
XS GIS Cut Line= 2
      2086423.11     13882260.99      2086814.88     13881944.24
#Sta/Elev= 30
  4723.8 1199.76  4737.0 1199.53  4743.4 1198.02  4786.6 1194.80  4821.7 1189.72
  4850.5 1187.49  4868.4 1181.43  4900.1 1168.87  4914.5 1165.33  4964.0 1162.44
  4997.1 1155.80  4997.4 1155.30  5001.3 1155.80  5021.6 1159.94  5028.0 1160.01
  5042.4 1167.89  5048.8 1168.55  5056.8 1173.54  5063.2 1176.12  5071.2 1184.19
  5085.5 1191.52  5106.3 1196.58  5127.2 1200.04  5141.5 1204.10  5155.9 1208.75
  5184.7 1221.93  5205.5 1227.63  5219.9 1233.21  5224.5 1236.88  5227.6 1236.88
#Mann=4,-1,0
  4723.8    0.07       0  4868.4    0.12       0  4997.1    0.05       0
  5001.3    0.12       0
Bank Sta=4997.1,5001.3
Exp/Cntr=0.3,0.1

Type RM Length L Ch R = 1,2399,477,477,477
BEGIN DESCRIPTION:
Stream0165_DS 5.0
END DESCRIPTION:
XS GIS Cut Line= 3
      2086724.98     13882725.04      2086875.00     13882375.00
      2086924.99     13882275.03
#Sta/Elev= 30
  4623.5 1251.56  4656.2 1247.48  4667.1 1242.27  4725.8 1221.36  4732.3 1219.52
  4743.2 1212.69  4764.5 1204.76  4784.9 1199.38  4808.5 1196.82  4819.4 1192.62
  4830.3 1190.58  4837.5 1186.76  4842.9 1174.43  4861.1 1164.56  4866.5 1159.03
  4873.8 1156.96  4884.7 1155.49  4913.7 1158.13  4937.2 1157.95  4961.5 1154.52
  4987.7 1150.19  4988.0 1149.69  4992.0 1150.19  5001.6 1157.13  5007.1 1157.13
  5012.7 1160.59  5040.7 1168.54  5079.8 1183.12  5093.8 1189.35  5116.1 1191.84
#Mann=6,-1,0
  4623.5    0.07       0  4725.8    0.12       0  4764.5    0.07       0
  4961.5    0.12       0  4987.7    0.05       0  4992.0    0.12       0
Bank Sta=4987.7,4992
Exp/Cntr=0.3,0.1

Type RM Length L Ch R = 1,1922,485,485,485
BEGIN DESCRIPTION:
Stream0165_DS 4.0
END DESCRIPTION:
XS GIS Cut Line= 3
      2087225.00     13882725.00      2087275.00     13882575.00
      2087275.00     13882375.02
#Sta/Elev= 30
  4841.9 1200.56  4844.5 1200.56  4863.0 1195.04  4873.5 1190.14  4884.1 1183.68
  4905.2 1174.97  4915.7 1169.95  4926.2 1164.04  4947.3 1156.29  4957.9 1149.03
  4968.4 1147.25  4987.3 1142.51  4987.6 1142.01  4991.3 1142.01  4991.6 1142.51
  4995.1 1147.33  4997.4 1150.49  5002.5 1150.49  5010.0 1152.04  5050.0 1155.77
  5070.0 1156.58  5090.0 1158.96  5100.0 1161.18  5110.0 1164.16  5130.0 1170.89
  5160.0 1184.64  5170.0 1187.19  5180.0 1188.66  5190.0 1190.97  5200.0 1191.79
#Mann=4,-1,0
  4841.9    0.07       0  4987.3    0.05       0  4991.6    0.07       0
  4995.1    0.12       0
Bank Sta=4987.3,4991.6
Exp/Cntr=0.3,0.1

Type RM Length L Ch R = 1,1437,471,471,471
BEGIN DESCRIPTION:
Stream0165_DS 3.0
END DESCRIPTION:
XS GIS Cut Line= 3
      2087425.44     13883137.84      2087725.00     13882575.00
      2087675.01     13882325.05
#Sta/Elev= 30
  4362.5 1229.91  4371.8 1230.74  4377.5 1227.88  4393.8 1226.59  4466.2 1225.27
  4513.0 1222.39  4525.6 1217.83  4541.9 1216.61  4547.6 1213.93  4607.8 1202.57
  4682.9 1197.78  4717.7 1192.47  4750.3 1190.23  4762.2 1187.05  4772.2 1187.30
  4821.8 1173.00  4882.1 1158.89  4948.0 1150.51  4970.0 1144.73  4991.9 1142.02
  5008.1 1136.85  5008.4 1136.35  5012.5 1136.85  5020.5 1136.85  5051.1 1155.95
  5114.2 1157.96  5142.9 1158.83  5163.3 1163.08  5214.3 1184.29  5255.0 1192.49
#Mann=5,-1,0
  4362.5    0.12       0  4466.2    0.07       0  5008.1    0.05       0
  5012.5    0.07       0  5114.2    0.12       0
Bank Sta=5008.1,5012.5
Exp/Cntr=0.3,0.1

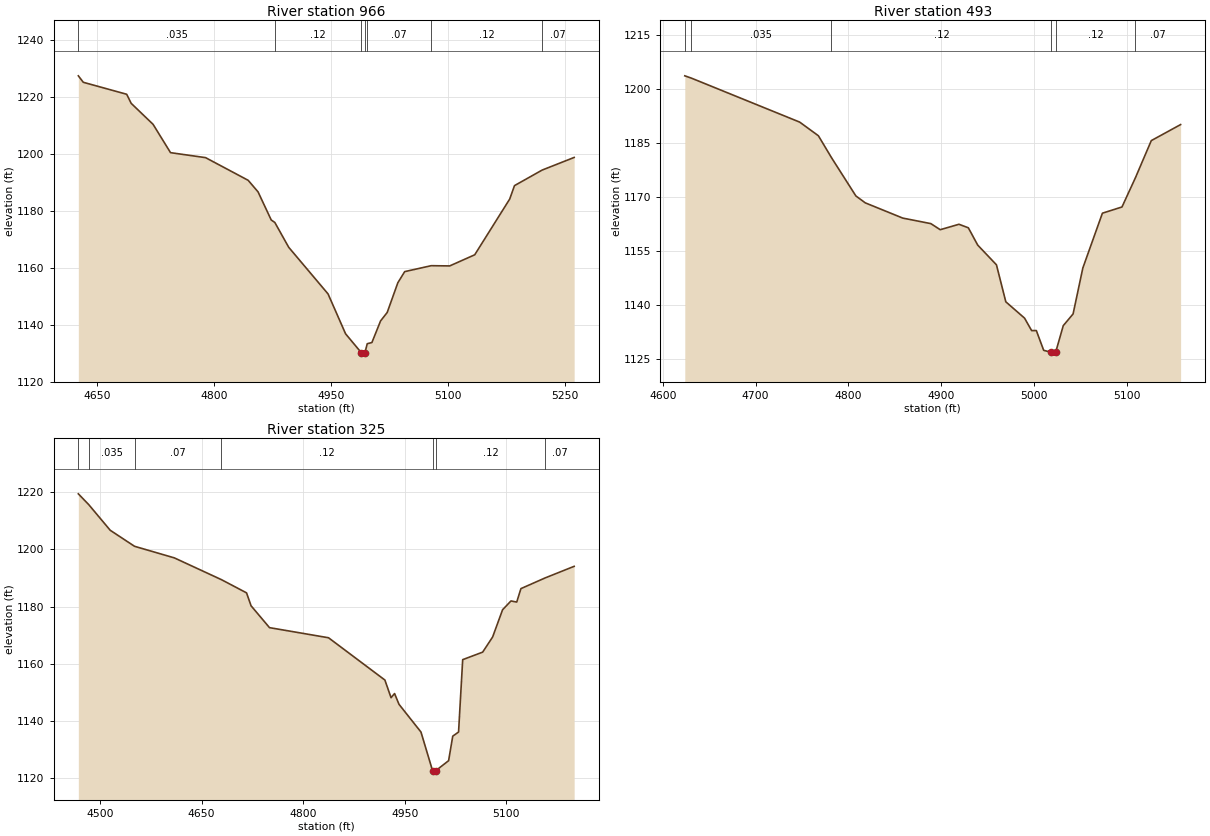
Type RM Length L Ch R = 1,966,473,473,473
BEGIN DESCRIPTION:
Stream0165_DS 2.0
END DESCRIPTION:
XS GIS Cut Line= 3
      2088290.04     13882710.77      2088125.00     13882375.00
      2088005.31     13882141.31
#Sta/Elev= 30
  4625.6 1227.28  4632.0 1225.01  4687.7 1220.81  4693.5 1217.62  4721.6 1210.26
  4744.0 1200.33  4789.0 1198.58  4843.7 1190.63  4856.4 1186.57  4873.3 1176.71
  4877.9 1175.85  4895.8 1167.12  4946.3 1150.77  4968.8 1136.78  4989.0 1130.16
  4989.3 1129.66  4993.6 1130.16  4996.6 1133.31  5002.6 1133.73  5013.7 1141.30
  5022.2 1144.26  5035.9 1154.70  5044.7 1158.60  5078.7 1160.68  5102.5 1160.60
  5134.6 1164.50  5179.5 1184.04  5185.7 1188.77  5221.2 1194.22  5262.3 1198.65
#Mann=7,-1,0
  4625.6   0.035       0  4877.9    0.12       0  4989.0    0.05       0
  4993.6    0.12       0  4996.6    0.07       0  5078.7    0.12       0
  5221.2    0.07       0
Bank Sta=4989,4993.6
Exp/Cntr=0.3,0.1

Type RM Length L Ch R = 1,493,168,168,168
BEGIN DESCRIPTION:
Stream0165_DS 1.0
END DESCRIPTION:
XS GIS Cut Line= 3
      2088578.22     13882547.53      2088525.00     13882175.00
      2088475.01     13882025.02
#Sta/Elev= 30
  4623.7 1203.64  4630.7 1203.01  4747.5 1190.77  4767.7 1186.97  4781.8 1180.88
  4808.1 1170.23  4818.2 1168.31  4858.6 1164.07  4888.9 1162.53  4899.0 1160.84
  4919.2 1162.35  4929.3 1161.37  4939.4 1156.56  4959.6 1151.07  4969.7 1140.78
  4989.9 1136.24  4997.5 1132.78  5002.6 1132.78  5010.5 1127.29  5018.7 1126.73
  5019.1 1126.23  5023.4 1126.73  5031.6 1134.15  5042.2 1137.41  5052.7 1150.18
  5073.8 1165.43  5094.9 1167.16  5109.4 1175.30  5126.5 1185.62  5158.1 1190.08
#Mann=6,-1,0
  4623.7    0.07       0  4630.7   0.035       0  4781.8    0.12       0
  5018.7    0.05       0  5023.4    0.12       0  5109.4    0.07       0
Bank Sta=5018.7,5023.4
Exp/Cntr=0.3,0.1

Type RM Length L Ch R = 1,325,0,0,0
BEGIN DESCRIPTION:
Stream0165_DS 0.0
END DESCRIPTION:
XS GIS Cut Line= 3
      2088807.74     13882600.32      2088661.83     13882088.72
      2088499.23     13881971.93
#Sta/Elev= 30
  4468.0 1219.45  4483.4 1215.67  4515.1 1206.71  4551.0 1201.11  4609.8 1197.06
  4679.4 1189.44  4716.4 1184.84  4723.1 1180.32  4750.3 1172.68  4837.5 1169.14
  4920.7 1154.37  4929.8 1148.20  4935.0 1149.65  4941.5 1145.90  4974.0 1136.19
  4991.1 1122.68  4991.5 1122.18  4995.8 1122.68  5014.8 1126.18  5020.9 1134.74
  5029.5 1136.20  5035.6 1161.49  5065.1 1164.12  5079.8 1169.41  5094.5 1178.93
  5106.9 1182.01  5115.4 1181.62  5121.6 1186.32  5157.5 1190.07  5200.2 1194.11
#Mann=7,-1,0
  4468.0    0.07       0  4483.4   0.035       0  4551.0    0.07       0
  4679.4    0.12       0  4991.1    0.05       0  4995.8    0.12       0
  5157.5    0.07       0
Bank Sta=4991.1,4995.8
Exp/Cntr=0.3,0.1

Chan Stop Cuts=-1