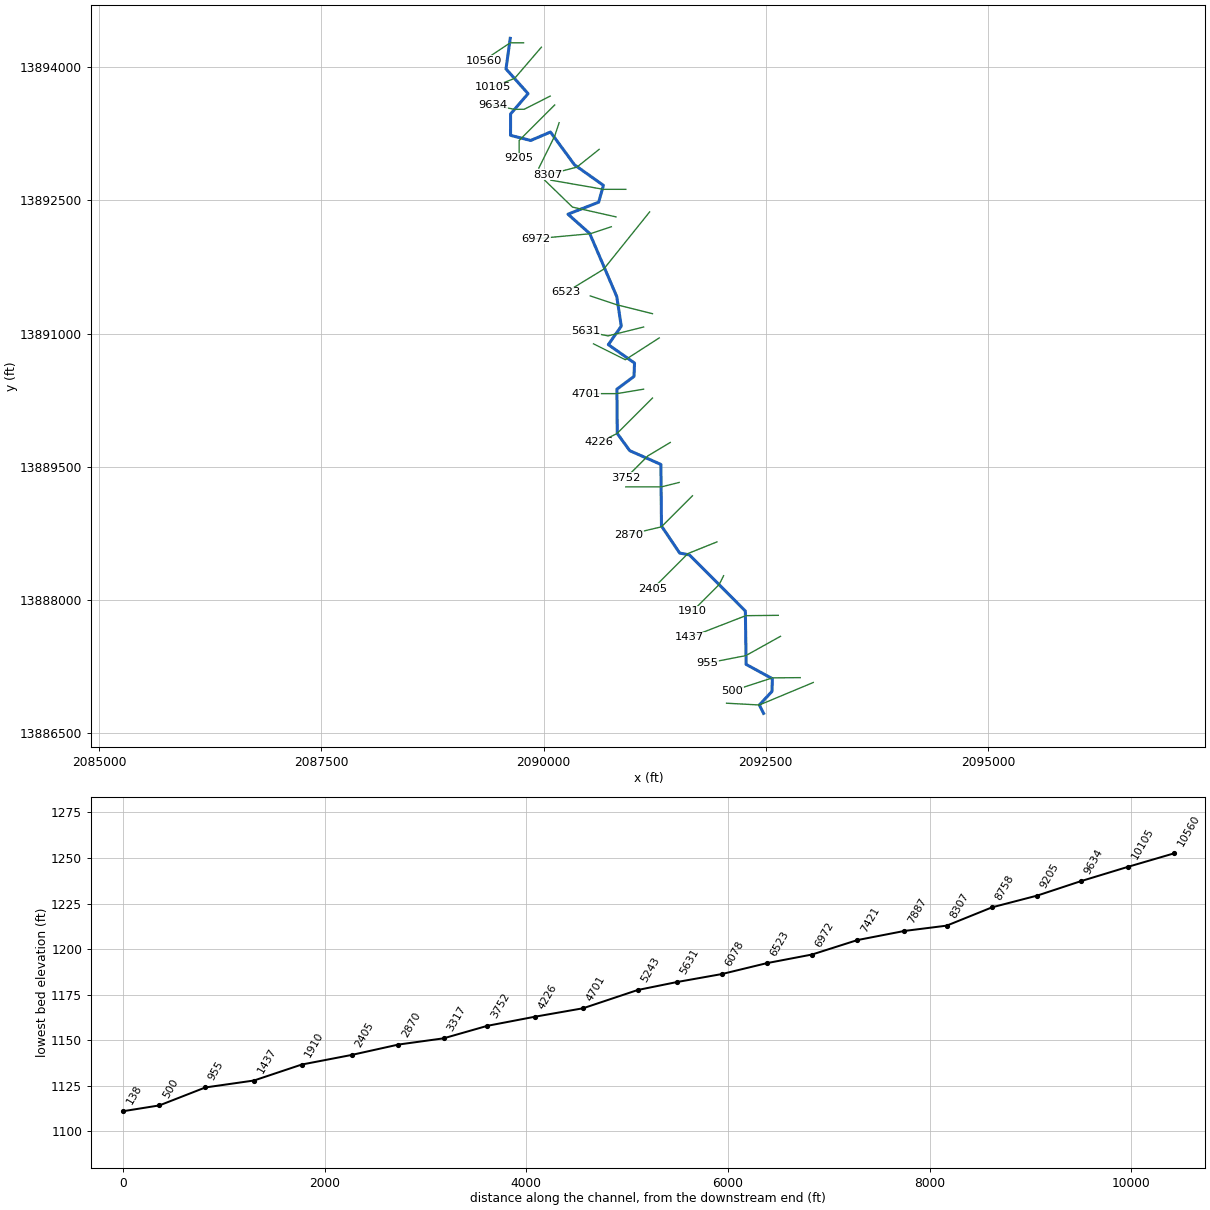
--- Stream0166_DS.prj (project) ---

Proj Title=Stream0166_DS Base Level Engineering
Current Plan=p01
Default Exp/Contr=0.3,0.1
English Units
Geom File=g01
Flow File=f01
Plan File=p01
BEGIN DESCRIPTION:
Stream0166_DS
END DESCRIPTION:

--- Stream0166_DS.p01 (plan) ---

Plan Title=Multiple Run
Short Identifier=Multiple
Geom File=g01
Flow File=f01
Subcritical Flow
K Sum by GR= 0
Std Step Tol= 0.01
Critical Tol= 0.01
Num of Std Step Trials= 20
Max Error Tol= 0.3
Flow Tol Ratio= 0.001
Split Flow NTrial= 30
Split Flow Tol= 0.02
Split Flow Ratio= 0.02
Log Output Level= 0
Friction Slope Method= 1
Unsteady Friction Slope Method= 2
Unsteady Bridges Friction Slope Method= 1
Parabolic Critical Depth
Global Vel Dist=  1 , 1 , 1
Global Log Level= 0
CheckData=True
Encroach Param= -1, 0, 0, 0
BEGIN DESCRIPTION:
Multiple Run
END DESCRIPTION:

--- Stream0166_DS.f01 (steady flow) ---

Flow Title=Multiple
Number of Profiles=7
Profile Names=10-year,25-year,50-year,1pct_min,100-year,1pct_plu,500-year
River Rch & RM= Stream0166_DS,Reach-1,10560
    1703    2964    4195    2875    5736   11444   10610
River Rch & RM= Stream0166_DS,Reach-1,4701
    1961    3433    4877    3353    6690   13349   12458
River Rch & RM= Stream0166_DS,Reach-1,1437
    2958    5290    7624    5310   10594   21139   20256
Boundary for River Rch & Prof#=Stream0166_DS,Reach-1,1
Up Type=0
Dn Type=3
Dn Slope=0.005
Boundary for River Rch & Prof#=Stream0166_DS,Reach-1,2
Up Type=0
Dn Type=3
Dn Slope=0.005
Boundary for River Rch & Prof#=Stream0166_DS,Reach-1,3
Up Type=0
Dn Type=3
Dn Slope=0.005
Boundary for River Rch & Prof#=Stream0166_DS,Reach-1,4
Up Type=0
Dn Type=3
Dn Slope=0.005
Boundary for River Rch & Prof#=Stream0166_DS,Reach-1,5
Up Type=0
Dn Type=3
Dn Slope=0.005
Boundary for River Rch & Prof#=Stream0166_DS,Reach-1,6
Up Type=0
Dn Type=3
Dn Slope=0.005
Boundary for River Rch & Prof#=Stream0166_DS,Reach-1,7
Up Type=0
Dn Type=3
Dn Slope=0.005

--- Stream0166_DS.g01 (geometry) ---

Geom Title=Existing Conditions

River Reach=Stream0166_DS,Reach-1
Reach XY= 30
      2089625.00     13894325.00      2089577.06     13893980.85
      2089825.57     13893702.20      2089628.54     13893473.54
      2089628.22     13893232.98      2089854.97     13893175.04
      2090077.30     13893269.91      2090347.72     13892901.10
      2090672.92     13892669.52      2090619.59     13892480.18
      2090274.45     13892345.13      2090519.17     13892127.30
      2090822.75     13891419.07      2090873.87     13891084.44
      2090728.37     13890876.29      2091022.96     13890669.15
      2091017.20     13890518.81      2090825.00     13890375.00
      2090828.75     13889876.55      2090968.79     13889682.81
      2091319.64     13889527.70      2091326.20     13888834.59
      2091530.44     13888530.25      2091641.73     13888508.53
      2092269.87     13887877.58      2092278.61     13887276.48
      2092573.88     13887115.58      2092569.55     13886972.55
      2092427.03     13886819.48      2092475.00     13886725.00

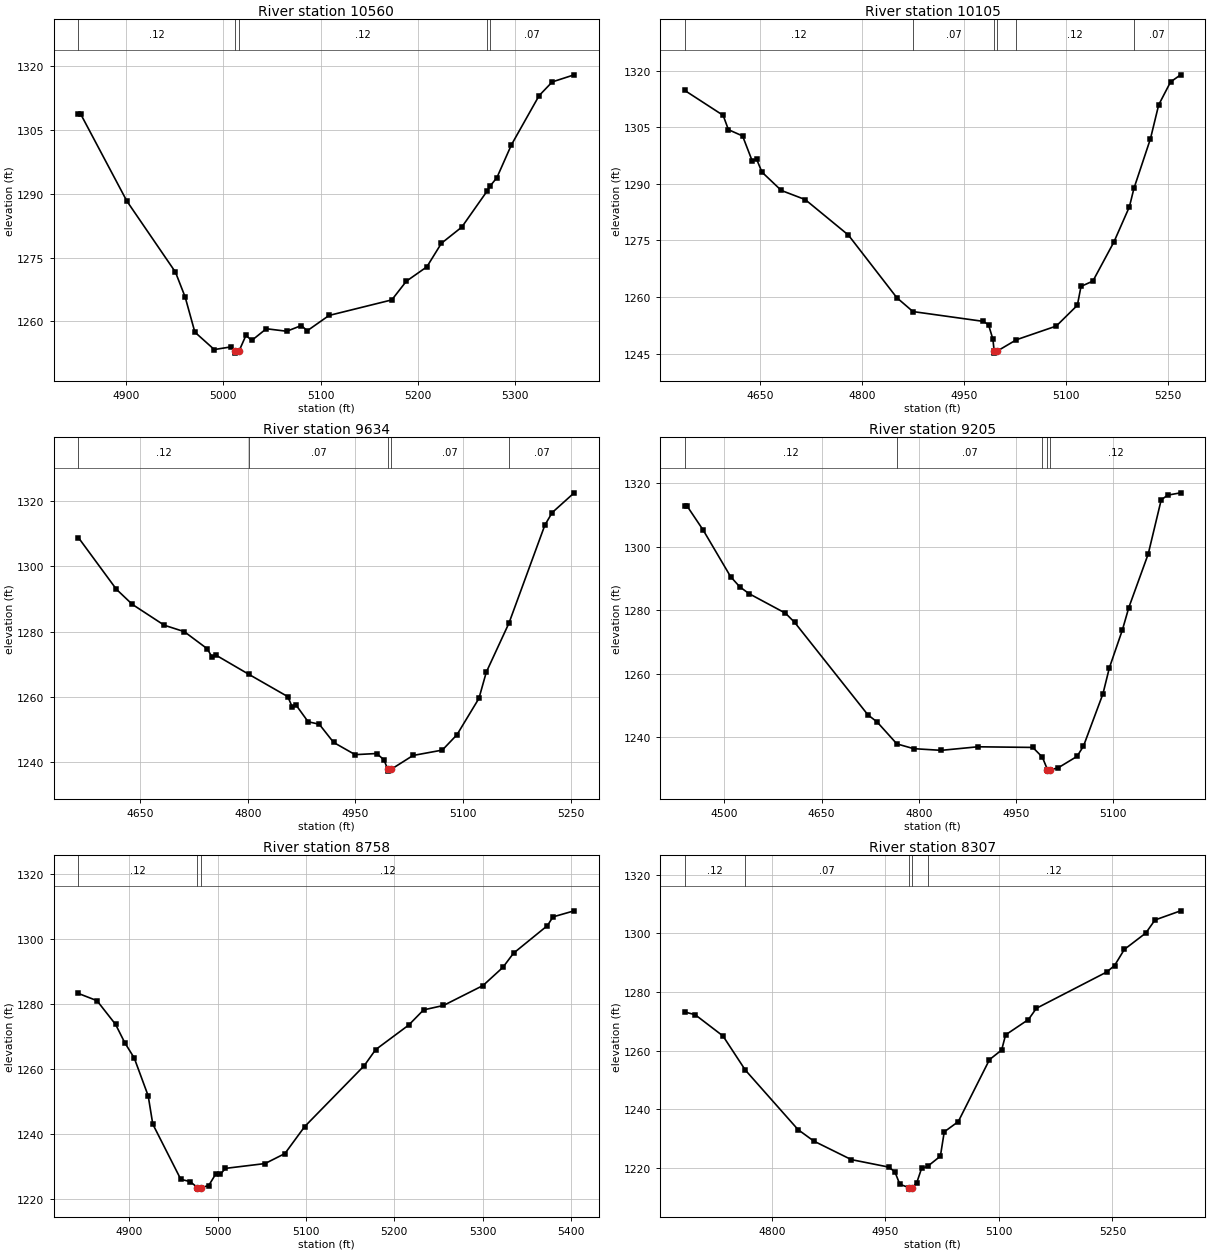
Type RM Length L Ch R = 1,10560,455,455,455
BEGIN DESCRIPTION:
Stream0166_DS 23.0
END DESCRIPTION:
XS GIS Cut Line= 3
      2089775.03     13894275.00      2089625.00     13894275.00
      2089324.99     13894074.99
#Sta/Elev= 30
  4850.6 1308.73  4853.1 1308.73  4900.6 1288.27  4950.6 1271.56  4960.6 1265.70
  4970.6 1257.43  4990.6 1253.33  5008.1 1253.97  5012.1 1252.99  5012.4 1252.49
  5016.1 1252.99  5023.2 1256.66  5029.2 1255.48  5044.2 1258.23  5065.2 1257.64
  5080.3 1258.98  5086.3 1257.75  5108.8 1261.36  5173.4 1265.02  5188.4 1269.42
  5209.5 1272.80  5224.5 1278.35  5245.5 1282.16  5271.7 1290.68  5274.5 1291.78
  5281.6 1293.78  5296.6 1301.53  5325.1 1313.10  5338.6 1316.33  5361.2 1318.00
#Mann=5,-1,0
  4850.6    0.12       0  5012.1    0.05       0  5016.1    0.12       0
  5271.7   0.035       0  5274.5    0.07       0
Bank Sta=5012.1,5016.1
Exp/Cntr=0.3,0.1

Type RM Length L Ch R = 1,10105,471,471,471
BEGIN DESCRIPTION:
Stream0166_DS 22.0
END DESCRIPTION:
XS GIS Cut Line= 3
      2089975.00     13894225.00      2089675.00     13893875.00
      2089425.03     13893775.01
#Sta/Elev= 30
  4539.0 1314.78  4595.5 1308.18  4603.2 1304.39  4624.1 1302.72  4638.3 1296.08
  4644.9 1296.50  4652.6 1293.14  4681.1 1288.27  4716.3 1285.85  4779.9 1276.44
  4851.3 1259.82  4875.0 1256.15  4978.6 1253.55  4986.3 1252.67  4992.8 1248.77
  4994.6 1245.63  4994.9 1245.13  4998.7 1245.63  5027.4 1248.68  5086.1 1252.31
  5117.1 1257.82  5122.5 1262.82  5140.0 1264.24  5171.0 1274.62  5193.8 1283.96
  5200.4 1288.79  5224.8 1302.00  5236.9 1310.97  5254.4 1317.05  5269.2 1318.93
#Mann=6,-1,0
  4539.0    0.12       0  4875.0    0.07       0  4994.6    0.05       0
  4998.7    0.07       0  5027.4    0.12       0  5200.4    0.07       0
Bank Sta=4994.6,4998.7
Exp/Cntr=0.3,0.1

Type RM Length L Ch R = 1,9634,429,429,429
BEGIN DESCRIPTION:
Stream0166_DS 21.0
END DESCRIPTION:
XS GIS Cut Line= 4
      2090075.03     13893675.02      2089783.08     13893526.72
      2089675.00     13893525.00      2089425.01     13893575.00
#Sta/Elev= 30
  4564.1 1308.83  4617.0 1292.98  4639.2 1288.34  4683.7 1281.94  4711.6 1279.97
  4743.6 1274.72  4750.5 1272.10  4756.1 1272.72  4801.8 1266.85  4855.8 1260.04
  4861.8 1256.98  4867.4 1257.43  4884.1 1252.34  4899.6 1251.58  4919.6 1246.00
  4949.6 1242.25  4979.7 1242.60  4989.7 1240.66  4995.1 1237.70  4995.4 1237.20
  4999.3 1237.70  5030.2 1242.00  5071.0 1243.65  5091.4 1248.36  5122.0 1259.51
  5132.2 1267.52  5163.8 1282.58  5213.8 1312.63  5224.0 1316.47  5254.6 1322.53
#Mann=5,-1,0
  4564.1    0.12       0  4801.8    0.07       0  4995.1    0.05       0
  4999.3    0.07       0  5163.8    0.07       0
Bank Sta=4995.1,4999.3
Exp/Cntr=0.3,0.1

Type RM Length L Ch R = 1,9205,447,447,447
BEGIN DESCRIPTION:
Stream0166_DS 20.0
END DESCRIPTION:
XS GIS Cut Line= 3
      2090124.98     13893574.98      2089725.00     13893175.00
      2089725.00     13892974.96
#Sta/Elev= 30
  4438.8 1312.78  4442.3 1312.78  4467.1 1305.24  4509.5 1290.57  4523.6 1287.37
  4537.8 1285.23  4594.3 1279.05  4608.5 1276.15  4721.6 1247.06  4735.8 1244.82
  4766.3 1237.92  4792.3 1236.42  4834.8 1235.89  4891.3 1237.01  4976.2 1236.81
  4990.9 1233.78  4998.8 1229.85  4999.1 1229.35  5003.1 1229.85  5014.5 1230.28
  5044.5 1233.99  5054.5 1237.23  5084.5 1253.66  5094.5 1261.89  5114.5 1273.74
  5124.5 1280.84  5154.5 1297.72  5174.5 1314.73  5184.5 1316.21  5204.5 1316.94
#Mann=5,-1,0
  4438.8    0.12       0  4766.3    0.07       0  4990.9    0.12       0
  4998.8    0.05       0  5003.1    0.12       0
Bank Sta=4998.8,5003.1
Exp/Cntr=0.3,0.1

Type RM Length L Ch R = 1,8758,451,451,451
BEGIN DESCRIPTION:
Stream0166_DS 19.0
END DESCRIPTION:
XS GIS Cut Line= 3
      2090175.00     13893375.01      2090125.00     13893225.00
      2089946.26     13892863.50
#Sta/Elev= 30
  4842.2 1283.18  4863.3 1280.95  4884.4 1273.63  4894.9 1267.95  4905.5 1263.30
  4921.3 1251.64  4926.5 1242.94  4958.2 1225.95  4968.7 1225.25  4977.1 1223.43
  4977.4 1222.93  4981.4 1223.43  4989.8 1224.03  4997.7 1227.54  5003.1 1227.54
  5008.8 1229.32  5053.6 1230.80  5076.1 1233.88  5098.5 1242.19  5165.8 1260.90
  5178.8 1265.87  5216.3 1273.45  5233.1 1278.11  5255.6 1279.47  5300.4 1285.61
  5322.9 1291.20  5335.0 1295.58  5373.3 1304.05  5379.6 1306.74  5403.6 1308.61
#Mann=3,-1,0
  4842.2    0.12       0  4977.1    0.05       0  4981.4    0.12       0
Bank Sta=4977.1,4981.4
Exp/Cntr=0.3,0.1

Type RM Length L Ch R = 1,8307,420,420,420
BEGIN DESCRIPTION:
Stream0166_DS 18.0
END DESCRIPTION:
XS GIS Cut Line= 3
      2090625.02     13893075.02      2090375.00     13892875.00
      2090050.48     13892790.61
#Sta/Elev= 30
  4684.7 1273.20  4698.3 1272.31  4735.2 1265.04  4764.7 1253.43  4834.4 1233.14
  4855.2 1229.24  4904.8 1222.92  4954.5 1220.36  4962.5 1218.71  4968.9 1214.54
  4981.0 1213.36  4981.3 1212.86  4985.5 1213.36  4991.3 1215.01  4997.7 1219.89
  5005.9 1220.66  5022.6 1224.09  5027.7 1232.38  5046.2 1235.85  5087.5 1256.98
  5103.6 1260.27  5108.8 1265.42  5139.0 1270.65  5149.5 1274.47  5242.5 1286.84
  5252.9 1289.06  5265.8 1294.54  5294.2 1300.13  5306.3 1304.57  5340.2 1307.69
#Mann=5,-1,0
  4684.7    0.12       0  4764.7    0.07       0  4981.0    0.05       0
  4985.5    0.07       0  5005.9    0.12       0
Bank Sta=4981,4985.5
Exp/Cntr=0.3,0.1

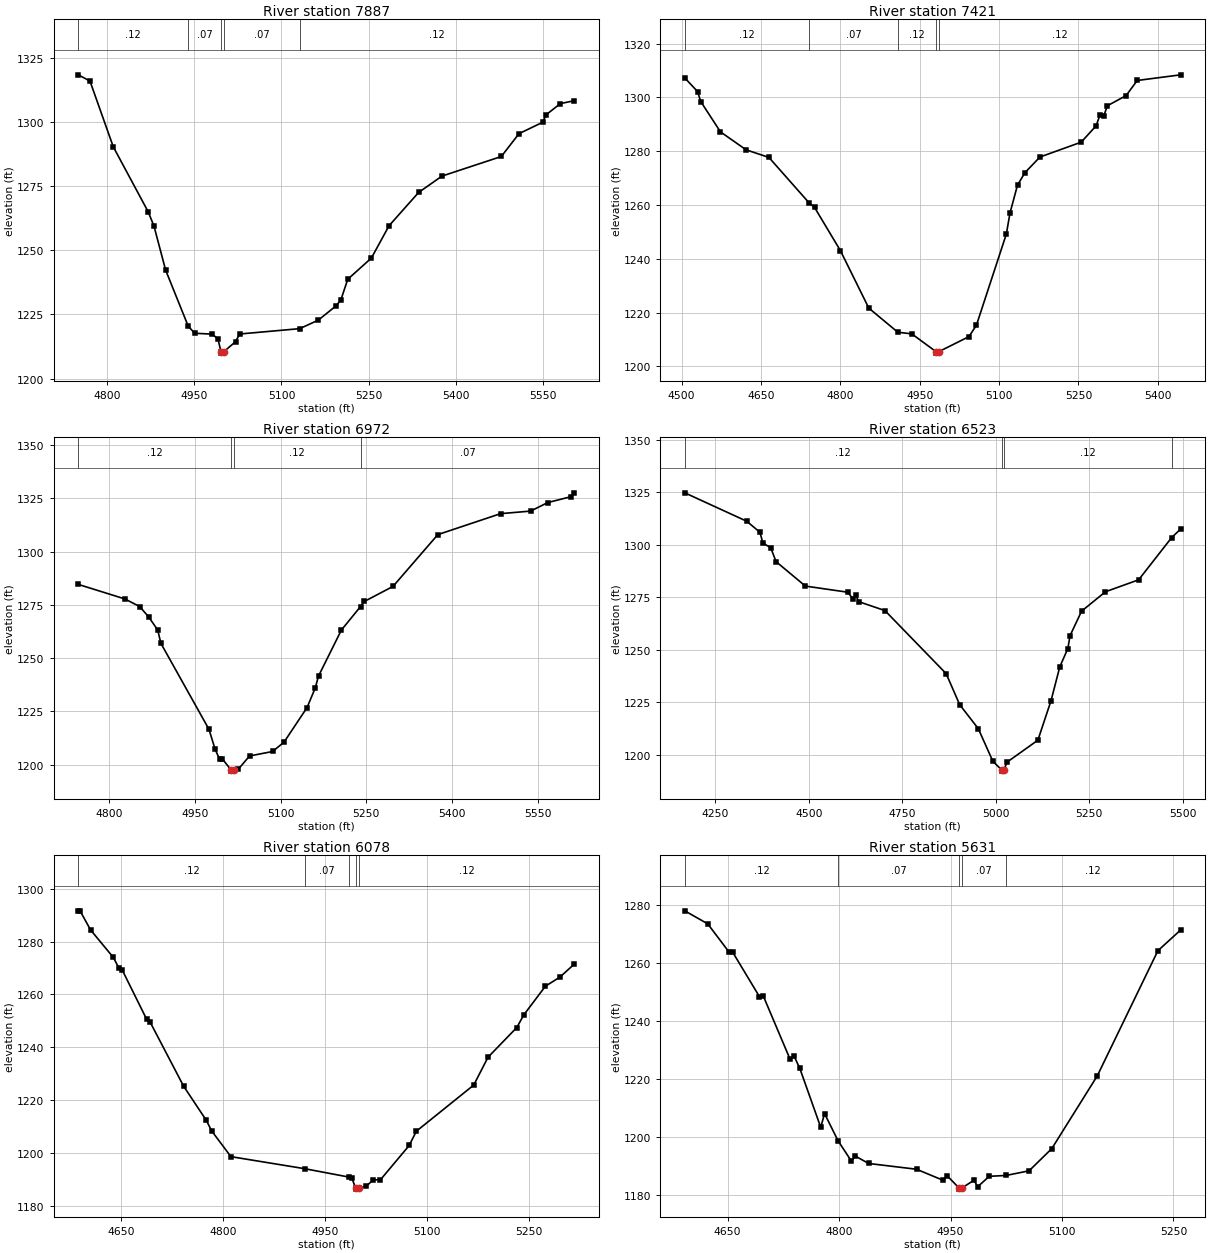
Type RM Length L Ch R = 1,7887,466,466,466
BEGIN DESCRIPTION:
Stream0166_DS 17.0
END DESCRIPTION:
XS GIS Cut Line= 3
      2090924.95     13892625.00      2090675.00     13892625.00
      2090081.65     13892728.11
#Sta/Elev= 30
  4750.9 1318.41  4770.9 1315.98  4810.9 1290.38  4870.9 1265.05  4880.9 1259.48
  4900.9 1242.32  4939.8 1220.42  4950.9 1217.69  4980.9 1217.34  4990.9 1215.49
  4996.1 1210.44  4996.4 1209.94  5000.6 1210.44  5021.2 1214.41  5028.1 1217.39
  5131.4 1219.48  5163.3 1222.80  5193.7 1228.33  5202.0 1230.60  5214.0 1238.74
  5254.6 1247.00  5285.0 1259.61  5335.8 1272.57  5375.9 1278.94  5477.9 1286.58
  5508.3 1295.48  5548.9 1299.91  5554.9 1302.84  5579.4 1307.20  5603.1 1308.31
#Mann=5,-1,0
  4750.9    0.12       0  4939.8    0.07       0  4996.1    0.05       0
  5000.6    0.07       0  5131.4    0.12       0
Bank Sta=4996.1,5000.6
Exp/Cntr=0.3,0.1

Type RM Length L Ch R = 1,7421,449,449,449
BEGIN DESCRIPTION:
Stream0166_DS 16.0
END DESCRIPTION:
XS GIS Cut Line= 3
      2090814.34     13892314.91      2090325.00     13892425.00
      2090012.25     13892728.10
#Sta/Elev= 30
  4506.1 1307.27  4530.2 1302.22  4536.2 1298.51  4573.5 1287.22  4621.9 1280.55
  4665.1 1277.71  4740.9 1260.84  4751.4 1259.10  4800.1 1243.09  4853.9 1221.67
  4908.8 1212.70  4935.1 1212.11  4981.2 1205.44  4981.5 1204.94  4985.7 1205.44
  5043.0 1211.06  5057.2 1215.28  5113.8 1249.22  5120.7 1257.03  5134.9 1267.43
  5149.0 1272.06  5177.3 1277.86  5255.3 1283.39  5283.5 1289.48  5290.5 1293.35
  5297.7 1293.00  5304.7 1296.92  5340.1 1300.70  5361.2 1306.33  5443.2 1308.43
#Mann=5,-1,0
  4506.1    0.12       0  4740.9    0.07       0  4908.8    0.12       0
  4981.2    0.05       0  4985.7    0.12       0
Bank Sta=4981.2,4985.7
Exp/Cntr=0.3,0.1

Type RM Length L Ch R = 1,6972,449,449,449
BEGIN DESCRIPTION:
Stream0166_DS 15.0
END DESCRIPTION:
XS GIS Cut Line= 3
      2090762.21     13892203.79      2090525.00     13892125.00
      2089909.04     13892068.47
#Sta/Elev= 30
  4745.5 1284.59  4826.9 1277.79  4852.9 1274.23  4869.0 1269.25  4884.6 1263.18
  4890.1 1256.96  4974.4 1216.59  4984.9 1207.40  4992.8 1202.68  4998.0 1202.68
  5013.2 1197.52  5013.5 1197.02  5017.8 1197.52  5025.6 1197.88  5045.4 1204.13
  5085.8 1206.23  5105.9 1210.65  5146.1 1226.83  5160.4 1235.95  5166.2 1241.61
  5206.3 1263.21  5239.8 1274.20  5246.5 1276.60  5296.7 1283.66  5375.2 1307.95
  5485.2 1317.79  5537.7 1318.98  5567.8 1322.99  5608.0 1325.71  5614.0 1327.55
#Mann=4,-1,0
  4745.5    0.12       0  5013.2    0.05       0  5017.8    0.12       0
  5239.8    0.07       0
Bank Sta=5013.2,5017.8
Exp/Cntr=0.3,0.1

Type RM Length L Ch R = 1,6523,445,445,445
BEGIN DESCRIPTION:
Stream0166_DS 14.0
END DESCRIPTION:
XS GIS Cut Line= 3
      2091192.80     13892370.47      2090675.00     13891725.00
      2090249.15     13891464.70
#Sta/Elev= 30
  4167.9 1324.82  4333.7 1311.28  4368.9 1306.04  4376.9 1300.87  4397.7 1298.70
  4412.1 1292.05  4490.5 1280.41  4604.1 1277.48  4618.5 1274.08  4624.9 1276.35
  4632.9 1273.00  4703.3 1268.75  4867.2 1238.70  4903.4 1223.91  4953.0 1212.55
  4992.2 1196.94  5016.2 1192.78  5016.6 1192.28  5020.9 1192.78  5030.6 1196.62
  5112.6 1207.02  5147.8 1225.84  5171.2 1241.96  5192.8 1250.68  5198.6 1256.77
  5229.5 1268.47  5293.4 1277.71  5382.2 1283.40  5470.5 1303.50  5494.5 1307.58
#Mann=4,-1,0
  4167.9    0.12       0  5016.2    0.05       0  5020.9    0.12       0
  5470.5    0.07       0
Bank Sta=5016.2,5020.9
Exp/Cntr=0.3,0.1

Type RM Length L Ch R = 1,6078,447,447,447
BEGIN DESCRIPTION:
Stream0166_DS 13.0
END DESCRIPTION:
XS GIS Cut Line= 3
      2091224.96     13891225.01      2090825.00     13891325.00
      2090525.00     13891425.00
#Sta/Elev= 30
  4587.4 1291.62  4589.9 1291.62  4605.4 1284.38  4638.9 1273.97  4646.6 1270.14
  4651.8 1269.28  4687.9 1250.51  4693.0 1249.46  4742.0 1225.30  4775.5 1212.31
  4783.2 1208.37  4811.6 1198.60  4919.8 1194.05  4984.4 1190.90  4989.4 1190.38
  4994.7 1186.81  4995.0 1186.31  4999.5 1186.81  5010.2 1187.38  5020.8 1189.82
  5031.3 1189.86  5073.5 1202.82  5084.0 1208.21  5168.3 1225.68  5189.4 1236.24
  5231.6 1247.46  5242.1 1252.31  5273.7 1263.11  5294.8 1266.50  5315.9 1271.41
#Mann=5,-1,0
  4587.4    0.12       0  4919.8    0.07       0  4984.4    0.12       0
  4994.7    0.05       0  4999.5    0.12       0
Bank Sta=4994.7,4999.5
Exp/Cntr=0.3,0.1

Type RM Length L Ch R = 1,5631,388,388,388
BEGIN DESCRIPTION:
Stream0166_DS 12.0
END DESCRIPTION:
XS GIS Cut Line= 3
      2091124.98     13891074.99      2090725.00     13890975.00
      2090475.04     13891024.99
#Sta/Elev= 30
  4592.4 1278.05  4623.3 1273.54  4651.6 1263.92  4656.8 1263.77  4692.9 1248.39
  4698.0 1248.64  4734.1 1226.75  4739.3 1227.91  4747.0 1223.74  4775.3 1203.27
  4780.5 1207.99  4798.7 1198.58  4816.6 1191.58  4821.7 1193.35  4839.8 1190.77
  4904.2 1188.78  4940.3 1184.93  4945.4 1186.54  4961.0 1182.41  4961.4 1181.91
  4965.9 1182.41  4981.5 1184.97  4986.6 1182.75  5002.1 1186.34  5024.6 1186.63
  5055.7 1188.24  5086.3 1195.93  5147.5 1221.06  5229.0 1264.27  5259.6 1271.42
#Mann=5,-1,0
  4592.4    0.12       0  4798.7    0.07       0  4961.0    0.05       0
  4965.9    0.07       0  5024.6    0.12       0
Bank Sta=4961,4965.9
Exp/Cntr=0.3,0.1

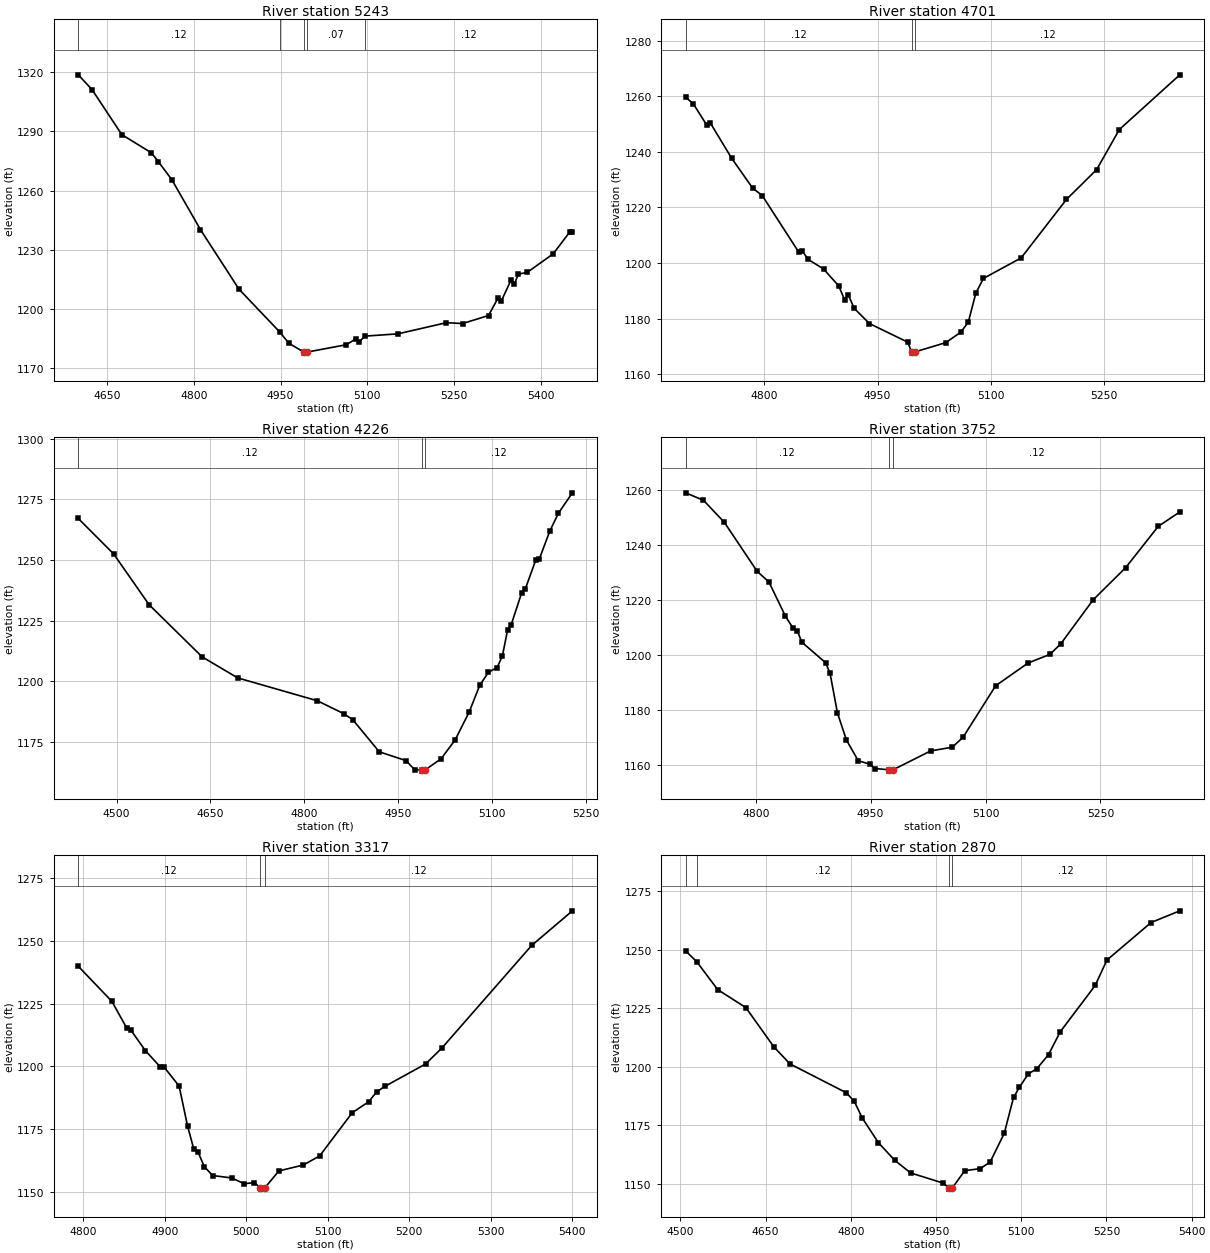
Type RM Length L Ch R = 1,5243,542,542,542
BEGIN DESCRIPTION:
Stream0166_DS 11.0
END DESCRIPTION:
XS GIS Cut Line= 3
      2091301.16     13890952.17      2090919.80     13890706.27
      2090561.38     13890885.48
#Sta/Elev= 30
  4600.2 1318.66  4624.0 1311.21  4675.5 1288.35  4726.5 1279.15  4738.9 1274.57
  4762.2 1265.41  4811.5 1240.18  4878.1 1209.99  4948.2 1188.39  4964.5 1182.53
  4990.5 1178.05  4990.9 1177.55  4995.4 1178.05  5063.6 1181.80  5080.4 1184.79
  5086.0 1183.20  5095.6 1186.16  5153.1 1187.33  5236.9 1192.99  5264.9 1192.55
  5309.6 1196.62  5326.4 1205.64  5331.9 1204.07  5348.7 1214.68  5354.3 1212.49
  5361.2 1217.61  5376.7 1218.51  5421.4 1227.88  5449.9 1238.87  5454.7 1238.87
#Mann=5,-1,0
  4600.2    0.12       0  4948.2    0.07       0  4990.5    0.05       0
  4995.4    0.07       0  5095.6    0.12       0
Bank Sta=4990.5,4995.4
Exp/Cntr=0.3,0.1

Type RM Length L Ch R = 1,4701,475,475,475
BEGIN DESCRIPTION:
Stream0166_DS 10.0
END DESCRIPTION:
XS GIS Cut Line= 3
      2091124.97     13890375.00      2090825.00     13890325.00
      2090475.01     13890325.00
#Sta/Elev= 30
  4696.0 1259.69  4706.1 1257.36  4723.9 1249.69  4728.9 1250.34  4756.8 1237.78
  4784.7 1226.97  4797.4 1224.29  4845.5 1204.01  4850.6 1204.28  4858.2 1201.28
  4878.5 1197.85  4898.7 1191.72  4906.3 1186.83  4911.4 1188.49  4919.0 1183.71
  4939.3 1178.18  4990.0 1171.48  4995.0 1168.03  4995.4 1167.53  5000.2 1168.03
  5040.1 1171.28  5060.1 1175.04  5070.1 1178.64  5080.1 1189.11  5090.1 1194.42
  5140.1 1201.83  5200.1 1222.89  5240.1 1233.65  5270.1 1248.07  5350.1 1267.77
#Mann=3,-1,0
  4696.0    0.12       0  4995.0    0.05       0  5000.2    0.12       0
Bank Sta=4995,5000.2
Exp/Cntr=0.3,0.1

Type RM Length L Ch R = 1,4226,474,474,474
BEGIN DESCRIPTION:
Stream0166_DS 9.0
END DESCRIPTION:
XS GIS Cut Line= 3
      2091225.01     13890275.01      2090825.00     13889875.00
      2090625.00     13889775.00
#Sta/Elev= 30
  4438.8 1267.16  4495.4 1252.52  4551.9 1231.59  4636.8 1210.04  4693.4 1201.39
  4820.6 1191.96  4863.1 1186.60  4877.2 1184.16  4919.6 1170.89  4962.1 1167.27
  4976.2 1163.52  4987.8 1163.42  4988.2 1162.92  4993.0 1163.42  5018.5 1168.06
  5040.8 1175.80  5063.2 1187.30  5080.0 1198.27  5093.9 1203.70  5107.9 1205.66
  5116.3 1210.51  5124.7 1221.31  5130.3 1223.32  5147.0 1236.45  5152.6 1237.92
  5169.4 1249.88  5175.0 1250.26  5191.8 1261.85  5205.7 1269.32  5228.1 1277.74
#Mann=3,-1,0
  4438.8    0.12       0  4987.8    0.05       0  4993.0    0.12       0
Bank Sta=4987.8,4993
Exp/Cntr=0.3,0.1

Type RM Length L Ch R = 1,3752,435,435,435
BEGIN DESCRIPTION:
Stream0166_DS 8.0
END DESCRIPTION:
XS GIS Cut Line= 3
      2091424.99     13889774.99      2091175.00     13889625.00
      2090924.99     13889374.99
#Sta/Elev= 30
  4708.5 1259.07  4731.8 1256.35  4759.0 1248.36  4801.8 1230.57  4817.3 1226.63
  4838.7 1214.27  4848.4 1210.01  4854.3 1208.92  4860.1 1204.81  4891.2 1197.31
  4897.0 1193.52  4906.7 1179.04  4918.4 1169.22  4933.9 1161.66  4949.5 1160.39
  4955.3 1158.84  4974.0 1158.40  4974.5 1157.90  4979.4 1158.40  5028.3 1165.24
  5056.6 1166.60  5070.7 1170.22  5113.2 1188.93  5155.6 1197.22  5183.9 1200.31
  5198.0 1204.08  5240.4 1220.15  5282.9 1231.85  5325.3 1246.83  5353.6 1252.13
#Mann=3,-1,0
  4708.5    0.12       0  4974.0    0.05       0  4979.4    0.12       0
Bank Sta=4974,4979.4
Exp/Cntr=0.3,0.1

Type RM Length L Ch R = 1,3317,447,447,447
BEGIN DESCRIPTION:
Stream0166_DS 7.0
END DESCRIPTION:
XS GIS Cut Line= 3
      2091524.96     13889324.99      2091325.00     13889275.00
      2090925.02     13889275.00
#Sta/Elev= 30
  4793.9 1239.89  4835.1 1225.91  4853.1 1215.40  4858.3 1214.49  4876.3 1206.22
  4894.4 1199.80  4899.5 1199.56  4917.6 1192.13  4927.9 1176.29  4935.6 1167.01
  4940.7 1165.94  4948.5 1159.99  4958.8 1156.45  4982.0 1155.50  4997.4 1153.19
  5010.0 1153.62  5017.3 1151.53  5017.8 1151.03  5022.7 1151.53  5040.0 1158.29
  5070.0 1160.65  5090.0 1164.27  5130.0 1181.51  5150.0 1185.84  5160.0 1189.83
  5170.0 1192.00  5220.0 1200.95  5240.0 1207.32  5350.0 1248.18  5400.0 1261.99
#Mann=3,-1,0
  4793.9    0.12       0  5017.3    0.05       0  5022.7    0.12       0
Bank Sta=5017.3,5022.7
Exp/Cntr=0.3,0.1

Type RM Length L Ch R = 1,2870,465,465,465
BEGIN DESCRIPTION:
Stream0166_DS 6.0
END DESCRIPTION:
XS GIS Cut Line= 3
      2091674.98     13889174.98      2091325.00     13888825.00
      2090960.16     13888738.52
#Sta/Elev= 30
  4509.3 1249.55  4529.0 1244.88  4565.8 1232.97  4615.3 1225.30  4664.8 1208.44
  4693.1 1201.18  4792.1 1188.87  4806.3 1185.12  4820.4 1177.98  4848.7 1167.48
  4877.0 1160.04  4905.3 1154.56  4961.8 1150.26  4973.3 1148.12  4973.7 1147.62
  4978.7 1148.12  5000.7 1155.53  5027.9 1156.38  5045.4 1159.24  5070.2 1171.49
  5086.5 1186.83  5096.7 1191.13  5112.4 1196.91  5127.6 1199.14  5148.1 1205.17
  5168.7 1214.92  5230.3 1234.78  5250.9 1245.62  5328.7 1261.70  5379.2 1266.70
#Mann=4,-1,0
  4509.3    0.07       0  4529.0    0.12       0  4973.3    0.05       0
  4978.7    0.12       0
Bank Sta=4973.3,4978.7
Exp/Cntr=0.3,0.1

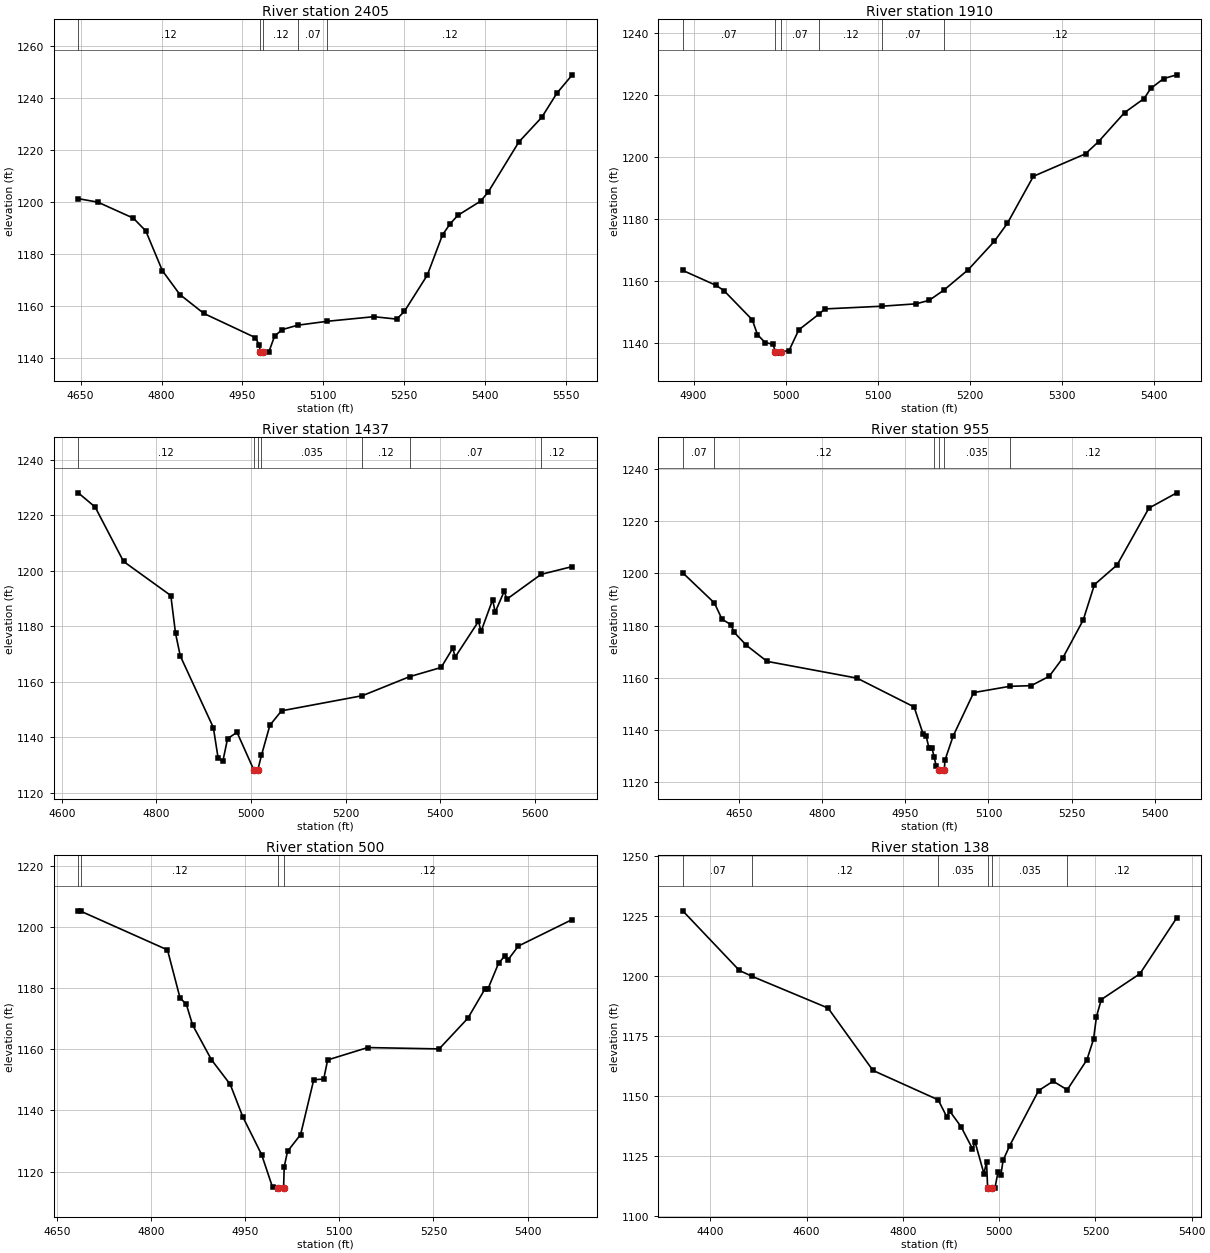
Type RM Length L Ch R = 1,2405,495,495,495
BEGIN DESCRIPTION:
Stream0166_DS 5.0
END DESCRIPTION:
XS GIS Cut Line= 3
      2091949.75     13888655.19      2091625.00     13888525.00
      2091224.97     13888124.97
#Sta/Elev= 30
  4645.7 1201.32  4682.1 1199.97  4747.8 1193.82  4770.9 1188.90  4801.6 1173.63
  4834.0 1164.45  4878.5 1157.17  4974.0 1147.87  4980.8 1145.14  4983.4 1142.41
  4983.9 1141.91  4988.9 1142.41  4999.1 1142.44  5009.7 1148.52  5023.9 1150.96
  5052.2 1152.64  5107.4 1154.16  5193.6 1155.92  5236.0 1154.99  5250.1 1157.95
  5292.6 1171.90  5320.8 1187.40  5335.0 1191.66  5349.1 1194.88  5391.6 1200.39
  5405.7 1203.93  5462.3 1223.12  5504.7 1232.59  5533.0 1241.94  5561.3 1248.94
#Mann=5,-1,0
  4645.7    0.12       0  4983.4    0.05       0  4988.9    0.12       0
  5052.2    0.07       0  5107.4    0.12       0
Bank Sta=4983.4,4988.9
Exp/Cntr=0.3,0.1

Type RM Length L Ch R = 1,1910,473,473,473
BEGIN DESCRIPTION:
Stream0166_DS 4.0
END DESCRIPTION:
XS GIS Cut Line= 3
      2092025.00     13888275.00      2091975.00     13888175.00
      2091674.98     13887874.98
#Sta/Elev= 30
  4888.2 1163.39  4924.5 1158.53  4932.9 1156.86  4963.7 1147.40  4969.3 1142.61
  4977.6 1140.06  4986.0 1139.52  4988.8 1137.14  4989.3 1136.64  4994.0 1136.64
  4994.5 1137.14  5003.5 1137.43  5014.1 1144.16  5036.4 1149.35  5042.4 1150.93
  5104.4 1151.81  5141.4 1152.58  5155.6 1153.71  5171.6 1157.02  5198.0 1163.61
  5226.3 1172.78  5240.4 1178.57  5268.7 1193.81  5325.3 1201.09  5339.4 1205.02
  5367.7 1214.42  5388.9 1218.96  5396.0 1222.21  5410.1 1225.41  5424.3 1226.62
#Mann=6,-1,0
  4888.2    0.07       0  4988.8    0.05       0  4994.5    0.07       0
  5036.4    0.12       0  5104.4    0.07       0  5171.6    0.12       0
Bank Sta=4988.8,4994.5
Exp/Cntr=0.3,0.1

Type RM Length L Ch R = 1,1437,482,482,482
BEGIN DESCRIPTION:
Stream0166_DS 3.0
END DESCRIPTION:
XS GIS Cut Line= 3
      2092640.71     13887828.80      2092275.00     13887825.00
      2091642.22     13887579.38
#Sta/Elev= 30
  4634.7 1228.06  4670.4 1222.95  4730.4 1203.37  4830.4 1191.09  4840.4 1177.49
  4850.4 1169.36  4920.4 1143.54  4930.4 1132.60  4940.4 1131.42  4950.4 1139.58
  4970.4 1141.86  5005.7 1128.39  5006.2 1127.89  5014.4 1128.39  5022.0 1133.53
  5039.9 1144.42  5064.5 1149.60  5235.6 1155.05  5335.1 1161.88  5401.9 1165.20
  5426.5 1172.10  5431.8 1168.98  5480.9 1181.79  5486.3 1178.15  5510.8 1189.59
  5516.2 1185.11  5535.4 1192.68  5540.7 1189.77  5613.2 1198.71  5679.2 1201.52
#Mann=7,-1,0
  4634.7    0.12       0  5005.7    0.05       0  5014.4    0.12       0
  5022.0   0.035       0  5235.6    0.12       0  5335.1    0.07       0
  5613.2    0.12       0
Bank Sta=5005.7,5014.4
Exp/Cntr=0.3,0.1

Type RM Length L Ch R = 1,955,455,455,455
BEGIN DESCRIPTION:
Stream0166_DS 2.0
END DESCRIPTION:
XS GIS Cut Line= 3
      2092665.03     13887592.69      2092275.00     13887375.00
      2091839.35     13887290.74
#Sta/Elev= 30
  4549.0 1200.26  4606.1 1188.66  4619.8 1182.42  4635.8 1180.35  4641.5 1177.45
  4663.6 1172.43  4700.9 1166.24  4863.1 1159.80  4966.0 1148.73  4982.0 1138.49
  4987.7 1137.52  4992.8 1133.00  4998.2 1133.00  5001.9 1129.64  5005.9 1126.00
  5011.6 1124.58  5012.1 1124.08  5020.4 1124.58  5021.6 1128.28  5036.4 1137.59
  5073.4 1154.25  5138.2 1156.65  5177.0 1156.91  5209.6 1160.52  5233.8 1167.47
  5270.7 1182.07  5291.0 1195.71  5331.8 1203.28  5389.2 1225.11  5439.4 1230.98
#Mann=6,-1,0
  4549.0    0.07       0  4606.1    0.12       0  5001.9   0.035       0
  5011.6    0.05       0  5020.4   0.035       0  5138.2    0.12       0
Bank Sta=5011.6,5020.4
Exp/Cntr=0.3,0.1

Type RM Length L Ch R = 1,500,362,362,362
BEGIN DESCRIPTION:
Stream0166_DS 1.0
END DESCRIPTION:
XS GIS Cut Line= 3
      2092887.24     13887127.41      2092575.00     13887125.00
      2092123.34     13886978.10
#Sta/Elev= 30
  4684.1 1205.33  4688.5 1205.17  4826.3 1192.54  4846.3 1176.81  4856.3 1174.76
  4866.3 1167.97  4896.3 1156.61  4926.3 1148.52  4946.3 1137.92  4976.3 1125.54
  4993.8 1114.80  5002.4 1114.75  5002.9 1114.25  5011.3 1114.75  5012.3 1121.56
  5017.6 1126.63  5038.4 1132.09  5059.4 1150.08  5075.2 1150.25  5081.5 1156.53
  5145.3 1160.58  5259.2 1160.14  5305.0 1170.20  5331.7 1179.59  5337.0 1179.80
  5353.9 1188.19  5363.6 1190.53  5368.9 1189.30  5385.4 1193.80  5471.3 1202.49
#Mann=4,-1,0
  4684.1    0.07       0  4688.5    0.12       0  5002.4    0.05       0
  5011.3    0.12       0
Bank Sta=5002.4,5011.3
Exp/Cntr=0.3,0.1

Type RM Length L Ch R = 1,138,0,0,0
BEGIN DESCRIPTION:
Stream0166_DS 0.0
END DESCRIPTION:
XS GIS Cut Line= 3
      2093033.64     13887072.61      2092427.03     13886819.48
      2092058.47     13886839.41
#Sta/Elev= 30
  4342.7 1226.96  4460.4 1202.12  4487.4 1199.61  4644.6 1186.46  4737.9 1160.48
  4873.4 1148.23  4891.6 1141.01  4897.0 1143.65  4920.8 1137.08  4944.7 1127.84
  4950.1 1130.64  4968.5 1117.46  4973.9 1122.44  4976.1 1111.54  4976.6 1111.04
  4985.0 1111.54  4991.4 1111.68  4997.7 1118.09  5003.5 1116.75  5008.3 1123.05
  5022.1 1129.20  5082.1 1152.09  5112.2 1155.99  5141.5 1152.40  5182.3 1164.87
  5196.1 1173.42  5202.3 1182.92  5212.3 1190.01  5292.5 1200.74  5369.1 1224.04
#Mann=6,-1,0
  4342.7    0.07       0  4487.4    0.12       0  4873.4   0.035       0
  4976.1   0.035       0  4985.0   0.035       0  5141.5    0.12       0
Bank Sta=4976.1,4985
Exp/Cntr=0.3,0.1

Chan Stop Cuts=-1