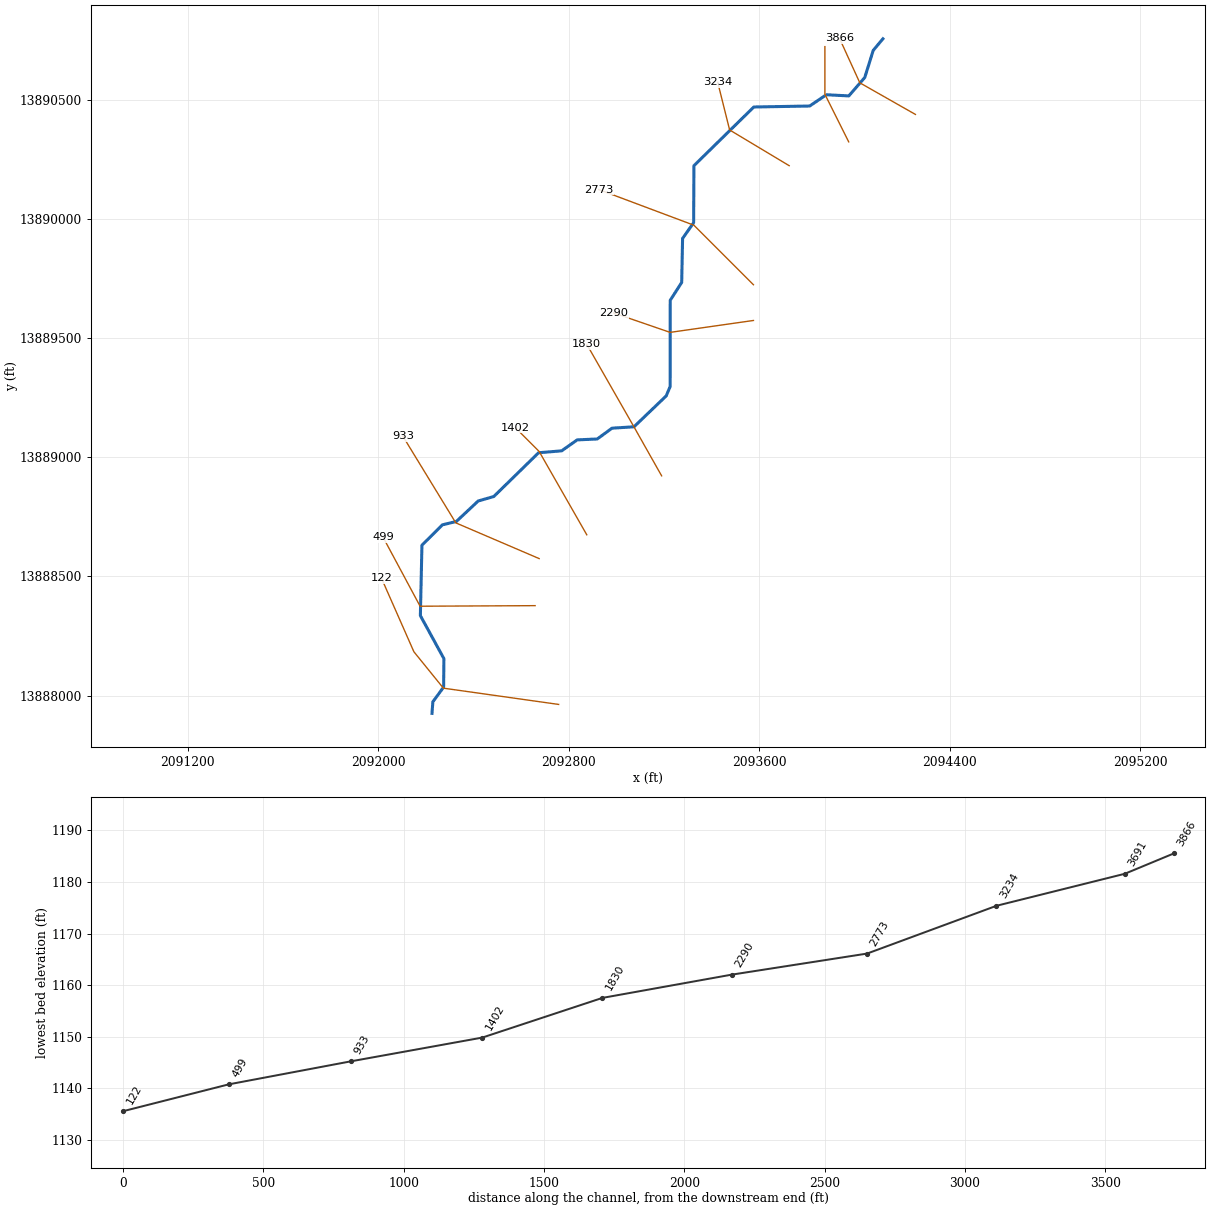
--- Stream0167_DS.prj (project) ---

Proj Title=Stream0167_DS Base Level Engineering
Current Plan=p01
Default Exp/Contr=0.3,0.1
English Units
Geom File=g01
Flow File=f01
Plan File=p01
BEGIN DESCRIPTION:
Stream0167_DS
END DESCRIPTION:

--- Stream0167_DS.p01 (plan) ---

Plan Title=Multiple Run
Short Identifier=Multiple
Geom File=g01
Flow File=f01
Subcritical Flow
K Sum by GR= 0
Std Step Tol= 0.01
Critical Tol= 0.01
Num of Std Step Trials= 20
Max Error Tol= 0.3
Flow Tol Ratio= 0.001
Split Flow NTrial= 30
Split Flow Tol= 0.02
Split Flow Ratio= 0.02
Log Output Level= 0
Friction Slope Method= 1
Unsteady Friction Slope Method= 2
Unsteady Bridges Friction Slope Method= 1
Parabolic Critical Depth
Global Vel Dist=  1 , 1 , 1
Global Log Level= 0
CheckData=True
Encroach Param= -1, 0, 0, 0
BEGIN DESCRIPTION:
Multiple Run
END DESCRIPTION:

--- Stream0167_DS.f01 (steady flow) ---

Flow Title=Multiple
Number of Profiles=7
Profile Names=10-year,25-year,50-year,1pct_min,100-year,1pct_plu,500-year
River Rch & RM= Stream0167_DS,Reach-1,3866
     876    1471    2034    1366    2726    5440    4837
River Rch & RM= Stream0167_DS,Reach-1,2773
    1606    2795    3957    2714    5415   10805   10033
Boundary for River Rch & Prof#=Stream0167_DS,Reach-1,1
Up Type=0
Dn Type=3
Dn Slope=0.005
Boundary for River Rch & Prof#=Stream0167_DS,Reach-1,2
Up Type=0
Dn Type=3
Dn Slope=0.005
Boundary for River Rch & Prof#=Stream0167_DS,Reach-1,3
Up Type=0
Dn Type=3
Dn Slope=0.005
Boundary for River Rch & Prof#=Stream0167_DS,Reach-1,4
Up Type=0
Dn Type=3
Dn Slope=0.005
Boundary for River Rch & Prof#=Stream0167_DS,Reach-1,5
Up Type=0
Dn Type=3
Dn Slope=0.005
Boundary for River Rch & Prof#=Stream0167_DS,Reach-1,6
Up Type=0
Dn Type=3
Dn Slope=0.005
Boundary for River Rch & Prof#=Stream0167_DS,Reach-1,7
Up Type=0
Dn Type=3
Dn Slope=0.005

--- Stream0167_DS.g01 (geometry) ---

Geom Title=Existing Conditions

River Reach=Stream0167_DS,Reach-1
Reach XY= 30
      2094118.67     13890757.90      2094077.96     13890709.18
      2094042.40     13890595.30      2093975.47     13890518.03
      2093881.27     13890523.01      2093811.11     13890475.60
      2093576.46     13890471.46      2093325.00     13890225.00
      2093323.78     13889985.50      2093277.38     13889919.47
      2093273.62     13889734.66      2093225.52     13889659.78
      2093225.20     13889297.65      2093208.57     13889258.23
      2093073.50     13889128.61      2092980.98     13889122.64
      2092919.03     13889077.35      2092834.71     13889073.51
      2092769.43     13889027.47      2092672.57     13889019.48
      2092484.68     13888835.78      2092418.96     13888816.82
      2092327.28     13888730.87      2092268.93     13888716.85
      2092182.80     13888631.21      2092176.20     13888335.50
      2092274.96     13888154.97      2092273.90     13888035.47
      2092228.65     13887973.49      2092225.00     13887925.00

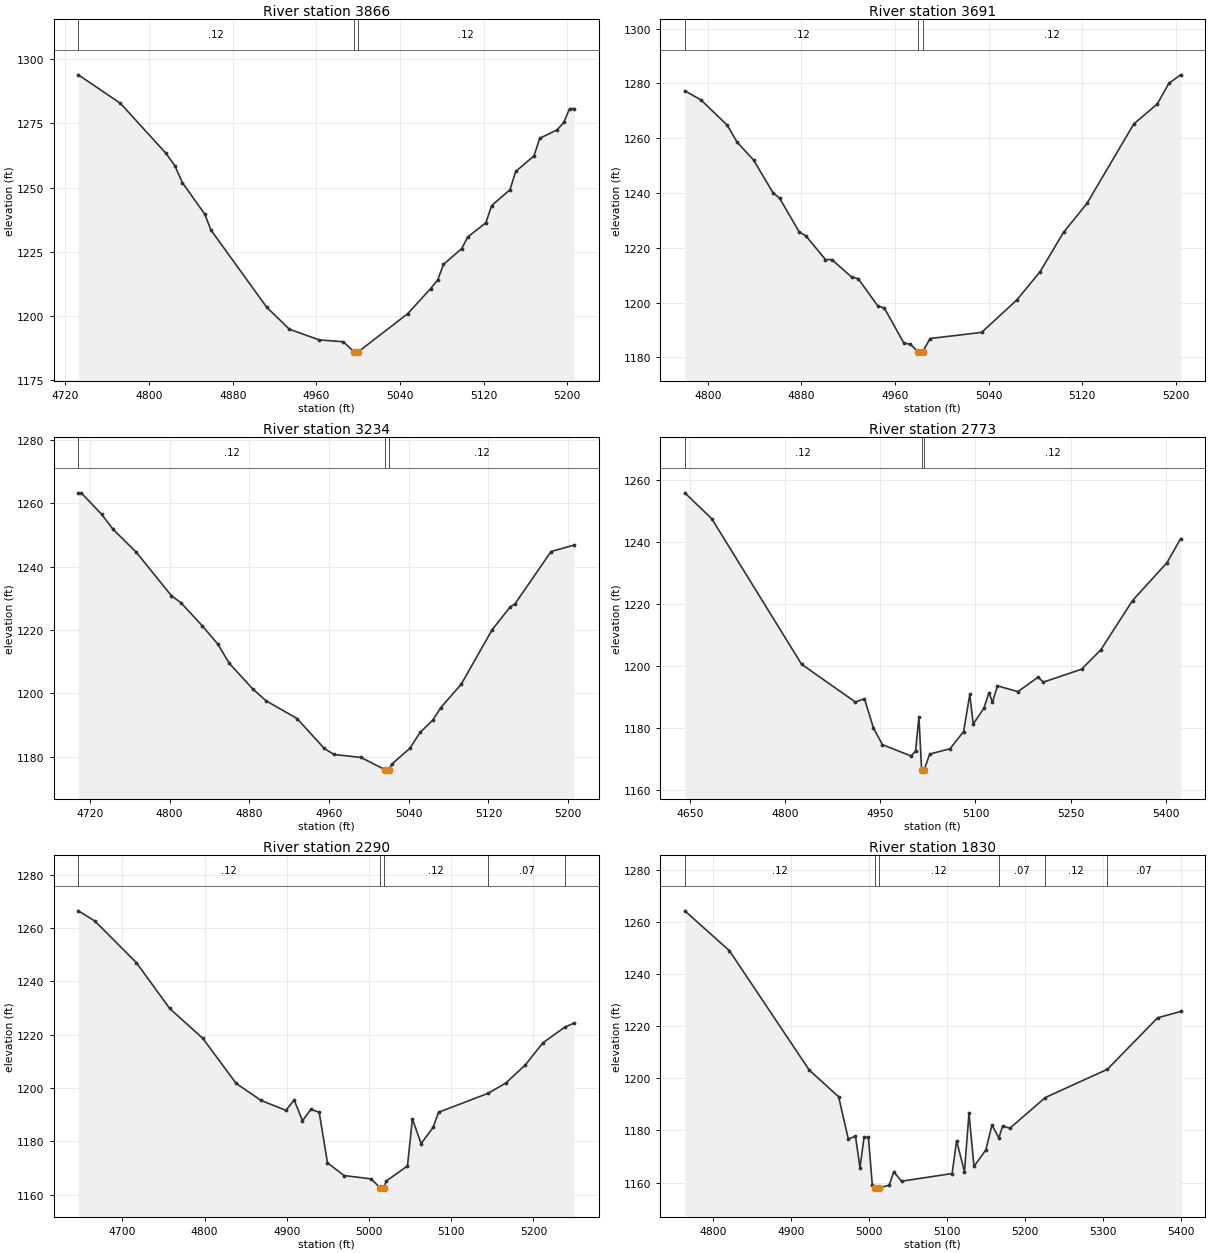
Type RM Length L Ch R = 1,3866,175,175,175
BEGIN DESCRIPTION:
Stream0167_DS 9.0
END DESCRIPTION:
XS GIS Cut Line= 3
      2094255.26     13890440.21      2094021.70     13890573.01
      2093936.30     13890759.83
#Sta/Elev= 30
  4732.4 1293.96  4772.7 1282.84  4815.9 1263.52  4824.7 1258.55  4831.8 1252.00
  4853.4 1239.61  4859.2 1233.49  4912.5 1203.42  4934.2 1194.84  4962.8 1190.68
  4985.8 1189.96  4996.0 1186.03  4996.3 1185.53  5000.0 1186.03  5047.2 1200.85
  5069.2 1210.64  5076.0 1214.02  5081.5 1220.09  5099.1 1226.29  5104.6 1230.73
  5122.1 1236.33  5127.6 1243.02  5145.1 1249.18  5150.6 1256.31  5168.1 1262.39
  5173.6 1269.24  5190.2 1272.51  5196.6 1275.44  5202.1 1280.79  5206.5 1280.79
#Mann=3,-1,0
  4732.4    0.12       0  4996.0    0.05       0  5000.0    0.12       0
Bank Sta=4996,5000
Exp/Cntr=0.3,0.1

Type RM Length L Ch R = 1,3691,457,457,457
BEGIN DESCRIPTION:
Stream0167_DS 8.0
END DESCRIPTION:
XS GIS Cut Line= 3
      2093974.98     13890325.03      2093875.00     13890525.00
      2093875.00     13890725.03
#Sta/Elev= 30
  4780.4 1277.33  4794.3 1273.94  4816.7 1264.74  4825.1 1258.54  4839.1 1252.09
  4855.8 1240.09  4861.4 1238.10  4878.2 1225.79  4883.8 1224.40  4900.6 1215.71
  4906.1 1215.69  4922.9 1209.34  4928.5 1208.76  4945.3 1198.81  4950.9 1198.01
  4967.6 1185.21  4973.2 1184.82  4979.6 1182.08  4979.9 1181.58  4983.6 1182.08
  4990.0 1186.91  5034.0 1189.15  5064.0 1200.95  5084.0 1211.33  5104.0 1225.68
  5124.0 1236.22  5164.0 1265.21  5184.0 1272.46  5194.0 1280.05  5204.0 1283.13
#Mann=3,-1,0
  4780.4    0.12       0  4979.6    0.05       0  4983.6    0.12       0
Bank Sta=4979.6,4983.6
Exp/Cntr=0.3,0.1

Type RM Length L Ch R = 1,3234,461,461,461
BEGIN DESCRIPTION:
Stream0167_DS 7.0
END DESCRIPTION:
XS GIS Cut Line= 3
      2093725.01     13890224.99      2093475.00     13890375.00
      2093425.00     13890574.98
#Sta/Elev= 30
  4708.4 1263.31  4711.3 1263.31  4731.7 1256.56  4743.4 1251.74  4766.7 1244.49
  4801.7 1230.85  4811.4 1228.59  4832.8 1221.30  4848.4 1215.52  4860.0 1209.41
  4883.3 1201.40  4896.9 1197.59  4928.0 1191.99  4955.3 1182.53  4965.0 1180.64
  4992.2 1179.69  5016.0 1175.88  5016.3 1175.38  5020.0 1175.88  5023.2 1177.63
  5041.2 1182.61  5051.5 1187.61  5064.4 1191.56  5072.1 1195.40  5092.7 1202.82
  5123.7 1220.00  5141.7 1227.21  5146.8 1228.26  5182.9 1244.77  5206.1 1246.80
#Mann=3,-1,0
  4708.4    0.12       0  5016.0    0.05       0  5020.0    0.12       0
Bank Sta=5016,5020
Exp/Cntr=0.3,0.1

Type RM Length L Ch R = 1,2773,483,483,483
BEGIN DESCRIPTION:
Stream0167_DS 6.0
END DESCRIPTION:
XS GIS Cut Line= 3
      2093575.03     13889724.97      2093325.00     13889975.00
      2092925.00     13890125.00
#Sta/Elev= 30
  4642.3 1255.89  4684.8 1247.52  4826.2 1200.60  4911.0 1188.40  4925.2 1189.48
  4939.3 1180.08  4953.5 1174.66  4998.6 1171.01  5005.7 1172.57  5011.0 1183.65
  5015.2 1166.62  5015.5 1166.12  5019.4 1166.62  5027.9 1171.61  5060.0 1173.35
  5081.3 1178.87  5091.1 1190.84  5096.5 1181.30  5113.4 1186.45  5121.4 1191.47
  5126.7 1188.28  5134.7 1193.64  5166.8 1191.76  5198.8 1196.44  5206.8 1194.82
  5267.3 1199.01  5297.6 1205.29  5347.4 1221.15  5401.7 1233.39  5423.1 1241.10
#Mann=3,-1,0
  4642.3    0.12       0  5015.2    0.05       0  5019.4    0.12       0
Bank Sta=5015.2,5019.4
Exp/Cntr=0.3,0.1

Type RM Length L Ch R = 1,2290,460,460,460
BEGIN DESCRIPTION:
Stream0167_DS 5.0
END DESCRIPTION:
XS GIS Cut Line= 3
      2093575.01     13889575.00      2093225.00     13889525.00
      2092988.95     13889606.23
#Sta/Elev= 30
  4646.4 1266.52  4666.6 1262.67  4717.1 1247.04  4757.5 1229.86  4797.9 1218.62
  4838.3 1201.76  4868.6 1195.34  4898.9 1191.61  4909.0 1195.50  4919.1 1187.70
  4929.2 1191.99  4939.4 1190.89  4949.5 1171.91  4969.7 1167.13  5002.6 1165.87
  5013.5 1162.53  5013.7 1162.03  5017.7 1162.53  5021.1 1165.08  5046.8 1170.72
  5052.8 1188.40  5063.4 1179.12  5078.0 1185.20  5084.6 1190.88  5144.8 1197.99
  5166.4 1201.84  5190.3 1208.70  5211.5 1216.94  5238.2 1222.84  5249.6 1224.40
#Mann=5,-1,0
  4646.4    0.12       0  5013.5    0.05       0  5017.7    0.12       0
  5144.8    0.07       0  5238.2    0.12       0
Bank Sta=5013.5,5017.7
Exp/Cntr=0.3,0.1

Type RM Length L Ch R = 1,1830,428,428,428
BEGIN DESCRIPTION:
Stream0167_DS 4.0
END DESCRIPTION:
XS GIS Cut Line= 3
      2093189.34     13888922.53      2093075.00     13889125.00
      2092875.02     13889474.97
#Sta/Elev= 30
  4763.5 1264.19  4820.6 1248.94  4923.1 1203.13  4960.7 1192.92  4973.1 1176.74
  4982.3 1177.77  4988.1 1165.73  4993.2 1177.37  4998.9 1177.37  5003.9 1158.97
  5007.6 1158.03  5007.9 1157.53  5011.9 1158.03  5025.5 1159.02  5031.3 1164.14
  5041.4 1160.58  5106.2 1163.50  5111.9 1176.11  5122.0 1164.21  5127.8 1186.62
  5134.2 1166.23  5149.4 1172.55  5157.3 1182.13  5166.1 1177.16  5170.9 1181.75
  5180.3 1180.89  5225.6 1192.64  5305.1 1203.43  5369.6 1223.19  5399.1 1225.62
#Mann=6,-1,0
  4763.5    0.12       0  5007.6    0.05       0  5011.9    0.12       0
  5166.1    0.07       0  5225.6    0.12       0  5305.1    0.07       0
Bank Sta=5007.6,5011.9
Exp/Cntr=0.3,0.1

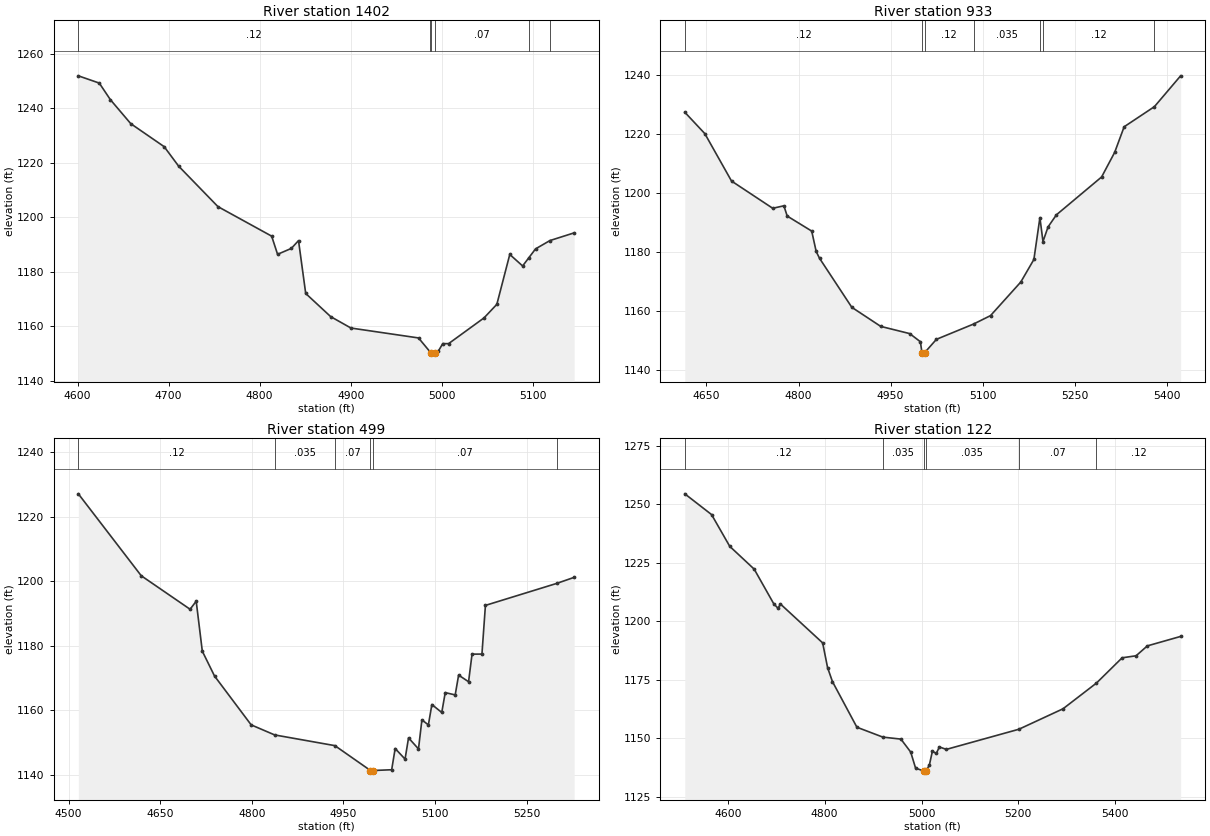
Type RM Length L Ch R = 1,1402,469,469,469
BEGIN DESCRIPTION:
Stream0167_DS 3.0
END DESCRIPTION:
XS GIS Cut Line= 3
      2092874.98     13888675.03      2092675.00     13889025.00
      2092575.00     13889125.00
#Sta/Elev= 30
  4600.9 1251.83  4623.9 1249.17  4636.1 1243.09  4658.5 1234.29  4695.2 1225.86
  4711.0 1218.75  4754.2 1203.90  4813.2 1193.08  4819.7 1186.42  4834.8 1188.58
  4842.7 1191.44  4850.6 1172.07  4878.0 1163.59  4900.3 1159.40  4974.5 1155.77
  4987.4 1150.57  4988.1 1150.34  4988.4 1149.84  4992.5 1150.34  4996.1 1150.87
  5001.1 1153.68  5007.5 1153.68  5046.4 1163.11  5060.5 1168.09  5074.7 1186.37
  5088.8 1182.15  5095.7 1185.19  5103.0 1188.41  5118.8 1191.46  5145.4 1194.28
#Mann=6,-1,0
  4600.9    0.12       0  4987.4    0.07       0  4988.1    0.05       0
  4992.5    0.07       0  5095.7   0.035       0  5118.8    0.07       0
Bank Sta=4988.1,4992.5
Exp/Cntr=0.3,0.1

Type RM Length L Ch R = 1,933,434,434,434
BEGIN DESCRIPTION:
Stream0167_DS 2.0
END DESCRIPTION:
XS GIS Cut Line= 3
      2092674.99     13888575.00      2092325.00     13888725.00
      2092102.51     13889089.24
#Sta/Elev= 30
  4614.8 1227.36  4647.4 1220.10  4690.9 1204.00  4758.0 1194.75  4776.2 1195.59
  4781.6 1192.11  4821.5 1187.01  4828.8 1180.08  4834.2 1177.79  4886.8 1161.13
  4933.9 1154.65  4981.1 1152.20  4998.5 1149.44  5001.1 1145.73  5001.4 1145.23
  5005.5 1145.73  5024.6 1150.25  5085.1 1155.44  5112.8 1158.31  5162.1 1169.72
  5183.4 1177.37  5193.2 1191.57  5198.2 1183.46  5206.5 1188.43  5220.1 1192.53
  5293.7 1205.38  5315.0 1213.74  5330.4 1222.42  5379.7 1229.25  5422.4 1239.72
#Mann=7,-1,0
  4614.8    0.12       0  5001.1    0.05       0  5005.5    0.12       0
  5085.1   0.035       0  5193.2    0.07       0  5198.2    0.12       0
  5379.7   0.035       0
Bank Sta=5001.1,5005.5
Exp/Cntr=0.3,0.1

Type RM Length L Ch R = 1,499,377,377,377
BEGIN DESCRIPTION:
Stream0167_DS 1.0
END DESCRIPTION:
XS GIS Cut Line= 3
      2092658.04     13888377.41      2092175.00     13888375.00
      2092019.61     13888664.82
#Sta/Elev= 30
  4516.1 1227.04  4619.1 1201.65  4699.1 1191.26  4709.1 1193.76  4719.1 1178.27
  4739.1 1170.57  4799.1 1155.43  4837.6 1152.31  4936.2 1148.99  4994.5 1141.28
  4994.8 1140.78  4998.9 1141.28  5029.2 1141.52  5034.9 1148.10  5051.1 1144.82
  5056.8 1151.40  5073.1 1147.97  5078.7 1156.98  5089.3 1155.41  5095.0 1161.73
  5111.2 1159.27  5116.9 1165.43  5133.2 1164.71  5138.8 1170.85  5155.1 1168.80
  5160.8 1177.35  5177.0 1177.37  5182.7 1192.46  5299.4 1199.27  5328.0 1201.15
#Mann=6,-1,0
  4516.1    0.12       0  4837.6   0.035       0  4936.2    0.07       0
  4994.5    0.05       0  4998.9    0.07       0  5299.4    0.12       0
Bank Sta=4994.5,4998.9
Exp/Cntr=0.3,0.1

Type RM Length L Ch R = 1,122,0,0,0
BEGIN DESCRIPTION:
Stream0167_DS 0.0
END DESCRIPTION:
XS GIS Cut Line= 4
      2092756.89     13887962.58      2092272.89     13888030.88
      2092149.09     13888183.57      2092012.50     13888493.33
#Sta/Elev= 30
  4511.2 1254.41  4566.5 1245.54  4604.0 1231.99  4654.5 1222.25  4694.9 1207.46
  4703.7 1205.54  4708.7 1207.36  4795.9 1190.75  4806.0 1180.23  4816.1 1174.23
  4866.6 1154.74  4920.2 1150.52  4957.5 1149.67  4977.7 1144.14  4987.8 1137.26
  5004.5 1136.07  5004.9 1135.57  5009.0 1136.07  5016.1 1138.46  5022.5 1144.51
  5030.5 1143.54  5036.9 1146.32  5051.3 1145.28  5201.1 1153.88  5292.2 1162.61
  5361.3 1173.60  5414.3 1184.39  5443.1 1185.25  5466.4 1189.48  5535.1 1193.52
#Mann=6,-1,0
  4511.2    0.12       0  4920.2   0.035       0  5004.5   0.035       0
  5009.0   0.035       0  5201.1    0.07       0  5361.3    0.12       0
Bank Sta=5004.5,5009
Exp/Cntr=0.3,0.1

Chan Stop Cuts=-1