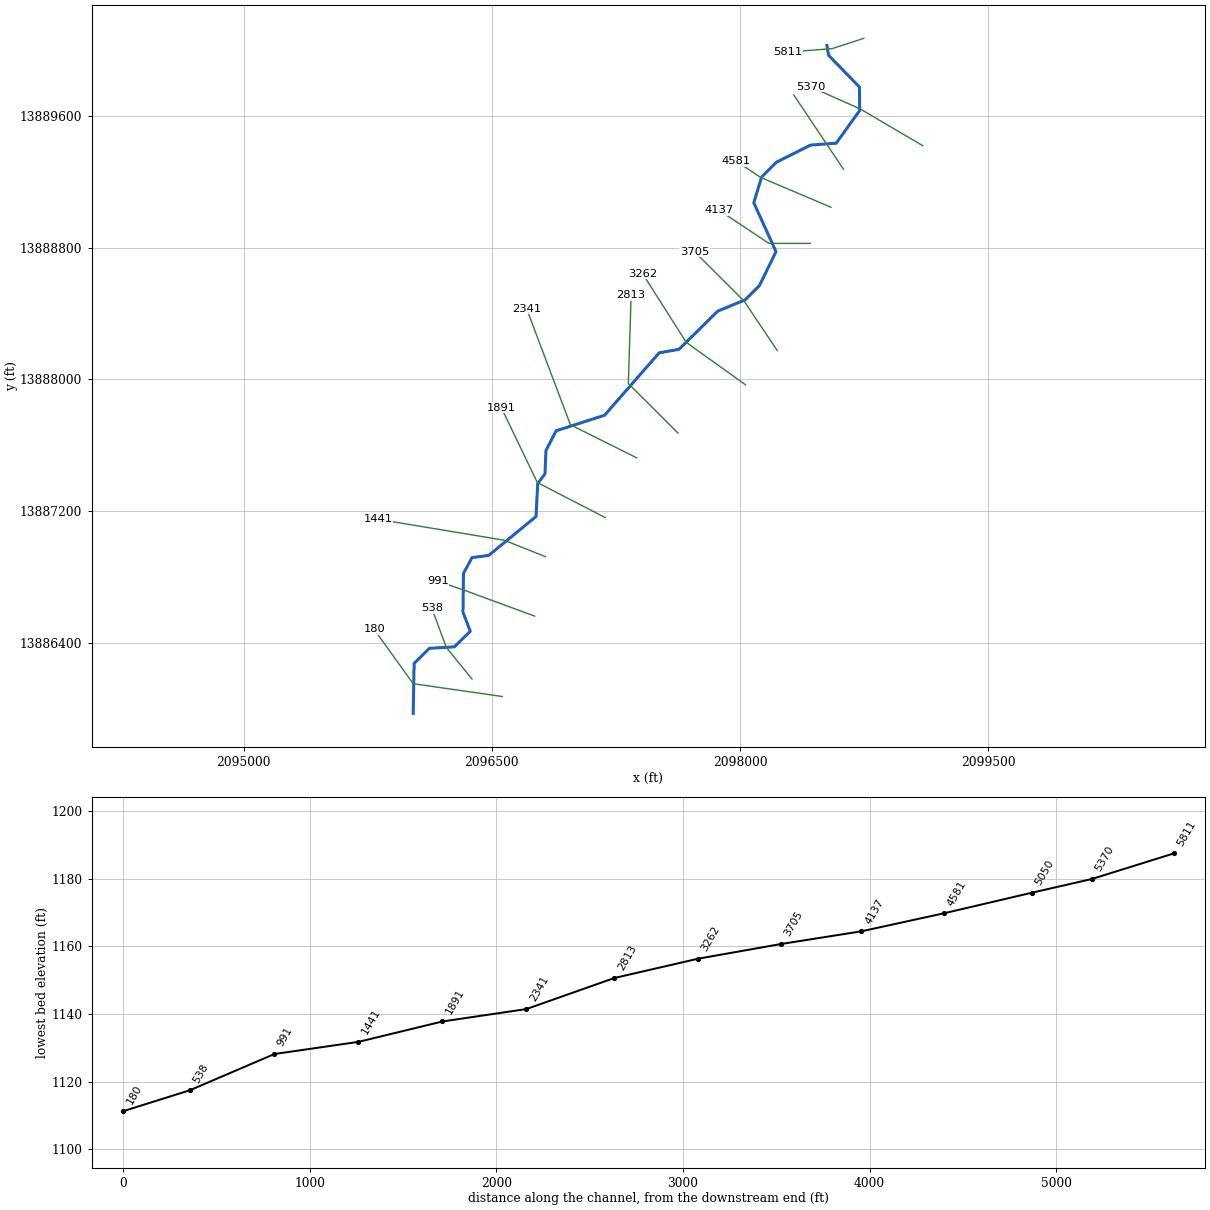
--- Stream0168_DS.prj (project) ---

Proj Title=Stream0168_DS Base Level Engineering
Current Plan=p01
Default Exp/Contr=0.3,0.1
English Units
Geom File=g01
Flow File=f01
Plan File=p01
BEGIN DESCRIPTION:
Stream0168_DS
END DESCRIPTION:

--- Stream0168_DS.p01 (plan) ---

Plan Title=Multiple Run
Short Identifier=Multiple
Geom File=g01
Flow File=f01
Subcritical Flow
K Sum by GR= 0
Std Step Tol= 0.01
Critical Tol= 0.01
Num of Std Step Trials= 20
Max Error Tol= 0.3
Flow Tol Ratio= 0.001
Split Flow NTrial= 30
Split Flow Tol= 0.02
Split Flow Ratio= 0.02
Log Output Level= 0
Friction Slope Method= 1
Unsteady Friction Slope Method= 2
Unsteady Bridges Friction Slope Method= 1
Parabolic Critical Depth
Global Vel Dist=  1 , 1 , 1
Global Log Level= 0
CheckData=True
Encroach Param= -1, 0, 0, 0
BEGIN DESCRIPTION:
Multiple Run
END DESCRIPTION:

--- Stream0168_DS.f01 (steady flow) ---

Flow Title=Multiple
Number of Profiles=7
Profile Names=10-year,25-year,50-year,1pct_min,100-year,1pct_plu,500-year
River Rch & RM= Stream0168_DS,Reach-1,5811
     735    1218    1669    1112    2218    4426    3867
River Rch & RM= Stream0168_DS,Reach-1,5370
    1111    1888    2631    1779    3549    7081    6380
River Rch & RM= Stream0168_DS,Reach-1,3705
    1732    3014    4267    2924    5835   11642   10796
Boundary for River Rch & Prof#=Stream0168_DS,Reach-1,1
Up Type=0
Dn Type=3
Dn Slope=0.005
Boundary for River Rch & Prof#=Stream0168_DS,Reach-1,2
Up Type=0
Dn Type=3
Dn Slope=0.005
Boundary for River Rch & Prof#=Stream0168_DS,Reach-1,3
Up Type=0
Dn Type=3
Dn Slope=0.005
Boundary for River Rch & Prof#=Stream0168_DS,Reach-1,4
Up Type=0
Dn Type=3
Dn Slope=0.005
Boundary for River Rch & Prof#=Stream0168_DS,Reach-1,5
Up Type=0
Dn Type=3
Dn Slope=0.005
Boundary for River Rch & Prof#=Stream0168_DS,Reach-1,6
Up Type=0
Dn Type=3
Dn Slope=0.005
Boundary for River Rch & Prof#=Stream0168_DS,Reach-1,7
Up Type=0
Dn Type=3
Dn Slope=0.005

--- Stream0168_DS.g01 (geometry) ---

Geom Title=Existing Conditions

River Reach=Stream0168_DS,Reach-1
Reach XY= 30
      2098525.00     13890025.00      2098535.52     13889965.21
      2098721.62     13889773.60      2098722.92     13889630.78
      2098581.21     13889432.81      2098426.56     13889421.24
      2098218.93     13889316.87      2098130.51     13889227.44
      2098083.08     13889071.70      2098217.50     13888775.00
      2098117.09     13888568.85      2098031.15     13888482.91
      2097865.32     13888414.24      2097631.17     13888182.86
      2097511.70     13888161.60      2097181.19     13887782.85
      2096888.45     13887688.63      2096827.25     13887569.07
      2096821.21     13887426.57      2096777.26     13887369.06
      2096767.19     13887168.81      2096481.12     13886932.90
      2096380.44     13886919.75      2096328.74     13886823.48
      2096325.70     13886588.91      2096369.92     13886472.69
      2096273.55     13886378.54      2096122.53     13886369.54
      2096030.45     13886277.47      2096025.00     13885975.00

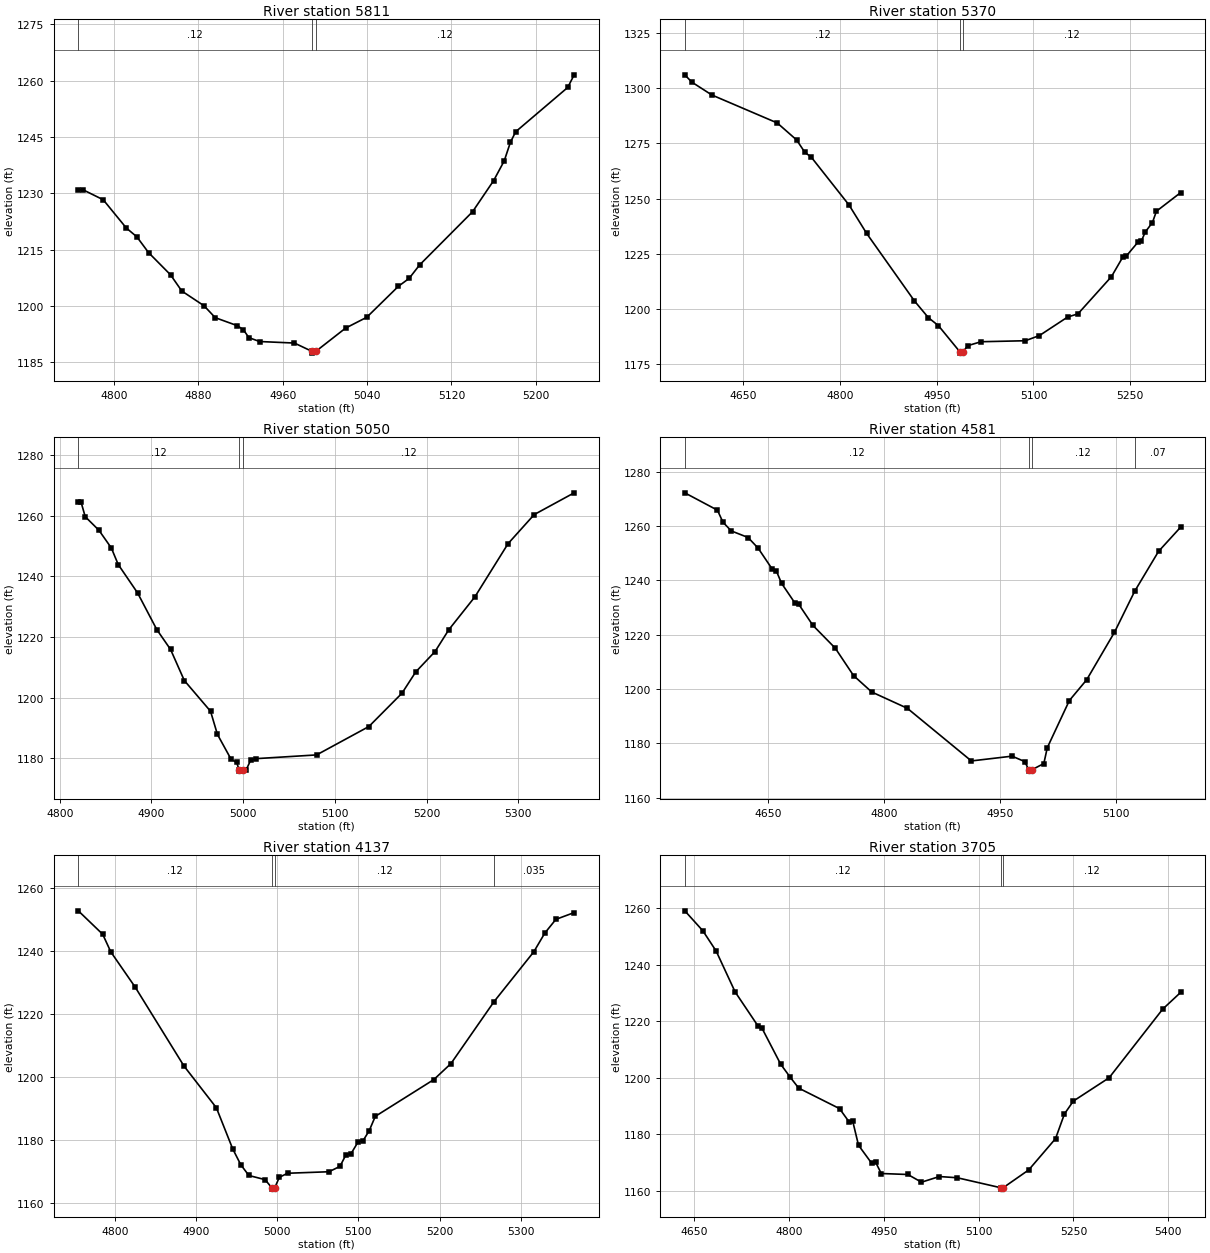
Type RM Length L Ch R = 1,5811,441,441,441
BEGIN DESCRIPTION:
Stream0168_DS 13.0
END DESCRIPTION:
XS GIS Cut Line= 3
      2098748.30     13890068.65      2098556.63     13890006.14
      2098288.94     13889985.39
#Sta/Elev= 30
  4766.2 1230.93  4770.6 1230.93  4789.8 1228.27  4811.7 1220.75  4821.7 1218.40
  4832.8 1214.20  4853.6 1208.30  4864.3 1203.98  4885.4 1200.05  4896.0 1196.89
  4916.9 1194.76  4922.7 1193.67  4927.9 1191.58  4938.0 1190.54  4971.1 1190.13
  4987.5 1187.95  4987.8 1187.45  4991.5 1187.95  5019.6 1194.11  5039.7 1197.00
  5069.7 1205.25  5079.8 1207.33  5089.8 1210.93  5140.0 1225.09  5160.0 1233.39
  5170.0 1238.62  5175.9 1243.60  5180.9 1246.38  5230.2 1258.16  5236.3 1261.52
#Mann=3,-1,0
  4766.2    0.12       0  4987.5    0.05       0  4991.5    0.12       0
Bank Sta=4987.5,4991.5
Exp/Cntr=0.3,0.1

Type RM Length L Ch R = 1,5370,320,320,320
BEGIN DESCRIPTION:
Stream0168_DS 12.0
END DESCRIPTION:
XS GIS Cut Line= 3
      2099104.29     13889417.68      2098724.74     13889641.45
      2098425.05     13889774.98
#Sta/Elev= 30
  4559.4 1306.13  4570.2 1302.84  4601.3 1296.99  4702.7 1284.30  4732.7 1276.60
  4745.6 1270.95  4755.5 1268.77  4814.0 1247.08  4841.3 1234.19  4915.5 1203.52
  4937.0 1195.97  4952.6 1192.34  4986.1 1180.37  4986.3 1179.87  4990.1 1180.37
  4998.6 1183.30  5018.6 1185.04  5087.3 1185.49  5109.2 1187.84  5153.0 1196.26
  5168.9 1197.68  5220.9 1214.59  5238.6 1223.53  5244.1 1223.99  5261.9 1230.20
  5267.3 1230.79  5273.4 1234.87  5284.4 1239.13  5290.6 1244.25  5328.1 1252.69
#Mann=3,-1,0
  4559.4    0.12       0  4986.1    0.05       0  4990.1    0.12       0
Bank Sta=4986.1,4990.1
Exp/Cntr=0.3,0.1

Type RM Length L Ch R = 1,5050,469,469,469
BEGIN DESCRIPTION:
Stream0168_DS 11.0
END DESCRIPTION:
XS GIS Cut Line= 3
      2098624.98     13889275.03      2098525.00     13889425.00
      2098325.00     13889725.01
#Sta/Elev= 30
  4820.2 1264.41  4823.2 1264.41  4827.7 1259.65  4842.7 1255.16  4856.2 1249.34
  4863.7 1243.89  4884.8 1234.55  4905.8 1222.45  4920.8 1215.91  4935.8 1205.68
  4964.4 1195.56  4971.9 1187.94  4986.9 1179.70  4992.9 1178.74  4995.4 1176.34
  4995.7 1175.84  4999.4 1176.34  5003.4 1176.34  5008.0 1179.35  5014.0 1179.95
  5080.1 1181.18  5137.1 1190.53  5173.2 1201.50  5188.2 1208.51  5209.3 1215.24
  5224.3 1222.42  5252.8 1233.27  5288.9 1250.76  5317.4 1260.33  5361.0 1267.50
#Mann=3,-1,0
  4820.2    0.12       0  4995.4    0.05       0  4999.4    0.12       0
Bank Sta=4995.4,4999.4
Exp/Cntr=0.3,0.1

Type RM Length L Ch R = 1,4581,444,444,444
BEGIN DESCRIPTION:
Stream0168_DS 10.0
END DESCRIPTION:
XS GIS Cut Line= 3
      2098550.43     13889044.08      2098125.00     13889225.00
      2097974.98     13889325.01
#Sta/Elev= 30
  4541.6 1272.26  4583.9 1265.87  4591.0 1261.47  4601.8 1258.24  4623.6 1255.81
  4636.6 1251.90  4654.8 1244.22  4660.3 1243.47  4667.0 1238.94  4683.9 1231.86
  4689.3 1231.21  4707.6 1223.46  4736.6 1215.06  4760.3 1204.97  4783.9 1198.92
  4830.0 1192.93  4913.0 1173.54  4965.7 1175.30  4982.2 1173.30  4987.4 1170.29
  4987.6 1169.79  4991.4 1170.29  5006.9 1172.58  5011.4 1178.42  5040.0 1195.79
  5062.5 1203.45  5098.5 1220.93  5124.6 1235.99  5155.6 1250.71  5184.2 1259.61
#Mann=4,-1,0
  4541.6    0.12       0  4987.4    0.05       0  4991.4    0.12       0
  5124.6    0.07       0
Bank Sta=4987.4,4991.4
Exp/Cntr=0.3,0.1

Type RM Length L Ch R = 1,4137,432,432,432
BEGIN DESCRIPTION:
Stream0168_DS 9.0
END DESCRIPTION:
XS GIS Cut Line= 3
      2098425.04     13888825.00      2098175.00     13888825.00
      2097875.00     13889025.00
#Sta/Elev= 30
  4755.2 1252.80  4785.2 1245.36  4795.2 1239.76  4825.2 1228.58  4885.2 1203.56
  4925.2 1190.27  4945.2 1177.28  4955.2 1172.21  4965.2 1168.77  4985.2 1167.45
  4993.2 1164.94  4993.5 1164.44  4997.2 1164.94  5002.7 1168.18  5012.8 1169.48
  5063.8 1169.96  5077.4 1171.66  5084.9 1175.41  5090.9 1175.65  5099.9 1179.50
  5105.9 1179.86  5113.4 1182.99  5120.9 1187.54  5193.0 1199.22  5214.1 1204.31
  5267.1 1223.96  5316.2 1239.83  5329.7 1245.75  5343.3 1250.09  5365.8 1252.24
#Mann=4,-1,0
  4755.2    0.12       0  4993.2    0.05       0  4997.2    0.12       0
  5267.1   0.035       0
Bank Sta=4993.2,4997.2
Exp/Cntr=0.3,0.1

Type RM Length L Ch R = 1,3705,443,443,443
BEGIN DESCRIPTION:
Stream0168_DS 8.0
END DESCRIPTION:
XS GIS Cut Line= 3
      2098225.02     13888174.97      2098025.00     13888475.00
      2097724.97     13888775.03
#Sta/Elev= 30
  4634.7 1259.03  4663.3 1251.97  4684.3 1244.83  4714.4 1230.36  4750.4 1218.39
  4756.4 1217.76  4786.5 1204.82  4801.5 1200.25  4815.0 1196.38  4879.6 1189.14
  4894.6 1184.50  4900.6 1184.61  4909.7 1176.18  4930.7 1169.77  4936.7 1170.22
  4945.7 1166.20  4987.8 1165.85  5009.4 1163.13  5037.7 1165.13  5066.0 1164.70
  5134.7 1161.18  5135.0 1160.68  5138.7 1161.18  5179.1 1167.46  5221.6 1178.53
  5235.7 1187.26  5249.8 1191.80  5306.4 1200.03  5391.3 1224.31  5419.6 1230.19
#Mann=3,-1,0
  4634.7    0.12       0  5134.7    0.05       0  5138.7    0.12       0
Bank Sta=5134.7,5138.7
Exp/Cntr=0.3,0.1

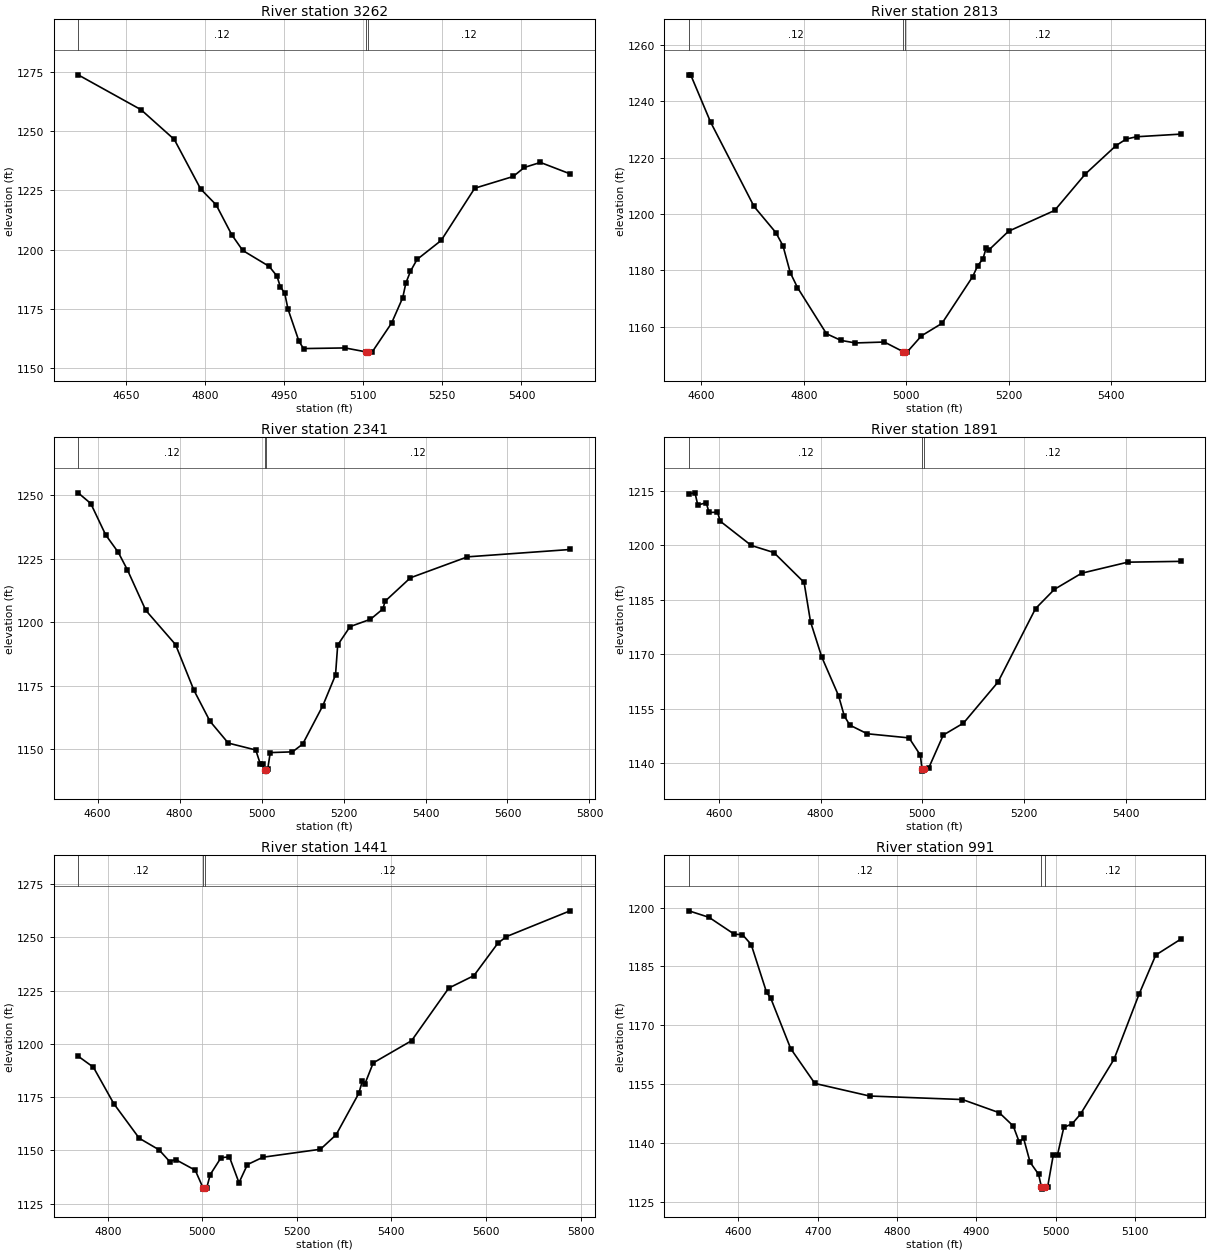
Type RM Length L Ch R = 1,3262,449,449,449
BEGIN DESCRIPTION:
Stream0168_DS 7.0
END DESCRIPTION:
XS GIS Cut Line= 3
      2098033.10     13887967.67      2097675.00     13888225.00
      2097411.94     13888640.69
#Sta/Elev= 30
  4559.3 1273.67  4678.6 1258.96  4741.7 1246.41  4791.6 1225.56  4821.0 1218.87
  4850.5 1206.30  4871.4 1199.64  4921.7 1192.90  4936.4 1188.81  4942.6 1184.38
  4951.0 1181.65  4957.3 1174.90  4978.2 1161.28  4986.8 1158.27  5065.5 1158.54
  5105.9 1156.85  5106.2 1156.35  5109.9 1156.85  5117.3 1156.96  5153.7 1169.00
  5174.9 1179.73  5180.8 1185.88  5189.6 1190.88  5202.0 1195.83  5247.8 1203.86
  5311.4 1225.87  5384.3 1230.81  5405.4 1234.62  5436.0 1236.74  5492.2 1231.93
#Mann=3,-1,0
  4559.3    0.12       0  5105.9    0.05       0  5109.9    0.12       0
Bank Sta=5105.9,5109.9
Exp/Cntr=0.3,0.1

Type RM Length L Ch R = 1,2813,472,472,472
BEGIN DESCRIPTION:
Stream0168_DS 6.0
END DESCRIPTION:
XS GIS Cut Line= 3
      2097625.00     13887675.00      2097325.00     13887975.00
      2097342.06     13888511.37
#Sta/Elev= 30
  4575.4 1249.42  4578.9 1249.42  4617.8 1232.63  4702.7 1202.69  4745.1 1193.46
  4759.2 1188.75  4773.4 1179.21  4787.5 1173.92  4844.1 1157.54  4872.4 1155.17
  4900.7 1154.26  4957.2 1154.59  4994.1 1151.15  4994.4 1150.65  4998.1 1151.15
  5002.2 1151.15  5029.7 1156.79  5069.7 1161.21  5129.7 1177.79  5139.7 1181.74
  5149.7 1184.07  5155.8 1187.81  5160.8 1187.16  5199.8 1193.91  5289.8 1201.29
  5349.8 1214.22  5409.9 1224.33  5429.9 1226.65  5449.9 1227.44  5536.3 1228.38
#Mann=3,-1,0
  4575.4    0.12       0  4994.1    0.05       0  4998.1    0.12       0
Bank Sta=4994.1,4998.1
Exp/Cntr=0.3,0.1

Type RM Length L Ch R = 1,2341,450,450,450
BEGIN DESCRIPTION:
Stream0168_DS 5.0
END DESCRIPTION:
XS GIS Cut Line= 3
      2097375.04     13887524.98      2096975.00     13887725.00
      2096710.16     13888429.50
#Sta/Elev= 30
  4552.7 1250.93  4583.5 1246.73  4619.8 1234.41  4650.6 1227.52  4672.9 1220.63
  4717.7 1204.71  4790.3 1191.24  4835.1 1173.28  4874.2 1161.12  4918.9 1152.50
  4986.0 1149.78  4997.2 1144.19  5002.6 1144.19  5007.6 1141.97  5007.9 1141.47
  5011.9 1141.97  5015.1 1142.30  5021.3 1148.76  5075.5 1149.05  5100.4 1152.10
  5149.5 1167.20  5180.5 1179.28  5185.8 1191.06  5216.0 1198.31  5265.8 1201.20
  5296.1 1205.26  5301.4 1208.29  5363.2 1217.51  5502.4 1225.75  5752.6 1228.64
#Mann=3,-1,0
  4552.7    0.12       0  5007.6    0.05       0  5011.9    0.12       0
Bank Sta=5007.6,5011.9
Exp/Cntr=0.3,0.1

Type RM Length L Ch R = 1,1891,450,450,450
BEGIN DESCRIPTION:
Stream0168_DS 4.0
END DESCRIPTION:
XS GIS Cut Line= 3
      2097185.86     13887162.13      2096775.00     13887375.00
      2096557.39     13887828.79
#Sta/Elev= 30
  4541.4 1214.16  4553.3 1214.42  4558.9 1211.06  4575.4 1211.69  4581.0 1209.01
  4597.5 1209.09  4603.1 1206.59  4663.9 1199.93  4708.2 1197.98  4767.6 1189.76
  4780.2 1178.95  4802.3 1169.21  4835.2 1158.60  4846.6 1152.97  4857.5 1150.46
  4891.5 1148.09  4973.7 1146.95  4995.9 1142.21  4999.2 1138.30  4999.5 1137.80
  5003.5 1138.30  5012.7 1138.78  5040.9 1147.73  5080.6 1151.02  5148.3 1162.30
  5222.1 1182.55  5259.2 1187.85  5312.7 1192.29  5403.3 1195.33  5507.4 1195.55
#Mann=3,-1,0
  4541.4    0.12       0  4999.2    0.05       0  5003.5    0.12       0
Bank Sta=4999.2,5003.5
Exp/Cntr=0.3,0.1

Type RM Length L Ch R = 1,1441,450,450,450
BEGIN DESCRIPTION:
Stream0168_DS 3.0
END DESCRIPTION:
XS GIS Cut Line= 3
      2096824.98     13886925.01      2096575.00     13887025.00
      2095814.32     13887151.72
#Sta/Elev= 30
  4737.5 1194.19  4769.8 1189.00  4812.9 1171.90  4866.7 1155.67  4908.5 1150.25
  4931.3 1144.68  4943.5 1145.68  4985.2 1140.65  5001.8 1132.28  5002.1 1131.78
  5006.2 1132.28  5009.3 1132.28  5016.9 1138.62  5039.7 1146.53  5057.4 1146.93
  5077.7 1134.79  5095.5 1143.30  5128.4 1146.76  5250.0 1150.50  5283.1 1157.29
  5331.1 1176.76  5338.8 1182.68  5343.9 1181.11  5361.6 1191.04  5442.7 1201.45
  5521.4 1226.16  5574.5 1231.99  5625.1 1247.18  5643.0 1250.29  5777.9 1262.42
#Mann=3,-1,0
  4737.5    0.12       0  5001.8    0.05       0  5006.2    0.12       0
Bank Sta=5001.8,5006.2
Exp/Cntr=0.3,0.1

Type RM Length L Ch R = 1,991,453,453,453
BEGIN DESCRIPTION:
Stream0168_DS 2.0
END DESCRIPTION:
XS GIS Cut Line= 3
      2096758.78     13886564.91      2096325.00     13886725.00
      2096175.00     13886775.00
#Sta/Elev= 30
  4537.5 1199.18  4562.9 1197.52  4594.8 1193.21  4605.1 1193.10  4616.1 1190.58
  4635.5 1178.37  4640.8 1176.86  4665.9 1164.03  4696.4 1155.15  4765.4 1151.94
  4882.6 1151.04  4929.1 1147.67  4946.6 1144.30  4954.2 1140.19  4959.6 1141.21
  4967.9 1135.04  4978.6 1131.97  4982.2 1128.69  4982.6 1128.19  4987.2 1128.69
  4990.0 1128.77  4997.2 1136.99  5002.5 1136.99  5010.4 1143.94  5021.0 1144.86
  5031.5 1147.34  5073.7 1161.30  5105.3 1177.90  5126.4 1187.90  5158.0 1191.96
#Mann=3,-1,0
  4537.5    0.12       0  4982.2    0.05       0  4987.2    0.12       0
Bank Sta=4982.2,4987.2
Exp/Cntr=0.3,0.1

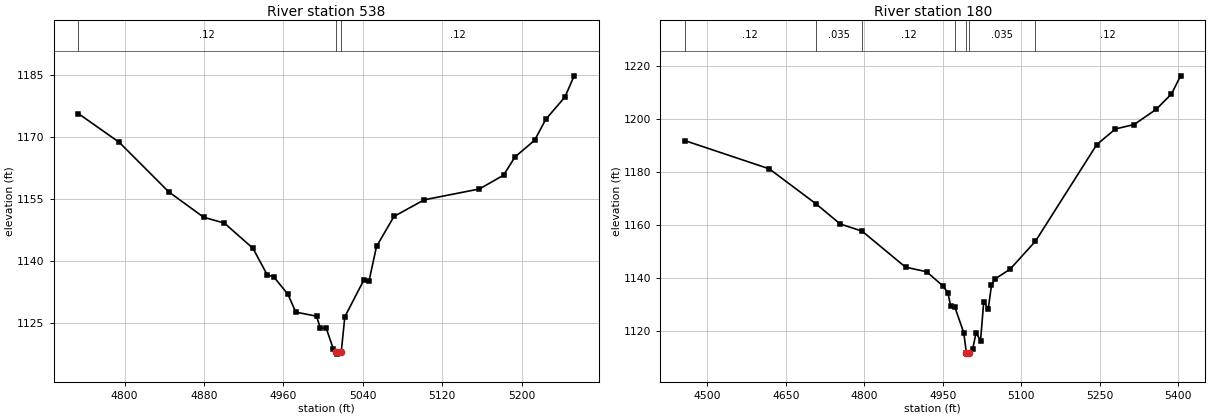
Type RM Length L Ch R = 1,538,358,358,358
BEGIN DESCRIPTION:
Stream0168_DS 1.0
END DESCRIPTION:
XS GIS Cut Line= 3
      2096380.29     13886182.98      2096225.00     13886375.00
      2096137.91     13886611.74
#Sta/Elev= 30
  4753.5 1175.71  4794.7 1168.75  4844.5 1156.77  4879.7 1150.61  4900.5 1149.20
  4929.3 1143.10  4943.7 1136.67  4950.1 1136.23  4964.5 1131.99  4972.4 1127.66
  4993.3 1126.67  4997.2 1123.76  5003.1 1123.76  5010.4 1118.62  5013.2 1117.99
  5013.5 1117.49  5018.2 1117.99  5021.8 1126.52  5040.8 1135.35  5046.1 1135.12
  5053.7 1143.54  5071.3 1150.81  5101.7 1154.83  5157.3 1157.46  5181.6 1160.79
  5193.1 1165.20  5212.9 1169.25  5224.2 1174.34  5243.4 1179.70  5252.7 1184.84
#Mann=3,-1,0
  4753.5    0.12       0  5013.2    0.05       0  5018.2    0.12       0
Bank Sta=5013.2,5018.2
Exp/Cntr=0.3,0.1

Type RM Length L Ch R = 1,180,0,0,0
BEGIN DESCRIPTION:
Stream0168_DS 0.0
END DESCRIPTION:
XS GIS Cut Line= 3
      2096562.59     13886077.35      2096024.97     13886155.01
      2095789.22     13886483.72
#Sta/Elev= 30
  4456.8 1191.98  4618.2 1181.31  4707.0 1168.17  4753.8 1160.47  4795.7 1157.75
  4878.7 1144.16  4919.1 1142.41  4949.4 1137.18  4959.6 1134.55  4964.8 1129.66
  4973.0 1129.03  4989.9 1119.43  4995.0 1111.79  4995.3 1111.29  5000.0 1111.79
  5007.3 1113.41  5013.5 1119.37  5022.1 1116.39  5028.2 1131.16  5036.8 1128.33
  5042.9 1137.23  5049.2 1139.63  5078.6 1143.39  5127.1 1153.97  5244.3 1190.49
  5280.0 1196.38  5315.6 1198.05  5357.4 1203.73  5386.8 1209.53  5404.5 1216.45
#Mann=7,-1,0
  4456.8    0.12       0  4707.0   0.035       0  4795.7    0.12       0
  4973.0   0.035       0  4995.0   0.035       0  5000.0   0.035       0
  5127.1    0.12       0
Bank Sta=4995,5000
Exp/Cntr=0.3,0.1

Chan Stop Cuts=-1