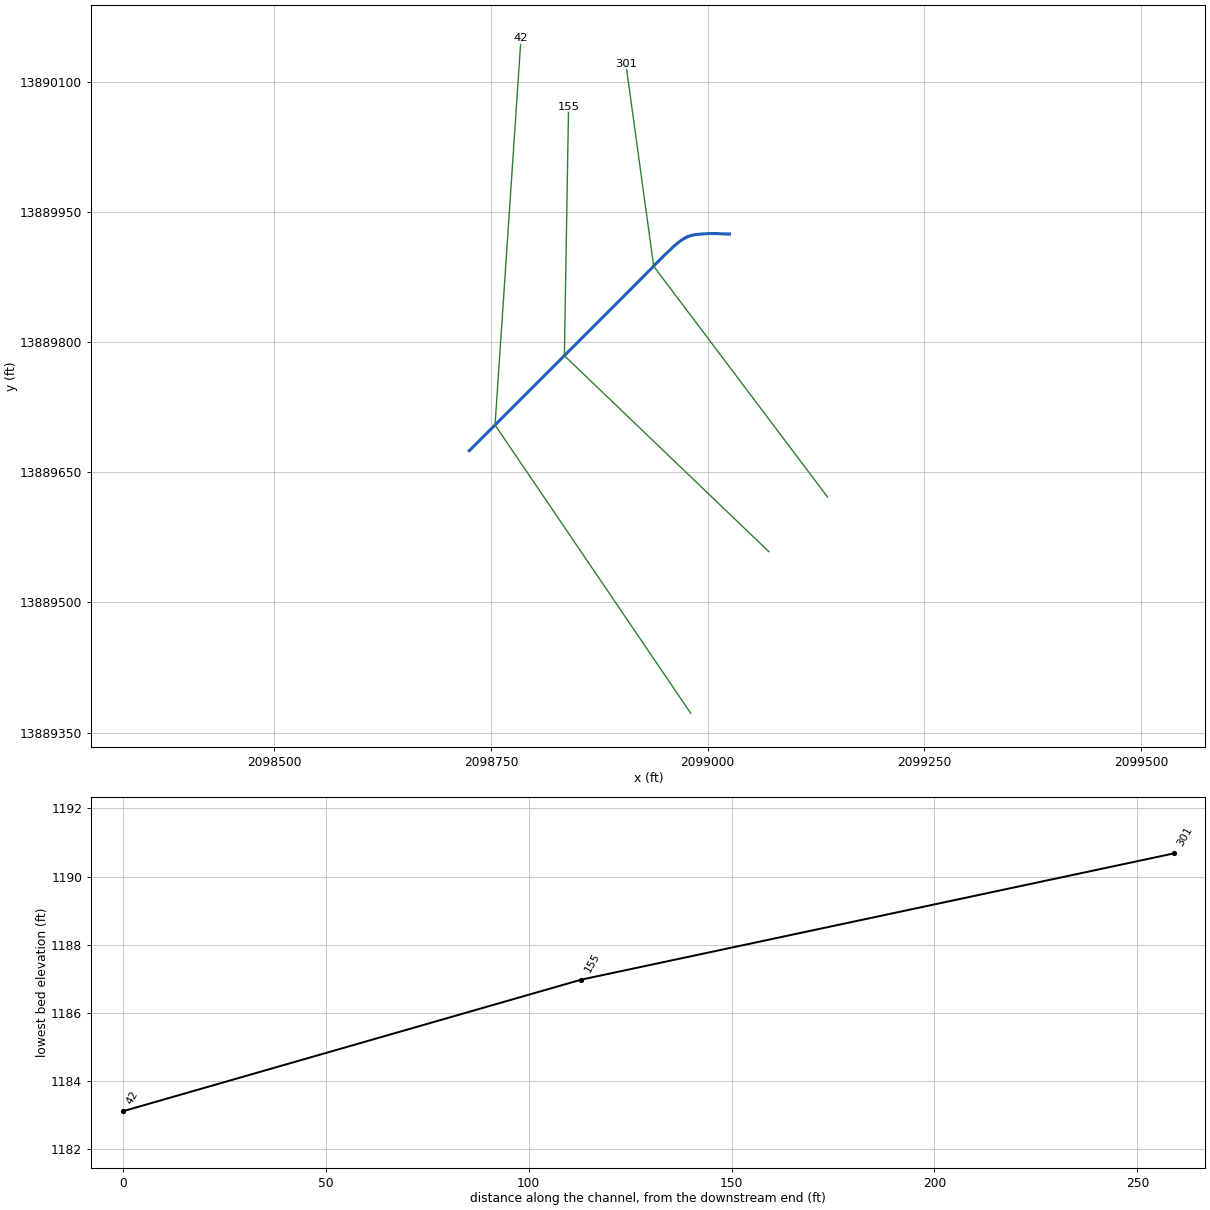
--- Stream0168_DS_Tributary 1.prj (project) ---

Proj Title=Stream0168_DS_Tributary 1 Base Level Engineering
Current Plan=p01
Default Exp/Contr=0.3,0.1
English Units
Geom File=g01
Flow File=f01
Plan File=p01
BEGIN DESCRIPTION:
Stream0168_DS_Tributary 1
END DESCRIPTION:

--- Stream0168_DS_Tributary 1.p01 (plan) ---

Plan Title=Multiple Run
Short Identifier=Multiple
Geom File=g01
Flow File=f01
Subcritical Flow
K Sum by GR= 0
Std Step Tol= 0.01
Critical Tol= 0.01
Num of Std Step Trials= 20
Max Error Tol= 0.3
Flow Tol Ratio= 0.001
Split Flow NTrial= 30
Split Flow Tol= 0.02
Split Flow Ratio= 0.02
Log Output Level= 0
Friction Slope Method= 1
Unsteady Friction Slope Method= 2
Unsteady Bridges Friction Slope Method= 1
Parabolic Critical Depth
Global Vel Dist=  1 , 1 , 1
Global Log Level= 0
CheckData=True
Encroach Param= -1, 0, 0, 0
BEGIN DESCRIPTION:
Multiple Run
END DESCRIPTION:

--- Stream0168_DS_Tributary 1.f01 (steady flow) ---

Flow Title=Multiple
Number of Profiles=7
Profile Names=10-year,25-year,50-year,1pct_min,100-year,1pct_plu,500-year
River Rch & RM= Stream0168_DS_Tr,Reach-1,301
     582     952    1293     855    1707    3405    2931
River Rch & RM= Stream0168_DS_Tr,Reach-1,42
    1111    1888    2631    1779    3549    7081    6380
Boundary for River Rch & Prof#=Stream0168_DS_Tr,Reach-1,1
Up Type=0
Dn Type=3
Dn Slope=0.005
Boundary for River Rch & Prof#=Stream0168_DS_Tr,Reach-1,2
Up Type=0
Dn Type=3
Dn Slope=0.005
Boundary for River Rch & Prof#=Stream0168_DS_Tr,Reach-1,3
Up Type=0
Dn Type=3
Dn Slope=0.005
Boundary for River Rch & Prof#=Stream0168_DS_Tr,Reach-1,4
Up Type=0
Dn Type=3
Dn Slope=0.005
Boundary for River Rch & Prof#=Stream0168_DS_Tr,Reach-1,5
Up Type=0
Dn Type=3
Dn Slope=0.005
Boundary for River Rch & Prof#=Stream0168_DS_Tr,Reach-1,6
Up Type=0
Dn Type=3
Dn Slope=0.005
Boundary for River Rch & Prof#=Stream0168_DS_Tr,Reach-1,7
Up Type=0
Dn Type=3
Dn Slope=0.005

--- Stream0168_DS_Tributary 1.g01 (geometry) ---

Geom Title=Existing Conditions

River Reach=Stream0168_DS_Tr,Reach-1
Reach XY= 18
      2099025.00     13889925.00      2099024.07     13889924.96
      2099012.02     13889925.43      2099006.04     13889925.50
      2098999.63     13889925.41      2098993.12     13889925.07
      2098986.84     13889924.41      2098981.14     13889923.32
      2098976.36     13889921.73      2098972.48     13889919.69
      2098968.79     13889917.24      2098965.21     13889914.49
      2098961.73     13889911.53      2098958.30     13889908.42
      2098954.91     13889905.22      2098948.20     13889898.65
      2098891.66     13889841.69      2098725.00     13889675.00

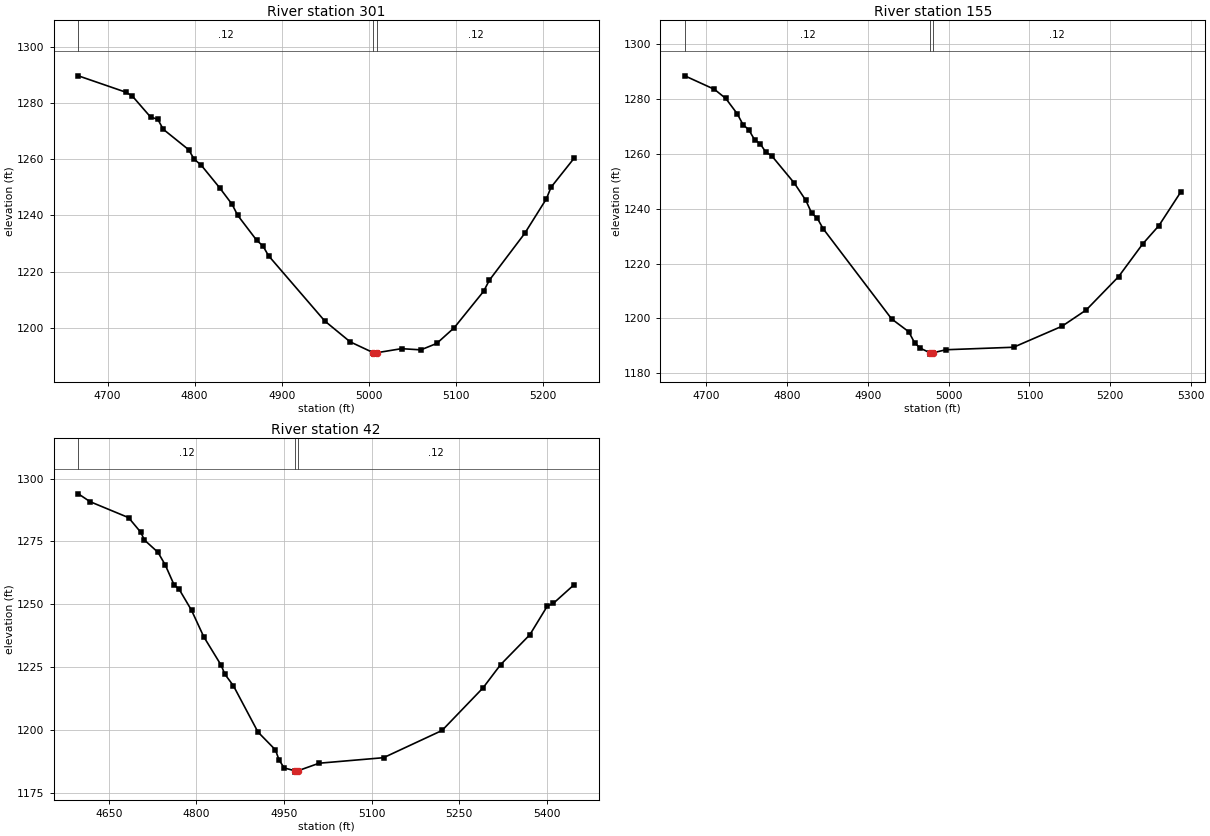
Type RM Length L Ch R = 1,301,146,146,146
BEGIN DESCRIPTION:
Stream0168_DS_Tributary 1 2.0
END DESCRIPTION:
XS GIS Cut Line= 3
      2099138.22     13889621.64      2098937.74     13889887.74
      2098905.60     13890121.27
#Sta/Elev= 30
  4666.5 1289.67  4720.8 1283.87  4728.5 1282.46  4749.4 1275.00  4757.7 1274.20
  4763.9 1270.67  4793.1 1263.39  4799.3 1260.06  4807.6 1257.85  4828.5 1249.90
  4843.0 1243.93  4849.3 1240.07  4871.0 1231.23  4878.4 1229.12  4884.7 1225.70
  4949.2 1202.48  4978.4 1195.05  5005.0 1191.18  5005.2 1190.68  5009.0 1191.18
  5037.3 1192.62  5059.5 1192.20  5077.7 1194.48  5097.8 1200.08  5131.5 1213.02
  5138.2 1217.02  5178.6 1233.59  5203.5 1245.90  5208.9 1250.05  5235.4 1260.39
#Mann=3,-1,0
  4666.5    0.12       0  5005.0    0.05       0  5009.0    0.12       0
Bank Sta=5005,5009
Exp/Cntr=0.3,0.1

Type RM Length L Ch R = 1,155,113,113,113
BEGIN DESCRIPTION:
Stream0168_DS_Tributary 1 1.0
END DESCRIPTION:
XS GIS Cut Line= 3
      2099070.60     13889558.58      2098834.67     13889784.67
      2098839.49     13890071.85
#Sta/Elev= 30
  4673.2 1288.50  4709.9 1283.57  4724.0 1280.23  4738.2 1274.63  4745.4 1270.63
  4752.3 1268.88  4759.6 1265.19  4766.5 1263.76  4773.7 1260.57  4780.6 1259.41
  4808.9 1249.33  4823.1 1243.06  4830.3 1238.42  4837.2 1236.57  4844.5 1232.74
  4929.4 1199.80  4950.5 1195.15  4957.7 1191.16  4964.6 1189.17  4976.8 1187.48
  4977.0 1186.98  4980.8 1187.48  4996.6 1188.58  5080.3 1189.49  5140.3 1197.15
  5170.3 1203.09  5210.3 1215.22  5240.3 1227.20  5260.3 1233.85  5287.2 1246.04
#Mann=3,-1,0
  4673.2    0.12       0  4976.8    0.05       0  4980.8    0.12       0
Bank Sta=4976.8,4980.8
Exp/Cntr=0.3,0.1

Type RM Length L Ch R = 1,42,0,0,0
BEGIN DESCRIPTION:
Stream0168_DS_Tributary 1 0.0
END DESCRIPTION:
XS GIS Cut Line= 3
      2098980.49     13889372.11      2098754.71     13889704.72
      2098784.63     13890150.71
#Sta/Elev= 30
  4598.0 1293.98  4618.2 1290.84  4684.0 1284.50  4705.0 1278.64  4711.0 1275.61
  4734.4 1270.68  4746.9 1265.62  4761.9 1257.75  4770.7 1255.93  4791.8 1247.60
  4812.8 1237.03  4842.7 1225.64  4848.7 1222.20  4863.6 1217.50  4905.6 1199.09
  4935.5 1191.98  4941.6 1188.02  4950.5 1184.79  4969.5 1183.62  4969.7 1183.12
  4973.5 1183.62  5010.3 1186.67  5120.6 1188.87  5220.8 1199.72  5290.9 1216.67
  5321.0 1225.92  5371.1 1237.84  5401.2 1249.33  5411.2 1250.32  5447.0 1257.80
#Mann=3,-1,0
  4598.0    0.12       0  4969.5    0.05       0  4973.5    0.12       0
Bank Sta=4969.5,4973.5
Exp/Cntr=0.3,0.1

Chan Stop Cuts=-1