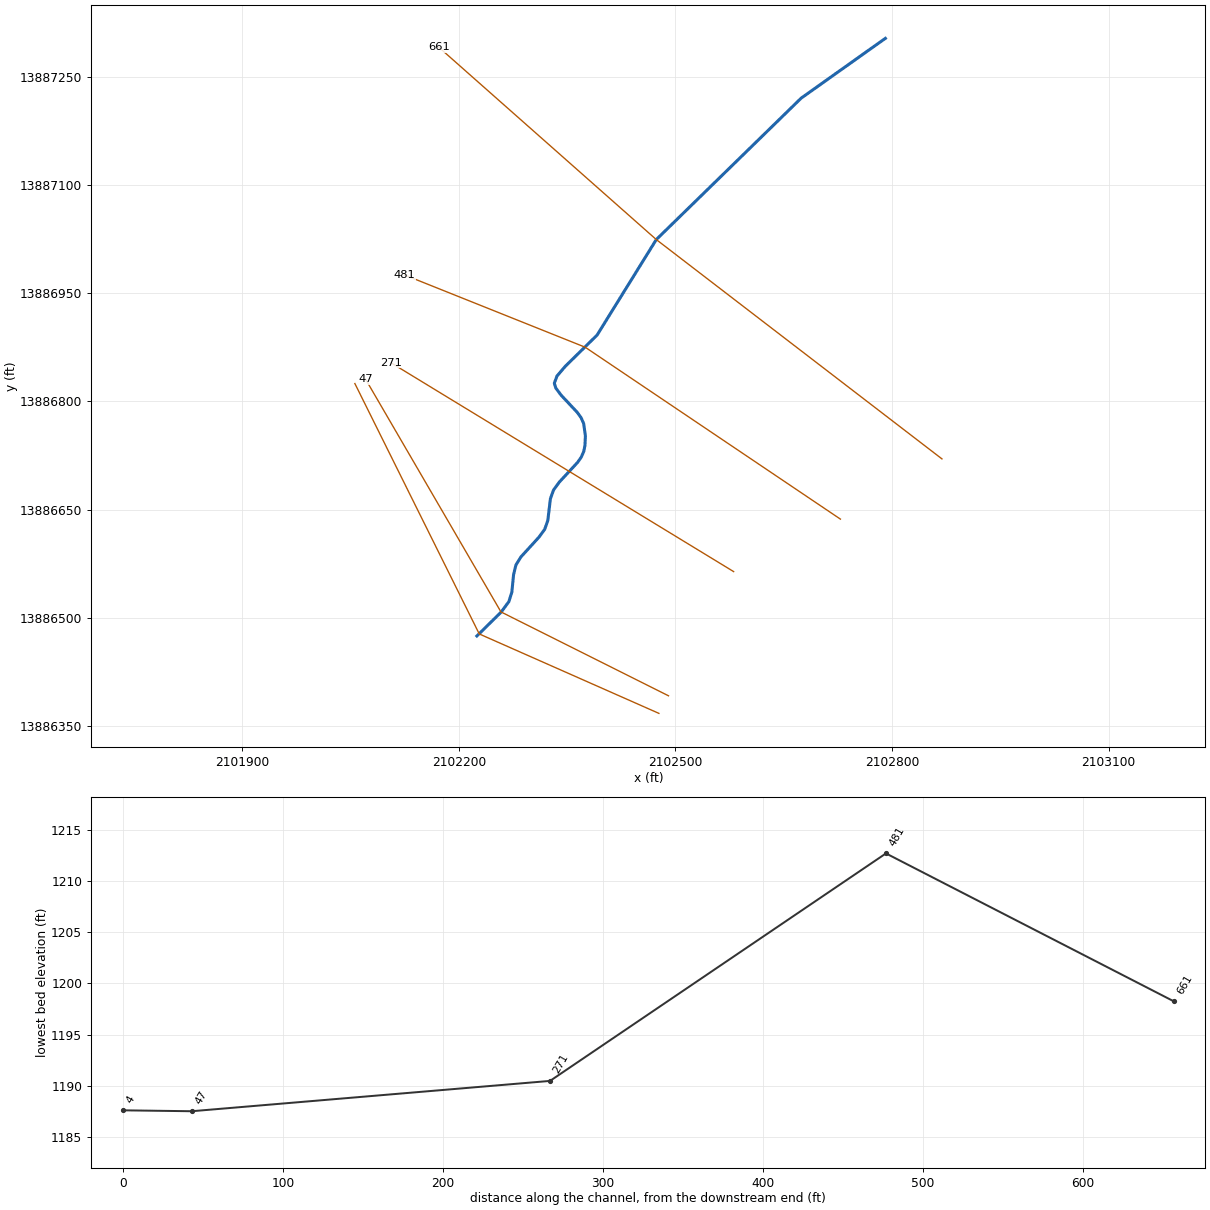
--- Stream0169_DS.prj (project) ---

Proj Title=Stream0169_DS Base Level Engineering
Current Plan=p01
Default Exp/Contr=0.3,0.1
English Units
Geom File=g01
Flow File=f01
Plan File=p01
BEGIN DESCRIPTION:
Stream0169_DS
END DESCRIPTION:

--- Stream0169_DS.p01 (plan) ---

Plan Title=Multiple Run
Short Identifier=Multiple
Geom File=g01
Flow File=f01
Subcritical Flow
K Sum by GR= 0
Std Step Tol= 0.01
Critical Tol= 0.01
Num of Std Step Trials= 20
Max Error Tol= 0.3
Flow Tol Ratio= 0.001
Split Flow NTrial= 30
Split Flow Tol= 0.02
Split Flow Ratio= 0.02
Log Output Level= 0
Friction Slope Method= 1
Unsteady Friction Slope Method= 2
Unsteady Bridges Friction Slope Method= 1
Parabolic Critical Depth
Global Vel Dist=  1 , 1 , 1
Global Log Level= 0
CheckData=True
Encroach Param= -1, 0, 0, 0
BEGIN DESCRIPTION:
Multiple Run
END DESCRIPTION:

--- Stream0169_DS.f01 (steady flow) ---

Flow Title=Multiple
Number of Profiles=7
Profile Names=10-year,25-year,50-year,1pct_min,100-year,1pct_plu,500-year
River Rch & RM= Stream0169_DS,Reach-1,661
     884    1484    2053    1379    2751    5488    4879
River Rch & RM= Stream0169_DS,Reach-1,4
    1069    1815    2527    1708    3408    6799    6124
Boundary for River Rch & Prof#=Stream0169_DS,Reach-1,1
Up Type=0
Dn Type=3
Dn Slope=0.005
Boundary for River Rch & Prof#=Stream0169_DS,Reach-1,2
Up Type=0
Dn Type=3
Dn Slope=0.005
Boundary for River Rch & Prof#=Stream0169_DS,Reach-1,3
Up Type=0
Dn Type=3
Dn Slope=0.005
Boundary for River Rch & Prof#=Stream0169_DS,Reach-1,4
Up Type=0
Dn Type=3
Dn Slope=0.005
Boundary for River Rch & Prof#=Stream0169_DS,Reach-1,5
Up Type=0
Dn Type=3
Dn Slope=0.005
Boundary for River Rch & Prof#=Stream0169_DS,Reach-1,6
Up Type=0
Dn Type=3
Dn Slope=0.005
Boundary for River Rch & Prof#=Stream0169_DS,Reach-1,7
Up Type=0
Dn Type=3
Dn Slope=0.005

--- Stream0169_DS.g01 (geometry) ---

Geom Title=Existing Conditions

River Reach=Stream0169_DS,Reach-1
Reach XY= 30
      2102790.87     13887302.88      2102674.21     13887220.03
      2102473.52     13887024.12      2102391.48     13886891.78
      2102347.24     13886848.36      2102335.95     13886835.06
      2102332.26     13886825.09      2102334.29     13886818.46
      2102341.74     13886808.49      2102364.07     13886784.69
      2102369.35     13886777.30      2102372.86     13886769.37
      2102375.29     13886752.23      2102374.72     13886739.12
      2102373.05     13886730.72      2102369.64     13886722.81
      2102364.48     13886715.46      2102339.11     13886688.07
      2102331.16     13886677.20      2102326.85     13886665.16
      2102323.20     13886634.84      2102318.93     13886622.80
      2102311.04     13886611.93      2102286.04     13886584.57
      2102279.04     13886573.33      2102275.77     13886559.68
      2102273.40     13886535.66      2102269.33     13886522.64
      2102258.59     13886508.07      2102225.00     13886475.00

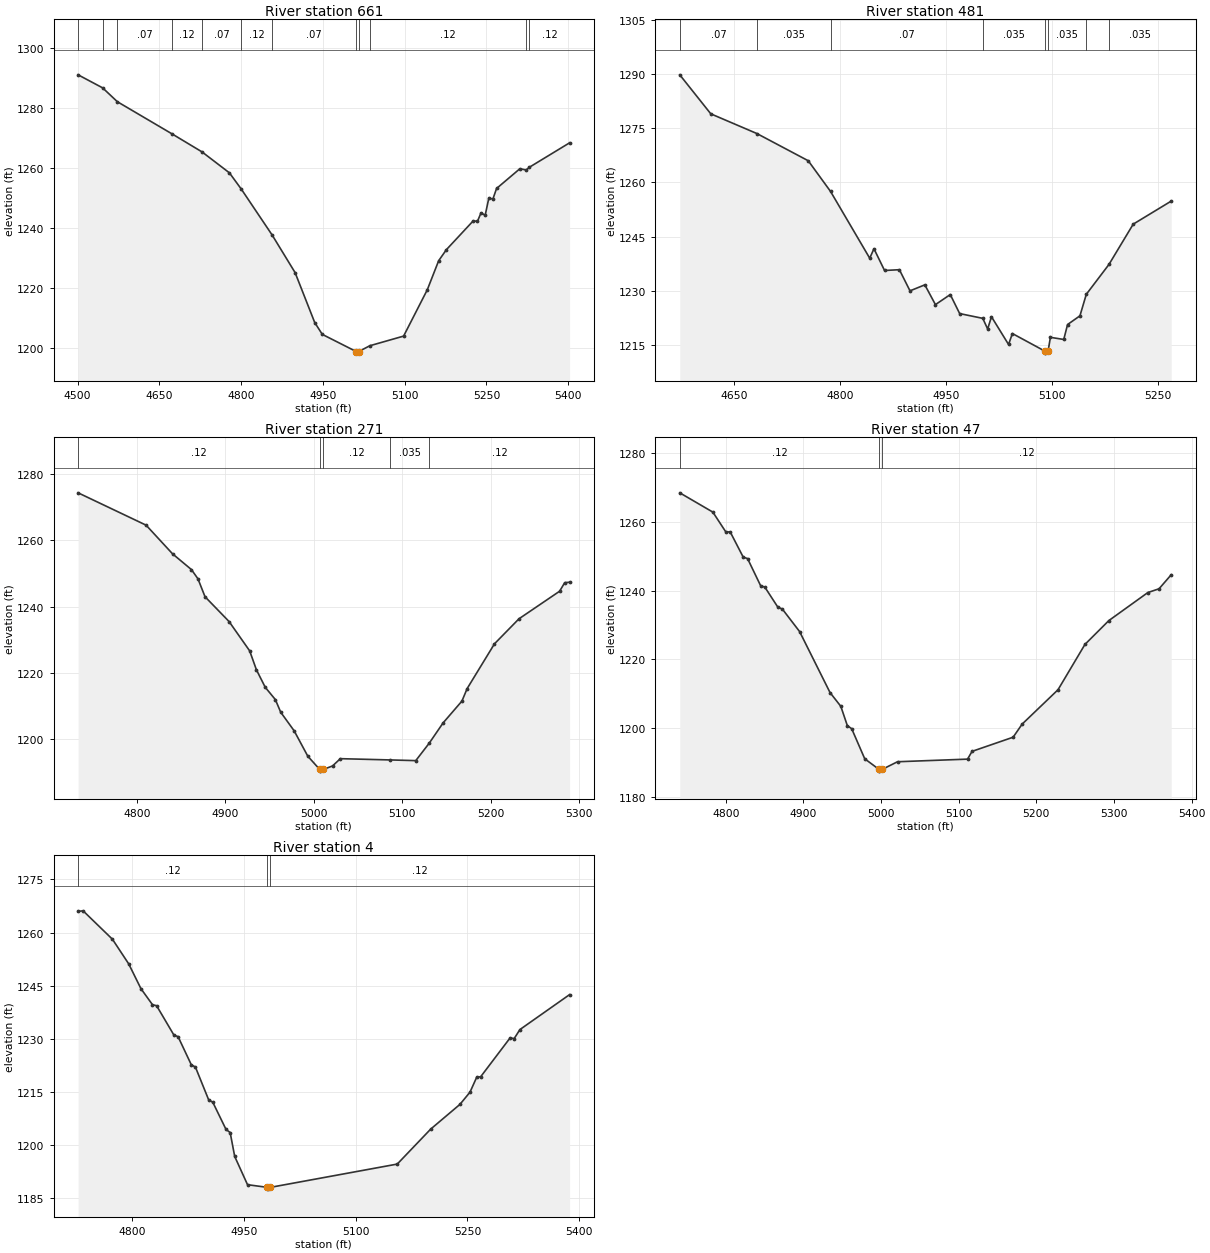
Type RM Length L Ch R = 1,661,180,180,180
BEGIN DESCRIPTION:
Stream0169_DS 2.0
END DESCRIPTION:
XS GIS Cut Line= 3
      2102869.23     13886720.29      2102473.52     13887024.12
      2102172.00     13887290.75
#Sta/Elev= 30
  4501.1 1291.07  4546.0 1286.73  4573.1 1282.10  4673.3 1271.38  4728.4 1265.36
  4778.6 1258.38  4800.5 1252.93  4856.9 1237.66  4899.1 1225.10  4935.1 1208.44
  4949.0 1204.50  5011.5 1198.75  5011.7 1198.25  5015.5 1198.75  5036.1 1200.71
  5098.1 1203.93  5141.5 1219.36  5162.4 1229.07  5176.6 1232.76  5225.9 1242.39
  5233.5 1242.18  5240.1 1245.04  5247.7 1244.22  5254.4 1249.95  5261.9 1249.66
  5268.6 1253.16  5311.3 1259.74  5323.1 1259.34  5329.0 1260.27  5402.5 1268.39
#Mann=12,-1,0
  4501.1    0.07       0  4546.0   0.035       0  4573.1    0.07       0
  4673.3    0.12       0  4728.4    0.07       0  4800.5    0.12       0
  4856.9    0.07       0  5011.5    0.05       0  5015.5    0.07       0
  5036.1    0.12       0  5323.1    0.07       0  5329.0    0.12       0
Bank Sta=5011.5,5015.5
Exp/Cntr=0.3,0.1

Type RM Length L Ch R = 1,481,210,210,210
BEGIN DESCRIPTION:
Stream0169_DS 1.0
END DESCRIPTION:
XS GIS Cut Line= 3
      2102728.54     13886636.88      2102375.00     13886875.00
      2102125.01     13886974.99
#Sta/Elev= 30
  4573.2 1289.73  4617.1 1278.94  4682.3 1273.49  4755.0 1265.96  4786.6 1257.46
  4842.0 1239.00  4848.0 1241.62  4863.0 1235.60  4884.0 1235.82  4899.0 1229.97
  4920.0 1231.63  4935.0 1226.16  4956.0 1228.94  4969.3 1223.68  5002.0 1222.36
  5008.9 1219.42  5014.3 1222.81  5038.5 1215.13  5043.9 1218.16  5090.4 1213.24
  5090.6 1212.74  5094.4 1213.24  5097.7 1217.11  5116.6 1216.52  5122.0 1220.65
  5139.5 1223.06  5148.5 1229.01  5180.6 1237.28  5214.9 1248.42  5268.7 1254.80
#Mann=8,-1,0
  4573.2    0.07       0  4682.3   0.035       0  4786.6    0.07       0
  5002.0   0.035       0  5090.4    0.05       0  5094.4   0.035       0
  5148.5    0.12       0  5180.6   0.035       0
Bank Sta=5090.4,5094.4
Exp/Cntr=0.3,0.1

Type RM Length L Ch R = 1,271,224,224,224
BEGIN DESCRIPTION:
Stream0169_DS 0.2
END DESCRIPTION:
XS GIS Cut Line= 2
      2102580.68     13886564.15      2102106.15     13886853.33
#Sta/Elev= 30
  4733.4 1274.24  4810.3 1264.50  4840.2 1255.87  4861.5 1251.14  4868.9 1248.36
  4876.9 1242.96  4904.1 1235.49  4927.4 1226.66  4935.0 1220.97  4945.0 1215.69
  4956.4 1212.01  4962.5 1208.19  4977.7 1202.59  4993.1 1194.96  5006.6 1190.96
  5006.9 1190.46  5010.6 1190.96  5021.1 1192.02  5029.9 1194.21  5086.2 1193.83
  5115.2 1193.62  5130.5 1198.91  5146.1 1204.98  5167.4 1211.55  5173.3 1215.32
  5204.2 1228.79  5231.9 1236.32  5277.8 1244.61  5283.6 1247.19  5289.1 1247.33
#Mann=5,-1,0
  4733.4    0.12       0  5006.6    0.05       0  5010.6    0.12       0
  5086.2   0.035       0  5130.5    0.12       0
Bank Sta=5006.6,5010.6
Exp/Cntr=0.3,0.1

Type RM Length L Ch R = 1,47,43,43,43
BEGIN DESCRIPTION:
Stream0169_DS 0.1
END DESCRIPTION:
XS GIS Cut Line= 3
      2102490.44     13886392.11      2102258.33     13886508.33
      2102070.60     13886831.02
#Sta/Elev= 30
  4740.8 1268.46  4783.4 1262.85  4800.2 1257.05  4805.7 1257.11  4822.5 1249.75
  4828.1 1249.33  4844.9 1241.45  4850.4 1241.01  4867.2 1235.16  4872.8 1234.67
  4895.1 1228.10  4934.3 1210.35  4948.2 1206.34  4956.6 1200.72  4962.2 1199.83
  4979.0 1191.08  4997.4 1187.99  4997.7 1187.49  5001.4 1187.99  5021.2 1190.22
  5111.4 1190.98  5117.2 1193.24  5170.1 1197.36  5181.7 1201.17  5227.9 1211.17
  5262.6 1224.36  5293.4 1231.30  5343.6 1239.45  5358.0 1240.54  5373.7 1244.63
#Mann=3,-1,0
  4740.8    0.12       0  4997.4    0.05       0  5001.4    0.12       0
Bank Sta=4997.4,5001.4
Exp/Cntr=0.3,0.1

Type RM Length L Ch R = 1,4,0,0,0
BEGIN DESCRIPTION:
Stream0169_DS 0.0
END DESCRIPTION:
XS GIS Cut Line= 3
      2102477.13     13886367.77      2102228.25     13886477.81
      2102055.97     13886824.66
#Sta/Elev= 30
  4727.6 1265.98  4734.3 1266.13  4773.7 1258.10  4795.5 1251.15  4811.9 1244.16
  4827.4 1239.63  4832.9 1239.35  4856.2 1231.04  4861.7 1230.62  4879.5 1222.67
  4885.0 1222.03  4902.8 1212.76  4908.3 1212.11  4926.1 1204.41  4931.6 1203.56
  4937.7 1196.81  4954.9 1188.83  4981.6 1188.08  4981.9 1187.58  4985.6 1188.08
  5155.8 1194.65  5200.6 1204.51  5239.9 1211.50  5253.4 1214.95  5262.3 1219.12
  5267.8 1219.32  5307.1 1230.23  5312.7 1230.09  5320.4 1232.62  5387.0 1242.48
#Mann=3,-1,0
  4727.6    0.12       0  4981.6    0.05       0  4985.6    0.12       0
Bank Sta=4981.6,4985.6
Exp/Cntr=0.3,0.1

Chan Stop Cuts=-1