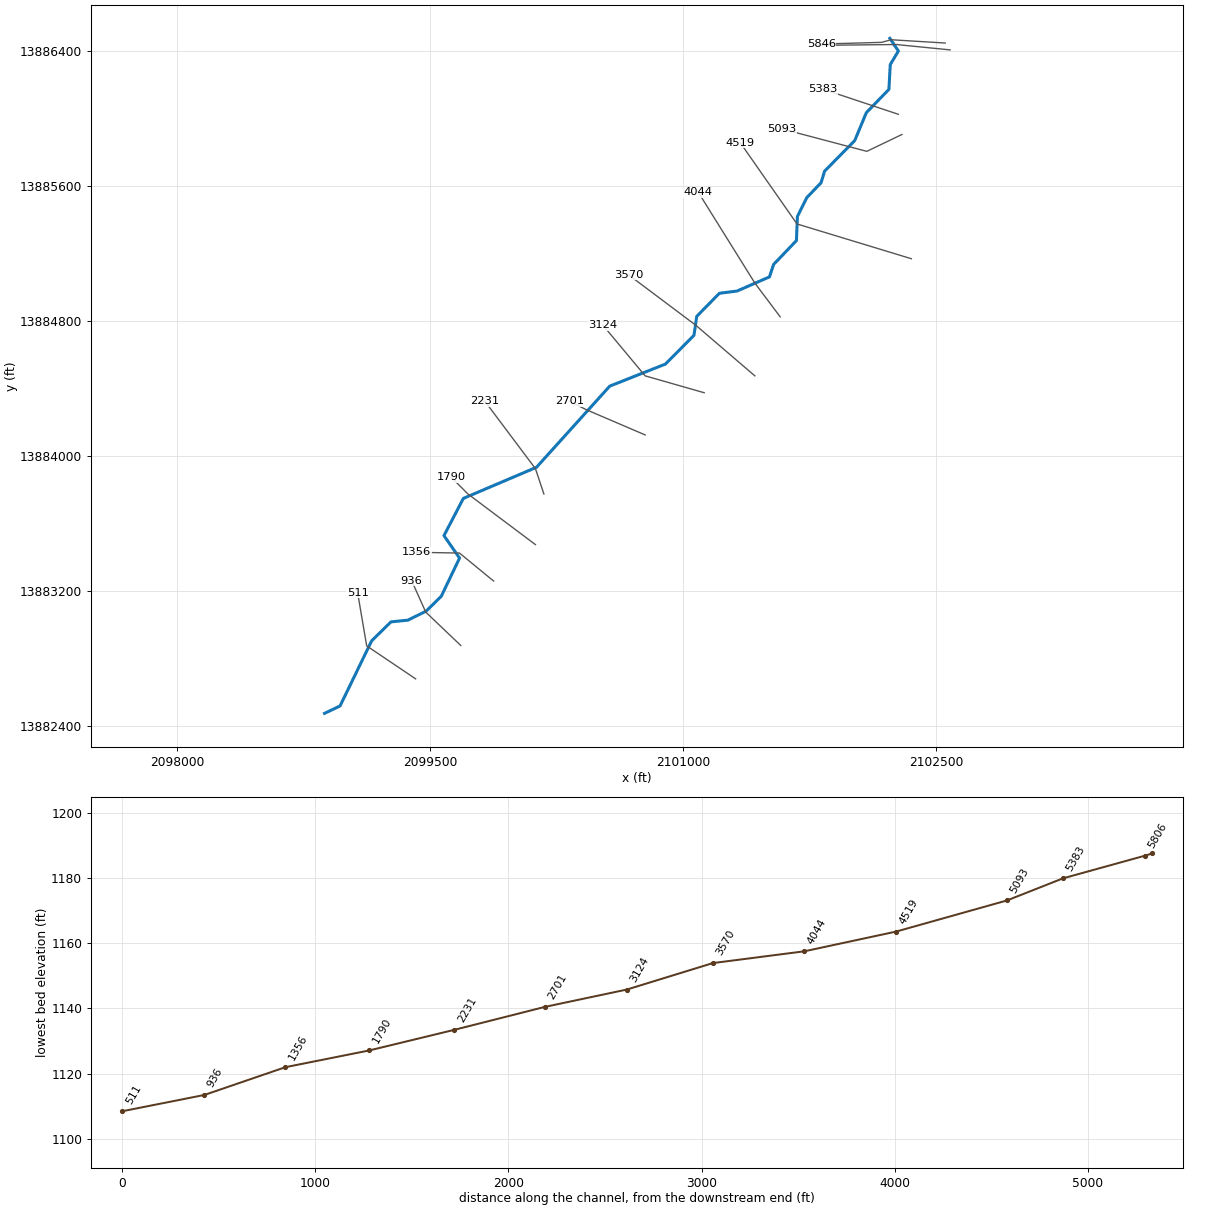
--- Stream0170_DS.prj (project) ---

Proj Title=Stream0170_DS Base Level Engineering
Current Plan=p01
Default Exp/Contr=0.3,0.1
English Units
Geom File=g01
Flow File=f01
Plan File=p01
BEGIN DESCRIPTION:
Stream0170_DS
END DESCRIPTION:

--- Stream0170_DS.p01 (plan) ---

Plan Title=Multiple Run
Short Identifier=Multiple
Geom File=g01
Flow File=f01
Subcritical Flow
K Sum by GR= 0
Std Step Tol= 0.01
Critical Tol= 0.01
Num of Std Step Trials= 20
Max Error Tol= 0.3
Flow Tol Ratio= 0.001
Split Flow NTrial= 30
Split Flow Tol= 0.02
Split Flow Ratio= 0.02
Log Output Level= 0
Friction Slope Method= 1
Unsteady Friction Slope Method= 2
Unsteady Bridges Friction Slope Method= 1
Parabolic Critical Depth
Global Vel Dist=  1 , 1 , 1
Global Log Level= 0
CheckData=True
Encroach Param= -1, 0, 0, 0
BEGIN DESCRIPTION:
Multiple Run
END DESCRIPTION:

--- Stream0170_DS.f01 (steady flow) ---

Flow Title=Multiple
Number of Profiles=7
Profile Names=10-year,25-year,50-year,1pct_min,100-year,1pct_plu,500-year
River Rch & RM= Stream0170_DS,Reach-1,5846
    1069    1815    2527    1708    3408    6799    6124
River Rch & RM= Stream0170_DS,Reach-1,4519
    1348    2319    3258    2220    4429    8836    8089
River Rch & RM= Stream0170_DS,Reach-1,3570
    1502    2590    3645    2484    4956    9889    9065
Boundary for River Rch & Prof#=Stream0170_DS,Reach-1,1
Up Type=0
Dn Type=3
Dn Slope=0.005
Boundary for River Rch & Prof#=Stream0170_DS,Reach-1,2
Up Type=0
Dn Type=3
Dn Slope=0.005
Boundary for River Rch & Prof#=Stream0170_DS,Reach-1,3
Up Type=0
Dn Type=3
Dn Slope=0.005
Boundary for River Rch & Prof#=Stream0170_DS,Reach-1,4
Up Type=0
Dn Type=3
Dn Slope=0.005
Boundary for River Rch & Prof#=Stream0170_DS,Reach-1,5
Up Type=0
Dn Type=3
Dn Slope=0.005
Boundary for River Rch & Prof#=Stream0170_DS,Reach-1,6
Up Type=0
Dn Type=3
Dn Slope=0.005
Boundary for River Rch & Prof#=Stream0170_DS,Reach-1,7
Up Type=0
Dn Type=3
Dn Slope=0.005

--- Stream0170_DS.g01 (geometry) ---

Geom Title=Existing Conditions

River Reach=Stream0170_DS,Reach-1
Reach XY= 30
      2102225.00     13886475.00      2102275.61     13886399.95
      2102227.40     13886319.48      2102219.53     13886172.55
      2102085.77     13886034.68      2102016.86     13885868.94
      2101838.57     13885688.23      2101817.06     13885618.86
      2101732.91     13885531.15      2101677.24     13885419.07
      2101671.46     13885276.47      2101535.79     13885134.66
      2101511.54     13885061.37      2101319.43     13884977.47
      2101215.21     13884964.48      2101080.52     13884827.43
      2101064.48     13884715.21      2100895.09     13884544.78
      2100565.32     13884414.24      2100131.06     13883933.14
      2099697.85     13883748.84      2099582.85     13883528.23
      2099675.37     13883395.20      2099566.87     13883168.93
      2099477.31     13883080.82      2099369.44     13883027.45
      2099268.83     13883017.14      2099154.61     13882905.16
      2098967.04     13882518.69      2098875.00     13882475.00

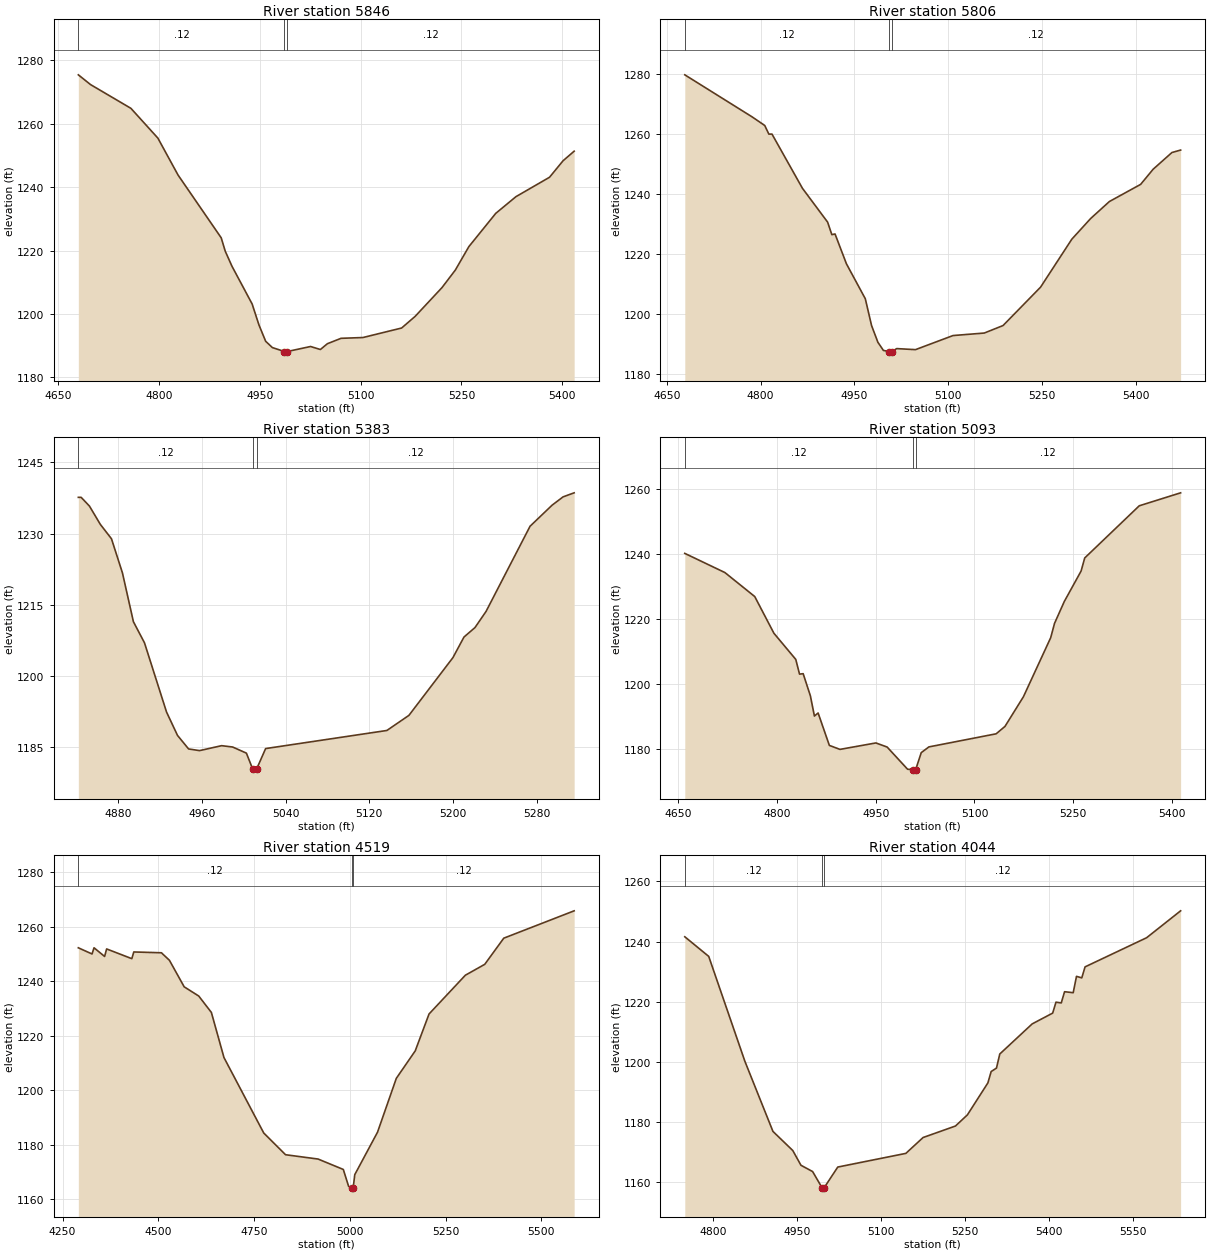
Type RM Length L Ch R = 1,5846,40,40,40
BEGIN DESCRIPTION:
Stream0170_DS 14.0
END DESCRIPTION:
XS GIS Cut Line= 4
      2102553.06     13886447.15      2102232.79     13886466.65
      2102175.65     13886451.14      2101818.46     13886441.13
#Sta/Elev= 30
  4680.2 1275.43  4698.3 1272.36  4758.4 1264.86  4798.5 1255.47  4828.5 1243.82
  4892.7 1224.01  4898.7 1219.79  4908.7 1215.05  4938.7 1203.14  4948.8 1196.55
  4958.8 1191.38  4968.8 1189.39  4986.8 1188.14  4987.1 1187.64  4990.8 1188.14
  5025.6 1189.73  5040.2 1188.78  5050.6 1190.61  5070.9 1192.31  5103.5 1192.56
  5161.0 1195.56  5181.0 1199.21  5221.0 1208.30  5241.0 1213.88  5261.0 1221.23
  5301.0 1231.73  5331.0 1236.99  5381.0 1243.12  5401.1 1248.32  5417.6 1251.34
#Mann=3,-1,0
  4680.2    0.12       0  4986.8    0.05       0  4990.8    0.12       0
Bank Sta=4986.8,4990.8
Exp/Cntr=0.3,0.1

Type RM Length L Ch R = 1,5806,423,423,423
BEGIN DESCRIPTION:
Stream0170_DS 13.0
END DESCRIPTION:
XS GIS Cut Line= 3
      2102582.18     13886406.55      2102262.46     13886438.35
      2101791.08     13886433.45
#Sta/Elev= 30
  4678.7 1279.75  4786.4 1265.71  4806.5 1262.85  4813.1 1259.97  4818.1 1259.98
  4866.8 1241.89  4907.0 1230.62  4913.8 1226.44  4918.9 1226.66  4937.1 1216.71
  4967.3 1205.05  4977.3 1196.11  4987.4 1190.54  4996.2 1187.82  5005.5 1187.41
  5005.7 1186.91  5009.5 1187.41  5017.5 1188.42  5047.5 1188.07  5107.5 1192.77
  5157.5 1193.61  5187.5 1196.11  5247.5 1208.92  5297.5 1224.93  5327.5 1231.80
  5357.5 1237.48  5407.5 1243.21  5427.5 1248.26  5457.5 1253.83  5471.4 1254.65
#Mann=3,-1,0
  4678.7    0.12       0  5005.5    0.05       0  5009.5    0.12       0
Bank Sta=5005.5,5009.5
Exp/Cntr=0.3,0.1

Type RM Length L Ch R = 1,5383,290,290,290
BEGIN DESCRIPTION:
Stream0170_DS 12.0
END DESCRIPTION:
XS GIS Cut Line= 3
      2102275.04     13886024.99      2102125.00     13886075.00
      2101824.99     13886175.00
#Sta/Elev= 30
  4841.6 1237.63  4844.3 1237.63  4852.2 1235.80  4862.7 1231.92  4873.3 1228.91
  4883.8 1221.72  4894.3 1211.44  4904.9 1206.99  4926.0 1192.41  4936.5 1187.49
  4947.1 1184.64  4957.6 1184.29  4978.7 1185.33  4989.2 1185.05  5002.4 1183.76
  5008.3 1180.47  5008.5 1179.97  5012.0 1179.97  5012.3 1180.47  5020.8 1184.72
  5136.8 1188.53  5157.9 1191.71  5200.0 1203.87  5210.6 1208.21  5221.1 1210.20
  5231.7 1213.60  5273.8 1231.54  5294.9 1235.98  5305.4 1237.73  5316.0 1238.58
#Mann=3,-1,0
  4841.6    0.12       0  5008.3    0.05       0  5012.3    0.12       0
Bank Sta=5008.3,5012.3
Exp/Cntr=0.3,0.1

Type RM Length L Ch R = 1,5093,574,574,574
BEGIN DESCRIPTION:
Stream0170_DS 11.0
END DESCRIPTION:
XS GIS Cut Line= 3
      2102296.94     13885905.41      2102088.53     13885805.37
      2101584.25     13885938.73
#Sta/Elev= 30
  4660.2 1240.17  4721.1 1234.27  4766.4 1226.89  4795.5 1215.60  4828.7 1207.55
  4834.4 1203.02  4839.9 1203.16  4850.9 1196.33  4857.0 1190.12  4862.6 1191.07
  4879.7 1181.09  4895.8 1179.87  4950.3 1181.85  4967.4 1180.59  4998.5 1173.75
  5006.8 1173.68  5007.1 1173.18  5010.8 1173.68  5019.2 1178.87  5030.8 1180.63
  5132.9 1184.66  5146.3 1186.93  5174.3 1196.05  5215.7 1214.21  5221.6 1218.66
  5236.4 1225.37  5261.9 1234.74  5267.4 1238.76  5350.2 1254.81  5413.0 1258.80
#Mann=3,-1,0
  4660.2    0.12       0  5006.8    0.05       0  5010.8    0.12       0
Bank Sta=5006.8,5010.8
Exp/Cntr=0.3,0.1

Type RM Length L Ch R = 1,4519,475,475,475
BEGIN DESCRIPTION:
Stream0170_DS 10.0
END DESCRIPTION:
XS GIS Cut Line= 3
      2102352.51     13885169.08      2101675.00     13885375.00
      2101339.34     13885855.57
#Sta/Elev= 30
  4291.3 1252.21  4327.1 1249.94  4332.3 1252.21  4359.9 1249.03  4365.2 1251.79
  4430.9 1248.22  4436.1 1250.68  4508.2 1250.38  4529.1 1247.62  4567.6 1237.89
  4605.7 1234.49  4638.6 1228.48  4671.5 1211.91  4775.3 1184.22  4832.2 1176.25
  4917.2 1174.66  4983.0 1170.84  4996.8 1164.66  5004.8 1164.12  5005.1 1163.62
  5008.8 1164.12  5012.9 1168.93  5072.3 1184.52  5121.4 1204.29  5170.8 1214.38
  5206.8 1227.91  5301.6 1242.14  5352.2 1246.14  5401.9 1255.74  5585.6 1265.78
#Mann=3,-1,0
  4291.3    0.12       0  5004.8    0.05       0  5008.8    0.12       0
Bank Sta=5004.8,5008.8
Exp/Cntr=0.3,0.1

Type RM Length L Ch R = 1,4044,474,474,474
BEGIN DESCRIPTION:
Stream0170_DS 9.0
END DESCRIPTION:
XS GIS Cut Line= 3
      2101574.98     13884825.03      2101425.00     13885025.00
      2101089.31     13885563.82
#Sta/Elev= 30
  4750.1 1241.58  4792.8 1235.05  4857.4 1200.09  4907.4 1176.78  4942.8 1170.41
  4957.4 1165.50  4978.2 1163.41  4994.9 1158.06  4995.2 1157.56  4998.9 1158.06
  5023.1 1164.91  5144.6 1169.46  5175.3 1174.74  5233.1 1178.57  5254.4 1182.28
  5291.0 1192.94  5296.8 1196.71  5306.3 1197.86  5312.2 1202.55  5370.0 1212.57
  5406.6 1216.17  5412.5 1219.81  5421.9 1219.55  5427.8 1223.29  5443.2 1222.96
  5449.1 1228.41  5458.5 1227.89  5464.4 1231.56  5574.2 1241.26  5634.9 1250.22
#Mann=3,-1,0
  4750.1    0.12       0  4994.9    0.05       0  4998.9    0.12       0
Bank Sta=4994.9,4998.9
Exp/Cntr=0.3,0.1

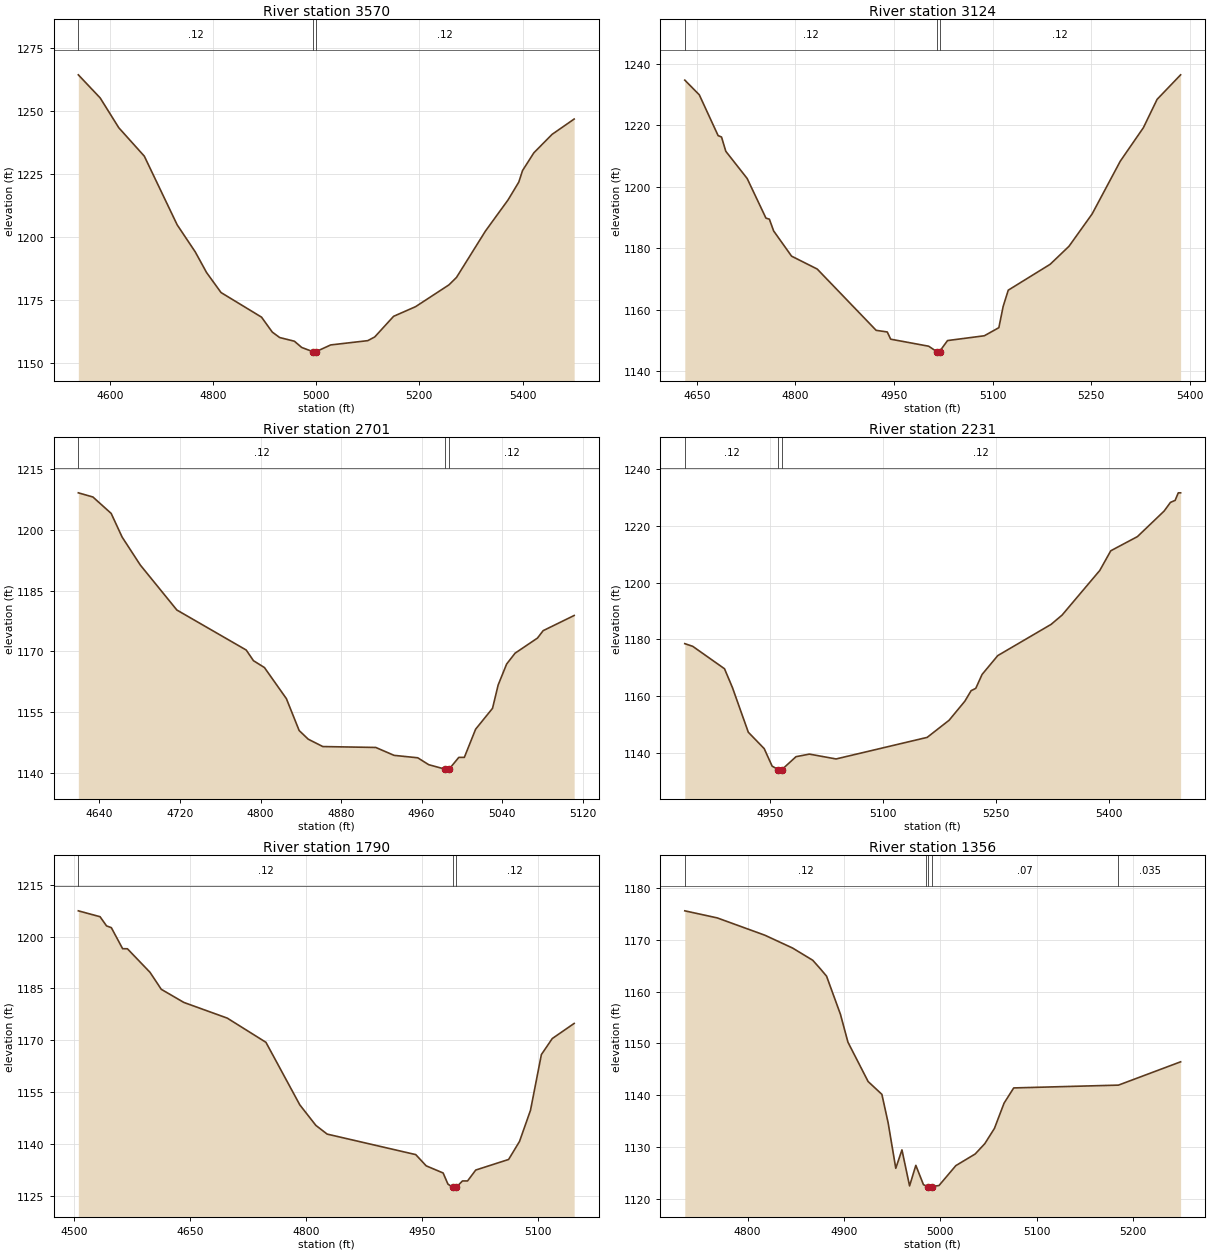
Type RM Length L Ch R = 1,3570,446,446,446
BEGIN DESCRIPTION:
Stream0170_DS 8.0
END DESCRIPTION:
XS GIS Cut Line= 3
      2101425.02     13884474.98      2101075.00     13884775.00
      2100675.01     13885075.00
#Sta/Elev= 30
  4539.0 1264.38  4581.3 1255.22  4617.5 1243.36  4666.9 1232.10  4730.6 1204.84
  4765.7 1194.09  4787.6 1185.90  4815.6 1177.98  4894.1 1168.21  4914.9 1162.29
  4929.2 1160.13  4957.8 1158.66  4972.0 1156.18  4994.7 1154.44  4994.9 1153.94
  4998.8 1154.44  5028.1 1157.19  5100.0 1158.89  5113.5 1160.36  5150.0 1168.54
  5192.7 1172.38  5257.3 1181.02  5271.9 1183.97  5328.1 1202.39  5371.9 1214.74
  5392.7 1221.82  5400.0 1226.41  5421.9 1233.43  5457.3 1240.77  5500.0 1246.83
#Mann=3,-1,0
  4539.0    0.12       0  4994.7    0.05       0  4998.8    0.12       0
Bank Sta=4994.7,4998.8
Exp/Cntr=0.3,0.1

Type RM Length L Ch R = 1,3124,423,423,423
BEGIN DESCRIPTION:
Stream0170_DS 7.0
END DESCRIPTION:
XS GIS Cut Line= 3
      2101124.98     13884375.01      2100775.00     13884475.00
      2100525.00     13884775.00
#Sta/Elev= 30
  4631.6 1234.70  4653.7 1229.90  4682.3 1216.63  4687.5 1216.17  4694.0 1211.52
  4726.5 1202.67  4755.1 1189.76  4760.3 1189.42  4766.8 1185.59  4794.1 1177.37
  4833.1 1173.18  4922.8 1153.22  4939.7 1152.69  4944.9 1150.34  5002.7 1148.05
  5015.0 1146.30  5015.2 1145.80  5019.2 1146.30  5031.4 1149.89  5087.4 1151.45
  5109.5 1154.09  5116.0 1160.96  5123.8 1166.30  5187.6 1174.73  5216.2 1180.58
  5251.4 1191.11  5294.3 1208.31  5329.5 1219.23  5350.3 1228.43  5386.1 1236.42
#Mann=3,-1,0
  4631.6    0.12       0  5015.0    0.05       0  5019.2    0.12       0
Bank Sta=5015,5019.2
Exp/Cntr=0.3,0.1

Type RM Length L Ch R = 1,2701,470,470,470
BEGIN DESCRIPTION:
Stream0170_DS 6.0
END DESCRIPTION:
XS GIS Cut Line= 3
      2100774.97     13884125.01      2100425.00     13884275.00
      2100324.96     13884325.02
#Sta/Elev= 30
  4619.0 1209.14  4633.5 1208.11  4651.6 1204.07  4662.5 1198.23  4680.6 1191.32
  4716.9 1180.23  4785.8 1170.36  4793.0 1167.73  4803.9 1166.04  4825.7 1158.37
  4838.4 1150.50  4847.4 1148.37  4861.9 1146.55  4914.5 1146.33  4932.7 1144.38
  4956.2 1143.78  4967.1 1142.08  4983.1 1140.99  4983.4 1140.49  4987.4 1140.99
  4997.0 1143.88  5002.5 1143.88  5013.7 1150.83  5030.5 1155.98  5036.1 1161.74
  5044.5 1166.90  5052.9 1169.58  5075.2 1173.32  5080.8 1175.14  5111.6 1178.88
#Mann=3,-1,0
  4619.0    0.12       0  4983.1    0.05       0  4987.4    0.12       0
Bank Sta=4983.1,4987.4
Exp/Cntr=0.3,0.1

Type RM Length L Ch R = 1,2231,441,441,441
BEGIN DESCRIPTION:
Stream0170_DS 5.0
END DESCRIPTION:
XS GIS Cut Line= 3
      2100175.00     13883775.00      2100125.00     13883925.00
      2099825.01     13884324.99
#Sta/Elev= 30
  4837.4 1178.46  4847.9 1177.52  4890.1 1169.60  4900.6 1162.97  4921.7 1147.17
  4942.8 1141.38  4953.3 1135.20  4961.7 1133.93  4962.0 1133.43  4966.1 1133.93
  4985.0 1138.53  5002.8 1139.44  5038.2 1137.73  5159.1 1145.35  5188.2 1151.40
  5209.1 1158.13  5217.4 1161.84  5223.6 1162.67  5232.0 1167.59  5252.8 1174.24
  5323.6 1185.27  5338.2 1188.56  5388.2 1204.32  5402.8 1211.27  5438.2 1216.28
  5473.6 1225.30  5482.0 1228.36  5488.2 1229.07  5492.4 1231.74  5495.5 1231.74
#Mann=3,-1,0
  4837.4    0.12       0  4961.7    0.05       0  4966.1    0.12       0
Bank Sta=4961.7,4966.1
Exp/Cntr=0.3,0.1

Type RM Length L Ch R = 1,1790,434,434,434
BEGIN DESCRIPTION:
Stream0170_DS 4.0
END DESCRIPTION:
XS GIS Cut Line= 3
      2100125.00     13883475.00      2099725.00     13883775.00
      2099625.02     13883874.98
#Sta/Elev= 30
  4505.0 1207.41  4533.1 1205.71  4541.5 1203.06  4547.7 1202.55  4562.3 1196.48
  4568.5 1196.46  4597.7 1189.67  4612.3 1184.76  4641.5 1180.97  4697.7 1176.44
  4747.7 1169.46  4791.5 1151.41  4812.3 1145.48  4826.9 1142.97  4941.5 1137.05
  4955.0 1133.81  4976.9 1131.75  4983.1 1128.55  4989.3 1127.59  4989.6 1127.09
  4993.7 1127.59  5001.9 1129.45  5008.5 1129.45  5019.1 1132.60  5061.6 1135.65
  5075.7 1140.85  5089.9 1149.83  5104.0 1165.92  5118.1 1170.55  5146.4 1174.91
#Mann=3,-1,0
  4505.0    0.12       0  4989.3    0.05       0  4993.7    0.12       0
Bank Sta=4989.3,4993.7
Exp/Cntr=0.3,0.1

Type RM Length L Ch R = 1,1356,420,420,420
BEGIN DESCRIPTION:
Stream0170_DS 3.0
END DESCRIPTION:
XS GIS Cut Line= 3
      2099876.83     13883259.36      2099675.00     13883425.00
      2099421.94     13883429.50
#Sta/Elev= 30
  4734.9 1175.55  4768.5 1174.19  4818.0 1170.85  4846.7 1168.38  4867.6 1166.03
  4875.4 1164.40  4881.9 1162.97  4896.3 1155.63  4904.1 1150.25  4925.0 1142.68
  4939.3 1140.20  4945.8 1134.70  4953.7 1125.96  4960.1 1129.51  4968.0 1122.57
  4974.5 1126.53  4982.4 1122.81  4985.4 1122.55  4986.6 1122.45  4986.9 1121.95
  4991.1 1122.45  4998.5 1122.64  5016.0 1126.48  5036.0 1128.71  5046.0 1130.70
  5056.0 1133.64  5066.0 1138.51  5076.0 1141.44  5184.6 1141.98  5249.1 1146.47
#Mann=5,-1,0
  4734.9    0.12       0  4985.4    0.07       0  4986.6    0.05       0
  4991.1    0.07       0  5184.6   0.035       0
Bank Sta=4986.6,4991.1
Exp/Cntr=0.3,0.1

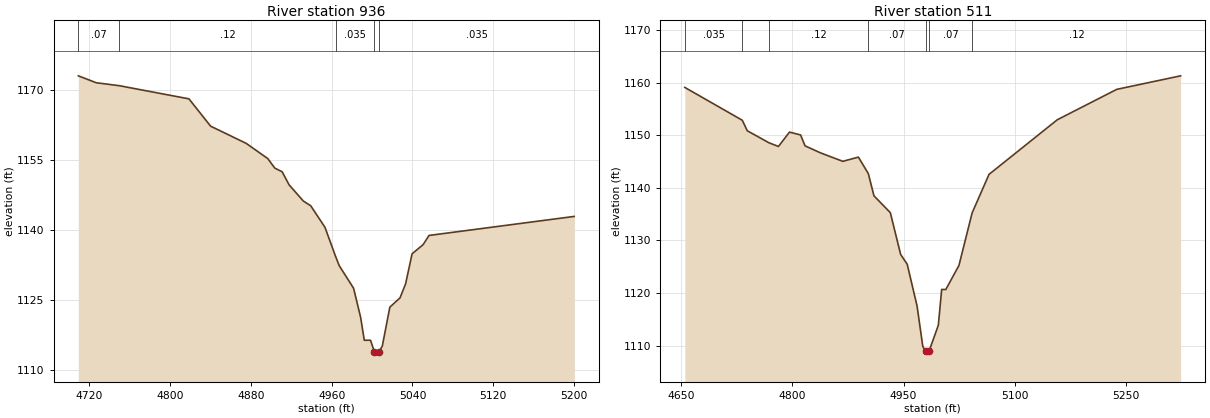
Type RM Length L Ch R = 1,936,425,425,425
BEGIN DESCRIPTION:
Stream0170_DS 2.0
END DESCRIPTION:
XS GIS Cut Line= 3
      2099682.37     13882877.42      2099475.00     13883075.00
      2099391.37     13883261.37
#Sta/Elev= 30
  4709.3 1172.97  4727.0 1171.49  4749.8 1170.86  4818.8 1168.04  4840.2 1162.20
  4875.4 1158.52  4896.8 1155.26  4903.7 1153.23  4911.0 1152.44  4917.9 1149.64
  4932.0 1146.17  4939.3 1145.16  4953.4 1140.55  4963.9 1134.32  4967.6 1132.30
  4981.7 1127.52  4988.7 1121.27  4992.3 1116.38  4998.5 1116.38  5002.3 1113.91
  5002.6 1113.41  5006.8 1113.91  5010.1 1115.10  5017.6 1123.47  5027.7 1125.46
  5033.2 1128.46  5039.6 1134.88  5050.5 1136.84  5056.4 1138.81  5200.0 1142.88
#Mann=5,-1,0
  4709.3    0.07       0  4749.8    0.12       0  4963.9   0.035       0
  5002.3   0.035       0  5006.8   0.035       0
Bank Sta=5002.3,5006.8
Exp/Cntr=0.3,0.1

Type RM Length L Ch R = 1,511,0,0,0
BEGIN DESCRIPTION:
Stream0170_DS 1.0
END DESCRIPTION:
XS GIS Cut Line= 3
      2099414.99     13882679.52      2099125.00     13882875.00
      2099071.27     13883189.93
#Sta/Elev= 30
  4654.7 1159.07  4732.3 1152.83  4739.0 1150.84  4768.2 1148.56  4781.1 1147.85
  4796.0 1150.58  4811.0 1150.04  4817.0 1147.97  4838.0 1146.63  4868.0 1145.03
  4889.0 1145.83  4902.4 1142.70  4910.0 1138.48  4932.1 1135.28  4946.0 1127.36
  4954.9 1125.48  4968.2 1117.54  4975.9 1109.90  4979.7 1108.91  4980.0 1108.41
  4984.2 1108.91  4996.9 1113.90  5001.4 1120.69  5007.0 1120.69  5024.7 1125.25
  5042.5 1135.23  5065.3 1142.55  5157.4 1152.92  5237.7 1158.70  5323.9 1161.27
#Mann=7,-1,0
  4654.7   0.035       0  4732.3    0.07       0  4768.2    0.12       0
  4902.4    0.07       0  4979.7    0.05       0  4984.2    0.07       0
  5042.5    0.12       0
Bank Sta=4979.7,4984.2
Exp/Cntr=0.3,0.1

Chan Stop Cuts=-1