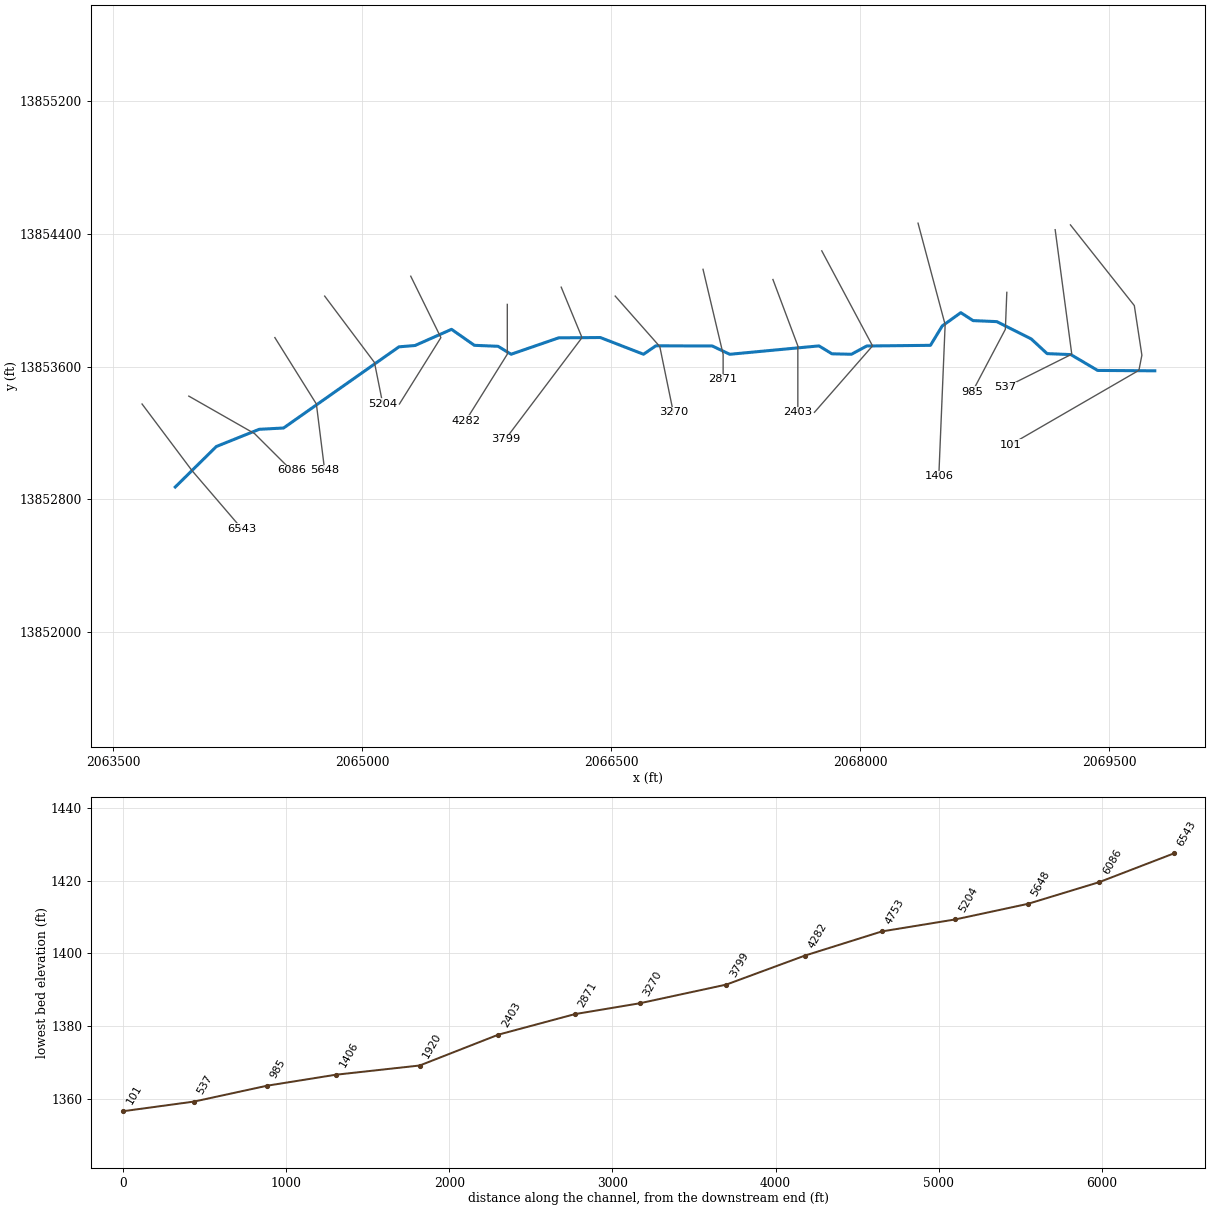
--- Stream0171_DS.prj (project) ---

Proj Title=Stream0171_DS Base Level Engineering
Current Plan=p01
Default Exp/Contr=0.3,0.1
English Units
Geom File=g01
Flow File=f01
Plan File=p01
BEGIN DESCRIPTION:
Stream0171_DS
END DESCRIPTION:

--- Stream0171_DS.p01 (plan) ---

Plan Title=Multiple Run
Short Identifier=Multiple
Geom File=g01
Flow File=f01
Subcritical Flow
K Sum by GR= 0
Std Step Tol= 0.01
Critical Tol= 0.01
Num of Std Step Trials= 20
Max Error Tol= 0.3
Flow Tol Ratio= 0.001
Split Flow NTrial= 30
Split Flow Tol= 0.02
Split Flow Ratio= 0.02
Log Output Level= 0
Friction Slope Method= 1
Unsteady Friction Slope Method= 2
Unsteady Bridges Friction Slope Method= 1
Parabolic Critical Depth
Global Vel Dist=  1 , 1 , 1
Global Log Level= 0
CheckData=True
Encroach Param= -1, 0, 0, 0
BEGIN DESCRIPTION:
Multiple Run
END DESCRIPTION:

--- Stream0171_DS.f01 (steady flow) ---

Flow Title=Multiple
Number of Profiles=7
Profile Names=10-year,25-year,50-year,1pct_min,100-year,1pct_plu,500-year
River Rch & RM= Stream0171_DS,Reach-1,6543
    2303    4044    5760    3970    7921   15804   14810
River Rch & RM= Stream0171_DS,Reach-1,1406
    2359    4140    5896    4061    8102   16166   15133
Boundary for River Rch & Prof#=Stream0171_DS,Reach-1,1
Up Type=0
Dn Type=3
Dn Slope=0.005
Boundary for River Rch & Prof#=Stream0171_DS,Reach-1,2
Up Type=0
Dn Type=3
Dn Slope=0.005
Boundary for River Rch & Prof#=Stream0171_DS,Reach-1,3
Up Type=0
Dn Type=3
Dn Slope=0.005
Boundary for River Rch & Prof#=Stream0171_DS,Reach-1,4
Up Type=0
Dn Type=3
Dn Slope=0.005
Boundary for River Rch & Prof#=Stream0171_DS,Reach-1,5
Up Type=0
Dn Type=3
Dn Slope=0.005
Boundary for River Rch & Prof#=Stream0171_DS,Reach-1,6
Up Type=0
Dn Type=3
Dn Slope=0.005
Boundary for River Rch & Prof#=Stream0171_DS,Reach-1,7
Up Type=0
Dn Type=3
Dn Slope=0.005

--- Stream0171_DS.g01 (geometry) ---

Geom Title=Existing Conditions

River Reach=Stream0171_DS,Reach-1
Reach XY= 30
      2063875.00     13852875.00      2064122.70     13853119.17
      2064380.53     13853222.61      2064527.44     13853230.48
      2065222.58     13853719.46      2065319.43     13853727.47
      2065539.12     13853824.81      2065676.47     13853728.56
      2065819.47     13853722.61      2065897.77     13853674.72
      2066184.66     13853773.62      2066435.19     13853775.45
      2066695.39     13853674.71      2066769.46     13853725.53
      2067109.78     13853724.48      2067214.81     13853674.55
      2067752.31     13853725.09      2067830.53     13853677.37
      2067947.83     13853674.69      2068040.22     13853724.48
      2068423.75     13853728.45      2068494.78     13853845.13
      2068606.54     13853925.25      2068680.52     13853877.41
      2068823.44     13853871.24      2069031.05     13853766.84
      2069126.47     13853678.55      2069269.48     13853672.64
      2069430.93     13853577.24      2069775.00     13853575.00

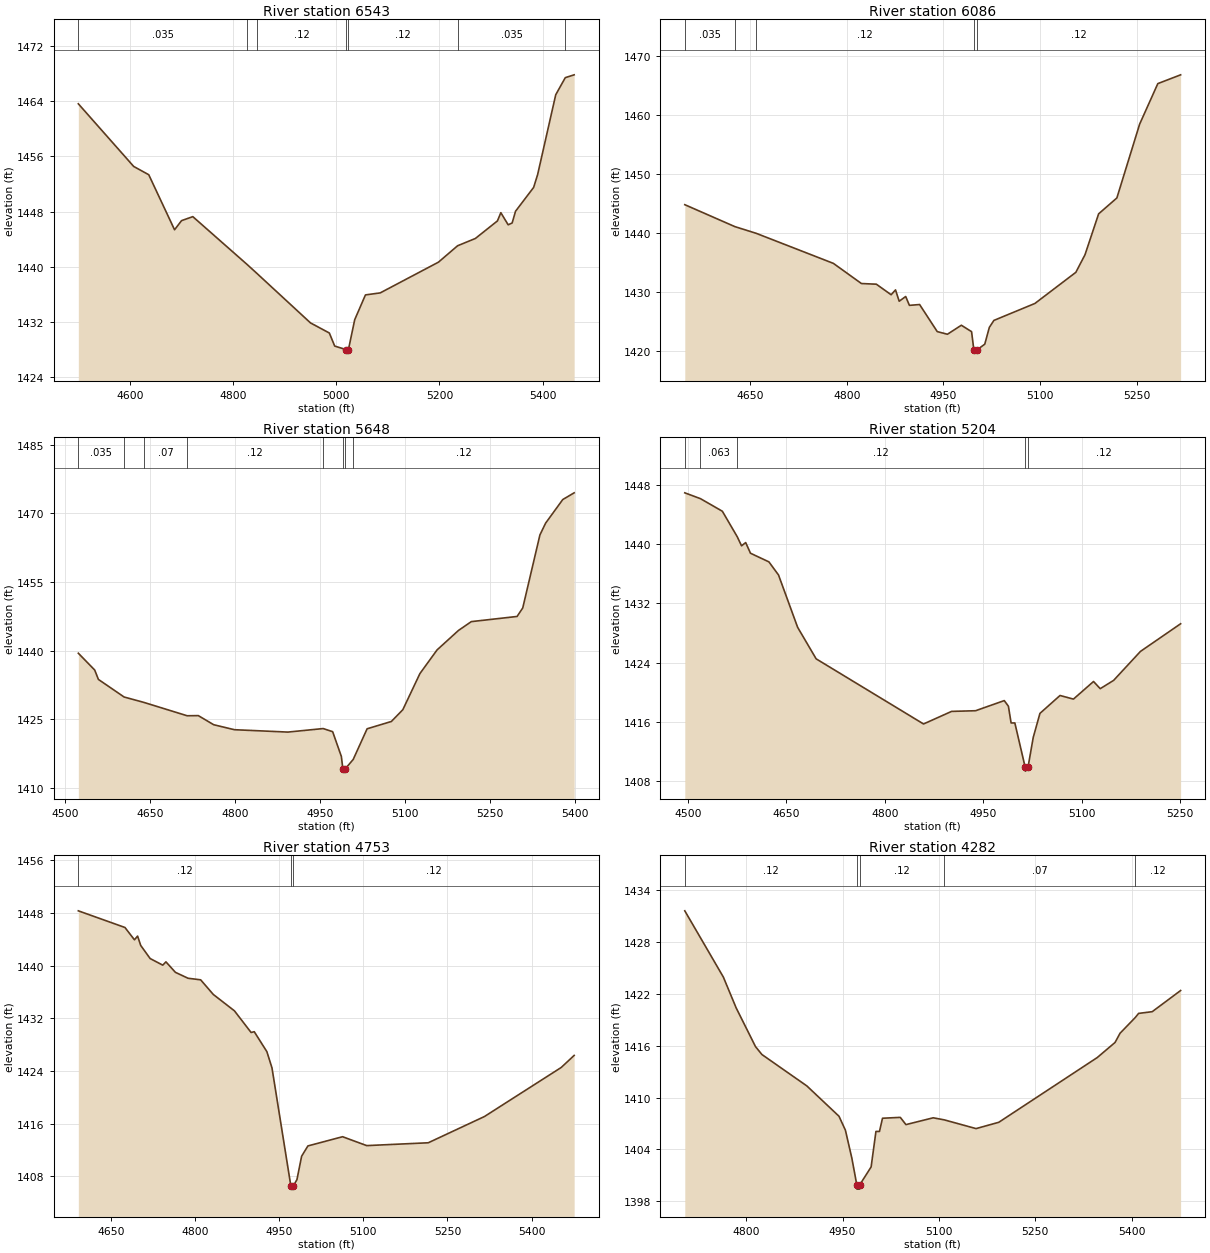
Type RM Length L Ch R = 1,6543,457,457,457
BEGIN DESCRIPTION:
Stream0171_DS 14.0
END DESCRIPTION:
XS GIS Cut Line= 3
      2063674.99     13853375.01      2063975.00     13852975.00
      2064275.00     13852625.00
#Sta/Elev= 30
  4500.0 1463.58  4607.3 1454.52  4636.5 1453.32  4686.5 1445.36  4700.0 1446.68
  4721.9 1447.26  4827.3 1440.33  4845.4 1439.10  4950.0 1431.89  4986.5 1430.43
  4996.9 1428.54  5019.4 1428.02  5019.6 1427.52  5023.5 1428.02  5035.7 1432.36
  5056.5 1435.94  5085.1 1436.23  5198.1 1440.68  5235.1 1443.05  5269.5 1444.10
  5312.3 1446.64  5318.9 1447.83  5333.1 1446.08  5340.8 1446.34  5347.4 1448.04
  5382.5 1451.49  5390.2 1453.34  5425.3 1464.89  5443.8 1467.36  5461.0 1467.77
#Mann=7,-1,0
  4500.0   0.035       0  4827.3    0.07       0  4845.4    0.12       0
  5019.4    0.05       0  5023.5    0.12       0  5235.1   0.035       0
  5443.8    0.12       0
Bank Sta=5019.4,5023.5
Exp/Cntr=0.3,0.1

Type RM Length L Ch R = 1,6086,438,438,438
BEGIN DESCRIPTION:
Stream0171_DS 13.0
END DESCRIPTION:
XS GIS Cut Line= 3
      2063956.67     13853422.56      2064352.53     13853196.86
      2064575.02     13852974.98
#Sta/Elev= 30
  4548.5 1444.79  4626.3 1441.07  4659.5 1439.93  4779.2 1434.84  4822.8 1431.42
  4845.9 1431.31  4868.9 1429.52  4875.7 1430.34  4881.4 1428.42  4891.5 1429.22
  4897.3 1427.72  4913.1 1427.86  4940.5 1423.27  4956.3 1422.82  4977.9 1424.35
  4993.8 1423.26  4997.4 1420.12  4997.7 1419.62  5001.6 1420.12  5014.3 1421.14
  5021.4 1423.99  5028.5 1425.17  5092.1 1428.04  5155.7 1433.32  5169.9 1436.30
  5191.1 1443.24  5219.4 1445.93  5254.7 1458.43  5283.0 1465.32  5318.4 1466.81
#Mann=5,-1,0
  4548.5   0.035       0  4626.3    0.07       0  4659.5    0.12       0
  4997.4    0.05       0  5001.6    0.12       0
Bank Sta=4997.4,5001.6
Exp/Cntr=0.3,0.1

Type RM Length L Ch R = 1,5648,444,444,444
BEGIN DESCRIPTION:
Stream0171_DS 12.0
END DESCRIPTION:
XS GIS Cut Line= 3
      2064474.99     13853775.01      2064725.00     13853375.00
      2064775.00     13852975.03
#Sta/Elev= 30
  4523.5 1439.42  4552.4 1435.74  4558.9 1433.69  4604.3 1429.84  4638.9 1428.67
  4715.5 1425.74  4735.2 1425.77  4762.3 1423.78  4798.9 1422.69  4893.2 1422.17
  4955.4 1422.94  4972.2 1422.26  4987.6 1416.83  4990.2 1414.13  4990.4 1413.63
  4994.4 1414.13  5008.5 1416.19  5033.0 1422.89  5075.8 1424.49  5096.0 1427.06
  5126.2 1434.97  5156.5 1440.15  5194.3 1444.41  5216.9 1446.33  5297.6 1447.46
  5307.6 1449.32  5337.9 1465.29  5347.9 1467.86  5378.2 1473.03  5398.3 1474.50
#Mann=8,-1,0
  4523.5   0.035       0  4604.3    0.12       0  4638.9    0.07       0
  4715.5    0.12       0  4955.4    0.07       0  4990.2    0.05       0
  4994.4    0.07       0  5008.5    0.12       0
Bank Sta=4990.2,4994.4
Exp/Cntr=0.3,0.1

Type RM Length L Ch R = 1,5204,451,451,451
BEGIN DESCRIPTION:
Stream0171_DS 11.0
END DESCRIPTION:
XS GIS Cut Line= 3
      2064775.03     13854024.96      2065075.00     13853625.00
      2065125.00     13853375.01
#Sta/Elev= 30
  4495.6 1446.95  4519.5 1446.16  4552.8 1444.46  4575.5 1441.01  4582.0 1439.79
  4588.3 1440.23  4595.6 1438.79  4623.7 1437.62  4638.3 1435.85  4667.4 1428.78
  4695.6 1424.52  4859.1 1415.72  4901.8 1417.42  4938.3 1417.51  4982.0 1418.88
  4988.3 1418.12  4992.4 1415.86  4998.1 1415.86  5013.9 1409.85  5014.1 1409.35
  5018.1 1409.85  5026.1 1413.90  5036.3 1417.15  5066.9 1419.57  5087.3 1419.08
  5117.9 1421.46  5128.1 1420.49  5148.5 1421.61  5189.3 1425.52  5250.5 1429.26
#Mann=5,-1,0
  4495.6   0.035       0  4519.5   0.063       0  4575.5    0.12       0
  5013.9    0.05       0  5018.1    0.12       0
Bank Sta=5013.9,5018.1
Exp/Cntr=0.3,0.1

Type RM Length L Ch R = 1,4753,471,471,471
BEGIN DESCRIPTION:
Stream0171_DS 10.0
END DESCRIPTION:
XS GIS Cut Line= 3
      2065293.49     13854144.78      2065475.00     13853775.00
      2065225.01     13853375.02
#Sta/Elev= 30
  4592.3 1448.31  4675.4 1445.78  4692.3 1443.91  4697.9 1444.47  4703.5 1443.05
  4720.3 1441.06  4742.8 1440.06  4748.4 1440.56  4765.3 1438.97  4787.8 1438.07
  4810.3 1437.83  4832.8 1435.61  4870.5 1433.12  4900.2 1429.83  4905.8 1429.95
  4928.3 1426.92  4937.4 1424.46  4971.0 1406.54  4971.3 1406.04  4975.3 1406.04
  4975.6 1406.54  4981.9 1407.49  4990.2 1411.03  5001.4 1412.60  5063.2 1414.00
  5106.2 1412.65  5215.9 1413.08  5316.1 1417.07  5452.9 1424.52  5475.9 1426.35
#Mann=3,-1,0
  4592.3    0.12       0  4971.0    0.05       0  4975.6    0.12       0
Bank Sta=4971,4975.6
Exp/Cntr=0.3,0.1

Type RM Length L Ch R = 1,4282,483,483,483
BEGIN DESCRIPTION:
Stream0171_DS 9.0
END DESCRIPTION:
XS GIS Cut Line= 3
      2065875.00     13853975.01      2065875.00     13853675.00
      2065625.01     13853275.01
#Sta/Elev= 30
  4704.5 1431.63  4764.5 1423.96  4784.5 1420.38  4814.5 1415.91  4824.5 1414.99
  4894.5 1411.35  4944.5 1407.84  4954.5 1406.22  4964.5 1402.99  4972.2 1399.90
  4972.5 1399.40  4976.5 1399.40  4976.8 1399.90  4994.5 1401.97  5002.0 1406.08
  5007.5 1406.08  5012.2 1407.61  5039.9 1407.71  5048.7 1406.87  5091.2 1407.66
  5108.4 1407.42  5157.8 1406.41  5193.2 1407.14  5346.5 1414.64  5374.2 1416.39
  5381.9 1417.45  5405.7 1419.28  5410.8 1419.75  5432.0 1419.95  5476.2 1422.40
#Mann=5,-1,0
  4704.5    0.12       0  4972.2    0.05       0  4976.8    0.12       0
  5108.4    0.07       0  5405.7    0.12       0
Bank Sta=4972.2,4976.8
Exp/Cntr=0.3,0.1

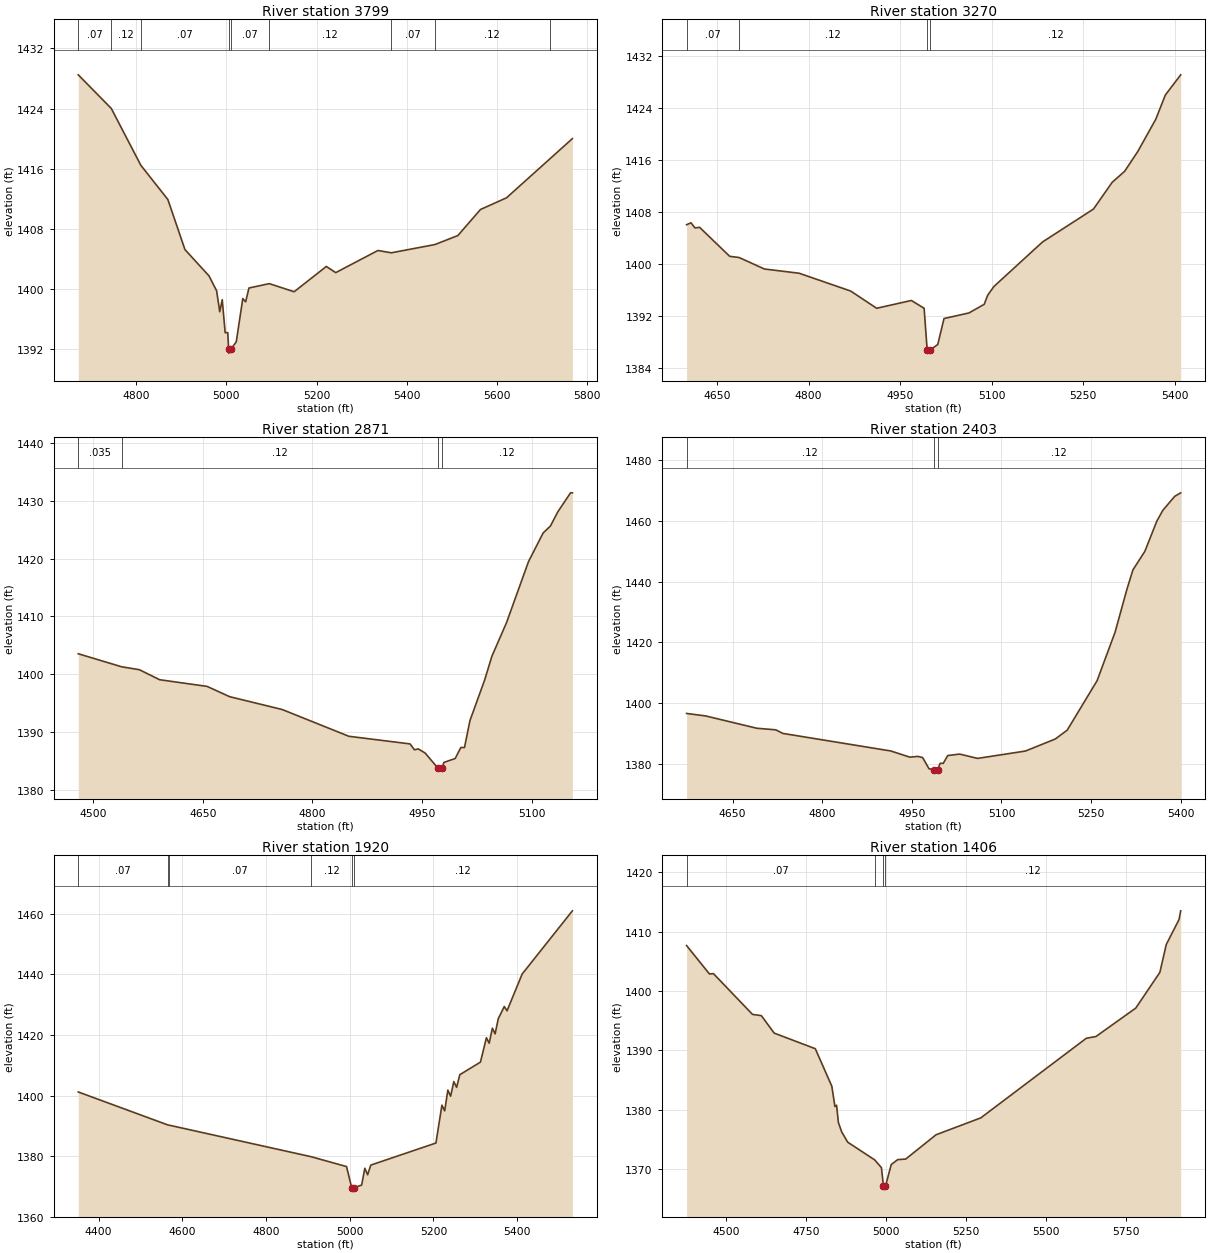
Type RM Length L Ch R = 1,3799,529,529,529
BEGIN DESCRIPTION:
Stream0171_DS 8.0
END DESCRIPTION:
XS GIS Cut Line= 3
      2066199.74     13854078.81      2066325.00     13853775.00
      2065862.97     13853162.17
#Sta/Elev= 30
  4671.4 1428.49  4744.7 1424.01  4810.3 1416.43  4870.2 1411.87  4908.1 1405.20
  4961.4 1401.70  4978.4 1399.70  4985.3 1396.91  4990.8 1398.52  4997.3 1394.13
  5003.1 1394.13  5005.0 1391.90  5005.3 1391.40  5009.7 1391.90  5021.9 1392.90
  5036.4 1398.67  5042.7 1398.24  5050.1 1400.08  5095.2 1400.66  5150.3 1399.58
  5221.7 1402.95  5242.6 1402.13  5336.2 1405.08  5365.9 1404.77  5462.6 1405.87
  5513.5 1407.07  5563.6 1410.54  5621.4 1412.10  5717.0 1417.26  5767.5 1419.99
#Mann=9,-1,0
  4671.4    0.07       0  4744.7    0.12       0  4810.3    0.07       0
  5005.0    0.05       0  5009.7    0.07       0  5095.2    0.12       0
  5365.9    0.07       0  5462.6    0.12       0  5717.0    0.07       0
Bank Sta=5005,5009.7
Exp/Cntr=0.3,0.1

Type RM Length L Ch R = 1,3270,399,399,399
BEGIN DESCRIPTION:
Stream0171_DS 7.0
END DESCRIPTION:
XS GIS Cut Line= 3
      2066524.97     13854025.03      2066793.50     13853721.16
      2066875.00     13853324.98
#Sta/Elev= 30
  4600.1 1406.02  4607.3 1406.32  4613.9 1405.53  4621.5 1405.62  4670.8 1401.16
  4686.2 1400.98  4727.7 1399.21  4784.6 1398.56  4869.1 1395.82  4911.7 1393.17
  4968.6 1394.37  4989.5 1393.17  4994.5 1386.77  4994.9 1386.27  4999.3 1386.27
  4999.7 1386.77  5011.9 1387.60  5022.1 1391.59  5063.0 1392.45  5088.0 1393.78
  5093.6 1395.16  5103.8 1396.51  5183.6 1403.37  5267.1 1408.43  5297.8 1412.55
  5318.2 1414.24  5339.7 1417.28  5369.2 1422.24  5384.9 1425.97  5410.1 1429.08
#Mann=4,-1,0
  4600.1    0.07       0  4686.2    0.12       0  4994.5    0.05       0
  4999.7    0.12       0
Bank Sta=4994.5,4999.7
Exp/Cntr=0.3,0.1

Type RM Length L Ch R = 1,2871,468,468,468
BEGIN DESCRIPTION:
Stream0171_DS 6.0
END DESCRIPTION:
XS GIS Cut Line= 3
      2067053.92     13854186.40      2067175.00     13853675.00
      2067175.00     13853525.03
#Sta/Elev= 30
  4479.8 1403.55  4539.0 1401.30  4563.4 1400.79  4591.1 1399.06  4655.9 1397.91
  4686.8 1396.13  4758.7 1393.91  4849.7 1389.29  4933.4 1387.97  4939.4 1386.95
  4944.5 1387.11  4954.0 1386.40  4971.6 1383.77  4972.1 1383.27  4977.0 1383.27
  4977.4 1383.77  4979.6 1384.77  4995.1 1385.45  5002.8 1387.35  5007.8 1387.35
  5015.3 1392.01  5035.3 1398.99  5045.3 1403.13  5065.3 1408.93  5095.3 1419.46
  5115.3 1424.41  5125.3 1425.62  5135.3 1428.05  5152.8 1431.35  5155.3 1431.35
#Mann=4,-1,0
  4479.8   0.035       0  4539.0    0.12       0  4971.6    0.05       0
  4977.4    0.12       0
Bank Sta=4971.6,4977.4
Exp/Cntr=0.3,0.1

Type RM Length L Ch R = 1,2403,483,483,483
BEGIN DESCRIPTION:
Stream0171_DS 5.0
END DESCRIPTION:
XS GIS Cut Line= 3
      2067475.00     13854125.01      2067625.00     13853725.00
      2067625.00     13853325.01
#Sta/Elev= 30
  4572.9 1396.62  4604.9 1395.80  4690.4 1391.75  4722.4 1391.22  4734.0 1390.05
  4914.7 1384.27  4946.7 1382.23  4960.1 1382.48  4968.1 1382.09  4978.7 1378.42
  4987.3 1378.13  4987.8 1377.63  4993.3 1378.13  4997.4 1380.20  5002.6 1380.20
  5010.1 1382.76  5030.1 1383.24  5060.1 1381.82  5140.1 1384.24  5190.1 1388.20
  5210.1 1391.12  5260.1 1407.40  5290.1 1423.29  5310.1 1437.52  5320.1 1443.88
  5340.1 1450.00  5360.1 1459.93  5370.1 1463.48  5390.1 1468.11  5400.1 1469.26
#Mann=3,-1,0
  4572.9    0.12       0  4987.3    0.05       0  4993.3    0.12       0
Bank Sta=4987.3,4993.3
Exp/Cntr=0.3,0.1

Type RM Length L Ch R = 1,1920,514,514,514
BEGIN DESCRIPTION:
Stream0171_DS 4.0
END DESCRIPTION:
XS GIS Cut Line= 3
      2067769.18     13854297.58      2068075.00     13853725.00
      2067725.03     13853325.03
#Sta/Elev= 30
  4351.3 1401.18  4566.2 1390.26  4568.6 1390.22  4907.8 1379.82  4992.3 1376.57
  5004.6 1369.63  5005.1 1369.13  5010.6 1369.63  5028.4 1370.47  5036.0 1376.01
  5042.7 1373.88  5050.3 1377.06  5205.9 1384.34  5220.2 1396.83  5226.8 1394.95
  5234.4 1401.80  5241.0 1399.78  5248.6 1404.60  5255.3 1402.70  5262.9 1406.87
  5312.2 1411.02  5326.5 1419.06  5333.1 1417.27  5340.7 1422.22  5347.3 1420.34
  5354.9 1425.36  5369.2 1429.36  5375.8 1427.95  5411.9 1440.08  5531.9 1460.93
#Mann=6,-1,0
  4351.3    0.07       0  4566.2    0.12       0  4568.6    0.07       0
  4907.8    0.12       0  5004.6    0.05       0  5010.6    0.12       0
Bank Sta=5004.6,5010.6
Exp/Cntr=0.3,0.1

Type RM Length L Ch R = 1,1406,421,421,421
BEGIN DESCRIPTION:
Stream0171_DS 3.0
END DESCRIPTION:
XS GIS Cut Line= 3
      2068349.05     13854464.21      2068512.25     13853853.11
      2068474.12     13852939.82
#Sta/Elev= 30
  4375.5 1407.65  4447.1 1402.86  4459.7 1402.91  4581.7 1396.05  4609.6 1395.83
  4649.7 1392.89  4778.4 1390.26  4830.1 1383.94  4839.8 1380.51  4845.0 1380.73
  4850.8 1377.79  4861.2 1376.22  4879.9 1374.50  4964.3 1371.52  4985.4 1370.21
  4991.8 1367.09  4992.3 1366.59  4998.1 1367.09  5016.1 1370.73  5036.2 1371.56
  5061.5 1371.66  5156.3 1375.75  5296.4 1378.60  5626.7 1392.02  5656.7 1392.31
  5781.5 1397.11  5856.9 1403.13  5876.9 1407.82  5916.9 1412.04  5922.1 1413.50
#Mann=4,-1,0
  4375.5    0.07       0  4964.3    0.12       0  4991.8    0.05       0
  4998.1    0.12       0
Bank Sta=4991.8,4998.1
Exp/Cntr=0.3,0.1

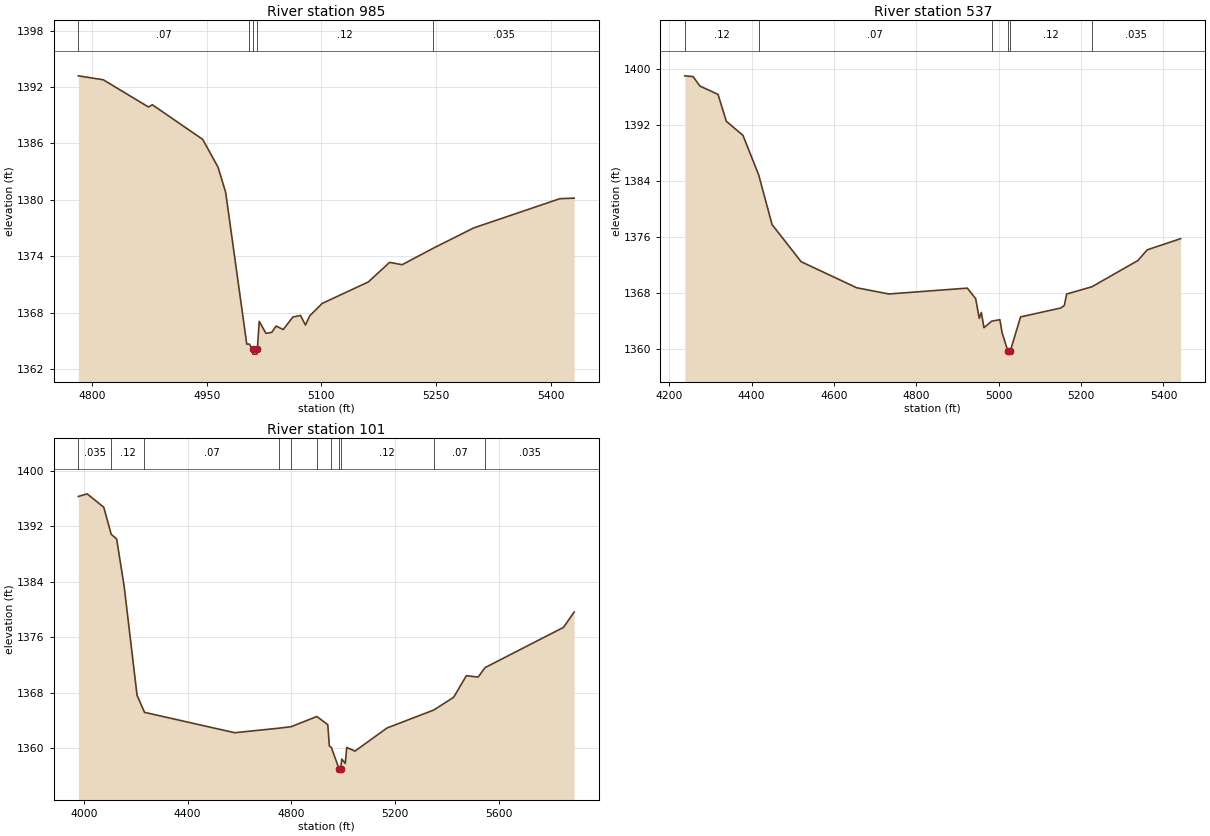
Type RM Length L Ch R = 1,985,448,448,448
BEGIN DESCRIPTION:
Stream0171_DS 2.0
END DESCRIPTION:
XS GIS Cut Line= 3
      2068883.78     13854047.58      2068875.00     13853825.00
      2068676.29     13853448.47
#Sta/Elev= 30
  4782.2 1393.20  4814.8 1392.78  4874.0 1389.88  4879.0 1390.12  4944.9 1386.43
  4964.9 1383.48  4974.9 1380.80  5002.5 1364.64  5005.9 1364.64  5010.0 1364.07
  5010.5 1363.57  5015.8 1363.57  5016.3 1364.07  5018.8 1367.06  5027.6 1365.78
  5035.2 1365.89  5040.8 1366.56  5050.2 1366.19  5062.8 1367.52  5072.8 1367.69
  5079.2 1366.67  5084.9 1367.65  5101.2 1368.97  5161.6 1371.26  5189.3 1373.34
  5205.7 1373.09  5246.3 1374.84  5299.4 1377.01  5412.0 1380.12  5430.7 1380.18
#Mann=5,-1,0
  4782.2    0.07       0  5005.9    0.12       0  5010.0    0.05       0
  5016.3    0.12       0  5246.3   0.035       0
Bank Sta=5010,5016.3
Exp/Cntr=0.3,0.1

Type RM Length L Ch R = 1,537,436,436,436
BEGIN DESCRIPTION:
Stream0171_DS 1.0
END DESCRIPTION:
XS GIS Cut Line= 3
      2069175.00     13854425.01      2069275.00     13853675.00
      2068874.97     13853474.98
#Sta/Elev= 30
  4237.7 1399.04  4257.9 1398.93  4274.3 1397.58  4318.4 1396.38  4338.6 1392.53
  4378.9 1390.52  4417.2 1384.84  4449.6 1377.75  4520.2 1372.43  4655.1 1368.70
  4733.3 1367.81  4923.7 1368.65  4943.9 1367.15  4952.7 1364.32  4957.8 1365.16
  4964.1 1362.99  4983.0 1363.92  5002.7 1364.13  5008.3 1362.22  5021.9 1359.70
  5022.4 1359.20  5028.3 1359.70  5053.0 1364.53  5150.9 1365.81  5159.3 1366.17
  5164.8 1367.80  5226.5 1368.85  5338.1 1372.61  5360.5 1374.13  5441.6 1375.73
#Mann=6,-1,0
  4237.7    0.12       0  4417.2    0.07       0  4983.0    0.12       0
  5021.9    0.05       0  5028.3    0.12       0  5226.5   0.035       0
Bank Sta=5021.9,5028.3
Exp/Cntr=0.3,0.1

Type RM Length L Ch R = 1,101,0,0,0
BEGIN DESCRIPTION:
Stream0171_DS 0.0
END DESCRIPTION:
XS GIS Cut Line= 5
      2069266.92     13854453.93      2069651.75     13853967.90
      2069697.29     13853669.07      2069679.49     13853577.98
      2068904.71     13853129.39
#Sta/Elev= 30
  3979.0 1396.28  4012.8 1396.66  4077.0 1394.73  4105.6 1390.83  4126.6 1390.15
  4155.5 1383.35  4205.2 1367.63  4233.9 1365.16  4581.7 1362.22  4750.3 1362.87
  4799.1 1363.09  4898.1 1364.56  4940.1 1363.38  4946.1 1360.32  4953.8 1360.10
  4983.4 1357.04  4983.9 1356.54  4989.8 1357.04  4994.0 1358.43  5007.5 1357.80
  5013.2 1360.10  5044.8 1359.57  5168.2 1362.90  5348.2 1365.49  5425.0 1367.33
  5473.9 1370.44  5519.2 1370.24  5546.1 1371.61  5848.3 1377.41  5889.3 1379.62
#Mann=11,-1,0
  3979.0   0.035       0  4105.6    0.12       0  4233.9    0.07       0
  4750.3   0.035       0  4799.1    0.07       0  4898.1   0.035       0
  4953.8    0.12       0  4983.4    0.05       0  4989.8    0.12       0
  5348.2    0.07       0  5546.1   0.035       0
Bank Sta=4983.4,4989.8
Exp/Cntr=0.3,0.1

Chan Stop Cuts=-1