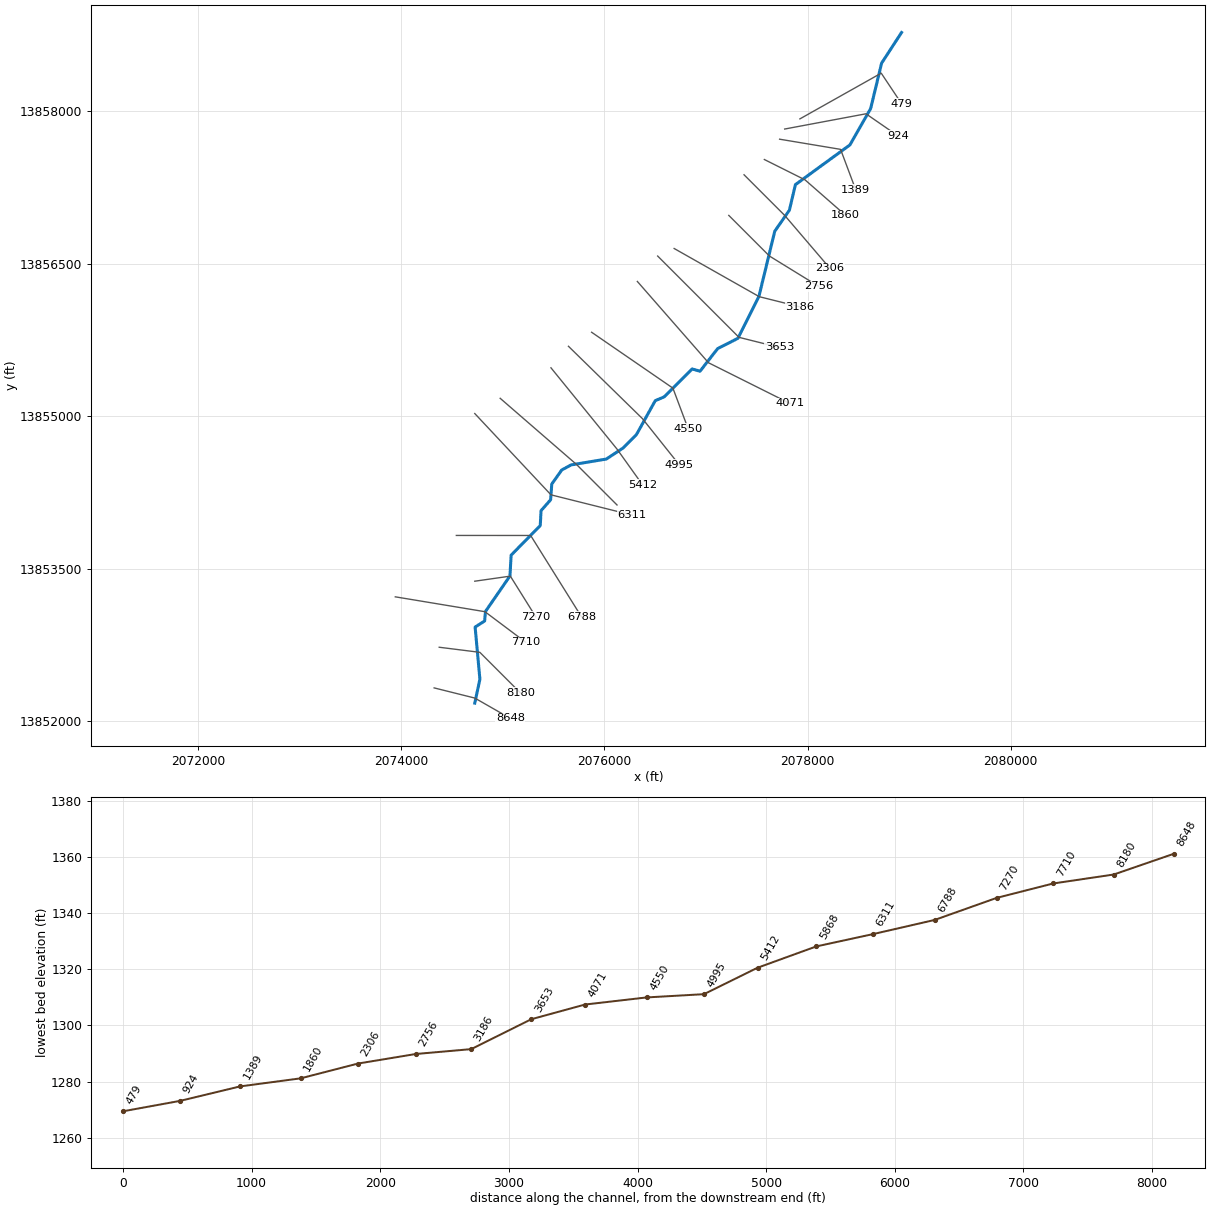
--- Stream0172_DS.prj (project) ---

Proj Title=Stream0172_DS Base Level Engineering
Current Plan=p01
Default Exp/Contr=0.3,0.1
English Units
Geom File=g01
Flow File=f01
Plan File=p01
BEGIN DESCRIPTION:
Stream0172_DS
END DESCRIPTION:

--- Stream0172_DS.p01 (plan) ---

Plan Title=Multiple Run
Short Identifier=Multiple
Geom File=g01
Flow File=f01
Subcritical Flow
K Sum by GR= 0
Std Step Tol= 0.01
Critical Tol= 0.01
Num of Std Step Trials= 20
Max Error Tol= 0.3
Flow Tol Ratio= 0.001
Split Flow NTrial= 30
Split Flow Tol= 0.02
Split Flow Ratio= 0.02
Log Output Level= 0
Friction Slope Method= 1
Unsteady Friction Slope Method= 2
Unsteady Bridges Friction Slope Method= 1
Parabolic Critical Depth
Global Vel Dist=  1 , 1 , 1
Global Log Level= 0
CheckData=True
Encroach Param= -1, 0, 0, 0
BEGIN DESCRIPTION:
Multiple Run
END DESCRIPTION:

--- Stream0172_DS.f01 (steady flow) ---

Flow Title=Multiple
Number of Profiles=7
Profile Names=10-year,25-year,50-year,1pct_min,100-year,1pct_plu,500-year
River Rch & RM= Stream0172_DS,Reach-1,8648
    1571    2694    3777    2563    5113   10202    9269
River Rch & RM= Stream0172_DS,Reach-1,5412
    2193    3829    5430    3724    7430   14825   13763
River Rch & RM= Stream0172_DS,Reach-1,3653
    2612    4593    6545    4506    8991   17939   16790
Boundary for River Rch & Prof#=Stream0172_DS,Reach-1,1
Up Type=0
Dn Type=3
Dn Slope=0.005
Boundary for River Rch & Prof#=Stream0172_DS,Reach-1,2
Up Type=0
Dn Type=3
Dn Slope=0.005
Boundary for River Rch & Prof#=Stream0172_DS,Reach-1,3
Up Type=0
Dn Type=3
Dn Slope=0.005
Boundary for River Rch & Prof#=Stream0172_DS,Reach-1,4
Up Type=0
Dn Type=3
Dn Slope=0.005
Boundary for River Rch & Prof#=Stream0172_DS,Reach-1,5
Up Type=0
Dn Type=3
Dn Slope=0.005
Boundary for River Rch & Prof#=Stream0172_DS,Reach-1,6
Up Type=0
Dn Type=3
Dn Slope=0.005
Boundary for River Rch & Prof#=Stream0172_DS,Reach-1,7
Up Type=0
Dn Type=3
Dn Slope=0.005

--- Stream0172_DS.g01 (geometry) ---

Geom Title=Existing Conditions

River Reach=Stream0172_DS,Reach-1
Reach XY= 30
      2074725.00     13852175.00      2074775.43     13852409.82
      2074728.48     13852923.74      2074821.81     13852983.35
      2074830.56     13853077.36      2075071.25     13853426.55
      2075082.81     13853631.19      2075369.53     13853922.55
      2075377.08     13854069.14      2075471.44     13854176.47
      2075482.83     13854331.19      2075580.61     13854469.41
      2075672.62     13854519.30      2076019.14     13854577.07
      2076184.68     13854685.78      2076316.86     13854818.94
      2076501.49     13855152.01      2076588.21     13855188.63
      2076865.00     13855463.76      2076941.70     13855441.38
      2077115.30     13855664.24      2077314.35     13855765.00
      2077521.17     13856176.58      2077677.25     13856819.07
      2077821.38     13857026.50      2077880.42     13857277.67
      2078416.96     13857668.67      2078621.17     13858026.58
      2078728.82     13858473.42      2078925.00     13858775.00

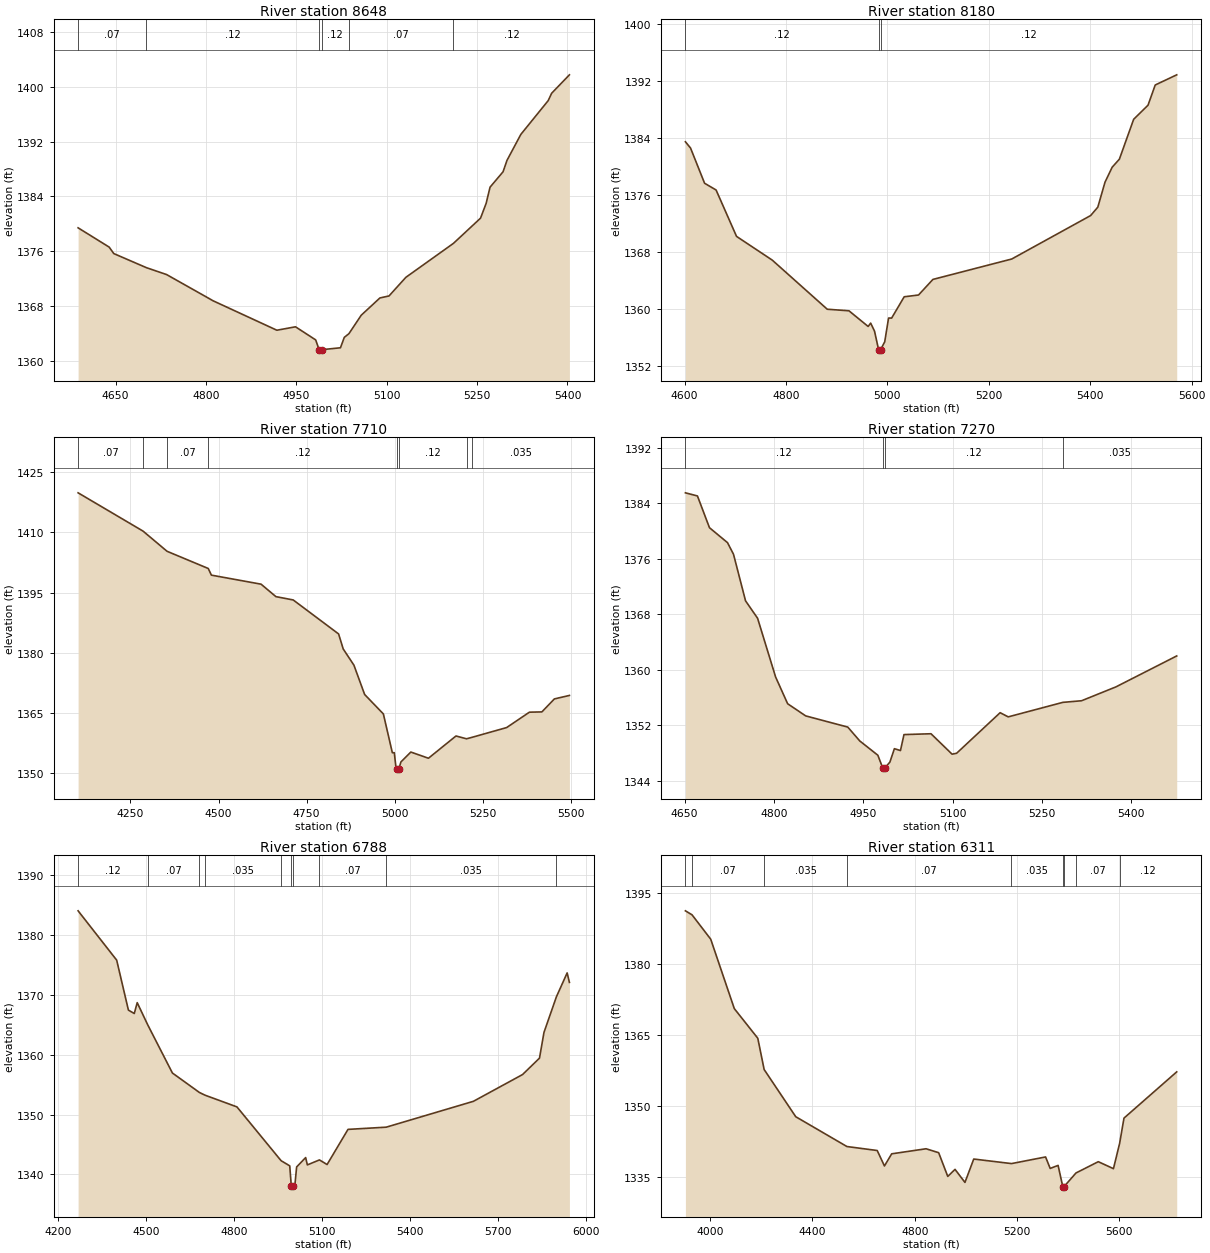
Type RM Length L Ch R = 1,8648,468,468,468
BEGIN DESCRIPTION:
Stream0172_DS 19.0
END DESCRIPTION:
XS GIS Cut Line= 3
      2074324.99     13852325.00      2074725.00     13852225.00
      2075074.97     13852025.02
#Sta/Elev= 30
  4587.8 1379.43  4639.3 1376.62  4647.1 1375.67  4701.1 1373.62  4734.7 1372.61
  4812.0 1368.78  4917.7 1364.49  4948.6 1364.99  4982.1 1363.08  4987.8 1361.65
  4988.1 1361.15  4991.6 1361.15  4991.8 1361.65  5023.2 1361.93  5029.6 1363.45
  5037.3 1363.99  5057.7 1366.68  5088.7 1369.20  5103.8 1369.49  5131.8 1372.21
  5210.7 1377.16  5255.7 1380.84  5265.0 1383.00  5271.5 1385.36  5293.1 1387.61
  5299.6 1389.27  5322.6 1393.06  5368.0 1397.99  5373.7 1399.06  5403.2 1401.75
#Mann=6,-1,0
  4587.8    0.07       0  4701.1    0.12       0  4987.8    0.05       0
  4991.8    0.12       0  5037.3    0.07       0  5210.7    0.12       0
Bank Sta=4987.8,4991.8
Exp/Cntr=0.3,0.1

Type RM Length L Ch R = 1,8180,470,470,470
BEGIN DESCRIPTION:
Stream0172_DS 18.0
END DESCRIPTION:
XS GIS Cut Line= 3
      2074375.00     13852725.00      2074775.00     13852675.00
      2075175.00     13852275.00
#Sta/Elev= 30
  4601.8 1383.46  4611.9 1382.58  4639.6 1377.63  4662.3 1376.68  4702.6 1370.16
  4773.1 1366.82  4881.5 1359.92  4924.3 1359.70  4962.1 1357.50  4967.1 1357.97
  4974.7 1356.84  4982.7 1354.25  4983.0 1353.75  4986.8 1354.25  4994.8 1355.34
  5002.4 1358.68  5008.5 1358.68  5033.2 1361.67  5061.5 1361.92  5089.8 1364.11
  5245.3 1366.98  5400.9 1373.09  5415.0 1374.27  5429.2 1377.78  5443.3 1379.88
  5457.5 1381.01  5485.7 1386.62  5514.0 1388.60  5528.2 1391.44  5570.6 1392.87
#Mann=3,-1,0
  4601.8    0.12       0  4982.7    0.05       0  4986.8    0.12       0
Bank Sta=4982.7,4986.8
Exp/Cntr=0.3,0.1

Type RM Length L Ch R = 1,7710,440,440,440
BEGIN DESCRIPTION:
Stream0172_DS 17.0
END DESCRIPTION:
XS GIS Cut Line= 3
      2073942.80     13853221.16      2074825.00     13853075.00
      2075224.98     13852775.01
#Sta/Elev= 30
  4101.6 1419.87  4286.0 1410.33  4354.0 1405.31  4470.9 1401.03  4479.9 1399.37
  4620.8 1397.12  4662.9 1394.02  4712.0 1393.19  4840.8 1384.73  4853.9 1380.99
  4884.3 1376.95  4914.7 1369.65  4967.9 1364.80  4993.3 1355.15  4998.9 1355.15
  5003.1 1351.85  5007.3 1351.06  5007.6 1350.56  5011.5 1351.06  5017.7 1352.85
  5045.8 1355.31  5095.8 1353.77  5173.9 1359.31  5203.9 1358.61  5219.2 1358.97
  5317.7 1361.41  5382.3 1365.24  5417.7 1365.31  5453.1 1368.54  5495.8 1369.41
#Mann=8,-1,0
  4101.6    0.07       0  4286.0    0.12       0  4354.0    0.07       0
  4470.9    0.12       0  5007.3    0.05       0  5011.5    0.12       0
  5203.9    0.07       0  5219.2   0.035       0
Bank Sta=5007.3,5011.5
Exp/Cntr=0.3,0.1

Type RM Length L Ch R = 1,7270,482,482,482
BEGIN DESCRIPTION:
Stream0172_DS 16.0
END DESCRIPTION:
XS GIS Cut Line= 3
      2074725.02     13853375.00      2075075.00     13853425.00
      2075324.99     13853025.02
#Sta/Elev= 30
  4651.4 1385.48  4671.6 1385.03  4691.8 1380.46  4722.1 1378.31  4732.2 1376.63
  4752.4 1369.93  4772.6 1367.43  4802.9 1358.97  4823.1 1355.12  4853.4 1353.37
  4924.1 1351.76  4944.3 1349.76  4974.6 1347.71  4982.6 1345.92  4982.9 1345.42
  4986.6 1345.42  4986.8 1345.92  4994.8 1346.71  5002.4 1348.65  5012.6 1348.38
  5018.5 1350.68  5063.9 1350.80  5099.3 1347.86  5106.9 1347.99  5180.0 1353.83
  5193.6 1353.23  5285.4 1355.32  5316.8 1355.55  5374.6 1357.55  5476.6 1362.00
#Mann=4,-1,0
  4651.4    0.12       0  4982.6    0.05       0  4986.8    0.12       0
  5285.4   0.035       0
Bank Sta=4982.6,4986.8
Exp/Cntr=0.3,0.1

Type RM Length L Ch R = 1,6788,477,477,477
BEGIN DESCRIPTION:
Stream0172_DS 15.0
END DESCRIPTION:
XS GIS Cut Line= 3
      2074543.53     13853825.33      2075275.00     13853825.00
      2075775.02     13853024.97
#Sta/Elev= 30
  4268.5 1383.96  4400.0 1375.74  4440.0 1367.41  4460.0 1366.84  4470.0 1368.65
  4506.2 1364.92  4590.0 1356.92  4682.2 1353.67  4701.3 1353.22  4810.0 1351.27
  4960.5 1342.30  4990.0 1341.44  4995.3 1338.06  4995.6 1337.56  4999.6 1338.06
  5007.6 1338.30  5013.5 1341.26  5044.2 1342.82  5050.1 1341.60  5091.3 1342.43
  5117.3 1341.66  5188.6 1347.52  5319.0 1347.89  5616.1 1352.20  5783.6 1356.66
  5841.4 1359.40  5856.7 1363.69  5899.0 1369.62  5935.7 1373.61  5943.4 1372.03
#Mann=10,-1,0
  4268.5    0.12       0  4506.2    0.07       0  4682.2    0.12       0
  4701.3   0.035       0  4960.5    0.12       0  4995.3   0.035       0
  4999.6    0.12       0  5091.3    0.07       0  5319.0   0.035       0
  5899.0    0.12       0
Bank Sta=4995.3,4999.6
Exp/Cntr=0.3,0.1

Type RM Length L Ch R = 1,6311,443,443,443
BEGIN DESCRIPTION:
Stream0172_DS 14.0
END DESCRIPTION:
XS GIS Cut Line= 3
      2074725.03     13855024.97      2075475.00     13854225.00
      2076275.04     13854024.99
#Sta/Elev= 30
  3903.1 1391.28  3928.9 1390.44  4002.0 1385.30  4094.3 1370.64  4186.1 1364.39
  4211.0 1357.78  4334.6 1347.82  4534.7 1341.53  4653.1 1340.69  4681.4 1337.43
  4709.7 1339.99  4844.1 1341.06  4893.4 1340.23  4929.0 1335.22  4957.4 1336.71
  4996.2 1333.96  5030.6 1338.89  5178.2 1337.93  5311.5 1339.33  5329.5 1336.91
  5360.4 1337.55  5378.9 1333.04  5379.2 1332.54  5383.2 1333.04  5430.4 1335.95
  5517.6 1338.33  5576.9 1336.86  5601.2 1342.24  5618.1 1347.53  5824.3 1357.29
#Mann=9,-1,0
  3903.1   0.035       0  3928.9    0.07       0  4211.0   0.035       0
  4534.7    0.07       0  5178.2   0.035       0  5378.9    0.05       0
  5383.2   0.035       0  5430.4    0.07       0  5601.2    0.12       0
Bank Sta=5378.9,5383.2
Exp/Cntr=0.3,0.1

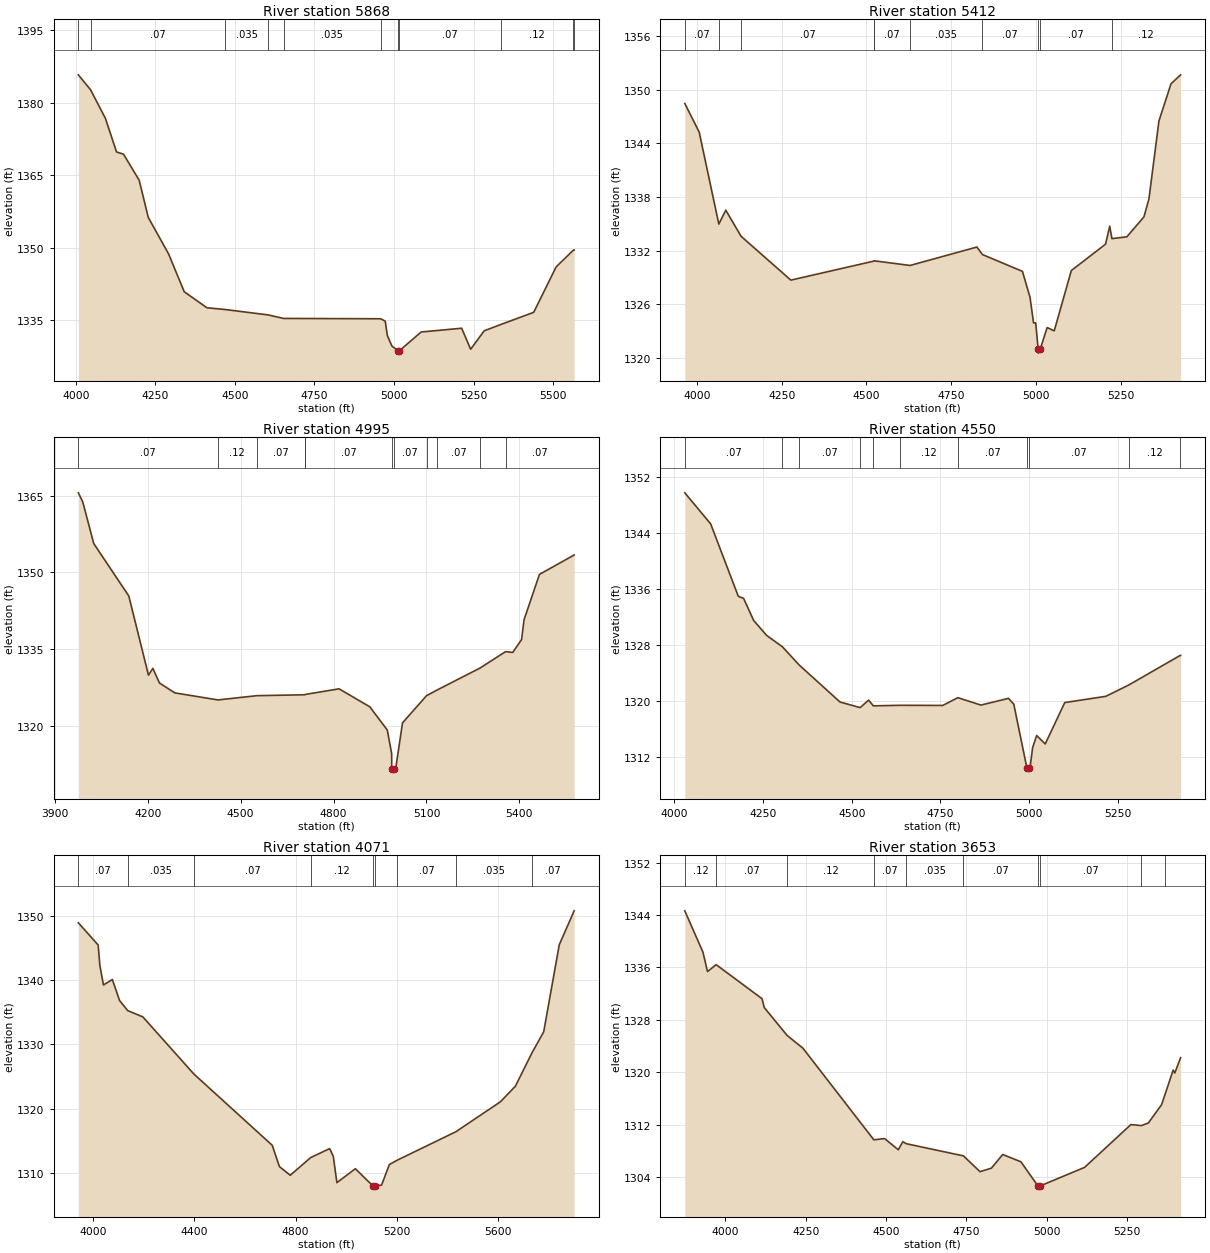
Type RM Length L Ch R = 1,5868,456,456,456
BEGIN DESCRIPTION:
Stream0172_DS 13.0
END DESCRIPTION:
XS GIS Cut Line= 3
      2074975.02     13855174.99      2075725.00     13854525.00
      2076124.98     13854125.02
#Sta/Elev= 30
  4008.0 1385.81  4046.4 1382.72  4093.0 1376.80  4128.1 1369.82  4150.0 1369.37
  4199.3 1363.95  4227.8 1356.25  4291.5 1348.71  4340.8 1340.85  4412.1 1337.53
  4469.3 1337.17  4604.5 1336.05  4652.8 1335.32  4958.3 1335.25  4972.5 1334.75
  4979.1 1331.77  4993.3 1329.62  5012.1 1328.63  5012.5 1328.13  5017.0 1328.63
  5085.3 1332.51  5212.6 1333.29  5240.9 1328.94  5283.3 1332.75  5335.0 1334.05
  5438.9 1336.58  5509.6 1346.01  5564.0 1349.50  5565.7 1349.50  5566.1 1349.50
#Mann=11,-1,0
  4008.0    0.12       0  4046.4    0.07       0  4469.3   0.035       0
  4604.5    0.07       0  4652.8   0.035       0  4958.3    0.07       0
  5012.1    0.05       0  5017.0    0.07       0  5335.0    0.12       0
  5564.0    0.07       0  5565.7    0.12       0
Bank Sta=5012.1,5017
Exp/Cntr=0.3,0.1

Type RM Length L Ch R = 1,5412,417,417,417
BEGIN DESCRIPTION:
Stream0172_DS 12.0
END DESCRIPTION:
XS GIS Cut Line= 3
      2075474.99     13855475.01      2076125.00     13854675.00
      2076375.00     13854325.01
#Sta/Elev= 30
  3964.7 1348.45  4007.1 1345.25  4065.0 1334.96  4085.4 1336.52  4130.6 1333.60
  4277.2 1328.70  4521.1 1330.82  4522.5 1330.86  4628.5 1330.34  4825.3 1332.40
  4841.6 1331.56  4959.6 1329.68  4981.9 1326.77  4992.3 1323.92  4998.6 1323.92
  5005.7 1321.04  5006.2 1320.54  5012.4 1321.04  5032.4 1323.40  5053.2 1323.03
  5103.6 1329.77  5204.4 1332.72  5216.7 1334.73  5223.2 1333.34  5267.1 1333.54
  5317.5 1335.77  5332.2 1337.76  5361.7 1346.49  5397.3 1350.65  5425.6 1351.65
#Mann=10,-1,0
  3964.7    0.07       0  4065.0   0.035       0  4130.6    0.07       0
  4521.1   0.035       0  4522.5    0.07       0  4628.5   0.035       0
  4841.6    0.07       0  5005.7    0.05       0  5012.4    0.07       0
  5223.2    0.12       0
Bank Sta=5005.7,5012.4
Exp/Cntr=0.3,0.1

Type RM Length L Ch R = 1,4995,445,445,445
BEGIN DESCRIPTION:
Stream0172_DS 11.0
END DESCRIPTION:
XS GIS Cut Line= 3
      2075646.81     13855687.06      2076375.00     13854975.00
      2076737.83     13854519.91
#Sta/Elev= 30
  3976.2 1365.53  3990.5 1363.76  4025.9 1355.62  4139.1 1345.36  4202.6 1329.89
  4216.8 1331.21  4238.1 1328.35  4287.5 1326.42  4426.9 1325.04  4552.2 1325.87
  4706.6 1326.05  4709.4 1326.12  4817.9 1327.21  4916.9 1323.70  4973.5 1319.16
  4987.6 1314.53  4987.8 1311.62  4988.3 1311.12  4994.5 1311.62  5001.9 1312.14
  5022.7 1320.56  5100.2 1325.87  5135.4 1327.01  5272.8 1331.27  5355.2 1334.48
  5378.4 1334.32  5407.0 1336.84  5415.0 1340.72  5464.7 1349.58  5576.7 1353.38
#Mann=11,-1,0
  3976.2    0.07       0  4426.9    0.12       0  4552.2    0.07       0
  4706.6   0.035       0  4709.4    0.07       0  4987.8    0.05       0
  4994.5    0.07       0  5100.2    0.12       0  5135.4    0.07       0
  5272.8    0.12       0  5355.2    0.07       0
Bank Sta=4987.8,4994.5
Exp/Cntr=0.3,0.1

Type RM Length L Ch R = 1,4550,479,479,479
BEGIN DESCRIPTION:
Stream0172_DS 10.0
END DESCRIPTION:
XS GIS Cut Line= 3
      2075874.96     13855825.03      2076675.00     13855275.00
      2076825.01     13854874.97
#Sta/Elev= 30
  4029.1 1349.70  4102.0 1345.27  4180.0 1334.92  4194.9 1334.63  4223.3 1331.47
  4259.7 1329.35  4304.2 1327.72  4351.9 1325.10  4466.8 1319.83  4523.6 1319.03
  4547.4 1320.10  4560.8 1319.28  4636.7 1319.36  4756.4 1319.34  4799.1 1320.45
  4864.0 1319.39  4941.8 1320.35  4956.7 1319.53  4993.6 1310.46  4994.1 1309.96
  5000.3 1310.46  5002.6 1310.46  5009.8 1313.30  5021.3 1315.05  5045.4 1313.84
  5100.5 1319.75  5216.2 1320.64  5280.7 1322.25  5426.0 1326.48  5427.2 1326.48
#Mann=11,-1,0
  4029.1    0.07       0  4304.2   0.035       0  4351.9    0.07       0
  4523.6    0.12       0  4560.8    0.07       0  4636.7    0.12       0
  4799.1    0.07       0  4993.6    0.05       0  5000.3    0.07       0
  5280.7    0.12       0  5426.0    0.07       0
Bank Sta=4993.6,5000.3
Exp/Cntr=0.3,0.1

Type RM Length L Ch R = 1,4071,418,418,418
BEGIN DESCRIPTION:
Stream0172_DS 9.0
END DESCRIPTION:
XS GIS Cut Line= 3
      2076325.03     13856324.97      2077025.00     13855525.00
      2077825.00     13855125.00
#Sta/Elev= 30
  3942.0 1348.96  4020.3 1345.49  4026.9 1342.34  4041.1 1339.26  4076.3 1340.11
  4104.7 1336.85  4137.0 1335.26  4196.8 1334.28  4398.3 1325.37  4707.4 1314.27
  4735.9 1310.94  4778.6 1309.59  4859.7 1312.36  4934.3 1313.75  4948.5 1312.55
  4962.7 1308.44  5035.7 1310.61  5105.0 1307.93  5105.5 1307.43  5111.8 1307.93
  5139.1 1308.06  5169.9 1311.26  5199.9 1311.92  5433.0 1316.39  5608.7 1321.06
  5667.4 1323.48  5733.1 1328.69  5779.2 1331.96  5840.7 1345.54  5899.4 1350.82
#Mann=9,-1,0
  3942.0    0.07       0  4137.0   0.035       0  4398.3    0.07       0
  4859.7    0.12       0  5105.0    0.05       0  5111.8    0.12       0
  5199.9    0.07       0  5433.0   0.035       0  5733.1    0.07       0
Bank Sta=5105,5111.8
Exp/Cntr=0.3,0.1

Type RM Length L Ch R = 1,3653,467,467,467
BEGIN DESCRIPTION:
Stream0172_DS 8.0
END DESCRIPTION:
XS GIS Cut Line= 3
      2076525.01     13856574.99      2077325.00     13855775.00
      2077725.04     13855674.99
#Sta/Elev= 30
  3873.3 1344.64  3929.8 1338.34  3944.0 1335.37  3970.9 1336.43  4113.7 1331.24
  4120.8 1329.88  4191.9 1325.63  4241.0 1323.69  4461.9 1309.71  4495.5 1309.90
  4538.0 1308.19  4552.1 1309.43  4562.8 1309.12  4740.8 1307.26  4792.5 1304.85
  4827.9 1305.39  4863.2 1307.47  4919.8 1306.36  4972.5 1302.69  4973.0 1302.19
  4980.2 1302.69  5118.0 1305.51  5262.3 1312.04  5294.8 1311.88  5316.5 1312.28
  5357.7 1315.07  5369.8 1316.82  5393.8 1320.35  5398.9 1319.90  5417.0 1322.24
#Mann=10,-1,0
  3873.3    0.12       0  3970.9    0.07       0  4191.9    0.12       0
  4461.9    0.07       0  4562.8   0.035       0  4740.8    0.07       0
  4972.5    0.05       0  4980.2    0.07       0  5294.8   0.035       0
  5369.8    0.07       0
Bank Sta=4972.5,4980.2
Exp/Cntr=0.3,0.1

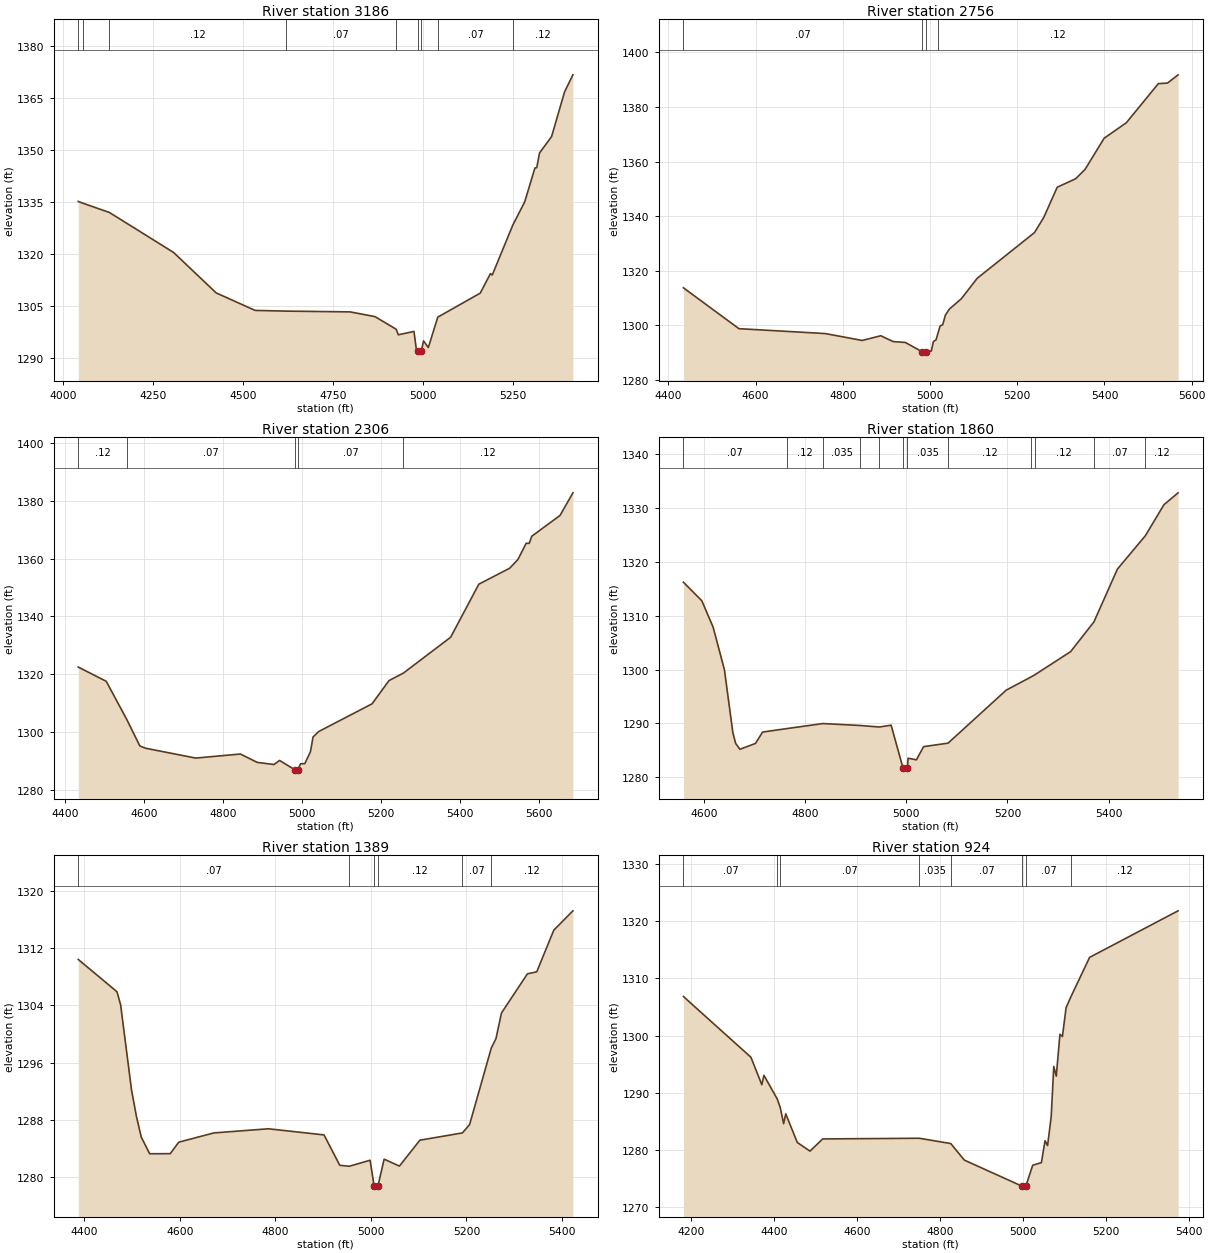
Type RM Length L Ch R = 1,3186,430,430,430
BEGIN DESCRIPTION:
Stream0172_DS 7.0
END DESCRIPTION:
XS GIS Cut Line= 3
      2076687.06     13856649.38      2077525.00     13856175.00
      2077924.99     13856075.00
#Sta/Elev= 30
  4041.3 1335.29  4053.8 1334.79  4127.9 1332.11  4306.4 1320.57  4424.8 1308.90
  4533.1 1303.86  4618.3 1303.66  4797.4 1303.43  4866.3 1302.07  4924.9 1298.45
  4931.3 1296.82  4974.6 1297.81  4981.2 1292.64  4986.4 1292.04  4986.9 1291.54
  4994.6 1292.04  5001.3 1295.07  5014.5 1293.15  5040.8 1301.92  5158.8 1308.84
  5187.2 1314.47  5192.3 1314.08  5249.5 1328.49  5282.5 1335.18  5310.9 1344.94
  5316.0 1345.06  5323.7 1349.28  5357.2 1354.00  5393.3 1366.89  5416.5 1371.81
#Mann=9,-1,0
  4041.3   0.035       0  4053.8    0.07       0  4127.9    0.12       0
  4618.3    0.07       0  4924.9    0.12       0  4986.4    0.05       0
  4994.6    0.12       0  5040.8    0.07       0  5249.5    0.12       0
Bank Sta=4986.4,4994.6
Exp/Cntr=0.3,0.1

Type RM Length L Ch R = 1,2756,450,450,450
BEGIN DESCRIPTION:
Stream0172_DS 6.0
END DESCRIPTION:
XS GIS Cut Line= 3
      2077224.99     13856975.01      2077625.00     13856575.00
      2078109.44     13856276.73
#Sta/Elev= 30
  4434.3 1313.74  4561.6 1298.77  4759.6 1296.98  4844.4 1294.45  4886.9 1296.18
  4915.1 1294.05  4943.4 1293.72  4981.8 1290.31  4982.3 1289.81  4990.0 1290.31
  5002.9 1290.58  5007.7 1294.07  5013.6 1294.64  5018.8 1297.45  5023.1 1299.78
  5029.0 1300.19  5035.2 1303.75  5044.4 1305.96  5071.5 1309.70  5108.2 1317.23
  5239.6 1333.98  5260.9 1339.56  5291.7 1350.60  5333.8 1353.68  5355.5 1357.11
  5399.3 1368.54  5450.2 1374.21  5523.6 1388.54  5544.8 1388.76  5568.9 1391.77
#Mann=4,-1,0
  4434.3    0.07       0  4981.8    0.05       0  4990.0    0.07       0
  5018.8    0.12       0
Bank Sta=4981.8,4990
Exp/Cntr=0.3,0.1

Type RM Length L Ch R = 1,2306,446,446,446
BEGIN DESCRIPTION:
Stream0172_DS 5.0
END DESCRIPTION:
XS GIS Cut Line= 3
      2077375.01     13857374.99      2077775.00     13856975.00
      2078220.27     13856454.17
#Sta/Elev= 30
  4434.3 1322.45  4505.0 1317.53  4556.7 1304.37  4589.9 1295.15  4604.0 1294.35
  4731.3 1290.92  4844.4 1292.33  4886.8 1289.43  4929.3 1288.70  4943.4 1290.10
  4981.7 1286.90  4982.2 1286.40  4990.0 1286.90  4996.4 1288.96  5007.1 1288.98
  5021.4 1293.10  5028.0 1298.21  5042.2 1300.11  5177.3 1309.73  5220.1 1317.77
  5256.5 1320.37  5376.0 1332.79  5447.3 1351.18  5525.3 1356.71  5546.1 1359.72
  5567.0 1365.35  5574.7 1365.33  5581.2 1367.80  5652.6 1374.99  5685.2 1382.83
#Mann=5,-1,0
  4434.3    0.12       0  4556.7    0.07       0  4981.7    0.05       0
  4990.0    0.07       0  5256.5    0.12       0
Bank Sta=4981.7,4990
Exp/Cntr=0.3,0.1

Type RM Length L Ch R = 1,1860,471,471,471
BEGIN DESCRIPTION:
Stream0172_DS 4.0
END DESCRIPTION:
XS GIS Cut Line= 3
      2077574.98     13857525.01      2077975.00     13857325.00
      2078374.96     13856975.03
#Sta/Elev= 30
  4558.9 1316.24  4595.3 1312.79  4617.6 1307.90  4640.0 1299.97  4656.8 1288.21
  4662.3 1286.27  4670.7 1285.19  4701.5 1286.28  4715.5 1288.39  4763.9 1289.04
  4834.8 1289.97  4908.5 1289.61  4946.7 1289.33  4969.8 1289.67  4993.6 1281.63
  4994.1 1281.13  5002.0 1281.63  5003.3 1283.53  5019.9 1283.23  5034.1 1285.68
  5082.5 1286.33  5197.4 1296.17  5246.8 1298.64  5254.0 1299.02  5325.0 1303.34
  5371.1 1308.86  5417.6 1318.68  5472.9 1324.88  5509.6 1330.64  5537.6 1332.85
#Mann=12,-1,0
  4558.9    0.07       0  4763.9    0.12       0  4834.8   0.035       0
  4908.5    0.07       0  4946.7   0.035       0  4993.6   0.035       0
  5002.0   0.035       0  5082.5    0.12       0  5246.8   0.035       0
  5254.0    0.12       0  5371.1    0.07       0  5472.9    0.12       0
Bank Sta=4993.6,5002
Exp/Cntr=0.3,0.1

Type RM Length L Ch R = 1,1389,465,465,465
BEGIN DESCRIPTION:
Stream0172_DS 3.0
END DESCRIPTION:
XS GIS Cut Line= 3
      2077725.01     13857725.00      2078325.00     13857625.00
      2078475.01     13857224.97
#Sta/Elev= 30
  4387.4 1310.45  4468.5 1305.92  4476.1 1304.08  4498.9 1292.15  4509.0 1288.50
  4519.2 1285.56  4536.9 1283.21  4580.0 1283.22  4597.7 1284.83  4671.2 1286.13
  4785.3 1286.71  4901.9 1285.85  4934.8 1281.59  4954.9 1281.46  4998.3 1282.30
  5006.6 1278.75  5007.1 1278.25  5015.0 1278.75  5027.7 1282.45  5059.7 1281.48
  5102.5 1285.11  5191.5 1286.13  5206.6 1287.30  5252.1 1298.05  5261.8 1299.35
  5273.3 1302.94  5327.6 1308.43  5347.2 1308.72  5382.8 1314.55  5422.9 1317.27
#Mann=6,-1,0
  4387.4    0.07       0  4954.9    0.12       0  5006.6    0.05       0
  5015.0    0.12       0  5191.5    0.07       0  5252.1    0.12       0
Bank Sta=5006.6,5015
Exp/Cntr=0.3,0.1

Type RM Length L Ch R = 1,924,445,445,445
BEGIN DESCRIPTION:
Stream0172_DS 2.0
END DESCRIPTION:
XS GIS Cut Line= 3
      2077775.04     13857825.01      2078575.00     13857975.00
      2078886.78     13857759.68
#Sta/Elev= 30
  4181.4 1306.84  4344.1 1296.21  4370.4 1291.40  4375.5 1293.04  4407.6 1288.90
  4414.7 1287.43  4423.0 1284.57  4428.1 1286.29  4456.1 1281.27  4486.6 1279.77
  4517.1 1281.90  4750.3 1282.02  4826.1 1281.09  4858.8 1278.19  4998.5 1273.61
  4999.0 1273.11  5007.0 1273.61  5023.7 1277.30  5044.6 1277.75  5053.4 1281.59
  5059.5 1280.74  5068.2 1285.77  5074.4 1294.59  5080.5 1292.90  5089.3 1300.23
  5095.3 1299.83  5104.1 1304.88  5115.7 1306.79  5160.9 1313.70  5374.2 1321.85
#Mann=8,-1,0
  4181.4    0.07       0  4407.6    0.12       0  4414.7    0.07       0
  4750.3   0.035       0  4826.1    0.07       0  4998.5    0.05       0
  5007.0    0.07       0  5115.7    0.12       0
Bank Sta=4998.5,5007
Exp/Cntr=0.3,0.1

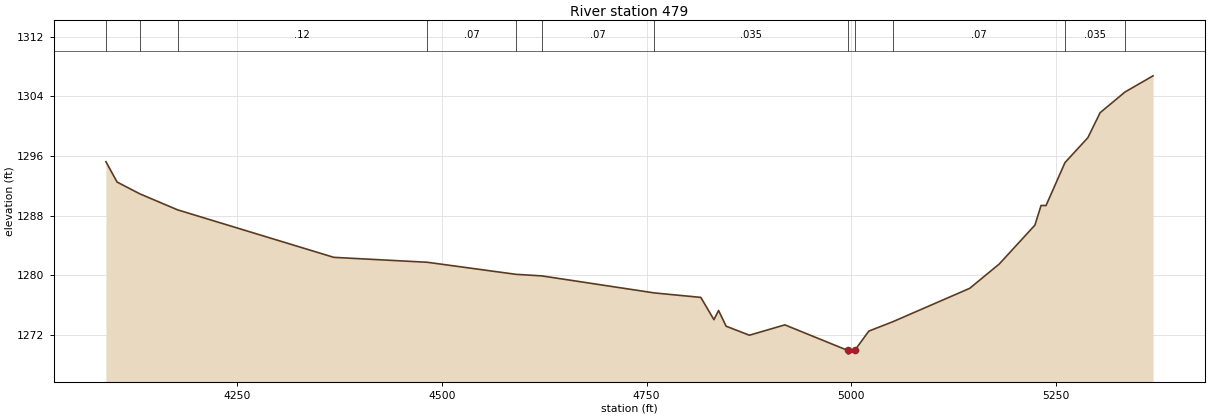
Type RM Length L Ch R = 1,479,0,0,0
BEGIN DESCRIPTION:
Stream0172_DS 1.0
END DESCRIPTION:
XS GIS Cut Line= 3
      2077925.01     13857925.01      2078725.00     13858375.00
      2078924.99     13858075.02
#Sta/Elev= 30
  4089.9 1295.24  4103.6 1292.50  4131.3 1290.92  4177.4 1288.77  4368.1 1282.39
  4482.1 1281.73  4590.3 1280.11  4621.9 1279.90  4759.5 1277.61  4816.2 1277.01
  4832.2 1274.02  4837.9 1275.25  4847.1 1273.14  4875.5 1271.93  4918.8 1273.32
  4995.5 1269.89  4996.0 1269.39  5004.1 1269.89  5021.3 1272.48  5051.2 1273.77
  5144.5 1278.23  5180.5 1281.49  5224.1 1286.72  5231.6 1289.36  5237.6 1289.34
  5260.8 1295.12  5288.7 1298.46  5303.7 1301.82  5334.1 1304.60  5368.3 1306.77
#Mann=12,-1,0
  4089.9    0.12       0  4131.3    0.07       0  4177.4    0.12       0
  4482.1    0.07       0  4590.3    0.12       0  4621.9    0.07       0
  4759.5   0.035       0  4995.5   0.035       0  5004.1   0.035       0
  5051.2    0.07       0  5260.8   0.035       0  5334.1    0.07       0
Bank Sta=4995.5,5004.1
Exp/Cntr=0.3,0.1

Chan Stop Cuts=-1