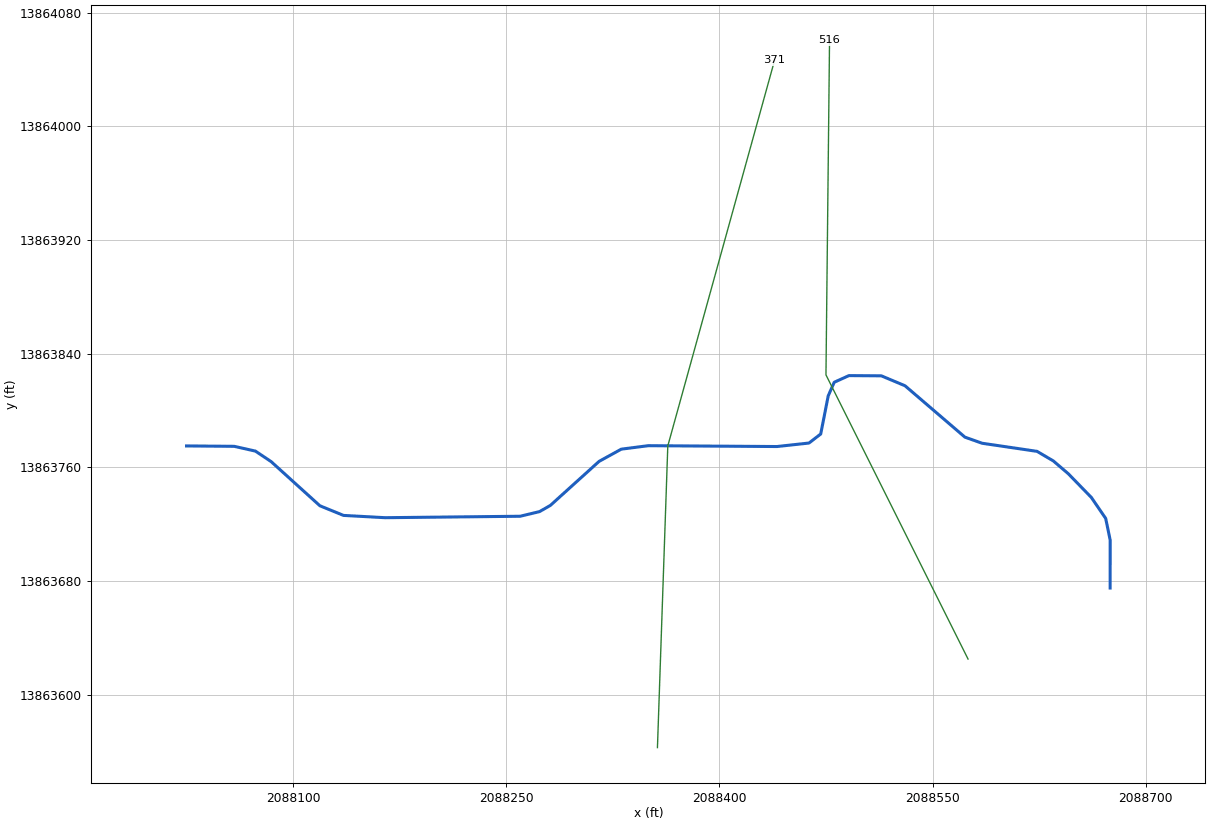
--- Stream0173_DS.prj (project) ---

Proj Title=Stream0173_DS Base Level Engineering
Current Plan=p01
Default Exp/Contr=0.3,0.1
English Units
Geom File=g01
Flow File=f01
Plan File=p01
BEGIN DESCRIPTION:
Stream0173_DS
END DESCRIPTION:

--- Stream0173_DS.p01 (plan) ---

Plan Title=Multiple Run
Short Identifier=Multiple
Geom File=g01
Flow File=f01
Subcritical Flow
K Sum by GR= 0
Std Step Tol= 0.01
Critical Tol= 0.01
Num of Std Step Trials= 20
Max Error Tol= 0.3
Flow Tol Ratio= 0.001
Split Flow NTrial= 30
Split Flow Tol= 0.02
Split Flow Ratio= 0.02
Log Output Level= 0
Friction Slope Method= 1
Unsteady Friction Slope Method= 2
Unsteady Bridges Friction Slope Method= 1
Parabolic Critical Depth
Global Vel Dist=  1 , 1 , 1
Global Log Level= 0
CheckData=True
Encroach Param= -1, 0, 0, 0
BEGIN DESCRIPTION:
Multiple Run
END DESCRIPTION:

--- Stream0173_DS.f01 (steady flow) ---

Flow Title=Multiple
Number of Profiles=7
Profile Names=10-year,25-year,50-year,1pct_min,100-year,1pct_plu,500-year
River Rch & RM= Stream0173_DS,Reach-1,516
    1219    2063    2866    1929    3849    7680    6862
Boundary for River Rch & Prof#=Stream0173_DS,Reach-1,1
Up Type=0
Dn Type=3
Dn Slope=0.005
Boundary for River Rch & Prof#=Stream0173_DS,Reach-1,2
Up Type=0
Dn Type=3
Dn Slope=0.005
Boundary for River Rch & Prof#=Stream0173_DS,Reach-1,3
Up Type=0
Dn Type=3
Dn Slope=0.005
Boundary for River Rch & Prof#=Stream0173_DS,Reach-1,4
Up Type=0
Dn Type=3
Dn Slope=0.005
Boundary for River Rch & Prof#=Stream0173_DS,Reach-1,5
Up Type=0
Dn Type=3
Dn Slope=0.005
Boundary for River Rch & Prof#=Stream0173_DS,Reach-1,6
Up Type=0
Dn Type=3
Dn Slope=0.005
Boundary for River Rch & Prof#=Stream0173_DS,Reach-1,7
Up Type=0
Dn Type=3
Dn Slope=0.005

--- Stream0173_DS.g01 (geometry) ---

Geom Title=Existing Conditions

River Reach=Stream0173_DS,Reach-1
Reach XY= 30
      2088675.00     13863675.00      2088675.01     13863708.82
      2088671.86     13863723.97      2088661.73     13863738.78
      2088645.47     13863755.50      2088634.98     13863764.46
      2088623.55     13863771.18      2088584.86     13863776.89
      2088572.79     13863781.18      2088530.66     13863817.33
      2088513.96     13863824.34      2088491.14     13863824.48
      2088480.79     13863819.79      2088476.58     13863810.20
      2088471.30     13863783.38      2088463.05     13863777.03
      2088440.48     13863774.57      2088349.95     13863775.17
      2088330.95     13863772.72      2088315.36     13863764.14
      2088281.05     13863733.14      2088273.43     13863728.77
      2088259.78     13863725.51      2088164.83     13863724.49
      2088135.47     13863726.10      2088118.84     13863732.89
      2088084.56     13863763.94      2088073.49     13863771.35
      2088058.54     13863774.72      2088025.00     13863775.00

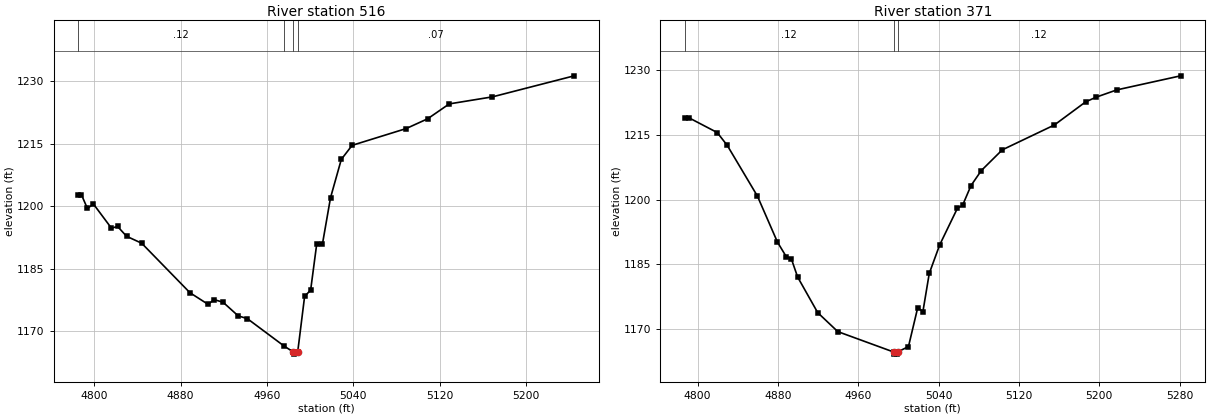
Type RM Length L Ch R = 1,516,145,145,145
BEGIN DESCRIPTION:
Stream0173_DS 1.0
END DESCRIPTION:
XS GIS Cut Line= 3
      2088574.99     13863625.02      2088475.00     13863825.00
      2088477.52     13864060.70
#Sta/Elev= 30
  4785.2 1202.80  4788.0 1202.80  4793.6 1199.46  4799.2 1200.52  4815.9 1194.72
  4821.5 1195.15  4829.9 1192.78  4843.9 1191.11  4888.6 1179.23  4905.4 1176.44
  4911.0 1177.58  4919.3 1176.94  4933.3 1173.67  4941.7 1173.02  4975.6 1166.47
  4984.4 1164.99  4984.7 1164.49  4988.4 1164.99  4994.8 1178.34  5000.4 1179.87
  5006.0 1190.88  5011.3 1190.88  5018.8 1202.03  5028.8 1211.24  5038.8 1214.61
  5088.8 1218.63  5108.8 1220.99  5128.8 1224.56  5168.8 1226.25  5244.5 1231.30
#Mann=4,-1,0
  4785.2    0.12       0  4975.6    0.07       0  4984.4    0.05       0
  4988.4    0.07       0
Bank Sta=4984.4,4988.4
Exp/Cntr=0.3,0.1

Type RM Length L Ch R = 1,371,0,0,0
BEGIN DESCRIPTION:
Stream0173_DS 0.1
END DESCRIPTION:
XS GIS Cut Line= 3
      2088356.40     13863562.71      2088363.69     13863775.00
      2088438.81     13864046.27
#Sta/Elev= 30
  4787.2 1218.93  4790.9 1218.93  4819.5 1215.47  4829.5 1212.50  4859.5 1200.81
  4879.5 1190.17  4888.3 1186.79  4893.3 1186.33  4899.6 1182.10  4919.6 1173.88
  4939.6 1169.50  4995.1 1164.80  4995.4 1164.30  4998.9 1164.30  4999.1 1164.80
  5010.0 1166.04  5019.2 1175.02  5024.4 1174.14  5030.7 1182.93  5041.1 1189.53
  5058.7 1197.96  5063.9 1198.67  5072.3 1203.23  5082.6 1206.70  5103.4 1211.47
  5155.3 1217.21  5186.4 1222.54  5196.8 1223.63  5217.5 1225.32  5281.1 1228.57
#Mann=3,-1,0
  4787.2    0.12       0  4995.1    0.05       0  4999.1    0.12       0
Bank Sta=4995.1,4999.1
Exp/Cntr=0.3,0.1

Chan Stop Cuts=-1