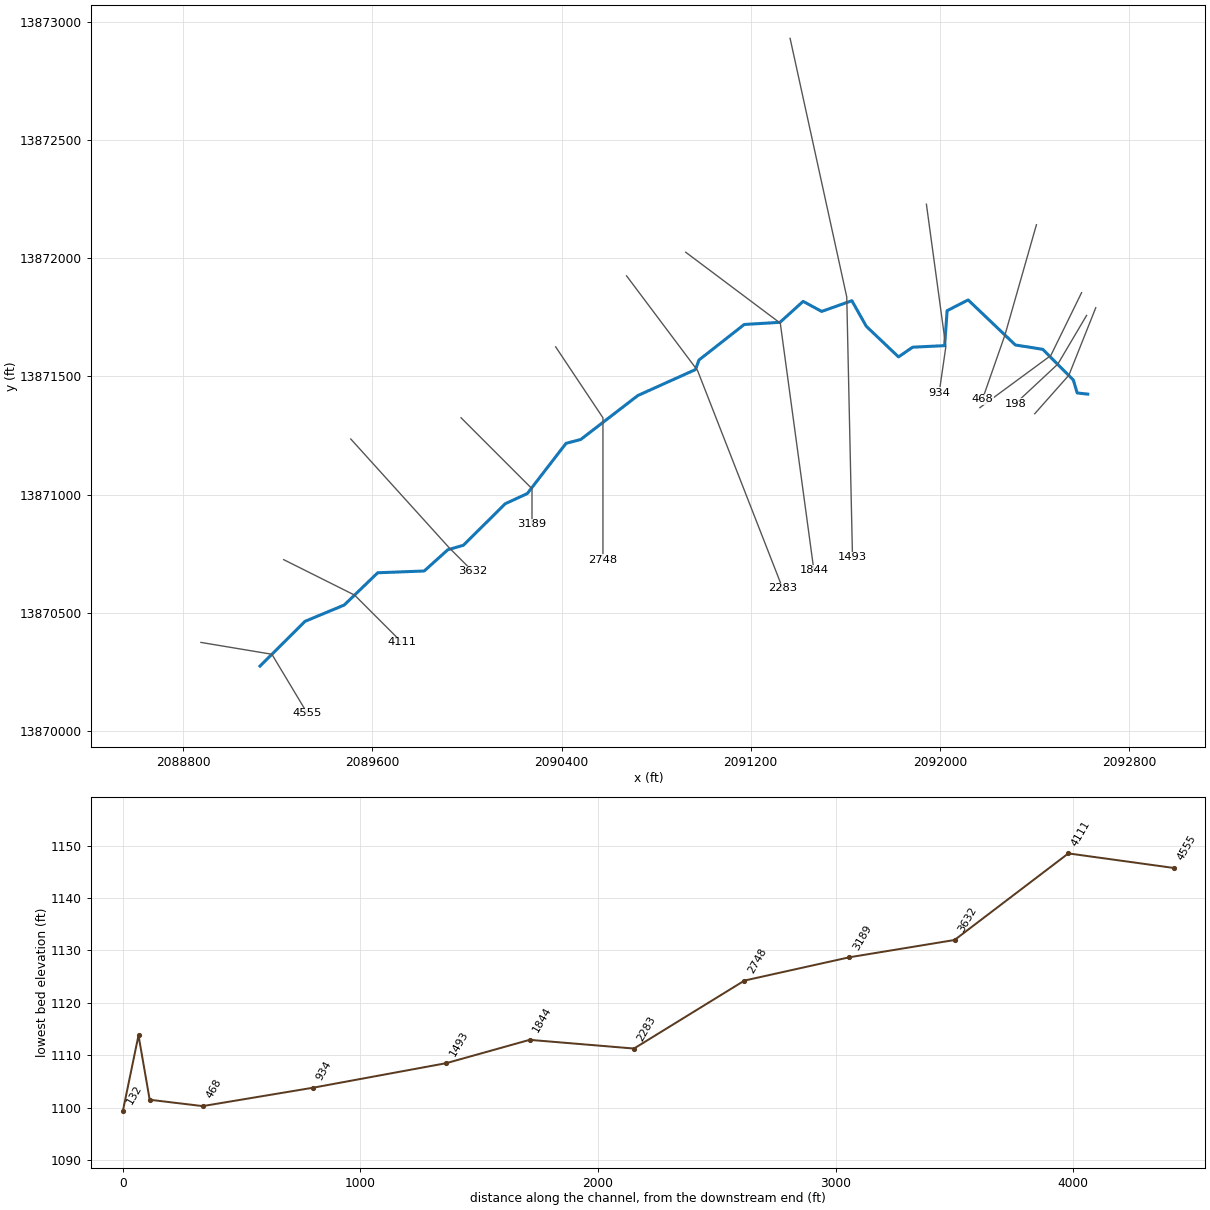
--- Stream0174_DS.prj (project) ---

Proj Title=Stream0174_DS Base Level Engineering
Current Plan=p01
Default Exp/Contr=0.3,0.1
English Units
Geom File=g01
Flow File=f01
Plan File=p01
BEGIN DESCRIPTION:
Stream0174_DS
END DESCRIPTION:

--- Stream0174_DS.p01 (plan) ---

Plan Title=Multiple Run
Short Identifier=Multiple
Geom File=g01
Flow File=f01
Subcritical Flow
K Sum by GR= 0
Std Step Tol= 0.01
Critical Tol= 0.01
Num of Std Step Trials= 20
Max Error Tol= 0.3
Flow Tol Ratio= 0.001
Split Flow NTrial= 30
Split Flow Tol= 0.02
Split Flow Ratio= 0.02
Log Output Level= 0
Friction Slope Method= 1
Unsteady Friction Slope Method= 2
Unsteady Bridges Friction Slope Method= 1
Parabolic Critical Depth
Global Vel Dist=  1 , 1 , 1
Global Log Level= 0
CheckData=True
Encroach Param= -1, 0, 0, 0
BEGIN DESCRIPTION:
Multiple Run
END DESCRIPTION:

--- Stream0174_DS.f01 (steady flow) ---

Flow Title=Multiple
Number of Profiles=7
Profile Names=10-year,25-year,50-year,1pct_min,100-year,1pct_plu,500-year
River Rch & RM= Stream0174_DS,Reach-1,4555
    1339    2288    3201    2169    4329    8637    7827
River Rch & RM= Stream0174_DS,Reach-1,2283
    1516    2605    3656    2485    4959    9894    9018
Boundary for River Rch & Prof#=Stream0174_DS,Reach-1,1
Up Type=0
Dn Type=3
Dn Slope=0.005
Boundary for River Rch & Prof#=Stream0174_DS,Reach-1,2
Up Type=0
Dn Type=3
Dn Slope=0.005
Boundary for River Rch & Prof#=Stream0174_DS,Reach-1,3
Up Type=0
Dn Type=3
Dn Slope=0.005
Boundary for River Rch & Prof#=Stream0174_DS,Reach-1,4
Up Type=0
Dn Type=3
Dn Slope=0.005
Boundary for River Rch & Prof#=Stream0174_DS,Reach-1,5
Up Type=0
Dn Type=3
Dn Slope=0.005
Boundary for River Rch & Prof#=Stream0174_DS,Reach-1,6
Up Type=0
Dn Type=3
Dn Slope=0.005
Boundary for River Rch & Prof#=Stream0174_DS,Reach-1,7
Up Type=0
Dn Type=3
Dn Slope=0.005

--- Stream0174_DS.g01 (geometry) ---

Geom Title=Existing Conditions

River Reach=Stream0174_DS,Reach-1
Reach XY= 30
      2089125.00     13870275.00      2089315.32     13870464.24
      2089481.06     13870533.14      2089622.55     13870669.54
      2089819.14     13870677.07      2089918.96     13870766.82
      2089984.68     13870785.78      2090161.79     13870961.37
      2090255.23     13871004.58      2090418.93     13871216.85
      2090481.04     13871233.18      2090722.71     13871419.15
      2090966.67     13871529.00      2090980.77     13871569.01
      2091172.55     13871719.53      2091323.53     13871728.57
      2091421.60     13871817.17      2091499.97     13871774.70
      2091627.55     13871820.01      2091688.64     13871711.80
      2091824.90     13871582.32      2091884.61     13871623.43
      2092019.99     13871630.01      2092030.37     13871777.77
      2092119.32     13871823.32      2092318.83     13871632.86
      2092434.79     13871614.48      2092564.28     13871484.54
      2092580.33     13871429.92      2092625.00     13871425.00

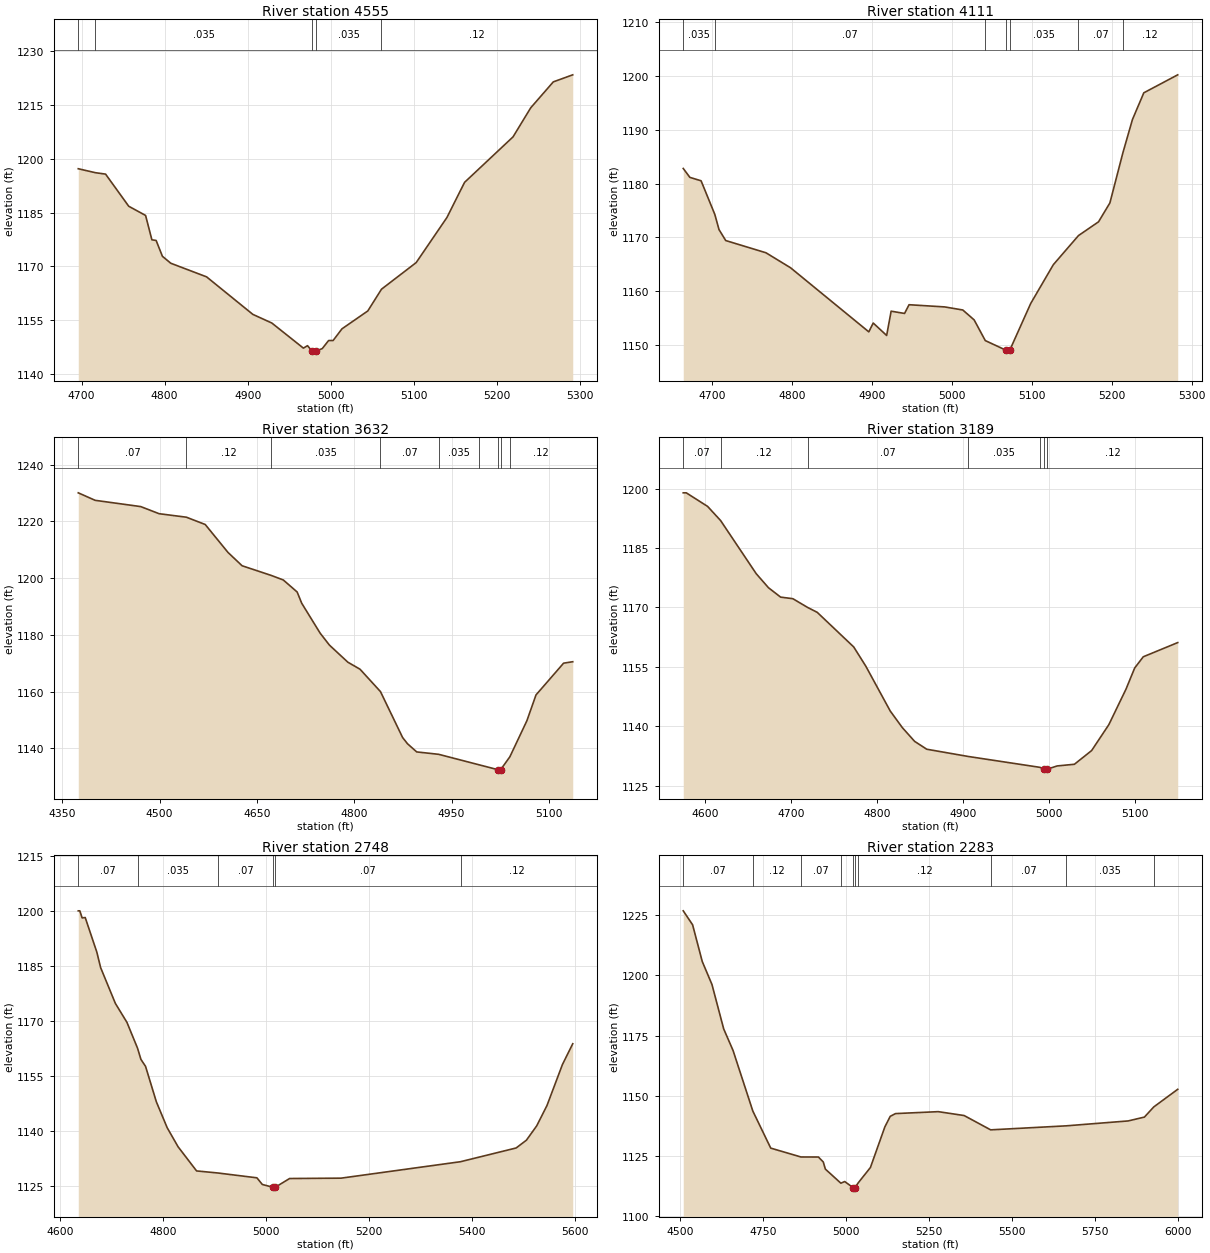
Type RM Length L Ch R = 1,4555,444,444,444
BEGIN DESCRIPTION:
Stream0174_DS 10.0
END DESCRIPTION:
XS GIS Cut Line= 3
      2088875.02     13870375.00      2089175.00     13870325.00
      2089325.02     13870074.97
#Sta/Elev= 30
  4695.9 1197.24  4716.6 1196.13  4728.8 1195.74  4756.7 1186.76  4777.0 1184.19
  4784.6 1177.38  4789.7 1177.20  4797.3 1172.77  4807.4 1170.83  4850.5 1167.03
  4906.2 1156.55  4929.1 1154.13  4967.1 1147.12  4972.1 1147.80  4977.7 1146.22
  4978.0 1145.72  4981.7 1146.22  4989.9 1147.00  4997.5 1149.24  5002.9 1149.24
  5013.6 1152.51  5044.7 1157.50  5061.2 1163.58  5103.0 1171.02  5140.0 1183.60
  5161.3 1193.44  5219.7 1206.15  5241.0 1214.27  5268.2 1221.51  5291.6 1223.48
#Mann=5,-1,0
  4695.9    0.12       0  4716.6   0.035       0  4977.7   0.035       0
  4981.7   0.035       0  5061.2    0.12       0
Bank Sta=4977.7,4981.7
Exp/Cntr=0.3,0.1

Type RM Length L Ch R = 1,4111,479,479,479
BEGIN DESCRIPTION:
Stream0174_DS 9.0
END DESCRIPTION:
XS GIS Cut Line= 3
      2089225.04     13870724.98      2089525.00     13870575.00
      2089724.99     13870375.01
#Sta/Elev= 30
  4664.4 1182.80  4672.7 1181.14  4686.7 1180.51  4703.9 1174.25  4709.1 1171.45
  4717.5 1169.41  4767.8 1167.14  4798.5 1164.36  4896.4 1152.45  4901.9 1154.09
  4918.7 1151.78  4924.3 1156.29  4941.1 1155.87  4946.7 1157.49  4991.4 1157.08
  5013.9 1156.51  5028.1 1154.67  5042.0 1150.83  5068.5 1149.00  5068.7 1148.50
  5072.5 1149.00  5098.8 1157.72  5127.1 1164.93  5158.5 1170.33  5183.6 1172.89
  5197.8 1176.40  5214.1 1185.74  5226.0 1191.89  5240.2 1196.85  5282.6 1200.19
#Mann=7,-1,0
  4664.4   0.035       0  4703.9    0.07       0  5042.0   0.035       0
  5068.5    0.05       0  5072.5   0.035       0  5158.5    0.07       0
  5214.1    0.12       0
Bank Sta=5068.5,5072.5
Exp/Cntr=0.3,0.1

Type RM Length L Ch R = 1,3632,443,443,443
BEGIN DESCRIPTION:
Stream0174_DS 8.0
END DESCRIPTION:
XS GIS Cut Line= 3
      2089508.78     13871235.05      2089925.00     13870775.00
      2090024.99     13870675.01
#Sta/Elev= 30
  4374.8 1230.05  4400.8 1227.41  4471.0 1225.20  4499.4 1222.69  4541.4 1221.46
  4570.4 1218.89  4605.5 1209.04  4627.2 1204.35  4671.9 1200.96  4690.7 1199.34
  4712.0 1195.11  4719.1 1191.13  4747.5 1180.58  4761.7 1176.40  4790.1 1170.37
  4808.9 1167.89  4840.4 1160.00  4874.5 1143.82  4882.0 1141.63  4896.2 1138.75
  4930.1 1137.90  4992.4 1134.20  5021.5 1132.48  5021.7 1131.98  5025.5 1132.48
  5039.7 1137.02  5065.9 1149.70  5080.0 1158.83  5122.5 1170.02  5136.6 1170.53
#Mann=9,-1,0
  4374.8    0.07       0  4541.4    0.12       0  4671.9   0.035       0
  4840.4    0.07       0  4930.1   0.035       0  4992.4    0.07       0
  5021.5    0.05       0  5025.5    0.07       0  5039.7    0.12       0
Bank Sta=5021.5,5025.5
Exp/Cntr=0.3,0.1

Type RM Length L Ch R = 1,3189,441,441,441
BEGIN DESCRIPTION:
Stream0174_DS 7.0
END DESCRIPTION:
XS GIS Cut Line= 3
      2089975.01     13871324.99      2090275.00     13871025.00
      2090275.00     13870874.95
#Sta/Elev= 30
  4575.1 1198.94  4578.6 1198.94  4603.4 1195.51  4618.5 1191.94  4659.9 1178.51
  4674.1 1174.98  4688.2 1172.61  4702.4 1172.21  4719.6 1170.00  4730.7 1168.77
  4773.1 1160.03  4787.2 1155.15  4815.5 1143.86  4829.6 1139.65  4843.8 1136.20
  4857.9 1134.21  4906.1 1132.38  4989.5 1129.63  4993.8 1129.18  4994.1 1128.68
  4997.6 1128.68  4997.8 1129.18  5009.4 1129.99  5029.4 1130.41  5049.4 1133.87
  5069.4 1140.41  5089.4 1149.41  5099.4 1154.71  5109.4 1157.55  5149.4 1161.13
#Mann=7,-1,0
  4575.1    0.07       0  4618.5    0.12       0  4719.6    0.07       0
  4906.1   0.035       0  4989.5    0.12       0  4993.8    0.05       0
  4997.8    0.12       0
Bank Sta=4993.8,4997.8
Exp/Cntr=0.3,0.1

Type RM Length L Ch R = 1,2748,465,465,465
BEGIN DESCRIPTION:
Stream0174_DS 6.0
END DESCRIPTION:
XS GIS Cut Line= 3
      2090375.02     13871624.97      2090575.00     13871325.00
      2090575.00     13870725.02
#Sta/Elev= 30
  4634.7 1200.07  4637.7 1200.07  4642.2 1198.15  4648.2 1198.24  4670.7 1188.85
  4678.2 1184.58  4706.8 1174.84  4729.3 1169.67  4749.9 1162.62  4756.4 1159.60
  4765.4 1157.69  4786.4 1148.03  4807.4 1140.98  4828.5 1135.80  4864.5 1129.20
  4906.3 1128.63  4981.7 1127.32  4992.2 1125.51  5013.2 1124.74  5013.5 1124.24
  5017.2 1124.74  5045.2 1127.13  5145.2 1127.23  5377.2 1131.71  5485.2 1135.45
  5505.2 1137.57  5525.2 1141.48  5545.2 1147.03  5575.2 1158.20  5595.2 1163.85
#Mann=6,-1,0
  4634.7    0.07       0  4749.9   0.035       0  4906.3    0.07       0
  5013.2    0.05       0  5017.2    0.07       0  5377.2    0.12       0
Bank Sta=5013.2,5017.2
Exp/Cntr=0.3,0.1

Type RM Length L Ch R = 1,2283,439,439,439
BEGIN DESCRIPTION:
Stream0174_DS 5.0
END DESCRIPTION:
XS GIS Cut Line= 3
      2090674.98     13871925.03      2090975.00     13871525.00
      2091335.17     13870603.09
#Sta/Elev= 30
  4508.5 1226.77  4536.7 1220.97  4565.8 1205.73  4595.0 1196.21  4630.4 1177.75
  4658.5 1168.84  4718.2 1143.65  4772.1 1128.29  4863.1 1124.61  4915.8 1124.59
  4930.4 1122.53  4936.7 1119.58  4983.4 1113.73  4995.0 1114.42  5021.4 1111.77
  5021.7 1111.27  5025.5 1111.77  5035.6 1113.86  5072.4 1120.24  5115.9 1137.08
  5132.1 1141.48  5148.1 1142.62  5276.9 1143.42  5354.8 1141.81  5434.7 1135.87
  5662.0 1137.53  5849.0 1139.57  5898.0 1141.17  5926.0 1145.37  5998.3 1152.70
#Mann=10,-1,0
  4508.5    0.07       0  4718.2    0.12       0  4863.1    0.07       0
  4983.4   0.035       0  5021.4   0.035       0  5025.5   0.035       0
  5035.6    0.12       0  5434.7    0.07       0  5662.0   0.035       0
  5926.0    0.07       0
Bank Sta=5021.4,5025.5
Exp/Cntr=0.3,0.1

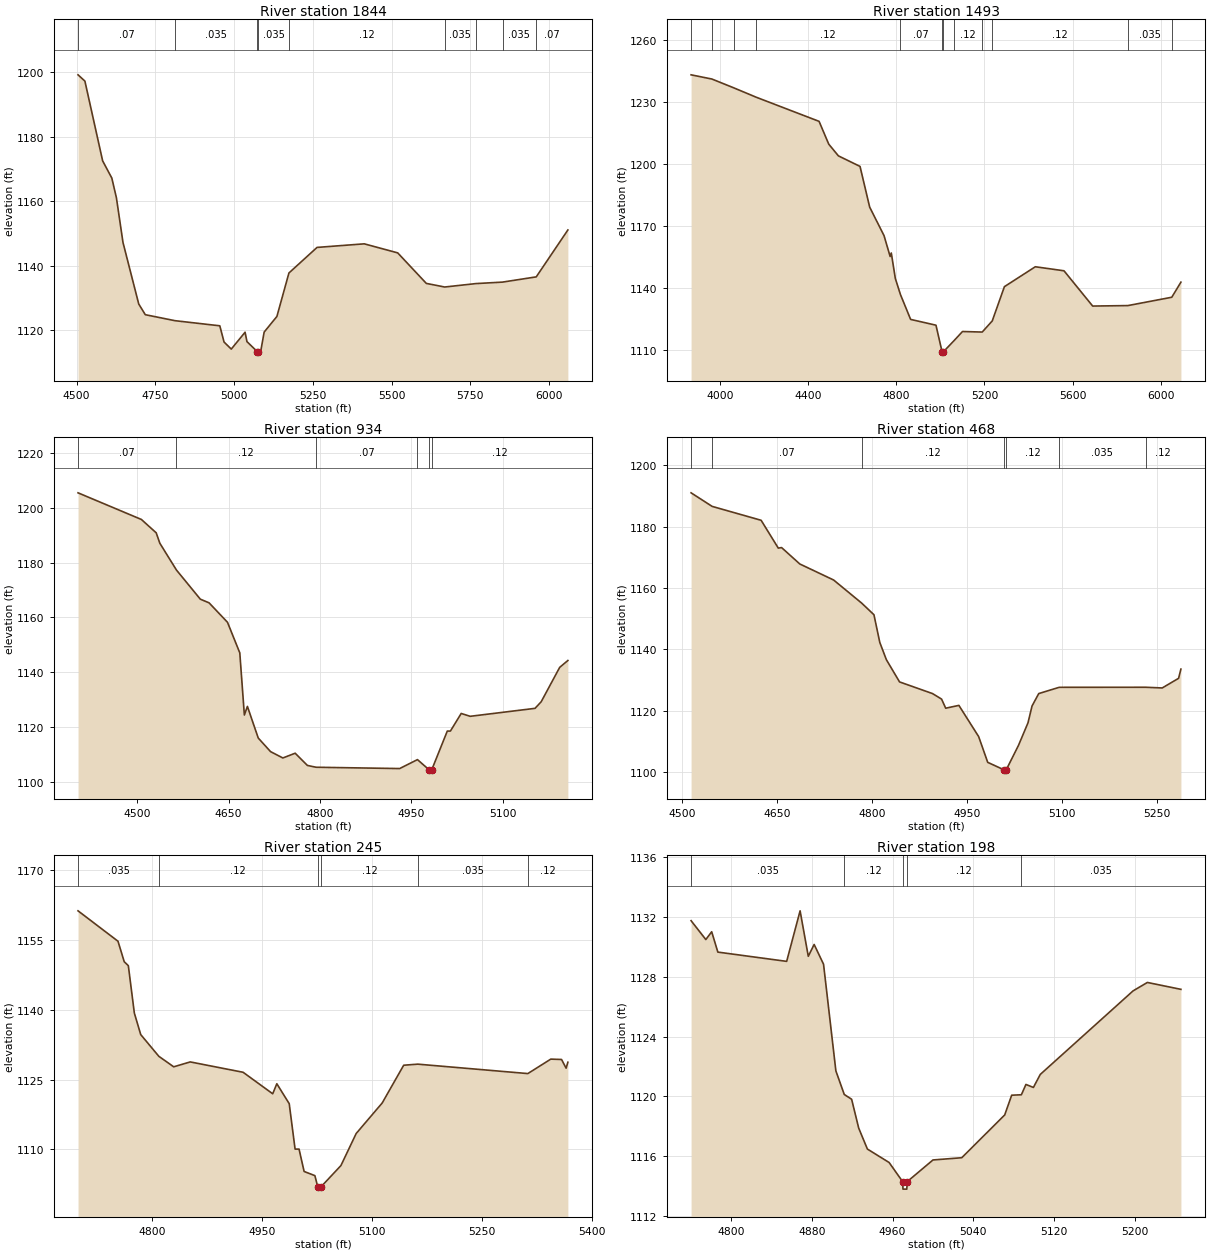
Type RM Length L Ch R = 1,1844,351,351,351
BEGIN DESCRIPTION:
Stream0174_DS 4.0
END DESCRIPTION:
XS GIS Cut Line= 3
      2090925.02     13872024.98      2091325.00     13871725.00
      2091467.07     13870679.78
#Sta/Elev= 30
  4504.7 1199.10  4526.5 1197.16  4582.8 1172.47  4612.0 1167.12  4626.5 1161.04
  4647.4 1147.19  4697.4 1128.14  4718.2 1124.83  4812.7 1122.97  4954.7 1121.39
  4968.2 1116.36  4991.1 1114.18  5034.9 1119.40  5040.9 1116.49  5073.3 1113.43
  5073.5 1112.93  5077.4 1113.43  5085.4 1113.95  5095.5 1119.45  5135.9 1124.28
  5174.1 1137.74  5263.3 1145.66  5413.2 1146.77  5519.4 1143.97  5610.2 1134.52
  5668.5 1133.40  5767.4 1134.46  5852.1 1134.92  5959.1 1136.54  6059.5 1151.06
#Mann=9,-1,0
  4504.7    0.07       0  4812.7   0.035       0  5073.3   0.035       0
  5077.4   0.035       0  5174.1    0.12       0  5668.5   0.035       0
  5767.4    0.07       0  5852.1   0.035       0  5959.1    0.07       0
Bank Sta=5073.3,5077.4
Exp/Cntr=0.3,0.1

Type RM Length L Ch R = 1,1493,559,559,559
BEGIN DESCRIPTION:
Stream0174_DS 3.0
END DESCRIPTION:
XS GIS Cut Line= 3
      2091366.41     13872929.51      2091606.00     13871835.74
      2091630.30     13870735.01
#Sta/Elev= 30
  3869.9 1243.17  3964.4 1241.13  4064.4 1236.83  4164.5 1232.36  4450.2 1220.65
  4494.0 1209.62  4537.9 1203.94  4635.8 1198.85  4679.6 1179.14  4744.7 1165.33
  4772.4 1155.24  4777.6 1156.95  4795.9 1144.60  4819.1 1136.83  4865.2 1124.80
  4980.1 1122.00  5008.1 1108.98  5008.4 1108.48  5012.5 1108.98  5063.5 1114.69
  5100.4 1118.94  5189.8 1118.68  5235.2 1124.05  5290.4 1140.65  5430.5 1150.28
  5560.5 1148.33  5690.5 1131.26  5850.2 1131.49  6049.1 1135.52  6090.6 1142.82
#Mann=12,-1,0
  3869.9   0.035       0  3964.4    0.07       0  4064.4   0.035       0
  4164.5    0.12       0  4819.1    0.07       0  5008.1    0.05       0
  5012.5    0.07       0  5063.5    0.12       0  5189.8    0.07       0
  5235.2    0.12       0  5850.2   0.035       0  6049.1    0.12       0
Bank Sta=5008.1,5012.5
Exp/Cntr=0.3,0.1

Type RM Length L Ch R = 1,934,466,466,466
BEGIN DESCRIPTION:
Stream0174_DS 2.0
END DESCRIPTION:
XS GIS Cut Line= 3
      2091942.81     13872228.09      2092025.00     13871625.00
      2091996.92     13871431.70
#Sta/Elev= 30
  4402.8 1205.55  4506.8 1195.81  4531.1 1190.93  4537.1 1187.11  4564.4 1177.31
  4603.5 1166.68  4617.9 1165.33  4648.1 1158.23  4668.3 1147.05  4675.8 1124.32
  4680.8 1127.48  4698.6 1115.91  4718.8 1110.94  4739.0 1108.62  4759.2 1110.36
  4779.3 1105.89  4793.5 1105.23  4930.7 1104.75  4959.9 1108.02  4979.0 1104.31
  4979.3 1103.81  4983.4 1104.31  5008.9 1118.45  5014.0 1118.45  5031.7 1124.89
  5046.5 1123.85  5152.9 1126.76  5163.0 1129.17  5193.4 1141.75  5206.8 1144.25
#Mann=6,-1,0
  4402.8    0.07       0  4564.4    0.12       0  4793.5    0.07       0
  4959.9    0.12       0  4979.0    0.05       0  4983.4    0.12       0
Bank Sta=4979,4983.4
Exp/Cntr=0.3,0.1

Type RM Length L Ch R = 1,468,223,223,223
BEGIN DESCRIPTION:
Stream0174_DS 1.0
END DESCRIPTION:
XS GIS Cut Line= 3
      2092408.08     13872141.29      2092275.00     13871675.00
      2092179.88     13871403.28
#Sta/Elev= 30
  4514.8 1191.01  4548.0 1186.59  4625.3 1182.06  4652.4 1172.99  4657.6 1173.16
  4686.3 1167.82  4739.7 1162.59  4783.9 1155.07  4803.3 1151.27  4812.5 1142.26
  4822.9 1136.62  4843.7 1129.37  4895.7 1125.57  4910.0 1123.77  4916.5 1120.80
  4937.3 1121.72  4968.5 1111.55  4982.8 1103.15  5007.7 1100.79  5008.0 1100.29
  5012.2 1100.79  5031.5 1108.76  5046.3 1116.02  5052.7 1121.51  5063.3 1125.57
  5095.5 1127.61  5231.8 1127.63  5258.1 1127.40  5283.9 1130.54  5287.6 1133.55
#Mann=7,-1,0
  4514.8    0.12       0  4548.0    0.07       0  4783.9    0.12       0
  5007.7    0.05       0  5012.2    0.12       0  5095.5   0.035       0
  5231.8    0.12       0
Bank Sta=5007.7,5012.2
Exp/Cntr=0.3,0.1

Type RM Length L Ch R = 1,245,47,47,47
BEGIN DESCRIPTION:
Stream0174_DS 0.2
END DESCRIPTION:
XS GIS Cut Line= 3
      2092598.98     13871853.97      2092468.83     13871588.16
      2092169.08     13871367.79
#Sta/Elev= 30
  4699.4 1161.16  4753.9 1154.64  4762.4 1150.25  4768.0 1149.40  4776.2 1139.24
  4784.9 1134.63  4809.6 1129.97  4829.9 1127.72  4852.4 1128.77  4924.5 1126.55
  4964.9 1121.94  4970.5 1124.09  4987.4 1119.82  4995.4 1110.08  5000.8 1110.08
  5007.7 1105.29  5022.4 1104.39  5026.3 1102.00  5026.7 1101.50  5030.8 1102.00
  5057.9 1106.55  5078.7 1113.42  5114.2 1119.97  5143.5 1128.06  5162.7 1128.29
  5312.8 1126.27  5344.1 1129.37  5358.8 1129.29  5365.0 1127.43  5367.4 1128.70
#Mann=6,-1,0
  4699.4   0.035       0  4809.6    0.12       0  5026.3    0.05       0
  5030.8    0.12       0  5162.7   0.035       0  5312.8    0.12       0
Bank Sta=5026.3,5030.8
Exp/Cntr=0.3,0.1

Type RM Length L Ch R = 1,198,66,66,66
BEGIN DESCRIPTION:
Stream0174_DS 0.1
END DESCRIPTION:
XS GIS Cut Line= 3
      2092620.21     13871757.85      2092498.41     13871551.75
      2092318.82     13871384.50
#Sta/Elev= 30
  4760.6 1131.75  4775.2 1130.49  4781.0 1131.01  4787.1 1129.65  4855.2 1129.03
  4868.5 1132.41  4876.6 1129.37  4882.4 1130.16  4891.7 1128.84  4903.9 1121.71
  4912.2 1120.13  4919.5 1119.81  4926.5 1117.88  4935.1 1116.48  4956.6 1115.58
  4970.0 1114.30  4970.3 1113.80  4974.1 1113.80  4974.5 1114.30  5000.0 1115.75
  5028.5 1115.90  5071.0 1118.76  5077.9 1120.08  5087.5 1120.11  5092.0 1120.80
  5099.4 1120.60  5106.2 1121.47  5198.1 1127.06  5212.2 1127.62  5245.4 1127.16
#Mann=5,-1,0
  4760.6   0.035       0  4912.2    0.12       0  4970.0    0.05       0
  4974.5    0.12       0  5087.5   0.035       0
Bank Sta=4970,4974.5
Exp/Cntr=0.3,0.1

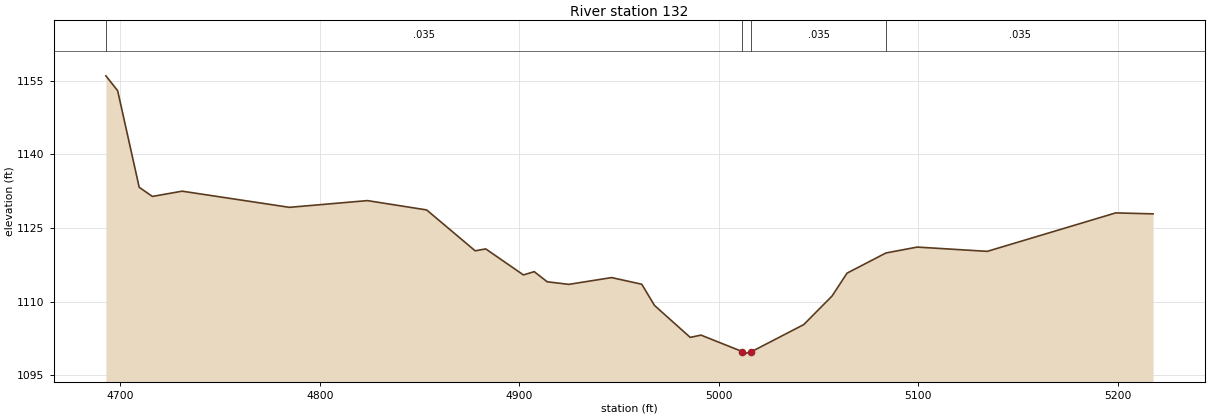
Type RM Length L Ch R = 1,132,0,0,0
BEGIN DESCRIPTION:
Stream0174_DS 0.0
END DESCRIPTION:
XS GIS Cut Line= 3
      2092659.05     13871790.48      2092545.37     13871505.09
      2092401.01     13871342.14
#Sta/Elev= 30
  4692.8 1155.96  4698.7 1152.93  4709.5 1133.27  4716.1 1131.41  4731.0 1132.48
  4784.8 1129.19  4823.9 1130.56  4853.6 1128.66  4877.9 1120.34  4883.2 1120.73
  4902.1 1115.43  4907.5 1116.10  4914.0 1114.04  4924.8 1113.51  4946.3 1114.89
  4961.4 1113.54  4967.8 1109.22  4985.7 1102.72  4991.1 1103.18  5011.9 1099.81
  5012.2 1099.31  5016.4 1099.81  5042.6 1105.32  5056.8 1111.14  5064.3 1115.79
  5083.8 1119.90  5099.5 1121.10  5134.6 1120.23  5199.0 1128.06  5217.7 1127.86
#Mann=4,-1,0
  4692.8   0.035       0  5011.9   0.035       0  5016.4   0.035       0
  5083.8   0.035       0
Bank Sta=5011.9,5016.4
Exp/Cntr=0.3,0.1

Chan Stop Cuts=-1