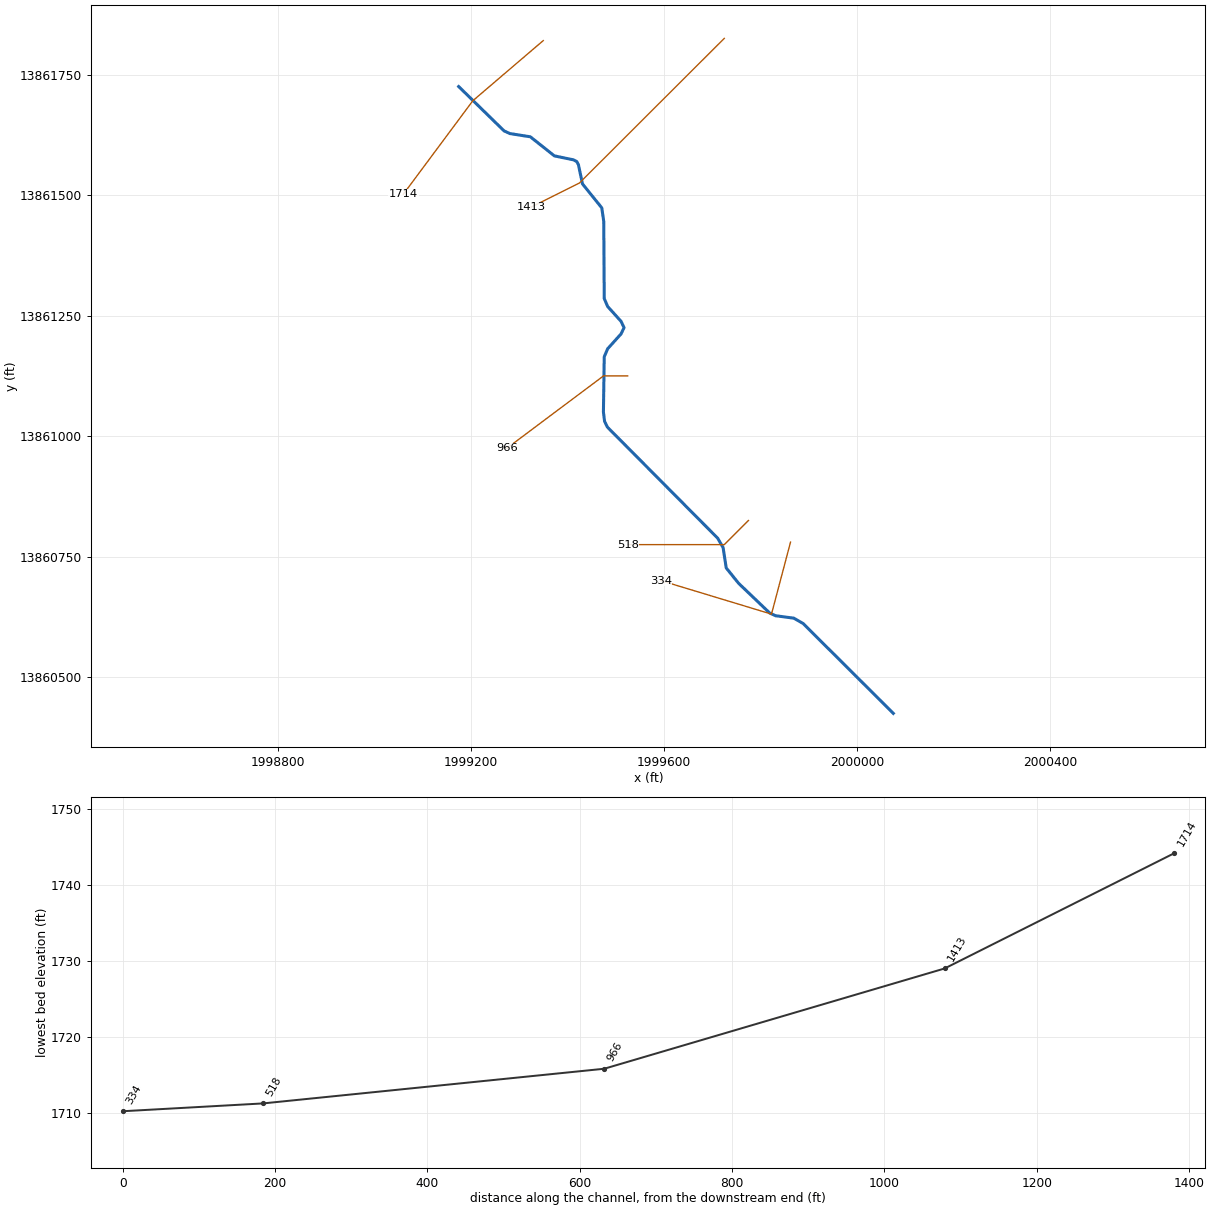
--- Stream0200_DS.prj (project) ---

Proj Title=Stream0200_DS Base Level Engineering
Current Plan=p01
Default Exp/Contr=0.3,0.1
English Units
Geom File=g01
Flow File=f01
Plan File=p01
BEGIN DESCRIPTION:
Stream0200_DS
END DESCRIPTION:

--- Stream0200_DS.p01 (plan) ---

Plan Title=Multiple Run
Short Identifier=Multiple
Geom File=g01
Flow File=f01
Subcritical Flow
K Sum by GR= 0
Std Step Tol= 0.01
Critical Tol= 0.01
Num of Std Step Trials= 20
Max Error Tol= 0.3
Flow Tol Ratio= 0.001
Split Flow NTrial= 30
Split Flow Tol= 0.02
Split Flow Ratio= 0.02
Log Output Level= 0
Friction Slope Method= 1
Unsteady Friction Slope Method= 2
Unsteady Bridges Friction Slope Method= 1
Parabolic Critical Depth
Global Vel Dist=  1 , 1 , 1
Global Log Level= 0
CheckData=True
Encroach Param= -1, 0, 0, 0
BEGIN DESCRIPTION:
Multiple Run
END DESCRIPTION:

--- Stream0200_DS.f01 (steady flow) ---

Flow Title=Multiple
Number of Profiles=7
Profile Names=10-year,25-year,50-year,1pct_min,100-year,1pct_plu,500-year
River Rch & RM= Stream0200_DS,Reach-1,1714
     909    1536    2131    1436    2865    5716    5116
Boundary for River Rch & Prof#=Stream0200_DS,Reach-1,1
Up Type=0
Dn Type=3
Dn Slope=0.005
Boundary for River Rch & Prof#=Stream0200_DS,Reach-1,2
Up Type=0
Dn Type=3
Dn Slope=0.005
Boundary for River Rch & Prof#=Stream0200_DS,Reach-1,3
Up Type=0
Dn Type=3
Dn Slope=0.005
Boundary for River Rch & Prof#=Stream0200_DS,Reach-1,4
Up Type=0
Dn Type=3
Dn Slope=0.005
Boundary for River Rch & Prof#=Stream0200_DS,Reach-1,5
Up Type=0
Dn Type=3
Dn Slope=0.005
Boundary for River Rch & Prof#=Stream0200_DS,Reach-1,6
Up Type=0
Dn Type=3
Dn Slope=0.005
Boundary for River Rch & Prof#=Stream0200_DS,Reach-1,7
Up Type=0
Dn Type=3
Dn Slope=0.005

--- Stream0200_DS.g01 (geometry) ---

Geom Title=Existing Conditions

River Reach=Stream0200_DS,Reach-1
Reach XY= 30
      1999175.00     13861725.00      1999268.92     13861633.09
      1999281.03     13861627.48      1999323.30     13861620.83
      1999373.15     13861581.24      1999413.01     13861572.93
      1999419.42     13861569.42      1999422.93     13861563.01
      1999431.28     13861523.16      1999471.26     13861473.48
      1999475.36     13861445.16      1999476.38     13861285.44
      1999483.45     13861268.82      1999511.05     13861238.21
      1999517.44     13861225.00      1999511.05     13861211.79
      1999483.45     13861181.18      1999476.37     13861164.56
      1999474.68     13861049.89      1999477.05     13861030.86
      1999482.81     13861018.81      1999711.37     13860788.21
      1999722.46     13860768.95      1999728.97     13860726.64
      1999754.58     13860694.77      1999818.93     13860633.15
      1999831.04     13860627.53      1999868.95     13860622.46
      1999888.21     13860611.37      2000075.00     13860425.00

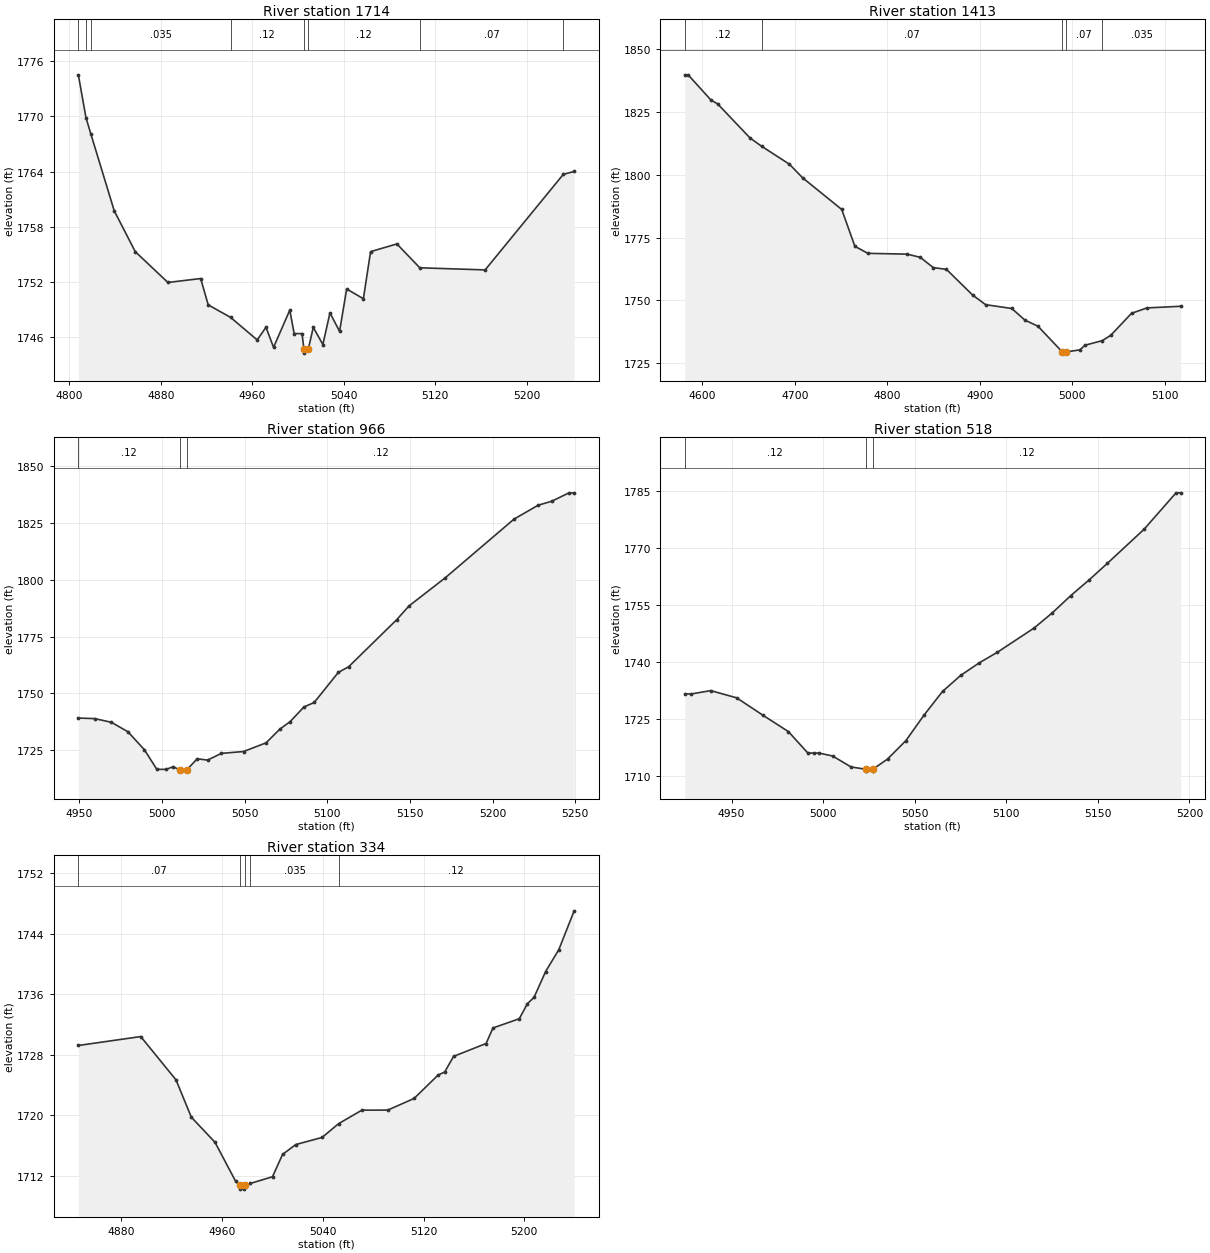
Type RM Length L Ch R = 1,1714,301,301,301
BEGIN DESCRIPTION:
Stream0200_DS 4.0
END DESCRIPTION:
XS GIS Cut Line= 3
      1999350.16     13861820.39      1999204.27     13861695.58
      1999060.44     13861501.82
#Sta/Elev= 30
  4808.0 1774.54  4814.7 1769.86  4819.0 1768.07  4839.4 1759.71  4857.8 1755.26
  4886.3 1751.91  4914.9 1752.34  4921.5 1749.47  4941.0 1748.11  4964.3 1745.65
  4972.0 1747.03  4978.6 1744.84  4992.8 1748.90  4996.6 1746.34  5003.5 1746.34
  5005.1 1744.71  5005.3 1744.21  5009.1 1744.71  5013.3 1747.02  5021.7 1745.15
  5027.9 1748.60  5036.3 1746.58  5042.5 1751.20  5057.1 1750.14  5063.4 1755.27
  5086.4 1756.11  5106.4 1753.51  5163.5 1753.28  5231.8 1763.69  5241.3 1764.01
#Mann=8,-1,0
  4808.0    0.12       0  4814.7    0.07       0  4819.0   0.035       0
  4941.0    0.12       0  5005.1    0.05       0  5009.1    0.12       0
  5106.4    0.07       0  5231.8   0.035       0
Bank Sta=5005.1,5009.1
Exp/Cntr=0.3,0.1

Type RM Length L Ch R = 1,1413,447,447,447
BEGIN DESCRIPTION:
Stream0200_DS 3.0
END DESCRIPTION:
XS GIS Cut Line= 3
      1999725.01     13861825.01      1999425.00     13861525.00
      1999324.99     13861474.99
#Sta/Elev= 30
  4581.1 1839.66  4584.7 1839.66  4609.4 1829.63  4616.5 1828.14  4651.8 1814.50
  4664.2 1811.26  4694.3 1804.11  4708.4 1798.75  4750.8 1786.14  4765.0 1771.50
  4779.1 1768.70  4821.5 1768.39  4835.7 1767.12  4849.8 1763.03  4864.0 1762.34
  4892.2 1752.16  4906.4 1748.29  4934.7 1746.78  4948.8 1742.17  4963.0 1739.72
  4989.2 1729.54  4989.5 1729.04  4993.2 1729.54  5008.2 1730.32  5013.8 1732.18
  5032.5 1734.01  5041.7 1736.13  5064.1 1744.86  5080.8 1747.01  5117.2 1747.66
#Mann=5,-1,0
  4581.1    0.12       0  4664.2    0.07       0  4989.2    0.05       0
  4993.2    0.07       0  5032.5   0.035       0
Bank Sta=4989.2,4993.2
Exp/Cntr=0.3,0.1

Type RM Length L Ch R = 1,966,448,448,448
BEGIN DESCRIPTION:
Stream0200_DS 2.0
END DESCRIPTION:
XS GIS Cut Line= 3
      1999525.03     13861125.00      1999475.00     13861125.00
      1999275.02     13860975.02
#Sta/Elev= 30
  4949.4 1739.18  4959.4 1738.91  4969.4 1737.30  4979.4 1733.15  4989.4 1725.20
  4996.9 1716.60  5002.6 1716.60  5006.7 1717.75  5011.0 1716.32  5011.2 1715.82
  5015.0 1716.32  5021.3 1721.26  5027.6 1720.66  5035.9 1723.62  5049.4 1724.45
  5063.0 1728.27  5071.3 1734.27  5077.6 1737.62  5085.9 1744.05  5092.1 1746.01
  5106.7 1759.24  5113.0 1761.76  5142.1 1782.48  5149.4 1788.44  5171.3 1800.80
  5213.0 1826.67  5227.6 1832.79  5235.9 1834.56  5246.3 1838.24  5249.4 1838.24
#Mann=3,-1,0
  4949.4    0.12       0  5011.0    0.05       0  5015.0    0.12       0
Bank Sta=5011,5015
Exp/Cntr=0.3,0.1

Type RM Length L Ch R = 1,518,184,184,184
BEGIN DESCRIPTION:
Stream0200_DS 1.0
END DESCRIPTION:
XS GIS Cut Line= 3
      1999775.02     13860825.02      1999725.00     13860775.00
      1999525.04     13860775.00
#Sta/Elev= 30
  4924.5 1731.59  4928.1 1731.59  4938.7 1732.46  4952.8 1730.56  4967.0 1726.03
  4981.1 1721.65  4991.7 1716.01  4995.2 1716.01  4997.7 1716.01  5005.2 1715.24
  5015.2 1712.36  5023.2 1711.75  5023.5 1711.25  5027.0 1711.25  5027.2 1711.75
  5035.2 1714.44  5045.2 1719.28  5055.2 1726.07  5065.2 1732.24  5075.2 1736.50
  5085.2 1739.76  5095.2 1742.58  5115.2 1748.95  5125.2 1752.97  5135.2 1757.48
  5145.2 1761.61  5155.2 1765.99  5175.2 1774.95  5192.7 1784.57  5195.2 1784.57
#Mann=3,-1,0
  4924.5    0.12       0  5023.2    0.05       0  5027.2    0.12       0
Bank Sta=5023.2,5027.2
Exp/Cntr=0.3,0.1

Type RM Length L Ch R = 1,334,0,0,0
BEGIN DESCRIPTION:
Stream0200_DS 0.0
END DESCRIPTION:
XS GIS Cut Line= 3
      1999862.09     13860780.04      1999822.70     13860630.85
      1999593.31     13860700.41
#Sta/Elev= 30
  4845.7 1729.23  4895.3 1730.41  4923.3 1724.68  4935.5 1719.74  4954.3 1716.42
  4970.6 1711.29  4973.8 1710.72  4974.0 1710.22  4977.5 1710.22  4977.8 1710.72
  4982.5 1710.98  5000.0 1711.86  5008.0 1714.82  5018.5 1716.12  5039.4 1717.06
  5052.5 1718.88  5071.0 1720.67  5091.6 1720.68  5112.5 1722.22  5131.6 1725.32
  5136.8 1725.72  5143.9 1727.79  5169.7 1729.49  5175.2 1731.55  5196.1 1732.77
  5202.6 1734.77  5207.8 1735.59  5217.0 1739.01  5227.5 1741.91  5239.7 1747.05
#Mann=5,-1,0
  4845.7    0.07       0  4973.8   0.035       0  4977.8    0.07       0
  4982.5   0.035       0  5052.5    0.12       0
Bank Sta=4973.8,4977.8
Exp/Cntr=0.3,0.1

Chan Stop Cuts=-1