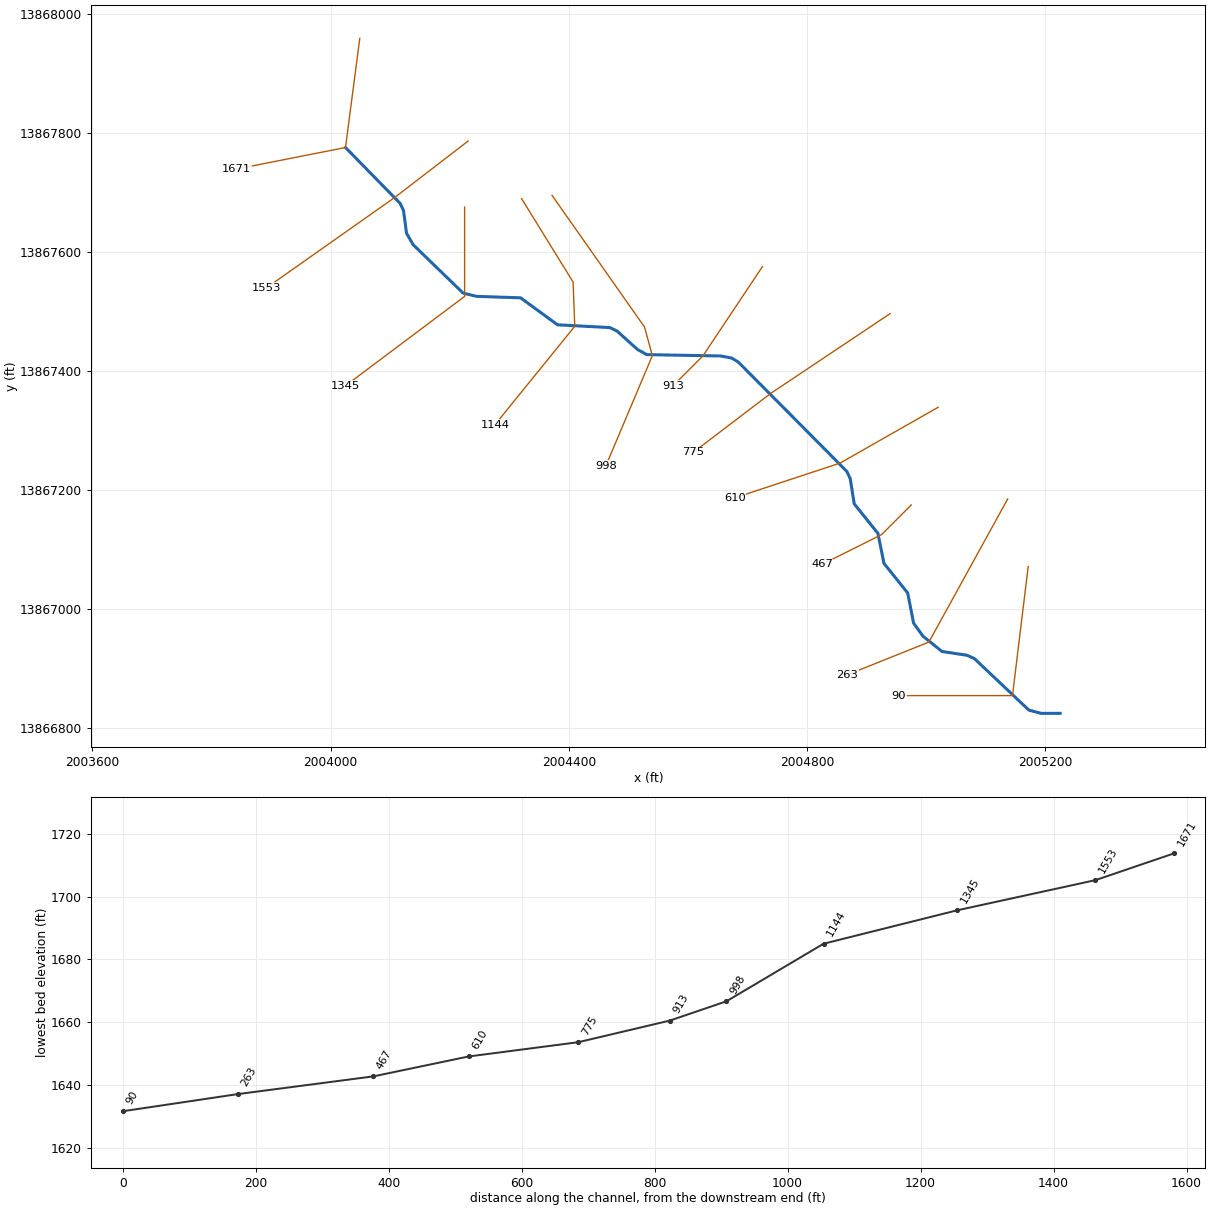
--- Stream0201_DS.prj (project) ---

Proj Title=Stream0201_DS Base Level Engineering
Current Plan=p01
Default Exp/Contr=0.3,0.1
English Units
Geom File=g01
Flow File=f01
Plan File=p01
BEGIN DESCRIPTION:
Stream0201_DS
END DESCRIPTION:

--- Stream0201_DS.p01 (plan) ---

Plan Title=Multiple Run
Short Identifier=Multiple
Geom File=g01
Flow File=f01
Subcritical Flow
K Sum by GR= 0
Std Step Tol= 0.01
Critical Tol= 0.01
Num of Std Step Trials= 20
Max Error Tol= 0.3
Flow Tol Ratio= 0.001
Split Flow NTrial= 30
Split Flow Tol= 0.02
Split Flow Ratio= 0.02
Log Output Level= 0
Friction Slope Method= 1
Unsteady Friction Slope Method= 2
Unsteady Bridges Friction Slope Method= 1
Parabolic Critical Depth
Global Vel Dist=  1 , 1 , 1
Global Log Level= 0
CheckData=True
Encroach Param= -1, 0, 0, 0
BEGIN DESCRIPTION:
Multiple Run
END DESCRIPTION:

--- Stream0201_DS.f01 (steady flow) ---

Flow Title=Multiple
Number of Profiles=7
Profile Names=10-year,25-year,50-year,1pct_min,100-year,1pct_plu,500-year
River Rch & RM= Stream0201_DS,Reach-1,1671
     331     524     697     453     905    1805    1498
Boundary for River Rch & Prof#=Stream0201_DS,Reach-1,1
Up Type=0
Dn Type=3
Dn Slope=0.005
Boundary for River Rch & Prof#=Stream0201_DS,Reach-1,2
Up Type=0
Dn Type=3
Dn Slope=0.005
Boundary for River Rch & Prof#=Stream0201_DS,Reach-1,3
Up Type=0
Dn Type=3
Dn Slope=0.005
Boundary for River Rch & Prof#=Stream0201_DS,Reach-1,4
Up Type=0
Dn Type=3
Dn Slope=0.005
Boundary for River Rch & Prof#=Stream0201_DS,Reach-1,5
Up Type=0
Dn Type=3
Dn Slope=0.005
Boundary for River Rch & Prof#=Stream0201_DS,Reach-1,6
Up Type=0
Dn Type=3
Dn Slope=0.005
Boundary for River Rch & Prof#=Stream0201_DS,Reach-1,7
Up Type=0
Dn Type=3
Dn Slope=0.005

--- Stream0201_DS.g01 (geometry) ---

Geom Title=Existing Conditions

River Reach=Stream0201_DS,Reach-1
Reach XY= 30
      2004025.00     13867775.00      2004116.89     13867681.07
      2004122.48     13867668.95      2004127.52     13867631.03
      2004138.62     13867611.76      2004222.56     13867530.52
      2004245.05     13867525.12      2004319.02     13867522.64
      2004380.97     13867477.35      2004469.02     13867472.64
      2004481.03     13867466.81      2004515.35     13867435.85
      2004530.94     13867427.27      2004655.01     13867425.02
      2004673.53     13867421.46      2004684.80     13867414.52
      2004866.86     13867231.06      2004872.50     13867218.97
      2004879.19     13867176.74      2004918.92     13867127.20
      2004929.16     13867076.72      2004968.89     13867027.16
      2004978.86     13866976.42      2004994.62     13866954.53
      2005026.43     13866928.88      2005068.91     13866922.45
      2005081.03     13866916.83      2005172.49     13866830.33
      2005193.12     13866824.93      2005225.00     13866825.00

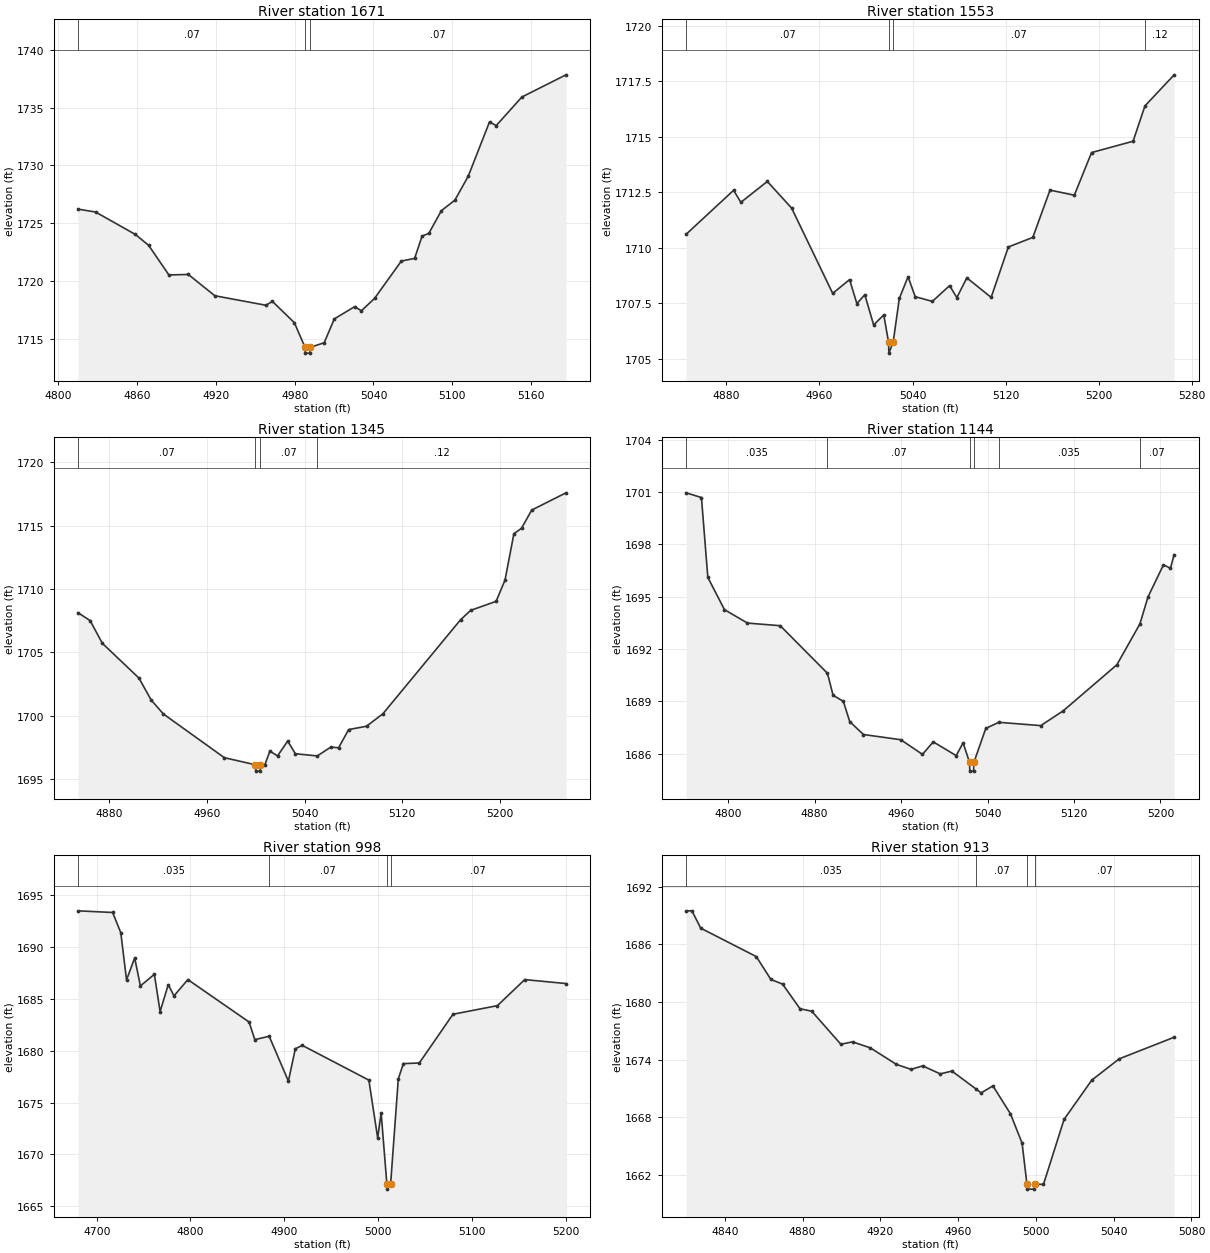
Type RM Length L Ch R = 1,1671,118,118,118
BEGIN DESCRIPTION:
Stream0201_DS 10.0
END DESCRIPTION:
XS GIS Cut Line= 3
      2004049.02     13867958.33      2004025.00     13867775.00
      2003842.02     13867738.91
#Sta/Elev= 30
  4815.1 1726.22  4828.5 1725.97  4858.8 1724.03  4868.9 1723.09  4884.3 1720.53
  4899.1 1720.57  4919.3 1718.73  4958.1 1717.91  4963.1 1718.24  4979.8 1716.40
  4987.9 1714.27  4988.2 1713.77  4991.7 1713.77  4991.9 1714.27  5002.5 1714.67
  5010.2 1716.73  5025.7 1717.79  5030.8 1717.43  5040.8 1718.50  5061.2 1721.73
  5071.3 1721.96  5077.0 1723.89  5082.1 1724.12  5091.7 1726.09  5101.9 1726.99
  5112.1 1729.06  5128.3 1733.76  5133.4 1733.44  5152.9 1735.91  5186.5 1737.83
#Mann=3,-1,0
  4815.1    0.07       0  4987.9    0.05       0  4991.9    0.07       0
Bank Sta=4987.9,4991.9
Exp/Cntr=0.3,0.1

Type RM Length L Ch R = 1,1553,208,208,208
BEGIN DESCRIPTION:
Stream0201_DS 9.0
END DESCRIPTION:
XS GIS Cut Line= 3
      2004230.98     13867785.95      2004108.43     13867691.71
      2003891.90     13867539.10
#Sta/Elev= 30
  4845.4 1710.60  4886.2 1712.58  4892.5 1712.04  4915.2 1712.98  4936.1 1711.78
  4971.4 1707.94  4985.9 1708.56  4992.2 1707.48  4999.0 1707.88  5006.6 1706.52
  5015.3 1706.97  5019.4 1705.75  5019.7 1705.25  5023.4 1705.75  5028.7 1707.72
  5036.2 1708.69  5042.3 1707.79  5057.1 1707.58  5071.9 1708.29  5078.1 1707.75
  5086.7 1708.64  5107.6 1707.76  5122.4 1710.03  5143.4 1710.46  5158.2 1712.59
  5179.1 1712.36  5193.9 1714.28  5229.6 1714.79  5239.8 1716.38  5264.9 1717.78
#Mann=4,-1,0
  4845.4    0.07       0  5019.4    0.05       0  5023.4    0.07       0
  5239.8    0.12       0
Bank Sta=5019.4,5023.4
Exp/Cntr=0.3,0.1

Type RM Length L Ch R = 1,1345,201,201,201
BEGIN DESCRIPTION:
Stream0201_DS 8.0
END DESCRIPTION:
XS GIS Cut Line= 3
      2004225.00     13867675.03      2004225.00     13867525.00
      2004025.02     13867375.02
#Sta/Elev= 30
  4854.3 1708.14  4864.3 1707.51  4874.3 1705.72  4904.3 1702.98  4914.3 1701.25
  4924.3 1700.15  4974.3 1696.70  4999.8 1696.14  5000.1 1695.64  5003.6 1695.64
  5003.8 1696.14  5007.5 1696.14  5011.6 1697.22  5017.9 1696.84  5026.2 1698.01
  5032.5 1697.01  5050.5 1696.84  5061.6 1697.54  5067.9 1697.48  5076.2 1698.92
  5090.8 1699.18  5104.3 1700.17  5167.9 1707.58  5176.2 1708.32  5197.0 1709.03
  5204.3 1710.70  5211.6 1714.36  5217.9 1714.80  5226.2 1716.23  5254.3 1717.59
#Mann=4,-1,0
  4854.3    0.07       0  4999.8    0.05       0  5003.8    0.07       0
  5050.5    0.12       0
Bank Sta=4999.8,5003.8
Exp/Cntr=0.3,0.1

Type RM Length L Ch R = 1,1144,146,146,146
BEGIN DESCRIPTION:
Stream0201_DS 7.0
END DESCRIPTION:
XS GIS Cut Line= 4
      2004320.70     13867689.15      2004407.17     13867549.11
      2004409.94     13867474.85      2004275.97     13867309.64
#Sta/Elev= 30
  4761.1 1700.95  4775.3 1700.68  4781.2 1696.10  4796.6 1694.25  4817.9 1693.48
  4848.2 1693.33  4891.9 1690.60  4897.1 1689.34  4906.6 1688.99  4912.5 1687.83
  4925.2 1687.09  4959.8 1686.79  4979.8 1685.95  4989.8 1686.67  5011.0 1685.88
  5017.4 1686.61  5023.4 1685.49  5023.6 1684.99  5027.1 1684.99  5027.4 1685.49
  5038.4 1687.44  5050.5 1687.79  5089.3 1687.60  5110.1 1688.45  5159.7 1691.09
  5181.0 1693.43  5188.5 1694.98  5202.8 1696.82  5209.3 1696.63  5212.7 1697.40
#Mann=6,-1,0
  4761.1   0.035       0  4891.9    0.07       0  5023.4    0.05       0
  5027.4    0.07       0  5050.5   0.035       0  5181.0    0.07       0
Bank Sta=5023.4,5027.4
Exp/Cntr=0.3,0.1

Type RM Length L Ch R = 1,998,85,85,85
BEGIN DESCRIPTION:
Stream0201_DS 6.0
END DESCRIPTION:
XS GIS Cut Line= 4
      2004371.81     13867694.70      2004527.12     13867473.53
      2004540.22     13867425.54      2004462.32     13867240.90
#Sta/Elev= 30
  4680.0 1693.49  4717.0 1693.33  4725.7 1691.38  4731.8 1686.83  4740.5 1688.95
  4746.6 1686.25  4761.5 1687.37  4767.6 1683.78  4776.3 1686.37  4782.4 1685.29
  4797.2 1686.86  4862.5 1682.77  4868.6 1681.07  4883.9 1681.40  4904.4 1677.07
  4911.8 1680.19  4919.2 1680.52  4990.2 1677.17  4999.6 1671.60  5003.3 1674.00
  5009.4 1667.16  5009.7 1666.66  5013.4 1667.16  5021.6 1677.29  5027.0 1678.76
  5044.0 1678.82  5079.9 1683.52  5127.3 1684.35  5156.4 1686.86  5200.4 1686.48
#Mann=4,-1,0
  4680.0   0.035       0  4883.9    0.07       0  5009.4    0.05       0
  5013.4    0.07       0
Bank Sta=5009.4,5013.4
Exp/Cntr=0.3,0.1

Type RM Length L Ch R = 1,913,138,138,138
BEGIN DESCRIPTION:
Stream0201_DS 5.0
END DESCRIPTION:
XS GIS Cut Line= 3
      2004725.01     13867575.01      2004625.00     13867425.00
      2004575.00     13867375.00
#Sta/Elev= 30
  4820.1 1689.47  4823.1 1689.47  4827.6 1687.67  4856.2 1684.71  4863.7 1682.33
  4869.7 1681.85  4878.7 1679.28  4884.7 1679.03  4899.7 1675.59  4905.7 1675.84
  4914.8 1675.22  4928.3 1673.49  4935.8 1672.98  4941.8 1673.34  4950.8 1672.51
  4956.8 1672.80  4969.4 1670.91  4971.8 1670.53  4977.9 1671.26  4986.9 1668.36
  4992.9 1665.30  4995.4 1661.02  4995.6 1660.52  4999.1 1660.52  4999.4 1661.02
  5003.9 1661.02  5014.5 1667.78  5028.7 1671.85  5042.8 1674.07  5071.1 1676.32
#Mann=4,-1,0
  4820.1   0.035       0  4969.4    0.07       0  4995.4    0.05       0
  4999.4    0.07       0
Bank Sta=4995.4,4999.4
Exp/Cntr=0.3,0.1

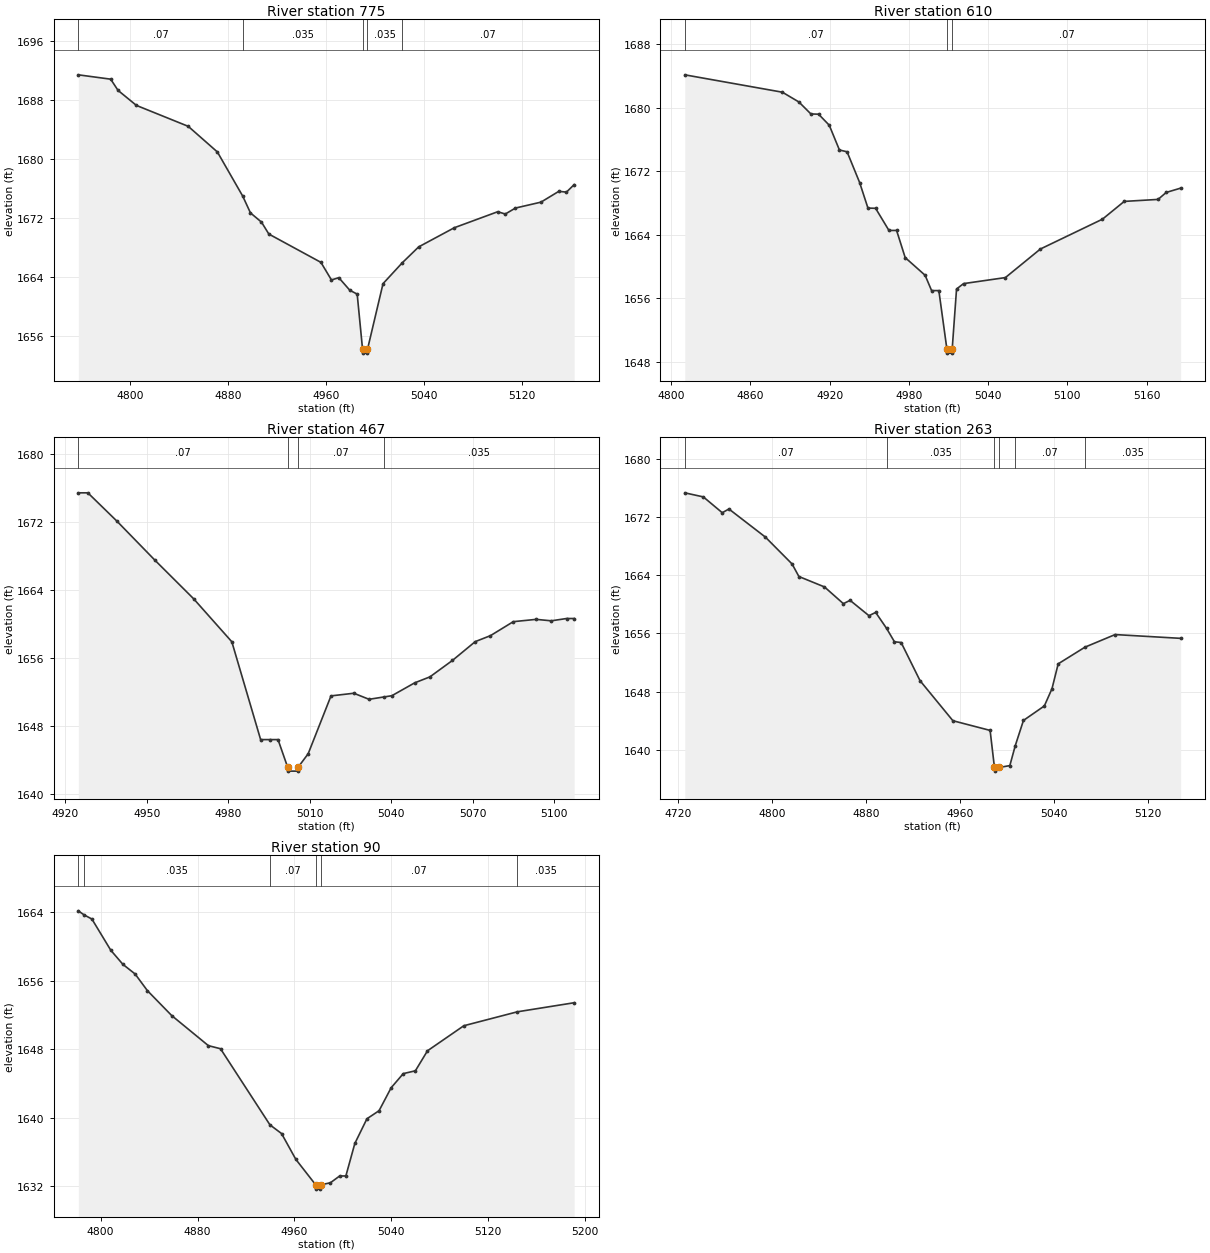
Type RM Length L Ch R = 1,775,165,165,165
BEGIN DESCRIPTION:
Stream0201_DS 4.0
END DESCRIPTION:
XS GIS Cut Line= 3
      2004939.60     13867496.24      2004738.38     13867361.79
      2004608.93     13867263.23
#Sta/Elev= 30
  4758.0 1691.39  4784.4 1690.80  4790.4 1689.28  4805.4 1687.24  4847.7 1684.40
  4871.5 1680.92  4892.2 1674.92  4898.5 1672.65  4907.5 1671.40  4913.5 1669.78
  4956.0 1665.94  4964.6 1663.55  4970.6 1663.86  4979.6 1662.15  4985.6 1661.63
  4990.0 1654.12  4990.3 1653.62  4993.8 1653.62  4994.0 1654.12  5006.7 1663.05
  5022.4 1665.88  5035.8 1668.04  5064.9 1670.64  5100.3 1672.81  5106.5 1672.50
  5114.8 1673.31  5135.6 1674.11  5150.2 1675.58  5156.4 1675.47  5162.7 1676.49
#Mann=5,-1,0
  4758.0    0.07       0  4892.2   0.035       0  4990.0   0.035       0
  4994.0   0.035       0  5022.4    0.07       0
Bank Sta=4990,4994
Exp/Cntr=0.3,0.1

Type RM Length L Ch R = 1,610,143,143,143
BEGIN DESCRIPTION:
Stream0201_DS 3.0
END DESCRIPTION:
XS GIS Cut Line= 3
      2005020.11     13867338.88      2004855.22     13867245.09
      2004678.78     13867186.86
#Sta/Elev= 30
  4810.3 1684.14  4884.2 1681.95  4896.7 1680.72  4905.8 1679.21  4911.6 1679.18
  4919.7 1677.79  4927.4 1674.67  4933.2 1674.44  4942.7 1670.57  4949.0 1667.35
  4954.8 1667.32  4964.9 1664.53  4970.7 1664.53  4977.2 1661.11  4992.3 1658.88
  4997.2 1656.95  5002.7 1656.95  5008.8 1649.57  5009.0 1649.07  5012.5 1649.07
  5012.8 1649.57  5016.1 1657.15  5021.4 1657.83  5053.1 1658.59  5079.6 1662.19
  5126.6 1665.95  5143.1 1668.19  5168.7 1668.44  5174.9 1669.32  5185.8 1669.86
#Mann=3,-1,0
  4810.3    0.07       0  5008.8    0.05       0  5012.8    0.07       0
Bank Sta=5008.8,5012.8
Exp/Cntr=0.3,0.1

Type RM Length L Ch R = 1,467,204,204,204
BEGIN DESCRIPTION:
Stream0201_DS 2.0
END DESCRIPTION:
XS GIS Cut Line= 3
      2004974.97     13867174.97      2004925.00     13867125.00
      2004824.97     13867074.99
#Sta/Elev= 29
  4924.8 1675.40  4928.3 1675.40  4938.9 1672.11  4953.0 1667.49  4967.2 1662.98
  4981.3 1657.92  4991.9 1646.44  4995.5 1646.44  4998.3 1646.44  5001.8 1643.24
  5002.1 1642.74  5005.6 1642.74  5005.8 1643.24  5009.4 1644.78  5017.8 1651.57
  5026.2 1651.88  5031.8 1651.17  5037.2 1651.44  5040.2 1651.59  5048.6 1653.10
  5054.2 1653.80  5062.5 1655.73  5070.9 1657.94  5076.5 1658.64  5084.9 1660.28
  5093.3 1660.55  5098.9 1660.38  5104.5 1660.65  5107.3 1660.65
#Mann=4,-1,0
  4924.8    0.07       0  5001.8    0.05       0  5005.8    0.07       0
  5037.2   0.035       0
Bank Sta=5001.8,5005.8
Exp/Cntr=0.3,0.1

Type RM Length L Ch R = 1,263,173,173,173
BEGIN DESCRIPTION:
Stream0201_DS 1.0
END DESCRIPTION:
XS GIS Cut Line= 3
      2005136.93     13867185.09      2005004.52     13866944.63
      2004867.25     13866889.59
#Sta/Elev= 30
  4725.5 1675.30  4741.3 1674.74  4757.4 1672.57  4763.1 1673.08  4794.1 1669.23
  4816.9 1665.53  4822.7 1663.81  4844.5 1662.38  4860.6 1660.08  4866.3 1660.54
  4882.4 1658.43  4888.1 1658.88  4897.4 1656.69  4904.1 1654.85  4909.8 1654.75
  4925.9 1649.51  4953.9 1644.01  4985.6 1642.68  4989.3 1637.59  4989.5 1637.09
  4993.3 1637.59  5002.4 1637.85  5007.0 1640.57  5014.0 1644.05  5031.8 1646.04
  5038.3 1648.40  5043.6 1651.82  5066.4 1654.11  5092.1 1655.84  5147.9 1655.32
#Mann=6,-1,0
  4725.5    0.07       0  4897.4   0.035       0  4989.3   0.035       0
  4993.3   0.035       0  5007.0    0.07       0  5066.4   0.035       0
Bank Sta=4989.3,4993.3
Exp/Cntr=0.3,0.1

Type RM Length L Ch R = 1,90,0,0,0
BEGIN DESCRIPTION:
Stream0201_DS 0.0
END DESCRIPTION:
XS GIS Cut Line= 3
      2005171.30     13867071.57      2005144.90     13866854.77
      2004953.90     13866854.76
#Sta/Elev= 30
  4781.6 1664.18  4786.4 1663.70  4792.8 1663.22  4808.4 1659.57  4818.4 1657.92
  4828.5 1656.79  4838.6 1654.85  4858.7 1651.93  4889.0 1648.41  4899.0 1648.05
  4939.8 1639.15  4949.4 1638.13  4961.2 1635.11  4977.6 1632.13  4977.9 1631.63
  4981.4 1631.63  4981.6 1632.13  4989.7 1632.37  4997.4 1633.17  5002.5 1633.17
  5009.9 1636.97  5019.9 1639.86  5029.9 1640.80  5039.9 1643.49  5049.9 1645.14
  5059.9 1645.47  5069.9 1647.81  5099.9 1650.74  5144.1 1652.37  5191.0 1653.43
#Mann=6,-1,0
  4781.6    0.07       0  4786.4   0.035       0  4939.8    0.07       0
  4977.6    0.05       0  4981.6    0.07       0  5144.1   0.035       0
Bank Sta=4977.6,4981.6
Exp/Cntr=0.3,0.1

Chan Stop Cuts=-1