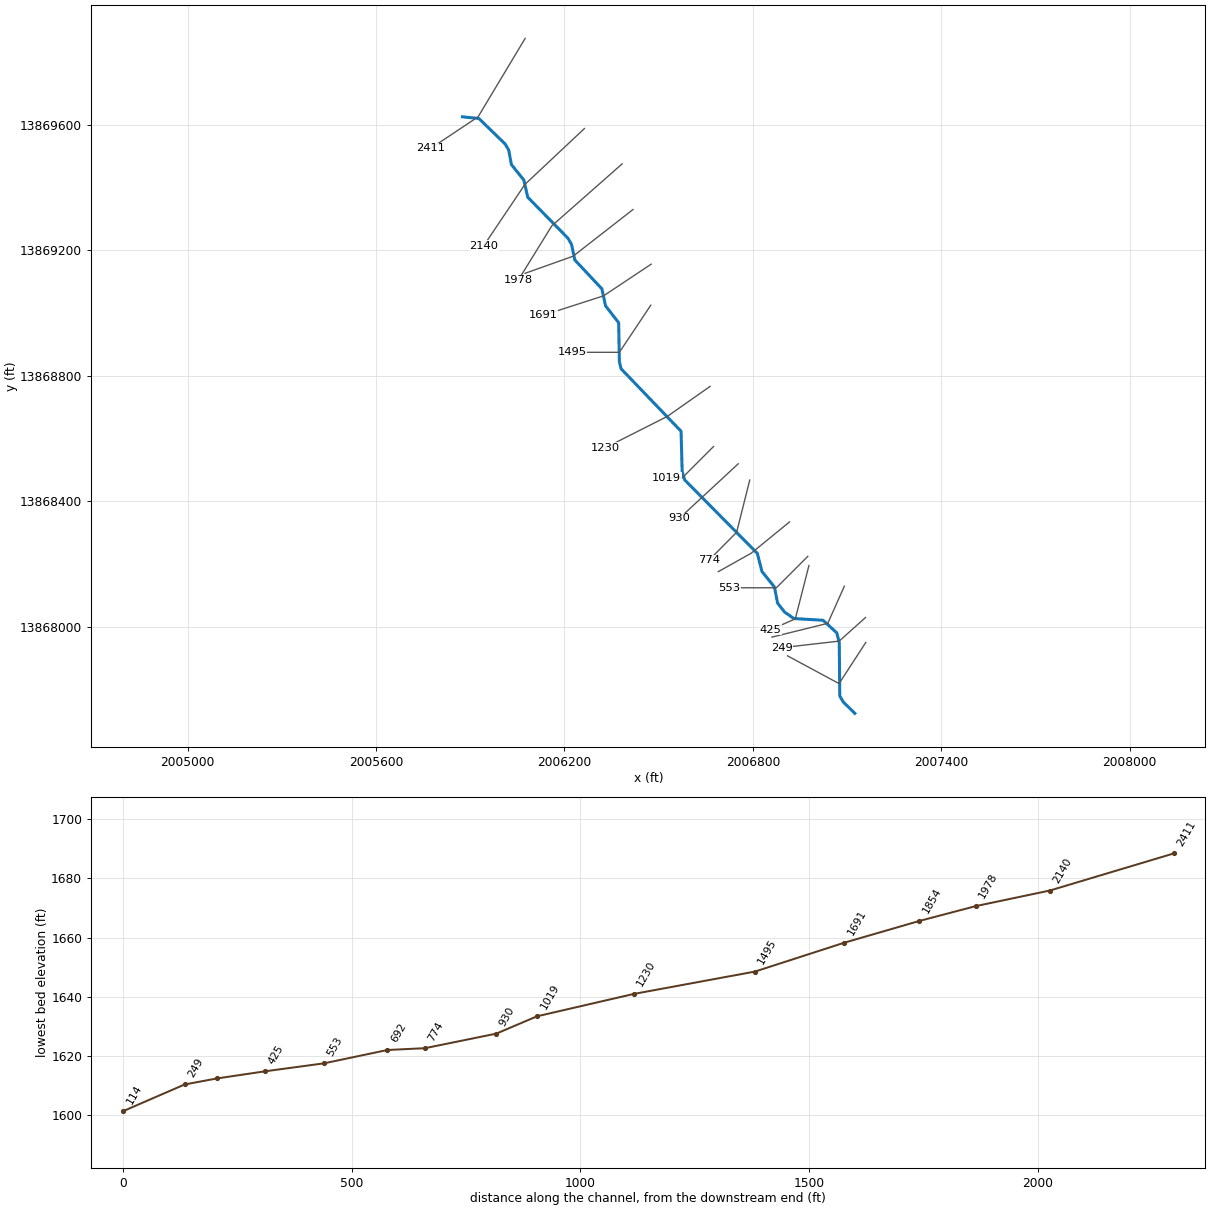
--- Stream0202_DS.prj (project) ---

Proj Title=Stream0202_DS Base Level Engineering
Current Plan=p01
Default Exp/Contr=0.3,0.1
English Units
Geom File=g01
Flow File=f01
Plan File=p01
Y Axis Title=Elevation
X Axis Title(PF)=Main Channel Distance
X Axis Title(XS)=Station
BEGIN DESCRIPTION:
Stream0202_DS
END DESCRIPTION:
DSS Export Rating Curves= 0
DSS Export Rating Curve Sorted= 0
DSS Export Volume Flow Curves= 0
DXF OffsetX= 0
DXF OffsetY= 0
DXF ScaleX= 1
DXF ScaleY= 10

--- Stream0202_DS.p01 (plan) ---

Plan Title=Multiple Run
Short Identifier=Multiple
Geom File=g01
Flow File=f01
Subcritical Flow
K Sum by GR= 0
Std Step Tol= 0.01
Critical Tol= 0.01
Num of Std Step Trials= 20
Max Error Tol= 0.3
Flow Tol Ratio= 0.001
Split Flow NTrial= 30
Split Flow Tol= 0.02
Split Flow Ratio= 0.02
Log Output Level= 0
Friction Slope Method= 1
Unsteady Friction Slope Method= 2
Unsteady Bridges Friction Slope Method= 1
Parabolic Critical Depth
Global Vel Dist=  1 , 1 , 1
Global Log Level= 0
CheckData=True
Encroach Param= -1, 0, 0, 0
BEGIN DESCRIPTION:
Multiple Run
END DESCRIPTION:

--- Stream0202_DS.f01 (steady flow) ---

Flow Title=Multiple
Number of Profiles=7
Profile Names=10-year,25-year,50-year,1pct_min,100-year,1pct_plu,500-year
River Rch & RM= Stream0202_DS,Reach-1,2411
     314     493     654     423     844    1684    1383
Boundary for River Rch & Prof#=Stream0202_DS,Reach-1,1
Up Type=0
Dn Type=3
Dn Slope=0.005
Boundary for River Rch & Prof#=Stream0202_DS,Reach-1,2
Up Type=0
Dn Type=3
Dn Slope=0.005
Boundary for River Rch & Prof#=Stream0202_DS,Reach-1,3
Up Type=0
Dn Type=3
Dn Slope=0.005
Boundary for River Rch & Prof#=Stream0202_DS,Reach-1,4
Up Type=0
Dn Type=3
Dn Slope=0.005
Boundary for River Rch & Prof#=Stream0202_DS,Reach-1,5
Up Type=0
Dn Type=3
Dn Slope=0.005
Boundary for River Rch & Prof#=Stream0202_DS,Reach-1,6
Up Type=0
Dn Type=3
Dn Slope=0.005
Boundary for River Rch & Prof#=Stream0202_DS,Reach-1,7
Up Type=0
Dn Type=3
Dn Slope=0.005

--- Stream0202_DS.g01 (geometry) ---

Geom Title=Existing Conditions
Program Version=4.10

River Reach=Stream0202_DS   ,Reach-1
Reach XY= 30
        2005875.       13869625.      2005927.54      13869619.7
       2006011.4     13869538.24      2006022.51     13869518.97
       2006031.1     13869472.81      2006070.81     13869423.26
      2006083.14     13869368.94      2006211.37     13869238.21
      2006222.47     13869218.95      2006233.18     13869168.96
      2006319.16     13869077.29      2006331.14     13869022.83
      2006372.75     13868969.07      2006374.98     13868844.99
      2006380.47     13868822.55      2006571.46     13868623.53
      2006574.98     13868494.99      2006582.82     13868468.81
      2006814.24     13868234.68      2006829.19     13868176.73
      2006868.89     13868127.16      2006878.85     13868076.39
       2006901.1     13868047.72      2006930.71     13868027.08
      2007023.75     13868021.49      2007067.32     13867981.52
      2007075.33     13867950.22      2007076.89     13867780.78
      2007087.92      13867761.5        2007125.       13867725.

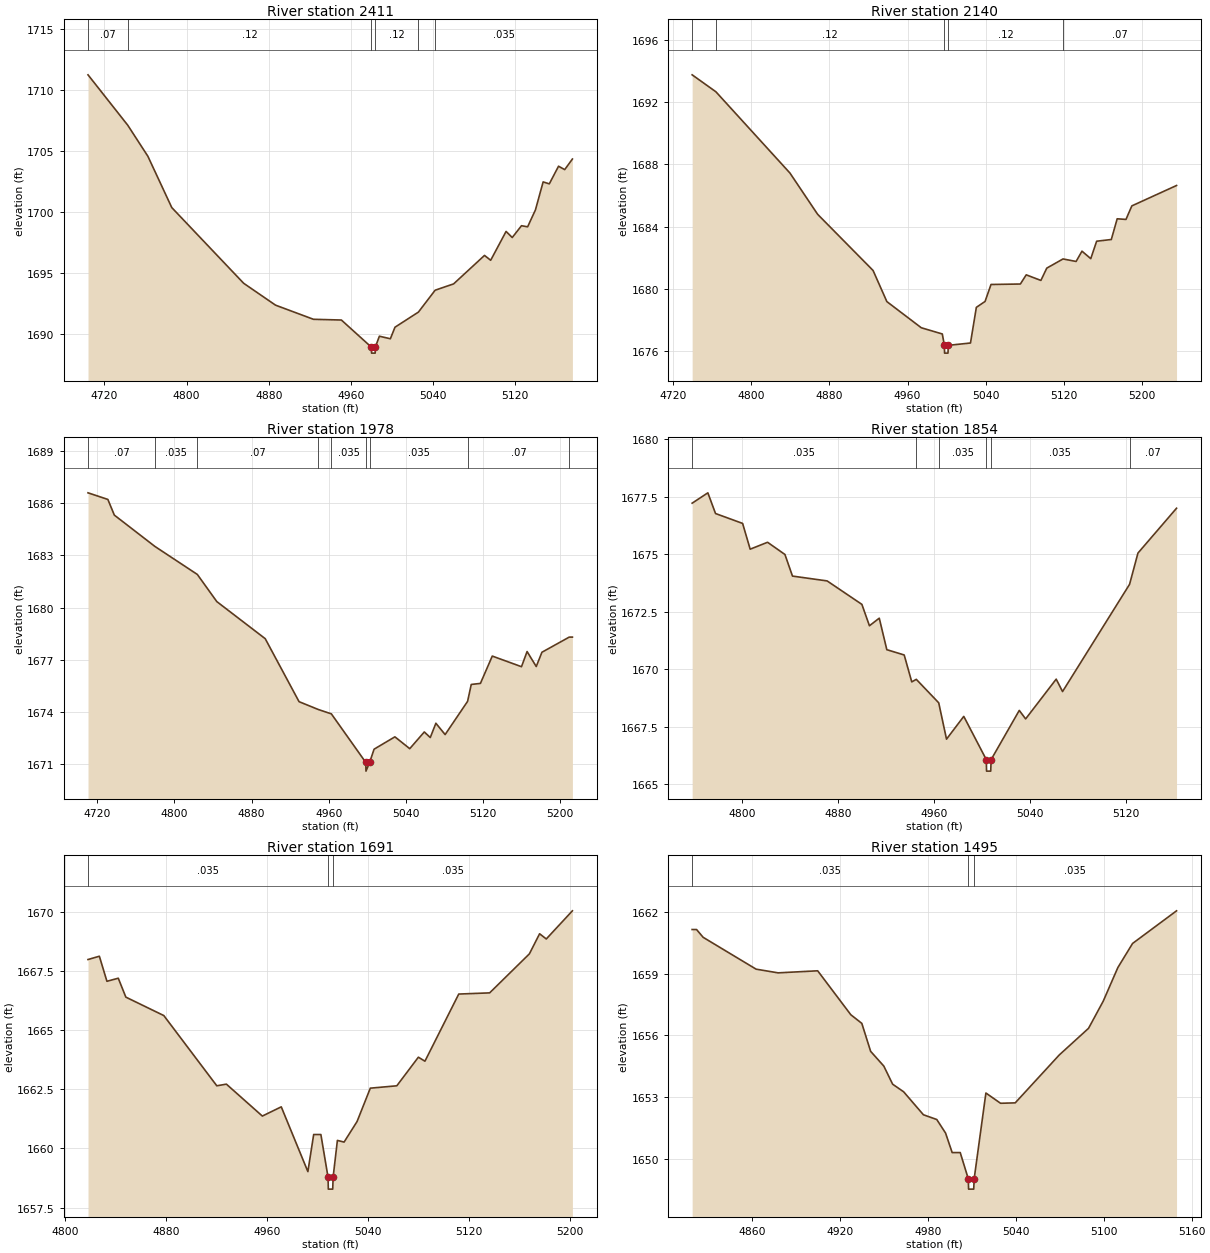
Type RM Length L Ch R = 1 ,2411    ,271,271,271
BEGIN DESCRIPTION:
Stream0202_DS 15.0
END DESCRIPTION:
XS GIS Cut Line= 3
        2006075.     13869874.99        2005925.       13869625.
      2005775.01     13869525.01
#Sta/Elev= 30
    4704 1711.26  4742.7 1707.12  4762.3 1704.57  4785.6 1700.35  4855.6 1694.13
  4886.7 1692.33  4923.6 1691.17  4950.8 1691.11  4979.9 1688.89  4980.2 1688.39
  4983.7 1688.39  4983.9 1688.89  4987.8 1689.78  4998.5 1689.57    5003 1690.52
  5025.8 1691.76  5042.1 1693.56  5060.1 1694.08  5090.2 1696.42  5096.2 1696.02
  5111.2 1698.39  5117.2 1697.89  5126.2 1698.86  5132.2 1698.77  5139.8 1700.16
  5147.3 1702.46  5153.3  1702.3  5162.3 1703.75  5168.3 1703.47  5175.8 1704.34
#Mann= 6 ,-1 , 0
    4704     .07       0  4742.7     .12       0  4979.9     .05       0
  4983.9     .12       0  5025.8     .07       0  5042.1    .035       0
Bank Sta=4979.9,4983.9
XS Rating Curve= 0 ,0
Exp/Cntr=0.3,0.1

Type RM Length L Ch R = 1 ,2140    ,162,162,162
BEGIN DESCRIPTION:
Stream0202_DS 14.0
END DESCRIPTION:
XS GIS Cut Line= 3
      2006263.67     13869587.72        2006074.     13869409.59
      2005942.97     13869214.39
#Sta/Elev= 30
  4739.8 1693.75  4764.1 1692.66  4839.8 1687.44  4868.1 1684.79  4924.8 1681.18
  4938.9 1679.18  4974.1  1677.5  4995.6  1677.1  4997.7 1676.37  4997.9 1675.87
  5001.4 1675.87  5001.7 1676.37  5024.4 1676.52  5030.4 1678.81  5039.3 1679.19
  5045.4 1680.28  5075.4 1680.31  5081.4  1680.9  5096.4 1680.54  5102.4 1681.33
    5119 1681.92  5132.4 1681.76  5138.4 1682.42  5147.4 1681.94  5153.4 1683.06
  5168.4 1683.17  5174.4  1684.5  5183.4 1684.46  5189.4 1685.33  5235.1 1686.64
#Mann= 5 ,-1 , 0
  4739.8     .07       0  4764.1     .12       0  4997.7     .05       0
  5001.7     .12       0    5119     .07       0
Bank Sta=4997.7,5001.7
XS Rating Curve= 0 ,0
Exp/Cntr=0.3,0.1

Type RM Length L Ch R = 1 ,1978    ,124,124,124
BEGIN DESCRIPTION:
Stream0202_DS 13.0
END DESCRIPTION:
XS GIS Cut Line= 3
      2006383.79     13869475.14      2006159.78     13869277.78
      2006052.66     13869104.34
#Sta/Elev= 30
  4710.4  1686.6    4731 1686.22  4737.7 1685.32  4779.8 1683.52  4823.8 1681.91
    4844 1680.35  4894.2 1678.22  4929.3  1674.6  4949.3 1674.15  4962.8  1673.9
  4998.5 1671.11  4998.7 1670.61  5002.5 1671.11  5007.1 1671.87  5028.7 1672.58
  5044.1  1671.9  5059.2 1672.86  5065.4 1672.54  5071.2 1673.36  5080.8 1672.71
  5104.1 1674.62  5107.9 1675.59  5117.4 1675.65  5129.7 1677.22    5160 1676.61
  5165.8 1677.48  5175.3 1676.62  5181.2 1677.44  5209.5 1678.31  5212.8 1678.31
#Mann= 9 ,-1 , 0
  4710.4     .07       0  4779.8    .035       0  4823.8     .07       0
  4949.3     .12       0  4962.8    .035       0  4998.5    .035       0
  5002.5    .035       0  5104.1     .07       0  5209.5    .035       0
Bank Sta=4998.5,5002.5
XS Rating Curve= 0 ,0
Exp/Cntr=0.3,0.1

Type RM Length L Ch R = 1 ,1854    ,163,163,163
BEGIN DESCRIPTION:
Stream0202_DS 12.0
END DESCRIPTION:
XS GIS Cut Line= 3
      2006418.27     13869329.68      2006227.54     13869181.05
      2006074.67     13869126.56
#Sta/Elev= 30
  4758.2 1677.22  4771.3 1677.67  4777.7 1676.77  4800.3 1676.34  4806.6 1675.22
  4821.1 1675.52  4835.6 1674.99  4841.9 1674.05  4870.8 1673.84  4899.8 1672.82
  4906.1 1671.89  4914.3 1672.22  4920.6 1670.85  4935.1 1670.62  4941.4 1669.45
  4945.2 1669.56  4963.9 1668.54  4970.4 1666.96  4984.8 1667.95  5003.6 1666.07
  5003.8 1665.57  5007.3 1665.57  5007.6 1666.07  5031.1 1668.21  5036.4 1667.84
  5061.9 1669.57  5067.2 1669.03  5123.1 1673.69  5130.1 1675.05  5162.3    1677
#Mann= 6 ,-1 , 0
  4758.2    .035       0  4945.2     .07       0  4963.9    .035       0
  5003.6    .035       0  5007.6    .035       0  5123.1     .07       0
Bank Sta=5003.6,5007.6
XS Rating Curve= 0 ,0
Exp/Cntr=0.3,0.1

Type RM Length L Ch R = 1 ,1691    ,196,196,196
BEGIN DESCRIPTION:
Stream0202_DS 11.0
END DESCRIPTION:
XS GIS Cut Line= 3
       2006476.3     13869155.73      2006324.68     13869054.87
      2006132.52     13868992.91
#Sta/Elev= 30
  4817.9 1667.99  4826.9 1668.13  4832.9 1667.07  4841.9  1667.2  4847.9  1666.4
    4878 1665.62    4920 1662.65  4927.6 1662.72  4956.1 1661.37  4971.1 1661.76
  4992.2 1659.02  4996.8 1660.59  5002.5 1660.59  5008.2 1658.78  5008.4 1658.28
  5011.9 1658.28  5012.2 1658.78  5015.6 1660.34  5020.9 1660.27  5031.2 1661.14
  5041.7 1662.55  5062.7 1662.65  5079.8 1663.86    5085 1663.69  5111.8 1666.53
  5136.3 1666.58  5167.8 1668.23  5175.9 1669.08  5181.2 1668.86  5201.9 1670.05
#Mann= 3 ,-1 , 0
  4817.9    .035       0  5008.2    .035       0  5012.2    .035       0
Bank Sta=5008.2,5012.2
XS Rating Curve= 0 ,0
Exp/Cntr=0.3,0.1

Type RM Length L Ch R = 1 ,1495    ,265,265,265
BEGIN DESCRIPTION:
Stream0202_DS 10.0
END DESCRIPTION:
XS GIS Cut Line= 3
        2006475.       13869025.        2006375.       13868875.
      2006224.98       13868875.
#Sta/Elev= 30
  4819.4 1661.15  4822.4 1661.15  4826.9 1660.77    4863 1659.22    4878 1659.04
    4905 1659.14  4927.6    1657  4935.1 1656.58  4941.1 1655.22  4950.1  1654.5
  4956.1 1653.62  4963.6 1653.25  4977.1 1652.13  4986.2  1651.9  4992.2 1651.24
  4996.7 1650.29  5002.2 1650.29  5007.7 1649.01  5007.9 1648.51  5011.4 1648.51
  5011.7 1649.01  5019.7 1653.19  5029.7 1652.69  5039.7 1652.71  5069.7 1655.04
  5089.7 1656.34  5099.7 1657.66  5109.7  1659.3  5119.7 1660.47  5149.7 1662.06
#Mann= 3 ,-1 , 0
  4819.4    .035       0  5007.7    .035       0  5011.7    .035       0
Bank Sta=5007.7,5011.7
XS Rating Curve= 0 ,0
Exp/Cntr=0.3,0.1

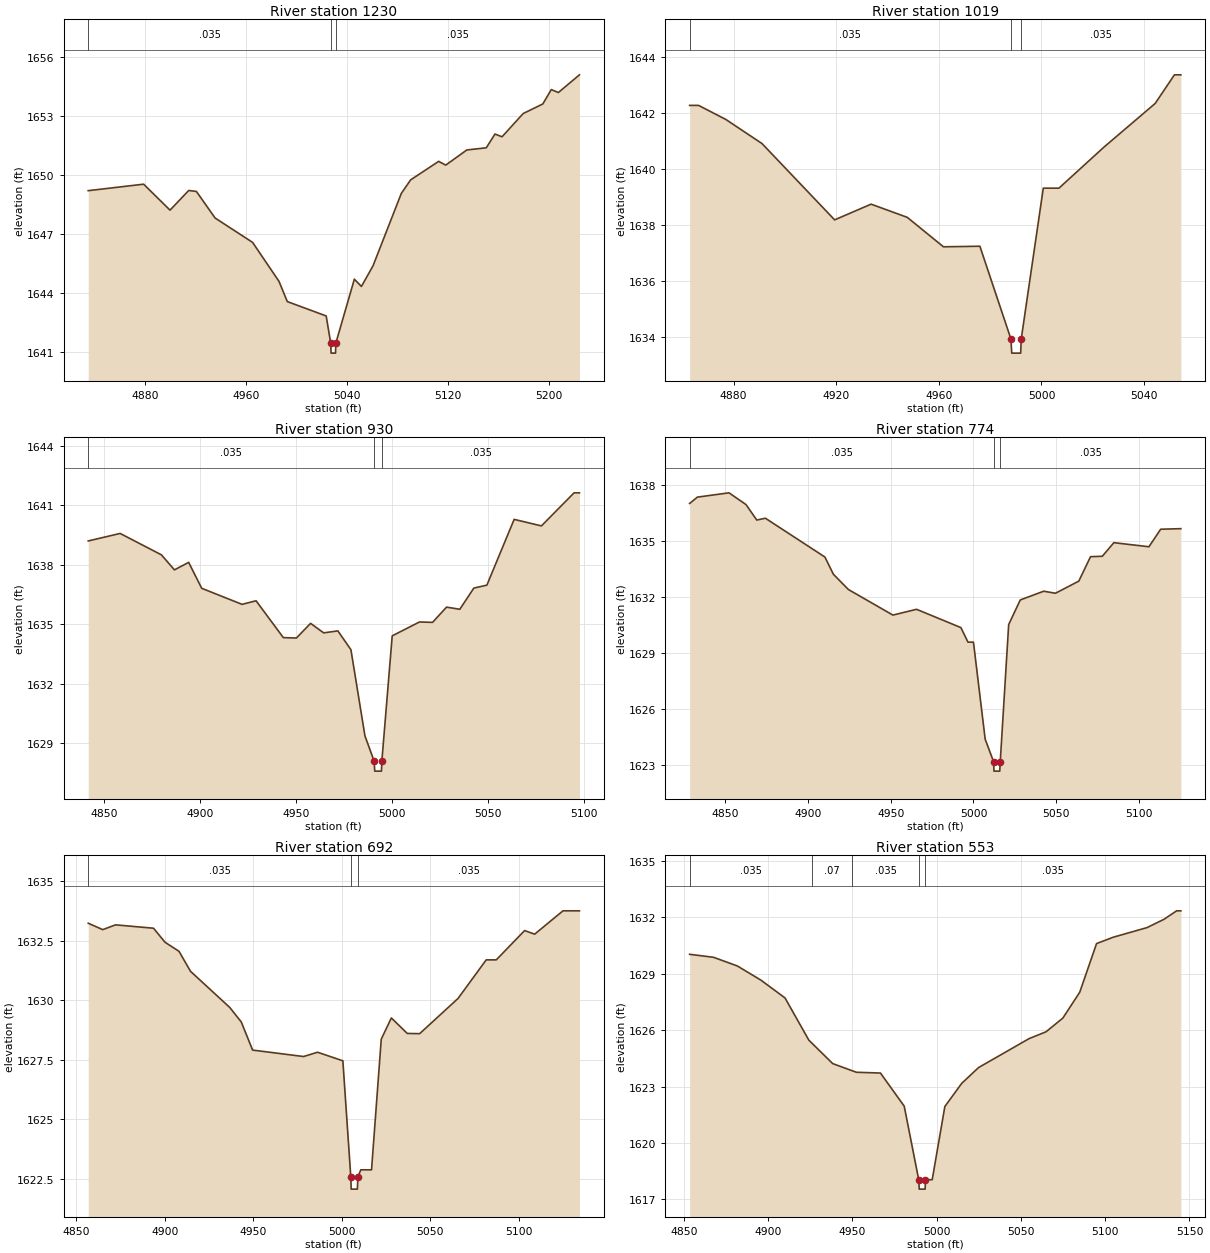
Type RM Length L Ch R = 1 ,1230    ,211,211,211
BEGIN DESCRIPTION:
Stream0202_DS 9.0
END DESCRIPTION:
XS GIS Cut Line= 3
      2006664.03     13868766.54      2006527.95       13868671.
      2006329.11     13868570.42
#Sta/Elev= 30
  4834.8 1649.22  4878.7 1649.55  4899.6 1648.23  4914.4 1649.23  4920.5 1649.18
  4935.3 1647.83    4965 1646.59  4985.9 1644.61  4992.5 1643.58  5023.3 1642.85
  5026.9 1641.46  5027.2 1640.96  5030.7 1640.96  5030.9 1641.46  5045.6 1644.72
  5051.2 1644.35  5060.4  1645.4  5082.8 1649.08  5090.2 1649.77  5112.4 1650.71
    5118 1650.52  5134.7 1651.29  5150.1  1651.4    5157  1652.1  5162.6 1651.96
  5179.3 1653.14  5194.9 1653.63  5201.6 1654.36  5207.2 1654.21  5223.9 1655.11
#Mann= 3 ,-1 , 0
  4834.8    .035       0  5026.9    .035       0  5030.9    .035       0
Bank Sta=5026.9,5030.9
XS Rating Curve= 0 ,0
Exp/Cntr=0.3,0.1

Type RM Length L Ch R = 1 ,1019    ,89,89,89
BEGIN DESCRIPTION:
Stream0202_DS 8.0
END DESCRIPTION:
XS GIS Cut Line= 3
      2006674.97     13868574.97        2006575.       13868475.
      2006524.97       13868475.
#Sta/Elev= 20
  4862.9 1642.26  4866.4 1642.26    4877 1641.76  4891.1  1640.9  4919.4 1638.18
  4933.6 1638.74  4947.7 1638.27  4961.8 1637.22    4976 1637.24  4988.1 1633.93
  4988.4 1633.43  4991.9 1633.43  4992.1 1633.93  5000.7 1639.31  5004.3 1639.31
  5006.8 1639.31  5024.3 1640.77  5044.3 1642.33  5051.8 1643.35  5054.3 1643.35
#Mann= 3 ,-1 , 0
  4862.9    .035       0  4988.1    .035       0  4992.1    .035       0
Bank Sta=4988.1,4992.1
XS Rating Curve= 0 ,0
Exp/Cntr=0.3,0.1

Type RM Length L Ch R = 1 ,930     ,156,156,156
BEGIN DESCRIPTION:
Stream0202_DS 7.0
END DESCRIPTION:
XS GIS Cut Line= 2
      2006753.59     13868519.92      2006565.88     13868346.14
#Sta/Elev= 30
  4841.7  1639.2  4858.3 1639.58  4879.8  1638.5  4886.6 1637.74    4894 1638.12
  4900.8 1636.81  4921.8    1636  4929.1 1636.18  4943.3 1634.32  4950.1  1634.3
  4957.5 1635.04  4964.3 1634.56  4971.7 1634.66  4978.5 1633.71  4985.8 1629.36
  4990.6 1628.08  4990.9 1627.58  4994.4 1627.58  4994.6 1628.08    5000 1634.41
  5014.2 1635.11    5021 1635.09  5028.3 1635.86  5035.2 1635.75  5042.5 1636.82
  5049.3 1636.97  5063.5 1640.29  5077.7 1639.96  5094.7 1641.63  5097.5 1641.63
#Mann= 3 ,-1 , 0
  4841.7    .035       0  4990.6    .035       0  4994.6    .035       0
Bank Sta=4990.6,4994.6
XS Rating Curve= 0 ,0
Exp/Cntr=0.3,0.1

Type RM Length L Ch R = 1 ,774     ,82,82,82
BEGIN DESCRIPTION:
Stream0202_DS 6.0
END DESCRIPTION:
XS GIS Cut Line= 3
      2006790.24      13868468.1      2006748.38     13868301.69
      2006660.09     13868212.64
#Sta/Elev= 30
  4828.4 1637.01  4833.1 1637.35  4852.2 1637.58  4862.5 1636.95    4869 1636.12
  4874.2 1636.22  4910.2 1634.14  4915.3 1633.22  4924.4  1632.4  4951.3 1631.03
  4965.6 1631.34  4992.4 1630.36  4996.7 1629.58    5000 1629.58  5007.1 1624.38
  5012.2 1623.17  5012.4 1622.67  5015.9 1622.67  5016.2 1623.17  5021.3 1630.52
  5028.3 1631.84  5042.5 1632.31  5049.6  1632.2  5063.7 1632.85  5070.8 1634.16
  5077.9 1634.18  5084.9 1634.91  5106.1 1634.69  5113.2 1635.63  5125.4 1635.66
#Mann= 3 ,-1 , 0
  4828.4    .035       0  5012.2    .035       0  5016.2    .035       0
Bank Sta=5012.2,5016.2
XS Rating Curve= 0 ,0
Exp/Cntr=0.3,0.1

Type RM Length L Ch R = 1 ,692     ,139,139,139
BEGIN DESCRIPTION:
Stream0202_DS 5.0
END DESCRIPTION:
XS GIS Cut Line= 3
      2006916.94     13868334.73      2006795.21     13868235.38
      2006690.18     13868176.38
#Sta/Elev= 30
  4856.8 1633.23    4865 1632.96  4872.2 1633.16  4893.7 1633.02  4900.2 1632.43
  4908.1 1632.05  4914.6 1631.21  4936.8 1629.69  4943.3 1629.08  4949.7  1627.9
  4978.5 1627.63  4986.4 1627.81  5000.7 1627.45  5005.2 1622.56  5005.4 1622.06
  5008.9 1622.06  5009.2 1622.56  5010.8 1622.87  5016.9 1622.87  5022.4 1628.36
  5028.1 1629.25  5037.1  1628.6  5044.1 1628.59  5065.8 1630.07  5081.7 1631.69
  5087.4 1631.69  5103.4 1632.92  5109.1 1632.77  5125.1 1633.75  5134.4 1633.75
#Mann= 3 ,-1 , 0
  4856.8    .035       0  5005.2    .035       0  5009.2    .035       0
Bank Sta=5005.2,5009.2
XS Rating Curve= 0 ,0
Exp/Cntr=0.3,0.1

Type RM Length L Ch R = 1 ,553     ,128,128,128
BEGIN DESCRIPTION:
Stream0202_DS 4.0
END DESCRIPTION:
XS GIS Cut Line= 3
      2006975.01     13868225.01        2006875.       13868125.
      2006725.04       13868125.
#Sta/Elev= 30
  4853.5 1630.03  4867.7 1629.87  4881.8 1629.41  4895.9 1628.65  4910.1 1627.71
  4924.2 1625.47    4926 1625.31  4938.4 1624.22    4950 1623.84  4952.5 1623.76
  4966.7 1623.72  4980.8 1621.96  4989.4 1618.05  4989.7 1617.55  4993.2 1617.55
  4993.4 1618.05  4997.4 1618.05  5004.9 1621.94  5014.9 1623.17  5024.9 1624.01
  5054.9 1625.55  5064.9 1625.91  5074.9 1626.64  5084.9 1628.01  5094.9  1630.6
  5104.9 1630.94  5124.9 1631.45  5134.9 1631.89  5142.4 1632.34  5144.9 1632.34
#Mann= 5 ,-1 , 0
  4853.5    .035       0    4926     .07       0    4950    .035       0
  4989.4    .035       0  4993.4    .035       0
Bank Sta=4989.4,4993.4
XS Rating Curve= 0 ,0
Exp/Cntr=0.3,0.1

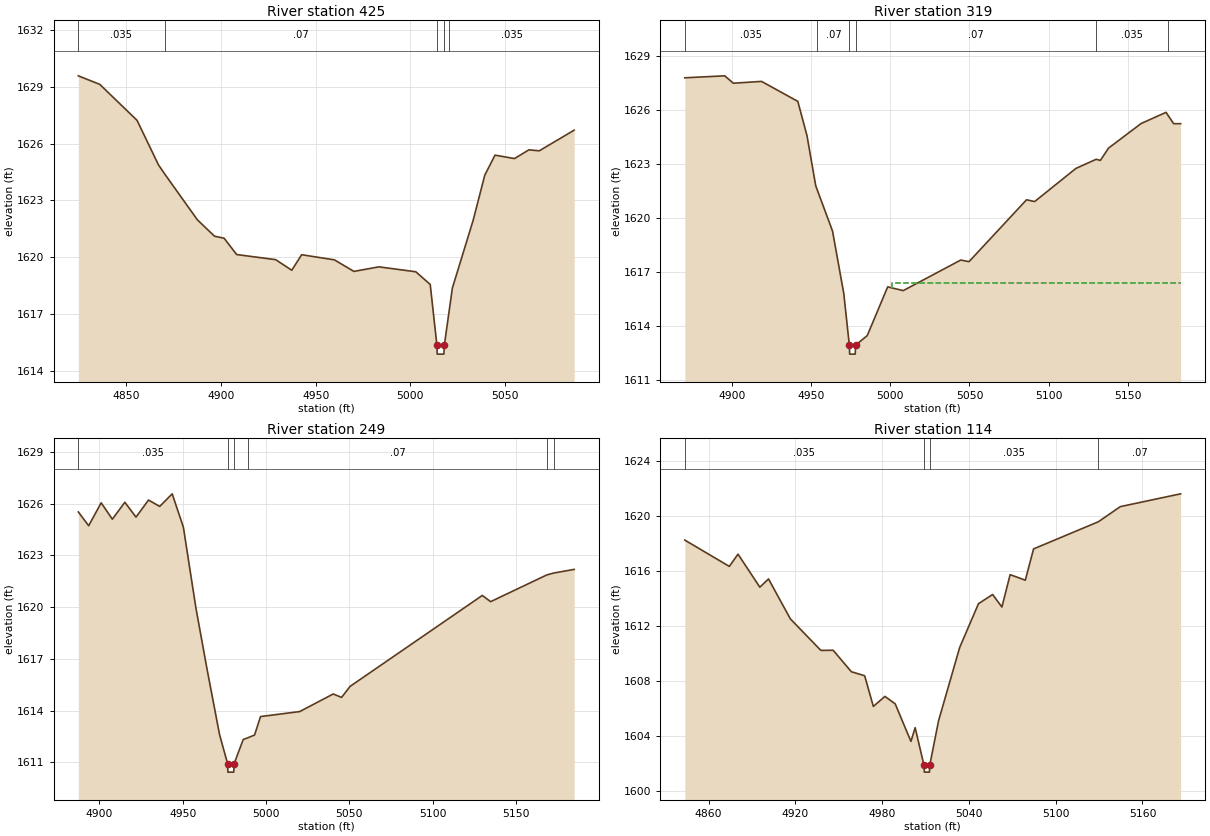
Type RM Length L Ch R = 1 ,425     ,106,106,106
BEGIN DESCRIPTION:
Stream0202_DS 3.0
END DESCRIPTION:
XS GIS Cut Line= 3
      2006978.73     13868195.95      2006935.34     13868026.11
      2006856.18     13867991.23
#Sta/Elev= 30
  4824.7 1629.58    4836 1629.13  4855.7 1627.23    4867 1624.88  4870.2 1624.41
  4887.6 1621.97  4896.6 1621.11  4901.7    1621  4908.3 1620.14  4928.9 1619.87
  4937.4 1619.31  4942.6 1620.13  4959.9 1619.86  4970.2 1619.25  4983.4 1619.49
  5002.9 1619.23  5010.5 1618.56    5014 1615.38  5014.2 1614.88  5017.7 1614.88
    5018 1615.38  5020.4 1617.09  5022.2 1618.37  5033.2 1621.96  5039.3 1624.33
  5044.7 1625.39    5055 1625.21  5062.6 1625.67  5068.1 1625.62  5086.5 1626.71
#Mann= 5 ,-1 , 0
  4824.7    .035       0  4870.2     .07       0    5014     .05       0
    5018     .07       0  5020.4    .035       0
Bank Sta=5014,5018
XS Rating Curve= 0 ,0
Exp/Cntr=0.3,0.1

Type RM Length L Ch R = 1 ,319     ,70,70,70
BEGIN DESCRIPTION:
Stream0202_DS 2.0
END DESCRIPTION:
XS GIS Cut Line= 3
      2007091.51     13868130.13      2007038.73     13868011.77
      2006860.86     13867967.87
#Sta/Elev= 30
  4870.4 1627.81  4895.6 1627.92    4901 1627.51  4918.8 1627.61  4941.7  1626.5
  4947.5 1624.59    4953 1621.81    4954 1621.57  4963.6 1619.29  4970.7 1615.82
  4974.2 1612.95  4974.4 1612.45  4977.9 1612.45  4978.2 1612.95  4985.5 1613.48
  4998.4 1616.19  5008.2 1615.98  5044.5 1617.68  5049.7 1617.59    5086 1621.03
  5091.1 1620.93  5117.1 1622.77  5129.9 1623.28  5132.6 1623.22  5137.7  1623.9
  5158.3 1625.27    5174 1625.89  5175.3 1625.72  5178.8 1625.26  5183.2 1625.26
#Mann= 6 ,-1 , 0
  4870.4    .035       0    4954     .07       0  4974.2     .05       0
  4978.2     .07       0  5129.9    .035       0  5175.3     .07       0
#XS Ineff= 2 , 0
       0                 5001.05       0 1616.41
Permanent Ineff=
       F       F
Bank Sta=4974.2,4978.2
XS Rating Curve= 0 ,0
Exp/Cntr=0.3,0.1

Type RM Length L Ch R = 1 ,249     ,135,135,135
BEGIN DESCRIPTION:
Stream0202_DS 1.0
END DESCRIPTION:
XS GIS Cut Line= 3
       2007158.9     13868030.32      2007075.09     13867955.13
      2006891.48     13867934.18
#Sta/Elev= 30
  4887.4 1625.52  4893.6 1624.72  4901.1 1626.05  4907.8  1625.1  4915.3 1626.08
    4922 1625.22  4929.5 1626.21  4936.2 1625.84  4943.7 1626.57  4950.4 1624.64
  4957.9 1619.97  4964.6 1616.41  4972.1 1612.62  4976.9 1610.94  4977.1 1610.44
  4980.6 1610.44  4980.9 1610.94  4986.3 1612.33  4989.3 1612.44  4993.1 1612.59
  4996.7 1613.66  5020.2 1613.95  5040.3 1614.97  5045.3 1614.77  5050.4 1615.41
  5129.7 1620.68  5134.7 1620.32  5168.4 1621.87  5172.6 1621.98  5184.8 1622.19
#Mann= 6 ,-1 , 0
  4887.4    .035       0  4976.9     .05       0  4980.9    .035       0
  4989.3     .07       0  5168.4    .035       0  5172.6     .07       0
Bank Sta=4976.9,4980.9
XS Rating Curve= 0 ,0
Exp/Cntr=0.3,0.1

Type RM Length L Ch R = 1 ,114     ,0,0,0
BEGIN DESCRIPTION:
Stream0202_DS 0.0
END DESCRIPTION:
XS GIS Cut Line= 3
      2007159.95     13867951.02      2007074.61     13867819.84
      2006910.53     13867908.28
#Sta/Elev= 30
  4843.5 1618.25  4874.3 1616.34  4880.3 1617.23  4895.4 1614.83  4901.4 1615.43
  4916.5 1612.53  4937.6 1610.24  4946.1 1610.25  4958.7 1608.69  4967.9  1608.4
  4973.9 1606.17  4981.9  1606.9    4989 1606.36  4999.9 1603.63  5002.8 1604.63
  5008.9  1601.9  5009.2  1601.4  5012.7  1601.4  5012.9  1601.9    5019 1605.13
  5033.6 1610.45  5046.6 1613.63  5056.4  1614.3  5062.8 1613.39  5068.5 1615.74
    5079 1615.34  5084.7 1617.61  5129.5 1619.58  5144.7 1620.68  5186.4 1621.61
#Mann= 4 ,-1 , 0
  4843.5    .035       0  5008.9    .035       0  5012.9    .035       0
  5129.5     .07       0
Bank Sta=5008.9,5012.9
XS Rating Curve= 0 ,0
Exp/Cntr=0.3,0.1

Chan Stop Cuts=-1
Use User Specified Reach Order=0
Composite Channel Slope=5