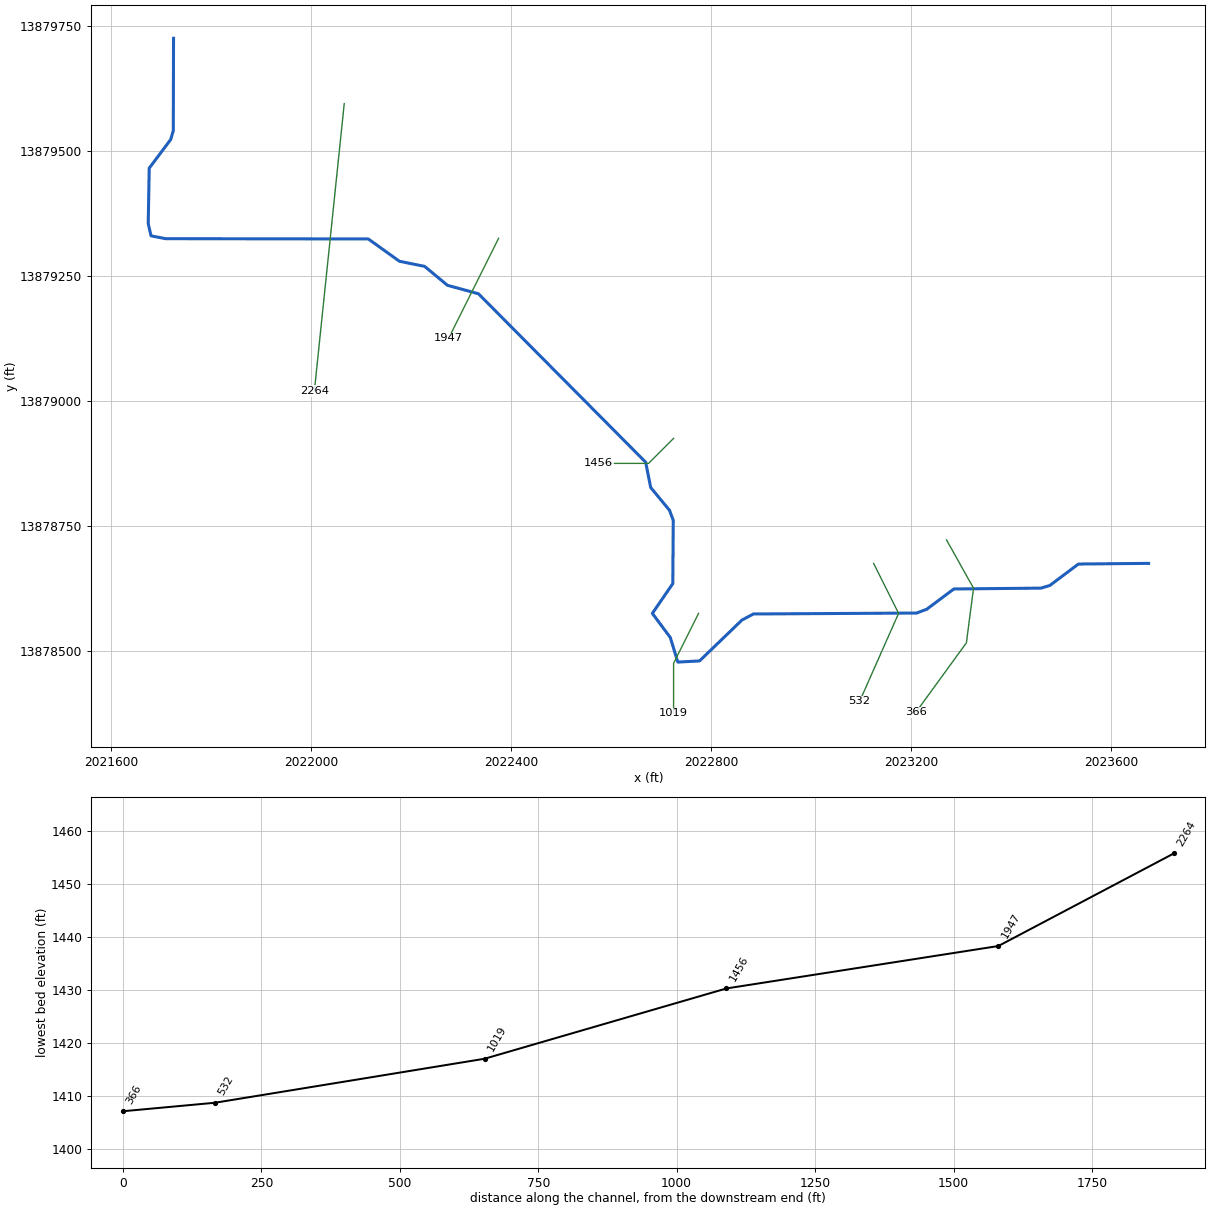
--- Stream0203_DS.prj (project) ---

Proj Title=Stream0203_DS Base Level Engineering
Current Plan=p01
Default Exp/Contr=0.3,0.1
English Units
Geom File=g01
Flow File=f01
Plan File=p01
BEGIN DESCRIPTION:
Stream0203_DS
END DESCRIPTION:

--- Stream0203_DS.p01 (plan) ---

Plan Title=Multiple Run
Short Identifier=Multiple
Geom File=g01
Flow File=f01
Subcritical Flow
K Sum by GR= 0
Std Step Tol= 0.01
Critical Tol= 0.01
Num of Std Step Trials= 20
Max Error Tol= 0.3
Flow Tol Ratio= 0.001
Split Flow NTrial= 30
Split Flow Tol= 0.02
Split Flow Ratio= 0.02
Log Output Level= 0
Friction Slope Method= 1
Unsteady Friction Slope Method= 2
Unsteady Bridges Friction Slope Method= 1
Parabolic Critical Depth
Global Vel Dist=  1 , 1 , 1
Global Log Level= 0
CheckData=True
Encroach Param= -1, 0, 0, 0
BEGIN DESCRIPTION:
Multiple Run
END DESCRIPTION:

--- Stream0203_DS.f01 (steady flow) ---

Flow Title=Multiple
Number of Profiles=7
Profile Names=10-year,25-year,50-year,1pct_min,100-year,1pct_plu,500-year
River Rch & RM= Stream0203_DS,Reach-1,2264
    1261    2171    3052    2080    4150    8280    7591
Boundary for River Rch & Prof#=Stream0203_DS,Reach-1,1
Up Type=0
Dn Type=3
Dn Slope=0.005
Boundary for River Rch & Prof#=Stream0203_DS,Reach-1,2
Up Type=0
Dn Type=3
Dn Slope=0.005
Boundary for River Rch & Prof#=Stream0203_DS,Reach-1,3
Up Type=0
Dn Type=3
Dn Slope=0.005
Boundary for River Rch & Prof#=Stream0203_DS,Reach-1,4
Up Type=0
Dn Type=3
Dn Slope=0.005
Boundary for River Rch & Prof#=Stream0203_DS,Reach-1,5
Up Type=0
Dn Type=3
Dn Slope=0.005
Boundary for River Rch & Prof#=Stream0203_DS,Reach-1,6
Up Type=0
Dn Type=3
Dn Slope=0.005
Boundary for River Rch & Prof#=Stream0203_DS,Reach-1,7
Up Type=0
Dn Type=3
Dn Slope=0.005

--- Stream0203_DS.g01 (geometry) ---

Geom Title=Existing Conditions

River Reach=Stream0203_DS,Reach-1
Reach XY= 30
      2021725.00     13879725.00      2021724.49     13879540.21
      2021719.26     13879522.66      2021676.36     13879465.32
      2021674.36     13879354.40      2021679.99     13879330.00
      2021709.30     13879324.31      2022114.50     13879323.80
      2022176.74     13879279.19      2022227.20     13879268.92
      2022272.81     13879231.10      2022334.68     13879214.24
      2022669.17     13878877.30      2022679.22     13878826.75
      2022716.91     13878781.07      2022724.35     13878761.08
      2022723.46     13878634.60      2022682.52     13878574.95
      2022718.45     13878526.82      2022733.45     13878477.59
      2022776.95     13878479.94      2022861.69     13878561.60
      2022884.59     13878573.79      2023211.08     13878575.68
      2023231.06     13878583.14      2023285.51     13878623.78
      2023459.78     13878625.52      2023477.34     13878630.74
      2023534.64     13878673.67      2023675.00     13878675.00

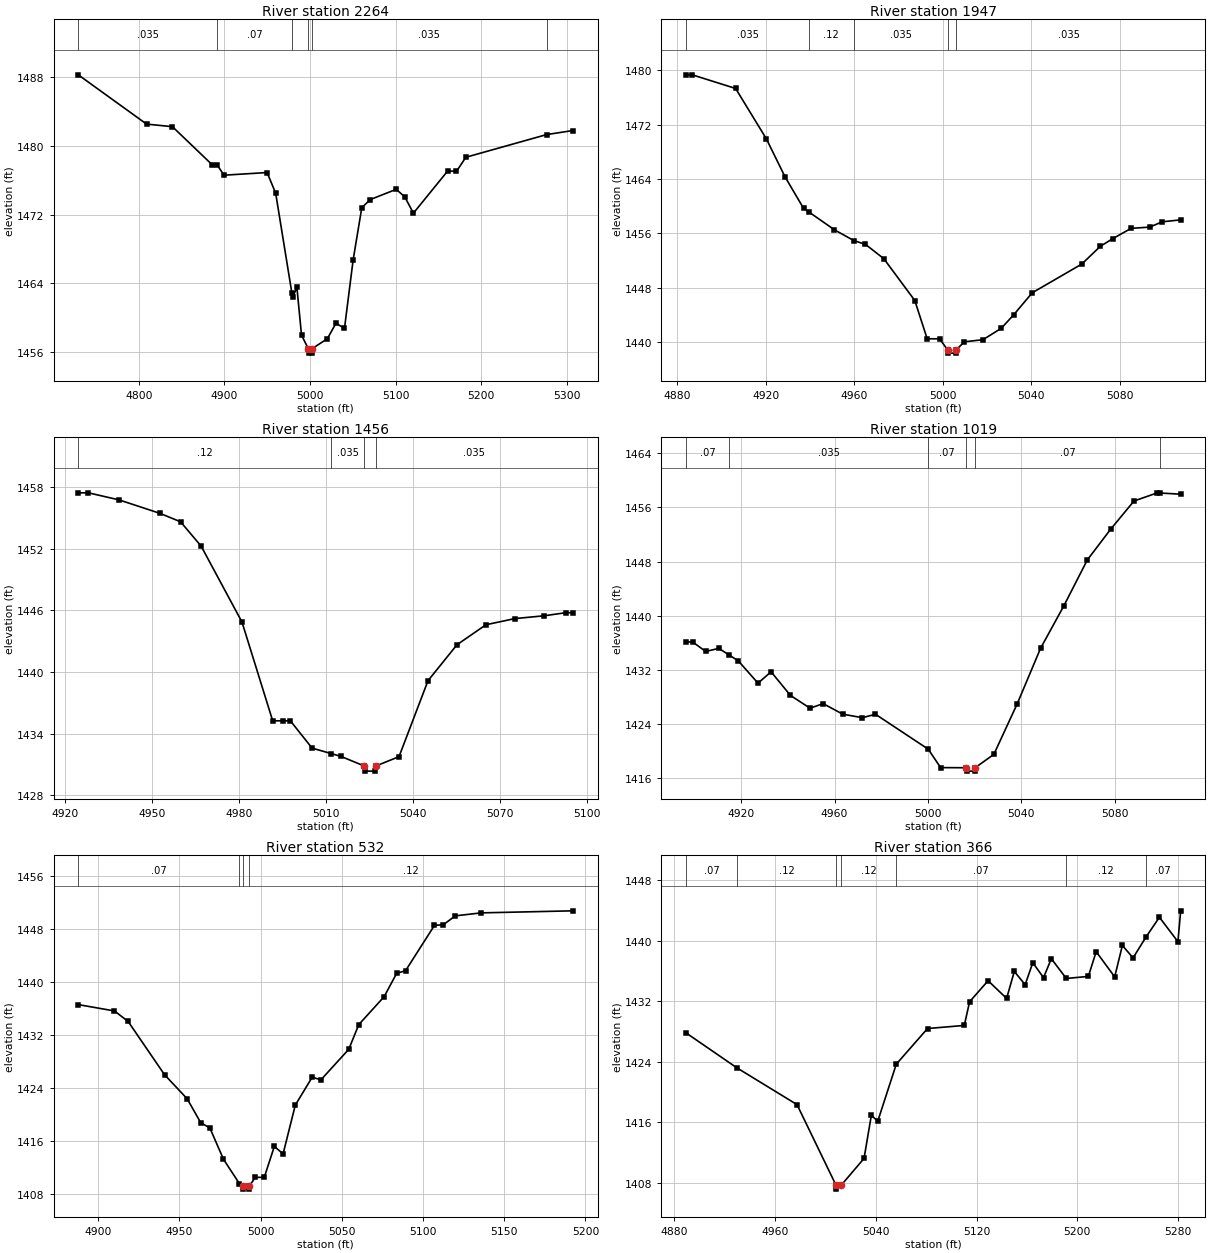
Type RM Length L Ch R = 1,2264,317,317,317
BEGIN DESCRIPTION:
Stream0203_DS 4.5
END DESCRIPTION:
XS GIS Cut Line= 2
      2022066.37     13879594.38      2022006.63     13879019.68
#Sta/Elev= 30
  4729.3 1488.31  4809.1 1482.56  4839.3 1482.26  4886.1 1477.78  4891.8 1477.75
  4899.6 1476.60  4949.9 1476.91  4959.9 1474.50  4978.8 1462.87  4979.7 1462.35
  4984.7 1463.51  4990.1 1457.94  4998.1 1456.34  4998.4 1455.84  5001.9 1455.84
  5002.1 1456.34  5020.2 1457.51  5030.3 1459.32  5040.3 1458.74  5050.4 1466.72
  5060.5 1472.81  5070.5 1473.76  5100.7 1474.95  5110.7 1474.07  5120.8 1472.17
  5161.0 1477.11  5171.1 1477.04  5182.0 1478.69  5276.5 1481.34  5307.1 1481.81
#Mann=6,-1,0
  4729.3   0.035       0  4891.8    0.07       0  4978.8   0.035       0
  4998.1   0.035       0  5002.1   0.035       0  5276.5    0.07       0
Bank Sta=4998.1,5002.1
Exp/Cntr=0.3,0.1

Type RM Length L Ch R = 1,1947,491,491,491
BEGIN DESCRIPTION:
Stream0203_DS 4.0
END DESCRIPTION:
XS GIS Cut Line= 3
      2022375.00     13879324.99      2022325.00     13879225.00
      2022275.00     13879125.00
#Sta/Elev= 30
  4883.9 1479.34  4886.7 1479.34  4906.3 1477.33  4920.2 1469.91  4928.6 1464.34
  4937.0 1459.68  4939.4 1459.14  4951.0 1456.51  4959.7 1454.93  4965.0 1454.37
  4973.3 1452.26  4987.3 1446.10  4992.9 1440.46  4998.5 1440.46  5002.1 1438.85
  5002.3 1438.35  5005.8 1438.35  5006.1 1438.85  5009.7 1440.02  5018.1 1440.32
  5026.4 1442.01  5032.0 1443.99  5040.4 1447.24  5062.8 1451.47  5071.2 1454.09
  5076.8 1455.21  5085.1 1456.73  5093.5 1456.91  5099.1 1457.69  5107.5 1457.98
#Mann=5,-1,0
  4883.9   0.035       0  4939.4    0.12       0  4959.7   0.035       0
  5002.1   0.035       0  5006.1   0.035       0
Bank Sta=5002.1,5006.1
Exp/Cntr=0.3,0.1

Type RM Length L Ch R = 1,1456,437,437,437
BEGIN DESCRIPTION:
Stream0203_DS 3.0
END DESCRIPTION:
XS GIS Cut Line= 3
      2022724.97     13878924.97      2022675.00     13878875.00
      2022574.97     13878875.00
#Sta/Elev= 25
  4924.6 1457.45  4928.1 1457.45  4938.7 1456.76  4952.8 1455.45  4959.9 1454.63
  4967.0 1452.26  4981.1 1444.86  4991.7 1435.24  4995.3 1435.24  4997.8 1435.24
  5005.3 1432.58  5011.9 1432.05  5015.3 1431.77  5023.3 1430.84  5023.5 1430.34
  5027.0 1430.34  5027.3 1430.84  5035.3 1431.75  5045.3 1439.15  5055.3 1442.65
  5065.3 1444.60  5075.3 1445.20  5085.3 1445.47  5092.8 1445.77  5095.3 1445.77
#Mann=4,-1,0
  4924.6    0.12       0  5011.9   0.035       0  5023.3    0.05       0
  5027.3   0.035       0
Bank Sta=5023.3,5027.3
Exp/Cntr=0.3,0.1

Type RM Length L Ch R = 1,1019,487,487,487
BEGIN DESCRIPTION:
Stream0203_DS 2.0
END DESCRIPTION:
XS GIS Cut Line= 3
      2022775.01     13878575.01      2022725.00     13878475.00
      2022725.00     13878375.02
#Sta/Elev= 30
  4896.4 1436.14  4899.2 1436.14  4904.8 1434.73  4910.4 1435.19  4914.8 1434.22
  4918.8 1433.33  4927.2 1430.05  4932.8 1431.73  4941.1 1428.24  4949.5 1426.35
  4955.1 1427.03  4963.5 1425.47  4971.9 1424.95  4977.5 1425.46  5000.1 1420.30
  5005.4 1417.58  5016.2 1417.56  5016.5 1417.06  5020.0 1417.06  5020.2 1417.56
  5028.2 1419.54  5038.2 1427.00  5048.2 1435.20  5058.2 1441.49  5068.2 1448.24
  5078.2 1452.78  5088.2 1456.95  5098.2 1458.16  5099.4 1458.13  5108.2 1457.96
#Mann=6,-1,0
  4896.4    0.07       0  4914.8   0.035       0  5000.1    0.07       0
  5016.2   0.035       0  5020.2    0.07       0  5099.4    0.12       0
Bank Sta=5016.2,5020.2
Exp/Cntr=0.3,0.1

Type RM Length L Ch R = 1,532,166,166,166
BEGIN DESCRIPTION:
Stream0203_DS 1.0
END DESCRIPTION:
XS GIS Cut Line= 3
      2023125.01     13878674.97      2023175.00     13878575.00
      2023096.94     13878398.78
#Sta/Elev= 30
  4887.8 1436.63  4910.1 1435.67  4918.5 1434.08  4940.9 1426.04  4954.8 1422.41
  4963.2 1418.78  4968.8 1418.00  4977.2 1413.26  4987.0 1409.58  4989.2 1409.25
  4989.4 1408.75  4992.9 1408.75  4993.2 1409.25  4996.8 1410.53  5002.3 1410.53
  5008.5 1415.20  5013.9 1414.08  5021.4 1421.44  5031.8 1425.66  5037.2 1425.27
  5054.3 1429.87  5060.5 1433.61  5076.1 1437.83  5083.8 1441.35  5089.3 1441.76
  5107.1 1448.61  5112.5 1448.69  5119.9 1450.04  5135.8 1450.49  5192.3 1450.80
#Mann=4,-1,0
  4887.8    0.07       0  4987.0    0.12       0  4989.2    0.05       0
  4993.2    0.12       0
Bank Sta=4989.2,4993.2
Exp/Cntr=0.3,0.1

Type RM Length L Ch R = 1,366,0,0,0
BEGIN DESCRIPTION:
Stream0203_DS 0.0
END DESCRIPTION:
XS GIS Cut Line= 4
      2023270.86     13878721.94      2023324.83     13878625.40
      2023310.56     13878516.03      2023209.52     13878377.08
#Sta/Elev= 30
  4889.4 1427.80  4929.6 1423.20  4977.5 1418.32  5008.5 1407.65  5008.7 1407.15
  5012.5 1407.65  5030.7 1411.21  5036.5 1416.91  5041.6 1416.13  5056.3 1423.67
  5081.1 1428.38  5110.3 1428.79  5114.5 1431.92  5129.2 1434.70  5143.9 1432.36
  5150.0 1435.93  5158.6 1434.18  5164.7 1437.08  5173.2 1435.11  5179.4 1437.61
  5191.3 1435.00  5208.8 1435.27  5215.0 1438.54  5229.7 1435.21  5235.8 1439.36
  5244.3 1437.72  5254.5 1440.46  5265.2 1443.09  5279.9 1439.86  5282.1 1443.94
#Mann=7,-1,0
  4889.4    0.07       0  4929.6    0.12       0  5008.5    0.05       0
  5012.5    0.12       0  5056.3    0.07       0  5191.3    0.12       0
  5254.5    0.07       0
Bank Sta=5008.5,5012.5
Exp/Cntr=0.3,0.1

Chan Stop Cuts=-1