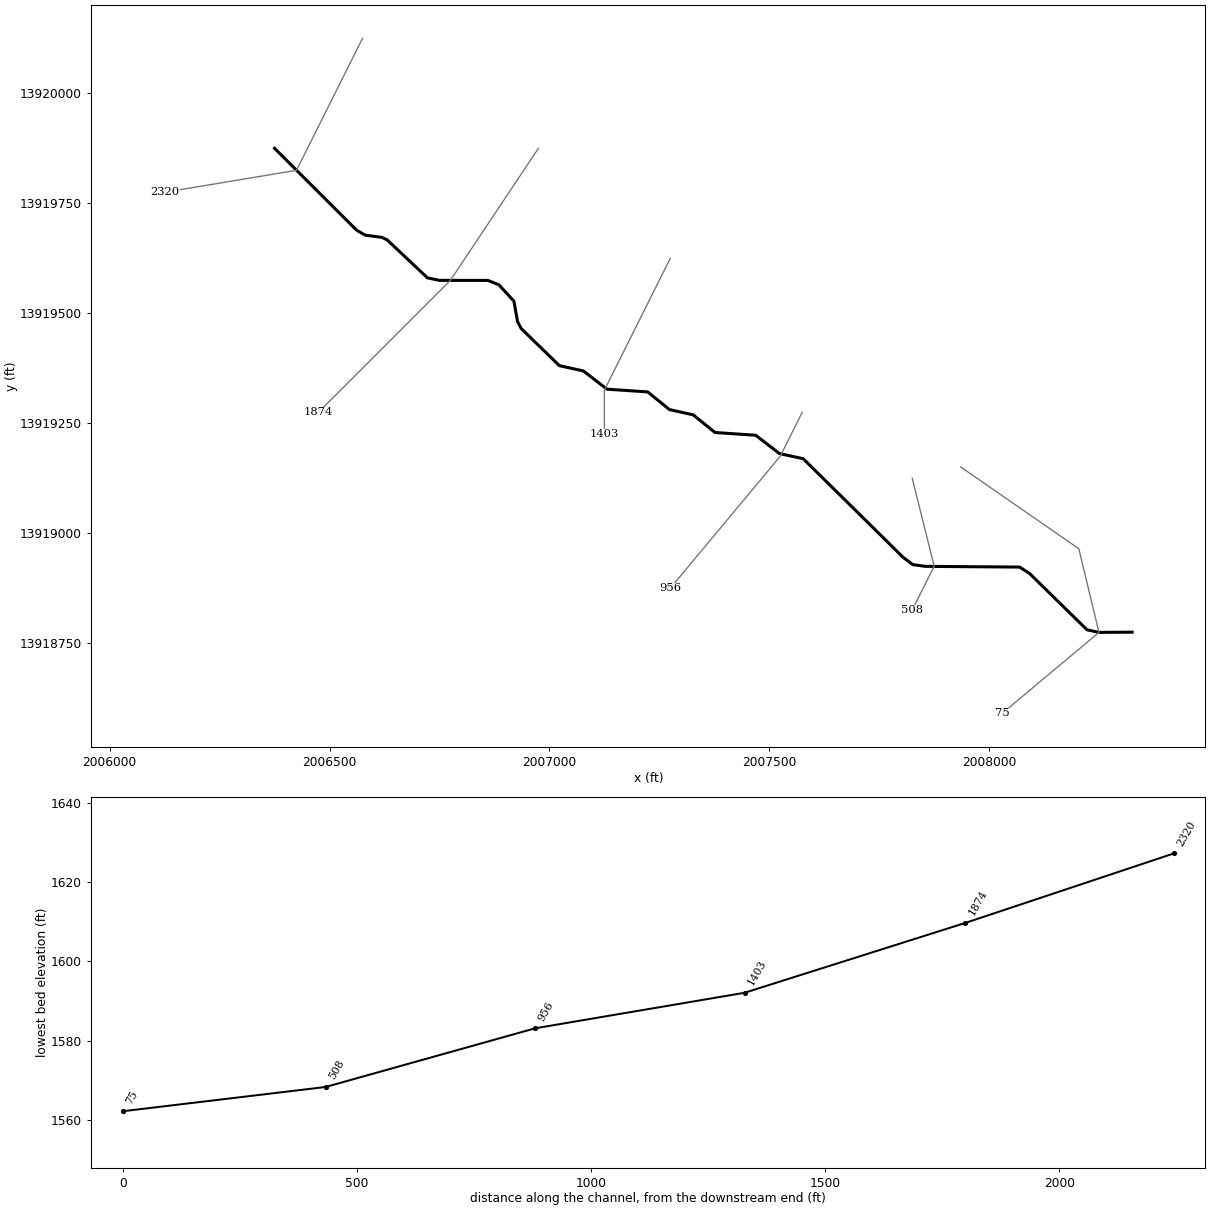
--- Stream0204_DS.prj (project) ---

Proj Title=Stream0204_DS Base Level Engineering
Current Plan=p01
Default Exp/Contr=0.3,0.1
English Units
Geom File=g01
Flow File=f01
Plan File=p01
BEGIN DESCRIPTION:
Stream0204_DS
END DESCRIPTION:

--- Stream0204_DS.p01 (plan) ---

Plan Title=Multiple Run
Short Identifier=Multiple
Geom File=g01
Flow File=f01
Subcritical Flow
K Sum by GR= 0
Std Step Tol= 0.01
Critical Tol= 0.01
Num of Std Step Trials= 20
Max Error Tol= 0.3
Flow Tol Ratio= 0.001
Split Flow NTrial= 30
Split Flow Tol= 0.02
Split Flow Ratio= 0.02
Log Output Level= 0
Friction Slope Method= 1
Unsteady Friction Slope Method= 2
Unsteady Bridges Friction Slope Method= 1
Parabolic Critical Depth
Global Vel Dist=  1 , 1 , 1
Global Log Level= 0
CheckData=True
Encroach Param= -1, 0, 0, 0
BEGIN DESCRIPTION:
Multiple Run
END DESCRIPTION:

--- Stream0204_DS.f01 (steady flow) ---

Flow Title=Multiple
Number of Profiles=7
Profile Names=10-year,25-year,50-year,1pct_min,100-year,1pct_plu,500-year
River Rch & RM= Stream0204_DS,Reach-1,2320
     602    1006    1386     930    1856    3704    3294
Boundary for River Rch & Prof#=Stream0204_DS,Reach-1,1
Up Type=0
Dn Type=3
Dn Slope=0.005
Boundary for River Rch & Prof#=Stream0204_DS,Reach-1,2
Up Type=0
Dn Type=3
Dn Slope=0.005
Boundary for River Rch & Prof#=Stream0204_DS,Reach-1,3
Up Type=0
Dn Type=3
Dn Slope=0.005
Boundary for River Rch & Prof#=Stream0204_DS,Reach-1,4
Up Type=0
Dn Type=3
Dn Slope=0.005
Boundary for River Rch & Prof#=Stream0204_DS,Reach-1,5
Up Type=0
Dn Type=3
Dn Slope=0.005
Boundary for River Rch & Prof#=Stream0204_DS,Reach-1,6
Up Type=0
Dn Type=3
Dn Slope=0.005
Boundary for River Rch & Prof#=Stream0204_DS,Reach-1,7
Up Type=0
Dn Type=3
Dn Slope=0.005

--- Stream0204_DS.g01 (geometry) ---

Geom Title=Existing Conditions

River Reach=Stream0204_DS,Reach-1
Reach XY= 30
      2006375.00     13919875.00      2006561.79     13919688.63
      2006581.05     13919677.53      2006618.95     13919672.46
      2006631.04     13919666.82      2006722.56     13919580.48
      2006749.89     13919574.73      2006859.96     13919574.65
      2006885.12     13919564.65      2006919.26     13919527.57
      2006927.55     13919481.08      2006935.78     13919465.32
      2007022.69     13919380.82      2007077.17     13919368.86
      2007130.97     13919327.33      2007223.42     13919321.17
      2007272.82     13919281.11      2007327.18     13919268.89
      2007376.58     13919228.83      2007469.03     13919222.67
      2007522.83     13919181.14      2007577.30     13919169.17
      2007804.84     13918944.60      2007826.46     13918928.54
      2007854.82     13918924.57      2008069.15     13918922.94
      2008091.76     13918908.57      2008222.50     13918780.35
      2008249.75     13918774.41      2008325.00     13918775.00

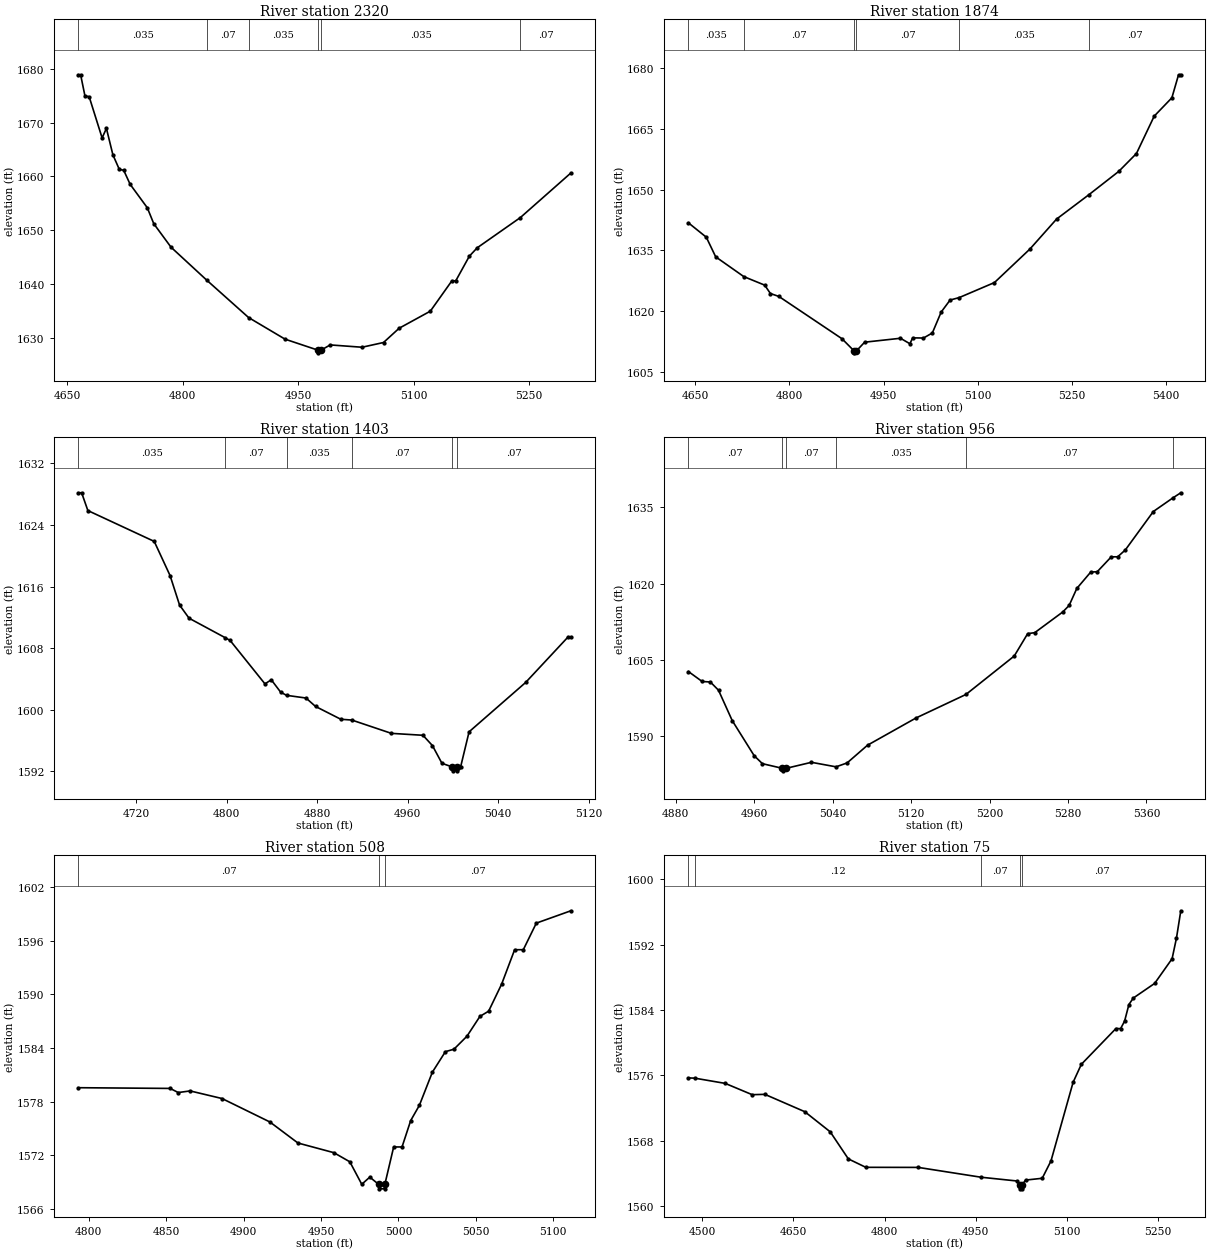
Type RM Length L Ch R = 1,2320,446,446,446
BEGIN DESCRIPTION:
Stream0204_DS 5.0
END DESCRIPTION:
XS GIS Cut Line= 3
      2006574.99     13920124.98      2006425.00     13919825.00
      2006125.02     13919775.00
#Sta/Elev= 30
  4664.6 1678.88  4667.4 1678.88  4673.0 1674.96  4678.5 1674.80  4695.3 1667.15
  4700.9 1668.92  4709.3 1664.02  4717.7 1661.29  4723.3 1661.16  4731.7 1658.54
  4754.0 1654.18  4762.4 1651.22  4784.8 1646.86  4831.4 1640.71  4885.5 1633.80
  4932.9 1629.78  4975.6 1627.74  4975.9 1627.24  4979.6 1627.74  4991.6 1628.71
  5032.9 1628.28  5060.8 1629.16  5081.1 1631.81  5121.6 1634.98  5149.5 1640.60
  5154.6 1640.61  5172.3 1645.20  5182.5 1646.75  5238.5 1652.36  5304.1 1660.64
#Mann=6,-1,0
  4664.6   0.035       0  4831.4    0.07       0  4885.5   0.035       0
  4975.6   0.035       0  4979.6   0.035       0  5238.5    0.07       0
Bank Sta=4975.6,4979.6
Exp/Cntr=0.3,0.1

Type RM Length L Ch R = 1,1874,471,471,471
BEGIN DESCRIPTION:
Stream0204_DS 4.0
END DESCRIPTION:
XS GIS Cut Line= 3
      2006974.98     13919874.96      2006775.00     13919575.00
      2006474.98     13919274.98
#Sta/Elev= 30
  4639.0 1641.78  4667.5 1638.23  4682.5 1633.38  4727.3 1628.50  4760.6 1626.39
  4769.7 1624.32  4783.2 1623.60  4883.8 1613.15  4902.9 1610.17  4903.1 1609.67
  4906.9 1610.17  4919.9 1612.30  4977.0 1613.27  4992.0 1611.92  4996.5 1613.37
  5013.7 1613.33  5027.8 1614.58  5041.9 1619.75  5056.1 1622.71  5070.5 1623.31
  5126.8 1627.03  5183.4 1635.32  5225.8 1642.71  5277.0 1648.69  5324.8 1654.47
  5353.1 1658.90  5381.4 1668.13  5409.6 1672.67  5420.2 1678.35  5423.8 1678.35
#Mann=6,-1,0
  4639.0   0.035       0  4727.3    0.07       0  4902.9    0.05       0
  4906.9    0.07       0  5070.5   0.035       0  5277.0    0.07       0
Bank Sta=4902.9,4906.9
Exp/Cntr=0.3,0.1

Type RM Length L Ch R = 1,1403,447,447,447
BEGIN DESCRIPTION:
Stream0204_DS 3.0
END DESCRIPTION:
XS GIS Cut Line= 3
      2007274.98     13919624.96      2007125.00     13919325.00
      2007125.00     13919224.97
#Sta/Elev= 30
  4668.8 1628.18  4671.6 1628.18  4677.1 1625.87  4735.8 1621.86  4749.8 1617.42
  4758.2 1613.59  4766.6 1611.88  4798.8 1609.33  4802.9 1608.99  4833.7 1603.35
  4839.3 1603.88  4847.6 1602.27  4852.8 1601.86  4870.0 1601.51  4878.4 1600.42
  4900.8 1598.75  4910.5 1598.65  4945.5 1596.92  4973.4 1596.67  4981.8 1595.33
  4990.2 1593.03  4999.4 1592.55  4999.6 1592.05  5003.1 1592.05  5003.4 1592.55
  5006.7 1592.55  5014.2 1597.12  5064.2 1603.53  5101.7 1609.44  5104.2 1609.44
#Mann=6,-1,0
  4668.8   0.035       0  4798.8    0.07       0  4852.8   0.035       0
  4910.5    0.07       0  4999.4    0.05       0  5003.4    0.07       0
Bank Sta=4999.4,5003.4
Exp/Cntr=0.3,0.1

Type RM Length L Ch R = 1,956,448,448,448
BEGIN DESCRIPTION:
Stream0204_DS 2.0
END DESCRIPTION:
XS GIS Cut Line= 3
      2007575.00     13919275.00      2007525.00     13919175.00
      2007275.01     13918875.01
#Sta/Elev= 30
  4892.8 1602.66  4906.8 1600.70  4915.2 1600.60  4923.5 1598.98  4937.5 1592.99
  4959.9 1586.07  4968.3 1584.50  4988.6 1583.59  4988.9 1583.09  4992.6 1583.59
  5018.3 1584.77  5043.4 1583.88  5054.7 1584.65  5075.5 1588.14  5125.0 1593.51
  5175.9 1598.14  5225.2 1605.72  5238.9 1610.13  5246.1 1610.32  5274.7 1614.40
  5281.2 1615.69  5289.0 1619.03  5303.3 1622.28  5309.8 1622.32  5324.2 1625.27
  5330.7 1625.27  5338.5 1626.62  5367.1 1634.20  5387.1 1636.89  5395.1 1637.89
#Mann=6,-1,0
  4892.8    0.07       0  4988.6    0.05       0  4992.6    0.07       0
  5043.4   0.035       0  5175.9    0.07       0  5387.1   0.035       0
Bank Sta=4988.6,4992.6
Exp/Cntr=0.3,0.1

Type RM Length L Ch R = 1,508,433,433,433
BEGIN DESCRIPTION:
Stream0204_DS 1.0
END DESCRIPTION:
XS GIS Cut Line= 3
      2007825.01     13919124.96      2007875.00     13918925.00
      2007825.01     13918825.01
#Sta/Elev= 30
  4793.4 1579.56  4852.6 1579.48  4857.8 1579.02  4865.5 1579.20  4886.1 1578.35
  4917.0 1575.73  4935.1 1573.38  4958.3 1572.30  4968.6 1571.28  4976.3 1568.77
  4981.5 1569.57  4987.2 1568.76  4987.5 1568.26  4991.0 1568.26  4991.2 1568.76
  4996.9 1572.94  5002.3 1572.94  5007.9 1575.89  5013.5 1577.59  5021.9 1581.30
  5030.3 1583.59  5035.8 1583.86  5044.2 1585.31  5052.6 1587.53  5058.2 1588.11
  5066.6 1591.13  5075.0 1594.98  5080.6 1594.98  5089.0 1597.95  5111.3 1599.33
#Mann=3,-1,0
  4793.4    0.07       0  4987.2    0.05       0  4991.2    0.07       0
Bank Sta=4987.2,4991.2
Exp/Cntr=0.3,0.1

Type RM Length L Ch R = 1,75,0,0,0
BEGIN DESCRIPTION:
Stream0204_DS 0.0
END DESCRIPTION:
XS GIS Cut Line= 4
      2007935.22     13919150.54      2008203.85     13918964.69
      2008249.75     13918774.41      2008029.55     13918590.34
#Sta/Elev= 30
  4477.6 1575.70  4488.0 1575.67  4538.1 1575.03  4582.4 1573.65  4603.3 1573.69
  4668.9 1571.57  4710.7 1569.11  4740.5 1565.80  4769.2 1564.77  4855.4 1564.76
  4958.6 1563.56  5017.6 1563.10  5022.1 1562.64  5022.4 1562.14  5025.9 1562.14
  5026.1 1562.64  5031.9 1563.21  5059.2 1563.43  5073.6 1565.55  5110.0 1575.17
  5123.5 1577.36  5180.3 1581.73  5188.1 1581.73  5194.6 1582.64  5201.7 1584.67
  5208.9 1585.46  5244.0 1587.25  5272.7 1590.27  5279.9 1592.80  5287.0 1596.13
#Mann=5,-1,0
  4477.6    0.07       0  4488.0    0.12       0  4958.6    0.07       0
  5022.1    0.05       0  5026.1    0.07       0
Bank Sta=5022.1,5026.1
Exp/Cntr=0.3,0.1

Chan Stop Cuts=-1