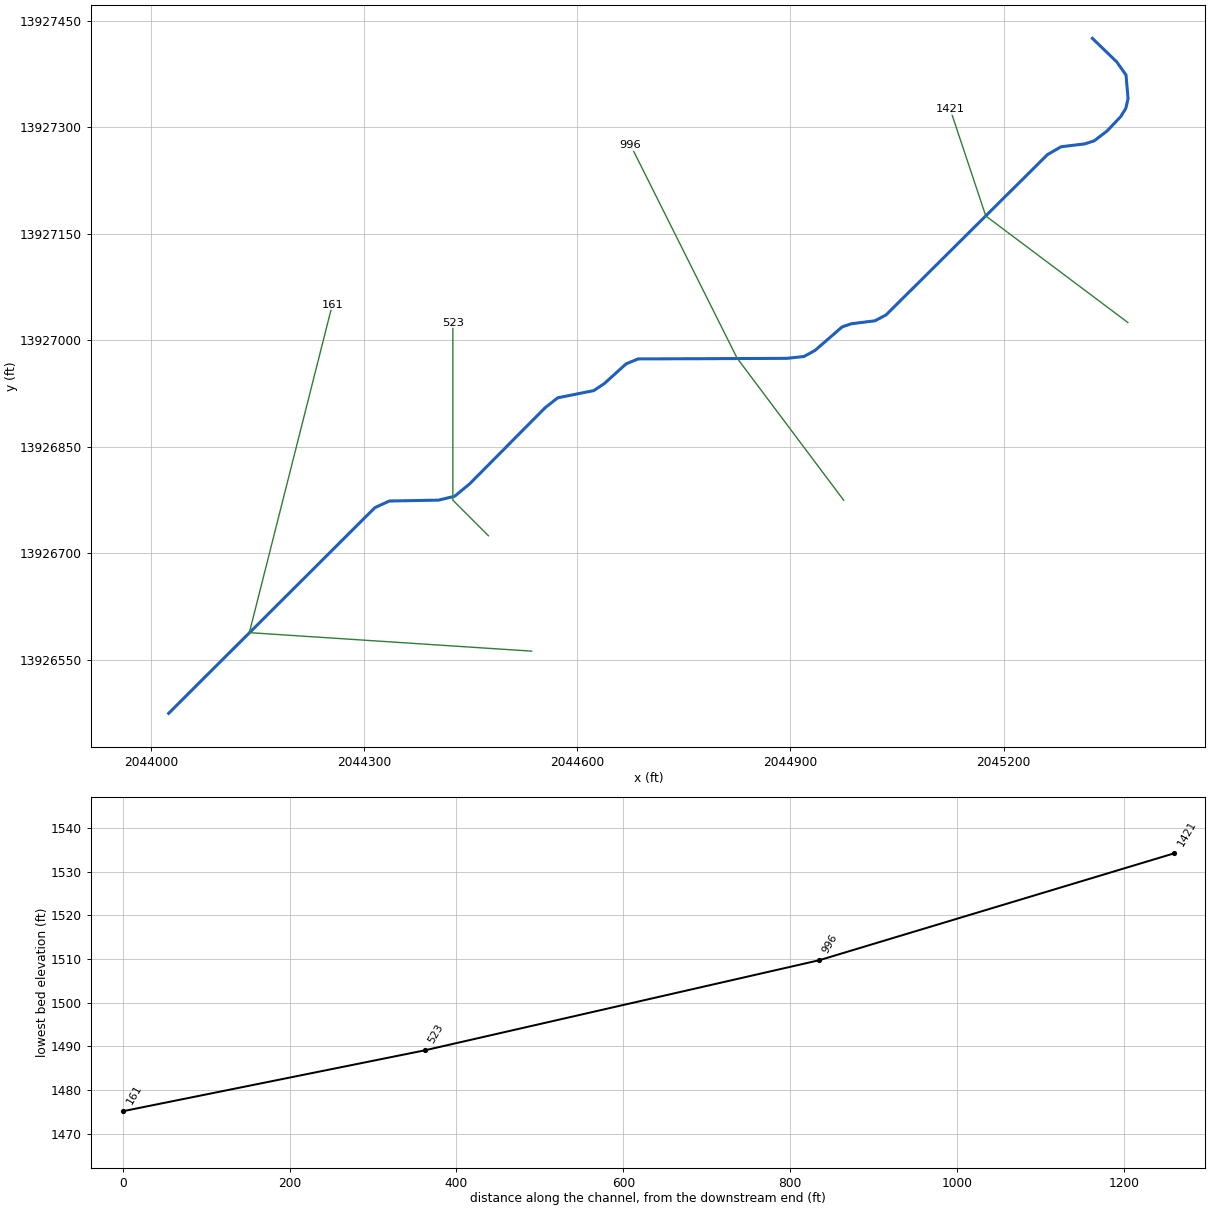
--- Stream0206_DS.prj (project) ---

Proj Title=Stream0206_DS Base Level Engineering
Current Plan=p01
Default Exp/Contr=0.3,0.1
English Units
Geom File=g01
Flow File=f01
Plan File=p01
BEGIN DESCRIPTION:
Stream0206_DS
END DESCRIPTION:

--- Stream0206_DS.p01 (plan) ---

Plan Title=Multiple Run
Short Identifier=Multiple
Geom File=g01
Flow File=f01
Subcritical Flow
K Sum by GR= 0
Std Step Tol= 0.01
Critical Tol= 0.01
Num of Std Step Trials= 20
Max Error Tol= 0.3
Flow Tol Ratio= 0.001
Split Flow NTrial= 30
Split Flow Tol= 0.02
Split Flow Ratio= 0.02
Log Output Level= 0
Friction Slope Method= 1
Unsteady Friction Slope Method= 2
Unsteady Bridges Friction Slope Method= 1
Parabolic Critical Depth
Global Vel Dist=  1 , 1 , 1
Global Log Level= 0
CheckData=True
Encroach Param= -1, 0, 0, 0
BEGIN DESCRIPTION:
Multiple Run
END DESCRIPTION:

--- Stream0206_DS.f01 (steady flow) ---

Flow Title=Multiple
Number of Profiles=7
Profile Names=10-year,25-year,50-year,1pct_min,100-year,1pct_plu,500-year
River Rch & RM= Stream0206_DS,Reach-1,1421
     279     443     591     385     769    1533    1283
Boundary for River Rch & Prof#=Stream0206_DS,Reach-1,1
Up Type=0
Dn Type=3
Dn Slope=0.005
Boundary for River Rch & Prof#=Stream0206_DS,Reach-1,2
Up Type=0
Dn Type=3
Dn Slope=0.005
Boundary for River Rch & Prof#=Stream0206_DS,Reach-1,3
Up Type=0
Dn Type=3
Dn Slope=0.005
Boundary for River Rch & Prof#=Stream0206_DS,Reach-1,4
Up Type=0
Dn Type=3
Dn Slope=0.005
Boundary for River Rch & Prof#=Stream0206_DS,Reach-1,5
Up Type=0
Dn Type=3
Dn Slope=0.005
Boundary for River Rch & Prof#=Stream0206_DS,Reach-1,6
Up Type=0
Dn Type=3
Dn Slope=0.005
Boundary for River Rch & Prof#=Stream0206_DS,Reach-1,7
Up Type=0
Dn Type=3
Dn Slope=0.005

--- Stream0206_DS.g01 (geometry) ---

Geom Title=Existing Conditions

River Reach=Stream0206_DS,Reach-1
Reach XY= 30
      2045325.00     13927425.00      2045359.26     13927391.91
      2045372.35     13927373.34      2045375.25     13927340.12
      2045372.02     13927326.34      2045364.95     13927314.95
      2045345.67     13927294.61      2045327.61     13927280.75
      2045314.54     13927276.48      2045281.09     13927272.45
      2045261.80     13927261.36      2045034.68     13927035.76
      2045018.97     13927027.50      2044985.71     13927023.28
      2044972.83     13927018.86      2044934.67     13926985.79
      2044919.07     13926977.24      2044895.15     13926974.64
      2044685.50     13926973.80      2044668.92     13926966.91
      2044638.03     13926939.05      2044623.25     13926929.22
      2044572.70     13926919.17      2044554.91     13926905.22
      2044448.52     13926797.88      2044427.43     13926780.52
      2044404.94     13926775.13      2044335.48     13926773.83
      2044315.21     13926764.48      2044025.00     13926475.00

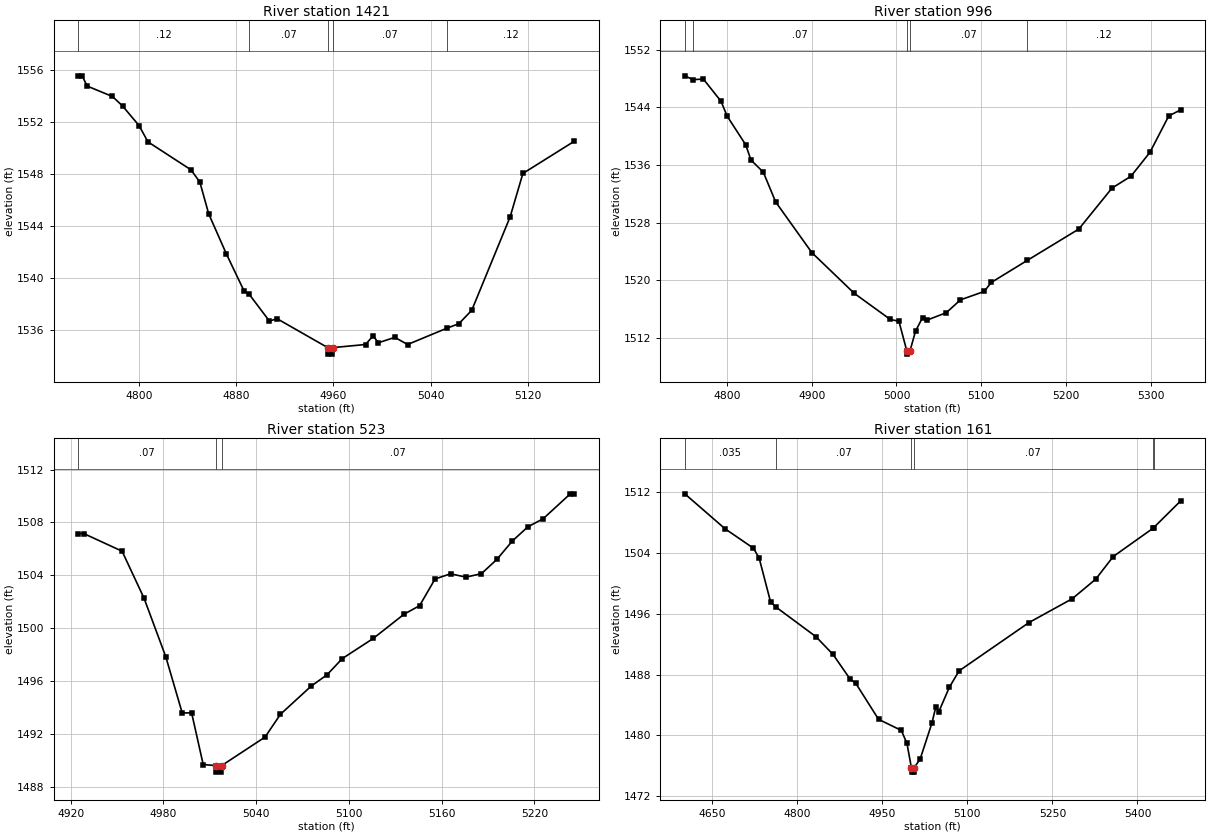
Type RM Length L Ch R = 1,1421,425,425,425
BEGIN DESCRIPTION:
Stream0206_DS 3.0
END DESCRIPTION:
XS GIS Cut Line= 3
      2045374.97     13927025.02      2045175.00     13927175.00
      2045124.99     13927325.02
#Sta/Elev= 30
  4750.0 1555.59  4753.1 1555.59  4757.3 1554.80  4778.1 1554.00  4786.4 1553.27
  4800.0 1551.76  4807.3 1550.51  4842.7 1548.36  4850.0 1547.42  4857.3 1544.97
  4871.8 1541.90  4886.4 1539.04  4890.5 1538.80  4907.3 1536.72  4913.5 1536.91
  4955.3 1534.68  4955.5 1534.18  4959.0 1534.18  4959.3 1534.68  4986.4 1534.92
  4992.7 1535.60  4996.8 1535.05  5010.5 1535.47  5021.0 1534.92  5053.5 1536.18
  5063.2 1536.52  5073.8 1537.55  5105.4 1544.74  5115.9 1548.08  5158.1 1550.55
#Mann=5,-1,0
  4750.0    0.12       0  4890.5    0.07       0  4955.3    0.05       0
  4959.3    0.07       0  5053.5    0.12       0
Bank Sta=4955.3,4959.3
Exp/Cntr=0.3,0.1

Type RM Length L Ch R = 1,996,473,473,473
BEGIN DESCRIPTION:
Stream0206_DS 2.0
END DESCRIPTION:
XS GIS Cut Line= 3
      2044975.00     13926775.00      2044825.00     13926975.00
      2044675.00     13927274.99
#Sta/Elev= 30
  4750.1 1548.39  4759.8 1547.86  4772.0 1547.94  4792.8 1544.87  4800.1 1542.79
  4822.0 1538.82  4828.2 1536.70  4842.8 1535.01  4857.4 1530.87  4900.1 1523.84
  4950.1 1518.19  4992.8 1514.55  5002.9 1514.31  5012.1 1510.24  5012.3 1509.74
  5016.1 1510.24  5022.5 1512.93  5030.8 1514.82  5036.4 1514.48  5058.8 1515.49
  5075.6 1517.28  5103.5 1518.44  5111.9 1519.69  5154.5 1522.76  5215.3 1527.11
  5254.5 1532.80  5276.8 1534.44  5299.2 1537.75  5321.5 1542.82  5335.5 1543.66
#Mann=5,-1,0
  4750.1    0.12       0  4759.8    0.07       0  5012.1    0.05       0
  5016.1    0.07       0  5154.5    0.12       0
Bank Sta=5012.1,5016.1
Exp/Cntr=0.3,0.1

Type RM Length L Ch R = 1,523,362,362,362
BEGIN DESCRIPTION:
Stream0206_DS 1.0
END DESCRIPTION:
XS GIS Cut Line= 3
      2044475.03     13926724.97      2044425.00     13926775.00
      2044425.00     13927025.04
#Sta/Elev= 30
  4924.9 1507.15  4928.5 1507.15  4953.2 1505.82  4967.4 1502.27  4981.5 1497.83
  4992.1 1493.59  4998.2 1493.59  5005.7 1489.68  5013.7 1489.61  5013.9 1489.11
  5017.4 1489.11  5017.7 1489.61  5045.7 1491.76  5055.7 1493.49  5075.7 1495.63
  5085.7 1496.46  5095.7 1497.70  5115.7 1499.22  5135.7 1501.06  5145.7 1501.70
  5155.7 1503.72  5165.7 1504.11  5175.7 1503.86  5185.7 1504.12  5195.7 1505.20
  5205.7 1506.59  5215.7 1507.66  5225.7 1508.28  5243.2 1510.16  5245.7 1510.16
#Mann=3,-1,0
  4924.9    0.07       0  5013.7    0.05       0  5017.7    0.07       0
Bank Sta=5013.7,5017.7
Exp/Cntr=0.3,0.1

Type RM Length L Ch R = 1,161,0,0,0
BEGIN DESCRIPTION:
Stream0206_DS 0.0
END DESCRIPTION:
XS GIS Cut Line= 3
      2044535.84     13926562.58      2044138.59     13926588.61
      2044255.36     13927050.17
#Sta/Elev= 30
  4601.9 1511.79  4672.9 1507.19  4723.0 1504.63  4733.0 1503.34  4753.1 1497.57
  4761.9 1496.93  4833.2 1492.99  4863.3 1490.65  4893.4 1487.41  4903.4 1486.85
  4943.5 1482.12  4983.6 1480.66  4993.6 1478.95  5001.6 1475.67  5001.8 1475.17
  5005.3 1475.17  5005.6 1475.67  5016.9 1476.90  5037.5 1481.60  5044.6 1483.77
  5049.8 1483.13  5068.5 1486.36  5085.6 1488.50  5208.7 1494.85  5285.1 1497.99
  5326.4 1500.56  5357.3 1503.54  5427.1 1507.24  5428.4 1507.33  5476.1 1510.85
#Mann=6,-1,0
  4601.9   0.035       0  4761.9    0.07       0  5001.6    0.05       0
  5005.6    0.07       0  5427.1   0.035       0  5428.4    0.07       0
Bank Sta=5001.6,5005.6
Exp/Cntr=0.3,0.1

Chan Stop Cuts=-1