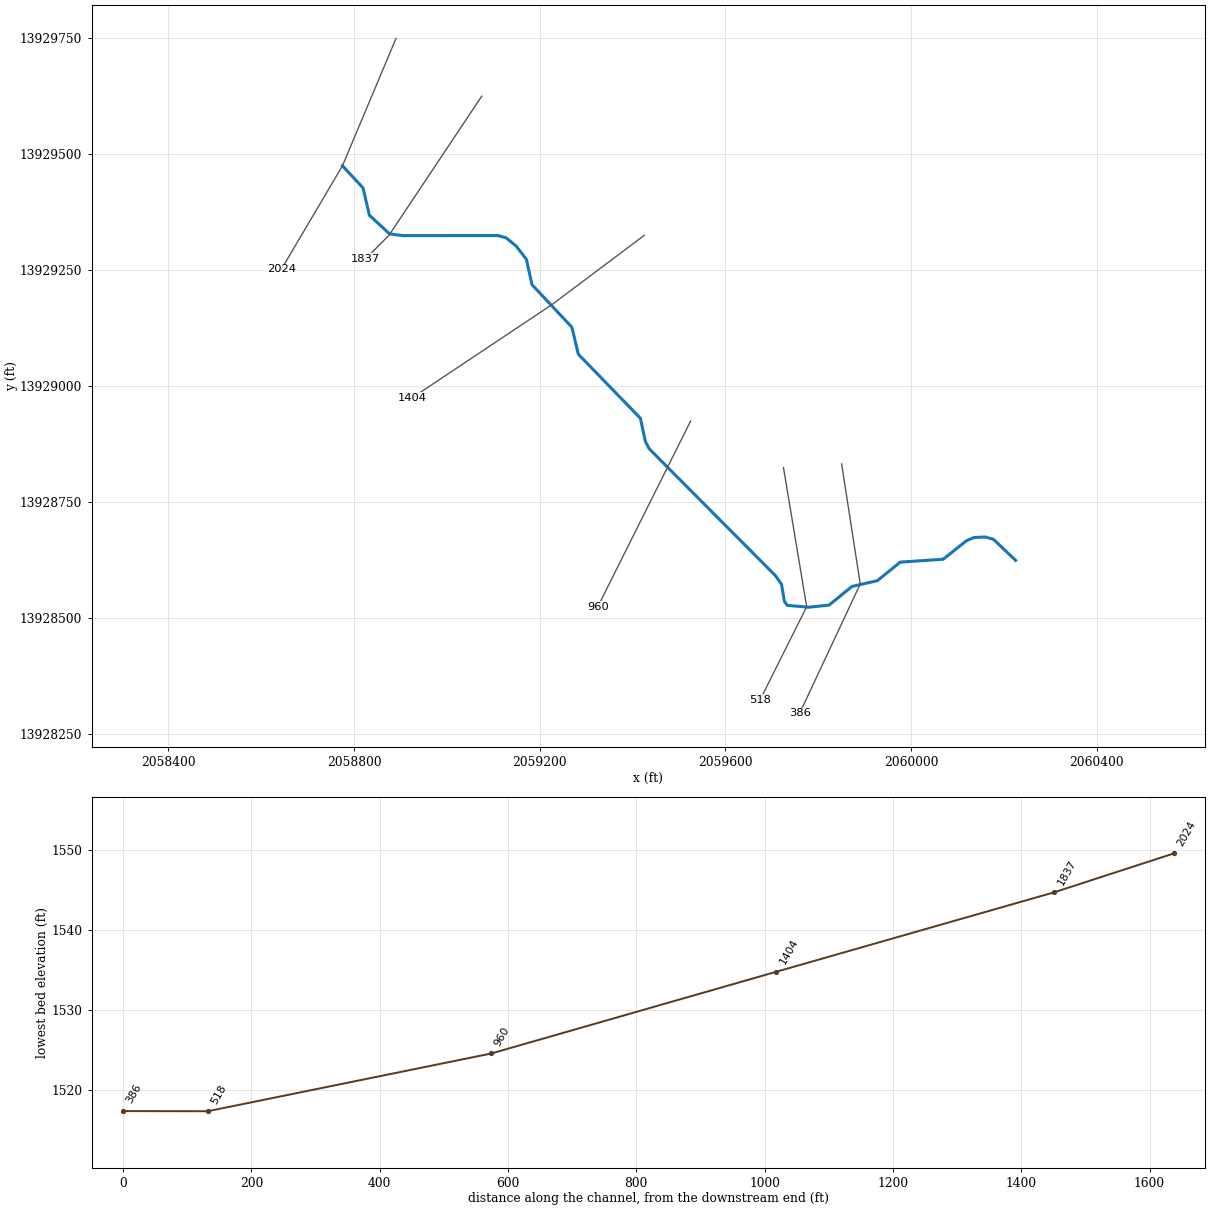
--- Stream0207_DS.prj (project) ---

Proj Title=Stream0207_DS Base Level Engineering
Current Plan=p01
Default Exp/Contr=0.3,0.1
English Units
Geom File=g01
Flow File=f01
Plan File=p01
BEGIN DESCRIPTION:
Stream0207_DS
END DESCRIPTION:

--- Stream0207_DS.p01 (plan) ---

Plan Title=Multiple Run
Short Identifier=Multiple
Geom File=g01
Flow File=f01
Subcritical Flow
K Sum by GR= 0
Std Step Tol= 0.01
Critical Tol= 0.01
Num of Std Step Trials= 20
Max Error Tol= 0.3
Flow Tol Ratio= 0.001
Split Flow NTrial= 30
Split Flow Tol= 0.02
Split Flow Ratio= 0.02
Log Output Level= 0
Friction Slope Method= 1
Unsteady Friction Slope Method= 2
Unsteady Bridges Friction Slope Method= 1
Parabolic Critical Depth
Global Vel Dist=  1 , 1 , 1
Global Log Level= 0
CheckData=True
Encroach Param= -1, 0, 0, 0
BEGIN DESCRIPTION:
Multiple Run
END DESCRIPTION:

--- Stream0207_DS.f01 (steady flow) ---

Flow Title=Multiple
Number of Profiles=7
Profile Names=10-year,25-year,50-year,1pct_min,100-year,1pct_plu,500-year
River Rch & RM= Stream0207_DS,Reach-1,2024
     564     941    1297     872    1740    3472    3094
River Rch & RM= Stream0207_DS,Reach-1,1837
     687    1154    1596    1075    2144    4279    3831
Boundary for River Rch & Prof#=Stream0207_DS,Reach-1,1
Up Type=0
Dn Type=3
Dn Slope=0.005
Boundary for River Rch & Prof#=Stream0207_DS,Reach-1,2
Up Type=0
Dn Type=3
Dn Slope=0.005
Boundary for River Rch & Prof#=Stream0207_DS,Reach-1,3
Up Type=0
Dn Type=3
Dn Slope=0.005
Boundary for River Rch & Prof#=Stream0207_DS,Reach-1,4
Up Type=0
Dn Type=3
Dn Slope=0.005
Boundary for River Rch & Prof#=Stream0207_DS,Reach-1,5
Up Type=0
Dn Type=3
Dn Slope=0.005
Boundary for River Rch & Prof#=Stream0207_DS,Reach-1,6
Up Type=0
Dn Type=3
Dn Slope=0.005
Boundary for River Rch & Prof#=Stream0207_DS,Reach-1,7
Up Type=0
Dn Type=3
Dn Slope=0.005

--- Stream0207_DS.g01 (geometry) ---

Geom Title=Existing Conditions

River Reach=Stream0207_DS,Reach-1
Reach XY= 30
      2058775.00     13929475.00      2058819.28     13929427.32
      2058832.91     13929368.55      2058876.25     13929328.44
      2058904.75     13929324.54      2059109.97     13929324.67
      2059127.70     13929319.64      2059148.90     13929302.30
      2059171.13     13929273.60      2059183.19     13929218.98
      2059269.13     13929127.28      2059283.16     13929068.95
      2059416.84     13928931.05      2059427.53     13928881.05
      2059435.78     13928865.32      2059708.26     13928591.45
      2059720.85     13928572.91      2059727.00     13928536.64
      2059733.34     13928527.98      2059779.69     13928524.03
      2059823.34     13928528.64      2059872.81     13928568.88
      2059927.18     13928581.11      2059976.58     13928621.17
      2060069.04     13928627.37      2060119.05     13928667.18
      2060135.63     13928674.32      2060159.60     13928675.25
      2060177.37     13928670.39      2060225.00     13928625.00

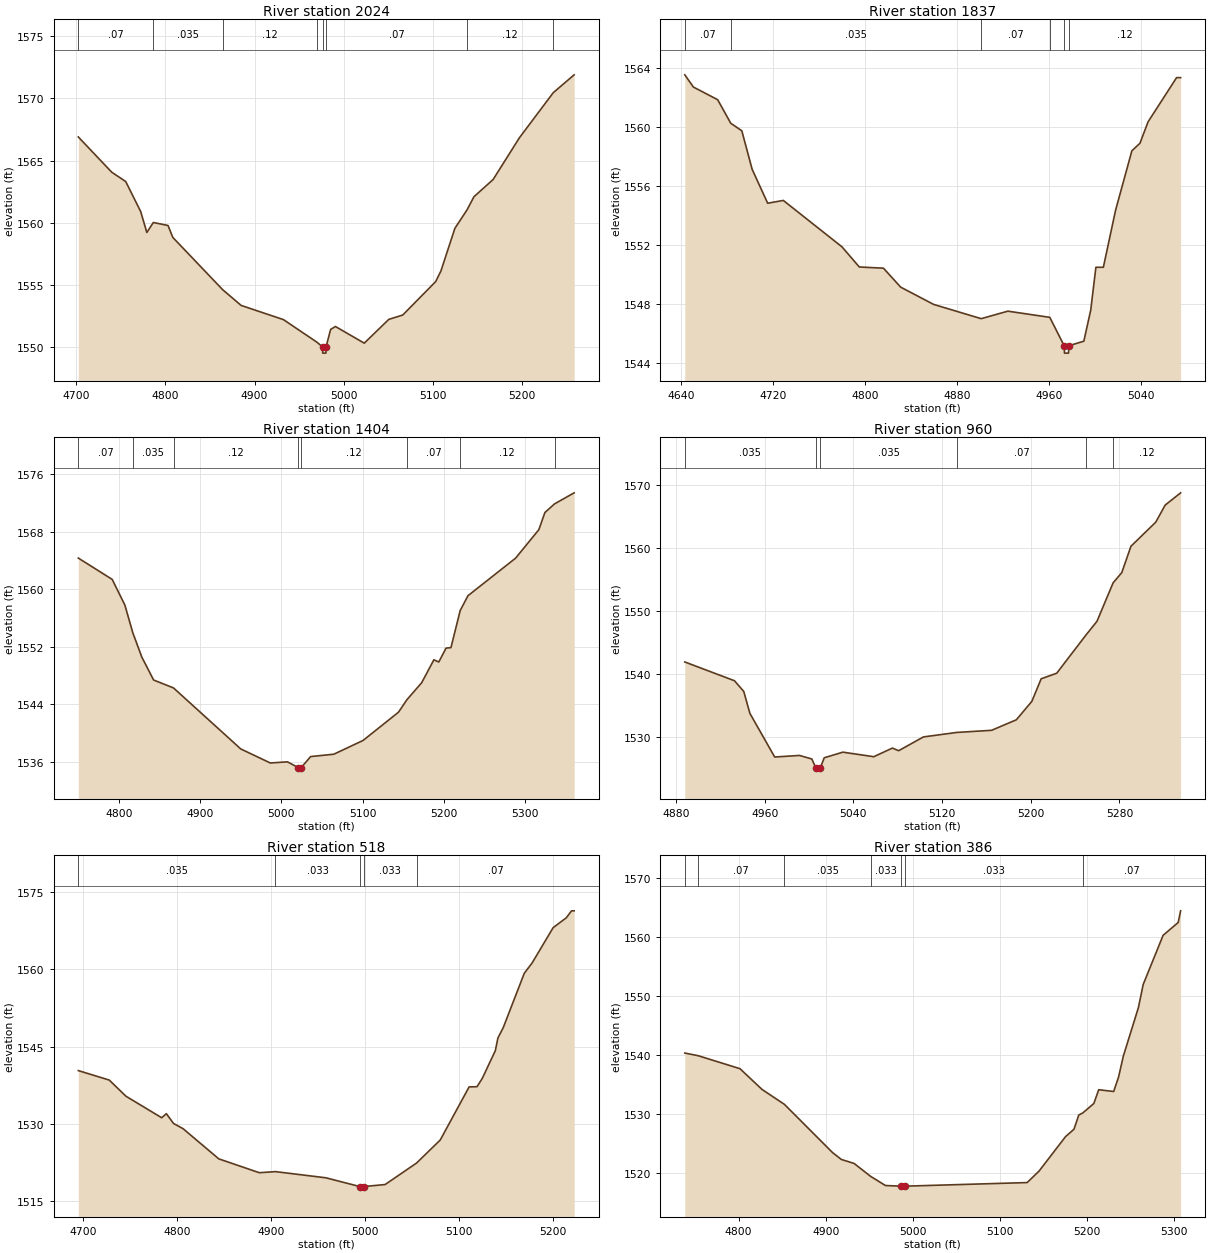
Type RM Length L Ch R = 1,2024,187,187,187
BEGIN DESCRIPTION:
Stream0207_DS 5.0
END DESCRIPTION:
XS GIS Cut Line= 3
      2058890.40     13929749.53      2058775.00     13929475.00
      2058643.41     13929252.15
#Sta/Elev= 30
  4702.2 1566.90  4739.7 1564.07  4755.4 1563.32  4772.2 1560.91  4779.1 1559.23
  4786.4 1560.03  4802.9 1559.79  4808.3 1558.83  4864.3 1554.63  4885.0 1553.37
  4932.5 1552.23  4970.2 1550.41  4976.3 1550.04  4976.6 1549.54  4980.1 1549.54
  4980.3 1550.04  4985.4 1551.44  4990.8 1551.68  5023.2 1550.34  5050.7 1552.25
  5066.4 1552.60  5103.4 1555.29  5109.2 1556.13  5124.9 1559.56  5138.6 1561.05
  5146.3 1562.10  5167.8 1563.48  5197.4 1566.84  5235.4 1570.46  5258.8 1571.89
#Mann=8,-1,0
  4702.2    0.07       0  4786.4   0.035       0  4864.3    0.12       0
  4970.2    0.07       0  4976.3    0.05       0  4980.3    0.07       0
  5138.6    0.12       0  5235.4    0.07       0
Bank Sta=4976.3,4980.3
Exp/Cntr=0.3,0.1

Type RM Length L Ch R = 1,1837,433,433,433
BEGIN DESCRIPTION:
Stream0207_DS 4.0
END DESCRIPTION:
XS GIS Cut Line= 3
      2059075.02     13929625.03      2058875.00     13929325.00
      2058825.00     13929275.00
#Sta/Elev= 30
  4643.2 1563.57  4650.7 1562.74  4671.8 1561.88  4683.2 1560.28  4692.8 1559.77
  4701.8 1557.15  4715.3 1554.85  4728.9 1555.04  4779.9 1551.89  4795.0 1550.52
  4816.0 1550.44  4831.0 1549.15  4859.6 1547.98  4901.0 1547.01  4924.2 1547.52
  4960.7 1547.10  4973.2 1545.17  4973.5 1544.67  4977.0 1544.67  4977.2 1545.17
  4990.3 1545.48  4996.3 1547.59  5000.8 1550.50  5007.3 1550.50  5017.9 1554.37
  5032.1 1558.41  5039.1 1558.92  5046.2 1560.38  5071.0 1563.38  5074.5 1563.38
#Mann=6,-1,0
  4643.2    0.07       0  4683.2   0.035       0  4901.0    0.07       0
  4960.7    0.12       0  4973.2    0.05       0  4977.2    0.12       0
Bank Sta=4973.2,4977.2
Exp/Cntr=0.3,0.1

Type RM Length L Ch R = 1,1404,444,444,444
BEGIN DESCRIPTION:
Stream0207_DS 3.0
END DESCRIPTION:
XS GIS Cut Line= 3
      2059424.99     13929324.99      2059225.00     13929175.00
      2058925.04     13928975.02
#Sta/Elev= 30
  4750.0 1564.32  4791.7 1561.36  4807.3 1557.80  4817.0 1553.98  4828.1 1550.59
  4842.7 1547.39  4867.2 1546.29  4950.0 1537.82  4986.4 1535.87  5007.5 1536.03
  5020.5 1535.24  5020.8 1534.74  5024.5 1535.24  5036.0 1536.76  5064.6 1537.09
  5100.6 1539.00  5144.2 1542.92  5154.6 1544.66  5172.8 1547.02  5187.8 1550.20
  5193.8 1549.89  5202.8 1551.82  5208.8 1551.89  5220.2 1557.04  5229.8 1559.10
  5288.4 1564.31  5317.0 1568.26  5324.5 1570.65  5336.3 1571.84  5360.5 1573.38
#Mann=8,-1,0
  4750.0    0.07       0  4817.0   0.035       0  4867.2    0.12       0
  5020.5    0.05       0  5024.5    0.12       0  5154.6    0.07       0
  5220.2    0.12       0  5336.3    0.07       0
Bank Sta=5020.5,5024.5
Exp/Cntr=0.3,0.1

Type RM Length L Ch R = 1,960,442,442,442
BEGIN DESCRIPTION:
Stream0207_DS 2.0
END DESCRIPTION:
XS GIS Cut Line= 3
      2059525.02     13928925.04      2059475.00     13928825.00
      2059324.98     13928524.96
#Sta/Elev= 30
  4887.9 1541.86  4932.7 1538.88  4941.1 1537.18  4946.6 1533.71  4969.0 1526.77
  4991.4 1527.02  5002.5 1526.46  5006.1 1525.03  5006.4 1524.53  5010.1 1525.03
  5013.7 1526.65  5030.5 1527.54  5058.4 1526.82  5075.2 1528.19  5080.8 1527.77
  5103.2 1529.96  5133.2 1530.67  5164.7 1531.01  5187.0 1532.68  5201.0 1535.61
  5209.4 1539.19  5223.4 1540.07  5250.0 1546.18  5259.7 1548.30  5274.3 1554.42
  5282.1 1556.04  5290.4 1560.23  5312.8 1564.06  5321.2 1566.75  5335.2 1568.71
#Mann=6,-1,0
  4887.9   0.035       0  5006.1   0.035       0  5010.1   0.035       0
  5133.2    0.07       0  5250.0   0.035       0  5274.3    0.12       0
Bank Sta=5006.1,5010.1
Exp/Cntr=0.3,0.1

Type RM Length L Ch R = 1,518,132,132,132
BEGIN DESCRIPTION:
Stream0207_DS 1.0
END DESCRIPTION:
XS GIS Cut Line= 3
      2059725.01     13928824.96      2059775.00     13928525.00
      2059675.00     13928325.00
#Sta/Elev= 30
  4694.8 1540.34  4727.7 1538.50  4745.4 1535.37  4783.5 1531.18  4788.5 1531.97
  4796.1 1530.07  4806.3 1529.05  4844.3 1523.19  4887.4 1520.50  4904.6 1520.71
  4958.3 1519.51  4994.4 1517.81  4994.6 1517.31  4998.1 1517.31  4998.4 1517.81
  5021.3 1518.20  5054.8 1522.38  5080.0 1526.86  5110.7 1537.17  5119.1 1537.21
  5124.7 1538.82  5138.6 1544.21  5141.4 1546.70  5147.0 1548.67  5169.4 1559.24
  5177.8 1561.26  5200.1 1568.10  5214.1 1570.02  5219.7 1571.38  5222.5 1571.38
#Mann=5,-1,0
  4694.8   0.035       0  4904.6   0.033       0  4994.4   0.033       0
  4998.4   0.033       0  5054.8    0.07       0
Bank Sta=4994.4,4998.4
Exp/Cntr=0.3,0.1

Type RM Length L Ch R = 1,386,0,0,0
BEGIN DESCRIPTION:
Stream0207_DS 0.0
END DESCRIPTION:
XS GIS Cut Line= 3
      2059850.33     13928832.76      2059890.39     13928574.05
      2059759.79     13928295.33
#Sta/Elev= 30
  4738.2 1540.37  4753.6 1539.92  4801.6 1537.72  4827.0 1534.20  4852.6 1531.69
  4908.0 1523.51  4918.1 1522.35  4932.7 1521.68  4951.7 1519.49  4968.7 1517.94
  4986.9 1517.83  4987.2 1517.33  4990.7 1517.33  4990.9 1517.83  5131.5 1518.44
  5145.2 1520.39  5175.6 1526.22  5185.3 1527.47  5190.8 1529.88  5195.4 1530.23
  5208.1 1531.83  5213.7 1534.16  5230.9 1533.86  5236.5 1536.30  5242.0 1539.86
  5259.3 1548.06  5264.8 1551.98  5287.7 1560.31  5305.0 1562.47  5307.8 1564.45
#Mann=7,-1,0
  4738.2   0.035       0  4753.6    0.07       0  4852.6   0.035       0
  4951.7   0.033       0  4986.9   0.033       0  4990.9   0.033       0
  5195.4    0.07       0
Bank Sta=4986.9,4990.9
Exp/Cntr=0.3,0.1

Chan Stop Cuts=-1