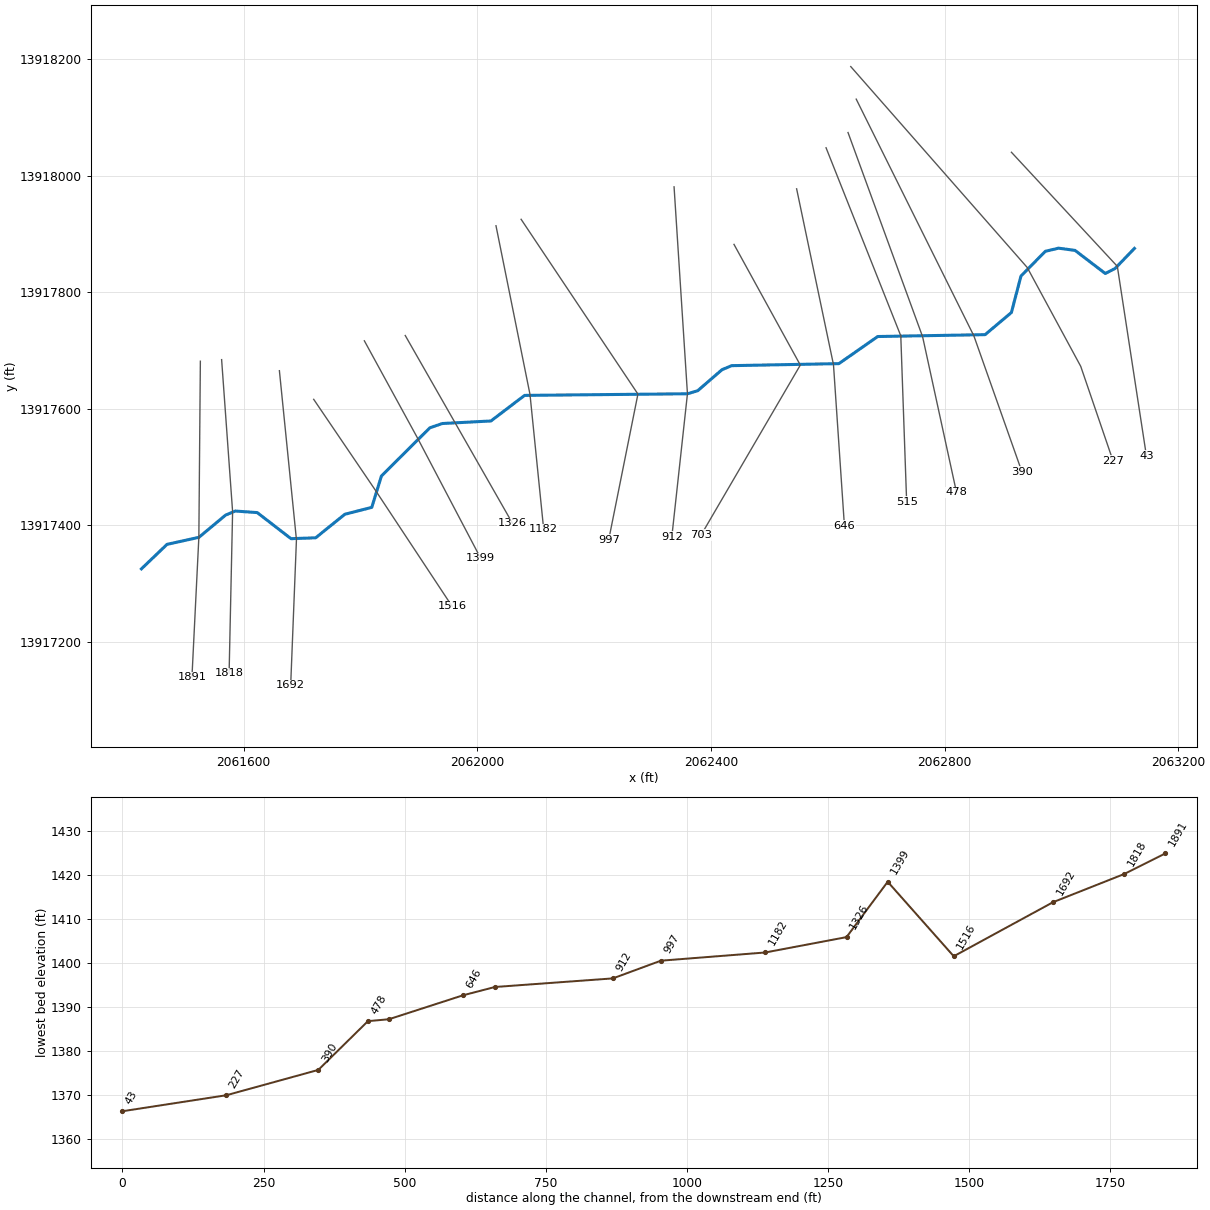
--- Stream0208_DS.prj (project) ---

Proj Title=Stream0208_DS Base Level Engineering
Current Plan=p01
Default Exp/Contr=0.3,0.1
English Units
Geom File=g01
Flow File=f01
Plan File=p01
BEGIN DESCRIPTION:
Stream0208_DS
END DESCRIPTION:

--- Stream0208_DS.p01 (plan) ---

Plan Title=Multiple Run
Short Identifier=Multiple
Geom File=g01
Flow File=f01
Subcritical Flow
K Sum by GR= 0
Std Step Tol= 0.01
Critical Tol= 0.01
Num of Std Step Trials= 20
Max Error Tol= 0.3
Flow Tol Ratio= 0.001
Split Flow NTrial= 30
Split Flow Tol= 0.02
Split Flow Ratio= 0.02
Log Output Level= 0
Friction Slope Method= 1
Unsteady Friction Slope Method= 2
Unsteady Bridges Friction Slope Method= 1
Parabolic Critical Depth
Global Vel Dist=  1 , 1 , 1
Global Log Level= 0
CheckData=True
Encroach Param= -1, 0, 0, 0
BEGIN DESCRIPTION:
Multiple Run
END DESCRIPTION:

--- Stream0208_DS.f01 (steady flow) ---

Flow Title=Multiple
Number of Profiles=7
Profile Names=10-year,25-year,50-year,1pct_min,100-year,1pct_plu,500-year
River Rch & RM= Stream0208_DS,Reach-1,1891
     296     466     617     398     795    1586    1304
Boundary for River Rch & Prof#=Stream0208_DS,Reach-1,1
Up Type=0
Dn Type=3
Dn Slope=0.005
Boundary for River Rch & Prof#=Stream0208_DS,Reach-1,2
Up Type=0
Dn Type=3
Dn Slope=0.005
Boundary for River Rch & Prof#=Stream0208_DS,Reach-1,3
Up Type=0
Dn Type=3
Dn Slope=0.005
Boundary for River Rch & Prof#=Stream0208_DS,Reach-1,4
Up Type=0
Dn Type=3
Dn Slope=0.005
Boundary for River Rch & Prof#=Stream0208_DS,Reach-1,5
Up Type=0
Dn Type=3
Dn Slope=0.005
Boundary for River Rch & Prof#=Stream0208_DS,Reach-1,6
Up Type=0
Dn Type=3
Dn Slope=0.005
Boundary for River Rch & Prof#=Stream0208_DS,Reach-1,7
Up Type=0
Dn Type=3
Dn Slope=0.005

--- Stream0208_DS.g01 (geometry) ---

Geom Title=Existing Conditions

River Reach=Stream0208_DS,Reach-1
Reach XY= 30
      2061425.00     13917325.00      2061468.85     13917367.09
      2061523.33     13917379.11      2061569.06     13917417.25
      2061585.68     13917424.26      2061623.28     13917421.60
      2061681.11     13917376.84      2061723.31     13917378.33
      2061773.15     13917418.68      2061819.39     13917430.59
      2061835.88     13917484.44      2061918.81     13917567.14
      2061940.21     13917574.48      2062023.40     13917578.86
      2062080.94     13917622.74      2062359.78     13917625.52
      2062377.33     13917630.75      2062418.94     13917666.86
      2062435.51     13917673.78      2062619.06     13917677.26
      2062685.51     13917723.78      2062869.33     13917726.98
      2062914.37     13917764.96      2062930.76     13917827.59
      2062972.46     13917870.00      2062995.05     13917875.41
      2063023.33     13917871.58      2063075.12     13917831.95
      2063091.83     13917840.56      2063125.00     13917875.00

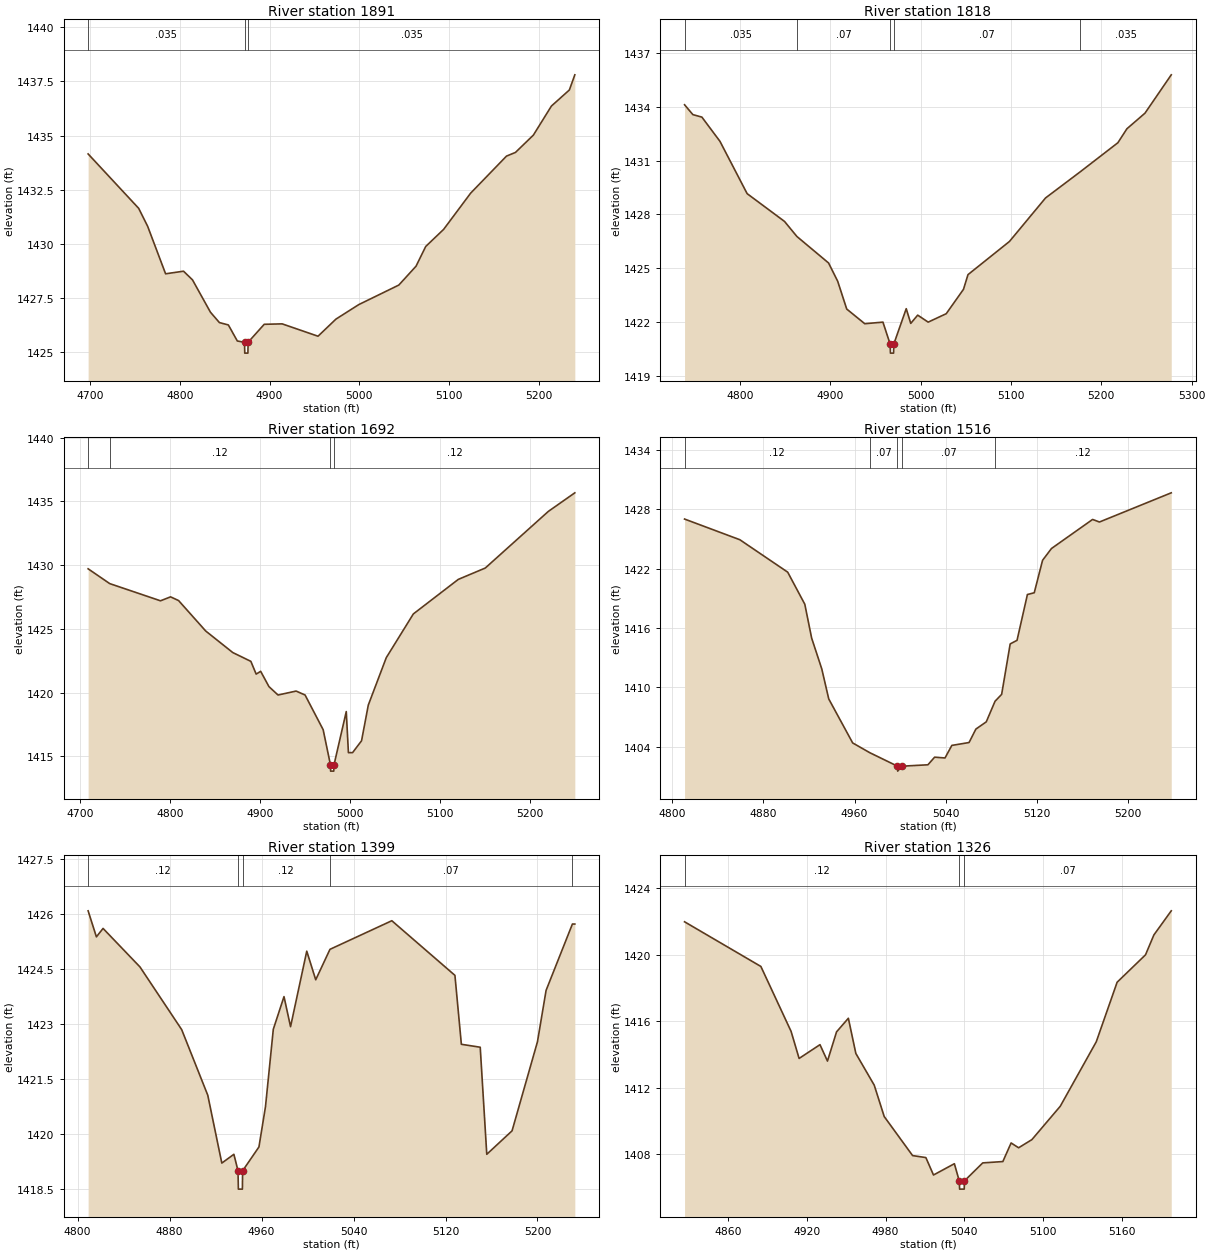
Type RM Length L Ch R = 1,1891,73,73,73
BEGIN DESCRIPTION:
Stream0208_DS 15.0
END DESCRIPTION:
XS GIS Cut Line= 3
      2061525.91     13917681.40      2061523.33     13917379.11
      2061511.49     13917138.90
#Sta/Elev= 30
  4697.7 1434.15  4754.1 1431.64  4764.1 1430.81  4784.1 1428.62  4804.1 1428.74
  4814.1 1428.34  4834.1 1426.85  4844.1 1426.37  4854.1 1426.26  4864.1 1425.52
  4872.1 1425.46  4872.4 1424.96  4875.9 1424.96  4876.1 1425.46  4894.1 1426.29
  4914.1 1426.31  4954.1 1425.74  4974.1 1426.53  4999.6 1427.20  5044.2 1428.10
  5063.4 1428.97  5074.2 1429.88  5094.2 1430.67  5124.3 1432.34  5164.3 1434.05
  5174.3 1434.22  5194.3 1435.02  5214.4 1436.36  5234.4 1437.10  5240.5 1437.80
#Mann=3,-1,0
  4697.7   0.035       0  4872.1   0.035       0  4876.1   0.035       0
Bank Sta=4872.1,4876.1
Exp/Cntr=0.3,0.1

Type RM Length L Ch R = 1,1818,126,126,126
BEGIN DESCRIPTION:
Stream0208_DS 14.0
END DESCRIPTION:
XS GIS Cut Line= 3
      2061562.31     13917684.13      2061581.11     13917423.21
      2061575.12     13917145.87
#Sta/Elev= 30
  4738.4 1434.12  4747.6 1433.57  4757.6 1433.43  4777.6 1432.08  4807.7 1429.16
  4849.1 1427.61  4862.8 1426.77  4897.9 1425.29  4908.0 1424.27  4918.0 1422.72
  4938.0 1421.90  4958.1 1421.99  4966.1 1420.76  4966.4 1420.26  4969.9 1420.26
  4970.1 1420.76  4983.9 1422.74  4988.9 1421.92  4996.6 1422.38  5008.2 1421.99
  5028.2 1422.46  5047.3 1423.82  5052.3 1424.64  5098.2 1426.49  5138.2 1428.92
  5176.4 1430.37  5218.3 1432.00  5228.3 1432.78  5248.3 1433.65  5277.4 1435.79
#Mann=5,-1,0
  4738.4   0.035       0  4862.8    0.07       0  4966.1    0.05       0
  4970.1    0.07       0  5176.4   0.035       0
Bank Sta=4966.1,4970.1
Exp/Cntr=0.3,0.1

Type RM Length L Ch R = 1,1692,176,176,176
BEGIN DESCRIPTION:
Stream0208_DS 13.0
END DESCRIPTION:
XS GIS Cut Line= 3
      2061661.22     13917665.14      2061690.40     13917375.10
      2061680.54     13917125.49
#Sta/Elev= 30
  4708.5 1429.72  4732.5 1428.56  4789.0 1427.21  4800.2 1427.52  4809.1 1427.23
  4839.3 1424.84  4869.4 1423.15  4889.5 1422.46  4895.4 1421.46  4900.4 1421.68
  4909.6 1420.48  4919.7 1419.82  4939.8 1420.13  4949.8 1419.82  4969.9 1417.10
  4978.0 1414.35  4978.2 1413.85  4981.7 1413.85  4982.0 1414.35  4995.6 1418.52
  4998.0 1415.30  5002.6 1415.30  5012.6 1416.23  5020.1 1419.03  5040.1 1422.75
  5070.2 1426.18  5120.2 1428.89  5150.2 1429.78  5220.3 1434.22  5249.8 1435.68
#Mann=4,-1,0
  4708.5   0.035       0  4732.5    0.12       0  4978.0    0.05       0
  4982.0    0.12       0
Bank Sta=4978,4982
Exp/Cntr=0.3,0.1

Type RM Length L Ch R = 1,1516,117,117,117
BEGIN DESCRIPTION:
Stream0208_DS 12.0
END DESCRIPTION:
XS GIS Cut Line= 3
      2061719.95     13917615.97      2061826.02     13917459.29
      2061956.89     13917260.75
#Sta/Elev= 30
  4810.8 1427.01  4859.3 1424.92  4901.3 1421.64  4916.3 1418.40  4922.3 1414.98
  4931.2 1411.86  4937.3 1408.83  4958.3 1404.38  4973.2 1403.40  4997.6 1402.03
  4997.8 1401.53  5001.6 1402.03  5024.3 1402.17  5030.2 1402.94  5039.3 1402.86
  5045.3 1404.13  5060.4 1404.42  5066.4 1405.78  5075.5 1406.51  5083.2 1408.59
  5089.0 1409.29  5096.5 1414.39  5102.5 1414.75  5111.6 1419.38  5117.6 1419.56
  5124.9 1422.84  5132.7 1424.03  5168.8 1426.97  5174.8 1426.71  5237.8 1429.66
#Mann=5,-1,0
  4810.8    0.12       0  4973.2    0.07       0  4997.6    0.05       0
  5001.6    0.07       0  5083.2    0.12       0
Bank Sta=4997.6,5001.6
Exp/Cntr=0.3,0.1

Type RM Length L Ch R = 1,1399,73,73,73
BEGIN DESCRIPTION:
Stream0208_DS 11.0
END DESCRIPTION:
XS GIS Cut Line= 3
      2061806.66     13917716.43      2061898.07     13917548.84
      2062005.95     13917342.88
#Sta/Elev= 30
  4809.1 1426.09  4816.3 1425.38  4822.1 1425.61  4854.2 1424.56  4890.5 1422.85
  4913.2 1421.06  4925.4 1419.21  4935.9 1419.45  4939.5 1419.00  4939.8 1418.50
  4943.3 1418.50  4943.5 1419.00  4957.7 1419.65  4963.4 1420.75  4970.2 1422.86
  4979.5 1423.75  4985.2 1422.93  4999.3 1424.99  5007.1 1424.21  5019.5 1425.04
  5073.3 1425.82  5128.2 1424.33  5133.8 1422.45  5150.2 1422.37  5155.9 1419.45
  5177.9 1420.09  5200.0 1422.52  5207.5 1423.92  5230.4 1425.73  5232.5 1425.73
#Mann=5,-1,0
  4809.1    0.12       0  4939.5    0.05       0  4943.5    0.12       0
  5019.5    0.07       0  5230.4    0.12       0
Bank Sta=4939.5,4943.5
Exp/Cntr=0.3,0.1

Type RM Length L Ch R = 1,1326,144,144,144
BEGIN DESCRIPTION:
Stream0208_DS 10.0
END DESCRIPTION:
XS GIS Cut Line= 2
      2061876.68     13917725.50      2062060.07     13917403.57
#Sta/Elev= 30
  4827.0 1421.99  4885.1 1419.30  4908.1 1415.39  4914.2 1413.76  4930.1 1414.59
  4935.8 1413.60  4942.7 1415.36  4951.7 1416.18  4957.4 1414.06  4971.4 1412.15
  4979.0 1410.26  5000.6 1407.91  5010.7 1407.79  5016.5 1406.74  5032.4 1407.42
  5036.1 1406.39  5036.4 1405.89  5039.9 1405.89  5040.1 1406.39  5054.0 1407.47
  5069.3 1407.55  5075.6 1408.67  5081.3 1408.38  5091.4 1408.87  5113.0 1410.88
  5140.4 1414.76  5156.3 1418.35  5177.9 1420.00  5184.3 1421.20  5197.5 1422.65
#Mann=3,-1,0
  4827.0    0.12       0  5036.1    0.05       0  5040.1    0.07       0
Bank Sta=5036.1,5040.1
Exp/Cntr=0.3,0.1

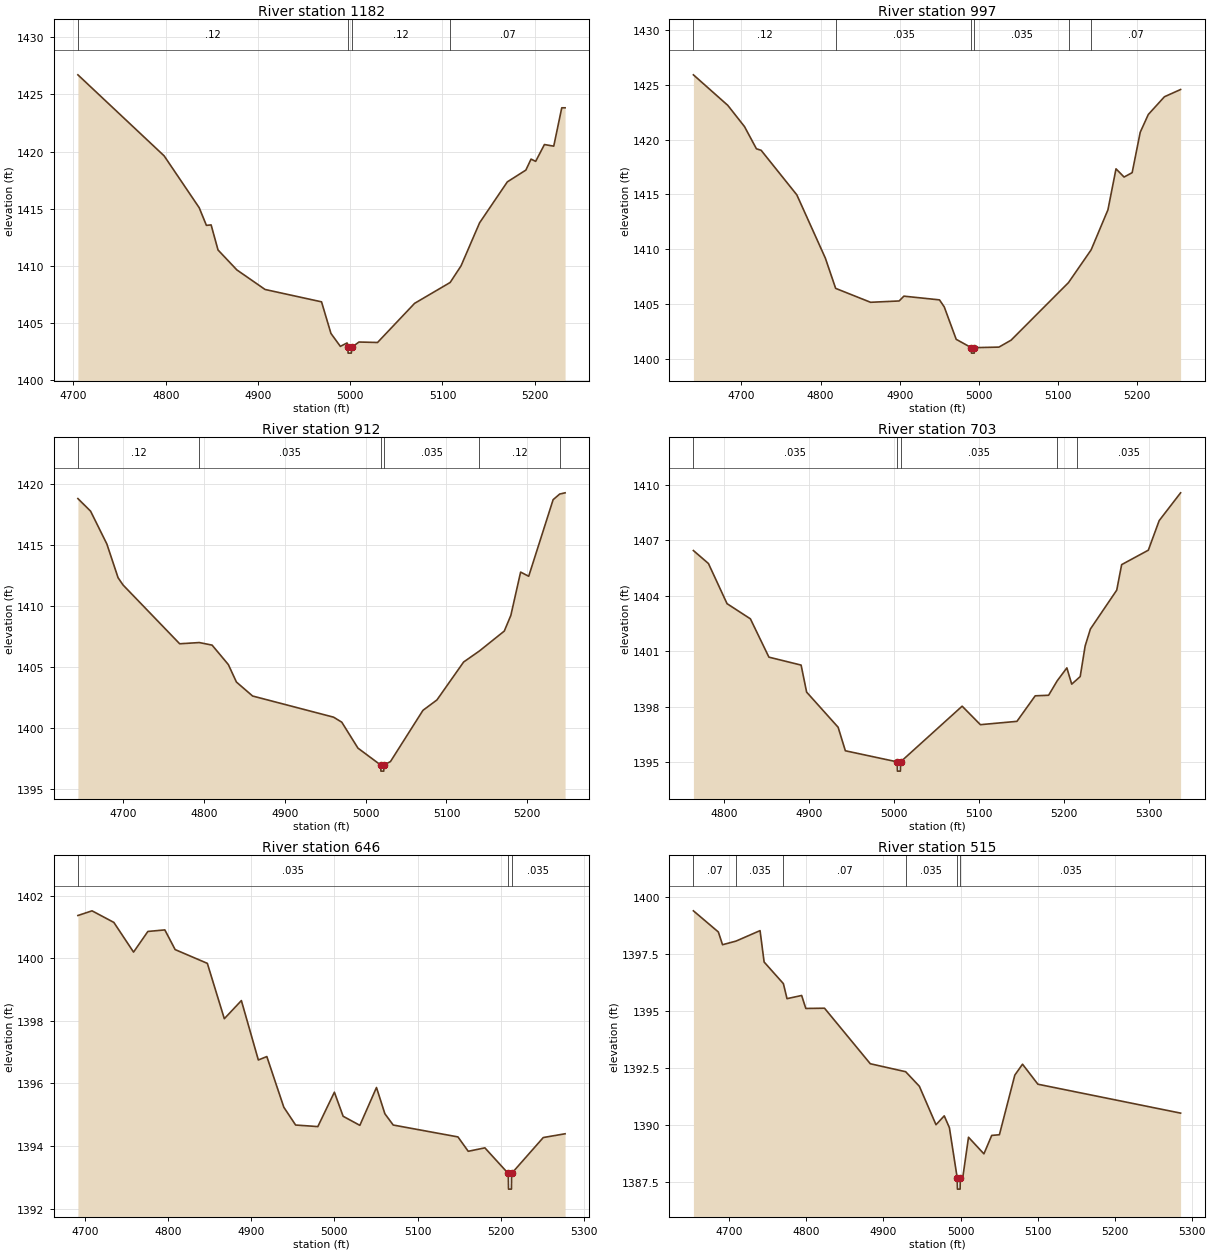
Type RM Length L Ch R = 1,1182,185,185,185
BEGIN DESCRIPTION:
Stream0208_DS 9.0
END DESCRIPTION:
XS GIS Cut Line= 3
      2062032.01     13917913.88      2062090.22     13917624.48
      2062113.67     13917392.76
#Sta/Elev= 30
  4704.8 1426.70  4798.3 1419.62  4836.3 1415.09  4844.1 1413.55  4849.2 1413.59
  4856.7 1411.40  4877.1 1409.66  4907.7 1407.95  4968.9 1406.87  4979.1 1404.11
  4989.3 1402.98  4996.6 1403.28  4997.5 1402.89  4997.7 1402.39  5001.2 1402.39
  5001.5 1402.89  5009.5 1403.36  5029.6 1403.32  5069.8 1406.74  5108.3 1408.56
  5120.1 1410.01  5140.2 1413.77  5170.3 1417.35  5190.4 1418.38  5196.0 1419.34
  5201.0 1419.14  5210.5 1420.61  5220.6 1420.47  5229.3 1423.82  5232.9 1423.82
#Mann=4,-1,0
  4704.8    0.12       0  4997.5    0.05       0  5001.5    0.12       0
  5108.3    0.07       0
Bank Sta=4997.5,5001.5
Exp/Cntr=0.3,0.1

Type RM Length L Ch R = 1,997,85,85,85
BEGIN DESCRIPTION:
Stream0208_DS 8.0
END DESCRIPTION:
XS GIS Cut Line= 3
      2062075.02     13917924.97      2062275.00     13917625.00
      2062224.99     13917374.97
#Sta/Elev= 30
  4639.4 1425.92  4682.9 1423.13  4704.0 1421.19  4719.0 1419.17  4725.0 1419.03
  4770.1 1414.96  4806.1 1409.19  4819.1 1406.43  4863.2 1405.16  4899.3 1405.28
  4905.3 1405.72  4950.3 1405.38  4956.3 1404.74  4971.4 1401.78  4990.4 1401.02
  4990.7 1400.52  4994.2 1400.52  4994.4 1401.02  5025.4 1401.07  5040.7 1401.70
  5113.3 1406.96  5141.9 1409.95  5163.1 1413.60  5173.3 1417.34  5183.5 1416.59
  5193.7 1416.99  5203.9 1420.68  5214.1 1422.30  5234.5 1423.92  5254.9 1424.58
#Mann=6,-1,0
  4639.4    0.12       0  4819.1   0.035       0  4990.4   0.035       0
  4994.4   0.035       0  5113.3    0.12       0  5141.9    0.07       0
Bank Sta=4990.4,4994.4
Exp/Cntr=0.3,0.1

Type RM Length L Ch R = 1,912,209,209,209
BEGIN DESCRIPTION:
Stream0208_DS 7.0
END DESCRIPTION:
XS GIS Cut Line= 3
      2062336.87     13917980.68      2062359.78     13917625.52
      2062333.05     13917380.27
#Sta/Elev= 30
  4644.1 1418.77  4659.8 1417.74  4679.9 1415.06  4693.8 1412.30  4699.9 1411.71
  4770.0 1406.90  4794.3 1407.00  4810.1 1406.79  4830.2 1405.20  4840.2 1403.77
  4860.2 1402.63  4960.4 1400.90  4970.5 1400.49  4990.5 1398.37  5018.6 1396.99
  5018.9 1396.49  5022.4 1396.49  5022.6 1396.99  5030.7 1397.27  5070.9 1401.46
  5088.2 1402.31  5121.2 1405.41  5140.7 1406.31  5171.5 1407.94  5179.6 1409.22
  5191.7 1412.76  5201.7 1412.42  5231.9 1418.68  5240.0 1419.14  5246.7 1419.24
#Mann=6,-1,0
  4644.1    0.12       0  4794.3   0.035       0  5018.6   0.035       0
  5022.6   0.035       0  5140.7    0.12       0  5240.0   0.035       0
Bank Sta=5018.6,5022.6
Exp/Cntr=0.3,0.1

Type RM Length L Ch R = 1,703,57,57,57
BEGIN DESCRIPTION:
Stream0208_DS 6.0
END DESCRIPTION:
XS GIS Cut Line= 3
      2062439.47     13917881.91      2062552.99     13917674.78
      2062383.20     13917383.22
#Sta/Elev= 30
  4763.8 1406.45  4781.5 1405.75  4803.4 1403.58  4830.9 1402.76  4852.7 1400.69
  4890.6 1400.26  4897.1 1398.80  4934.2 1396.90  4942.7 1395.63  5003.7 1395.03
  5004.0 1394.53  5007.5 1394.53  5007.7 1395.03  5080.2 1398.04  5101.7 1397.04
  5144.7 1397.22  5166.2 1398.60  5182.0 1398.63  5192.1 1399.41  5203.5 1400.11
  5209.2 1399.23  5215.3 1399.48  5219.2 1399.64  5225.0 1401.29  5231.2 1402.21
  5262.2 1404.31  5268.0 1405.69  5299.4 1406.47  5312.2 1408.07  5337.4 1409.57
#Mann=5,-1,0
  4763.8   0.035       0  5003.7   0.035       0  5007.7   0.035       0
  5192.1    0.12       0  5215.3   0.035       0
Bank Sta=5003.7,5007.7
Exp/Cntr=0.3,0.1

Type RM Length L Ch R = 1,646,131,131,131
BEGIN DESCRIPTION:
Stream0208_DS 5.0
END DESCRIPTION:
XS GIS Cut Line= 3
      2062546.68     13917977.30      2062609.78     13917675.52
      2062628.52     13917398.86
#Sta/Elev= 30
  4691.7 1401.37  4708.7 1401.52  4734.9 1401.15  4758.6 1400.20  4775.8 1400.86
  4796.2 1400.91  4808.6 1400.28  4847.3 1399.84  4867.7 1398.07  4888.2 1398.65
  4908.6 1396.75  4918.8 1396.86  4939.2 1395.24  4953.4 1394.67  4980.1 1394.62
  5000.0 1395.72  5010.5 1394.95  5030.6 1394.66  5050.6 1395.87  5060.7 1395.03
  5070.7 1394.67  5148.5 1394.29  5160.9 1393.83  5180.9 1393.94  5209.0 1393.12
  5209.3 1392.62  5212.8 1392.62  5213.0 1393.12  5251.1 1394.27  5277.3 1394.39
#Mann=3,-1,0
  4691.7   0.035       0  5209.0   0.035       0  5213.0   0.035       0
Bank Sta=5209,5213
Exp/Cntr=0.3,0.1

Type RM Length L Ch R = 1,515,37,37,37
BEGIN DESCRIPTION:
Stream0208_DS 4.0
END DESCRIPTION:
XS GIS Cut Line= 3
      2062597.08     13918047.70      2062725.00     13917725.00
      2062735.04     13917439.91
#Sta/Elev= 30
  4653.3 1399.41  4685.7 1398.48  4691.1 1397.92  4708.6 1398.08  4739.8 1398.54
  4745.1 1397.16  4770.1 1396.21  4774.8 1395.55  4793.8 1395.69  4799.2 1395.12
  4823.5 1395.13  4882.9 1392.69  4928.8 1392.34  4946.6 1391.70  4968.2 1390.01
  4978.9 1390.40  4985.6 1389.88  4995.7 1387.68  4996.0 1387.18  4999.5 1387.18
  4999.7 1387.68  5002.9 1387.68  5010.4 1389.46  5030.4 1388.73  5040.5 1389.54
  5050.5 1389.57  5070.5 1392.19  5080.5 1392.67  5100.5 1391.79  5285.7 1390.52
#Mann=6,-1,0
  4653.3    0.07       0  4708.6   0.035       0  4770.1    0.07       0
  4928.8   0.035       0  4995.7   0.035       0  4999.7   0.035       0
Bank Sta=4995.7,4999.7
Exp/Cntr=0.3,0.1

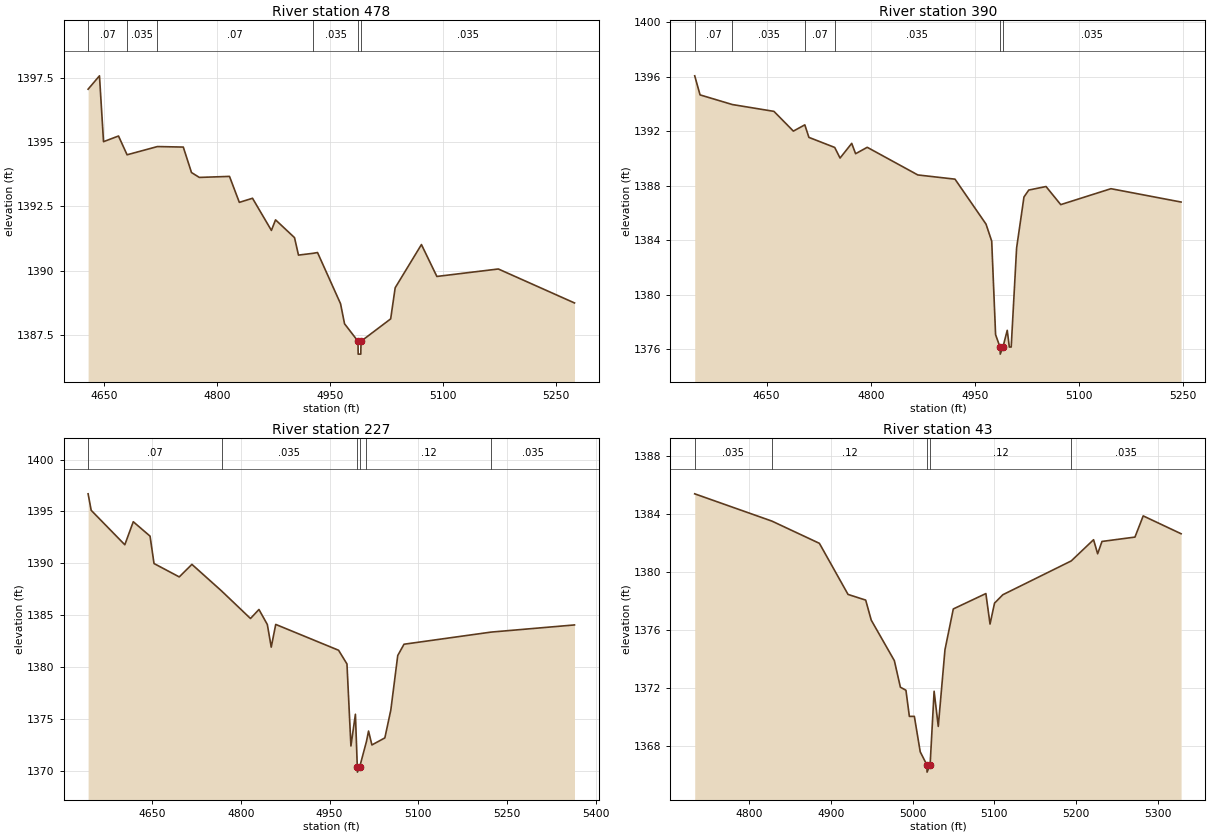
Type RM Length L Ch R = 1,478,88,88,88
BEGIN DESCRIPTION:
Stream0208_DS 3.0
END DESCRIPTION:
XS GIS Cut Line= 3
      2062634.68     13918073.86      2062762.38     13917723.35
      2062820.41     13917456.23
#Sta/Elev= 30
  4628.8 1397.05  4643.9 1397.57  4649.3 1395.01  4669.2 1395.23  4680.6 1394.50
  4720.9 1394.82  4755.3 1394.80  4766.2 1393.81  4776.6 1393.62  4816.7 1393.66
  4829.8 1392.65  4847.3 1392.81  4872.4 1391.56  4877.9 1391.97  4903.1 1391.28
  4908.4 1390.60  4927.9 1390.67  4933.7 1390.70  4964.3 1388.71  4969.6 1387.93
  4987.5 1387.25  4987.7 1386.75  4991.2 1386.75  4991.5 1387.25  5030.9 1388.12
  5036.9 1389.33  5071.8 1391.01  5092.3 1389.77  5174.0 1390.06  5275.2 1388.74
#Mann=6,-1,0
  4628.8    0.07       0  4680.6   0.035       0  4720.9    0.07       0
  4927.9   0.035       0  4987.5   0.035       0  4991.5   0.035       0
Bank Sta=4987.5,4991.5
Exp/Cntr=0.3,0.1

Type RM Length L Ch R = 1,390,163,163,163
BEGIN DESCRIPTION:
Stream0208_DS 2.0
END DESCRIPTION:
XS GIS Cut Line= 3
      2062648.72     13918131.18      2062850.21     13917724.67
      2062932.47     13917491.35
#Sta/Elev= 30
  4546.3 1396.08  4554.0 1394.68  4600.6 1393.97  4660.5 1393.47  4688.5 1392.02
  4705.0 1392.48  4710.9 1391.56  4748.1 1390.82  4755.8 1390.04  4772.6 1391.12
  4778.2 1390.36  4795.0 1390.83  4867.9 1388.80  4921.5 1388.49  4966.2 1385.19
  4974.4 1383.94  4980.0 1377.07  4986.5 1376.14  4986.7 1375.64  4990.5 1376.14
  4996.8 1377.39  4999.8 1376.16  5002.5 1376.16  5010.3 1383.44  5020.9 1387.18
  5027.8 1387.69  5052.7 1387.95  5073.9 1386.62  5146.3 1387.79  5247.4 1386.81
#Mann=6,-1,0
  4546.3    0.07       0  4600.6   0.035       0  4705.0    0.07       0
  4748.1   0.035       0  4986.5   0.035       0  4990.5   0.035       0
Bank Sta=4986.5,4990.5
Exp/Cntr=0.3,0.1

Type RM Length L Ch R = 1,227,184,184,184
BEGIN DESCRIPTION:
Stream0208_DS 1.0
END DESCRIPTION:
XS GIS Cut Line= 4
      2062639.35     13918187.06      2062941.50     13917842.21
      2063033.09     13917672.54      2063088.43     13917510.23
#Sta/Elev= 30
  4541.5 1396.70  4546.7 1395.11  4603.6 1391.79  4617.9 1394.01  4646.3 1392.62
  4653.0 1389.98  4695.7 1388.69  4717.1 1389.90  4767.2 1387.34  4816.2 1384.68
  4830.5 1385.55  4844.7 1384.10  4851.3 1381.92  4858.9 1384.11  4965.2 1381.62
  4979.4 1380.30  4986.1 1372.39  4993.7 1375.45  4996.9 1370.37  4997.1 1369.87
  5000.9 1370.37  5012.4 1372.83  5015.9 1373.83  5021.6 1372.49  5043.5 1373.17
  5053.6 1375.86  5065.3 1381.11  5075.9 1382.20  5223.2 1383.37  5364.3 1384.06
#Mann=6,-1,0
  4541.5    0.07       0  4767.2   0.035       0  4996.9   0.035       0
  5000.9   0.035       0  5012.4    0.12       0  5223.2   0.035       0
Bank Sta=4996.9,5000.9
Exp/Cntr=0.3,0.1

Type RM Length L Ch R = 1,43,0,0,0
BEGIN DESCRIPTION:
Stream0208_DS 0.0
END DESCRIPTION:
XS GIS Cut Line= 3
      2062914.40     13918040.03      2063095.73     13917844.18
      2063145.48     13917519.17
#Sta/Elev= 30
  4733.1 1385.40  4827.7 1383.52  4885.8 1381.99  4920.9 1378.47  4942.5 1378.08
  4949.3 1376.70  4977.6 1373.91  4985.0 1372.08  4991.8 1371.87  4996.0 1370.07
  5002.1 1370.07  5009.3 1367.63  5017.4 1366.73  5017.7 1366.23  5021.4 1366.73
  5026.3 1371.80  5031.4 1369.38  5039.6 1374.66  5049.8 1377.47  5089.7 1378.53
  5094.8 1376.43  5100.3 1377.87  5110.5 1378.45  5194.3 1380.78  5221.6 1382.24
  5226.6 1381.27  5231.9 1382.12  5272.3 1382.42  5282.4 1383.88  5328.8 1382.65
#Mann=5,-1,0
  4733.1   0.035       0  4827.7    0.12       0  5017.4    0.05       0
  5021.4    0.12       0  5194.3   0.035       0
Bank Sta=5017.4,5021.4
Exp/Cntr=0.3,0.1

Chan Stop Cuts=-1