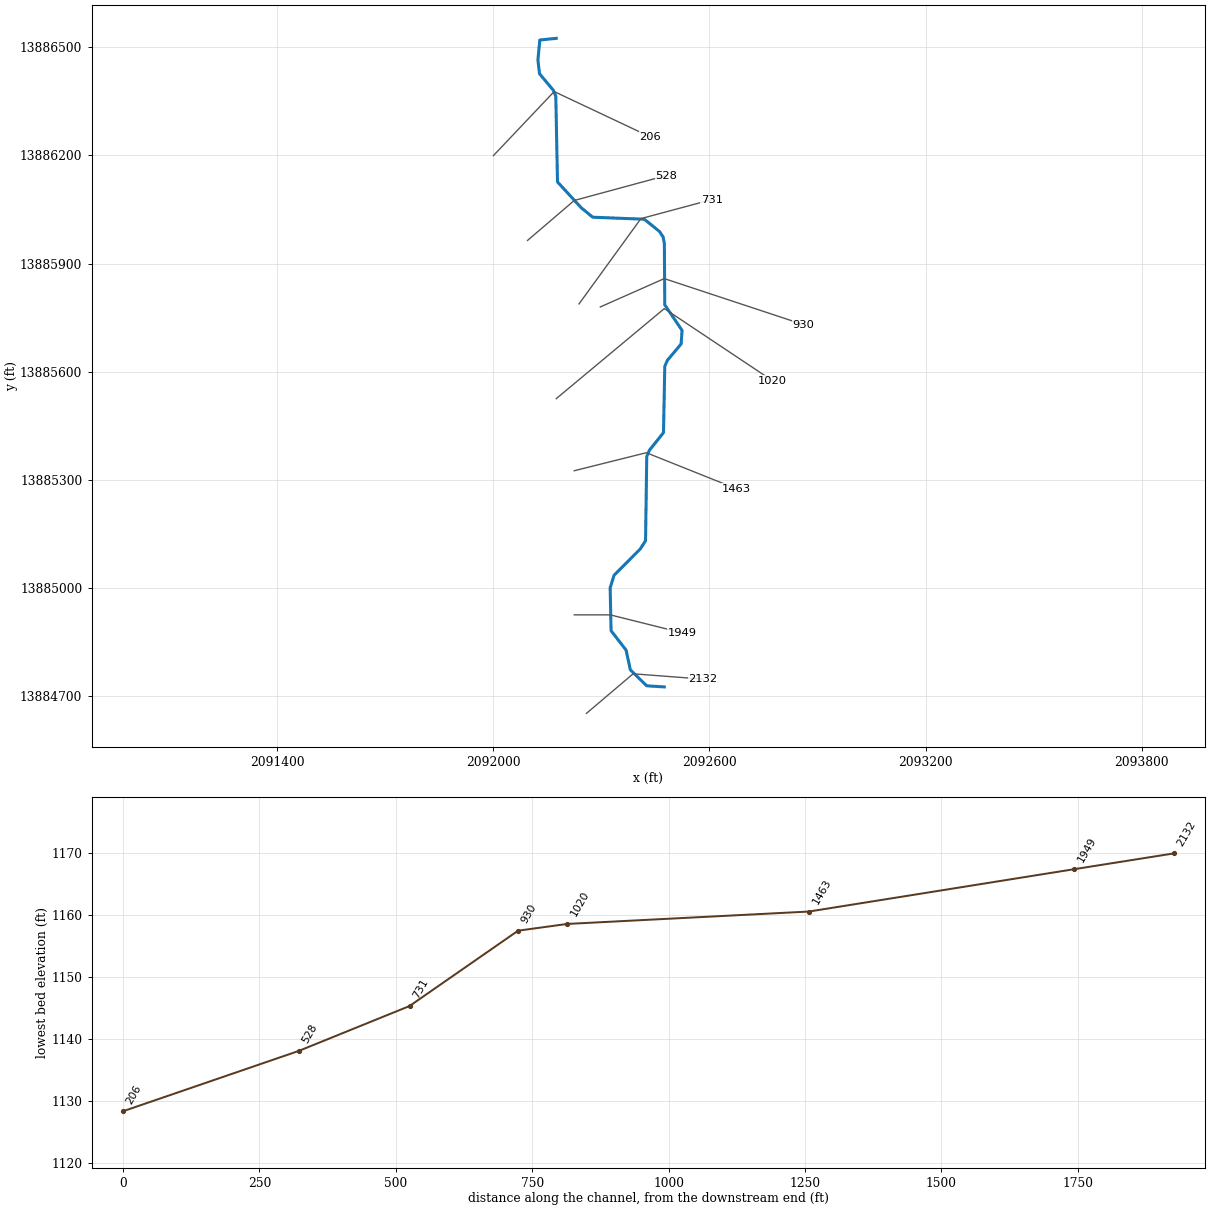
--- Stream0209_DS.prj (project) ---

Proj Title=Stream0209_DS Base Level Engineering
Current Plan=p01
Default Exp/Contr=0.3,0.1
English Units
Geom File=g01
Flow File=f01
Plan File=p01
BEGIN DESCRIPTION:
Stream0209_DS
END DESCRIPTION:

--- Stream0209_DS.p01 (plan) ---

Plan Title=Multiple Run
Short Identifier=Multiple
Geom File=g01
Flow File=f01
Subcritical Flow
K Sum by GR= 0
Std Step Tol= 0.01
Critical Tol= 0.01
Num of Std Step Trials= 20
Max Error Tol= 0.3
Flow Tol Ratio= 0.001
Split Flow NTrial= 30
Split Flow Tol= 0.02
Split Flow Ratio= 0.02
Log Output Level= 0
Friction Slope Method= 1
Unsteady Friction Slope Method= 2
Unsteady Bridges Friction Slope Method= 1
Parabolic Critical Depth
Global Vel Dist=  1 , 1 , 1
Global Log Level= 0
CheckData=True
Encroach Param= -1, 0, 0, 0
BEGIN DESCRIPTION:
Multiple Run
END DESCRIPTION:

--- Stream0209_DS.f01 (steady flow) ---

Flow Title=Multiple
Number of Profiles=7
Profile Names=10-year,25-year,50-year,1pct_min,100-year,1pct_plu,500-year
River Rch & RM= Stream0209_DS,Reach-1,2132
     364     574     760     491     979    1954    1600
Boundary for River Rch & Prof#=Stream0209_DS,Reach-1,1
Up Type=0
Dn Type=3
Dn Slope=0.005
Boundary for River Rch & Prof#=Stream0209_DS,Reach-1,2
Up Type=0
Dn Type=3
Dn Slope=0.005
Boundary for River Rch & Prof#=Stream0209_DS,Reach-1,3
Up Type=0
Dn Type=3
Dn Slope=0.005
Boundary for River Rch & Prof#=Stream0209_DS,Reach-1,4
Up Type=0
Dn Type=3
Dn Slope=0.005
Boundary for River Rch & Prof#=Stream0209_DS,Reach-1,5
Up Type=0
Dn Type=3
Dn Slope=0.005
Boundary for River Rch & Prof#=Stream0209_DS,Reach-1,6
Up Type=0
Dn Type=3
Dn Slope=0.005
Boundary for River Rch & Prof#=Stream0209_DS,Reach-1,7
Up Type=0
Dn Type=3
Dn Slope=0.005

--- Stream0209_DS.g01 (geometry) ---

Geom Title=Existing Conditions

River Reach=Stream0209_DS,Reach-1
Reach XY= 30
      2092475.00     13884725.00      2092426.03     13884728.14
      2092380.68     13884772.48      2092368.87     13884827.16
      2092327.23     13884880.93      2092324.68     13885000.11
      2092335.50     13885034.79      2092408.53     13885108.25
      2092422.93     13885130.86      2092426.22     13885364.50
      2092433.14     13885381.06      2092472.74     13885430.94
      2092476.24     13885614.50      2092483.19     13885631.07
      2092521.63     13885676.74      2092524.23     13885714.31
      2092476.24     13885785.50      2092475.09     13885955.13
      2092471.57     13885973.78      2092461.80     13885988.74
      2092419.35     13886023.02      2092276.46     13886028.54
      2092244.71     13886054.47      2092178.53     13886126.45
      2092173.78     13886364.50      2092166.86     13886381.06
      2092128.67     13886426.63      2092124.15     13886465.10
      2092129.51     13886520.32      2092175.00     13886525.00

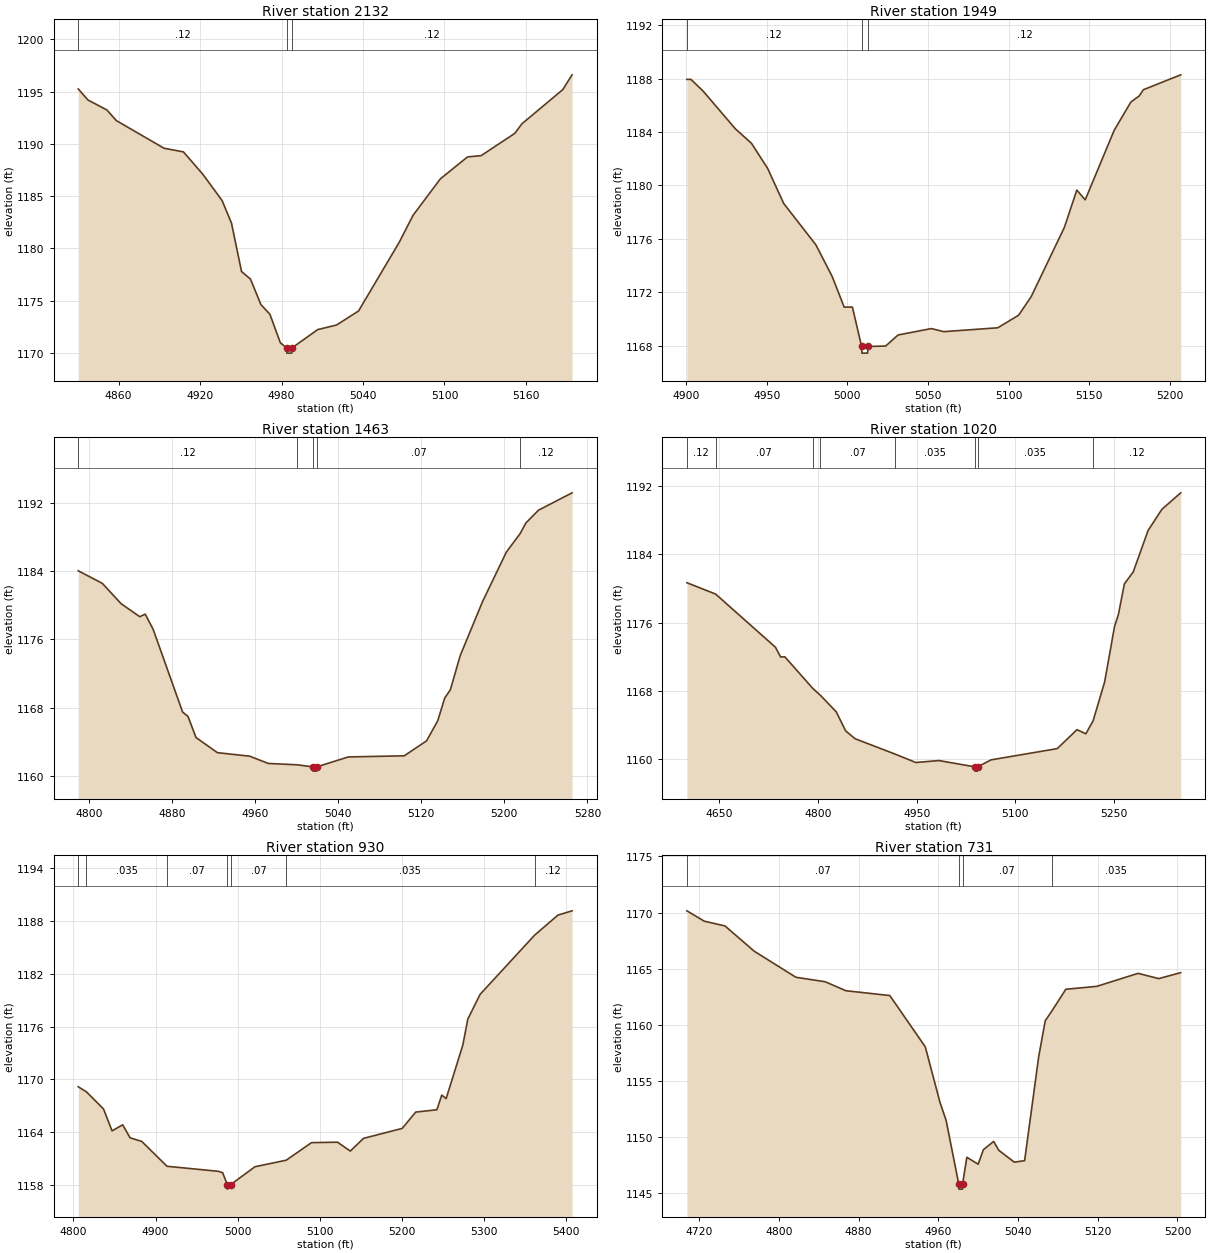
Type RM Length L Ch R = 1,2132,183,183,183
BEGIN DESCRIPTION:
Stream0209_DS 7.0
END DESCRIPTION:
XS GIS Cut Line= 3
      2092258.89     13884651.61      2092388.37     13884761.45
      2092581.82     13884746.79
#Sta/Elev= 30
  4830.2 1195.25  4837.4 1194.19  4851.3 1193.24  4858.3 1192.22  4893.4 1189.58
  4907.7 1189.23  4922.0 1187.09  4936.2 1184.57  4943.1 1182.42  4950.5 1177.79
  4957.1 1177.06  4964.8 1174.62  4971.4 1173.70  4979.1 1170.97  4983.7 1170.48
  4983.9 1169.98  4987.4 1169.98  4987.7 1170.48  5006.6 1172.23  5020.5 1172.67
  5036.7 1174.01  5066.8 1180.61  5076.8 1183.15  5096.9 1186.64  5117.0 1188.75
  5127.0 1188.87  5151.8 1191.00  5157.1 1191.92  5187.2 1195.19  5194.0 1196.60
#Mann=3,-1,0
  4830.2    0.12       0  4983.7    0.05       0  4987.7    0.12       0
Bank Sta=4983.7,4987.7
Exp/Cntr=0.3,0.1

Type RM Length L Ch R = 1,1949,486,486,486
BEGIN DESCRIPTION:
Stream0209_DS 6.0
END DESCRIPTION:
XS GIS Cut Line= 3
      2092225.02     13884925.00      2092325.00     13884925.00
      2092524.97     13884875.01
#Sta/Elev= 30
  4900.5 1187.95  4903.0 1187.95  4910.5 1187.08  4930.5 1184.25  4940.5 1183.16
  4950.5 1181.29  4960.5 1178.65  4980.5 1175.54  4990.5 1173.19  4998.0 1170.88
  5003.1 1170.88  5008.8 1167.93  5009.0 1167.43  5012.5 1167.43  5012.8 1167.93
  5023.7 1167.96  5031.4 1168.79  5052.0 1169.27  5059.7 1169.04  5093.2 1169.33
  5106.1 1170.27  5113.9 1171.66  5134.5 1176.86  5142.2 1179.65  5147.4 1178.92
  5165.4 1184.14  5175.7 1186.25  5180.9 1186.71  5183.4 1187.17  5206.6 1188.29
#Mann=3,-1,0
  4900.5    0.12       0  5008.8    0.05       0  5012.8    0.12       0
Bank Sta=5008.8,5012.8
Exp/Cntr=0.3,0.1

Type RM Length L Ch R = 1,1463,443,443,443
BEGIN DESCRIPTION:
Stream0209_DS 5.0
END DESCRIPTION:
XS GIS Cut Line= 3
      2092224.95     13885324.99      2092425.00     13885375.00
      2092675.04     13885274.99
#Sta/Elev= 30
  4789.7 1184.03  4812.9 1182.56  4831.0 1180.18  4849.0 1178.66  4854.2 1178.96
  4861.9 1177.17  4890.2 1167.51  4895.4 1167.00  4903.1 1164.53  4923.7 1162.76
  4954.7 1162.35  4972.7 1161.50  5000.4 1161.34  5015.4 1161.10  5015.7 1160.60
  5019.2 1160.60  5019.4 1161.10  5049.8 1162.26  5103.6 1162.39  5125.1 1164.14
  5135.9 1166.50  5142.6 1169.15  5148.0 1170.11  5157.5 1174.11  5179.0 1180.43
  5201.9 1186.21  5215.3 1188.40  5220.7 1189.62  5232.9 1191.12  5265.2 1193.15
#Mann=5,-1,0
  4789.7    0.12       0  5000.4    0.07       0  5015.4    0.05       0
  5019.4    0.07       0  5215.3    0.12       0
Bank Sta=5015.4,5019.4
Exp/Cntr=0.3,0.1

Type RM Length L Ch R = 1,1020,90,90,90
BEGIN DESCRIPTION:
Stream0209_DS 4.0
END DESCRIPTION:
XS GIS Cut Line= 3
      2092175.01     13885525.01      2092475.00     13885775.00
      2092775.04     13885574.97
#Sta/Elev= 30
  4600.5 1180.69  4644.2 1179.36  4735.2 1173.13  4743.0 1171.99  4749.5 1172.00
  4792.0 1168.30  4803.7 1167.48  4827.6 1165.56  4842.0 1163.32  4856.3 1162.40
  4917.1 1160.60  4948.7 1159.61  4983.8 1159.84  5038.6 1159.10  5038.8 1158.60
  5042.3 1158.60  5042.6 1159.10  5063.1 1159.92  5163.8 1161.24  5193.8 1163.46
  5207.3 1162.98  5218.3 1164.49  5235.9 1169.06  5250.9 1175.55  5256.9 1176.99
  5265.9 1180.55  5279.4 1181.96  5302.0 1186.82  5323.0 1189.30  5351.6 1191.23
#Mann=8,-1,0
  4600.5    0.12       0  4644.2    0.07       0  4792.0    0.12       0
  4803.7    0.07       0  4917.1   0.035       0  5038.6   0.035       0
  5042.6   0.035       0  5218.3    0.12       0
Bank Sta=5038.6,5042.6
Exp/Cntr=0.3,0.1

Type RM Length L Ch R = 1,930,199,199,199
BEGIN DESCRIPTION:
Stream0209_DS 3.0
END DESCRIPTION:
XS GIS Cut Line= 3
      2092297.32     13885779.55      2092474.88     13885858.21
      2092861.31     13885730.46
#Sta/Elev= 30
  4805.8 1169.16  4815.8 1168.58  4836.6 1166.63  4847.0 1164.14  4859.9 1164.83
  4868.9 1163.35  4883.1 1162.94  4913.9 1160.11  4976.3 1159.54  4981.7 1159.37
  4987.2 1158.01  4987.4 1157.51  4991.2 1158.01  5021.0 1160.06  5059.0 1160.80
  5089.8 1162.80  5121.5 1162.85  5137.0 1161.84  5153.2 1163.29  5200.2 1164.42
  5216.7 1166.28  5242.4 1166.54  5248.4 1168.21  5253.7 1167.81  5274.0 1173.90
  5280.1 1176.86  5295.0 1179.67  5361.4 1186.41  5389.8 1188.69  5407.0 1189.18
#Mann=7,-1,0
  4805.8    0.07       0  4815.8   0.035       0  4913.9    0.07       0
  4987.2    0.05       0  4991.2    0.07       0  5059.0   0.035       0
  5361.4    0.12       0
Bank Sta=4987.2,4991.2
Exp/Cntr=0.3,0.1

Type RM Length L Ch R = 1,731,203,203,203
BEGIN DESCRIPTION:
Stream0209_DS 2.0
END DESCRIPTION:
XS GIS Cut Line= 3
      2092238.32     13885787.95      2092409.98     13886024.66
      2092606.33     13886077.35
#Sta/Elev= 30
  4707.6 1170.15  4725.0 1169.23  4745.9 1168.80  4775.2 1166.55  4817.0 1164.23
  4846.4 1163.83  4867.2 1163.03  4911.3 1162.60  4946.9 1158.03  4961.6 1153.10
  4967.8 1151.48  4980.4 1145.85  4980.7 1145.35  4984.2 1145.35  4984.4 1145.85
  4988.6 1148.19  5000.0 1147.57  5005.2 1148.86  5015.5 1149.60  5020.7 1148.81
  5036.3 1147.75  5046.6 1147.89  5060.7 1157.13  5067.3 1160.35  5073.7 1161.19
  5088.0 1163.16  5119.1 1163.42  5160.5 1164.58  5181.2 1164.11  5203.3 1164.64
#Mann=4,-1,0
  4707.6    0.07       0  4980.4    0.05       0  4984.4    0.07       0
  5073.7   0.035       0
Bank Sta=4980.4,4984.4
Exp/Cntr=0.3,0.1

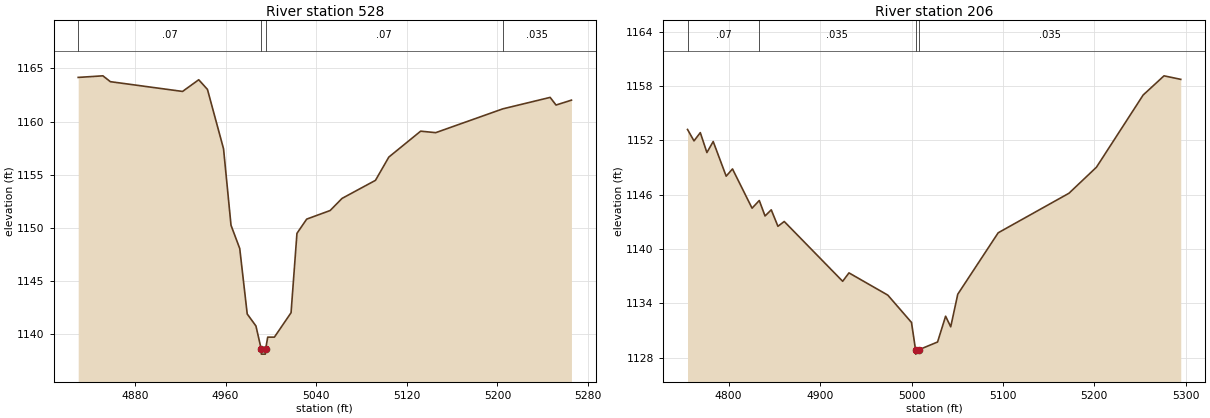
Type RM Length L Ch R = 1,528,322,322,322
BEGIN DESCRIPTION:
Stream0209_DS 1.0
END DESCRIPTION:
XS GIS Cut Line= 3
      2092095.35     13885964.12      2092225.00     13886075.00
      2092480.59     13886144.25
#Sta/Elev= 30
  4829.9 1164.16  4851.7 1164.31  4858.3 1163.76  4922.0 1162.84  4936.3 1163.94
  4944.0 1163.03  4958.2 1157.44  4964.8 1150.24  4972.5 1148.05  4979.1 1141.89
  4986.8 1140.76  4991.4 1138.61  4991.6 1138.11  4995.1 1138.11  4995.4 1138.61
  4997.2 1139.71  5003.1 1139.71  5017.8 1142.01  5023.0 1149.48  5031.6 1150.82
  5052.3 1151.63  5062.8 1152.77  5092.3 1154.47  5104.1 1156.66  5132.2 1159.10
  5145.5 1158.96  5204.7 1161.20  5246.5 1162.28  5251.7 1161.56  5265.3 1162.02
#Mann=4,-1,0
  4829.9    0.07       0  4991.4    0.05       0  4995.4    0.07       0
  5204.7   0.035       0
Bank Sta=4991.4,4995.4
Exp/Cntr=0.3,0.1

Type RM Length L Ch R = 1,206,0,0,0
BEGIN DESCRIPTION:
Stream0209_DS 0.0
END DESCRIPTION:
XS GIS Cut Line= 3
      2092000.73     13886199.51      2092169.25     13886377.34
      2092435.62     13886251.72
#Sta/Elev= 30
  4755.0 1153.21  4762.1 1151.95  4769.0 1152.86  4776.2 1150.66  4783.1 1151.88
  4797.3 1148.05  4804.2 1148.85  4825.6 1144.51  4833.5 1145.36  4839.8 1143.65
  4846.6 1144.33  4853.9 1142.51  4860.8 1143.04  4924.7 1136.43  4931.6 1137.36
  4974.1 1134.90  5000.0 1131.88  5004.4 1128.88  5004.6 1128.38  5008.4 1128.88
  5028.5 1129.72  5037.3 1132.57  5042.9 1131.40  5050.6 1135.00  5094.8 1141.79
  5172.2 1146.16  5202.3 1149.04  5253.4 1157.02  5276.2 1159.14  5294.5 1158.75
#Mann=4,-1,0
  4755.0    0.07       0  4833.5   0.035       0  5004.4   0.035       0
  5008.4   0.035       0
Bank Sta=5004.4,5008.4
Exp/Cntr=0.3,0.1

Chan Stop Cuts=-1