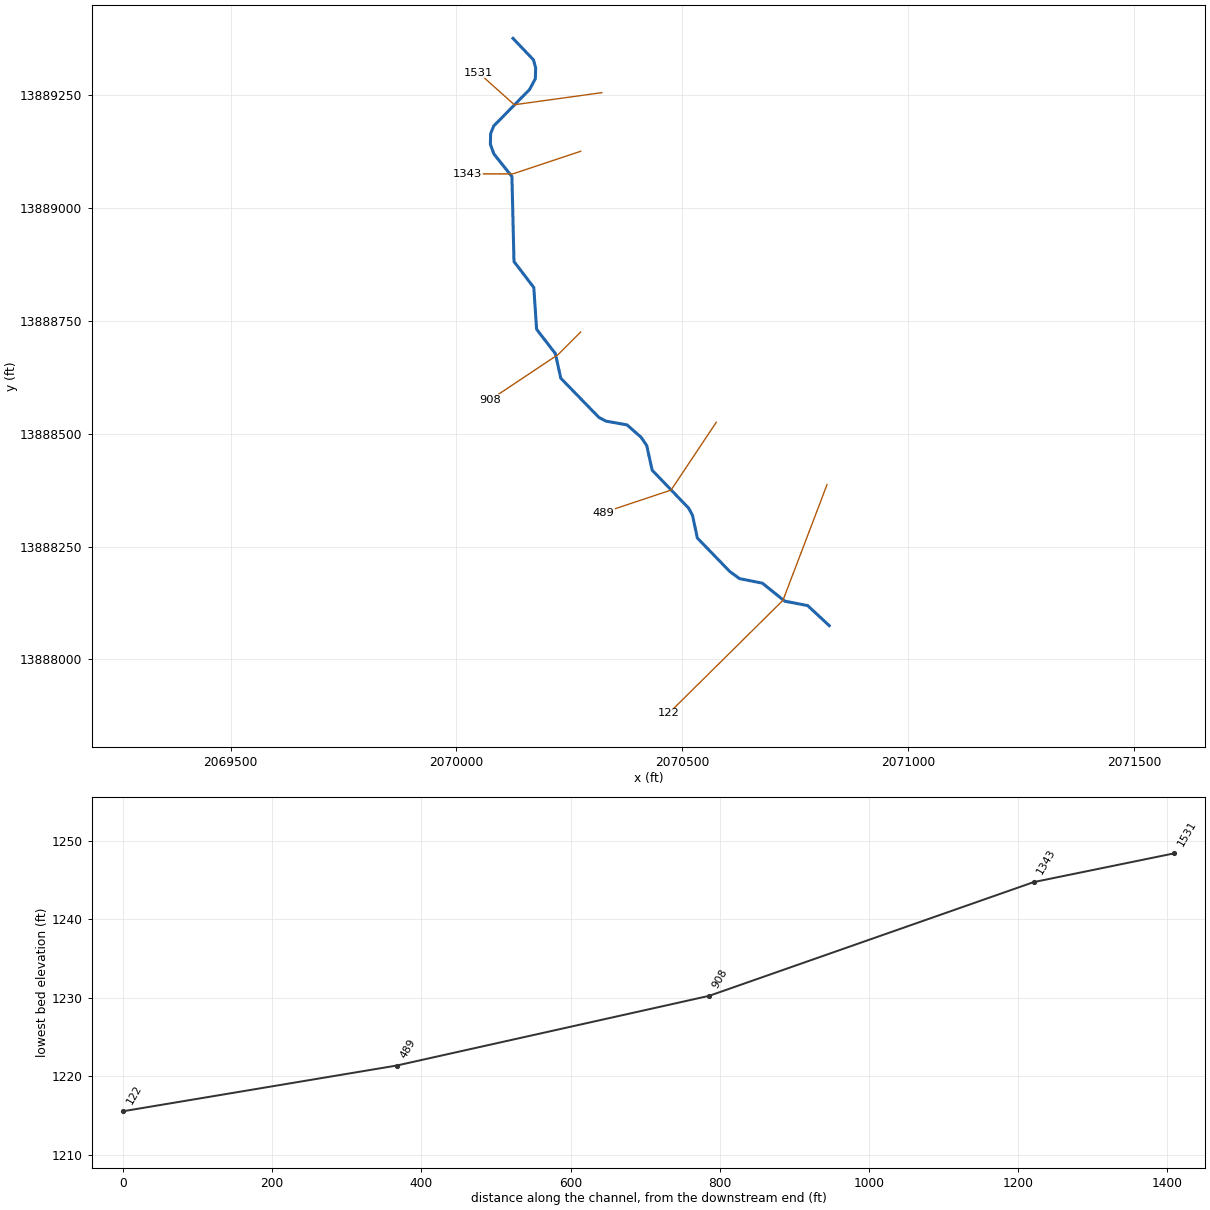
--- Stream0211_DS.prj (project) ---

Proj Title=Stream0211_DS Base Level Engineering
Current Plan=p01
Default Exp/Contr=0.3,0.1
English Units
Geom File=g01
Flow File=f01
Plan File=p01
BEGIN DESCRIPTION:
Stream0211_DS
END DESCRIPTION:

--- Stream0211_DS.p01 (plan) ---

Plan Title=Multiple Run
Short Identifier=Multiple
Geom File=g01
Flow File=f01
Subcritical Flow
K Sum by GR= 0
Std Step Tol= 0.01
Critical Tol= 0.01
Num of Std Step Trials= 20
Max Error Tol= 0.3
Flow Tol Ratio= 0.001
Split Flow NTrial= 30
Split Flow Tol= 0.02
Split Flow Ratio= 0.02
Log Output Level= 0
Friction Slope Method= 1
Unsteady Friction Slope Method= 2
Unsteady Bridges Friction Slope Method= 1
Parabolic Critical Depth
Global Vel Dist=  1 , 1 , 1
Global Log Level= 0
CheckData=True
Encroach Param= -1, 0, 0, 0
BEGIN DESCRIPTION:
Multiple Run
END DESCRIPTION:

--- Stream0211_DS.f01 (steady flow) ---

Flow Title=Multiple
Number of Profiles=7
Profile Names=10-year,25-year,50-year,1pct_min,100-year,1pct_plu,500-year
River Rch & RM= Stream0211_DS,Reach-1,1531
     273     419     545     345     688    1373    1082
Boundary for River Rch & Prof#=Stream0211_DS,Reach-1,1
Up Type=0
Dn Type=3
Dn Slope=0.005
Boundary for River Rch & Prof#=Stream0211_DS,Reach-1,2
Up Type=0
Dn Type=3
Dn Slope=0.005
Boundary for River Rch & Prof#=Stream0211_DS,Reach-1,3
Up Type=0
Dn Type=3
Dn Slope=0.005
Boundary for River Rch & Prof#=Stream0211_DS,Reach-1,4
Up Type=0
Dn Type=3
Dn Slope=0.005
Boundary for River Rch & Prof#=Stream0211_DS,Reach-1,5
Up Type=0
Dn Type=3
Dn Slope=0.005
Boundary for River Rch & Prof#=Stream0211_DS,Reach-1,6
Up Type=0
Dn Type=3
Dn Slope=0.005
Boundary for River Rch & Prof#=Stream0211_DS,Reach-1,7
Up Type=0
Dn Type=3
Dn Slope=0.005

--- Stream0211_DS.g01 (geometry) ---

Geom Title=Existing Conditions

River Reach=Stream0211_DS,Reach-1
Reach XY= 30
      2070125.00     13889375.00      2070170.43     13889327.35
      2070175.32     13889309.57      2070174.50     13889285.55
      2070161.83     13889261.78      2070082.50     13889181.05
      2070075.60     13889164.38      2070075.03     13889140.42
      2070082.79     13889119.09      2070122.71     13889069.07
      2070127.26     13888880.94      2070171.14     13888823.40
      2070177.33     13888730.97      2070218.86     13888677.17
      2070230.82     13888622.69      2070315.32     13888535.78
      2070331.08     13888527.55      2070377.54     13888519.25
      2070408.50     13888492.05      2070421.11     13888473.57
      2070433.18     13888418.98      2070514.20     13888334.67
      2070522.46     13888318.95      2070533.15     13888268.93
      2070604.87     13888194.77      2070626.62     13888178.94
      2070677.19     13888168.90      2070726.67     13888129.04
      2070777.36     13888119.33      2070825.00     13888075.00

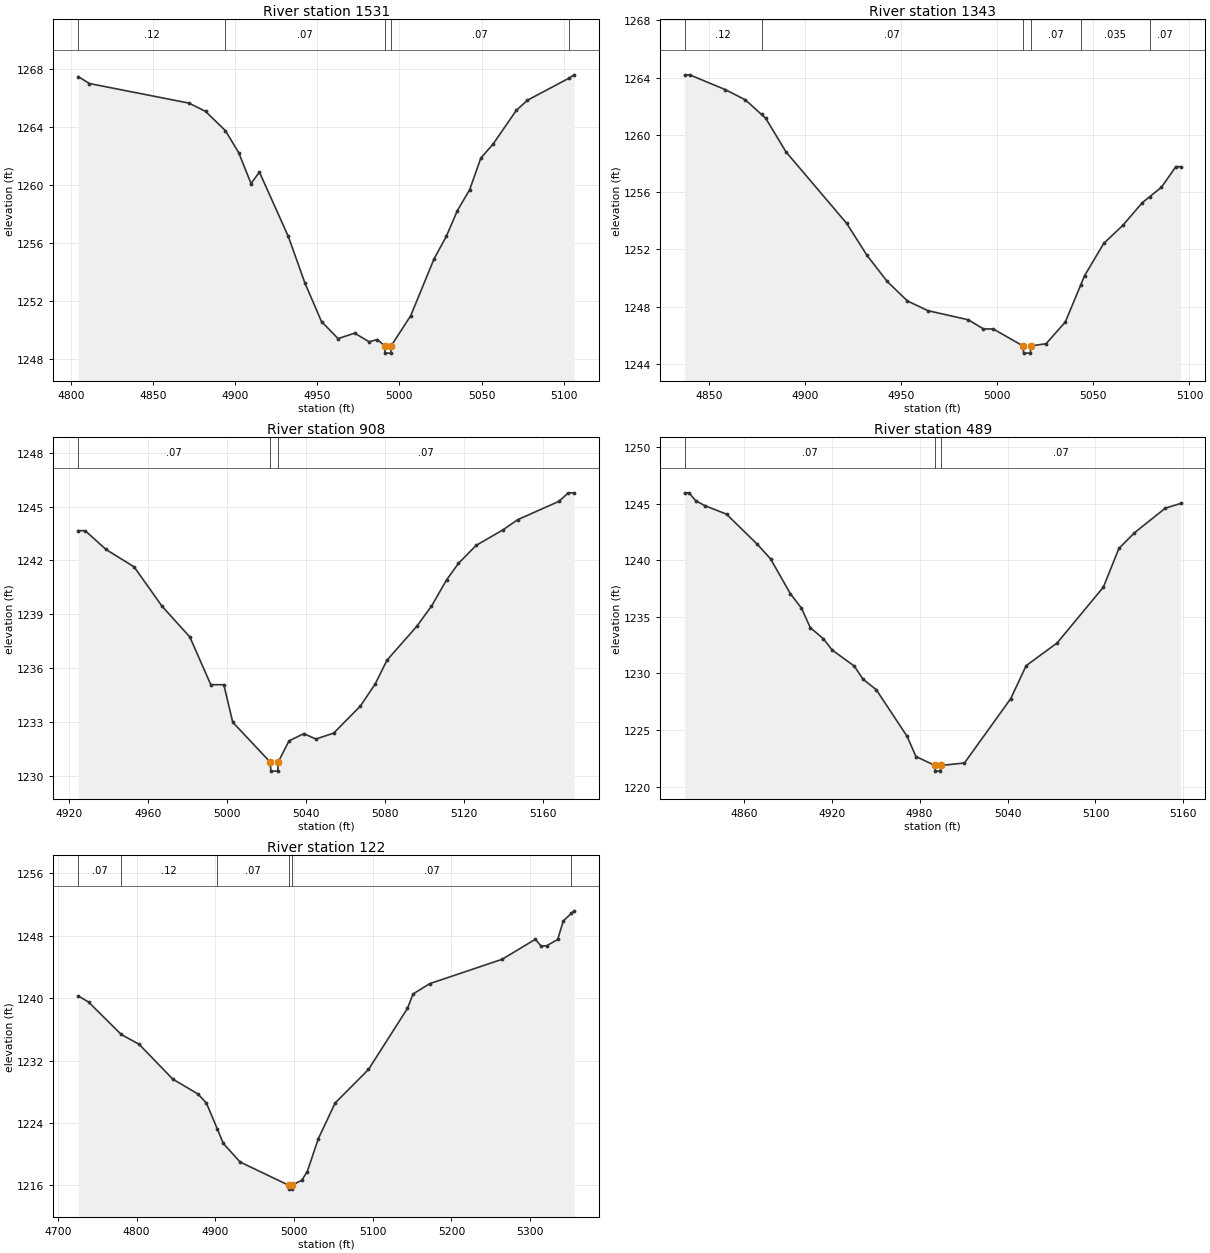
Type RM Length L Ch R = 1,1531,188,188,188
BEGIN DESCRIPTION:
Stream0211_DS 4.0
END DESCRIPTION:
XS GIS Cut Line= 3
      2070321.74     13889254.76      2070128.08     13889227.99
      2070048.79     13889298.93
#Sta/Elev= 30
  4804.5 1267.49  4811.3 1267.01  4871.9 1265.66  4882.0 1265.09  4894.1 1263.76
  4902.2 1262.24  4909.7 1260.11  4914.8 1260.90  4932.4 1256.46  4942.5 1253.25
  4952.6 1250.59  4962.7 1249.41  4972.8 1249.79  4981.6 1249.19  4986.6 1249.35
  4991.0 1248.91  4991.3 1248.41  4994.8 1248.41  4995.0 1248.91  5006.9 1250.99
  5021.1 1254.91  5028.6 1256.47  5035.3 1258.24  5042.8 1259.69  5049.6 1261.87
  5057.1 1262.84  5071.2 1265.16  5078.0 1265.86  5103.1 1267.37  5106.4 1267.61
#Mann=5,-1,0
  4804.5    0.12       0  4894.1    0.07       0  4991.0    0.05       0
  4995.0    0.07       0  5103.1   0.035       0
Bank Sta=4991,4995
Exp/Cntr=0.3,0.1

Type RM Length L Ch R = 1,1343,435,435,435
BEGIN DESCRIPTION:
Stream0211_DS 3.0
END DESCRIPTION:
XS GIS Cut Line= 3
      2070274.99     13889125.00      2070125.00     13889075.00
      2070025.00     13889075.00
#Sta/Elev= 30
  4837.3 1264.20  4839.9 1264.20  4858.4 1263.17  4868.9 1262.45  4877.3 1261.43
  4879.5 1261.16  4890.0 1258.82  4921.6 1253.82  4932.2 1251.58  4942.7 1249.76
  4953.2 1248.40  4963.8 1247.72  4984.9 1247.08  4992.8 1246.44  4997.9 1246.44
  5013.4 1245.25  5013.7 1244.75  5017.2 1244.75  5017.4 1245.25  5025.4 1245.41
  5035.4 1246.93  5043.3 1249.48  5045.4 1250.16  5055.4 1252.42  5065.4 1253.69
  5075.4 1255.26  5079.3 1255.68  5085.4 1256.34  5092.9 1257.78  5095.4 1257.78
#Mann=6,-1,0
  4837.3    0.12       0  4877.3    0.07       0  5013.4    0.05       0
  5017.4    0.07       0  5043.3   0.035       0  5079.3    0.07       0
Bank Sta=5013.4,5017.4
Exp/Cntr=0.3,0.1

Type RM Length L Ch R = 1,908,419,419,419
BEGIN DESCRIPTION:
Stream0211_DS 2.0
END DESCRIPTION:
XS GIS Cut Line= 3
      2070274.98     13888724.98      2070225.00     13888675.00
      2070074.97     13888574.98
#Sta/Elev= 30
  4924.6 1243.66  4928.1 1243.66  4938.7 1242.61  4952.9 1241.64  4967.0 1239.45
  4981.1 1237.73  4991.7 1235.07  4998.3 1235.07  5002.8 1232.98  5021.8 1230.75
  5022.1 1230.25  5025.6 1230.25  5025.8 1230.75  5031.3 1231.94  5038.8 1232.34
  5044.9 1232.04  5053.9 1232.37  5067.4 1233.88  5074.9 1235.11  5080.9 1236.44
  5095.9 1238.32  5103.4 1239.45  5111.0 1240.91  5117.0 1241.83  5126.0 1242.84
  5139.5 1243.70  5147.0 1244.27  5168.0 1245.30  5172.6 1245.77  5175.6 1245.77
#Mann=3,-1,0
  4924.6    0.07       0  5021.8    0.05       0  5025.8    0.07       0
Bank Sta=5021.8,5025.8
Exp/Cntr=0.3,0.1

Type RM Length L Ch R = 1,489,367,367,367
BEGIN DESCRIPTION:
Stream0211_DS 1.0
END DESCRIPTION:
XS GIS Cut Line= 3
      2070575.02     13888525.03      2070475.00     13888375.00
      2070325.02     13888325.01
#Sta/Elev= 30
  4819.7 1245.95  4822.7 1245.95  4827.2 1245.25  4833.3 1244.83  4848.3 1244.06
  4869.3 1241.40  4878.3 1240.12  4891.8 1237.04  4899.4 1235.76  4905.4 1234.04
  4914.4 1233.05  4920.4 1232.05  4935.4 1230.65  4941.4 1229.48  4950.4 1228.56
  4971.5 1224.43  4977.5 1222.65  4990.5 1221.86  4990.7 1221.36  4994.2 1221.36
  4994.5 1221.86  5010.6 1222.08  5042.2 1227.77  5052.7 1230.68  5073.8 1232.68
  5105.4 1237.62  5116.0 1241.04  5126.5 1242.41  5147.6 1244.59  5158.1 1245.01
#Mann=3,-1,0
  4819.7    0.07       0  4990.5    0.05       0  4994.5    0.07       0
Bank Sta=4990.5,4994.5
Exp/Cntr=0.3,0.1

Type RM Length L Ch R = 1,122,0,0,0
BEGIN DESCRIPTION:
Stream0211_DS 0.0
END DESCRIPTION:
XS GIS Cut Line= 3
      2070820.32     13888387.25      2070722.77     13888130.99
      2070469.76     13887880.68
#Sta/Elev= 30
  4725.8 1240.28  4738.9 1239.50  4780.5 1235.34  4803.1 1234.09  4845.9 1229.63
  4878.0 1227.71  4888.7 1226.55  4902.7 1223.20  4910.1 1221.39  4931.5 1219.00
  4993.2 1216.03  4993.4 1215.53  4996.9 1215.53  4997.2 1216.03  5009.8 1216.66
  5016.8 1217.77  5030.9 1222.00  5052.2 1226.56  5094.6 1230.86  5144.1 1238.68
  5151.2 1240.53  5172.4 1241.85  5264.3 1244.97  5306.7 1247.54  5313.8 1246.67
  5320.8 1246.70  5335.0 1247.51  5342.1 1249.89  5352.4 1250.85  5355.9 1251.18
#Mann=6,-1,0
  4725.8    0.07       0  4780.5    0.12       0  4902.7    0.07       0
  4993.2    0.05       0  4997.2    0.07       0  5352.4   0.035       0
Bank Sta=4993.2,4997.2
Exp/Cntr=0.3,0.1

Chan Stop Cuts=-1