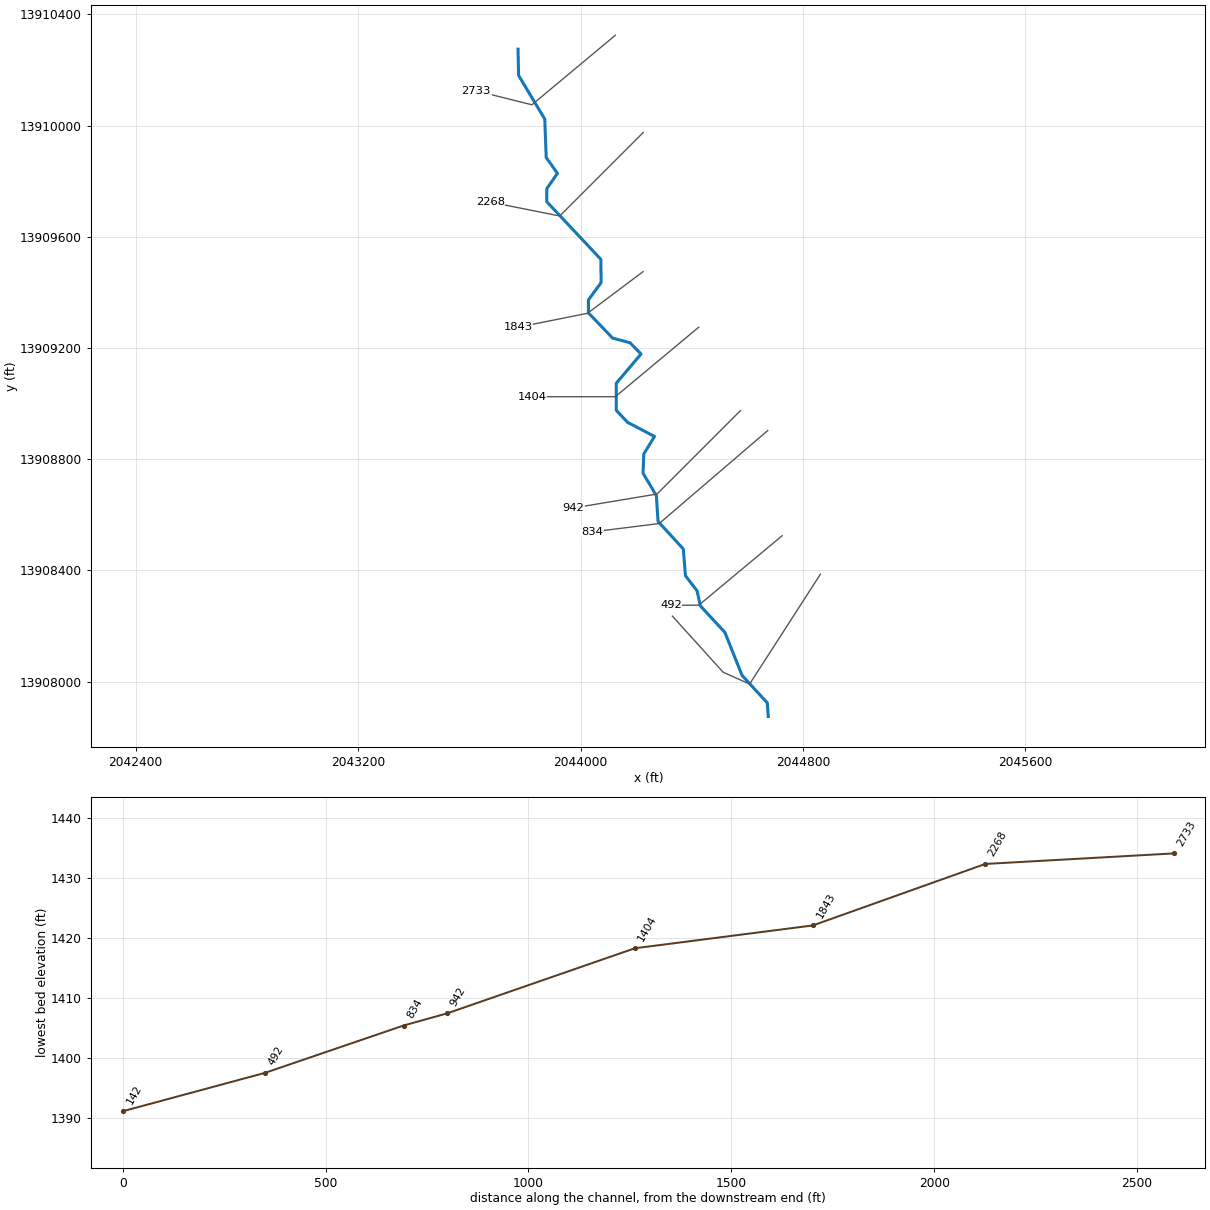
--- Stream0213_DS.prj (project) ---

Proj Title=Stream0213_DS Base Level Engineering
Current Plan=p01
Default Exp/Contr=0.3,0.1
English Units
Geom File=g01
Flow File=f01
Plan File=p01
BEGIN DESCRIPTION:
Stream0213_DS
END DESCRIPTION:

--- Stream0213_DS.p01 (plan) ---

Plan Title=Multiple Run
Short Identifier=Multiple
Geom File=g01
Flow File=f01
Subcritical Flow
K Sum by GR= 0
Std Step Tol= 0.01
Critical Tol= 0.01
Num of Std Step Trials= 20
Max Error Tol= 0.3
Flow Tol Ratio= 0.001
Split Flow NTrial= 30
Split Flow Tol= 0.02
Split Flow Ratio= 0.02
Log Output Level= 0
Friction Slope Method= 1
Unsteady Friction Slope Method= 2
Unsteady Bridges Friction Slope Method= 1
Parabolic Critical Depth
Global Vel Dist=  1 , 1 , 1
Global Log Level= 0
CheckData=True
Encroach Param= -1, 0, 0, 0
BEGIN DESCRIPTION:
Multiple Run
END DESCRIPTION:

--- Stream0213_DS.f01 (steady flow) ---

Flow Title=Multiple
Number of Profiles=7
Profile Names=10-year,25-year,50-year,1pct_min,100-year,1pct_plu,500-year
River Rch & RM= Stream0213_DS,Reach-1,2733
     491     795    1073     704    1405    2804    2385
Boundary for River Rch & Prof#=Stream0213_DS,Reach-1,1
Up Type=0
Dn Type=3
Dn Slope=0.005
Boundary for River Rch & Prof#=Stream0213_DS,Reach-1,2
Up Type=0
Dn Type=3
Dn Slope=0.005
Boundary for River Rch & Prof#=Stream0213_DS,Reach-1,3
Up Type=0
Dn Type=3
Dn Slope=0.005
Boundary for River Rch & Prof#=Stream0213_DS,Reach-1,4
Up Type=0
Dn Type=3
Dn Slope=0.005
Boundary for River Rch & Prof#=Stream0213_DS,Reach-1,5
Up Type=0
Dn Type=3
Dn Slope=0.005
Boundary for River Rch & Prof#=Stream0213_DS,Reach-1,6
Up Type=0
Dn Type=3
Dn Slope=0.005
Boundary for River Rch & Prof#=Stream0213_DS,Reach-1,7
Up Type=0
Dn Type=3
Dn Slope=0.005

--- Stream0213_DS.g01 (geometry) ---

Geom Title=Existing Conditions

River Reach=Stream0213_DS,Reach-1
Reach XY= 30
      2043775.00     13910275.00      2043777.07     13910180.86
      2043871.24     13910023.44      2043876.39     13909885.44
      2043916.89     13909828.29      2043878.57     13909773.35
      2043878.16     13909726.65      2044073.04     13909519.11
      2044073.88     13909435.55      2044028.34     13909373.25
      2044028.12     13909326.62      2044115.33     13909235.77
      2044177.86     13909219.14      2044217.51     13909178.58
      2044128.48     13909073.50      2044128.37     13908976.28
      2044168.66     13908933.02      2044265.98     13908882.02
      2044227.38     13908819.12      2044224.61     13908750.00
      2044272.64     13908669.02      2044278.62     13908576.50
      2044369.46     13908477.42      2044377.33     13908380.97
      2044418.86     13908327.17      2044430.84     13908272.71
      2044519.15     13908177.29      2044580.84     13908022.70
      2044671.71     13907923.64      2044675.00     13907875.00

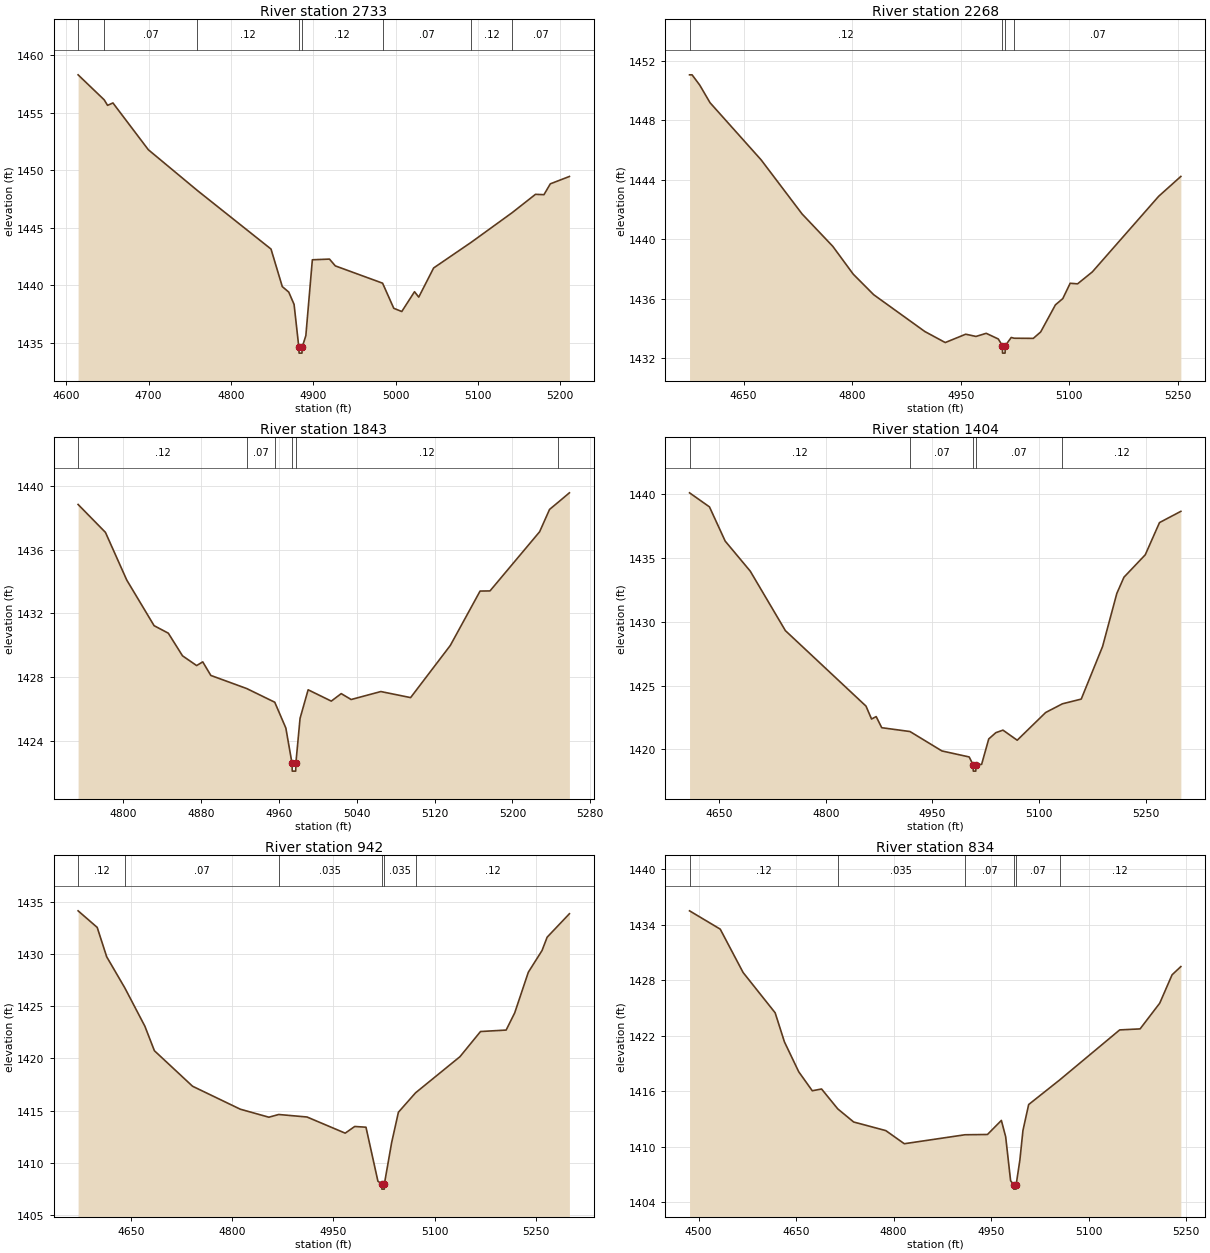
Type RM Length L Ch R = 1,2733,465,465,465
BEGIN DESCRIPTION:
Stream0213_DS 6.0
END DESCRIPTION:
XS GIS Cut Line= 3
      2044125.03     13910325.02      2043825.00     13910075.00
      2043625.00     13910125.00
#Sta/Elev= 30
  4614.3 1458.27  4646.0 1456.10  4650.1 1455.62  4656.6 1455.83  4699.6 1451.77
  4759.2 1448.23  4848.6 1443.15  4862.3 1439.89  4870.1 1439.42  4876.6 1438.35
  4882.4 1434.62  4882.7 1434.12  4886.2 1434.12  4886.4 1434.62  4890.9 1435.64
  4898.8 1442.22  4919.6 1442.28  4926.7 1441.69  4984.1 1440.19  4997.7 1438.01
  5007.4 1437.73  5022.9 1439.45  5028.0 1438.98  5046.1 1441.51  5091.8 1443.74
  5141.5 1446.31  5169.8 1447.90  5180.1 1447.87  5187.8 1448.81  5211.0 1449.45
#Mann=8,-1,0
  4614.3    0.12       0  4646.0    0.07       0  4759.2    0.12       0
  4882.4    0.05       0  4886.4    0.12       0  4984.1    0.07       0
  5091.8    0.12       0  5141.5    0.07       0
Bank Sta=4882.4,4886.4
Exp/Cntr=0.3,0.1

Type RM Length L Ch R = 1,2268,425,425,425
BEGIN DESCRIPTION:
Stream0213_DS 5.0
END DESCRIPTION:
XS GIS Cut Line= 3
      2044225.00     13909975.00      2043925.00     13909675.00
      2043675.01     13909725.00
#Sta/Elev= 30
  4575.2 1451.04  4578.7 1451.04  4589.3 1450.35  4603.5 1449.17  4674.2 1445.33
  4730.8 1441.70  4773.2 1439.53  4801.5 1437.66  4829.8 1436.28  4900.5 1433.81
  4928.7 1433.07  4957.0 1433.63  4971.2 1433.48  4985.3 1433.69  5002.0 1433.31
  5007.7 1432.86  5007.9 1432.36  5011.4 1432.36  5011.7 1432.86  5019.9 1433.41
  5024.1 1433.36  5050.4 1433.35  5060.6 1433.78  5081.0 1435.60  5091.2 1436.02
  5101.4 1437.05  5111.6 1437.01  5132.0 1437.81  5223.8 1442.89  5254.4 1444.22
#Mann=4,-1,0
  4575.2    0.12       0  5007.7    0.05       0  5011.7    0.12       0
  5024.1    0.07       0
Bank Sta=5007.7,5011.7
Exp/Cntr=0.3,0.1

Type RM Length L Ch R = 1,1843,439,439,439
BEGIN DESCRIPTION:
Stream0213_DS 4.0
END DESCRIPTION:
XS GIS Cut Line= 3
      2044224.97     13909474.98      2044025.00     13909325.00
      2043775.01     13909275.00
#Sta/Elev= 30
  4753.7 1438.83  4781.8 1437.08  4803.7 1434.09  4831.8 1431.23  4846.4 1430.76
  4861.0 1429.34  4875.5 1428.73  4881.8 1428.96  4890.1 1428.11  4926.9 1427.29
  4955.8 1426.43  4967.2 1424.81  4973.5 1422.61  4973.8 1422.11  4977.3 1422.11
  4977.5 1422.61  4981.8 1425.42  4990.1 1427.21  5013.9 1426.50  5024.1 1426.97
  5034.3 1426.60  5064.8 1427.10  5095.4 1426.72  5136.2 1429.99  5166.8 1433.40
  5177.0 1433.41  5228.0 1437.12  5238.2 1438.52  5246.9 1438.96  5258.6 1439.56
#Mann=6,-1,0
  4753.7    0.12       0  4926.9    0.07       0  4955.8    0.12       0
  4973.5    0.05       0  4977.5    0.12       0  5246.9    0.07       0
Bank Sta=4973.5,4977.5
Exp/Cntr=0.3,0.1

Type RM Length L Ch R = 1,1404,462,462,462
BEGIN DESCRIPTION:
Stream0213_DS 3.0
END DESCRIPTION:
XS GIS Cut Line= 3
      2044425.00     13909275.00      2044125.00     13909025.00
      2043825.01     13909025.00
#Sta/Elev= 30
  4608.6 1440.09  4636.6 1438.99  4658.7 1436.31  4693.9 1433.96  4743.3 1429.30
  4856.6 1423.39  4864.4 1422.38  4870.9 1422.57  4878.7 1421.70  4918.4 1421.40
  4963.3 1419.88  5001.6 1419.41  5007.1 1418.80  5007.4 1418.30  5010.9 1418.30
  5011.1 1418.80  5019.1 1418.83  5029.1 1420.82  5039.1 1421.31  5049.1 1421.51
  5069.1 1420.72  5109.1 1422.89  5132.6 1423.57  5159.1 1423.94  5189.1 1428.06
  5209.1 1432.21  5219.1 1433.48  5249.1 1435.24  5269.1 1437.76  5299.1 1438.64
#Mann=5,-1,0
  4608.6    0.12       0  4918.4    0.07       0  5007.1    0.05       0
  5011.1    0.07       0  5132.6    0.12       0
Bank Sta=5007.1,5011.1
Exp/Cntr=0.3,0.1

Type RM Length L Ch R = 1,942,108,108,108
BEGIN DESCRIPTION:
Stream0213_DS 2.0
END DESCRIPTION:
XS GIS Cut Line= 3
      2044574.98     13908974.98      2044275.00     13908675.00
      2043974.98     13908625.00
#Sta/Elev= 30
  4571.4 1434.16  4599.7 1432.57  4613.8 1429.75  4640.8 1426.75  4670.4 1423.09
  4684.5 1420.74  4741.1 1417.33  4811.8 1415.13  4854.2 1414.36  4868.8 1414.62
  4910.8 1414.38  4967.4 1412.83  4981.5 1413.47  4998.2 1413.40  5015.9 1408.22
  5021.5 1407.96  5021.8 1407.46  5025.3 1407.46  5025.5 1407.96  5036.2 1411.91
  5046.3 1414.84  5071.7 1416.70  5137.6 1420.17  5168.0 1422.58  5206.0 1422.72
  5218.7 1424.37  5238.9 1428.27  5259.2 1430.35  5266.8 1431.63  5299.8 1433.88
#Mann=6,-1,0
  4571.4    0.12       0  4640.8    0.07       0  4868.8   0.035       0
  5021.5   0.035       0  5025.5   0.035       0  5071.7    0.12       0
Bank Sta=5021.5,5025.5
Exp/Cntr=0.3,0.1

Type RM Length L Ch R = 1,834,342,342,342
BEGIN DESCRIPTION:
Stream0213_DS 1.5
END DESCRIPTION:
XS GIS Cut Line= 3
      2044673.03     13908903.16      2044282.88     13908568.84
      2044042.75     13908538.81
#Sta/Elev= 30
  4486.2 1435.52  4533.4 1433.54  4568.6 1428.85  4617.9 1424.49  4632.2 1421.34
  4654.2 1418.11  4675.0 1416.06  4689.3 1416.25  4714.2 1414.10  4738.7 1412.68
  4788.1 1411.75  4816.6 1410.33  4910.0 1411.30  4944.5 1411.33  4965.9 1412.85
  4972.5 1411.09  4980.1 1406.33  4984.7 1405.92  4985.0 1405.42  4988.5 1405.42
  4988.7 1405.92  4994.4 1408.58  4999.1 1411.77  5007.9 1414.57  5055.6 1417.23
  5147.9 1422.64  5179.3 1422.75  5209.5 1425.53  5228.5 1428.60  5242.0 1429.49
#Mann=6,-1,0
  4486.2    0.12       0  4714.2   0.035       0  4910.0    0.07       0
  4984.7    0.05       0  4988.7    0.07       0  5055.6    0.12       0
Bank Sta=4984.7,4988.7
Exp/Cntr=0.3,0.1

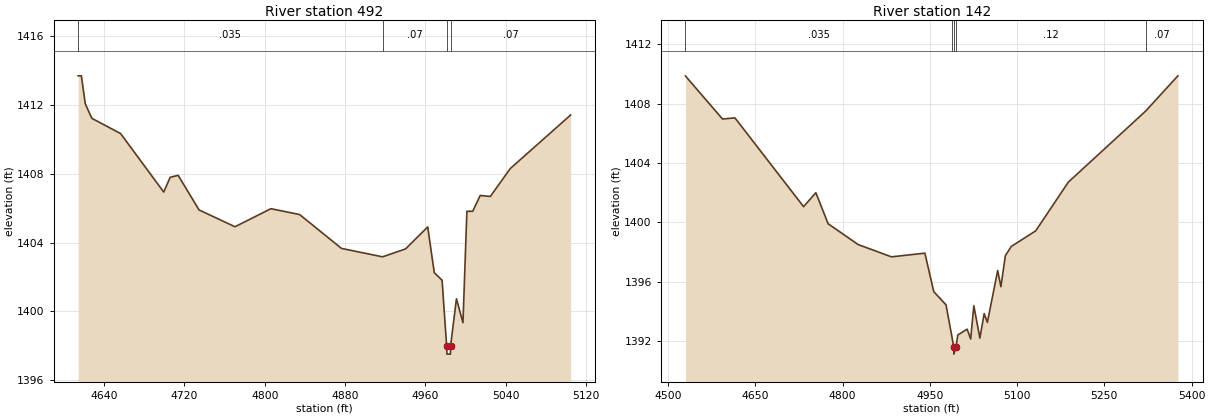
Type RM Length L Ch R = 1,492,350,350,350
BEGIN DESCRIPTION:
Stream0213_DS 1.0
END DESCRIPTION:
XS GIS Cut Line= 3
      2044724.98     13908524.99      2044425.00     13908275.00
      2044324.99     13908275.00
#Sta/Elev= 30
  4614.1 1413.71  4617.3 1413.71  4621.2 1412.08  4627.7 1411.24  4656.4 1410.35
  4699.3 1406.95  4705.8 1407.81  4713.7 1407.92  4734.5 1405.91  4770.3 1404.93
  4806.1 1405.98  4834.7 1405.64  4876.4 1403.67  4917.3 1403.18  4940.2 1403.64
  4962.3 1404.92  4968.8 1402.26  4976.6 1401.82  4981.1 1398.02  4981.4 1397.52
  4984.9 1397.52  4985.1 1398.02  4990.9 1400.74  4997.4 1399.35  5001.3 1405.83
  5007.1 1405.83  5014.6 1406.75  5024.6 1406.69  5044.6 1408.32  5104.6 1411.43
#Mann=4,-1,0
  4614.1   0.035       0  4917.3    0.07       0  4981.1    0.05       0
  4985.1    0.07       0
Bank Sta=4981.1,4985.1
Exp/Cntr=0.3,0.1

Type RM Length L Ch R = 1,142,0,0,0
BEGIN DESCRIPTION:
Stream0213_DS 0.0
END DESCRIPTION:
XS GIS Cut Line= 4
      2044862.62     13908386.47      2044608.00     13907991.53
      2044513.13     13908033.81      2044330.18     13908235.81
#Sta/Elev= 30
  4530.1 1409.86  4593.8 1406.96  4615.1 1407.04  4733.1 1401.06  4754.2 1402.00
  4775.3 1399.91  4826.8 1398.51  4884.2 1397.68  4941.6 1397.93  4956.8 1395.34
  4977.9 1394.45  4987.5 1392.42  4991.1 1391.63  4991.4 1391.13  4995.1 1391.63
  4998.2 1392.42  5014.2 1392.81  5020.3 1392.15  5025.7 1394.39  5036.1 1392.21
  5043.5 1393.86  5049.0 1393.27  5066.7 1396.76  5072.2 1395.67  5079.9 1397.76
  5090.0 1398.38  5132.0 1399.43  5188.1 1402.71  5321.1 1407.50  5376.4 1409.87
#Mann=5,-1,0
  4530.1   0.035       0  4987.5    0.12       0  4991.1    0.05       0
  4995.1    0.12       0  5321.1    0.07       0
Bank Sta=4991.1,4995.1
Exp/Cntr=0.3,0.1

Chan Stop Cuts=-1