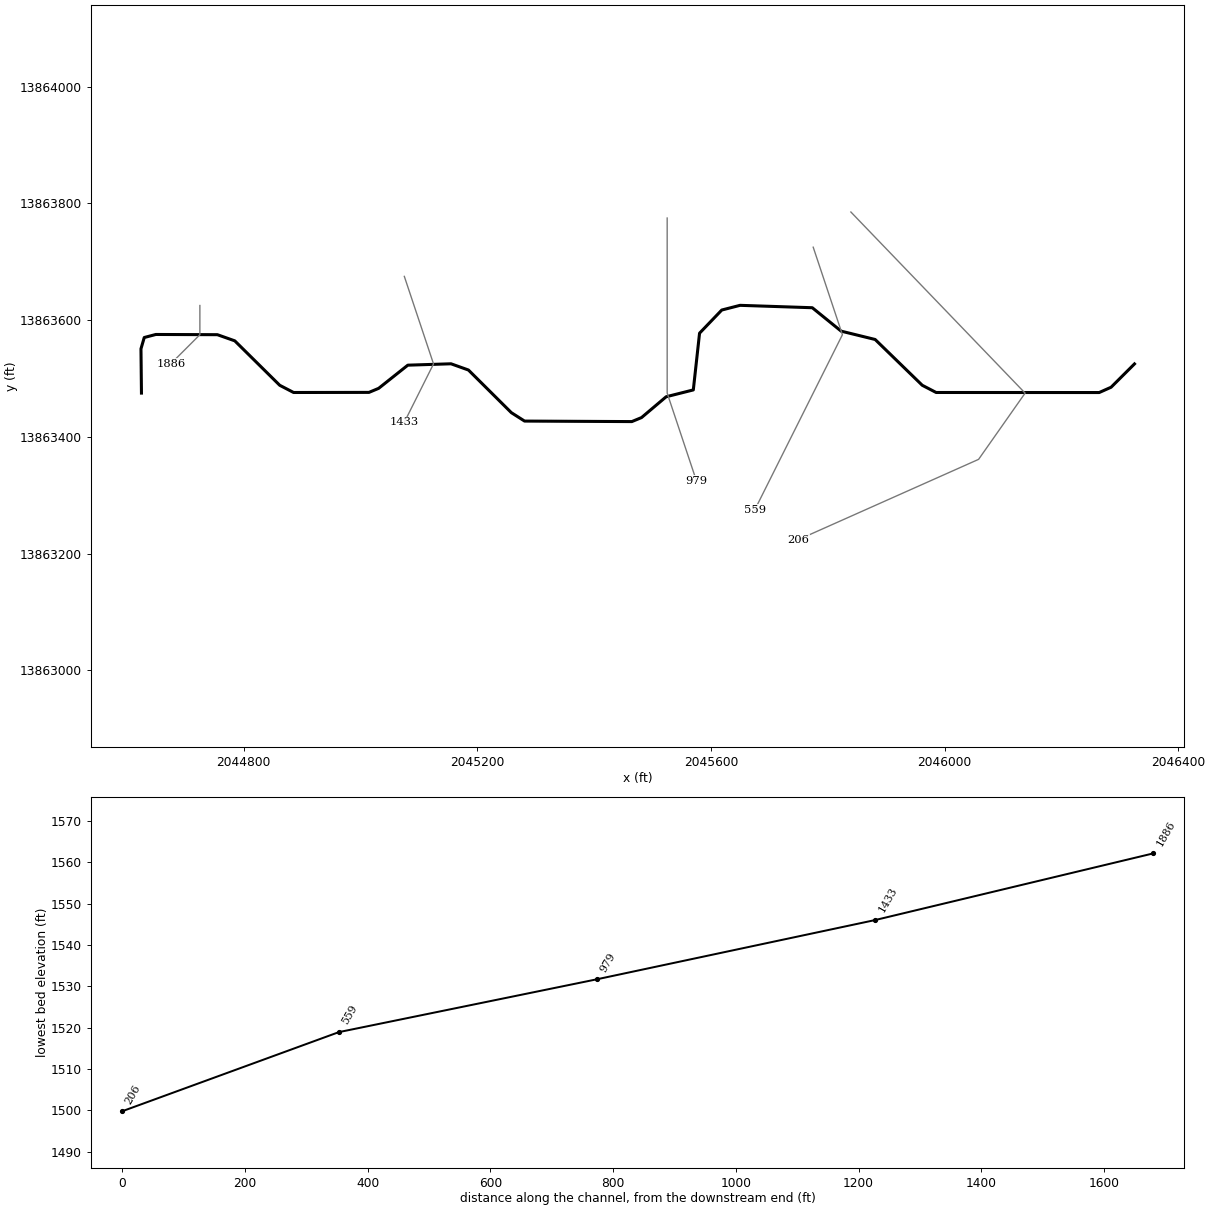
--- Stream0215_DS.prj (project) ---

Proj Title=Stream0215_DS Base Level Engineering
Current Plan=p01
Default Exp/Contr=0.3,0.1
English Units
Geom File=g01
Flow File=f01
Plan File=p01
BEGIN DESCRIPTION:
Stream0215_DS
END DESCRIPTION:

--- Stream0215_DS.p01 (plan) ---

Plan Title=Multiple Run
Short Identifier=Multiple
Geom File=g01
Flow File=f01
Subcritical Flow
K Sum by GR= 0
Std Step Tol= 0.01
Critical Tol= 0.01
Num of Std Step Trials= 20
Max Error Tol= 0.3
Flow Tol Ratio= 0.001
Split Flow NTrial= 30
Split Flow Tol= 0.02
Split Flow Ratio= 0.02
Log Output Level= 0
Friction Slope Method= 1
Unsteady Friction Slope Method= 2
Unsteady Bridges Friction Slope Method= 1
Parabolic Critical Depth
Global Vel Dist=  1 , 1 , 1
Global Log Level= 0
CheckData=True
Encroach Param= -1, 0, 0, 0
BEGIN DESCRIPTION:
Multiple Run
END DESCRIPTION:

--- Stream0215_DS.f01 (steady flow) ---

Flow Title=Multiple
Number of Profiles=7
Profile Names=10-year,25-year,50-year,1pct_min,100-year,1pct_plu,500-year
River Rch & RM= Stream0215_DS,Reach-1,1886
     384     609     811     527    1052    2099    1740
Boundary for River Rch & Prof#=Stream0215_DS,Reach-1,1
Up Type=0
Dn Type=3
Dn Slope=0.005
Boundary for River Rch & Prof#=Stream0215_DS,Reach-1,2
Up Type=0
Dn Type=3
Dn Slope=0.005
Boundary for River Rch & Prof#=Stream0215_DS,Reach-1,3
Up Type=0
Dn Type=3
Dn Slope=0.005
Boundary for River Rch & Prof#=Stream0215_DS,Reach-1,4
Up Type=0
Dn Type=3
Dn Slope=0.005
Boundary for River Rch & Prof#=Stream0215_DS,Reach-1,5
Up Type=0
Dn Type=3
Dn Slope=0.005
Boundary for River Rch & Prof#=Stream0215_DS,Reach-1,6
Up Type=0
Dn Type=3
Dn Slope=0.005
Boundary for River Rch & Prof#=Stream0215_DS,Reach-1,7
Up Type=0
Dn Type=3
Dn Slope=0.005

--- Stream0215_DS.g01 (geometry) ---

Geom Title=Existing Conditions

River Reach=Stream0215_DS,Reach-1
Reach XY= 30
      2044625.00     13863475.00      2044624.16     13863550.84
      2044629.78     13863570.23      2044649.60     13863575.44
      2044754.99     13863575.07      2044784.79     13863564.51
      2044861.70     13863488.40      2044885.44     13863476.04
      2045014.49     13863476.21      2045031.06     13863483.14
      2045080.98     13863522.84      2045154.95     13863525.21
      2045184.78     13863514.54      2045258.25     13863441.47
      2045280.86     13863427.06      2045464.52     13863426.19
      2045481.12     13863433.07      2045523.22     13863468.70
      2045569.75     13863480.44      2045580.43     13863577.65
      2045618.48     13863617.33      2045649.79     13863625.36
      2045773.44     13863621.26      2045822.83     13863581.14
      2045881.05     13863566.84      2045961.69     13863488.40
      2045985.44     13863476.05      2046264.60     13863475.96
      2046284.98     13863485.05      2046325.00     13863525.00

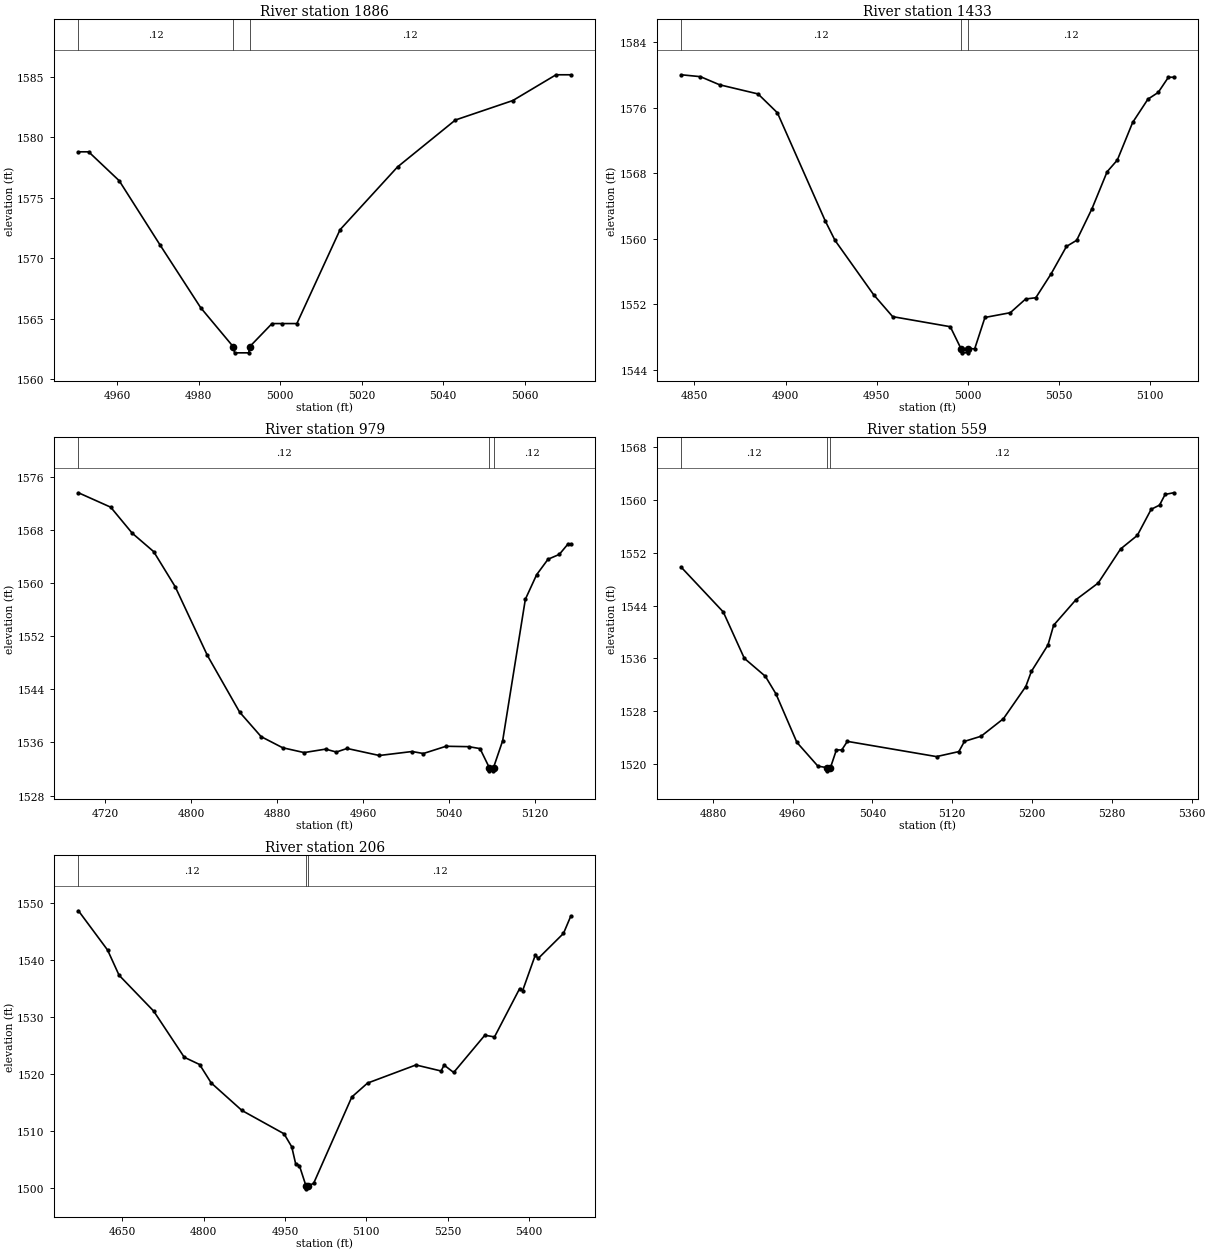
Type RM Length L Ch R = 1,1886,453,453,453
BEGIN DESCRIPTION:
Stream0215_DS 4.0
END DESCRIPTION:
XS GIS Cut Line= 3
      2044725.00     13863625.05      2044725.00     13863575.00
      2044674.97     13863524.97
#Sta/Elev= 18
  4950.5 1578.81  4953.0 1578.81  4960.5 1576.42  4970.5 1571.12  4980.5 1565.92
  4988.5 1562.69  4988.8 1562.19  4992.3 1562.19  4992.5 1562.69  4998.0 1564.61
  5000.5 1564.61  5004.1 1564.61  5014.7 1572.37  5028.8 1577.56  5043.0 1581.44
  5057.1 1583.05  5067.7 1585.18  5071.3 1585.18
#Mann=3,-1,0
  4950.5    0.12       0  4988.5    0.05       0  4992.5    0.12       0
Bank Sta=4988.5,4992.5
Exp/Cntr=0.3,0.1

Type RM Length L Ch R = 1,1433,454,454,454
BEGIN DESCRIPTION:
Stream0215_DS 3.0
END DESCRIPTION:
XS GIS Cut Line= 3
      2045075.01     13863674.96      2045125.00     13863525.00
      2045074.99     13863424.98
#Sta/Elev= 30
  4842.8 1580.02  4853.3 1579.79  4863.8 1578.80  4884.9 1577.68  4895.5 1575.38
  4921.8 1562.15  4927.1 1559.80  4948.2 1553.19  4958.7 1550.49  4990.3 1549.26
  4996.2 1546.57  4996.5 1546.07  5000.0 1546.07  5000.2 1546.57  5003.7 1546.57
  5009.3 1550.39  5023.2 1550.97  5031.6 1552.64  5037.2 1552.80  5045.6 1555.72
  5054.0 1559.06  5059.6 1559.81  5068.0 1563.67  5076.3 1568.18  5081.9 1569.61
  5090.3 1574.20  5098.7 1577.05  5104.3 1577.86  5109.9 1579.72  5112.7 1579.72
#Mann=3,-1,0
  4842.8    0.12       0  4996.2    0.05       0  5000.2    0.12       0
Bank Sta=4996.2,5000.2
Exp/Cntr=0.3,0.1

Type RM Length L Ch R = 1,979,420,420,420
BEGIN DESCRIPTION:
Stream0215_DS 2.0
END DESCRIPTION:
XS GIS Cut Line= 3
      2045525.00     13863774.95      2045525.00     13863475.00
      2045575.01     13863324.97
#Sta/Elev= 30
  4695.1 1573.59  4725.1 1571.42  4745.1 1567.51  4765.1 1564.73  4785.1 1559.45
  4815.1 1549.09  4845.1 1540.56  4865.1 1536.87  4885.1 1535.20  4905.1 1534.47
  4925.1 1534.99  4935.1 1534.55  4945.1 1535.09  4975.1 1534.03  5005.6 1534.63
  5016.1 1534.33  5037.2 1535.42  5058.3 1535.36  5068.8 1535.07  5077.4 1532.22
  5077.6 1531.72  5081.1 1531.72  5081.4 1532.22  5089.9 1536.26  5111.0 1557.55
  5121.5 1561.25  5132.1 1563.58  5142.6 1564.31  5150.5 1565.84  5153.2 1565.84
#Mann=3,-1,0
  4695.1    0.12       0  5077.4    0.05       0  5081.4    0.12       0
Bank Sta=5077.4,5081.4
Exp/Cntr=0.3,0.1

Type RM Length L Ch R = 1,559,353,353,353
BEGIN DESCRIPTION:
Stream0215_DS 1.0
END DESCRIPTION:
XS GIS Cut Line= 3
      2045775.00     13863724.99      2045825.00     13863575.00
      2045675.00     13863275.01
#Sta/Elev= 30
  4848.3 1549.83  4890.4 1543.05  4911.5 1536.02  4932.6 1533.29  4943.2 1530.63
  4964.2 1523.27  4985.3 1519.66  4993.9 1519.45  4994.1 1518.95  4997.9 1519.45
  5003.8 1522.12  5009.2 1522.12  5014.8 1523.42  5104.2 1521.11  5126.6 1521.87
  5132.2 1523.42  5148.9 1524.20  5171.3 1526.86  5193.7 1531.74  5199.3 1534.03
  5216.0 1538.06  5221.6 1541.03  5244.0 1544.91  5266.3 1547.44  5288.7 1552.60
  5305.5 1554.66  5319.4 1558.62  5327.8 1559.26  5333.4 1560.88  5341.8 1561.13
#Mann=3,-1,0
  4848.3    0.12       0  4993.9    0.05       0  4997.9    0.12       0
Bank Sta=4993.9,4997.9
Exp/Cntr=0.3,0.1

Type RM Length L Ch R = 1,206,0,0,0
BEGIN DESCRIPTION:
Stream0215_DS 0.0
END DESCRIPTION:
XS GIS Cut Line= 4
      2045839.50     13863785.25      2046137.77     13863474.96
      2046058.14     13863361.49      2045749.47     13863223.83
#Sta/Elev= 30
  4569.6 1548.70  4623.3 1541.79  4644.4 1537.37  4708.2 1531.06  4764.5 1522.95
  4792.8 1521.67  4814.2 1518.43  4870.8 1513.59  4948.4 1509.49  4962.6 1507.20
  4969.8 1504.22  4976.7 1503.89  4988.9 1500.31  4989.1 1499.81  4992.9 1500.31
  5003.0 1500.79  5073.3 1515.96  5102.2 1518.40  5191.4 1521.59  5237.8 1520.53
  5243.3 1521.57  5261.0 1520.27  5318.4 1526.82  5336.2 1526.52  5382.6 1535.03
  5388.1 1534.67  5411.3 1540.89  5416.8 1540.32  5463.3 1544.72  5476.6 1547.72
#Mann=3,-1,0
  4569.6    0.12       0  4988.9    0.05       0  4992.9    0.12       0
Bank Sta=4988.9,4992.9
Exp/Cntr=0.3,0.1

Chan Stop Cuts=-1