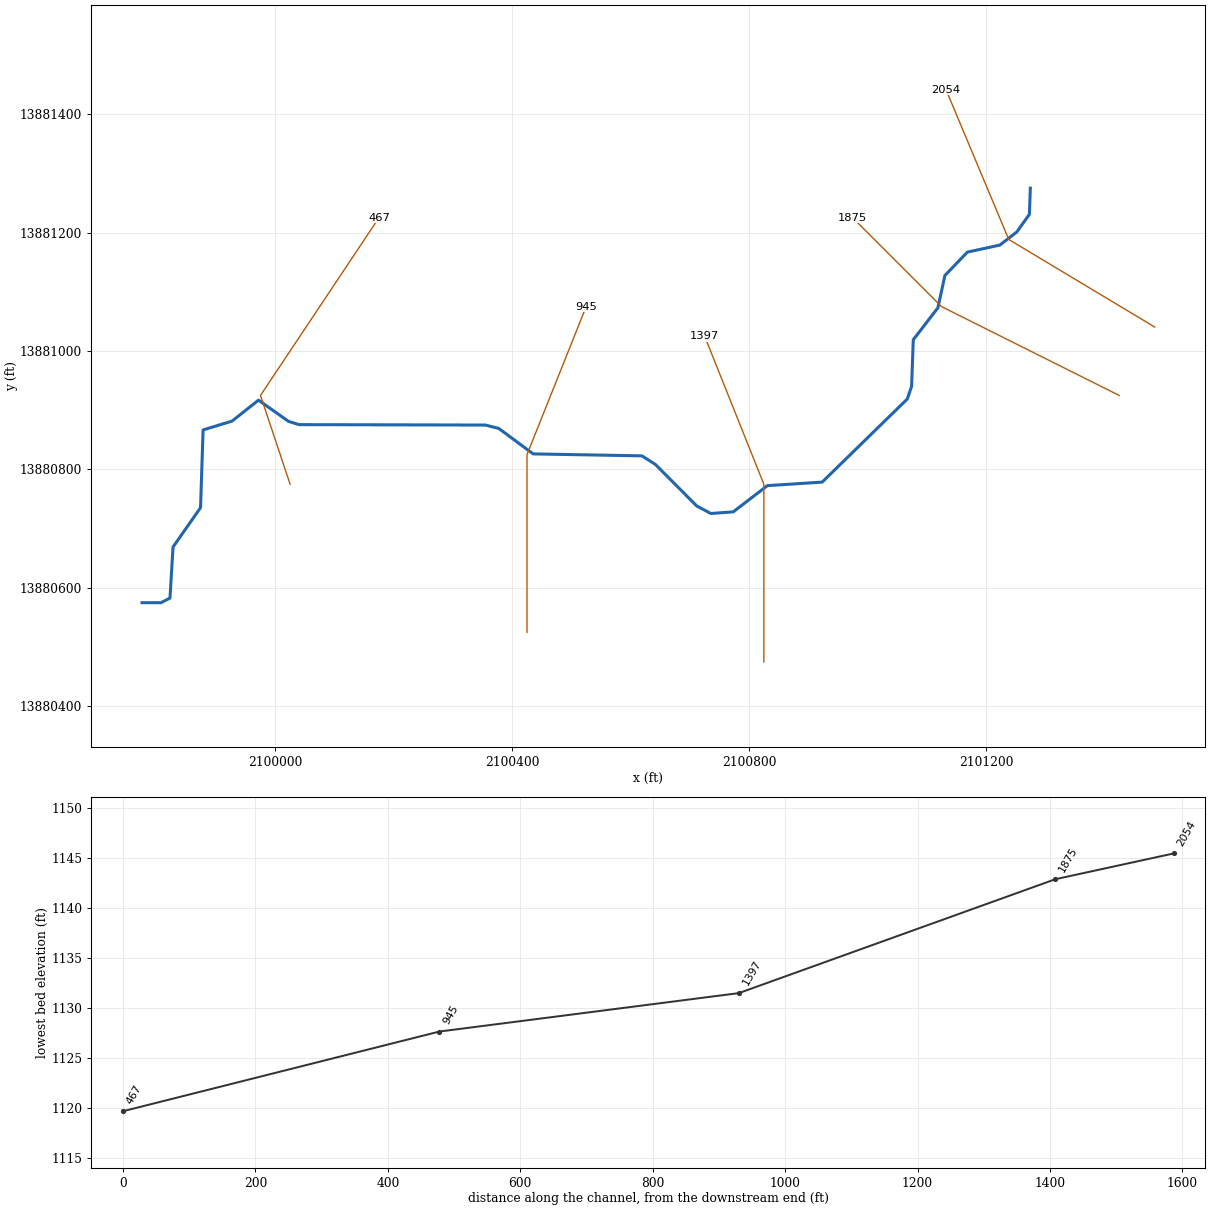
--- Stream0217_DS.prj (project) ---

Proj Title=Stream0217_DS Base Level Engineering
Current Plan=p01
Default Exp/Contr=0.3,0.1
English Units
Geom File=g01
Flow File=f01
Plan File=p01
BEGIN DESCRIPTION:
Stream0217_DS
END DESCRIPTION:

--- Stream0217_DS.p01 (plan) ---

Plan Title=Multiple Run
Short Identifier=Multiple
Geom File=g01
Flow File=f01
Subcritical Flow
K Sum by GR= 0
Std Step Tol= 0.01
Critical Tol= 0.01
Num of Std Step Trials= 20
Max Error Tol= 0.3
Flow Tol Ratio= 0.001
Split Flow NTrial= 30
Split Flow Tol= 0.02
Split Flow Ratio= 0.02
Log Output Level= 0
Friction Slope Method= 1
Unsteady Friction Slope Method= 2
Unsteady Bridges Friction Slope Method= 1
Parabolic Critical Depth
Global Vel Dist=  1 , 1 , 1
Global Log Level= 0
CheckData=True
Encroach Param= -1, 0, 0, 0
BEGIN DESCRIPTION:
Multiple Run
END DESCRIPTION:

--- Stream0217_DS.f01 (steady flow) ---

Flow Title=Multiple
Number of Profiles=7
Profile Names=10-year,25-year,50-year,1pct_min,100-year,1pct_plu,500-year
River Rch & RM= Stream0217_DS,Reach-1,2054
     549     894    1211     798    1593    3178    2716
River Rch & RM= Stream0217_DS,Reach-1,1875
     696    1149    1572    1045    2086    4162    3624
Boundary for River Rch & Prof#=Stream0217_DS,Reach-1,1
Up Type=0
Dn Type=3
Dn Slope=0.005
Boundary for River Rch & Prof#=Stream0217_DS,Reach-1,2
Up Type=0
Dn Type=3
Dn Slope=0.005
Boundary for River Rch & Prof#=Stream0217_DS,Reach-1,3
Up Type=0
Dn Type=3
Dn Slope=0.005
Boundary for River Rch & Prof#=Stream0217_DS,Reach-1,4
Up Type=0
Dn Type=3
Dn Slope=0.005
Boundary for River Rch & Prof#=Stream0217_DS,Reach-1,5
Up Type=0
Dn Type=3
Dn Slope=0.005
Boundary for River Rch & Prof#=Stream0217_DS,Reach-1,6
Up Type=0
Dn Type=3
Dn Slope=0.005
Boundary for River Rch & Prof#=Stream0217_DS,Reach-1,7
Up Type=0
Dn Type=3
Dn Slope=0.005

--- Stream0217_DS.g01 (geometry) ---

Geom Title=Existing Conditions

River Reach=Stream0217_DS,Reach-1
Reach XY= 30
      2101275.00     13881275.00      2101273.44     13881230.87
      2101252.17     13881201.02      2101223.50     13881178.87
      2101168.67     13881166.97      2101130.73     13881127.55
      2101118.85     13881072.85      2101077.33     13881019.03
      2101074.48     13880940.22      2101067.14     13880918.83
      2100923.50     13880778.61      2100830.97     13880772.62
      2100773.25     13880728.34      2100735.62     13880725.60
      2100711.80     13880738.15      2100641.75     13880808.53
      2100619.14     13880822.93      2100435.51     13880826.22
      2100377.33     13880869.25      2100354.97     13880874.93
      2100040.16     13880875.66      2100022.55     13880881.02
      2099971.64     13880916.97      2099926.89     13880881.58
      2099878.08     13880866.74      2099873.77     13880735.52
      2099827.31     13880668.99      2099822.16     13880582.76
      2099806.90     13880574.92      2099775.00     13880575.00

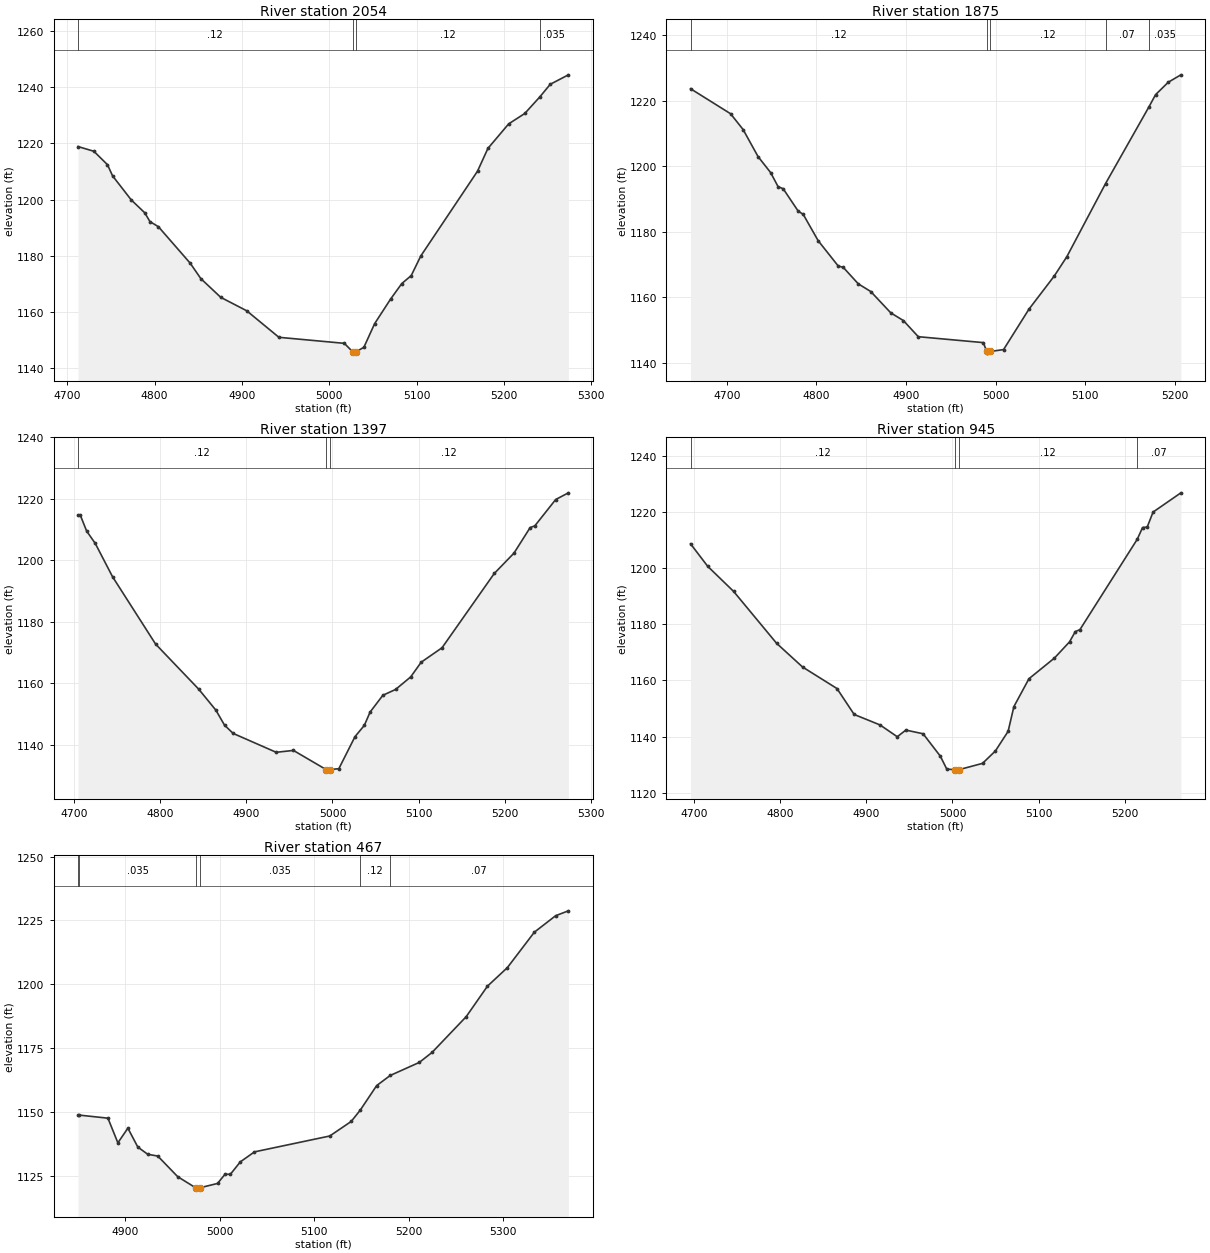
Type RM Length L Ch R = 1,2054,179,179,179
BEGIN DESCRIPTION:
Stream0217_DS 5.0
END DESCRIPTION:
XS GIS Cut Line= 3
      2101485.14     13881040.43      2101238.53     13881188.39
      2101132.71     13881441.03
#Sta/Elev= 30
  4712.4 1218.84  4730.5 1217.17  4746.1 1212.39  4751.9 1208.45  4773.3 1199.89
  4788.8 1195.30  4794.7 1192.19  4804.4 1190.37  4840.8 1177.41  4853.0 1171.92
  4875.8 1165.27  4905.5 1160.50  4942.4 1151.07  5017.3 1148.93  5026.8 1145.95
  5027.1 1145.45  5030.8 1145.95  5039.7 1147.52  5052.0 1155.92  5070.3 1164.67
  5083.1 1170.17  5093.9 1173.00  5104.9 1179.99  5169.8 1210.09  5181.7 1218.18
  5205.5 1226.91  5223.9 1230.59  5241.3 1236.54  5253.1 1240.97  5273.9 1244.33
#Mann=4,-1,0
  4712.4    0.12       0  5026.8    0.05       0  5030.8    0.12       0
  5241.3   0.035       0
Bank Sta=5026.8,5030.8
Exp/Cntr=0.3,0.1

Type RM Length L Ch R = 1,1875,478,478,478
BEGIN DESCRIPTION:
Stream0217_DS 4.0
END DESCRIPTION:
XS GIS Cut Line= 3
      2101424.98     13880925.01      2101125.00     13881075.00
      2100975.02     13881224.98
#Sta/Elev= 30
  4659.5 1223.67  4704.2 1216.02  4718.2 1211.19  4734.9 1202.92  4748.9 1198.05
  4757.3 1193.72  4762.9 1193.12  4779.7 1186.26  4785.3 1185.28  4802.0 1177.23
  4824.4 1169.49  4830.0 1169.08  4846.8 1164.04  4860.7 1161.70  4883.1 1155.17
  4897.1 1152.83  4913.8 1147.89  4986.5 1146.08  4990.1 1143.37  4990.3 1142.87
  4994.1 1143.37  5009.0 1143.95  5037.3 1156.28  5065.6 1166.43  5079.7 1172.36
  5122.9 1194.70  5171.1 1218.01  5178.7 1221.84  5192.9 1225.65  5207.0 1227.91
#Mann=5,-1,0
  4659.5    0.12       0  4990.1    0.05       0  4994.1    0.12       0
  5122.9    0.07       0  5171.1   0.035       0
Bank Sta=4990.1,4994.1
Exp/Cntr=0.3,0.1

Type RM Length L Ch R = 1,1397,452,452,452
BEGIN DESCRIPTION:
Stream0217_DS 3.0
END DESCRIPTION:
XS GIS Cut Line= 3
      2100825.00     13880475.01      2100825.00     13880775.00
      2100725.02     13881024.96
#Sta/Elev= 30
  4704.7 1214.75  4707.2 1214.75  4714.7 1209.49  4724.7 1205.48  4744.7 1194.68
  4794.7 1172.78  4844.7 1158.14  4864.7 1151.29  4874.7 1146.43  4884.7 1143.74
  4934.7 1137.60  4954.7 1138.21  4992.7 1131.98  4992.9 1131.48  4996.7 1131.98
  5007.4 1132.27  5026.2 1142.70  5037.0 1146.35  5043.7 1150.68  5058.5 1156.13
  5073.3 1158.03  5090.8 1162.10  5103.0 1166.88  5127.2 1171.58  5187.8 1195.72
  5210.7 1202.34  5229.5 1210.65  5234.9 1211.20  5259.1 1219.76  5273.9 1221.94
#Mann=3,-1,0
  4704.7    0.12       0  4992.7    0.05       0  4996.7    0.12       0
Bank Sta=4992.7,4996.7
Exp/Cntr=0.3,0.1

Type RM Length L Ch R = 1,945,478,478,478
BEGIN DESCRIPTION:
Stream0217_DS 2.0
END DESCRIPTION:
XS GIS Cut Line= 3
      2100425.00     13880525.00      2100425.00     13880825.00
      2100525.01     13881075.04
#Sta/Elev= 30
  4695.9 1208.80  4715.9 1200.74  4745.9 1191.81  4795.9 1173.25  4825.9 1164.83
  4865.9 1157.13  4885.9 1147.87  4915.9 1144.13  4935.9 1139.92  4945.9 1142.29
  4965.9 1140.98  4985.9 1132.98  4993.4 1128.36  5003.3 1128.14  5003.6 1127.64
  5007.3 1128.14  5034.9 1130.41  5049.8 1134.83  5064.6 1141.84  5071.3 1150.67
  5088.8 1160.63  5118.4 1168.01  5135.9 1173.79  5142.6 1177.45  5148.0 1178.17
  5214.5 1210.41  5220.7 1214.61  5226.1 1214.79  5232.9 1220.13  5265.2 1227.00
#Mann=4,-1,0
  4695.9    0.12       0  5003.3    0.05       0  5007.3    0.12       0
  5214.5    0.07       0
Bank Sta=5003.3,5007.3
Exp/Cntr=0.3,0.1

Type RM Length L Ch R = 1,467,0,0,0
BEGIN DESCRIPTION:
Stream0217_DS 1.0
END DESCRIPTION:
XS GIS Cut Line= 3
      2100024.99     13880775.04      2099975.00     13880925.00
      2100174.98     13881224.97
#Sta/Elev= 30
  4850.3 1148.68  4851.5 1148.68  4881.9 1147.47  4892.4 1137.82  4903.0 1143.55
  4913.5 1136.15  4924.0 1133.32  4934.6 1132.63  4955.7 1124.54  4974.8 1120.17
  4975.0 1119.67  4978.8 1120.17  4997.8 1121.89  5005.7 1125.49  5011.4 1125.49
  5021.9 1130.35  5036.9 1134.27  5116.5 1140.49  5139.1 1146.17  5148.6 1150.54
  5166.1 1160.24  5180.4 1164.20  5211.2 1169.32  5224.7 1173.24  5260.8 1187.25
  5283.3 1199.21  5304.3 1206.45  5332.9 1220.36  5355.4 1226.81  5368.9 1228.72
#Mann=6,-1,0
  4850.3    0.12       0  4851.5   0.035       0  4974.8   0.035       0
  4978.8   0.035       0  5148.6    0.12       0  5180.4    0.07       0
Bank Sta=4974.8,4978.8
Exp/Cntr=0.3,0.1

Chan Stop Cuts=-1