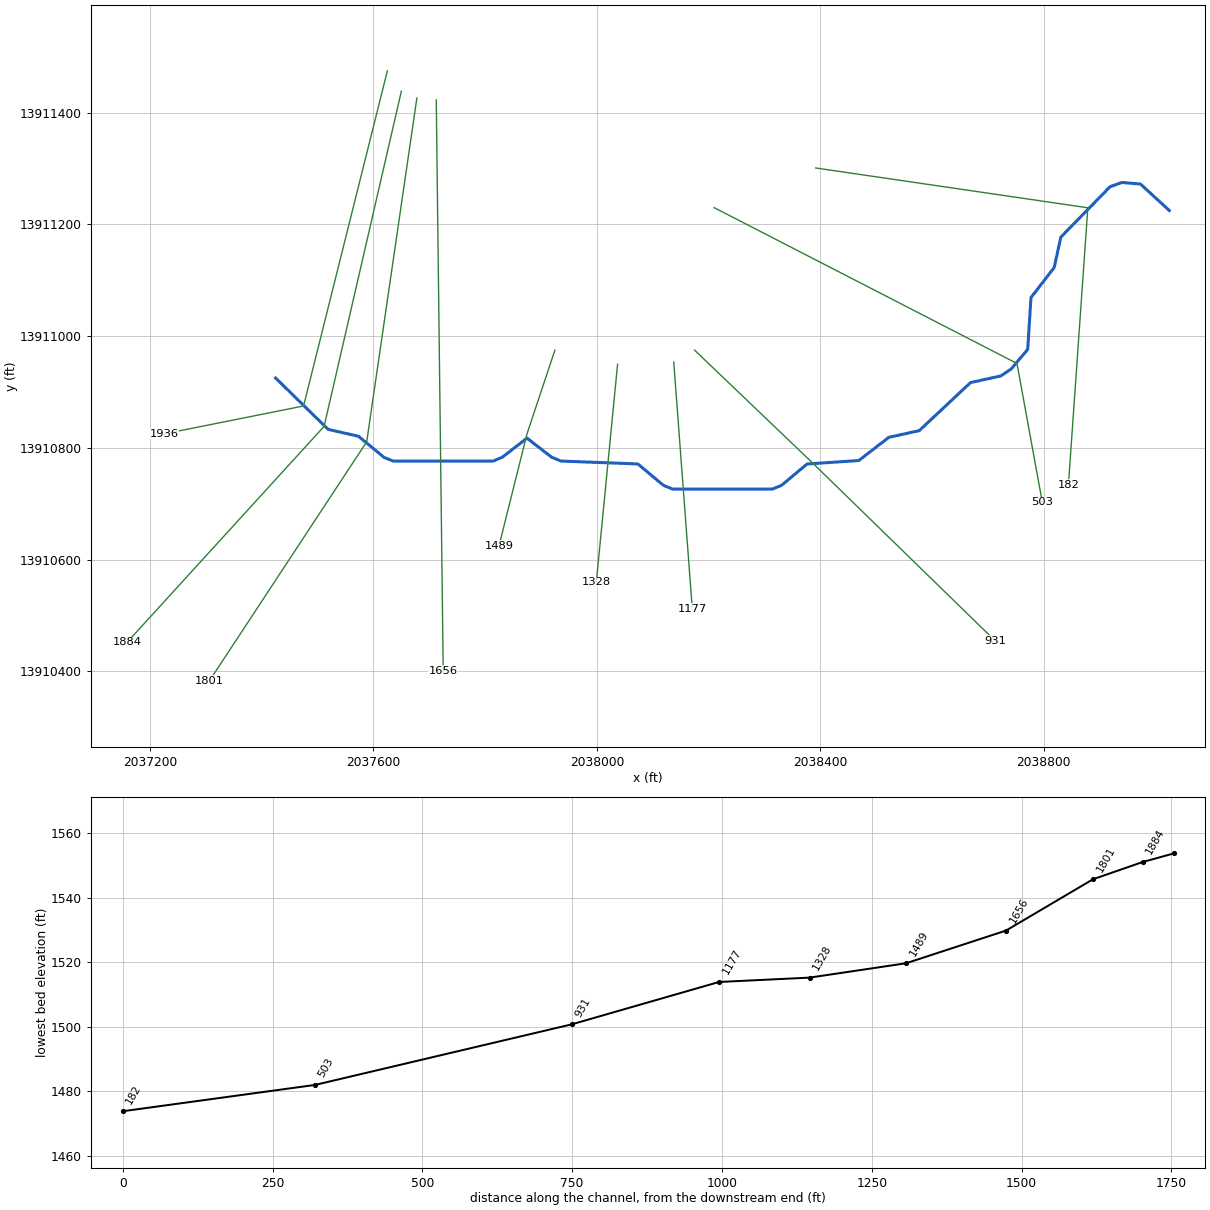
--- Stream0218_DS.prj (project) ---

Proj Title=Stream0218_DS Base Level Engineering
Current Plan=p01
Default Exp/Contr=0.3,0.1
English Units
Geom File=g01
Flow File=f01
Plan File=p01
Y Axis Title=Elevation
X Axis Title(PF)=Main Channel Distance
X Axis Title(XS)=Station
BEGIN DESCRIPTION:
Stream0218_DS
END DESCRIPTION:
DSS Export Rating Curves= 0
DSS Export Rating Curve Sorted= 0
DSS Export Volume Flow Curves= 0
DXF OffsetX= 0
DXF OffsetY= 0
DXF ScaleX= 1
DXF ScaleY= 10

--- Stream0218_DS.p01 (plan) ---

Plan Title=Multiple Run
Short Identifier=Multiple
Geom File=g01
Flow File=f01
Subcritical Flow
K Sum by GR= 0
Std Step Tol= 0.01
Critical Tol= 0.01
Num of Std Step Trials= 20
Max Error Tol= 0.3
Flow Tol Ratio= 0.001
Split Flow NTrial= 30
Split Flow Tol= 0.02
Split Flow Ratio= 0.02
Log Output Level= 0
Friction Slope Method= 1
Unsteady Friction Slope Method= 2
Unsteady Bridges Friction Slope Method= 1
Parabolic Critical Depth
Global Vel Dist=  1 , 1 , 1
Global Log Level= 0
CheckData=True
Encroach Param= -1, 0, 0, 0
BEGIN DESCRIPTION:
Multiple Run
END DESCRIPTION:

--- Stream0218_DS.f01 (steady flow) ---

Flow Title=Multiple
Number of Profiles=7
Profile Names=10-year,25-year,50-year,1pct_min,100-year,1pct_plu,500-year
River Rch & RM= Stream0218_DS,Reach-1,1936
     424     685     923     608    1213    2419    2059
Boundary for River Rch & Prof#=Stream0218_DS,Reach-1,1
Up Type=0
Dn Type=3
Dn Slope=0.005
Boundary for River Rch & Prof#=Stream0218_DS,Reach-1,2
Up Type=0
Dn Type=3
Dn Slope=0.005
Boundary for River Rch & Prof#=Stream0218_DS,Reach-1,3
Up Type=0
Dn Type=3
Dn Slope=0.005
Boundary for River Rch & Prof#=Stream0218_DS,Reach-1,4
Up Type=0
Dn Type=3
Dn Slope=0.005
Boundary for River Rch & Prof#=Stream0218_DS,Reach-1,5
Up Type=0
Dn Type=3
Dn Slope=0.005
Boundary for River Rch & Prof#=Stream0218_DS,Reach-1,6
Up Type=0
Dn Type=3
Dn Slope=0.005
Boundary for River Rch & Prof#=Stream0218_DS,Reach-1,7
Up Type=0
Dn Type=3
Dn Slope=0.005

--- Stream0218_DS.g01 (geometry) ---

Geom Title=Existing Conditions
Program Version=4.10

River Reach=Stream0218_DS   ,Reach-1
Reach XY= 30
        2037425.       13910925.      2037518.92     13910833.09
      2037573.26     13910820.79      2037618.92     13910783.09
       2037635.5      13910776.2      2037814.56     13910776.38
      2037831.18     13910783.45        2037875.     13910817.44
      2037918.82     13910783.46      2037935.44      13910776.4
      2038073.43     13910771.21      2038118.94     13910733.14
      2038135.51     13910726.22       2038314.5     13910726.22
      2038331.06     13910733.14       2038376.6     13910771.14
      2038469.03     13910777.33      2038522.83     13910818.86
      2038577.29     13910830.84      2038668.98     13910916.81
       2038723.6     13910928.87      2038742.13     13910941.46
      2038771.48     13910976.28      2038777.34     13911069.03
      2038818.86     13911122.83      2038830.82     13911177.32
      2038918.89     13911267.54      2038940.26     13911275.19
      2038973.38     13911272.33        2039025.       13911225.

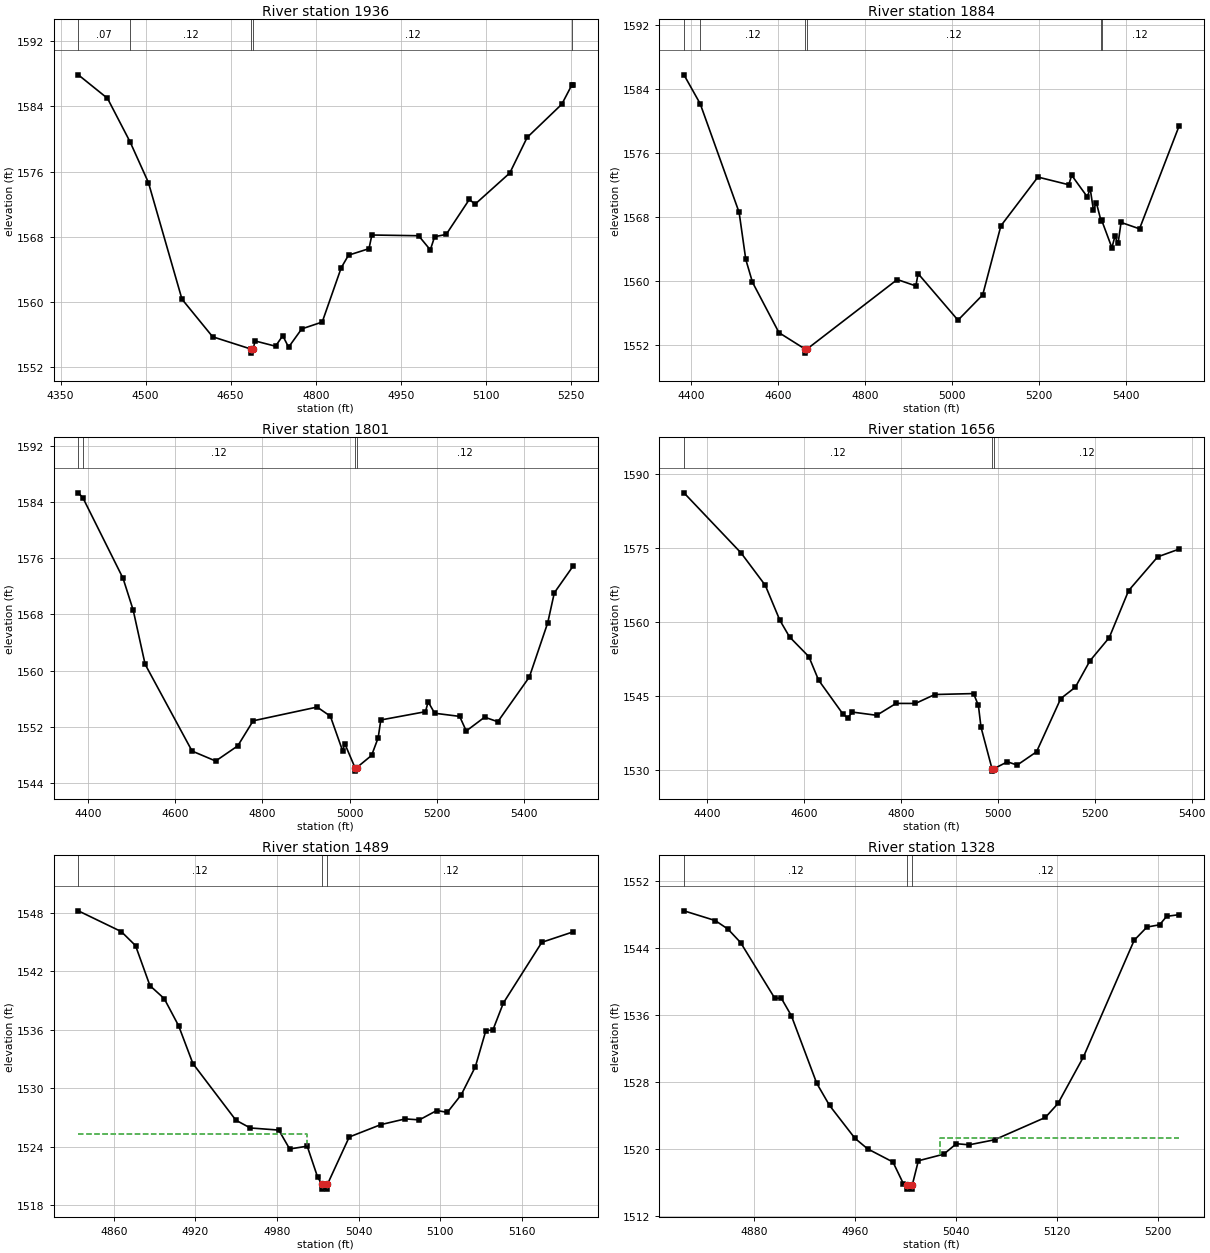
Type RM Length L Ch R = 1 ,1936    ,52,52,52
BEGIN DESCRIPTION:
Stream0218_DS 4.0
END DESCRIPTION:
XS GIS Cut Line= 3
      2037624.99     13911474.97        2037475.       13910875.
      2037224.98       13910825.
#Sta/Elev= 30
  4381.2 1587.89  4432.7    1585  4472.6 1579.64  4504.9 1574.65  4564.1 1560.31
  4618.2 1555.69  4685.8 1554.18  4686.1 1553.68  4689.8 1554.18    4693 1555.18
  4729.1 1554.53  4741.9 1555.82  4752.2 1554.41  4775.4 1556.66  4811.5  1557.5
    4845 1564.17  4857.9 1565.72    4894 1566.52  4899.1  1568.2  4981.6 1568.11
  5002.2 1566.37  5009.8 1567.99  5030.2 1568.27    5071 1572.57  5081.2 1571.99
  5142.4 1575.82    5173 1580.19  5234.2 1584.28    5252 1586.66  5254.6 1586.66
#Mann= 5 ,-1 , 0
  4381.2     .07       0  4472.6     .12       0  4685.8     .05       0
  4689.8     .12       0    5252     .07       0
Bank Sta=4685.8,4689.8
XS Rating Curve= 0 ,0
Exp/Cntr=0.3,0.1

Type RM Length L Ch R = 1 ,1884    ,83,83,83
BEGIN DESCRIPTION:
Stream0218_DS 3.7
END DESCRIPTION:
XS GIS Cut Line= 3
      2037650.07     13911438.61      2037511.75     13910838.54
      2037159.33     13910452.25
#Sta/Elev= 30
  4384.2 1585.81  4421.6 1582.19  4511.1 1568.61  4526.4 1562.73  4541.8 1559.88
  4602.7 1553.58    4663 1551.52  4663.2 1551.02    4667 1551.52  4874.8 1560.22
  4917.6 1559.42  4922.7 1560.96  5014.5 1555.14  5071.3  1558.3  5113.2 1566.94
  5198.3 1573.03  5269.2 1572.07    5276 1573.25  5311.8 1570.56  5318.5 1571.59
    5326 1568.89  5332.7 1569.83  5343.5 1567.55  5344.7 1567.67  5368.5 1564.19
  5375.3 1565.61  5382.7 1564.74  5389.5 1567.36    5432 1566.56  5522.9  1579.4
#Mann= 6 ,-1 , 0
  4384.2     .07       0  4421.6     .12       0    4663     .05       0
    4667     .12       0  5343.5     .07       0  5344.7     .12       0
Bank Sta=4663,4667
XS Rating Curve= 0 ,0
Exp/Cntr=0.3,0.1

Type RM Length L Ch R = 1 ,1801    ,145,145,145
BEGIN DESCRIPTION:
Stream0218_DS 3.6
END DESCRIPTION:
XS GIS Cut Line= 3
      2037677.85     13911426.53      2037588.04     13910810.95
      2037306.39     13910382.89
#Sta/Elev= 30
  4377.9 1585.33  4388.2 1584.65  4480.5 1573.14  4503.7 1568.61    4531  1560.9
  4638.6 1548.53  4692.7 1547.11  4743.3 1549.27  4778.6 1552.84  4925.2  1554.8
  4955.5  1553.5  4983.6 1548.56  4988.6 1549.58  5011.9 1546.17  5012.1 1545.67
  5015.9 1546.17    5050 1547.91  5065.1 1550.43  5071.1 1552.96  5173.5 1554.14
  5179.5 1555.55  5194.6 1553.92  5251.8 1553.47  5266.9 1551.39    5309 1553.36
  5339.2 1552.71  5411.5 1559.08  5453.6 1566.81  5468.7 1571.08  5512.4 1574.95
#Mann= 4 ,-1 , 0
  4377.9     .07       0  4388.2     .12       0  5011.9     .05       0
  5015.9     .12       0
Bank Sta=5011.9,5015.9
XS Rating Curve= 0 ,0
Exp/Cntr=0.3,0.1

Type RM Length L Ch R = 1 ,1656    ,167,167,167
BEGIN DESCRIPTION:
Stream0218_DS 3.5
END DESCRIPTION:
XS GIS Cut Line= 2
      2037712.53     13911422.89      2037724.98     13910400.87
#Sta/Elev= 30
  4351.9 1586.13  4469.8 1573.96  4519.8 1567.41  4549.8 1560.35  4569.8 1556.97
  4609.8 1552.96  4629.8 1548.22  4679.8 1541.39  4689.8 1540.56  4699.8 1541.74
  4749.8 1541.09  4789.8  1543.5  4829.8 1543.49  4869.8  1545.3  4949.8 1545.49
  4959.8 1543.08  4965.1 1538.71  4987.8 1530.29  4988.1 1529.79  4991.8 1530.29
  5019.8 1531.68  5039.8 1531.01  5079.8  1533.7  5129.8 1544.48  5159.9 1546.78
  5189.9  1552.1  5229.9 1556.82  5269.9 1566.34  5329.9 1573.17    5374 1574.73
#Mann= 3 ,-1 , 0
  4351.9     .12       0  4987.8     .05       0  4991.8     .12       0
Bank Sta=4987.8,4991.8
XS Rating Curve= 0 ,0
Exp/Cntr=0.3,0.1

Type RM Length L Ch R = 1 ,1489    ,161,161,161
BEGIN DESCRIPTION:
Stream0218_DS 3.0
END DESCRIPTION:
XS GIS Cut Line= 3
      2037924.99     13910974.97        2037875.       13910825.
      2037825.01     13910625.04
#Sta/Elev= 30
  4833.8 1548.22  4865.4 1546.09  4875.9 1544.65  4886.5 1540.54    4897 1539.21
  4907.6 1536.42  4918.1 1532.54  4949.7 1526.73  4960.3 1525.93  4981.3 1525.71
  4989.3 1523.77  5002.2 1524.06  5009.9 1520.86  5013.1 1520.15  5013.3 1519.65
  5016.8 1519.65  5017.1 1520.15  5033.1    1525  5056.3 1526.27  5074.3 1526.86
  5084.7 1526.76  5097.5 1527.72  5105.3 1527.53  5115.6 1529.36  5125.9 1532.22
  5133.6 1535.92  5138.8 1535.99  5146.5 1538.76  5174.8 1544.99    5198 1546.07
#Mann= 3 ,-1 , 0
  4833.8     .12       0  5013.1     .05       0  5017.1     .12       0
#XS Ineff= 2 , 0
       0 5002.11 1525.33               0
Permanent Ineff=
       F       F
Bank Sta=5013.1,5017.1
XS Rating Curve= 0 ,0
Exp/Cntr=0.3,0.1

Type RM Length L Ch R = 1 ,1328    ,151,151,151
BEGIN DESCRIPTION:
Stream0218_DS 2.2
END DESCRIPTION:
XS GIS Cut Line= 2
      2038037.18     13910949.63      2037999.11     13910559.68
#Sta/Elev= 30
  4824.8 1548.49  4849.5 1547.33  4859.6 1546.31  4869.6  1544.7  4896.7 1538.03
  4901.8 1538.05  4909.8 1535.95  4929.9 1527.86    4940 1525.22  4960.1 1521.29
  4970.1 1520.03  4990.2 1518.45  4998.4 1515.87  5001.5 1515.71  5001.7 1515.21
  5005.2 1515.21  5005.5 1515.71  5010.3  1518.6  5030.4 1519.39  5040.4 1520.64
  5050.5 1520.51  5070.6 1521.11  5110.8 1523.78  5120.8 1525.45  5140.9 1531.01
  5181.1 1544.97  5191.2 1546.55  5201.2 1546.82  5206.8 1547.83  5216.6 1548.03
#Mann= 3 ,-1 , 0
  4824.8     .12       0  5001.5     .05       0  5005.5     .12       0
#XS Ineff= 2 , 0
       0                 5027.75       0 1521.27
Permanent Ineff=
       F       F
Bank Sta=5001.5,5005.5
XS Rating Curve= 0 ,0
Exp/Cntr=0.3,0.1

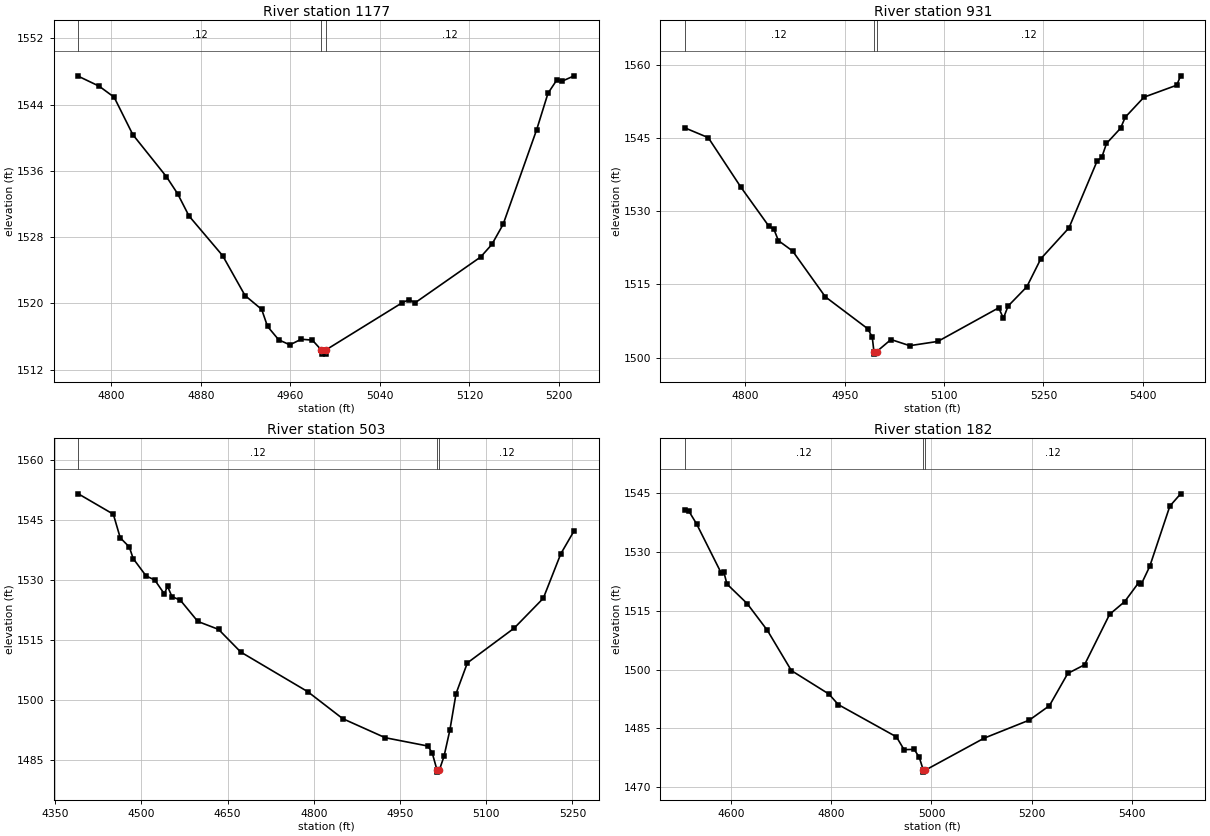
Type RM Length L Ch R = 1 ,1177    ,246,246,246
BEGIN DESCRIPTION:
Stream0218_DS 2.1
END DESCRIPTION:
XS GIS Cut Line= 2
      2038137.73     13910953.59      2038170.95     13910511.64
#Sta/Elev= 30
  4770.4 1547.42    4789 1546.22  4802.4 1544.89  4819.1 1540.37  4849.2 1535.28
  4859.2 1533.22  4869.3 1530.55  4899.4 1525.75  4919.4 1520.94  4934.3 1519.26
  4939.5 1517.21  4949.5 1515.59  4959.5 1514.98  4969.6 1515.66  4979.6 1515.55
  4987.6 1514.36  4987.9 1513.86  4991.4 1513.86  4991.6 1514.36  5059.8 1520.06
  5066.2 1520.45  5071.2 1520.04    5130 1525.59    5140  1527.1  5150.1 1529.53
  5180.1 1540.97  5190.2 1545.36  5198.1 1546.97  5203.1 1546.84  5213.6 1547.47
#Mann= 3 ,-1 , 0
  4770.4     .12       0  4987.6     .05       0  4991.6     .12       0
Bank Sta=4987.6,4991.6
XS Rating Curve= 0 ,0
Exp/Cntr=0.3,0.1

Type RM Length L Ch R = 1 ,931     ,428,428,428
BEGIN DESCRIPTION:
Stream0218_DS 2.0
END DESCRIPTION:
XS GIS Cut Line= 3
      2038175.01     13910974.99      2038385.55     13910773.67
      2038713.01     13910454.74
#Sta/Elev= 30
  4708.7 1547.07  4744.1 1545.06  4793.4 1534.91  4835.9 1526.87  4843.1 1526.33
    4850 1523.97  4871.4 1521.85  4920.8 1512.47  4984.7 1505.94  4991.6 1504.25
  4994.2 1501.23  4994.4 1500.73  4998.2 1501.23  5019.9 1503.72  5048.2 1502.46
  5090.6 1503.33  5182.5 1510.21  5189.6 1508.07  5196.6 1510.56  5224.9 1514.51
  5246.2 1520.28  5288.6 1526.59  5331.1 1540.29  5338.1 1541.03  5345.2 1543.87
  5366.4 1546.98  5373.5 1549.24  5401.8 1553.35  5451.2  1555.8  5457.1 1557.72
#Mann= 3 ,-1 , 0
  4708.7     .12       0  4994.2     .05       0  4998.2     .12       0
Bank Sta=4994.2,4998.2
XS Rating Curve= 0 ,0
Exp/Cntr=0.3,0.1

Type RM Length L Ch R = 1 ,503     ,321,321,321
BEGIN DESCRIPTION:
Stream0218_DS 1.0
END DESCRIPTION:
XS GIS Cut Line= 3
      2038210.14     13911230.08      2038752.28     13910951.11
       2038797.7     13910702.22
#Sta/Elev= 30
  4390.3 1551.46  4451.2 1546.37  4463.2 1540.48    4479 1538.19  4485.7  1535.3
  4508.2 1530.96  4523.3 1529.94  4539.9 1526.48  4545.5 1528.38  4553.2 1525.79
  4567.7 1524.92  4598.2  1519.6  4634.2 1517.62  4672.9 1511.96  4789.4 1502.07
  4850.3 1495.33  4924.3 1490.57  4998.7 1488.49  5006.2 1486.69  5014.4 1482.48
  5014.6 1481.98  5018.4 1482.48  5026.5 1485.89  5036.7 1492.44  5047.5 1501.59
  5067.2 1509.25  5148.5 1517.91  5199.3 1525.38  5229.8  1536.5    5253 1542.24
#Mann= 3 ,-1 , 0
  4390.3     .12       0  5014.4     .05       0  5018.4     .12       0
Bank Sta=5014.4,5018.4
XS Rating Curve= 0 ,0
Exp/Cntr=0.3,0.1

Type RM Length L Ch R = 1 ,182     ,0,0,0
BEGIN DESCRIPTION:
Stream0218_DS 0.0
END DESCRIPTION:
XS GIS Cut Line= 3
      2038391.83     13911301.13      2038879.15     13911229.88
      2038844.37     13910733.59
#Sta/Elev= 30
  4507.5 1540.77  4515.3 1540.45  4530.9 1537.17  4580.4 1524.56  4585.5 1524.86
  4591.6 1521.81    4632 1516.82  4672.4 1509.98  4720.3 1499.73  4795.3 1493.74
  4813.9 1491.06  4930.1 1482.82  4945.3 1479.56  4965.5 1479.63  4975.6 1477.63
  4983.7 1474.33    4984 1473.83  4987.7 1474.33  5105.1 1482.49  5195.4  1487.1
  5235.5 1490.77  5272.2 1499.01  5305.6  1501.2  5355.7 1514.07  5385.8 1517.32
  5413.9 1522.18  5418.9 1521.75  5435.9 1526.33    5476 1541.68  5497.5 1544.81
#Mann= 3 ,-1 , 0
  4507.5     .12       0  4983.7     .05       0  4987.7     .12       0
Bank Sta=4983.7,4987.7
XS Rating Curve= 0 ,0
Exp/Cntr=0.3,0.1

Chan Stop Cuts=-1
Use User Specified Reach Order=0
Composite Channel Slope=5