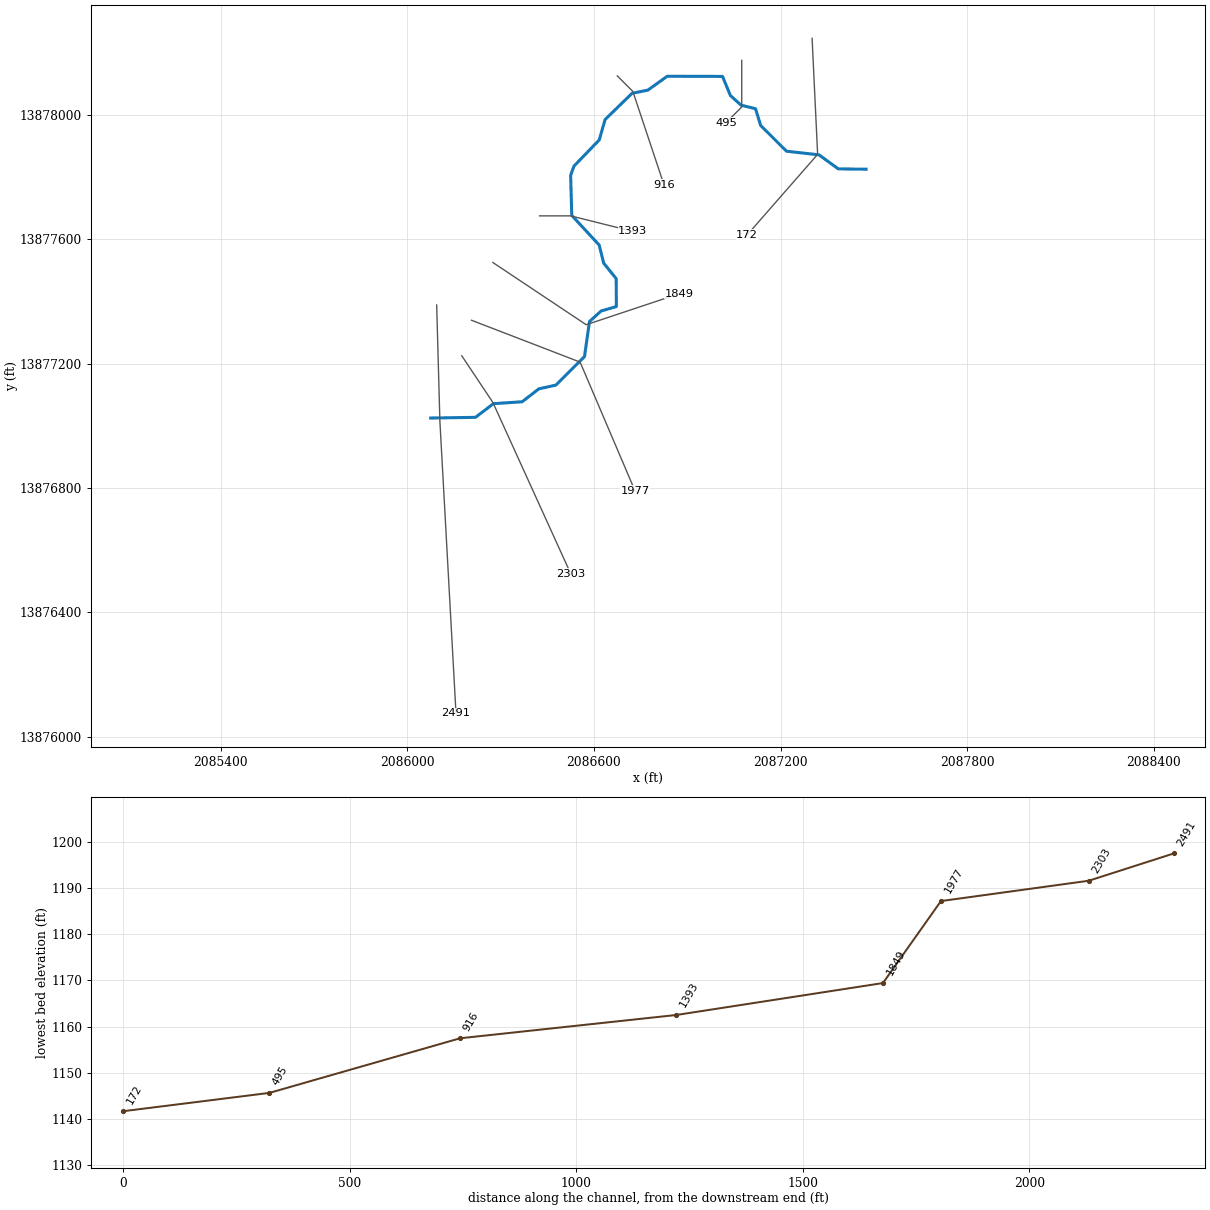
--- Stream0219_DS.prj (project) ---

Proj Title=Stream0219_DS Base Level Engineering
Current Plan=p01
Default Exp/Contr=0.3,0.1
English Units
Geom File=g01
Flow File=f01
Plan File=p01
BEGIN DESCRIPTION:
Stream0219_DS
END DESCRIPTION:

--- Stream0219_DS.p01 (plan) ---

Plan Title=Multiple Run
Short Identifier=Multiple
Geom File=g01
Flow File=f01
Subcritical Flow
K Sum by GR= 0
Std Step Tol= 0.01
Critical Tol= 0.01
Num of Std Step Trials= 20
Max Error Tol= 0.3
Flow Tol Ratio= 0.001
Split Flow NTrial= 30
Split Flow Tol= 0.02
Split Flow Ratio= 0.02
Log Output Level= 0
Friction Slope Method= 1
Unsteady Friction Slope Method= 2
Unsteady Bridges Friction Slope Method= 1
Parabolic Critical Depth
Global Vel Dist=  1 , 1 , 1
Global Log Level= 0
CheckData=True
Encroach Param= -1, 0, 0, 0
BEGIN DESCRIPTION:
Multiple Run
END DESCRIPTION:

--- Stream0219_DS.f01 (steady flow) ---

Flow Title=Multiple
Number of Profiles=7
Profile Names=10-year,25-year,50-year,1pct_min,100-year,1pct_plu,500-year
River Rch & RM= Stream0219_DS,Reach-1,2491
     690    1133    1542    1020    2035    4061    3499
Boundary for River Rch & Prof#=Stream0219_DS,Reach-1,1
Up Type=0
Dn Type=3
Dn Slope=0.005
Boundary for River Rch & Prof#=Stream0219_DS,Reach-1,2
Up Type=0
Dn Type=3
Dn Slope=0.005
Boundary for River Rch & Prof#=Stream0219_DS,Reach-1,3
Up Type=0
Dn Type=3
Dn Slope=0.005
Boundary for River Rch & Prof#=Stream0219_DS,Reach-1,4
Up Type=0
Dn Type=3
Dn Slope=0.005
Boundary for River Rch & Prof#=Stream0219_DS,Reach-1,5
Up Type=0
Dn Type=3
Dn Slope=0.005
Boundary for River Rch & Prof#=Stream0219_DS,Reach-1,6
Up Type=0
Dn Type=3
Dn Slope=0.005
Boundary for River Rch & Prof#=Stream0219_DS,Reach-1,7
Up Type=0
Dn Type=3
Dn Slope=0.005

--- Stream0219_DS.g01 (geometry) ---

Geom Title=Existing Conditions

River Reach=Stream0219_DS,Reach-1
Reach XY= 30
      2086075.00     13877025.00      2086219.08     13877027.22
      2086276.60     13877071.15      2086369.03     13877077.33
      2086422.83     13877118.86      2086477.31     13877130.82
      2086569.48     13877222.56      2086585.45     13877335.08
      2086622.83     13877369.10      2086672.00     13877383.35
      2086671.36     13877473.34      2086631.15     13877522.83
      2086616.84     13877581.05      2086528.54     13877676.47
      2086524.94     13877805.01      2086535.49     13877834.79
      2086616.82     13877918.96      2086635.77     13877984.70
      2086722.69     13878069.18      2086773.25     13878079.22
      2086835.50     13878123.80      2087013.17     13878123.36
      2087038.66     13878061.73      2087072.81     13878030.93
      2087119.35     13878019.37      2087135.88     13877965.56
      2087218.81     13877882.86      2087323.41     13877871.17
      2087385.42     13877826.02      2087475.00     13877825.00

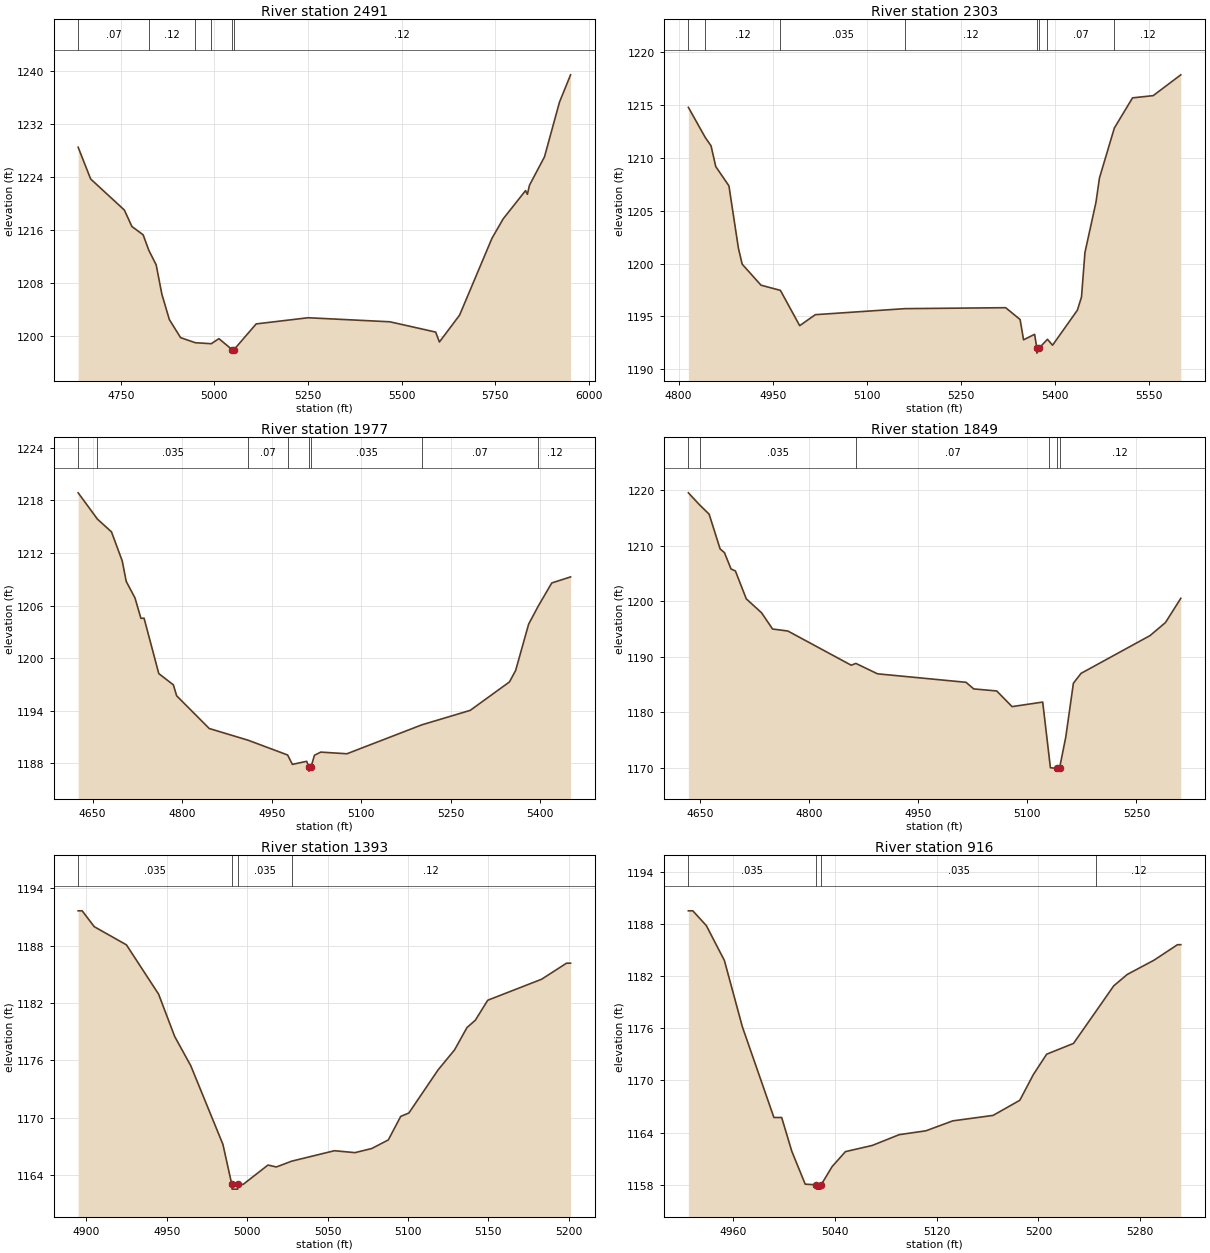
Type RM Length L Ch R = 1,2491,188,188,188
BEGIN DESCRIPTION:
Stream0219_DS 6.0
END DESCRIPTION:
XS GIS Cut Line= 3
      2086094.25     13877388.39      2086104.56     13877015.71
      2086156.37     13876075.46
#Sta/Elev= 30
  4636.4 1228.44  4669.8 1223.66  4759.8 1218.98  4779.8 1216.51  4809.9 1215.25
  4825.0 1212.92  4844.6 1210.74  4859.9 1206.30  4879.9 1202.48  4909.9 1199.76
  4949.0 1199.00  4991.8 1198.85  5012.1 1199.61  5048.0 1197.93  5048.2 1197.43
  5052.0 1197.93  5111.6 1201.83  5250.3 1202.76  5468.6 1202.15  5590.8 1200.60
  5600.8 1199.11  5654.7 1203.16  5741.0 1214.72  5771.1 1217.66  5830.7 1221.91
  5835.7 1221.35  5841.2 1222.72  5881.3 1227.00  5921.3 1235.23  5950.9 1239.35
#Mann=6,-1,0
  4636.4    0.07       0  4825.0    0.12       0  4949.0   0.035       0
  4991.8    0.12       0  5048.0    0.05       0  5052.0    0.12       0
Bank Sta=5048,5052
Exp/Cntr=0.3,0.1

Type RM Length L Ch R = 1,2303,326,326,326
BEGIN DESCRIPTION:
Stream0219_DS 5.0
END DESCRIPTION:
XS GIS Cut Line= 3
      2086174.98     13877225.03      2086275.00     13877075.00
      2086525.01     13876524.97
#Sta/Elev= 30
  4815.5 1214.78  4842.4 1211.93  4851.6 1211.14  4859.1 1209.18  4880.1 1207.35
  4895.2 1201.45  4901.2 1199.94  4931.2 1197.95  4962.1 1197.46  4992.8 1194.12
  5017.8 1195.16  5160.6 1195.73  5321.0 1195.82  5344.0 1194.70  5349.5 1192.78
  5367.1 1193.30  5370.6 1192.02  5370.8 1191.52  5374.6 1192.02  5387.6 1192.83
  5395.7 1192.27  5435.2 1195.58  5441.8 1196.83  5447.3 1201.04  5464.9 1205.81
  5470.4 1208.09  5494.1 1212.82  5523.1 1215.68  5556.0 1215.89  5600.0 1217.86
#Mann=8,-1,0
  4815.5    0.07       0  4842.4    0.12       0  4962.1   0.035       0
  5160.6    0.12       0  5370.6   0.035       0  5374.6    0.12       0
  5387.6    0.07       0  5494.1    0.12       0
Bank Sta=5370.6,5374.6
Exp/Cntr=0.3,0.1

Type RM Length L Ch R = 1,1977,128,128,128
BEGIN DESCRIPTION:
Stream0219_DS 4.5
END DESCRIPTION:
XS GIS Cut Line= 3
      2086206.13     13877339.40      2086555.39     13877204.81
      2086732.10     13876790.41
#Sta/Elev= 30
  4625.7 1218.87  4658.0 1215.87  4681.5 1214.42  4699.5 1211.11  4706.2 1208.77
  4720.9 1206.88  4730.8 1204.56  4736.1 1204.57  4760.8 1198.25  4785.2 1196.97
  4790.7 1195.72  4845.3 1191.99  4910.2 1190.66  4976.6 1188.97  4984.5 1187.90
  5008.5 1188.25  5011.9 1187.63  5012.2 1187.13  5015.9 1187.63  5021.5 1188.94
  5032.1 1189.30  5075.9 1189.11  5201.4 1192.41  5282.4 1194.06  5348.1 1197.30
  5358.5 1198.61  5380.3 1203.90  5396.3 1205.94  5419.0 1208.59  5450.5 1209.28
#Mann=8,-1,0
  4625.7    0.07       0  4658.0   0.035       0  4910.2    0.07       0
  4976.6   0.035       0  5011.9   0.035       0  5015.9   0.035       0
  5201.4    0.07       0  5396.3    0.12       0
Bank Sta=5011.9,5015.9
Exp/Cntr=0.3,0.1

Type RM Length L Ch R = 1,1849,456,456,456
BEGIN DESCRIPTION:
Stream0219_DS 4.0
END DESCRIPTION:
XS GIS Cut Line= 3
      2086275.01     13877525.00      2086575.00     13877325.00
      2086875.02     13877425.01
#Sta/Elev= 30
  4634.2 1219.54  4649.6 1217.37  4662.7 1215.70  4677.8 1209.44  4683.8 1208.76
  4692.8 1205.83  4698.8 1205.47  4713.8 1200.44  4734.8 1197.93  4749.9 1195.01
  4770.9 1194.65  4858.0 1188.49  4864.5 1188.81  4894.1 1186.94  5015.8 1185.41
  5026.4 1184.22  5058.0 1183.85  5079.1 1181.03  5121.2 1181.85  5129.8 1172.25
  5131.8 1170.02  5140.3 1169.91  5140.6 1169.41  5144.3 1169.91  5152.9 1175.54
  5163.4 1185.25  5173.9 1187.02  5268.8 1193.83  5289.9 1196.17  5311.0 1200.54
#Mann=6,-1,0
  4634.2    0.07       0  4649.6   0.035       0  4864.5    0.07       0
  5129.8    0.12       0  5140.3    0.05       0  5144.3    0.12       0
Bank Sta=5140.3,5144.3
Exp/Cntr=0.3,0.1

Type RM Length L Ch R = 1,1393,477,477,477
BEGIN DESCRIPTION:
Stream0219_DS 3.0
END DESCRIPTION:
XS GIS Cut Line= 3
      2086425.01     13877675.00      2086525.00     13877675.00
      2086724.96     13877625.01
#Sta/Elev= 30
  4895.0 1191.64  4897.5 1191.64  4905.0 1189.98  4925.0 1188.08  4945.0 1182.92
  4955.0 1178.49  4965.0 1175.43  4985.0 1167.19  4990.5 1163.01  4990.7 1162.51
  4994.2 1162.51  4994.5 1163.01  4997.6 1163.01  5013.0 1165.03  5018.2 1164.83
  5027.8 1165.44  5054.3 1166.53  5067.1 1166.33  5077.5 1166.76  5087.8 1167.66
  5095.5 1170.12  5100.6 1170.48  5118.7 1174.98  5129.0 1177.09  5136.7 1179.42
  5141.9 1180.19  5149.6 1182.28  5183.1 1184.48  5198.6 1186.16  5201.1 1186.16
#Mann=4,-1,0
  4895.0   0.035       0  4990.5   0.035       0  4994.5   0.035       0
  5027.8    0.12       0
Bank Sta=4990.5,4994.5
Exp/Cntr=0.3,0.1

Type RM Length L Ch R = 1,916,421,421,421
BEGIN DESCRIPTION:
Stream0219_DS 2.0
END DESCRIPTION:
XS GIS Cut Line= 3
      2086675.00     13878125.00      2086725.00     13878075.00
      2086824.99     13877775.04
#Sta/Elev= 30
  4925.0 1189.53  4928.5 1189.53  4939.1 1187.83  4953.3 1183.81  4967.4 1176.18
  4992.2 1165.73  4998.3 1165.73  5006.3 1161.82  5016.8 1158.05  5025.3 1157.98
  5025.6 1157.48  5029.1 1157.48  5029.3 1157.98  5037.9 1160.07  5048.4 1161.80
  5069.5 1162.51  5090.6 1163.75  5111.7 1164.20  5132.7 1165.34  5164.4 1165.97
  5185.4 1167.71  5196.0 1170.66  5206.5 1173.02  5227.6 1174.26  5245.4 1177.99
  5259.2 1180.89  5269.8 1182.20  5290.9 1183.85  5309.3 1185.63  5311.9 1185.63
#Mann=4,-1,0
  4925.0   0.035       0  5025.3   0.035       0  5029.3   0.035       0
  5245.4    0.12       0
Bank Sta=5025.3,5029.3
Exp/Cntr=0.3,0.1

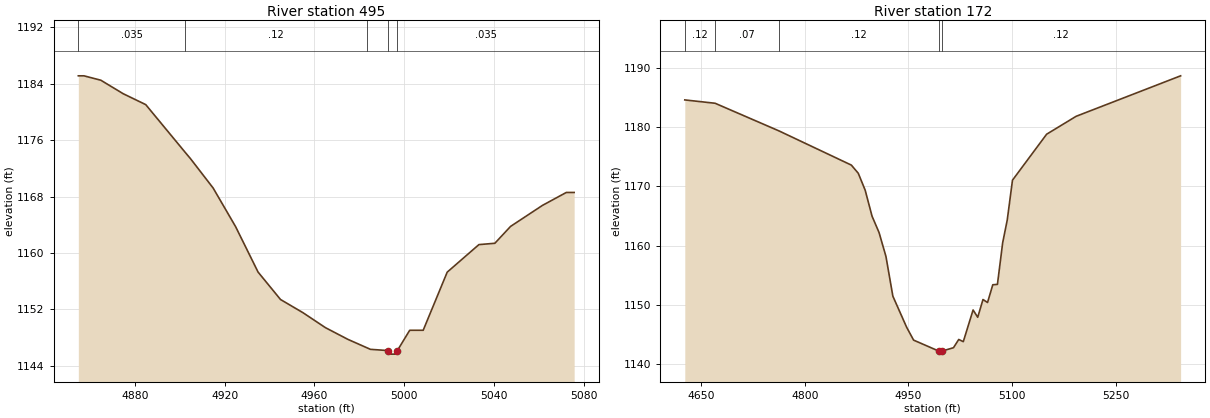
Type RM Length L Ch R = 1,495,323,323,323
BEGIN DESCRIPTION:
Stream0219_DS 1.0
END DESCRIPTION:
XS GIS Cut Line= 3
      2087075.00     13878175.01      2087075.00     13878025.00
      2087025.02     13877975.02
#Sta/Elev= 29
  4854.9 1185.11  4857.4 1185.11  4864.9 1184.49  4874.9 1182.57  4884.9 1181.03
  4902.4 1174.29  4904.9 1173.34  4914.9 1169.21  4924.9 1163.74  4934.9 1157.30
  4944.9 1153.41  4954.9 1151.54  4964.9 1149.42  4974.9 1147.76  4983.5 1146.55
  4984.9 1146.35  4992.9 1146.17  4993.2 1145.67  4996.7 1145.67  4996.9 1146.17
  5002.4 1149.05  5008.4 1149.05  5019.1 1157.29  5033.2 1161.19  5040.3 1161.38
  5047.3 1163.77  5061.5 1166.75  5072.1 1168.58  5075.6 1168.58
#Mann=5,-1,0
  4854.9   0.035       0  4902.4    0.12       0  4983.5   0.035       0
  4992.9   0.035       0  4996.9   0.035       0
Bank Sta=4992.9,4996.9
Exp/Cntr=0.3,0.1

Type RM Length L Ch R = 1,172,0,0,0
BEGIN DESCRIPTION:
Stream0219_DS 0.0
END DESCRIPTION:
XS GIS Cut Line= 3
      2087301.26     13878245.74      2087319.03     13877872.66
      2087092.54     13877613.75
#Sta/Elev= 30
  4626.5 1184.54  4670.3 1183.98  4762.8 1179.32  4867.5 1173.56  4877.5 1172.19
  4887.5 1169.34  4897.5 1164.94  4907.6 1162.20  4917.6 1158.16  4927.6 1151.47
  4947.6 1146.22  4957.6 1144.07  4994.3 1142.21  4994.6 1141.71  4998.3 1142.21
  5015.3 1142.79  5022.9 1144.18  5029.5 1143.81  5043.7 1149.15  5050.4 1147.92
  5058.0 1150.91  5064.6 1150.41  5072.2 1153.40  5078.9 1153.46  5086.5 1160.48
  5093.1 1164.30  5100.7 1171.02  5150.1 1178.76  5192.8 1181.78  5344.0 1188.60
#Mann=5,-1,0
  4626.5    0.12       0  4670.3    0.07       0  4762.8    0.12       0
  4994.3    0.05       0  4998.3    0.12       0
Bank Sta=4994.3,4998.3
Exp/Cntr=0.3,0.1

Chan Stop Cuts=-1