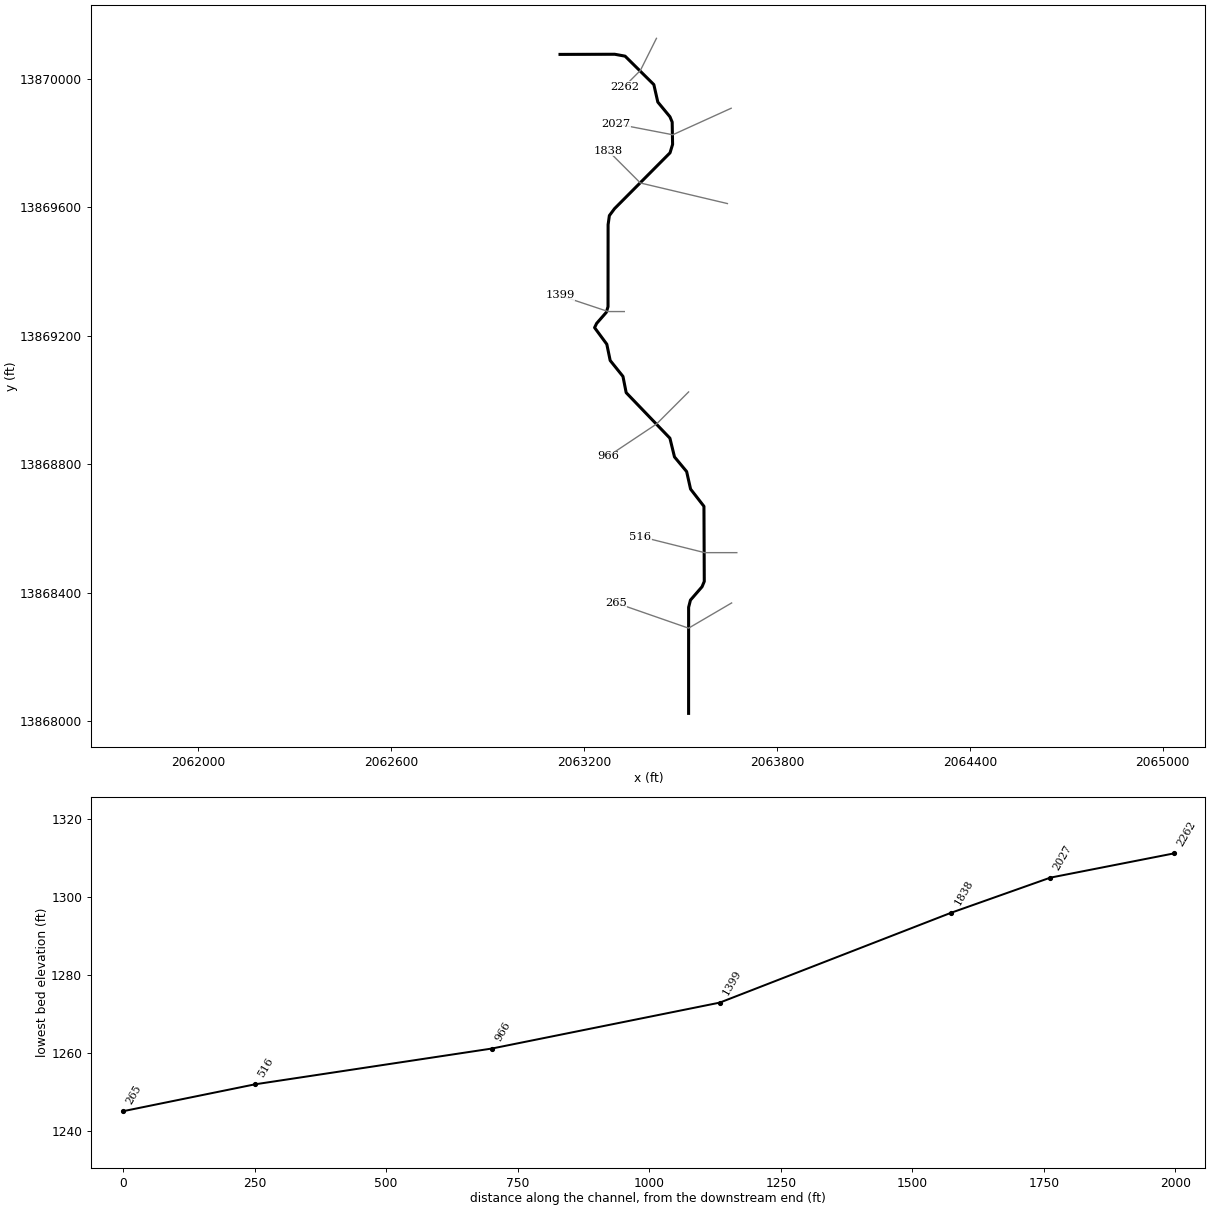
--- Stream0220_DS.prj (project) ---

Proj Title=Stream0220_DS Base Level Engineering
Current Plan=p01
Default Exp/Contr=0.3,0.1
English Units
Geom File=g01
Flow File=f01
Plan File=p01
BEGIN DESCRIPTION:
Stream0220_DS
END DESCRIPTION:

--- Stream0220_DS.p01 (plan) ---

Plan Title=Multiple Run
Short Identifier=Multiple
Geom File=g01
Flow File=f01
Subcritical Flow
K Sum by GR= 0
Std Step Tol= 0.01
Critical Tol= 0.01
Num of Std Step Trials= 20
Max Error Tol= 0.3
Flow Tol Ratio= 0.001
Split Flow NTrial= 30
Split Flow Tol= 0.02
Split Flow Ratio= 0.02
Log Output Level= 0
Friction Slope Method= 1
Unsteady Friction Slope Method= 2
Unsteady Bridges Friction Slope Method= 1
Parabolic Critical Depth
Global Vel Dist=  1 , 1 , 1
Global Log Level= 0
CheckData=True
Encroach Param= -1, 0, 0, 0
BEGIN DESCRIPTION:
Multiple Run
END DESCRIPTION:

--- Stream0220_DS.f01 (steady flow) ---

Flow Title=Multiple
Number of Profiles=7
Profile Names=10-year,25-year,50-year,1pct_min,100-year,1pct_plu,500-year
River Rch & RM= Stream0220_DS,Reach-1,2262
     335     523     689     443     883    1762    1428
River Rch & RM= Stream0220_DS,Reach-1,2027
     621    1014    1376     909    1813    3617    3103
Boundary for River Rch & Prof#=Stream0220_DS,Reach-1,1
Up Type=0
Dn Type=3
Dn Slope=0.005
Boundary for River Rch & Prof#=Stream0220_DS,Reach-1,2
Up Type=0
Dn Type=3
Dn Slope=0.005
Boundary for River Rch & Prof#=Stream0220_DS,Reach-1,3
Up Type=0
Dn Type=3
Dn Slope=0.005
Boundary for River Rch & Prof#=Stream0220_DS,Reach-1,4
Up Type=0
Dn Type=3
Dn Slope=0.005
Boundary for River Rch & Prof#=Stream0220_DS,Reach-1,5
Up Type=0
Dn Type=3
Dn Slope=0.005
Boundary for River Rch & Prof#=Stream0220_DS,Reach-1,6
Up Type=0
Dn Type=3
Dn Slope=0.005
Boundary for River Rch & Prof#=Stream0220_DS,Reach-1,7
Up Type=0
Dn Type=3
Dn Slope=0.005

--- Stream0220_DS.g01 (geometry) ---

Geom Title=Existing Conditions

River Reach=Stream0220_DS,Reach-1
Reach XY= 30
      2063125.00     13870075.00      2063295.19     13870075.45
      2063327.47     13870069.55      2063416.87     13869981.08
      2063429.22     13869926.75      2063466.96     13869881.05
      2063473.92     13869864.45      2063475.21     13869795.05
      2063467.24     13869768.83      2063294.60     13869595.16
      2063278.54     13869573.54      2063274.57     13869545.18
      2063274.34     13869290.16      2063268.98     13869272.55
      2063238.94     13869238.20      2063232.53     13869224.99
      2063270.57     13869173.36      2063281.05     13869122.81
      2063320.81     13869073.26      2063330.83     13869022.70
      2063466.86     13868881.06      2063481.10     13868822.81
      2063518.92     13868777.20      2063531.12     13868722.82
      2063572.76     13868669.07      2063573.78     13868435.50
      2063566.86     13868418.94      2063530.75     13868377.33
      2063525.07     13868354.97      2063525.00     13868025.00

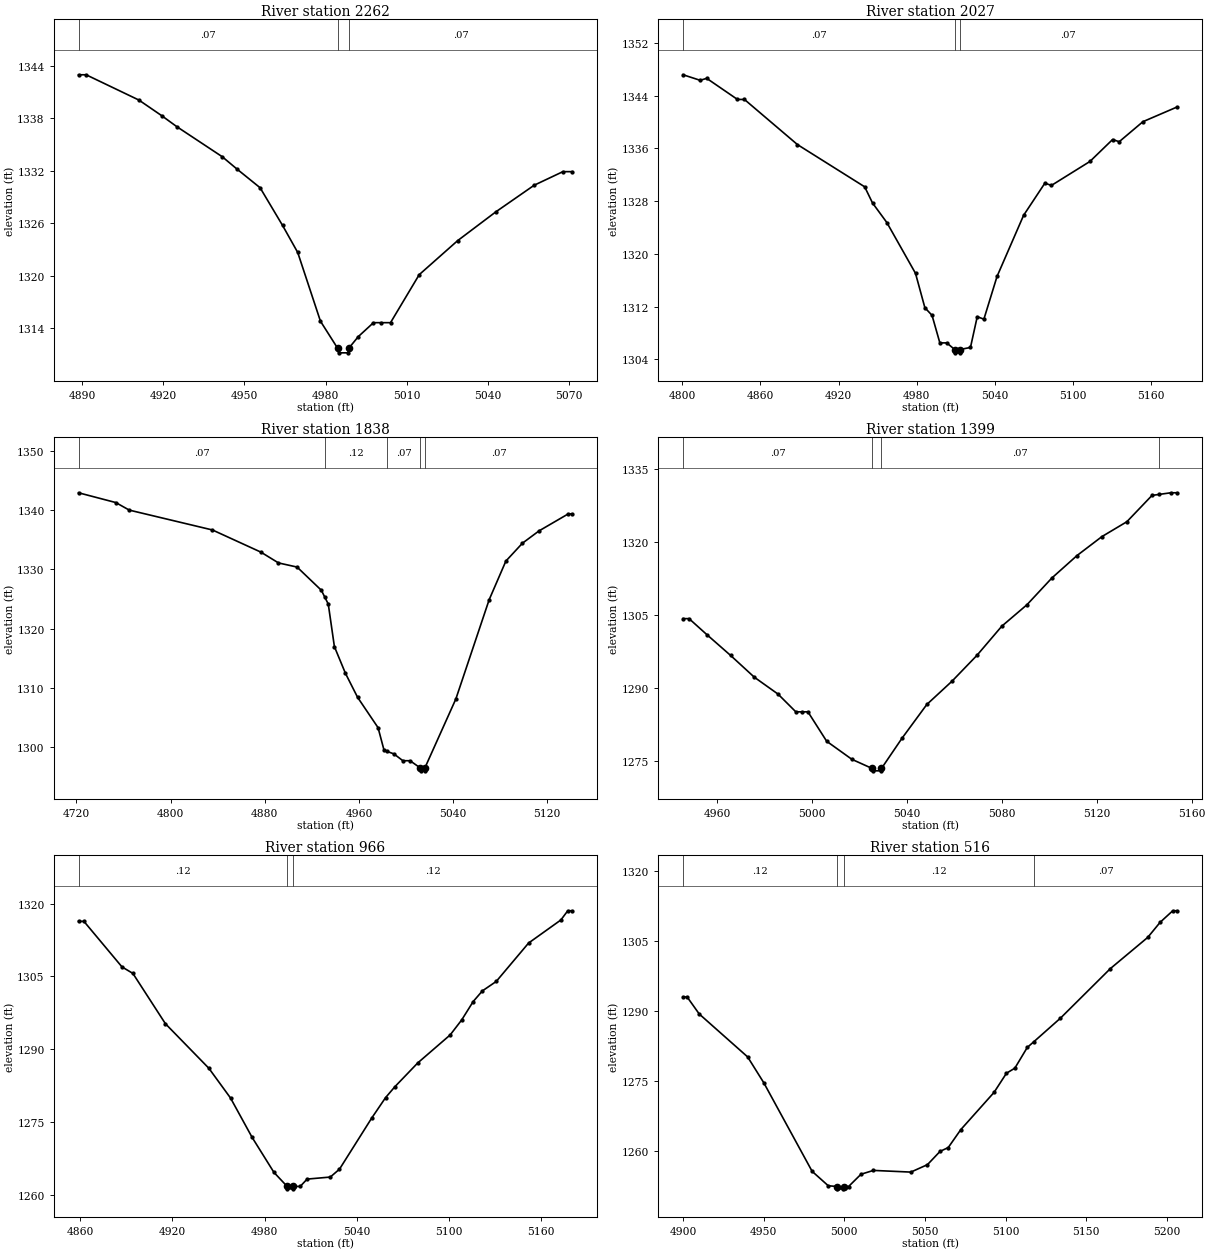
Type RM Length L Ch R = 1,2262,235,235,235
BEGIN DESCRIPTION:
Stream0220_DS 5.0
END DESCRIPTION:
XS GIS Cut Line= 3
      2063424.99     13870124.98      2063375.00     13870025.00
      2063325.00     13869975.00
#Sta/Elev= 25
  4888.7 1343.00  4891.5 1343.00  4911.0 1340.11  4919.4 1338.33  4925.0 1337.07
  4941.8 1333.63  4947.4 1332.18  4955.8 1330.08  4964.1 1325.77  4969.7 1322.68
  4978.1 1314.82  4984.5 1311.70  4984.8 1311.20  4988.3 1311.20  4988.5 1311.70
  4992.1 1313.06  4997.7 1314.65  5000.5 1314.65  5004.0 1314.65  5014.6 1320.14
  5028.8 1324.03  5042.9 1327.32  5057.1 1330.37  5067.7 1331.92  5071.2 1331.92
#Mann=3,-1,0
  4888.7    0.07       0  4984.5    0.05       0  4988.5    0.07       0
Bank Sta=4984.5,4988.5
Exp/Cntr=0.3,0.1

Type RM Length L Ch R = 1,2027,189,189,189
BEGIN DESCRIPTION:
Stream0220_DS 4.5
END DESCRIPTION:
XS GIS Cut Line= 3
      2063657.39     13869907.47      2063475.85     13869824.99
      2063299.39     13869858.94
#Sta/Elev= 30
  4800.6 1347.19  4813.7 1346.35  4818.7 1346.65  4842.3 1343.45  4847.7 1343.44
  4888.4 1336.59  4940.0 1330.18  4946.0 1327.73  4957.0 1324.76  4979.0 1317.05
  4986.2 1311.83  4991.7 1310.67  4997.7 1306.49  5003.0 1306.49  5009.1 1305.48
  5009.3 1304.98  5012.8 1304.98  5013.1 1305.48  5021.2 1305.80  5026.4 1310.47
  5031.5 1310.09  5041.6 1316.58  5062.0 1325.86  5078.3 1330.73  5083.4 1330.40
  5112.9 1334.03  5130.3 1337.36  5135.4 1337.03  5153.6 1340.07  5179.7 1342.29
#Mann=3,-1,0
  4800.6    0.07       0  5009.1    0.05       0  5013.1    0.07       0
Bank Sta=5009.1,5013.1
Exp/Cntr=0.3,0.1

Type RM Length L Ch R = 1,1838,439,439,439
BEGIN DESCRIPTION:
Stream0220_DS 4.0
END DESCRIPTION:
XS GIS Cut Line= 3
      2063645.73     13869610.97      2063375.00     13869675.00
      2063275.02     13869774.98
#Sta/Elev= 30
  4721.8 1342.96  4753.4 1341.31  4764.9 1340.03  4835.6 1336.67  4876.7 1332.93
  4891.7 1331.10  4907.5 1330.40  4928.1 1326.48  4931.1 1325.29  4934.0 1324.14
  4939.2 1316.95  4948.6 1312.43  4958.9 1308.38  4976.3 1303.25  4981.4 1299.42
  4984.0 1299.23  4989.7 1298.82  4997.4 1297.66  5003.5 1297.66  5012.1 1296.45
  5012.4 1295.95  5015.9 1295.95  5016.1 1296.45  5042.4 1308.10  5070.7 1324.88
  5084.9 1331.41  5099.0 1334.44  5113.1 1336.52  5137.9 1339.39  5141.4 1339.39
#Mann=5,-1,0
  4721.8    0.07       0  4931.1    0.12       0  4984.0    0.07       0
  5012.1    0.05       0  5016.1    0.07       0
Bank Sta=5012.1,5016.1
Exp/Cntr=0.3,0.1

Type RM Length L Ch R = 1,1399,433,433,433
BEGIN DESCRIPTION:
Stream0220_DS 3.0
END DESCRIPTION:
XS GIS Cut Line= 3
      2063325.01     13869275.00      2063275.00     13869275.00
      2063125.02     13869324.99
#Sta/Elev= 29
  4945.7 1304.19  4948.2 1304.19  4955.7 1300.91  4965.7 1296.64  4975.7 1292.17
  4985.7 1288.70  4993.2 1285.06  4995.7 1285.06  4998.3 1285.06  5006.2 1279.02
  5016.8 1275.32  5025.3 1273.45  5025.6 1272.95  5029.1 1272.95  5029.3 1273.45
  5037.9 1279.61  5048.4 1286.57  5059.0 1291.34  5069.5 1296.64  5080.0 1302.64
  5090.6 1307.04  5101.1 1312.53  5111.7 1317.14  5122.2 1321.03  5132.7 1324.08
  5143.3 1329.48  5146.1 1329.67  5151.2 1330.02  5153.8 1330.02
#Mann=4,-1,0
  4945.7    0.07       0  5025.3    0.05       0  5029.3    0.07       0
  5146.1   0.035       0
Bank Sta=5025.3,5029.3
Exp/Cntr=0.3,0.1

Type RM Length L Ch R = 1,966,450,450,450
BEGIN DESCRIPTION:
Stream0220_DS 2.0
END DESCRIPTION:
XS GIS Cut Line= 3
      2063525.00     13869025.00      2063425.00     13868925.00
      2063275.00     13868825.00
#Sta/Elev= 30
  4858.8 1316.36  4862.3 1316.36  4887.1 1306.96  4894.2 1305.62  4915.4 1295.24
  4943.7 1286.05  4957.8 1279.92  4971.9 1271.78  4986.1 1264.57  4994.7 1261.68
  4994.9 1261.18  4998.4 1261.18  4998.7 1261.68  5003.2 1261.68  5007.7 1263.19
  5022.8 1263.61  5028.8 1265.24  5049.8 1275.79  5058.8 1279.99  5064.8 1282.22
  5079.8 1287.16  5100.9 1292.93  5108.4 1296.02  5115.9 1299.82  5121.9 1302.02
  5130.9 1303.96  5152.0 1311.89  5173.0 1316.64  5177.5 1318.54  5180.5 1318.54
#Mann=3,-1,0
  4858.8    0.12       0  4994.7    0.05       0  4998.7    0.12       0
Bank Sta=4994.7,4998.7
Exp/Cntr=0.3,0.1

Type RM Length L Ch R = 1,516,251,251,251
BEGIN DESCRIPTION:
Stream0220_DS 1.0
END DESCRIPTION:
XS GIS Cut Line= 3
      2063675.00     13868525.00      2063575.00     13868525.00
      2063374.96     13868575.01
#Sta/Elev= 30
  4900.1 1293.03  4902.6 1293.03  4910.1 1289.39  4940.1 1280.22  4950.1 1274.70
  4980.1 1255.75  4990.1 1252.67  4995.6 1252.51  4995.8 1252.01  4999.3 1252.01
  4999.6 1252.51  5002.7 1252.51  5010.4 1255.13  5018.1 1255.95  5041.3 1255.59
  5051.6 1257.18  5059.4 1260.01  5064.5 1260.84  5072.3 1264.68  5092.9 1272.63
  5100.6 1276.73  5105.8 1277.81  5113.5 1282.24  5117.7 1283.50  5134.1 1288.51
  5165.0 1299.09  5188.2 1305.77  5195.9 1309.00  5203.7 1311.46  5206.3 1311.46
#Mann=4,-1,0
  4900.1    0.12       0  4995.6    0.05       0  4999.6    0.12       0
  5117.7    0.07       0
Bank Sta=4995.6,4999.6
Exp/Cntr=0.3,0.1

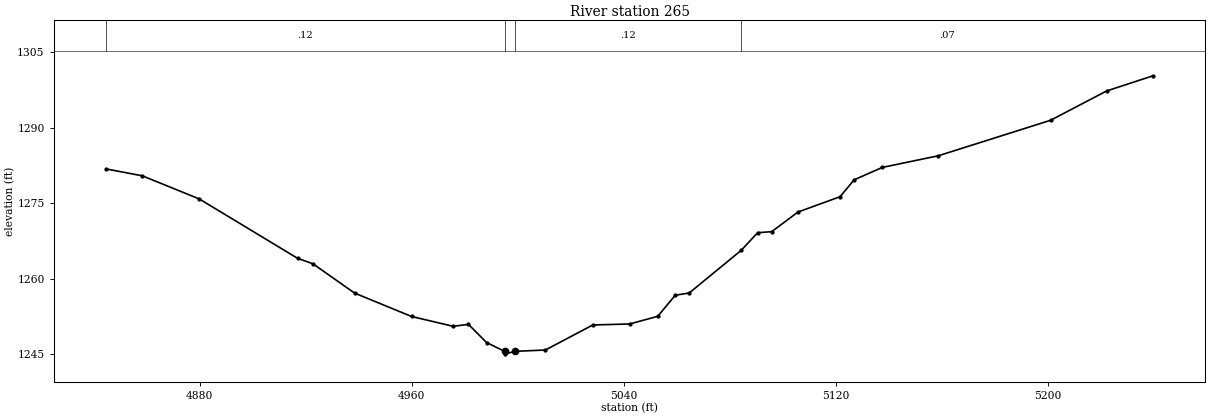
Type RM Length L Ch R = 1,265,0,0,0
BEGIN DESCRIPTION:
Stream0220_DS 0.0
END DESCRIPTION:
XS GIS Cut Line= 3
      2063658.86     13868368.55      2063524.86     13868290.06
      2063298.46     13868368.80
#Sta/Elev= 30
  4844.7 1281.82  4858.3 1280.46  4879.8 1275.87  4916.9 1264.08  4922.7 1262.99
  4938.4 1257.18  4959.9 1252.53  4975.6 1250.58  4981.4 1250.96  4988.2 1247.36
  4995.0 1245.61  4995.3 1245.11  4999.0 1245.61  5010.4 1245.87  5028.3 1250.84
  5042.2 1251.04  5052.8 1252.56  5059.4 1256.74  5064.7 1257.20  5084.3 1265.66
  5090.5 1269.16  5095.8 1269.37  5105.7 1273.26  5121.6 1276.31  5126.9 1279.66
  5137.5 1282.12  5158.7 1284.44  5201.0 1291.48  5222.2 1297.31  5239.7 1300.32
#Mann=4,-1,0
  4844.7    0.12       0  4995.0    0.05       0  4999.0    0.12       0
  5084.3    0.07       0
Bank Sta=4995,4999
Exp/Cntr=0.3,0.1

Chan Stop Cuts=-1