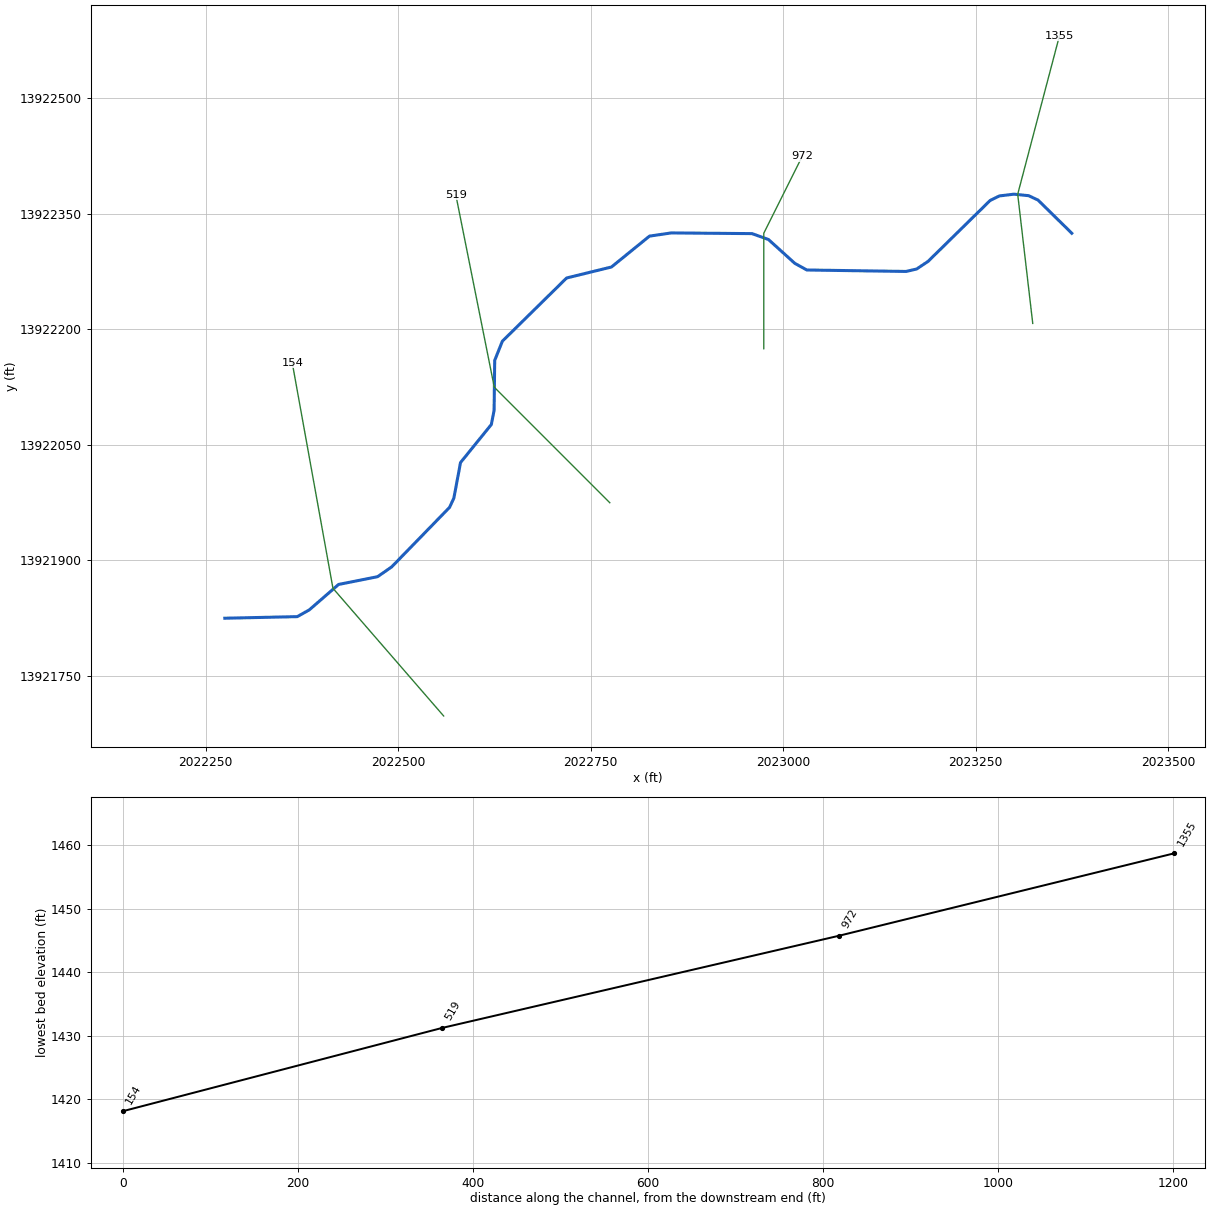
--- Stream0221_DS.prj (project) ---

Proj Title=Stream0221_DS Base Level Engineering
Current Plan=p01
Default Exp/Contr=0.3,0.1
English Units
Geom File=g01
Flow File=f01
Plan File=p01
BEGIN DESCRIPTION:
Stream0221_DS
END DESCRIPTION:

--- Stream0221_DS.p01 (plan) ---

Plan Title=Multiple Run
Short Identifier=Multiple
Geom File=g01
Flow File=f01
Subcritical Flow
K Sum by GR= 0
Std Step Tol= 0.01
Critical Tol= 0.01
Num of Std Step Trials= 20
Max Error Tol= 0.3
Flow Tol Ratio= 0.001
Split Flow NTrial= 30
Split Flow Tol= 0.02
Split Flow Ratio= 0.02
Log Output Level= 0
Friction Slope Method= 1
Unsteady Friction Slope Method= 2
Unsteady Bridges Friction Slope Method= 1
Parabolic Critical Depth
Global Vel Dist=  1 , 1 , 1
Global Log Level= 0
CheckData=True
Encroach Param= -1, 0, 0, 0
BEGIN DESCRIPTION:
Multiple Run
END DESCRIPTION:

--- Stream0221_DS.f01 (steady flow) ---

Flow Title=Multiple
Number of Profiles=7
Profile Names=10-year,25-year,50-year,1pct_min,100-year,1pct_plu,500-year
River Rch & RM= Stream0221_DS,Reach-1,1355
     503     829    1132     754    1503    3000    2621
Boundary for River Rch & Prof#=Stream0221_DS,Reach-1,1
Up Type=0
Dn Type=3
Dn Slope=0.005
Boundary for River Rch & Prof#=Stream0221_DS,Reach-1,2
Up Type=0
Dn Type=3
Dn Slope=0.005
Boundary for River Rch & Prof#=Stream0221_DS,Reach-1,3
Up Type=0
Dn Type=3
Dn Slope=0.005
Boundary for River Rch & Prof#=Stream0221_DS,Reach-1,4
Up Type=0
Dn Type=3
Dn Slope=0.005
Boundary for River Rch & Prof#=Stream0221_DS,Reach-1,5
Up Type=0
Dn Type=3
Dn Slope=0.005
Boundary for River Rch & Prof#=Stream0221_DS,Reach-1,6
Up Type=0
Dn Type=3
Dn Slope=0.005
Boundary for River Rch & Prof#=Stream0221_DS,Reach-1,7
Up Type=0
Dn Type=3
Dn Slope=0.005

--- Stream0221_DS.g01 (geometry) ---

Geom Title=Existing Conditions

River Reach=Stream0221_DS,Reach-1
Reach XY= 30
      2023375.00     13922325.00      2023331.14     13922368.08
      2023318.94     13922373.77      2023299.90     13922375.72
      2023280.97     13922373.45      2023268.92     13922367.51
      2023188.31     13922288.40      2023173.53     13922278.54
      2023159.83     13922275.37      2023030.94     13922277.25
      2023015.35     13922285.85      2022981.05     13922316.86
      2022959.78     13922324.49      2022854.86     13922325.40
      2022826.56     13922321.26      2022777.17     13922281.14
      2022718.92     13922266.87      2022635.51     13922184.81
      2022625.52     13922159.79      2022624.76     13922095.10
      2022621.17     13922076.59      2022581.14     13922027.17
      2022572.51     13921981.02      2022566.87     13921968.93
      2022491.71     13921891.63      2022473.38     13921878.94
      2022422.82     13921868.89      2022384.67     13921835.79
      2022369.14     13921827.07      2022275.00     13921825.00

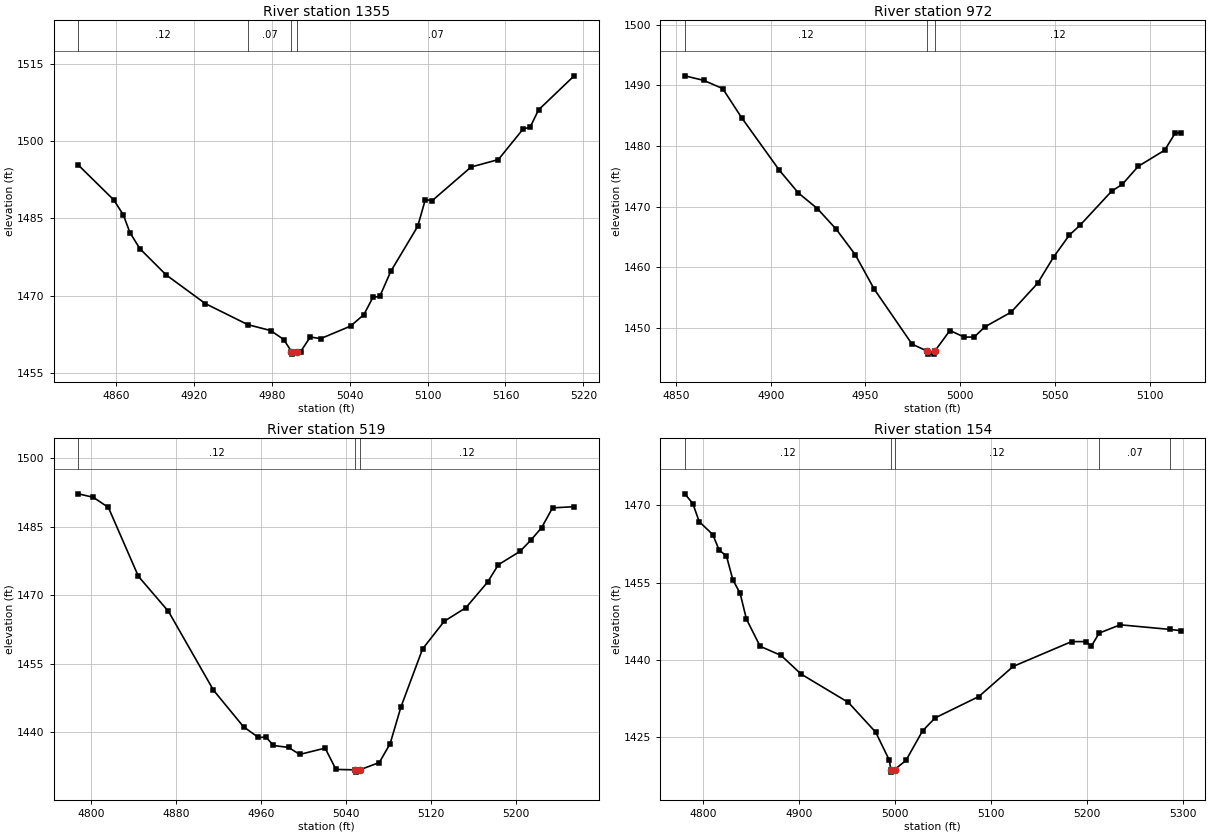
Type RM Length L Ch R = 1,1355,383,383,383
BEGIN DESCRIPTION:
Stream0221_DS 3.0
END DESCRIPTION:
XS GIS Cut Line= 3
      2023324.29     13922207.87      2023304.75     13922375.64
      2023359.01     13922581.51
#Sta/Elev= 30
  4831.1 1495.36  4858.4 1488.60  4865.8 1485.68  4870.8 1482.27  4878.5 1479.14
  4898.7 1474.06  4928.9 1468.49  4961.6 1464.41  4979.2 1463.26  4989.3 1461.52
  4995.2 1459.19  4995.4 1458.69  4999.2 1459.19  5002.3 1459.19  5009.7 1462.01
  5017.7 1461.70  5040.7 1464.12  5051.0 1466.36  5058.0 1469.73  5063.2 1469.87
  5071.7 1474.75  5092.4 1483.46  5098.3 1488.68  5103.5 1488.44  5133.5 1494.98
  5154.5 1496.42  5173.8 1502.42  5178.9 1502.66  5185.5 1506.07  5212.9 1512.67
#Mann=4,-1,0
  4831.1    0.12       0  4961.6    0.07       0  4995.2    0.05       0
  4999.2    0.07       0
Bank Sta=4995.2,4999.2
Exp/Cntr=0.3,0.1

Type RM Length L Ch R = 1,972,453,453,453
BEGIN DESCRIPTION:
Stream0221_DS 2.0
END DESCRIPTION:
XS GIS Cut Line= 3
      2022975.00     13922175.04      2022975.00     13922325.00
      2023025.01     13922425.03
#Sta/Elev= 30
  4854.6 1491.55  4864.6 1490.80  4874.6 1489.45  4884.6 1484.66  4904.6 1475.97
  4914.6 1472.25  4924.6 1469.69  4934.6 1466.27  4944.6 1462.10  4954.6 1456.43
  4974.6 1447.36  4982.6 1446.22  4982.8 1445.72  4986.3 1445.72  4986.6 1446.22
  4994.6 1449.61  5002.1 1448.53  5007.4 1448.53  5013.0 1450.20  5026.9 1452.63
  5040.9 1457.39  5049.3 1461.70  5057.7 1465.34  5063.3 1466.95  5080.0 1472.56
  5085.6 1473.68  5094.0 1476.64  5108.0 1479.31  5113.6 1482.16  5116.4 1482.16
#Mann=3,-1,0
  4854.6    0.12       0  4982.6    0.05       0  4986.6    0.12       0
Bank Sta=4982.6,4986.6
Exp/Cntr=0.3,0.1

Type RM Length L Ch R = 1,519,365,365,365
BEGIN DESCRIPTION:
Stream0221_DS 1.0
END DESCRIPTION:
XS GIS Cut Line= 3
      2022775.00     13921975.00      2022625.00     13922125.00
      2022575.00     13922375.02
#Sta/Elev= 30
  4787.6 1492.21  4801.7 1491.45  4815.9 1489.23  4844.2 1474.12  4872.5 1466.45
  4914.9 1449.19  4943.2 1441.17  4957.3 1438.82  4964.4 1438.91  4971.4 1437.07
  4985.6 1436.64  4996.2 1435.11  5020.1 1436.49  5030.3 1431.82  5048.7 1431.73
  5049.0 1431.23  5052.7 1431.73  5071.1 1433.33  5081.3 1437.44  5091.5 1445.50
  5111.9 1458.22  5132.3 1464.29  5152.7 1467.25  5173.1 1472.85  5183.3 1476.68
  5203.7 1479.59  5213.9 1482.06  5224.1 1484.81  5234.3 1489.13  5254.7 1489.39
#Mann=3,-1,0
  4787.6    0.12       0  5048.7    0.05       0  5052.7    0.12       0
Bank Sta=5048.7,5052.7
Exp/Cntr=0.3,0.1

Type RM Length L Ch R = 1,154,0,0,0
BEGIN DESCRIPTION:
Stream0221_DS 0.0
END DESCRIPTION:
XS GIS Cut Line= 3
      2022559.25     13921698.04      2022415.46     13921863.89
      2022362.56     13922156.95
#Sta/Elev= 30
  4780.5 1472.26  4788.9 1470.36  4795.5 1466.86  4809.7 1464.33  4816.3 1461.33
  4824.0 1460.15  4830.6 1455.55  4838.2 1452.91  4844.8 1447.89  4859.1 1442.60
  4881.0 1440.82  4901.8 1437.20  4951.2 1431.67  4979.7 1425.88  4994.0 1420.39
  4995.4 1418.62  4995.7 1418.12  4999.4 1418.62  5011.3 1420.41  5028.6 1426.16
  5041.8 1428.68  5087.3 1432.83  5123.1 1438.68  5184.0 1443.51  5199.4 1443.51
  5204.5 1442.56  5212.8 1445.17  5234.8 1446.78  5286.2 1445.89  5297.8 1445.65
#Mann=5,-1,0
  4780.5    0.12       0  4995.4    0.05       0  4999.4    0.12       0
  5212.8    0.07       0  5286.2   0.035       0
Bank Sta=4995.4,4999.4
Exp/Cntr=0.3,0.1

Chan Stop Cuts=-1