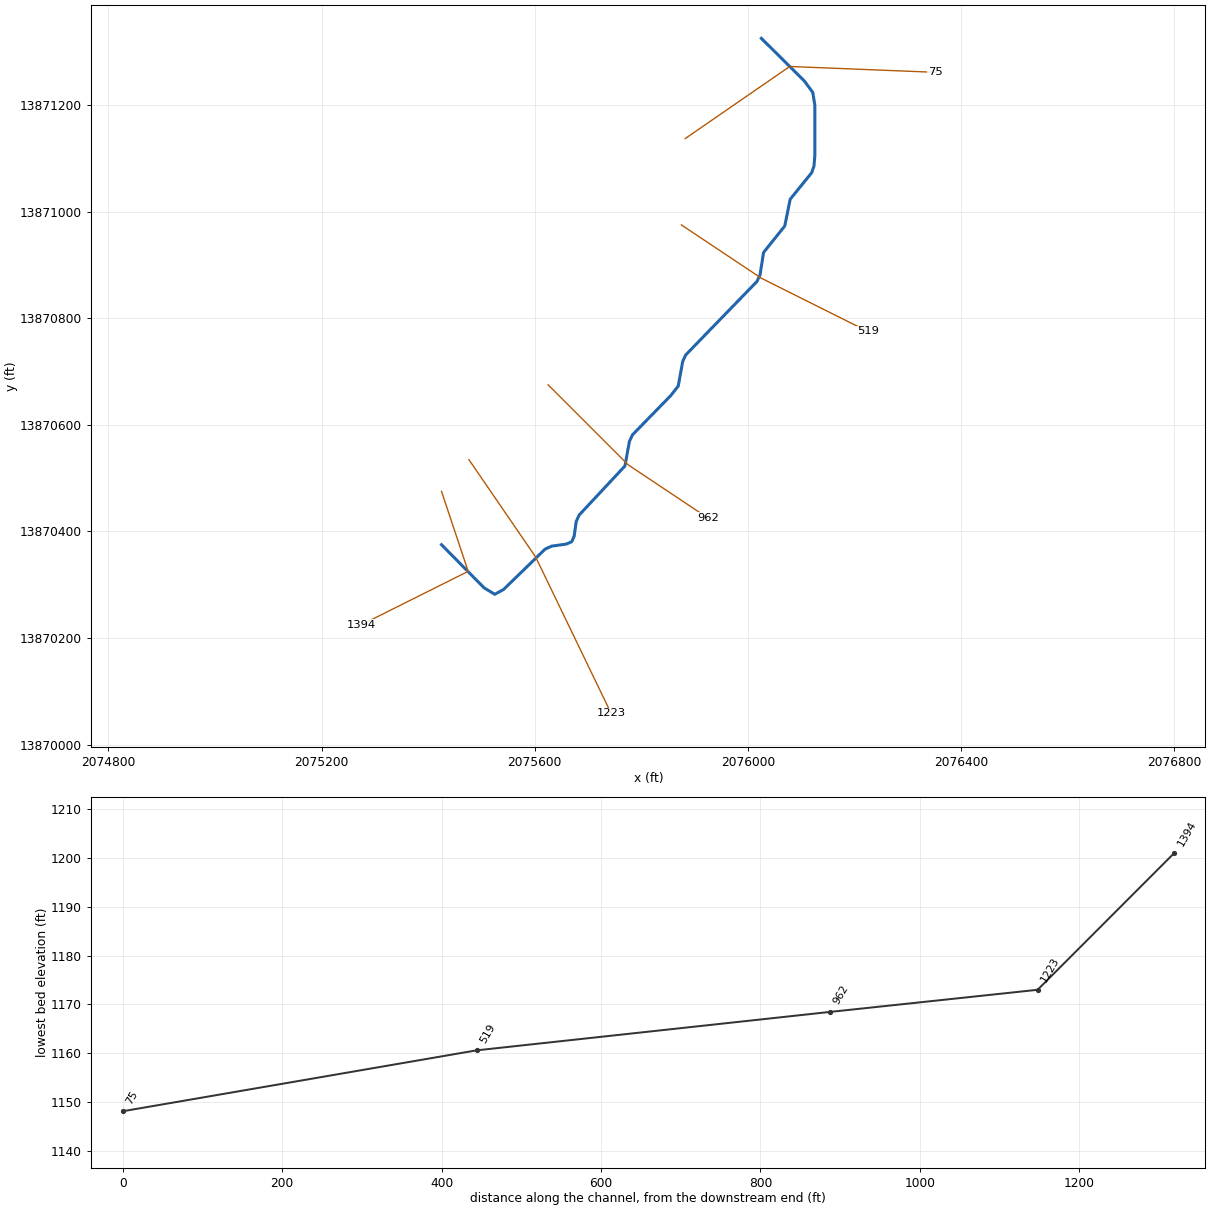
--- Stream0223_DS.prj (project) ---

Proj Title=Stream0223_DS Base Level Engineering
Current Plan=p01
Default Exp/Contr=0.3,0.1
English Units
Geom File=g01
Flow File=f01
Plan File=p01
BEGIN DESCRIPTION:
Stream0223_DS
END DESCRIPTION:

--- Stream0223_DS.p01 (plan) ---

Plan Title=Multiple Run
Short Identifier=Multiple
Geom File=g01
Flow File=f01
Subcritical Flow
K Sum by GR= 0
Std Step Tol= 0.01
Critical Tol= 0.01
Num of Std Step Trials= 20
Max Error Tol= 0.3
Flow Tol Ratio= 0.001
Split Flow NTrial= 30
Split Flow Tol= 0.02
Split Flow Ratio= 0.02
Log Output Level= 0
Friction Slope Method= 1
Unsteady Friction Slope Method= 2
Unsteady Bridges Friction Slope Method= 1
Parabolic Critical Depth
Global Vel Dist=  1 , 1 , 1
Global Log Level= 0
CheckData=True
Encroach Param= -1, 0, 0, 0
BEGIN DESCRIPTION:
Multiple Run
END DESCRIPTION:

--- Stream0223_DS.f01 (steady flow) ---

Flow Title=Multiple
Number of Profiles=7
Profile Names=10-year,25-year,50-year,1pct_min,100-year,1pct_plu,500-year
River Rch & RM= Stream0223_DS,Reach-1,1394
    1175    1998    2786    1885    3761    7503    6768
Boundary for River Rch & Prof#=Stream0223_DS,Reach-1,1
Up Type=0
Dn Type=3
Dn Slope=0.005
Boundary for River Rch & Prof#=Stream0223_DS,Reach-1,2
Up Type=0
Dn Type=3
Dn Slope=0.005
Boundary for River Rch & Prof#=Stream0223_DS,Reach-1,3
Up Type=0
Dn Type=3
Dn Slope=0.005
Boundary for River Rch & Prof#=Stream0223_DS,Reach-1,4
Up Type=0
Dn Type=3
Dn Slope=0.005
Boundary for River Rch & Prof#=Stream0223_DS,Reach-1,5
Up Type=0
Dn Type=3
Dn Slope=0.005
Boundary for River Rch & Prof#=Stream0223_DS,Reach-1,6
Up Type=0
Dn Type=3
Dn Slope=0.005
Boundary for River Rch & Prof#=Stream0223_DS,Reach-1,7
Up Type=0
Dn Type=3
Dn Slope=0.005

--- Stream0223_DS.g01 (geometry) ---

Geom Title=Existing Conditions

River Reach=Stream0223_DS,Reach-1
Reach XY= 30
      2075425.00     13870375.00      2075505.00     13870294.00
      2075525.00     13870281.98      2075541.66     13870291.21
      2075619.25     13870366.68      2075631.43     13870372.29
      2075658.96     13870376.15      2075669.38     13870380.62
      2075673.85     13870391.04      2075677.70     13870418.56
      2075683.30     13870430.74      2075769.13     13870522.72
      2075777.54     13870568.95      2075783.18     13870581.04
      2075855.17     13870654.93      2075869.13     13870672.72
      2075877.53     13870718.95      2075883.16     13870731.05
      2076016.86     13870868.94      2076022.50     13870881.04
      2076029.19     13870923.26      2076068.92     13870972.80
      2076079.19     13871023.26      2076119.30     13871072.65
      2076123.81     13871085.50      2076125.40     13871104.86
      2076125.33     13871200.11      2076121.52     13871223.55
      2076105.51     13871245.21      2076025.00     13871325.00

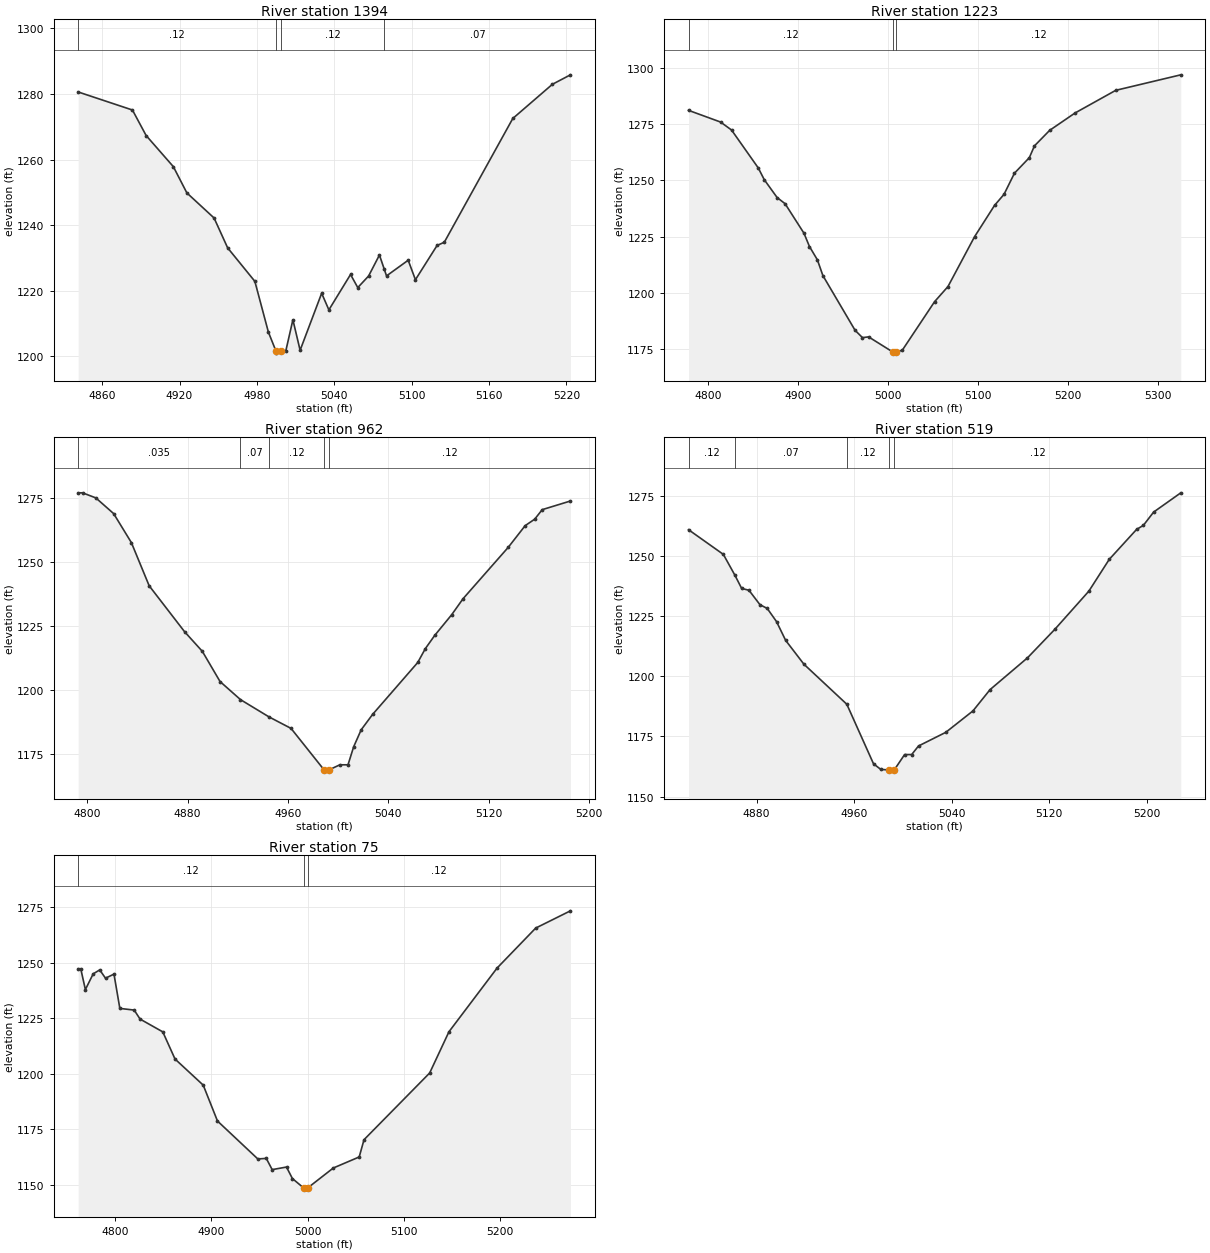
Type RM Length L Ch R = 1,1394,171,171,171
BEGIN DESCRIPTION:
Stream0223_DS 3.0
END DESCRIPTION:
XS GIS Cut Line= 3
      2075425.01     13870474.97      2075475.00     13870325.00
      2075274.99     13870225.00
#Sta/Elev= 30
  4841.4 1280.61  4883.5 1275.10  4894.1 1267.32  4915.2 1257.82  4925.7 1249.80
  4946.8 1242.14  4957.3 1233.04  4978.4 1222.82  4988.9 1207.32  4994.9 1201.41
  4995.1 1200.91  4998.9 1201.41  5002.3 1201.41  5007.9 1211.09  5013.5 1201.78
  5030.2 1219.18  5035.8 1214.11  5052.6 1224.91  5058.2 1220.91  5066.6 1224.45
  5075.0 1230.85  5078.8 1226.45  5080.5 1224.48  5097.3 1229.26  5102.9 1223.31
  5119.7 1233.77  5125.3 1234.75  5178.4 1272.52  5209.1 1282.95  5223.1 1285.84
#Mann=4,-1,0
  4841.4    0.12       0  4994.9    0.05       0  4998.9    0.12       0
  5078.8    0.07       0
Bank Sta=4994.9,4998.9
Exp/Cntr=0.3,0.1

Type RM Length L Ch R = 1,1223,261,261,261
BEGIN DESCRIPTION:
Stream0223_DS 2.5
END DESCRIPTION:
XS GIS Cut Line= 3
      2075476.52     13870534.45      2075601.67     13870351.82
      2075743.20     13870058.58
#Sta/Elev= 30
  4778.6 1281.28  4814.2 1276.06  4826.4 1272.51  4856.1 1255.59  4862.8 1250.33
  4877.1 1242.36  4885.9 1239.64  4906.9 1226.46  4913.0 1220.53  4921.8 1214.60
  4927.9 1207.58  4963.7 1183.15  4971.9 1179.89  4978.7 1180.23  5005.6 1173.48
  5005.8 1172.98  5009.6 1173.48  5016.1 1174.25  5052.0 1195.92  5066.9 1202.68
  5096.4 1224.88  5118.6 1238.85  5129.2 1243.83  5140.8 1253.26  5157.3 1260.17
  5163.0 1265.43  5179.9 1272.36  5208.1 1280.10  5253.3 1290.20  5325.6 1297.12
#Mann=3,-1,0
  4778.6    0.12       0  5005.6    0.05       0  5009.6    0.12       0
Bank Sta=5005.6,5009.6
Exp/Cntr=0.3,0.1

Type RM Length L Ch R = 1,962,443,443,443
BEGIN DESCRIPTION:
Stream0223_DS 2.0
END DESCRIPTION:
XS GIS Cut Line= 3
      2075625.01     13870674.99      2075775.00     13870525.00
      2075925.00     13870425.00
#Sta/Elev= 30
  4792.7 1277.10  4796.2 1277.10  4806.8 1275.12  4821.0 1268.98  4835.1 1257.69
  4849.3 1240.81  4877.5 1222.89  4891.7 1215.20  4905.8 1203.42  4922.1 1196.36
  4944.8 1189.62  4962.4 1185.12  4988.7 1168.94  4988.9 1168.44  4992.7 1168.94
  5001.3 1170.91  5007.8 1170.91  5012.3 1177.94  5018.3 1184.58  5027.4 1190.59
  5063.4 1210.87  5069.4 1216.24  5076.9 1221.42  5090.5 1229.55  5099.5 1235.76
  5135.5 1255.81  5149.0 1264.28  5156.6 1266.81  5162.6 1270.53  5185.1 1273.91
#Mann=5,-1,0
  4792.7   0.035       0  4922.1    0.07       0  4944.8    0.12       0
  4988.7    0.05       0  4992.7    0.12       0
Bank Sta=4988.7,4992.7
Exp/Cntr=0.3,0.1

Type RM Length L Ch R = 1,519,444,444,444
BEGIN DESCRIPTION:
Stream0223_DS 1.0
END DESCRIPTION:
XS GIS Cut Line= 3
      2075874.96     13870975.02      2076025.00     13870875.00
      2076224.98     13870775.01
#Sta/Elev= 30
  4824.1 1261.12  4852.7 1250.83  4862.2 1242.13  4867.7 1236.66  4873.7 1235.90
  4882.7 1229.90  4888.7 1228.32  4896.3 1222.86  4903.8 1215.03  4918.8 1205.10
  4954.0 1188.42  4975.9 1163.62  4981.9 1161.28  4988.9 1161.08  4989.1 1160.58
  4992.9 1161.08  5001.4 1167.48  5007.2 1167.48  5012.8 1171.05  5035.2 1176.74
  5057.5 1185.67  5071.5 1194.52  5102.2 1207.75  5124.6 1219.60  5152.6 1235.55
  5169.3 1248.77  5191.7 1261.22  5197.3 1262.93  5205.7 1268.45  5228.0 1276.47
#Mann=5,-1,0
  4824.1    0.12       0  4862.2    0.07       0  4954.0    0.12       0
  4988.9    0.05       0  4992.9    0.12       0
Bank Sta=4988.9,4992.9
Exp/Cntr=0.3,0.1

Type RM Length L Ch R = 1,75,0,0,0
BEGIN DESCRIPTION:
Stream0223_DS 0.0
END DESCRIPTION:
XS GIS Cut Line= 3
      2075882.16     13871136.92      2076078.32     13871272.23
      2076351.10     13871261.25
#Sta/Elev= 30
  4761.7 1247.30  4764.4 1247.30  4769.2 1237.94  4777.3 1245.02  4784.1 1246.80
  4790.1 1243.06  4798.9 1244.90  4805.0 1229.46  4819.9 1228.71  4826.0 1224.66
  4849.6 1218.90  4862.3 1206.68  4891.6 1194.92  4906.4 1178.77  4948.3 1161.70
  4957.1 1161.94  4963.2 1156.89  4978.1 1158.05  4984.2 1152.88  4996.0 1148.61
  4996.3 1148.11  5000.0 1148.61  5026.7 1157.62  5053.6 1162.59  5058.6 1170.36
  5126.8 1200.40  5146.8 1218.94  5196.8 1247.63  5236.9 1265.62  5273.0 1273.39
#Mann=3,-1,0
  4761.7    0.12       0  4996.0    0.05       0  5000.0    0.12       0
Bank Sta=4996,5000
Exp/Cntr=0.3,0.1

Chan Stop Cuts=-1