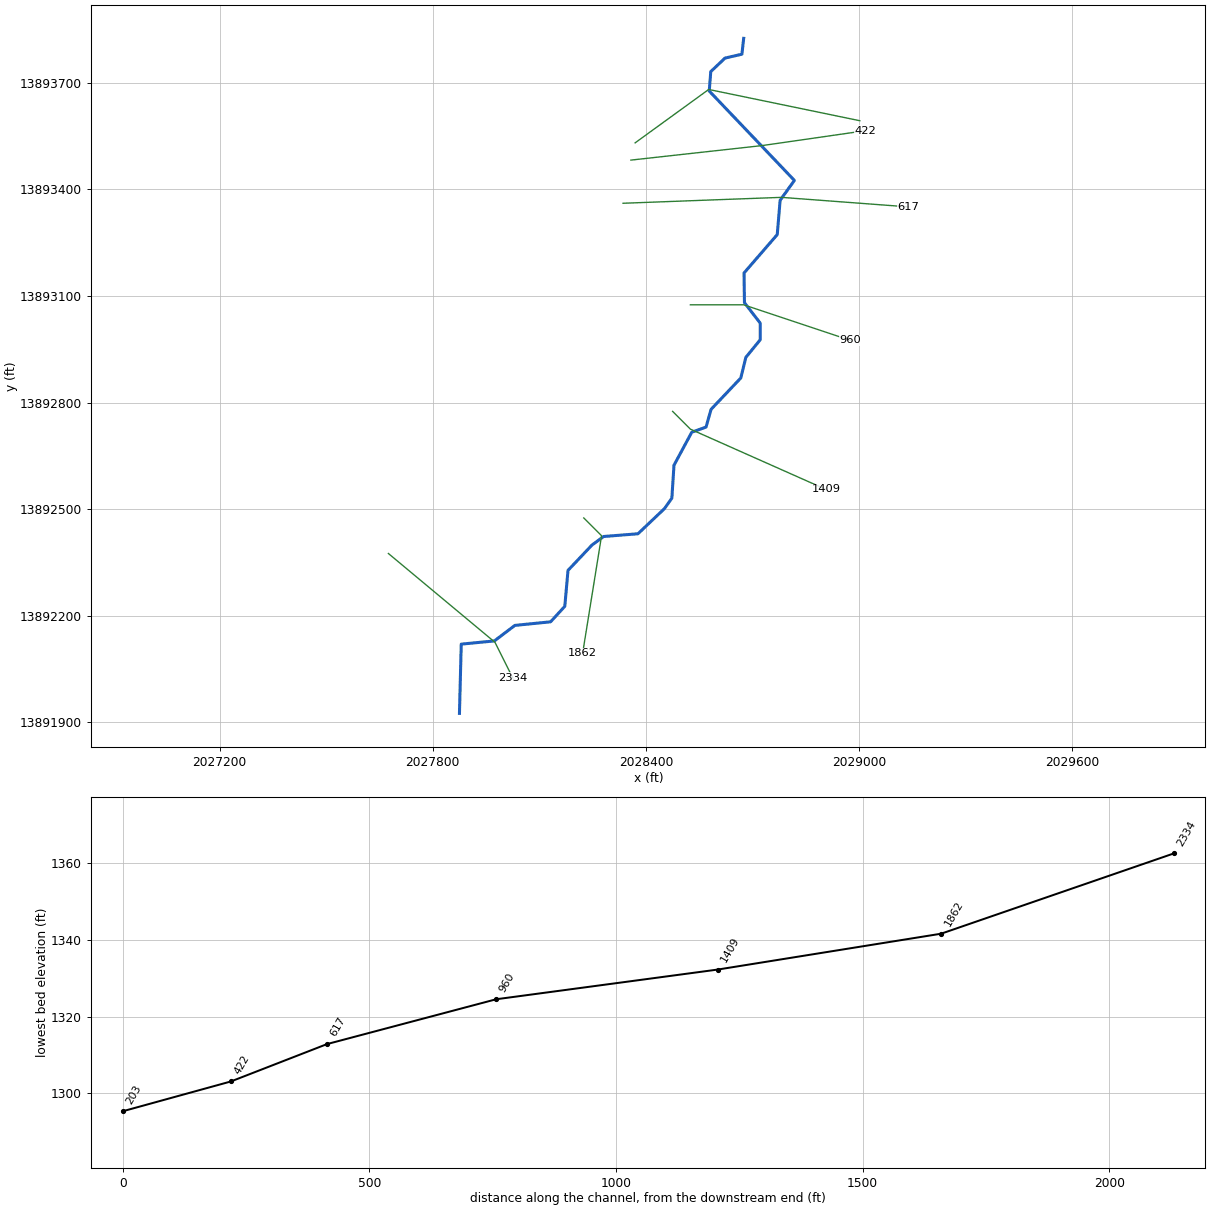
--- Stream0224_DS.prj (project) ---

Proj Title=Stream0224_DS Base Level Engineering
Current Plan=p01
Default Exp/Contr=0.3,0.1
English Units
Geom File=g01
Flow File=f01
Plan File=p01
Y Axis Title=Elevation
X Axis Title(PF)=Main Channel Distance
X Axis Title(XS)=Station
BEGIN DESCRIPTION:
Stream0224_DS
END DESCRIPTION:
DSS Export Rating Curves= 0
DSS Export Rating Curve Sorted= 0
DSS Export Volume Flow Curves= 0
DXF OffsetX= 0
DXF OffsetY= 0
DXF ScaleX= 1
DXF ScaleY= 10

--- Stream0224_DS.p01 (plan) ---

Plan Title=Multiple Run
Short Identifier=Multiple
Geom File=g01
Flow File=f01
Subcritical Flow
K Sum by GR= 0
Std Step Tol= 0.01
Critical Tol= 0.01
Num of Std Step Trials= 20
Max Error Tol= 0.3
Flow Tol Ratio= 0.001
Split Flow NTrial= 30
Split Flow Tol= 0.02
Split Flow Ratio= 0.02
Log Output Level= 0
Friction Slope Method= 1
Unsteady Friction Slope Method= 2
Unsteady Bridges Friction Slope Method= 1
Parabolic Critical Depth
Global Vel Dist=  1 , 1 , 1
Global Log Level= 0
CheckData=True
Encroach Param= -1, 0, 0, 0
BEGIN DESCRIPTION:
Multiple Run
END DESCRIPTION:

--- Stream0224_DS.f01 (steady flow) ---

Flow Title=Multiple
Number of Profiles=7
Profile Names=10-year,25-year,50-year,1pct_min,100-year,1pct_plu,500-year
River Rch & RM= Stream0224_DS,Reach-1,2334
     827    1389    1922    1291    2577    5141    4576
Boundary for River Rch & Prof#=Stream0224_DS,Reach-1,1
Up Type=0
Dn Type=3
Dn Slope=0.005
Boundary for River Rch & Prof#=Stream0224_DS,Reach-1,2
Up Type=0
Dn Type=3
Dn Slope=0.005
Boundary for River Rch & Prof#=Stream0224_DS,Reach-1,3
Up Type=0
Dn Type=3
Dn Slope=0.005
Boundary for River Rch & Prof#=Stream0224_DS,Reach-1,4
Up Type=0
Dn Type=3
Dn Slope=0.005
Boundary for River Rch & Prof#=Stream0224_DS,Reach-1,5
Up Type=0
Dn Type=3
Dn Slope=0.005
Boundary for River Rch & Prof#=Stream0224_DS,Reach-1,6
Up Type=0
Dn Type=3
Dn Slope=0.005
Boundary for River Rch & Prof#=Stream0224_DS,Reach-1,7
Up Type=0
Dn Type=3
Dn Slope=0.005

--- Stream0224_DS.g01 (geometry) ---

Geom Title=Existing Conditions
Program Version=4.10

River Reach=Stream0224_DS   ,Reach-1
Reach XY= 30
        2027875.       13891925.      2027880.02     13892119.93
      2027973.32     13892128.89      2028030.98     13892172.64
       2028131.5     13892182.73      2028171.49     13892226.25
      2028180.52     13892327.44      2028248.07     13892398.85
      2028280.88     13892422.85      2028377.44     13892430.52
      2028452.15     13892501.42      2028472.85     13892530.88
      2028478.82     13892623.44      2028528.84     13892716.38
      2028569.01     13892730.77      2028583.25     13892780.76
      2028666.85     13892868.95      2028681.18     13892927.19
      2028721.66     13892976.72      2028721.63     13893023.26
      2028677.19     13893080.97      2028675.94     13893164.52
      2028769.46     13893272.58      2028777.56     13893369.11
      2028817.69      13893425.1      2028578.08     13893676.67
      2028582.34     13893731.32      2028622.49      13893769.4
      2028670.03     13893780.34        2028675.       13893825.

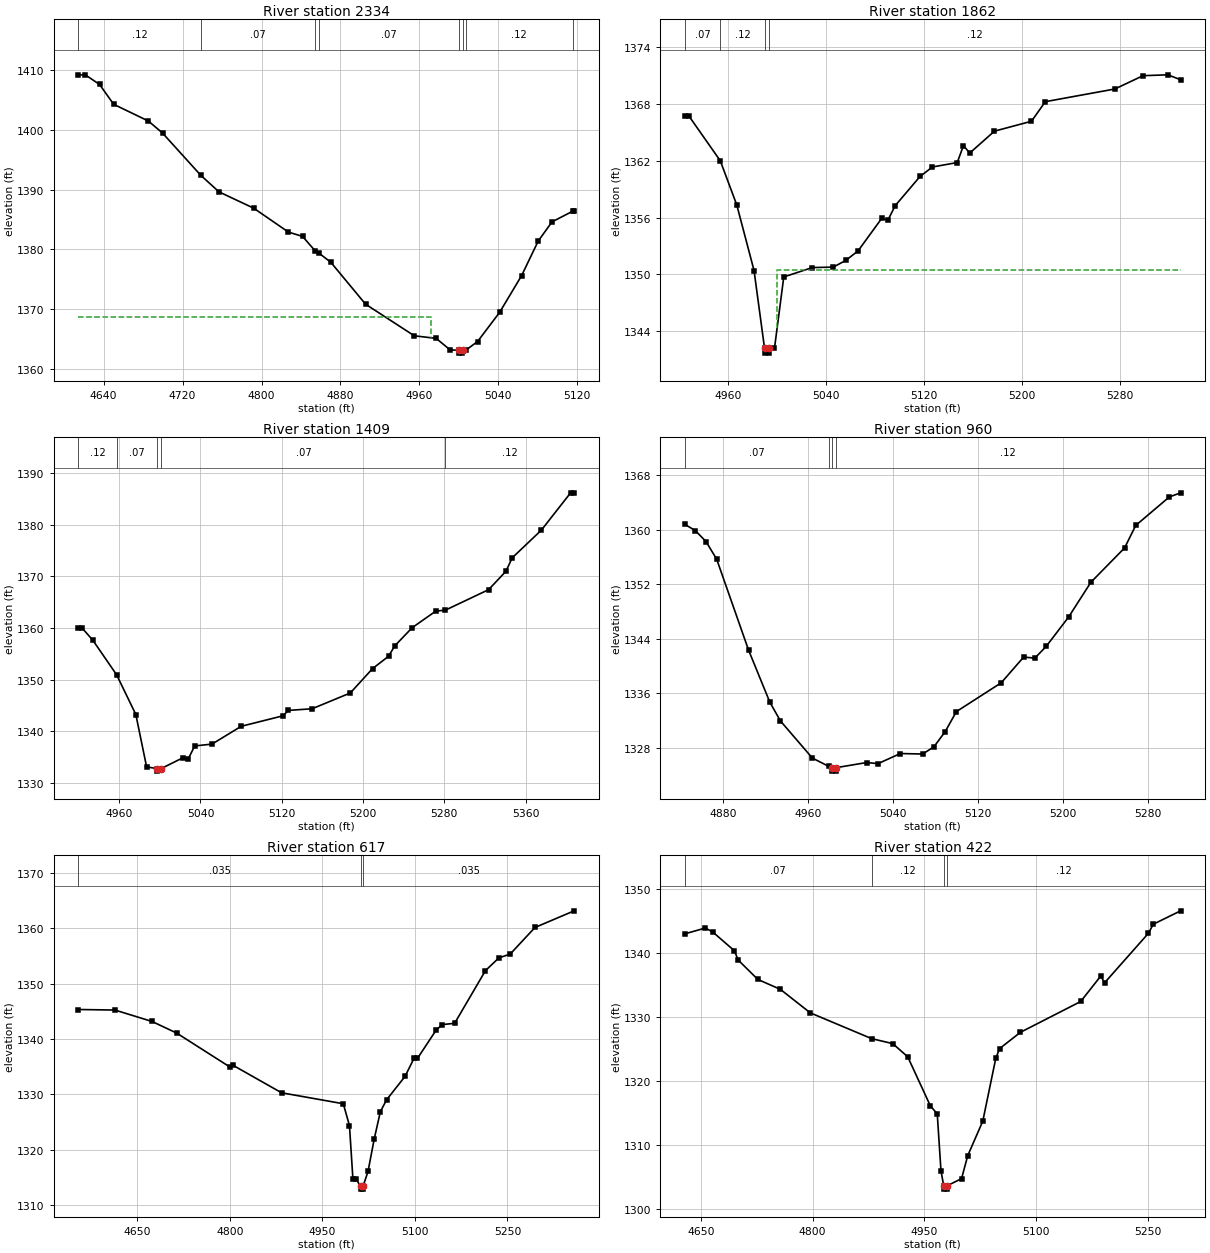
Type RM Length L Ch R = 1 ,2334    ,472,472,472
BEGIN DESCRIPTION:
Stream0224_DS 5.0
END DESCRIPTION:
XS GIS Cut Line= 3
      2027674.97     13892375.02        2027975.       13892125.
      2028025.02     13892024.96
#Sta/Elev= 30
  4614.4 1409.26  4621.6 1409.24  4635.9 1407.65  4650.2 1404.32  4685.4 1401.51
  4699.7  1399.5  4738.6 1392.39    4757 1389.63  4792.1  1386.9  4827.3 1382.89
  4841.6 1382.17  4854.6  1379.7  4858.3 1379.35  4870.2 1377.84  4905.4 1370.81
  4954.8 1365.51    4977 1365.07  4991.3 1363.12  4999.7  1363.1  4999.9  1362.6
  5003.4  1362.6  5003.7  1363.1  5007.1  1363.1  5018.9 1364.54  5041.3 1369.44
  5063.6 1375.61  5080.4  1381.4  5094.4 1384.61  5115.4  1386.4  5116.8  1386.4
#Mann= 8 ,-1 , 0
  4614.4     .12       0  4738.6     .07       0  4854.6     .12       0
  4858.3     .07       0  4999.7     .05       0  5003.7     .07       0
  5007.1     .12       0  5115.4     .07       0
#XS Ineff= 2 , 0
       0 4971.48 1368.66               0
Permanent Ineff=
       F       F
Bank Sta=4999.7,5003.7
XS Rating Curve= 0 ,0
Exp/Cntr=0.3,0.1

Type RM Length L Ch R = 1 ,1862    ,453,453,453
BEGIN DESCRIPTION:
Stream0224_DS 4.0
END DESCRIPTION:
XS GIS Cut Line= 3
      2028224.98     13892475.02        2028275.       13892425.
       2028221.8      13892094.7
#Sta/Elev= 30
  4924.5  1366.7  4928.1  1366.7  4953.5 1362.01    4967 1357.33  4981.1  1350.4
  4989.7 1342.16    4990 1341.66  4993.5 1341.66  4993.7 1342.16  4997.8 1342.16
  5005.4 1349.72  5028.7 1350.71  5045.9 1350.76    5056 1351.46  5066.1 1352.47
  5085.5 1355.92  5090.5 1355.72  5096.5 1357.26  5116.8 1360.35  5126.9 1361.35
  5147.2 1361.82  5152.3 1363.62  5157.4 1362.82  5177.6 1365.14  5207.9 1366.19
  5219.2 1368.26    5276  1369.6  5299.1 1371.01  5319.4  1371.1  5329.8 1370.58
#Mann= 4 ,-1 , 0
  4924.5     .07       0  4953.5     .12       0  4989.7     .05       0
  4993.7     .12       0
#XS Ineff= 2 , 0
       0                    5000       0 1350.44
Permanent Ineff=
       F       F
Bank Sta=4989.7,4993.7
XS Rating Curve= 0 ,0
Exp/Cntr=0.3,0.1

Type RM Length L Ch R = 1 ,1409    ,449,449,449
BEGIN DESCRIPTION:
Stream0224_DS 3.0
END DESCRIPTION:
XS GIS Cut Line= 3
      2028474.98     13892775.02        2028525.       13892725.
      2028906.28     13892555.49
#Sta/Elev= 30
  4919.8 1360.01  4923.4 1360.01    4934 1357.65  4957.5 1350.94  4976.4 1343.26
    4987 1333.12  4997.4 1332.81  4997.7 1332.31  5001.4 1332.81  5022.7 1334.89
  5028.1 1334.71  5034.3 1337.18  5051.4 1337.54  5080.1 1340.98  5121.2 1343.01
  5126.6 1344.06  5149.9 1344.37  5187.5 1347.43  5209.4 1352.14  5225.1 1354.52
  5231.3 1356.55  5248.4 1360.06  5271.6 1363.26  5281.1 1363.45  5323.6 1367.41
  5340.7 1370.98  5346.8 1373.56  5375.6 1378.94  5404.3 1386.14  5407.8 1386.14
#Mann= 5 ,-1 , 0
  4919.8     .12       0  4957.5     .07       0  4997.4     .05       0
  5001.4     .07       0  5281.1     .12       0
Bank Sta=4997.4,5001.4
XS Rating Curve= 0 ,0
Exp/Cntr=0.3,0.1

Type RM Length L Ch R = 1 ,960     ,343,343,343
BEGIN DESCRIPTION:
Stream0224_DS 2.0
END DESCRIPTION:
XS GIS Cut Line= 3
      2028524.96       13893075.        2028675.       13893075.
      2028975.03     13892974.99
#Sta/Elev= 30
  4844.2 1360.77  4854.2 1359.84  4864.2 1358.23  4874.2 1355.65  4904.2 1342.31
  4924.2 1334.67  4934.2 1331.92  4964.2 1326.48  4979.7 1325.26  4982.2 1325.07
  4982.5 1324.57    4986 1324.57  4986.2 1325.07  5015.3 1325.83  5025.9 1325.67
  5046.9 1327.15    5068 1327.08  5078.6 1328.16  5089.1 1330.37  5099.6  1333.3
  5141.8 1337.53  5162.9  1341.3  5173.4 1341.15    5184 1342.85  5205.1 1347.16
  5226.1 1352.27  5257.8 1357.31  5268.3 1360.61  5299.9 1364.79  5310.5 1365.39
#Mann= 4 ,-1 , 0
  4844.2     .07       0  4979.7     .12       0  4982.2     .05       0
  4986.2     .12       0
Bank Sta=4982.2,4986.2
XS Rating Curve= 0 ,0
Exp/Cntr=0.3,0.1

Type RM Length L Ch R = 1 ,617     ,195,195,195
BEGIN DESCRIPTION:
Stream0224_DS 1.5
END DESCRIPTION:
XS GIS Cut Line= 3
      2028335.61     13893360.81       2028781.1     13893377.43
      2029138.39     13893350.61
#Sta/Elev= 30
  4554.2 1345.32  4613.6 1345.22  4673.7 1343.16  4713.7 1341.06  4799.8 1334.95
  4804.8 1335.26  4883.8 1330.28  4983.9  1328.3  4993.9 1324.35  4999.5 1314.72
  5004.5 1314.72  5011.9 1313.38  5012.2 1312.88  5015.7 1312.88  5015.9 1313.38
    5024 1316.07    5034 1321.91    5044 1326.86  5054.1 1329.01  5084.1 1333.25
  5099.2 1336.64  5104.2 1336.49  5134.3 1341.57  5144.3  1342.6  5164.4 1342.82
  5214.5 1352.35  5236.2 1354.64  5254.6 1355.33  5294.7 1360.13  5358.3 1363.14
#Mann= 3 ,-1 , 0
  4554.2    .035       0  5011.9    .035       0  5015.9    .035       0
Bank Sta=5011.9,5015.9
XS Rating Curve= 0 ,0
Exp/Cntr=0.3,0.1

Type RM Length L Ch R = 1 ,422     ,219,219,219
BEGIN DESCRIPTION:
Stream0224_DS 1.0
END DESCRIPTION:
XS GIS Cut Line= 3
       2028357.6     13893482.27       2028726.8     13893523.11
      2029017.75     13893565.04
#Sta/Elev= 30
  4628.4 1342.94    4656 1343.85    4666 1343.22    4695  1340.3    4700 1338.86
  4726.4 1335.83  4756.6 1334.29  4796.8 1330.62  4879.1  1326.6  4907.5 1325.82
  4927.6 1323.76  4957.8 1316.15  4967.2 1314.85  4972.2 1305.98  4975.9 1303.63
  4976.2 1303.13  4979.7 1303.13  4979.9 1303.63  4999.8 1304.76  5008.1 1308.35
  5028.3 1313.73  5045.8 1323.57  5050.9 1325.05  5078.9 1327.59  5159.7 1332.39
  5186.7 1336.37  5191.7  1335.3  5250.6 1343.03  5257.1 1344.44  5293.8 1346.53
#Mann= 4 ,-1 , 0
  4628.4     .07       0  4879.1     .12       0  4975.9     .05       0
  4979.9     .12       0
Bank Sta=4975.9,4979.9
XS Rating Curve= 0 ,0
Exp/Cntr=0.3,0.1

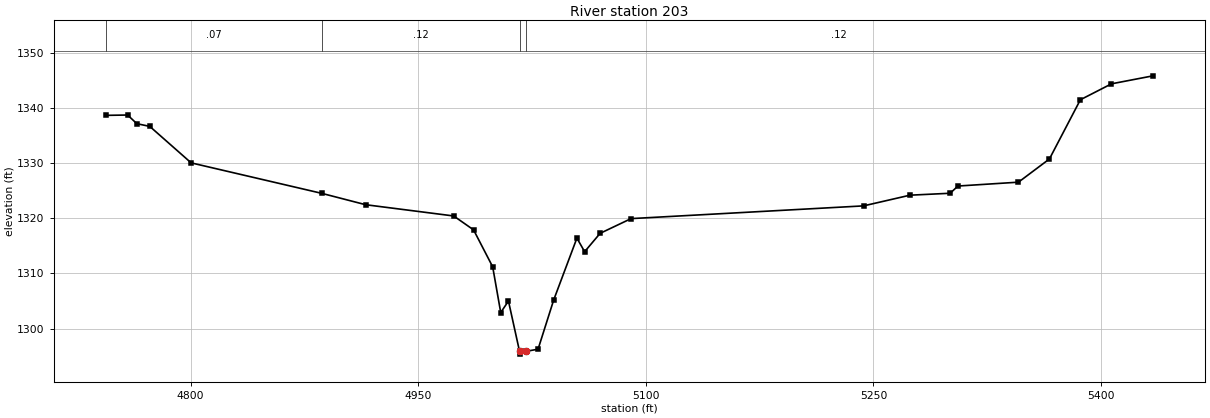
Type RM Length L Ch R = 1 ,203     ,0,0,0
BEGIN DESCRIPTION:
Stream0224_DS 0.0
END DESCRIPTION:
XS GIS Cut Line= 3
      2028369.52     13893530.86      2028576.56     13893681.08
      2029001.86     13893593.11
#Sta/Elev= 30
  4744.2 1338.68  4758.5 1338.74  4764.6 1337.17  4773.1 1336.68  4800.4 1330.06
  4886.5 1324.53  4915.4 1322.47  4973.4 1320.43  4986.5 1317.91  4999.1 1311.21
  5004.4 1302.92  5009.5    1305  5016.8 1295.87  5017.1 1295.37  5020.8 1295.87
    5029 1296.26  5039.3 1305.19  5054.6 1316.41  5059.7 1313.95  5069.9 1317.28
  5090.3 1319.95  5243.5 1322.26  5274.1  1324.2  5300.6 1324.55  5305.7 1325.86
  5345.6 1326.56    5366 1330.77  5386.4 1341.51  5406.9  1344.4  5434.3 1345.85
#Mann= 4 ,-1 , 0
  4744.2     .07       0  4886.5     .12       0  5016.8     .05       0
  5020.8     .12       0
Bank Sta=5016.8,5020.8
XS Rating Curve= 0 ,0
Exp/Cntr=0.3,0.1

Chan Stop Cuts=-1
Use User Specified Reach Order=0
Composite Channel Slope=5