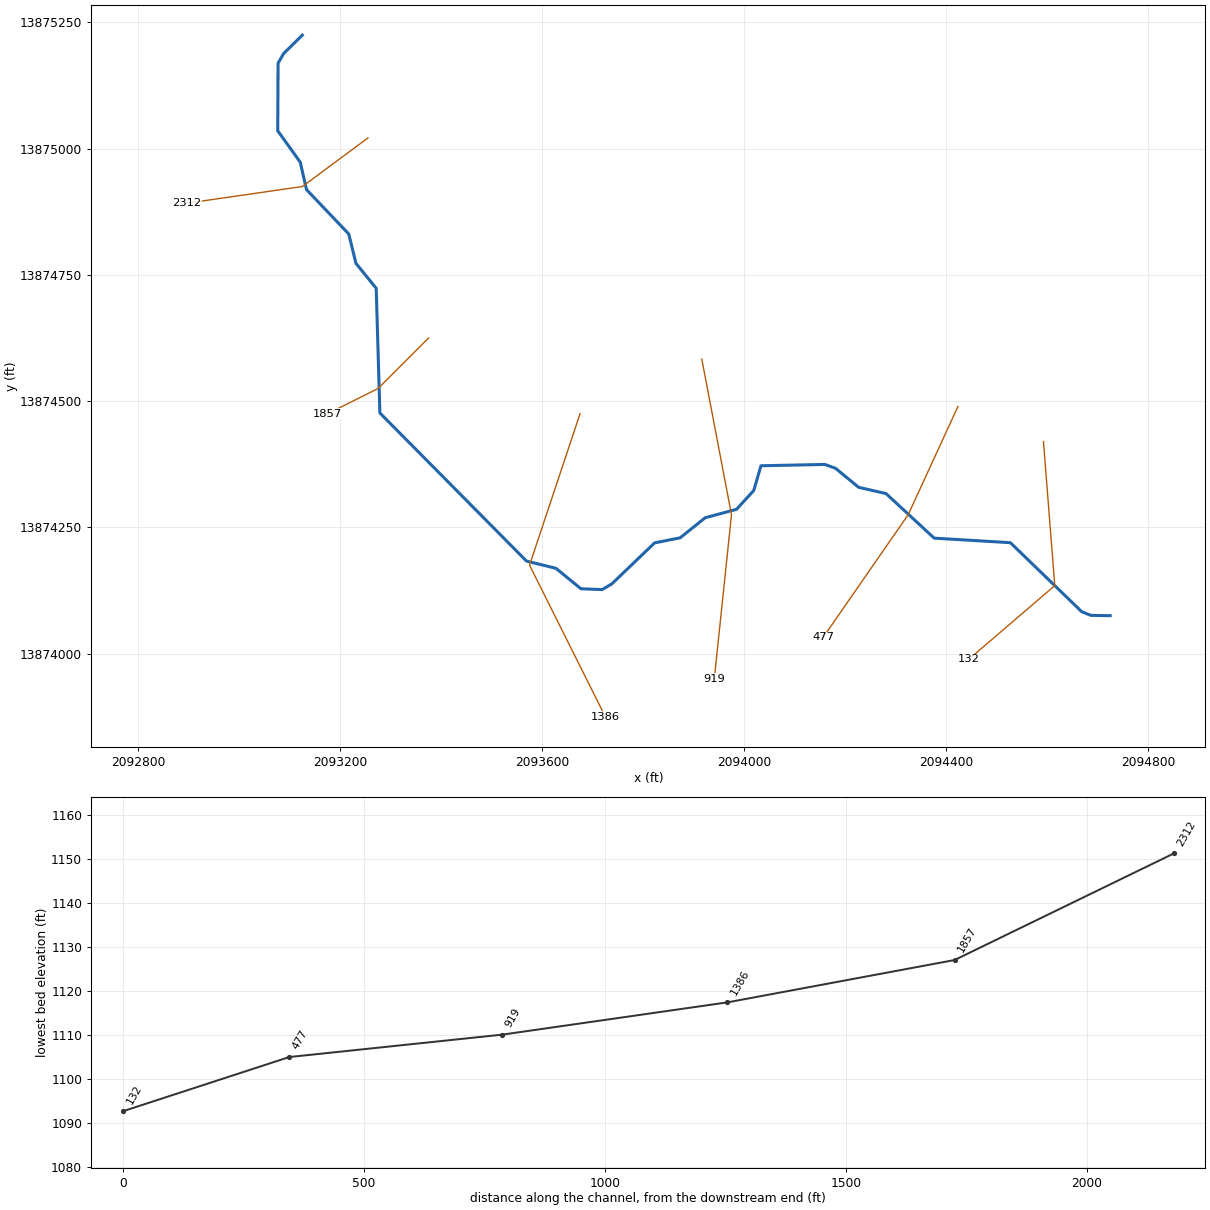
--- Stream0225_DS.prj (project) ---

Proj Title=Stream0225_DS Base Level Engineering
Current Plan=p01
Default Exp/Contr=0.3,0.1
English Units
Geom File=g01
Flow File=f01
Plan File=p01
BEGIN DESCRIPTION:
Stream0225_DS
END DESCRIPTION:

--- Stream0225_DS.p01 (plan) ---

Plan Title=Multiple Run
Short Identifier=Multiple
Geom File=g01
Flow File=f01
Subcritical Flow
K Sum by GR= 0
Std Step Tol= 0.01
Critical Tol= 0.01
Num of Std Step Trials= 20
Max Error Tol= 0.3
Flow Tol Ratio= 0.001
Split Flow NTrial= 30
Split Flow Tol= 0.02
Split Flow Ratio= 0.02
Log Output Level= 0
Friction Slope Method= 1
Unsteady Friction Slope Method= 2
Unsteady Bridges Friction Slope Method= 1
Parabolic Critical Depth
Global Vel Dist=  1 , 1 , 1
Global Log Level= 0
CheckData=True
Encroach Param= -1, 0, 0, 0
BEGIN DESCRIPTION:
Multiple Run
END DESCRIPTION:

--- Stream0225_DS.f01 (steady flow) ---

Flow Title=Multiple
Number of Profiles=7
Profile Names=10-year,25-year,50-year,1pct_min,100-year,1pct_plu,500-year
River Rch & RM= Stream0225_DS,Reach-1,2312
     945    1588    2196    1473    2939    5864    5204
Boundary for River Rch & Prof#=Stream0225_DS,Reach-1,1
Up Type=0
Dn Type=3
Dn Slope=0.005
Boundary for River Rch & Prof#=Stream0225_DS,Reach-1,2
Up Type=0
Dn Type=3
Dn Slope=0.005
Boundary for River Rch & Prof#=Stream0225_DS,Reach-1,3
Up Type=0
Dn Type=3
Dn Slope=0.005
Boundary for River Rch & Prof#=Stream0225_DS,Reach-1,4
Up Type=0
Dn Type=3
Dn Slope=0.005
Boundary for River Rch & Prof#=Stream0225_DS,Reach-1,5
Up Type=0
Dn Type=3
Dn Slope=0.005
Boundary for River Rch & Prof#=Stream0225_DS,Reach-1,6
Up Type=0
Dn Type=3
Dn Slope=0.005
Boundary for River Rch & Prof#=Stream0225_DS,Reach-1,7
Up Type=0
Dn Type=3
Dn Slope=0.005

--- Stream0225_DS.g01 (geometry) ---

Geom Title=Existing Conditions

River Reach=Stream0225_DS,Reach-1
Reach XY= 30
      2093125.00     13875225.00      2093087.91     13875188.50
      2093076.88     13875169.21      2093076.18     13875035.50
      2093120.78     13874973.25      2093133.16     13874918.95
      2093216.84     13874831.05      2093231.14     13874772.83
      2093271.25     13874723.45      2093278.54     13874476.46
      2093568.94     13874183.14      2093627.19     13874168.82
      2093676.73     13874128.31      2093718.96     13874126.62
      2093738.20     13874138.15      2093822.71     13874219.15
      2093873.27     13874229.19      2093922.84     13874268.89
      2093984.98     13874285.69      2094019.08     13874322.86
      2094033.31     13874371.92      2094159.77     13874374.52
      2094181.07     13874366.91      2094226.75     13874329.22
      2094281.05     13874316.84      2094376.47     13874228.55
      2094527.45     13874219.53      2094668.79     13874082.76
      2094686.84     13874075.59      2094725.00     13874075.00

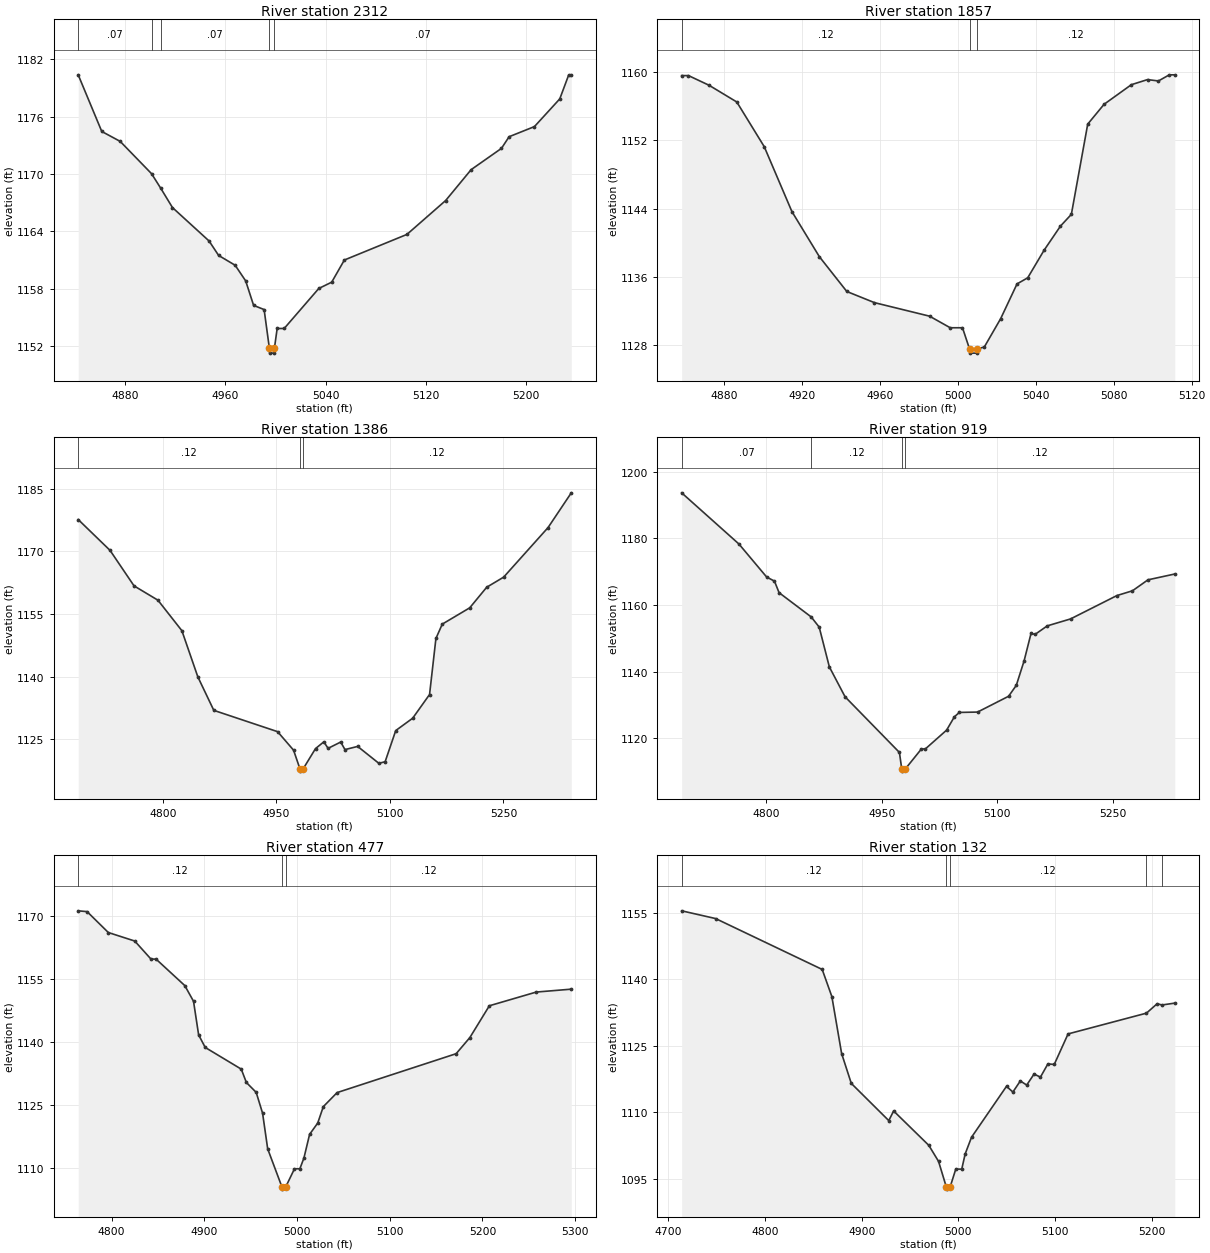
Type RM Length L Ch R = 1,2312,455,455,455
BEGIN DESCRIPTION:
Stream0225_DS 5.0
END DESCRIPTION:
XS GIS Cut Line= 3
      2093255.00     13875021.33      2093125.00     13874925.00
      2092895.87     13874891.90
#Sta/Elev= 30
  4842.7 1180.38  4861.5 1174.45  4876.2 1173.41  4901.2 1170.03  4908.6 1168.49
  4917.9 1166.48  4947.1 1162.98  4954.7 1161.47  4967.9 1160.44  4976.3 1158.80
  4982.6 1156.24  4991.0 1155.80  4995.2 1151.74  4995.4 1151.24  4998.9 1151.24
  4999.2 1151.74  5001.4 1153.82  5007.0 1153.82  5034.6 1158.01  5044.9 1158.67
  5055.0 1160.99  5104.9 1163.67  5135.8 1167.22  5156.1 1170.45  5180.3 1172.68
  5186.4 1173.90  5206.6 1174.96  5226.8 1177.86  5233.9 1180.36  5236.0 1180.36
#Mann=5,-1,0
  4842.7    0.07       0  4901.2    0.12       0  4908.6    0.07       0
  4995.2    0.05       0  4999.2    0.07       0
Bank Sta=4995.2,4999.2
Exp/Cntr=0.3,0.1

Type RM Length L Ch R = 1,1857,471,471,471
BEGIN DESCRIPTION:
Stream0225_DS 4.0
END DESCRIPTION:
XS GIS Cut Line= 3
      2093374.99     13874624.99      2093275.00     13874525.00
      2093175.01     13874475.01
#Sta/Elev= 30
  4858.1 1159.62  4861.6 1159.62  4872.2 1158.48  4886.4 1156.52  4900.5 1151.27
  4914.7 1143.65  4928.8 1138.35  4942.9 1134.26  4957.1 1132.95  4985.4 1131.36
  4996.0 1130.00  5002.3 1130.00  5005.9 1127.52  5006.1 1127.02  5009.6 1127.02
  5009.9 1127.52  5013.5 1127.74  5021.9 1131.07  5030.3 1135.15  5035.8 1135.87
  5044.2 1139.11  5052.6 1141.94  5058.2 1143.32  5066.6 1153.92  5075.0 1156.25
  5089.0 1158.55  5097.3 1159.15  5102.9 1158.99  5108.5 1159.71  5111.3 1159.71
#Mann=3,-1,0
  4858.1    0.12       0  5005.9    0.05       0  5009.9    0.12       0
Bank Sta=5005.9,5009.9
Exp/Cntr=0.3,0.1

Type RM Length L Ch R = 1,1386,467,467,467
BEGIN DESCRIPTION:
Stream0225_DS 3.0
END DESCRIPTION:
XS GIS Cut Line= 3
      2093674.99     13874474.97      2093575.00     13874175.00
      2093725.00     13873875.00
#Sta/Elev= 30
  4688.1 1177.60  4730.2 1170.22  4761.9 1161.73  4793.5 1158.30  4825.1 1151.01
  4846.2 1139.96  4867.3 1131.95  4951.6 1126.85  4972.7 1122.42  4981.2 1117.91
  4981.5 1117.41  4985.2 1117.91  5001.7 1122.80  5012.7 1124.42  5018.3 1122.86
  5035.0 1124.37  5040.6 1122.56  5057.4 1123.32  5085.4 1119.28  5093.7 1119.66
  5107.7 1127.11  5130.1 1130.07  5152.4 1135.74  5160.8 1149.14  5169.2 1152.58
  5205.5 1156.48  5227.9 1161.40  5250.3 1163.82  5309.0 1175.68  5339.7 1183.99
#Mann=3,-1,0
  4688.1    0.12       0  4981.2    0.05       0  4985.2    0.12       0
Bank Sta=4981.2,4985.2
Exp/Cntr=0.3,0.1

Type RM Length L Ch R = 1,919,442,442,442
BEGIN DESCRIPTION:
Stream0225_DS 2.0
END DESCRIPTION:
XS GIS Cut Line= 3
      2093916.12     13874583.40      2093975.00     13874275.00
      2093940.99     13873950.34
#Sta/Elev= 30
  4690.3 1193.67  4764.7 1178.29  4800.7 1168.37  4810.8 1167.15  4816.8 1163.68
  4858.5 1156.40  4868.9 1153.34  4882.1 1141.39  4902.5 1132.41  4973.1 1115.69
  4976.2 1110.58  4976.5 1110.08  4980.2 1110.58  5001.7 1116.75  5006.8 1116.75
  5034.4 1122.40  5044.5 1126.40  5050.9 1127.71  5074.6 1127.82  5114.9 1132.57
  5124.9 1135.85  5135.0 1143.18  5144.1 1151.51  5149.1 1151.12  5165.1 1153.71
  5195.3 1155.79  5255.6 1162.82  5275.7 1164.24  5295.9 1167.54  5330.7 1169.29
#Mann=4,-1,0
  4690.3    0.07       0  4858.5    0.12       0  4976.2    0.05       0
  4980.2    0.12       0
Bank Sta=4976.2,4980.2
Exp/Cntr=0.3,0.1

Type RM Length L Ch R = 1,477,345,345,345
BEGIN DESCRIPTION:
Stream0225_DS 1.0
END DESCRIPTION:
XS GIS Cut Line= 3
      2094423.62     13874489.48      2094325.00     13874275.00
      2094156.45     13874031.89
#Sta/Elev= 30
  4763.9 1171.32  4773.5 1171.13  4796.4 1166.15  4824.9 1164.12  4842.4 1159.82
  4847.9 1159.81  4878.9 1153.50  4888.3 1149.76  4893.8 1141.76  4900.9 1138.76
  4939.8 1133.59  4945.3 1130.41  4955.9 1128.05  4962.8 1123.08  4968.3 1114.59
  4983.7 1105.49  4984.0 1104.99  4987.7 1105.49  4997.2 1109.84  5003.0 1109.84
  5007.4 1112.41  5013.5 1118.04  5022.3 1120.75  5028.3 1124.65  5043.2 1128.00
  5171.6 1137.27  5186.4 1141.12  5207.4 1148.69  5258.0 1151.96  5295.8 1152.65
#Mann=3,-1,0
  4763.9    0.12       0  4983.7    0.05       0  4987.7    0.12       0
Bank Sta=4983.7,4987.7
Exp/Cntr=0.3,0.1

Type RM Length L Ch R = 1,132,0,0,0
BEGIN DESCRIPTION:
Stream0225_DS 0.0
END DESCRIPTION:
XS GIS Cut Line= 3
      2094592.94     13874419.95      2094615.35     13874134.53
      2094445.35     13873988.82
#Sta/Elev= 30
  4713.7 1155.40  4748.8 1153.66  4859.1 1142.19  4869.1 1136.07  4879.2 1123.24
  4889.2 1116.51  4928.0 1108.12  4933.0 1110.30  4969.4 1102.55  4979.5 1098.93
  4987.5 1093.18  4987.8 1092.68  4991.5 1093.18  4997.3 1097.19  5003.5 1097.19
  5007.0 1100.59  5013.6 1104.37  5049.8 1115.85  5056.4 1114.56  5064.1 1117.06
  5070.7 1116.13  5078.3 1118.61  5084.9 1117.92  5092.6 1120.90  5099.2 1120.78
  5113.5 1127.66  5194.6 1132.34  5205.7 1134.47  5210.6 1134.18  5223.9 1134.60
#Mann=5,-1,0
  4713.7    0.12       0  4987.5    0.05       0  4991.5    0.12       0
  5194.6   0.035       0  5210.6    0.12       0
Bank Sta=4987.5,4991.5
Exp/Cntr=0.3,0.1

Chan Stop Cuts=-1