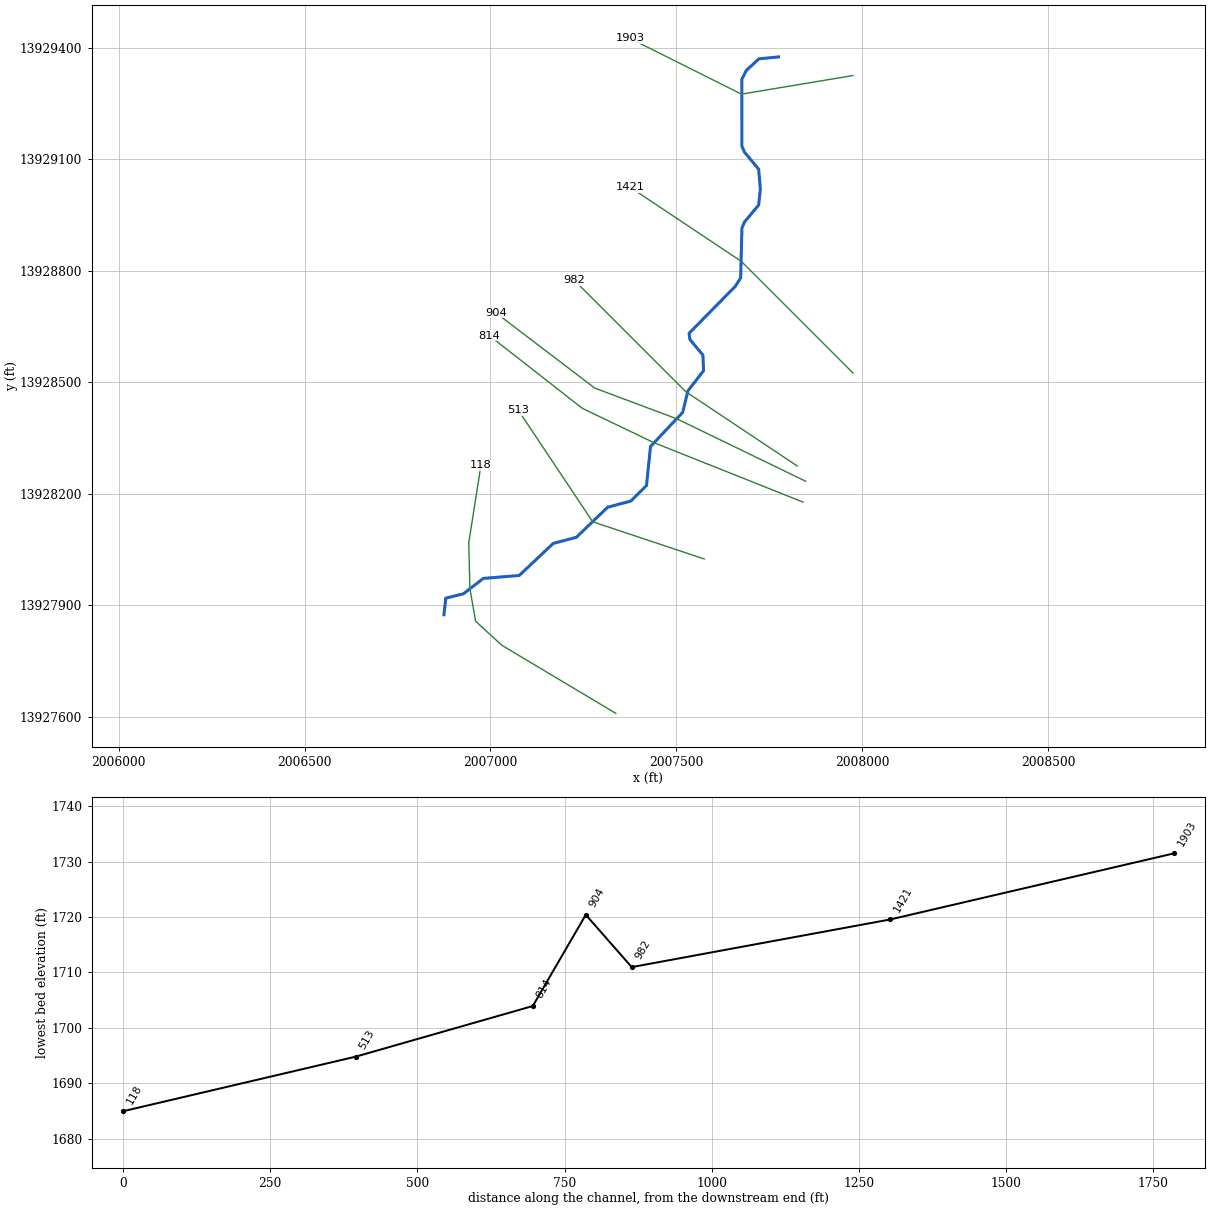
--- Stream0228_DS.prj (project) ---

Proj Title=Stream0228_DS Base Level Engineering
Current Plan=p01
Default Exp/Contr=0.3,0.1
English Units
Geom File=g01
Flow File=f01
Plan File=p01
BEGIN DESCRIPTION:
Stream0228_DS
END DESCRIPTION:

--- Stream0228_DS.p01 (plan) ---

Plan Title=Multiple Run
Short Identifier=Multiple
Geom File=g01
Flow File=f01
Subcritical Flow
K Sum by GR= 0
Std Step Tol= 0.01
Critical Tol= 0.01
Num of Std Step Trials= 20
Max Error Tol= 0.3
Flow Tol Ratio= 0.001
Split Flow NTrial= 30
Split Flow Tol= 0.02
Split Flow Ratio= 0.02
Log Output Level= 0
Friction Slope Method= 1
Unsteady Friction Slope Method= 2
Unsteady Bridges Friction Slope Method= 1
Parabolic Critical Depth
Global Vel Dist=  1 , 1 , 1
Global Log Level= 0
CheckData=True
Encroach Param= -1, 0, 0, 0
BEGIN DESCRIPTION:
Multiple Run
END DESCRIPTION:

--- Stream0228_DS.f01 (steady flow) ---

Flow Title=Multiple
Number of Profiles=7
Profile Names=10-year,25-year,50-year,1pct_min,100-year,1pct_plu,500-year
River Rch & RM= Stream0228_DS,Reach-1,1903
     647    1090    1510    1018    2031    4052    3638
Boundary for River Rch & Prof#=Stream0228_DS,Reach-1,1
Up Type=0
Dn Type=3
Dn Slope=0.005
Boundary for River Rch & Prof#=Stream0228_DS,Reach-1,2
Up Type=0
Dn Type=3
Dn Slope=0.005
Boundary for River Rch & Prof#=Stream0228_DS,Reach-1,3
Up Type=0
Dn Type=3
Dn Slope=0.005
Boundary for River Rch & Prof#=Stream0228_DS,Reach-1,4
Up Type=0
Dn Type=3
Dn Slope=0.005
Boundary for River Rch & Prof#=Stream0228_DS,Reach-1,5
Up Type=0
Dn Type=3
Dn Slope=0.005
Boundary for River Rch & Prof#=Stream0228_DS,Reach-1,6
Up Type=0
Dn Type=3
Dn Slope=0.005
Boundary for River Rch & Prof#=Stream0228_DS,Reach-1,7
Up Type=0
Dn Type=3
Dn Slope=0.005

--- Stream0228_DS.g01 (geometry) ---

Geom Title=Existing Conditions

River Reach=Stream0228_DS,Reach-1
Reach XY= 30
      2007775.00     13929375.00      2007722.05     13929369.87
      2007688.08     13929338.67      2007675.95     13929314.70
      2007676.22     13929135.50      2007683.15     13929118.94
      2007721.30     13929073.40      2007725.81     13929019.97
      2007721.30     13928976.60      2007683.15     13928931.06
      2007676.23     13928914.49      2007672.93     13928780.86
      2007658.57     13928758.24      2007534.15     13928631.73
      2007536.39     13928615.13      2007571.39     13928573.37
      2007573.16     13928531.12      2007531.18     13928477.19
      2007516.84     13928418.95      2007430.54     13928327.42
      2007419.58     13928222.33      2007377.57     13928180.74
      2007315.35     13928164.19      2007231.04     13928083.18
      2007168.96     13928066.82      2007077.42     13927980.54
      2006980.94     13927972.69      2006927.00     13927931.04
      2006879.90     13927919.72      2006875.00     13927875.00

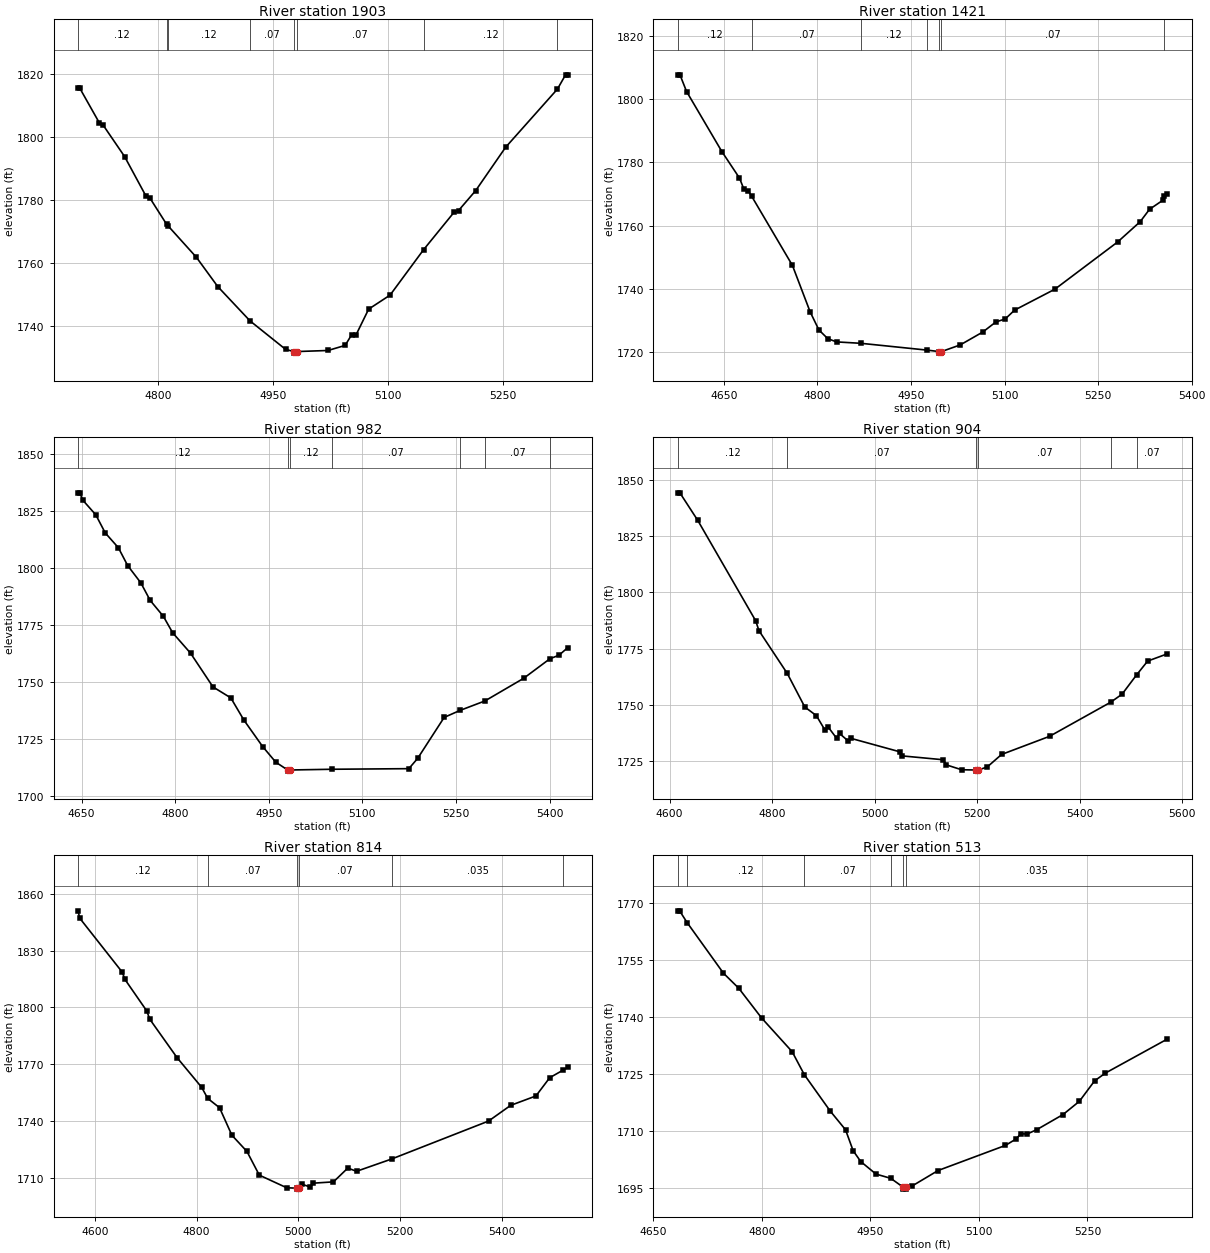
Type RM Length L Ch R = 1,1903,482,482,482
BEGIN DESCRIPTION:
Stream0228_DS 4.0
END DESCRIPTION:
XS GIS Cut Line= 3
      2007975.01     13929325.00      2007675.00     13929275.00
      2007374.96     13929425.02
#Sta/Elev= 30
  4695.4 1815.51  4697.9 1815.51  4723.3 1804.56  4728.4 1803.80  4756.2 1793.90
  4784.1 1781.35  4789.2 1780.75  4811.2 1772.34  4812.8 1771.93  4850.0 1761.90
  4877.9 1752.60  4920.1 1741.69  4966.6 1732.64  4977.3 1731.96  4977.5 1731.46
  4981.3 1731.96  5021.9 1732.30  5044.3 1733.91  5052.7 1737.26  5058.2 1737.08
  5075.0 1745.43  5103.0 1749.89  5146.7 1764.29  5186.8 1776.27  5192.4 1776.74
  5214.8 1783.07  5253.9 1796.83  5321.6 1815.32  5332.2 1819.84  5335.0 1819.84
#Mann=8,-1,0
  4695.4    0.12       0  4811.2    0.07       0  4812.8    0.12       0
  4920.1    0.07       0  4977.3    0.05       0  4981.3    0.07       0
  5146.7    0.12       0  5321.6    0.07       0
Bank Sta=4977.3,4981.3
Exp/Cntr=0.3,0.1

Type RM Length L Ch R = 1,1421,439,439,439
BEGIN DESCRIPTION:
Stream0228_DS 3.0
END DESCRIPTION:
XS GIS Cut Line= 3
      2007975.02     13928524.98      2007675.00     13928825.00
      2007374.96     13929025.03
#Sta/Elev= 30
  4576.2 1807.80  4579.8 1807.80  4590.4 1802.50  4646.9 1783.48  4675.2 1775.06
  4682.3 1771.52  4689.4 1770.94  4694.7 1769.30  4760.1 1747.34  4788.4 1732.65
  4802.5 1726.89  4816.7 1724.13  4830.8 1723.10  4870.1 1722.65  4976.1 1720.49
  4995.0 1720.04  4995.2 1719.54  4999.0 1720.04  5029.0 1722.14  5065.1 1726.22
  5086.1 1729.41  5101.2 1730.39  5116.2 1733.18  5180.8 1739.82  5281.4 1754.80
  5317.5 1761.23  5332.5 1765.16  5353.5 1767.98  5356.4 1769.37  5361.1 1770.13
#Mann=7,-1,0
  4576.2    0.12       0  4694.7    0.07       0  4870.1    0.12       0
  4976.1    0.07       0  4995.0    0.05       0  4999.0    0.07       0
  5356.4   0.035       0
Bank Sta=4995,4999
Exp/Cntr=0.3,0.1

Type RM Length L Ch R = 1,982,78,78,78
BEGIN DESCRIPTION:
Stream0228_DS 2.0
END DESCRIPTION:
XS GIS Cut Line= 3
      2007824.99     13928275.01      2007525.00     13928475.00
      2007225.00     13928775.00
#Sta/Elev= 30
  4644.2 1832.94  4647.2 1832.94  4651.7 1829.77  4672.7 1823.29  4687.8 1815.38
  4708.8 1808.90  4723.8 1801.04  4744.8 1793.51  4759.9 1785.76  4780.9 1778.84
  4795.9 1771.59  4824.5 1762.67  4860.5 1747.86  4889.1 1743.05  4910.1 1733.30
  4940.1 1721.72  4961.2 1714.85  4980.2 1711.45  4980.5 1710.95  4984.2 1711.45
  5051.5 1711.77  5174.4 1712.03  5188.6 1716.56  5231.0 1734.50  5256.5 1737.57
  5296.3 1741.71  5358.3 1751.61  5400.6 1760.23  5414.9 1761.73  5429.0 1765.06
#Mann=7,-1,0
  4644.2    0.12       0  4980.2    0.05       0  4984.2    0.12       0
  5051.5    0.07       0  5256.5   0.035       0  5296.3    0.07       0
  5400.6   0.035       0
Bank Sta=4980.2,4984.2
Exp/Cntr=0.3,0.1

Type RM Length L Ch R = 1,904,90,90,90
BEGIN DESCRIPTION:
Stream0228_DS 1.2
END DESCRIPTION:
XS GIS Cut Line= 4
      2007847.50     13928234.09      2007501.94     13928401.55
      2007280.53     13928484.50      2007014.27     13928687.08
#Sta/Elev= 30
  4616.0 1844.41  4620.2 1844.41  4655.1 1832.12  4768.0 1787.41  4774.4 1783.00
  4829.7 1763.90  4863.8 1748.97  4886.4 1745.12  4903.4 1738.58  4909.0 1740.17
  4926.0 1734.99  4931.6 1737.16  4948.6 1733.79  4954.1 1734.98  5048.7 1729.03
  5054.0 1727.17  5134.2 1725.45  5139.5 1723.20  5169.8 1721.00  5198.0 1720.89
  5198.3 1720.39  5202.0 1720.89  5219.6 1722.24  5247.6 1727.82  5341.1 1735.89
  5460.5 1751.11  5482.6 1754.68  5511.1 1763.33  5532.5 1769.43  5571.0 1772.67
#Mann=6,-1,0
  4616.0    0.12       0  4829.7    0.07       0  5198.0    0.05       0
  5202.0    0.07       0  5460.5   0.035       0  5511.1    0.07       0
Bank Sta=5198,5202
Exp/Cntr=0.3,0.1

Type RM Length L Ch R = 1,814,301,301,301
BEGIN DESCRIPTION:
Stream0228_DS 1.1
END DESCRIPTION:
XS GIS Cut Line= 4
      2007840.72     13928177.84      2007438.43     13928338.29
      2007247.40     13928429.87      2006997.00     13928625.49
#Sta/Elev= 30
  4566.9 1851.08  4570.2 1847.21  4653.7 1818.70  4659.2 1814.79  4702.2 1798.09
  4707.7 1793.87  4761.6 1773.45  4809.9 1757.78  4821.9 1751.89  4845.1 1746.98
  4869.4 1732.43  4899.0 1723.85  4923.3 1711.33  4977.2 1704.65  4997.2 1704.43
  4997.4 1703.93  5001.2 1704.43  5006.7 1706.58  5023.8 1704.99  5029.3 1707.08
  5069.1 1707.77  5097.3 1715.07  5114.4 1713.35  5183.4 1719.85  5374.0 1739.92
  5417.4 1748.21  5467.1 1753.19  5494.3 1762.85  5521.2 1766.96  5529.6 1768.30
#Mann=6,-1,0
  4566.9    0.12       0  4821.9    0.07       0  4997.2    0.05       0
  5001.2    0.07       0  5183.4   0.035       0  5521.2    0.07       0
Bank Sta=4997.2,5001.2
Exp/Cntr=0.3,0.1

Type RM Length L Ch R = 1,513,395,395,395
BEGIN DESCRIPTION:
Stream0228_DS 1.0
END DESCRIPTION:
XS GIS Cut Line= 3
      2007574.97     13928025.01      2007275.00     13928125.00
      2007075.03     13928424.96
#Sta/Elev= 30
  4683.8 1767.91  4686.4 1767.91  4696.7 1764.84  4747.0 1751.52  4768.1 1747.58
  4799.7 1739.76  4841.9 1730.91  4858.9 1724.81  4894.6 1715.29  4915.7 1710.39
  4926.2 1704.89  4936.7 1702.04  4957.8 1698.74  4978.2 1697.63  4995.4 1695.29
  4995.6 1694.79  4999.1 1694.79  4999.4 1695.29  5007.5 1695.59  5043.6 1699.68
  5136.7 1706.28  5151.7 1708.00  5157.7 1709.33  5166.8 1709.27  5180.3 1710.45
  5216.3 1714.39  5238.9 1717.87  5259.9 1723.24  5274.9 1725.29  5360.5 1734.23
#Mann=6,-1,0
  4683.8    0.07       0  4696.7    0.12       0  4858.9    0.07       0
  4978.2   0.035       0  4995.4   0.035       0  4999.4   0.035       0
Bank Sta=4995.4,4999.4
Exp/Cntr=0.3,0.1

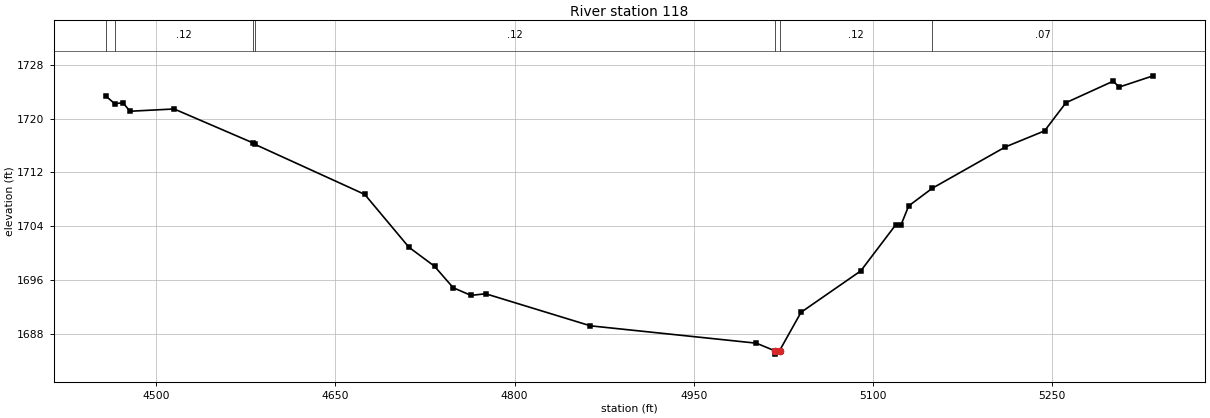
Type RM Length L Ch R = 1,118,0,0,0
BEGIN DESCRIPTION:
Stream0228_DS 0.0
END DESCRIPTION:
XS GIS Cut Line= 6
      2007337.31     13927609.72      2007030.72     13927792.80
      2006960.14     13927857.48      2006944.76     13927945.32
      2006941.72     13928068.79      2006974.57     13928277.01
#Sta/Elev= 30
  4458.0 1723.33  4465.4 1722.20  4472.3 1722.35  4478.1 1721.08  4515.1 1721.42
  4580.7 1716.40  4582.4 1716.18  4674.6 1708.71  4711.6 1700.85  4733.0 1698.02
  4748.6 1694.83  4763.5 1693.69  4775.8 1693.93  4863.5 1689.16  5002.3 1686.58
  5017.7 1685.45  5017.9 1684.95  5021.7 1685.45  5039.7 1691.17  5089.7 1697.33
  5119.1 1704.22  5123.5 1704.22  5129.8 1707.00  5149.6 1709.63  5210.8 1715.78
  5243.5 1718.16  5261.4 1722.35  5300.9 1725.55  5306.0 1724.68  5334.3 1726.35
#Mann=7,-1,0
  4458.0   0.035       0  4465.4    0.12       0  4580.7   0.035       0
  4582.4    0.12       0  5017.7    0.05       0  5021.7    0.12       0
  5149.6    0.07       0
Bank Sta=5017.7,5021.7
Exp/Cntr=0.3,0.1

Chan Stop Cuts=-1