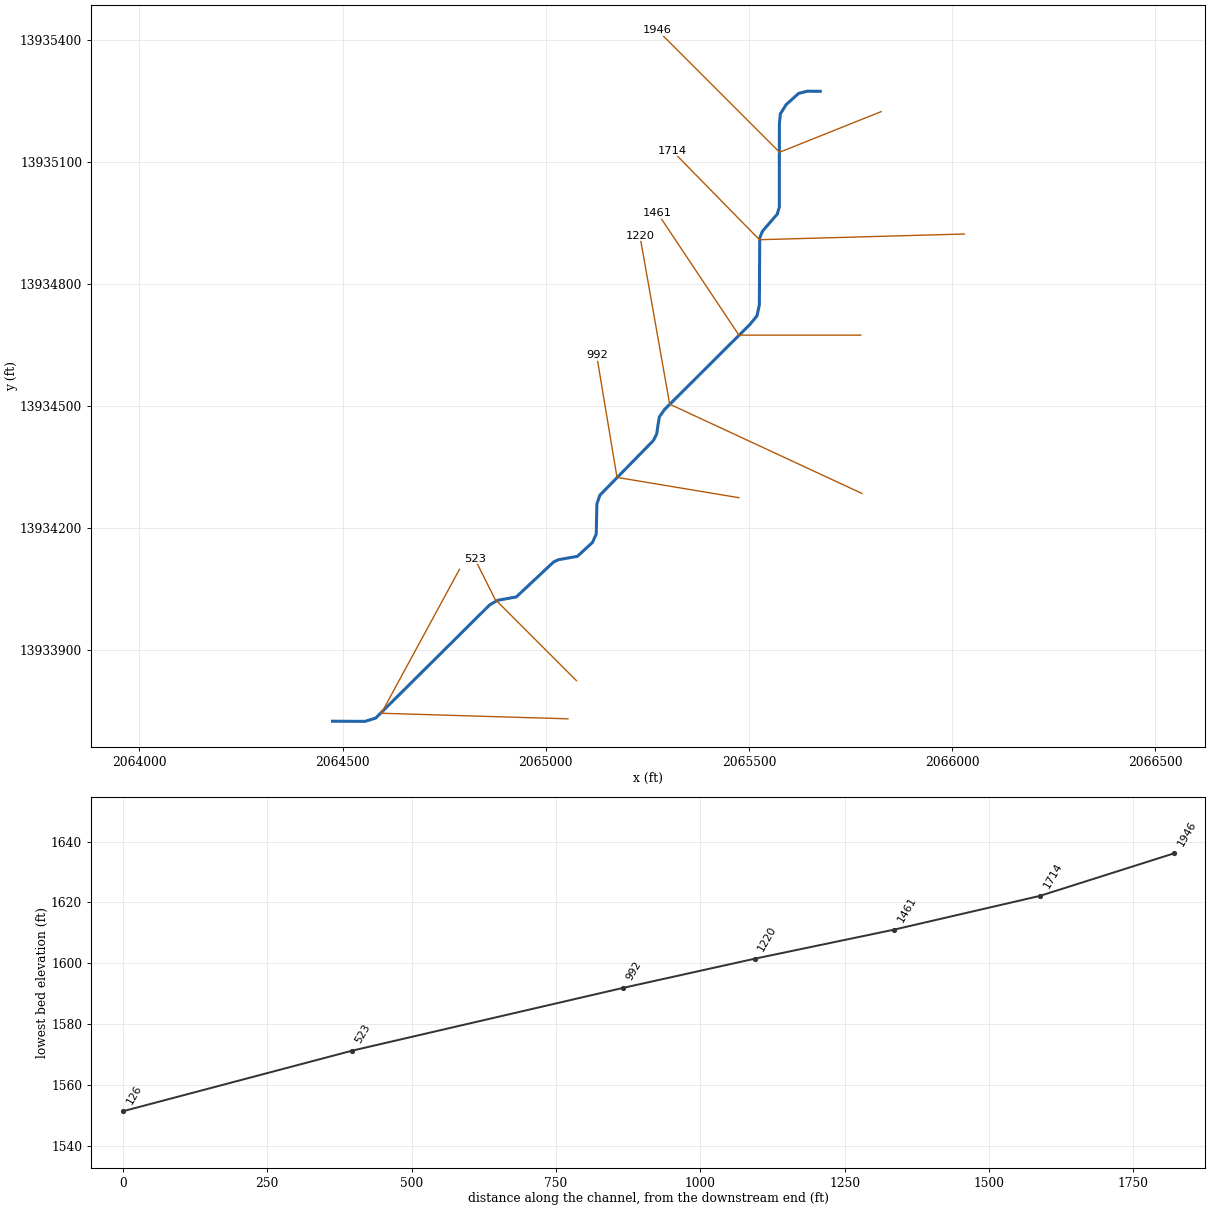
--- Stream0230_DS.prj (project) ---

Proj Title=Stream0230_DS Base Level Engineering
Current Plan=p01
Default Exp/Contr=0.3,0.1
English Units
Geom File=g01
Flow File=f01
Plan File=p01
BEGIN DESCRIPTION:
Stream0230_DS
END DESCRIPTION:

--- Stream0230_DS.p01 (plan) ---

Plan Title=Multiple Run
Short Identifier=Multiple
Geom File=g01
Flow File=f01
Subcritical Flow
K Sum by GR= 0
Std Step Tol= 0.01
Critical Tol= 0.01
Num of Std Step Trials= 20
Max Error Tol= 0.3
Flow Tol Ratio= 0.001
Split Flow NTrial= 30
Split Flow Tol= 0.02
Split Flow Ratio= 0.02
Log Output Level= 0
Friction Slope Method= 1
Unsteady Friction Slope Method= 2
Unsteady Bridges Friction Slope Method= 1
Parabolic Critical Depth
Global Vel Dist=  1 , 1 , 1
Global Log Level= 0
CheckData=True
Encroach Param= -1, 0, 0, 0
BEGIN DESCRIPTION:
Multiple Run
END DESCRIPTION:

--- Stream0230_DS.f01 (steady flow) ---

Flow Title=Multiple
Number of Profiles=7
Profile Names=10-year,25-year,50-year,1pct_min,100-year,1pct_plu,500-year
River Rch & RM= Stream0230_DS,Reach-1,1946
     307     490     656     429     855    1707    1436
Boundary for River Rch & Prof#=Stream0230_DS,Reach-1,1
Up Type=0
Dn Type=3
Dn Slope=0.005
Boundary for River Rch & Prof#=Stream0230_DS,Reach-1,2
Up Type=0
Dn Type=3
Dn Slope=0.005
Boundary for River Rch & Prof#=Stream0230_DS,Reach-1,3
Up Type=0
Dn Type=3
Dn Slope=0.005
Boundary for River Rch & Prof#=Stream0230_DS,Reach-1,4
Up Type=0
Dn Type=3
Dn Slope=0.005
Boundary for River Rch & Prof#=Stream0230_DS,Reach-1,5
Up Type=0
Dn Type=3
Dn Slope=0.005
Boundary for River Rch & Prof#=Stream0230_DS,Reach-1,6
Up Type=0
Dn Type=3
Dn Slope=0.005
Boundary for River Rch & Prof#=Stream0230_DS,Reach-1,7
Up Type=0
Dn Type=3
Dn Slope=0.005

--- Stream0230_DS.g01 (geometry) ---

Geom Title=Existing Conditions

River Reach=Stream0230_DS,Reach-1
Reach XY= 30
      2065675.00     13935275.00      2065642.92     13935275.16
      2065622.05     13935269.87      2065591.12     13935242.14
      2065576.93     13935219.31      2065574.55     13935195.23
      2065574.48     13934990.22      2065569.25     13934972.67
      2065533.14     13934931.06      2065526.22     13934914.49
      2065525.29     13934749.88      2065519.54     13934722.55
      2065502.14     13934701.47      2065291.65     13934491.67
      2065278.98     13934473.35      2065272.46     13934431.05
      2065264.22     13934415.32      2065132.86     13934281.17
      2065125.53     13934259.78      2065123.90     13934185.33
      2065114.61     13934164.90      2065077.57     13934130.74
      2065031.09     13934122.44      2065018.98     13934116.81
      2064927.28     13934030.87      2064881.05     13934022.47
      2064861.79     13934011.37      2064581.22     13933732.74
      2064555.14     13933724.67      2064475.00     13933725.00

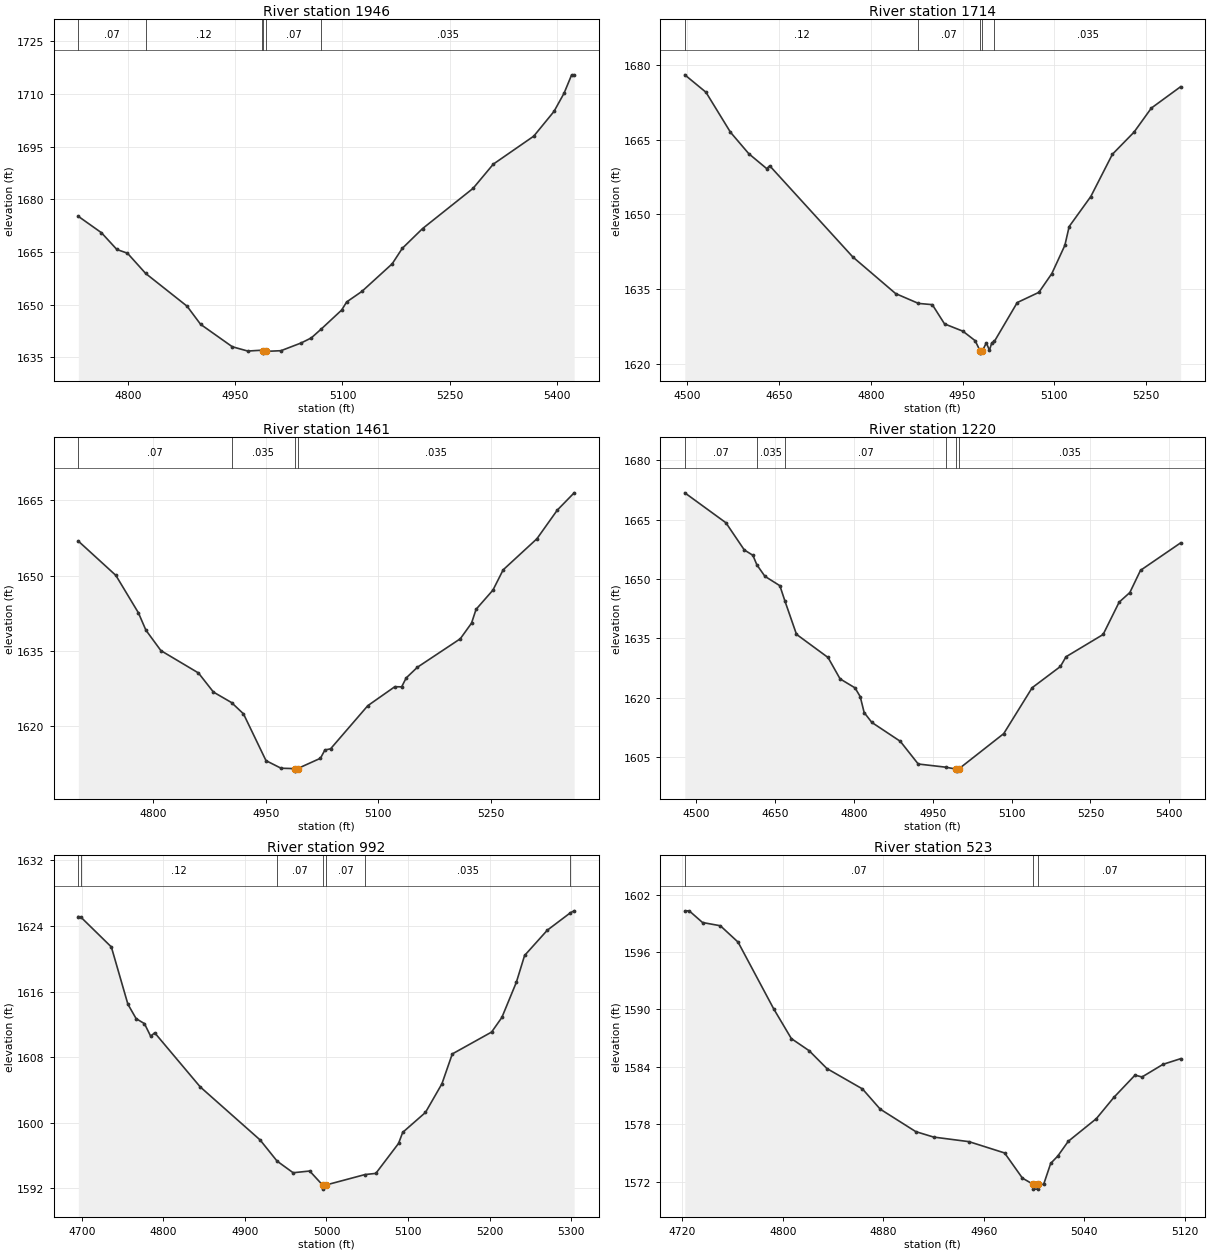
Type RM Length L Ch R = 1,1946,232,232,232
BEGIN DESCRIPTION:
Stream0230_DS 4.0
END DESCRIPTION:
XS GIS Cut Line= 3
      2065825.01     13935225.01      2065575.00     13935125.00
      2065275.03     13935424.97
#Sta/Elev= 30
  4730.6 1675.12  4762.9 1670.46  4784.5 1665.68  4799.3 1664.62  4824.8 1658.85
  4882.7 1649.52  4901.6 1644.36  4946.0 1637.96  4967.6 1636.74  4986.8 1636.98
  4988.4 1636.65  4988.7 1636.15  4992.4 1636.65  5014.0 1636.84  5042.3 1639.05
  5056.4 1640.48  5070.5 1643.04  5098.9 1648.42  5105.9 1650.73  5127.2 1653.73
  5169.6 1661.60  5183.7 1666.00  5212.0 1671.62  5282.7 1683.09  5311.0 1689.99
  5367.6 1697.97  5395.9 1705.01  5410.0 1710.21  5420.6 1715.44  5424.1 1715.44
#Mann=6,-1,0
  4730.6    0.07       0  4824.8    0.12       0  4986.8    0.07       0
  4988.4    0.05       0  4992.4    0.07       0  5070.5   0.035       0
Bank Sta=4988.4,4992.4
Exp/Cntr=0.3,0.1

Type RM Length L Ch R = 1,1714,253,253,253
BEGIN DESCRIPTION:
Stream0230_DS 3.5
END DESCRIPTION:
XS GIS Cut Line= 3
      2066029.63     13934923.85      2065525.52     13934909.78
      2065310.89     13935128.72
#Sta/Elev= 30
  4495.7 1677.97  4530.3 1674.48  4570.4 1666.46  4600.4 1662.15  4629.6 1659.17
  4634.6 1659.73  4770.4 1641.46  4840.5 1634.11  4877.8 1632.14  4900.5 1631.89
  4920.5 1628.03  4950.5 1626.57  4970.5 1624.67  4978.5 1622.67  4978.8 1622.17
  4982.5 1622.67  4988.9 1624.24  4993.9 1622.74  4997.8 1624.25  5002.0 1624.52
  5039.4 1632.31  5074.8 1634.36  5096.0 1638.13  5117.3 1643.79  5124.3 1647.55
  5159.7 1653.57  5195.0 1662.04  5230.4 1666.48  5258.7 1671.30  5306.6 1675.59
#Mann=5,-1,0
  4495.7    0.12       0  4877.8    0.07       0  4978.5    0.05       0
  4982.5    0.07       0  5002.0   0.035       0
Bank Sta=4978.5,4982.5
Exp/Cntr=0.3,0.1

Type RM Length L Ch R = 1,1461,241,241,241
BEGIN DESCRIPTION:
Stream0230_DS 3.0
END DESCRIPTION:
XS GIS Cut Line= 3
      2065774.96     13934675.00      2065475.00     13934675.00
      2065275.01     13934974.99
#Sta/Elev= 30
  4700.4 1656.87  4750.4 1650.04  4780.4 1642.59  4790.4 1639.13  4810.4 1635.05
  4860.4 1630.60  4880.4 1626.79  4904.5 1624.70  4920.4 1622.45  4950.4 1613.13
  4970.4 1611.62  4988.4 1611.54  4988.6 1611.04  4992.4 1611.54  5022.9 1613.60
  5028.9 1615.26  5036.4 1615.48  5086.0 1624.08  5122.0 1627.86  5131.1 1627.83
  5137.1 1629.60  5152.1 1631.74  5209.2 1637.41  5224.2 1640.53  5230.2 1643.27
  5252.7 1647.11  5266.3 1651.14  5311.3 1657.34  5338.4 1663.04  5360.9 1666.49
#Mann=4,-1,0
  4700.4    0.07       0  4904.5   0.035       0  4988.4   0.035       0
  4992.4   0.035       0
Bank Sta=4988.4,4992.4
Exp/Cntr=0.3,0.1

Type RM Length L Ch R = 1,1220,228,228,228
BEGIN DESCRIPTION:
Stream0230_DS 2.5
END DESCRIPTION:
XS GIS Cut Line= 3
      2065777.60     13934285.51      2065304.62     13934505.16
      2065231.23     13934920.12
#Sta/Elev= 30
  4478.5 1671.77  4556.7 1664.21  4591.6 1657.35  4608.0 1655.99  4615.6 1653.57
  4630.9 1650.68  4659.3 1648.31  4669.2 1644.33  4690.9 1636.03  4750.9 1630.18
  4773.8 1624.78  4802.2 1622.51  4812.1 1620.30  4819.6 1616.27  4834.2 1613.78
  4888.3 1609.01  4922.4 1603.28  4974.5 1602.48  4995.0 1601.98  4995.3 1601.48
  4999.0 1601.98  5085.0 1610.95  5139.1 1622.55  5192.8 1627.91  5203.4 1630.36
  5274.0 1635.99  5304.5 1644.16  5324.8 1646.58  5345.1 1652.19  5421.4 1659.13
#Mann=6,-1,0
  4478.5    0.07       0  4615.6   0.035       0  4669.2    0.07       0
  4974.5   0.035       0  4995.0   0.035       0  4999.0   0.035       0
Bank Sta=4995,4999
Exp/Cntr=0.3,0.1

Type RM Length L Ch R = 1,992,469,469,469
BEGIN DESCRIPTION:
Stream0230_DS 2.0
END DESCRIPTION:
XS GIS Cut Line= 3
      2065474.96     13934275.01      2065175.00     13934325.00
      2065125.01     13934624.96
#Sta/Elev= 30
  4695.6 1625.15  4698.4 1625.11  4736.1 1621.44  4756.4 1614.45  4766.5 1612.69
  4776.7 1612.08  4784.3 1610.55  4789.3 1610.96  4845.1 1604.36  4918.6 1597.88
  4939.4 1595.30  4959.1 1593.88  4979.4 1594.09  4995.2 1592.38  4995.4 1591.88
  4999.2 1592.38  5047.3 1593.66  5060.5 1593.80  5088.4 1597.46  5093.5 1598.81
  5121.4 1601.24  5141.6 1604.74  5154.3 1608.38  5202.5 1611.05  5215.1 1612.83
  5232.9 1617.13  5243.0 1620.40  5270.9 1623.49  5299.3 1625.62  5303.8 1625.85
#Mann=7,-1,0
  4695.6    0.07       0  4698.4    0.12       0  4939.4    0.07       0
  4995.2    0.05       0  4999.2    0.07       0  5047.3   0.035       0
  5299.3    0.07       0
Bank Sta=4995.2,4999.2
Exp/Cntr=0.3,0.1

Type RM Length L Ch R = 1,523,397,397,397
BEGIN DESCRIPTION:
Stream0230_DS 1.0
END DESCRIPTION:
XS GIS Cut Line= 3
      2065074.98     13933825.02      2064875.00     13934025.00
      2064825.01     13934124.99
#Sta/Elev= 30
  4722.0 1600.30  4725.5 1600.30  4736.1 1599.08  4750.3 1598.74  4764.4 1597.03
  4792.7 1590.07  4806.8 1586.95  4821.0 1585.68  4835.1 1583.82  4863.4 1581.69
  4877.5 1579.58  4905.8 1577.23  4920.0 1576.66  4948.2 1576.18  4976.5 1575.00
  4990.7 1572.37  4999.3 1571.72  4999.5 1571.22  5003.0 1571.22  5003.3 1571.72
  5007.6 1571.72  5013.2 1573.91  5018.8 1574.67  5027.2 1576.22  5049.5 1578.58
  5063.5 1580.81  5080.3 1583.13  5085.9 1582.94  5102.6 1584.26  5116.6 1584.85
#Mann=3,-1,0
  4722.0    0.07       0  4999.3    0.05       0  5003.3    0.07       0
Bank Sta=4999.3,5003.3
Exp/Cntr=0.3,0.1

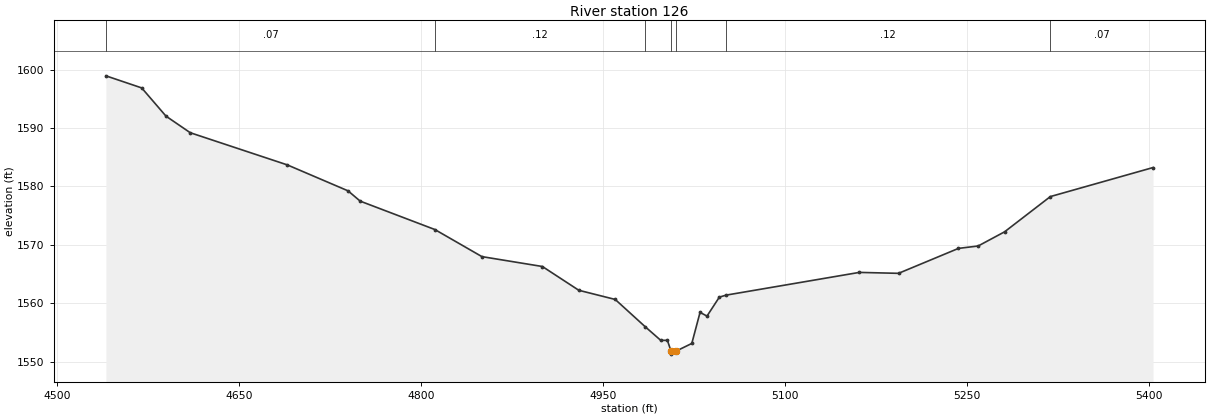
Type RM Length L Ch R = 1,126,0,0,0
BEGIN DESCRIPTION:
Stream0230_DS 0.0
END DESCRIPTION:
XS GIS Cut Line= 3
      2065054.45     13933730.89      2064595.16     13933744.62
      2064787.49     13934098.99
#Sta/Elev= 30
  4540.5 1598.92  4570.0 1596.85  4590.0 1592.02  4610.0 1589.18  4690.0 1583.67
  4740.0 1579.23  4750.0 1577.47  4811.5 1572.61  4850.3 1567.97  4900.1 1566.28
  4930.1 1562.21  4960.1 1560.64  4984.8 1555.97  4997.6 1553.64  5003.1 1553.64
  5006.1 1551.78  5006.4 1551.28  5010.1 1551.78  5023.2 1553.11  5030.0 1558.43
  5035.7 1557.79  5045.9 1561.04  5051.5 1561.38  5161.2 1565.27  5193.5 1565.11
  5242.9 1569.38  5259.1 1569.79  5280.9 1572.22  5318.6 1578.25  5403.2 1583.22
#Mann=7,-1,0
  4540.5    0.07       0  4811.5    0.12       0  4984.8    0.07       0
  5006.1    0.05       0  5010.1    0.07       0  5051.5    0.12       0
  5318.6    0.07       0
Bank Sta=5006.1,5010.1
Exp/Cntr=0.3,0.1

Chan Stop Cuts=-1