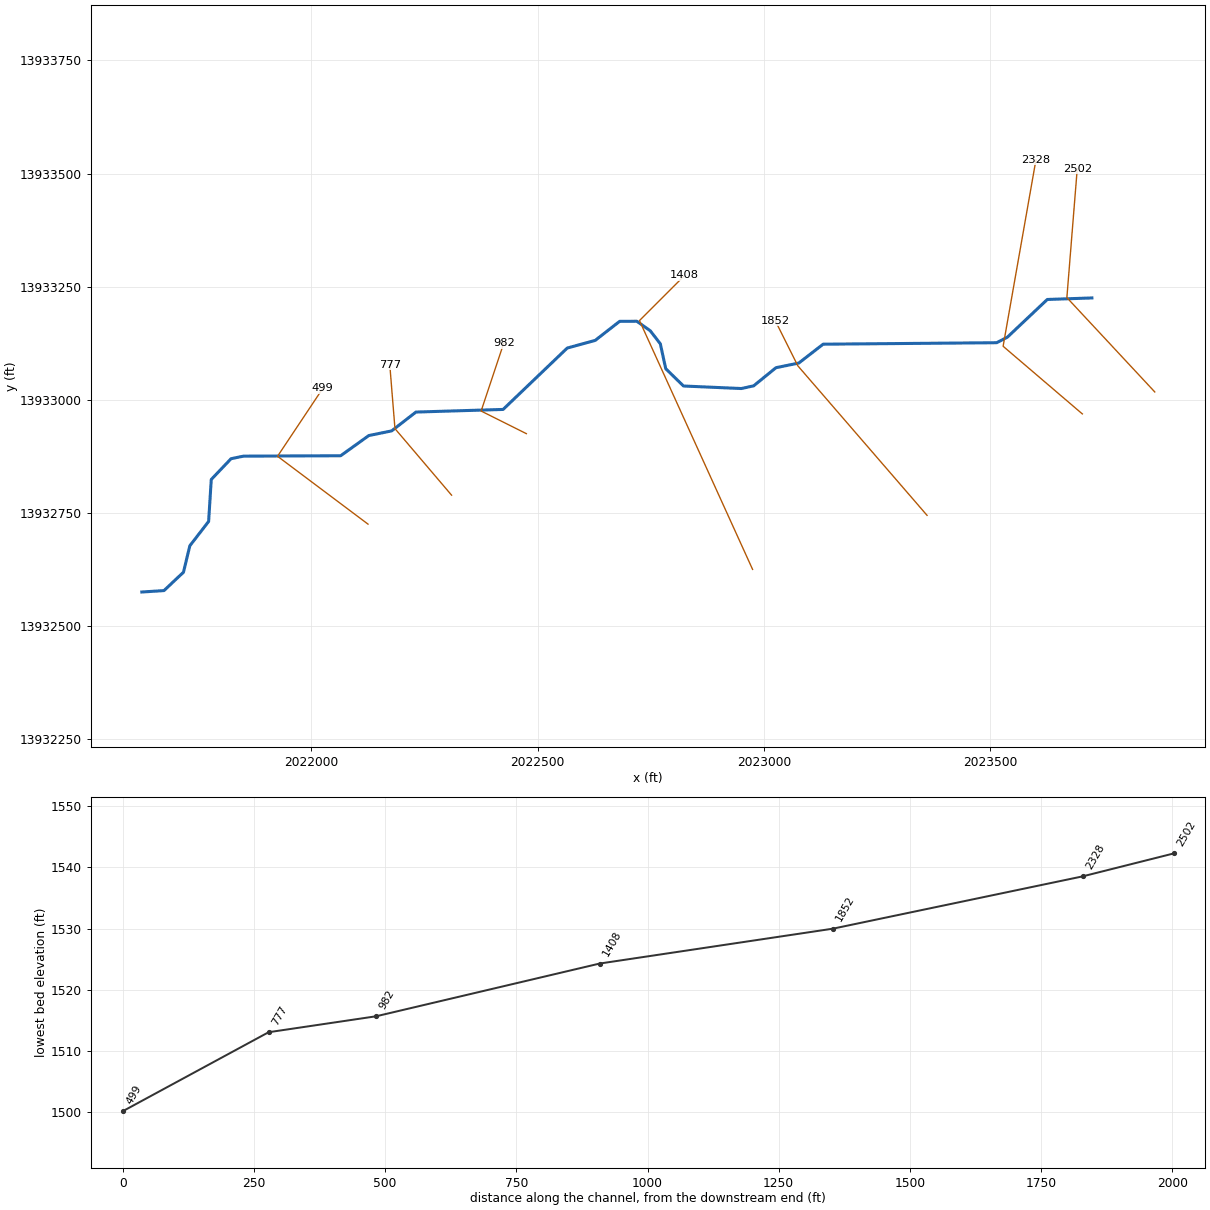
--- Stream0231_DS.prj (project) ---

Proj Title=Stream0231_DS Base Level Engineering
Current Plan=p01
Default Exp/Contr=0.3,0.1
English Units
Geom File=g01
Flow File=f01
Plan File=p01
BEGIN DESCRIPTION:
Stream0231_DS
END DESCRIPTION:

--- Stream0231_DS.p01 (plan) ---

Plan Title=Multiple Run
Short Identifier=Multiple
Geom File=g01
Flow File=f01
Subcritical Flow
K Sum by GR= 0
Std Step Tol= 0.01
Critical Tol= 0.01
Num of Std Step Trials= 20
Max Error Tol= 0.3
Flow Tol Ratio= 0.001
Split Flow NTrial= 30
Split Flow Tol= 0.02
Split Flow Ratio= 0.02
Log Output Level= 0
Friction Slope Method= 1
Unsteady Friction Slope Method= 2
Unsteady Bridges Friction Slope Method= 1
Parabolic Critical Depth
Global Vel Dist=  1 , 1 , 1
Global Log Level= 0
CheckData=True
Encroach Param= -1, 0, 0, 0
BEGIN DESCRIPTION:
Multiple Run
END DESCRIPTION:

--- Stream0231_DS.f01 (steady flow) ---

Flow Title=Multiple
Number of Profiles=7
Profile Names=10-year,25-year,50-year,1pct_min,100-year,1pct_plu,500-year
River Rch & RM= Stream0231_DS,Reach-1,2502
     570     948    1303     872    1739    3470    3068
Boundary for River Rch & Prof#=Stream0231_DS,Reach-1,1
Up Type=0
Dn Type=3
Dn Slope=0.005
Boundary for River Rch & Prof#=Stream0231_DS,Reach-1,2
Up Type=0
Dn Type=3
Dn Slope=0.005
Boundary for River Rch & Prof#=Stream0231_DS,Reach-1,3
Up Type=0
Dn Type=3
Dn Slope=0.005
Boundary for River Rch & Prof#=Stream0231_DS,Reach-1,4
Up Type=0
Dn Type=3
Dn Slope=0.005
Boundary for River Rch & Prof#=Stream0231_DS,Reach-1,5
Up Type=0
Dn Type=3
Dn Slope=0.005
Boundary for River Rch & Prof#=Stream0231_DS,Reach-1,6
Up Type=0
Dn Type=3
Dn Slope=0.005
Boundary for River Rch & Prof#=Stream0231_DS,Reach-1,7
Up Type=0
Dn Type=3
Dn Slope=0.005

--- Stream0231_DS.g01 (geometry) ---

Geom Title=Existing Conditions

River Reach=Stream0231_DS,Reach-1
Reach XY= 30
      2023725.00     13933225.00      2023626.41     13933221.61
      2023538.31     13933138.40      2023514.56     13933126.05
      2023130.93     13933122.76      2023077.18     13933081.12
      2023026.74     13933070.81      2022977.35     13933030.70
      2022950.08     13933024.76      2022822.30     13933030.35
      2022783.03     13933068.64      2022771.10     13933123.60
      2022748.84     13933152.44      2022719.15     13933173.46
      2022681.16     13933173.26      2022627.19     13933131.18
      2022565.32     13933114.24      2022423.54     13932978.54
      2022230.93     13932972.76      2022177.18     13932931.12
      2022126.74     13932920.81      2022064.50     13932876.20
      2021849.78     13932875.33      2021822.26     13932869.66
      2021778.51     13932823.75      2021772.67     13932730.97
      2021731.13     13932677.16      2021717.05     13932618.69
      2021673.97     13932578.14      2021625.00     13932575.00

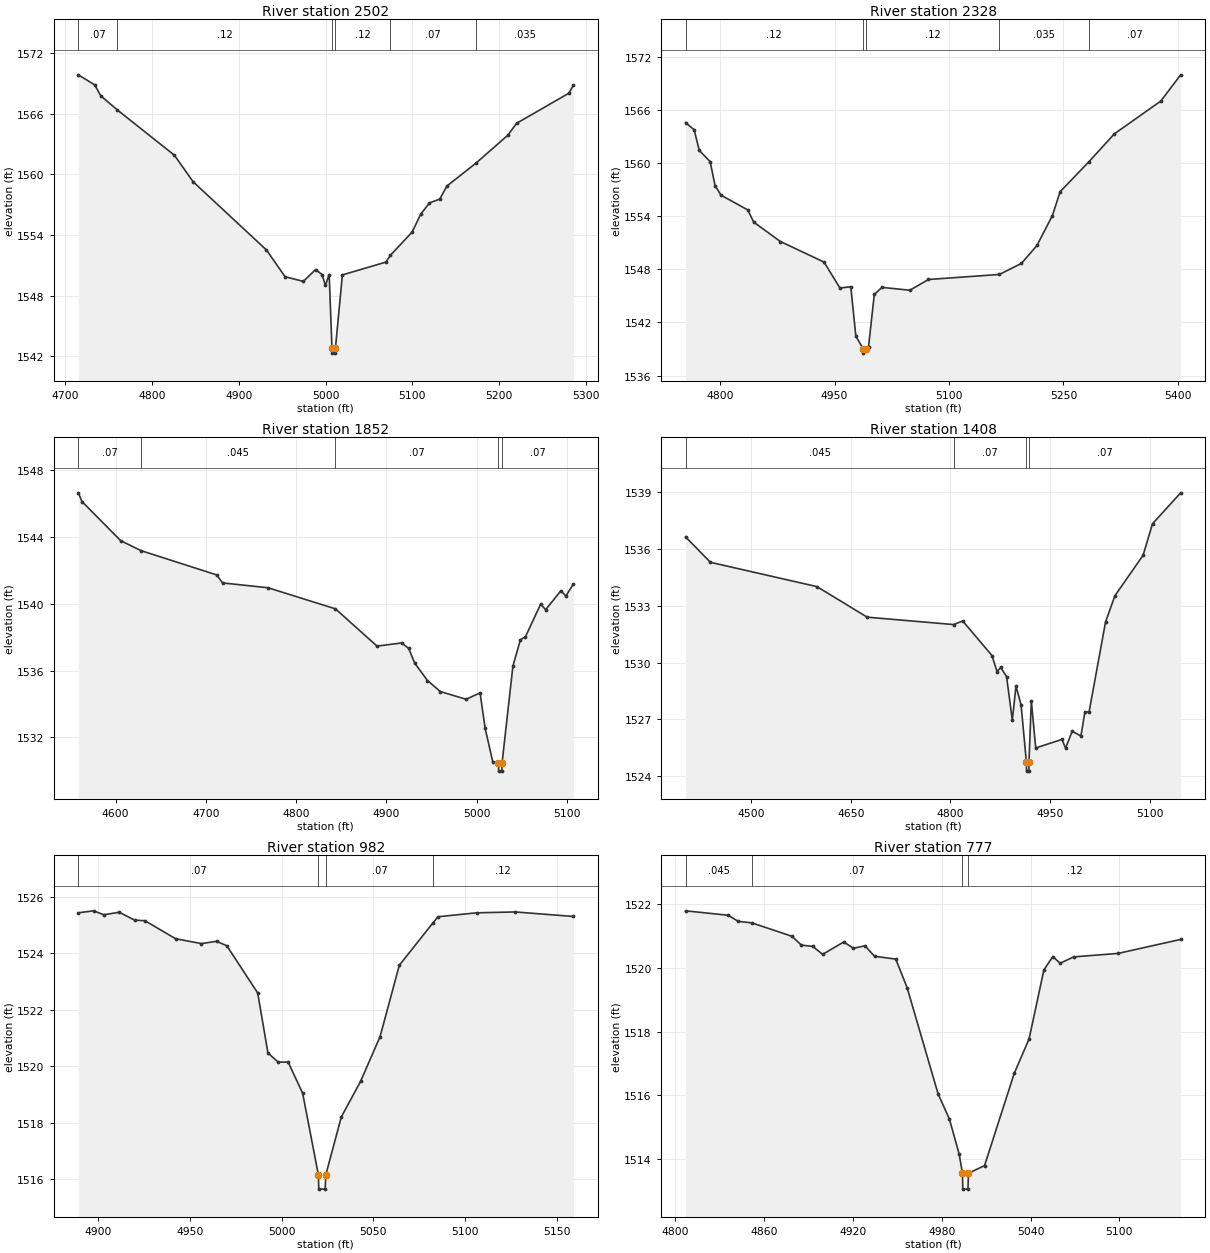
Type RM Length L Ch R = 1,2502,174,174,174
BEGIN DESCRIPTION:
Stream0231_DS 6.0
END DESCRIPTION:
XS GIS Cut Line= 3
      2023863.97     13933017.24      2023669.69     13933225.76
      2023692.60     13933510.33
#Sta/Elev= 30
  4715.0 1569.84  4734.0 1568.84  4740.8 1567.77  4759.8 1566.38  4825.8 1561.88
  4847.3 1559.26  4931.8 1552.51  4953.3 1549.86  4974.3 1549.40  4988.5 1550.57
  4995.8 1550.08  4999.8 1549.00  5004.1 1550.08  5007.3 1542.80  5007.5 1542.30
  5011.0 1542.30  5011.3 1542.80  5019.3 1550.04  5069.5 1551.31  5074.6 1551.98
  5099.6 1554.27  5109.6 1556.05  5119.6 1557.16  5131.6 1557.55  5139.7 1558.83
  5173.5 1561.12  5209.9 1563.86  5220.0 1565.04  5280.1 1568.01  5285.5 1568.81
#Mann=6,-1,0
  4715.0    0.07       0  4759.8    0.12       0  5007.3    0.05       0
  5011.3    0.12       0  5074.6    0.07       0  5173.5   0.035       0
Bank Sta=5007.3,5011.3
Exp/Cntr=0.3,0.1

Type RM Length L Ch R = 1,2328,476,476,476
BEGIN DESCRIPTION:
Stream0231_DS 5.0
END DESCRIPTION:
XS GIS Cut Line= 3
      2023703.89     13932968.64      2023528.78     13933118.17
      2023601.41     13933530.56
#Sta/Elev= 30
  4754.7 1564.55  4766.0 1563.75  4772.6 1561.42  4786.9 1560.16  4793.4 1557.45
  4801.1 1556.37  4836.3 1554.70  4844.0 1553.33  4879.1 1551.13  4936.2 1548.82
  4957.0 1545.89  4971.3 1546.03  4977.9 1540.46  4987.4 1539.04  4987.7 1538.54
  4991.4 1539.04  4994.5 1539.21  5002.1 1545.17  5012.2 1545.96  5048.7 1545.64
  5073.1 1546.85  5166.1 1547.42  5195.0 1548.67  5215.3 1550.69  5235.6 1554.07
  5245.7 1556.76  5283.0 1560.10  5316.8 1563.29  5377.7 1566.99  5403.7 1569.95
#Mann=5,-1,0
  4754.7    0.12       0  4987.4    0.05       0  4991.4    0.12       0
  5166.1   0.035       0  5283.0    0.07       0
Bank Sta=4987.4,4991.4
Exp/Cntr=0.3,0.1

Type RM Length L Ch R = 1,1852,444,444,444
BEGIN DESCRIPTION:
Stream0231_DS 4.0
END DESCRIPTION:
XS GIS Cut Line= 3
      2023360.62     13932744.47      2023075.00     13933075.00
      2023025.02     13933174.97
#Sta/Elev= 30
  4558.6 1546.63  4562.7 1546.11  4605.5 1543.77  4628.2 1543.17  4711.9 1541.72
  4718.5 1541.24  4768.9 1540.95  4843.5 1539.69  4889.6 1537.46  4917.0 1537.65
  4924.7 1537.32  4931.3 1536.45  4945.5 1535.40  4959.8 1534.74  4988.3 1534.28
  5003.8 1534.66  5009.4 1532.55  5017.8 1530.55  5024.2 1530.48  5024.4 1529.98
  5027.9 1529.98  5028.2 1530.48  5040.2 1536.27  5048.5 1537.84  5054.1 1538.02
  5070.9 1539.97  5076.5 1539.64  5093.3 1540.77  5098.9 1540.46  5107.2 1541.18
#Mann=5,-1,0
  4558.6    0.07       0  4628.2   0.045       0  4843.5    0.07       0
  5024.2    0.05       0  5028.2    0.07       0
Bank Sta=5024.2,5028.2
Exp/Cntr=0.3,0.1

Type RM Length L Ch R = 1,1408,426,426,426
BEGIN DESCRIPTION:
Stream0231_DS 3.0
END DESCRIPTION:
XS GIS Cut Line= 3
      2022975.01     13932624.97      2022725.00     13933175.00
      2022825.00     13933275.00
#Sta/Elev= 30
  4401.1 1536.62  4438.5 1535.28  4598.9 1534.00  4674.6 1532.39  4804.8 1532.00
  4818.5 1532.19  4862.5 1530.37  4870.2 1529.52  4875.7 1529.74  4884.5 1529.26
  4893.2 1526.96  4898.7 1528.76  4906.4 1527.77  4914.3 1524.78  4914.6 1524.28
  4918.1 1524.28  4918.3 1524.78  4921.8 1527.99  4928.4 1525.50  4967.9 1525.95
  4973.4 1525.49  4983.3 1526.38  4996.5 1526.13  5002.5 1527.40  5008.8 1527.40
  5033.6 1532.14  5047.7 1533.52  5090.1 1535.65  5104.3 1537.31  5146.7 1538.94
#Mann=4,-1,0
  4401.1   0.045       0  4804.8    0.07       0  4914.3    0.05       0
  4918.3    0.07       0
Bank Sta=4914.3,4918.3
Exp/Cntr=0.3,0.1

Type RM Length L Ch R = 1,982,205,205,205
BEGIN DESCRIPTION:
Stream0231_DS 2.0
END DESCRIPTION:
XS GIS Cut Line= 3
      2022474.98     13932925.01      2022375.00     13932975.00
      2022425.00     13933125.01
#Sta/Elev= 28
  4889.2 1525.44  4897.6 1525.51  4903.1 1525.37  4911.5 1525.46  4919.9 1525.18
  4925.5 1525.16  4942.3 1524.52  4956.3 1524.35  4964.6 1524.43  4970.2 1524.27
  4987.0 1522.60  4992.6 1520.47  4998.2 1520.15  5003.6 1520.15  5011.5 1519.05
  5020.1 1516.15  5020.3 1515.65  5023.8 1515.65  5024.1 1516.15  5032.6 1518.21
  5043.1 1519.47  5053.7 1521.05  5064.2 1523.58  5082.5 1525.08  5085.3 1525.30
  5106.4 1525.44  5127.5 1525.47  5159.1 1525.31
#Mann=4,-1,0
  4889.2    0.07       0  5020.1    0.05       0  5024.1    0.07       0
  5082.5    0.12       0
Bank Sta=5020.1,5024.1
Exp/Cntr=0.3,0.1

Type RM Length L Ch R = 1,777,278,278,278
BEGIN DESCRIPTION:
Stream0231_DS 1.5
END DESCRIPTION:
XS GIS Cut Line= 3
      2022309.65     13932789.07      2022184.53     13932936.14
      2022173.10     13933077.08
#Sta/Elev= 30
  4806.9 1521.80  4835.8 1521.66  4842.4 1521.47  4851.8 1521.42  4878.7 1521.00
  4885.2 1520.72  4892.9 1520.68  4899.5 1520.43  4913.8 1520.82  4920.3 1520.62
  4928.1 1520.70  4934.6 1520.37  4948.9 1520.28  4956.6 1519.38  4977.5 1516.04
  4985.2 1515.24  4991.7 1514.15  4994.0 1513.54  4994.2 1513.04  4997.7 1513.04
  4998.0 1513.54  5008.9 1513.78  5029.0 1516.69  5039.0 1517.77  5049.0 1519.94
  5055.0 1520.36  5060.0 1520.15  5069.1 1520.35  5099.2 1520.46  5141.4 1520.90
#Mann=4,-1,0
  4806.9   0.045       0  4851.8    0.07       0  4994.0    0.05       0
  4998.0    0.12       0
Bank Sta=4994,4998
Exp/Cntr=0.3,0.1

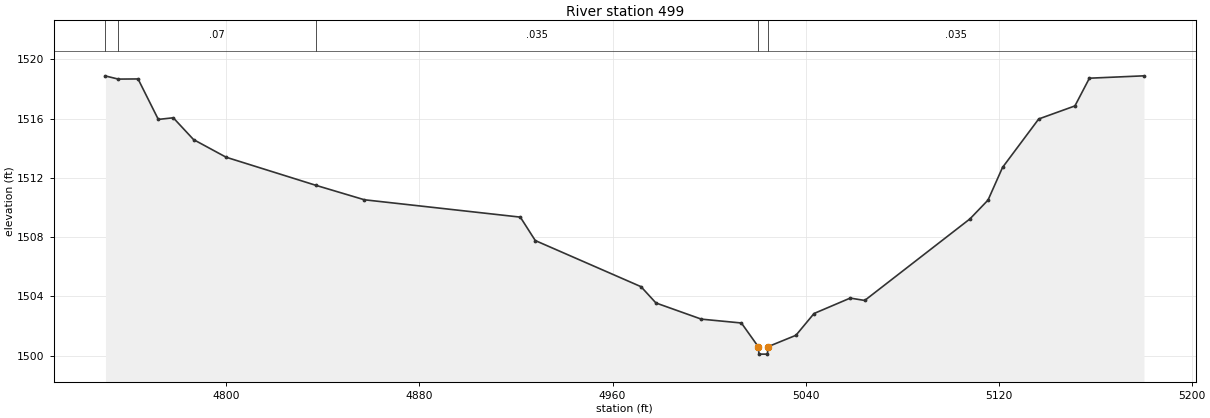
Type RM Length L Ch R = 1,499,0,0,0
BEGIN DESCRIPTION:
Stream0231_DS 1.0
END DESCRIPTION:
XS GIS Cut Line= 3
      2022125.00     13932725.00      2021925.00     13932875.00
      2022025.01     13933025.02
#Sta/Elev= 30
  4749.9 1518.87  4755.2 1518.66  4763.4 1518.67  4771.8 1515.94  4778.0 1516.05
  4786.4 1514.58  4799.9 1513.39  4837.2 1511.49  4857.2 1510.52  4921.8 1509.35
  4928.0 1507.77  4971.8 1504.66  4978.0 1503.56  4996.8 1502.47  5013.4 1502.21
  5020.4 1500.61  5020.7 1500.11  5024.2 1500.11  5024.4 1500.61  5036.0 1501.38
  5043.5 1502.85  5058.5 1503.89  5064.5 1503.73  5108.1 1509.23  5115.6 1510.50
  5121.6 1512.70  5136.6 1515.97  5151.6 1516.85  5157.6 1518.72  5180.2 1518.88
#Mann=5,-1,0
  4749.9   0.045       0  4755.2    0.07       0  4837.2   0.035       0
  5020.4   0.035       0  5024.4   0.035       0
Bank Sta=5020.4,5024.4
Exp/Cntr=0.3,0.1

Chan Stop Cuts=-1