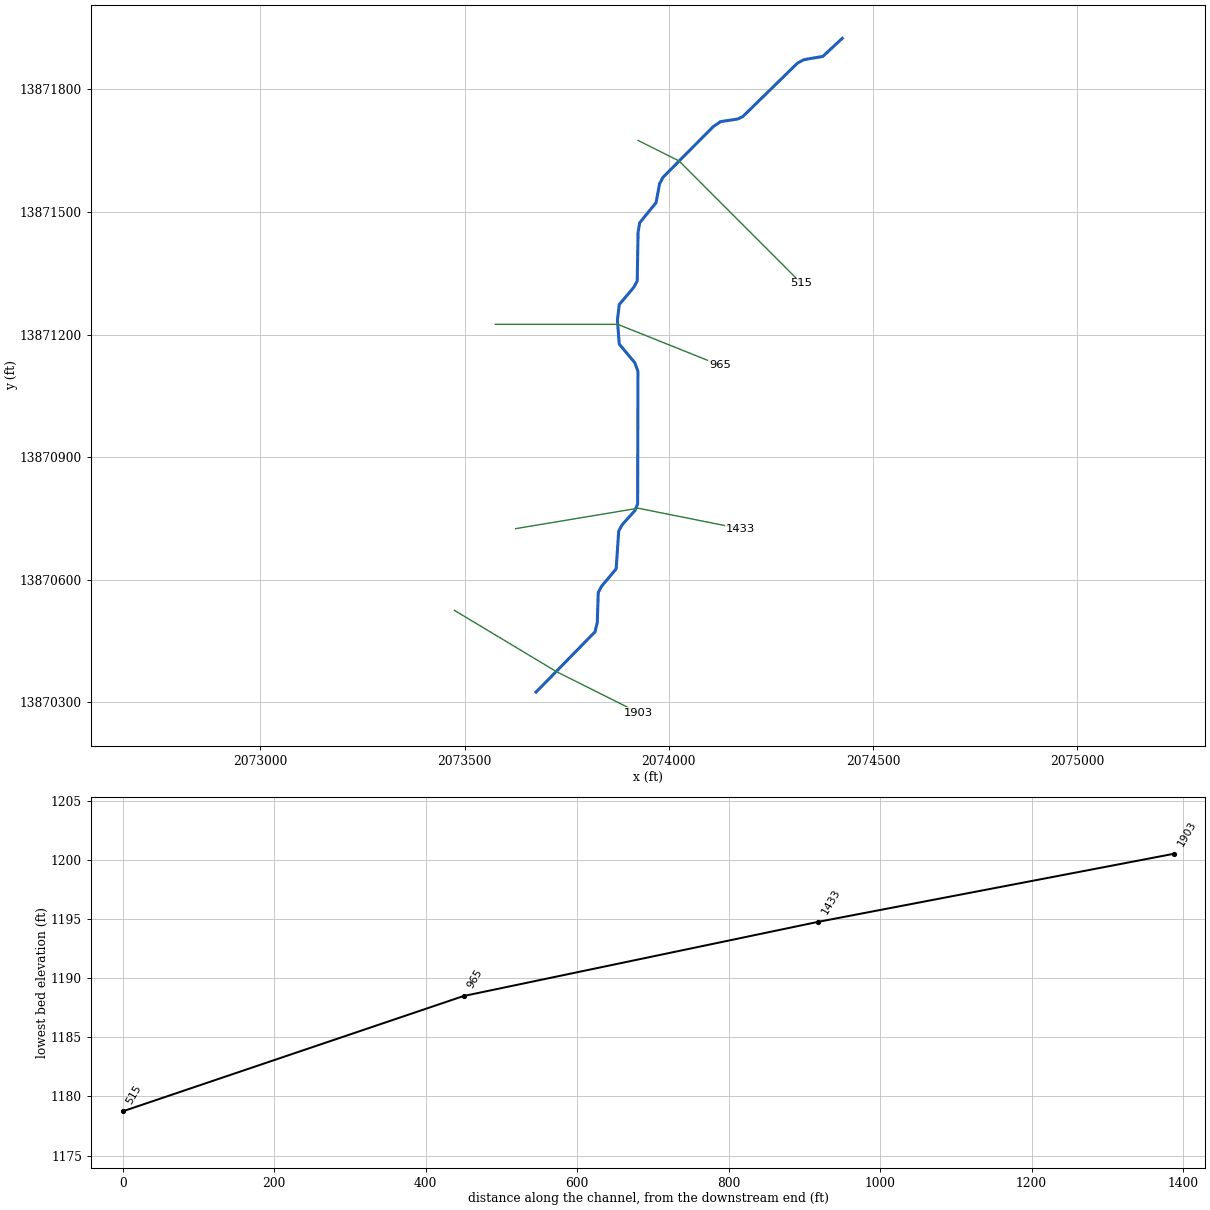
--- Stream0234_DS.prj (project) ---

Proj Title=Stream0234_DS Base Level Engineering
Current Plan=p01
Default Exp/Contr=0.3,0.1
English Units
Geom File=g01
Flow File=f01
Plan File=p01
BEGIN DESCRIPTION:
Stream0234_DS
END DESCRIPTION:

--- Stream0234_DS.p01 (plan) ---

Plan Title=Multiple Run
Short Identifier=Multiple
Geom File=g01
Flow File=f01
Subcritical Flow
K Sum by GR= 0
Std Step Tol= 0.01
Critical Tol= 0.01
Num of Std Step Trials= 20
Max Error Tol= 0.3
Flow Tol Ratio= 0.001
Split Flow NTrial= 30
Split Flow Tol= 0.02
Split Flow Ratio= 0.02
Log Output Level= 0
Friction Slope Method= 1
Unsteady Friction Slope Method= 2
Unsteady Bridges Friction Slope Method= 1
Parabolic Critical Depth
Global Vel Dist=  1 , 1 , 1
Global Log Level= 0
CheckData=True
Encroach Param= -1, 0, 0, 0
BEGIN DESCRIPTION:
Multiple Run
END DESCRIPTION:

--- Stream0234_DS.f01 (steady flow) ---

Flow Title=Multiple
Number of Profiles=7
Profile Names=10-year,25-year,50-year,1pct_min,100-year,1pct_plu,500-year
River Rch & RM= Stream0234_DS,Reach-1,1903
     500     802    1076     702    1402    2796    2343
Boundary for River Rch & Prof#=Stream0234_DS,Reach-1,1
Up Type=0
Dn Type=3
Dn Slope=0.005
Boundary for River Rch & Prof#=Stream0234_DS,Reach-1,2
Up Type=0
Dn Type=3
Dn Slope=0.005
Boundary for River Rch & Prof#=Stream0234_DS,Reach-1,3
Up Type=0
Dn Type=3
Dn Slope=0.005
Boundary for River Rch & Prof#=Stream0234_DS,Reach-1,4
Up Type=0
Dn Type=3
Dn Slope=0.005
Boundary for River Rch & Prof#=Stream0234_DS,Reach-1,5
Up Type=0
Dn Type=3
Dn Slope=0.005
Boundary for River Rch & Prof#=Stream0234_DS,Reach-1,6
Up Type=0
Dn Type=3
Dn Slope=0.005
Boundary for River Rch & Prof#=Stream0234_DS,Reach-1,7
Up Type=0
Dn Type=3
Dn Slope=0.005

--- Stream0234_DS.g01 (geometry) ---

Geom Title=Existing Conditions

River Reach=Stream0234_DS,Reach-1
Reach XY= 30
      2073675.00     13870325.00      2073819.48     13870472.57
      2073824.88     13870495.05      2073827.36     13870569.02
      2073835.89     13870584.63      2073871.15     13870626.60
      2073877.36     13870719.02      2073885.89     13870734.63
      2073916.86     13870768.94      2073923.78     13870785.50
      2073924.48     13871109.78      2073916.85     13871131.06
      2073878.70     13871176.60      2073874.23     13871235.05
      2073878.70     13871273.40      2073914.14     13871315.35
      2073922.73     13871330.94      2073924.81     13871450.08
      2073928.76     13871473.44      2073968.86     13871522.83
      2073977.49     13871568.97      2073985.76     13871584.68
      2074108.33     13871708.35      2074126.65     13871721.02
      2074168.95     13871727.54      2074181.05     13871733.16
      2074315.29     13871864.30      2074330.97     13871872.66
      2074377.35     13871880.71      2074425.00     13871925.00

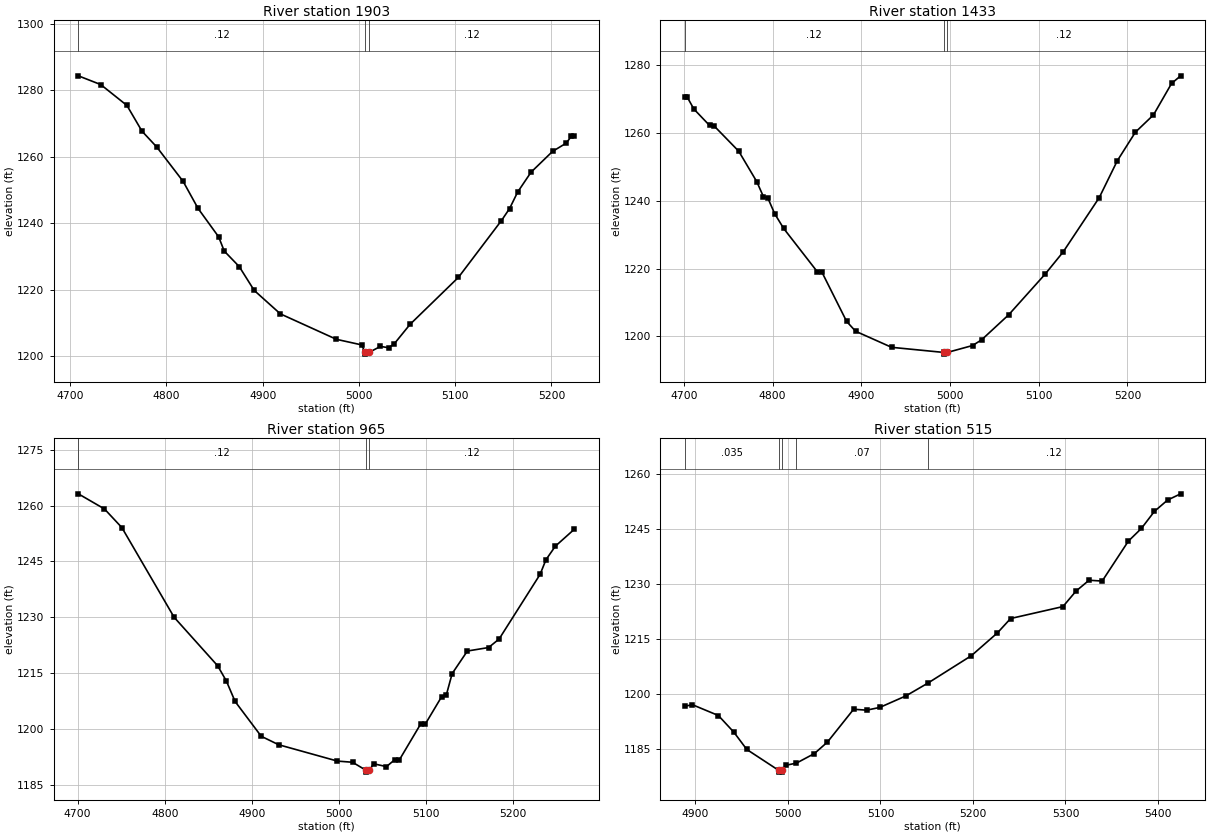
Type RM Length L Ch R = 1,1903,470,470,470
BEGIN DESCRIPTION:
Stream0234_DS 4.0
END DESCRIPTION:
XS GIS Cut Line= 3
      2073474.99     13870525.00      2073725.00     13870375.00
      2073925.03     13870274.98
#Sta/Elev= 30
  4708.4 1284.41  4731.7 1281.77  4758.9 1275.48  4774.5 1267.74  4790.0 1262.91
  4817.3 1252.58  4832.8 1244.44  4854.2 1235.87  4860.0 1231.59  4875.6 1226.90
  4891.1 1219.74  4918.3 1212.66  4976.6 1204.98  5002.8 1203.30  5006.3 1201.02
  5006.6 1200.52  5010.3 1201.02  5022.3 1202.84  5030.7 1202.46  5036.3 1203.50
  5053.1 1209.50  5103.4 1223.68  5148.1 1240.80  5156.5 1244.40  5164.9 1249.38
  5178.8 1255.36  5201.2 1261.64  5215.2 1264.09  5220.8 1266.21  5223.6 1266.21
#Mann=3,-1,0
  4708.4    0.12       0  5006.3    0.05       0  5010.3    0.12       0
Bank Sta=5006.3,5010.3
Exp/Cntr=0.3,0.1

Type RM Length L Ch R = 1,1433,468,468,468
BEGIN DESCRIPTION:
Stream0234_DS 3.0
END DESCRIPTION:
XS GIS Cut Line= 3
      2073624.98     13870725.00      2073925.00     13870775.00
      2074175.00     13870725.00
#Sta/Elev= 30
  4700.9 1270.66  4703.5 1270.66  4711.1 1267.09  4728.8 1262.24  4733.9 1262.11
  4761.7 1254.64  4782.0 1245.68  4789.6 1241.21  4794.7 1240.73  4802.3 1236.17
  4812.4 1231.84  4850.5 1219.01  4855.5 1218.96  4883.4 1204.40  4893.5 1201.51
  4934.1 1196.77  4992.9 1195.26  4993.2 1194.76  4996.9 1195.26  5025.4 1197.30
  5035.6 1198.98  5066.2 1206.39  5107.0 1218.30  5127.4 1224.86  5168.2 1240.93
  5188.6 1251.82  5209.0 1260.25  5229.4 1265.35  5249.8 1274.63  5260.0 1276.88
#Mann=3,-1,0
  4700.9    0.12       0  4992.9    0.05       0  4996.9    0.12       0
Bank Sta=4992.9,4996.9
Exp/Cntr=0.3,0.1

Type RM Length L Ch R = 1,965,450,450,450
BEGIN DESCRIPTION:
Stream0234_DS 2.0
END DESCRIPTION:
XS GIS Cut Line= 3
      2073575.00     13871225.00      2073875.00     13871225.00
      2074125.04     13871124.98
#Sta/Elev= 30
  4700.8 1263.15  4730.8 1259.09  4750.8 1254.09  4810.8 1230.03  4860.8 1217.01
  4870.8 1212.92  4880.8 1207.44  4910.8 1198.11  4930.8 1195.84  4998.3 1191.45
  5015.6 1191.14  5031.1 1188.99  5031.4 1188.49  5035.1 1188.99  5039.8 1190.73
  5054.6 1189.97  5064.1 1191.82  5069.5 1191.81  5093.7 1201.34  5099.1 1201.35
  5117.9 1208.71  5123.3 1209.16  5130.0 1214.92  5147.5 1220.98  5171.8 1221.91
  5183.9 1224.19  5231.0 1241.55  5237.7 1245.46  5248.5 1249.10  5270.1 1253.61
#Mann=3,-1,0
  4700.8    0.12       0  5031.1    0.05       0  5035.1    0.12       0
Bank Sta=5031.1,5035.1
Exp/Cntr=0.3,0.1

Type RM Length L Ch R = 1,515,0,0,0
BEGIN DESCRIPTION:
Stream0234_DS 1.0
END DESCRIPTION:
XS GIS Cut Line= 3
      2073925.03     13871674.98      2074025.00     13871625.00
      2074324.98     13871325.02
#Sta/Elev= 30
  4888.5 1196.73  4896.8 1197.13  4924.8 1194.19  4941.6 1189.62  4955.5 1184.93
  4989.9 1179.24  4990.1 1178.74  4993.6 1178.74  4993.9 1179.24  4997.5 1180.60
  5009.1 1181.19  5028.6 1183.81  5042.7 1186.94  5071.0 1195.90  5085.1 1195.65
  5099.3 1196.40  5127.5 1199.54  5151.0 1202.99  5198.3 1210.52  5226.5 1216.75
  5240.7 1220.66  5297.3 1223.92  5311.4 1228.14  5325.5 1231.11  5339.7 1230.88
  5368.0 1241.78  5382.1 1245.25  5396.2 1249.91  5410.4 1252.99  5424.5 1254.69
#Mann=5,-1,0
  4888.5   0.035       0  4989.9   0.035       0  4993.9   0.035       0
  5009.1    0.07       0  5151.0    0.12       0
Bank Sta=4989.9,4993.9
Exp/Cntr=0.3,0.1

Chan Stop Cuts=-1