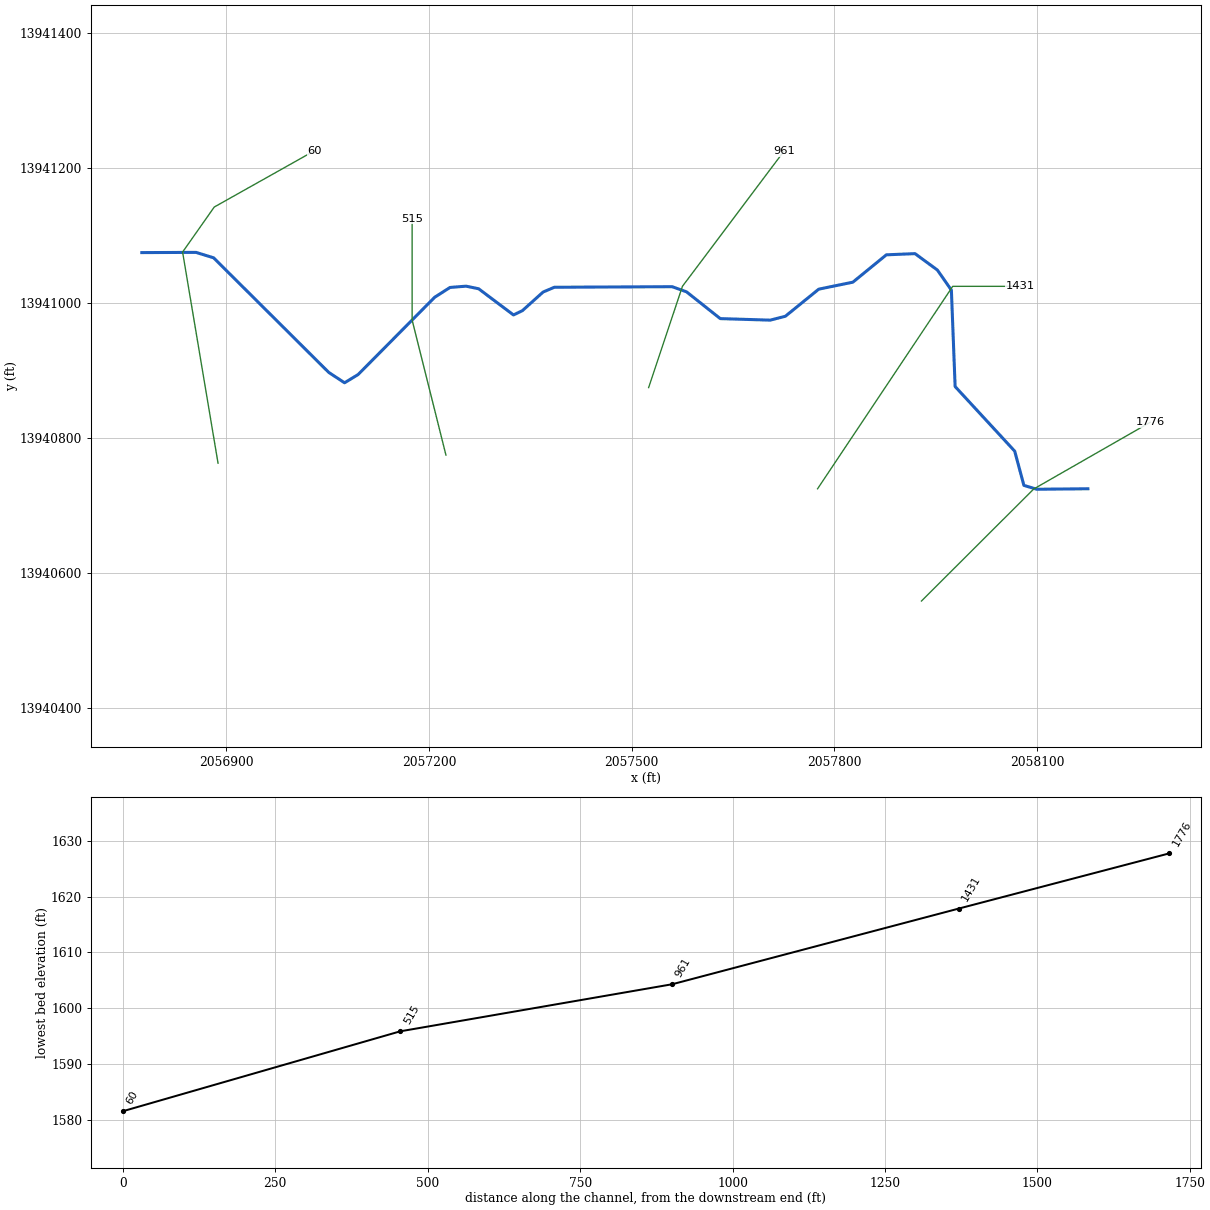
--- Stream0235_DS.prj (project) ---

Proj Title=Stream0235_DS Base Level Engineering
Current Plan=p01
Default Exp/Contr=0.3,0.1
English Units
Geom File=g01
Flow File=f01
Plan File=p01
BEGIN DESCRIPTION:
Stream0235_DS
END DESCRIPTION:

--- Stream0235_DS.p01 (plan) ---

Plan Title=Multiple Run
Short Identifier=Multiple
Geom File=g01
Flow File=f01
Subcritical Flow
K Sum by GR= 0
Std Step Tol= 0.01
Critical Tol= 0.01
Num of Std Step Trials= 20
Max Error Tol= 0.3
Flow Tol Ratio= 0.001
Split Flow NTrial= 30
Split Flow Tol= 0.02
Split Flow Ratio= 0.02
Log Output Level= 0
Friction Slope Method= 1
Unsteady Friction Slope Method= 2
Unsteady Bridges Friction Slope Method= 1
Parabolic Critical Depth
Global Vel Dist=  1 , 1 , 1
Global Log Level= 0
CheckData=True
Encroach Param= -1, 0, 0, 0
BEGIN DESCRIPTION:
Multiple Run
END DESCRIPTION:

--- Stream0235_DS.f01 (steady flow) ---

Flow Title=Multiple
Number of Profiles=7
Profile Names=10-year,25-year,50-year,1pct_min,100-year,1pct_plu,500-year
River Rch & RM= Stream0235_DS,Reach-1,1776
     635    1065    1472     991    1977    3944    3529
Boundary for River Rch & Prof#=Stream0235_DS,Reach-1,1
Up Type=0
Dn Type=3
Dn Slope=0.005
Boundary for River Rch & Prof#=Stream0235_DS,Reach-1,2
Up Type=0
Dn Type=3
Dn Slope=0.005
Boundary for River Rch & Prof#=Stream0235_DS,Reach-1,3
Up Type=0
Dn Type=3
Dn Slope=0.005
Boundary for River Rch & Prof#=Stream0235_DS,Reach-1,4
Up Type=0
Dn Type=3
Dn Slope=0.005
Boundary for River Rch & Prof#=Stream0235_DS,Reach-1,5
Up Type=0
Dn Type=3
Dn Slope=0.005
Boundary for River Rch & Prof#=Stream0235_DS,Reach-1,6
Up Type=0
Dn Type=3
Dn Slope=0.005
Boundary for River Rch & Prof#=Stream0235_DS,Reach-1,7
Up Type=0
Dn Type=3
Dn Slope=0.005

--- Stream0235_DS.g01 (geometry) ---

Geom Title=Existing Conditions

River Reach=Stream0235_DS,Reach-1
Reach XY= 30
      2058175.00     13940725.00      2058099.44     13940724.27
      2058080.31     13940730.00      2058066.72     13940780.72
      2057978.55     13940876.47      2057973.01     13941019.37
      2057952.30     13941049.16      2057919.17     13941073.47
      2057876.77     13941071.70      2057827.20     13941031.16
      2057776.74     13941020.81      2057727.32     13940980.65
      2057704.91     13940974.89      2057630.98     13940977.17
      2057581.06     13941016.85      2057559.78     13941024.48
      2057385.44     13941023.62      2057368.81     13941016.55
      2057338.20     13940988.97      2057324.99     13940982.59
      2057273.35     13941021.43      2057254.84     13941025.25
      2057231.05     13941023.34      2057208.33     13941008.77
      2057095.00     13940894.21      2057075.00     13940882.07
      2057051.67     13940897.38      2056881.22     13941067.26
      2056855.14     13941075.33      2056775.00     13941075.00

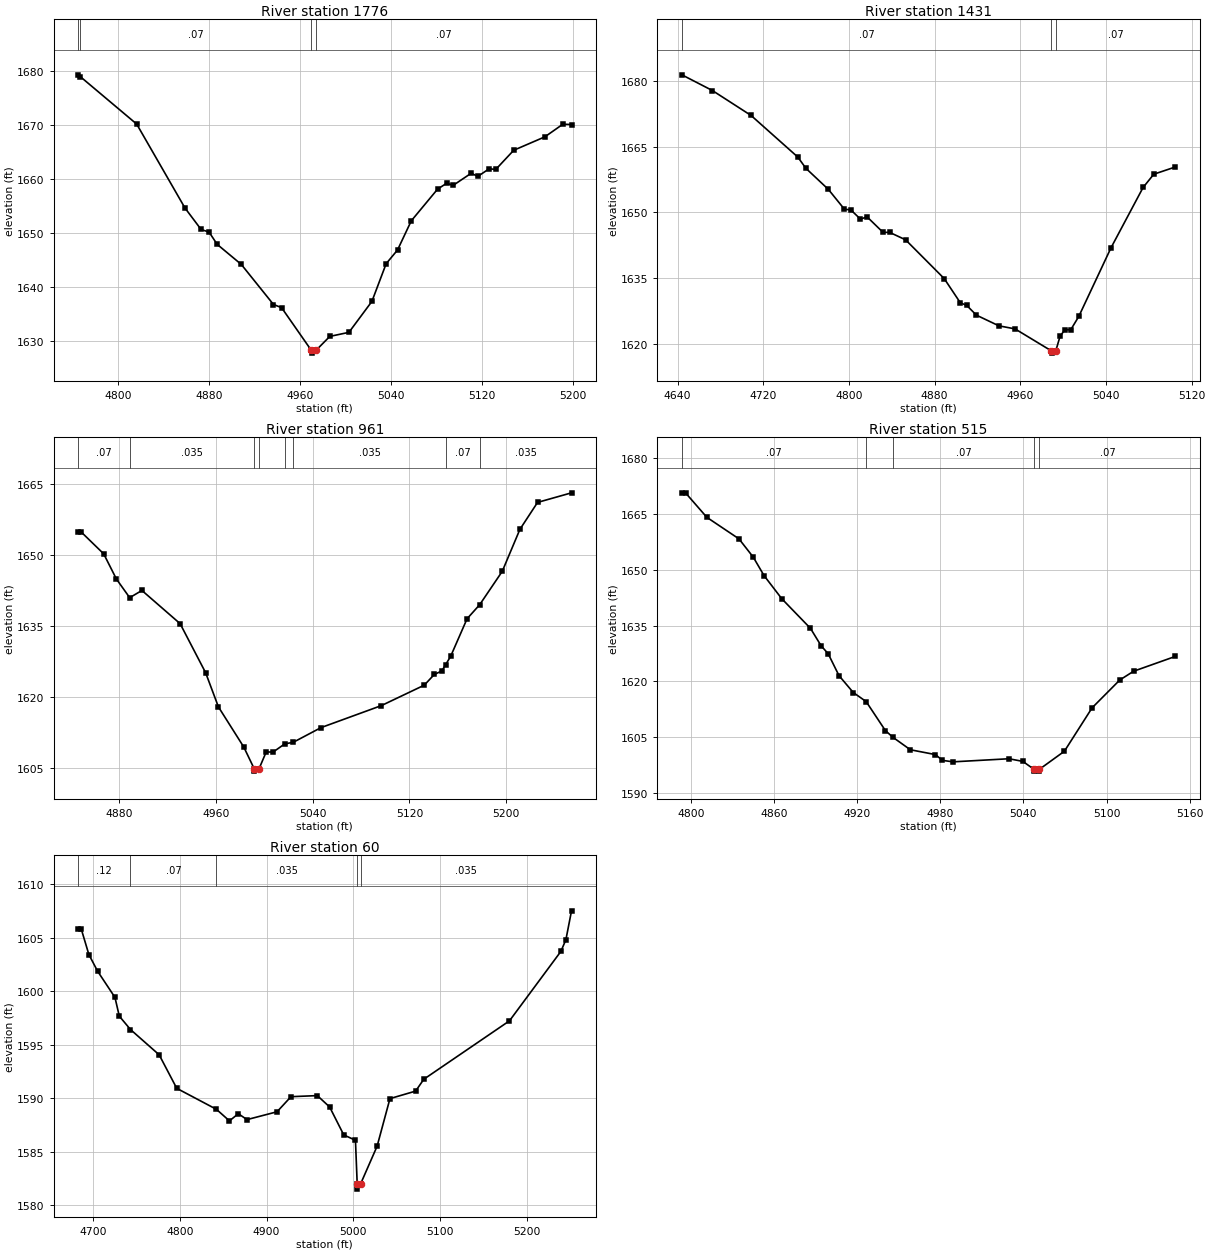
Type RM Length L Ch R = 1,1776,345,345,345
BEGIN DESCRIPTION:
Stream0235_DS 4.0
END DESCRIPTION:
XS GIS Cut Line= 3
      2057928.71     13940558.62      2058094.86     13940724.67
      2058267.14     13940823.46
#Sta/Elev= 30
  4765.1 1679.31  4766.8 1679.00  4816.5 1670.18  4858.9 1654.64  4873.1 1650.65
  4880.1 1650.17  4887.2 1647.90  4908.4 1644.18  4936.7 1636.75  4943.8 1636.17
  4970.0 1628.24  4970.3 1627.74  4974.0 1628.24  4986.2 1630.84  5003.0 1631.59
  5023.2 1637.33  5035.7 1644.31  5045.7 1646.85  5057.8 1652.26  5080.9 1658.13
  5088.9 1659.22  5094.6 1658.83  5110.5 1661.08  5116.2 1660.48  5126.3 1661.91
  5132.0 1661.77  5147.8 1665.33  5175.2 1667.82  5191.0 1670.16  5198.6 1670.10
#Mann=4,-1,0
  4765.1   0.035       0  4766.8    0.07       0  4970.0    0.05       0
  4974.0    0.07       0
Bank Sta=4970,4974
Exp/Cntr=0.3,0.1

Type RM Length L Ch R = 1,1431,470,470,470
BEGIN DESCRIPTION:
Stream0235_DS 3.0
END DESCRIPTION:
XS GIS Cut Line= 3
      2057775.01     13940725.01      2057975.00     13941025.00
      2058074.96     13941025.00
#Sta/Elev= 30
  4644.1 1681.36  4672.6 1677.77  4708.7 1672.08  4752.3 1662.59  4759.8 1660.04
  4780.8 1655.22  4795.8 1650.69  4801.8 1650.54  4810.8 1648.42  4816.9 1648.96
  4831.9 1645.40  4837.9 1645.42  4852.9 1643.71  4889.0 1634.85  4904.0 1629.34
  4910.0 1628.73  4919.0 1626.52  4940.0 1624.08  4955.1 1623.38  4989.1 1618.35
  4989.4 1617.85  4993.1 1618.35  4997.1 1621.70  5001.6 1623.19  5007.1 1623.19
  5014.6 1626.23  5044.6 1641.86  5074.6 1655.65  5084.6 1658.68  5104.6 1660.32
#Mann=3,-1,0
  4644.1    0.07       0  4989.1    0.05       0  4993.1    0.07       0
Bank Sta=4989.1,4993.1
Exp/Cntr=0.3,0.1

Type RM Length L Ch R = 1,961,446,446,446
BEGIN DESCRIPTION:
Stream0235_DS 2.0
END DESCRIPTION:
XS GIS Cut Line= 3
      2057525.00     13940874.99      2057575.00     13941025.00
      2057724.98     13941224.98
#Sta/Elev= 30
  4846.0 1654.90  4848.6 1654.90  4867.1 1650.30  4877.6 1644.97  4888.6 1641.02
  4898.7 1642.55  4930.3 1635.52  4951.4 1625.13  4962.0 1617.88  4983.0 1609.37
  4991.6 1604.78  4991.8 1604.28  4995.6 1604.78  5001.5 1608.33  5007.3 1608.33
  5016.8 1610.04  5024.0 1610.40  5046.8 1613.49  5096.8 1618.16  5132.3 1622.49
  5140.6 1624.76  5146.8 1625.49  5149.9 1626.81  5154.1 1628.59  5167.7 1636.56
  5178.1 1639.52  5196.8 1646.60  5211.4 1655.49  5226.0 1661.20  5254.1 1663.23
#Mann=8,-1,0
  4846.0    0.07       0  4888.6   0.035       0  4991.6   0.035       0
  4995.6   0.035       0  5016.8    0.07       0  5024.0   0.035       0
  5149.9    0.07       0  5178.1   0.035       0
Bank Sta=4991.6,4995.6
Exp/Cntr=0.3,0.1

Type RM Length L Ch R = 1,515,455,455,455
BEGIN DESCRIPTION:
Stream0235_DS 1.0
END DESCRIPTION:
XS GIS Cut Line= 3
      2057225.00     13940775.01      2057175.00     13940975.00
      2057175.00     13941124.95
#Sta/Elev= 30
  4793.5 1670.71  4796.1 1670.71  4811.5 1664.12  4834.7 1658.32  4845.0 1653.41
  4852.8 1648.44  4865.6 1642.22  4886.3 1634.25  4894.0 1629.56  4899.1 1627.41
  4906.9 1621.53  4917.2 1616.99  4926.5 1614.55  4940.4 1606.74  4945.8 1604.95
  4958.4 1601.59  4976.5 1600.29  4981.6 1598.73  4989.3 1598.34  5029.6 1599.17
  5039.6 1598.46  5047.6 1596.34  5047.9 1595.84  5051.4 1595.84  5051.6 1596.34
  5069.6 1601.19  5089.6 1612.87  5109.6 1620.36  5119.6 1622.72  5149.6 1626.69
#Mann=5,-1,0
  4793.5    0.07       0  4926.5   0.035       0  4945.8    0.07       0
  5047.6    0.05       0  5051.6    0.07       0
Bank Sta=5047.6,5051.6
Exp/Cntr=0.3,0.1

Type RM Length L Ch R = 1,60,0,0,0
BEGIN DESCRIPTION:
Stream0235_DS 0.0
END DESCRIPTION:
XS GIS Cut Line= 4
      2056887.78     13940762.86      2056835.33     13941075.79
      2056882.18     13941142.53      2057030.67     13941226.04
#Sta/Elev= 30
  4682.7 1605.77  4686.3 1605.77  4695.0 1603.41  4705.1 1601.85  4725.1 1599.41
  4730.1 1597.66  4743.0 1596.41  4776.1 1594.05  4796.4 1590.92  4842.2 1588.96
  4857.2 1587.88  4867.4 1588.55  4877.5 1588.00  4912.1 1588.73  4928.2 1590.14
  4958.6 1590.24  4972.8 1589.18  4989.1 1586.57  5002.6 1586.07  5004.6 1582.01
  5004.9 1581.51  5008.6 1582.01  5027.6 1585.52  5042.4 1589.96  5072.0 1590.66
  5081.5 1591.77  5180.3 1597.22  5239.6 1603.70  5245.4 1604.79  5251.9 1607.49
#Mann=5,-1,0
  4682.7    0.12       0  4743.0    0.07       0  4842.2   0.035       0
  5004.6   0.035       0  5008.6   0.035       0
Bank Sta=5004.6,5008.6
Exp/Cntr=0.3,0.1

Chan Stop Cuts=-1