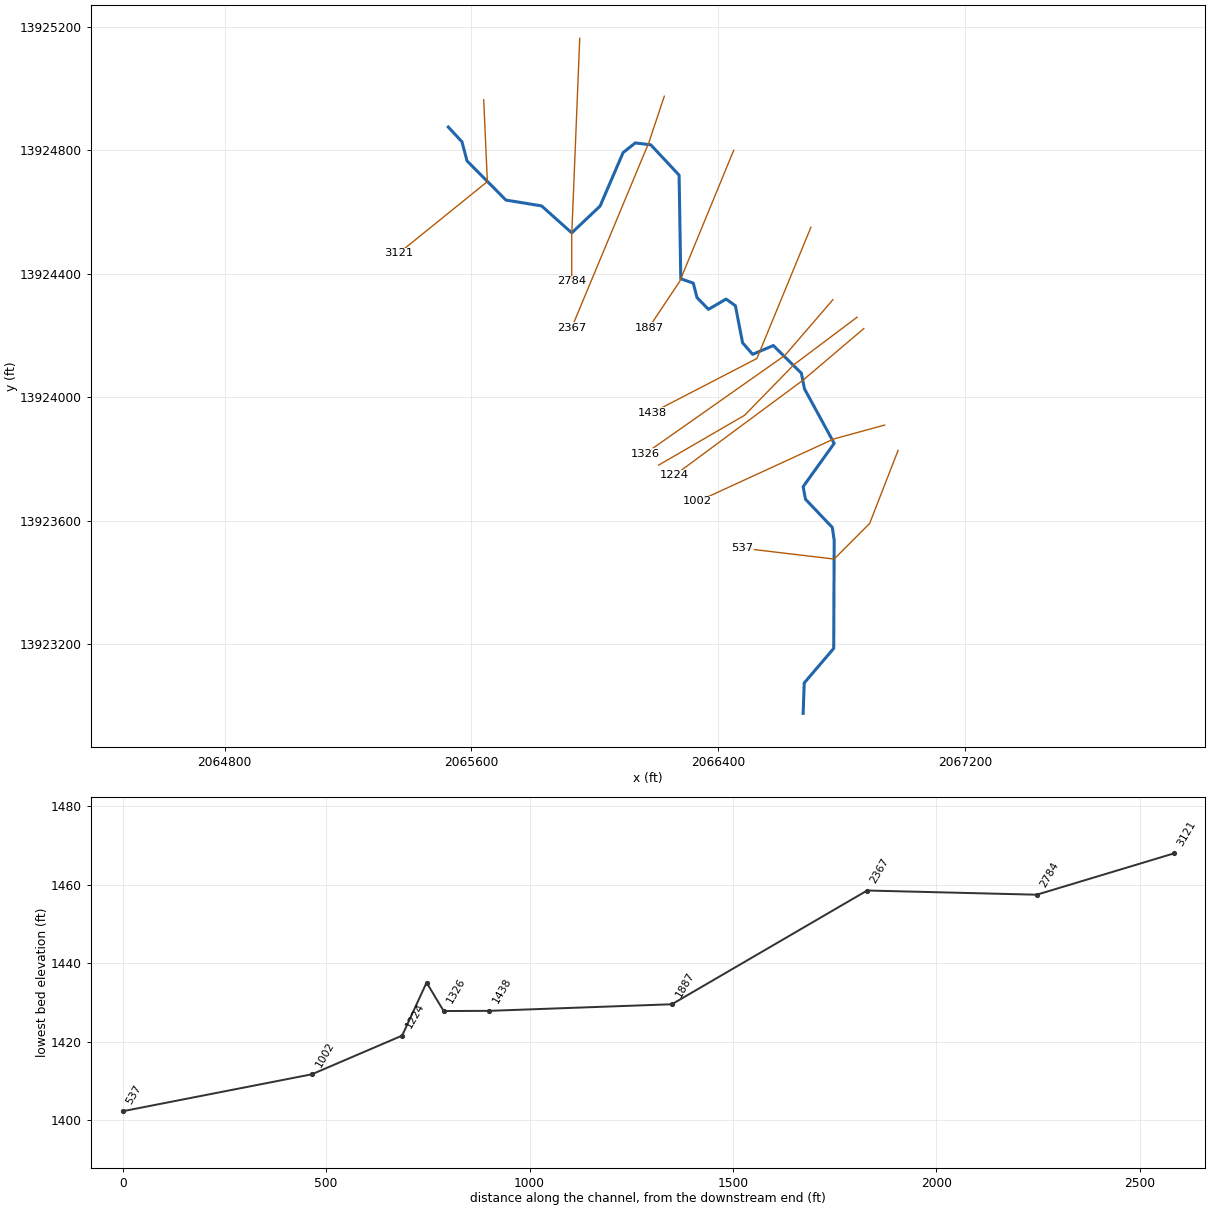
--- Stream0237_DS.prj (project) ---

Proj Title=Stream0237_DS Base Level Engineering
Current Plan=p01
Default Exp/Contr=0.3,0.1
English Units
Geom File=g01
Flow File=f01
Plan File=p01
BEGIN DESCRIPTION:
Stream0237_DS
END DESCRIPTION:

--- Stream0237_DS.p01 (plan) ---

Plan Title=Multiple Run
Short Identifier=Multiple
Geom File=g01
Flow File=f01
Subcritical Flow
K Sum by GR= 0
Std Step Tol= 0.01
Critical Tol= 0.01
Num of Std Step Trials= 20
Max Error Tol= 0.3
Flow Tol Ratio= 0.001
Split Flow NTrial= 30
Split Flow Tol= 0.02
Split Flow Ratio= 0.02
Log Output Level= 0
Friction Slope Method= 1
Unsteady Friction Slope Method= 2
Unsteady Bridges Friction Slope Method= 1
Parabolic Critical Depth
Global Vel Dist=  1 , 1 , 1
Global Log Level= 0
CheckData=True
Encroach Param= -1, 0, 0, 0
BEGIN DESCRIPTION:
Multiple Run
END DESCRIPTION:

--- Stream0237_DS.f01 (steady flow) ---

Flow Title=Multiple
Number of Profiles=7
Profile Names=10-year,25-year,50-year,1pct_min,100-year,1pct_plu,500-year
River Rch & RM= Stream0237_DS,Reach-1,3121
     171     257     331     208     415     828     643
River Rch & RM= Stream0237_DS,Reach-1,2367
     418     672     904     592    1181    2357    1993
Boundary for River Rch & Prof#=Stream0237_DS,Reach-1,1
Up Type=0
Dn Type=3
Dn Slope=0.005
Boundary for River Rch & Prof#=Stream0237_DS,Reach-1,2
Up Type=0
Dn Type=3
Dn Slope=0.005
Boundary for River Rch & Prof#=Stream0237_DS,Reach-1,3
Up Type=0
Dn Type=3
Dn Slope=0.005
Boundary for River Rch & Prof#=Stream0237_DS,Reach-1,4
Up Type=0
Dn Type=3
Dn Slope=0.005
Boundary for River Rch & Prof#=Stream0237_DS,Reach-1,5
Up Type=0
Dn Type=3
Dn Slope=0.005
Boundary for River Rch & Prof#=Stream0237_DS,Reach-1,6
Up Type=0
Dn Type=3
Dn Slope=0.005
Boundary for River Rch & Prof#=Stream0237_DS,Reach-1,7
Up Type=0
Dn Type=3
Dn Slope=0.005

--- Stream0237_DS.g01 (geometry) ---

Geom Title=Existing Conditions

River Reach=Stream0237_DS,Reach-1
Reach XY= 30
      2065525.00     13924875.00      2065569.29     13924827.35
      2065585.70     13924765.29      2065711.70     13924638.40
      2065827.43     13924619.45      2065925.02     13924532.08
      2066016.86     13924618.91      2066091.49     13924792.23
      2066130.87     13924823.50      2066181.05     13924817.55
      2066272.95     13924719.16      2066278.40     13924383.43
      2066318.94     13924369.13      2066330.93     13924322.47
      2066368.07     13924284.23      2066425.23     13924317.53
      2066455.37     13924296.05      2066478.61     13924176.04
      2066511.25     13924138.48      2066578.34     13924167.00
      2066669.17     13924077.33      2066679.19     13924026.74
      2066775.50     13923849.97      2066674.90     13923709.64
      2066682.48     13923668.96      2066769.52     13923577.45
      2066775.50     13923535.21      2066773.95     13923185.44
      2066678.39     13923073.59      2066675.00     13922975.00

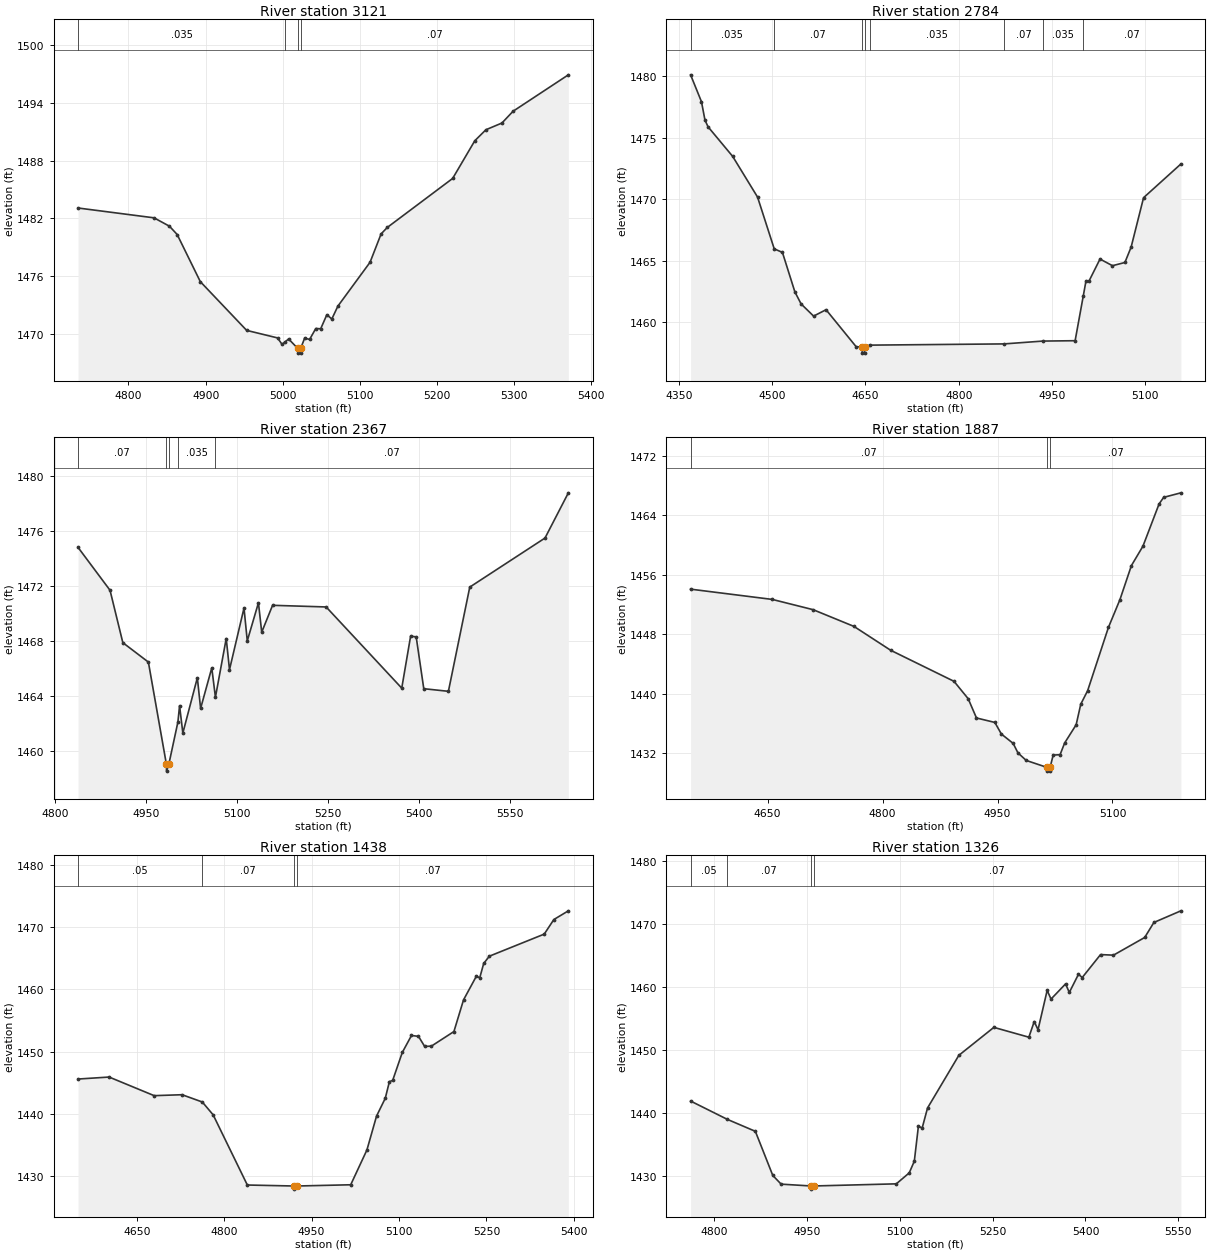
Type RM Length L Ch R = 1,3121,337,337,337
BEGIN DESCRIPTION:
Stream0237_DS 7.0
END DESCRIPTION:
XS GIS Cut Line= 3
      2065639.75     13924963.38      2065651.59     13924698.25
      2065363.65     13924465.41
#Sta/Elev= 30
  4734.6 1483.08  4833.1 1482.06  4853.1 1481.19  4863.1 1480.33  4893.1 1475.44
  4953.2 1470.38  4993.2 1469.60  4999.1 1468.93  5003.4 1469.21  5007.6 1469.49
  5019.3 1468.52  5019.6 1468.02  5023.1 1468.02  5023.3 1468.52  5028.4 1469.58
  5034.8 1469.44  5042.8 1470.57  5049.2 1470.55  5057.2 1472.01  5063.6 1471.56
  5071.5 1472.90  5113.2 1477.45  5127.5 1480.39  5135.5 1481.06  5220.3 1486.15
  5249.0 1490.06  5263.4 1491.20  5284.2 1491.90  5298.6 1493.12  5370.3 1496.90
#Mann=4,-1,0
  4734.6   0.035       0  5003.4    0.07       0  5019.3   0.035       0
  5023.3    0.07       0
Bank Sta=5019.3,5023.3
Exp/Cntr=0.3,0.1

Type RM Length L Ch R = 1,2784,417,417,417
BEGIN DESCRIPTION:
Stream0237_DS 6.0
END DESCRIPTION:
XS GIS Cut Line= 3
      2065950.96     13925162.50      2065925.00     13924525.00
      2065925.00     13924375.03
#Sta/Elev= 30
  4369.1 1480.13  4386.6 1477.94  4392.2 1476.45  4397.2 1475.90  4436.7 1473.50
  4476.7 1470.19  4503.5 1465.98  4516.7 1465.69  4536.7 1462.48  4546.7 1461.50
  4566.8 1460.51  4586.8 1461.03  4635.2 1458.02  4644.8 1458.00  4645.1 1457.50
  4648.6 1457.50  4648.8 1458.00  4656.8 1458.15  4873.0 1458.25  4935.2 1458.48
  4987.1 1458.51  5000.2 1462.15  5004.6 1463.38  5009.6 1463.38  5027.1 1465.15
  5047.1 1464.61  5067.1 1464.87  5077.1 1466.12  5097.1 1470.14  5157.1 1472.88
#Mann=8,-1,0
  4369.1   0.035       0  4503.5    0.07       0  4644.8   0.035       0
  4648.8    0.07       0  4656.8   0.035       0  4873.0    0.07       0
  4935.2   0.035       0  5000.2    0.07       0
Bank Sta=4644.8,4648.8
Exp/Cntr=0.3,0.1

Type RM Length L Ch R = 1,2367,480,480,480
BEGIN DESCRIPTION:
Stream0237_DS 5.0
END DESCRIPTION:
XS GIS Cut Line= 3
      2066224.99     13924974.98      2066175.00     13924825.00
      2065925.00     13924224.99
#Sta/Elev= 30
  4838.4 1474.80  4891.1 1471.69  4912.2 1467.89  4954.3 1466.48  4984.0 1459.07
  4984.2 1458.57  4988.0 1459.07  5003.0 1462.14  5005.7 1463.32  5011.1 1461.33
  5035.0 1465.34  5040.4 1463.12  5058.8 1466.06  5064.8 1463.93  5082.6 1468.19
  5088.0 1465.93  5111.9 1470.40  5117.3 1468.02  5135.7 1470.78  5141.1 1468.65
  5159.0 1470.60  5247.3 1470.48  5371.9 1464.59  5386.5 1468.36  5395.7 1468.31
  5408.2 1464.55  5448.8 1464.36  5484.0 1471.92  5608.0 1475.48  5646.5 1478.76
#Mann=5,-1,0
  4838.4    0.07       0  4984.0    0.05       0  4988.0    0.07       0
  5003.0   0.035       0  5064.8    0.07       0
Bank Sta=4984,4988
Exp/Cntr=0.3,0.1

Type RM Length L Ch R = 1,1887,449,449,449
BEGIN DESCRIPTION:
Stream0237_DS 4.0
END DESCRIPTION:
XS GIS Cut Line= 3
      2066450.01     13924800.03      2066275.00     13924375.00
      2066175.02     13924225.03
#Sta/Elev= 30
  4549.4 1454.08  4656.0 1452.70  4709.3 1451.32  4762.6 1449.07  4810.5 1445.86
  4893.2 1441.68  4911.7 1439.34  4922.5 1436.75  4946.5 1436.15  4955.0 1434.59
  4970.4 1433.33  4976.6 1432.06  4987.4 1431.04  5014.6 1430.10  5014.8 1429.60
  5018.3 1429.60  5018.6 1430.10  5022.6 1431.76  5031.6 1431.81  5037.6 1433.39
  5052.6 1435.84  5058.6 1438.60  5067.6 1440.43  5094.7 1448.93  5109.7 1452.66
  5124.7 1457.25  5139.8 1459.87  5160.8 1465.54  5166.8 1466.43  5189.3 1467.04
#Mann=3,-1,0
  4549.4    0.07       0  5014.6    0.05       0  5018.6    0.07       0
Bank Sta=5014.6,5018.6
Exp/Cntr=0.3,0.1

Type RM Length L Ch R = 1,1438,112,112,112
BEGIN DESCRIPTION:
Stream0237_DS 3.0
END DESCRIPTION:
XS GIS Cut Line= 3
      2066700.01     13924550.02      2066525.00     13924125.00
      2066185.97     13923949.52
#Sta/Elev= 30
  4549.2 1445.61  4602.5 1445.93  4679.8 1442.94  4727.7 1443.09  4762.4 1441.92
  4781.0 1439.86  4839.7 1428.58  4920.3 1428.42  4920.6 1427.92  4924.3 1428.42
  5017.1 1428.62  5044.9 1434.21  5061.4 1439.65  5076.4 1442.52  5083.5 1445.19
  5089.1 1445.39  5105.6 1449.88  5121.4 1452.61  5133.4 1452.47  5144.0 1450.85
  5155.6 1450.90  5194.2 1453.24  5210.7 1458.33  5232.8 1462.15  5238.5 1461.87
  5245.3 1464.18  5255.0 1465.35  5349.2 1468.90  5365.7 1471.24  5390.6 1472.64
#Mann=4,-1,0
  4549.2    0.05       0  4762.4    0.07       0  4920.3    0.05       0
  4924.3    0.07       0
Bank Sta=4920.3,4924.3
Exp/Cntr=0.3,0.1

Type RM Length L Ch R = 1,1326,42,42,42
BEGIN DESCRIPTION:
Stream0237_DS 2.0
END DESCRIPTION:
XS GIS Cut Line= 3
      2066771.41     13924315.69      2066615.86     13924135.03
      2066162.43     13923816.20
#Sta/Elev= 30
  4761.6 1441.86  4821.0 1438.95  4866.3 1437.05  4894.5 1430.04  4908.0 1428.66
  4956.4 1428.37  4956.7 1427.87  4960.4 1428.37  5094.2 1428.71  5115.1 1430.45
  5123.3 1432.31  5129.9 1437.86  5136.0 1437.58  5144.7 1440.76  5195.3 1449.12
  5251.9 1453.56  5308.5 1452.00  5317.2 1454.49  5323.3 1453.18  5338.1 1459.44
  5344.3 1458.05  5367.8 1460.46  5373.9 1459.11  5388.7 1461.99  5394.8 1461.48
  5424.4 1465.12  5445.3 1465.03  5495.8 1467.84  5510.6 1470.22  5554.3 1472.07
#Mann=4,-1,0
  4761.6    0.05       0  4821.0    0.07       0  4956.4    0.05       0
  4960.4    0.07       0
Bank Sta=4956.4,4960.4
Exp/Cntr=0.3,0.1

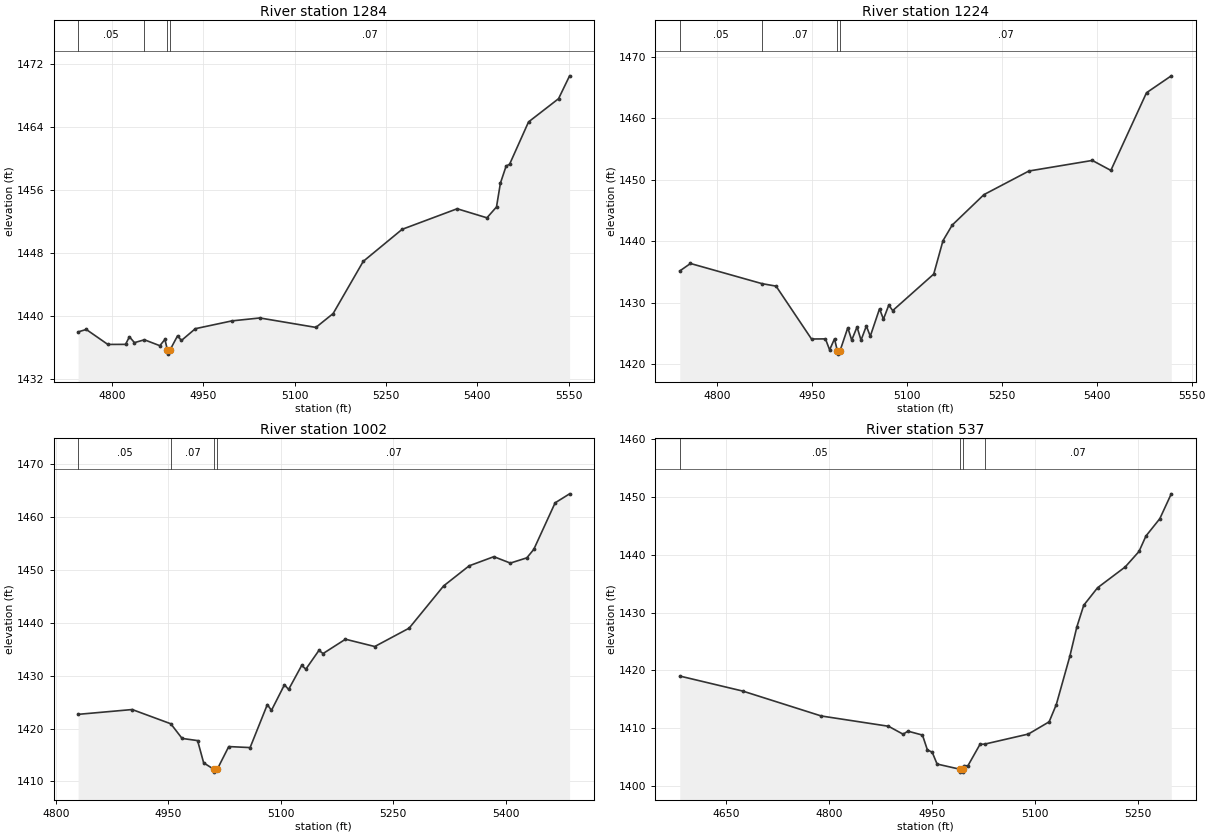
Type RM Length L Ch R = 1,1284,60,60,60
BEGIN DESCRIPTION:
Stream0237_DS 1.2
END DESCRIPTION:
XS GIS Cut Line= 4
      2066849.66     13924258.78      2066645.39     13924105.32
      2066484.83     13923940.75      2066206.69     13923779.54
#Sta/Elev= 30
  4744.5 1437.94  4757.9 1438.25  4793.3 1436.35  4822.4 1436.36  4828.7 1437.32
  4837.0 1436.58  4853.4 1436.94  4878.7 1436.19  4887.0 1436.99  4891.2 1435.62
  4891.5 1435.12  4895.2 1435.62  4907.8 1437.45  4914.1 1436.85  4937.0 1438.35
  4997.1 1439.34  5042.9 1439.71  5134.9 1438.51  5163.2 1440.27  5212.6 1446.89
  5276.5 1450.96  5366.8 1453.57  5415.7 1452.42  5431.4 1453.80  5437.8 1456.81
  5447.2 1458.99  5452.9 1459.22  5484.0 1464.59  5533.3 1467.54  5551.4 1470.44
#Mann=4,-1,0
  4744.5    0.05       0  4853.4    0.07       0  4891.2    0.05       0
  4895.2    0.07       0
Bank Sta=4891.2,4895.2
Exp/Cntr=0.3,0.1

Type RM Length L Ch R = 1,1224,222,222,222
BEGIN DESCRIPTION:
Stream0237_DS 1.1
END DESCRIPTION:
XS GIS Cut Line= 3
      2066871.56     13924222.08      2066674.68     13924054.88
      2066258.48     13923746.82
#Sta/Elev= 30
  4741.7 1435.15  4758.6 1436.36  4871.6 1433.08  4893.7 1432.68  4949.7 1424.08
  4971.7 1424.10  4978.3 1422.31  4986.0 1424.11  4990.6 1422.12  4990.8 1421.62
  4994.6 1422.12  5007.0 1425.91  5013.2 1423.90  5021.6 1426.04  5027.9 1423.89
  5036.3 1426.20  5042.5 1424.53  5057.1 1428.99  5063.3 1427.31  5071.7 1429.59
  5077.9 1428.70  5142.7 1434.64  5157.3 1440.07  5171.9 1442.61  5222.0 1447.56
  5293.0 1451.40  5393.1 1453.12  5422.4 1451.50  5478.7 1464.13  5517.8 1466.88
#Mann=4,-1,0
  4741.7    0.05       0  4871.6    0.07       0  4990.6    0.05       0
  4994.6    0.07       0
Bank Sta=4990.6,4994.6
Exp/Cntr=0.3,0.1

Type RM Length L Ch R = 1,1002,465,465,465
BEGIN DESCRIPTION:
Stream0237_DS 1.0
END DESCRIPTION:
XS GIS Cut Line= 3
      2066938.87     13923909.24      2066774.30     13923864.30
      2066333.12     13923661.63
#Sta/Elev= 30
  4829.4 1422.68  4901.6 1423.59  4953.1 1420.90  4968.2 1418.13  4988.9 1417.72
  4997.0 1413.51  5011.0 1412.26  5011.3 1411.76  5015.0 1412.26  5030.5 1416.59
  5059.0 1416.40  5082.0 1424.53  5087.5 1423.43  5104.9 1428.28  5110.4 1427.38
  5127.9 1431.94  5133.4 1431.22  5150.9 1434.77  5156.4 1434.17  5186.3 1436.88
  5225.4 1435.50  5271.3 1438.97  5317.3 1446.95  5351.4 1450.75  5384.4 1452.48
  5406.4 1451.27  5428.4 1452.26  5437.7 1453.86  5466.2 1462.66  5485.5 1464.36
#Mann=4,-1,0
  4829.4    0.05       0  4953.1    0.07       0  5011.0    0.05       0
  5015.0    0.07       0
Bank Sta=5011,5015
Exp/Cntr=0.3,0.1

Type RM Length L Ch R = 1,537,0,0,0
BEGIN DESCRIPTION:
Stream0237_DS 0.0
END DESCRIPTION:
XS GIS Cut Line= 4
      2066982.55     13923827.07      2066890.41     13923590.41
      2066775.08     13923475.03      2066478.37     13923510.36
#Sta/Elev= 30
  4582.9 1419.00  4674.5 1416.40  4789.0 1412.08  4886.9 1410.30  4908.2 1408.92
  4915.2 1409.45  4936.4 1408.77  4943.5 1406.22  4950.6 1405.79  4957.7 1403.75
  4991.0 1402.85  4991.3 1402.35  4994.8 1402.35  4995.0 1402.85  4996.5 1403.46
  5002.6 1403.46  5020.2 1407.17  5026.9 1407.20  5090.7 1408.95  5120.9 1411.07
  5131.3 1414.05  5151.1 1422.45  5161.2 1427.49  5171.3 1431.27  5191.4 1434.30
  5231.7 1437.91  5251.8 1440.59  5261.9 1443.27  5282.1 1446.27  5298.8 1450.58
#Mann=4,-1,0
  4582.9    0.05       0  4991.0    0.05       0  4995.0    0.05       0
  5026.9    0.07       0
Bank Sta=4991,4995
Exp/Cntr=0.3,0.1

Chan Stop Cuts=-1