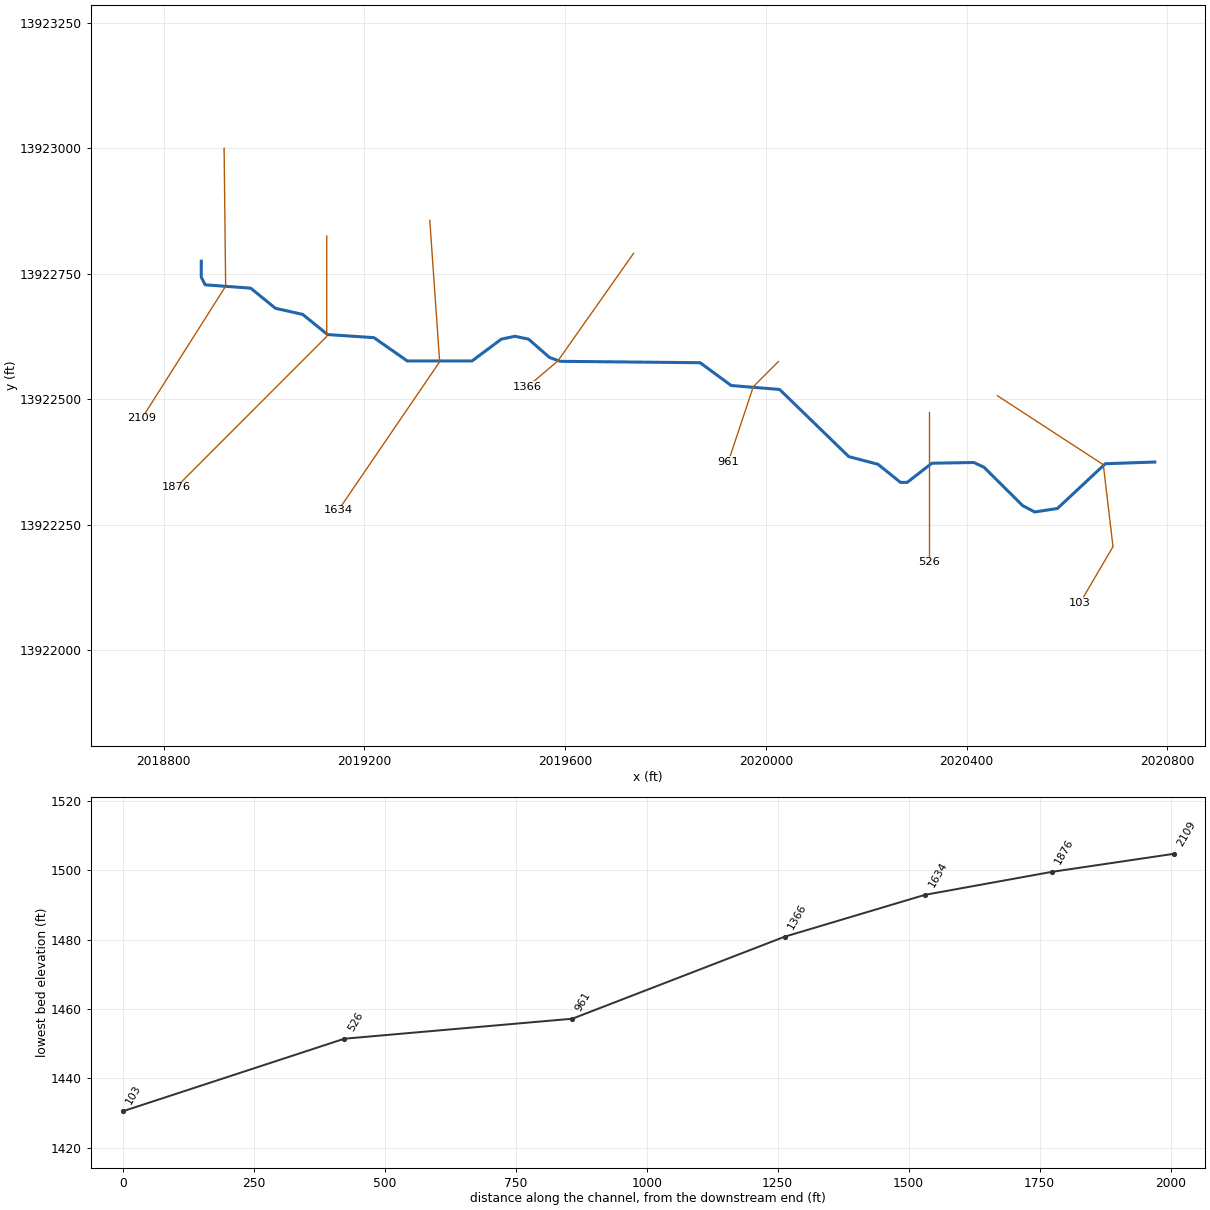
--- Stream0239_DS.prj (project) ---

Proj Title=Stream0239_DS Base Level Engineering
Current Plan=p01
Default Exp/Contr=0.3,0.1
English Units
Geom File=g01
Flow File=f01
Plan File=p01
BEGIN DESCRIPTION:
Stream0239_DS
END DESCRIPTION:

--- Stream0239_DS.p01 (plan) ---

Plan Title=Multiple Run
Short Identifier=Multiple
Geom File=g01
Flow File=f01
Subcritical Flow
K Sum by GR= 0
Std Step Tol= 0.01
Critical Tol= 0.01
Num of Std Step Trials= 20
Max Error Tol= 0.3
Flow Tol Ratio= 0.001
Split Flow NTrial= 30
Split Flow Tol= 0.02
Split Flow Ratio= 0.02
Log Output Level= 0
Friction Slope Method= 1
Unsteady Friction Slope Method= 2
Unsteady Bridges Friction Slope Method= 1
Parabolic Critical Depth
Global Vel Dist=  1 , 1 , 1
Global Log Level= 0
CheckData=True
Encroach Param= -1, 0, 0, 0
BEGIN DESCRIPTION:
Multiple Run
END DESCRIPTION:

--- Stream0239_DS.f01 (steady flow) ---

Flow Title=Multiple
Number of Profiles=7
Profile Names=10-year,25-year,50-year,1pct_min,100-year,1pct_plu,500-year
River Rch & RM= Stream0239_DS,Reach-1,2109
     515     852    1167     779    1555    3103    2730
Boundary for River Rch & Prof#=Stream0239_DS,Reach-1,1
Up Type=0
Dn Type=3
Dn Slope=0.005
Boundary for River Rch & Prof#=Stream0239_DS,Reach-1,2
Up Type=0
Dn Type=3
Dn Slope=0.005
Boundary for River Rch & Prof#=Stream0239_DS,Reach-1,3
Up Type=0
Dn Type=3
Dn Slope=0.005
Boundary for River Rch & Prof#=Stream0239_DS,Reach-1,4
Up Type=0
Dn Type=3
Dn Slope=0.005
Boundary for River Rch & Prof#=Stream0239_DS,Reach-1,5
Up Type=0
Dn Type=3
Dn Slope=0.005
Boundary for River Rch & Prof#=Stream0239_DS,Reach-1,6
Up Type=0
Dn Type=3
Dn Slope=0.005
Boundary for River Rch & Prof#=Stream0239_DS,Reach-1,7
Up Type=0
Dn Type=3
Dn Slope=0.005

--- Stream0239_DS.g01 (geometry) ---

Geom Title=Existing Conditions

River Reach=Stream0239_DS,Reach-1
Reach XY= 30
      2018875.00     13922775.00      2018874.92     13922743.10
      2018882.76     13922727.84      2018973.38     13922721.21
      2019022.81     13922681.11      2019077.18     13922668.89
      2019126.58     13922628.83      2019219.02     13922622.64
      2019285.51     13922576.20      2019414.50     13922576.23
      2019472.82     13922619.62      2019500.00     13922625.40
      2019527.18     13922619.62      2019568.92     13922583.19
      2019590.21     13922575.54      2019869.06     13922572.74
      2019930.98     13922527.36      2020027.43     13922519.48
      2020165.32     13922385.75      2020223.35     13922370.55
      2020268.38     13922334.41      2020281.60     13922334.44
      2020330.90     13922372.64      2020414.51     13922374.05
      2020434.78     13922364.54      2020511.80     13922288.14
      2020535.64     13922275.56      2020581.04     13922282.48
      2020676.41     13922371.60      2020775.00     13922375.00

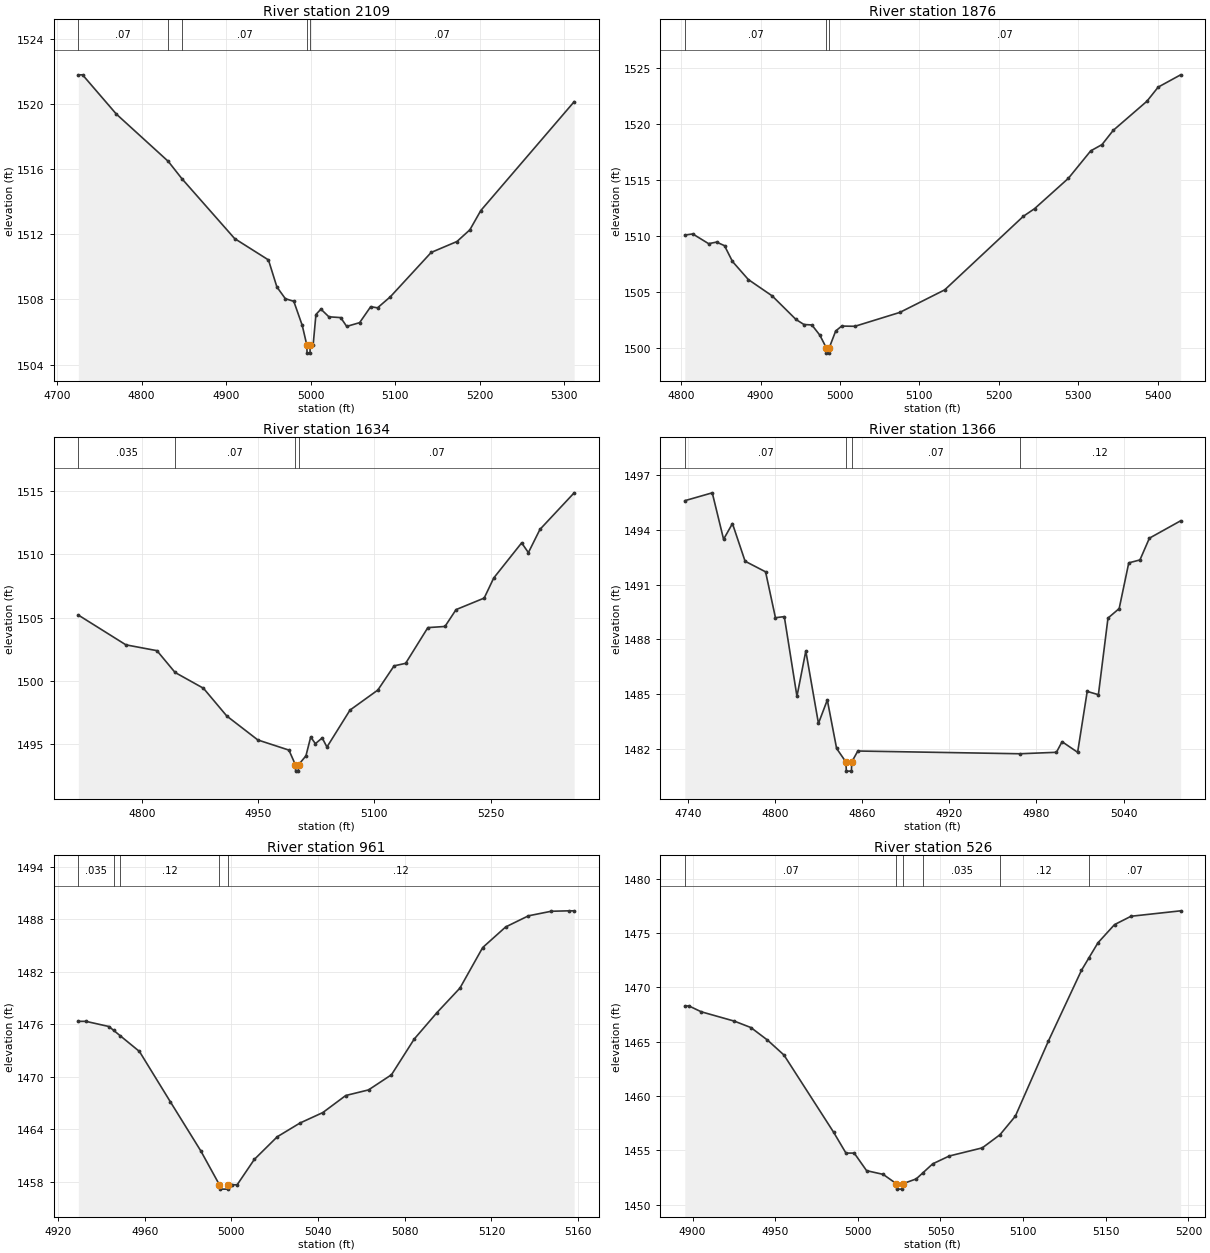
Type RM Length L Ch R = 1,2109,233,233,233
BEGIN DESCRIPTION:
Stream0239_DS 5.0
END DESCRIPTION:
XS GIS Cut Line= 3
      2018920.48     13922999.95      2018923.55     13922725.07
      2018756.49     13922461.68
#Sta/Elev= 30
  4725.1 1521.78  4730.1 1521.78  4770.1 1519.37  4831.5 1516.47  4847.6 1515.41
  4910.1 1511.73  4950.1 1510.42  4960.1 1508.76  4970.1 1508.04  4980.1 1507.88
  4990.1 1506.40  4995.5 1505.20  4995.8 1504.70  4999.3 1504.70  4999.5 1505.20
  5003.0 1505.20  5006.3 1507.07  5012.2 1507.40  5021.6 1506.93  5035.6 1506.88
  5042.7 1506.34  5058.0 1506.57  5071.1 1507.55  5079.2 1507.48  5094.4 1508.16
  5142.7 1510.88  5173.2 1511.55  5188.5 1512.27  5201.4 1513.45  5311.9 1520.13
#Mann=5,-1,0
  4725.1    0.07       0  4831.5   0.035       0  4847.6    0.07       0
  4995.5    0.05       0  4999.5    0.07       0
Bank Sta=4995.5,4999.5
Exp/Cntr=0.3,0.1

Type RM Length L Ch R = 1,1876,242,242,242
BEGIN DESCRIPTION:
Stream0239_DS 4.0
END DESCRIPTION:
XS GIS Cut Line= 3
      2019125.00     13922825.01      2019125.00     13922625.00
      2018824.98     13922324.98
#Sta/Elev= 30
  4804.6 1510.06  4814.6 1510.16  4834.6 1509.29  4844.6 1509.43  4854.6 1509.11
  4864.6 1507.70  4884.6 1506.08  4914.6 1504.62  4944.6 1502.51  4954.6 1502.06
  4964.6 1502.02  4974.6 1501.11  4982.6 1500.00  4982.9 1499.50  4986.4 1499.50
  4986.6 1500.00  4994.6 1501.48  5002.1 1501.92  5018.8 1501.90  5075.3 1503.14
  5131.9 1505.16  5230.9 1511.74  5245.0 1512.42  5287.5 1515.13  5315.7 1517.59
  5329.9 1518.15  5344.0 1519.42  5386.5 1522.03  5400.6 1523.29  5428.9 1524.39
#Mann=3,-1,0
  4804.6    0.07       0  4982.6    0.05       0  4986.6    0.07       0
Bank Sta=4982.6,4986.6
Exp/Cntr=0.3,0.1

Type RM Length L Ch R = 1,1634,268,268,268
BEGIN DESCRIPTION:
Stream0239_DS 3.5
END DESCRIPTION:
XS GIS Cut Line= 3
      2019330.34     13922856.21      2019350.00     13922574.60
      2019148.18     13922279.03
#Sta/Elev= 30
  4717.7 1505.20  4779.1 1502.85  4819.2 1502.39  4842.6 1500.67  4879.3 1499.42
  4909.4 1497.23  4949.5 1495.34  4989.6 1494.54  4998.0 1493.38  4998.3 1492.88
  5001.8 1492.88  5002.0 1493.38  5011.6 1494.09  5017.7 1495.57  5023.8 1495.05
  5032.6 1495.50  5038.7 1494.78  5068.5 1497.70  5104.4 1499.28  5125.4 1501.19
  5140.3 1501.39  5169.0 1504.21  5191.1 1504.30  5205.4 1505.63  5241.7 1506.54
  5254.1 1508.13  5290.1 1510.90  5298.8 1510.13  5313.7 1511.96  5357.9 1514.85
#Mann=4,-1,0
  4717.7   0.035       0  4842.6    0.07       0  4998.0    0.05       0
  5002.0    0.07       0
Bank Sta=4998,5002
Exp/Cntr=0.3,0.1

Type RM Length L Ch R = 1,1366,405,405,405
BEGIN DESCRIPTION:
Stream0239_DS 3.0
END DESCRIPTION:
XS GIS Cut Line= 3
      2019736.36     13922790.45      2019585.50     13922576.24
      2019524.98     13922524.99
#Sta/Elev= 30
  4738.0 1495.59  4756.9 1496.02  4764.7 1493.48  4770.8 1494.34  4779.5 1492.28
  4793.6 1491.70  4800.4 1489.19  4806.5 1489.25  4815.2 1484.89  4821.3 1487.37
  4830.0 1483.41  4836.1 1484.69  4842.5 1482.04  4848.9 1481.30  4849.2 1480.80
  4852.7 1480.80  4852.9 1481.30  4857.1 1481.90  4968.7 1481.75  4993.8 1481.83
  4997.7 1482.41  5008.4 1481.83  5015.0 1485.16  5022.7 1484.98  5029.3 1489.17
  5037.0 1489.69  5043.6 1492.19  5051.3 1492.35  5057.8 1493.54  5079.3 1494.49
#Mann=4,-1,0
  4738.0    0.07       0  4848.9    0.05       0  4852.9    0.07       0
  4968.7    0.12       0
Bank Sta=4848.9,4852.9
Exp/Cntr=0.3,0.1

Type RM Length L Ch R = 1,961,435,435,435
BEGIN DESCRIPTION:
Stream0239_DS 2.0
END DESCRIPTION:
XS GIS Cut Line= 3
      2020024.97     13922574.97      2019975.00     13922525.00
      2019925.00     13922374.99
#Sta/Elev= 30
  4929.4 1476.34  4932.9 1476.34  4943.5 1475.75  4945.7 1475.31  4948.8 1474.68
  4957.6 1472.90  4971.8 1467.18  4985.9 1461.55  4994.5 1457.68  4994.8 1457.18
  4998.3 1457.18  4998.5 1457.68  5000.1 1457.68  5002.7 1457.68  5010.6 1460.57
  5021.2 1463.16  5031.7 1464.73  5042.2 1465.92  5052.8 1467.87  5063.3 1468.51
  5073.9 1470.24  5084.4 1474.32  5094.9 1477.34  5105.5 1480.14  5116.0 1484.77
  5126.6 1487.12  5137.1 1488.39  5147.6 1488.91  5155.6 1488.96  5158.2 1488.96
#Mann=5,-1,0
  4929.4   0.035       0  4945.7    0.07       0  4948.8    0.12       0
  4994.5    0.05       0  4998.5    0.12       0
Bank Sta=4994.5,4998.5
Exp/Cntr=0.3,0.1

Type RM Length L Ch R = 1,526,423,423,423
BEGIN DESCRIPTION:
Stream0239_DS 1.0
END DESCRIPTION:
XS GIS Cut Line= 3
      2020325.00     13922474.99      2020325.00     13922375.00
      2020325.00     13922174.99
#Sta/Elev= 30
  4895.3 1468.29  4897.8 1468.29  4905.3 1467.75  4925.3 1466.89  4935.3 1466.30
  4945.3 1465.15  4955.3 1463.77  4985.3 1456.67  4992.8 1454.74  4997.8 1454.74
  5005.3 1453.12  5015.3 1452.78  5023.3 1451.92  5023.5 1451.42  5027.0 1451.42
  5027.3 1451.92  5035.3 1452.36  5039.5 1452.94  5045.3 1453.75  5055.3 1454.47
  5075.3 1455.22  5086.0 1456.43  5095.3 1458.14  5115.3 1465.06  5135.3 1471.57
  5139.7 1472.69  5145.3 1474.11  5155.3 1475.78  5165.3 1476.55  5195.3 1477.05
#Mann=6,-1,0
  4895.3    0.07       0  5023.3    0.05       0  5027.3    0.07       0
  5039.5   0.035       0  5086.0    0.12       0  5139.7    0.07       0
Bank Sta=5023.3,5027.3
Exp/Cntr=0.3,0.1

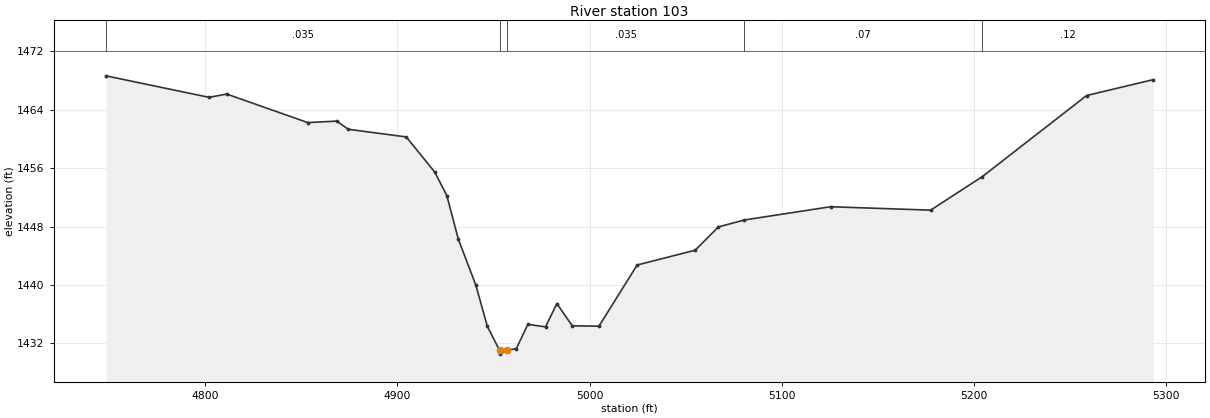
Type RM Length L Ch R = 1,103,0,0,0
BEGIN DESCRIPTION:
Stream0239_DS 0.0
END DESCRIPTION:
XS GIS Cut Line= 4
      2020461.49     13922507.02      2020672.51     13922369.63
      2020691.75     13922206.38      2020626.40     13922095.14
#Sta/Elev= 30
  4748.2 1468.66  4801.9 1465.71  4811.1 1466.16  4853.3 1462.25  4868.4 1462.45
  4874.4 1461.33  4904.6 1460.28  4919.4 1455.47  4925.7 1452.24  4931.7 1446.25
  4940.8 1439.97  4946.8 1434.31  4953.2 1431.00  4953.5 1430.50  4957.2 1431.00
  4961.9 1431.27  4967.9 1434.58  4977.1 1434.24  4983.0 1437.43  4991.0 1434.38
  5004.9 1434.33  5024.8 1442.72  5055.0 1444.75  5067.1 1447.94  5080.5 1448.89
  5125.5 1450.71  5177.6 1450.24  5204.5 1454.84  5258.8 1465.96  5293.4 1468.13
#Mann=5,-1,0
  4748.2   0.035       0  4953.2   0.035       0  4957.2   0.035       0
  5080.5    0.07       0  5204.5    0.12       0
Bank Sta=4953.2,4957.2
Exp/Cntr=0.3,0.1

Chan Stop Cuts=-1