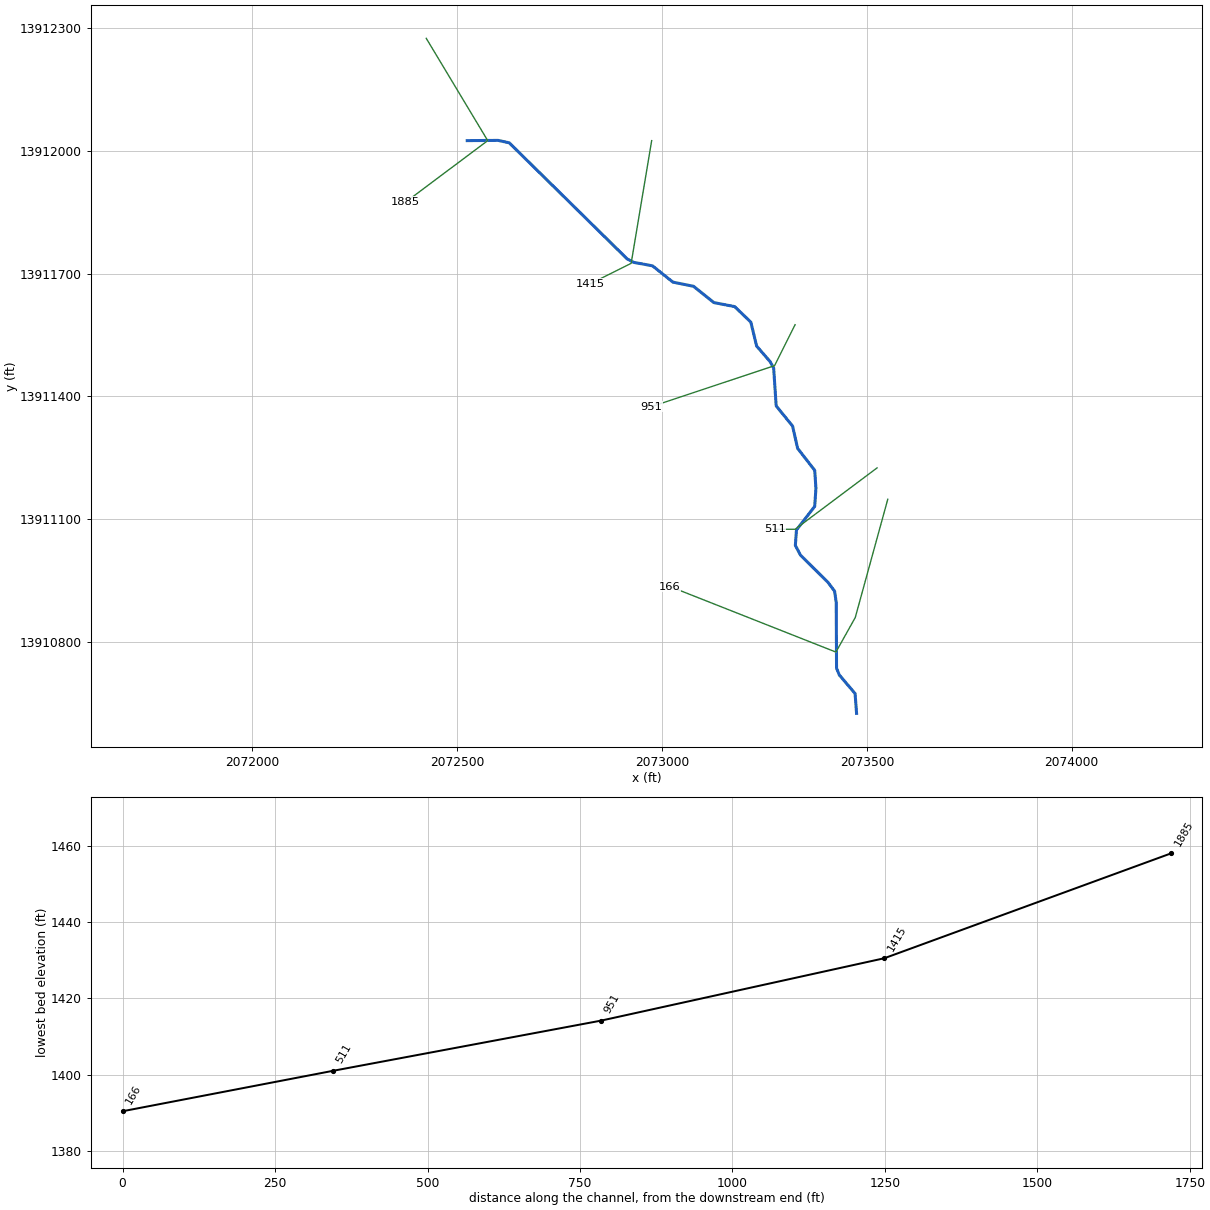
--- Stream0240_DS.prj (project) ---

Proj Title=Stream0240_DS Base Level Engineering
Current Plan=p01
Default Exp/Contr=0.3,0.1
English Units
Geom File=g01
Flow File=f01
Plan File=p01
BEGIN DESCRIPTION:
Stream0240_DS
END DESCRIPTION:

--- Stream0240_DS.p01 (plan) ---

Plan Title=Multiple Run
Short Identifier=Multiple
Geom File=g01
Flow File=f01
Subcritical Flow
K Sum by GR= 0
Std Step Tol= 0.01
Critical Tol= 0.01
Num of Std Step Trials= 20
Max Error Tol= 0.3
Flow Tol Ratio= 0.001
Split Flow NTrial= 30
Split Flow Tol= 0.02
Split Flow Ratio= 0.02
Log Output Level= 0
Friction Slope Method= 1
Unsteady Friction Slope Method= 2
Unsteady Bridges Friction Slope Method= 1
Parabolic Critical Depth
Global Vel Dist=  1 , 1 , 1
Global Log Level= 0
CheckData=True
Encroach Param= -1, 0, 0, 0
BEGIN DESCRIPTION:
Multiple Run
END DESCRIPTION:

--- Stream0240_DS.f01 (steady flow) ---

Flow Title=Multiple
Number of Profiles=7
Profile Names=10-year,25-year,50-year,1pct_min,100-year,1pct_plu,500-year
River Rch & RM= Stream0240_DS,Reach-1,1885
     238     366     477     305     608    1213     970
Boundary for River Rch & Prof#=Stream0240_DS,Reach-1,1
Up Type=0
Dn Type=3
Dn Slope=0.005
Boundary for River Rch & Prof#=Stream0240_DS,Reach-1,2
Up Type=0
Dn Type=3
Dn Slope=0.005
Boundary for River Rch & Prof#=Stream0240_DS,Reach-1,3
Up Type=0
Dn Type=3
Dn Slope=0.005
Boundary for River Rch & Prof#=Stream0240_DS,Reach-1,4
Up Type=0
Dn Type=3
Dn Slope=0.005
Boundary for River Rch & Prof#=Stream0240_DS,Reach-1,5
Up Type=0
Dn Type=3
Dn Slope=0.005
Boundary for River Rch & Prof#=Stream0240_DS,Reach-1,6
Up Type=0
Dn Type=3
Dn Slope=0.005
Boundary for River Rch & Prof#=Stream0240_DS,Reach-1,7
Up Type=0
Dn Type=3
Dn Slope=0.005

--- Stream0240_DS.g01 (geometry) ---

Geom Title=Existing Conditions

River Reach=Stream0240_DS,Reach-1
Reach XY= 30
      2072525.00     13912025.00      2072600.25     13912025.59
      2072627.50     13912019.65      2072915.32     13911735.76
      2072931.03     13911727.50      2072977.19     13911718.90
      2073026.72     13911679.16      2073077.20     13911668.92
      2073126.76     13911629.20      2073177.55     13911619.27
      2073216.98     13911581.34      2073231.15     13911522.85
      2073264.17     13911484.66      2073272.67     13911469.04
      2073278.83     13911376.58      2073318.89     13911327.18
      2073331.12     13911272.82      2073372.86     13911219.03
      2073375.82     13911175.00      2073372.81     13911130.97
      2073328.34     13911073.25      2073325.61     13911035.62
      2073338.15     13911011.80      2073405.35     13910945.15
      2073421.45     13910923.53      2073425.43     13910895.18
      2073426.12     13910735.46      2073432.89     13910718.84
      2073471.35     13910673.49      2073475.00     13910625.00

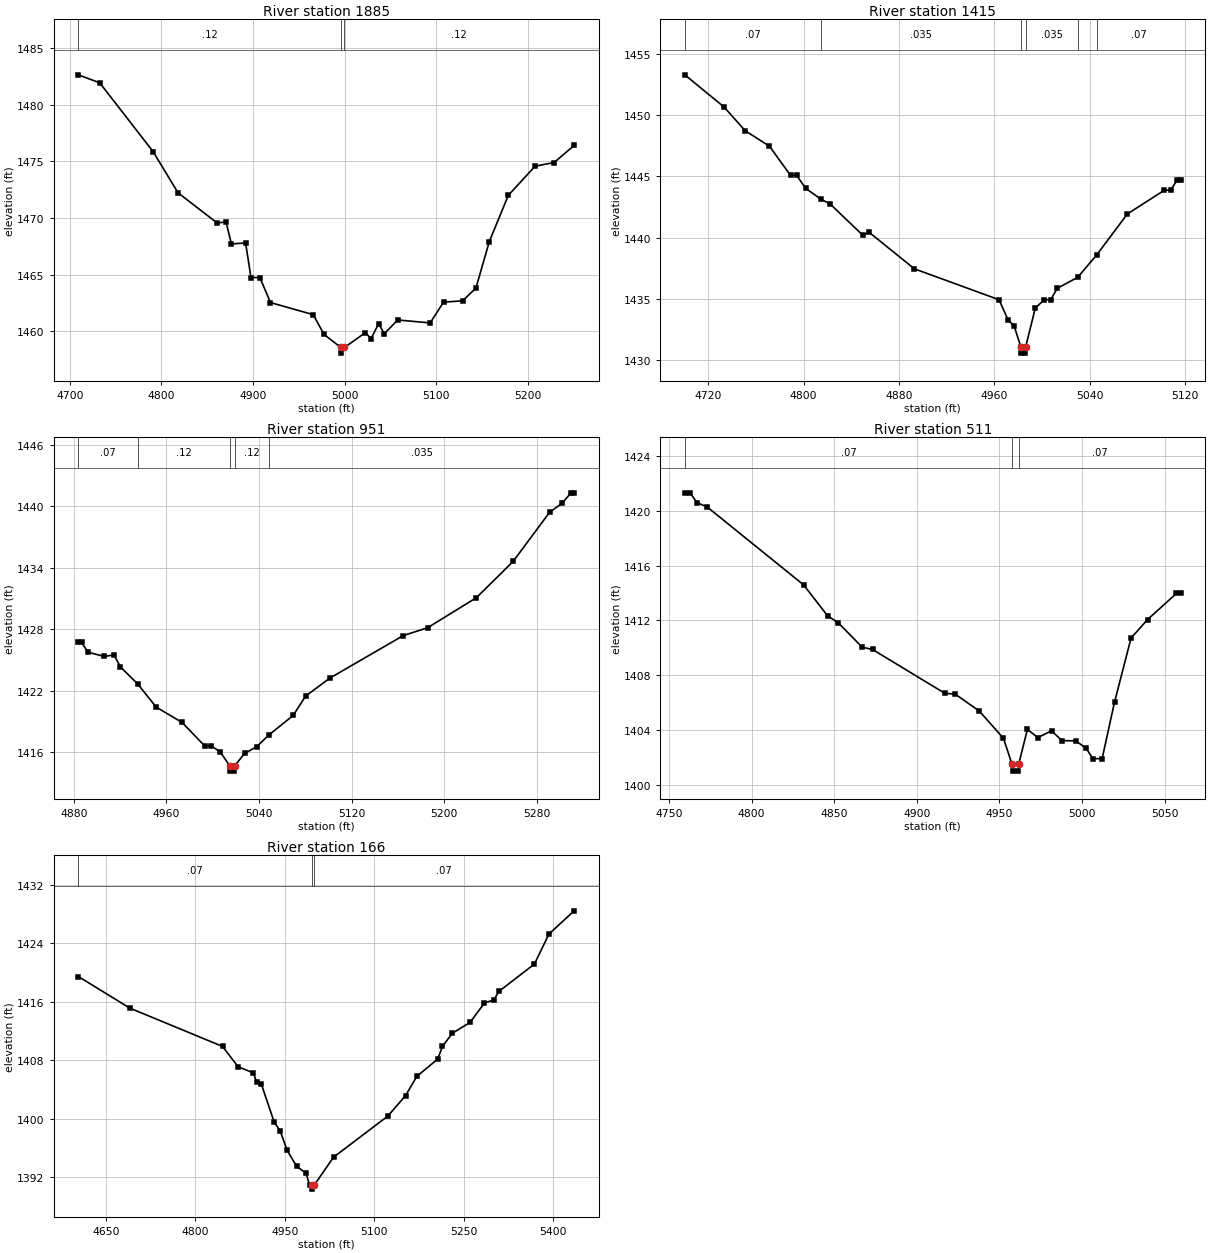
Type RM Length L Ch R = 1,1885,470,470,470
BEGIN DESCRIPTION:
Stream0240_DS 4.0
END DESCRIPTION:
XS GIS Cut Line= 3
      2072424.98     13912275.03      2072575.00     13912025.00
      2072374.99     13911874.99
#Sta/Elev= 30
  4709.2 1482.66  4732.6 1481.95  4790.9 1475.87  4818.1 1472.23  4860.8 1469.57
  4870.6 1469.65  4876.4 1467.71  4891.9 1467.80  4897.8 1464.74  4907.5 1464.74
  4919.1 1462.53  4965.8 1461.46  4977.5 1459.72  4995.9 1458.56  4996.1 1458.06
  4999.9 1458.56  5022.7 1459.87  5028.9 1459.34  5037.2 1460.65  5043.5 1459.78
  5058.1 1460.99  5093.5 1460.73  5108.1 1462.57  5128.9 1462.68  5143.5 1463.81
  5158.1 1467.92  5178.9 1472.01  5208.1 1474.58  5228.9 1474.91  5250.8 1476.42
#Mann=3,-1,0
  4709.2    0.12       0  4995.9    0.05       0  4999.9    0.12       0
Bank Sta=4995.9,4999.9
Exp/Cntr=0.3,0.1

Type RM Length L Ch R = 1,1415,464,464,464
BEGIN DESCRIPTION:
Stream0240_DS 3.0
END DESCRIPTION:
XS GIS Cut Line= 3
      2072975.00     13912025.00      2072925.00     13911725.00
      2072825.04     13911675.02
#Sta/Elev= 30
  4700.3 1453.32  4733.3 1450.68  4751.0 1448.74  4771.3 1447.48  4789.0 1445.09
  4794.1 1445.09  4801.7 1444.03  4814.8 1443.12  4822.0 1442.77  4849.8 1440.17
  4854.9 1440.43  4892.9 1437.44  4963.9 1434.91  4971.5 1433.25  4976.6 1432.75
  4982.2 1431.04  4982.4 1430.54  4985.9 1430.54  4986.2 1431.04  4994.3 1434.23
  5001.9 1434.92  5007.2 1434.92  5012.8 1435.85  5029.8 1436.74  5045.9 1438.59
  5071.5 1441.93  5102.3 1443.86  5107.9 1443.90  5113.4 1444.72  5116.2 1444.72
#Mann=6,-1,0
  4700.3    0.07       0  4814.8   0.035       0  4982.2   0.035       0
  4986.2   0.035       0  5029.8    0.12       0  5045.9    0.07       0
Bank Sta=4982.2,4986.2
Exp/Cntr=0.3,0.1

Type RM Length L Ch R = 1,951,440,440,440
BEGIN DESCRIPTION:
Stream0240_DS 2.0
END DESCRIPTION:
XS GIS Cut Line= 3
      2073325.01     13911575.02      2073275.00     13911475.00
      2072974.96     13911374.99
#Sta/Elev= 30
  4884.0 1426.72  4886.8 1426.72  4892.4 1425.77  4906.4 1425.36  4914.8 1425.51
  4920.4 1424.33  4935.2 1422.69  4951.1 1420.43  4973.5 1418.93  4993.0 1416.65
  4998.5 1416.65  5006.4 1416.07  5014.9 1414.68  5015.2 1414.18  5018.7 1414.18
  5018.9 1414.68  5027.5 1415.90  5038.0 1416.56  5048.6 1417.71  5069.6 1419.62
  5080.2 1421.49  5101.2 1423.25  5164.5 1427.39  5185.6 1428.16  5227.7 1431.09
  5259.4 1434.62  5291.0 1439.43  5301.5 1440.27  5309.4 1441.31  5312.1 1441.31
#Mann=5,-1,0
  4884.0    0.07       0  4935.2    0.12       0  5014.9    0.05       0
  5018.9    0.12       0  5048.6   0.035       0
Bank Sta=5014.9,5018.9
Exp/Cntr=0.3,0.1

Type RM Length L Ch R = 1,511,345,345,345
BEGIN DESCRIPTION:
Stream0240_DS 1.0
END DESCRIPTION:
XS GIS Cut Line= 3
      2073525.03     13911225.03      2073325.00     13911075.00
      2073275.04     13911075.00
#Sta/Elev= 30
  4759.6 1421.33  4762.8 1421.33  4766.9 1420.62  4773.2 1420.29  4831.5 1414.60
  4846.1 1412.33  4852.4 1411.84  4866.9 1410.05  4873.2 1409.88  4916.9 1406.68
  4923.2 1406.62  4937.8 1405.38  4952.4 1403.39  4957.6 1401.49  4957.9 1400.99
  4961.4 1400.99  4961.6 1401.49  4966.9 1404.04  4973.2 1403.44  4981.5 1403.94
  4987.8 1403.22  4996.1 1403.20  5002.4 1402.67  5006.5 1401.90  5012.1 1401.90
  5019.6 1406.03  5029.6 1410.71  5039.6 1412.07  5057.1 1413.98  5059.6 1413.98
#Mann=3,-1,0
  4759.6    0.07       0  4957.6    0.05       0  4961.6    0.07       0
Bank Sta=4957.6,4961.6
Exp/Cntr=0.3,0.1

Type RM Length L Ch R = 1,166,0,0,0
BEGIN DESCRIPTION:
Stream0240_DS 0.0
END DESCRIPTION:
XS GIS Cut Line= 4
      2073551.14     13911148.35      2073471.79     13910859.28
      2073424.60     13910774.83      2073019.44     13910935.09
#Sta/Elev= 30
  4603.5 1419.45  4689.9 1415.13  4845.5 1409.89  4871.8 1407.10  4897.3 1406.28
  4902.9 1404.96  4910.4 1404.81  4932.1 1399.57  4942.4 1398.31  4954.0 1395.68
  4969.8 1393.51  4985.8 1392.54  4991.5 1390.93  4995.0 1390.88  4995.3 1390.38
  4999.0 1390.88  5031.8 1394.74  5123.0 1400.37  5152.7 1403.16  5171.6 1405.79
  5206.8 1408.17  5214.6 1409.89  5231.2 1411.69  5260.9 1413.17  5285.2 1415.83
  5300.7 1416.24  5309.6 1417.43  5369.0 1421.15  5393.4 1425.26  5435.7 1428.43
#Mann=3,-1,0
  4603.5    0.07       0  4995.0    0.05       0  4999.0    0.07       0
Bank Sta=4995,4999
Exp/Cntr=0.3,0.1

Chan Stop Cuts=-1