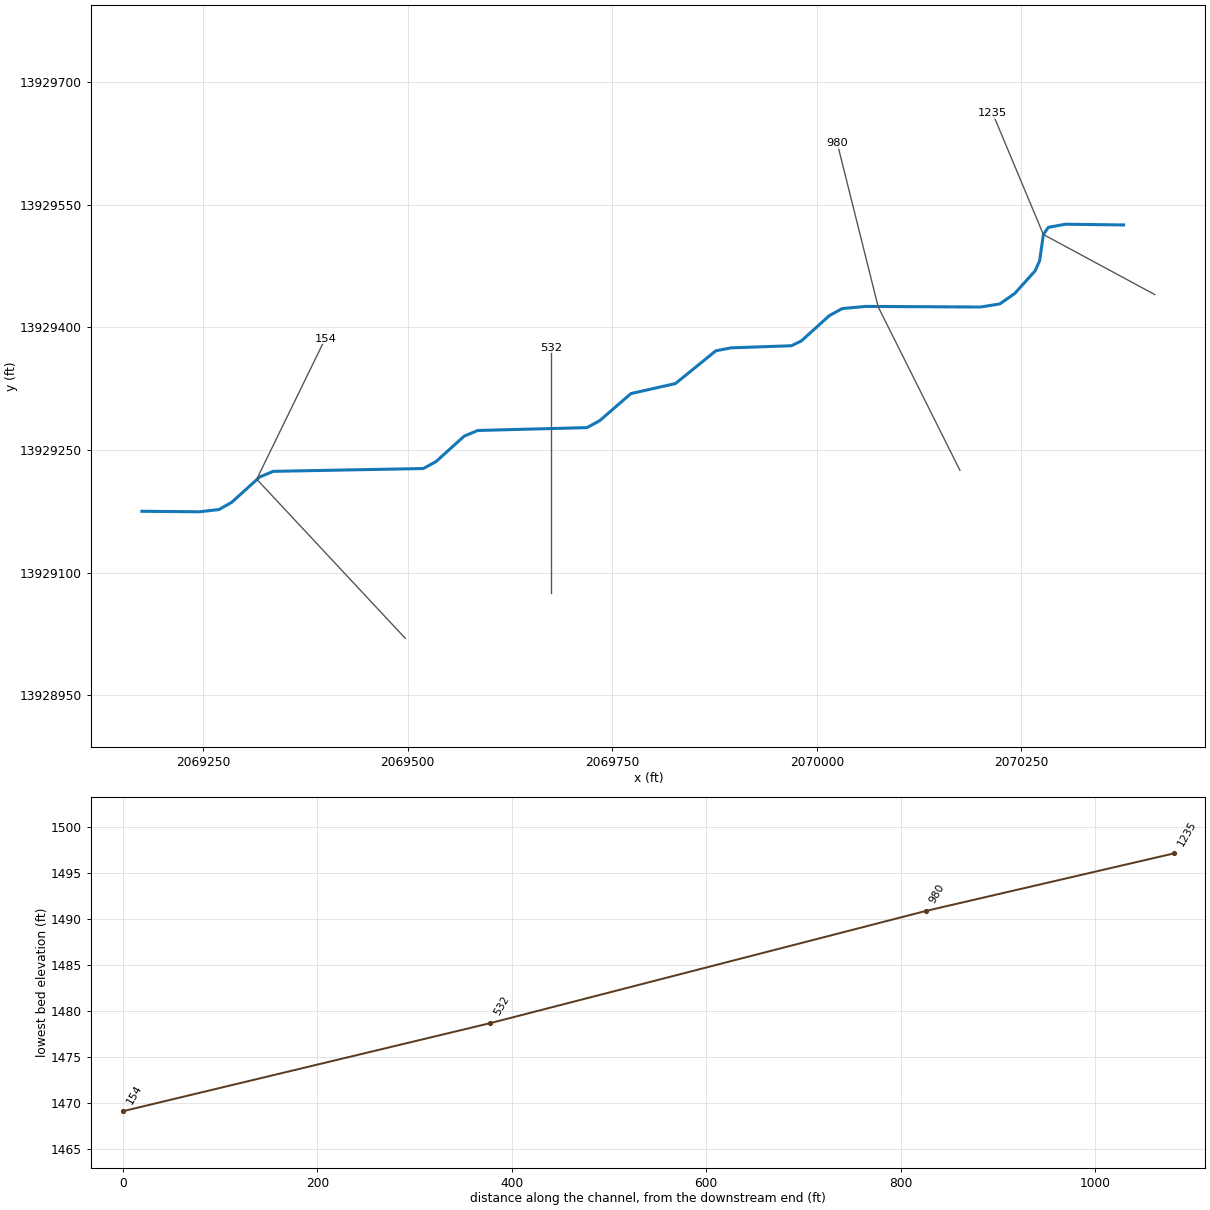
--- Stream0242_DS.prj (project) ---

Proj Title=Stream0242_DS Base Level Engineering
Current Plan=p01
Default Exp/Contr=0.3,0.1
English Units
Geom File=g01
Flow File=f01
Plan File=p01
BEGIN DESCRIPTION:
Stream0242_DS
END DESCRIPTION:

--- Stream0242_DS.p01 (plan) ---

Plan Title=Multiple Run
Short Identifier=Multiple
Geom File=g01
Flow File=f01
Subcritical Flow
K Sum by GR= 0
Std Step Tol= 0.01
Critical Tol= 0.01
Num of Std Step Trials= 20
Max Error Tol= 0.3
Flow Tol Ratio= 0.001
Split Flow NTrial= 30
Split Flow Tol= 0.02
Split Flow Ratio= 0.02
Log Output Level= 0
Friction Slope Method= 1
Unsteady Friction Slope Method= 2
Unsteady Bridges Friction Slope Method= 1
Parabolic Critical Depth
Global Vel Dist=  1 , 1 , 1
Global Log Level= 0
CheckData=True
Encroach Param= -1, 0, 0, 0
BEGIN DESCRIPTION:
Multiple Run
END DESCRIPTION:

--- Stream0242_DS.f01 (steady flow) ---

Flow Title=Multiple
Number of Profiles=7
Profile Names=10-year,25-year,50-year,1pct_min,100-year,1pct_plu,500-year
River Rch & RM= Stream0242_DS,Reach-1,1235
     710    1194    1652    1114    2222    4434    3976
Boundary for River Rch & Prof#=Stream0242_DS,Reach-1,1
Up Type=0
Dn Type=3
Dn Slope=0.005
Boundary for River Rch & Prof#=Stream0242_DS,Reach-1,2
Up Type=0
Dn Type=3
Dn Slope=0.005
Boundary for River Rch & Prof#=Stream0242_DS,Reach-1,3
Up Type=0
Dn Type=3
Dn Slope=0.005
Boundary for River Rch & Prof#=Stream0242_DS,Reach-1,4
Up Type=0
Dn Type=3
Dn Slope=0.005
Boundary for River Rch & Prof#=Stream0242_DS,Reach-1,5
Up Type=0
Dn Type=3
Dn Slope=0.005
Boundary for River Rch & Prof#=Stream0242_DS,Reach-1,6
Up Type=0
Dn Type=3
Dn Slope=0.005
Boundary for River Rch & Prof#=Stream0242_DS,Reach-1,7
Up Type=0
Dn Type=3
Dn Slope=0.005

--- Stream0242_DS.g01 (geometry) ---

Geom Title=Existing Conditions

River Reach=Stream0242_DS,Reach-1
Reach XY= 30
      2070375.00     13929525.00      2070304.20     13929525.93
      2070283.12     13929522.14      2070276.99     13929513.32
      2070272.44     13929481.26      2070266.88     13929468.93
      2070242.11     13929441.35      2070223.74     13929428.48
      2070200.20     13929424.68      2070059.82     13929425.43
      2070030.94     13929422.74      2070015.35     13929414.15
      2069981.03     13929383.19      2069969.02     13929377.36
      2069895.09     13929374.77      2069876.58     13929371.17
      2069827.18     13929331.11      2069772.82     13929318.88
      2069734.67     13929285.80      2069719.07     13929277.25
      2069585.51     13929273.77      2069568.95     13929266.85
      2069534.65     13929235.85      2069519.06     13929227.26
      2069335.50     13929223.80      2069318.93     13929216.90
      2069284.64     13929185.86      2069269.13     13929177.10
      2069245.26     13929174.37      2069175.00     13929175.00

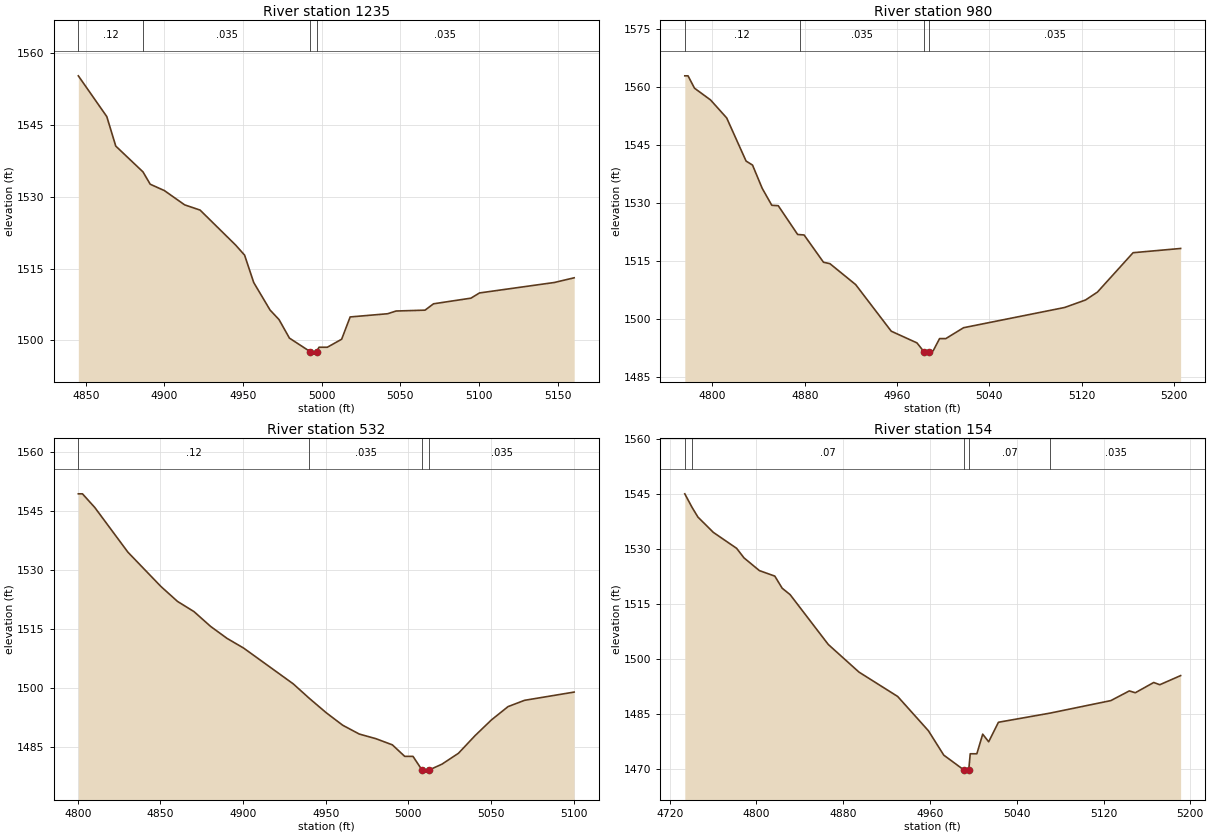
Type RM Length L Ch R = 1,1235,255,255,255
BEGIN DESCRIPTION:
Stream0242_DS 4.0
END DESCRIPTION:
XS GIS Cut Line= 3
      2070413.17     13929439.91      2070276.99     13929513.32
      2070215.05     13929661.38
#Sta/Elev= 30
  4845.3 1555.32  4863.4 1546.79  4869.1 1540.62  4886.4 1535.22  4891.0 1532.64
  4900.0 1531.31  4912.9 1528.32  4922.7 1527.23  4945.3 1519.91  4951.0 1517.80
  4956.8 1512.07  4967.2 1506.31  4972.9 1504.31  4979.5 1500.44  4992.8 1497.59
  4993.0 1497.09  4996.5 1497.09  4996.8 1497.59  4998.3 1498.53  5003.6 1498.53
  5012.7 1500.21  5018.1 1504.87  5041.9 1505.54  5047.3 1506.11  5065.7 1506.29
  5071.1 1507.62  5094.9 1508.80  5100.3 1509.89  5147.9 1512.08  5160.5 1513.06
#Mann=4,-1,0
  4845.3    0.12       0  4886.4   0.035       0  4992.8   0.035       0
  4996.8   0.035       0
Bank Sta=4992.8,4996.8
Exp/Cntr=0.3,0.1

Type RM Length L Ch R = 1,980,448,448,448
BEGIN DESCRIPTION:
Stream0242_DS 2.0
END DESCRIPTION:
XS GIS Cut Line= 3
      2070174.99     13929225.02      2070075.00     13929425.00
      2070025.01     13929624.96
#Sta/Elev= 30
  4776.0 1562.91  4778.8 1562.91  4784.4 1559.71  4798.3 1556.67  4812.3 1552.01
  4829.1 1540.84  4834.7 1539.80  4843.1 1533.77  4851.4 1529.39  4857.0 1529.28
  4873.8 1521.83  4875.6 1521.79  4879.4 1521.70  4896.2 1514.64  4901.8 1514.27
  4924.1 1508.85  4954.9 1496.79  4977.2 1493.76  4983.6 1491.35  4983.9 1490.85
  4987.6 1491.35  4991.2 1491.69  4996.8 1494.87  5002.2 1494.87  5017.6 1497.69
  5105.2 1502.93  5123.3 1504.87  5133.6 1506.91  5164.5 1517.11  5205.7 1518.21
#Mann=4,-1,0
  4776.0    0.12       0  4875.6   0.035       0  4983.6   0.035       0
  4987.6   0.035       0
Bank Sta=4983.6,4987.6
Exp/Cntr=0.3,0.1

Type RM Length L Ch R = 1,532,378,378,378
BEGIN DESCRIPTION:
Stream0242_DS 1.0
END DESCRIPTION:
XS GIS Cut Line= 3
      2069675.00     13929074.99      2069675.00     13929275.00
      2069675.00     13929374.99
#Sta/Elev= 30
  4800.3 1549.36  4802.8 1549.36  4810.3 1545.87  4830.3 1534.54  4850.3 1525.82
  4860.3 1522.04  4870.3 1519.44  4880.3 1515.70  4890.3 1512.64  4900.3 1510.19
  4930.3 1501.11  4940.0 1497.44  4950.3 1493.76  4960.3 1490.58  4970.3 1488.35
  4980.3 1487.18  4990.3 1485.61  4997.8 1482.68  5002.8 1482.68  5008.3 1479.18
  5008.6 1478.68  5012.1 1478.68  5012.3 1479.18  5020.3 1480.70  5030.3 1483.47
  5040.3 1487.93  5050.3 1491.96  5060.3 1495.32  5070.3 1496.92  5100.3 1499.01
#Mann=4,-1,0
  4800.3    0.12       0  4940.0   0.035       0  5008.3   0.035       0
  5012.3   0.035       0
Bank Sta=5008.3,5012.3
Exp/Cntr=0.3,0.1

Type RM Length L Ch R = 1,154,0,0,0
BEGIN DESCRIPTION:
Stream0242_DS 0.0
END DESCRIPTION:
XS GIS Cut Line= 3
      2069496.93     13929019.70      2069315.33     13929214.20
      2069399.05     13929385.98
#Sta/Elev= 30
  4733.9 1545.09  4740.6 1541.39  4746.0 1538.75  4760.2 1534.57  4781.7 1530.21
  4788.5 1527.60  4802.7 1524.13  4816.9 1522.63  4823.7 1519.32  4831.0 1517.58
  4866.2 1503.97  4894.5 1496.43  4930.2 1489.77  4958.5 1480.43  4972.7 1473.76
  4991.7 1469.62  4992.0 1469.12  4995.7 1469.62  4997.1 1474.13  5003.2 1474.13
  5008.6 1479.48  5014.1 1477.40  5023.1 1482.73  5070.9 1485.24  5126.8 1488.65
  5143.8 1491.29  5149.3 1490.79  5166.3 1493.59  5171.9 1492.98  5191.1 1495.47
#Mann=5,-1,0
  4733.9    0.12       0  4740.6    0.07       0  4991.7    0.05       0
  4995.7    0.07       0  5070.9   0.035       0
Bank Sta=4991.7,4995.7
Exp/Cntr=0.3,0.1

Chan Stop Cuts=-1