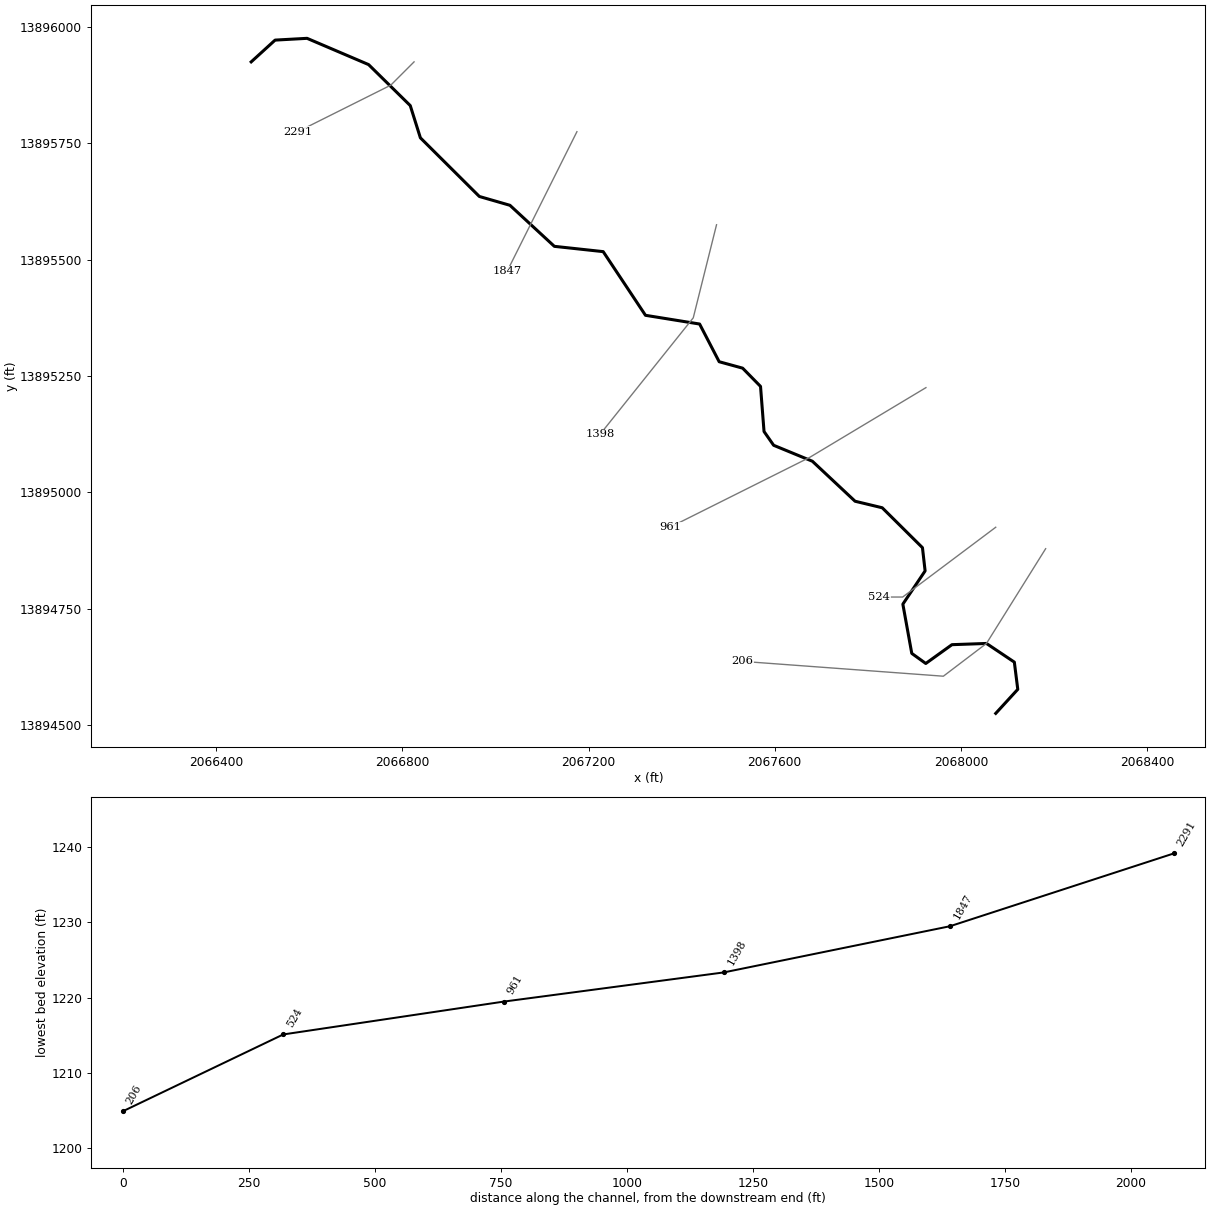
--- Stream0243_DS.prj (project) ---

Proj Title=Stream0243_DS Base Level Engineering
Current Plan=p01
Default Exp/Contr=0.3,0.1
English Units
Geom File=g01
Flow File=f01
Plan File=p01
BEGIN DESCRIPTION:
Stream0243_DS
END DESCRIPTION:

--- Stream0243_DS.p01 (plan) ---

Plan Title=Multiple Run
Short Identifier=Multiple
Geom File=g01
Flow File=f01
Subcritical Flow
K Sum by GR= 0
Std Step Tol= 0.01
Critical Tol= 0.01
Num of Std Step Trials= 20
Max Error Tol= 0.3
Flow Tol Ratio= 0.001
Split Flow NTrial= 30
Split Flow Tol= 0.02
Split Flow Ratio= 0.02
Log Output Level= 0
Friction Slope Method= 1
Unsteady Friction Slope Method= 2
Unsteady Bridges Friction Slope Method= 1
Parabolic Critical Depth
Global Vel Dist=  1 , 1 , 1
Global Log Level= 0
CheckData=True
Encroach Param= -1, 0, 0, 0
BEGIN DESCRIPTION:
Multiple Run
END DESCRIPTION:

--- Stream0243_DS.f01 (steady flow) ---

Flow Title=Multiple
Number of Profiles=7
Profile Names=10-year,25-year,50-year,1pct_min,100-year,1pct_plu,500-year
River Rch & RM= Stream0243_DS,Reach-1,2291
     206     310     397     248     495     987     757
Boundary for River Rch & Prof#=Stream0243_DS,Reach-1,1
Up Type=0
Dn Type=3
Dn Slope=0.005
Boundary for River Rch & Prof#=Stream0243_DS,Reach-1,2
Up Type=0
Dn Type=3
Dn Slope=0.005
Boundary for River Rch & Prof#=Stream0243_DS,Reach-1,3
Up Type=0
Dn Type=3
Dn Slope=0.005
Boundary for River Rch & Prof#=Stream0243_DS,Reach-1,4
Up Type=0
Dn Type=3
Dn Slope=0.005
Boundary for River Rch & Prof#=Stream0243_DS,Reach-1,5
Up Type=0
Dn Type=3
Dn Slope=0.005
Boundary for River Rch & Prof#=Stream0243_DS,Reach-1,6
Up Type=0
Dn Type=3
Dn Slope=0.005
Boundary for River Rch & Prof#=Stream0243_DS,Reach-1,7
Up Type=0
Dn Type=3
Dn Slope=0.005

--- Stream0243_DS.g01 (geometry) ---

Geom Title=Existing Conditions

River Reach=Stream0243_DS,Reach-1
Reach XY= 30
      2066475.00     13895925.00      2066526.40     13895971.81
      2066595.08     13895975.61      2066727.31     13895919.18
      2066816.85     13895831.07      2066838.63     13895761.79
      2066965.32     13895635.78      2067031.04     13895616.82
      2067126.50     13895528.63      2067231.45     13895517.25
      2067322.33     13895380.42      2067438.63     13895361.67
      2067480.67     13895280.67      2067531.08     13895266.85
      2067569.54     13895227.66      2067577.08     13895130.71
      2067597.72     13895101.11      2067681.02     13895066.81
      2067772.72     13894980.87      2067831.07     13894966.85
      2067917.53     13894881.07      2067923.22     13894831.14
      2067875.39     13894759.72      2067894.56     13894653.90
      2067924.65     13894632.22      2067980.89     13894672.63
      2068055.07     13894675.25      2068114.97     13894635.12
      2068122.35     13894576.66      2068075.00     13894525.00

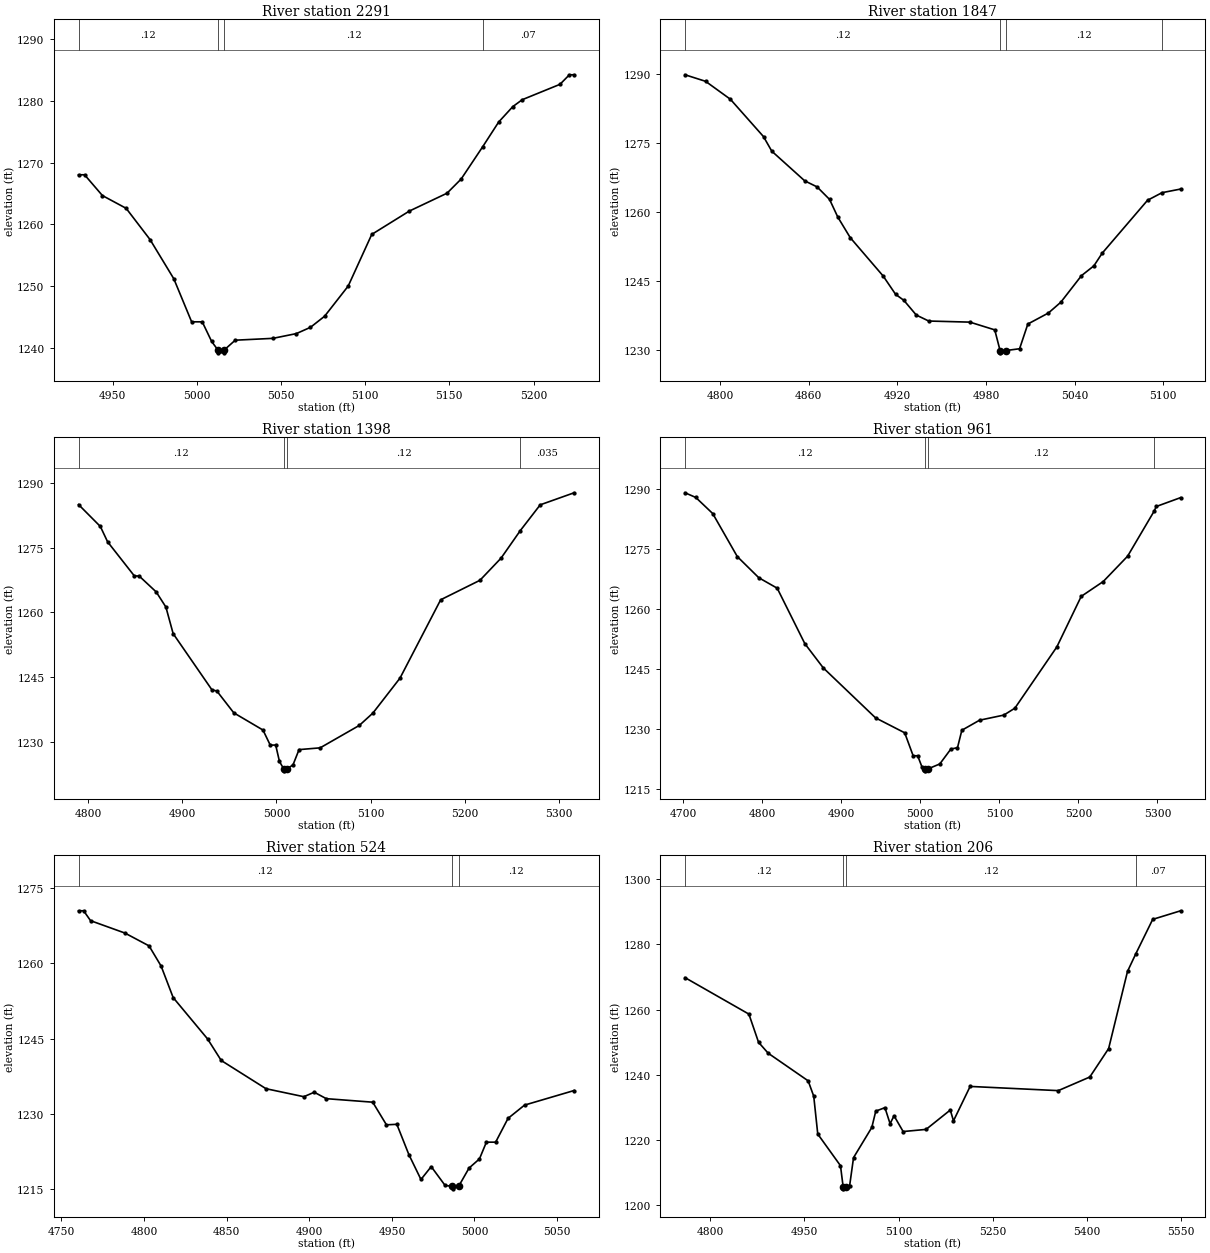
Type RM Length L Ch R = 1,2291,444,444,444
BEGIN DESCRIPTION:
Stream0243_DS 5.0
END DESCRIPTION:
XS GIS Cut Line= 3
      2066825.03     13895925.03      2066775.00     13895875.00
      2066574.96     13895774.98
#Sta/Elev= 30
  4929.7 1268.04  4933.3 1268.04  4943.9 1264.67  4958.0 1262.60  4972.2 1257.53
  4986.3 1251.18  4996.9 1244.19  5003.2 1244.19  5008.8 1241.00  5012.4 1239.66
  5012.7 1239.16  5016.2 1239.16  5016.4 1239.66  5022.8 1241.21  5045.2 1241.51
  5059.1 1242.28  5067.5 1243.30  5075.9 1245.10  5089.9 1249.99  5103.9 1258.37
  5126.2 1262.15  5148.6 1265.05  5157.0 1267.35  5169.8 1272.59  5179.3 1276.60
  5187.7 1279.10  5193.3 1280.22  5215.7 1282.71  5221.3 1284.26  5224.1 1284.26
#Mann=4,-1,0
  4929.7    0.12       0  5012.4    0.05       0  5016.4    0.12       0
  5169.8    0.07       0
Bank Sta=5012.4,5016.4
Exp/Cntr=0.3,0.1

Type RM Length L Ch R = 1,1847,449,449,449
BEGIN DESCRIPTION:
Stream0243_DS 4.0
END DESCRIPTION:
XS GIS Cut Line= 3
      2067174.99     13895774.97      2067075.00     13895575.00
      2067024.99     13895474.98
#Sta/Elev= 30
  4776.4 1289.89  4790.3 1288.47  4807.1 1284.57  4829.5 1276.46  4835.1 1273.30
  4857.4 1266.85  4865.8 1265.53  4874.2 1262.82  4879.8 1258.97  4888.2 1254.51
  4910.5 1246.17  4918.9 1242.20  4924.5 1240.89  4932.9 1237.70  4941.3 1236.40
  4969.2 1236.16  4986.0 1234.48  4989.6 1229.99  4989.8 1229.49  4993.6 1229.99
  5002.8 1230.38  5008.4 1235.75  5022.3 1238.14  5030.7 1240.48  5044.7 1246.26
  5053.1 1248.39  5058.7 1251.13  5089.4 1262.63  5099.2 1264.28  5111.8 1265.07
#Mann=4,-1,0
  4776.4    0.12       0  4989.6    0.05       0  4993.6    0.12       0
  5099.2    0.07       0
Bank Sta=4989.6,4993.6
Exp/Cntr=0.3,0.1

Type RM Length L Ch R = 1,1398,437,437,437
BEGIN DESCRIPTION:
Stream0243_DS 3.0
END DESCRIPTION:
XS GIS Cut Line= 3
      2067475.00     13895575.01      2067425.00     13895375.00
      2067225.01     13895125.01
#Sta/Elev= 30
  4789.8 1284.97  4813.0 1279.89  4820.7 1276.34  4849.1 1268.45  4854.2 1268.43
  4872.3 1264.75  4882.6 1261.25  4890.3 1255.10  4931.5 1242.09  4936.7 1241.82
  4954.7 1236.77  4985.7 1232.79  4993.4 1229.31  4999.2 1229.31  5003.2 1225.52
  5007.6 1223.85  5007.8 1223.35  5011.6 1223.85  5017.6 1224.74  5024.0 1228.26
  5046.4 1228.67  5088.0 1233.86  5102.4 1236.71  5131.2 1244.80  5174.4 1262.93
  5216.1 1267.44  5238.5 1272.56  5259.0 1278.95  5280.1 1284.90  5316.1 1287.69
#Mann=4,-1,0
  4789.8    0.12       0  5007.6    0.05       0  5011.6    0.12       0
  5259.0   0.035       0
Bank Sta=5007.6,5011.6
Exp/Cntr=0.3,0.1

Type RM Length L Ch R = 1,961,437,437,437
BEGIN DESCRIPTION:
Stream0243_DS 2.0
END DESCRIPTION:
XS GIS Cut Line= 3
      2067925.00     13895225.00      2067675.00     13895075.00
      2067374.96     13894924.98
#Sta/Elev= 30
  4702.3 1289.00  4715.9 1287.83  4737.3 1283.81  4768.4 1273.05  4795.6 1267.76
  4818.9 1265.14  4853.9 1251.26  4877.2 1245.21  4943.3 1232.72  4980.2 1228.98
  4990.9 1223.24  4996.6 1223.24  5002.2 1220.37  5005.8 1219.97  5006.1 1219.47
  5009.8 1219.97  5024.6 1221.19  5038.6 1224.92  5047.0 1225.26  5052.5 1229.62
  5074.9 1232.13  5105.6 1233.41  5119.6 1235.14  5172.7 1250.46  5203.5 1263.09
  5231.4 1266.81  5262.2 1273.14  5295.7 1284.38  5298.5 1285.57  5329.3 1287.79
#Mann=4,-1,0
  4702.3    0.12       0  5005.8    0.05       0  5009.8    0.12       0
  5295.7   0.035       0
Bank Sta=5005.8,5009.8
Exp/Cntr=0.3,0.1

Type RM Length L Ch R = 1,524,318,318,318
BEGIN DESCRIPTION:
Stream0243_DS 1.0
END DESCRIPTION:
XS GIS Cut Line= 3
      2068074.99     13894924.99      2067875.00     13894775.00
      2067824.99     13894775.00
#Sta/Elev= 30
  4760.3 1270.40  4763.4 1270.40  4767.6 1268.43  4788.4 1265.97  4803.0 1263.42
  4810.3 1259.41  4817.6 1253.14  4838.4 1244.93  4846.7 1240.63  4873.8 1235.02
  4896.7 1233.43  4903.0 1234.32  4910.3 1233.04  4938.4 1232.34  4946.7 1227.84
  4953.0 1227.94  4960.3 1221.90  4967.6 1216.97  4973.8 1219.53  4982.2 1215.79
  4986.4 1215.61  4986.7 1215.11  4990.4 1215.61  4996.7 1219.24  5003.0 1221.06
  5007.2 1224.39  5012.8 1224.39  5020.3 1229.12  5030.3 1231.76  5060.3 1234.66
#Mann=3,-1,0
  4760.3    0.12       0  4986.4    0.05       0  4990.4    0.12       0
Bank Sta=4986.4,4990.4
Exp/Cntr=0.3,0.1

Type RM Length L Ch R = 1,206,0,0,0
BEGIN DESCRIPTION:
Stream0243_DS 0.0
END DESCRIPTION:
XS GIS Cut Line= 4
      2068182.26     13894878.89      2068055.07     13894675.25
      2067962.45     13894604.87      2067530.65     13894636.75
#Sta/Elev= 30
  4759.9 1269.79  4861.6 1258.59  4877.0 1249.93  4892.3 1246.58  4956.0 1238.09
  4964.9 1233.36  4971.3 1221.74  5007.5 1212.02  5011.8 1205.41  5012.0 1204.91
  5015.8 1205.41  5022.1 1205.91  5028.3 1214.50  5057.4 1223.77  5063.7 1228.78
  5078.3 1229.85  5086.5 1224.92  5092.8 1227.35  5107.3 1222.51  5143.8 1223.17
  5182.4 1229.12  5187.5 1225.80  5214.0 1236.37  5354.4 1235.08  5404.6 1239.26
  5434.6 1248.00  5464.7 1271.72  5477.9 1277.12  5504.8 1287.69  5549.3 1290.33
#Mann=4,-1,0
  4759.9    0.12       0  5011.8    0.05       0  5015.8    0.12       0
  5477.9    0.07       0
Bank Sta=5011.8,5015.8
Exp/Cntr=0.3,0.1

Chan Stop Cuts=-1