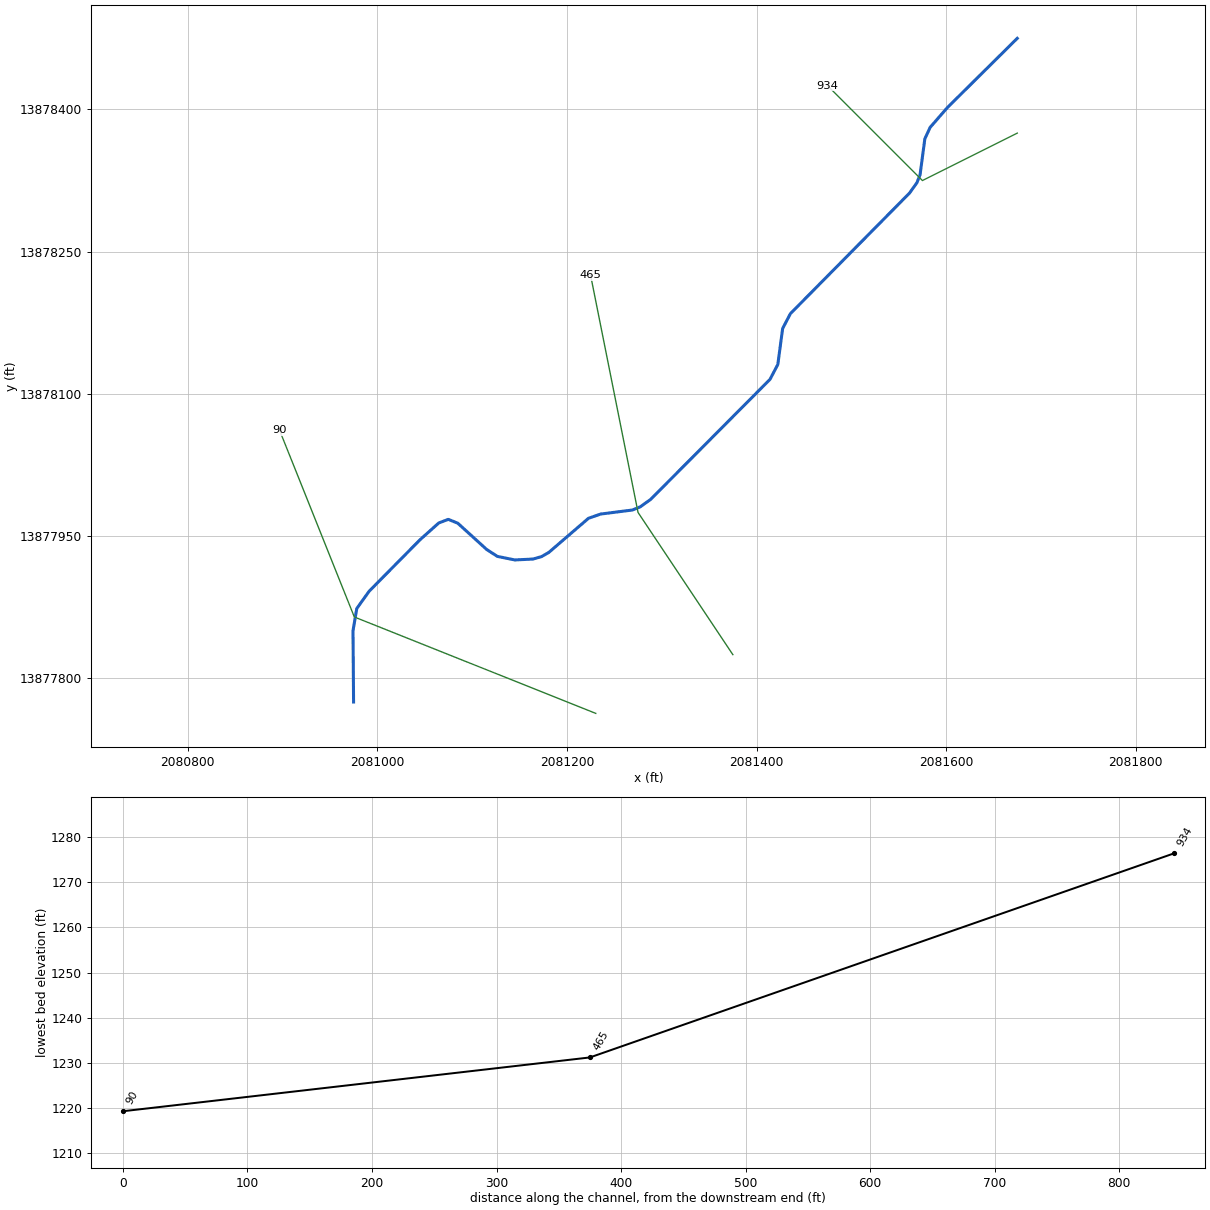
--- Stream0244_DS.prj (project) ---

Proj Title=Stream0244_DS Base Level Engineering
Current Plan=p01
Default Exp/Contr=0.3,0.1
English Units
Geom File=g01
Flow File=f01
Plan File=p01
BEGIN DESCRIPTION:
Stream0244_DS
END DESCRIPTION:

--- Stream0244_DS.p01 (plan) ---

Plan Title=Multiple Run
Short Identifier=Multiple
Geom File=g01
Flow File=f01
Subcritical Flow
K Sum by GR= 0
Std Step Tol= 0.01
Critical Tol= 0.01
Num of Std Step Trials= 20
Max Error Tol= 0.3
Flow Tol Ratio= 0.001
Split Flow NTrial= 30
Split Flow Tol= 0.02
Split Flow Ratio= 0.02
Log Output Level= 0
Friction Slope Method= 1
Unsteady Friction Slope Method= 2
Unsteady Bridges Friction Slope Method= 1
Parabolic Critical Depth
Global Vel Dist=  1 , 1 , 1
Global Log Level= 0
CheckData=True
Encroach Param= -1, 0, 0, 0
BEGIN DESCRIPTION:
Multiple Run
END DESCRIPTION:

--- Stream0244_DS.f01 (steady flow) ---

Flow Title=Multiple
Number of Profiles=7
Profile Names=10-year,25-year,50-year,1pct_min,100-year,1pct_plu,500-year
River Rch & RM= Stream0244_DS,Reach-1,934
     273     422     551     353     703    1404    1124
Boundary for River Rch & Prof#=Stream0244_DS,Reach-1,1
Up Type=0
Dn Type=3
Dn Slope=0.005
Boundary for River Rch & Prof#=Stream0244_DS,Reach-1,2
Up Type=0
Dn Type=3
Dn Slope=0.005
Boundary for River Rch & Prof#=Stream0244_DS,Reach-1,3
Up Type=0
Dn Type=3
Dn Slope=0.005
Boundary for River Rch & Prof#=Stream0244_DS,Reach-1,4
Up Type=0
Dn Type=3
Dn Slope=0.005
Boundary for River Rch & Prof#=Stream0244_DS,Reach-1,5
Up Type=0
Dn Type=3
Dn Slope=0.005
Boundary for River Rch & Prof#=Stream0244_DS,Reach-1,6
Up Type=0
Dn Type=3
Dn Slope=0.005
Boundary for River Rch & Prof#=Stream0244_DS,Reach-1,7
Up Type=0
Dn Type=3
Dn Slope=0.005

--- Stream0244_DS.g01 (geometry) ---

Geom Title=Existing Conditions

River Reach=Stream0244_DS,Reach-1
Reach XY= 30
      2081675.00     13878475.00      2081601.20     13878401.86
      2081583.11     13878381.07      2081577.52     13878368.96
      2081572.48     13878331.04      2081569.15     13878322.71
      2081561.37     13878311.79      2081435.78     13878184.68
      2081427.54     13878168.95      2081422.47     13878131.05
      2081414.22     13878115.32      2081288.22     13877988.62
      2081277.30     13877980.83      2081268.97     13877977.49
      2081235.70     13877973.26      2081222.81     13877968.82
      2081180.93     13877932.79      2081173.26     13877928.37
      2081164.30     13877925.80      2081145.13     13877924.83
      2081126.63     13877928.61      2081115.32     13877935.94
      2081084.86     13877963.62      2081074.90     13877967.66
      2081064.92     13877963.90      2081044.90     13877945.98
      2080991.43     13877891.84      2080978.38     13877873.63
      2080974.41     13877850.26      2080975.00     13877775.00

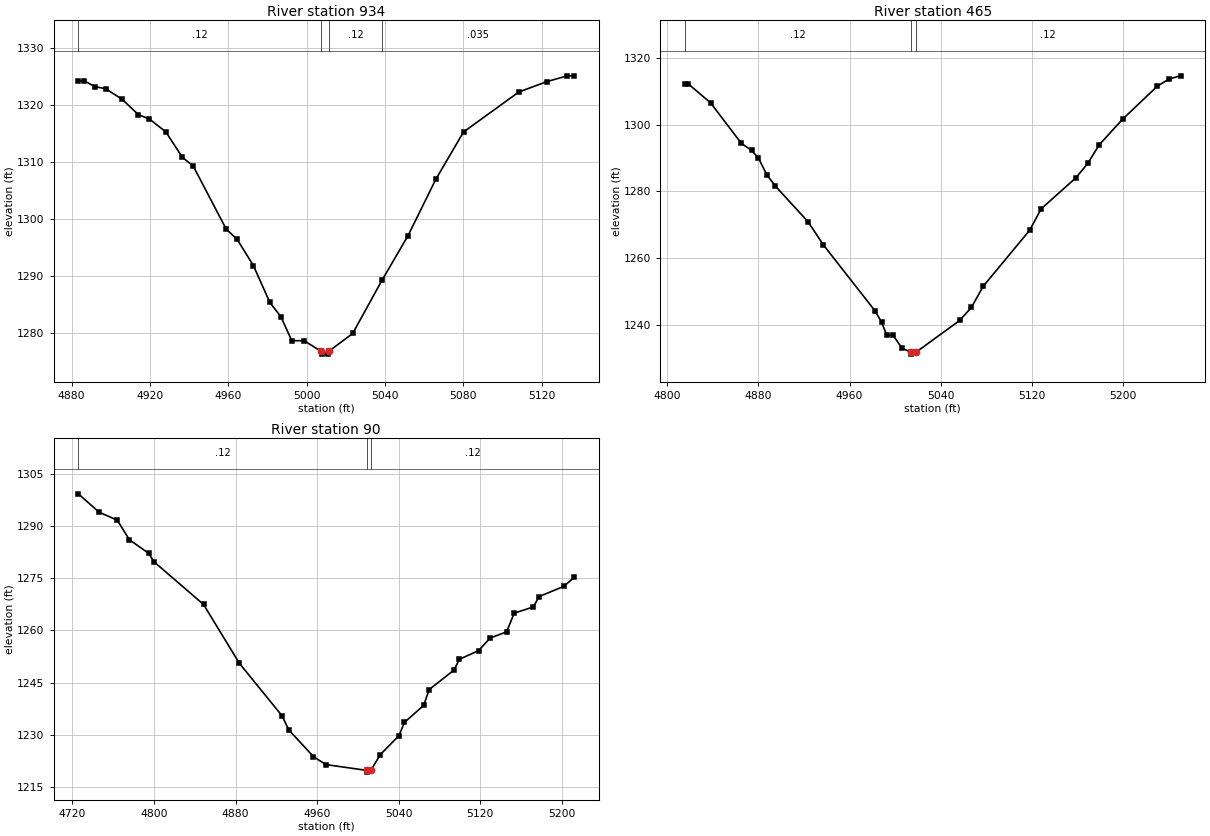
Type RM Length L Ch R = 1,934,469,469,469
BEGIN DESCRIPTION:
Stream0244_DS 2.0
END DESCRIPTION:
XS GIS Cut Line= 3
      2081675.00     13878375.00      2081575.00     13878325.00
      2081475.02     13878424.98
#Sta/Elev= 30
  4883.4 1324.21  4886.2 1324.21  4891.8 1323.19  4897.4 1322.79  4905.8 1320.95
  4914.1 1318.26  4919.7 1317.51  4928.1 1315.25  4936.5 1310.83  4942.1 1309.26
  4958.9 1298.26  4964.5 1296.46  4972.8 1291.88  4981.2 1285.42  4986.8 1282.96
  4992.4 1278.74  4998.7 1278.74  5007.3 1276.89  5007.6 1276.39  5011.1 1276.39
  5011.3 1276.89  5023.5 1280.00  5038.5 1289.33  5051.8 1297.13  5065.9 1306.93
  5080.1 1315.24  5108.3 1322.22  5122.5 1324.03  5133.1 1325.06  5136.6 1325.06
#Mann=4,-1,0
  4883.4    0.12       0  5007.3    0.05       0  5011.3    0.12       0
  5038.5   0.035       0
Bank Sta=5007.3,5011.3
Exp/Cntr=0.3,0.1

Type RM Length L Ch R = 1,465,375,375,375
BEGIN DESCRIPTION:
Stream0244_DS 1.0
END DESCRIPTION:
XS GIS Cut Line= 3
      2081375.01     13877824.98      2081275.00     13877975.00
      2081224.99     13878225.04
#Sta/Elev= 30
  4815.3 1312.19  4818.3 1312.19  4837.9 1306.51  4864.9 1294.38  4873.9 1292.24
  4879.9 1289.97  4887.4 1284.90  4894.9 1281.51  4923.5 1270.86  4937.0 1263.90
  4982.1 1244.24  4988.1 1240.75  4992.6 1236.82  4998.2 1236.82  5005.8 1233.05
  5014.0 1231.68  5014.2 1231.18  5018.0 1231.68  5056.8 1241.32  5067.0 1245.23
  5077.2 1251.47  5118.0 1268.28  5128.2 1274.74  5158.8 1284.07  5169.0 1288.32
  5179.2 1293.94  5199.6 1301.57  5230.2 1311.50  5240.4 1313.64  5250.6 1314.59
#Mann=3,-1,0
  4815.3    0.12       0  5014.0    0.05       0  5018.0    0.12       0
Bank Sta=5014,5018
Exp/Cntr=0.3,0.1

Type RM Length L Ch R = 1,90,0,0,0
BEGIN DESCRIPTION:
Stream0244_DS 0.0
END DESCRIPTION:
XS GIS Cut Line= 3
      2081230.47     13877763.02      2080975.81     13877864.68
      2080896.95     13878061.58
#Sta/Elev= 30
  4725.8 1299.26  4746.2 1293.98  4764.0 1291.68  4775.9 1286.06  4794.7 1282.18
  4800.1 1279.70  4848.6 1267.46  4883.7 1250.56  4925.5 1235.49  4932.2 1231.41
  4956.4 1223.72  4968.6 1221.43  5008.7 1219.76  5008.9 1219.26  5012.7 1219.76
  5021.9 1224.27  5040.3 1229.76  5045.7 1233.57  5064.5 1238.44  5069.9 1243.00
  5094.1 1248.55  5099.5 1251.70  5118.3 1254.17  5129.6 1257.78  5145.8 1259.58
  5153.3 1264.96  5172.2 1266.75  5177.5 1269.70  5201.8 1272.64  5212.1 1275.24
#Mann=3,-1,0
  4725.8    0.12       0  5008.7    0.05       0  5012.7    0.12       0
Bank Sta=5008.7,5012.7
Exp/Cntr=0.3,0.1

Chan Stop Cuts=-1