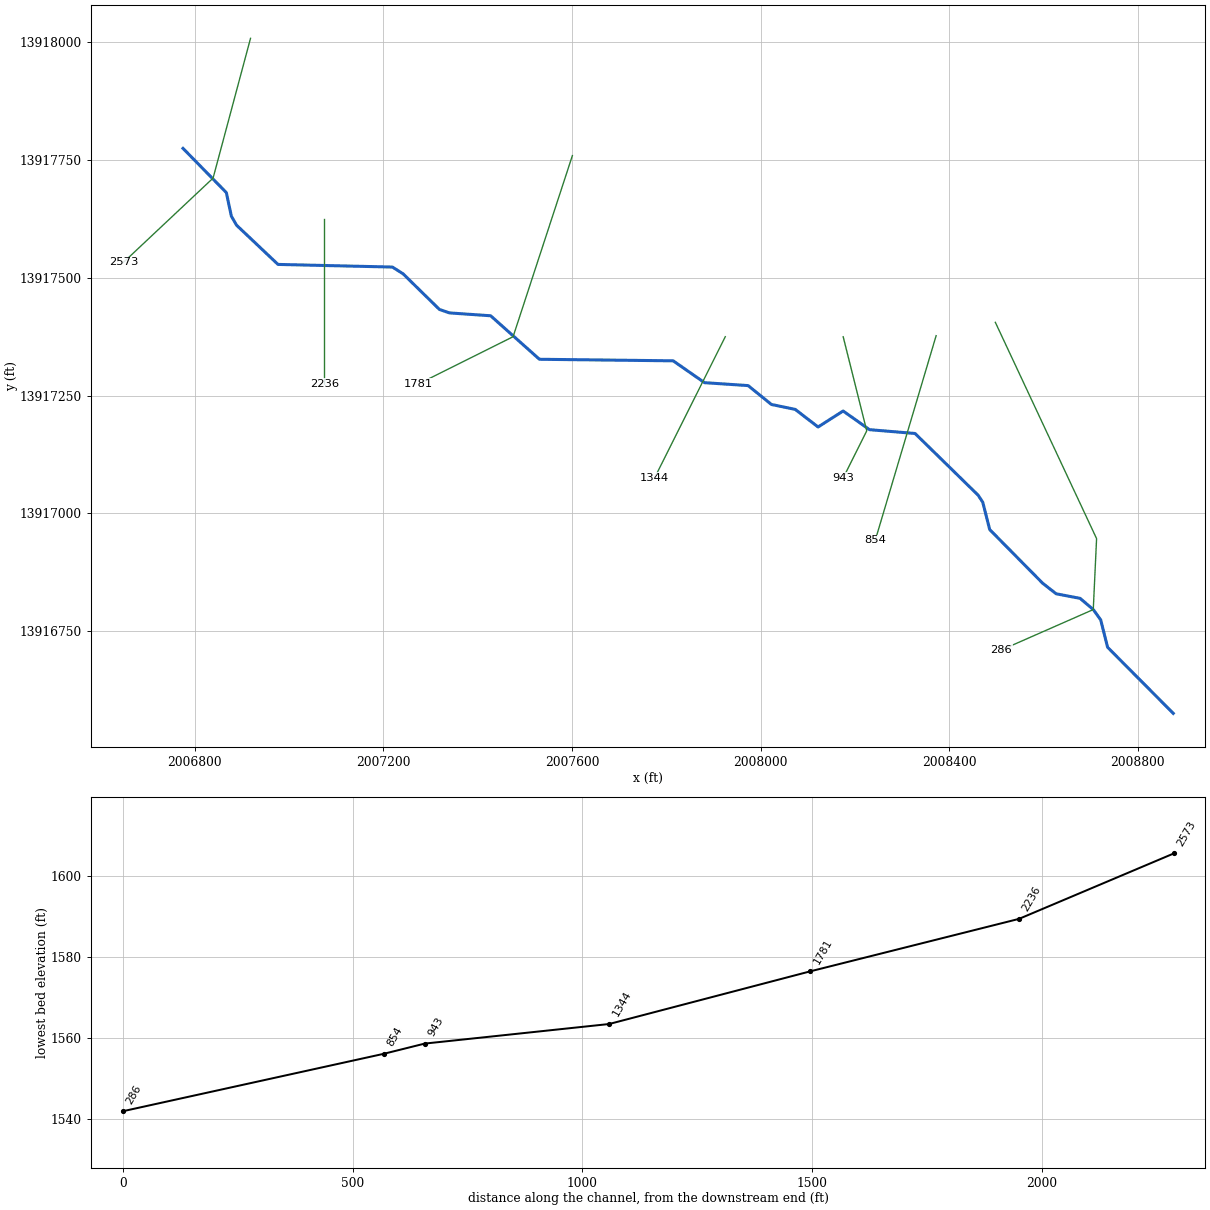
--- Stream0246_DS.prj (project) ---

Proj Title=Stream0246_DS Base Level Engineering
Current Plan=p01
Default Exp/Contr=0.3,0.1
English Units
Geom File=g01
Flow File=f01
Plan File=p01
BEGIN DESCRIPTION:
Stream0246_DS
END DESCRIPTION:

--- Stream0246_DS.p01 (plan) ---

Plan Title=Multiple Run
Short Identifier=Multiple
Geom File=g01
Flow File=f01
Subcritical Flow
K Sum by GR= 0
Std Step Tol= 0.01
Critical Tol= 0.01
Num of Std Step Trials= 20
Max Error Tol= 0.3
Flow Tol Ratio= 0.001
Split Flow NTrial= 30
Split Flow Tol= 0.02
Split Flow Ratio= 0.02
Log Output Level= 0
Friction Slope Method= 1
Unsteady Friction Slope Method= 2
Unsteady Bridges Friction Slope Method= 1
Parabolic Critical Depth
Global Vel Dist=  1 , 1 , 1
Global Log Level= 0
CheckData=True
Encroach Param= -1, 0, 0, 0
BEGIN DESCRIPTION:
Multiple Run
END DESCRIPTION:

--- Stream0246_DS.f01 (steady flow) ---

Flow Title=Multiple
Number of Profiles=7
Profile Names=10-year,25-year,50-year,1pct_min,100-year,1pct_plu,500-year
River Rch & RM= Stream0246_DS,Reach-1,2573
     460     754    1028     683    1363    2719    2368
Boundary for River Rch & Prof#=Stream0246_DS,Reach-1,1
Up Type=0
Dn Type=3
Dn Slope=0.005
Boundary for River Rch & Prof#=Stream0246_DS,Reach-1,2
Up Type=0
Dn Type=3
Dn Slope=0.005
Boundary for River Rch & Prof#=Stream0246_DS,Reach-1,3
Up Type=0
Dn Type=3
Dn Slope=0.005
Boundary for River Rch & Prof#=Stream0246_DS,Reach-1,4
Up Type=0
Dn Type=3
Dn Slope=0.005
Boundary for River Rch & Prof#=Stream0246_DS,Reach-1,5
Up Type=0
Dn Type=3
Dn Slope=0.005
Boundary for River Rch & Prof#=Stream0246_DS,Reach-1,6
Up Type=0
Dn Type=3
Dn Slope=0.005
Boundary for River Rch & Prof#=Stream0246_DS,Reach-1,7
Up Type=0
Dn Type=3
Dn Slope=0.005

--- Stream0246_DS.g01 (geometry) ---

Geom Title=Existing Conditions

River Reach=Stream0246_DS,Reach-1
Reach XY= 30
      2006775.00     13917775.00      2006866.89     13917681.07
      2006877.52     13917631.03      2006888.62     13917611.76
      2006976.45     13917528.53      2007219.14     13917522.93
      2007241.75     13917508.53      2007318.84     13917432.88
      2007340.22     13917425.53      2007427.42     13917419.46
      2007530.86     13917327.07      2007814.50     13917323.78
      2007880.98     13917277.36      2007973.42     13917271.17
      2008022.83     13917231.09      2008073.37     13917220.59
      2008121.77     13917183.24      2008174.90     13917217.21
      2008230.89     13917177.55      2008327.43     13917169.48
      2008461.37     13917038.21      2008471.02     13917023.35
      2008485.78     13916965.32      2008598.18     13916851.30
      2008626.68     13916828.99      2008677.54     13916819.25
      2008705.37     13916795.47      2008721.11     13916773.57
      2008735.78     13916715.34      2008875.00     13916575.00

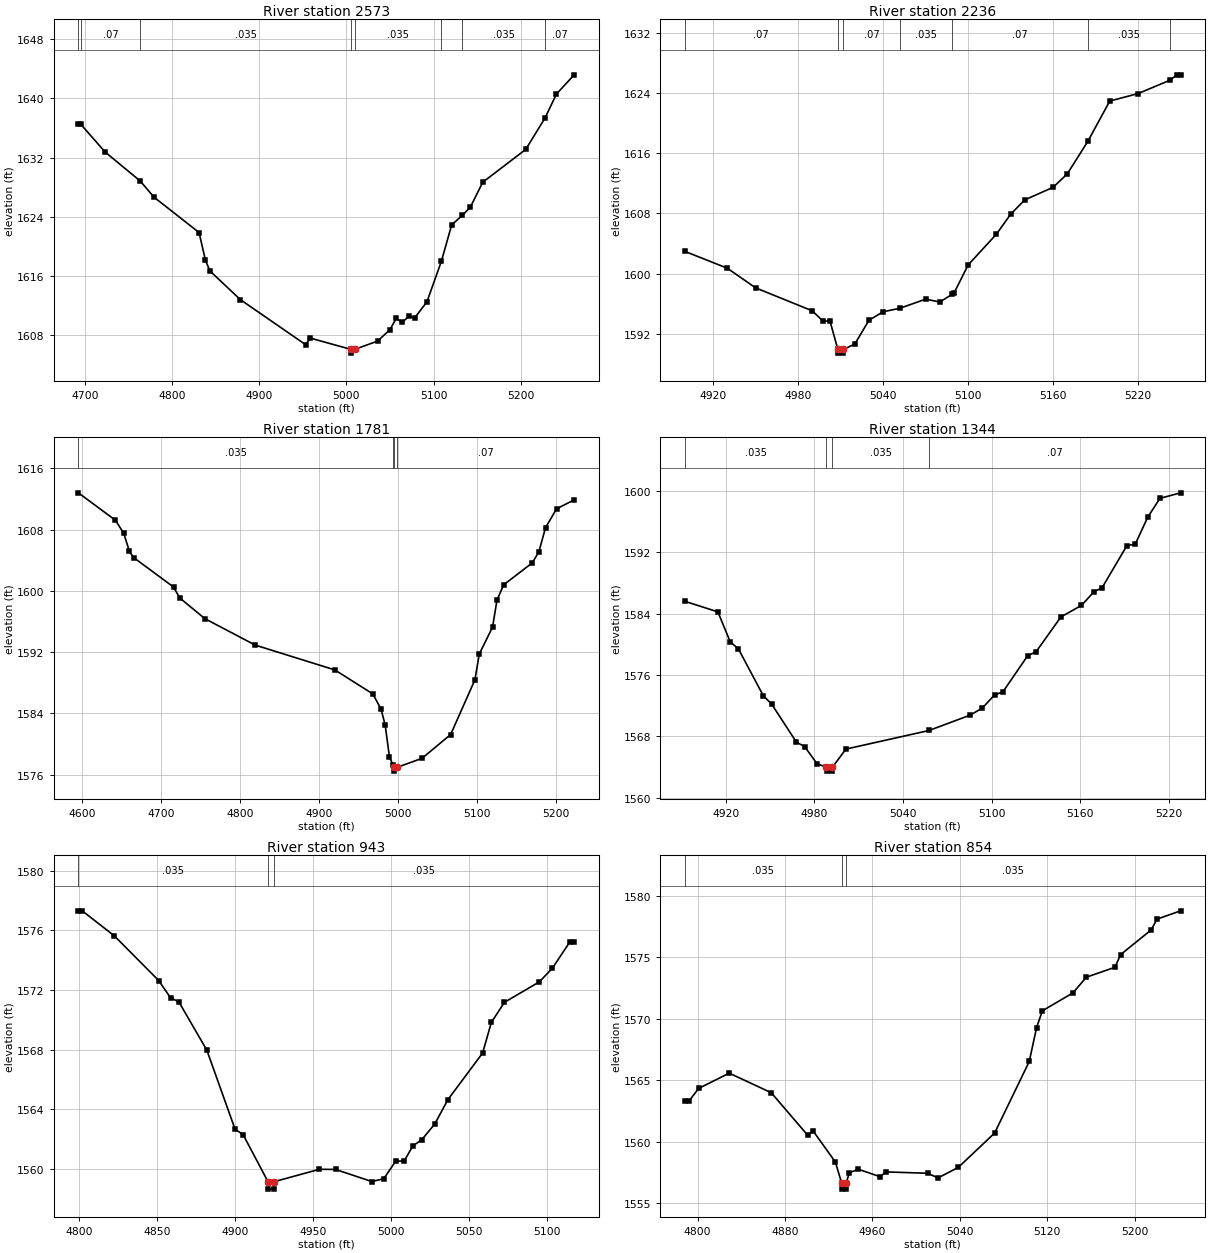
Type RM Length L Ch R = 1,2573,337,337,337
BEGIN DESCRIPTION:
Stream0246_DS 5.0
END DESCRIPTION:
XS GIS Cut Line= 3
      2006918.19     13918008.71      2006838.78     13917711.85
      2006648.70     13917532.85
#Sta/Elev= 30
  4692.7 1636.49  4695.5 1636.49  4723.4 1632.75  4763.7 1628.83  4779.4 1626.66
  4831.1 1621.89  4838.4 1618.15  4843.6 1616.70  4878.4 1612.84  4953.4 1606.75
  4958.5 1607.65  5005.4 1606.12  5005.6 1605.62  5009.4 1606.12  5035.7 1607.24
  5049.9 1608.78  5057.2 1610.32  5064.0 1609.76  5071.3 1610.57  5078.2 1610.36
  5092.3 1612.53  5109.0 1618.05  5120.7 1622.92  5132.9 1624.20  5142.1 1625.31
  5156.3 1628.67  5205.6 1633.10  5227.7 1637.34  5240.8 1640.57  5261.1 1643.16
#Mann=8,-1,0
  4692.7   0.035       0  4695.5    0.07       0  4763.7   0.035       0
  5005.4   0.035       0  5009.4   0.035       0  5109.0    0.07       0
  5132.9   0.035       0  5227.7    0.07       0
Bank Sta=5005.4,5009.4
Exp/Cntr=0.3,0.1

Type RM Length L Ch R = 1,2236,455,455,455
BEGIN DESCRIPTION:
Stream0246_DS 4.0
END DESCRIPTION:
XS GIS Cut Line= 3
      2007075.00     13917625.01      2007075.00     13917525.00
      2007075.00     13917275.01
#Sta/Elev= 30
  4899.9 1602.97  4929.9 1600.73  4949.9 1598.12  4989.9 1595.07  4997.4 1593.71
  5002.4 1593.71  5007.9 1589.95  5008.2 1589.45  5011.7 1589.45  5011.9 1589.95
  5019.9 1590.65  5029.9 1593.82  5039.9 1594.94  5051.9 1595.42  5069.9 1596.62
  5079.9 1596.24  5088.8 1597.28  5089.9 1597.41  5099.9 1601.16  5119.9 1605.26
  5129.9 1607.90  5139.9 1609.81  5159.9 1611.48  5169.9 1613.26  5184.5 1617.62
  5199.9 1622.94  5219.9 1623.93  5242.3 1625.70  5247.4 1626.42  5249.9 1626.42
#Mann=7,-1,0
  4899.9    0.07       0  5007.9    0.05       0  5011.9    0.07       0
  5051.9   0.035       0  5088.8    0.07       0  5184.5   0.035       0
  5242.3    0.07       0
Bank Sta=5007.9,5011.9
Exp/Cntr=0.3,0.1

Type RM Length L Ch R = 1,1781,437,437,437
BEGIN DESCRIPTION:
Stream0246_DS 3.0
END DESCRIPTION:
XS GIS Cut Line= 3
      2007600.76     13917759.67      2007475.00     13917375.00
      2007275.01     13917275.01
#Sta/Elev= 30
  4595.3 1612.82  4642.3 1609.24  4652.8 1607.54  4660.1 1605.16  4665.4 1604.36
  4715.9 1600.52  4723.8 1599.09  4755.7 1596.38  4819.5 1592.93  4920.3 1589.69
  4968.4 1586.56  4978.8 1584.60  4984.1 1582.51  4989.5 1578.33  4993.9 1577.32
  4995.4 1576.97  4995.6 1576.47  4999.4 1576.97  5030.8 1578.14  5067.1 1581.25
  5097.8 1588.39  5103.4 1591.77  5120.2 1595.28  5125.8 1598.80  5134.2 1600.80
  5170.5 1603.67  5178.9 1605.12  5187.3 1608.26  5201.3 1610.73  5223.6 1611.90
#Mann=4,-1,0
  4595.3   0.035       0  4993.9    0.07       0  4995.4    0.05       0
  4999.4    0.07       0
Bank Sta=4995.4,4999.4
Exp/Cntr=0.3,0.1

Type RM Length L Ch R = 1,1344,401,401,401
BEGIN DESCRIPTION:
Stream0246_DS 2.0
END DESCRIPTION:
XS GIS Cut Line= 3
      2007925.00     13917375.00      2007875.00     13917275.00
      2007775.00     13917075.01
#Sta/Elev= 30
  4892.4 1585.59  4914.8 1584.21  4923.1 1580.32  4928.7 1579.38  4945.5 1573.30
  4951.1 1572.22  4967.9 1567.25  4973.5 1566.67  4981.8 1564.45  4988.2 1563.98
  4988.5 1563.48  4992.0 1563.48  4992.2 1563.98  5001.4 1566.35  5057.6 1568.77
  5085.3 1570.76  5093.6 1571.68  5102.0 1573.41  5107.6 1573.80  5124.4 1578.52
  5130.0 1579.01  5146.8 1583.55  5160.7 1585.05  5169.1 1586.81  5174.7 1587.36
  5191.5 1592.85  5197.1 1593.02  5205.5 1596.52  5213.8 1598.99  5227.8 1599.71
#Mann=4,-1,0
  4892.4   0.035       0  4988.2   0.035       0  4992.2   0.035       0
  5057.6    0.07       0
Bank Sta=4988.2,4992.2
Exp/Cntr=0.3,0.1

Type RM Length L Ch R = 1,943,89,89,89
BEGIN DESCRIPTION:
Stream0246_DS 1.0
END DESCRIPTION:
XS GIS Cut Line= 3
      2008175.01     13917374.96      2008225.00     13917175.00
      2008175.01     13917075.01
#Sta/Elev= 30
  4799.6 1577.30  4802.1 1577.30  4822.7 1575.62  4851.1 1572.63  4858.8 1571.46
  4864.0 1571.21  4882.0 1567.96  4900.1 1562.66  4905.2 1562.31  4921.2 1559.15
  4921.5 1558.65  4925.0 1558.65  4925.2 1559.15  4954.2 1559.98  4964.5 1559.97
  4987.7 1559.16  4995.4 1559.34  5003.1 1560.53  5008.5 1560.53  5014.1 1561.55
  5019.7 1561.95  5028.1 1563.01  5036.5 1564.64  5058.8 1567.77  5064.4 1569.82
  5072.8 1571.17  5095.2 1572.54  5103.5 1573.45  5114.7 1575.21  5117.5 1575.21
#Mann=3,-1,0
  4799.6   0.035       0  4921.2   0.035       0  4925.2   0.035       0
Bank Sta=4921.2,4925.2
Exp/Cntr=0.3,0.1

Type RM Length L Ch R = 1,854,568,568,568
BEGIN DESCRIPTION:
Stream0246_DS 0.5
END DESCRIPTION:
XS GIS Cut Line= 2
      2008372.12     13917377.14      2008242.92     13916942.23
#Sta/Elev= 30
  4788.3 1563.28  4792.0 1563.28  4801.0 1564.32  4829.0 1565.56  4867.4 1563.97
  4900.6 1560.53  4905.8 1560.85  4926.1 1558.33  4931.8 1556.63  4932.0 1556.13
  4935.5 1556.13  4935.8 1556.63  4939.0 1557.46  4947.0 1557.75  4967.0 1557.14
  4972.2 1557.53  5010.6 1557.42  5020.0 1557.04  5038.6 1557.90  5071.8 1560.69
  5103.5 1566.51  5110.2 1569.27  5115.5 1570.63  5143.5 1572.09  5155.7 1573.36
  5181.9 1574.17  5187.1 1575.20  5215.1 1577.21  5220.3 1578.08  5242.0 1578.76
#Mann=3,-1,0
  4788.3   0.035       0  4931.8   0.035       0  4935.8   0.035       0
Bank Sta=4931.8,4935.8
Exp/Cntr=0.3,0.1

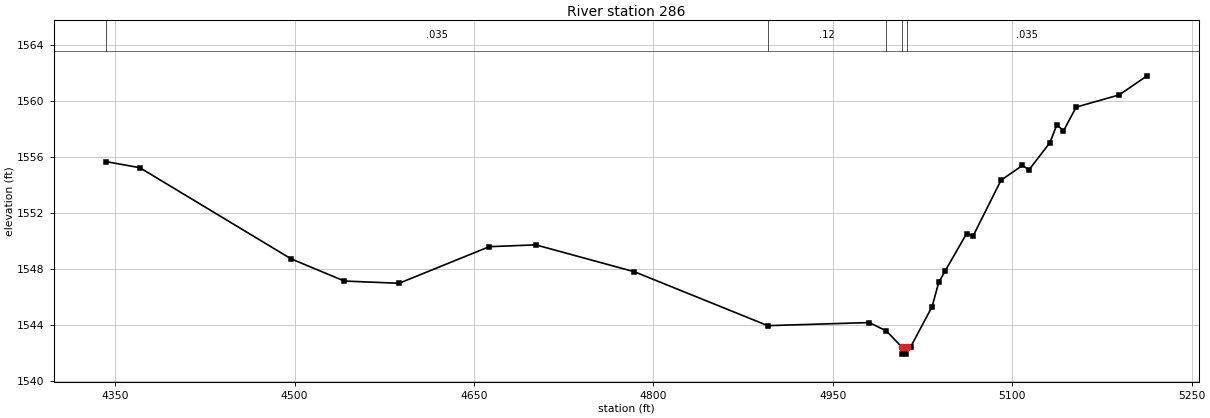
Type RM Length L Ch R = 1,286,0,0,0
BEGIN DESCRIPTION:
Stream0246_DS 0.0
END DESCRIPTION:
XS GIS Cut Line= 4
      2008497.69     13917405.50      2008712.40     13916946.21
      2008705.37     13916795.47      2008510.72     13916709.72
#Sta/Elev= 30
  4342.1 1555.67  4370.7 1555.23  4497.2 1548.73  4541.7 1547.15  4587.4 1546.99
  4662.8 1549.60  4701.6 1549.73  4784.2 1547.81  4895.6 1543.97  4980.4 1544.19
  4994.8 1543.59  5007.7 1542.44  5008.0 1541.94  5011.5 1541.94  5011.7 1542.44
  5015.2 1542.48  5033.0 1545.33  5038.5 1547.05  5044.1 1547.90  5061.8 1550.53
  5067.3 1550.37  5090.6 1554.34  5108.5 1555.39  5114.0 1555.08  5131.5 1557.02
  5137.3 1558.30  5142.8 1557.85  5153.4 1559.55  5189.4 1560.42  5212.7 1561.78
#Mann=5,-1,0
  4342.1   0.035       0  4895.6    0.12       0  4994.8   0.035       0
  5007.7   0.035       0  5011.7   0.035       0
Bank Sta=5007.7,5011.7
Exp/Cntr=0.3,0.1

Chan Stop Cuts=-1