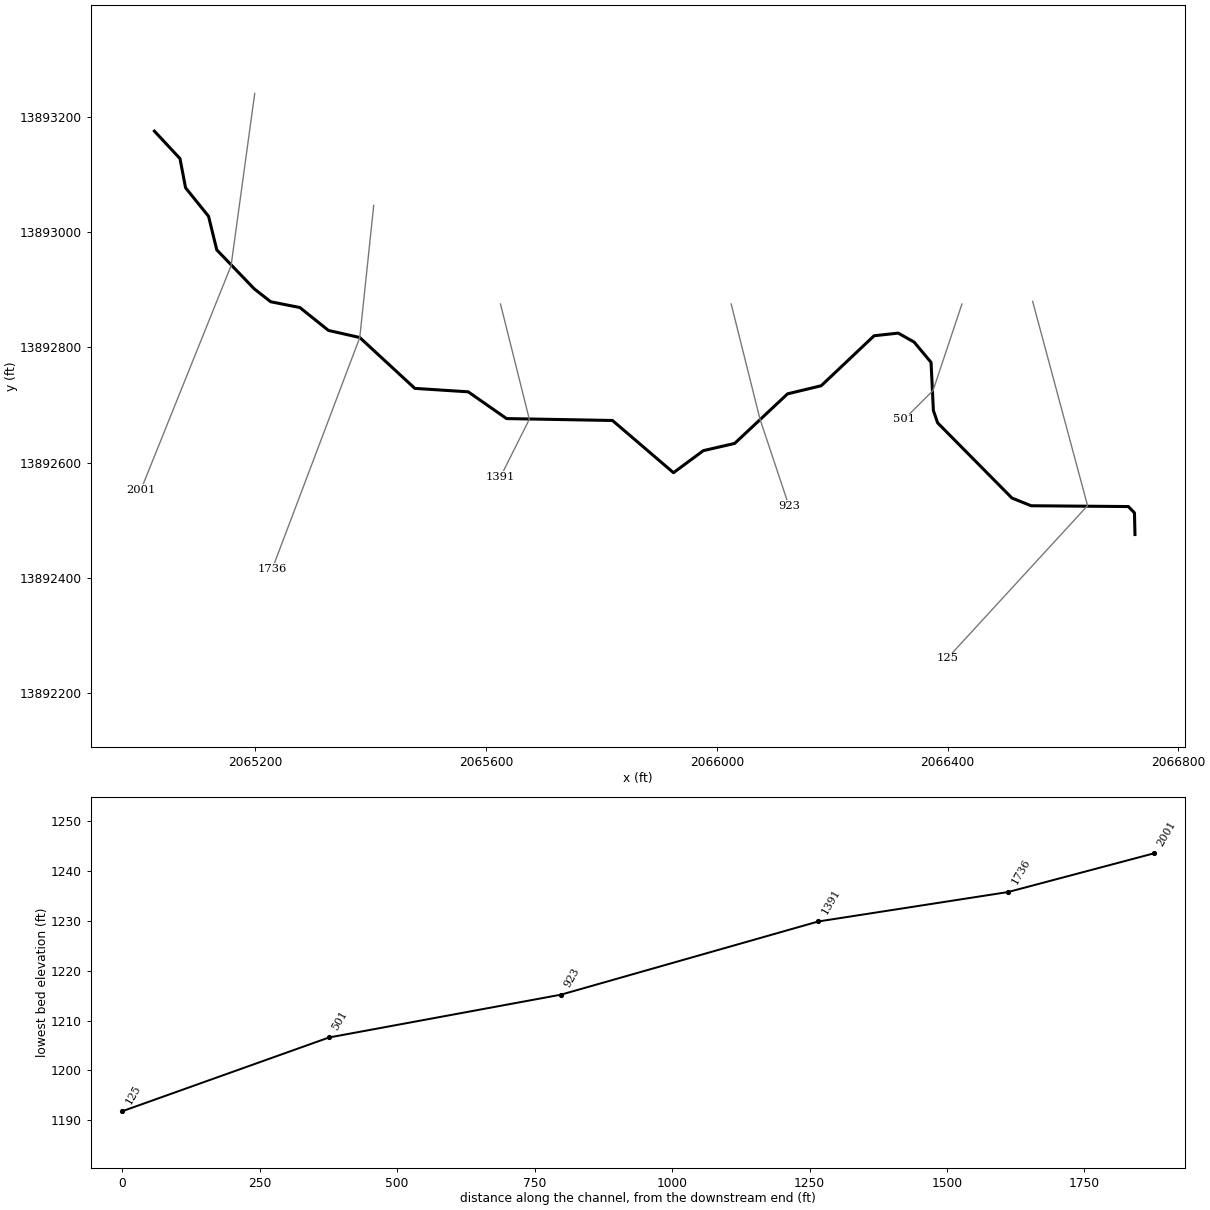
--- Stream0247_DS.prj (project) ---

Proj Title=Stream0247_DS Base Level Engineering
Current Plan=p01
Default Exp/Contr=0.3,0.1
English Units
Geom File=g01
Flow File=f01
Plan File=p01
BEGIN DESCRIPTION:
Stream0247_DS
END DESCRIPTION:

--- Stream0247_DS.p01 (plan) ---

Plan Title=Multiple Run
Short Identifier=Multiple
Geom File=g01
Flow File=f01
Subcritical Flow
K Sum by GR= 0
Std Step Tol= 0.01
Critical Tol= 0.01
Num of Std Step Trials= 20
Max Error Tol= 0.3
Flow Tol Ratio= 0.001
Split Flow NTrial= 30
Split Flow Tol= 0.02
Split Flow Ratio= 0.02
Log Output Level= 0
Friction Slope Method= 1
Unsteady Friction Slope Method= 2
Unsteady Bridges Friction Slope Method= 1
Parabolic Critical Depth
Global Vel Dist=  1 , 1 , 1
Global Log Level= 0
CheckData=True
Encroach Param= -1, 0, 0, 0
BEGIN DESCRIPTION:
Multiple Run
END DESCRIPTION:

--- Stream0247_DS.f01 (steady flow) ---

Flow Title=Multiple
Number of Profiles=7
Profile Names=10-year,25-year,50-year,1pct_min,100-year,1pct_plu,500-year
River Rch & RM= Stream0247_DS,Reach-1,2001
     401     637     849     552    1102    2198    1824
Boundary for River Rch & Prof#=Stream0247_DS,Reach-1,1
Up Type=0
Dn Type=3
Dn Slope=0.005
Boundary for River Rch & Prof#=Stream0247_DS,Reach-1,2
Up Type=0
Dn Type=3
Dn Slope=0.005
Boundary for River Rch & Prof#=Stream0247_DS,Reach-1,3
Up Type=0
Dn Type=3
Dn Slope=0.005
Boundary for River Rch & Prof#=Stream0247_DS,Reach-1,4
Up Type=0
Dn Type=3
Dn Slope=0.005
Boundary for River Rch & Prof#=Stream0247_DS,Reach-1,5
Up Type=0
Dn Type=3
Dn Slope=0.005
Boundary for River Rch & Prof#=Stream0247_DS,Reach-1,6
Up Type=0
Dn Type=3
Dn Slope=0.005
Boundary for River Rch & Prof#=Stream0247_DS,Reach-1,7
Up Type=0
Dn Type=3
Dn Slope=0.005

--- Stream0247_DS.g01 (geometry) ---

Geom Title=Existing Conditions

River Reach=Stream0247_DS,Reach-1
Reach XY= 30
      2065025.00     13893175.00      2065069.33     13893127.36
      2065079.04     13893076.67      2065118.90     13893027.19
      2065133.13     13892968.93      2065198.12     13892901.27
      2065226.62     13892878.94      2065277.19     13892868.90
      2065326.73     13892829.19      2065381.05     13892816.84
      2065476.50     13892728.62      2065569.02     13892722.64
      2065635.50     13892676.22      2065819.15     13892672.92
      2065924.92     13892582.30      2065976.65     13892620.54
      2066031.04     13892633.14      2066122.72     13892719.13
      2066181.04     13892733.18      2066272.74     13892819.93
      2066314.53     13892824.52      2066342.13     13892808.98
      2066371.47     13892773.78      2066375.53     13892690.22
      2066382.86     13892668.83      2066511.68     13892538.37
      2066544.98     13892524.96      2066713.57     13892523.57
      2066724.17     13892512.57      2066725.00     13892475.00

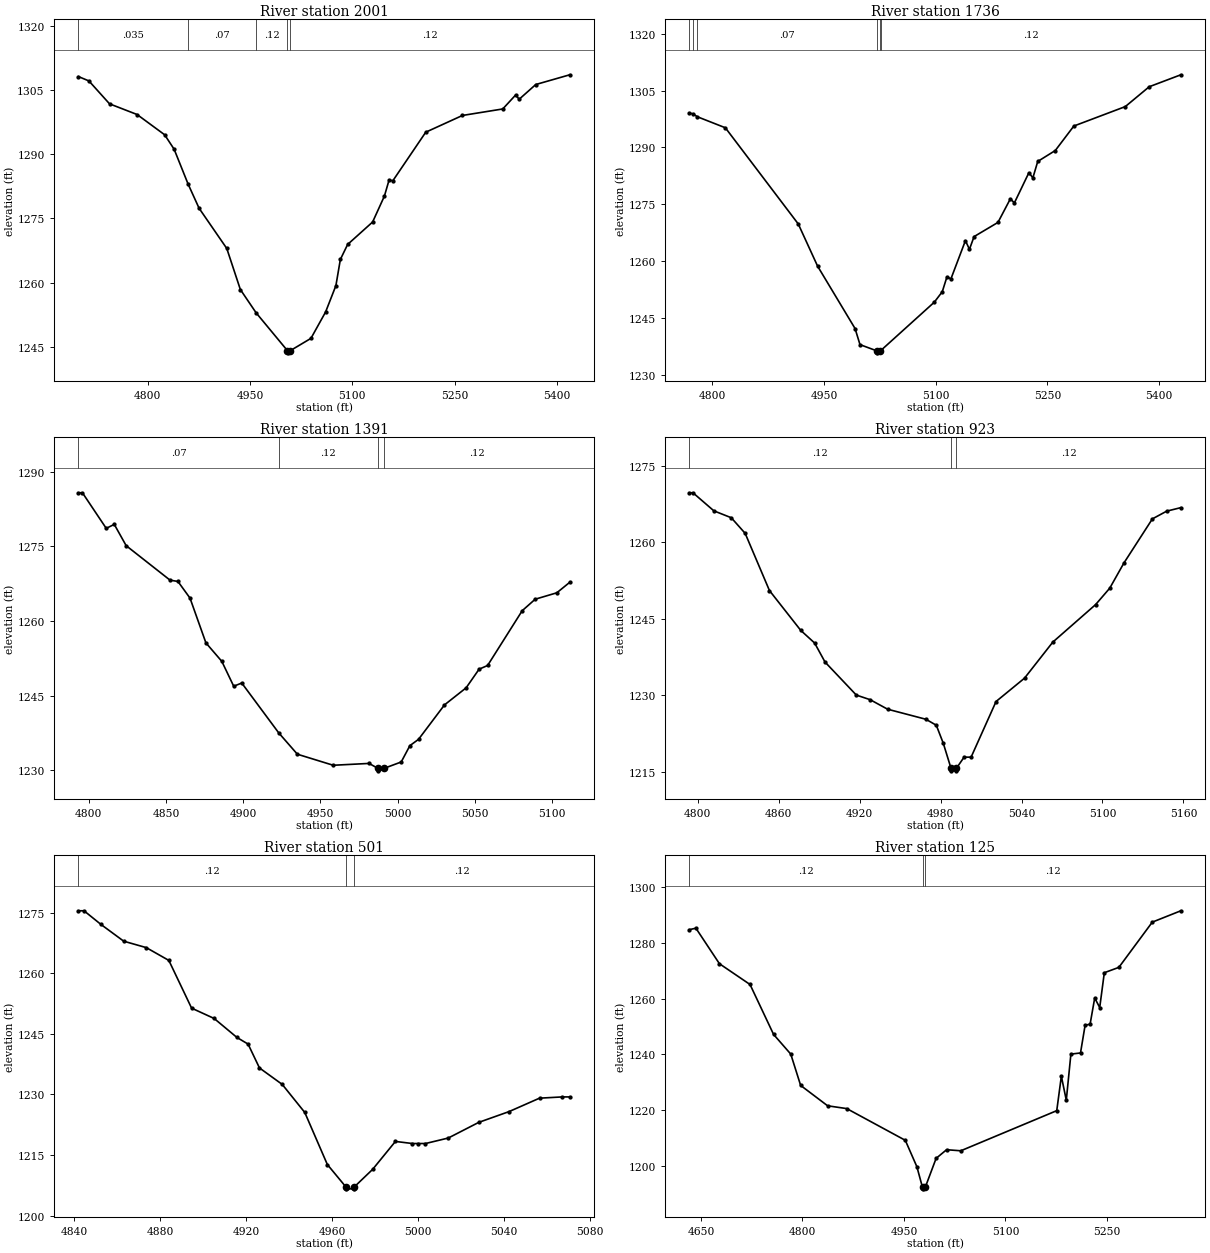
Type RM Length L Ch R = 1,2001,265,265,265
BEGIN DESCRIPTION:
Stream0247_DS 6.0
END DESCRIPTION:
XS GIS Cut Line= 3
      2065198.92     13893240.22      2065157.92     13892941.42
      2065001.75     13892552.83
#Sta/Elev= 30
  4698.4 1308.20  4713.8 1307.18  4744.0 1301.82  4784.4 1299.32  4824.8 1294.58
  4838.7 1291.20  4859.2 1283.04  4875.3 1277.38  4915.9 1267.97  4935.8 1258.36
  4959.0 1252.89  5004.9 1244.04  5005.2 1243.54  5008.9 1244.04  5039.3 1246.93
  5060.8 1253.11  5075.9 1259.28  5082.4 1265.39  5093.1 1268.91  5129.7 1274.16
  5147.0 1280.23  5153.9 1284.02  5159.3 1283.80  5207.6 1295.18  5261.4 1299.10
  5320.5 1300.62  5339.3 1303.87  5344.7 1302.91  5368.9 1306.34  5418.8 1308.62
#Mann=5,-1,0
  4698.4   0.035       0  4859.2    0.07       0  4959.0    0.12       0
  5004.9    0.05       0  5008.9    0.12       0
Bank Sta=5004.9,5008.9
Exp/Cntr=0.3,0.1

Type RM Length L Ch R = 1,1736,345,345,345
BEGIN DESCRIPTION:
Stream0247_DS 5.0
END DESCRIPTION:
XS GIS Cut Line= 3
      2065405.24     13893046.17      2065381.05     13892816.84
      2065229.32     13892415.25
#Sta/Elev= 30
  4769.4 1299.08  4774.0 1298.89  4780.1 1298.10  4817.6 1295.20  4915.5 1269.81
  4941.5 1258.66  4991.8 1242.20  4998.4 1237.96  5021.3 1236.29  5021.6 1235.79
  5025.3 1236.29  5026.8 1236.48  5098.2 1249.16  5108.9 1251.92  5115.2 1255.86
  5120.5 1255.30  5140.0 1265.41  5145.4 1263.12  5151.6 1266.47  5183.7 1270.22
  5200.4 1276.47  5205.7 1275.35  5225.2 1283.33  5230.6 1281.99  5237.1 1286.31
  5260.7 1289.20  5285.6 1295.66  5354.7 1300.79  5386.8 1306.03  5429.3 1309.19
#Mann=6,-1,0
  4769.4    0.07       0  4774.0    0.12       0  4780.1    0.07       0
  5021.3    0.05       0  5025.3    0.07       0  5026.8    0.12       0
Bank Sta=5021.3,5025.3
Exp/Cntr=0.3,0.1

Type RM Length L Ch R = 1,1391,468,468,468
BEGIN DESCRIPTION:
Stream0247_DS 3.0
END DESCRIPTION:
XS GIS Cut Line= 3
      2065625.00     13892875.00      2065675.00     13892675.00
      2065624.98     13892574.96
#Sta/Elev= 30
  4793.4 1285.77  4796.0 1285.77  4811.4 1278.62  4816.6 1279.42  4824.3 1275.14
  4852.7 1268.21  4857.8 1267.95  4865.6 1264.61  4875.9 1255.61  4886.2 1251.89
  4893.9 1246.89  4899.1 1247.54  4923.0 1237.53  4935.1 1233.23  4958.3 1231.01
  4981.5 1231.38  4987.2 1230.39  4987.5 1229.89  4991.2 1230.39  5002.3 1231.67
  5007.9 1234.95  5013.5 1236.22  5030.3 1243.14  5044.3 1246.57  5052.7 1250.32
  5058.2 1251.06  5080.6 1262.07  5089.0 1264.38  5103.0 1265.67  5111.4 1267.79
#Mann=4,-1,0
  4793.4    0.07       0  4923.0    0.12       0  4987.2    0.05       0
  4991.2    0.12       0
Bank Sta=4987.2,4991.2
Exp/Cntr=0.3,0.1

Type RM Length L Ch R = 1,923,422,422,422
BEGIN DESCRIPTION:
Stream0247_DS 2.0
END DESCRIPTION:
XS GIS Cut Line= 3
      2066024.99     13892875.04      2066075.00     13892675.00
      2066125.00     13892525.01
#Sta/Elev= 30
  4793.8 1269.67  4796.4 1269.67  4811.9 1266.13  4824.8 1264.78  4835.1 1261.72
  4853.1 1250.52  4876.3 1242.72  4886.6 1240.24  4894.3 1236.52  4917.5 1230.05
  4927.8 1229.14  4940.7 1227.28  4969.1 1225.31  4976.8 1224.14  4982.0 1220.59
  4987.7 1215.71  4987.9 1215.21  4991.4 1215.21  4991.7 1215.71  4997.4 1217.89
  5002.6 1217.89  5021.1 1228.79  5042.2 1233.36  5063.2 1240.43  5094.9 1247.77
  5105.4 1250.99  5115.9 1255.92  5137.0 1264.56  5147.6 1266.07  5158.1 1266.76
#Mann=3,-1,0
  4793.8    0.12       0  4987.7    0.05       0  4991.7    0.12       0
Bank Sta=4987.7,4991.7
Exp/Cntr=0.3,0.1

Type RM Length L Ch R = 1,501,376,376,376
BEGIN DESCRIPTION:
Stream0247_DS 1.0
END DESCRIPTION:
XS GIS Cut Line= 3
      2066424.99     13892874.98      2066375.00     13892725.00
      2066325.01     13892675.01
#Sta/Elev= 29
  4841.9 1275.53  4844.5 1275.53  4852.4 1272.14  4863.0 1267.99  4873.5 1266.40
  4884.0 1263.23  4894.6 1251.40  4905.1 1248.84  4915.7 1244.14  4920.9 1242.49
  4926.2 1236.58  4936.8 1232.50  4947.3 1225.55  4957.8 1212.65  4966.4 1207.12
  4966.6 1206.62  4970.1 1206.62  4970.4 1207.12  4978.9 1211.45  4989.5 1218.37
  4997.4 1217.85  5000.0 1217.85  5003.5 1217.85  5014.1 1219.21  5028.3 1223.09
  5042.4 1225.76  5056.6 1229.09  5067.2 1229.40  5070.7 1229.40
#Mann=3,-1,0
  4841.9    0.12       0  4966.4    0.05       0  4970.4    0.12       0
Bank Sta=4966.4,4970.4
Exp/Cntr=0.3,0.1

Type RM Length L Ch R = 1,125,0,0,0
BEGIN DESCRIPTION:
Stream0247_DS 0.0
END DESCRIPTION:
XS GIS Cut Line= 3
      2066547.63     13892879.57      2066642.85     13892525.13
      2066399.99     13892260.47
#Sta/Elev= 30
  4633.0 1284.73  4642.5 1285.25  4677.3 1272.51  4722.5 1265.07  4757.3 1247.18
  4782.7 1240.12  4797.3 1228.90  4837.2 1221.59  4865.5 1220.59  4952.0 1209.22
  4969.1 1199.75  4977.4 1192.33  4977.7 1191.83  4981.4 1192.33  4997.5 1202.75
  5013.0 1205.85  5034.0 1205.47  5175.8 1219.85  5182.6 1232.19  5189.9 1223.61
  5196.7 1240.12  5210.9 1240.53  5217.7 1250.45  5225.1 1250.86  5231.9 1260.24
  5239.3 1256.81  5246.1 1269.29  5267.6 1271.21  5317.0 1287.42  5359.2 1291.49
#Mann=3,-1,0
  4633.0    0.12       0  4977.4    0.05       0  4981.4    0.12       0
Bank Sta=4977.4,4981.4
Exp/Cntr=0.3,0.1

Chan Stop Cuts=-1