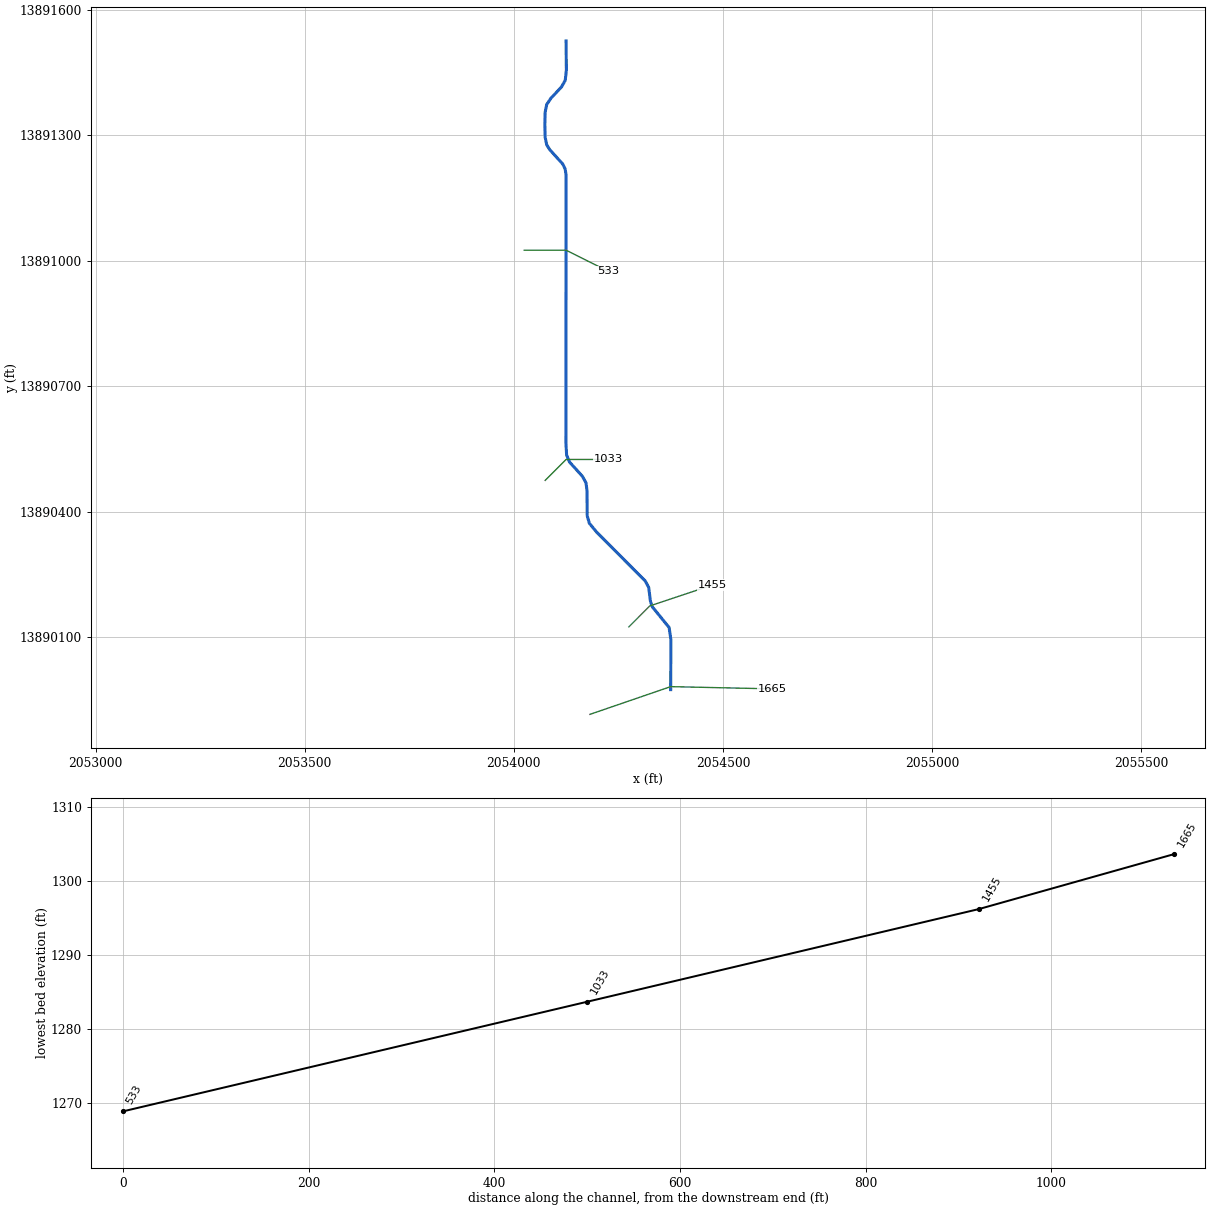
--- Stream0250_DS.prj (project) ---

Proj Title=Stream0250_DS Base Level Engineering
Current Plan=p01
Default Exp/Contr=0.3,0.1
English Units
Geom File=g01
Flow File=f01
Plan File=p01
BEGIN DESCRIPTION:
Stream0250_DS
END DESCRIPTION:

--- Stream0250_DS.p01 (plan) ---

Plan Title=Multiple Run
Short Identifier=Multiple
Geom File=g01
Flow File=f01
Subcritical Flow
K Sum by GR= 0
Std Step Tol= 0.01
Critical Tol= 0.01
Num of Std Step Trials= 20
Max Error Tol= 0.3
Flow Tol Ratio= 0.001
Split Flow NTrial= 30
Split Flow Tol= 0.02
Split Flow Ratio= 0.02
Log Output Level= 0
Friction Slope Method= 1
Unsteady Friction Slope Method= 2
Unsteady Bridges Friction Slope Method= 1
Parabolic Critical Depth
Global Vel Dist=  1 , 1 , 1
Global Log Level= 0
CheckData=True
Encroach Param= -1, 0, 0, 0
BEGIN DESCRIPTION:
Multiple Run
END DESCRIPTION:

--- Stream0250_DS.f01 (steady flow) ---

Flow Title=Multiple
Number of Profiles=7
Profile Names=10-year,25-year,50-year,1pct_min,100-year,1pct_plu,500-year
River Rch & RM= Stream0250_DS,Reach-1,1665
     509     818    1099     718    1432    2858    2399
Boundary for River Rch & Prof#=Stream0250_DS,Reach-1,1
Up Type=0
Dn Type=3
Dn Slope=0.005
Boundary for River Rch & Prof#=Stream0250_DS,Reach-1,2
Up Type=0
Dn Type=3
Dn Slope=0.005
Boundary for River Rch & Prof#=Stream0250_DS,Reach-1,3
Up Type=0
Dn Type=3
Dn Slope=0.005
Boundary for River Rch & Prof#=Stream0250_DS,Reach-1,4
Up Type=0
Dn Type=3
Dn Slope=0.005
Boundary for River Rch & Prof#=Stream0250_DS,Reach-1,5
Up Type=0
Dn Type=3
Dn Slope=0.005
Boundary for River Rch & Prof#=Stream0250_DS,Reach-1,6
Up Type=0
Dn Type=3
Dn Slope=0.005
Boundary for River Rch & Prof#=Stream0250_DS,Reach-1,7
Up Type=0
Dn Type=3
Dn Slope=0.005

--- Stream0250_DS.g01 (geometry) ---

Geom Title=Existing Conditions

River Reach=Stream0250_DS,Reach-1
Reach XY= 30
      2054375.00     13889975.00      2054375.44     13890095.18
      2054371.28     13890123.46      2054331.14     13890172.83
      2054326.72     13890185.71      2054322.50     13890218.97
      2054314.24     13890234.68      2054197.88     13890351.48
      2054180.52     13890372.57      2054175.52     13890390.22
      2054174.99     13890450.00      2054172.64     13890469.02
      2054164.10     13890484.63      2054133.14     13890518.94
      2054126.22     13890535.50      2054124.55     13890564.81
      2054124.93     13891204.97      2054122.74     13891219.06
      2054116.85     13891231.06      2054085.81     13891265.37
      2054078.70     13891276.60      2054074.90     13891295.10
      2054074.18     13891325.00      2054074.89     13891354.90
      2054078.67     13891373.42      2054088.70     13891388.15
      2054114.14     13891415.35      2054122.89     13891430.87
      2054125.63     13891454.74      2054125.00     13891525.00

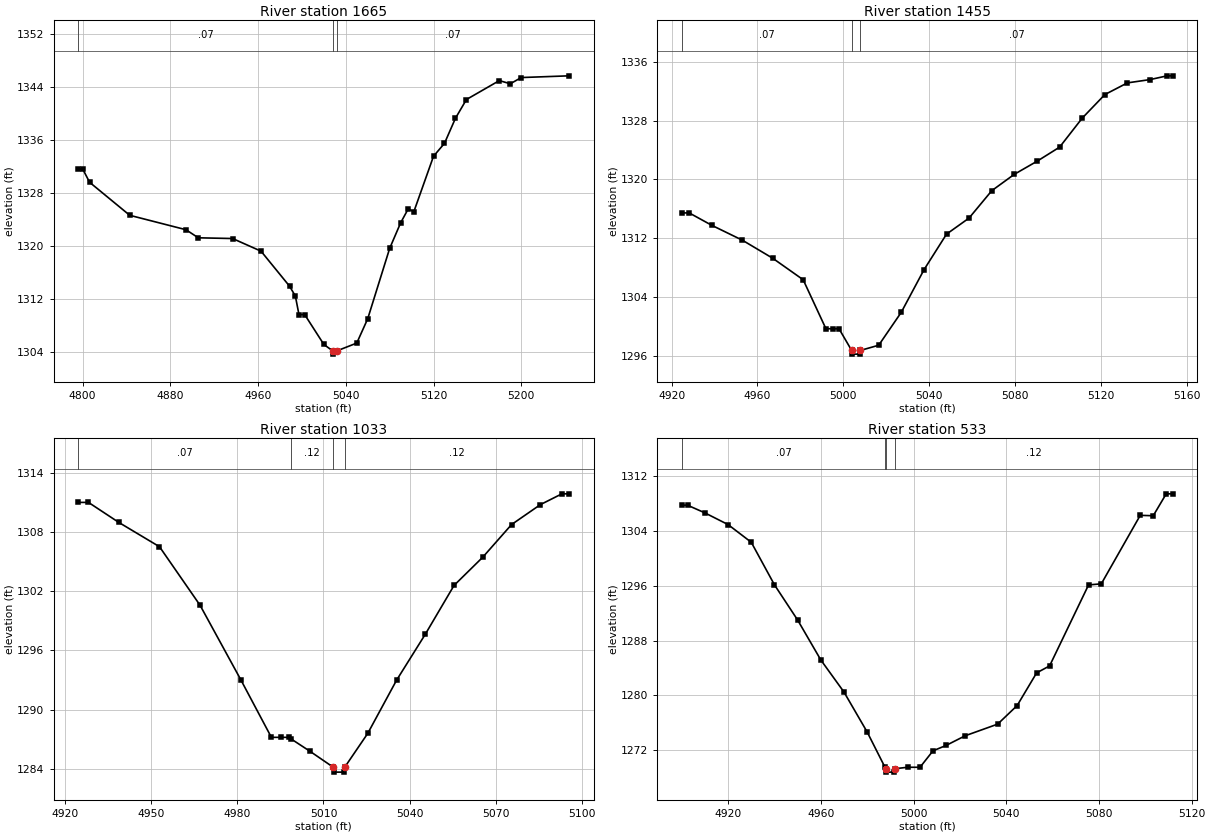
Type RM Length L Ch R = 1,1665,210,210,210
BEGIN DESCRIPTION:
Stream0250_DS 4.0
END DESCRIPTION:
XS GIS Cut Line= 3
      2054181.97     13889915.91      2054375.02     13889982.17
      2054618.56     13889976.83
#Sta/Elev= 30
  4795.9 1331.61  4800.1 1331.61  4806.4 1329.60  4843.0 1324.61  4894.3 1322.43
  4905.5 1321.21  4936.8 1321.10  4962.7 1319.19  4988.7 1313.90  4994.0 1312.41
  4997.3 1309.61  5002.5 1309.61  5020.0 1305.09  5028.0 1304.13  5028.2 1303.63
  5032.0 1304.13  5050.0 1305.30  5060.0 1308.98  5080.0 1319.61  5090.0 1323.47
  5097.0 1325.61  5102.0 1325.13  5120.0 1333.54  5130.0 1335.49  5140.0 1339.28
  5150.0 1342.11  5180.0 1344.97  5190.0 1344.49  5200.0 1345.43  5243.6 1345.69
#Mann=3,-1,0
  4795.9    0.07       0  5028.0    0.05       0  5032.0    0.07       0
Bank Sta=5028,5032
Exp/Cntr=0.3,0.1

Type RM Length L Ch R = 1,1455,422,422,422
BEGIN DESCRIPTION:
Stream0250_DS 3.0
END DESCRIPTION:
XS GIS Cut Line= 3
      2054275.01     13890125.01      2054325.00     13890175.00
      2054474.98     13890224.99
#Sta/Elev= 28
  4924.7 1315.43  4928.2 1315.43  4938.8 1313.73  4953.0 1311.71  4967.1 1309.26
  4981.3 1306.33  4991.9 1299.66  4995.4 1299.66  4998.0 1299.66  5003.9 1296.70
  5004.2 1296.20  5007.7 1296.20  5007.9 1296.70  5016.5 1297.41  5027.0 1301.89
  5037.6 1307.69  5048.1 1312.54  5058.6 1314.73  5069.2 1318.46  5079.7 1320.69
  5090.3 1322.47  5100.8 1324.39  5111.4 1328.36  5121.9 1331.55  5132.4 1333.14
  5143.0 1333.59  5150.9 1334.10  5153.5 1334.10
#Mann=3,-1,0
  4924.7    0.07       0  5003.9    0.05       0  5007.9    0.07       0
Bank Sta=5003.9,5007.9
Exp/Cntr=0.3,0.1

Type RM Length L Ch R = 1,1033,500,500,500
BEGIN DESCRIPTION:
Stream0250_DS 2.0
END DESCRIPTION:
XS GIS Cut Line= 3
      2054074.98     13890474.98      2054125.00     13890525.00
      2054224.97     13890525.00
#Sta/Elev= 24
  4924.7 1311.03  4928.3 1311.03  4938.9 1308.99  4953.0 1306.53  4967.1 1300.59
  4981.3 1293.01  4991.9 1287.18  4995.4 1287.18  4997.9 1287.18  4998.7 1287.03
  5005.4 1285.75  5013.4 1284.15  5013.7 1283.65  5017.2 1283.65  5017.4 1284.15
  5025.4 1287.58  5035.4 1292.97  5045.4 1297.64  5055.4 1302.60  5065.4 1305.47
  5075.4 1308.78  5085.4 1310.80  5092.9 1311.90  5095.4 1311.90
#Mann=4,-1,0
  4924.7    0.07       0  4998.7    0.12       0  5013.4    0.05       0
  5017.4    0.12       0
Bank Sta=5013.4,5017.4
Exp/Cntr=0.3,0.1

Type RM Length L Ch R = 1,533,0,0,0
BEGIN DESCRIPTION:
Stream0250_DS 1.0
END DESCRIPTION:
XS GIS Cut Line= 3
      2054025.01     13891025.00      2054125.00     13891025.00
      2054225.01     13890975.00
#Sta/Elev= 30
  4900.0 1307.78  4902.5 1307.78  4910.0 1306.66  4920.0 1304.95  4930.0 1302.37
  4940.0 1296.16  4950.0 1291.02  4960.0 1285.19  4970.0 1280.50  4980.0 1274.67
  4987.7 1269.51  4988.0 1269.31  4988.2 1268.81  4991.7 1268.81  4992.0 1269.31
  4997.5 1269.52  5002.8 1269.52  5008.4 1271.92  5014.0 1272.70  5022.3 1274.12
  5036.3 1275.82  5044.7 1278.53  5053.1 1283.30  5058.7 1284.32  5075.5 1296.14
  5081.0 1296.30  5097.8 1306.30  5103.4 1306.24  5109.0 1309.44  5111.8 1309.44
#Mann=4,-1,0
  4900.0    0.07       0  4987.7    0.12       0  4988.0    0.05       0
  4992.0    0.12       0
Bank Sta=4988,4992
Exp/Cntr=0.3,0.1

Chan Stop Cuts=-1