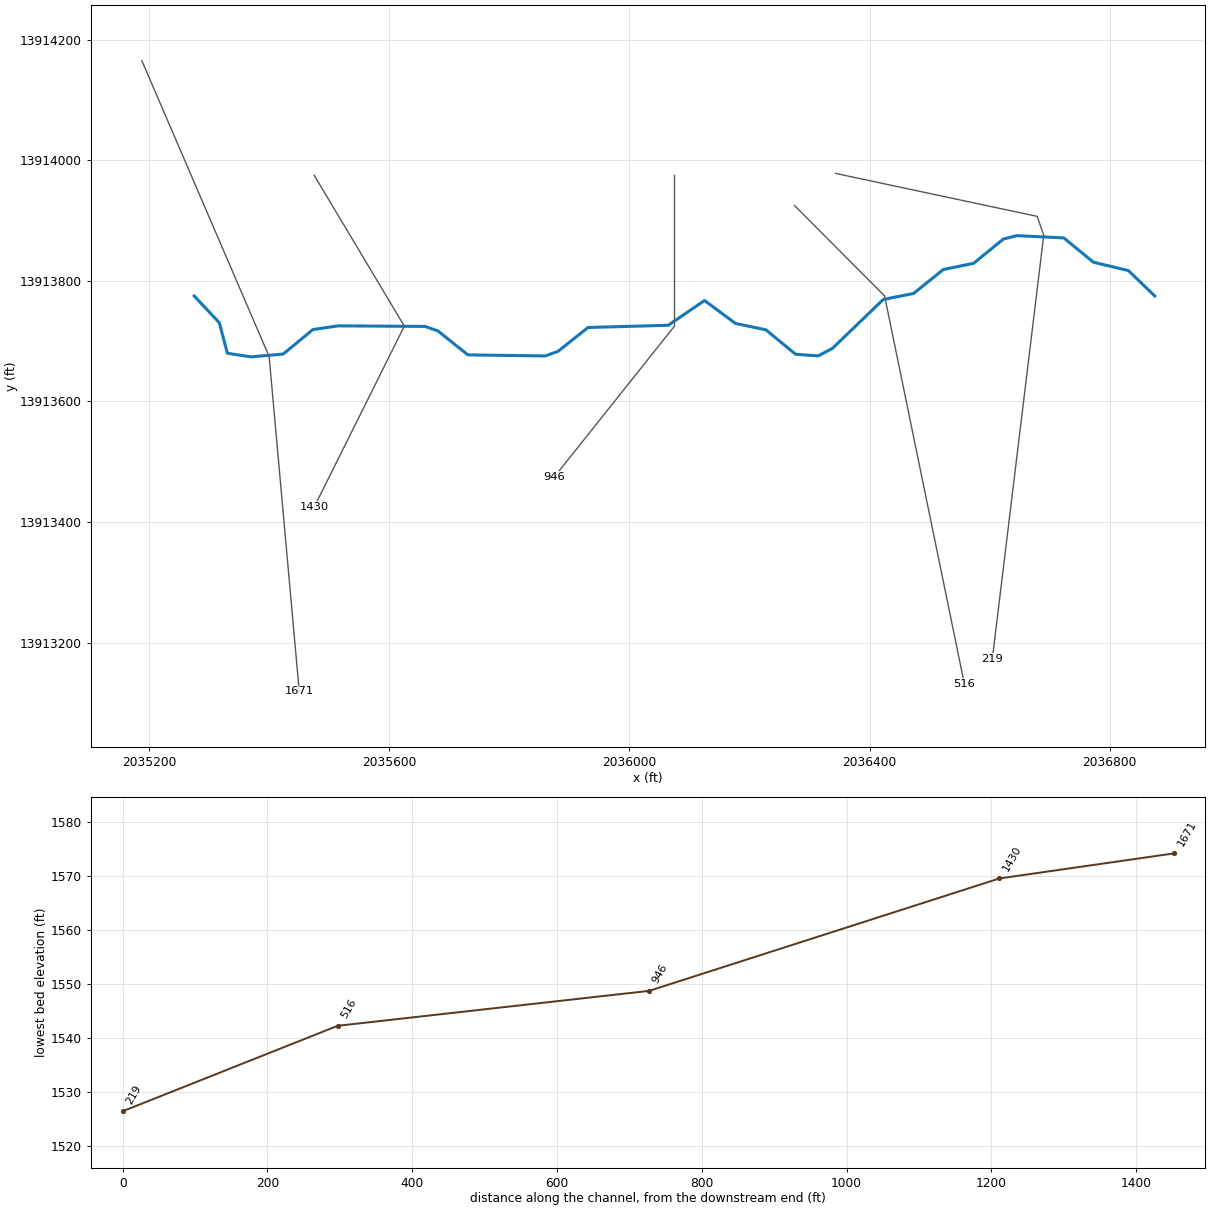
--- Stream0251_DS.prj (project) ---

Proj Title=Stream0251_DS Base Level Engineering
Current Plan=p01
Default Exp/Contr=0.3,0.1
English Units
Geom File=g01
Flow File=f01
Plan File=p01
BEGIN DESCRIPTION:
Stream0251_DS
END DESCRIPTION:

--- Stream0251_DS.p01 (plan) ---

Plan Title=Multiple Run
Short Identifier=Multiple
Geom File=g01
Flow File=f01
Subcritical Flow
K Sum by GR= 0
Std Step Tol= 0.01
Critical Tol= 0.01
Num of Std Step Trials= 20
Max Error Tol= 0.3
Flow Tol Ratio= 0.001
Split Flow NTrial= 30
Split Flow Tol= 0.02
Split Flow Ratio= 0.02
Log Output Level= 0
Friction Slope Method= 1
Unsteady Friction Slope Method= 2
Unsteady Bridges Friction Slope Method= 1
Parabolic Critical Depth
Global Vel Dist=  1 , 1 , 1
Global Log Level= 0
CheckData=True
Encroach Param= -1, 0, 0, 0
BEGIN DESCRIPTION:
Multiple Run
END DESCRIPTION:

--- Stream0251_DS.f01 (steady flow) ---

Flow Title=Multiple
Number of Profiles=7
Profile Names=10-year,25-year,50-year,1pct_min,100-year,1pct_plu,500-year
River Rch & RM= Stream0251_DS,Reach-1,1671
     597     995    1369     918    1832    3656    3245
Boundary for River Rch & Prof#=Stream0251_DS,Reach-1,1
Up Type=0
Dn Type=3
Dn Slope=0.005
Boundary for River Rch & Prof#=Stream0251_DS,Reach-1,2
Up Type=0
Dn Type=3
Dn Slope=0.005
Boundary for River Rch & Prof#=Stream0251_DS,Reach-1,3
Up Type=0
Dn Type=3
Dn Slope=0.005
Boundary for River Rch & Prof#=Stream0251_DS,Reach-1,4
Up Type=0
Dn Type=3
Dn Slope=0.005
Boundary for River Rch & Prof#=Stream0251_DS,Reach-1,5
Up Type=0
Dn Type=3
Dn Slope=0.005
Boundary for River Rch & Prof#=Stream0251_DS,Reach-1,6
Up Type=0
Dn Type=3
Dn Slope=0.005
Boundary for River Rch & Prof#=Stream0251_DS,Reach-1,7
Up Type=0
Dn Type=3
Dn Slope=0.005

--- Stream0251_DS.g01 (geometry) ---

Geom Title=Existing Conditions

River Reach=Stream0251_DS,Reach-1
Reach XY= 30
      2035275.00     13913775.00      2035316.85     13913730.62
      2035330.27     13913679.94      2035369.57     13913673.99
      2035423.33     13913678.67      2035472.66     13913719.25
      2035514.81     13913725.45      2035659.78     13913724.48
      2035681.06     13913716.86      2035730.94     13913677.25
      2035859.78     13913675.51      2035881.05     13913683.14
      2035930.94     13913722.73      2036064.56     13913726.40
      2036125.01     13913767.47      2036176.64     13913729.42
      2036227.19     13913718.87      2036276.73     13913678.31
      2036314.37     13913675.60      2036338.20     13913688.15
      2036422.71     13913769.15      2036473.26     13913779.19
      2036522.80     13913818.92      2036573.26     13913829.19
      2036622.68     13913869.35      2036645.09     13913875.11
      2036723.42     13913871.34      2036772.78     13913831.03
      2036831.15     13913817.09      2036875.00     13913775.00

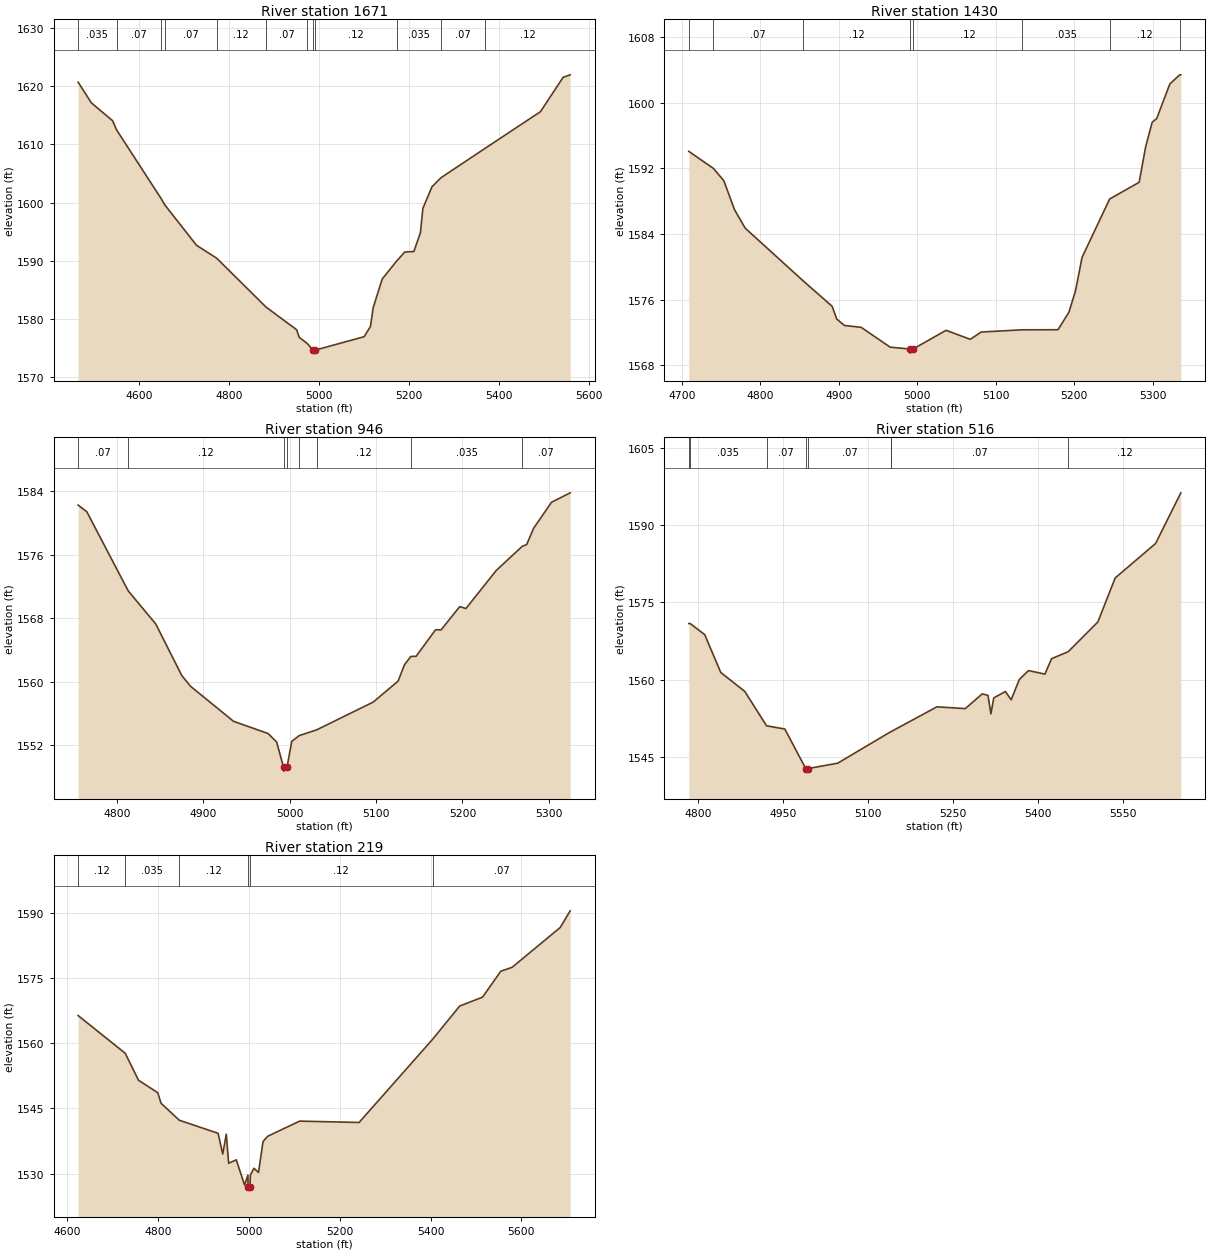
Type RM Length L Ch R = 1,1671,241,241,241
BEGIN DESCRIPTION:
Stream0251_DS 4.0
END DESCRIPTION:
XS GIS Cut Line= 3
      2035187.73     13914165.57      2035399.82     13913674.51
      2035449.92     13913119.37
#Sta/Elev= 30
  4465.1 1620.69  4494.5 1617.13  4541.5 1614.07  4550.6 1612.47  4649.0 1600.72
  4657.2 1599.63  4727.8 1592.66  4772.6 1590.44  4882.3 1582.03  4950.2 1578.14
  4955.9 1576.84  4973.4 1575.80  4986.6 1574.62  4986.8 1574.12  4990.6 1574.62
  5099.9 1576.94  5114.1 1578.71  5120.0 1581.91  5140.1 1586.85  5172.2 1589.95
  5190.3 1591.50  5210.4 1591.58  5225.0 1594.84  5230.4 1598.98  5250.5 1602.70
  5270.7 1604.27  5369.2 1609.35  5491.5 1615.62  5541.7 1621.52  5557.4 1621.95
#Mann=12,-1,0
  4465.1   0.035       0  4550.6    0.07       0  4649.0    0.12       0
  4657.2    0.07       0  4772.6    0.12       0  4882.3    0.07       0
  4973.4    0.12       0  4986.6    0.05       0  4990.6    0.12       0
  5172.2   0.035       0  5270.7    0.07       0  5369.2    0.12       0
Bank Sta=4986.6,4990.6
Exp/Cntr=0.3,0.1

Type RM Length L Ch R = 1,1430,484,484,484
BEGIN DESCRIPTION:
Stream0251_DS 3.0
END DESCRIPTION:
XS GIS Cut Line= 3
      2035474.99     13913975.02      2035625.00     13913725.00
      2035474.99     13913424.99
#Sta/Elev= 30
  4708.9 1594.07  4740.3 1591.99  4753.6 1590.49  4767.2 1586.96  4780.8 1584.71
  4854.5 1578.31  4891.6 1575.19  4897.5 1573.64  4907.2 1572.86  4928.6 1572.63
  4965.5 1570.22  4990.7 1569.99  4991.0 1569.49  4994.7 1569.99  5036.8 1572.27
  5067.6 1571.17  5081.5 1572.06  5133.5 1572.33  5179.4 1572.34  5193.3 1574.47
  5201.7 1577.08  5210.1 1581.16  5245.2 1588.26  5282.8 1590.30  5291.2 1594.68
  5299.5 1597.63  5305.1 1598.05  5321.9 1602.27  5334.5 1603.39  5335.9 1603.39
#Mann=8,-1,0
  4708.9    0.12       0  4740.3    0.07       0  4854.5    0.12       0
  4990.7    0.05       0  4994.7    0.12       0  5133.5   0.035       0
  5245.2    0.12       0  5334.5   0.035       0
Bank Sta=4990.7,4994.7
Exp/Cntr=0.3,0.1

Type RM Length L Ch R = 1,946,430,430,430
BEGIN DESCRIPTION:
Stream0251_DS 2.0
END DESCRIPTION:
XS GIS Cut Line= 3
      2036075.00     13913974.98      2036075.00     13913725.00
      2035875.02     13913475.02
#Sta/Elev= 30
  4754.8 1582.27  4764.8 1581.44  4812.8 1571.45  4844.8 1567.26  4874.8 1560.78
  4884.8 1559.43  4934.8 1554.99  4974.8 1553.45  4984.8 1552.38  4992.8 1549.20
  4993.0 1548.70  4996.8 1549.20  5002.3 1552.45  5011.1 1553.19  5031.4 1553.92
  5096.8 1557.42  5125.6 1560.07  5132.8 1562.10  5140.2 1563.17  5146.4 1563.19
  5168.9 1566.54  5175.3 1566.52  5196.9 1569.46  5204.1 1569.22  5239.3 1574.03
  5269.4 1577.07  5274.5 1577.29  5282.5 1579.34  5303.3 1582.63  5324.9 1583.82
#Mann=8,-1,0
  4754.8    0.07       0  4812.8    0.12       0  4992.8    0.05       0
  4996.8    0.12       0  5011.1   0.035       0  5031.4    0.12       0
  5140.2   0.035       0  5269.4    0.07       0
Bank Sta=4992.8,4996.8
Exp/Cntr=0.3,0.1

Type RM Length L Ch R = 1,516,297,297,297
BEGIN DESCRIPTION:
Stream0251_DS 1.0
END DESCRIPTION:
XS GIS Cut Line= 3
      2036275.03     13913924.97      2036425.00     13913775.00
      2036557.84     13913131.46
#Sta/Elev= 30
  4783.5 1570.90  4786.0 1570.90  4811.7 1568.74  4840.0 1561.40  4882.5 1557.72
  4920.9 1551.05  4953.2 1550.42  4990.1 1542.75  4990.3 1542.25  4994.1 1542.75
  5046.6 1543.79  5140.1 1549.89  5141.4 1549.95  5221.8 1554.73  5272.0 1554.39
  5301.9 1557.24  5312.1 1556.96  5317.2 1553.37  5322.3 1556.46  5342.8 1557.71
  5353.0 1556.10  5367.4 1560.04  5383.6 1561.77  5412.6 1561.08  5424.4 1564.07
  5453.8 1565.44  5506.1 1571.19  5536.8 1579.75  5608.2 1586.44  5652.7 1596.27
#Mann=8,-1,0
  4783.5    0.12       0  4786.0   0.035       0  4920.9    0.07       0
  4990.1    0.05       0  4994.1    0.07       0  5140.1    0.12       0
  5141.4    0.07       0  5453.8    0.12       0
Bank Sta=4990.1,4994.1
Exp/Cntr=0.3,0.1

Type RM Length L Ch R = 1,219,0,0,0
BEGIN DESCRIPTION:
Stream0251_DS 0.0
END DESCRIPTION:
XS GIS Cut Line= 4
      2036343.31     13913978.35      2036679.14     13913907.06
      2036690.06     13913875.72      2036604.46     13913173.32
#Sta/Elev= 30
  4623.5 1566.36  4727.2 1557.70  4756.5 1551.49  4799.0 1548.62  4806.2 1546.20
  4846.4 1542.29  4931.9 1539.29  4942.1 1534.51  4949.9 1539.09  4955.1 1532.40
  4971.9 1533.19  4990.2 1527.40  4997.6 1529.68  4997.9 1526.95  4998.2 1526.45
  5001.9 1526.95  5003.1 1529.68  5010.8 1531.25  5020.9 1530.29  5030.9 1537.38
  5041.0 1538.60  5111.5 1542.09  5242.5 1541.78  5404.6 1560.92  5464.1 1568.55
  5514.5 1570.60  5554.8 1576.57  5579.6 1577.45  5685.8 1586.63  5707.6 1590.45
#Mann=6,-1,0
  4623.5    0.12       0  4727.2   0.035       0  4846.4    0.12       0
  4997.9    0.05       0  5001.9    0.12       0  5404.6    0.07       0
Bank Sta=4997.9,5001.9
Exp/Cntr=0.3,0.1

Chan Stop Cuts=-1