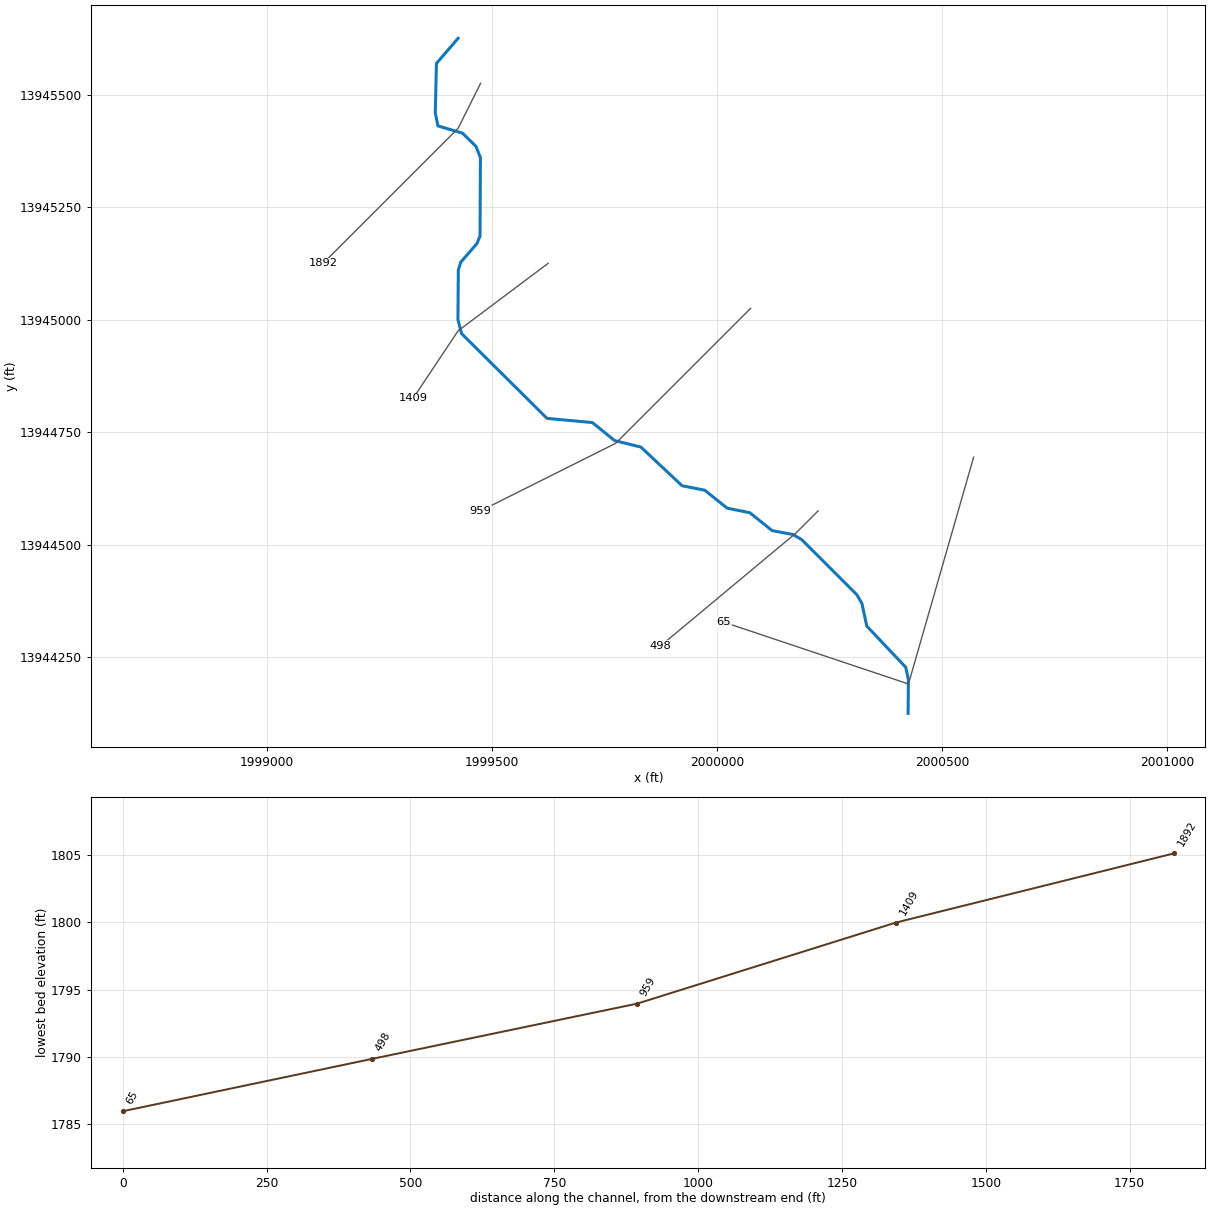
--- Stream0253_DS.prj (project) ---

Proj Title=Stream0253_DS Base Level Engineering
Current Plan=p01
Default Exp/Contr=0.3,0.1
English Units
Geom File=g01
Flow File=f01
Plan File=p01
BEGIN DESCRIPTION:
Stream0253_DS
END DESCRIPTION:

--- Stream0253_DS.p01 (plan) ---

Plan Title=Multiple Run
Short Identifier=Multiple
Geom File=g01
Flow File=f01
Subcritical Flow
K Sum by GR= 0
Std Step Tol= 0.01
Critical Tol= 0.01
Num of Std Step Trials= 20
Max Error Tol= 0.3
Flow Tol Ratio= 0.001
Split Flow NTrial= 30
Split Flow Tol= 0.02
Split Flow Ratio= 0.02
Log Output Level= 0
Friction Slope Method= 1
Unsteady Friction Slope Method= 2
Unsteady Bridges Friction Slope Method= 1
Parabolic Critical Depth
Global Vel Dist=  1 , 1 , 1
Global Log Level= 0
CheckData=True
Encroach Param= -1, 0, 0, 0
BEGIN DESCRIPTION:
Multiple Run
END DESCRIPTION:

--- Stream0253_DS.f01 (steady flow) ---

Flow Title=Multiple
Number of Profiles=7
Profile Names=10-year,25-year,50-year,1pct_min,100-year,1pct_plu,500-year
River Rch & RM= Stream0253_DS,Reach-1,1892
     965    1656    2322    1580    3153    6292    5768
Boundary for River Rch & Prof#=Stream0253_DS,Reach-1,1
Up Type=0
Dn Type=3
Dn Slope=0.005
Boundary for River Rch & Prof#=Stream0253_DS,Reach-1,2
Up Type=0
Dn Type=3
Dn Slope=0.005
Boundary for River Rch & Prof#=Stream0253_DS,Reach-1,3
Up Type=0
Dn Type=3
Dn Slope=0.005
Boundary for River Rch & Prof#=Stream0253_DS,Reach-1,4
Up Type=0
Dn Type=3
Dn Slope=0.005
Boundary for River Rch & Prof#=Stream0253_DS,Reach-1,5
Up Type=0
Dn Type=3
Dn Slope=0.005
Boundary for River Rch & Prof#=Stream0253_DS,Reach-1,6
Up Type=0
Dn Type=3
Dn Slope=0.005
Boundary for River Rch & Prof#=Stream0253_DS,Reach-1,7
Up Type=0
Dn Type=3
Dn Slope=0.005

--- Stream0253_DS.g01 (geometry) ---

Geom Title=Existing Conditions

River Reach=Stream0253_DS,Reach-1
Reach XY= 30
      1999425.00     13945625.00      1999376.87     13945569.20
      1999374.33     13945459.46      1999380.20     13945430.45
      1999434.75     13945414.25      1999464.60     13945385.10
      1999474.66     13945359.96      1999473.78     13945185.51
      1999466.86     13945168.94      1999430.74     13945127.33
      1999425.51     13945109.78      1999424.68     13944999.89
      1999432.81     13944968.81      1999622.57     13944780.52
      1999723.41     13944771.17      1999772.83     13944731.14
      1999831.05     13944716.84      1999922.71     13944630.85
      1999973.26     13944620.81      2000022.80     13944581.08
      2000073.28     13944570.84      2000122.81     13944531.10
      2000168.97     13944522.50      2000188.22     13944511.38
      2000311.37     13944388.21      2000322.47     13944368.95
      2000333.18     13944318.96      2000419.64     13944227.49
      2000425.59     13944200.24      2000425.00     13944125.00

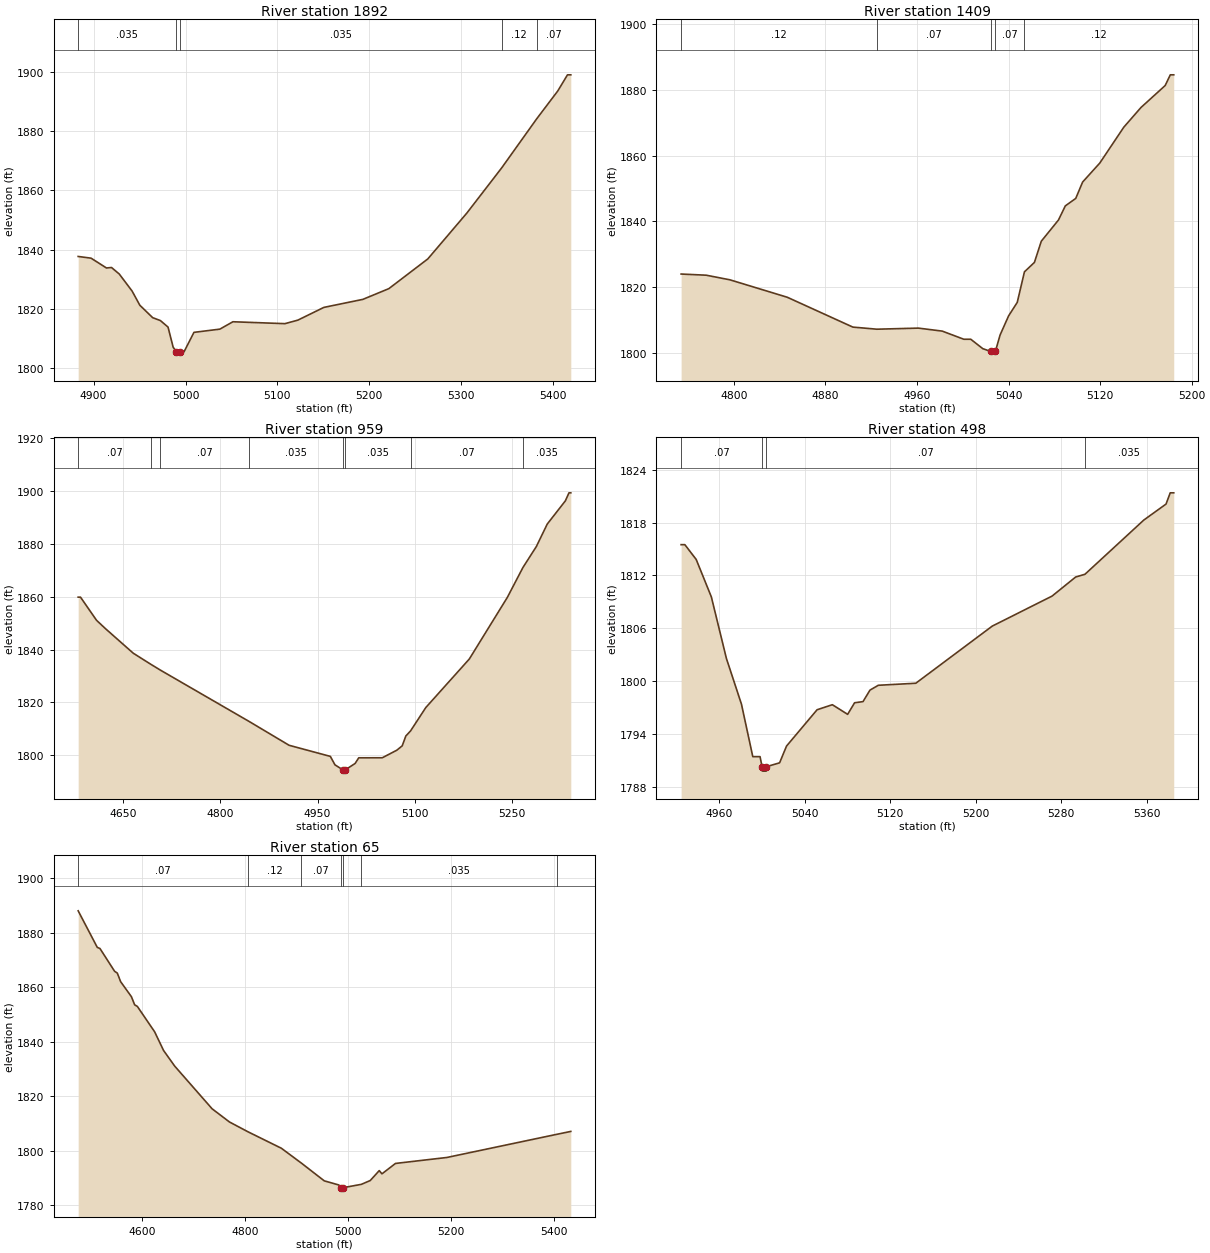
Type RM Length L Ch R = 1,1892,483,483,483
BEGIN DESCRIPTION:
Stream0253_DS 4.0
END DESCRIPTION:
XS GIS Cut Line= 3
      1999475.00     13945525.01      1999425.00     13945425.00
      1999124.98     13945124.98
#Sta/Elev= 30
  4883.2 1837.70  4897.2 1837.13  4914.0 1833.82  4919.5 1833.98  4927.9 1831.79
  4941.9 1826.04  4950.3 1821.27  4964.3 1817.07  4972.7 1816.10  4981.0 1813.90
  4986.6 1807.09  4990.2 1805.63  4990.5 1805.13  4994.2 1805.63  4998.5 1805.63
  5009.2 1812.13  5037.4 1813.21  5051.6 1815.70  5108.2 1815.06  5122.3 1816.25
  5150.6 1820.54  5193.0 1823.24  5221.3 1826.86  5263.7 1836.87  5306.1 1852.29
  5344.1 1867.55  5382.3 1884.12  5405.1 1893.45  5415.7 1898.90  5419.3 1898.90
#Mann=5,-1,0
  4883.2   0.035       0  4990.2    0.05       0  4994.2   0.035       0
  5344.1    0.12       0  5382.3    0.07       0
Bank Sta=4990.2,4994.2
Exp/Cntr=0.3,0.1

Type RM Length L Ch R = 1,1409,450,450,450
BEGIN DESCRIPTION:
Stream0253_DS 3.0
END DESCRIPTION:
XS GIS Cut Line= 3
      1999625.01     13945125.01      1999425.00     13944975.00
      1999324.99     13944824.99
#Sta/Elev= 30
  4754.0 1824.02  4775.9 1823.67  4796.7 1822.26  4846.7 1816.97  4904.0 1807.90
  4925.0 1807.26  4961.3 1807.59  4982.1 1806.68  5000.9 1804.21  5007.0 1804.21
  5017.5 1801.35  5024.5 1800.49  5024.8 1799.99  5028.5 1800.49  5032.6 1805.48
  5040.1 1811.34  5047.6 1815.40  5053.9 1824.70  5062.6 1827.55  5068.6 1833.99
  5083.6 1840.43  5089.6 1844.73  5098.7 1847.00  5104.7 1851.97  5119.7 1857.74
  5140.7 1868.65  5155.7 1874.63  5176.8 1881.29  5181.3 1884.55  5184.3 1884.55
#Mann=5,-1,0
  4754.0    0.12       0  4925.0    0.07       0  5024.5    0.05       0
  5028.5    0.07       0  5053.9    0.12       0
Bank Sta=5024.5,5028.5
Exp/Cntr=0.3,0.1

Type RM Length L Ch R = 1,959,461,461,461
BEGIN DESCRIPTION:
Stream0253_DS 2.0
END DESCRIPTION:
XS GIS Cut Line= 3
      2000075.01     13945025.01      1999775.00     13944725.00
      1999474.99     13944575.00
#Sta/Elev= 30
  4580.8 1859.88  4584.4 1859.88  4609.1 1851.12  4623.2 1847.88  4665.7 1838.65
  4692.6 1834.48  4707.5 1832.25  4844.7 1812.74  4906.1 1803.75  4969.7 1799.54
  4976.8 1796.35  4988.9 1794.46  4989.2 1793.96  4992.9 1794.46  5007.9 1796.87
  5013.5 1799.01  5049.8 1799.02  5072.2 1801.89  5080.5 1803.54  5086.1 1807.27
  5093.4 1809.20  5116.9 1818.05  5184.0 1836.44  5242.7 1859.81  5266.7 1871.12
  5287.4 1879.07  5304.2 1887.58  5332.1 1896.36  5337.7 1899.41  5340.5 1899.41
#Mann=8,-1,0
  4580.8    0.07       0  4692.6    0.12       0  4707.5    0.07       0
  4844.7   0.035       0  4988.9   0.035       0  4992.9   0.035       0
  5093.4    0.07       0  5266.7   0.035       0
Bank Sta=4988.9,4992.9
Exp/Cntr=0.3,0.1

Type RM Length L Ch R = 1,498,433,433,433
BEGIN DESCRIPTION:
Stream0253_DS 1.0
END DESCRIPTION:
XS GIS Cut Line= 3
      2000224.98     13944574.98      2000175.00     13944525.00
      1999874.99     13944274.99
#Sta/Elev= 30
  4924.3 1815.49  4927.8 1815.49  4938.4 1813.82  4952.6 1809.58  4966.7 1802.61
  4980.8 1797.43  4991.4 1791.49  4998.2 1791.49  5000.1 1790.35  5000.4 1789.85
  5003.9 1789.85  5004.1 1790.35  5016.5 1790.79  5023.0 1792.69  5051.6 1796.80
  5065.9 1797.37  5080.2 1796.28  5086.7 1797.59  5094.6 1797.72  5101.1 1799.02
  5108.9 1799.57  5144.0 1799.80  5215.6 1806.27  5271.6 1809.67  5293.7 1811.83
  5302.4 1812.14  5357.5 1818.28  5378.3 1820.09  5382.2 1821.36  5385.5 1821.36
#Mann=4,-1,0
  4924.3    0.07       0  5000.1    0.05       0  5004.1    0.07       0
  5302.4   0.035       0
Bank Sta=5000.1,5004.1
Exp/Cntr=0.3,0.1

Type RM Length L Ch R = 1,65,0,0,0
BEGIN DESCRIPTION:
Stream0253_DS 0.0
END DESCRIPTION:
XS GIS Cut Line= 3
      2000570.60     13944694.34      2000425.79     13944190.33
      2000015.66     13944327.63
#Sta/Elev= 30
  4475.6 1888.01  4512.7 1874.61  4517.9 1874.20  4546.4 1865.83  4551.6 1865.18
  4558.1 1862.03  4579.0 1856.53  4585.3 1853.55  4590.5 1852.97  4624.2 1843.63
  4641.4 1836.83  4663.1 1831.07  4735.7 1815.43  4769.5 1810.58  4805.5 1806.98
  4870.3 1800.95  4908.7 1795.57  4953.6 1789.00  4982.1 1787.47  4985.3 1786.46
  4985.6 1785.96  4989.3 1786.46  5025.6 1787.71  5043.0 1789.12  5060.4 1792.75
  5065.7 1791.57  5092.0 1795.38  5191.9 1797.57  5405.6 1806.07  5432.5 1807.12
#Mann=7,-1,0
  4475.6    0.07       0  4805.5    0.12       0  4908.7    0.07       0
  4985.3    0.05       0  4989.3    0.07       0  5025.6   0.035       0
  5405.6    0.07       0
Bank Sta=4985.3,4989.3
Exp/Cntr=0.3,0.1

Chan Stop Cuts=-1