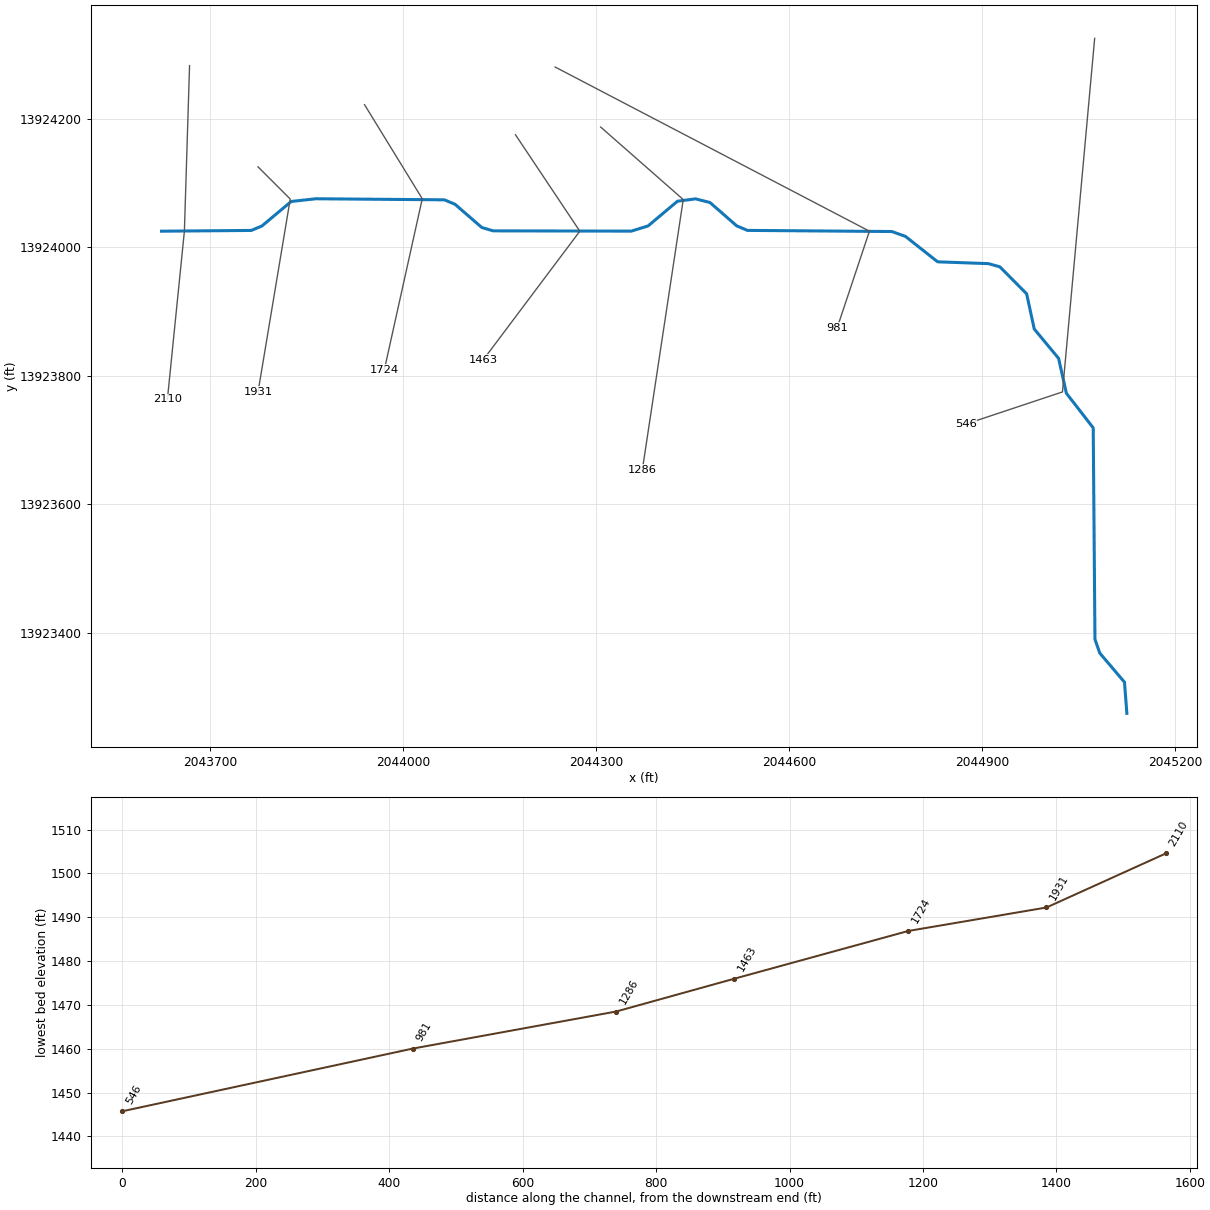
--- Stream0254_DS.prj (project) ---

Proj Title=Stream0254_DS Base Level Engineering
Current Plan=p01
Default Exp/Contr=0.3,0.1
English Units
Geom File=g01
Flow File=f01
Plan File=p01
BEGIN DESCRIPTION:
Stream0254_DS
END DESCRIPTION:

--- Stream0254_DS.p01 (plan) ---

Plan Title=Multiple Run
Short Identifier=Multiple
Geom File=g01
Flow File=f01
Subcritical Flow
K Sum by GR= 0
Std Step Tol= 0.01
Critical Tol= 0.01
Num of Std Step Trials= 20
Max Error Tol= 0.3
Flow Tol Ratio= 0.001
Split Flow NTrial= 30
Split Flow Tol= 0.02
Split Flow Ratio= 0.02
Log Output Level= 0
Friction Slope Method= 1
Unsteady Friction Slope Method= 2
Unsteady Bridges Friction Slope Method= 1
Parabolic Critical Depth
Global Vel Dist=  1 , 1 , 1
Global Log Level= 0
CheckData=True
Encroach Param= -1, 0, 0, 0
BEGIN DESCRIPTION:
Multiple Run
END DESCRIPTION:

--- Stream0254_DS.f01 (steady flow) ---

Flow Title=Multiple
Number of Profiles=7
Profile Names=10-year,25-year,50-year,1pct_min,100-year,1pct_plu,500-year
River Rch & RM= Stream0254_DS,Reach-1,2110
     294     464     614     398     794    1584    1307
Boundary for River Rch & Prof#=Stream0254_DS,Reach-1,1
Up Type=0
Dn Type=3
Dn Slope=0.005
Boundary for River Rch & Prof#=Stream0254_DS,Reach-1,2
Up Type=0
Dn Type=3
Dn Slope=0.005
Boundary for River Rch & Prof#=Stream0254_DS,Reach-1,3
Up Type=0
Dn Type=3
Dn Slope=0.005
Boundary for River Rch & Prof#=Stream0254_DS,Reach-1,4
Up Type=0
Dn Type=3
Dn Slope=0.005
Boundary for River Rch & Prof#=Stream0254_DS,Reach-1,5
Up Type=0
Dn Type=3
Dn Slope=0.005
Boundary for River Rch & Prof#=Stream0254_DS,Reach-1,6
Up Type=0
Dn Type=3
Dn Slope=0.005
Boundary for River Rch & Prof#=Stream0254_DS,Reach-1,7
Up Type=0
Dn Type=3
Dn Slope=0.005

--- Stream0254_DS.g01 (geometry) ---

Geom Title=Existing Conditions

River Reach=Stream0254_DS,Reach-1
Reach XY= 30
      2043625.00     13924025.00      2043764.52     13924026.17
      2043781.06     13924033.13      2043826.56     13924071.22
      2043864.81     13924075.45      2044064.50     13924073.78
      2044081.06     13924066.86      2044122.67     13924030.75
      2044140.22     13924025.52      2044354.97     13924025.09
      2044381.08     13924033.19      2044426.74     13924071.63
      2044454.82     13924075.28      2044477.18     13924069.62
      2044518.92     13924033.19      2044535.50     13924026.24
      2044759.78     13924024.48      2044781.06     13924016.86
      2044830.98     13923977.36      2044909.91     13923974.53
      2044927.68     13923969.58      2044969.28     13923927.58
      2044981.12     13923872.84      2045018.92     13923827.20
      2045031.12     13923772.82      2045072.76     13923719.07
      2045075.45     13923390.19      2045082.89     13923368.84
      2045121.35     13923323.49      2045125.00     13923275.00

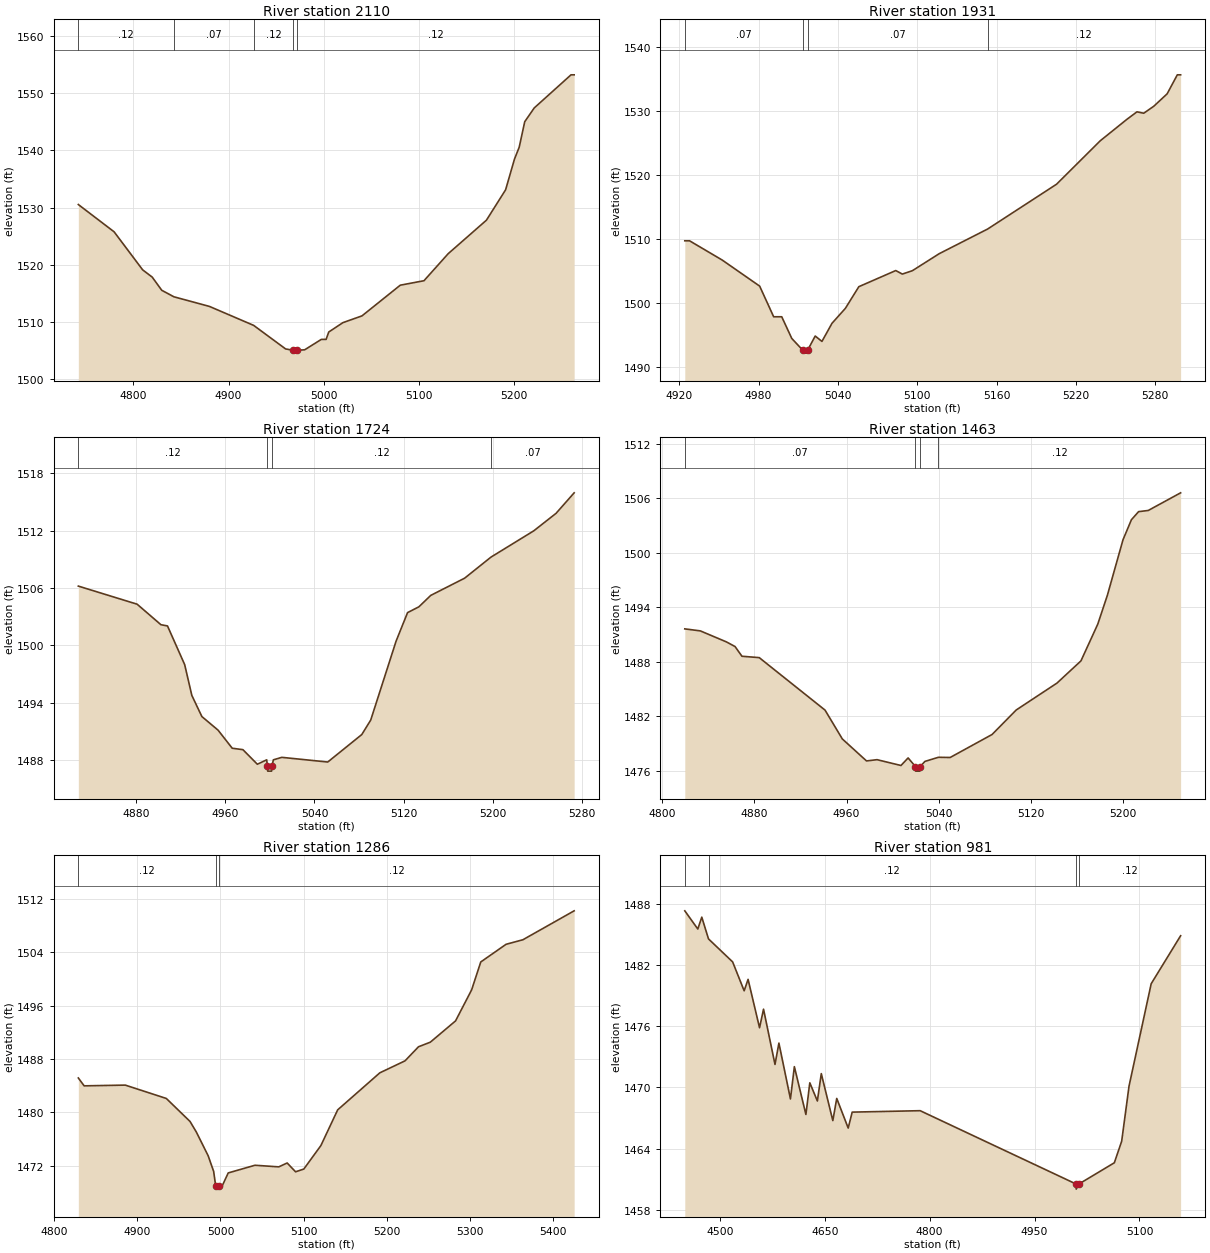
Type RM Length L Ch R = 1,2110,179,179,179
BEGIN DESCRIPTION:
Stream0254_DS 5.0
END DESCRIPTION:
XS GIS Cut Line= 3
      2043668.58     13924282.59      2043660.55     13924024.99
      2043634.13     13923763.35
#Sta/Elev= 30
  4742.2 1530.53  4779.8 1525.76  4809.8 1519.11  4819.8 1517.85  4829.8 1515.55
  4842.6 1514.41  4879.9 1512.73  4926.3 1509.42  4959.9 1505.30  4967.9 1505.07
  4968.2 1504.57  4971.7 1504.57  4971.9 1505.07  4979.9 1505.15  4997.4 1506.97
  5002.4 1506.97  5005.2 1508.26  5020.0 1509.89  5040.1 1511.08  5080.3 1516.44
  5105.2 1517.22  5130.6 1521.94  5170.8 1527.80  5190.9 1533.10  5200.2 1538.45
  5205.2 1540.55  5211.0 1545.00  5221.0 1547.41  5259.6 1553.19  5262.9 1553.19
#Mann=5,-1,0
  4742.2    0.12       0  4842.6    0.07       0  4926.3    0.12       0
  4967.9    0.05       0  4971.9    0.12       0
Bank Sta=4967.9,4971.9
Exp/Cntr=0.3,0.1

Type RM Length L Ch R = 1,1931,207,207,207
BEGIN DESCRIPTION:
Stream0254_DS 4.0
END DESCRIPTION:
XS GIS Cut Line= 3
      2043774.97     13924125.03      2043825.00     13924075.00
      2043775.00     13923774.99
#Sta/Elev= 30
  4924.2 1509.78  4927.8 1509.78  4952.5 1506.77  4980.8 1502.70  4991.4 1497.91
  4997.5 1497.91  5005.1 1494.52  5013.2 1492.73  5013.5 1492.23  5017.0 1492.23
  5017.2 1492.73  5022.8 1494.90  5027.9 1494.06  5035.5 1496.89  5045.6 1499.22
  5055.8 1502.61  5083.7 1505.13  5088.7 1504.58  5096.3 1505.11  5116.6 1507.77
  5153.2 1511.62  5205.3 1518.62  5238.3 1525.40  5258.5 1528.76  5266.1 1529.93
  5271.2 1529.71  5278.8 1530.80  5288.9 1532.74  5296.6 1535.71  5299.1 1535.71
#Mann=4,-1,0
  4924.2    0.07       0  5013.2    0.05       0  5017.2    0.07       0
  5153.2    0.12       0
Bank Sta=5013.2,5017.2
Exp/Cntr=0.3,0.1

Type RM Length L Ch R = 1,1724,261,261,261
BEGIN DESCRIPTION:
Stream0254_DS 3.5
END DESCRIPTION:
XS GIS Cut Line= 3
      2043940.49     13924221.74      2044030.18     13924075.44
      2043971.16     13923809.20
#Sta/Elev= 30
  4828.4 1506.20  4881.1 1504.31  4902.4 1502.17  4908.3 1502.04  4923.7 1498.00
  4930.1 1494.79  4939.1 1492.58  4953.6 1491.16  4966.3 1489.27  4975.9 1489.12
  4988.8 1487.60  4997.2 1488.06  4997.8 1487.38  4998.1 1486.88  5001.6 1486.88
  5001.8 1487.38  5003.2 1488.06  5010.7 1488.32  5051.9 1487.83  5082.4 1490.70
  5090.4 1492.21  5113.1 1500.44  5123.4 1503.43  5133.6 1504.04  5144.2 1505.23
  5174.6 1507.03  5198.2 1509.23  5236.5 1511.97  5256.5 1513.80  5272.7 1515.94
#Mann=4,-1,0
  4828.4    0.12       0  4997.8    0.05       0  5001.8    0.12       0
  5198.2    0.07       0
Bank Sta=4997.8,5001.8
Exp/Cntr=0.3,0.1

Type RM Length L Ch R = 1,1463,177,177,177
BEGIN DESCRIPTION:
Stream0254_DS 3.0
END DESCRIPTION:
XS GIS Cut Line= 3
      2044175.00     13924175.00      2044275.00     13924025.00
      2044124.99     13923824.98
#Sta/Elev= 30
  4819.6 1491.62  4833.1 1491.40  4855.7 1490.19  4863.2 1489.68  4869.2 1488.61
  4884.2 1488.46  4941.3 1482.69  4956.3 1479.52  4977.3 1477.10  4986.4 1477.24
  5007.2 1476.60  5013.4 1477.43  5019.8 1476.48  5020.0 1475.98  5023.5 1475.98
  5023.8 1476.48  5028.0 1477.05  5039.7 1477.50  5049.9 1477.48  5086.3 1480.01
  5107.2 1482.70  5142.6 1485.66  5163.4 1488.10  5178.0 1492.14  5186.3 1495.30
  5199.9 1501.42  5207.2 1503.62  5213.4 1504.51  5221.8 1504.64  5249.9 1506.58
#Mann=4,-1,0
  4819.6    0.07       0  5019.8    0.05       0  5023.8    0.07       0
  5039.7    0.12       0
Bank Sta=5019.8,5023.8
Exp/Cntr=0.3,0.1

Type RM Length L Ch R = 1,1286,305,305,305
BEGIN DESCRIPTION:
Stream0254_DS 2.5
END DESCRIPTION:
XS GIS Cut Line= 3
      2044307.39     13924186.97      2044435.69     13924074.23
      2044372.19     13923654.10
#Sta/Elev= 30
  4829.2 1485.17  4836.2 1483.99  4885.6 1484.10  4934.9 1482.10  4963.4 1478.65
  4971.0 1477.06  4985.2 1473.50  4991.8 1471.15  4994.2 1469.00  4994.5 1468.50
  4998.2 1469.00  5002.1 1469.00  5009.3 1470.93  5041.4 1472.08  5070.0 1471.84
  5080.1 1472.42  5090.2 1471.10  5100.1 1471.51  5120.6 1475.03  5140.8 1480.39
  5191.4 1485.94  5221.7 1487.74  5237.9 1489.85  5252.1 1490.54  5282.4 1493.73
  5301.7 1498.38  5312.7 1502.57  5343.1 1505.22  5363.3 1505.90  5424.9 1510.24
#Mann=3,-1,0
  4829.2    0.12       0  4994.2    0.05       0  4998.2    0.12       0
Bank Sta=4994.2,4998.2
Exp/Cntr=0.3,0.1

Type RM Length L Ch R = 1,981,435,435,435
BEGIN DESCRIPTION:
Stream0254_DS 2.0
END DESCRIPTION:
XS GIS Cut Line= 3
      2044236.71     13924280.31      2044725.00     13924025.00
      2044675.01     13923875.02
#Sta/Elev= 30
  4449.8 1487.29  4468.4 1485.51  4474.1 1486.67  4483.7 1484.54  4518.2 1482.29
  4534.7 1479.46  4540.3 1480.58  4556.7 1475.84  4562.4 1477.66  4578.8 1472.25
  4584.4 1474.34  4600.9 1468.87  4606.5 1472.03  4623.0 1467.35  4628.6 1470.45
  4639.4 1468.67  4645.0 1471.35  4661.5 1466.75  4667.1 1468.92  4683.5 1466.02
  4689.2 1467.58  4786.4 1467.72  5009.4 1460.54  5009.6 1460.04  5013.4 1460.54
  5064.1 1462.62  5074.6 1464.73  5085.1 1470.12  5116.8 1480.15  5158.9 1484.85
#Mann=4,-1,0
  4449.8    0.07       0  4483.7    0.12       0  5009.4    0.05       0
  5013.4    0.12       0
Bank Sta=5009.4,5013.4
Exp/Cntr=0.3,0.1

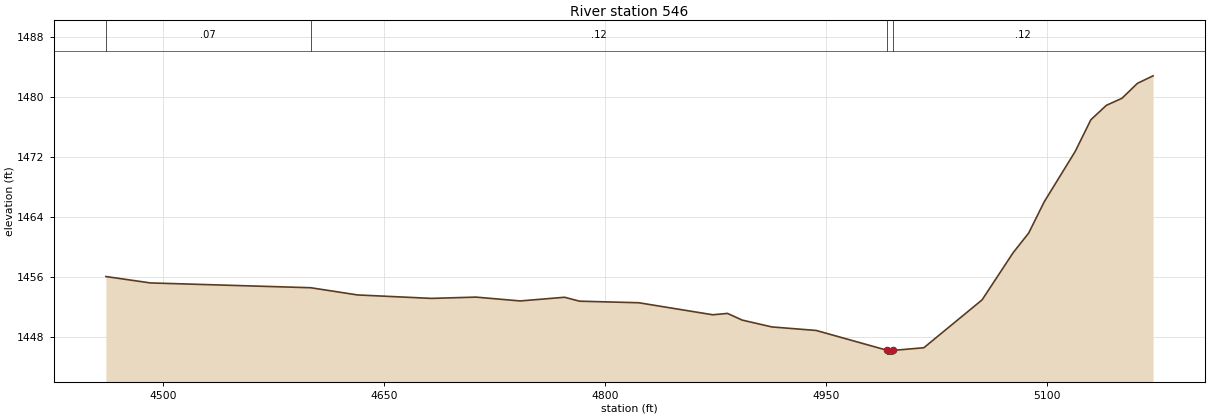
Type RM Length L Ch R = 1,546,0,0,0
BEGIN DESCRIPTION:
Stream0254_DS 1.0
END DESCRIPTION:
XS GIS Cut Line= 3
      2045075.00     13924324.97      2045025.00     13923775.00
      2044874.95     13923724.98
#Sta/Elev= 30
  4461.4 1456.08  4491.5 1455.23  4600.3 1454.59  4632.1 1453.63  4682.3 1453.17
  4712.4 1453.34  4742.5 1452.83  4772.6 1453.32  4782.7 1452.80  4822.9 1452.59
  4873.1 1450.99  4883.1 1451.17  4893.1 1450.28  4913.2 1449.37  4943.3 1448.90
  4991.6 1446.25  4991.8 1445.75  4995.3 1445.75  4995.6 1446.25  5016.3 1446.60
  5055.8 1452.97  5076.9 1459.26  5087.4 1461.86  5098.0 1466.04  5119.0 1472.74
  5129.6 1476.95  5140.1 1478.87  5150.7 1479.81  5161.2 1481.80  5171.8 1482.80
#Mann=4,-1,0
  4461.4    0.07       0  4600.3    0.12       0  4991.6    0.05       0
  4995.6    0.12       0
Bank Sta=4991.6,4995.6
Exp/Cntr=0.3,0.1

Chan Stop Cuts=-1