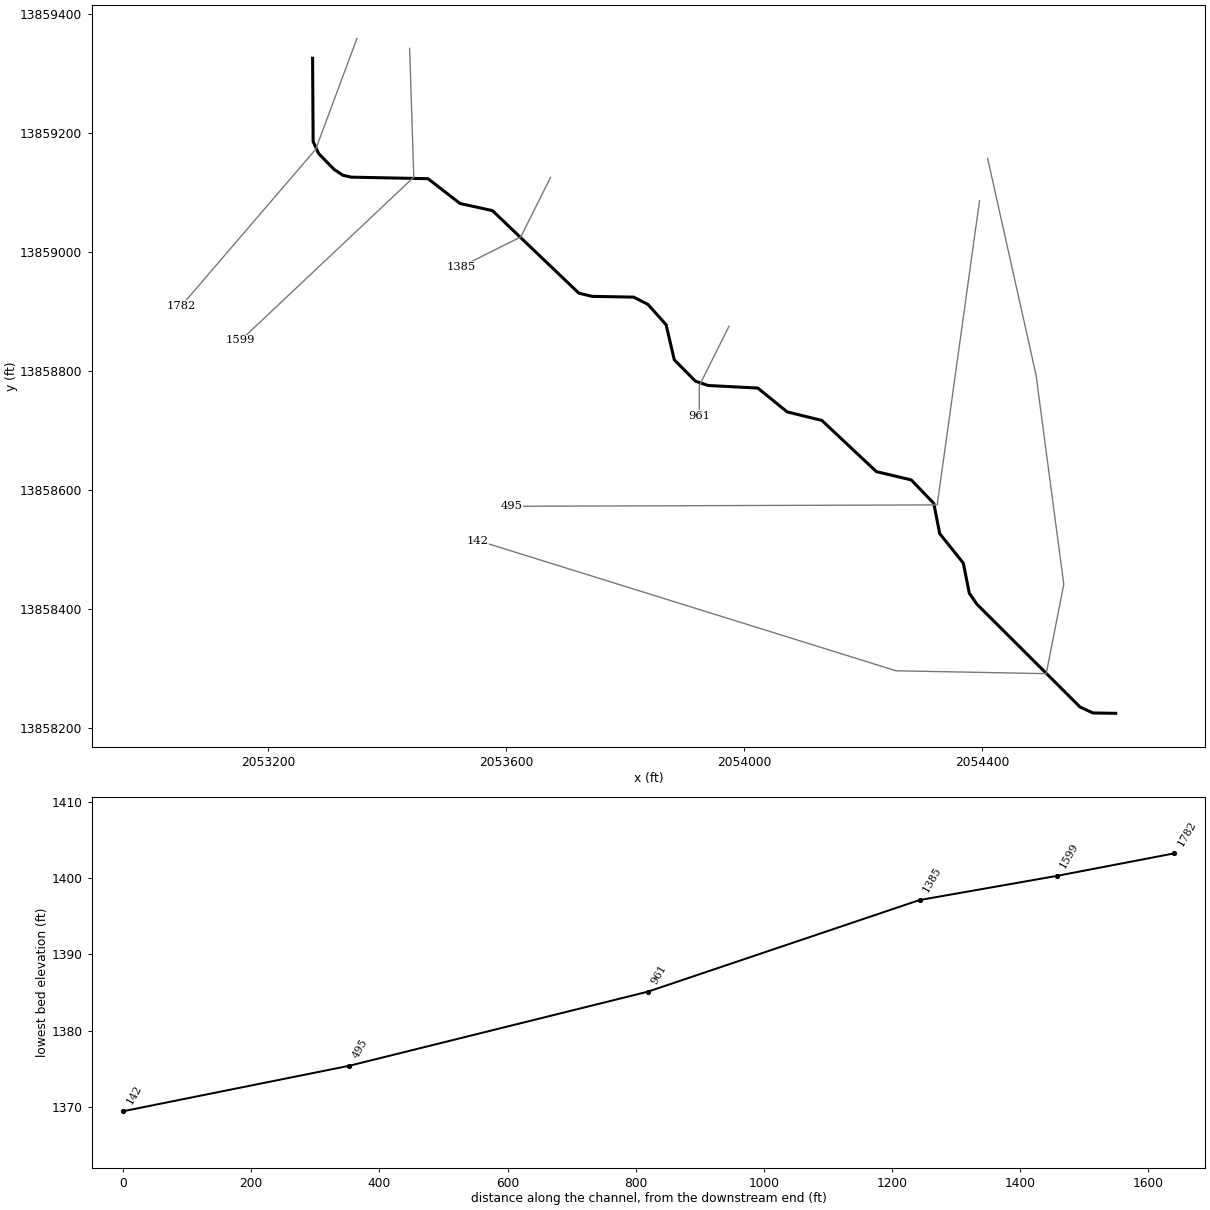
--- Stream0255_DS.prj (project) ---

Proj Title=Stream0255_DS Base Level Engineering
Current Plan=p01
Default Exp/Contr=0.3,0.1
English Units
Geom File=g01
Flow File=f01
Plan File=p01
BEGIN DESCRIPTION:
Stream0255_DS
END DESCRIPTION:

--- Stream0255_DS.p01 (plan) ---

Plan Title=Multiple Run
Short Identifier=Multiple
Geom File=g01
Flow File=f01
Subcritical Flow
K Sum by GR= 0
Std Step Tol= 0.01
Critical Tol= 0.01
Num of Std Step Trials= 20
Max Error Tol= 0.3
Flow Tol Ratio= 0.001
Split Flow NTrial= 30
Split Flow Tol= 0.02
Split Flow Ratio= 0.02
Log Output Level= 0
Friction Slope Method= 1
Unsteady Friction Slope Method= 2
Unsteady Bridges Friction Slope Method= 1
Parabolic Critical Depth
Global Vel Dist=  1 , 1 , 1
Global Log Level= 0
CheckData=True
Encroach Param= -1, 0, 0, 0
BEGIN DESCRIPTION:
Multiple Run
END DESCRIPTION:

--- Stream0255_DS.f01 (steady flow) ---

Flow Title=Multiple
Number of Profiles=7
Profile Names=10-year,25-year,50-year,1pct_min,100-year,1pct_plu,500-year
River Rch & RM= Stream0255_DS,Reach-1,1782
     591     965    1309     865    1726    3444    2956
Boundary for River Rch & Prof#=Stream0255_DS,Reach-1,1
Up Type=0
Dn Type=3
Dn Slope=0.005
Boundary for River Rch & Prof#=Stream0255_DS,Reach-1,2
Up Type=0
Dn Type=3
Dn Slope=0.005
Boundary for River Rch & Prof#=Stream0255_DS,Reach-1,3
Up Type=0
Dn Type=3
Dn Slope=0.005
Boundary for River Rch & Prof#=Stream0255_DS,Reach-1,4
Up Type=0
Dn Type=3
Dn Slope=0.005
Boundary for River Rch & Prof#=Stream0255_DS,Reach-1,5
Up Type=0
Dn Type=3
Dn Slope=0.005
Boundary for River Rch & Prof#=Stream0255_DS,Reach-1,6
Up Type=0
Dn Type=3
Dn Slope=0.005
Boundary for River Rch & Prof#=Stream0255_DS,Reach-1,7
Up Type=0
Dn Type=3
Dn Slope=0.005

--- Stream0255_DS.g01 (geometry) ---

Geom Title=Existing Conditions

River Reach=Stream0255_DS,Reach-1
Reach XY= 30
      2053275.00     13859325.00      2053275.91     13859185.23
      2053285.30     13859164.81      2053311.26     13859138.19
      2053326.22     13859128.44      2053340.02     13859125.34
      2053469.07     13859122.75      2053522.83     13859081.14
      2053577.30     13859069.17      2053722.58     13858930.53
      2053745.06     13858925.14      2053814.67     13858923.90
      2053838.65     13858911.74      2053869.25     13858877.55
      2053883.03     13858818.65      2053918.55     13858782.75
      2053940.09     13858775.47      2054023.41     13858771.17
      2054072.83     13858731.14      2054131.05     13858716.84
      2054222.74     13858630.88      2054281.33     13858616.96
      2054319.27     13858577.55      2054329.20     13858526.76
      2054368.90     13858477.19      2054378.95     13858426.63
      2054391.64     13858408.32      2054565.21     13858235.51
      2054586.84     13858225.59      2054625.00     13858225.00

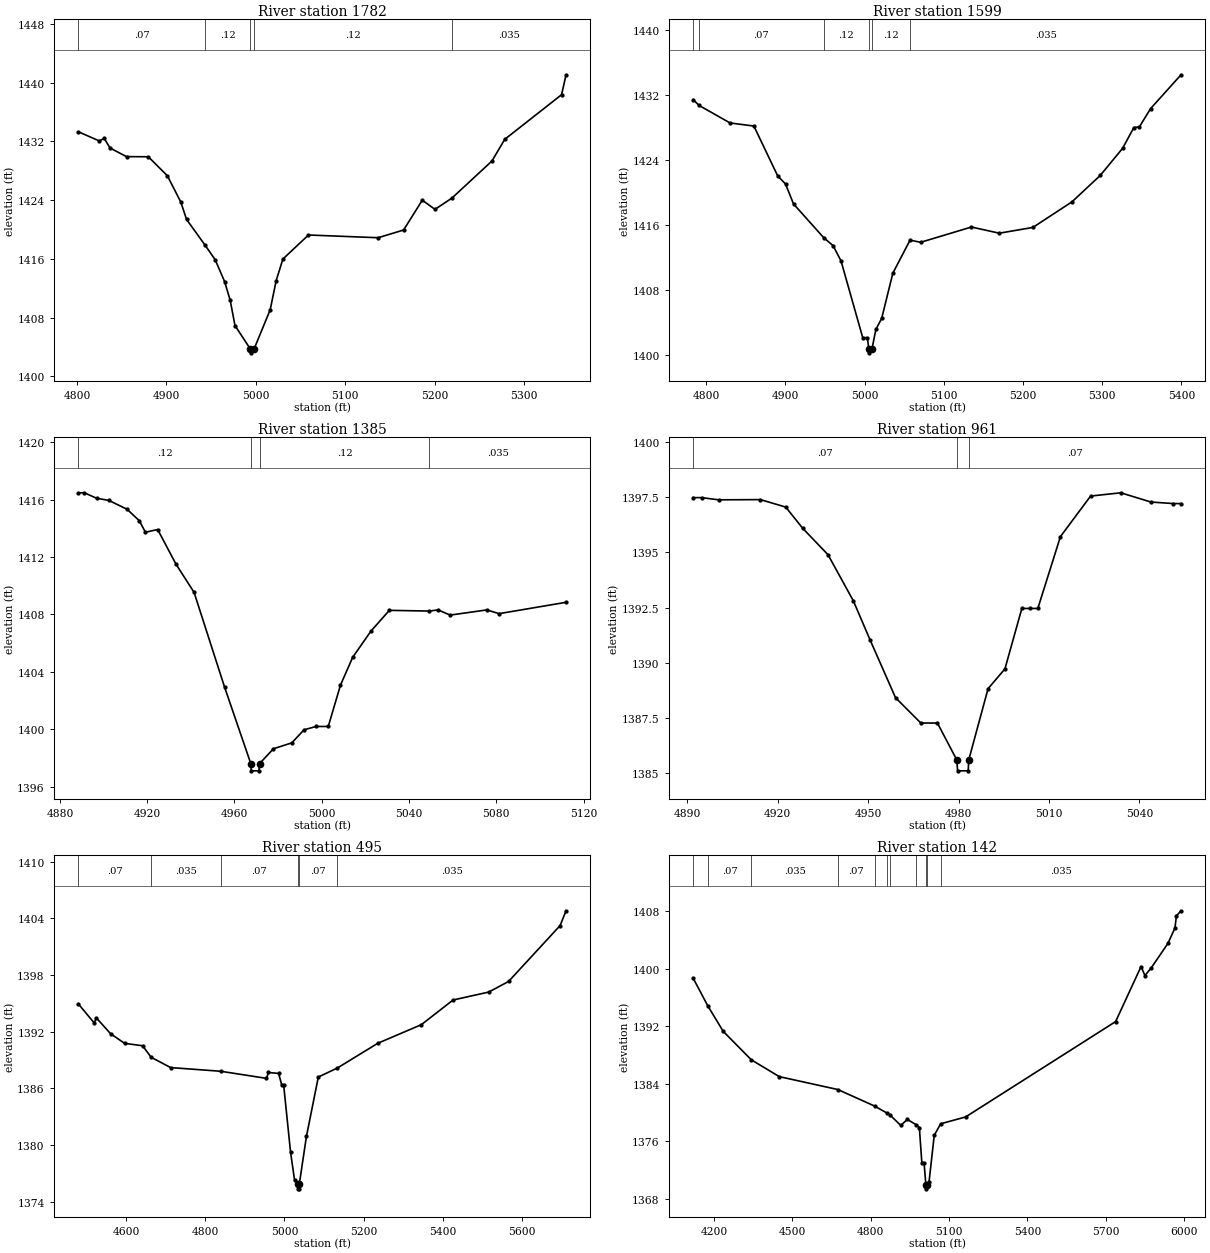
Type RM Length L Ch R = 1,1782,183,183,183
BEGIN DESCRIPTION:
Stream0255_DS 4.0
END DESCRIPTION:
XS GIS Cut Line= 3
      2053349.62     13859358.46      2053280.31     13859172.24
      2053054.28     13858909.09
#Sta/Elev= 30
  4801.3 1433.31  4824.9 1432.05  4830.3 1432.40  4837.0 1431.08  4855.3 1429.92
  4879.7 1429.90  4901.0 1427.31  4916.0 1423.74  4922.4 1421.38  4942.9 1417.91
  4954.4 1415.90  4965.0 1412.91  4971.3 1410.34  4976.6 1406.93  4993.9 1403.71
  4994.1 1403.21  4997.9 1403.71  5016.0 1409.08  5022.7 1413.05  5030.2 1415.98
  5058.8 1419.25  5136.7 1418.88  5165.2 1419.93  5186.1 1423.99  5200.3 1422.74
  5219.3 1424.28  5264.0 1429.32  5278.3 1432.27  5341.9 1438.35  5346.9 1441.06
#Mann=5,-1,0
  4801.3    0.07       0  4942.9    0.12       0  4993.9    0.05       0
  4997.9    0.12       0  5219.3   0.035       0
Bank Sta=4993.9,4997.9
Exp/Cntr=0.3,0.1

Type RM Length L Ch R = 1,1599,214,214,214
BEGIN DESCRIPTION:
Stream0255_DS 3.5
END DESCRIPTION:
XS GIS Cut Line= 3
      2053438.11     13859341.52      2053445.14     13859125.33
      2053154.31     13858851.43
#Sta/Elev= 30
  4783.7 1431.47  4791.1 1430.76  4830.2 1428.60  4860.3 1428.22  4890.3 1422.08
  4900.3 1421.07  4910.3 1418.62  4948.5 1414.45  4960.3 1413.47  4970.3 1411.59
  4997.7 1402.13  5003.5 1402.13  5005.4 1400.76  5005.7 1400.26  5009.4 1400.76
  5014.3 1403.15  5021.6 1404.50  5035.7 1410.08  5057.4 1414.15  5070.9 1413.89
  5134.9 1415.77  5170.1 1415.01  5212.5 1415.72  5261.9 1418.88  5297.5 1422.13
  5325.8 1425.48  5340.0 1428.04  5346.9 1428.11  5361.0 1430.36  5399.5 1434.54
#Mann=6,-1,0
  4783.7    0.12       0  4791.1    0.07       0  4948.5    0.12       0
  5005.4    0.05       0  5009.4    0.12       0  5057.4   0.035       0
Bank Sta=5005.4,5009.4
Exp/Cntr=0.3,0.1

Type RM Length L Ch R = 1,1385,424,424,424
BEGIN DESCRIPTION:
Stream0255_DS 3.0
END DESCRIPTION:
XS GIS Cut Line= 3
      2053675.02     13859125.03      2053625.00     13859025.00
      2053525.04     13858975.02
#Sta/Elev= 30
  4888.4 1416.47  4891.2 1416.47  4896.8 1416.09  4902.4 1415.94  4910.8 1415.32
  4916.4 1414.52  4919.2 1413.72  4924.8 1413.91  4933.2 1411.50  4941.5 1409.53
  4955.5 1402.92  4967.5 1397.60  4967.7 1397.10  4971.2 1397.10  4971.5 1397.60
  4977.9 1398.64  4986.3 1399.05  4991.9 1399.96  4997.4 1400.19  5003.0 1400.19
  5008.6 1403.07  5014.2 1405.01  5022.6 1406.84  5031.0 1408.28  5049.4 1408.23
  5053.3 1408.31  5058.9 1407.95  5075.7 1408.31  5081.3 1408.05  5112.0 1408.84
#Mann=4,-1,0
  4888.4    0.12       0  4967.5    0.05       0  4971.5    0.12       0
  5049.4   0.035       0
Bank Sta=4967.5,4971.5
Exp/Cntr=0.3,0.1

Type RM Length L Ch R = 1,961,466,466,466
BEGIN DESCRIPTION:
Stream0255_DS 2.0
END DESCRIPTION:
XS GIS Cut Line= 3
      2053974.99     13858874.99      2053925.00     13858775.00
      2053925.00     13858724.99
#Sta/Elev= 27
  4892.0 1397.49  4894.8 1397.49  4900.4 1397.39  4914.3 1397.40  4922.7 1397.06
  4928.3 1396.10  4936.7 1394.90  4945.1 1392.81  4950.7 1391.02  4959.1 1388.41
  4967.5 1387.26  4973.0 1387.26  4979.4 1385.59  4979.7 1385.09  4983.2 1385.09
  4983.4 1385.59  4989.8 1388.82  4995.4 1389.72  5001.0 1392.46  5003.8 1392.46
  5006.3 1392.46  5013.8 1395.72  5023.8 1397.56  5033.8 1397.71  5043.8 1397.29
  5051.3 1397.22  5053.8 1397.22
#Mann=3,-1,0
  4892.0    0.07       0  4979.4    0.05       0  4983.4    0.07       0
Bank Sta=4979.4,4983.4
Exp/Cntr=0.3,0.1

Type RM Length L Ch R = 1,495,353,353,353
BEGIN DESCRIPTION:
Stream0255_DS 1.0
END DESCRIPTION:
XS GIS Cut Line= 3
      2054396.17     13859085.84      2054325.00     13858575.00
      2053609.88     13858572.63
#Sta/Elev= 30
  4479.7 1394.96  4520.2 1392.92  4525.2 1393.48  4561.3 1391.79  4596.8 1390.77
  4642.1 1390.52  4663.6 1389.30  4712.8 1388.21  4839.1 1387.82  4954.6 1387.07
  4959.7 1387.69  4985.4 1387.59  4993.0 1386.38  4998.0 1386.38  5015.5 1379.23
  5025.5 1376.32  5033.5 1375.88  5033.7 1375.38  5037.2 1375.38  5037.5 1375.88
  5055.5 1380.93  5085.5 1387.21  5133.4 1388.16  5235.5 1390.78  5345.5 1392.75
  5425.5 1395.36  5515.5 1396.20  5565.5 1397.32  5695.5 1403.23  5710.6 1404.80
#Mann=6,-1,0
  4479.7    0.07       0  4663.6   0.035       0  4839.1    0.07       0
  5033.5    0.05       0  5037.5    0.07       0  5133.4   0.035       0
Bank Sta=5033.5,5037.5
Exp/Cntr=0.3,0.1

Type RM Length L Ch R = 1,142,0,0,0
BEGIN DESCRIPTION:
Stream0255_DS 0.0
END DESCRIPTION:
XS GIS Cut Line= 6
      2054409.72     13859156.96      2054491.10     13858793.28
      2054537.75     13858441.59      2054508.30     13858291.60
      2054255.84     13858296.43      2053552.79     13858515.16
#Sta/Elev= 30
  4119.7 1398.65  4175.4 1394.84  4234.4 1391.30  4342.5 1387.33  4449.6 1385.00
  4673.7 1383.21  4814.9 1380.91  4861.7 1379.95  4871.9 1379.74  4915.0 1378.22
  4939.9 1379.06  4972.7 1378.35  4986.2 1377.93  4995.7 1373.05  5004.2 1373.05
  5011.3 1369.92  5011.6 1369.42  5015.3 1369.92  5023.3 1370.40  5043.3 1376.86
  5067.7 1378.45  5163.3 1379.40  5738.1 1392.64  5835.7 1400.29  5850.3 1399.04
  5873.5 1400.04  5938.6 1403.50  5965.5 1405.63  5971.1 1407.32  5988.8 1408.03
#Mann=11,-1,0
  4119.7    0.12       0  4175.4    0.07       0  4342.5   0.035       0
  4673.7    0.07       0  4814.9   0.035       0  4861.7    0.07       0
  4871.9    0.12       0  4972.7    0.07       0  5011.3    0.05       0
  5015.3    0.07       0  5067.7   0.035       0
Bank Sta=5011.3,5015.3
Exp/Cntr=0.3,0.1

Chan Stop Cuts=-1