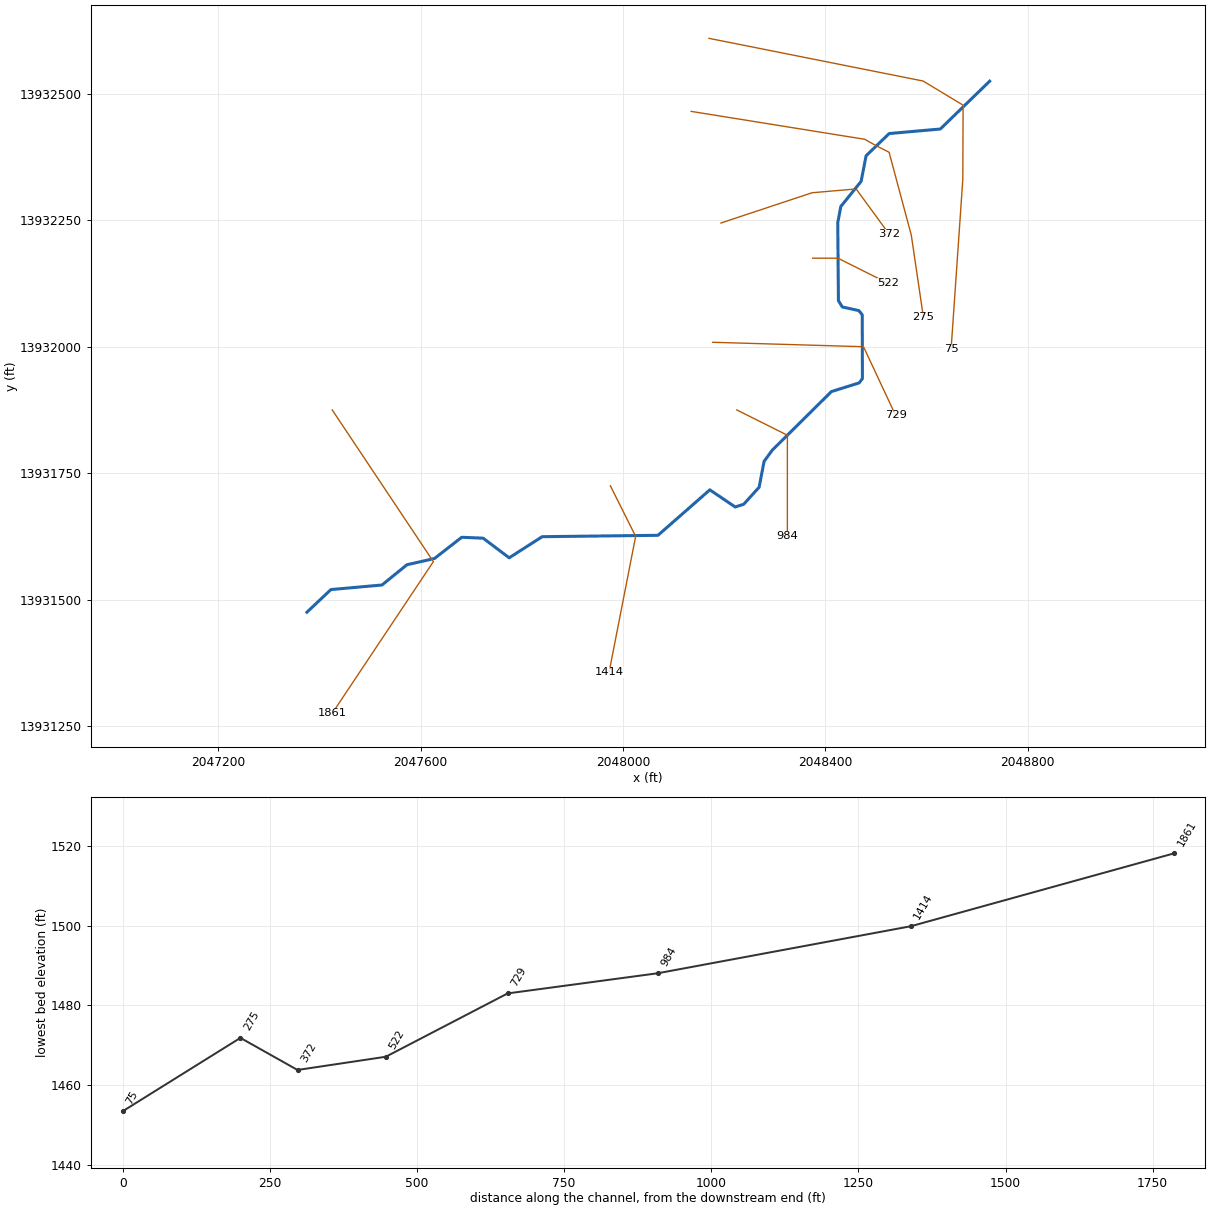
--- Stream0256_DS.prj (project) ---

Proj Title=Stream0256_DS Base Level Engineering
Current Plan=p01
Default Exp/Contr=0.3,0.1
English Units
Geom File=g01
Flow File=f01
Plan File=p01
BEGIN DESCRIPTION:
Stream0256_DS
END DESCRIPTION:

--- Stream0256_DS.p01 (plan) ---

Plan Title=Multiple Run
Short Identifier=Multiple
Geom File=g01
Flow File=f01
Subcritical Flow
K Sum by GR= 0
Std Step Tol= 0.01
Critical Tol= 0.01
Num of Std Step Trials= 20
Max Error Tol= 0.3
Flow Tol Ratio= 0.001
Split Flow NTrial= 30
Split Flow Tol= 0.02
Split Flow Ratio= 0.02
Log Output Level= 0
Friction Slope Method= 1
Unsteady Friction Slope Method= 2
Unsteady Bridges Friction Slope Method= 1
Parabolic Critical Depth
Global Vel Dist=  1 , 1 , 1
Global Log Level= 0
CheckData=True
Encroach Param= -1, 0, 0, 0
BEGIN DESCRIPTION:
Multiple Run
END DESCRIPTION:

--- Stream0256_DS.f01 (steady flow) ---

Flow Title=Multiple
Number of Profiles=7
Profile Names=10-year,25-year,50-year,1pct_min,100-year,1pct_plu,500-year
River Rch & RM= Stream0256_DS,Reach-1,1861
     435     712     969     644    1284    2563    2229
Boundary for River Rch & Prof#=Stream0256_DS,Reach-1,1
Up Type=0
Dn Type=3
Dn Slope=0.005
Boundary for River Rch & Prof#=Stream0256_DS,Reach-1,2
Up Type=0
Dn Type=3
Dn Slope=0.005
Boundary for River Rch & Prof#=Stream0256_DS,Reach-1,3
Up Type=0
Dn Type=3
Dn Slope=0.005
Boundary for River Rch & Prof#=Stream0256_DS,Reach-1,4
Up Type=0
Dn Type=3
Dn Slope=0.005
Boundary for River Rch & Prof#=Stream0256_DS,Reach-1,5
Up Type=0
Dn Type=3
Dn Slope=0.005
Boundary for River Rch & Prof#=Stream0256_DS,Reach-1,6
Up Type=0
Dn Type=3
Dn Slope=0.005
Boundary for River Rch & Prof#=Stream0256_DS,Reach-1,7
Up Type=0
Dn Type=3
Dn Slope=0.005

--- Stream0256_DS.g01 (geometry) ---

Geom Title=Existing Conditions

River Reach=Stream0256_DS,Reach-1
Reach XY= 30
      2047375.00     13931475.00      2047422.45     13931519.78
      2047523.43     13931528.80      2047572.82     13931568.89
      2047627.20     13931581.15      2047681.12     13931623.16
      2047723.36     13931621.40      2047774.99     13931582.59
      2047840.16     13931624.34      2048069.15     13931627.07
      2048171.68     13931716.98      2048221.85     13931683.08
      2048238.68     13931688.50      2048269.14     13931722.17
      2048278.98     13931773.29      2048294.79     13931795.07
      2048412.05     13931911.26      2048466.90     13931928.39
      2048473.39     13931936.84      2048473.05     13932063.01
      2048466.42     13932071.41      2048433.59     13932078.58
      2048425.96     13932090.96      2048424.63     13932245.15
      2048430.71     13932277.35      2048470.77     13932326.78
      2048480.71     13932377.58      2048526.28     13932421.48
      2048627.45     13932430.46      2048725.00     13932525.00

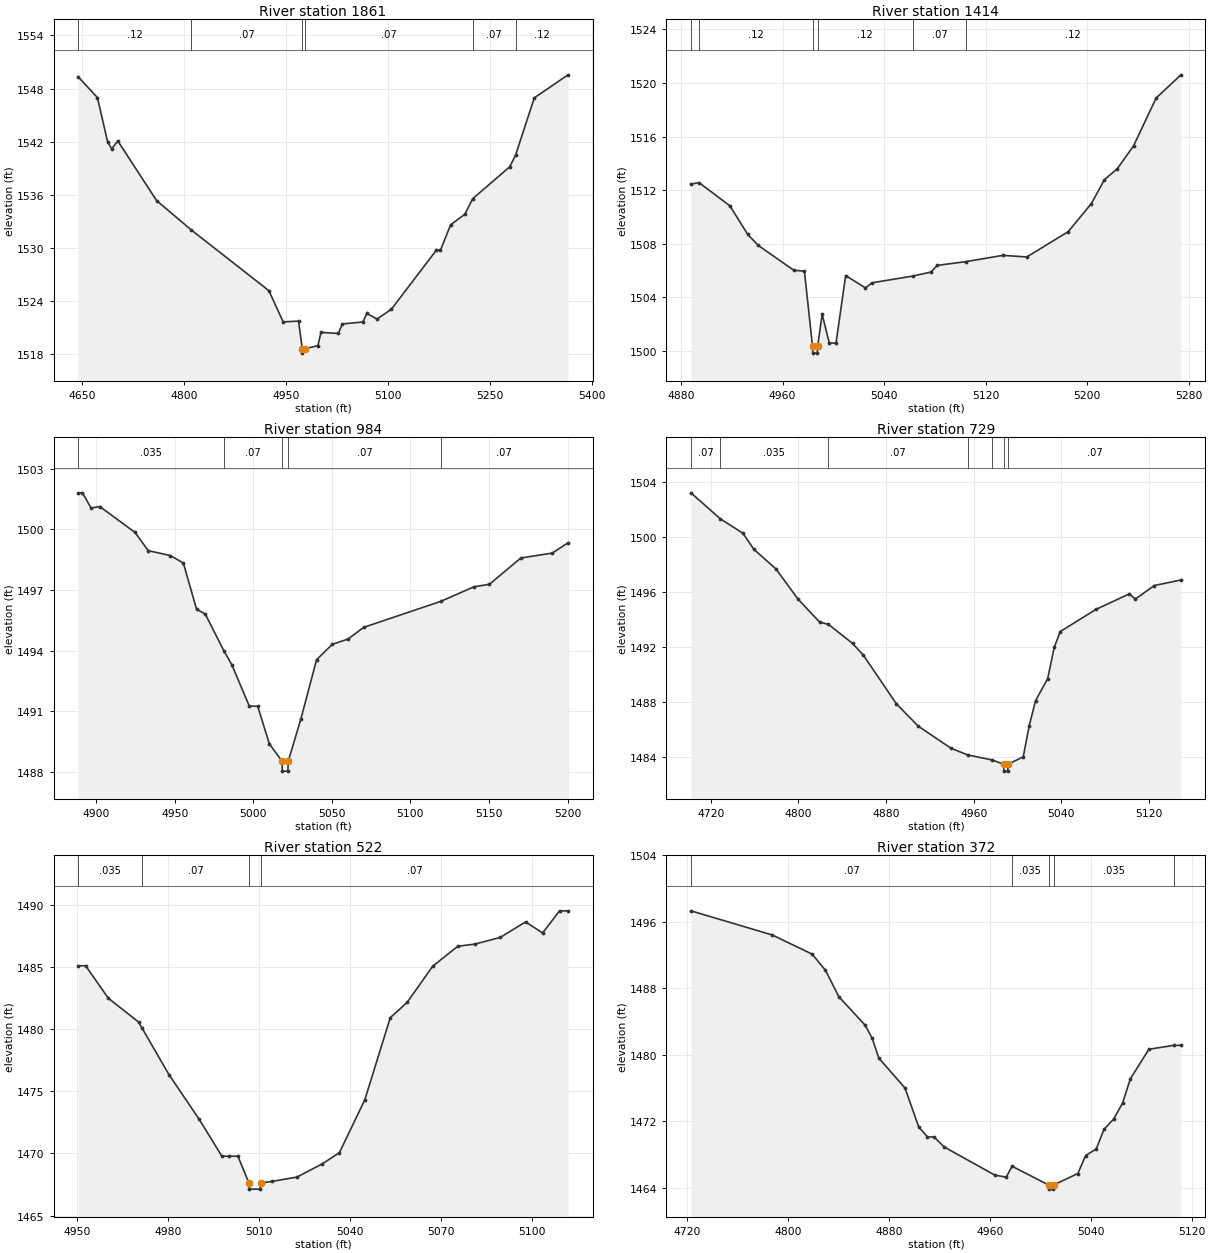
Type RM Length L Ch R = 1,1861,447,447,447
BEGIN DESCRIPTION:
Stream0256_DS 4.0
END DESCRIPTION:
XS GIS Cut Line= 3
      2047425.03     13931874.96      2047625.00     13931575.00
      2047424.98     13931274.97
#Sta/Elev= 30
  4644.2 1549.34  4672.7 1546.98  4687.7 1541.98  4693.7 1541.17  4702.7 1542.08
  4759.8 1535.33  4810.7 1532.02  4925.1 1525.14  4946.1 1521.61  4968.7 1521.70
  4974.2 1518.58  4974.4 1518.08  4978.2 1518.58  4997.2 1518.92  5001.7 1520.42
  5027.2 1520.31  5033.3 1521.38  5063.3 1521.60  5069.3 1522.57  5084.3 1521.93
  5105.4 1523.05  5171.5 1529.72  5177.5 1529.71  5192.5 1532.59  5213.5 1533.79
  5225.0 1535.54  5279.6 1539.16  5288.2 1540.49  5315.7 1546.95  5365.3 1549.55
#Mann=6,-1,0
  4644.2    0.12       0  4810.7    0.07       0  4974.2    0.05       0
  4978.2    0.07       0  5225.0    0.07       0  5288.2    0.12       0
Bank Sta=4974.2,4978.2
Exp/Cntr=0.3,0.1

Type RM Length L Ch R = 1,1414,430,430,430
BEGIN DESCRIPTION:
Stream0256_DS 3.0
END DESCRIPTION:
XS GIS Cut Line= 3
      2047975.02     13931724.96      2048025.00     13931625.00
      2047972.37     13931355.86
#Sta/Elev= 30
  4887.8 1512.45  4894.2 1512.56  4918.5 1510.83  4932.5 1508.70  4940.9 1507.87
  4968.8 1506.02  4977.2 1505.95  4983.6 1500.33  4983.8 1499.83  4987.3 1499.83
  4987.6 1500.33  4991.2 1502.73  4996.8 1500.58  5002.1 1500.58  5009.7 1505.62
  5025.3 1504.70  5030.4 1505.08  5062.8 1505.59  5076.8 1505.88  5081.9 1506.38
  5104.3 1506.66  5133.5 1507.13  5152.4 1507.01  5185.0 1508.90  5203.3 1511.00
  5213.5 1512.78  5223.7 1513.60  5236.5 1515.31  5254.3 1518.88  5273.8 1520.61
#Mann=6,-1,0
  4887.8    0.07       0  4894.2    0.12       0  4983.6    0.05       0
  4987.6    0.12       0  5062.8    0.07       0  5104.3    0.12       0
Bank Sta=4983.6,4987.6
Exp/Cntr=0.3,0.1

Type RM Length L Ch R = 1,984,255,255,255
BEGIN DESCRIPTION:
Stream0256_DS 2.0
END DESCRIPTION:
XS GIS Cut Line= 3
      2048225.03     13931874.98      2048325.00     13931825.00
      2048325.00     13931624.97
#Sta/Elev= 30
  4888.5 1501.81  4891.3 1501.81  4896.8 1501.06  4902.4 1501.13  4924.8 1499.85
  4933.2 1498.95  4947.2 1498.71  4955.5 1498.34  4963.9 1496.06  4969.5 1495.81
  4981.5 1493.97  4986.3 1493.32  4997.5 1491.26  5002.8 1491.26  5010.3 1489.39
  5018.3 1488.55  5018.5 1488.05  5022.0 1488.05  5022.3 1488.55  5030.3 1490.63
  5040.3 1493.56  5050.3 1494.32  5060.3 1494.58  5070.3 1495.16  5119.2 1496.44
  5140.3 1497.16  5150.3 1497.29  5170.3 1498.59  5190.3 1498.83  5200.3 1499.34
#Mann=5,-1,0
  4888.5   0.035       0  4981.5    0.07       0  5018.3    0.05       0
  5022.3    0.07       0  5119.2    0.07       0
Bank Sta=5018.3,5022.3
Exp/Cntr=0.3,0.1

Type RM Length L Ch R = 1,729,207,207,207
BEGIN DESCRIPTION:
Stream0256_DS 1.5
END DESCRIPTION:
XS GIS Cut Line= 3
      2048177.48     13932008.76      2048475.55     13931999.99
      2048538.80     13931864.75
#Sta/Elev= 30
  4701.8 1503.24  4728.5 1501.36  4749.3 1500.30  4759.3 1499.13  4779.4 1497.71
  4799.4 1495.53  4819.4 1493.83  4827.3 1493.68  4849.4 1492.29  4859.4 1491.42
  4889.4 1487.90  4909.4 1486.27  4939.4 1484.66  4954.5 1484.18  4977.0 1483.81
  4987.4 1483.50  4987.7 1483.00  4991.2 1483.00  4991.4 1483.50  5005.3 1484.04
  5010.8 1486.31  5016.5 1488.12  5027.6 1489.72  5033.6 1492.00  5039.1 1493.15
  5071.7 1494.76  5102.1 1495.89  5107.7 1495.51  5125.0 1496.50  5149.3 1496.90
#Mann=7,-1,0
  4701.8    0.07       0  4728.5   0.035       0  4827.3    0.07       0
  4954.5   0.035       0  4977.0    0.07       0  4987.4    0.05       0
  4991.4    0.07       0
Bank Sta=4987.4,4991.4
Exp/Cntr=0.3,0.1

Type RM Length L Ch R = 1,522,150,150,150
BEGIN DESCRIPTION:
Stream0256_DS 1.0
END DESCRIPTION:
XS GIS Cut Line= 3
      2048375.02     13932175.00      2048425.00     13932175.00
      2048525.02     13932124.99
#Sta/Elev= 29
  4950.2 1485.10  4952.7 1485.10  4960.2 1482.49  4970.2 1480.57  4971.4 1480.06
  4980.2 1476.35  4990.2 1472.75  4997.7 1469.78  5000.2 1469.78  5003.0 1469.78
  5006.6 1467.63  5006.8 1467.13  5010.3 1467.13  5010.6 1467.63  5014.2 1467.75
  5022.5 1468.10  5030.9 1469.17  5036.5 1470.06  5044.9 1474.32  5053.3 1480.92
  5058.9 1482.16  5067.3 1485.06  5075.6 1486.67  5081.2 1486.84  5089.6 1487.38
  5098.0 1488.63  5103.6 1487.74  5109.2 1489.52  5112.0 1489.52
#Mann=4,-1,0
  4950.2   0.035       0  4971.4    0.07       0  5006.6    0.05       0
  5010.6    0.07       0
Bank Sta=5006.6,5010.6
Exp/Cntr=0.3,0.1

Type RM Length L Ch R = 1,372,97,97,97
BEGIN DESCRIPTION:
Stream0256_DS 0.7
END DESCRIPTION:
XS GIS Cut Line= 4
      2048193.73     13932244.63      2048373.83     13932304.41
      2048460.94     13932311.98      2048526.79     13932221.87
#Sta/Elev= 30
  4722.8 1497.31  4787.4 1494.40  4819.0 1492.10  4829.5 1490.17  4840.2 1486.97
  4861.1 1483.54  4866.6 1481.98  4871.9 1479.59  4892.7 1475.98  4903.5 1471.32
  4910.5 1470.10  4915.7 1470.10  4923.8 1468.89  4963.9 1465.51  4973.0 1465.26
  4977.6 1466.58  5006.6 1464.32  5006.9 1463.82  5010.4 1463.82  5010.6 1464.32
  5029.8 1465.70  5036.0 1467.86  5044.4 1468.65  5050.6 1471.03  5058.2 1472.24
  5065.3 1474.17  5071.5 1477.10  5086.2 1480.65  5105.8 1481.12  5111.6 1481.13
#Mann=5,-1,0
  4722.8    0.07       0  4977.6   0.035       0  5006.6   0.035       0
  5010.6   0.035       0  5105.8    0.07       0
Bank Sta=5006.6,5010.6
Exp/Cntr=0.3,0.1

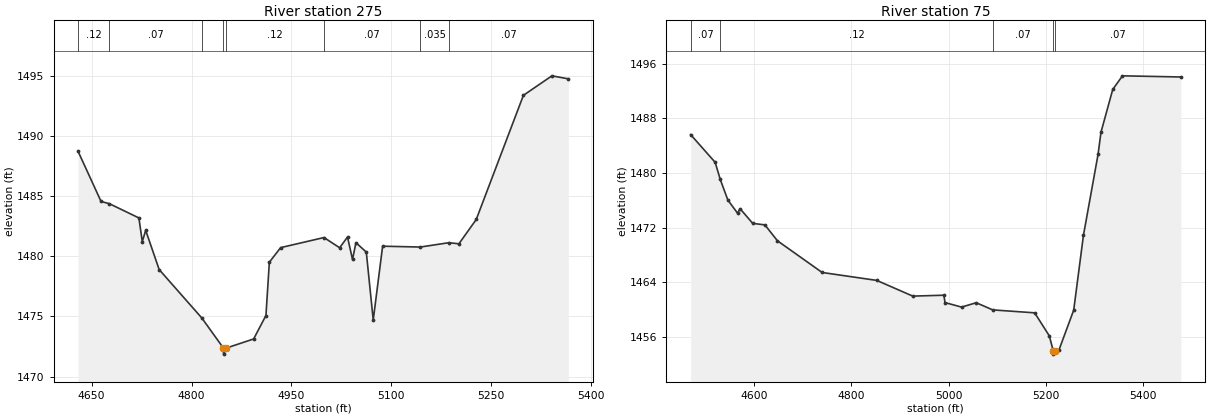
Type RM Length L Ch R = 1,275,200,200,200
BEGIN DESCRIPTION:
Stream0256_DS 0.5
END DESCRIPTION:
XS GIS Cut Line= 6
      2048134.84     13932465.31      2048477.93     13932410.13
      2048497.81     13932398.95      2048526.14     13932384.45
      2048570.04     13932220.63      2048593.98     13932058.32
#Sta/Elev= 30
  4629.7 1488.72  4664.2 1484.55  4676.8 1484.36  4721.0 1483.18  4726.1 1481.21
  4731.2 1482.15  4751.4 1478.89  4815.5 1474.86  4847.9 1472.36  4848.1 1471.86
  4851.9 1472.36  4893.2 1473.12  4911.7 1475.07  4916.8 1479.50  4933.7 1480.71
  4998.8 1481.55  5022.3 1480.70  5034.1 1481.59  5041.6 1479.73  5046.8 1481.12
  5062.3 1480.34  5072.7 1474.69  5086.8 1480.83  5143.4 1480.76  5186.1 1481.12
  5201.3 1481.03  5227.3 1483.05  5298.1 1493.37  5340.9 1494.99  5365.5 1494.74
#Mann=8,-1,0
  4629.7    0.12       0  4676.8    0.07       0  4815.5    0.12       0
  4847.9    0.05       0  4851.9    0.12       0  4998.8    0.07       0
  5143.4   0.035       0  5186.1    0.07       0
Bank Sta=4847.9,4851.9
Exp/Cntr=0.3,0.1

Type RM Length L Ch R = 1,75,0,0,0
BEGIN DESCRIPTION:
Stream0256_DS 0.0
END DESCRIPTION:
XS GIS Cut Line= 5
      2048170.00     13932609.75      2048593.33     13932525.35
      2048672.48     13932477.61      2048671.91     13932330.85
      2048648.75     13931995.30
#Sta/Elev= 30
  4470.2 1485.64  4520.6 1481.58  4531.0 1479.08  4546.7 1476.05  4566.6 1474.13
  4571.7 1474.79  4597.7 1472.64  4622.8 1472.41  4648.6 1470.08  4740.4 1465.44
  4852.6 1464.28  4926.5 1461.98  4990.5 1462.11  4992.8 1461.03  5026.9 1460.37
  5056.9 1461.01  5090.8 1459.96  5177.0 1459.53  5207.1 1456.15  5215.1 1453.98
  5215.3 1453.48  5219.1 1453.98  5227.1 1454.13  5257.2 1459.93  5277.2 1470.89
  5307.3 1482.77  5313.2 1485.98  5337.4 1492.26  5357.4 1494.25  5477.4 1494.08
#Mann=5,-1,0
  4470.2    0.07       0  4531.0    0.12       0  5090.8    0.07       0
  5215.1    0.05       0  5219.1    0.07       0
Bank Sta=5215.1,5219.1
Exp/Cntr=0.3,0.1

Chan Stop Cuts=-1