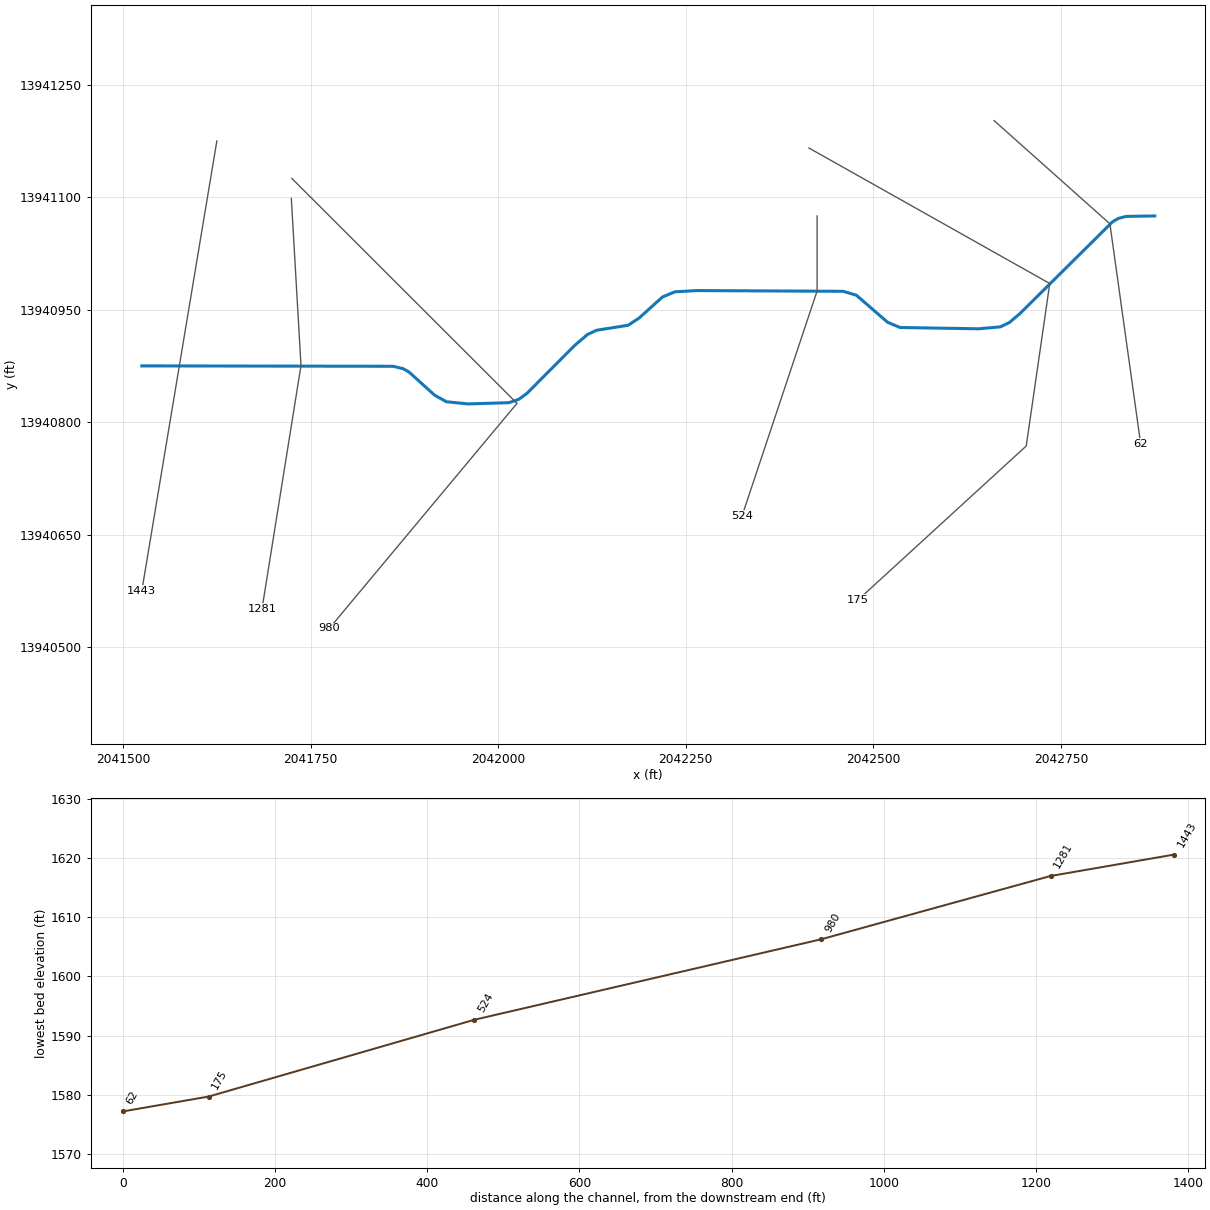
--- Stream0257_DS.prj (project) ---

Proj Title=Stream0257_DS Base Level Engineering
Current Plan=p01
Default Exp/Contr=0.3,0.1
English Units
Geom File=g01
Flow File=f01
Plan File=p01
Y Axis Title=Elevation
X Axis Title(PF)=Main Channel Distance
X Axis Title(XS)=Station
BEGIN DESCRIPTION:
Stream0257_DS
END DESCRIPTION:
DSS Export Rating Curves= 0
DSS Export Rating Curve Sorted= 0
DSS Export Volume Flow Curves= 0
DXF OffsetX= 0
DXF OffsetY= 0
DXF ScaleX= 1
DXF ScaleY= 10

--- Stream0257_DS.p01 (plan) ---

Plan Title=Multiple Run
Short Identifier=Multiple
Geom File=g01
Flow File=f01
Subcritical Flow
K Sum by GR= 0
Std Step Tol= 0.01
Critical Tol= 0.01
Num of Std Step Trials= 20
Max Error Tol= 0.3
Flow Tol Ratio= 0.001
Split Flow NTrial= 30
Split Flow Tol= 0.02
Split Flow Ratio= 0.02
Log Output Level= 0
Friction Slope Method= 1
Unsteady Friction Slope Method= 2
Unsteady Bridges Friction Slope Method= 1
Parabolic Critical Depth
Global Vel Dist=  1 , 1 , 1
Global Log Level= 0
CheckData=True
Encroach Param= -1, 0, 0, 0
BEGIN DESCRIPTION:
Multiple Run
END DESCRIPTION:

--- Stream0257_DS.f01 (steady flow) ---

Flow Title=Multiple
Number of Profiles=7
Profile Names=10-year,25-year,50-year,1pct_min,100-year,1pct_plu,500-year
River Rch & RM= Stream0257_DS,Reach-1,1443
     697    1182    1645    1114    2223    4436    4024
Boundary for River Rch & Prof#=Stream0257_DS,Reach-1,1
Up Type=0
Dn Type=3
Dn Slope=0.005
Boundary for River Rch & Prof#=Stream0257_DS,Reach-1,2
Up Type=0
Dn Type=3
Dn Slope=0.005
Boundary for River Rch & Prof#=Stream0257_DS,Reach-1,3
Up Type=0
Dn Type=3
Dn Slope=0.005
Boundary for River Rch & Prof#=Stream0257_DS,Reach-1,4
Up Type=0
Dn Type=3
Dn Slope=0.005
Boundary for River Rch & Prof#=Stream0257_DS,Reach-1,5
Up Type=0
Dn Type=3
Dn Slope=0.005
Boundary for River Rch & Prof#=Stream0257_DS,Reach-1,6
Up Type=0
Dn Type=3
Dn Slope=0.005
Boundary for River Rch & Prof#=Stream0257_DS,Reach-1,7
Up Type=0
Dn Type=3
Dn Slope=0.005

--- Stream0257_DS.g01 (geometry) ---

Geom Title=Existing Conditions
Program Version=4.10

River Reach=Stream0257_DS   ,Reach-1
Reach XY= 30
        2041525.       13940875.      2041859.78     13940874.48
      2041873.44     13940871.22      2041881.06     13940866.85
      2041915.37     13940835.81      2041930.98     13940827.16
      2041959.94     13940824.27      2042014.52     13940825.94
      2042027.42     13940830.41      2042038.29     13940838.36
      2042101.55     13940901.94      2042118.95     13940916.84
      2042131.04      13940922.5      2042173.25     13940929.22
      2042188.03     13940939.05      2042218.92     13940966.91
       2042235.5      13940973.8      2042264.81     13940975.46
      2042459.78     13940974.48      2042477.33     13940969.25
      2042518.95     13940933.14      2042535.51     13940926.21
      2042640.19     13940924.47      2042669.14     13940927.05
      2042681.19     13940932.81      2042695.16      13940944.6
      2042818.79     13941067.24      2042826.36     13941071.73
      2042836.84     13941074.41        2042875.       13941075.

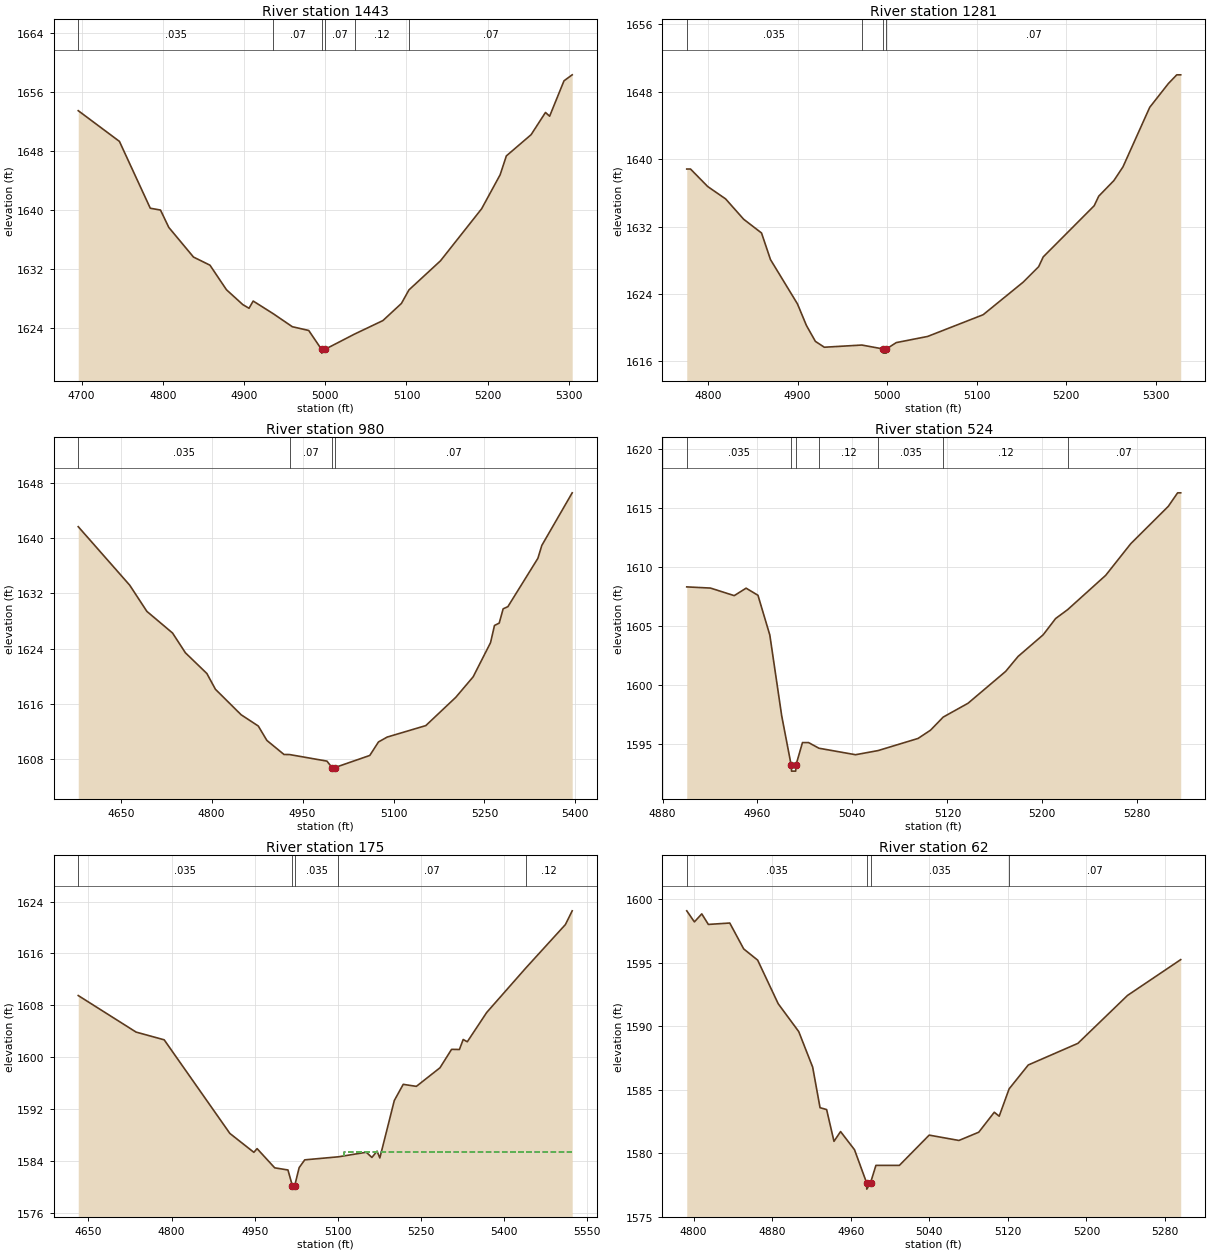
Type RM Length L Ch R = 1 ,1443    ,162,162,162
BEGIN DESCRIPTION:
Stream0257_DS 3.0
END DESCRIPTION:
XS GIS Cut Line= 3
      2041624.99     13941174.97        2041575.       13940875.
      2041525.01     13940575.04
#Sta/Elev= 30
  4695.9 1653.43  4746.6 1649.27  4784.6 1640.21  4797.2 1639.96  4807.4 1637.61
  4837.8 1633.59  4858.1 1632.49  4878.4 1629.16  4898.6 1627.14  4906.2 1626.65
  4911.3 1627.63  4935.9 1625.92  4959.5 1624.15  4979.7 1623.64  4995.5 1621.07
  4995.7 1620.57  4999.5 1621.07  5036.1 1623.15    5071 1624.98  5093.8  1627.3
  5103.1 1629.14  5141.9 1633.08  5192.6 1640.14  5215.4 1644.75    5223  1647.3
  5253.5 1650.18  5271.2 1653.19  5276.3 1652.68    5294 1657.48  5304.1 1658.29
#Mann= 6 ,-1 , 0
  4695.9    .035       0  4935.9     .07       0  4995.5     .05       0
  4999.5     .07       0  5036.1     .12       0  5103.1     .07       0
Bank Sta=4995.5,4999.5
XS Rating Curve= 0 ,0
Exp/Cntr=0.3,0.1

Type RM Length L Ch R = 1 ,1281    ,301,301,301
BEGIN DESCRIPTION:
Stream0257_DS 2.5
END DESCRIPTION:
XS GIS Cut Line= 3
      2041724.27     13941098.35      2041737.14     13940875.37
      2041685.24     13940551.36
#Sta/Elev= 30
  4776.3 1638.83  4780.5 1638.83  4799.7 1636.75  4819.7 1635.28  4839.8 1632.87
  4859.8 1631.23  4869.8 1628.07  4899.9 1622.81  4909.9 1620.25  4919.9 1618.36
  4929.9 1617.66  4971.8 1617.92  4995.3 1617.46  4995.6 1616.96  4999.1 1616.96
  4999.3 1617.46  5010.2 1618.21  5045.2 1618.94  5107.2 1621.52  5151.9 1625.39
  5169.2 1627.23  5174.3 1628.39  5231.2 1634.47  5236.3 1635.61  5253.2 1637.46
  5263.3 1639.08  5293.2 1646.16    5314 1648.98  5323.4 1650.02  5327.8 1650.02
#Mann= 4 ,-1 , 0
  4776.3    .035       0  4971.8     .07       0  4995.3     .05       0
  4999.3     .07       0
Bank Sta=4995.3,4999.3
XS Rating Curve= 0 ,0
Exp/Cntr=0.3,0.1

Type RM Length L Ch R = 1 ,980     ,456,456,456
BEGIN DESCRIPTION:
Stream0257_DS 2.0
END DESCRIPTION:
XS GIS Cut Line= 3
      2041724.97     13941125.03        2042025.       13940825.
      2041775.01     13940525.01
#Sta/Elev= 30
  4579.9 1641.67  4664.8  1633.2  4693.1 1629.41  4735.5 1626.27  4756.7 1623.41
  4792.1 1620.41  4806.2 1618.13  4848.6 1614.44  4876.9 1612.81  4891.1 1610.72
  4919.3 1608.69  4928.4 1608.68  4990.1 1607.73  4998.7 1606.78  4998.9 1606.28
  5002.7 1606.78  5060.8 1608.55  5075.1  1610.5  5089.5 1611.21  5153.2 1612.87
  5202.7 1616.97  5231.3 1619.93    5260 1624.88  5266.5 1627.37  5274.3 1627.71
  5280.8 1629.78  5288.6 1630.09  5338.1 1637.09  5344.6 1638.96  5394.7 1646.57
#Mann= 4 ,-1 , 0
  4579.9    .035       0  4928.4     .07       0  4998.7     .05       0
  5002.7     .07       0
Bank Sta=4998.7,5002.7
XS Rating Curve= 0 ,0
Exp/Cntr=0.3,0.1

Type RM Length L Ch R = 1 ,524     ,349,349,349
BEGIN DESCRIPTION:
Stream0257_DS 1.0
END DESCRIPTION:
XS GIS Cut Line= 3
        2042425.       13941075.        2042425.       13940975.
      2042325.01     13940675.03
#Sta/Elev= 30
  4900.4 1608.28  4920.4 1608.18  4940.4 1607.54  4950.4 1608.17  4960.4 1607.57
  4970.4  1604.2  4980.4 1597.36  4988.4 1593.17  4988.7 1592.67  4992.2 1592.67
  4992.4 1593.17  4997.9 1595.09    5003 1595.09  5011.8 1594.61  5042.6 1594.06
  5061.6 1594.41  5095.3 1595.44  5105.8 1596.14  5116.5 1597.25  5137.4 1598.42
  5169.1 1601.12  5179.6 1602.39  5200.7 1604.22  5211.2  1605.6  5221.3 1606.35
  5253.4 1609.26  5274.5 1611.94  5306.1  1615.1    5314 1616.25  5316.6 1616.25
#Mann= 7 ,-1 , 0
  4900.4    .035       0  4988.4    .035       0  4992.4    .035       0
  5011.8     .12       0  5061.6    .035       0  5116.5     .12       0
  5221.3     .07       0
Bank Sta=4988.4,4992.4
XS Rating Curve= 0 ,0
Exp/Cntr=0.3,0.1

Type RM Length L Ch R = 1 ,175     ,113,113,113
BEGIN DESCRIPTION:
Stream0257_DS 0.01
END DESCRIPTION:
XS GIS Cut Line= 4
      2042414.06     13941165.64      2042735.05     13940984.87
       2042703.7     13940768.14      2042479.59     13940562.86
#Sta/Elev= 30
  4631.6 1609.52    4736 1603.89  4786.7  1602.7  4905.2 1588.28  4948.5 1585.37
  4954.3 1585.94  4986.1 1582.98    5010 1582.65  5018.1  1580.2  5018.3  1579.7
  5022.1  1580.2  5030.2 1583.01  5040.3 1584.21  5101.2 1584.68  5151.4 1585.38
  5161.5 1584.58  5170.8 1585.55  5175.8  1584.5  5201.9 1593.35    5218 1595.84
  5241.7 1595.53  5284.3 1598.39  5305.2 1601.23  5319.4 1601.21  5326.2 1602.75
  5333.6  1602.4  5368.7 1606.92  5439.6  1613.8  5510.6 1620.45  5522.9 1622.57
#Mann= 5 ,-1 , 0
  4631.6    .035       0  5018.1    .035       0  5022.1    .035       0
  5101.2     .07       0  5439.6     .12       0
#XS Ineff= 2 , 0
       0                 5110.82       0 1585.43
Permanent Ineff=
       F       F
Bank Sta=5018.1,5022.1
XS Rating Curve= 0 ,0
Exp/Cntr=0.3,0.1

Type RM Length L Ch R = 1 ,62      ,0,0,0
BEGIN DESCRIPTION:
Stream0257_DS 0.0
END DESCRIPTION:
XS GIS Cut Line= 3
      2042660.83     13941202.23      2042815.21     13941064.48
      2042856.16     13940771.33
#Sta/Elev= 30
  4793.1 1599.08  4800.9 1598.21  4808.4 1598.84  4815.1 1598.01  4836.9 1598.12
  4851.1 1596.08  4865.3  1595.2  4886.2 1591.77  4907.1 1589.58  4921.3 1586.78
  4928.8 1583.59  4935.5 1583.44    4943 1580.94  4949.7 1581.71  4963.9 1580.28
  4976.2 1577.68  4976.4 1577.18  4980.2 1577.68  4985.7 1579.05  5009.6 1579.05
  5039.9 1581.43  5070.2 1581.01  5090.4 1581.66  5106.2 1583.23  5111.2 1582.92
  5121.3 1585.07  5140.8 1586.95  5191.3 1588.65  5241.8 1592.42    5296 1595.24
#Mann= 4 ,-1 , 0
  4793.1    .035       0  4976.2    .035       0  4980.2    .035       0
  5121.3     .07       0
Bank Sta=4976.2,4980.2
XS Rating Curve= 0 ,0
Exp/Cntr=0.3,0.1

Chan Stop Cuts=-1
Use User Specified Reach Order=0
Composite Channel Slope=5