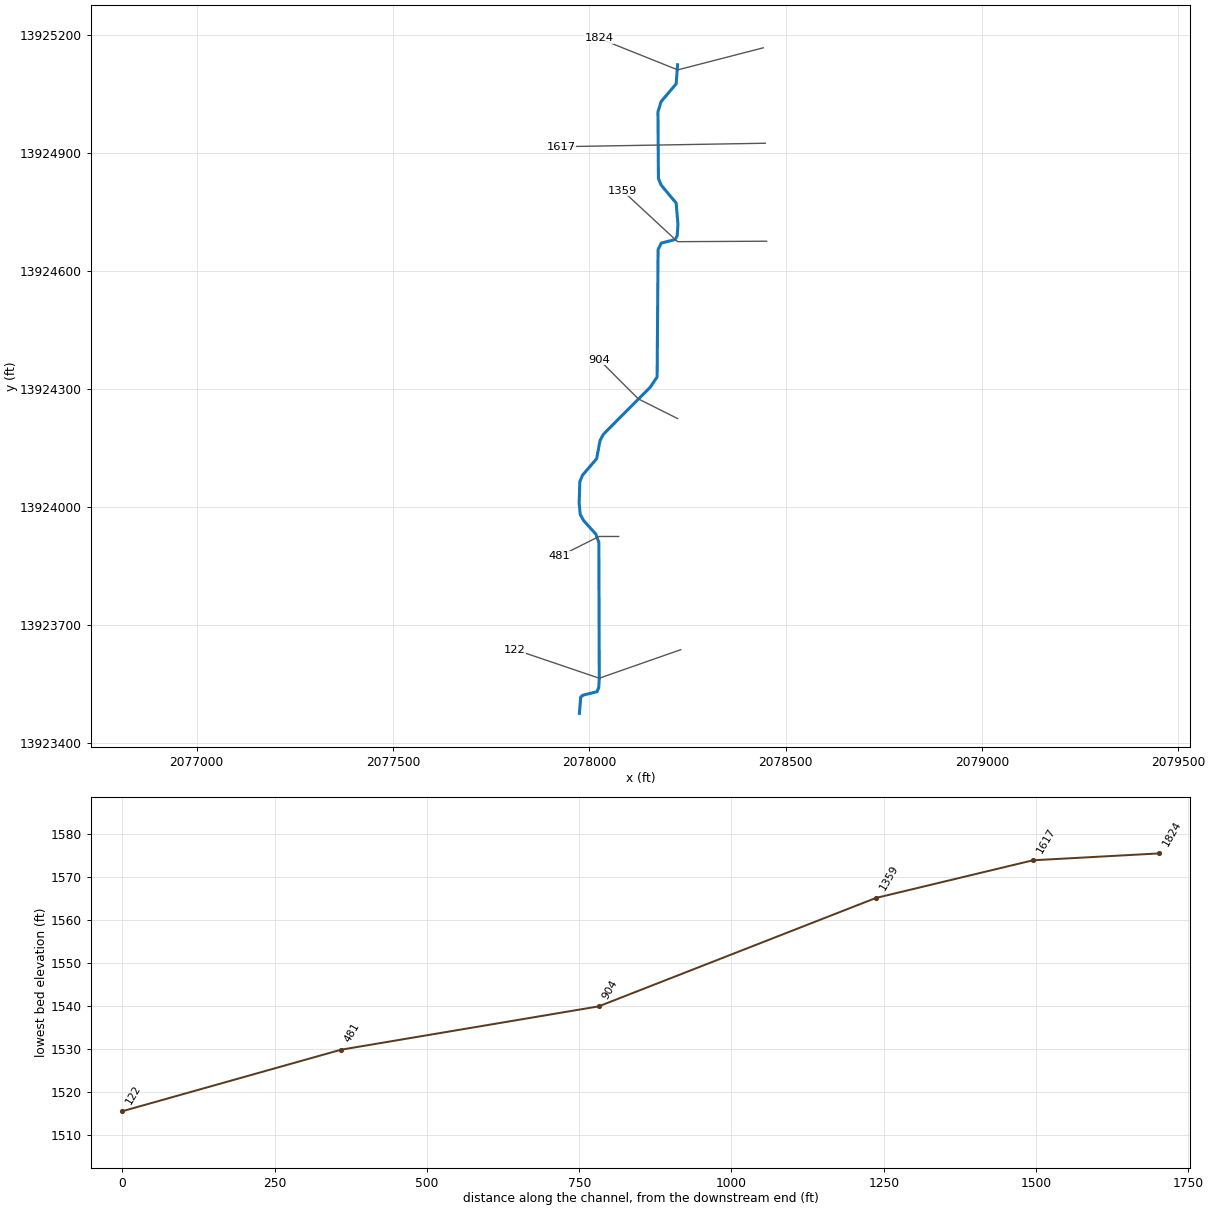
--- Stream0258_DS.prj (project) ---

Proj Title=Stream0258_DS Base Level Engineering
Current Plan=p01
Default Exp/Contr=0.3,0.1
English Units
Geom File=g01
Flow File=f01
Plan File=p01
BEGIN DESCRIPTION:
Stream0258_DS
END DESCRIPTION:

--- Stream0258_DS.p01 (plan) ---

Plan Title=Multiple Run
Short Identifier=Multiple
Geom File=g01
Flow File=f01
Subcritical Flow
K Sum by GR= 0
Std Step Tol= 0.01
Critical Tol= 0.01
Num of Std Step Trials= 20
Max Error Tol= 0.3
Flow Tol Ratio= 0.001
Split Flow NTrial= 30
Split Flow Tol= 0.02
Split Flow Ratio= 0.02
Log Output Level= 0
Friction Slope Method= 1
Unsteady Friction Slope Method= 2
Unsteady Bridges Friction Slope Method= 1
Parabolic Critical Depth
Global Vel Dist=  1 , 1 , 1
Global Log Level= 0
CheckData=True
Encroach Param= -1, 0, 0, 0
BEGIN DESCRIPTION:
Multiple Run
END DESCRIPTION:

--- Stream0258_DS.f01 (steady flow) ---

Flow Title=Multiple
Number of Profiles=7
Profile Names=10-year,25-year,50-year,1pct_min,100-year,1pct_plu,500-year
River Rch & RM= Stream0258_DS,Reach-1,1824
     541     894    1224     817    1631    3254    2861
Boundary for River Rch & Prof#=Stream0258_DS,Reach-1,1
Up Type=0
Dn Type=3
Dn Slope=0.005
Boundary for River Rch & Prof#=Stream0258_DS,Reach-1,2
Up Type=0
Dn Type=3
Dn Slope=0.005
Boundary for River Rch & Prof#=Stream0258_DS,Reach-1,3
Up Type=0
Dn Type=3
Dn Slope=0.005
Boundary for River Rch & Prof#=Stream0258_DS,Reach-1,4
Up Type=0
Dn Type=3
Dn Slope=0.005
Boundary for River Rch & Prof#=Stream0258_DS,Reach-1,5
Up Type=0
Dn Type=3
Dn Slope=0.005
Boundary for River Rch & Prof#=Stream0258_DS,Reach-1,6
Up Type=0
Dn Type=3
Dn Slope=0.005
Boundary for River Rch & Prof#=Stream0258_DS,Reach-1,7
Up Type=0
Dn Type=3
Dn Slope=0.005

--- Stream0258_DS.g01 (geometry) ---

Geom Title=Existing Conditions

River Reach=Stream0258_DS,Reach-1
Reach XY= 30
      2078225.00     13925125.00      2078221.35     13925076.51
      2078182.89     13925031.16      2078175.02     13925004.99
      2078176.22     13924835.50      2078183.15     13924818.94
      2078221.32     13924773.33      2078225.91     13924719.61
      2078224.18     13924691.01      2078219.45     13924680.65
      2078183.59     13924671.42      2078175.30     13924654.71
      2078172.94     13924330.85      2078155.39     13924304.84
      2078035.76     13924184.68      2078027.50     13924168.97
      2078018.85     13924122.83      2077983.04     13924081.05
      2077976.08     13924064.46      2077974.29     13924009.94
      2077977.17     13923980.98      2077985.81     13923965.37
      2078016.85     13923931.06      2078024.48     13923909.78
      2078025.56     13923564.44      2078024.24     13923540.76
      2078019.81     13923530.19      2077983.77     13923521.23
      2077978.24     13923516.31      2077975.00     13923475.00

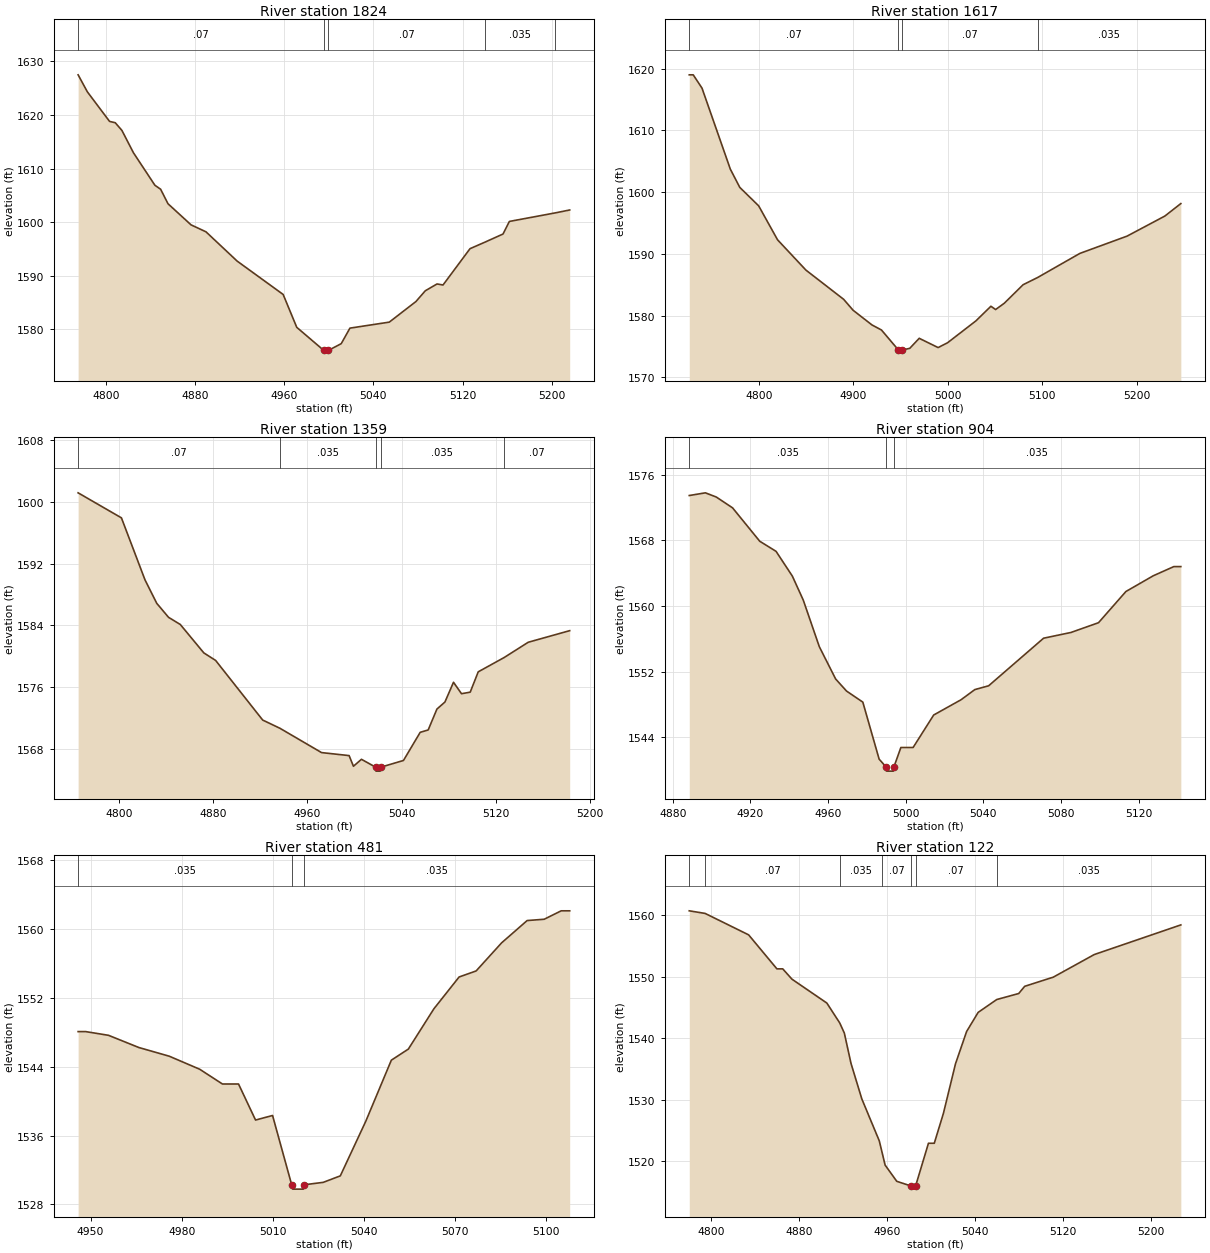
Type RM Length L Ch R = 1,1824,207,207,207
BEGIN DESCRIPTION:
Stream0258_DS 5.0
END DESCRIPTION:
XS GIS Cut Line= 3
      2078443.07     13925168.11      2078225.38     13925112.04
      2078024.72     13925192.27
#Sta/Elev= 30
  4775.2 1627.50  4783.5 1624.32  4803.4 1618.80  4808.5 1618.55  4814.5 1617.11
  4824.8 1612.95  4844.1 1606.86  4849.2 1606.13  4855.8 1603.42  4876.5 1599.47
  4889.9 1598.17  4917.8 1592.71  4959.1 1586.47  4971.3 1580.33  4995.6 1576.01
  4995.9 1575.51  4999.6 1576.01  5011.2 1577.28  5019.0 1580.18  5054.3 1581.30
  5078.2 1585.15  5086.6 1587.16  5097.1 1588.43  5102.5 1588.24  5126.7 1595.02
  5140.3 1596.26  5156.3 1597.76  5162.0 1600.11  5202.7 1601.69  5216.1 1602.25
#Mann=5,-1,0
  4775.2    0.07       0  4995.6    0.05       0  4999.6    0.07       0
  5140.3   0.035       0  5202.7    0.07       0
Bank Sta=4995.6,4999.6
Exp/Cntr=0.3,0.1

Type RM Length L Ch R = 1,1617,258,258,258
BEGIN DESCRIPTION:
Stream0258_DS 4.0
END DESCRIPTION:
XS GIS Cut Line= 2
      2078448.50     13924925.40      2077928.07     13924916.62
#Sta/Elev= 30
  4726.3 1618.98  4730.5 1618.98  4739.8 1616.82  4769.8 1603.70  4779.8 1600.75
  4799.8 1597.76  4819.8 1592.26  4849.8 1587.36  4889.8 1582.62  4899.8 1580.85
  4919.8 1578.47  4929.8 1577.66  4947.8 1574.41  4948.1 1573.91  4951.6 1573.91
  4951.8 1574.41  4959.8 1574.69  4969.8 1576.31  4989.8 1574.81  4999.8 1575.59
  5029.8 1579.13  5045.7 1581.50  5050.7 1580.97  5059.8 1581.98  5079.8 1584.99
  5095.1 1586.15  5139.9 1590.06  5189.9 1592.86  5229.9 1596.11  5246.8 1598.13
#Mann=4,-1,0
  4726.3    0.07       0  4947.8    0.05       0  4951.8    0.07       0
  5095.1   0.035       0
Bank Sta=4947.8,4951.8
Exp/Cntr=0.3,0.1

Type RM Length L Ch R = 1,1359,455,455,455
BEGIN DESCRIPTION:
Stream0258_DS 3.0
END DESCRIPTION:
XS GIS Cut Line= 3
      2078451.80     13924676.17      2078225.00     13924675.00
      2078084.95     13924804.58
#Sta/Elev= 30
  4765.2 1601.15  4802.0 1597.91  4822.0 1589.89  4832.0 1586.85  4842.0 1585.04
  4852.0 1584.11  4872.0 1580.43  4882.0 1579.46  4922.0 1571.74  4936.6 1570.68
  4972.0 1567.53  4995.4 1567.14  4999.1 1565.76  5005.9 1566.66  5018.1 1565.63
  5018.3 1565.13  5021.8 1565.13  5022.1 1565.63  5041.6 1566.51  5055.8 1570.15
  5062.6 1570.46  5070.0 1573.16  5076.8 1574.07  5084.1 1576.63  5090.9 1575.15
  5098.3 1575.35  5105.1 1577.98  5127.2 1579.84  5147.6 1581.81  5182.8 1583.31
#Mann=5,-1,0
  4765.2    0.07       0  4936.6   0.035       0  5018.1   0.035       0
  5022.1   0.035       0  5127.2    0.07       0
Bank Sta=5018.1,5022.1
Exp/Cntr=0.3,0.1

Type RM Length L Ch R = 1,904,423,423,423
BEGIN DESCRIPTION:
Stream0258_DS 2.0
END DESCRIPTION:
XS GIS Cut Line= 3
      2078224.96     13924225.02      2078125.00     13924275.00
      2078024.99     13924375.01
#Sta/Elev= 30
  4888.5 1573.47  4896.8 1573.80  4902.4 1573.29  4910.8 1571.97  4924.8 1567.90
  4933.2 1566.67  4941.6 1563.65  4947.2 1560.74  4955.5 1555.04  4963.9 1551.11
  4969.5 1549.64  4977.9 1548.29  4986.3 1541.34  4989.9 1540.38  4990.1 1539.88
  4993.6 1539.88  4993.9 1540.38  4997.5 1542.76  5003.8 1542.76  5014.4 1546.72
  5028.5 1548.58  5035.6 1549.82  5042.7 1550.28  5071.0 1556.08  5085.1 1556.78
  5099.3 1557.97  5113.4 1561.77  5127.5 1563.69  5138.1 1564.81  5141.7 1564.81
#Mann=3,-1,0
  4888.5   0.035       0  4989.9   0.035       0  4993.9   0.035       0
Bank Sta=4989.9,4993.9
Exp/Cntr=0.3,0.1

Type RM Length L Ch R = 1,481,359,359,359
BEGIN DESCRIPTION:
Stream0258_DS 1.0
END DESCRIPTION:
XS GIS Cut Line= 3
      2078074.98     13923925.00      2078025.00     13923925.00
      2077924.98     13923874.99
#Sta/Elev= 28
  4945.9 1548.09  4948.4 1548.09  4955.9 1547.66  4965.9 1546.24  4975.9 1545.23
  4985.9 1543.72  4993.4 1542.00  4995.9 1542.00  4998.7 1542.00  5004.3 1537.81
  5009.9 1538.34  5016.2 1530.28  5016.5 1529.78  5020.0 1529.78  5020.2 1530.28
  5026.6 1530.57  5032.2 1531.32  5040.6 1537.68  5049.0 1544.77  5054.6 1546.06
  5063.0 1550.74  5071.3 1554.44  5076.9 1555.14  5085.3 1558.41  5093.7 1561.00
  5099.3 1561.15  5104.9 1562.13  5107.7 1562.13
#Mann=3,-1,0
  4945.9   0.035       0  5016.2   0.035       0  5020.2   0.035       0
Bank Sta=5016.2,5020.2
Exp/Cntr=0.3,0.1

Type RM Length L Ch R = 1,122,0,0,0
BEGIN DESCRIPTION:
Stream0258_DS 0.0
END DESCRIPTION:
XS GIS Cut Line= 3
      2078233.13     13923637.04      2078025.56     13923564.44
      2077810.48     13923637.35
#Sta/Elev= 30
  4780.1 1560.72  4794.5 1560.30  4834.1 1556.81  4859.8 1551.28  4865.1 1551.28
  4873.5 1549.60  4905.2 1545.72  4916.9 1542.49  4921.1 1540.84  4927.2 1535.89
  4937.0 1530.13  4952.9 1523.30  4955.4 1521.44  4958.2 1519.36  4968.8 1516.72
  4981.9 1515.95  4982.2 1515.45  4985.9 1515.95  4997.6 1522.91  5002.9 1522.91
  5011.2 1527.77  5022.2 1535.84  5032.3 1541.09  5042.8 1544.20  5059.7 1546.29
  5079.7 1547.27  5085.1 1548.44  5111.1 1549.93  5148.4 1553.61  5227.1 1558.43
#Mann=7,-1,0
  4780.1   0.035       0  4794.5    0.07       0  4916.9   0.035       0
  4955.4    0.07       0  4981.9    0.05       0  4985.9    0.07       0
  5059.7   0.035       0
Bank Sta=4981.9,4985.9
Exp/Cntr=0.3,0.1

Chan Stop Cuts=-1