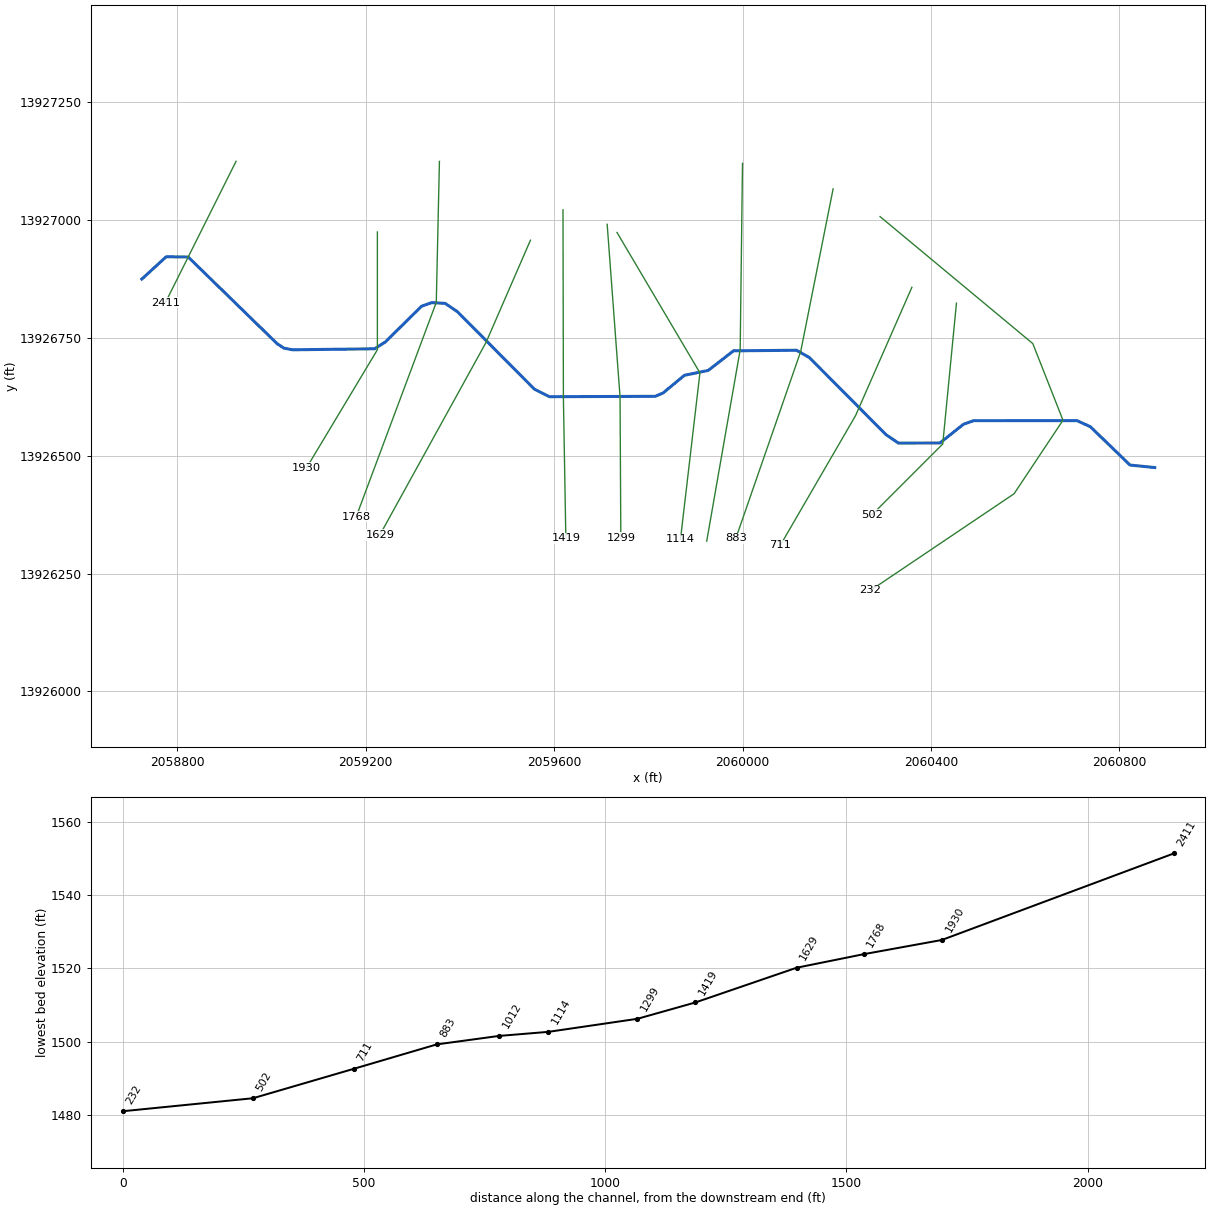
--- Stream0260_DS.prj (project) ---

Proj Title=Stream0260_DS Base Level Engineering
Current Plan=p01
Default Exp/Contr=0.3,0.1
English Units
Geom File=g01
Flow File=f01
Plan File=p01
BEGIN DESCRIPTION:
Stream0260_DS
END DESCRIPTION:

--- Stream0260_DS.p01 (plan) ---

Plan Title=Multiple Run
Short Identifier=Multiple
Geom File=g01
Flow File=f01
Subcritical Flow
K Sum by GR= 0
Std Step Tol= 0.01
Critical Tol= 0.01
Num of Std Step Trials= 20
Max Error Tol= 0.3
Flow Tol Ratio= 0.001
Split Flow NTrial= 30
Split Flow Tol= 0.02
Split Flow Ratio= 0.02
Log Output Level= 0
Friction Slope Method= 1
Unsteady Friction Slope Method= 2
Unsteady Bridges Friction Slope Method= 1
Parabolic Critical Depth
Global Vel Dist=  1 , 1 , 1
Global Log Level= 0
CheckData=True
Encroach Param= -1, 0, 0, 0
BEGIN DESCRIPTION:
Multiple Run
END DESCRIPTION:

--- Stream0260_DS.f01 (steady flow) ---

Flow Title=Multiple
Number of Profiles=7
Profile Names=10-year,25-year,50-year,1pct_min,100-year,1pct_plu,500-year
River Rch & RM= Stream0260_DS,Reach-1,2411
     339     541     724     473     943    1882    1581
River Rch & RM= Stream0260_DS,Reach-1,1930
     443     719     972     641    1279    2552    2187
Boundary for River Rch & Prof#=Stream0260_DS,Reach-1,1
Up Type=0
Dn Type=3
Dn Slope=0.005
Boundary for River Rch & Prof#=Stream0260_DS,Reach-1,2
Up Type=0
Dn Type=3
Dn Slope=0.005
Boundary for River Rch & Prof#=Stream0260_DS,Reach-1,3
Up Type=0
Dn Type=3
Dn Slope=0.005
Boundary for River Rch & Prof#=Stream0260_DS,Reach-1,4
Up Type=0
Dn Type=3
Dn Slope=0.005
Boundary for River Rch & Prof#=Stream0260_DS,Reach-1,5
Up Type=0
Dn Type=3
Dn Slope=0.005
Boundary for River Rch & Prof#=Stream0260_DS,Reach-1,6
Up Type=0
Dn Type=3
Dn Slope=0.005
Boundary for River Rch & Prof#=Stream0260_DS,Reach-1,7
Up Type=0
Dn Type=3
Dn Slope=0.005

--- Stream0260_DS.g01 (geometry) ---

Geom Title=Existing Conditions

River Reach=Stream0260_DS,Reach-1
Reach XY= 30
      2058725.00     13926875.00      2058776.62     13926922.33
      2058823.42     13926921.93      2059011.68     13926738.37
      2059026.46     13926728.53      2059044.98     13926724.96
      2059219.14     13926727.07      2059241.75     13926741.47
      2059318.96     13926817.52      2059340.36     13926825.10
      2059368.95     13926823.42      2059395.09     13926805.58
      2059558.24     13926641.43      2059590.16     13926625.38
      2059814.50     13926626.20      2059831.08     13926633.09
      2059876.74     13926670.81      2059927.18     13926681.12
      2059980.93     13926722.77      2060114.56     13926723.96
      2060141.76     13926708.57      2060304.84     13926544.58
      2060330.89     13926526.96      2060419.02     13926527.16
      2060468.94     13926566.85      2060490.22     13926574.48
      2060709.84     13926574.62      2060738.32     13926561.63
      2060822.49     13926480.33      2060875.00     13926475.00

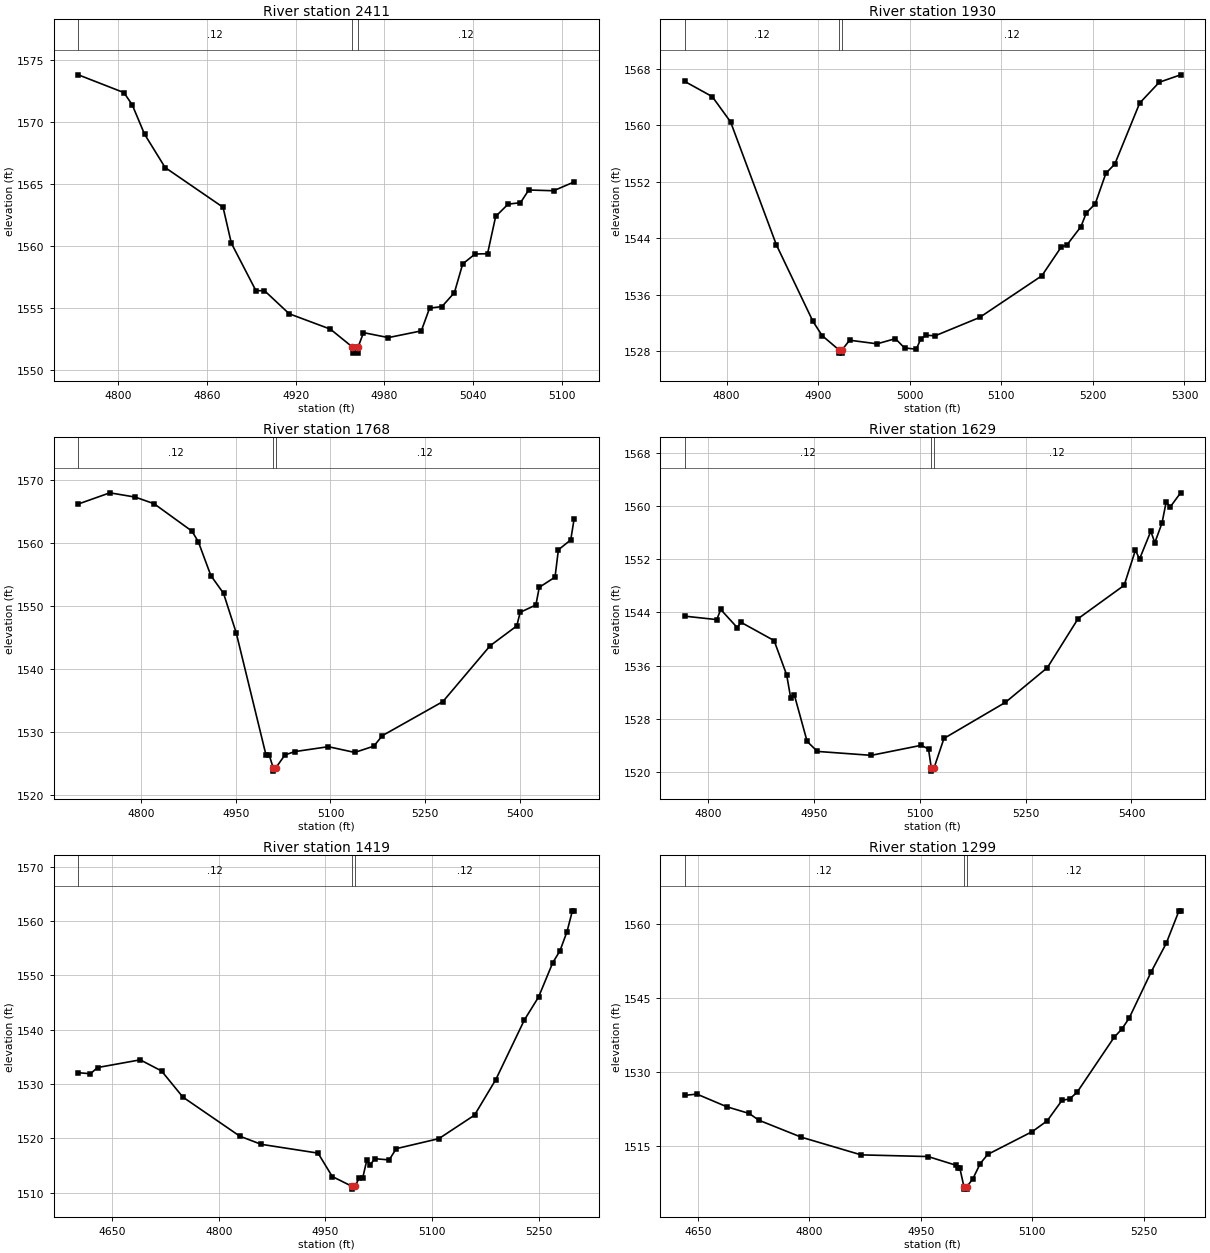
Type RM Length L Ch R = 1,2411,481,481,481
BEGIN DESCRIPTION:
Stream0260_DS 11.0
END DESCRIPTION:
XS GIS Cut Line= 3
      2058925.02     13927125.03      2058825.00     13926925.00
      2058775.02     13926825.04
#Sta/Elev= 30
  4772.9 1573.79  4803.7 1572.36  4809.3 1571.39  4817.7 1569.01  4831.6 1566.33
  4870.8 1563.13  4876.4 1560.24  4893.1 1556.40  4898.7 1556.43  4915.5 1554.56
  4943.4 1553.32  4958.2 1551.89  4958.5 1551.39  4962.0 1551.39  4962.2 1551.89
  4965.8 1553.04  4982.6 1552.64  5004.9 1553.18  5010.5 1555.01  5018.9 1555.14
  5027.3 1556.26  5032.9 1558.57  5041.3 1559.37  5049.7 1559.39  5055.2 1562.39
  5063.6 1563.38  5072.0 1563.50  5077.6 1564.52  5094.4 1564.46  5108.3 1565.17
#Mann=3,-1,0
  4772.9    0.12       0  4958.2    0.05       0  4962.2    0.12       0
Bank Sta=4958.2,4962.2
Exp/Cntr=0.3,0.1

Type RM Length L Ch R = 1,1930,162,162,162
BEGIN DESCRIPTION:
Stream0260_DS 10.0
END DESCRIPTION:
XS GIS Cut Line= 3
      2059225.00     13926974.97      2059225.00     13926725.00
      2059075.01     13926475.02
#Sta/Elev= 30
  4754.3 1566.24  4784.3 1564.09  4804.3 1560.51  4854.3 1543.09  4894.3 1532.23
  4904.3 1530.22  4922.3 1528.24  4922.5 1527.74  4926.0 1527.74  4926.3 1528.24
  4934.3 1529.57  4964.3 1529.06  4984.3 1529.79  4994.3 1528.47  5007.2 1528.30
  5012.0 1529.77  5017.9 1530.28  5027.6 1530.19  5076.2 1532.79  5144.2 1538.70
  5165.6 1542.82  5171.4 1543.03  5187.0 1545.68  5192.8 1547.62  5202.5 1548.89
  5214.2 1553.23  5223.9 1554.53  5251.1 1563.18  5272.5 1566.13  5295.8 1567.18
#Mann=3,-1,0
  4754.3    0.12       0  4922.3    0.05       0  4926.3    0.12       0
Bank Sta=4922.3,4926.3
Exp/Cntr=0.3,0.1

Type RM Length L Ch R = 1,1768,139,139,139
BEGIN DESCRIPTION:
Stream0260_DS 9.0
END DESCRIPTION:
XS GIS Cut Line= 3
      2059356.68     13927124.91      2059350.00     13926825.59
      2059179.89     13926370.23
#Sta/Elev= 30
  4700.6 1566.17  4750.5 1567.94  4790.5 1567.27  4820.5 1566.22  4880.6 1561.87
  4890.6 1560.21  4910.6 1554.82  4930.6 1552.03  4950.6 1545.80  4997.8 1526.45
  5003.0 1526.42  5009.3 1524.36  5009.6 1523.86  5013.3 1524.36  5027.9 1526.42
  5043.3 1526.95  5096.7 1527.73  5138.5 1526.82  5168.8 1527.82  5182.1 1529.47
  5278.2 1534.88  5352.9 1543.71  5395.2 1546.86  5400.5 1549.01  5425.5 1550.18
  5430.8 1552.97  5455.8 1554.59  5461.1 1558.91  5480.7 1560.49  5486.1 1563.85
#Mann=3,-1,0
  4700.6    0.12       0  5009.3    0.05       0  5013.3    0.12       0
Bank Sta=5009.3,5013.3
Exp/Cntr=0.3,0.1

Type RM Length L Ch R = 1,1629,210,210,210
BEGIN DESCRIPTION:
Stream0260_DS 8.0
END DESCRIPTION:
XS GIS Cut Line= 3
      2059549.89     13926957.54      2059455.50     13926740.39
      2059230.18     13926331.89
#Sta/Elev= 30
  4766.4 1543.43  4811.8 1542.91  4817.3 1544.44  4840.7 1541.72  4846.2 1542.50
  4893.1 1539.76  4910.9 1534.61  4916.5 1531.21  4922.0 1531.52  4939.9 1524.62
  4954.5 1523.12  5030.9 1522.53  5101.9 1524.04  5112.1 1523.47  5116.0 1520.66
  5116.2 1520.16  5120.0 1520.66  5134.0 1525.07  5221.1 1530.48  5280.7 1535.70
  5324.3 1543.06  5389.6 1548.06  5405.6 1553.34  5411.4 1552.00  5427.4 1556.18
  5433.1 1554.46  5443.3 1557.42  5449.2 1560.57  5454.9 1559.82  5469.7 1561.95
#Mann=3,-1,0
  4766.4    0.12       0  5116.0    0.05       0  5120.0    0.12       0
Bank Sta=5116,5120
Exp/Cntr=0.3,0.1

Type RM Length L Ch R = 1,1419,120,120,120
BEGIN DESCRIPTION:
Stream0260_DS 7.0
END DESCRIPTION:
XS GIS Cut Line= 3
      2059618.96     13927022.02      2059619.80     13926624.52
      2059625.00     13926324.97
#Sta/Elev= 30
  4602.5 1532.10  4619.5 1531.91  4629.5 1533.05  4689.5 1534.47  4719.5 1532.42
  4749.5 1527.61  4829.5 1520.42  4859.5 1518.92  4939.5 1517.30  4959.5 1512.99
  4987.5 1511.17  4987.8 1510.67  4991.5 1511.17  4997.3 1512.73  5002.3 1512.73
  5008.0 1515.95  5013.0 1515.20  5019.5 1516.27  5039.5 1516.05  5049.5 1518.12
  5109.5 1519.97  5159.5 1524.29  5189.5 1530.85  5229.6 1541.81  5249.6 1546.04
  5269.6 1552.38  5279.6 1554.52  5289.6 1558.09  5297.1 1561.90  5299.6 1561.90
#Mann=3,-1,0
  4602.5    0.12       0  4987.5    0.05       0  4991.5    0.12       0
Bank Sta=4987.5,4991.5
Exp/Cntr=0.3,0.1

Type RM Length L Ch R = 1,1299,185,185,185
BEGIN DESCRIPTION:
Stream0260_DS 6.0
END DESCRIPTION:
XS GIS Cut Line= 3
      2059712.73     13926991.24      2059740.06     13926624.86
      2059741.72     13926325.56
#Sta/Elev= 30
  4632.6 1525.21  4648.9 1525.46  4689.0 1522.90  4719.1 1521.54  4732.2 1520.17
  4789.3 1516.73  4869.7 1513.15  4959.7 1512.81  4997.0 1511.06  4999.6 1510.49
  5002.4 1510.49  5007.9 1506.71  5008.1 1506.21  5011.6 1506.21  5011.9 1506.71
  5019.9 1508.29  5029.9 1511.40  5039.9 1513.24  5099.9 1517.87  5119.9 1520.05
  5139.9 1524.22  5149.9 1524.47  5159.9 1525.79  5209.9 1536.97  5219.9 1538.58
  5229.9 1540.79  5259.9 1550.28  5279.9 1555.99  5297.1 1562.59  5299.3 1562.59
#Mann=3,-1,0
  4632.6    0.12       0  5007.9    0.05       0  5011.9    0.12       0
Bank Sta=5007.9,5011.9
Exp/Cntr=0.3,0.1

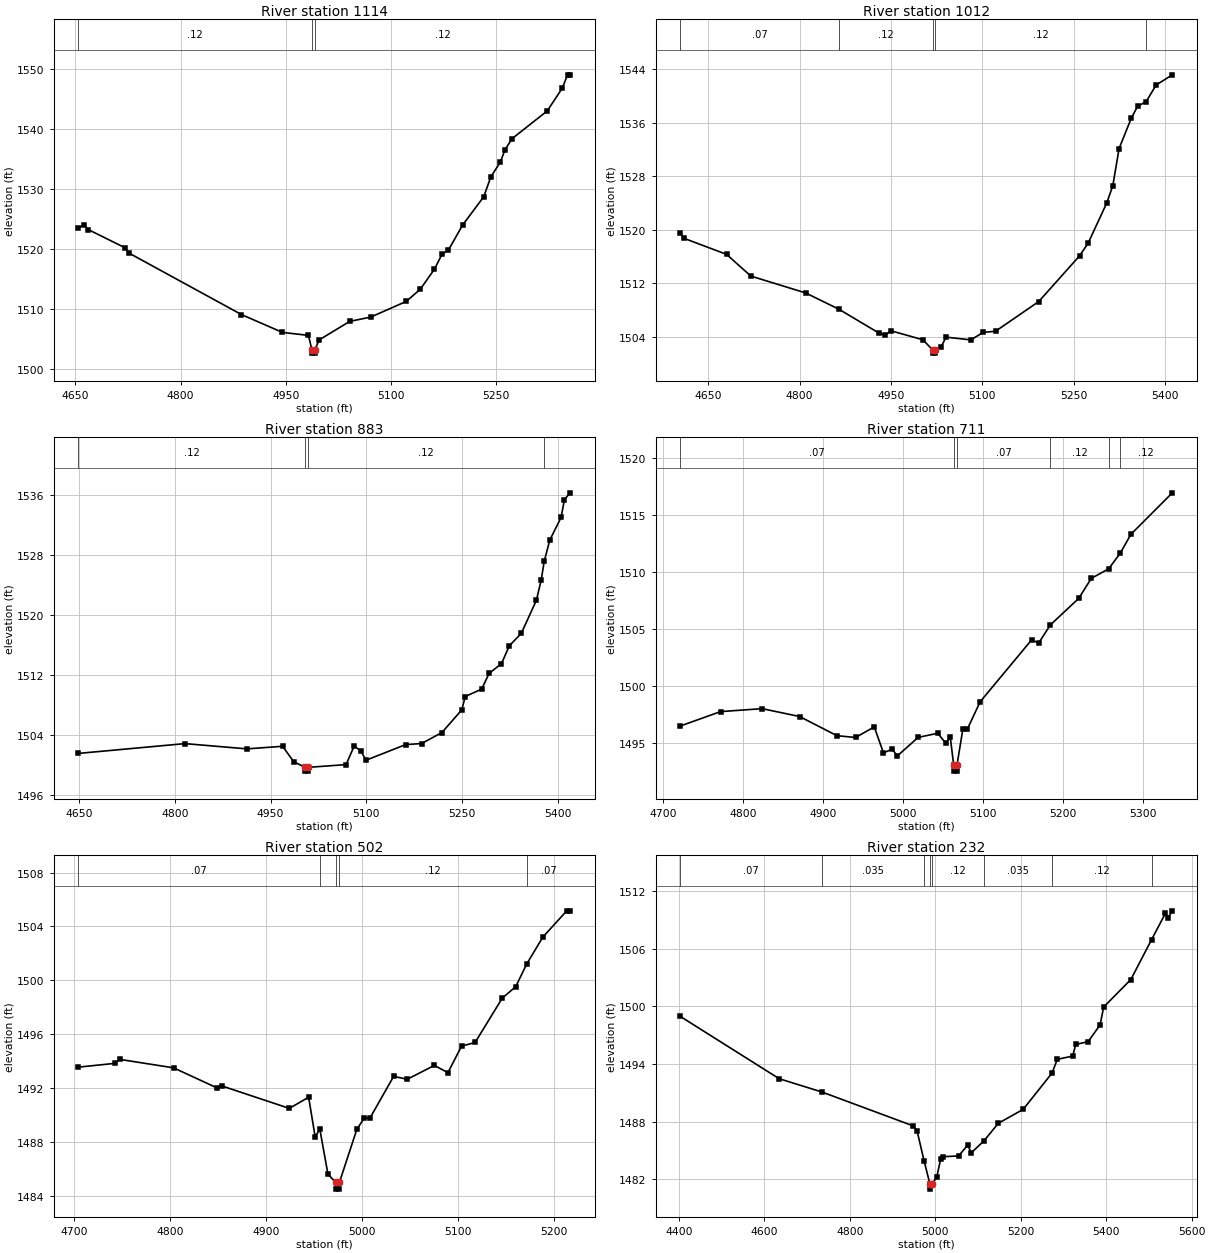
Type RM Length L Ch R = 1,1114,102,102,102
BEGIN DESCRIPTION:
Stream0260_DS 5.0
END DESCRIPTION:
XS GIS Cut Line= 3
      2059733.62     13926973.97      2059909.61     13926675.95
      2059868.31     13926322.66
#Sta/Elev= 30
  4653.9 1523.56  4662.5 1524.03  4668.3 1523.26  4721.0 1520.21  4726.8 1519.31
  4886.8 1509.08  4945.3 1506.10  4982.4 1505.60  4987.5 1503.14  4987.7 1502.64
  4991.2 1502.64  4991.5 1503.14  4997.6 1504.84  5041.2 1507.93  5071.4 1508.66
  5121.8 1511.26  5141.9 1513.29  5162.0 1516.62  5173.0 1519.14  5182.2 1519.86
  5202.3 1524.00  5232.5 1528.74  5242.6 1532.05  5256.3 1534.55  5262.7 1536.55
  5272.8 1538.42  5323.1 1543.06  5344.7 1546.89  5352.0 1549.08  5355.7 1549.08
#Mann=3,-1,0
  4653.9    0.12       0  4987.5    0.05       0  4991.5    0.12       0
Bank Sta=4987.5,4991.5
Exp/Cntr=0.3,0.1

Type RM Length L Ch R = 1,1012,129,129,129
BEGIN DESCRIPTION:
Stream0260_DS 4.0
END DESCRIPTION:
XS GIS Cut Line= 3
      2059999.97     13927120.83      2059995.03     13926724.96
      2059924.01     13926318.82
#Sta/Elev= 30
  4604.1 1519.44  4609.9 1518.70  4679.9 1516.30  4719.9 1513.05  4809.9 1510.53
  4864.4 1508.10  4930.0 1504.55  4940.0 1504.21  4950.0 1504.87  5002.5 1503.53
  5018.3 1502.03  5018.5 1501.53  5022.0 1501.53  5022.3 1502.03  5032.4 1502.46
  5040.6 1503.92  5081.2 1503.51  5101.5 1504.63  5121.8 1504.80  5192.8 1509.24
  5260.1 1516.10  5274.1 1518.00  5304.5 1523.97  5314.5 1526.56  5324.8 1532.12
  5345.1 1536.71  5355.3 1538.44  5369.3 1539.14  5385.7 1541.62  5412.3 1543.14
#Mann=5,-1,0
  4604.1    0.07       0  4864.4    0.12       0  5018.3    0.05       0
  5022.3    0.12       0  5369.3    0.07       0
Bank Sta=5018.3,5022.3
Exp/Cntr=0.3,0.1

Type RM Length L Ch R = 1,883,172,172,172
BEGIN DESCRIPTION:
Stream0260_DS 3.0
END DESCRIPTION:
XS GIS Cut Line= 3
      2060192.27     13927066.49      2060123.53     13926721.47
      2059985.88     13926324.99
#Sta/Elev= 30
  4648.2 1501.58  4815.7 1502.89  4912.7 1502.19  4968.9 1502.53  4986.2 1500.48
  5004.2 1499.72  5004.4 1499.22  5007.9 1499.22  5008.2 1499.72  5068.4 1500.09
  5081.0 1502.56  5091.5 1501.94  5099.5 1500.67  5161.8 1502.76  5186.8 1502.90
  5218.6 1504.36  5249.9 1507.40  5255.2 1509.17  5281.0 1510.16  5292.7 1512.26
  5312.1 1513.56  5324.4 1515.94  5343.2 1517.60  5366.8 1522.01  5374.4 1524.72
  5379.1 1527.21  5387.9 1530.05  5405.5 1533.05  5410.8 1535.44  5419.7 1536.34
#Mann=4,-1,0
  4648.2    0.12       0  5004.2    0.05       0  5008.2    0.12       0
  5379.1    0.07       0
Bank Sta=5004.2,5008.2
Exp/Cntr=0.3,0.1

Type RM Length L Ch R = 1,711,209,209,209
BEGIN DESCRIPTION:
Stream0260_DS 2.0
END DESCRIPTION:
XS GIS Cut Line= 3
      2060359.46     13926857.55      2060239.76     13926584.95
      2060080.39     13926310.26
#Sta/Elev= 30
  4721.4 1496.51  4771.6 1497.77  4823.7 1498.03  4870.5 1497.34  4917.2 1495.66
  4940.5 1495.50  4963.9 1496.43  4975.4 1494.15  4986.3 1494.48  4992.7 1493.88
  5018.8 1495.51  5043.3 1495.87  5053.2 1495.01  5059.0 1495.51  5063.3 1493.05
  5063.6 1492.55  5067.1 1492.55  5067.3 1493.05  5074.8 1496.28  5080.5 1496.26
  5096.3 1498.63  5160.9 1504.08  5169.4 1503.77  5184.1 1505.37  5219.6 1507.70
  5235.4 1509.46  5257.0 1510.29  5271.3 1511.64  5285.0 1513.33  5336.7 1516.96
#Mann=6,-1,0
  4721.4    0.07       0  5063.3    0.05       0  5067.3    0.07       0
  5184.1    0.12       0  5257.0    0.07       0  5271.3    0.12       0
Bank Sta=5063.3,5067.3
Exp/Cntr=0.3,0.1

Type RM Length L Ch R = 1,502,270,270,270
BEGIN DESCRIPTION:
Stream0260_DS 1.0
END DESCRIPTION:
XS GIS Cut Line= 3
      2060454.07     13926823.96      2060425.00     13926525.00
      2060275.00     13926375.00
#Sta/Elev= 30
  4704.4 1493.56  4742.5 1493.84  4747.5 1494.14  4803.8 1493.51  4849.4 1492.01
  4854.4 1492.16  4924.4 1490.50  4944.5 1491.33  4951.3 1488.40  4956.2 1488.95
  4964.6 1485.63  4972.6 1485.01  4972.9 1484.51  4976.4 1484.51  4976.6 1485.01
  4994.7 1488.94  5002.3 1489.77  5008.3 1489.77  5033.1 1492.88  5047.2 1492.66
  5075.5 1493.69  5089.6 1493.15  5103.8 1495.12  5117.9 1495.39  5146.2 1498.68
  5160.3 1499.54  5171.7 1501.22  5188.6 1503.22  5213.4 1505.16  5216.9 1505.16
#Mann=5,-1,0
  4704.4    0.07       0  4956.2    0.12       0  4972.6    0.05       0
  4976.6    0.12       0  5171.7    0.07       0
Bank Sta=4972.6,4976.6
Exp/Cntr=0.3,0.1

Type RM Length L Ch R = 1,232,0,0,0
BEGIN DESCRIPTION:
Stream0260_DS 0.0
END DESCRIPTION:
XS GIS Cut Line= 5
      2060291.95     13927007.64      2060616.13     13926738.14
      2060680.20     13926575.48      2060576.37     13926419.36
      2060271.67     13926214.25
#Sta/Elev= 30
  4403.6 1498.96  4634.8 1492.47  4735.1 1491.08  4948.5 1487.55  4957.5 1487.03
  4973.9 1483.90  4987.8 1481.46  4988.0 1480.96  4991.8 1481.46  5003.5 1482.21
  5012.5 1484.05  5018.5 1484.34  5054.6 1484.42  5075.6 1485.53  5084.6 1484.76
  5113.7 1485.98  5147.8 1487.83  5205.7 1489.27  5273.3 1493.06  5285.6 1494.49
  5321.7 1494.83  5328.7 1496.04  5357.9 1496.34  5385.7 1498.08  5394.1 1499.94
  5457.7 1502.81  5506.1 1506.96  5538.6 1509.71  5544.6 1509.25  5554.8 1509.97
#Mann=8,-1,0
  4403.6    0.07       0  4735.1   0.035       0  4973.9    0.12       0
  4987.8    0.05       0  4991.8    0.12       0  5113.7   0.035       0
  5273.3    0.12       0  5506.1    0.07       0
Bank Sta=4987.8,4991.8
Exp/Cntr=0.3,0.1

Chan Stop Cuts=-1