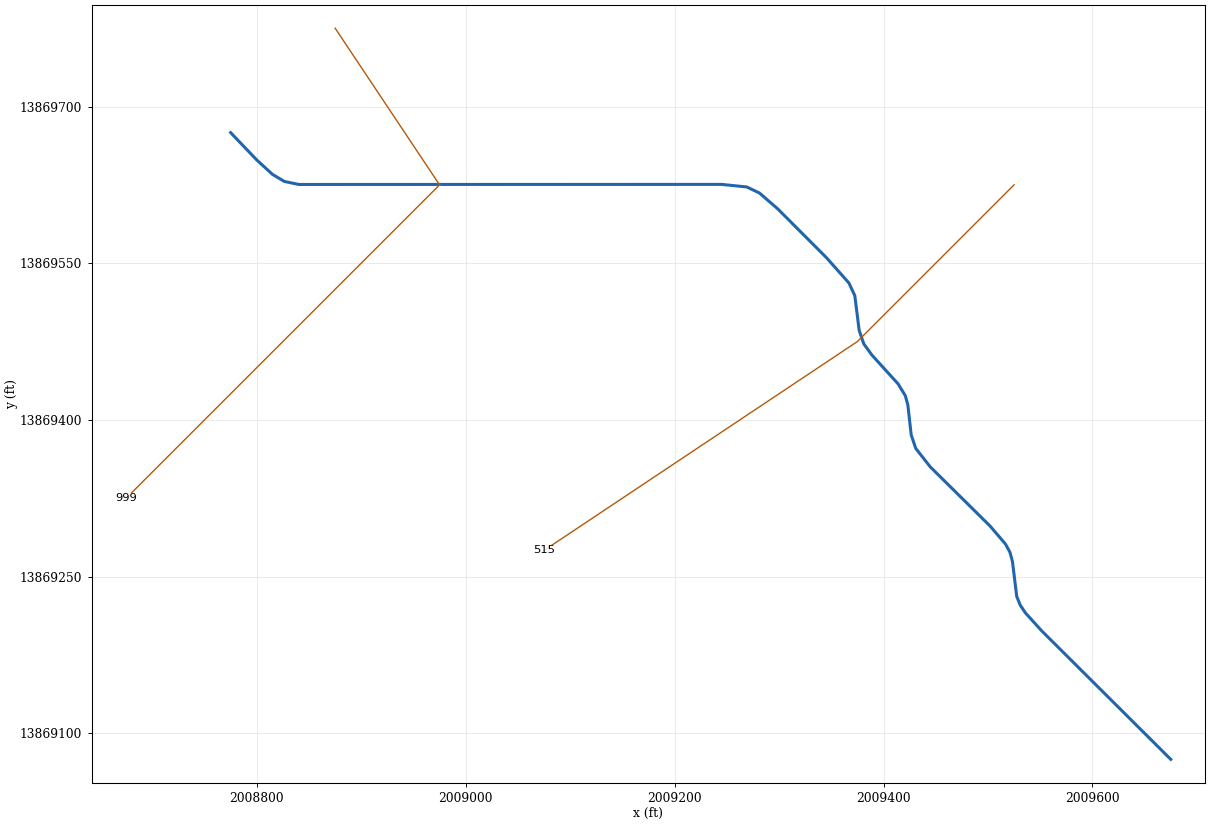
--- Stream0261_DS.prj (project) ---

Proj Title=Stream0261_DS Base Level Engineering
Current Plan=p01
Default Exp/Contr=0.3,0.1
English Units
Geom File=g01
Flow File=f01
Plan File=p01
BEGIN DESCRIPTION:
Stream0261_DS
END DESCRIPTION:

--- Stream0261_DS.p01 (plan) ---

Plan Title=Multiple Run
Short Identifier=Multiple
Geom File=g01
Flow File=f01
Subcritical Flow
K Sum by GR= 0
Std Step Tol= 0.01
Critical Tol= 0.01
Num of Std Step Trials= 20
Max Error Tol= 0.3
Flow Tol Ratio= 0.001
Split Flow NTrial= 30
Split Flow Tol= 0.02
Split Flow Ratio= 0.02
Log Output Level= 0
Friction Slope Method= 1
Unsteady Friction Slope Method= 2
Unsteady Bridges Friction Slope Method= 1
Parabolic Critical Depth
Global Vel Dist=  1 , 1 , 1
Global Log Level= 0
CheckData=True
Encroach Param= -1, 0, 0, 0
BEGIN DESCRIPTION:
Multiple Run
END DESCRIPTION:

--- Stream0261_DS.f01 (steady flow) ---

Flow Title=Multiple
Number of Profiles=7
Profile Names=10-year,25-year,50-year,1pct_min,100-year,1pct_plu,500-year
River Rch & RM= Stream0261_DS,Reach-1,999
     236     361     470     299     596    1190     943
Boundary for River Rch & Prof#=Stream0261_DS,Reach-1,1
Up Type=0
Dn Type=3
Dn Slope=0.005
Boundary for River Rch & Prof#=Stream0261_DS,Reach-1,2
Up Type=0
Dn Type=3
Dn Slope=0.005
Boundary for River Rch & Prof#=Stream0261_DS,Reach-1,3
Up Type=0
Dn Type=3
Dn Slope=0.005
Boundary for River Rch & Prof#=Stream0261_DS,Reach-1,4
Up Type=0
Dn Type=3
Dn Slope=0.005
Boundary for River Rch & Prof#=Stream0261_DS,Reach-1,5
Up Type=0
Dn Type=3
Dn Slope=0.005
Boundary for River Rch & Prof#=Stream0261_DS,Reach-1,6
Up Type=0
Dn Type=3
Dn Slope=0.005
Boundary for River Rch & Prof#=Stream0261_DS,Reach-1,7
Up Type=0
Dn Type=3
Dn Slope=0.005

--- Stream0261_DS.g01 (geometry) ---

Geom Title=Existing Conditions

River Reach=Stream0261_DS,Reach-1
Reach XY= 30
      2008775.00     13869675.00      2008799.71     13869649.11
      2008815.02     13869635.05      2008826.36     13869628.29
      2008840.15     13869625.36      2009245.18     13869625.43
      2009269.16     13869622.95      2009281.21     13869617.20
      2009298.58     13869602.16      2009345.42     13869555.24
      2009366.87     13869531.07      2009372.51     13869518.97
      2009376.70     13869485.71      2009381.10     13869472.81
      2009388.98     13869461.94      2009413.90     13869434.55
      2009420.81     13869423.27      2009423.30     13869414.30
      2009426.51     13869385.63      2009430.85     13869372.71
      2009444.82     13869354.93      2009501.94     13869298.44
      2009516.82     13869281.04      2009521.01     13869273.35
      2009523.45     13869264.36      2009527.53     13869231.05
      2009530.85     13869222.71      2009535.77     13869215.32
      2009551.29     13869198.18      2009675.00     13869075.00

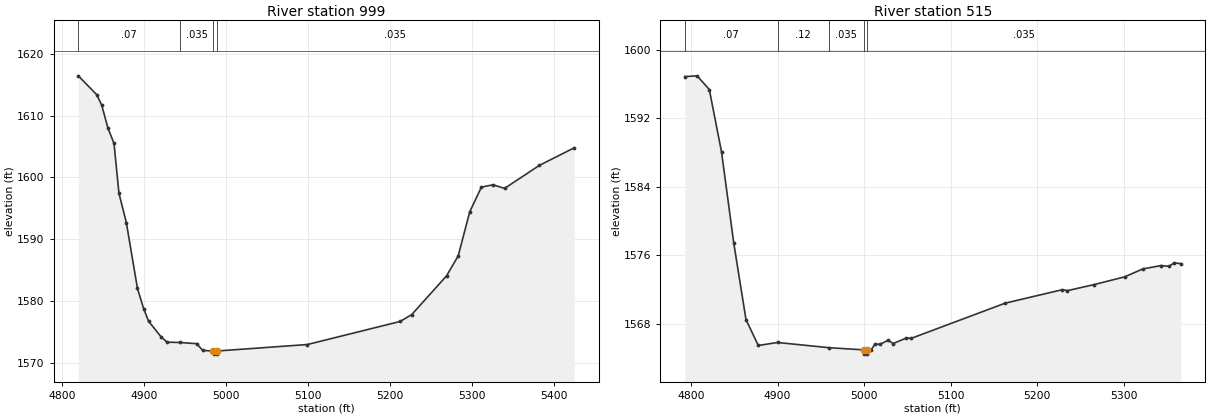
Type RM Length L Ch R = 1,999,484,484,484
BEGIN DESCRIPTION:
Stream0261_DS 2.0
END DESCRIPTION:
XS GIS Cut Line= 3
      2008875.02     13869774.98      2008975.00     13869625.00
      2008675.01     13869325.01
#Sta/Elev= 30
  4819.7 1616.41  4842.2 1613.35  4848.2 1611.68  4855.7 1608.01  4863.2 1605.49
  4869.2 1597.45  4878.3 1592.66  4891.8 1582.06  4899.3 1578.81  4905.3 1576.79
  4920.3 1574.30  4927.8 1573.39  4943.7 1573.34  4963.9 1573.15  4971.4 1572.06
  4984.4 1571.96  4984.7 1571.46  4988.2 1571.46  4988.4 1571.96  5098.9 1573.01
  5212.1 1576.74  5226.2 1577.85  5268.6 1584.10  5282.8 1587.32  5296.9 1594.45
  5311.1 1598.43  5325.2 1598.81  5339.4 1598.23  5381.8 1601.95  5424.2 1604.78
#Mann=4,-1,0
  4819.7    0.07       0  4943.7   0.035       0  4984.4   0.035       0
  4988.4   0.035       0
Bank Sta=4984.4,4988.4
Exp/Cntr=0.3,0.1

Type RM Length L Ch R = 1,515,0,0,0
BEGIN DESCRIPTION:
Stream0261_DS 1.0
END DESCRIPTION:
XS GIS Cut Line= 3
      2009525.01     13869625.01      2009375.00     13869475.00
      2009075.01     13869275.00
#Sta/Elev= 30
  4792.9 1596.86  4807.1 1596.95  4821.2 1595.35  4835.3 1588.07  4849.5 1577.37
  4863.6 1568.46  4877.8 1565.44  4900.0 1565.79  4959.5 1565.18  4999.5 1564.93
  4999.8 1564.43  5003.3 1564.43  5003.5 1564.93  5008.1 1564.93  5012.6 1565.60
  5018.6 1565.58  5027.6 1566.05  5033.6 1565.67  5048.6 1566.30  5054.6 1566.28
  5162.8 1570.38  5228.9 1571.96  5234.9 1571.85  5265.0 1572.54  5301.0 1573.46
  5322.0 1574.39  5343.1 1574.78  5352.1 1574.69  5358.1 1575.09  5365.6 1575.01
#Mann=5,-1,0
  4792.9    0.07       0  4900.0    0.12       0  4959.5   0.035       0
  4999.5   0.035       0  5003.5   0.035       0
Bank Sta=4999.5,5003.5
Exp/Cntr=0.3,0.1

Chan Stop Cuts=-1