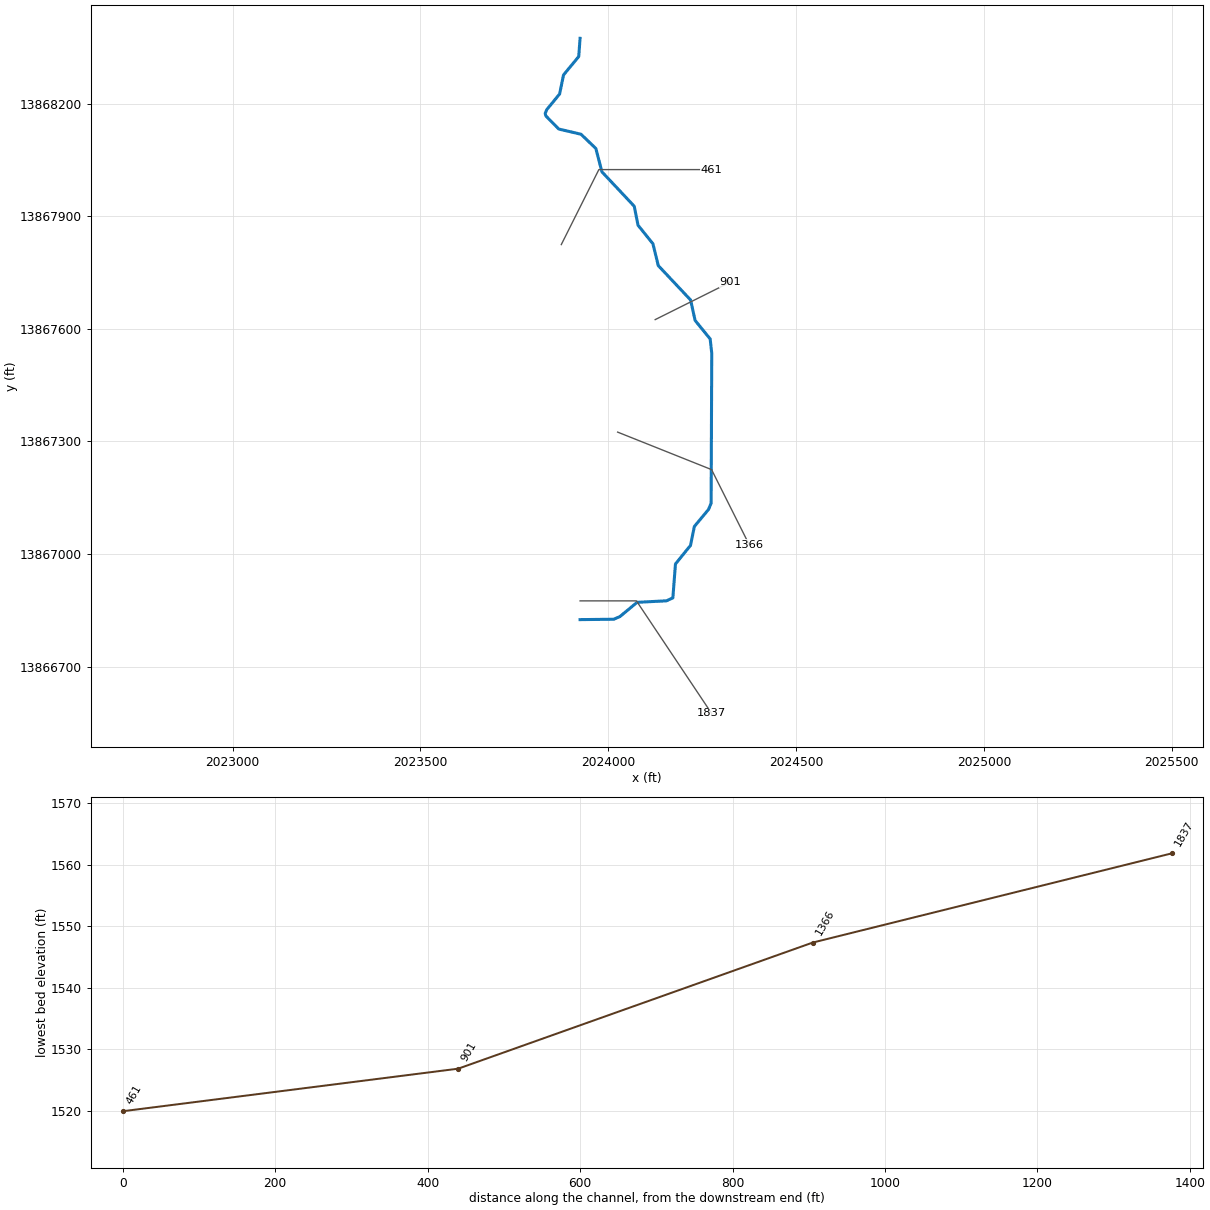
--- Stream0262_DS.prj (project) ---

Proj Title=Stream0262_DS Base Level Engineering
Current Plan=p01
Default Exp/Contr=0.3,0.1
English Units
Geom File=g01
Flow File=f01
Plan File=p01
BEGIN DESCRIPTION:
Stream0262_DS
END DESCRIPTION:

--- Stream0262_DS.p01 (plan) ---

Plan Title=Multiple Run
Short Identifier=Multiple
Geom File=g01
Flow File=f01
Subcritical Flow
K Sum by GR= 0
Std Step Tol= 0.01
Critical Tol= 0.01
Num of Std Step Trials= 20
Max Error Tol= 0.3
Flow Tol Ratio= 0.001
Split Flow NTrial= 30
Split Flow Tol= 0.02
Split Flow Ratio= 0.02
Log Output Level= 0
Friction Slope Method= 1
Unsteady Friction Slope Method= 2
Unsteady Bridges Friction Slope Method= 1
Parabolic Critical Depth
Global Vel Dist=  1 , 1 , 1
Global Log Level= 0
CheckData=True
Encroach Param= -1, 0, 0, 0
BEGIN DESCRIPTION:
Multiple Run
END DESCRIPTION:

--- Stream0262_DS.f01 (steady flow) ---

Flow Title=Multiple
Number of Profiles=7
Profile Names=10-year,25-year,50-year,1pct_min,100-year,1pct_plu,500-year
River Rch & RM= Stream0262_DS,Reach-1,1837
     770    1290    1781    1194    2383    4755    4216
Boundary for River Rch & Prof#=Stream0262_DS,Reach-1,1
Up Type=0
Dn Type=3
Dn Slope=0.005
Boundary for River Rch & Prof#=Stream0262_DS,Reach-1,2
Up Type=0
Dn Type=3
Dn Slope=0.005
Boundary for River Rch & Prof#=Stream0262_DS,Reach-1,3
Up Type=0
Dn Type=3
Dn Slope=0.005
Boundary for River Rch & Prof#=Stream0262_DS,Reach-1,4
Up Type=0
Dn Type=3
Dn Slope=0.005
Boundary for River Rch & Prof#=Stream0262_DS,Reach-1,5
Up Type=0
Dn Type=3
Dn Slope=0.005
Boundary for River Rch & Prof#=Stream0262_DS,Reach-1,6
Up Type=0
Dn Type=3
Dn Slope=0.005
Boundary for River Rch & Prof#=Stream0262_DS,Reach-1,7
Up Type=0
Dn Type=3
Dn Slope=0.005

--- Stream0262_DS.g01 (geometry) ---

Geom Title=Existing Conditions

River Reach=Stream0262_DS,Reach-1
Reach XY= 30
      2023925.00     13866825.00      2024014.58     13866826.02
      2024031.08     13866833.11      2024076.67     13866871.14
      2024154.96     13866875.12      2024171.97     13866883.01
      2024178.86     13866973.34      2024218.89     13867022.81
      2024229.19     13867073.26      2024266.91     13867118.92
      2024273.80     13867135.50      2024275.46     13867535.19
      2024271.25     13867573.45      2024231.14     13867622.83
      2024219.16     13867677.29      2024133.16     13867768.95
      2024118.90     13867827.19      2024079.19     13867876.73
      2024069.15     13867927.29      2023983.18     13868018.98
      2023966.95     13868081.33      2023927.49     13868119.25
      2023868.33     13868133.16      2023833.99     13868167.99
      2023832.20     13868174.70      2023836.21     13868184.74
      2023870.57     13868226.61      2023880.92     13868277.24
      2023921.40     13868326.49      2023925.00     13868375.00

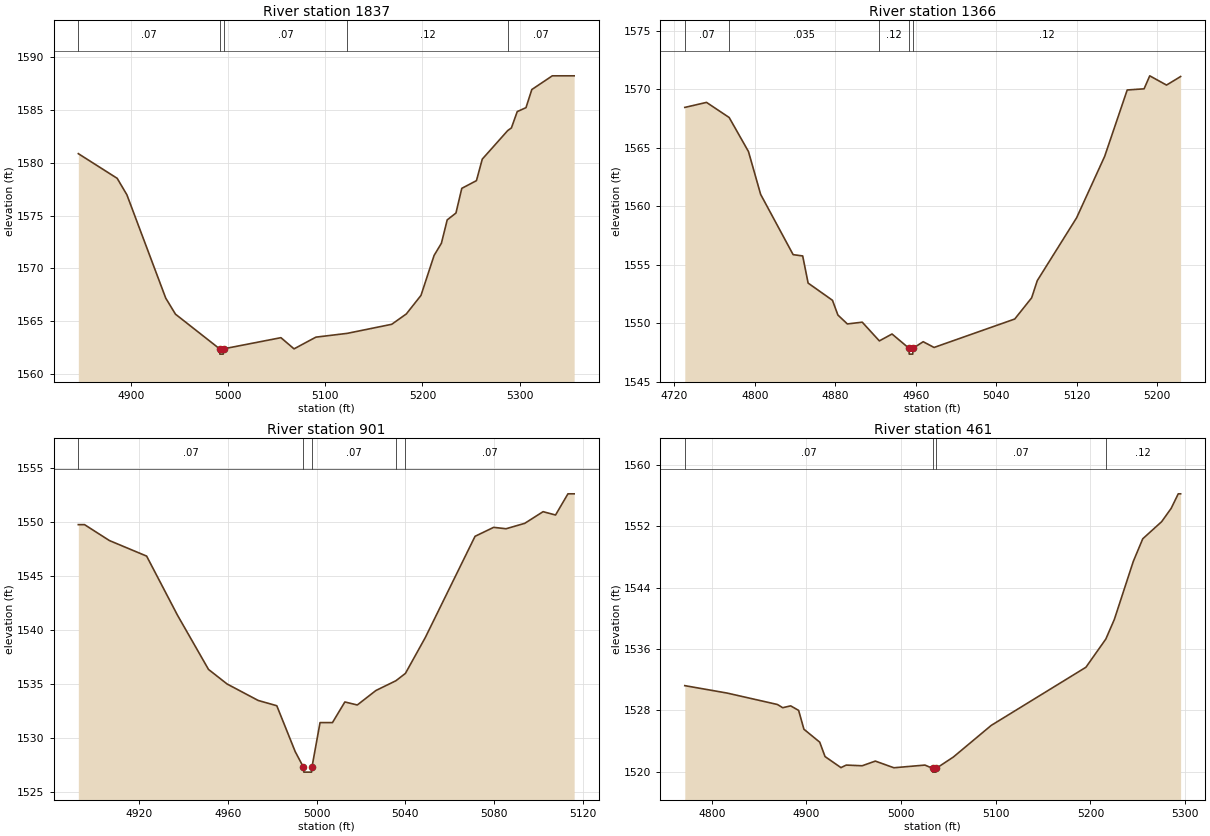
Type RM Length L Ch R = 1,1837,471,471,471
BEGIN DESCRIPTION:
Stream0262_DS 4.0
END DESCRIPTION:
XS GIS Cut Line= 3
      2023925.04     13866875.00      2024075.00     13866875.00
      2024274.99     13866575.01
#Sta/Elev= 30
  4845.7 1580.88  4885.7 1578.54  4895.7 1576.98  4935.7 1567.18  4945.7 1565.66
  4991.2 1562.37  4991.4 1561.87  4994.9 1561.87  4995.2 1562.37  5054.3 1563.43
  5067.8 1562.37  5090.3 1563.48  5122.6 1563.84  5168.4 1564.70  5183.4 1565.68
  5198.5 1567.44  5212.0 1571.23  5219.5 1572.38  5225.5 1574.60  5234.5 1575.25
  5240.5 1577.59  5255.6 1578.32  5261.6 1580.36  5287.8 1583.07  5291.6 1583.32
  5297.6 1584.87  5306.6 1585.24  5312.6 1586.96  5333.7 1588.26  5356.2 1588.26
#Mann=5,-1,0
  4845.7    0.07       0  4991.2    0.05       0  4995.2    0.07       0
  5122.6    0.12       0  5287.8    0.07       0
Bank Sta=4991.2,4995.2
Exp/Cntr=0.3,0.1

Type RM Length L Ch R = 1,1366,465,465,465
BEGIN DESCRIPTION:
Stream0262_DS 3.0
END DESCRIPTION:
XS GIS Cut Line= 3
      2024024.96     13867325.01      2024275.00     13867225.00
      2024375.00     13867025.00
#Sta/Elev= 30
  4730.5 1568.44  4752.1 1568.87  4774.6 1567.58  4793.8 1564.67  4805.9 1561.01
  4838.2 1555.86  4847.7 1555.75  4853.1 1553.43  4877.3 1551.96  4882.7 1550.70
  4892.1 1549.94  4906.9 1550.09  4923.9 1548.49  4936.5 1549.08  4953.4 1547.86
  4953.6 1547.36  4957.1 1547.36  4957.4 1547.86  4967.5 1548.42  4978.3 1547.93
  5058.5 1550.36  5075.3 1552.17  5080.9 1553.64  5120.0 1559.01  5147.9 1564.26
  5170.3 1569.93  5187.1 1570.03  5192.7 1571.14  5209.4 1570.35  5223.4 1571.08
#Mann=5,-1,0
  4730.5    0.07       0  4774.6   0.035       0  4923.9    0.12       0
  4953.4    0.05       0  4957.4    0.12       0
Bank Sta=4953.4,4957.4
Exp/Cntr=0.3,0.1

Type RM Length L Ch R = 1,901,440,440,440
BEGIN DESCRIPTION:
Stream0262_DS 2.0
END DESCRIPTION:
XS GIS Cut Line= 3
      2024124.99     13867625.00      2024225.00     13867675.00
      2024324.98     13867724.99
#Sta/Elev= 30
  4892.5 1549.74  4895.3 1549.74  4906.5 1548.27  4923.3 1546.83  4937.2 1541.37
  4951.2 1536.35  4959.6 1535.00  4973.6 1533.48  4982.0 1532.99  4990.3 1528.75
  4993.9 1527.35  4994.2 1526.85  4997.7 1526.85  4997.9 1527.35  5001.5 1531.43
  5007.1 1531.43  5012.7 1533.34  5018.3 1533.06  5026.7 1534.40  5035.7 1535.30
  5040.0 1535.98  5049.0 1539.31  5071.4 1548.66  5079.8 1549.49  5085.4 1549.36
  5093.8 1549.86  5102.1 1550.94  5107.7 1550.63  5113.3 1552.59  5116.1 1552.59
#Mann=5,-1,0
  4892.5    0.07       0  4993.9    0.05       0  4997.9    0.07       0
  5035.7    0.12       0  5040.0    0.07       0
Bank Sta=4993.9,4997.9
Exp/Cntr=0.3,0.1

Type RM Length L Ch R = 1,461,0,0,0
BEGIN DESCRIPTION:
Stream0262_DS 1.0
END DESCRIPTION:
XS GIS Cut Line= 3
      2023875.00     13867825.01      2023975.00     13868025.00
      2024275.00     13868025.00
#Sta/Elev= 30
  4771.6 1531.22  4816.3 1530.25  4869.4 1528.76  4875.0 1528.34  4883.4 1528.58
  4891.8 1527.99  4897.4 1525.53  4914.1 1523.84  4919.7 1521.96  4936.5 1520.52
  4942.1 1520.85  4958.9 1520.76  4972.8 1521.37  4992.4 1520.50  5025.2 1520.85
  5033.2 1520.43  5033.4 1519.93  5036.9 1519.93  5037.2 1520.43  5055.2 1521.90
  5095.2 1526.03  5195.2 1533.62  5216.2 1537.30  5225.2 1539.86  5245.2 1547.43
  5255.2 1550.39  5275.2 1552.63  5285.2 1554.36  5292.7 1556.26  5295.2 1556.26
#Mann=4,-1,0
  4771.6    0.07       0  5033.2    0.05       0  5037.2    0.07       0
  5216.2    0.12       0
Bank Sta=5033.2,5037.2
Exp/Cntr=0.3,0.1

Chan Stop Cuts=-1