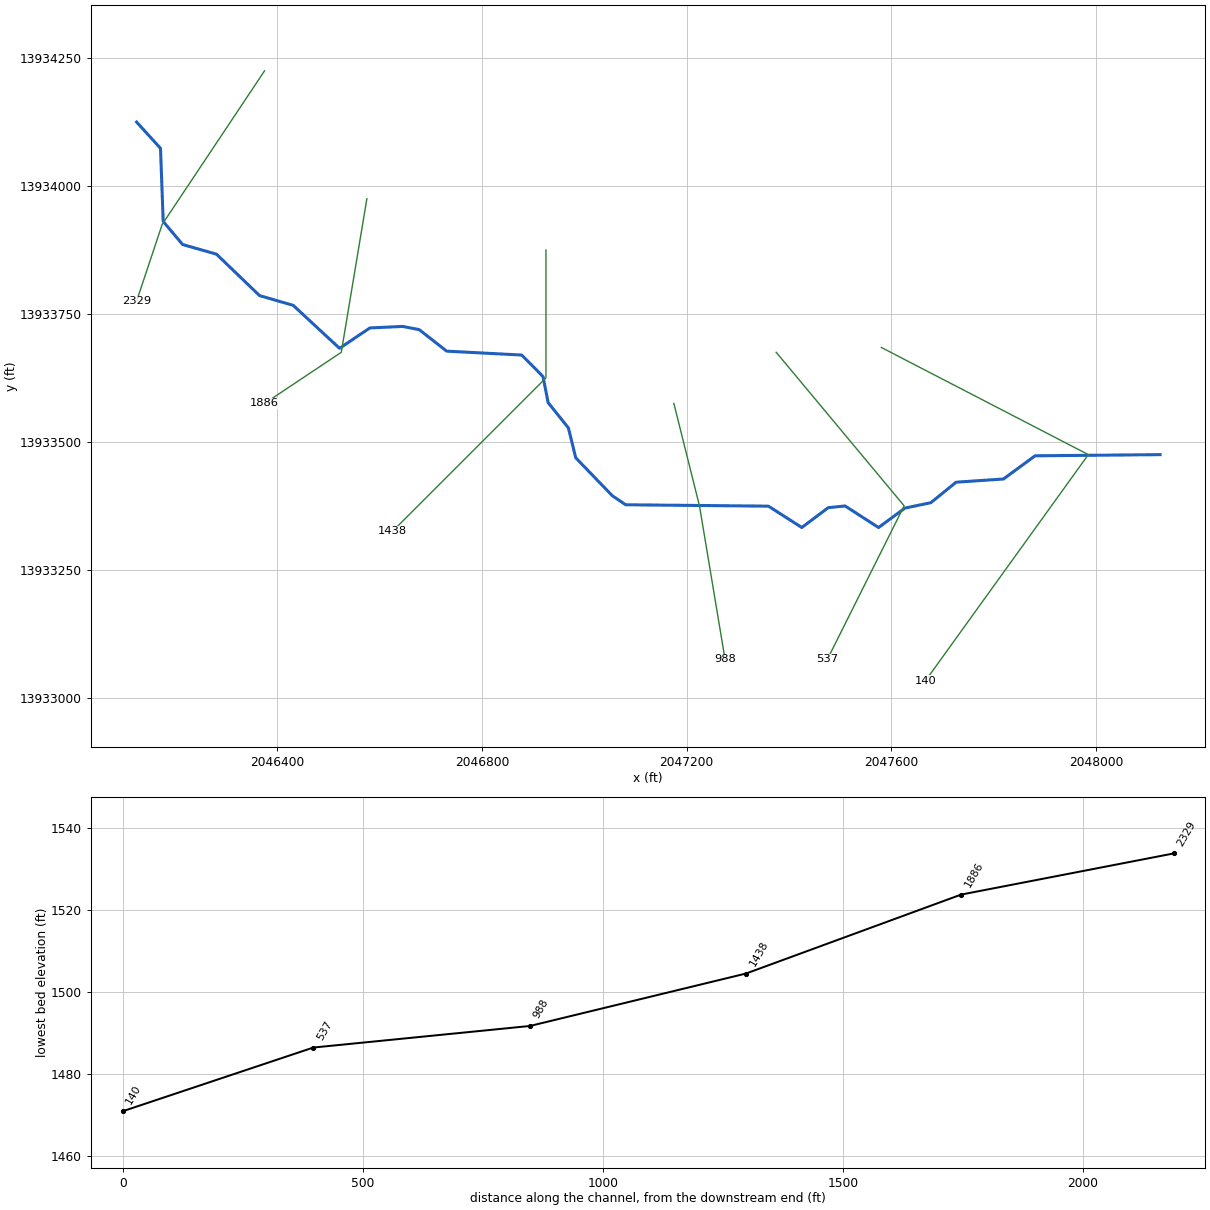
--- Stream0265_DS.prj (project) ---

Proj Title=Stream0265_DS Base Level Engineering
Current Plan=p01
Default Exp/Contr=0.3,0.1
English Units
Geom File=g01
Flow File=f01
Plan File=p01
BEGIN DESCRIPTION:
Stream0265_DS
END DESCRIPTION:

--- Stream0265_DS.p01 (plan) ---

Plan Title=Multiple Run
Short Identifier=Multiple
Geom File=g01
Flow File=f01
Subcritical Flow
K Sum by GR= 0
Std Step Tol= 0.01
Critical Tol= 0.01
Num of Std Step Trials= 20
Max Error Tol= 0.3
Flow Tol Ratio= 0.001
Split Flow NTrial= 30
Split Flow Tol= 0.02
Split Flow Ratio= 0.02
Log Output Level= 0
Friction Slope Method= 1
Unsteady Friction Slope Method= 2
Unsteady Bridges Friction Slope Method= 1
Parabolic Critical Depth
Global Vel Dist=  1 , 1 , 1
Global Log Level= 0
CheckData=True
Encroach Param= -1, 0, 0, 0
BEGIN DESCRIPTION:
Multiple Run
END DESCRIPTION:

--- Stream0265_DS.f01 (steady flow) ---

Flow Title=Multiple
Number of Profiles=7
Profile Names=10-year,25-year,50-year,1pct_min,100-year,1pct_plu,500-year
River Rch & RM= Stream0265_DS,Reach-1,2329
     249     389     513     331     660    1317    1077
River Rch & RM= Stream0265_DS,Reach-1,1886
     376     606     814     534    1065    2126    1802
Boundary for River Rch & Prof#=Stream0265_DS,Reach-1,1
Up Type=0
Dn Type=3
Dn Slope=0.005
Boundary for River Rch & Prof#=Stream0265_DS,Reach-1,2
Up Type=0
Dn Type=3
Dn Slope=0.005
Boundary for River Rch & Prof#=Stream0265_DS,Reach-1,3
Up Type=0
Dn Type=3
Dn Slope=0.005
Boundary for River Rch & Prof#=Stream0265_DS,Reach-1,4
Up Type=0
Dn Type=3
Dn Slope=0.005
Boundary for River Rch & Prof#=Stream0265_DS,Reach-1,5
Up Type=0
Dn Type=3
Dn Slope=0.005
Boundary for River Rch & Prof#=Stream0265_DS,Reach-1,6
Up Type=0
Dn Type=3
Dn Slope=0.005
Boundary for River Rch & Prof#=Stream0265_DS,Reach-1,7
Up Type=0
Dn Type=3
Dn Slope=0.005

--- Stream0265_DS.g01 (geometry) ---

Geom Title=Existing Conditions

River Reach=Stream0265_DS,Reach-1
Reach XY= 30
      2046125.00     13934125.00      2046171.70     13934073.63
      2046176.99     13933930.67      2046214.95     13933885.62
      2046281.02     13933866.81      2046365.33     13933785.80
      2046431.05     13933766.80      2046521.59     13933682.81
      2046580.89     13933722.63      2046645.04     13933725.58
      2046677.31     13933719.31      2046730.94     13933677.27
      2046877.70     13933669.64      2046919.29     13933627.58
      2046929.20     13933576.77      2046968.90     13933527.19
      2046983.13     13933468.93      2047054.80     13933394.59
      2047080.84     13933377.05      2047359.84     13933374.34
      2047425.01     13933332.59      2047476.65     13933371.36
      2047509.64     13933374.71      2047575.00     13933332.56
      2047626.64     13933370.58      2047677.17     13933381.09
      2047726.58     13933421.17      2047819.02     13933427.36
      2047880.94     13933472.74      2048125.00     13933475.00

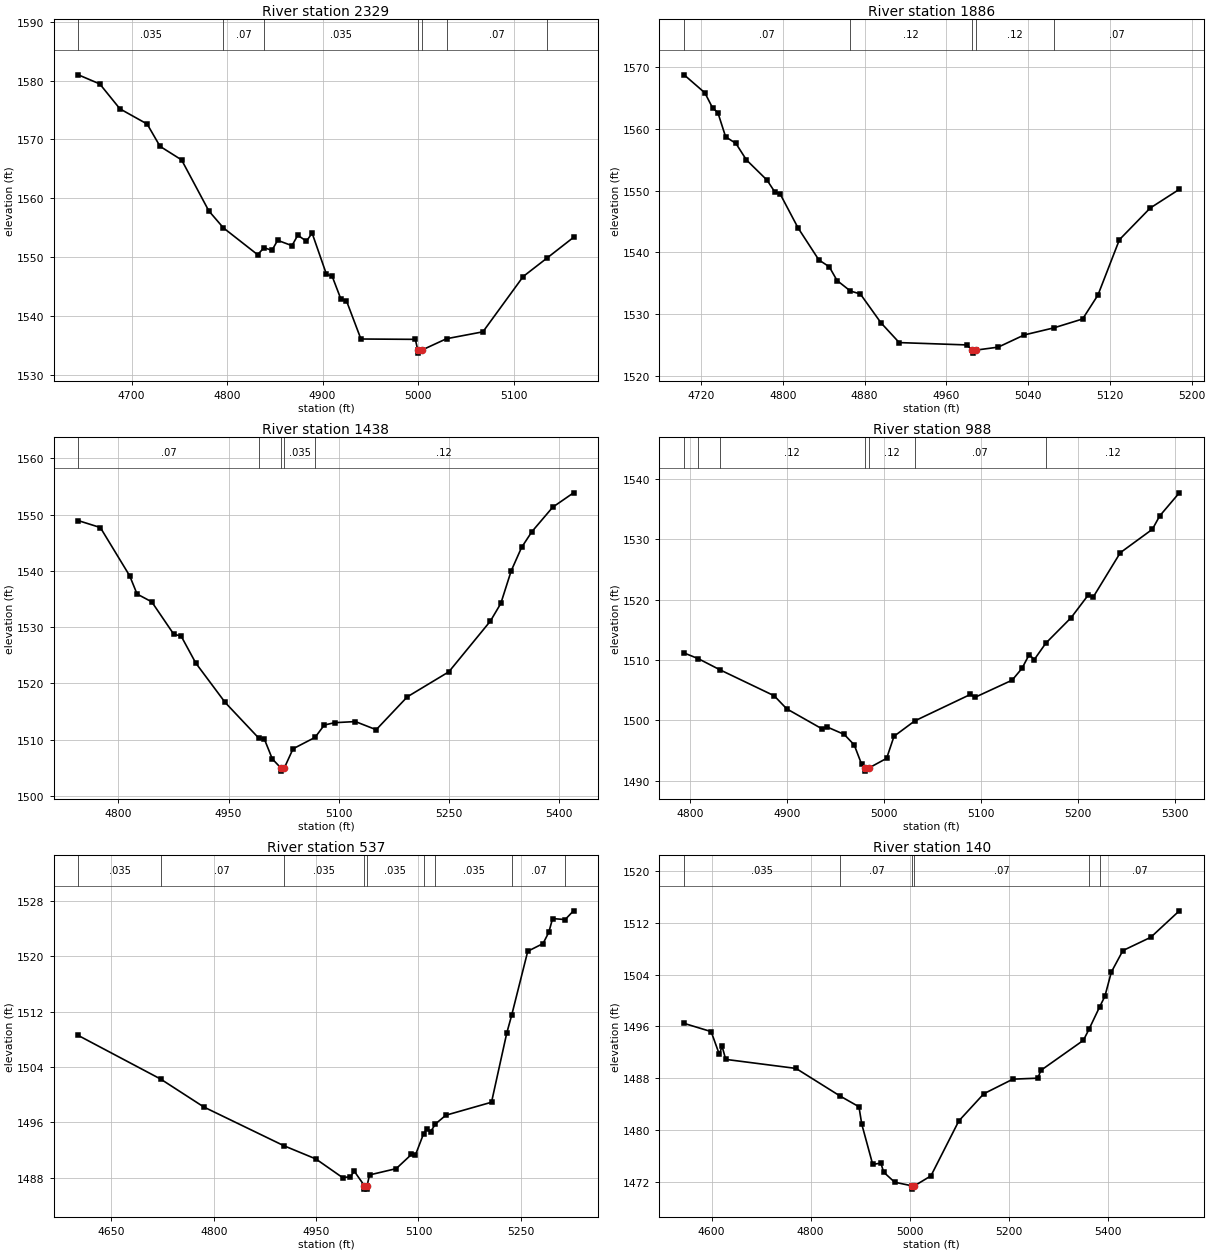
Type RM Length L Ch R = 1,2329,443,443,443
BEGIN DESCRIPTION:
Stream0265_DS 5.0
END DESCRIPTION:
XS GIS Cut Line= 3
      2046375.00     13934225.00      2046175.00     13933925.00
      2046124.99     13933774.97
#Sta/Elev= 30
  4644.1 1580.98  4666.6 1579.43  4687.7 1575.20  4716.2 1572.62  4729.7 1568.83
  4752.3 1566.52  4780.8 1557.86  4796.1 1554.97  4831.9 1550.42  4838.7 1551.61
  4846.9 1551.15  4852.9 1552.86  4867.9 1551.95  4874.0 1553.73  4883.0 1552.71
  4889.0 1554.08  4904.0 1547.09  4910.0 1546.75  4919.0 1542.93  4925.0 1542.57
  4940.1 1536.09  4997.1 1536.03  4999.7 1534.19  4999.9 1533.69  5003.7 1534.19
  5029.8 1536.14  5067.9 1537.31  5110.1 1546.71  5134.6 1549.79  5162.8 1553.36
#Mann=7,-1,0
  4644.1   0.035       0  4796.1    0.07       0  4838.7   0.035       0
  4999.7   0.035       0  5003.7   0.035       0  5029.8    0.07       0
  5134.6    0.12       0
Bank Sta=4999.7,5003.7
Exp/Cntr=0.3,0.1

Type RM Length L Ch R = 1,1886,448,448,448
BEGIN DESCRIPTION:
Stream0265_DS 4.0
END DESCRIPTION:
XS GIS Cut Line= 3
      2046575.00     13933975.02      2046525.00     13933675.00
      2046375.03     13933575.02
#Sta/Elev= 30
  4703.5 1568.79  4723.8 1565.87  4731.4 1563.41  4736.5 1562.67  4744.1 1558.74
  4754.2 1557.66  4764.4 1555.00  4784.6 1551.71  4792.2 1549.80  4797.3 1549.51
  4815.0 1543.95  4835.3 1538.77  4845.5 1537.65  4853.1 1535.43  4866.1 1533.73
  4875.9 1533.24  4896.1 1528.56  4913.9 1525.36  4979.8 1524.98  4985.4 1524.15
  4985.6 1523.65  4989.4 1524.15  5010.7 1524.62  5036.2 1526.60  5065.0 1527.74
  5093.3 1529.19  5108.3 1533.07  5129.3 1542.05  5159.4 1547.18  5187.9 1550.22
#Mann=5,-1,0
  4703.5    0.07       0  4866.1    0.12       0  4985.4    0.05       0
  4989.4    0.12       0  5065.0    0.07       0
Bank Sta=4985.4,4989.4
Exp/Cntr=0.3,0.1

Type RM Length L Ch R = 1,1438,450,450,450
BEGIN DESCRIPTION:
Stream0265_DS 3.0
END DESCRIPTION:
XS GIS Cut Line= 3
      2046925.00     13933875.01      2046925.00     13933625.00
      2046624.98     13933324.98
#Sta/Elev= 30
  4745.4 1548.93  4775.4 1547.70  4815.4 1539.11  4825.4 1535.88  4845.4 1534.49
  4875.4 1528.73  4885.4 1528.41  4905.4 1523.60  4945.4 1516.60  4990.8 1510.31
  4998.9 1510.04  5009.6 1506.56  5021.7 1504.90  5021.9 1504.40  5025.7 1504.90
  5037.8 1508.37  5067.8 1510.40  5080.3 1512.59  5094.4 1513.01  5122.7 1513.21
  5151.0 1511.76  5193.4 1517.61  5250.0 1522.06  5306.5 1531.07  5320.7 1534.21
  5334.8 1539.99  5349.0 1544.17  5363.1 1546.98  5391.4 1551.32  5419.7 1553.87
#Mann=5,-1,0
  4745.4    0.07       0  4990.8   0.035       0  5021.7   0.035       0
  5025.7   0.035       0  5067.8    0.12       0
Bank Sta=5021.7,5025.7
Exp/Cntr=0.3,0.1

Type RM Length L Ch R = 1,988,451,451,451
BEGIN DESCRIPTION:
Stream0265_DS 2.0
END DESCRIPTION:
XS GIS Cut Line= 3
      2047174.99     13933575.04      2047225.00     13933375.00
      2047275.00     13933075.03
#Sta/Elev= 30
  4793.8 1511.17  4808.3 1510.24  4830.7 1508.39  4886.6 1504.09  4899.5 1501.93
  4935.6 1498.64  4940.7 1498.95  4958.8 1497.69  4969.1 1495.95  4976.8 1492.71
  4980.0 1492.11  4980.2 1491.61  4984.0 1492.11  5002.5 1493.73  5010.1 1497.38
  5031.4 1499.92  5088.7 1504.30  5093.8 1503.85  5131.8 1506.67  5141.9 1508.61
  5149.5 1510.92  5154.6 1510.07  5166.6 1512.81  5192.6 1517.02  5210.4 1520.80
  5215.4 1520.44  5243.3 1527.78  5276.3 1531.65  5283.9 1533.87  5304.1 1537.69
#Mann=7,-1,0
  4793.8   0.035       0  4808.3    0.07       0  4830.7    0.12       0
  4980.0    0.05       0  4984.0    0.12       0  5031.4    0.07       0
  5166.6    0.12       0
Bank Sta=4980,4984
Exp/Cntr=0.3,0.1

Type RM Length L Ch R = 1,537,397,397,397
BEGIN DESCRIPTION:
Stream0265_DS 1.0
END DESCRIPTION:
XS GIS Cut Line= 3
      2047375.00     13933675.00      2047625.00     13933375.00
      2047475.01     13933075.02
#Sta/Elev= 30
  4601.4 1508.54  4722.0 1502.25  4785.6 1498.20  4902.9 1492.61  4949.6 1490.71
  4988.7 1488.02  5000.3 1488.14  5005.9 1488.94  5020.7 1486.85  5020.9 1486.35
  5024.4 1486.35  5024.7 1486.85  5028.3 1488.40  5067.4 1489.31  5089.7 1491.36
  5095.3 1491.21  5107.4 1494.32  5112.1 1495.06  5117.7 1494.62  5124.9 1495.76
  5140.1 1497.02  5207.1 1498.90  5229.5 1508.91  5236.6 1511.45  5260.2 1520.70
  5282.6 1521.81  5291.0 1523.43  5296.6 1525.42  5315.0 1525.28  5327.3 1526.54
#Mann=9,-1,0
  4601.4   0.035       0  4722.0    0.07       0  4902.9   0.035       0
  5020.7   0.035       0  5024.7   0.035       0  5107.4    0.07       0
  5124.9   0.035       0  5236.6    0.07       0  5315.0    0.12       0
Bank Sta=5020.7,5024.7
Exp/Cntr=0.3,0.1

Type RM Length L Ch R = 1,140,0,0,0
BEGIN DESCRIPTION:
Stream0265_DS 0.0
END DESCRIPTION:
XS GIS Cut Line= 3
      2047580.38     13933684.51      2047984.98     13933475.05
      2047666.59     13933032.97
#Sta/Elev= 30
  4544.4 1496.47  4599.0 1495.20  4615.5 1491.69  4621.1 1492.94  4628.4 1490.90
  4770.5 1489.50  4860.1 1485.20  4897.6 1483.57  4903.3 1480.87  4925.4 1474.64
  4941.9 1474.85  4947.5 1473.45  4969.7 1471.89  5005.4 1471.32  5005.6 1470.82
  5009.4 1471.32  5043.0 1472.87  5099.4 1481.38  5149.8 1485.58  5208.6 1487.84
  5258.9 1487.99  5265.1 1489.20  5351.0 1493.85  5362.2 1495.54  5383.6 1498.99
  5394.4 1500.66  5407.5 1504.42  5430.8 1507.74  5487.2 1509.80  5544.8 1513.89
#Mann=6,-1,0
  4544.4   0.035       0  4860.1    0.07       0  5005.4    0.05       0
  5009.4    0.07       0  5362.2   0.035       0  5383.6    0.07       0
Bank Sta=5005.4,5009.4
Exp/Cntr=0.3,0.1

Chan Stop Cuts=-1