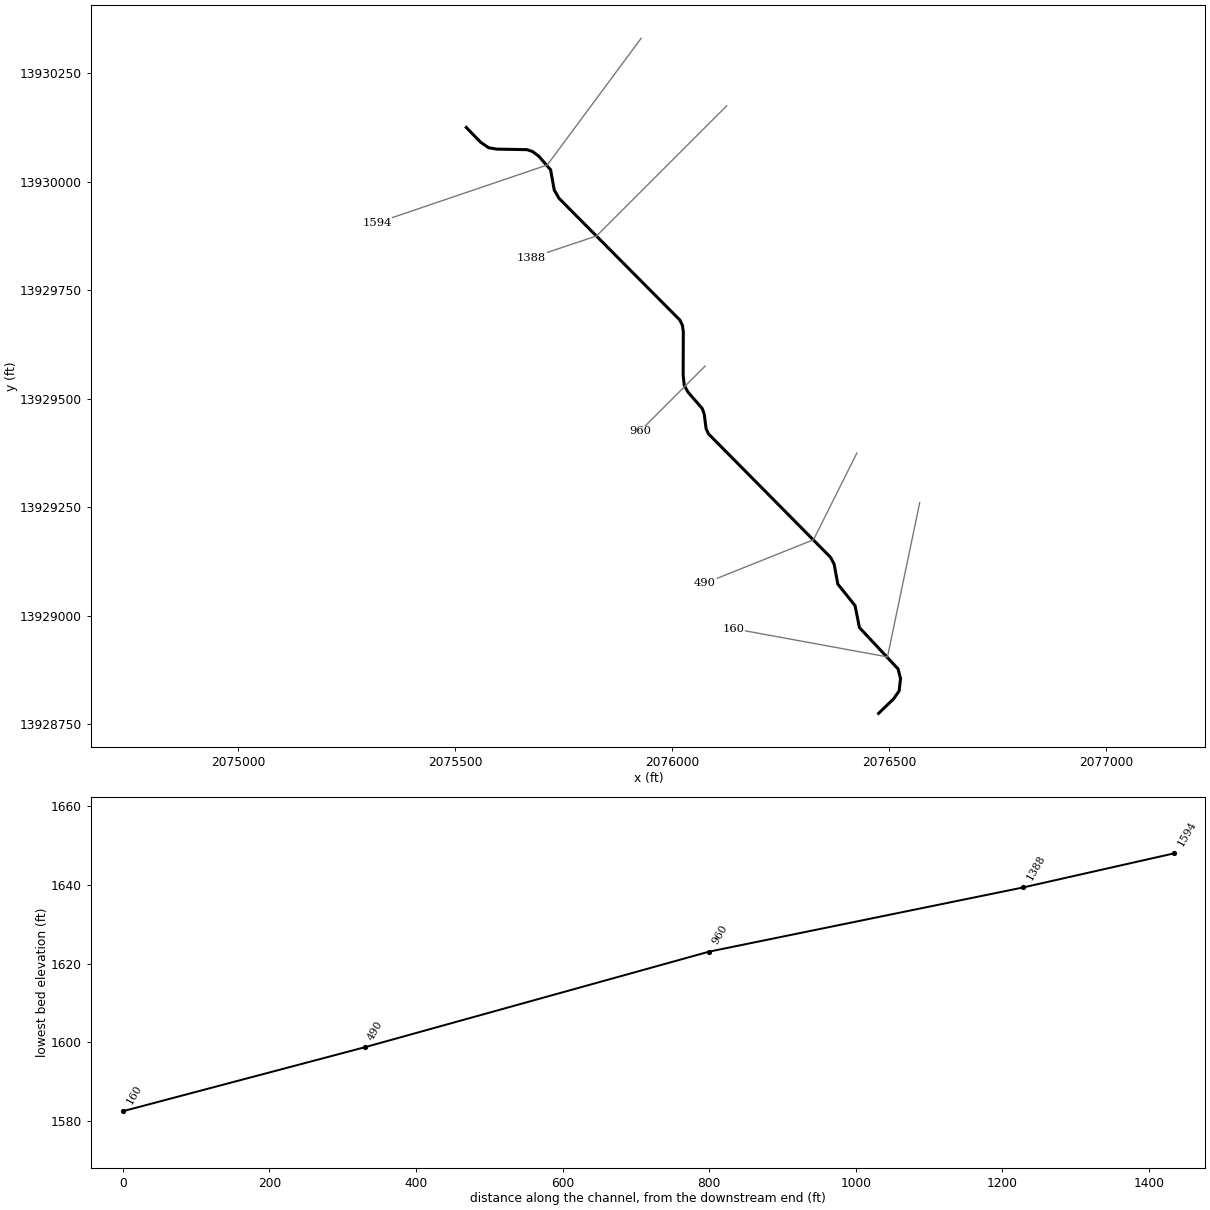
--- Stream0267_DS.prj (project) ---

Proj Title=Stream0267_DS Base Level Engineering
Current Plan=p01
Default Exp/Contr=0.3,0.1
English Units
Geom File=g01
Flow File=f01
Plan File=p01
BEGIN DESCRIPTION:
Stream0267_DS
END DESCRIPTION:

--- Stream0267_DS.p01 (plan) ---

Plan Title=Multiple Run
Short Identifier=Multiple
Geom File=g01
Flow File=f01
Subcritical Flow
K Sum by GR= 0
Std Step Tol= 0.01
Critical Tol= 0.01
Num of Std Step Trials= 20
Max Error Tol= 0.3
Flow Tol Ratio= 0.001
Split Flow NTrial= 30
Split Flow Tol= 0.02
Split Flow Ratio= 0.02
Log Output Level= 0
Friction Slope Method= 1
Unsteady Friction Slope Method= 2
Unsteady Bridges Friction Slope Method= 1
Parabolic Critical Depth
Global Vel Dist=  1 , 1 , 1
Global Log Level= 0
CheckData=True
Encroach Param= -1, 0, 0, 0
BEGIN DESCRIPTION:
Multiple Run
END DESCRIPTION:

--- Stream0267_DS.f01 (steady flow) ---

Flow Title=Multiple
Number of Profiles=7
Profile Names=10-year,25-year,50-year,1pct_min,100-year,1pct_plu,500-year
River Rch & RM= Stream0267_DS,Reach-1,1594
     297     470     625     407     812    1619    1347
Boundary for River Rch & Prof#=Stream0267_DS,Reach-1,1
Up Type=0
Dn Type=3
Dn Slope=0.005
Boundary for River Rch & Prof#=Stream0267_DS,Reach-1,2
Up Type=0
Dn Type=3
Dn Slope=0.005
Boundary for River Rch & Prof#=Stream0267_DS,Reach-1,3
Up Type=0
Dn Type=3
Dn Slope=0.005
Boundary for River Rch & Prof#=Stream0267_DS,Reach-1,4
Up Type=0
Dn Type=3
Dn Slope=0.005
Boundary for River Rch & Prof#=Stream0267_DS,Reach-1,5
Up Type=0
Dn Type=3
Dn Slope=0.005
Boundary for River Rch & Prof#=Stream0267_DS,Reach-1,6
Up Type=0
Dn Type=3
Dn Slope=0.005
Boundary for River Rch & Prof#=Stream0267_DS,Reach-1,7
Up Type=0
Dn Type=3
Dn Slope=0.005

--- Stream0267_DS.g01 (geometry) ---

Geom Title=Existing Conditions

River Reach=Stream0267_DS,Reach-1
Reach XY= 30
      2075525.00     13930125.00      2075557.96     13930091.13
      2075576.41     13930078.39      2075595.09     13930075.20
      2075664.69     13930073.94      2075677.69     13930069.60
      2075692.13     13930058.71      2075719.26     13930027.57
      2075727.55     13929981.09      2075738.64     13929961.80
      2076017.18     13929681.19      2076022.93     13929669.14
      2076025.02     13929655.01      2076024.67     13929554.86
      2076027.25     13929530.93      2076035.80     13929515.33
      2076068.86     13929477.17      2076073.28     13929464.29
      2076077.50     13929431.03      2076083.14     13929418.94
      2076364.24     13929134.68      2076372.50     13929118.96
      2076381.10     13929072.81      2076420.81     13929023.27
      2076430.85     13928972.71      2076519.93     13928877.34
      2076525.57     13928854.94      2076522.33     13928826.62
      2076509.26     13928808.08      2076475.00     13928775.00

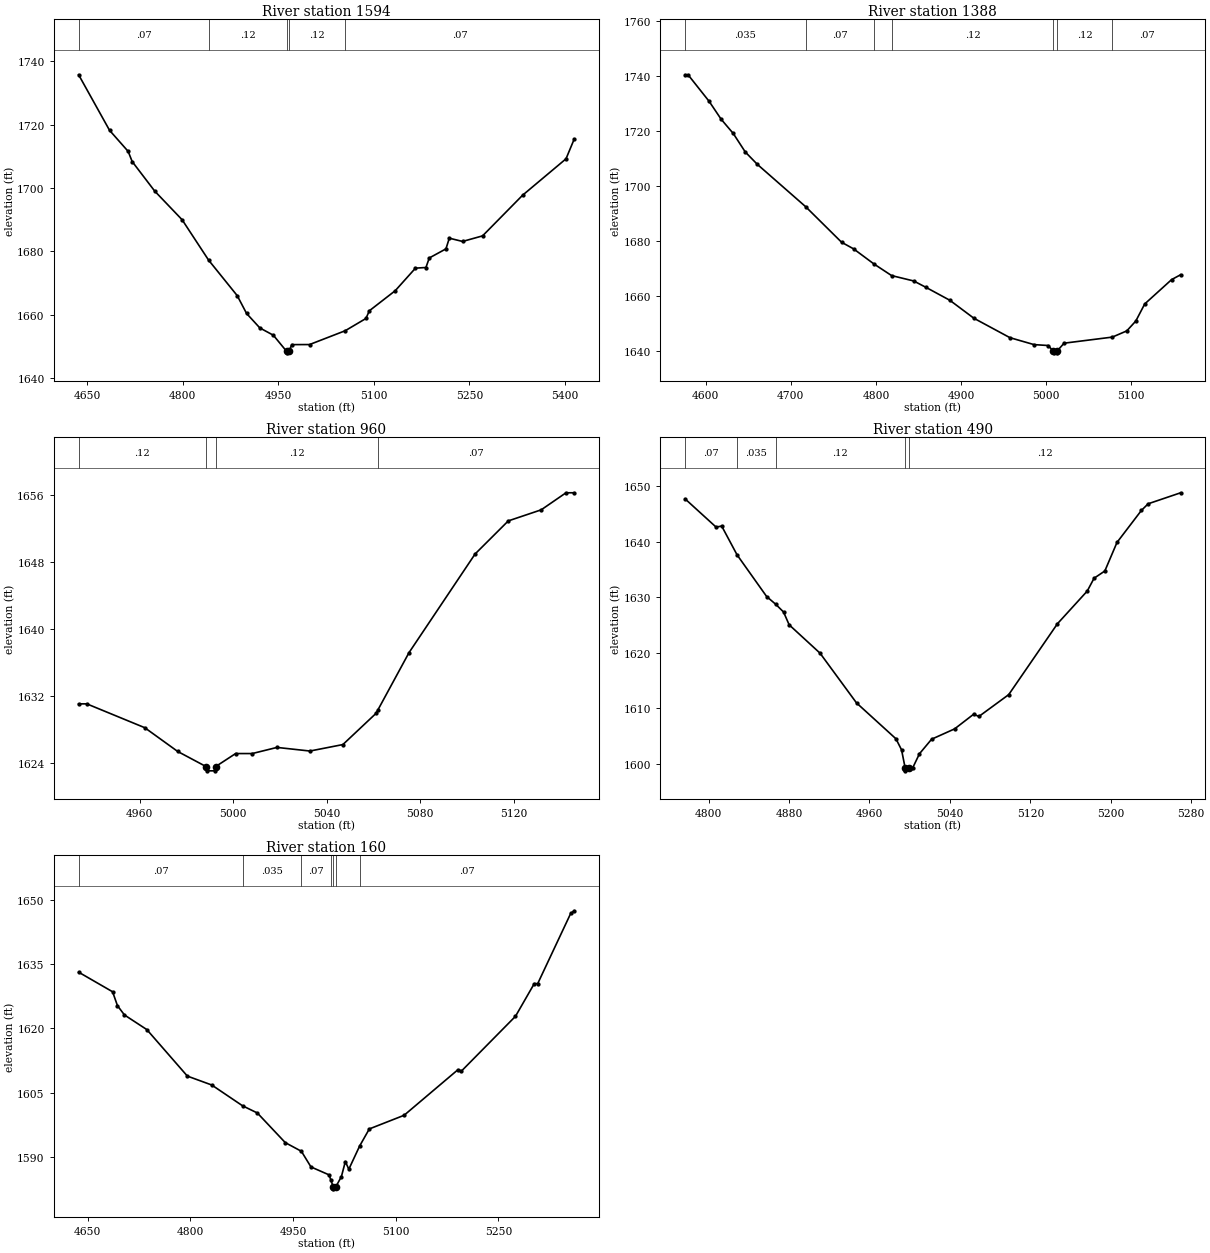
Type RM Length L Ch R = 1,1594,206,206,206
BEGIN DESCRIPTION:
Stream0267_DS 4.0
END DESCRIPTION:
XS GIS Cut Line= 3
      2075927.76     13930330.46      2075711.54     13930038.63
      2075319.24     13929905.41
#Sta/Elev= 30
  4636.8 1735.68  4685.3 1718.18  4714.5 1711.54  4720.8 1708.34  4756.2 1699.02
  4799.2 1689.99  4840.7 1677.28  4885.6 1666.09  4900.3 1660.47  4921.1 1655.91
  4942.3 1653.61  4963.0 1648.56  4963.2 1648.06  4967.0 1648.56  4971.2 1650.65
  4999.1 1650.67  5055.0 1655.02  5087.6 1658.89  5092.9 1661.31  5133.6 1667.65
  5165.3 1674.75  5181.7 1674.95  5187.0 1677.96  5213.1 1680.82  5218.4 1684.19
  5239.2 1683.16  5270.6 1684.92  5333.4 1697.73  5401.5 1709.20  5414.3 1715.39
#Mann=5,-1,0
  4636.8    0.07       0  4840.7    0.12       0  4963.0    0.05       0
  4967.0    0.12       0  5055.0    0.07       0
Bank Sta=4963,4967
Exp/Cntr=0.3,0.1

Type RM Length L Ch R = 1,1388,428,428,428
BEGIN DESCRIPTION:
Stream0267_DS 3.0
END DESCRIPTION:
XS GIS Cut Line= 3
      2076125.01     13930175.01      2075825.00     13929875.00
      2075674.99     13929825.00
#Sta/Elev= 30
  4575.7 1740.49  4579.2 1740.49  4604.0 1730.81  4618.1 1724.31  4632.3 1719.15
  4646.4 1712.43  4660.6 1707.92  4717.3 1692.55  4759.6 1679.60  4773.7 1677.20
  4797.8 1671.67  4818.4 1667.48  4844.4 1665.52  4858.6 1663.23  4886.8 1658.51
  4915.1 1651.97  4957.5 1644.90  4985.8 1642.38  5002.6 1642.05  5008.5 1639.89
  5008.8 1639.39  5012.3 1639.39  5012.5 1639.89  5021.1 1642.90  5077.8 1645.11
  5094.8 1647.37  5105.4 1650.95  5115.9 1657.17  5147.5 1666.02  5158.1 1667.79
#Mann=7,-1,0
  4575.7   0.035       0  4717.3    0.07       0  4797.8   0.035       0
  4818.4    0.12       0  5008.5    0.05       0  5012.5    0.12       0
  5077.8    0.07       0
Bank Sta=5008.5,5012.5
Exp/Cntr=0.3,0.1

Type RM Length L Ch R = 1,960,470,470,470
BEGIN DESCRIPTION:
Stream0267_DS 2.0
END DESCRIPTION:
XS GIS Cut Line= 3
      2076075.00     13929575.00      2076025.00     13929525.00
      2075925.03     13929425.03
#Sta/Elev= 21
  4933.8 1631.06  4937.3 1631.06  4962.1 1628.22  4976.2 1625.39  4988.4 1623.58
  4988.6 1623.08  4992.1 1623.08  4992.4 1623.58  5001.0 1625.14  5008.1 1625.14
  5018.7 1625.87  5032.8 1625.44  5046.9 1626.21  5061.1 1629.93  5061.8 1630.29
  5075.2 1637.16  5103.5 1648.92  5117.7 1652.86  5131.8 1654.18  5142.4 1656.21
  5145.9 1656.21
#Mann=4,-1,0
  4933.8    0.12       0  4988.4    0.05       0  4992.4    0.12       0
  5061.8    0.07       0
Bank Sta=4988.4,4992.4
Exp/Cntr=0.3,0.1

Type RM Length L Ch R = 1,490,330,330,330
BEGIN DESCRIPTION:
Stream0267_DS 1.0
END DESCRIPTION:
XS GIS Cut Line= 3
      2076425.02     13929375.04      2076325.00     13929175.00
      2076075.01     13929075.01
#Sta/Elev= 30
  4776.6 1647.68  4807.4 1642.61  4813.0 1642.79  4828.3 1637.61  4857.7 1630.12
  4866.7 1628.73  4874.5 1627.34  4880.1 1625.03  4910.8 1619.93  4947.1 1610.98
  4986.3 1604.53  4991.9 1602.54  4995.5 1599.26  4995.7 1598.76  4999.5 1599.26
  5002.9 1599.26  5009.7 1601.83  5021.8 1604.45  5044.7 1606.31  5063.5 1608.93
  5068.9 1608.55  5098.5 1612.47  5147.0 1625.23  5176.6 1631.10  5183.4 1633.41
  5194.1 1634.71  5206.2 1639.85  5230.5 1645.61  5237.2 1646.80  5269.5 1648.78
#Mann=5,-1,0
  4776.6    0.07       0  4828.3   0.035       0  4866.7    0.12       0
  4995.5    0.05       0  4999.5    0.12       0
Bank Sta=4995.5,4999.5
Exp/Cntr=0.3,0.1

Type RM Length L Ch R = 1,160,0,0,0
BEGIN DESCRIPTION:
Stream0267_DS 0.0
END DESCRIPTION:
XS GIS Cut Line= 3
      2076569.73     13929260.46      2076495.50     13928905.13
      2076140.70     13928970.13
#Sta/Elev= 30
  4637.0 1633.13  4686.6 1628.55  4693.7 1625.30  4703.9 1623.13  4736.6 1619.71
  4795.8 1608.84  4831.4 1606.76  4876.5 1601.89  4898.0 1600.22  4938.8 1593.29
  4962.3 1591.27  4976.3 1587.61  5002.8 1585.75  5005.5 1584.49  5008.7 1582.99
  5008.9 1582.49  5012.7 1582.99  5020.8 1585.37  5026.5 1588.87  5031.6 1587.08
  5047.4 1592.50  5061.5 1596.49  5112.3 1599.68  5191.0 1610.34  5196.1 1610.02
  5275.0 1622.82  5302.4 1630.45  5307.5 1630.47  5355.6 1646.85  5360.7 1647.48
#Mann=7,-1,0
  4637.0    0.07       0  4876.5   0.035       0  4962.3    0.07       0
  5005.5   0.035       0  5008.7    0.05       0  5012.7   0.035       0
  5047.4    0.07       0
Bank Sta=5008.7,5012.7
Exp/Cntr=0.3,0.1

Chan Stop Cuts=-1