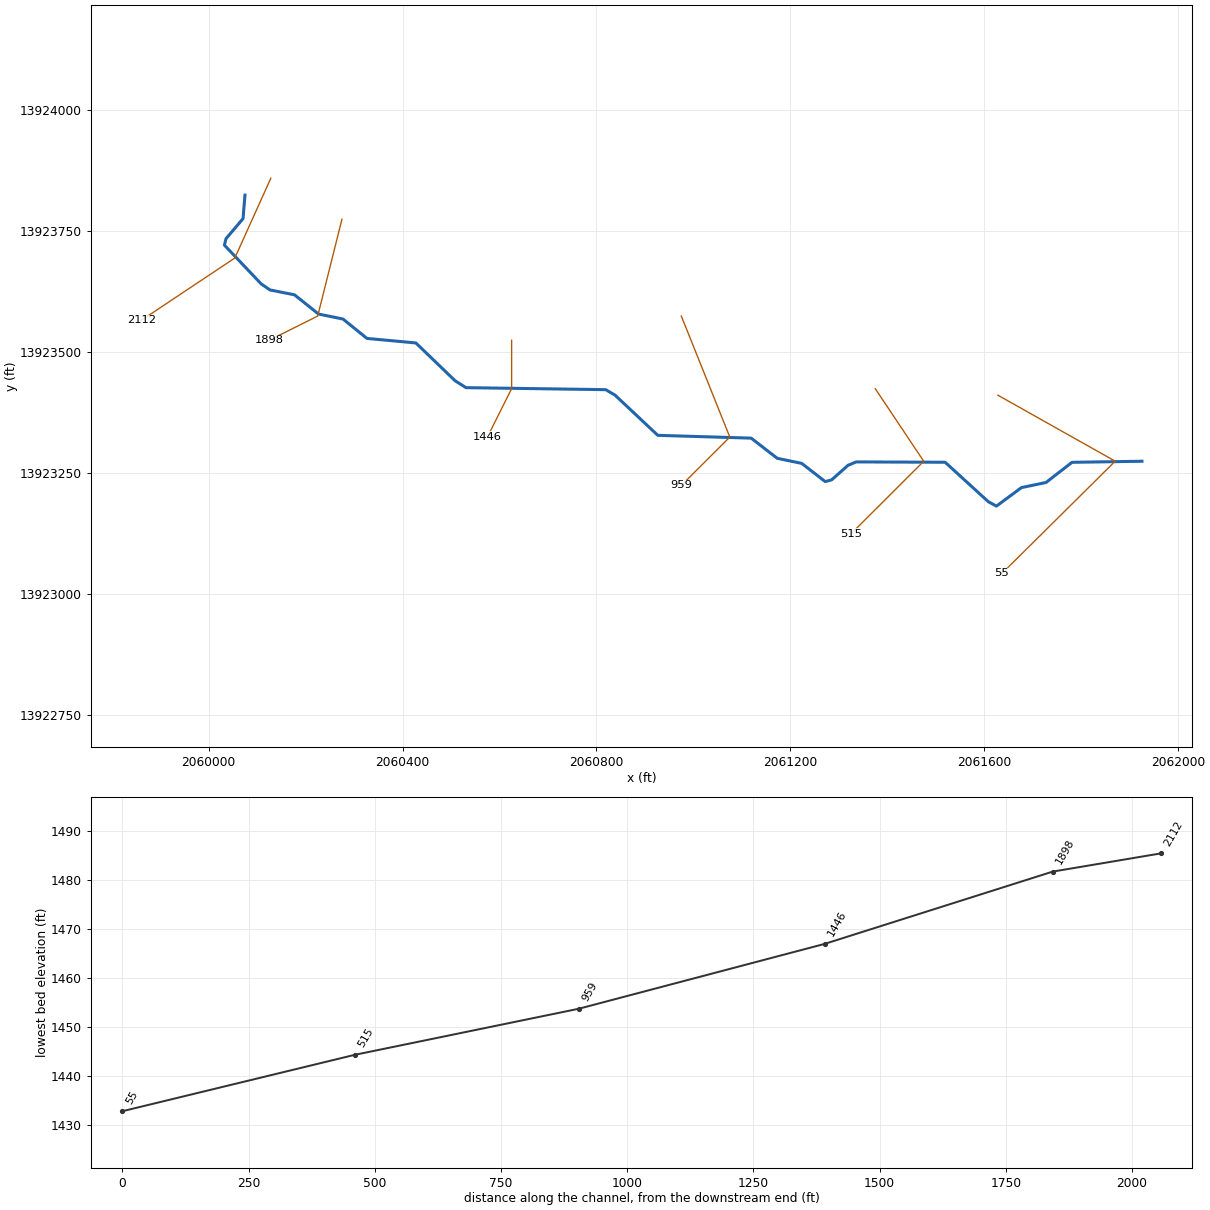
--- Stream0268_DS.prj (project) ---

Proj Title=Stream0268_DS Base Level Engineering
Current Plan=p01
Default Exp/Contr=0.3,0.1
English Units
Geom File=g01
Flow File=f01
Plan File=p01
BEGIN DESCRIPTION:
Stream0268_DS
END DESCRIPTION:

--- Stream0268_DS.p01 (plan) ---

Plan Title=Multiple Run
Short Identifier=Multiple
Geom File=g01
Flow File=f01
Subcritical Flow
K Sum by GR= 0
Std Step Tol= 0.01
Critical Tol= 0.01
Num of Std Step Trials= 20
Max Error Tol= 0.3
Flow Tol Ratio= 0.001
Split Flow NTrial= 30
Split Flow Tol= 0.02
Split Flow Ratio= 0.02
Log Output Level= 0
Friction Slope Method= 1
Unsteady Friction Slope Method= 2
Unsteady Bridges Friction Slope Method= 1
Parabolic Critical Depth
Global Vel Dist=  1 , 1 , 1
Global Log Level= 0
CheckData=True
Encroach Param= -1, 0, 0, 0
BEGIN DESCRIPTION:
Multiple Run
END DESCRIPTION:

--- Stream0268_DS.f01 (steady flow) ---

Flow Title=Multiple
Number of Profiles=7
Profile Names=10-year,25-year,50-year,1pct_min,100-year,1pct_plu,500-year
River Rch & RM= Stream0268_DS,Reach-1,2112
     451     735     997     660    1316    2626    2264
Boundary for River Rch & Prof#=Stream0268_DS,Reach-1,1
Up Type=0
Dn Type=3
Dn Slope=0.005
Boundary for River Rch & Prof#=Stream0268_DS,Reach-1,2
Up Type=0
Dn Type=3
Dn Slope=0.005
Boundary for River Rch & Prof#=Stream0268_DS,Reach-1,3
Up Type=0
Dn Type=3
Dn Slope=0.005
Boundary for River Rch & Prof#=Stream0268_DS,Reach-1,4
Up Type=0
Dn Type=3
Dn Slope=0.005
Boundary for River Rch & Prof#=Stream0268_DS,Reach-1,5
Up Type=0
Dn Type=3
Dn Slope=0.005
Boundary for River Rch & Prof#=Stream0268_DS,Reach-1,6
Up Type=0
Dn Type=3
Dn Slope=0.005
Boundary for River Rch & Prof#=Stream0268_DS,Reach-1,7
Up Type=0
Dn Type=3
Dn Slope=0.005

--- Stream0268_DS.g01 (geometry) ---

Geom Title=Existing Conditions

River Reach=Stream0268_DS,Reach-1
Reach XY= 30
      2060075.00     13923825.00      2060070.98     13923776.36
      2060035.88     13923734.89      2060032.58     13923721.59
      2060108.25     13923641.64      2060126.61     13923628.95
      2060177.18     13923618.90      2060226.72     13923579.16
      2060277.18     13923568.88      2060326.59     13923528.83
      2060427.42     13923519.46      2060508.25     13923441.47
      2060530.86     13923427.07      2060819.14     13923422.93
      2060838.31     13923411.60      2060926.47     13923328.55
      2061119.07     13923322.76      2061172.83     13923281.09
      2061223.36     13923270.58      2061271.68     13923233.04
      2061284.90     13923236.46      2061318.81     13923266.54
      2061335.44     13923273.62      2061519.15     13923272.93
      2061608.31     13923191.32      2061624.92     13923182.30
      2061676.63     13923220.57      2061727.17     13923231.09
      2061780.91     13923272.80      2061925.00     13923275.00

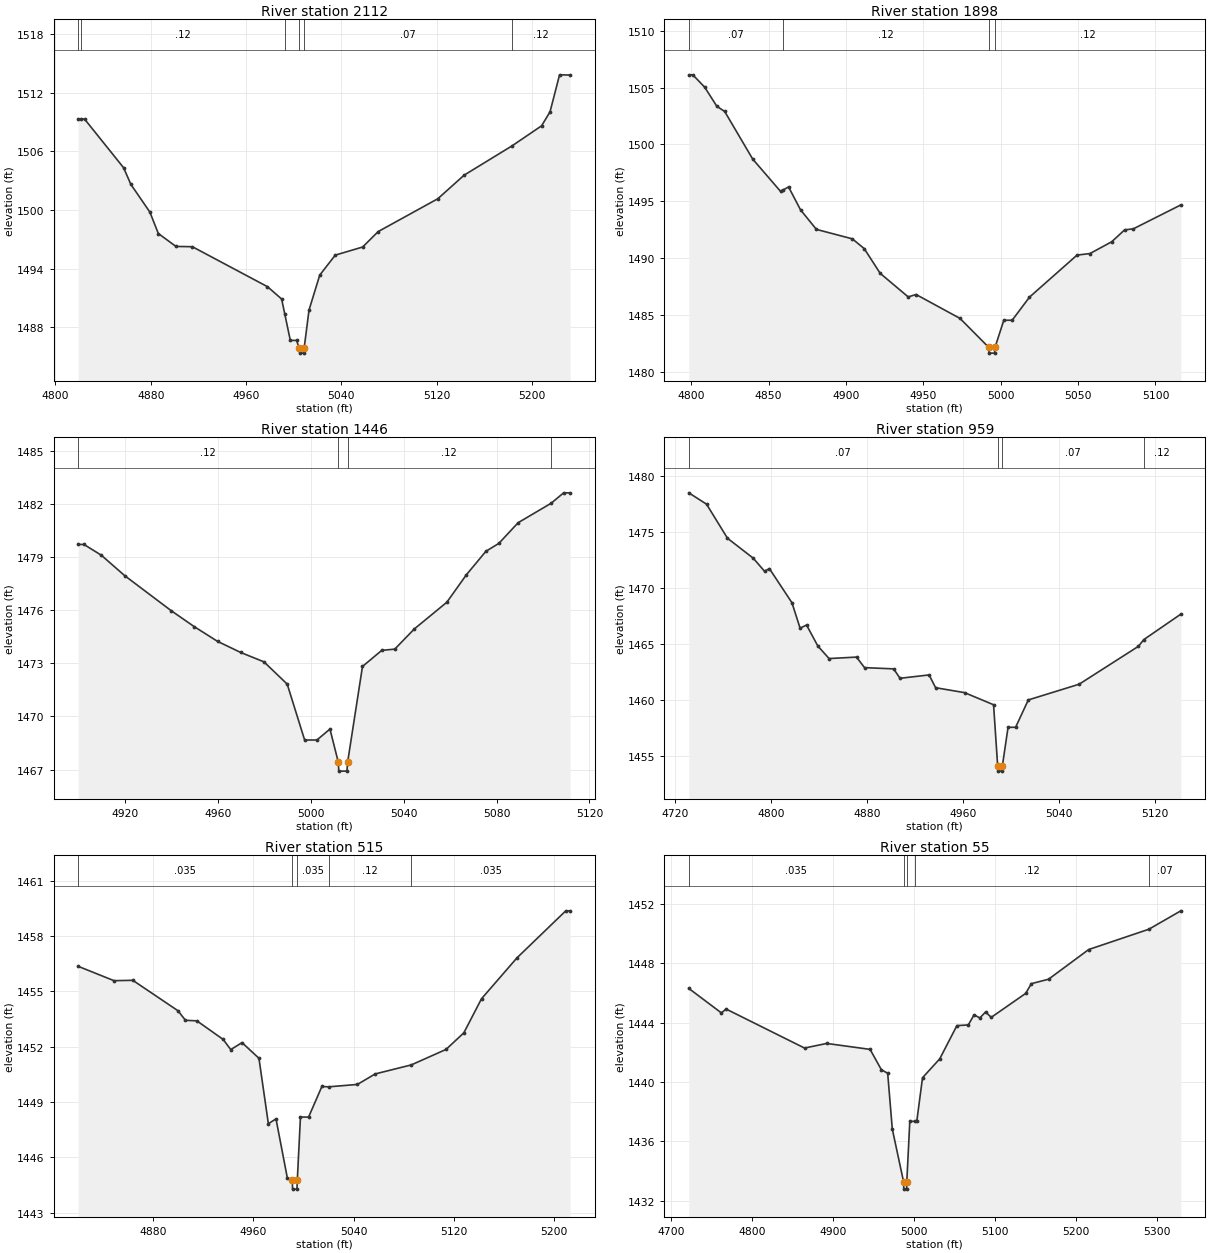
Type RM Length L Ch R = 1,2112,214,214,214
BEGIN DESCRIPTION:
Stream0268_DS 5.0
END DESCRIPTION:
XS GIS Cut Line= 3
      2060128.34     13923859.84      2060054.03     13923694.91
      2059860.95     13923566.11
#Sta/Elev= 30
  4819.1 1509.29  4821.2 1509.29  4824.5 1509.29  4857.3 1504.31  4863.3 1502.63
  4879.3 1499.79  4886.4 1497.60  4901.2 1496.28  4915.0 1496.25  4978.0 1492.17
  4989.9 1490.91  4992.6 1489.35  4997.2 1486.68  5002.4 1486.68  5004.8 1485.88
  5005.1 1485.38  5008.6 1485.38  5008.8 1485.88  5012.9 1489.78  5021.9 1493.35
  5034.9 1495.39  5057.9 1496.22  5071.0 1497.80  5121.0 1501.15  5143.1 1503.56
  5183.4 1506.56  5208.1 1508.60  5215.2 1510.03  5223.2 1513.81  5232.1 1513.79
#Mann=6,-1,0
  4819.1    0.07       0  4821.2    0.12       0  4992.6    0.07       0
  5004.8    0.05       0  5008.8    0.07       0  5183.4    0.12       0
Bank Sta=5004.8,5008.8
Exp/Cntr=0.3,0.1

Type RM Length L Ch R = 1,1898,452,452,452
BEGIN DESCRIPTION:
Stream0268_DS 4.0
END DESCRIPTION:
XS GIS Cut Line= 3
      2060275.01     13923775.04      2060225.00     13923575.00
      2060125.00     13923525.00
#Sta/Elev= 30
  4798.4 1506.12  4801.0 1506.12  4808.7 1505.03  4816.5 1503.36  4821.6 1502.90
  4839.7 1498.72  4857.7 1495.88  4859.4 1496.01  4862.9 1496.27  4870.6 1494.26
  4880.9 1492.54  4904.1 1491.71  4911.8 1490.85  4922.1 1488.68  4940.2 1486.61
  4945.3 1486.82  4973.7 1484.72  4992.3 1482.17  4992.5 1481.67  4996.0 1481.67
  4996.3 1482.17  5002.0 1484.56  5007.4 1484.56  5018.6 1486.59  5049.3 1490.28
  5057.7 1490.42  5071.7 1491.45  5080.1 1492.50  5085.7 1492.59  5116.4 1494.69
#Mann=4,-1,0
  4798.4    0.07       0  4859.4    0.12       0  4992.3    0.05       0
  4996.3    0.12       0
Bank Sta=4992.3,4996.3
Exp/Cntr=0.3,0.1

Type RM Length L Ch R = 1,1446,487,487,487
BEGIN DESCRIPTION:
Stream0268_DS 3.0
END DESCRIPTION:
XS GIS Cut Line= 3
      2060625.00     13923525.00      2060625.00     13923425.00
      2060575.00     13923325.00
#Sta/Elev= 29
  4899.9 1479.73  4902.4 1479.73  4909.9 1479.12  4919.9 1477.97  4939.9 1475.99
  4949.9 1475.08  4959.9 1474.25  4969.9 1473.62  4979.9 1473.09  4989.9 1471.83
  4997.4 1468.67  5002.7 1468.67  5008.3 1469.29  5011.9 1467.41  5012.1 1466.91
  5015.6 1466.91  5015.9 1467.41  5022.3 1472.83  5030.6 1473.74  5036.2 1473.81
  5044.6 1474.95  5058.6 1476.46  5067.0 1478.01  5075.4 1479.34  5081.0 1479.79
  5089.3 1480.96  5103.5 1482.06  5108.9 1482.65  5111.7 1482.65
#Mann=4,-1,0
  4899.9    0.12       0  5011.9    0.05       0  5015.9    0.12       0
  5103.5    0.07       0
Bank Sta=5011.9,5015.9
Exp/Cntr=0.3,0.1

Type RM Length L Ch R = 1,959,444,444,444
BEGIN DESCRIPTION:
Stream0268_DS 2.0
END DESCRIPTION:
XS GIS Cut Line= 3
      2060975.01     13923574.97      2061075.00     13923325.00
      2060974.97     13923224.97
#Sta/Elev= 30
  4731.2 1478.50  4746.0 1477.49  4763.5 1474.45  4785.0 1472.67  4794.4 1471.51
  4798.5 1471.74  4817.3 1468.70  4824.1 1466.43  4829.5 1466.71  4838.9 1464.84
  4848.3 1463.72  4871.2 1463.85  4877.9 1462.91  4902.2 1462.80  4907.5 1461.96
  4931.8 1462.26  4937.2 1461.12  4961.4 1460.68  4985.6 1459.60  4989.0 1454.18
  4989.3 1453.68  4992.8 1453.68  4993.0 1454.18  4997.7 1457.59  5004.0 1457.59
  5014.6 1460.03  5057.0 1461.43  5106.5 1464.81  5111.0 1465.41  5141.9 1467.68
#Mann=4,-1,0
  4731.2    0.07       0  4989.0    0.05       0  4993.0    0.07       0
  5111.0    0.12       0
Bank Sta=4989,4993
Exp/Cntr=0.3,0.1

Type RM Length L Ch R = 1,515,460,460,460
BEGIN DESCRIPTION:
Stream0268_DS 1.0
END DESCRIPTION:
XS GIS Cut Line= 3
      2061375.00     13923425.01      2061475.00     13923275.00
      2061325.01     13923125.01
#Sta/Elev= 30
  4820.2 1456.36  4848.8 1455.58  4863.8 1455.60  4899.8 1453.95  4905.8 1453.43
  4914.9 1453.40  4935.9 1452.39  4941.9 1451.84  4950.9 1452.22  4964.4 1451.37
  4971.9 1447.82  4978.0 1448.08  4987.0 1444.89  4991.0 1444.77  4991.2 1444.27
  4994.7 1444.27  4995.0 1444.77  4997.5 1448.18  5004.0 1448.18  5014.6 1449.84
  5019.9 1449.82  5042.9 1449.95  5057.1 1450.52  5085.9 1451.01  5113.6 1451.85
  5127.8 1452.75  5141.9 1454.60  5170.2 1456.82  5209.1 1459.37  5212.6 1459.37
#Mann=5,-1,0
  4820.2   0.035       0  4991.0   0.035       0  4995.0   0.035       0
  5019.9    0.12       0  5085.9   0.035       0
Bank Sta=4991,4995
Exp/Cntr=0.3,0.1

Type RM Length L Ch R = 1,55,0,0,0
BEGIN DESCRIPTION:
Stream0268_DS 0.0
END DESCRIPTION:
XS GIS Cut Line= 3
      2061628.00     13923411.45      2061869.94     13923275.14
      2061636.17     13923043.07
#Sta/Elev= 30
  4722.3 1446.30  4762.5 1444.65  4768.3 1444.91  4865.1 1442.28  4892.5 1442.59
  4946.0 1442.19  4959.9 1440.82  4967.7 1440.58  4973.4 1436.82  4987.3 1433.27
  4987.6 1432.77  4991.1 1432.77  4991.3 1433.27  4995.0 1437.34  5001.8 1437.34
  5003.6 1437.34  5010.7 1440.28  5031.9 1441.55  5053.1 1443.79  5067.2 1443.84
  5074.3 1444.52  5081.4 1444.31  5088.5 1444.71  5095.5 1444.35  5137.9 1445.96
  5145.0 1446.62  5166.2 1446.92  5215.7 1448.92  5290.0 1450.29  5329.4 1451.53
#Mann=5,-1,0
  4722.3   0.035       0  4987.3   0.035       0  4991.3   0.035       0
  5001.8    0.12       0  5290.0    0.07       0
Bank Sta=4987.3,4991.3
Exp/Cntr=0.3,0.1

Chan Stop Cuts=-1