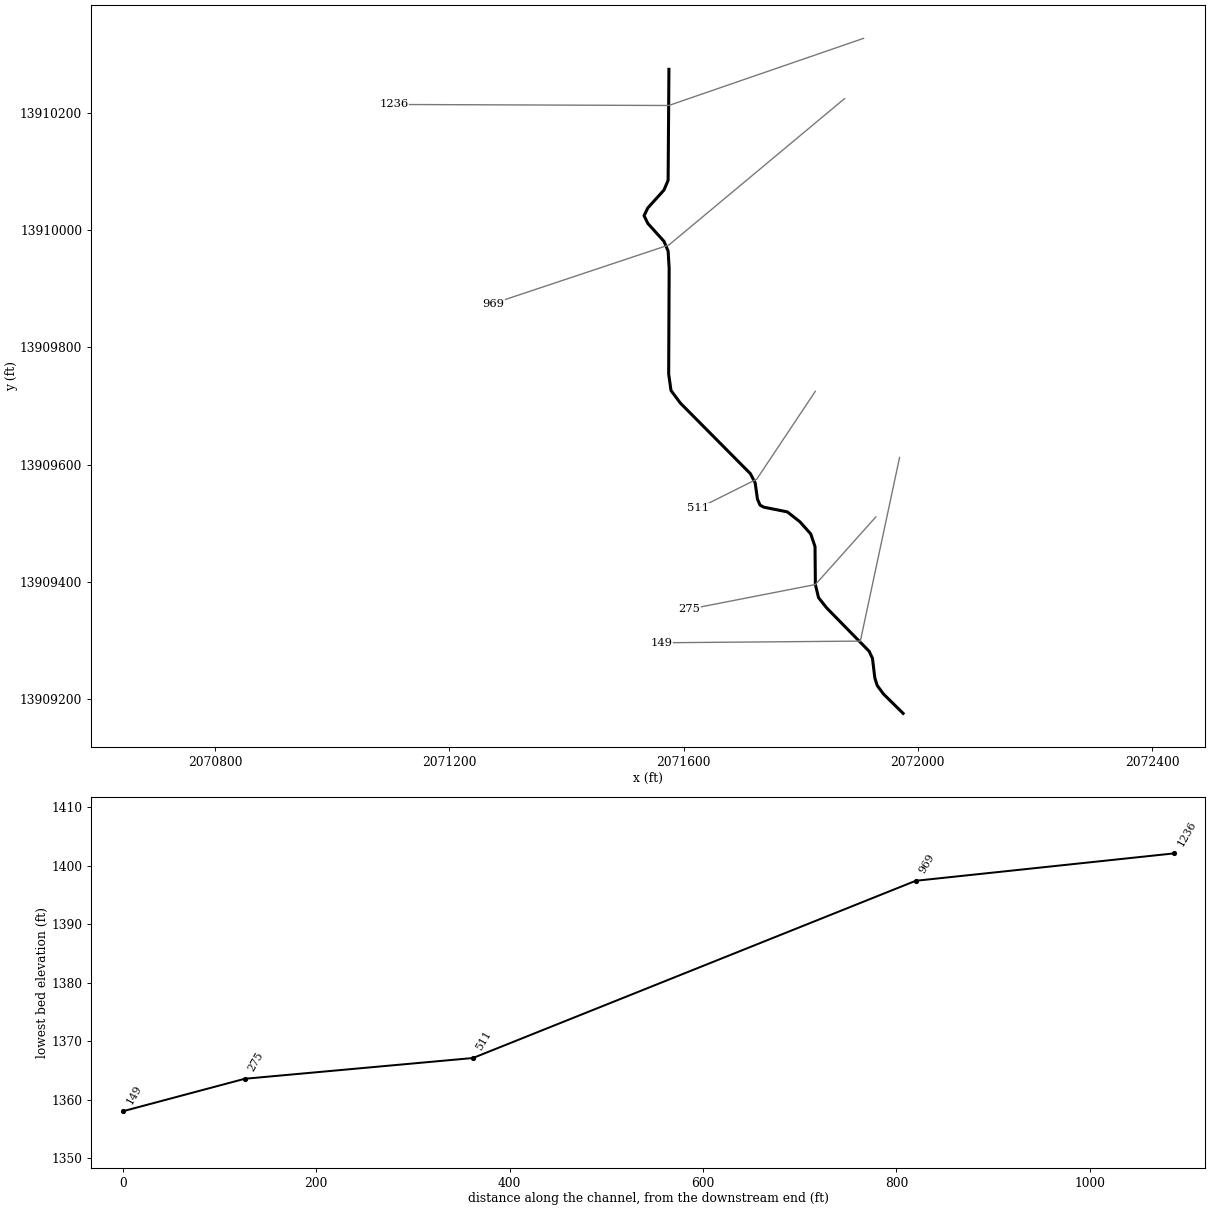
--- Stream0269_DS.prj (project) ---

Proj Title=Stream0269_DS Base Level Engineering
Current Plan=p01
Default Exp/Contr=0.3,0.1
English Units
Geom File=g01
Flow File=f01
Plan File=p01
BEGIN DESCRIPTION:
Stream0269_DS
END DESCRIPTION:

--- Stream0269_DS.p01 (plan) ---

Plan Title=Multiple Run
Short Identifier=Multiple
Geom File=g01
Flow File=f01
Subcritical Flow
K Sum by GR= 0
Std Step Tol= 0.01
Critical Tol= 0.01
Num of Std Step Trials= 20
Max Error Tol= 0.3
Flow Tol Ratio= 0.001
Split Flow NTrial= 30
Split Flow Tol= 0.02
Split Flow Ratio= 0.02
Log Output Level= 0
Friction Slope Method= 1
Unsteady Friction Slope Method= 2
Unsteady Bridges Friction Slope Method= 1
Parabolic Critical Depth
Global Vel Dist=  1 , 1 , 1
Global Log Level= 0
CheckData=True
Encroach Param= -1, 0, 0, 0
BEGIN DESCRIPTION:
Multiple Run
END DESCRIPTION:

--- Stream0269_DS.f01 (steady flow) ---

Flow Title=Multiple
Number of Profiles=7
Profile Names=10-year,25-year,50-year,1pct_min,100-year,1pct_plu,500-year
River Rch & RM= Stream0269_DS,Reach-1,1236
     396     629     838     544    1086    2167    1797
Boundary for River Rch & Prof#=Stream0269_DS,Reach-1,1
Up Type=0
Dn Type=3
Dn Slope=0.005
Boundary for River Rch & Prof#=Stream0269_DS,Reach-1,2
Up Type=0
Dn Type=3
Dn Slope=0.005
Boundary for River Rch & Prof#=Stream0269_DS,Reach-1,3
Up Type=0
Dn Type=3
Dn Slope=0.005
Boundary for River Rch & Prof#=Stream0269_DS,Reach-1,4
Up Type=0
Dn Type=3
Dn Slope=0.005
Boundary for River Rch & Prof#=Stream0269_DS,Reach-1,5
Up Type=0
Dn Type=3
Dn Slope=0.005
Boundary for River Rch & Prof#=Stream0269_DS,Reach-1,6
Up Type=0
Dn Type=3
Dn Slope=0.005
Boundary for River Rch & Prof#=Stream0269_DS,Reach-1,7
Up Type=0
Dn Type=3
Dn Slope=0.005

--- Stream0269_DS.g01 (geometry) ---

Geom Title=Existing Conditions

River Reach=Stream0269_DS,Reach-1
Reach XY= 30
      2071575.00     13910275.00      2071573.63     13910085.43
      2071566.55     13910068.81      2071538.95     13910038.21
      2071532.56     13910025.00      2071538.95     13910011.79
      2071566.55     13909981.19      2071573.62     13909964.56
      2071575.40     13909935.21      2071574.57     13909754.82
      2071578.54     13909726.46      2071594.61     13909704.84
      2071714.11     13909584.42      2071722.31     13909568.57
      2071726.17     13909541.04      2071730.65     13909530.64
      2071737.08     13909527.15      2071777.24     13909519.12
      2071798.81     13909502.13      2071817.21     13909481.44
      2071824.51     13909459.90      2071825.14     13909395.06
      2071830.54     13909372.58      2071844.67     13909354.86
      2071916.93     13909281.08      2071922.65     13909269.03
      2071926.65     13909235.68      2071930.70     13909222.65
      2071941.42     13909208.08      2071975.00     13909175.00

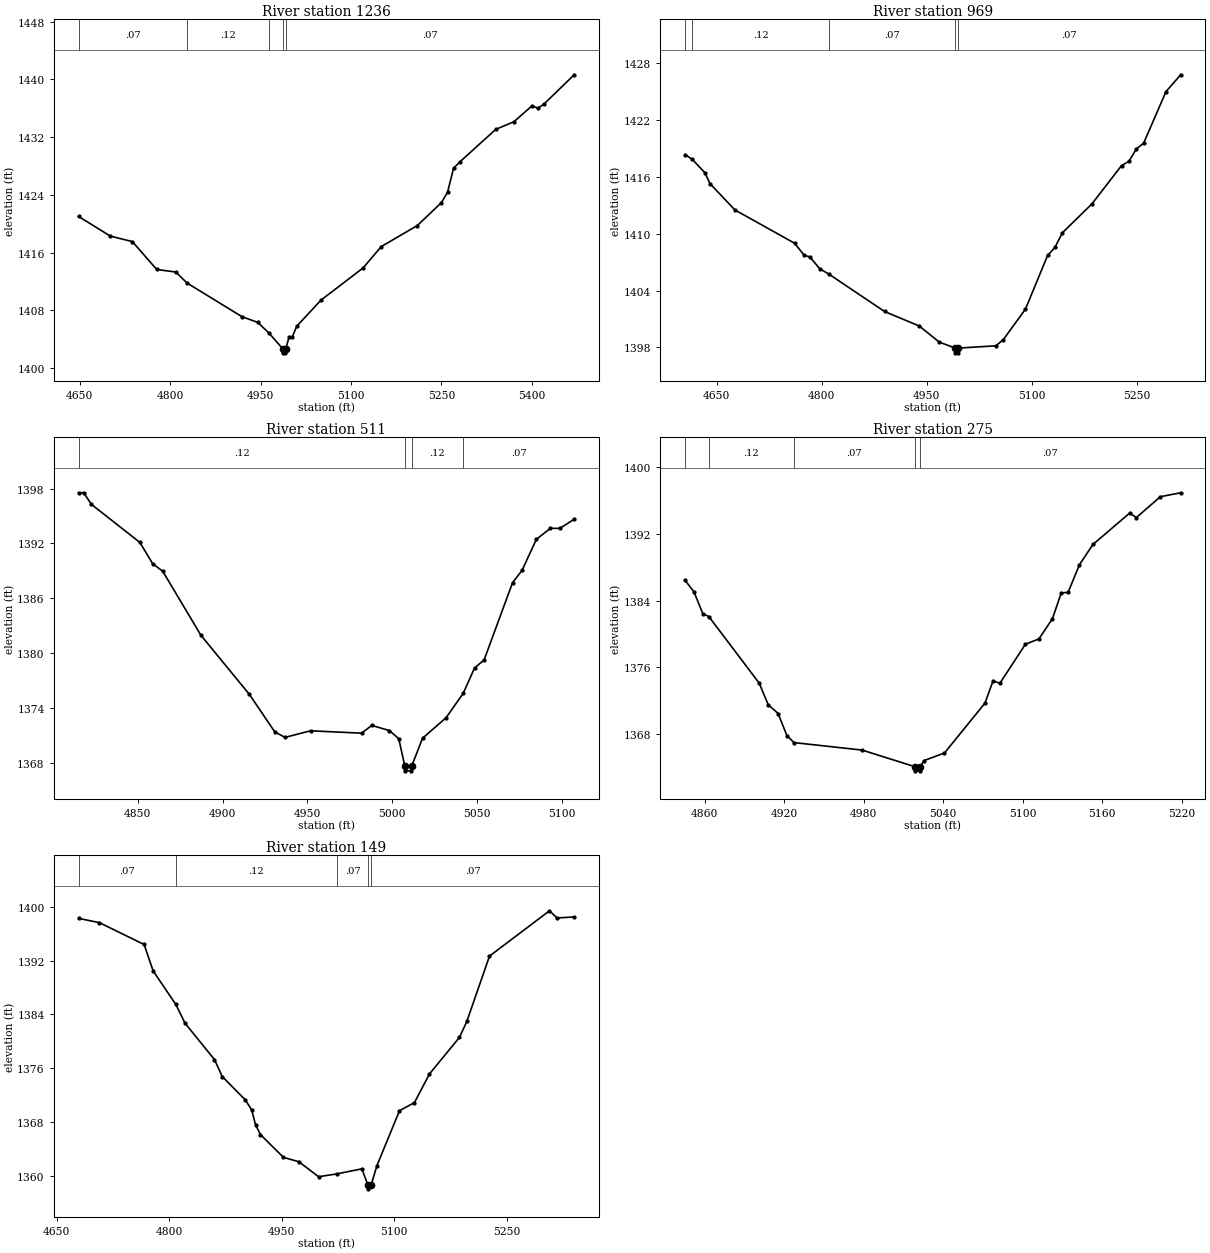
Type RM Length L Ch R = 1,1236,267,267,267
BEGIN DESCRIPTION:
Stream0269_DS 3.0
END DESCRIPTION:
XS GIS Cut Line= 3
      2071907.44     13910327.90      2071574.68     13910213.19
      2071104.96     13910214.96
#Sta/Elev= 30
  4648.4 1421.00  4701.0 1418.28  4737.5 1417.52  4777.9 1413.66  4809.6 1413.30
  4828.2 1411.78  4919.4 1407.11  4945.3 1406.33  4963.8 1404.87  4987.5 1402.61
  4987.7 1402.11  4991.2 1402.11  4991.5 1402.61  4997.6 1404.33  5002.7 1404.33
  5010.1 1405.80  5050.1 1409.40  5120.1 1413.87  5150.1 1416.82  5210.1 1419.75
  5250.1 1422.93  5260.1 1424.35  5270.1 1427.67  5280.1 1428.53  5340.1 1433.07
  5370.1 1434.12  5400.1 1436.32  5410.1 1436.00  5420.1 1436.58  5470.1 1440.63
#Mann=5,-1,0
  4648.4    0.07       0  4828.2    0.12       0  4963.8    0.07       0
  4987.5    0.05       0  4991.5    0.07       0
Bank Sta=4987.5,4991.5
Exp/Cntr=0.3,0.1

Type RM Length L Ch R = 1,969,458,458,458
BEGIN DESCRIPTION:
Stream0269_DS 2.0
END DESCRIPTION:
XS GIS Cut Line= 3
      2071875.00     13910225.00      2071575.00     13909975.00
      2071275.03     13909875.01
#Sta/Elev= 30
  4605.2 1418.33  4615.7 1417.81  4633.2 1416.43  4641.0 1415.24  4676.1 1412.50
  4761.4 1408.98  4775.1 1407.71  4782.9 1407.55  4797.2 1406.30  4810.2 1405.73
  4889.6 1401.79  4939.1 1400.26  4967.7 1398.56  4990.5 1397.93  4990.7 1397.43
  4994.2 1397.43  4994.5 1397.93  5048.4 1398.17  5059.0 1398.82  5090.6 1402.04
  5122.2 1407.70  5132.7 1408.55  5143.3 1410.09  5185.4 1413.13  5227.6 1417.17
  5238.1 1417.61  5248.7 1418.91  5259.2 1419.54  5290.9 1424.95  5311.9 1426.74
#Mann=5,-1,0
  4605.2    0.07       0  4615.7    0.12       0  4810.2    0.07       0
  4990.5    0.05       0  4994.5    0.07       0
Bank Sta=4990.5,4994.5
Exp/Cntr=0.3,0.1

Type RM Length L Ch R = 1,511,236,236,236
BEGIN DESCRIPTION:
Stream0269_DS 1.0
END DESCRIPTION:
XS GIS Cut Line= 3
      2071825.02     13909725.03      2071725.00     13909575.00
      2071625.01     13909525.00
#Sta/Elev= 30
  4815.1 1397.54  4818.1 1397.54  4822.6 1396.28  4851.2 1392.11  4858.7 1389.80
  4864.7 1388.95  4887.2 1381.95  4915.8 1375.48  4930.8 1371.37  4936.8 1370.79
  4951.8 1371.51  4981.9 1371.25  4987.9 1372.10  4998.2 1371.54  5003.8 1370.65
  5007.4 1367.63  5007.6 1367.13  5011.1 1367.13  5011.4 1367.63  5017.8 1370.69
  5031.7 1372.94  5041.8 1375.61  5048.5 1378.39  5054.1 1379.25  5070.9 1387.72
  5076.5 1389.06  5084.9 1392.45  5093.2 1393.65  5098.8 1393.65  5107.2 1394.65
#Mann=4,-1,0
  4815.1    0.12       0  5007.4    0.05       0  5011.4    0.12       0
  5041.8    0.07       0
Bank Sta=5007.4,5011.4
Exp/Cntr=0.3,0.1

Type RM Length L Ch R = 1,275,126,126,126
BEGIN DESCRIPTION:
Stream0269_DS 0.01
END DESCRIPTION:
XS GIS Cut Line= 3
      2071928.39     13909510.53      2071825.14     13909395.06
      2071610.01     13909353.04
#Sta/Elev= 30
  4845.1 1386.44  4851.8 1385.06  4858.5 1382.44  4863.0 1382.10  4901.1 1374.09
  4907.8 1371.53  4915.3 1370.46  4922.0 1367.80  4927.3 1366.97  4978.8 1366.07
  5018.5 1364.08  5018.8 1363.58  5022.3 1363.58  5022.5 1364.08  5025.6 1364.82
  5040.9 1365.72  5071.5 1371.71  5077.6 1374.39  5082.7 1374.08  5102.0 1378.77
  5112.2 1379.41  5122.4 1381.83  5129.1 1384.94  5134.2 1384.99  5142.8 1388.31
  5153.0 1390.75  5180.7 1394.51  5185.8 1393.98  5203.9 1396.48  5219.2 1396.95
#Mann=5,-1,0
  4845.1    0.07       0  4863.0    0.12       0  4927.3    0.07       0
  5018.5    0.05       0  5022.5    0.07       0
Bank Sta=5018.5,5022.5
Exp/Cntr=0.3,0.1

Type RM Length L Ch R = 1,149,0,0,0
BEGIN DESCRIPTION:
Stream0269_DS 0.0
END DESCRIPTION:
XS GIS Cut Line= 3
      2071968.92     13909612.08      2071901.95     13909298.45
      2071562.06     13909295.58
#Sta/Elev= 30
  4679.3 1398.31  4707.0 1397.67  4766.6 1394.42  4778.6 1390.49  4808.8 1385.50
  4821.2 1382.69  4860.4 1377.28  4870.7 1374.76  4901.3 1371.30  4910.0 1369.79
  4915.1 1367.58  4921.7 1366.11  4952.4 1362.71  4972.9 1362.07  4999.2 1359.83
  5023.7 1360.26  5057.0 1361.01  5065.0 1358.53  5065.2 1358.03  5069.0 1358.53
  5077.0 1361.49  5107.0 1369.66  5127.0 1370.88  5147.0 1375.14  5187.0 1380.59
  5197.0 1383.02  5227.0 1392.69  5307.0 1399.44  5317.0 1398.37  5339.9 1398.52
#Mann=5,-1,0
  4679.3    0.07       0  4808.8    0.12       0  5023.7    0.07       0
  5065.0    0.05       0  5069.0    0.07       0
Bank Sta=5065,5069
Exp/Cntr=0.3,0.1

Chan Stop Cuts=-1