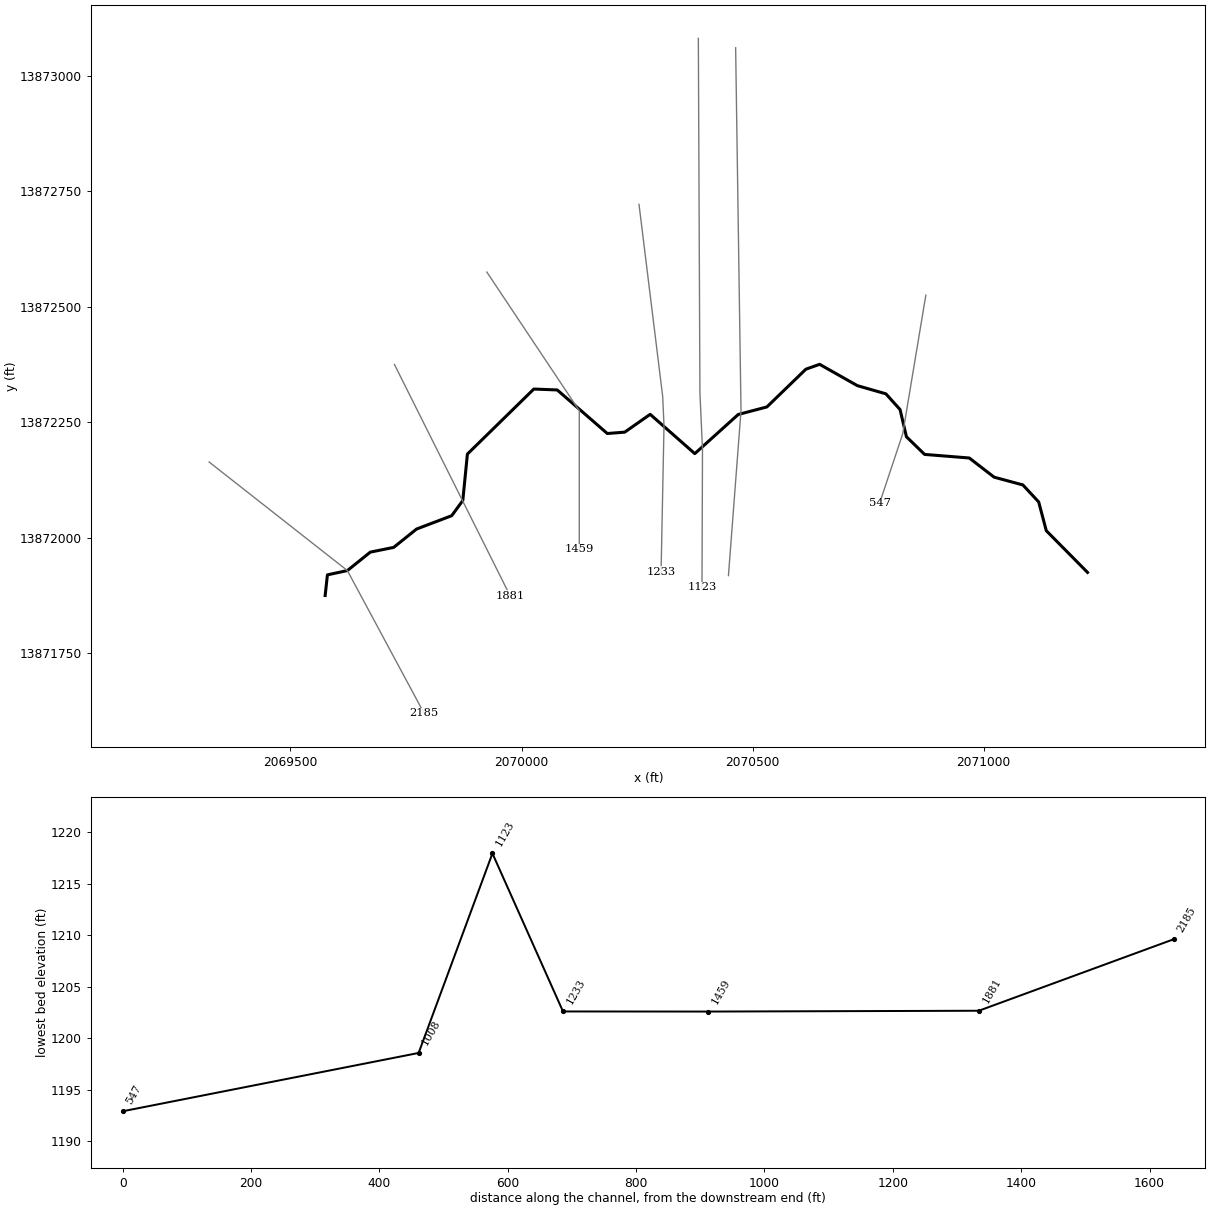
--- Stream0271_DS.prj (project) ---

Proj Title=Stream0271_DS Base Level Engineering
Current Plan=p01
Default Exp/Contr=0.3,0.1
English Units
Geom File=g01
Flow File=f01
Plan File=p01
BEGIN DESCRIPTION:
Stream0271_DS
END DESCRIPTION:

--- Stream0271_DS.p01 (plan) ---

Plan Title=Multiple Run
Short Identifier=Multiple
Geom File=g01
Flow File=f01
Subcritical Flow
K Sum by GR= 0
Std Step Tol= 0.01
Critical Tol= 0.01
Num of Std Step Trials= 20
Max Error Tol= 0.3
Flow Tol Ratio= 0.001
Split Flow NTrial= 30
Split Flow Tol= 0.02
Split Flow Ratio= 0.02
Log Output Level= 0
Friction Slope Method= 1
Unsteady Friction Slope Method= 2
Unsteady Bridges Friction Slope Method= 1
Parabolic Critical Depth
Global Vel Dist=  1 , 1 , 1
Global Log Level= 0
CheckData=True
Encroach Param= -1, 0, 0, 0
BEGIN DESCRIPTION:
Multiple Run
END DESCRIPTION:

--- Stream0271_DS.f01 (steady flow) ---

Flow Title=Multiple
Number of Profiles=7
Profile Names=10-year,25-year,50-year,1pct_min,100-year,1pct_plu,500-year
River Rch & RM= Stream0271_DS,Reach-1,2185
     910    1513    2076    1383    2759    5504    4811
Boundary for River Rch & Prof#=Stream0271_DS,Reach-1,1
Up Type=0
Dn Type=3
Dn Slope=0.005
Boundary for River Rch & Prof#=Stream0271_DS,Reach-1,2
Up Type=0
Dn Type=3
Dn Slope=0.005
Boundary for River Rch & Prof#=Stream0271_DS,Reach-1,3
Up Type=0
Dn Type=3
Dn Slope=0.005
Boundary for River Rch & Prof#=Stream0271_DS,Reach-1,4
Up Type=0
Dn Type=3
Dn Slope=0.005
Boundary for River Rch & Prof#=Stream0271_DS,Reach-1,5
Up Type=0
Dn Type=3
Dn Slope=0.005
Boundary for River Rch & Prof#=Stream0271_DS,Reach-1,6
Up Type=0
Dn Type=3
Dn Slope=0.005
Boundary for River Rch & Prof#=Stream0271_DS,Reach-1,7
Up Type=0
Dn Type=3
Dn Slope=0.005

--- Stream0271_DS.g01 (geometry) ---

Geom Title=Existing Conditions

River Reach=Stream0271_DS,Reach-1
Reach XY= 30
      2069575.00     13871875.00      2069579.90     13871919.72
      2069623.09     13871929.04      2069672.77     13871968.95
      2069723.28     13871979.16      2069772.84     13872018.89
      2069848.95     13872047.81      2069872.92     13872080.71
      2069882.86     13872181.17      2070026.65     13872321.90
      2070077.28     13872319.92      2070185.64     13872225.65
      2070223.35     13872228.59      2070278.41     13872267.15
      2070375.00     13872182.11      2070468.95     13872266.80
      2070531.04     13872283.18      2070615.33     13872364.79
      2070645.13     13872375.40      2070726.76     13872329.26
      2070788.56     13872311.53      2070819.24     13872277.51
      2070833.03     13872218.64      2070872.33     13872180.42
      2070969.03     13872172.67      2071022.85     13872131.15
      2071085.00     13872114.37      2071119.26     13872077.54
      2071135.72     13872015.31      2071225.00     13871925.00

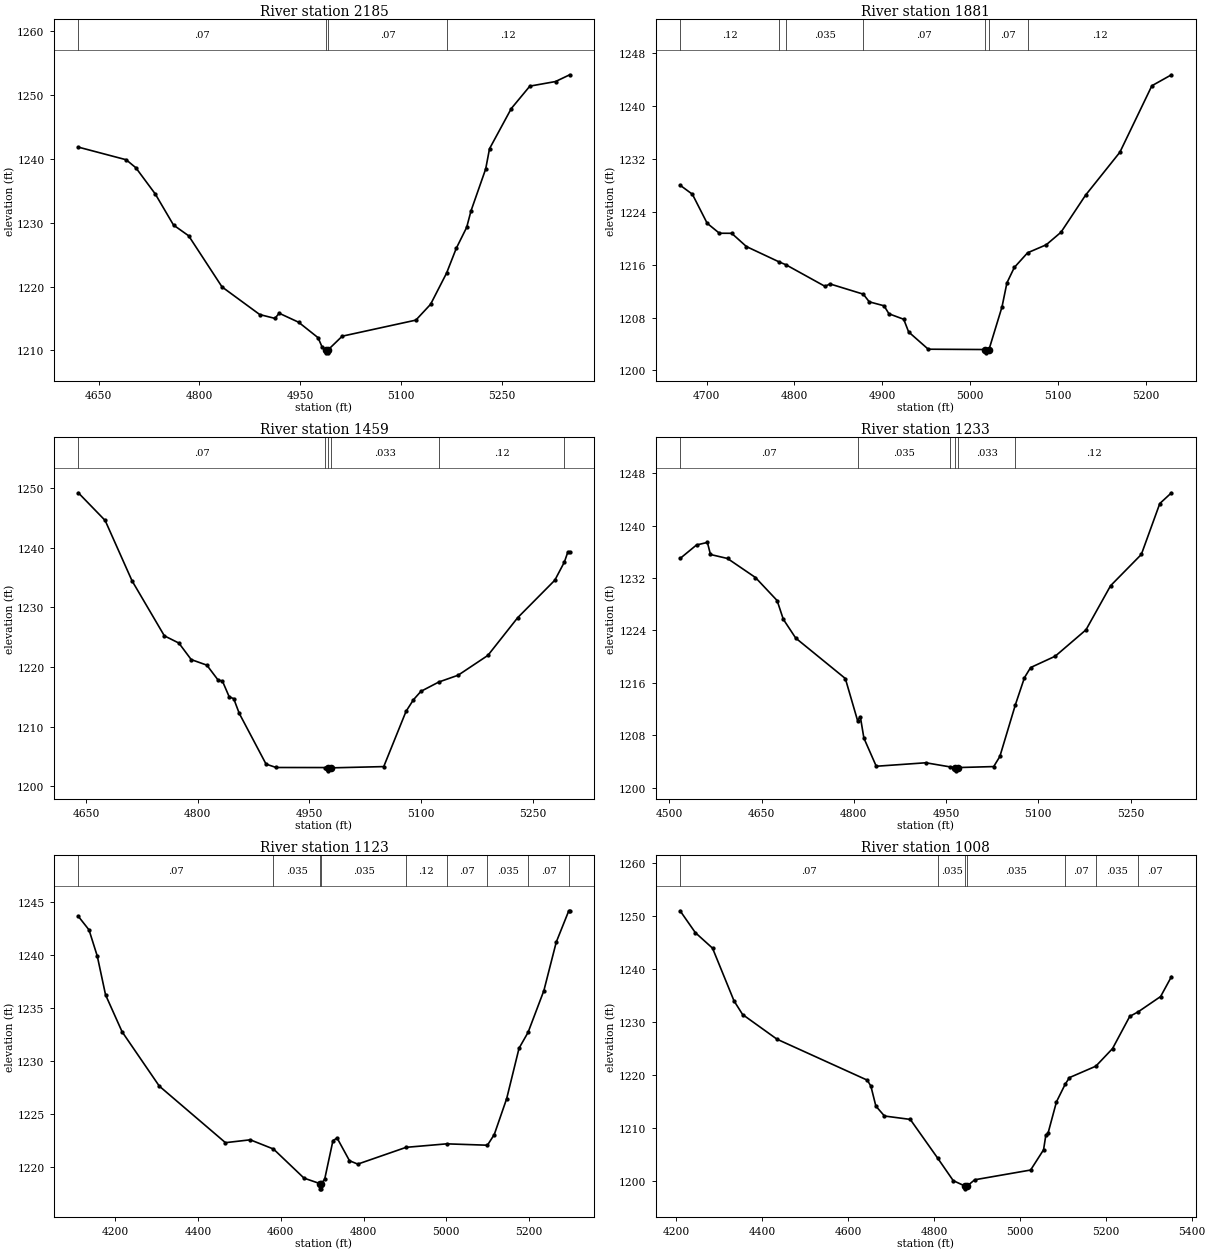
Type RM Length L Ch R = 1,2185,304,304,304
BEGIN DESCRIPTION:
Stream0271_DS 5.0
END DESCRIPTION:
XS GIS Cut Line= 3
      2069323.97     13872163.89      2069623.09     13871929.04
      2069789.22     13871619.96
#Sta/Elev= 30
  4619.7 1241.87  4690.9 1239.89  4705.3 1238.64  4734.2 1234.53  4761.4 1229.65
  4783.9 1227.97  4833.6 1219.95  4889.7 1215.62  4912.3 1215.02  4918.6 1215.83
  4947.5 1214.42  4976.4 1212.00  4982.8 1210.46  4987.7 1210.12  4988.0 1209.62
  4991.5 1209.62  4991.7 1210.12  5012.4 1212.23  5122.0 1214.75  5143.9 1217.23
  5167.7 1222.12  5182.1 1226.00  5197.6 1229.29  5204.0 1231.86  5225.9 1238.45
  5231.6 1241.62  5264.0 1247.92  5291.6 1251.43  5329.8 1252.15  5350.9 1253.21
#Mann=4,-1,0
  4619.7    0.07       0  4987.7    0.05       0  4991.7    0.07       0
  5167.7    0.12       0
Bank Sta=4987.7,4991.7
Exp/Cntr=0.3,0.1

Type RM Length L Ch R = 1,1881,422,422,422
BEGIN DESCRIPTION:
Stream0271_DS 4.0
END DESCRIPTION:
XS GIS Cut Line= 3
      2069724.99     13872375.02      2069875.00     13872075.00
      2069974.98     13871875.04
#Sta/Elev= 30
  4669.9 1228.04  4683.9 1226.67  4700.7 1222.28  4714.6 1220.77  4728.6 1220.76
  4745.4 1218.75  4782.6 1216.43  4790.3 1216.00  4834.8 1212.73  4840.4 1213.10
  4878.3 1211.55  4885.1 1210.39  4901.9 1209.79  4907.5 1208.58  4924.3 1207.75
  4929.9 1205.83  4952.2 1203.22  5017.3 1203.17  5017.6 1202.67  5021.3 1203.17
  5036.1 1209.62  5041.7 1213.26  5050.1 1215.59  5065.2 1217.81  5086.4 1219.02
  5103.2 1220.92  5131.1 1226.52  5170.2 1233.03  5206.6 1243.09  5228.9 1244.75
#Mann=7,-1,0
  4669.9    0.12       0  4782.6    0.07       0  4790.3   0.035       0
  4878.3    0.07       0  5017.3    0.05       0  5021.3    0.07       0
  5065.2    0.12       0
Bank Sta=5017.3,5021.3
Exp/Cntr=0.3,0.1

Type RM Length L Ch R = 1,1459,226,226,226
BEGIN DESCRIPTION:
Stream0271_DS 3.0
END DESCRIPTION:
XS GIS Cut Line= 3
      2069924.98     13872575.03      2070125.00     13872275.00
      2070125.00     13871975.00
#Sta/Elev= 30
  4639.4 1249.18  4675.5 1244.54  4711.6 1234.44  4755.1 1225.21  4774.6 1224.00
  4791.2 1221.23  4812.2 1220.30  4827.2 1217.82  4833.2 1217.62  4842.3 1214.98
  4848.3 1214.69  4855.8 1212.21  4891.8 1203.72  4905.3 1203.15  4970.6 1203.14
  4975.5 1203.09  4975.7 1202.59  4979.5 1203.09  5050.0 1203.30  5080.0 1212.56
  5090.0 1214.51  5100.0 1215.91  5124.0 1217.47  5150.0 1218.61  5190.0 1221.93
  5230.0 1228.24  5280.0 1234.53  5292.8 1237.56  5297.5 1239.25  5300.0 1239.25
#Mann=6,-1,0
  4639.4    0.07       0  4970.6   0.033       0  4975.5   0.033       0
  4979.5   0.033       0  5124.0    0.12       0  5292.8    0.07       0
Bank Sta=4975.5,4979.5
Exp/Cntr=0.3,0.1

Type RM Length L Ch R = 1,1233,110,110,110
BEGIN DESCRIPTION:
Stream0271_DS 2.2
END DESCRIPTION:
XS GIS Cut Line= 4
      2070254.26     13872721.54      2070305.52     13872305.67
      2070308.35     13872242.35      2070302.01     13871926.02
#Sta/Elev= 30
  4517.6 1234.98  4544.3 1237.04  4562.0 1237.43  4567.0 1235.59  4594.7 1234.98
  4640.1 1232.08  4675.3 1228.57  4685.4 1225.71  4705.6 1222.84  4786.2 1216.68
  4806.1 1210.27  4810.6 1210.85  4816.4 1207.59  4836.5 1203.30  4917.1 1203.83
  4956.6 1203.20  4965.3 1203.10  4965.6 1202.60  4969.3 1203.10  5027.4 1203.25
  5037.4 1204.79  5062.7 1212.69  5077.4 1216.81  5087.4 1218.35  5127.4 1220.08
  5177.4 1224.10  5217.4 1230.83  5267.4 1235.60  5297.4 1243.36  5316.4 1245.00
#Mann=6,-1,0
  4517.6    0.07       0  4806.1   0.035       0  4956.6   0.033       0
  4965.3   0.033       0  4969.3   0.033       0  5062.7    0.12       0
Bank Sta=4965.3,4969.3
Exp/Cntr=0.3,0.1

Type RM Length L Ch R = 1,1123,115,115,115
BEGIN DESCRIPTION:
Stream0271_DS 2.1
END DESCRIPTION:
XS GIS Cut Line= 4
      2070382.68     13873080.90      2070386.09     13872313.83
      2070391.65     13872191.23      2070390.57     13871892.53
#Sta/Elev= 30
  4110.2 1243.63  4136.1 1242.35  4156.1 1239.88  4176.1 1236.23  4216.1 1232.75
  4306.1 1227.63  4466.1 1222.30  4526.1 1222.57  4582.3 1221.70  4656.1 1218.96
  4694.1 1218.45  4694.4 1217.95  4697.9 1217.95  4698.1 1218.45  4706.1 1218.86
  4726.1 1222.49  4736.1 1222.74  4766.1 1220.60  4786.1 1220.28  4903.0 1221.86
  5001.3 1222.19  5099.7 1222.06  5116.2 1223.06  5146.2 1226.44  5176.2 1231.20
  5198.1 1232.70  5236.2 1236.62  5266.2 1241.20  5296.5 1244.15  5298.7 1244.15
#Mann=9,-1,0
  4110.2    0.07       0  4582.3   0.035       0  4694.1    0.05       0
  4698.1   0.035       0  4903.0    0.12       0  5001.3    0.07       0
  5099.7   0.035       0  5198.1    0.07       0  5296.5   0.035       0
Bank Sta=4694.1,4698.1
Exp/Cntr=0.3,0.1

Type RM Length L Ch R = 1,1008,461,461,461
BEGIN DESCRIPTION:
Stream0271_DS 2.0
END DESCRIPTION:
XS GIS Cut Line= 3
      2070463.38     13873060.53      2070475.00     13872275.00
      2070447.82     13871918.15
#Sta/Elev= 30
  4209.4 1251.07  4244.9 1246.94  4284.9 1244.01  4334.9 1234.06  4354.9 1231.48
  4435.0 1226.82  4645.0 1219.09  4653.4 1217.96  4665.0 1214.19  4685.0 1212.32
  4745.0 1211.68  4809.4 1204.30  4845.0 1200.12  4873.0 1199.07  4873.3 1198.57
  4877.0 1199.07  4895.0 1200.28  5025.1 1202.12  5055.2 1205.94  5060.5 1208.69
  5065.5 1209.03  5085.3 1215.01  5105.3 1218.28  5115.4 1219.57  5176.9 1221.73
  5215.7 1225.05  5255.8 1231.13  5275.8 1232.01  5327.6 1234.88  5352.9 1238.65
#Mann=7,-1,0
  4209.4    0.07       0  4809.4   0.035       0  4873.0   0.035       0
  4877.0   0.035       0  5105.3    0.07       0  5176.9   0.035       0
  5275.8    0.07       0
Bank Sta=4873,4877
Exp/Cntr=0.3,0.1

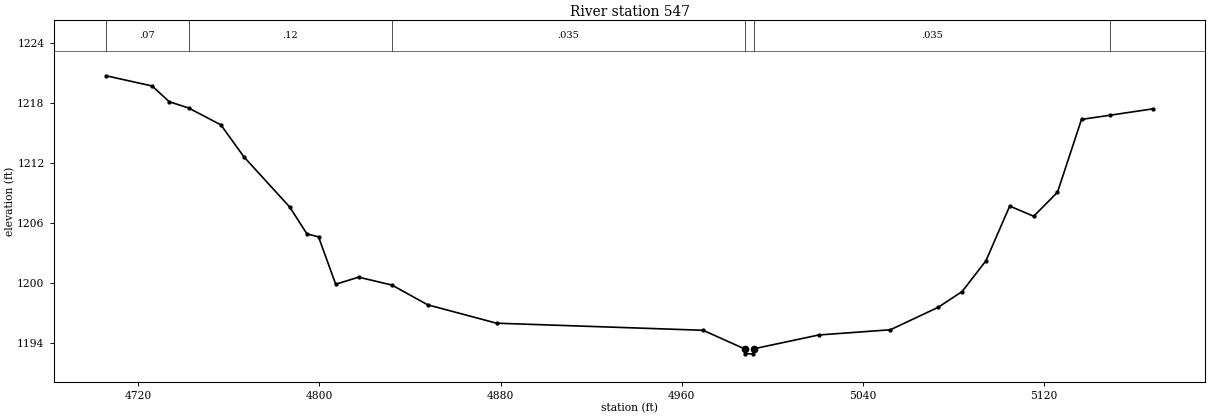
Type RM Length L Ch R = 1,547,0,0,0
BEGIN DESCRIPTION:
Stream0271_DS 1.0
END DESCRIPTION:
XS GIS Cut Line= 3
      2070875.01     13872525.03      2070825.00     13872225.00
      2070775.00     13872074.99
#Sta/Elev= 30
  4705.8 1220.76  4726.1 1219.74  4733.7 1218.16  4742.2 1217.54  4756.5 1215.84
  4766.7 1212.63  4786.9 1207.61  4794.5 1204.92  4799.6 1204.63  4807.2 1199.88
  4817.3 1200.59  4832.0 1199.80  4847.8 1197.82  4878.2 1195.98  4969.4 1195.27
  4987.7 1193.41  4987.9 1192.91  4991.4 1192.91  4991.7 1193.41  5020.5 1194.80
  5052.1 1195.32  5073.2 1197.57  5083.8 1199.15  5094.3 1202.23  5104.8 1207.71
  5115.4 1206.69  5125.9 1209.10  5136.5 1216.39  5149.1 1216.81  5168.1 1217.45
#Mann=6,-1,0
  4705.8    0.07       0  4742.2    0.12       0  4832.0   0.035       0
  4987.7   0.035       0  4991.7   0.035       0  5149.1    0.07       0
Bank Sta=4987.7,4991.7
Exp/Cntr=0.3,0.1

Chan Stop Cuts=-1