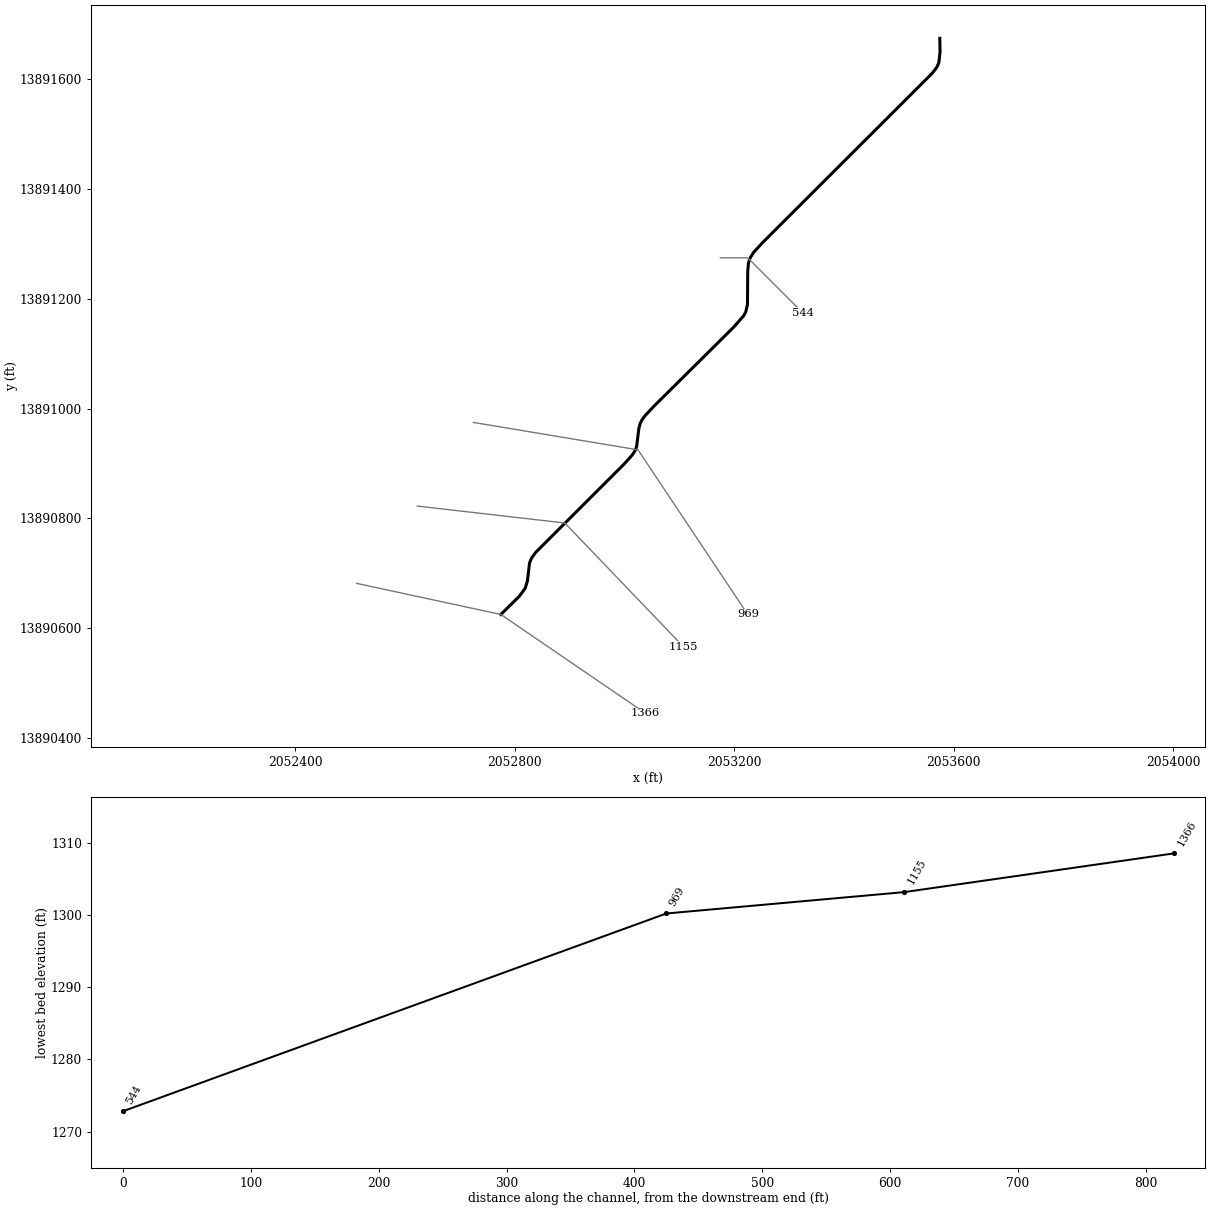
--- Stream0272_DS.prj (project) ---

Proj Title=Stream0272_DS Base Level Engineering
Current Plan=p01
Default Exp/Contr=0.3,0.1
English Units
Geom File=g01
Flow File=f01
Plan File=p01
BEGIN DESCRIPTION:
Stream0272_DS
END DESCRIPTION:

--- Stream0272_DS.p01 (plan) ---

Plan Title=Multiple Run
Short Identifier=Multiple
Geom File=g01
Flow File=f01
Subcritical Flow
K Sum by GR= 0
Std Step Tol= 0.01
Critical Tol= 0.01
Num of Std Step Trials= 20
Max Error Tol= 0.3
Flow Tol Ratio= 0.001
Split Flow NTrial= 30
Split Flow Tol= 0.02
Split Flow Ratio= 0.02
Log Output Level= 0
Friction Slope Method= 1
Unsteady Friction Slope Method= 2
Unsteady Bridges Friction Slope Method= 1
Parabolic Critical Depth
Global Vel Dist=  1 , 1 , 1
Global Log Level= 0
CheckData=True
Encroach Param= -1, 0, 0, 0
BEGIN DESCRIPTION:
Multiple Run
END DESCRIPTION:

--- Stream0272_DS.f01 (steady flow) ---

Flow Title=Multiple
Number of Profiles=7
Profile Names=10-year,25-year,50-year,1pct_min,100-year,1pct_plu,500-year
River Rch & RM= Stream0272_DS,Reach-1,1366
     507     814    1093     713    1423    2840    2381
Boundary for River Rch & Prof#=Stream0272_DS,Reach-1,1
Up Type=0
Dn Type=3
Dn Slope=0.005
Boundary for River Rch & Prof#=Stream0272_DS,Reach-1,2
Up Type=0
Dn Type=3
Dn Slope=0.005
Boundary for River Rch & Prof#=Stream0272_DS,Reach-1,3
Up Type=0
Dn Type=3
Dn Slope=0.005
Boundary for River Rch & Prof#=Stream0272_DS,Reach-1,4
Up Type=0
Dn Type=3
Dn Slope=0.005
Boundary for River Rch & Prof#=Stream0272_DS,Reach-1,5
Up Type=0
Dn Type=3
Dn Slope=0.005
Boundary for River Rch & Prof#=Stream0272_DS,Reach-1,6
Up Type=0
Dn Type=3
Dn Slope=0.005
Boundary for River Rch & Prof#=Stream0272_DS,Reach-1,7
Up Type=0
Dn Type=3
Dn Slope=0.005

--- Stream0272_DS.g01 (geometry) ---

Geom Title=Existing Conditions

River Reach=Stream0272_DS,Reach-1
Reach XY= 30
      2052775.00     13890625.00      2052808.58     13890658.08
      2052819.29     13890672.65      2052823.34     13890685.69
      2052827.34     13890719.03      2052830.72     13890727.34
      2052838.57     13890738.23      2052998.70     13890898.18
      2053014.22     13890915.32      2053019.14     13890922.71
      2053022.47     13890931.05      2053026.55     13890964.36
      2053028.98     13890973.35      2053033.16     13890981.05
      2053038.63     13890988.21      2053054.62     13891005.16
      2053198.82     13891148.13      2053217.14     13891168.83
      2053221.39     13891176.50      2053224.47     13891190.22
      2053224.92     13891250.04      2053226.17     13891264.52
      2053228.61     13891273.50      2053235.52     13891284.79
      2053251.18     13891301.87      2053561.53     13891611.73
      2053569.69     13891622.48      2053573.32     13891631.14
      2053575.41     13891649.63      2053575.00     13891675.00

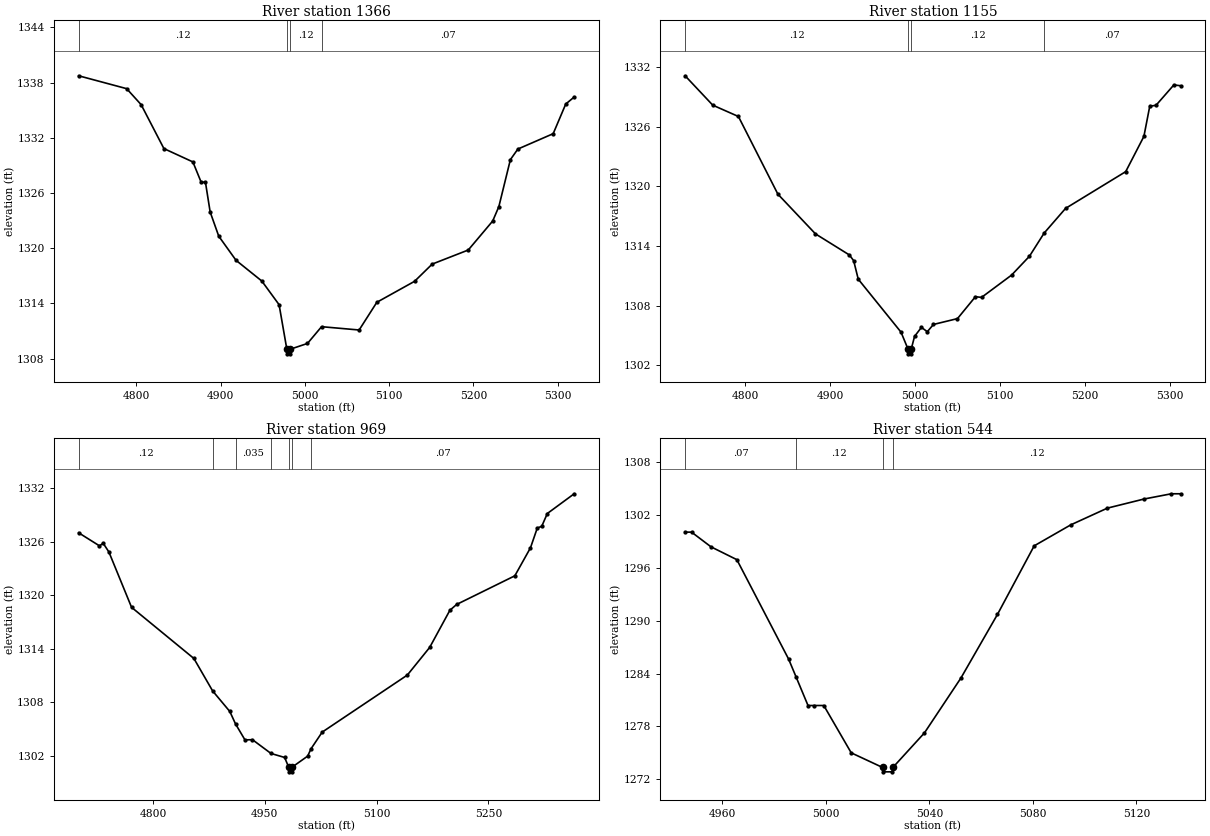
Type RM Length L Ch R = 1,1366,211,211,211
BEGIN DESCRIPTION:
Stream0272_DS 4.0
END DESCRIPTION:
XS GIS Cut Line= 3
      2052512.45     13890681.63      2052775.00     13890625.00
      2053038.83     13890444.75
#Sta/Elev= 30
  4731.4 1338.74  4788.4 1337.34  4805.6 1335.60  4832.6 1330.83  4867.0 1329.38
  4876.8 1327.18  4881.9 1327.18  4887.5 1323.94  4897.7 1321.31  4918.2 1318.69
  4948.8 1316.44  4969.3 1313.87  4978.5 1309.03  4978.7 1308.53  4982.2 1308.53
  4982.5 1309.03  5003.0 1309.66  5019.7 1311.48  5064.3 1311.12  5085.3 1314.13
  5130.1 1316.41  5151.0 1318.28  5193.8 1319.81  5222.8 1322.96  5230.1 1324.52
  5243.8 1329.63  5252.7 1330.78  5294.6 1332.45  5309.5 1335.67  5319.5 1336.43
#Mann=4,-1,0
  4731.4    0.12       0  4978.5    0.05       0  4982.5    0.12       0
  5019.7    0.07       0
Bank Sta=4978.5,4982.5
Exp/Cntr=0.3,0.1

Type RM Length L Ch R = 1,1155,186,186,186
BEGIN DESCRIPTION:
Stream0272_DS 3.0
END DESCRIPTION:
XS GIS Cut Line= 3
      2052622.74     13890822.56      2052891.58     13890791.70
      2053107.60     13890566.45
#Sta/Elev= 30
  4729.4 1331.10  4761.9 1328.15  4792.1 1327.01  4838.5 1319.21  4882.7 1315.22
  4922.6 1313.10  4927.6 1312.53  4933.0 1310.67  4983.3 1305.35  4991.4 1303.67
  4991.6 1303.17  4995.1 1303.17  4995.4 1303.67  4999.2 1304.92  5007.3 1305.83
  5014.2 1305.39  5021.4 1306.12  5049.7 1306.71  5070.8 1308.91  5078.0 1308.84
  5113.3 1311.08  5134.3 1312.97  5151.6 1315.30  5176.8 1317.78  5247.5 1321.47
  5268.9 1325.01  5275.8 1328.05  5283.1 1328.13  5304.1 1330.18  5312.1 1330.10
#Mann=4,-1,0
  4729.4    0.12       0  4991.4    0.05       0  4995.4    0.12       0
  5151.6    0.07       0
Bank Sta=4991.4,4995.4
Exp/Cntr=0.3,0.1

Type RM Length L Ch R = 1,969,425,425,425
BEGIN DESCRIPTION:
Stream0272_DS 2.0
END DESCRIPTION:
XS GIS Cut Line= 3
      2052724.97     13890975.01      2053025.00     13890925.00
      2053224.98     13890625.02
#Sta/Elev= 30
  4700.3 1326.99  4728.2 1325.53  4733.3 1325.81  4740.9 1324.84  4771.3 1318.64
  4854.9 1312.91  4880.0 1309.28  4903.1 1306.97  4910.8 1305.57  4923.4 1303.79
  4933.5 1303.81  4958.3 1302.27  4976.6 1301.82  4982.2 1300.71  4982.4 1300.21
  4985.9 1300.21  4986.2 1300.71  5007.5 1301.97  5012.0 1302.79  5027.0 1304.66
  5141.2 1311.05  5171.2 1314.15  5198.3 1318.31  5207.3 1318.96  5285.4 1322.17
  5306.4 1325.31  5315.5 1327.52  5321.5 1327.72  5329.0 1329.15  5365.0 1331.36
#Mann=7,-1,0
  4700.3    0.12       0  4880.0    0.07       0  4910.8   0.035       0
  4958.3    0.12       0  4982.2    0.05       0  4986.2    0.12       0
  5012.0    0.07       0
Bank Sta=4982.2,4986.2
Exp/Cntr=0.3,0.1

Type RM Length L Ch R = 1,544,0,0,0
BEGIN DESCRIPTION:
Stream0272_DS 1.0
END DESCRIPTION:
XS GIS Cut Line= 3
      2053174.96     13891275.00      2053225.00     13891275.00
      2053325.03     13891174.97
#Sta/Elev= 23
  4945.6 1300.08  4948.1 1300.08  4955.6 1298.41  4965.6 1296.95  4985.6 1285.65
  4988.5 1283.61  4993.1 1280.37  4995.6 1280.37  4999.2 1280.37  5009.8 1274.99
  5021.9 1273.33  5022.2 1272.83  5025.7 1272.83  5025.9 1273.33  5038.1 1277.26
  5052.2 1283.50  5066.3 1290.72  5080.5 1298.52  5094.6 1300.90  5108.8 1302.81
  5122.9 1303.84  5133.5 1304.44  5137.1 1304.44
#Mann=4,-1,0
  4945.6    0.07       0  4988.5    0.12       0  5021.9    0.05       0
  5025.9    0.12       0
Bank Sta=5021.9,5025.9
Exp/Cntr=0.3,0.1

Chan Stop Cuts=-1