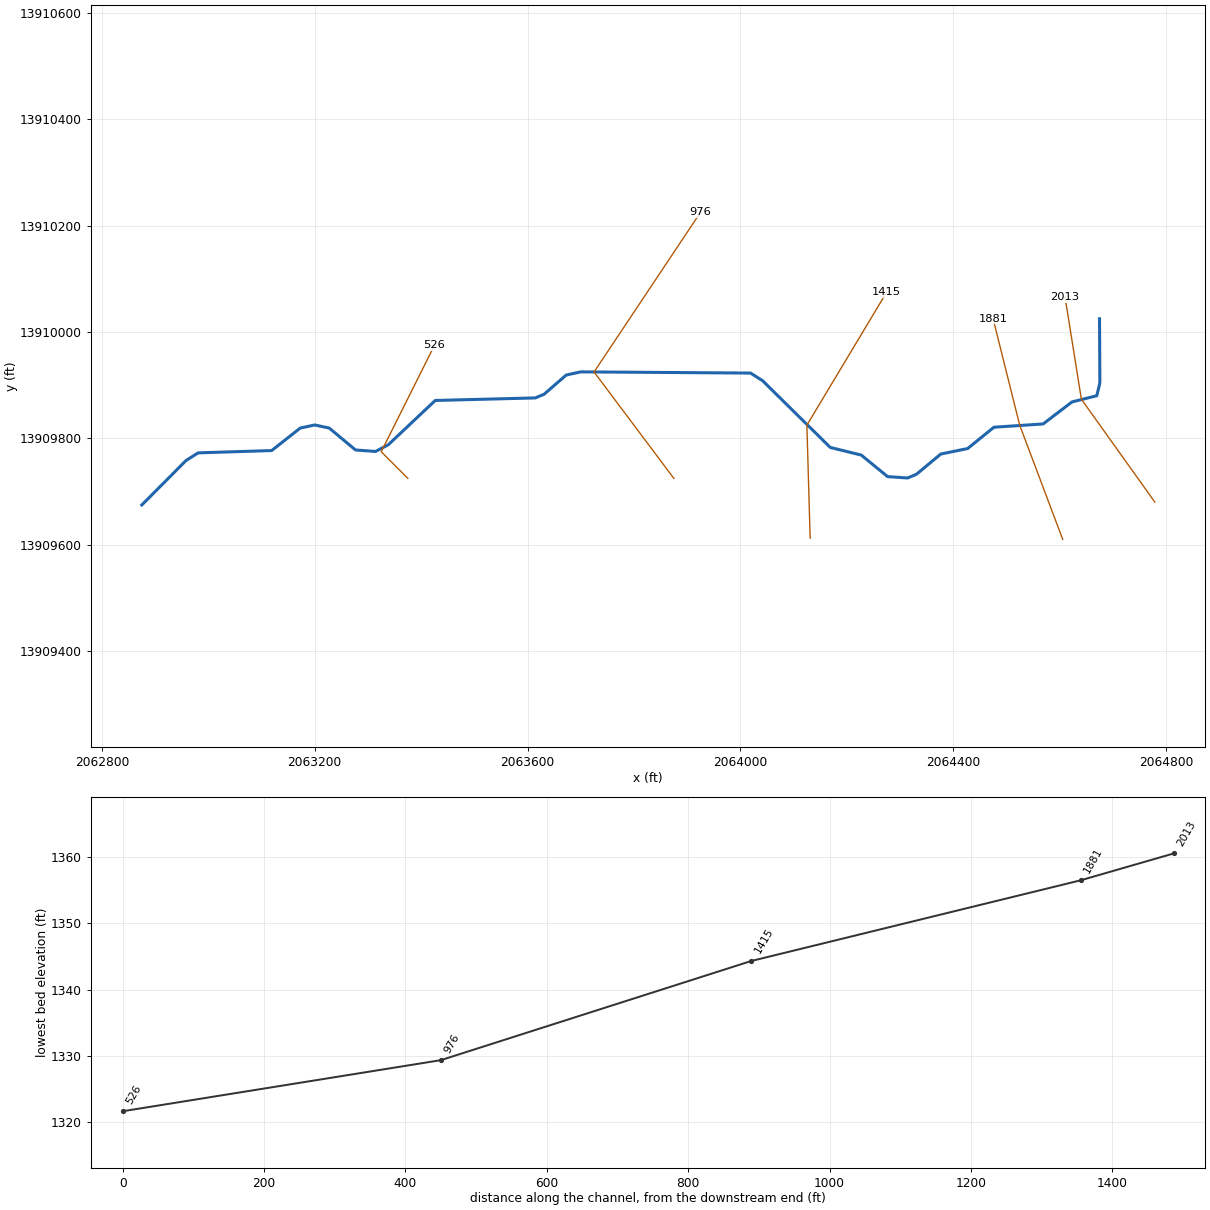
--- Stream0273_DS.prj (project) ---

Proj Title=Stream0273_DS Base Level Engineering
Current Plan=p01
Default Exp/Contr=0.3,0.1
English Units
Geom File=g01
Flow File=f01
Plan File=p01
BEGIN DESCRIPTION:
Stream0273_DS
END DESCRIPTION:

--- Stream0273_DS.p01 (plan) ---

Plan Title=Multiple Run
Short Identifier=Multiple
Geom File=g01
Flow File=f01
Subcritical Flow
K Sum by GR= 0
Std Step Tol= 0.01
Critical Tol= 0.01
Num of Std Step Trials= 20
Max Error Tol= 0.3
Flow Tol Ratio= 0.001
Split Flow NTrial= 30
Split Flow Tol= 0.02
Split Flow Ratio= 0.02
Log Output Level= 0
Friction Slope Method= 1
Unsteady Friction Slope Method= 2
Unsteady Bridges Friction Slope Method= 1
Parabolic Critical Depth
Global Vel Dist=  1 , 1 , 1
Global Log Level= 0
CheckData=True
Encroach Param= -1, 0, 0, 0
BEGIN DESCRIPTION:
Multiple Run
END DESCRIPTION:

--- Stream0273_DS.f01 (steady flow) ---

Flow Title=Multiple
Number of Profiles=7
Profile Names=10-year,25-year,50-year,1pct_min,100-year,1pct_plu,500-year
River Rch & RM= Stream0273_DS,Reach-1,2013
     423     678     908     594    1184    2363    1982
River Rch & RM= Stream0273_DS,Reach-1,1881
     643    1060    1447     961    1918    3826    3323
Boundary for River Rch & Prof#=Stream0273_DS,Reach-1,1
Up Type=0
Dn Type=3
Dn Slope=0.005
Boundary for River Rch & Prof#=Stream0273_DS,Reach-1,2
Up Type=0
Dn Type=3
Dn Slope=0.005
Boundary for River Rch & Prof#=Stream0273_DS,Reach-1,3
Up Type=0
Dn Type=3
Dn Slope=0.005
Boundary for River Rch & Prof#=Stream0273_DS,Reach-1,4
Up Type=0
Dn Type=3
Dn Slope=0.005
Boundary for River Rch & Prof#=Stream0273_DS,Reach-1,5
Up Type=0
Dn Type=3
Dn Slope=0.005
Boundary for River Rch & Prof#=Stream0273_DS,Reach-1,6
Up Type=0
Dn Type=3
Dn Slope=0.005
Boundary for River Rch & Prof#=Stream0273_DS,Reach-1,7
Up Type=0
Dn Type=3
Dn Slope=0.005

--- Stream0273_DS.g01 (geometry) ---

Geom Title=Existing Conditions

River Reach=Stream0273_DS,Reach-1
Reach XY= 30
      2064675.00     13910025.00      2064675.65     13909904.45
      2064669.88     13909880.37      2064623.22     13909868.70
      2064569.06     13909827.32      2064476.59     13909821.17
      2064427.18     13909781.11      2064376.72     13909770.78
      2064330.94     13909732.76      2064314.31     13909725.74
      2064276.72     13909728.34      2064227.19     13909768.82
      2064168.94     13909783.14      2064041.76     13909908.57
      2064019.15     13909922.94      2063699.92     13909925.20
      2063672.67     13909919.25      2063631.06     13909883.14
      2063614.49     13909876.22      2063426.47     13909871.45
      2063338.20     13909788.15      2063314.37     13909775.61
      2063276.74     13909778.37      2063227.20     13909819.58
      2063200.00     13909825.39      2063172.82     13909819.62
      2063119.07     13909777.30      2062980.84     13909772.97
      2062958.19     13909758.67      2062875.00     13909675.00

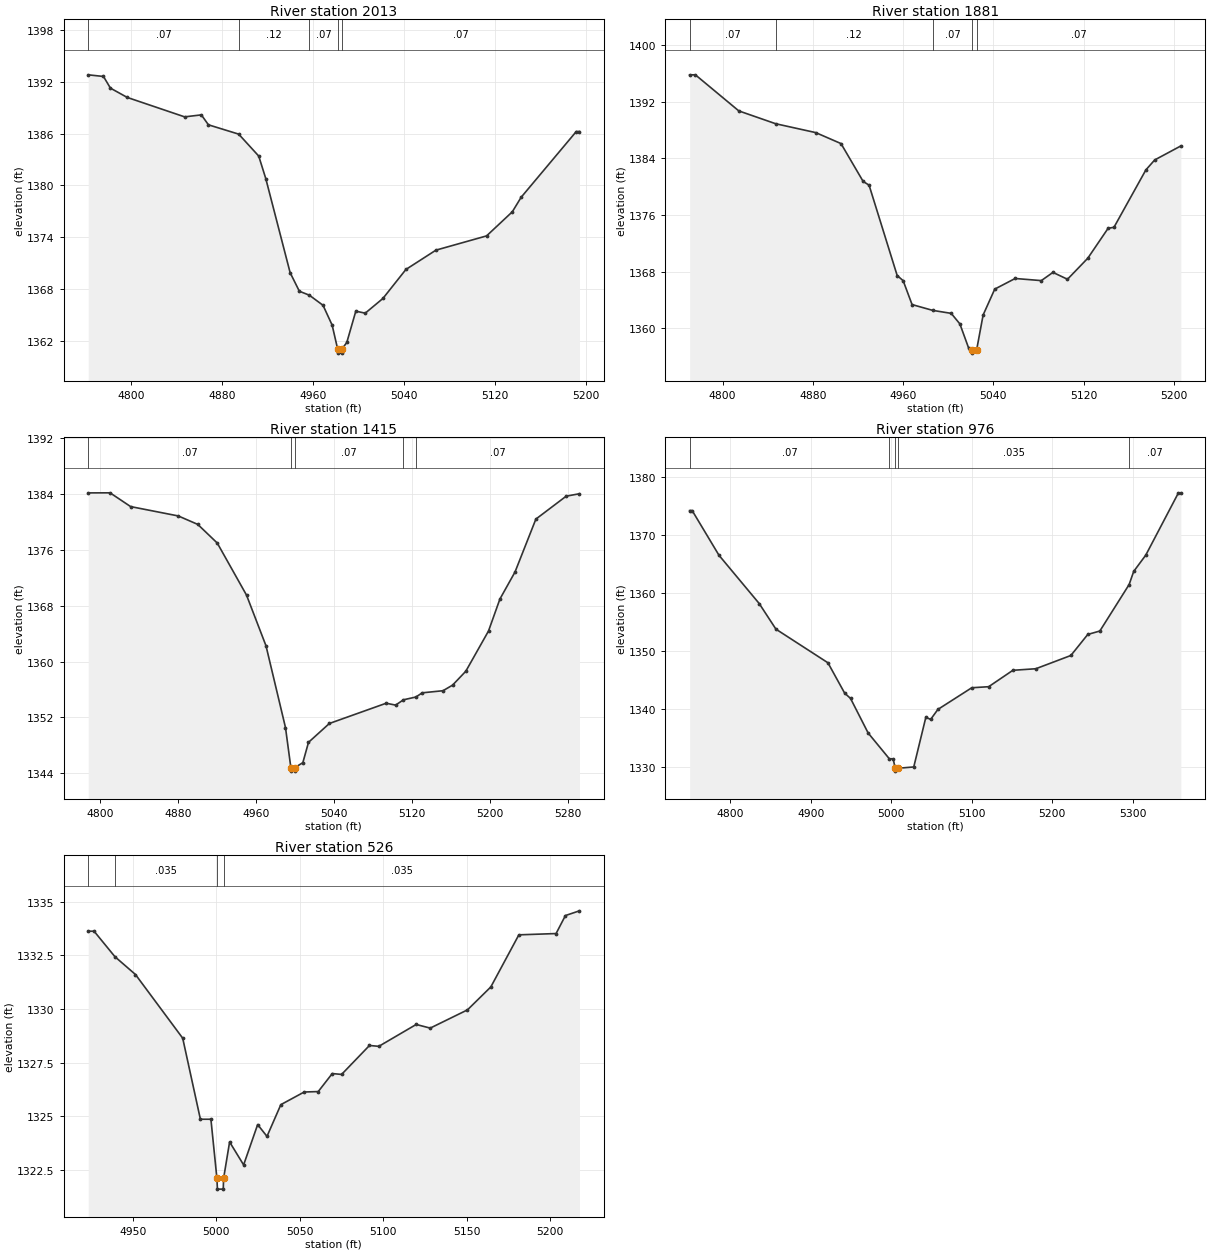
Type RM Length L Ch R = 1,2013,132,132,132
BEGIN DESCRIPTION:
Stream0273_DS 5.0
END DESCRIPTION:
XS GIS Cut Line= 3
      2064778.84     13909680.58      2064640.90     13909873.80
      2064610.25     13910065.56
#Sta/Elev= 30
  4762.6 1392.82  4776.0 1392.63  4782.1 1391.28  4796.9 1390.20  4847.3 1387.95
  4862.0 1388.18  4868.2 1387.03  4894.8 1385.95  4912.4 1383.41  4918.6 1380.80
  4940.0 1369.90  4948.1 1367.75  4956.9 1367.29  4968.9 1366.12  4976.9 1363.83
  4981.7 1361.08  4981.9 1360.58  4985.4 1360.58  4985.7 1361.08  4989.8 1361.82
  4997.7 1365.44  5006.0 1365.21  5021.5 1366.91  5041.7 1370.27  5068.1 1372.51
  5112.6 1374.16  5135.2 1376.95  5143.0 1378.64  5191.4 1386.25  5194.2 1386.25
#Mann=5,-1,0
  4762.6    0.07       0  4894.8    0.12       0  4956.9    0.07       0
  4981.7    0.05       0  4985.7    0.07       0
Bank Sta=4981.7,4985.7
Exp/Cntr=0.3,0.1

Type RM Length L Ch R = 1,1881,466,466,466
BEGIN DESCRIPTION:
Stream0273_DS 4.0
END DESCRIPTION:
XS GIS Cut Line= 3
      2064605.80     13909610.40      2064525.00     13909825.00
      2064474.99     13910025.04
#Sta/Elev= 30
  4770.7 1395.77  4775.8 1395.77  4814.3 1390.68  4847.0 1388.87  4882.5 1387.62
  4904.9 1386.07  4924.5 1380.74  4929.8 1380.20  4954.7 1367.46  4960.0 1366.73
  4967.9 1363.36  4986.2 1362.54  5002.6 1362.12  5010.3 1360.63  5018.0 1357.25
  5021.2 1357.01  5021.4 1356.51  5025.2 1357.01  5030.9 1361.89  5041.2 1365.54
  5059.3 1367.04  5082.5 1366.74  5092.8 1367.90  5105.7 1366.93  5123.7 1369.90
  5141.7 1374.12  5146.9 1374.26  5175.2 1382.36  5183.0 1383.76  5206.2 1385.74
#Mann=5,-1,0
  4770.7    0.07       0  4847.0    0.12       0  4986.2    0.07       0
  5021.2    0.05       0  5025.2    0.07       0
Bank Sta=5021.2,5025.2
Exp/Cntr=0.3,0.1

Type RM Length L Ch R = 1,1415,439,439,439
BEGIN DESCRIPTION:
Stream0273_DS 3.0
END DESCRIPTION:
XS GIS Cut Line= 3
      2064131.14     13909612.65      2064125.00     13909825.00
      2064275.01     13910075.01
#Sta/Elev= 30
  4787.9 1384.14  4810.3 1384.15  4831.4 1382.18  4880.3 1380.84  4900.3 1379.63
  4920.3 1376.96  4950.3 1369.51  4970.3 1362.25  4990.3 1350.54  4995.8 1344.81
  4996.1 1344.31  4999.6 1344.31  4999.8 1344.81  5008.1 1345.52  5013.9 1348.43
  5035.3 1351.13  5093.6 1354.03  5103.3 1353.76  5111.3 1354.52  5124.1 1354.92
  5130.6 1355.52  5151.9 1355.82  5161.7 1356.62  5175.3 1358.61  5198.6 1364.37
  5210.3 1368.95  5225.8 1372.82  5247.2 1380.39  5278.3 1383.67  5291.9 1384.02
#Mann=5,-1,0
  4787.9    0.07       0  4995.8    0.05       0  4999.8    0.07       0
  5111.3   0.035       0  5124.1    0.07       0
Bank Sta=4995.8,4999.8
Exp/Cntr=0.3,0.1

Type RM Length L Ch R = 1,976,450,450,450
BEGIN DESCRIPTION:
Stream0273_DS 2.0
END DESCRIPTION:
XS GIS Cut Line= 3
      2063875.02     13909724.97      2063725.00     13909925.00
      2063925.01     13910225.01
#Sta/Elev= 30
  4749.5 1374.28  4752.7 1374.28  4786.0 1366.57  4836.0 1358.24  4856.8 1353.82
  4921.4 1348.02  4942.2 1342.78  4949.5 1341.87  4971.4 1335.90  4997.8 1331.44
  5002.5 1331.44  5005.0 1329.82  5005.3 1329.32  5009.0 1329.82  5028.1 1330.04
  5043.1 1338.60  5049.1 1338.25  5058.1 1339.97  5100.2 1343.71  5121.2 1343.89
  5151.3 1346.72  5179.8 1346.99  5223.4 1349.28  5244.4 1352.91  5259.4 1353.50
  5295.8 1361.52  5301.5 1363.79  5316.5 1366.60  5357.1 1377.35  5360.1 1377.35
#Mann=5,-1,0
  4749.5    0.07       0  4997.8   0.035       0  5005.0   0.035       0
  5009.0   0.035       0  5295.8    0.07       0
Bank Sta=5005,5009
Exp/Cntr=0.3,0.1

Type RM Length L Ch R = 1,526,0,0,0
BEGIN DESCRIPTION:
Stream0273_DS 1.0
END DESCRIPTION:
XS GIS Cut Line= 3
      2063375.00     13909725.00      2063325.00     13909775.00
      2063424.99     13909974.98
#Sta/Elev= 30
  4923.3 1333.63  4926.8 1333.63  4939.3 1332.44  4951.6 1331.61  4979.9 1328.64
  4990.5 1324.86  4996.8 1324.86  5000.4 1322.10  5000.7 1321.60  5004.2 1321.60
  5004.4 1322.10  5008.0 1323.80  5016.4 1322.73  5024.8 1324.61  5030.4 1324.06
  5038.7 1325.54  5052.7 1326.13  5061.1 1326.15  5069.5 1326.99  5075.1 1326.95
  5091.8 1328.30  5097.4 1328.26  5119.8 1329.28  5128.2 1329.11  5150.5 1329.96
  5164.5 1331.03  5181.3 1333.46  5203.6 1333.52  5209.2 1334.36  5217.6 1334.58
#Mann=4,-1,0
  4923.3    0.07       0  4939.3   0.035       0  5000.4   0.035       0
  5004.4   0.035       0
Bank Sta=5000.4,5004.4
Exp/Cntr=0.3,0.1

Chan Stop Cuts=-1