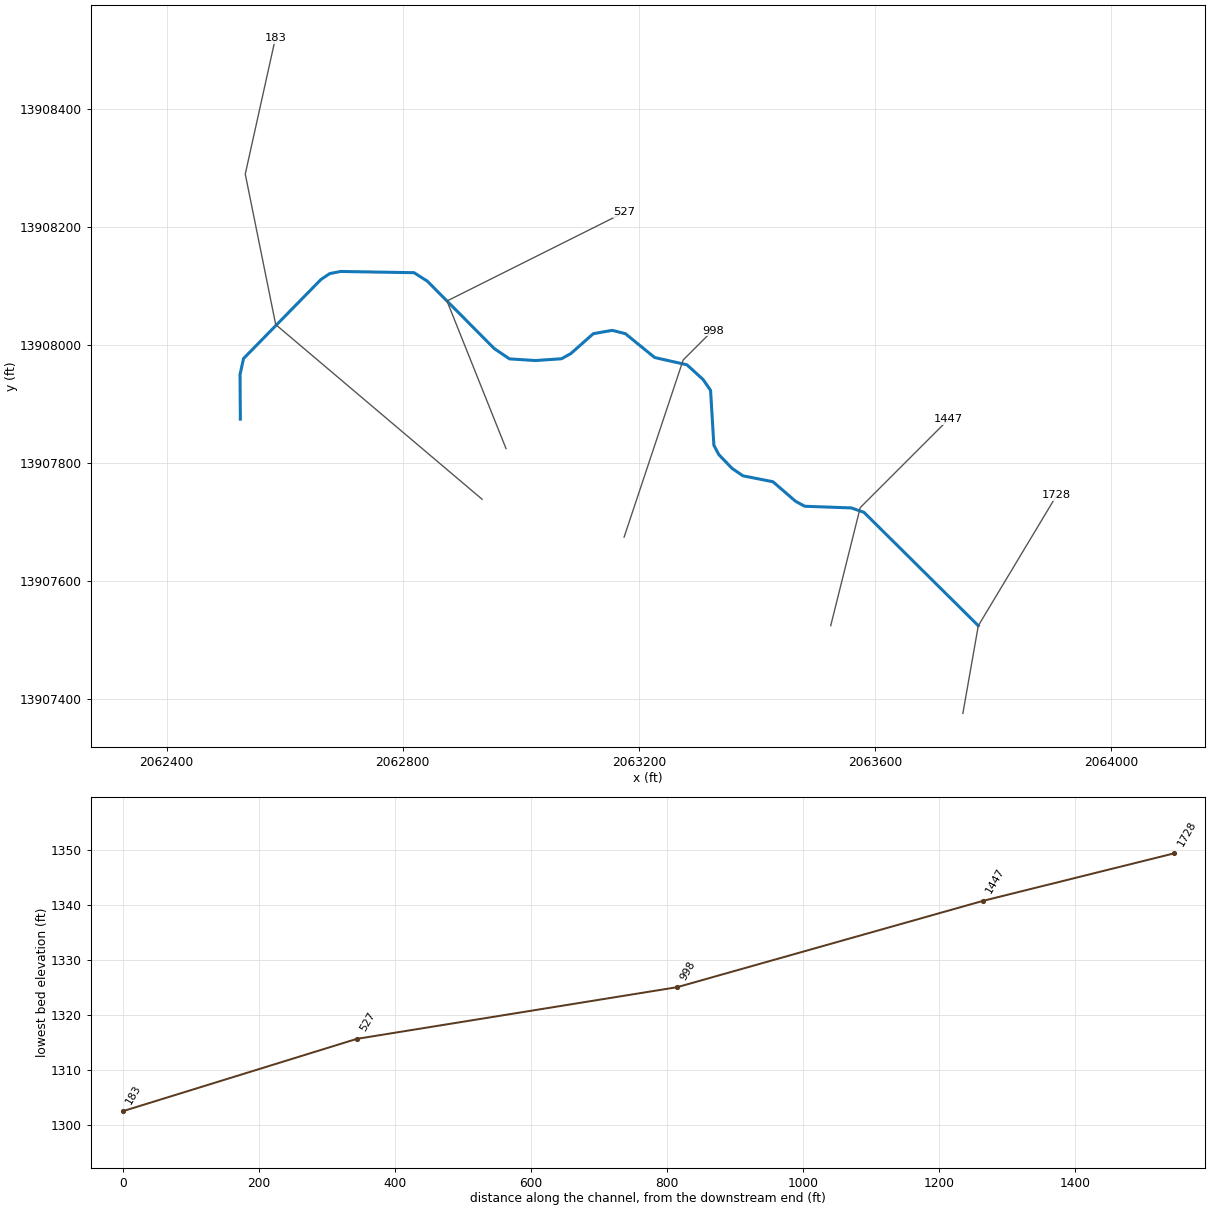
--- Stream0274_DS.prj (project) ---

Proj Title=Stream0274_DS Base Level Engineering
Current Plan=p01
Default Exp/Contr=0.3,0.1
English Units
Geom File=g01
Flow File=f01
Plan File=p01
BEGIN DESCRIPTION:
Stream0274_DS
END DESCRIPTION:

--- Stream0274_DS.p01 (plan) ---

Plan Title=Multiple Run
Short Identifier=Multiple
Geom File=g01
Flow File=f01
Subcritical Flow
K Sum by GR= 0
Std Step Tol= 0.01
Critical Tol= 0.01
Num of Std Step Trials= 20
Max Error Tol= 0.3
Flow Tol Ratio= 0.001
Split Flow NTrial= 30
Split Flow Tol= 0.02
Split Flow Ratio= 0.02
Log Output Level= 0
Friction Slope Method= 1
Unsteady Friction Slope Method= 2
Unsteady Bridges Friction Slope Method= 1
Parabolic Critical Depth
Global Vel Dist=  1 , 1 , 1
Global Log Level= 0
CheckData=True
Encroach Param= -1, 0, 0, 0
BEGIN DESCRIPTION:
Multiple Run
END DESCRIPTION:

--- Stream0274_DS.f01 (steady flow) ---

Flow Title=Multiple
Number of Profiles=7
Profile Names=10-year,25-year,50-year,1pct_min,100-year,1pct_plu,500-year
River Rch & RM= Stream0274_DS,Reach-1,1728
     252     386     502     319     636    1269    1004
River Rch & RM= Stream0274_DS,Reach-1,1447
     365     575     762     492     982    1960    1607
Boundary for River Rch & Prof#=Stream0274_DS,Reach-1,1
Up Type=0
Dn Type=3
Dn Slope=0.005
Boundary for River Rch & Prof#=Stream0274_DS,Reach-1,2
Up Type=0
Dn Type=3
Dn Slope=0.005
Boundary for River Rch & Prof#=Stream0274_DS,Reach-1,3
Up Type=0
Dn Type=3
Dn Slope=0.005
Boundary for River Rch & Prof#=Stream0274_DS,Reach-1,4
Up Type=0
Dn Type=3
Dn Slope=0.005
Boundary for River Rch & Prof#=Stream0274_DS,Reach-1,5
Up Type=0
Dn Type=3
Dn Slope=0.005
Boundary for River Rch & Prof#=Stream0274_DS,Reach-1,6
Up Type=0
Dn Type=3
Dn Slope=0.005
Boundary for River Rch & Prof#=Stream0274_DS,Reach-1,7
Up Type=0
Dn Type=3
Dn Slope=0.005

--- Stream0274_DS.g01 (geometry) ---

Geom Title=Existing Conditions

River Reach=Stream0274_DS,Reach-1
Reach XY= 30
      2063775.00     13907525.00      2063581.17     13907717.14
      2063559.78     13907724.48      2063480.97     13907727.33
      2063465.34     13907735.84      2063427.15     13907768.85
      2063376.39     13907778.84      2063357.87     13907791.45
      2063335.39     13907814.90      2063327.08     13907830.71
      2063321.47     13907923.71      2063308.70     13907942.13
      2063281.38     13907967.00      2063226.77     13907979.26
      2063177.20     13908019.66      2063154.83     13908025.29
      2063122.82     13908019.62      2063084.65     13907985.87
      2063069.03     13907977.19      2063024.99     13907974.15
      2062980.89     13907976.96      2062954.85     13907994.58
      2062841.76     13908108.57      2062819.14     13908122.95
      2062694.99     13908125.06      2062676.47     13908121.47
      2062661.68     13908111.63      2062530.35     13907977.50
      2062524.40     13907950.25      2062525.00     13907875.00

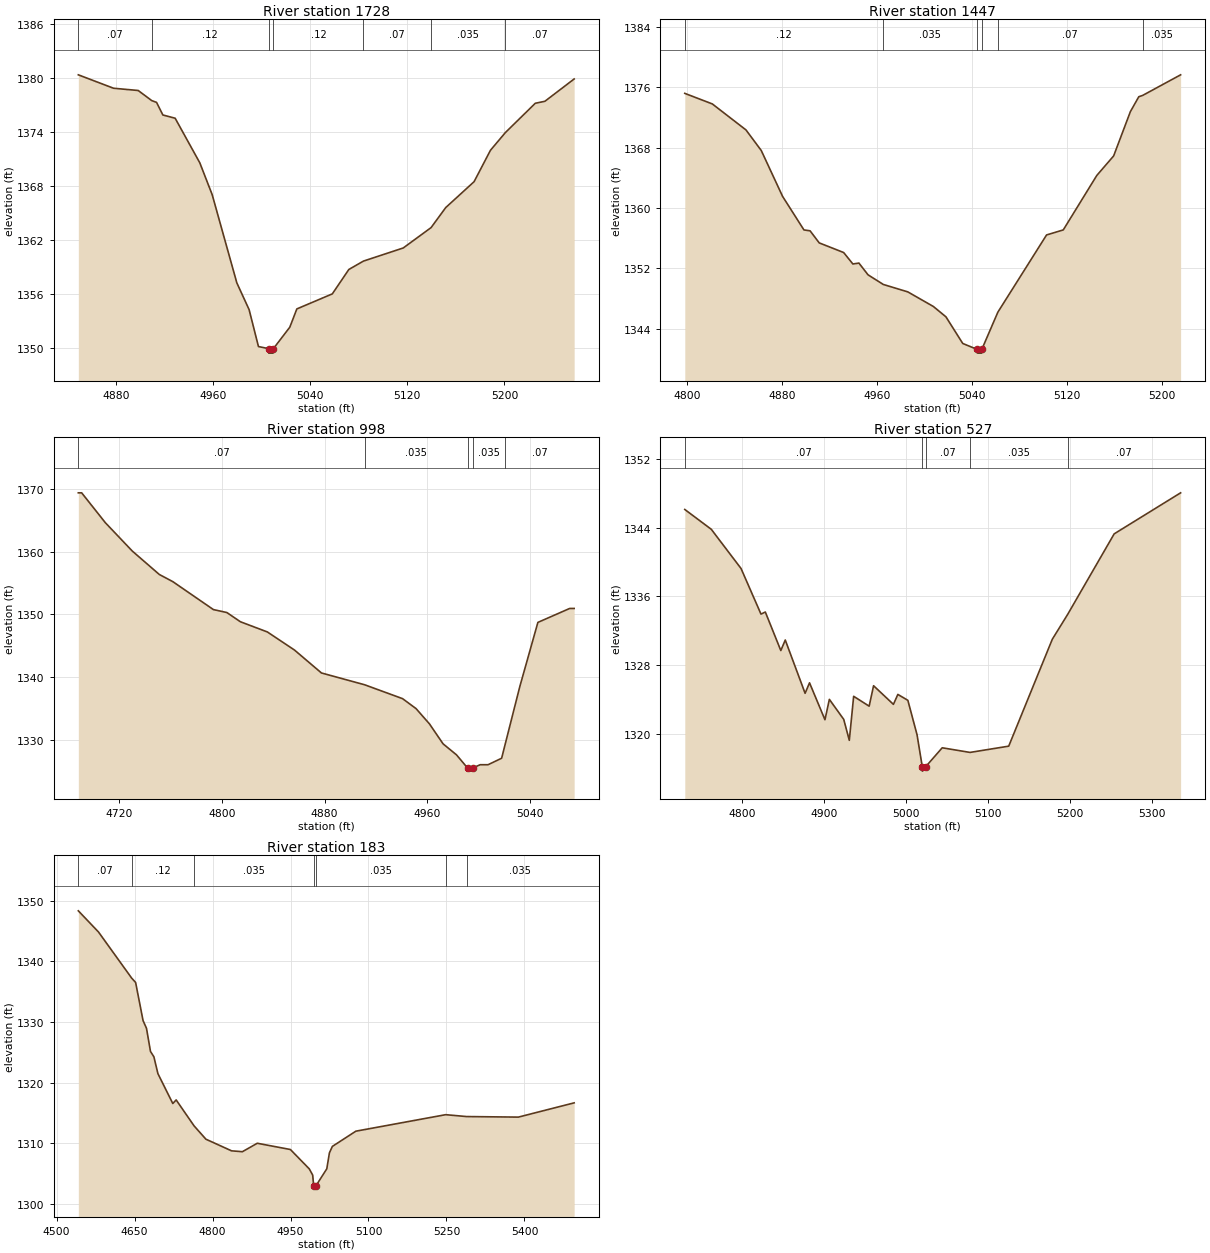
Type RM Length L Ch R = 1,1728,281,281,281
BEGIN DESCRIPTION:
Stream0274_DS 4.0
END DESCRIPTION:
XS GIS Cut Line= 3
      2063748.86     13907376.48      2063775.00     13907525.00
      2063907.57     13907745.63
#Sta/Elev= 30
  4849.2 1380.32  4878.2 1378.83  4898.5 1378.58  4909.6 1377.46  4913.6 1377.26
  4918.8 1375.86  4928.9 1375.50  4949.2 1370.55  4959.4 1367.01  4979.7 1357.21
  4989.8 1354.24  4997.5 1350.14  5005.8 1349.91  5006.0 1349.41  5009.5 1349.41
  5009.8 1349.91  5023.3 1352.29  5029.1 1354.32  5058.3 1355.99  5071.9 1358.70
  5083.9 1359.63  5116.7 1361.09  5139.6 1363.35  5151.7 1365.58  5175.0 1368.45
  5188.5 1371.94  5200.8 1373.91  5225.4 1377.16  5233.3 1377.38  5257.4 1379.86
#Mann=7,-1,0
  4849.2    0.07       0  4909.6    0.12       0  5005.8    0.05       0
  5009.8    0.12       0  5083.9    0.07       0  5139.6   0.035       0
  5200.8    0.07       0
Bank Sta=5005.8,5009.8
Exp/Cntr=0.3,0.1

Type RM Length L Ch R = 1,1447,449,449,449
BEGIN DESCRIPTION:
Stream0274_DS 3.0
END DESCRIPTION:
XS GIS Cut Line= 3
      2063524.99     13907524.97      2063575.00     13907725.00
      2063724.99     13907874.99
#Sta/Elev= 30
  4797.8 1375.22  4821.0 1373.82  4849.4 1370.37  4862.3 1367.64  4880.3 1361.55
  4898.3 1357.10  4903.5 1356.98  4911.2 1355.38  4931.8 1354.10  4939.6 1352.58
  4944.7 1352.70  4952.4 1351.14  4965.3 1349.86  4985.9 1348.88  5007.5 1346.94
  5018.1 1345.57  5032.3 1342.03  5044.4 1341.25  5044.7 1340.75  5048.2 1340.75
  5048.4 1341.25  5061.9 1346.18  5103.0 1356.43  5117.1 1357.10  5145.4 1364.33
  5159.6 1366.92  5173.7 1372.79  5180.8 1374.77  5184.1 1374.95  5216.1 1377.68
#Mann=6,-1,0
  4797.8    0.12       0  4965.3   0.035       0  5044.4   0.035       0
  5048.4   0.035       0  5061.9    0.07       0  5184.1   0.035       0
Bank Sta=5044.4,5048.4
Exp/Cntr=0.3,0.1

Type RM Length L Ch R = 1,998,471,471,471
BEGIN DESCRIPTION:
Stream0274_DS 2.0
END DESCRIPTION:
XS GIS Cut Line= 3
      2063175.01     13907675.03      2063275.00     13907975.00
      2063324.99     13908024.99
#Sta/Elev= 30
  4687.9 1369.35  4690.5 1369.35  4709.0 1364.59  4730.0 1360.08  4751.1 1356.35
  4761.7 1355.20  4793.3 1350.76  4803.8 1350.29  4814.4 1348.82  4835.4 1347.20
  4856.5 1344.33  4877.6 1340.67  4911.3 1338.79  4940.9 1336.58  4951.4 1335.00
  4961.9 1332.56  4972.5 1329.39  4983.0 1327.63  4991.6 1325.54  4991.8 1325.04
  4995.3 1325.04  4995.6 1325.54  5001.5 1326.06  5007.6 1326.06  5018.2 1327.09
  5021.0 1329.34  5032.4 1338.51  5046.5 1348.72  5071.3 1350.94  5074.8 1350.94
#Mann=5,-1,0
  4687.9    0.07       0  4911.3   0.035       0  4991.6   0.035       0
  4995.6   0.035       0  5021.0    0.07       0
Bank Sta=4991.6,4995.6
Exp/Cntr=0.3,0.1

Type RM Length L Ch R = 1,527,344,344,344
BEGIN DESCRIPTION:
Stream0274_DS 1.0
END DESCRIPTION:
XS GIS Cut Line= 3
      2062974.98     13907825.04      2062875.00     13908075.00
      2063174.98     13908224.99
#Sta/Elev= 30
  4730.5 1346.11  4762.8 1343.80  4799.1 1339.23  4823.4 1333.92  4828.7 1334.16
  4847.6 1329.67  4853.0 1330.90  4877.2 1324.69  4882.6 1325.91  4901.4 1321.61
  4906.8 1323.98  4924.3 1321.65  4931.1 1319.21  4936.4 1324.34  4955.3 1323.19
  4960.7 1325.57  4984.9 1323.40  4990.3 1324.56  5002.5 1323.87  5013.7 1319.86
  5020.1 1316.12  5020.3 1315.62  5024.1 1316.12  5044.4 1318.34  5078.3 1317.80
  5125.5 1318.53  5178.6 1330.98  5197.4 1333.89  5254.1 1343.27  5335.1 1348.05
#Mann=5,-1,0
  4730.5    0.07       0  5020.1    0.05       0  5024.1    0.07       0
  5078.3   0.035       0  5197.4    0.07       0
Bank Sta=5020.1,5024.1
Exp/Cntr=0.3,0.1

Type RM Length L Ch R = 1,183,0,0,0
BEGIN DESCRIPTION:
Stream0274_DS 0.0
END DESCRIPTION:
XS GIS Cut Line= 4
      2062934.53     13907739.14      2062584.85     13908035.08
      2062533.30     13908290.00      2062584.28     13908519.94
#Sta/Elev= 30
  4541.9 1348.31  4580.7 1344.82  4644.5 1337.22  4652.1 1336.50  4666.4 1330.22
  4673.0 1328.95  4680.7 1325.13  4687.2 1324.26  4695.0 1321.47  4723.6 1316.55
  4730.1 1317.14  4764.6 1312.86  4787.3 1310.67  4836.7 1308.75  4857.5 1308.61
  4886.1 1310.00  4949.8 1308.97  4986.1 1305.78  4992.7 1304.75  4994.6 1302.94
  4994.9 1302.44  4998.6 1302.94  5019.8 1305.79  5024.9 1308.43  5030.5 1309.48
  5075.7 1311.99  5248.5 1314.71  5288.8 1314.40  5388.3 1314.31  5495.6 1316.66
#Mann=7,-1,0
  4541.9    0.07       0  4644.5    0.12       0  4764.6   0.035       0
  4994.6   0.035       0  4998.6   0.035       0  5248.5    0.07       0
  5288.8   0.035       0
Bank Sta=4994.6,4998.6
Exp/Cntr=0.3,0.1

Chan Stop Cuts=-1