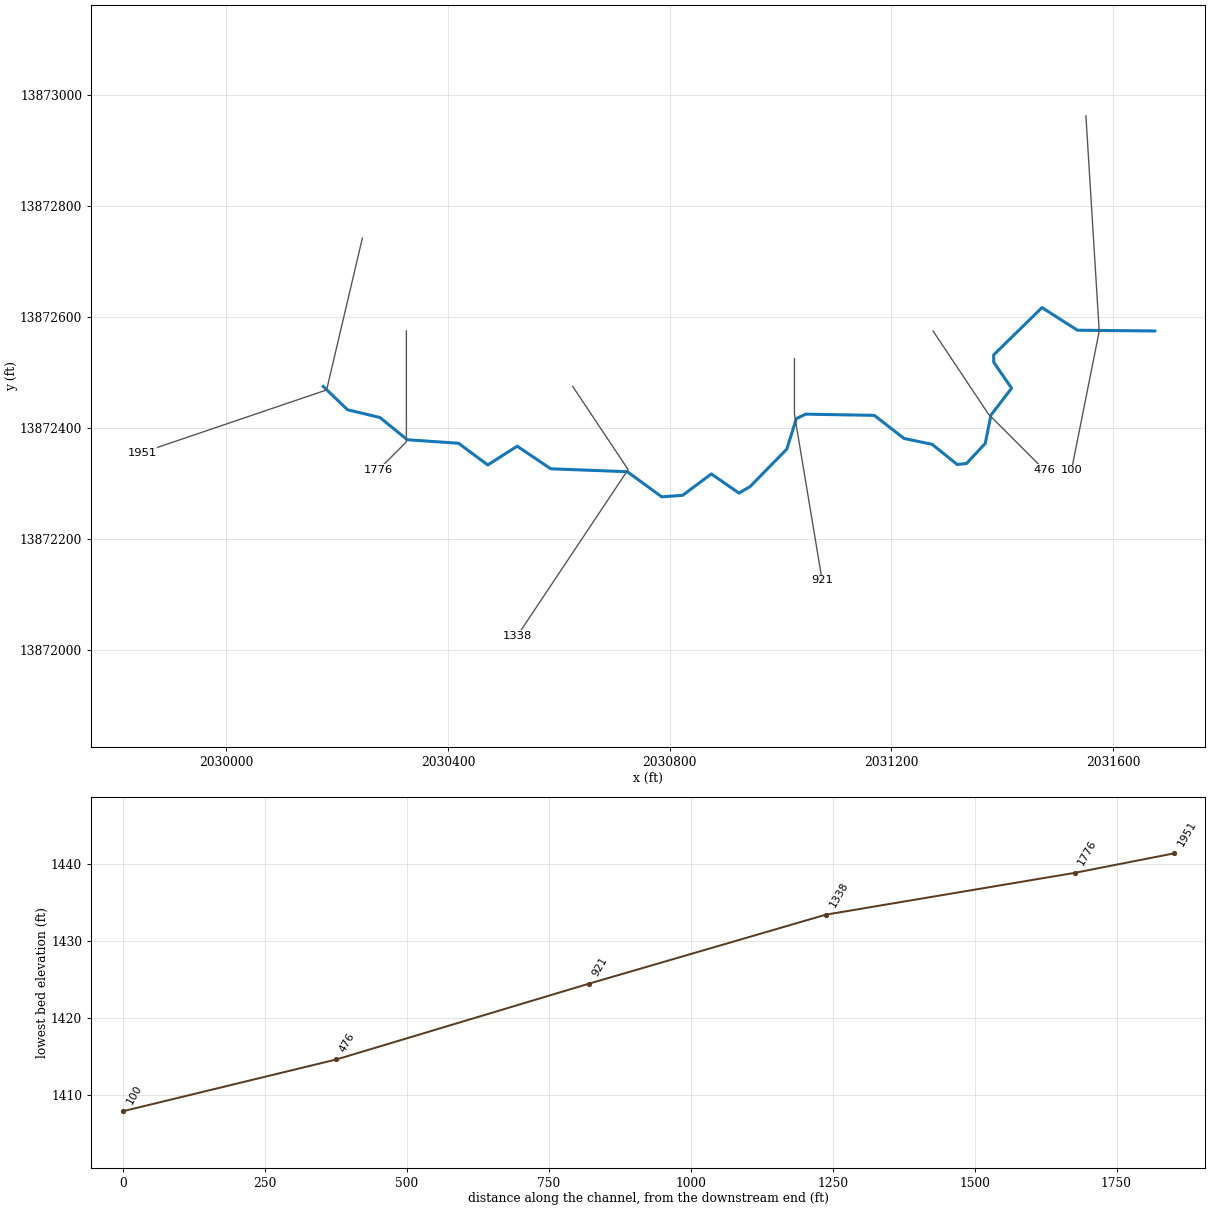
--- Stream0277_DS.prj (project) ---

Proj Title=Stream0277_DS Base Level Engineering
Current Plan=p01
Default Exp/Contr=0.3,0.1
English Units
Geom File=g01
Flow File=f01
Plan File=p01
BEGIN DESCRIPTION:
Stream0277_DS
END DESCRIPTION:

--- Stream0277_DS.p01 (plan) ---

Plan Title=Multiple Run
Short Identifier=Multiple
Geom File=g01
Flow File=f01
Subcritical Flow
K Sum by GR= 0
Std Step Tol= 0.01
Critical Tol= 0.01
Num of Std Step Trials= 20
Max Error Tol= 0.3
Flow Tol Ratio= 0.001
Split Flow NTrial= 30
Split Flow Tol= 0.02
Split Flow Ratio= 0.02
Log Output Level= 0
Friction Slope Method= 1
Unsteady Friction Slope Method= 2
Unsteady Bridges Friction Slope Method= 1
Parabolic Critical Depth
Global Vel Dist=  1 , 1 , 1
Global Log Level= 0
CheckData=True
Encroach Param= -1, 0, 0, 0
BEGIN DESCRIPTION:
Multiple Run
END DESCRIPTION:

--- Stream0277_DS.f01 (steady flow) ---

Flow Title=Multiple
Number of Profiles=7
Profile Names=10-year,25-year,50-year,1pct_min,100-year,1pct_plu,500-year
River Rch & RM= Stream0277_DS,Reach-1,1951
     663    1094    1494     992    1979    3949    3428
Boundary for River Rch & Prof#=Stream0277_DS,Reach-1,1
Up Type=0
Dn Type=3
Dn Slope=0.005
Boundary for River Rch & Prof#=Stream0277_DS,Reach-1,2
Up Type=0
Dn Type=3
Dn Slope=0.005
Boundary for River Rch & Prof#=Stream0277_DS,Reach-1,3
Up Type=0
Dn Type=3
Dn Slope=0.005
Boundary for River Rch & Prof#=Stream0277_DS,Reach-1,4
Up Type=0
Dn Type=3
Dn Slope=0.005
Boundary for River Rch & Prof#=Stream0277_DS,Reach-1,5
Up Type=0
Dn Type=3
Dn Slope=0.005
Boundary for River Rch & Prof#=Stream0277_DS,Reach-1,6
Up Type=0
Dn Type=3
Dn Slope=0.005
Boundary for River Rch & Prof#=Stream0277_DS,Reach-1,7
Up Type=0
Dn Type=3
Dn Slope=0.005

--- Stream0277_DS.g01 (geometry) ---

Geom Title=Existing Conditions

River Reach=Stream0277_DS,Reach-1
Reach XY= 30
      2030175.00     13872475.00      2030218.85     13872432.91
      2030277.22     13872418.97      2030326.58     13872378.81
      2030419.11     13872372.46      2030471.78     13872333.28
      2030524.90     13872367.21      2030585.44     13872326.39
      2030723.44     13872321.18      2030785.71     13872275.81
      2030823.37     13872278.59      2030875.09     13872317.16
      2030925.02     13872282.54      2030945.04     13872294.36
      2031011.26     13872361.99      2031028.39     13872416.90
      2031045.20     13872424.98      2031169.06     13872422.78
      2031222.83     13872381.09      2031273.38     13872370.56
      2031318.61     13872334.17      2031335.38     13872335.95
      2031369.20     13872372.15      2031379.44     13872423.29
      2031416.75     13872471.77      2031384.60     13872518.36
      2031384.30     13872531.71      2031471.55     13872617.21
      2031535.41     13872576.35      2031675.00     13872575.00

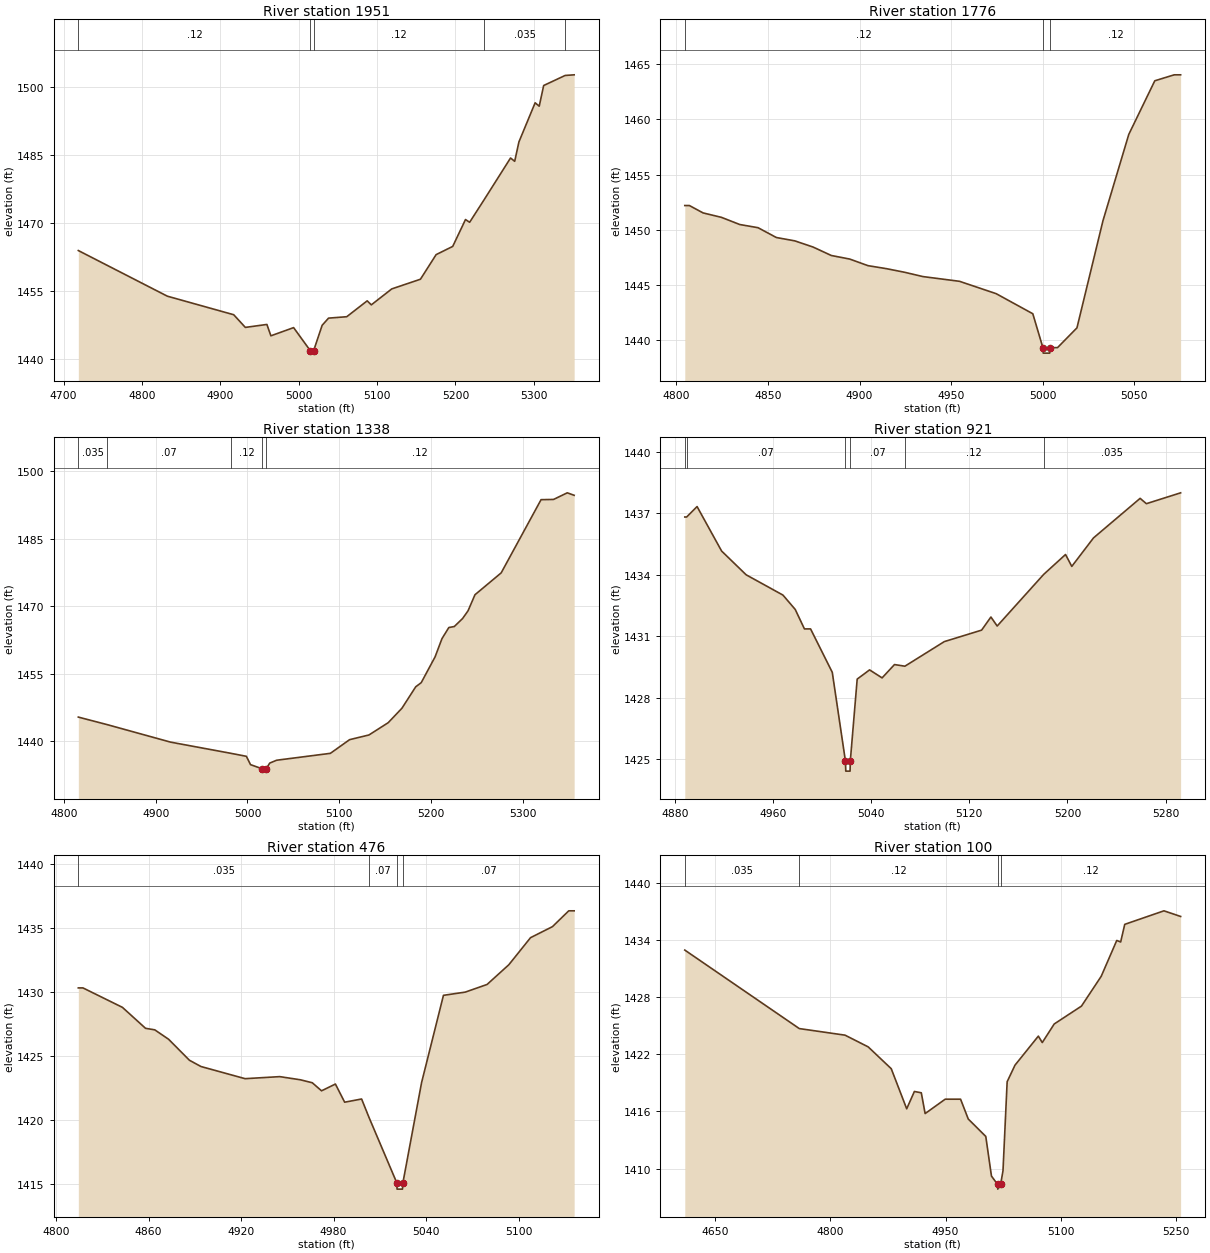
Type RM Length L Ch R = 1,1951,175,175,175
BEGIN DESCRIPTION:
Stream0277_DS 5.0
END DESCRIPTION:
XS GIS Cut Line= 3
      2030245.61     13872742.47      2030181.11     13872468.67
      2029848.20     13872355.53
#Sta/Elev= 30
  4718.7 1463.91  4832.3 1453.87  4917.0 1449.79  4931.9 1447.00  4959.4 1447.65
  4964.5 1445.15  4993.5 1446.95  5015.0 1441.84  5015.3 1441.34  5019.0 1441.84
  5029.9 1447.46  5038.1 1449.04  5061.3 1449.35  5087.4 1452.84  5092.7 1451.96
  5118.8 1455.47  5155.4 1457.60  5175.4 1463.01  5196.6 1464.82  5212.9 1470.73
  5218.2 1470.13  5237.1 1475.20  5270.4 1484.27  5275.7 1483.54  5281.1 1487.81
  5301.8 1496.42  5307.0 1495.67  5312.7 1500.22  5340.1 1502.43  5351.6 1502.57
#Mann=5,-1,0
  4718.7    0.12       0  5015.0    0.05       0  5019.0    0.12       0
  5237.1   0.035       0  5340.1    0.07       0
Bank Sta=5015,5019
Exp/Cntr=0.3,0.1

Type RM Length L Ch R = 1,1776,438,438,438
BEGIN DESCRIPTION:
Stream0277_DS 4.0
END DESCRIPTION:
XS GIS Cut Line= 3
      2030325.00     13872575.00      2030325.00     13872375.00
      2030275.01     13872325.01
#Sta/Elev= 30
  4804.6 1452.19  4807.1 1452.19  4814.6 1451.52  4824.6 1451.12  4834.6 1450.47
  4844.6 1450.18  4854.6 1449.29  4864.6 1448.99  4874.6 1448.43  4884.6 1447.66
  4894.6 1447.34  4904.6 1446.74  4914.6 1446.47  4924.6 1446.14  4934.6 1445.75
  4954.6 1445.32  4974.6 1444.20  4994.6 1442.38  5000.1 1439.31  5000.3 1438.81
  5003.8 1438.81  5004.1 1439.31  5004.6 1439.31  5008.1 1439.31  5018.7 1441.10
  5032.9 1450.81  5047.0 1458.64  5061.2 1463.50  5071.8 1464.04  5075.3 1464.04
#Mann=3,-1,0
  4804.6    0.12       0  5000.1    0.05       0  5004.1    0.12       0
Bank Sta=5000.1,5004.1
Exp/Cntr=0.3,0.1

Type RM Length L Ch R = 1,1338,417,417,417
BEGIN DESCRIPTION:
Stream0277_DS 3.0
END DESCRIPTION:
XS GIS Cut Line= 3
      2030625.02     13872474.97      2030725.00     13872325.00
      2030525.00     13872025.00
#Sta/Elev= 30
  4815.5 1445.38  4847.3 1443.69  4916.1 1439.82  4981.8 1437.34  4998.8 1436.67
  5003.3 1434.82  5016.3 1433.88  5016.5 1433.38  5020.3 1433.88  5024.3 1435.17
  5031.8 1435.80  5090.4 1437.33  5111.4 1440.37  5132.5 1441.41  5153.5 1444.14
  5168.5 1447.36  5183.5 1452.11  5189.5 1453.03  5204.6 1458.75  5212.1 1462.79
  5219.6 1465.27  5225.6 1465.50  5234.6 1467.27  5240.6 1469.00  5248.1 1472.55
  5276.7 1477.41  5320.2 1493.67  5333.8 1493.72  5348.8 1495.19  5356.3 1494.64
#Mann=5,-1,0
  4815.5   0.035       0  4847.3    0.07       0  4981.8    0.12       0
  5016.3    0.05       0  5020.3    0.12       0
Bank Sta=5016.3,5020.3
Exp/Cntr=0.3,0.1

Type RM Length L Ch R = 1,921,445,445,445
BEGIN DESCRIPTION:
Stream0277_DS 2.0
END DESCRIPTION:
XS GIS Cut Line= 3
      2031025.00     13872524.96      2031025.00     13872425.00
      2031075.00     13872125.00
#Sta/Elev= 30
  4888.1 1436.82  4889.6 1436.82  4898.1 1437.33  4918.1 1435.16  4938.1 1434.00
  4968.1 1433.01  4978.1 1432.31  4985.6 1431.36  4990.6 1431.36  5008.3 1429.24
  5019.0 1424.92  5019.3 1424.42  5022.8 1424.42  5023.0 1424.92  5028.6 1428.91
  5038.7 1429.36  5048.9 1428.97  5059.0 1429.62  5067.5 1429.54  5099.6 1430.74
  5130.0 1431.30  5137.6 1431.94  5142.7 1431.50  5180.6 1434.02  5198.4 1434.99
  5203.5 1434.41  5221.2 1435.80  5259.2 1437.73  5264.3 1437.47  5292.2 1438.00
#Mann=6,-1,0
  4888.1   0.035       0  4889.6    0.07       0  5019.0    0.05       0
  5023.0    0.07       0  5067.5    0.12       0  5180.6   0.035       0
Bank Sta=5019,5023
Exp/Cntr=0.3,0.1

Type RM Length L Ch R = 1,476,376,376,376
BEGIN DESCRIPTION:
Stream0277_DS 1.0
END DESCRIPTION:
XS GIS Cut Line= 3
      2031274.99     13872575.02      2031375.00     13872425.00
      2031474.98     13872325.02
#Sta/Elev= 30
  4814.4 1430.31  4817.4 1430.31  4843.0 1428.79  4858.0 1427.15  4864.0 1427.03
  4873.0 1426.29  4886.5 1424.65  4894.0 1424.16  4922.6 1423.21  4945.1 1423.37
  4958.6 1423.12  4966.2 1422.89  4972.2 1422.26  4981.2 1422.79  4987.2 1421.37
  4998.2 1421.62  5003.1 1420.15  5021.0 1415.07  5021.2 1414.57  5024.7 1414.57
  5025.0 1415.07  5037.1 1422.90  5051.3 1429.73  5065.4 1429.98  5079.6 1430.58
  5093.7 1432.12  5107.8 1434.24  5122.0 1435.10  5132.6 1436.34  5136.1 1436.34
#Mann=4,-1,0
  4814.4   0.035       0  5003.1    0.07       0  5021.0   0.035       0
  5025.0    0.07       0
Bank Sta=5021,5025
Exp/Cntr=0.3,0.1

Type RM Length L Ch R = 1,100,0,0,0
BEGIN DESCRIPTION:
Stream0277_DS 0.0
END DESCRIPTION:
XS GIS Cut Line= 3
      2031550.77     13872963.11      2031574.78     13872574.55
      2031524.69     13872323.70
#Sta/Elev= 30
  4610.7 1432.93  4759.7 1424.69  4819.2 1424.00  4849.3 1422.77  4879.3 1420.48
  4899.4 1416.27  4909.4 1418.09  4918.4 1417.95  4923.4 1415.77  4949.5 1417.28
  4969.5 1417.28  4979.5 1415.20  5002.3 1413.37  5009.7 1409.21  5017.6 1408.34
  5017.9 1407.84  5021.6 1408.34  5024.7 1409.77  5030.1 1419.11  5040.3 1420.85
  5070.7 1423.90  5075.8 1423.22  5091.3 1425.17  5126.8 1427.05  5152.5 1430.18
  5172.7 1433.94  5177.8 1433.78  5183.1 1435.63  5234.1 1437.05  5255.8 1436.46
#Mann=4,-1,0
  4610.7   0.035       0  4759.7    0.12       0  5017.6    0.05       0
  5021.6    0.12       0
Bank Sta=5017.6,5021.6
Exp/Cntr=0.3,0.1

Chan Stop Cuts=-1