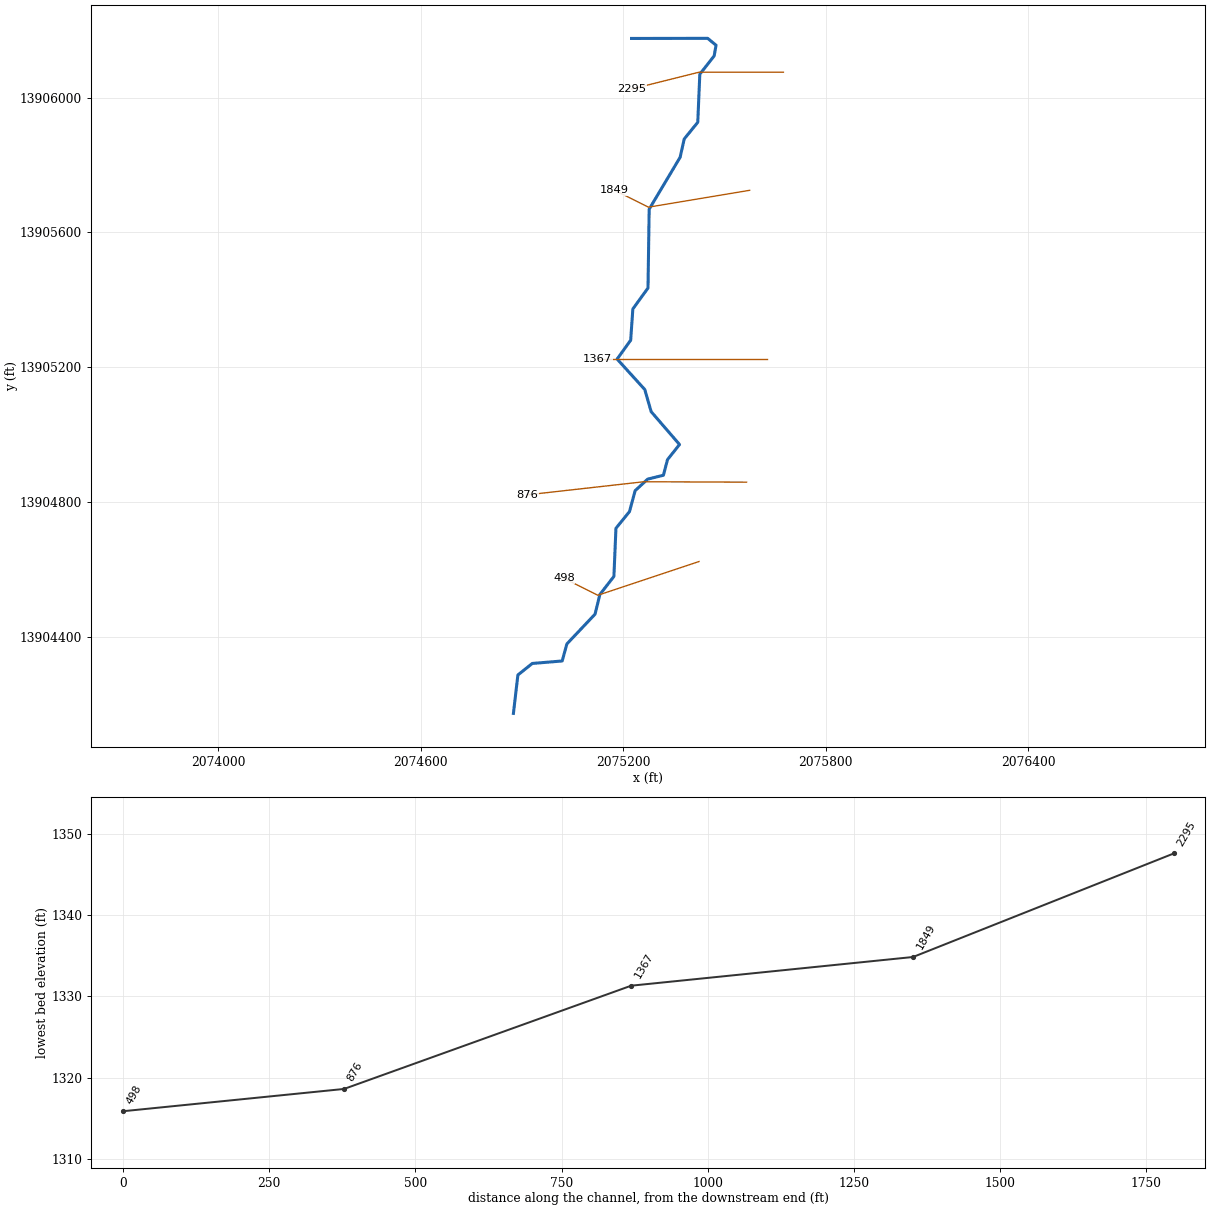
--- Stream0278_DS.prj (project) ---

Proj Title=Stream0278_DS Base Level Engineering
Current Plan=p01
Default Exp/Contr=0.3,0.1
English Units
Geom File=g01
Flow File=f01
Plan File=p01
BEGIN DESCRIPTION:
Stream0278_DS
END DESCRIPTION:

--- Stream0278_DS.p01 (plan) ---

Plan Title=Multiple Run
Short Identifier=Multiple
Geom File=g01
Flow File=f01
Subcritical Flow
K Sum by GR= 0
Std Step Tol= 0.01
Critical Tol= 0.01
Num of Std Step Trials= 20
Max Error Tol= 0.3
Flow Tol Ratio= 0.001
Split Flow NTrial= 30
Split Flow Tol= 0.02
Split Flow Ratio= 0.02
Log Output Level= 0
Friction Slope Method= 1
Unsteady Friction Slope Method= 2
Unsteady Bridges Friction Slope Method= 1
Parabolic Critical Depth
Global Vel Dist=  1 , 1 , 1
Global Log Level= 0
CheckData=True
Encroach Param= -1, 0, 0, 0
BEGIN DESCRIPTION:
Multiple Run
END DESCRIPTION:

--- Stream0278_DS.f01 (steady flow) ---

Flow Title=Multiple
Number of Profiles=7
Profile Names=10-year,25-year,50-year,1pct_min,100-year,1pct_plu,500-year
River Rch & RM= Stream0278_DS,Reach-1,2295
     634    1043    1423     944    1883    3757    3255
River Rch & RM= Stream0278_DS,Reach-1,1849
     715    1182    1617    1075    2145    4281    3728
Boundary for River Rch & Prof#=Stream0278_DS,Reach-1,1
Up Type=0
Dn Type=3
Dn Slope=0.005
Boundary for River Rch & Prof#=Stream0278_DS,Reach-1,2
Up Type=0
Dn Type=3
Dn Slope=0.005
Boundary for River Rch & Prof#=Stream0278_DS,Reach-1,3
Up Type=0
Dn Type=3
Dn Slope=0.005
Boundary for River Rch & Prof#=Stream0278_DS,Reach-1,4
Up Type=0
Dn Type=3
Dn Slope=0.005
Boundary for River Rch & Prof#=Stream0278_DS,Reach-1,5
Up Type=0
Dn Type=3
Dn Slope=0.005
Boundary for River Rch & Prof#=Stream0278_DS,Reach-1,6
Up Type=0
Dn Type=3
Dn Slope=0.005
Boundary for River Rch & Prof#=Stream0278_DS,Reach-1,7
Up Type=0
Dn Type=3
Dn Slope=0.005

--- Stream0278_DS.g01 (geometry) ---

Geom Title=Existing Conditions

River Reach=Stream0278_DS,Reach-1
Reach XY= 30
      2075225.00     13906175.00      2075450.62     13906175.34
      2075475.42     13906154.91      2075469.81     13906123.23
      2075427.31     13906069.09      2075421.24     13905926.56
      2075381.12     13905877.18      2075368.92     13905822.80
      2075277.24     13905669.07      2075273.78     13905435.50
      2075228.85     13905373.40      2075222.44     13905280.89
      2075182.32     13905224.90      2075264.17     13905134.68
      2075283.20     13905068.95      2075367.17     13904971.73
      2075331.56     13904926.96      2075319.41     13904880.63
      2075272.80     13904869.11      2075235.69     13904834.98
      2075218.85     13904772.85      2075178.76     13904723.44
      2075172.75     13904580.93      2075131.14     13904527.17
      2075116.84     13904468.95      2075033.32     13904380.70
      2075019.53     13904330.26      2074930.78     13904322.90
      2074888.17     13904288.78      2074875.00     13904175.00

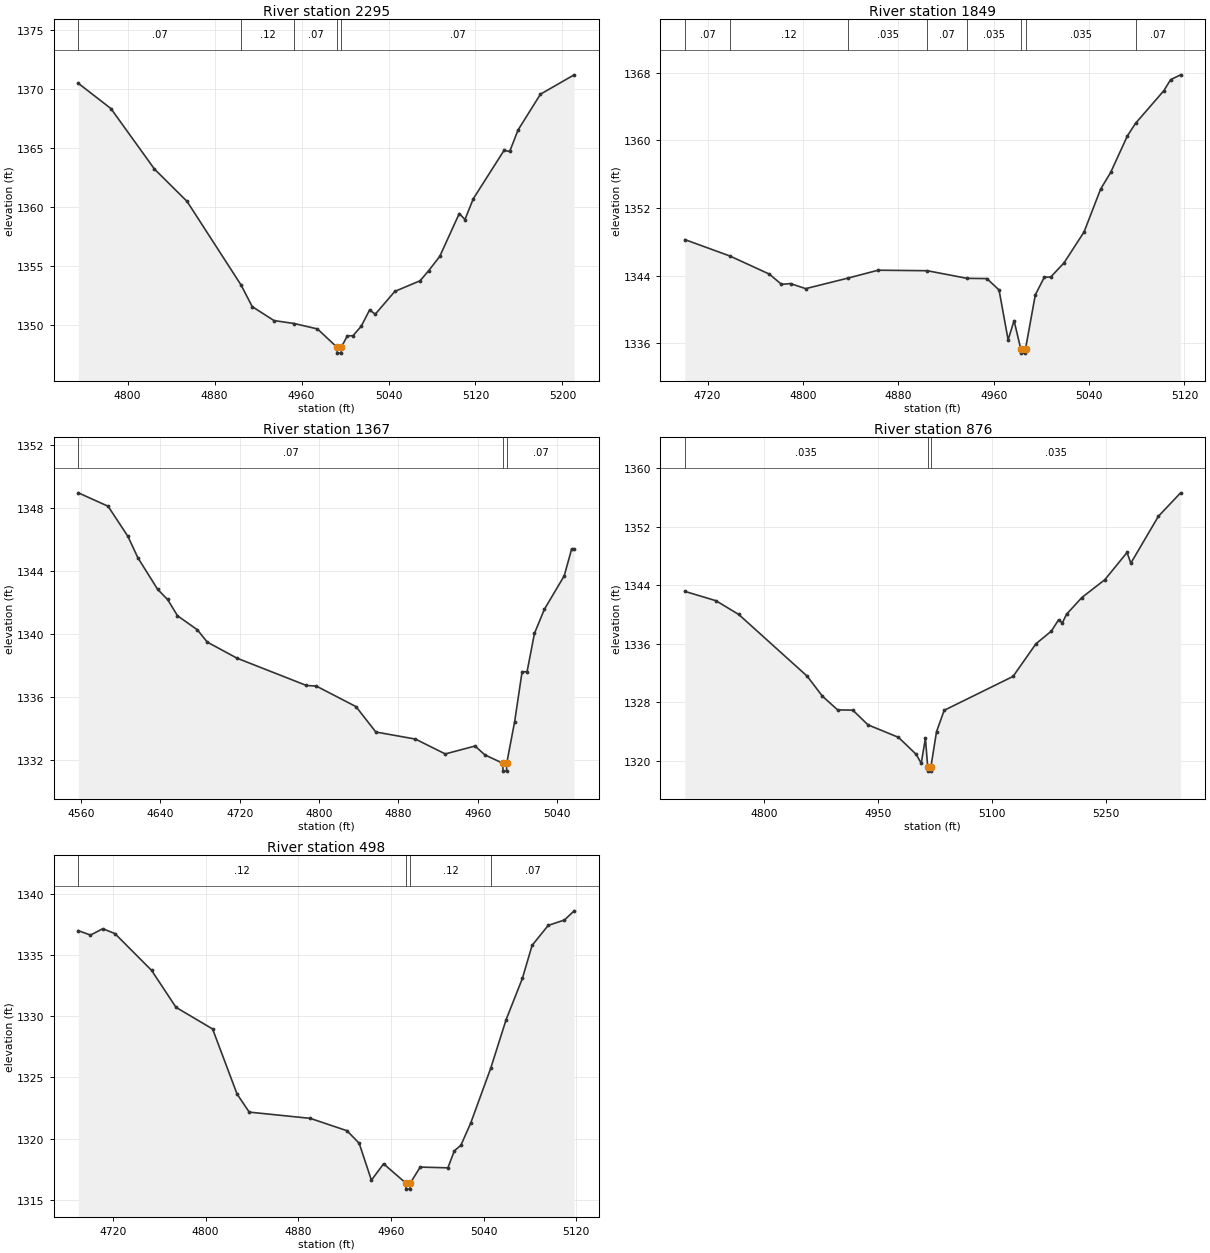
Type RM Length L Ch R = 1,2295,446,446,446
BEGIN DESCRIPTION:
Stream0278_DS 5.0
END DESCRIPTION:
XS GIS Cut Line= 3
      2075675.00     13906075.00      2075425.00     13906075.00
      2075224.96     13906024.99
#Sta/Elev= 30
  4754.6 1370.44  4784.6 1368.30  4824.6 1363.18  4854.6 1360.44  4904.4 1353.34
  4914.6 1351.52  4934.6 1350.34  4953.1 1350.09  4974.6 1349.63  4992.6 1348.08
  4992.9 1347.58  4996.4 1347.58  4996.6 1348.08  5002.1 1349.05  5007.2 1349.05
  5014.9 1349.86  5022.6 1351.24  5027.8 1350.88  5045.8 1352.81  5069.0 1353.71
  5076.8 1354.55  5087.1 1355.77  5105.1 1359.41  5110.3 1358.90  5118.0 1360.66
  5146.3 1364.76  5151.5 1364.67  5159.2 1366.49  5179.8 1369.52  5210.8 1371.16
#Mann=5,-1,0
  4754.6    0.07       0  4904.4    0.12       0  4953.1    0.07       0
  4992.6    0.05       0  4996.6    0.07       0
Bank Sta=4992.6,4996.6
Exp/Cntr=0.3,0.1

Type RM Length L Ch R = 1,1849,482,482,482
BEGIN DESCRIPTION:
Stream0278_DS 4.0
END DESCRIPTION:
XS GIS Cut Line= 3
      2075574.97     13905725.00      2075275.00     13905675.00
      2075175.01     13905724.99
#Sta/Elev= 30
  4700.9 1348.26  4738.7 1346.32  4771.8 1344.18  4782.0 1342.97  4789.6 1343.06
  4802.3 1342.46  4838.1 1343.72  4863.1 1344.64  4904.3 1344.58  4937.6 1343.68
  4954.3 1343.65  4964.5 1342.30  4972.1 1336.41  4977.1 1338.68  4982.7 1335.34
  4983.0 1334.84  4986.5 1334.84  4986.7 1335.34  4994.9 1341.72  5002.5 1343.83
  5007.8 1343.83  5019.0 1345.51  5035.8 1349.16  5049.7 1354.23  5058.1 1356.19
  5072.1 1360.50  5079.0 1362.00  5102.8 1365.87  5108.4 1367.16  5116.8 1367.73
#Mann=8,-1,0
  4700.9    0.07       0  4738.7    0.12       0  4838.1   0.035       0
  4904.3    0.07       0  4937.6   0.035       0  4982.7   0.035       0
  4986.7   0.035       0  5079.0    0.07       0
Bank Sta=4982.7,4986.7
Exp/Cntr=0.3,0.1

Type RM Length L Ch R = 1,1367,491,491,491
BEGIN DESCRIPTION:
Stream0278_DS 3.0
END DESCRIPTION:
XS GIS Cut Line= 3
      2075625.04     13905225.00      2075175.00     13905225.00
      2075125.04     13905225.00
#Sta/Elev= 30
  4557.3 1348.95  4587.3 1348.10  4607.3 1346.19  4617.3 1344.84  4637.3 1342.83
  4647.3 1342.19  4657.3 1341.16  4677.3 1340.27  4687.3 1339.49  4717.3 1338.47
  4787.3 1336.74  4797.3 1336.70  4837.3 1335.40  4857.3 1333.79  4897.3 1333.34
  4927.3 1332.40  4957.3 1332.90  4967.3 1332.34  4985.3 1331.81  4985.6 1331.31
  4989.1 1331.31  4989.3 1331.81  4997.3 1334.45  5004.8 1337.61  5009.8 1337.61
  5017.3 1340.05  5027.3 1341.57  5047.3 1343.69  5054.8 1345.40  5057.3 1345.40
#Mann=3,-1,0
  4557.3    0.07       0  4985.3    0.05       0  4989.3    0.07       0
Bank Sta=4985.3,4989.3
Exp/Cntr=0.3,0.1

Type RM Length L Ch R = 1,876,378,378,378
BEGIN DESCRIPTION:
Stream0278_DS 2.0
END DESCRIPTION:
XS GIS Cut Line= 3
      2075565.96     13904860.13      2075261.67     13904861.42
      2074915.94     13904822.57
#Sta/Elev= 30
  4695.7 1343.17  4736.7 1341.89  4766.7 1340.01  4856.7 1331.58  4876.7 1328.85
  4896.7 1326.98  4916.7 1326.94  4936.7 1324.93  4976.7 1323.23  5000.0 1320.91
  5006.7 1319.68  5012.2 1323.09  5015.3 1319.11  5015.5 1318.61  5019.0 1318.61
  5019.3 1319.11  5026.8 1323.99  5036.9 1326.92  5127.5 1331.55  5157.7 1336.02
  5177.8 1337.73  5187.3 1339.27  5192.3 1338.86  5197.9 1340.05  5218.0 1342.33
  5248.2 1344.76  5277.4 1348.48  5282.4 1347.02  5318.7 1353.43  5347.9 1356.63
#Mann=3,-1,0
  4695.7   0.035       0  5015.3   0.035       0  5019.3   0.035       0
Bank Sta=5015.3,5019.3
Exp/Cntr=0.3,0.1

Type RM Length L Ch R = 1,498,0,0,0
BEGIN DESCRIPTION:
Stream0278_DS 1.0
END DESCRIPTION:
XS GIS Cut Line= 3
      2075424.97     13904624.99      2075125.00     13904525.00
      2075025.00     13904575.00
#Sta/Elev= 30
  4690.2 1336.98  4700.7 1336.62  4711.3 1337.14  4721.8 1336.74  4753.4 1333.74
  4774.5 1330.72  4806.1 1328.95  4827.2 1323.64  4837.7 1322.16  4890.4 1321.65
  4922.1 1320.64  4932.6 1319.62  4943.2 1316.60  4953.7 1317.94  4972.8 1316.37
  4973.0 1315.87  4976.5 1315.87  4976.8 1316.37  4985.3 1317.67  5009.2 1317.61
  5014.8 1319.00  5020.4 1319.45  5028.8 1321.24  5046.2 1325.75  5059.5 1329.72
  5073.5 1333.08  5081.9 1335.78  5095.8 1337.41  5109.8 1337.85  5118.2 1338.60
#Mann=4,-1,0
  4690.2    0.12       0  4972.8    0.05       0  4976.8    0.12       0
  5046.2    0.07       0
Bank Sta=4972.8,4976.8
Exp/Cntr=0.3,0.1

Chan Stop Cuts=-1