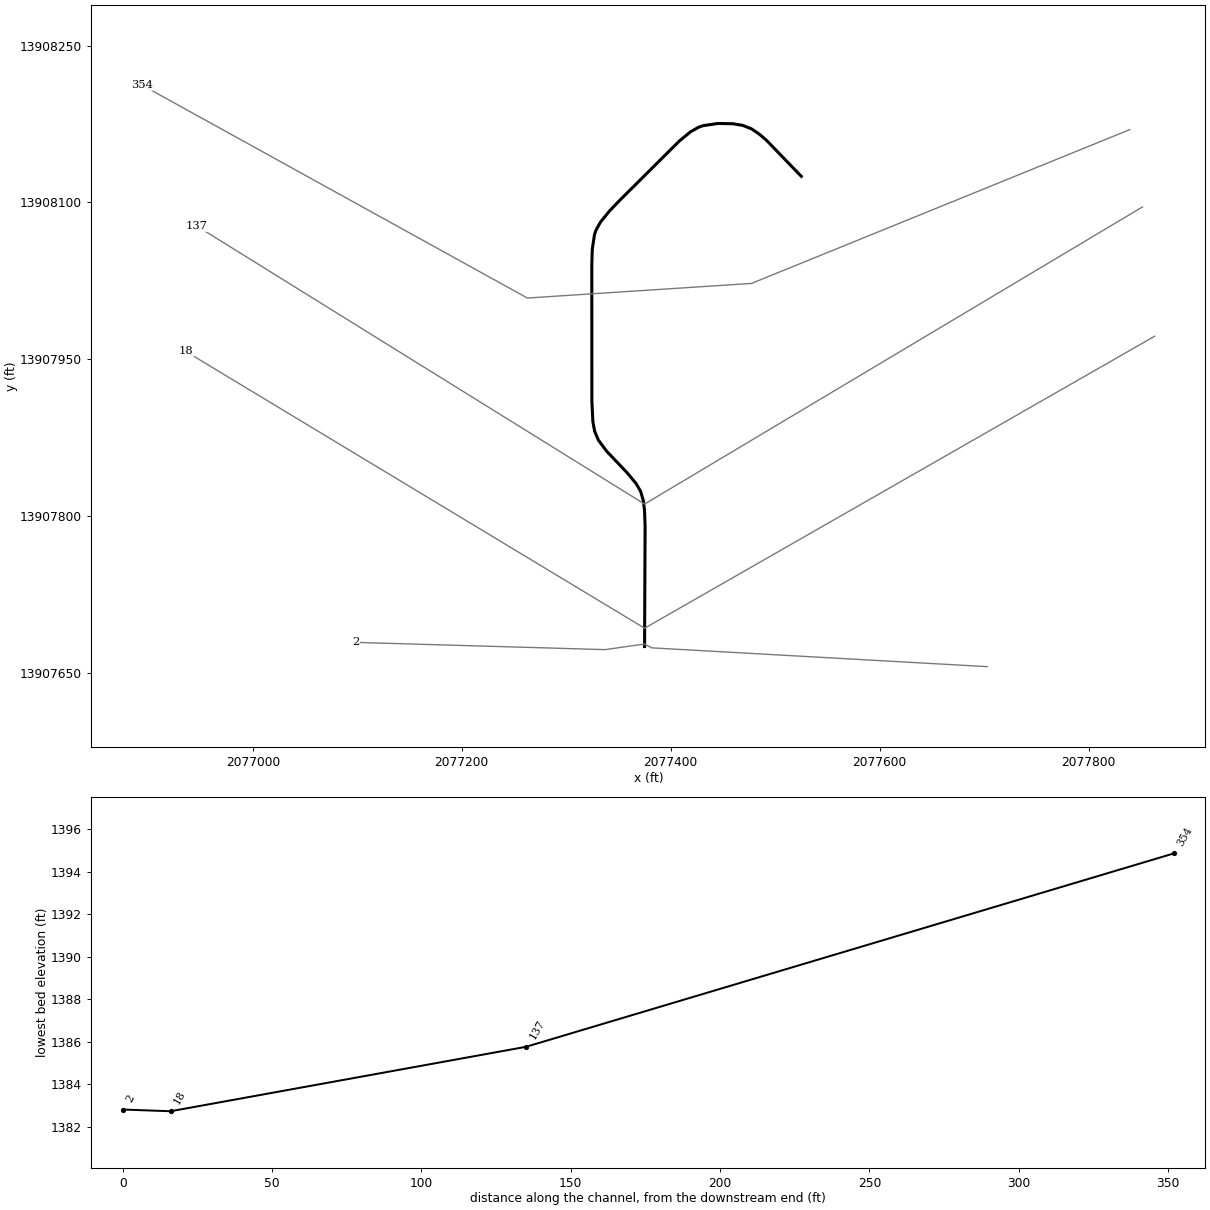
--- Stream0281_DS.prj (project) ---

Proj Title=Stream0281_DS Base Level Engineering
Current Plan=p01
Default Exp/Contr=0.3,0.1
English Units
Geom File=g01
Flow File=f01
Plan File=p01
Y Axis Title=Elevation
X Axis Title(PF)=Main Channel Distance
X Axis Title(XS)=Station
BEGIN DESCRIPTION:
Stream0281_DS
END DESCRIPTION:
DSS Export Rating Curves= 0
DSS Export Rating Curve Sorted= 0
DSS Export Volume Flow Curves= 0
DXF OffsetX= 0
DXF OffsetY= 0
DXF ScaleX= 1
DXF ScaleY= 10

--- Stream0281_DS.p01 (plan) ---

Plan Title=Multiple Run
Short Identifier=Multiple
Geom File=g01
Flow File=f01
Subcritical Flow
K Sum by GR= 0
Std Step Tol= 0.01
Critical Tol= 0.01
Num of Std Step Trials= 20
Max Error Tol= 0.3
Flow Tol Ratio= 0.001
Split Flow NTrial= 30
Split Flow Tol= 0.02
Split Flow Ratio= 0.02
Log Output Level= 0
Friction Slope Method= 1
Unsteady Friction Slope Method= 2
Unsteady Bridges Friction Slope Method= 1
Parabolic Critical Depth
Global Vel Dist=  1 , 1 , 1
Global Log Level= 0
CheckData=True
Encroach Param= -1, 0, 0, 0
BEGIN DESCRIPTION:
Multiple Run
END DESCRIPTION:

--- Stream0281_DS.f01 (steady flow) ---

Flow Title=Multiple
Number of Profiles=7
Profile Names=10-year,25-year,50-year,1pct_min,100-year,1pct_plu,500-year
River Rch & RM= Stream0281_DS,Reach-1,354
     771    1297    1796    1211    2417    4823    4318
River Rch & RM= Stream0281_DS,Reach-1,18
    1229    2126    3001    2057    4104    8188    7583
Boundary for River Rch & Prof#=Stream0281_DS,Reach-1,1
Up Type=0
Dn Type=3
Dn Slope=0.005
Boundary for River Rch & Prof#=Stream0281_DS,Reach-1,2
Up Type=0
Dn Type=3
Dn Slope=0.005
Boundary for River Rch & Prof#=Stream0281_DS,Reach-1,3
Up Type=0
Dn Type=3
Dn Slope=0.005
Boundary for River Rch & Prof#=Stream0281_DS,Reach-1,4
Up Type=0
Dn Type=3
Dn Slope=0.005
Boundary for River Rch & Prof#=Stream0281_DS,Reach-1,5
Up Type=0
Dn Type=3
Dn Slope=0.005
Boundary for River Rch & Prof#=Stream0281_DS,Reach-1,6
Up Type=0
Dn Type=3
Dn Slope=0.005
Boundary for River Rch & Prof#=Stream0281_DS,Reach-1,7
Up Type=0
Dn Type=3
Dn Slope=0.005

--- Stream0281_DS.g01 (geometry) ---

Geom Title=Existing Conditions
Program Version=4.10

River Reach=Stream0281_DS   ,Reach-1
Reach XY= 30
        2077525.       13908125.      2077491.92     13908159.26
      2077484.79      13908165.4      2077477.35     13908170.43
      2077468.94     13908173.77      2077459.56     13908175.33
      2077445.05     13908175.58      2077430.96     13908173.47
      2077426.56     13908171.93      2077418.89     13908167.54
      2077408.27     13908158.78      2077351.14     13908101.95
      2077341.41      13908091.8       2077332.8     13908081.21
      2077328.53     13908073.55      2077327.05     13908069.16
      2077324.95     13908055.02       2077324.5      13908040.2
      2077324.57     13907909.82      2077325.52     13907890.22
      2077327.26     13907880.94      2077330.74     13907872.66
      2077338.79     13907861.85       2077358.1     13907841.57
      2077366.87     13907831.06      2077371.25     13907823.45
      2077373.83     13907814.52      2077374.99       13907805.
      2077375.51     13907790.21        2077375.       13907675.

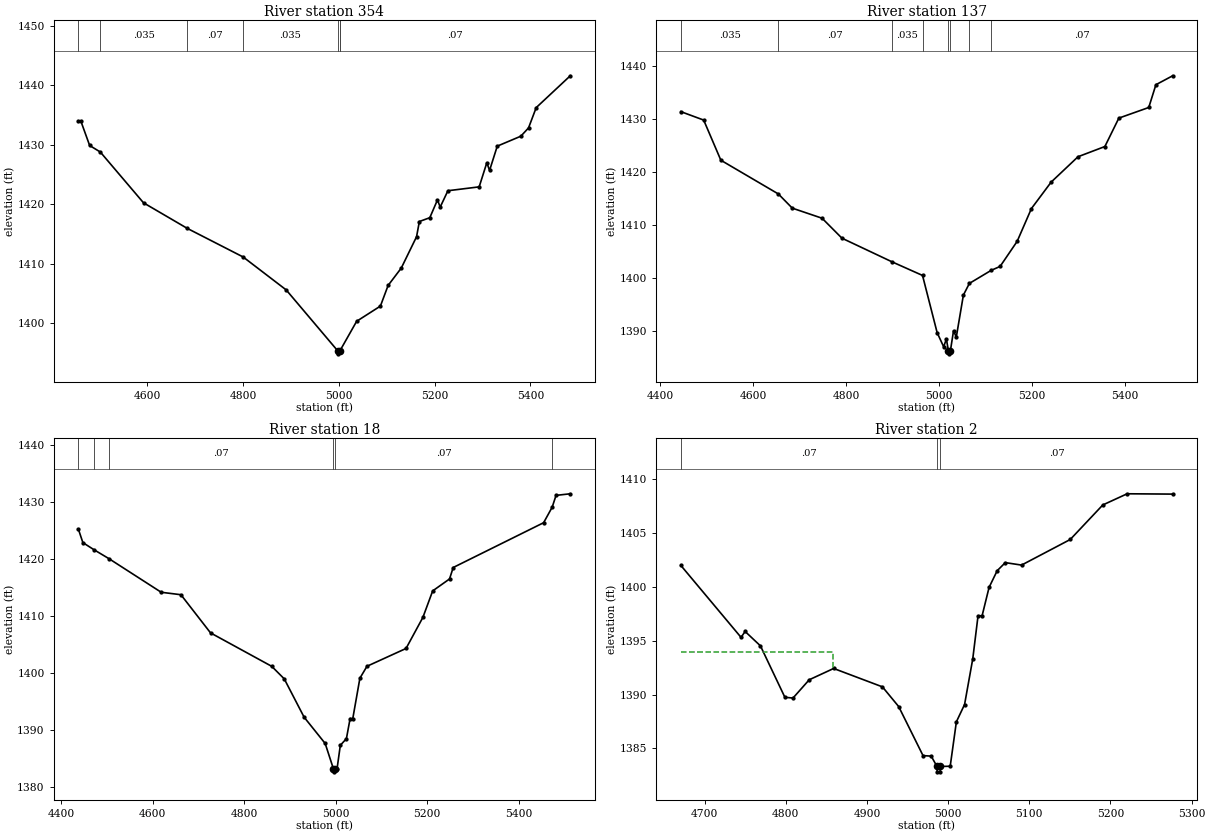
Type RM Length L Ch R = 1 ,354     ,217,217,217
BEGIN DESCRIPTION:
Stream0281_DS 2.0
END DESCRIPTION:
XS GIS Cut Line= 4
      2077839.44     13908169.74       2077477.3      13908022.5
       2077262.8     13908008.55      2076893.94     13908212.35
#Sta/Elev= 30
  4456.1 1433.95  4461.2 1433.95  4479.5 1429.87  4501.8 1428.77    4592 1420.24
  4683.3 1415.95  4800.1 1411.14    4890 1405.61  4997.7 1395.37  4997.9 1394.87
  5001.7 1395.37  5002.5 1395.41  5037.2 1400.34  5086.8 1402.89  5102.9 1406.36
  5130.4 1409.28  5162.3 1414.54  5168.2  1417.1    5190 1417.74    5206 1420.73
  5211.7 1419.52  5227.8 1422.27  5293.1 1422.92  5309.1 1426.98  5314.8 1425.68
  5330.9 1429.76  5380.1 1431.43  5396.2 1432.82  5412.2 1436.23  5483.4 1441.58
#Mann= 7 ,-1 , 0
  4456.1     .07       0  4501.8    .035       0  4683.3     .07       0
  4800.1    .035       0  4997.7    .035       0  5001.7    .035       0
  5002.5     .07       0
Bank Sta=4997.7,5001.7
XS Rating Curve= 0 ,0
Exp/Cntr=0.3,0.1

Type RM Length L Ch R = 1 ,137     ,119,119,119
BEGIN DESCRIPTION:
Stream0281_DS 1.0
END DESCRIPTION:
XS GIS Cut Line= 3
      2077851.51      13908095.7        2077375.     13907811.36
      2076946.55     13908077.34
#Sta/Elev= 30
  4444.2 1431.37  4493.4 1429.78  4530.4 1422.22  4654.2 1415.87  4684.2  1413.2
  4748.4  1411.3  4791.2 1407.54  4898.8  1403.1  4964.7 1400.53  4996.2 1389.75
  5010.2  1387.1  5016.1 1388.56  5020.6 1386.27  5020.9 1385.77  5024.6 1386.27
  5031.5 1390.13  5037.4 1388.91  5052.7 1396.83  5065.6 1399.03  5112.4 1401.48
  5131.8 1402.23  5168.5 1406.95  5199.2 1413.12  5241.7  1418.1  5299.6 1422.88
  5357.4  1424.8  5387.5 1430.15  5451.9 1432.15  5467.3 1436.44  5503.4 1438.12
#Mann= 8 ,-1 , 0
  4444.2    .035       0  4654.2     .07       0  4898.8    .035       0
  4964.7     .07       0  5020.6     .05       0  5024.6     .07       0
  5065.6    .035       0  5112.4     .07       0
Bank Sta=5020.6,5024.6
XS Rating Curve= 0 ,0
Exp/Cntr=0.3,0.1

Type RM Length L Ch R = 1 ,18      ,16,16,16
BEGIN DESCRIPTION:
Stream0281_DS 0.1
END DESCRIPTION:
XS GIS Cut Line= 3
      2077863.31     13907972.05      2077375.04     13907692.56
      2076935.77     13907957.53
#Sta/Elev= 30
  4437.4 1425.23  4447.1 1422.91  4471.1 1421.68  4504.5 1420.08  4618.4 1414.21
  4661.5 1413.78  4726.3 1407.09  4860.1 1401.23  4887.5 1399.03  4930.9 1392.32
    4977 1387.71  4995.1 1383.24  4995.4 1382.74  4999.1 1383.24  5002.9 1383.24
  5010.1 1387.39  5023.4 1388.55  5031.5 1392.08  5037.3 1392.05  5052.9 1399.15
  5068.4 1401.24  5153.8 1404.36  5190.7 1409.81  5212.1 1414.45  5248.9 1416.54
    5257 1418.55  5454.7  1426.4  5473.4 1429.12  5481.9 1431.19    5513 1431.47
#Mann= 6 ,-1 , 0
  4437.4     .07       0  4471.1    .035       0  4504.5     .07       0
  4995.1     .05       0  4999.1     .07       0  5473.4     .12       0
Bank Sta=4995.1,4999.1
XS Rating Curve= 0 ,0
Exp/Cntr=0.3,0.1

Type RM Length L Ch R = 1 ,2       ,0,0,0
BEGIN DESCRIPTION:
Stream0281_DS 0.0
END DESCRIPTION:
XS GIS Cut Line= 5
      2077702.98     13907655.78      2077381.73     13907673.78
      2077374.99     13907677.44      2077337.09     13907672.07
      2077098.89     13907678.99
#Sta/Elev= 30
  4670.6 1402.01  4744.8 1395.32  4749.8 1395.87  4768.7 1394.53  4798.8 1389.75
  4808.8 1389.68  4828.8 1391.38  4858.9 1392.43    4919 1390.72    4939 1388.89
    4969 1384.33  4979.1 1384.28  4986.2 1383.32  4986.5 1382.82    4990 1382.82
  4990.2 1383.32  5002.5 1383.34  5010.1 1387.47  5020.2 1389.08  5030.3 1393.33
  5036.8 1397.33  5041.8 1397.33  5050.4 1399.97  5060.4 1401.52  5070.4 1402.27
  5090.4 1402.04  5150.4 1404.42  5190.5 1407.63  5220.5 1408.67  5276.6 1408.64
#Mann= 3 ,-1 , 0
  4670.6     .07       0  4986.2     .05       0  4990.2     .07       0
#XS Ineff= 2 , 0
       0 4857.65    1394               0
Permanent Ineff=
       F       F
Bank Sta=4986.2,4990.2
XS Rating Curve= 0 ,0
Exp/Cntr=0.3,0.1

Chan Stop Cuts=-1
Use User Specified Reach Order=0
Composite Channel Slope=5