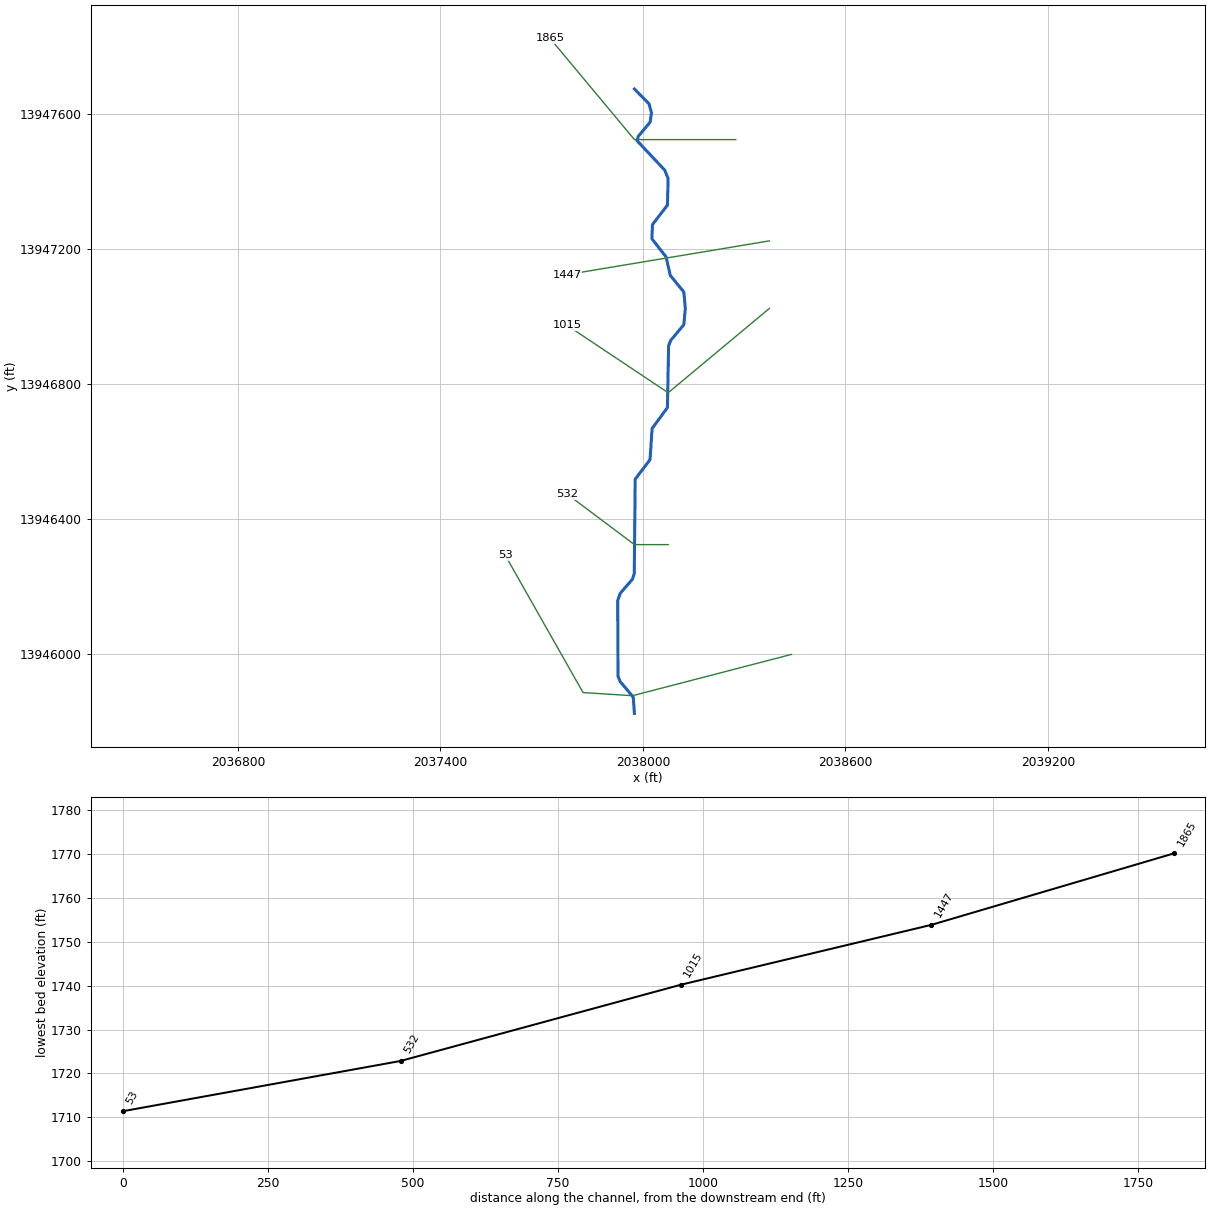
--- Stream0282_DS.prj (project) ---

Proj Title=Stream0282_DS Base Level Engineering
Current Plan=p01
Default Exp/Contr=0.3,0.1
English Units
Geom File=g01
Flow File=f01
Plan File=p01
BEGIN DESCRIPTION:
Stream0282_DS
END DESCRIPTION:

--- Stream0282_DS.p01 (plan) ---

Plan Title=Multiple Run
Short Identifier=Multiple
Geom File=g01
Flow File=f01
Subcritical Flow
K Sum by GR= 0
Std Step Tol= 0.01
Critical Tol= 0.01
Num of Std Step Trials= 20
Max Error Tol= 0.3
Flow Tol Ratio= 0.001
Split Flow NTrial= 30
Split Flow Tol= 0.02
Split Flow Ratio= 0.02
Log Output Level= 0
Friction Slope Method= 1
Unsteady Friction Slope Method= 2
Unsteady Bridges Friction Slope Method= 1
Parabolic Critical Depth
Global Vel Dist=  1 , 1 , 1
Global Log Level= 0
CheckData=True
Encroach Param= -1, 0, 0, 0
BEGIN DESCRIPTION:
Multiple Run
END DESCRIPTION:

--- Stream0282_DS.f01 (steady flow) ---

Flow Title=Multiple
Number of Profiles=7
Profile Names=10-year,25-year,50-year,1pct_min,100-year,1pct_plu,500-year
River Rch & RM= Stream0282_DS,Reach-1,1865
     255     403     536     349     696    1389    1157
River Rch & RM= Stream0282_DS,Reach-1,1447
     390     636     862     571    1139    2273    1964
Boundary for River Rch & Prof#=Stream0282_DS,Reach-1,1
Up Type=0
Dn Type=3
Dn Slope=0.005
Boundary for River Rch & Prof#=Stream0282_DS,Reach-1,2
Up Type=0
Dn Type=3
Dn Slope=0.005
Boundary for River Rch & Prof#=Stream0282_DS,Reach-1,3
Up Type=0
Dn Type=3
Dn Slope=0.005
Boundary for River Rch & Prof#=Stream0282_DS,Reach-1,4
Up Type=0
Dn Type=3
Dn Slope=0.005
Boundary for River Rch & Prof#=Stream0282_DS,Reach-1,5
Up Type=0
Dn Type=3
Dn Slope=0.005
Boundary for River Rch & Prof#=Stream0282_DS,Reach-1,6
Up Type=0
Dn Type=3
Dn Slope=0.005
Boundary for River Rch & Prof#=Stream0282_DS,Reach-1,7
Up Type=0
Dn Type=3
Dn Slope=0.005

--- Stream0282_DS.g01 (geometry) ---

Geom Title=Existing Conditions

River Reach=Stream0282_DS,Reach-1
Reach XY= 30
      2037975.00     13947675.00      2038018.02     13947631.14
      2038025.46     13947604.75      2038021.39     13947576.58
      2037986.35     13947534.87      2037982.81     13947521.60
      2038064.52     13947434.79      2038074.75     13947409.78
      2038072.81     13947330.97      2038028.37     13947273.26
      2038026.80     13947231.11      2038068.85     13947177.20
      2038081.12     13947122.82      2038121.33     13947073.42
      2038125.82     13947025.00      2038121.30     13946976.60
      2038083.15     13946931.06      2038076.22     13946914.50
      2038072.74     13946730.94      2038027.36     13946669.02
      2038021.14     13946576.60      2037977.26     13946519.06
      2037974.48     13946240.22      2037969.25     13946222.67
      2037933.14     13946181.06      2037925.52     13946159.78
      2037926.12     13945935.46      2037932.89     13945918.84
      2037971.35     13945873.49      2037975.00     13945825.00

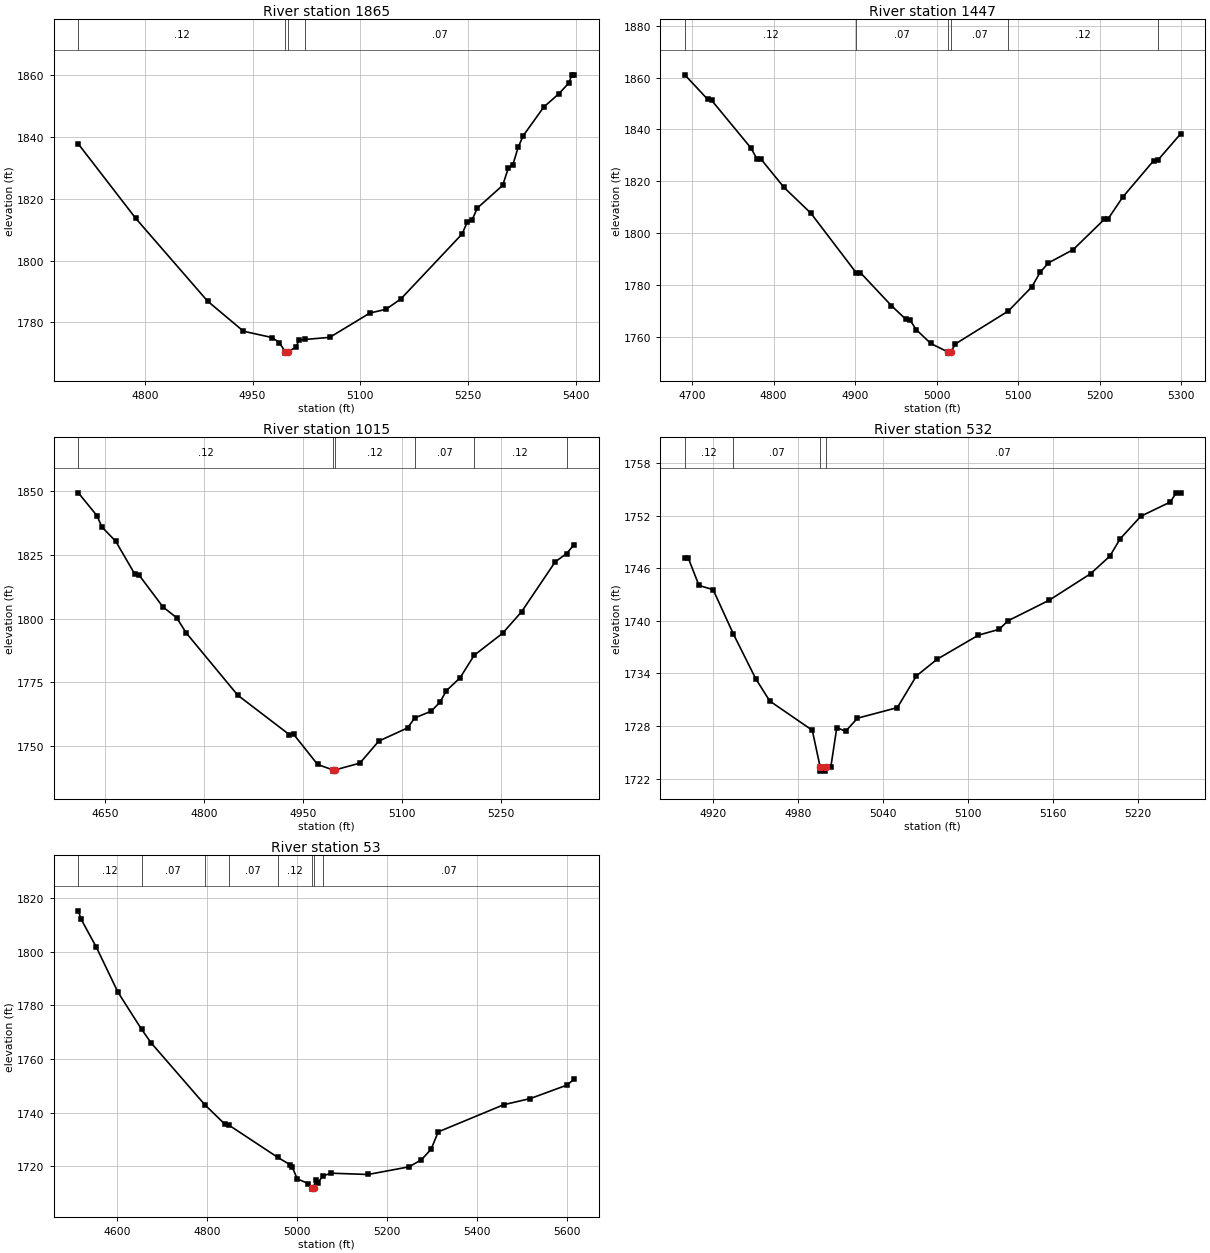
Type RM Length L Ch R = 1,1865,418,418,418
BEGIN DESCRIPTION:
Stream0282_DS 4.0
END DESCRIPTION:
XS GIS Cut Line= 3
      2038275.05     13947525.00      2037975.00     13947525.00
      2037724.97     13947825.03
#Sta/Elev= 30
  4707.3 1837.80  4787.3 1813.70  4887.3 1786.92  4937.3 1777.17  4977.3 1775.11
  4987.3 1773.47  4995.3 1770.58  4995.6 1770.08  4999.3 1770.58  5010.6 1771.98
  5014.5 1774.29  5023.6 1774.51  5057.5 1775.19  5113.4 1783.06  5135.6 1784.25
  5156.4 1787.59  5241.7 1808.62  5248.8 1812.40  5255.3 1813.02  5263.1 1817.06
  5298.3 1824.38  5306.1 1829.90  5312.6 1831.10  5319.8 1836.67  5326.9 1840.44
  5355.6 1849.76  5376.4 1854.01  5390.7 1857.58  5394.6 1860.18  5397.9 1860.18
#Mann=4,-1,0
  4707.3    0.12       0  4995.3    0.05       0  4999.3    0.12       0
  5023.6    0.07       0
Bank Sta=4995.3,4999.3
Exp/Cntr=0.3,0.1

Type RM Length L Ch R = 1,1447,432,432,432
BEGIN DESCRIPTION:
Stream0282_DS 3.0
END DESCRIPTION:
XS GIS Cut Line= 3
      2038375.01     13947225.00      2038075.00     13947175.00
      2037774.99     13947125.00
#Sta/Elev= 30
  4691.1 1861.05  4719.0 1851.66  4724.1 1851.19  4772.2 1832.88  4779.8 1828.54
  4784.9 1828.44  4812.8 1817.67  4845.7 1807.76  4901.4 1784.78  4906.5 1784.84
  4944.6 1772.10  4962.3 1766.85  4967.4 1766.55  4975.0 1762.88  4992.7 1757.58
  5013.5 1754.32  5013.8 1753.82  5017.5 1754.32  5023.1 1757.37  5088.1 1770.06
  5116.9 1779.37  5127.0 1784.94  5137.2 1788.58  5167.6 1793.70  5205.6 1805.32
  5210.7 1805.68  5228.4 1813.94  5266.4 1828.02  5271.7 1828.25  5299.4 1838.32
#Mann=6,-1,0
  4691.1    0.12       0  4901.4    0.07       0  5013.5    0.05       0
  5017.5    0.07       0  5088.1    0.12       0  5271.7    0.07       0
Bank Sta=5013.5,5017.5
Exp/Cntr=0.3,0.1

Type RM Length L Ch R = 1,1015,483,483,483
BEGIN DESCRIPTION:
Stream0282_DS 2.0
END DESCRIPTION:
XS GIS Cut Line= 3
      2038375.00     13947025.00      2038075.00     13946775.00
      2037774.97     13946975.02
#Sta/Elev= 30
  4610.0 1849.26  4638.0 1840.36  4645.8 1835.84  4666.6 1830.29  4695.3 1817.51
  4701.8 1817.09  4738.2 1804.54  4759.0 1800.29  4773.4 1794.36  4851.5 1769.94
  4929.6 1754.51  4936.1 1754.64  4972.5 1742.80  4995.3 1740.69  4995.5 1740.19
  4999.3 1740.69  5036.6 1743.34  5065.1 1751.96  5108.7 1757.12  5119.7 1761.05
  5144.7 1763.69  5158.2 1767.34  5167.3 1771.65  5188.3 1776.78  5209.6 1785.58
  5252.9 1794.27  5281.4 1802.64  5332.5 1822.24  5349.5 1825.43  5361.1 1828.95
#Mann=6,-1,0
  4610.0    0.12       0  4995.3    0.05       0  4999.3    0.12       0
  5119.7    0.07       0  5209.6    0.12       0  5349.5    0.07       0
Bank Sta=4995.3,4999.3
Exp/Cntr=0.3,0.1

Type RM Length L Ch R = 1,532,479,479,479
BEGIN DESCRIPTION:
Stream0282_DS 1.0
END DESCRIPTION:
XS GIS Cut Line= 3
      2038074.98     13946325.00      2037975.00     13946325.00
      2037774.99     13946475.01
#Sta/Elev= 30
  4900.1 1747.13  4902.6 1747.13  4910.1 1744.03  4920.1 1743.54  4934.3 1738.52
  4950.1 1733.41  4960.1 1730.84  4990.1 1727.51  4995.6 1723.35  4995.8 1722.85
  4999.3 1722.85  4999.6 1723.35  5003.2 1723.35  5007.4 1727.82  5013.6 1727.39
  5022.0 1728.89  5050.1 1730.09  5063.6 1733.71  5078.2 1735.61  5107.4 1738.36
  5122.0 1739.02  5128.2 1739.99  5157.4 1742.35  5186.5 1745.36  5200.1 1747.36
  5207.4 1749.34  5222.0 1751.92  5242.8 1753.54  5247.0 1754.59  5250.1 1754.59
#Mann=4,-1,0
  4900.1    0.12       0  4934.3    0.07       0  4995.6    0.05       0
  4999.6    0.07       0
Bank Sta=4995.6,4999.6
Exp/Cntr=0.3,0.1

Type RM Length L Ch R = 1,53,0,0,0
BEGIN DESCRIPTION:
Stream0282_DS 0.0
END DESCRIPTION:
XS GIS Cut Line= 4
      2038440.32     13945999.73      2037969.26     13945877.34
      2037822.70     13945886.69      2037591.75     13946294.12
#Sta/Elev= 30
  4513.3 1815.31  4518.8 1812.39  4553.5 1801.67  4601.5 1784.88  4653.7 1771.12
  4675.1 1766.01  4794.0 1742.98  4839.1 1735.64  4847.5 1735.35  4956.8 1723.23
  4983.7 1720.55  4989.2 1719.49  4999.6 1715.26  5024.3 1713.48  5032.3 1711.91
  5032.6 1711.41  5036.3 1711.91  5040.6 1714.92  5045.6 1713.82  5056.7 1716.30
  5074.4 1717.36  5157.2 1716.88  5248.2 1719.73  5275.6 1722.36  5297.2 1726.28
  5313.1 1732.78  5458.8 1742.93  5517.9 1745.23  5598.5 1750.20  5615.2 1752.41
#Mann=8,-1,0
  4513.3    0.12       0  4653.7    0.07       0  4794.0    0.12       0
  4847.5    0.07       0  4956.8    0.12       0  5032.3    0.05       0
  5036.3    0.12       0  5056.7    0.07       0
Bank Sta=5032.3,5036.3
Exp/Cntr=0.3,0.1

Chan Stop Cuts=-1