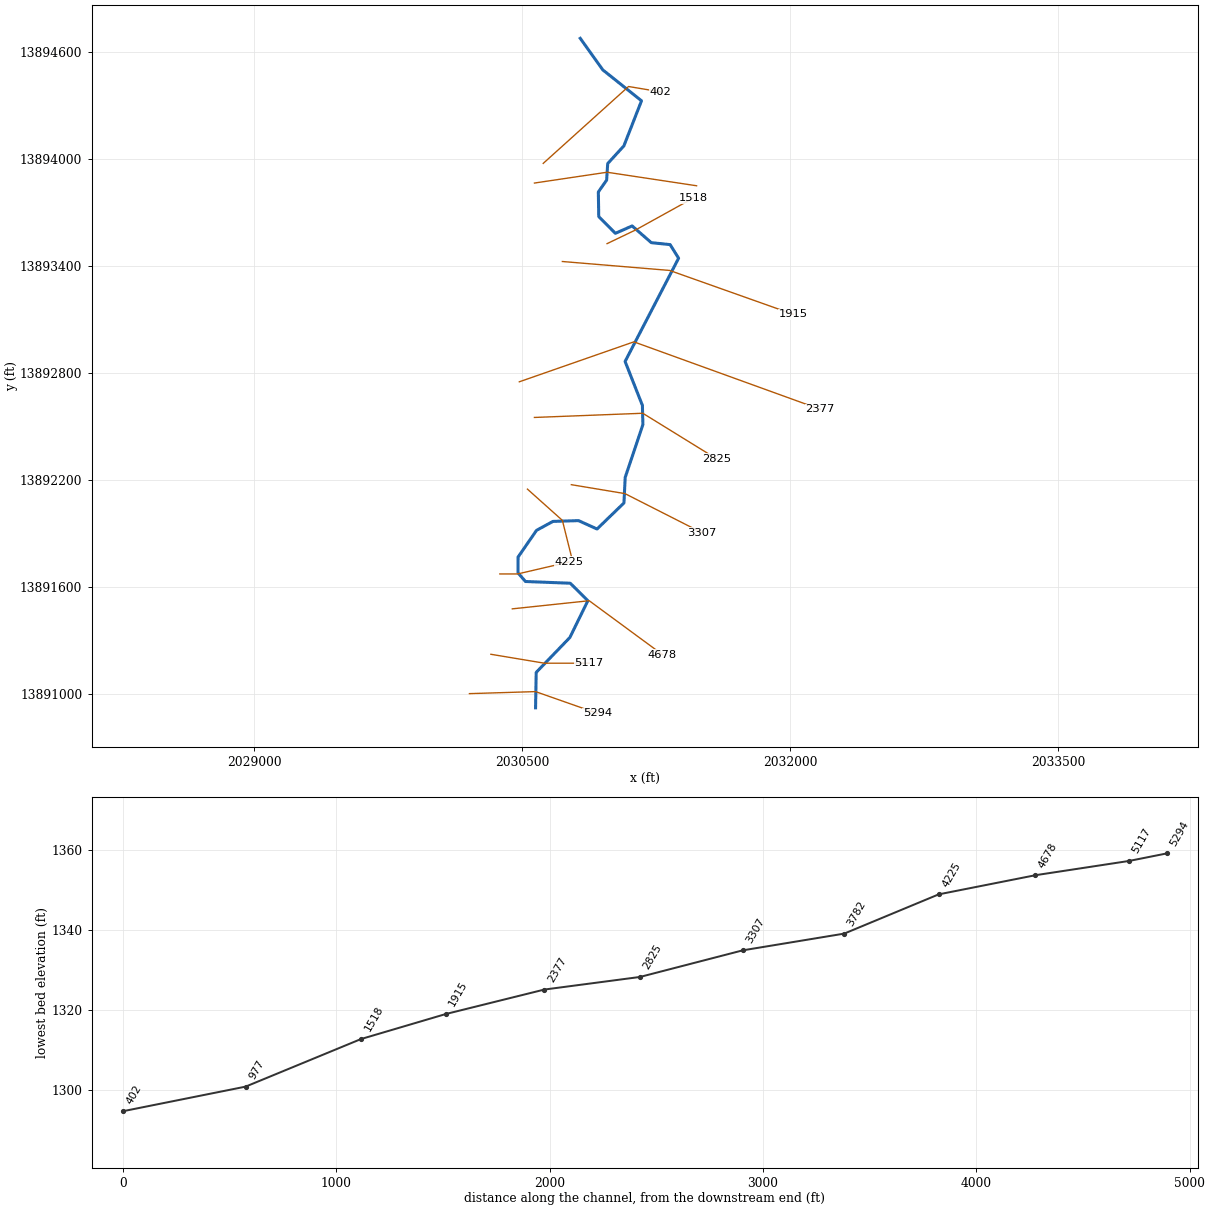
--- UNNAMED TRIBUTARY NO. 2.prj (project) ---

Proj Title=UNNAMED TRIBUTARY NO. 2 Base Level Engineering
Current Plan=p01
Default Exp/Contr=0.3,0.1
English Units
Geom File=g01
Flow File=f01
Plan File=p01
BEGIN DESCRIPTION:
UNNAMED TRIBUTARY NO. 2
END DESCRIPTION:

--- UNNAMED TRIBUTARY NO. 2.p01 (plan) ---

Plan Title=Multiple Run
Short Identifier=Multiple
Geom File=g01
Flow File=f01
Subcritical Flow
K Sum by GR= 0
Std Step Tol= 0.01
Critical Tol= 0.01
Num of Std Step Trials= 20
Max Error Tol= 0.3
Flow Tol Ratio= 0.001
Split Flow NTrial= 30
Split Flow Tol= 0.02
Split Flow Ratio= 0.02
Log Output Level= 0
Friction Slope Method= 1
Unsteady Friction Slope Method= 2
Unsteady Bridges Friction Slope Method= 1
Parabolic Critical Depth
Global Vel Dist=  1 , 1 , 1
Global Log Level= 0
CheckData=True
Encroach Param= -1, 0, 0, 0
BEGIN DESCRIPTION:
Multiple Run
END DESCRIPTION:

--- UNNAMED TRIBUTARY NO. 2.f01 (steady flow) ---

Flow Title=Multiple
Number of Profiles=7
Profile Names=10-year,25-year,50-year,1pct_min,100-year,1pct_plu,500-year
River Rch & RM= UNNAMED TRIBUTAR,Reach-1,5294
    1043    1775    2475    1674    3341    6666    6018
River Rch & RM= UNNAMED TRIBUTAR,Reach-1,5117
    1237    2121    2972    2018    4027    8035    7316
River Rch & RM= UNNAMED TRIBUTAR,Reach-1,1518
    1427    2466    3472    2368    4725    9427    8659
Boundary for River Rch & Prof#=UNNAMED TRIBUTAR,Reach-1,1
Up Type=0
Dn Type=3
Dn Slope=0.005
Boundary for River Rch & Prof#=UNNAMED TRIBUTAR,Reach-1,2
Up Type=0
Dn Type=3
Dn Slope=0.005
Boundary for River Rch & Prof#=UNNAMED TRIBUTAR,Reach-1,3
Up Type=0
Dn Type=3
Dn Slope=0.005
Boundary for River Rch & Prof#=UNNAMED TRIBUTAR,Reach-1,4
Up Type=0
Dn Type=3
Dn Slope=0.005
Boundary for River Rch & Prof#=UNNAMED TRIBUTAR,Reach-1,5
Up Type=0
Dn Type=3
Dn Slope=0.005
Boundary for River Rch & Prof#=UNNAMED TRIBUTAR,Reach-1,6
Up Type=0
Dn Type=3
Dn Slope=0.005
Boundary for River Rch & Prof#=UNNAMED TRIBUTAR,Reach-1,7
Up Type=0
Dn Type=3
Dn Slope=0.005

--- UNNAMED TRIBUTARY NO. 2.g01 (geometry) ---

Geom Title=Existing Conditions

River Reach=UNNAMED TRIBUTAR,Reach-1
Reach XY= 30
      2030575.00     13890925.00      2030578.53     13891123.54
      2030766.86     13891318.94      2030867.72     13891525.10
      2030769.17     13891622.94      2030518.47     13891632.68
      2030476.87     13891680.69      2030477.08     13891769.51
      2030580.61     13891919.41      2030672.62     13891969.31
      2030815.34     13891973.61      2030918.97     13891926.62
      2031069.53     13892072.55      2031076.39     13892215.33
      2031175.48     13892511.20      2031172.75     13892619.06
      2031075.91     13892865.16      2031375.29     13893443.53
      2031327.75     13893519.58      2031222.58     13893530.54
      2031115.20     13893624.19      2031021.58     13893582.81
      2030928.53     13893676.44      2030926.20     13893814.49
      2030972.64     13893880.98      2030978.62     13893973.50
      2031069.15     13894072.71      2031167.69     13894325.11
      2030951.27     13894498.12      2030825.00     13894675.00

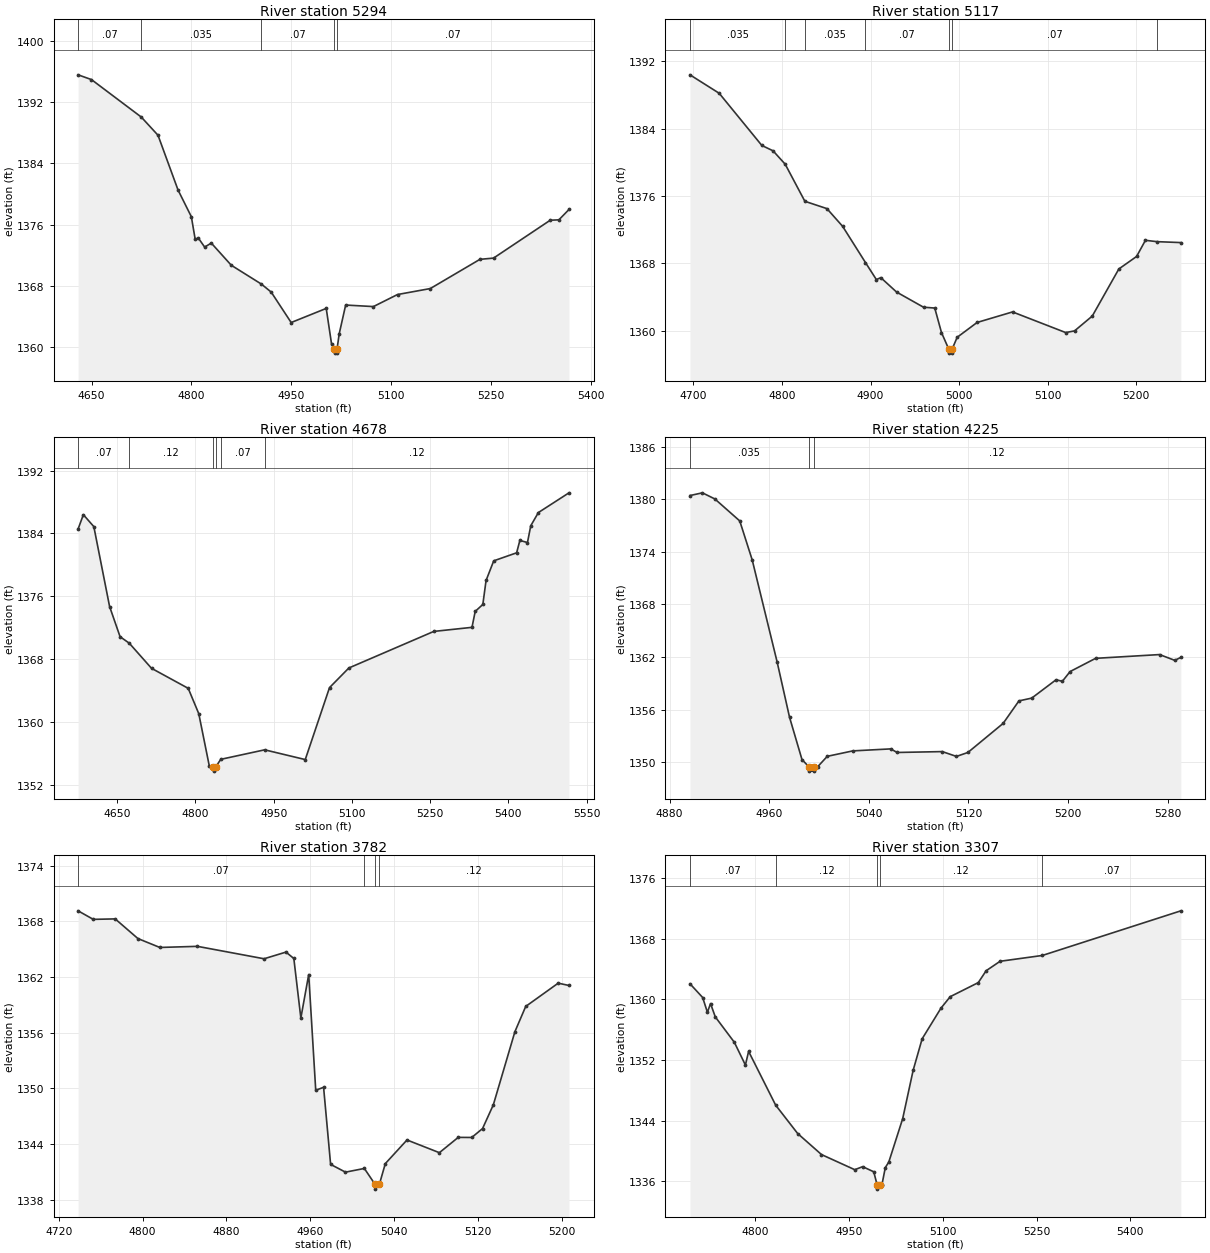
Type RM Length L Ch R = 1,5294,177,177,177
BEGIN DESCRIPTION:
UNNAMED TRIBUTARY NO. 2 12.0
END DESCRIPTION:
XS GIS Cut Line= 3
      2030204.91     13891004.58      2030574.94     13891015.94
      2030921.62     13890894.00
#Sta/Elev= 30
  4629.8 1395.53  4649.9 1394.91  4724.8 1390.02  4749.9 1387.65  4780.0 1380.51
  4800.0 1377.03  4805.7 1374.12  4810.7 1374.22  4820.0 1373.07  4830.0 1373.59
  4860.0 1370.70  4905.3 1368.24  4920.0 1367.20  4950.0 1363.23  5002.7 1365.07
  5010.7 1360.43  5014.9 1359.74  5015.2 1359.24  5018.7 1359.24  5018.9 1359.74
  5022.2 1361.76  5031.9 1365.51  5073.6 1365.31  5109.8 1366.88  5159.1 1367.66
  5233.7 1371.47  5254.1 1371.63  5339.3 1376.57  5352.3 1376.62  5367.5 1377.97
#Mann=5,-1,0
  4629.8    0.07       0  4724.8   0.035       0  4905.3    0.07       0
  5014.9    0.05       0  5018.9    0.07       0
Bank Sta=5014.9,5018.9
Exp/Cntr=0.3,0.1

Type RM Length L Ch R = 1,5117,439,439,439
BEGIN DESCRIPTION:
UNNAMED TRIBUTARY NO. 2 11.0
END DESCRIPTION:
XS GIS Cut Line= 3
      2030325.00     13891225.00      2030625.00     13891175.00
      2030874.96     13891175.00
#Sta/Elev= 30
  4696.2 1390.38  4729.2 1388.19  4777.3 1382.00  4790.0 1381.36  4803.7 1379.77
  4825.9 1375.37  4850.8 1374.50  4868.5 1372.40  4894.3 1368.10  4906.6 1366.08
  4911.6 1366.31  4929.4 1364.60  4959.8 1362.80  4972.5 1362.70  4980.1 1359.79
  4988.2 1357.85  4988.5 1357.35  4992.0 1357.35  4992.2 1357.85  4997.8 1359.23
  5020.3 1360.99  5060.3 1362.24  5120.3 1359.79  5130.3 1359.99  5150.3 1361.75
  5180.3 1367.34  5200.3 1368.82  5210.3 1370.74  5223.4 1370.58  5250.3 1370.47
#Mann=7,-1,0
  4696.2   0.035       0  4803.7    0.07       0  4825.9   0.035       0
  4894.3    0.07       0  4988.2    0.05       0  4992.2    0.07       0
  5223.4    0.12       0
Bank Sta=4988.2,4992.2
Exp/Cntr=0.3,0.1

Type RM Length L Ch R = 1,4678,453,453,453
BEGIN DESCRIPTION:
UNNAMED TRIBUTARY NO. 2 10.0
END DESCRIPTION:
XS GIS Cut Line= 3
      2030444.93     13891479.46      2030875.00     13891525.00
      2031284.80     13891223.38
#Sta/Elev= 30
  4575.0 1384.56  4585.1 1386.39  4605.2 1384.87  4635.4 1374.71  4655.5 1370.87
  4673.2 1370.04  4715.8 1366.85  4786.2 1364.30  4806.4 1361.08  4826.5 1354.46
  4834.5 1354.27  4834.8 1353.77  4838.5 1354.27  4848.6 1355.27  4932.8 1356.48
  5010.6 1355.24  5057.1 1364.39  5094.2 1366.89  5257.0 1371.54  5330.3 1372.06
  5336.5 1374.09  5351.1 1374.97  5357.3 1378.02  5372.0 1380.52  5415.9 1381.54
  5422.1 1383.11  5436.7 1382.85  5443.0 1384.98  5457.6 1386.66  5516.3 1389.17
#Mann=6,-1,0
  4575.0    0.07       0  4673.2    0.12       0  4834.5    0.05       0
  4838.5    0.12       0  4848.6    0.07       0  4932.8    0.12       0
Bank Sta=4834.5,4838.5
Exp/Cntr=0.3,0.1

Type RM Length L Ch R = 1,4225,443,443,443
BEGIN DESCRIPTION:
UNNAMED TRIBUTARY NO. 2 9.0
END DESCRIPTION:
XS GIS Cut Line= 3
      2030374.96     13891675.00      2030475.00     13891675.00
      2030761.66     13891741.85
#Sta/Elev= 30
  4896.3 1380.44  4906.3 1380.75  4916.3 1380.05  4936.3 1377.54  4946.3 1373.09
  4966.3 1361.45  4976.3 1355.12  4986.3 1350.29  4991.8 1349.47  4992.1 1348.97
  4995.6 1348.97  4995.8 1349.47  4998.9 1349.47  5006.6 1350.66  5027.1 1351.28
  5057.6 1351.51  5062.7 1351.10  5099.0 1351.20  5110.4 1350.65  5119.6 1351.10
  5147.9 1354.42  5160.6 1356.99  5170.9 1357.31  5190.4 1359.40  5195.5 1359.23
  5201.7 1360.34  5222.2 1361.85  5273.6 1362.28  5285.8 1361.62  5290.7 1361.96
#Mann=3,-1,0
  4896.3   0.035       0  4991.8    0.05       0  4995.8    0.12       0
Bank Sta=4991.8,4995.8
Exp/Cntr=0.3,0.1

Type RM Length L Ch R = 1,3782,475,475,475
BEGIN DESCRIPTION:
UNNAMED TRIBUTARY NO. 2 8.0
END DESCRIPTION:
XS GIS Cut Line= 3
      2030529.60     13892150.01      2030725.00     13891975.00
      2030775.01     13891774.97
#Sta/Elev= 30
  4738.4 1369.13  4752.9 1368.21  4773.8 1368.26  4795.5 1366.14  4816.4 1365.18
  4852.3 1365.30  4915.9 1363.96  4936.8 1364.68  4944.3 1363.99  4951.0 1357.57
  4958.5 1362.26  4965.2 1349.78  4972.7 1350.10  4979.4 1341.79  4993.6 1340.95
  5011.6 1341.35  5021.9 1339.62  5022.2 1339.12  5025.9 1339.62  5031.6 1341.87
  5052.3 1344.42  5083.2 1343.05  5101.2 1344.70  5114.1 1344.69  5124.4 1345.65
  5134.7 1348.21  5155.3 1356.10  5165.6 1358.82  5196.6 1361.33  5206.9 1361.08
#Mann=4,-1,0
  4738.4    0.07       0  5011.6    0.12       0  5021.9    0.05       0
  5025.9    0.12       0
Bank Sta=5021.9,5025.9
Exp/Cntr=0.3,0.1

Type RM Length L Ch R = 1,3307,482,482,482
BEGIN DESCRIPTION:
UNNAMED TRIBUTARY NO. 2 7.0
END DESCRIPTION:
XS GIS Cut Line= 3
      2030775.01     13892175.00      2031075.00     13892125.00
      2031503.95     13891906.99
#Sta/Elev= 30
  4695.5 1362.08  4715.8 1360.26  4723.4 1358.31  4728.4 1359.46  4736.0 1357.70
  4766.5 1354.34  4784.2 1351.33  4789.3 1353.14  4832.6 1346.03  4867.8 1342.28
  4905.9 1339.50  4959.1 1337.50  4971.8 1337.90  4989.5 1337.22  4995.1 1335.43
  4995.3 1334.93  4999.1 1335.43  5002.4 1335.43  5008.0 1337.78  5013.6 1338.52
  5035.8 1344.25  5052.5 1350.63  5066.9 1354.80  5097.0 1358.85  5111.8 1360.37
  5156.7 1362.23  5169.3 1363.80  5191.6 1365.05  5259.2 1365.82  5480.8 1371.72
#Mann=5,-1,0
  4695.5    0.07       0  4832.6    0.12       0  4995.1    0.05       0
  4999.1    0.12       0  5259.2    0.07       0
Bank Sta=4995.1,4999.1
Exp/Cntr=0.3,0.1

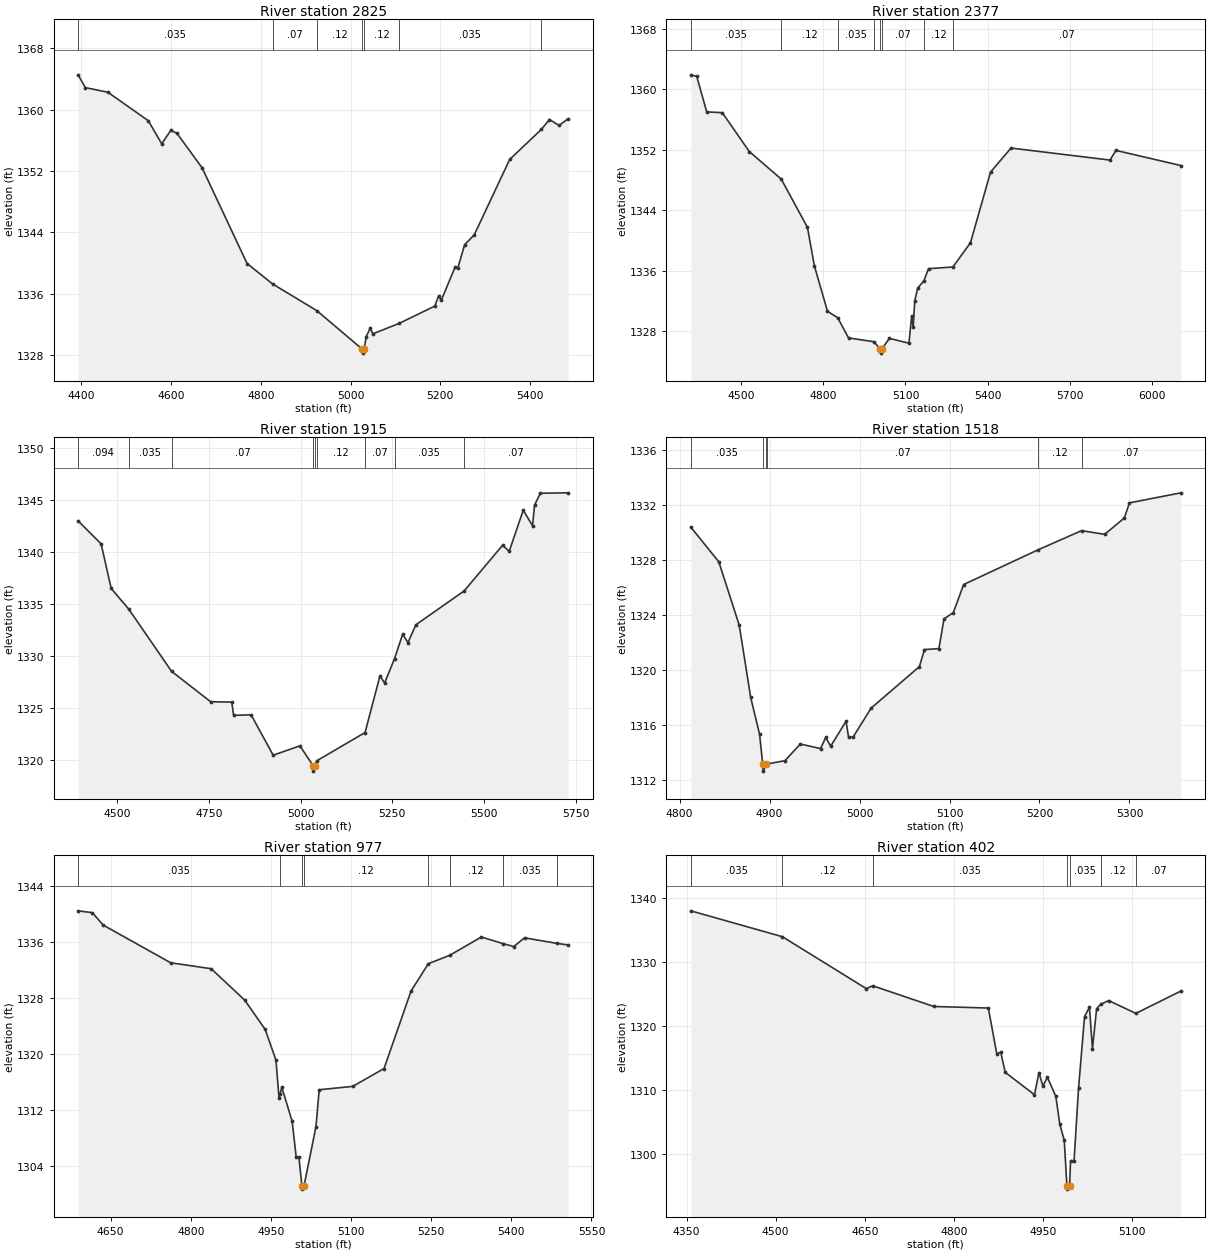
Type RM Length L Ch R = 1,2825,448,448,448
BEGIN DESCRIPTION:
UNNAMED TRIBUTARY NO. 2 6.0
END DESCRIPTION:
XS GIS Cut Line= 3
      2030568.61     13892551.51      2031175.00     13892575.00
      2031588.00     13892319.68
#Sta/Elev= 30
  4392.6 1364.55  4409.0 1362.88  4459.0 1362.28  4549.1 1358.57  4579.1 1355.55
  4599.1 1357.29  4613.0 1356.93  4669.2 1352.41  4769.3 1339.94  4826.0 1337.28
  4924.5 1333.80  5026.4 1328.75  5026.7 1328.25  5030.4 1328.75  5034.7 1330.41
  5043.8 1331.49  5049.7 1330.77  5107.9 1332.12  5187.6 1334.38  5196.3 1335.71
  5202.2 1335.15  5232.9 1339.47  5238.8 1339.31  5254.2 1342.40  5275.5 1343.66
  5354.6 1353.51  5425.3 1357.44  5443.3 1358.72  5464.6 1357.95  5485.0 1358.83
#Mann=7,-1,0
  4392.6   0.035       0  4826.0    0.07       0  4924.5    0.12       0
  5026.4    0.05       0  5030.4    0.12       0  5107.9   0.035       0
  5425.3    0.07       0
Bank Sta=5026.4,5030.4
Exp/Cntr=0.3,0.1

Type RM Length L Ch R = 1,2377,462,462,462
BEGIN DESCRIPTION:
UNNAMED TRIBUTARY NO. 2 5.0
END DESCRIPTION:
XS GIS Cut Line= 3
      2030483.97     13892751.16      2031125.00     13892975.00
      2032168.06     13892597.07
#Sta/Elev= 30
  4316.5 1361.88  4338.4 1361.67  4374.7 1356.98  4431.6 1356.88  4530.0 1351.74
  4646.4 1348.11  4742.1 1341.73  4767.9 1336.58  4815.4 1330.62  4852.9 1329.76
  4892.1 1327.10  4984.7 1326.60  5008.8 1325.59  5009.0 1325.09  5012.8 1325.59
  5041.4 1327.04  5112.5 1326.40  5122.7 1330.04  5128.0 1328.49  5133.8 1332.01
  5144.4 1333.67  5167.2 1334.66  5184.0 1336.25  5273.2 1336.48  5337.1 1339.69
  5410.3 1349.02  5485.0 1352.20  5846.4 1350.61  5867.6 1351.89  6104.9 1349.89
#Mann=8,-1,0
  4316.5   0.035       0  4646.4    0.12       0  4852.9   0.035       0
  4984.7    0.07       0  5008.8    0.05       0  5012.8    0.07       0
  5167.2    0.12       0  5273.2    0.07       0
Bank Sta=5008.8,5012.8
Exp/Cntr=0.3,0.1

Type RM Length L Ch R = 1,1915,397,397,397
BEGIN DESCRIPTION:
UNNAMED TRIBUTARY NO. 2 4.0
END DESCRIPTION:
XS GIS Cut Line= 3
      2030724.96     13893425.00      2031325.00     13893375.00
      2032016.56     13893129.38
#Sta/Elev= 30
  4393.3 1343.00  4456.1 1340.79  4483.7 1336.50  4531.6 1334.51  4648.2 1328.54
  4754.6 1325.62  4812.3 1325.58  4817.3 1324.31  4865.0 1324.36  4925.2 1320.48
  4998.1 1321.38  5034.4 1319.45  5034.6 1318.95  5038.4 1319.45  5044.4 1319.95
  5175.6 1322.66  5216.2 1328.10  5228.9 1327.42  5256.0 1329.76  5278.0 1332.10
  5292.6 1331.30  5314.1 1333.01  5445.9 1336.27  5550.4 1340.65  5568.5 1340.07
  5606.8 1344.02  5632.1 1342.53  5637.6 1344.51  5653.4 1345.65  5729.3 1345.69
#Mann=9,-1,0
  4393.3   0.094       0  4531.6   0.035       0  4648.2    0.07       0
  5034.4    0.05       0  5038.4    0.07       0  5044.4    0.12       0
  5175.6    0.07       0  5256.0   0.035       0  5445.9    0.07       0
Bank Sta=5034.4,5038.4
Exp/Cntr=0.3,0.1

Type RM Length L Ch R = 1,1518,541,541,541
BEGIN DESCRIPTION:
UNNAMED TRIBUTARY NO. 2 3.0
END DESCRIPTION:
XS GIS Cut Line= 3
      2030974.96     13893524.98      2031135.04     13893601.86
      2031456.25     13893779.83
#Sta/Elev= 30
  4812.4 1330.43  4843.6 1327.90  4866.3 1323.29  4879.0 1318.04  4888.9 1315.36
  4892.4 1313.18  4892.7 1312.68  4896.5 1313.18  4897.3 1313.20  4917.1 1313.44
  4934.2 1314.65  4956.7 1314.32  4962.4 1315.13  4967.9 1314.49  4985.0 1316.31
  4987.8 1315.15  4992.8 1315.15  5012.8 1317.26  5066.5 1320.28  5072.2 1321.52
  5088.2 1321.59  5093.9 1323.76  5104.2 1324.20  5115.7 1326.25  5197.9 1328.76
  5246.8 1330.17  5272.5 1329.90  5294.3 1331.09  5300.0 1332.19  5357.2 1332.92
#Mann=6,-1,0
  4812.4   0.035       0  4892.4    0.05       0  4896.5   0.035       0
  4897.3    0.07       0  5197.9    0.12       0  5246.8    0.07       0
Bank Sta=4892.4,4896.5
Exp/Cntr=0.3,0.1

Type RM Length L Ch R = 1,977,575,575,575
BEGIN DESCRIPTION:
UNNAMED TRIBUTARY NO. 2 2.0
END DESCRIPTION:
XS GIS Cut Line= 3
      2030568.63     13893864.45      2030975.00     13893925.00
      2031475.75     13893849.26
#Sta/Elev= 30
  4589.2 1340.45  4615.9 1340.19  4636.1 1338.42  4762.5 1333.04  4838.3 1332.19
  4901.1 1327.71  4939.4 1323.53  4959.6 1319.14  4965.4 1313.70  4967.6 1314.38
  4970.5 1315.28  4989.9 1310.41  4997.5 1305.28  5002.6 1305.28  5008.1 1301.24
  5008.4 1300.74  5012.2 1301.24  5034.5 1309.67  5040.5 1314.92  5103.3 1315.40
  5161.9 1317.95  5212.4 1329.01  5244.8 1332.91  5284.5 1334.09  5343.9 1336.71
  5384.7 1335.77  5404.6 1335.35  5424.8 1336.60  5484.8 1335.81  5506.5 1335.58
#Mann=8,-1,0
  4589.2   0.035       0  4967.6    0.12       0  5008.1    0.05       0
  5012.2    0.12       0  5244.8    0.07       0  5284.5    0.12       0
  5384.7   0.035       0  5484.8    0.07       0
Bank Sta=5008.1,5012.2
Exp/Cntr=0.3,0.1

Type RM Length L Ch R = 1,402,0,0,0
BEGIN DESCRIPTION:
UNNAMED TRIBUTARY NO. 2 1.0
END DESCRIPTION:
XS GIS Cut Line= 3
      2030617.83     13893974.55      2031095.17     13894405.21
      2031274.95     13894375.01
#Sta/Elev= 30
  4357.1 1338.01  4511.4 1333.97  4652.6 1325.87  4663.5 1326.31  4766.2 1323.08
  4858.1 1322.84  4872.3 1315.69  4879.0 1315.94  4886.5 1312.80  4935.8 1309.30
  4943.3 1312.76  4950.0 1310.64  4957.5 1312.03  4971.7 1309.05  4978.4 1304.70
  4985.9 1302.20  4990.4 1295.07  4990.7 1294.57  4994.9 1295.07  4996.5 1299.00
  5002.4 1299.00  5010.0 1310.35  5020.1 1321.51  5028.3 1322.95  5033.4 1316.51
  5040.4 1322.73  5047.1 1323.41  5060.7 1324.00  5106.4 1322.00  5182.3 1325.49
#Mann=7,-1,0
  4357.1   0.035       0  4511.4    0.12       0  4663.5   0.035       0
  4990.4   0.035       0  4994.9   0.035       0  5047.1    0.12       0
  5106.4    0.07       0
Bank Sta=4990.4,4994.9
Exp/Cntr=0.3,0.1

Chan Stop Cuts=-1