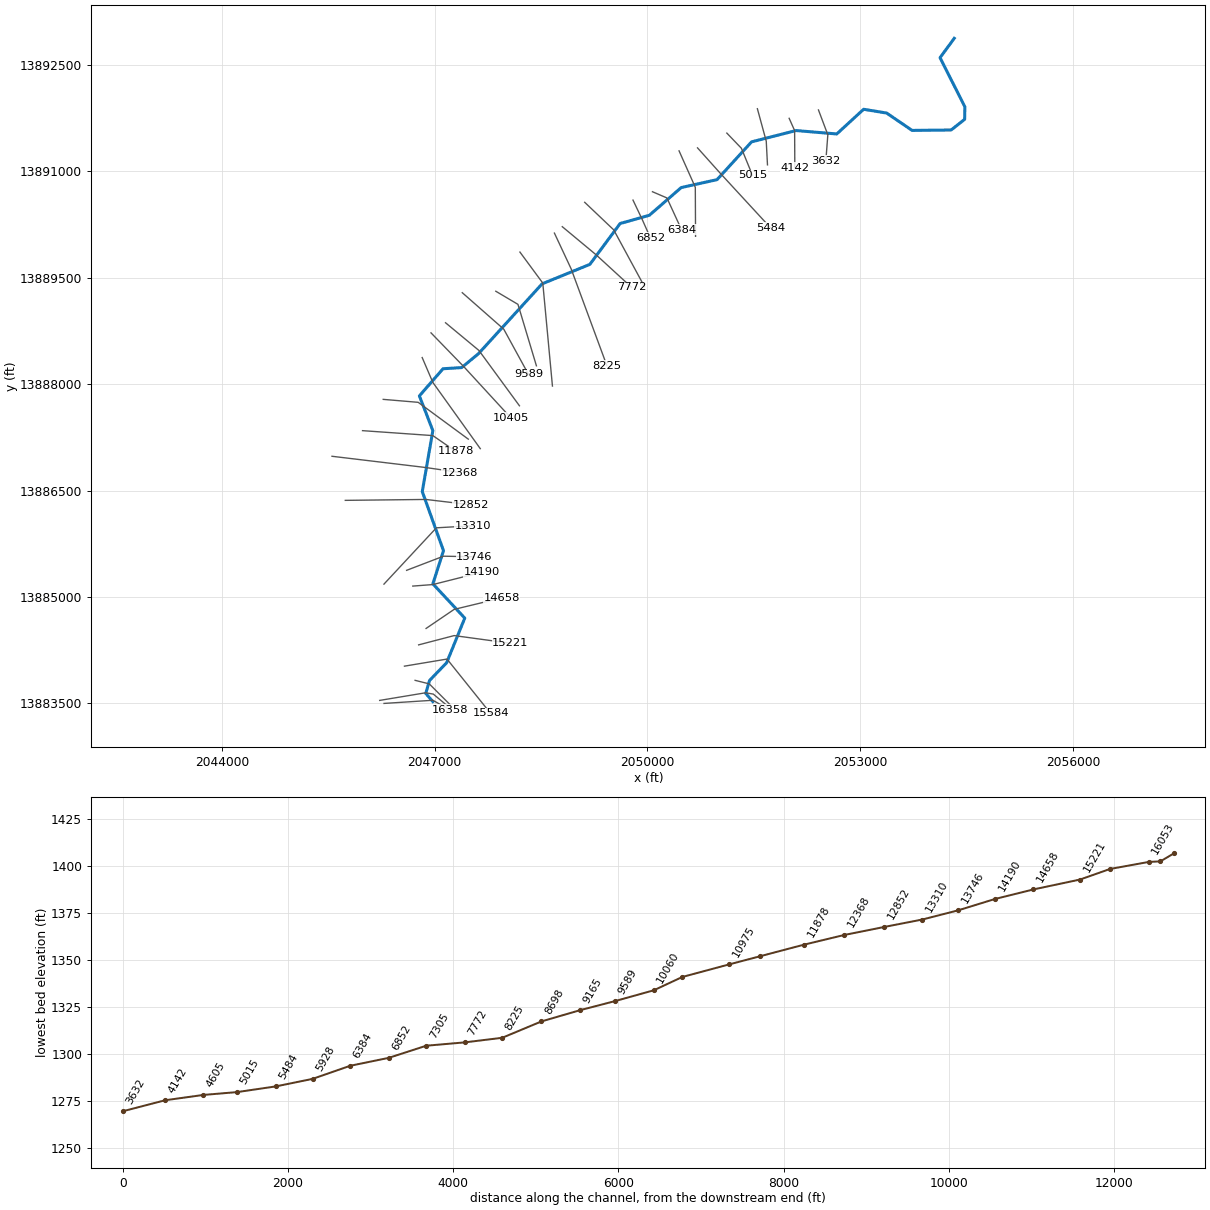
--- VIOLET CREEK.prj (project) ---

Proj Title=VIOLET CREEK Base Level Engineering
Current Plan=p01
Default Exp/Contr=0.3,0.1
English Units
Geom File=g01
Flow File=f01
Plan File=p01
BEGIN DESCRIPTION:
VIOLET CREEK
END DESCRIPTION:

--- VIOLET CREEK.p01 (plan) ---

Plan Title=Multiple Run
Short Identifier=Multiple
Geom File=g01
Flow File=f01
Subcritical Flow
K Sum by GR= 0
Std Step Tol= 0.01
Critical Tol= 0.01
Num of Std Step Trials= 20
Max Error Tol= 0.3
Flow Tol Ratio= 0.001
Split Flow NTrial= 30
Split Flow Tol= 0.02
Split Flow Ratio= 0.02
Log Output Level= 0
Friction Slope Method= 1
Unsteady Friction Slope Method= 2
Unsteady Bridges Friction Slope Method= 1
Parabolic Critical Depth
Global Vel Dist=  1 , 1 , 1
Global Log Level= 0
CheckData=True
Encroach Param= -1, 0, 0, 0
BEGIN DESCRIPTION:
Multiple Run
END DESCRIPTION:

--- VIOLET CREEK.f01 (steady flow) ---

Flow Title=Multiple
Number of Profiles=7
Profile Names=10-year,25-year,50-year,1pct_min,100-year,1pct_plu,500-year
River Rch & RM= VIOLET CREEK,Reach-1,16358
     838    1391    1908    1270    2534    5057    4417
River Rch & RM= VIOLET CREEK,Reach-1,16194
    1114    1880    2604    1748    3488    6959    6188
River Rch & RM= VIOLET CREEK,Reach-1,12852
    1808    3132    4418    3014    6015   12001   11031
River Rch & RM= VIOLET CREEK,Reach-1,10975
    2368    4153    5906    4057    8095   16152   15060
River Rch & RM= VIOLET CREEK,Reach-1,5484
    2536    4454    6340    4358    8695   17350   16197
River Rch & RM= VIOLET CREEK,Reach-1,2314
    2726    4805    6855    4722    9421   18798   17623
River Rch & RM= VIOLET CREEK,Reach-1,1378
    2907    5137    7341    5064   10105   20162   18960
Boundary for River Rch & Prof#=VIOLET CREEK,Reach-1,1
Up Type=0
Dn Type=3
Dn Slope=0.005
Boundary for River Rch & Prof#=VIOLET CREEK,Reach-1,2
Up Type=0
Dn Type=3
Dn Slope=0.005
Boundary for River Rch & Prof#=VIOLET CREEK,Reach-1,3
Up Type=0
Dn Type=3
Dn Slope=0.005
Boundary for River Rch & Prof#=VIOLET CREEK,Reach-1,4
Up Type=0
Dn Type=3
Dn Slope=0.005
Boundary for River Rch & Prof#=VIOLET CREEK,Reach-1,5
Up Type=0
Dn Type=3
Dn Slope=0.005
Boundary for River Rch & Prof#=VIOLET CREEK,Reach-1,6
Up Type=0
Dn Type=3
Dn Slope=0.005
Boundary for River Rch & Prof#=VIOLET CREEK,Reach-1,7
Up Type=0
Dn Type=3
Dn Slope=0.005

--- VIOLET CREEK.g01 (geometry) ---

Geom Title=Existing Conditions

River Reach=VIOLET CREEK,Reach-1
Reach XY= 30
      2046975.00     13883525.00      2046875.22     13883641.01
      2046928.82     13883823.42      2047169.48     13884072.56
      2047425.24     13884702.44      2046975.60     13885185.62
      2047125.28     13885652.24      2046826.22     13886485.50
      2046975.36     13887345.15      2046785.43     13887834.79
      2047118.83     13888217.14      2047382.01     13888234.03
      2047619.39     13888430.59      2048515.32     13889414.22
      2049188.24     13889688.61      2049615.20     13890264.52
      2050027.30     13890380.83      2050476.47     13890771.45
      2050981.34     13890883.02      2051468.34     13891415.69
      2052095.10     13891575.09      2052669.16     13891527.05
      2053047.68     13891875.11      2053373.42     13891821.18
      2053730.85     13891577.06      2054281.18     13891582.85
      2054471.93     13891733.30      2054474.46     13891911.14
      2054124.60     13892602.20      2054325.00     13892875.00

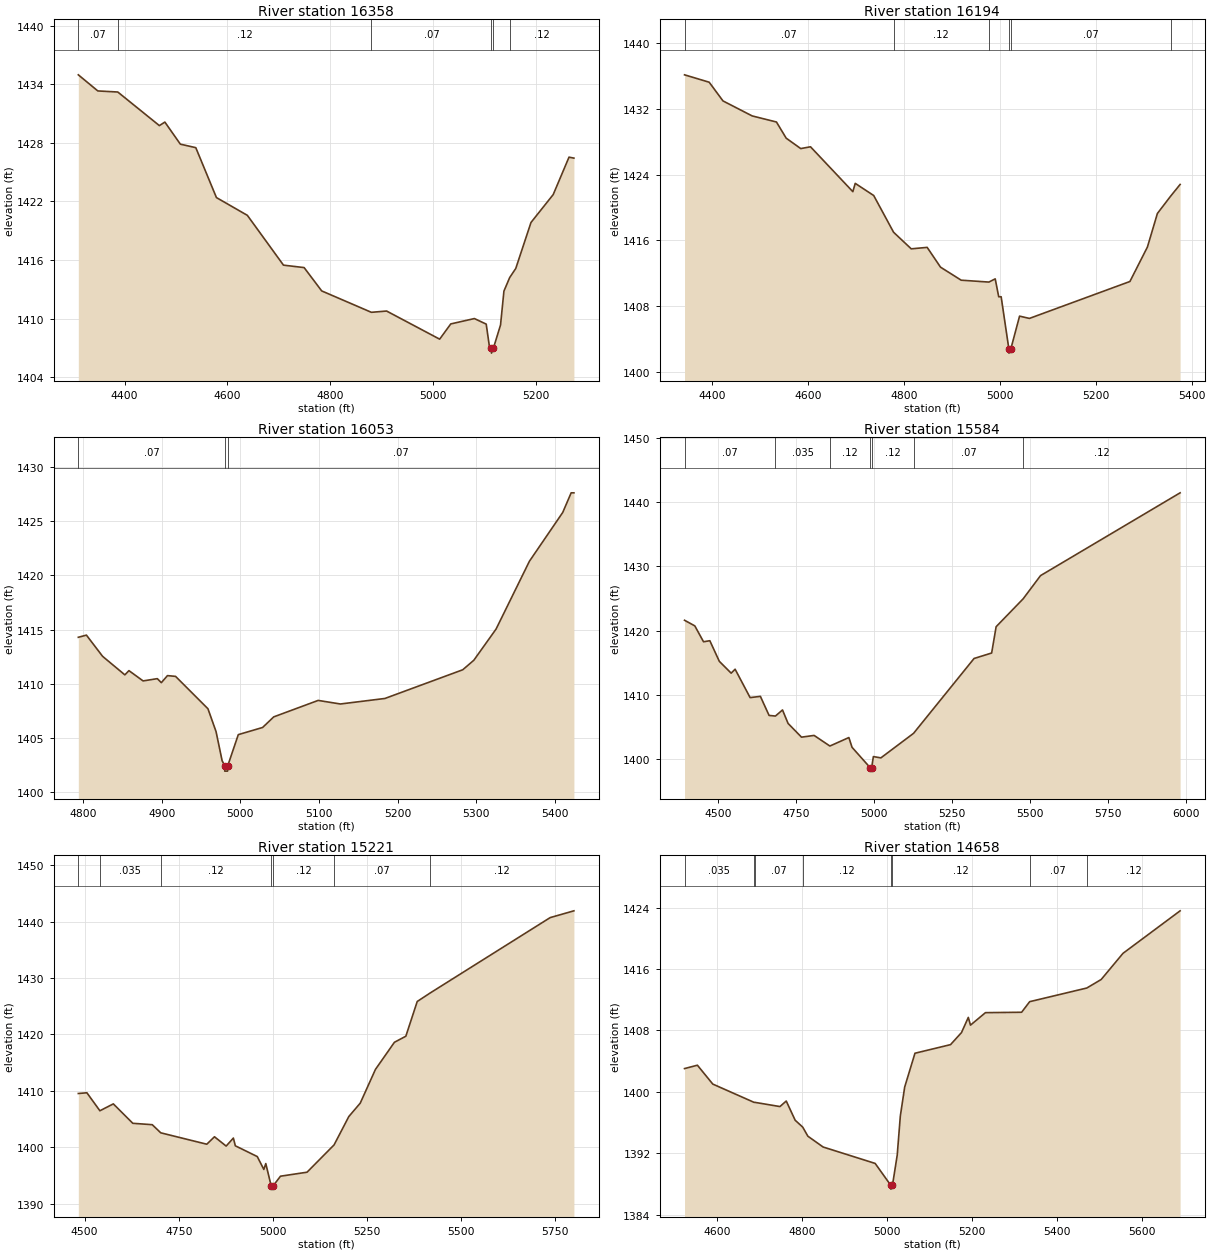
Type RM Length L Ch R = 1,16358,164,164,164
BEGIN DESCRIPTION:
VIOLET CREEK 37.0
END DESCRIPTION:
XS GIS Cut Line= 3
      2046287.16     13883499.56      2046975.52     13883544.04
      2047213.29     13883409.27
#Sta/Elev= 30
  4310.2 1434.97  4348.1 1433.32  4386.9 1433.21  4467.7 1429.77  4478.4 1430.13
  4508.5 1427.87  4538.5 1427.51  4578.6 1422.40  4638.7 1420.58  4708.9 1415.48
  4749.0 1415.23  4783.2 1412.84  4879.7 1410.65  4909.3 1410.78  5012.4 1407.90
  5034.0 1409.46  5079.9 1410.01  5102.9 1409.44  5109.1 1407.14  5112.8 1406.97
  5113.1 1406.47  5116.8 1406.97  5130.7 1409.35  5137.3 1412.82  5148.5 1414.21
  5160.3 1415.14  5189.9 1419.85  5233.1 1422.71  5263.8 1426.54  5273.3 1426.44
#Mann=6,-1,0
  4310.2    0.07       0  4386.9    0.12       0  4879.7    0.07       0
  5112.8    0.05       0  5116.8    0.07       0  5148.5    0.12       0
Bank Sta=5112.8,5116.8
Exp/Cntr=0.3,0.1

Type RM Length L Ch R = 1,16194,141,141,141
BEGIN DESCRIPTION:
VIOLET CREEK 36.0
END DESCRIPTION:
XS GIS Cut Line= 4
      2046225.85     13883542.15      2046874.46     13883649.87
      2046981.75     13883630.95      2047187.11     13883460.23
#Sta/Elev= 30
  4342.5 1436.16  4393.9 1435.26  4422.7 1432.98  4483.6 1431.15  4534.2 1430.41
  4554.5 1428.44  4584.9 1427.17  4605.2 1427.39  4693.5 1421.92  4698.5 1422.93
  4737.0 1421.45  4778.5 1416.97  4815.3 1414.95  4848.5 1415.13  4876.3 1412.72
  4919.4 1411.13  4977.2 1410.90  4990.4 1411.29  4997.7 1409.11  5002.8 1409.11
  5018.9 1402.74  5019.1 1402.24  5022.9 1402.74  5041.2 1406.75  5061.7 1406.47
  5271.3 1410.97  5307.8 1415.17  5328.6 1419.26  5356.2 1421.37  5376.0 1422.80
#Mann=6,-1,0
  4342.5    0.07       0  4778.5    0.12       0  4977.2    0.07       0
  5018.9    0.05       0  5022.9    0.07       0  5356.2    0.12       0
Bank Sta=5018.9,5022.9
Exp/Cntr=0.3,0.1

Type RM Length L Ch R = 1,16053,469,469,469
BEGIN DESCRIPTION:
VIOLET CREEK 35.0
END DESCRIPTION:
XS GIS Cut Line= 3
      2046725.03     13883824.99      2046925.00     13883775.00
      2047225.01     13883474.99
#Sta/Elev= 30
  4793.9 1414.29  4804.2 1414.49  4824.8 1412.53  4853.1 1410.82  4858.3 1411.21
  4876.3 1410.26  4894.4 1410.47  4899.5 1410.10  4907.3 1410.75  4917.6 1410.68
  4958.8 1407.69  4969.1 1405.58  4976.8 1402.90  4980.0 1402.43  4980.2 1401.93
  4983.7 1401.93  4984.0 1402.43  4997.4 1405.30  5028.3 1405.96  5042.5 1406.94
  5099.0 1408.46  5127.3 1408.13  5183.9 1408.64  5282.9 1411.29  5297.0 1412.17
  5325.3 1415.05  5367.7 1421.31  5410.1 1425.82  5420.8 1427.63  5424.3 1427.63
#Mann=3,-1,0
  4793.9    0.07       0  4980.0    0.05       0  4984.0    0.07       0
Bank Sta=4980,4984
Exp/Cntr=0.3,0.1

Type RM Length L Ch R = 1,15584,363,363,363
BEGIN DESCRIPTION:
VIOLET CREEK 34.0
END DESCRIPTION:
XS GIS Cut Line= 3
      2046574.95     13884024.99      2047175.00     13884125.00
      2047789.02     13883359.31
#Sta/Elev= 30
  4391.6 1421.64  4424.6 1420.77  4452.5 1418.30  4472.8 1418.46  4503.2 1415.26
  4541.2 1413.42  4553.9 1414.03  4602.0 1409.62  4635.0 1409.81  4662.8 1406.85
  4683.2 1406.75  4705.9 1407.70  4723.7 1405.61  4766.8 1403.47  4807.3 1403.74
  4857.9 1402.09  4918.8 1403.41  4929.0 1401.89  4987.8 1398.69  4988.0 1398.19
  4991.8 1398.69  4997.4 1400.45  5021.5 1400.25  5126.2 1404.06  5320.4 1415.70
  5376.8 1416.55  5391.2 1420.64  5477.8 1424.97  5533.6 1428.58  5981.4 1441.45
#Mann=7,-1,0
  4391.6    0.07       0  4683.2   0.035       0  4857.9    0.12       0
  4987.8    0.05       0  4991.8    0.12       0  5126.2    0.07       0
  5477.8    0.12       0
Bank Sta=4987.8,4991.8
Exp/Cntr=0.3,0.1

Type RM Length L Ch R = 1,15221,563,563,563
BEGIN DESCRIPTION:
VIOLET CREEK 33.0
END DESCRIPTION:
XS GIS Cut Line= 3
      2046775.00     13884325.00      2047275.74     13884455.78
      2048067.42     13884348.13
#Sta/Elev= 30
  4483.1 1409.52  4505.9 1409.65  4540.4 1406.46  4576.1 1407.68  4627.8 1404.24
  4679.5 1403.99  4702.1 1402.55  4824.4 1400.53  4844.8 1401.85  4875.8 1400.20
  4895.0 1401.62  4900.2 1400.25  4958.5 1398.34  4975.9 1396.06  4981.1 1397.10
  4995.7 1393.07  4995.9 1392.57  4999.7 1393.07  5020.1 1394.86  5090.7 1395.57
  5162.5 1400.41  5201.7 1405.44  5232.0 1407.81  5272.4 1413.79  5322.8 1418.60
  5353.1 1419.67  5383.4 1425.83  5417.6 1427.33  5736.6 1440.70  5799.6 1441.90
#Mann=7,-1,0
  4483.1    0.07       0  4540.4   0.035       0  4702.1    0.12       0
  4995.7    0.05       0  4999.7    0.12       0  5162.5    0.07       0
  5417.6    0.12       0
Bank Sta=4995.7,4999.7
Exp/Cntr=0.3,0.1

Type RM Length L Ch R = 1,14658,468,468,468
BEGIN DESCRIPTION:
VIOLET CREEK 32.0
END DESCRIPTION:
XS GIS Cut Line= 3
      2046879.94     13884556.49      2047275.00     13884825.00
      2047945.84     13884987.02
#Sta/Elev= 30
  4522.8 1403.03  4553.1 1403.47  4589.4 1401.01  4686.6 1398.63  4689.5 1398.62
  4747.6 1398.08  4762.5 1398.80  4783.5 1396.30  4801.3 1395.40  4813.4 1394.22
  4849.3 1392.81  4972.0 1390.67  5008.8 1387.82  5009.0 1387.32  5012.8 1387.82
  5024.0 1391.76  5031.3 1396.84  5041.6 1400.63  5065.8 1405.03  5149.6 1406.15
  5175.4 1407.72  5191.5 1409.70  5196.6 1408.69  5231.9 1410.32  5317.1 1410.37
  5336.1 1411.75  5470.7 1413.53  5504.6 1414.64  5556.0 1418.05  5690.6 1423.59
#Mann=8,-1,0
  4522.8   0.035       0  4686.6    0.12       0  4689.5    0.07       0
  4801.3    0.12       0  5008.8    0.05       0  5012.8    0.12       0
  5336.1    0.07       0  5470.7    0.12       0
Bank Sta=5008.8,5012.8
Exp/Cntr=0.3,0.1

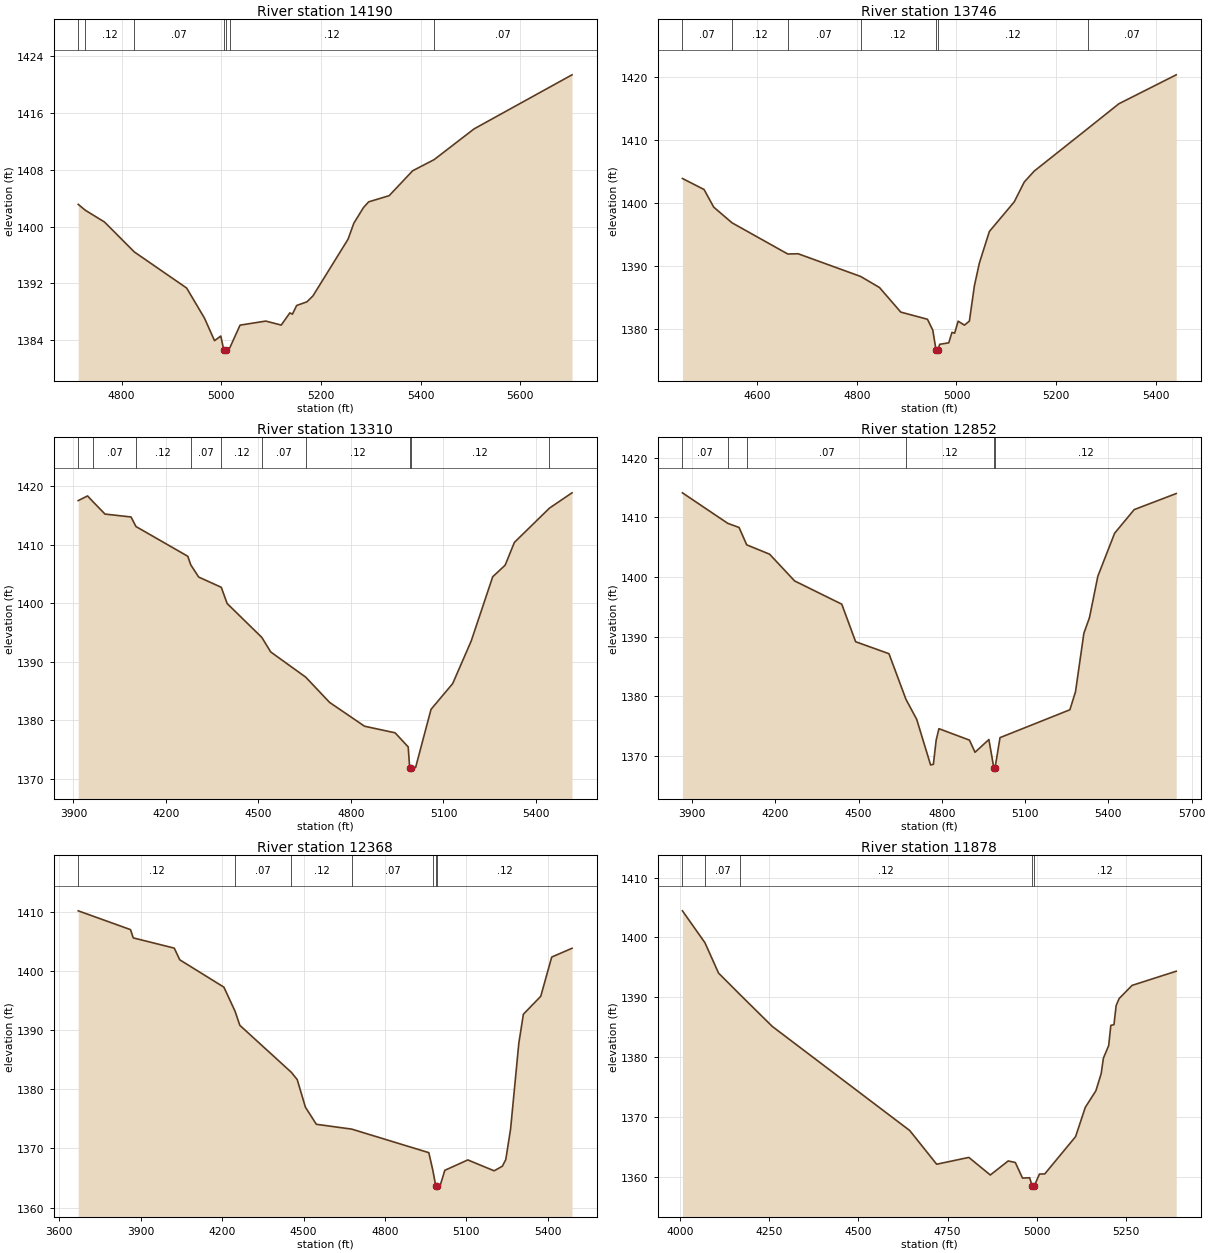
Type RM Length L Ch R = 1,14190,444,444,444
BEGIN DESCRIPTION:
VIOLET CREEK 31.0
END DESCRIPTION:
XS GIS Cut Line= 3
      2046692.41     13885153.69      2046975.00     13885175.00
      2047660.62     13885348.00
#Sta/Elev= 30
  4713.0 1403.11  4727.1 1402.29  4765.7 1400.63  4825.7 1396.42  4930.5 1391.36
  4966.3 1387.13  4986.4 1383.97  4999.0 1384.62  5004.7 1382.72  5005.0 1382.22
  5008.5 1382.22  5008.7 1382.72  5017.1 1382.97  5037.6 1386.15  5089.2 1386.72
  5120.2 1386.16  5137.5 1387.87  5142.7 1387.69  5151.1 1388.91  5171.7 1389.42
  5183.8 1390.25  5254.2 1398.21  5265.9 1400.47  5285.2 1402.66  5295.5 1403.46
  5336.7 1404.33  5383.9 1407.83  5426.9 1409.39  5507.1 1413.71  5703.5 1421.30
#Mann=7,-1,0
  4713.0    0.07       0  4727.1    0.12       0  4825.7    0.07       0
  5004.7    0.05       0  5008.7    0.07       0  5017.1    0.12       0
  5426.9    0.07       0
Bank Sta=5004.7,5008.7
Exp/Cntr=0.3,0.1

Type RM Length L Ch R = 1,13746,436,436,436
BEGIN DESCRIPTION:
VIOLET CREEK 30.0
END DESCRIPTION:
XS GIS Cut Line= 3
      2046605.61     13885375.92      2047125.00     13885575.00
      2047560.18     13885566.89
#Sta/Elev= 30
  4449.7 1403.95  4493.1 1402.20  4512.5 1399.40  4549.2 1396.91  4661.2 1391.95
  4682.0 1391.99  4807.6 1388.38  4845.3 1386.63  4888.1 1382.72  4941.7 1381.58
  4952.4 1379.86  4958.9 1376.70  4959.1 1376.20  4962.9 1376.70  4966.2 1377.60
  4984.5 1377.84  4990.9 1379.50  4996.3 1379.37  5003.3 1381.28  5015.9 1380.65
  5025.9 1381.29  5035.9 1386.88  5045.9 1390.50  5066.0 1395.53  5116.0 1400.24
  5136.0 1403.38  5156.0 1405.12  5264.4 1411.93  5326.0 1415.82  5441.2 1420.42
#Mann=7,-1,0
  4449.7    0.07       0  4549.2    0.12       0  4661.2    0.07       0
  4807.6    0.12       0  4958.9    0.05       0  4962.9    0.12       0
  5264.4    0.07       0
Bank Sta=4958.9,4962.9
Exp/Cntr=0.3,0.1

Type RM Length L Ch R = 1,13310,458,458,458
BEGIN DESCRIPTION:
VIOLET CREEK 29.0
END DESCRIPTION:
XS GIS Cut Line= 3
      2046286.15     13885181.46      2047025.00     13885975.00
      2047541.52     13886004.30
#Sta/Elev= 30
  3915.4 1417.55  3945.6 1418.35  3964.2 1417.31  4002.2 1415.25  4086.8 1414.75
  4102.6 1413.12  4270.9 1408.03  4280.3 1406.58  4306.1 1404.48  4379.4 1402.73
  4398.5 1399.95  4511.1 1394.15  4539.7 1391.68  4653.5 1387.36  4730.7 1383.05
  4844.0 1378.98  4943.2 1377.85  4985.7 1375.44  4990.6 1371.80  4990.8 1371.30
  4994.6 1371.80  5009.7 1371.92  5059.7 1381.86  5129.9 1386.26  5190.0 1393.54
  5259.8 1404.53  5300.1 1406.51  5330.2 1410.41  5444.0 1416.27  5517.0 1418.88
#Mann=10,-1,0
  3915.4   0.035       0  3964.2    0.07       0  4102.6    0.12       0
  4280.3    0.07       0  4379.4    0.12       0  4511.1    0.07       0
  4653.5    0.12       0  4990.6    0.05       0  4994.6    0.12       0
  5444.0    0.07       0
Bank Sta=4990.6,4994.6
Exp/Cntr=0.3,0.1

Type RM Length L Ch R = 1,12852,484,484,484
BEGIN DESCRIPTION:
VIOLET CREEK 28.0
END DESCRIPTION:
XS GIS Cut Line= 3
      2045741.06     13886362.03      2046875.00     13886375.00
      2047515.35     13886299.52
#Sta/Elev= 30
  3865.6 1414.14  4029.0 1409.01  4069.6 1408.32  4097.2 1405.40  4179.6 1403.83
  4269.6 1399.34  4439.6 1395.43  4489.6 1389.12  4609.6 1387.11  4670.8 1379.45
  4709.6 1376.07  4759.6 1368.42  4769.6 1368.53  4779.6 1372.57  4789.6 1374.51
  4899.6 1372.59  4919.6 1370.55  4969.6 1372.69  4987.6 1367.88  4987.9 1367.38
  4991.6 1367.88  5009.7 1373.01  5261.4 1377.69  5281.6 1380.72  5311.8 1390.55
  5331.9 1393.17  5362.1 1400.13  5422.5 1407.35  5493.0 1411.32  5644.4 1414.02
#Mann=6,-1,0
  3865.6    0.07       0  4029.0    0.12       0  4097.2    0.07       0
  4670.8    0.12       0  4987.6    0.05       0  4991.6    0.12       0
Bank Sta=4987.6,4991.6
Exp/Cntr=0.3,0.1

Type RM Length L Ch R = 1,12368,490,490,490
BEGIN DESCRIPTION:
VIOLET CREEK 27.0
END DESCRIPTION:
XS GIS Cut Line= 3
      2045553.53     13886983.55      2046875.00     13886825.00
      2047359.03     13886754.39
#Sta/Elev= 30
  3669.4 1410.20  3862.2 1407.02  3872.3 1405.62  4023.4 1403.89  4043.5 1401.92
  4206.3 1397.29  4247.3 1393.24  4265.1 1390.83  4455.0 1382.88  4476.6 1381.65
  4506.8 1376.99  4547.1 1374.09  4677.7 1373.27  4961.7 1369.29  4976.7 1366.27
  4987.5 1363.62  4988.0 1363.12  4993.0 1363.62  5002.9 1363.63  5020.6 1366.30
  5105.4 1368.06  5202.5 1366.22  5232.8 1367.00  5245.4 1368.12  5263.1 1373.28
  5293.4 1387.78  5310.3 1392.71  5374.3 1395.74  5414.7 1402.38  5489.5 1403.86
#Mann=7,-1,0
  3669.4    0.12       0  4247.3    0.07       0  4455.0    0.12       0
  4677.7    0.07       0  4976.7    0.12       0  4987.5    0.05       0
  4993.0    0.12       0
Bank Sta=4987.5,4993
Exp/Cntr=0.3,0.1

Type RM Length L Ch R = 1,11878,533,533,533
BEGIN DESCRIPTION:
VIOLET CREEK 26.0
END DESCRIPTION:
XS GIS Cut Line= 3
      2045984.06     13887344.67      2046975.00     13887275.00
      2047296.61     13887052.97
#Sta/Elev= 30
  4006.5 1404.44  4069.7 1399.10  4107.7 1394.04  4168.7 1390.40  4258.1 1385.14
  4643.7 1367.73  4719.2 1362.10  4809.4 1363.24  4869.6 1360.30  4919.7 1362.65
  4939.7 1362.39  4959.8 1359.79  4979.8 1359.84  4987.1 1358.44  4987.5 1357.94
  4992.6 1358.44  5007.3 1360.46  5022.2 1360.48  5108.7 1366.72  5135.8 1371.60
  5165.5 1374.37  5180.4 1377.25  5186.5 1379.81  5201.4 1381.93  5207.4 1385.30
  5216.2 1385.42  5222.3 1388.62  5230.8 1389.79  5266.9 1391.98  5390.7 1394.35
#Mann=5,-1,0
  4006.5   0.035       0  4069.7    0.07       0  4168.7    0.12       0
  4987.1    0.05       0  4992.6    0.12       0
Bank Sta=4987.1,4992.6
Exp/Cntr=0.3,0.1

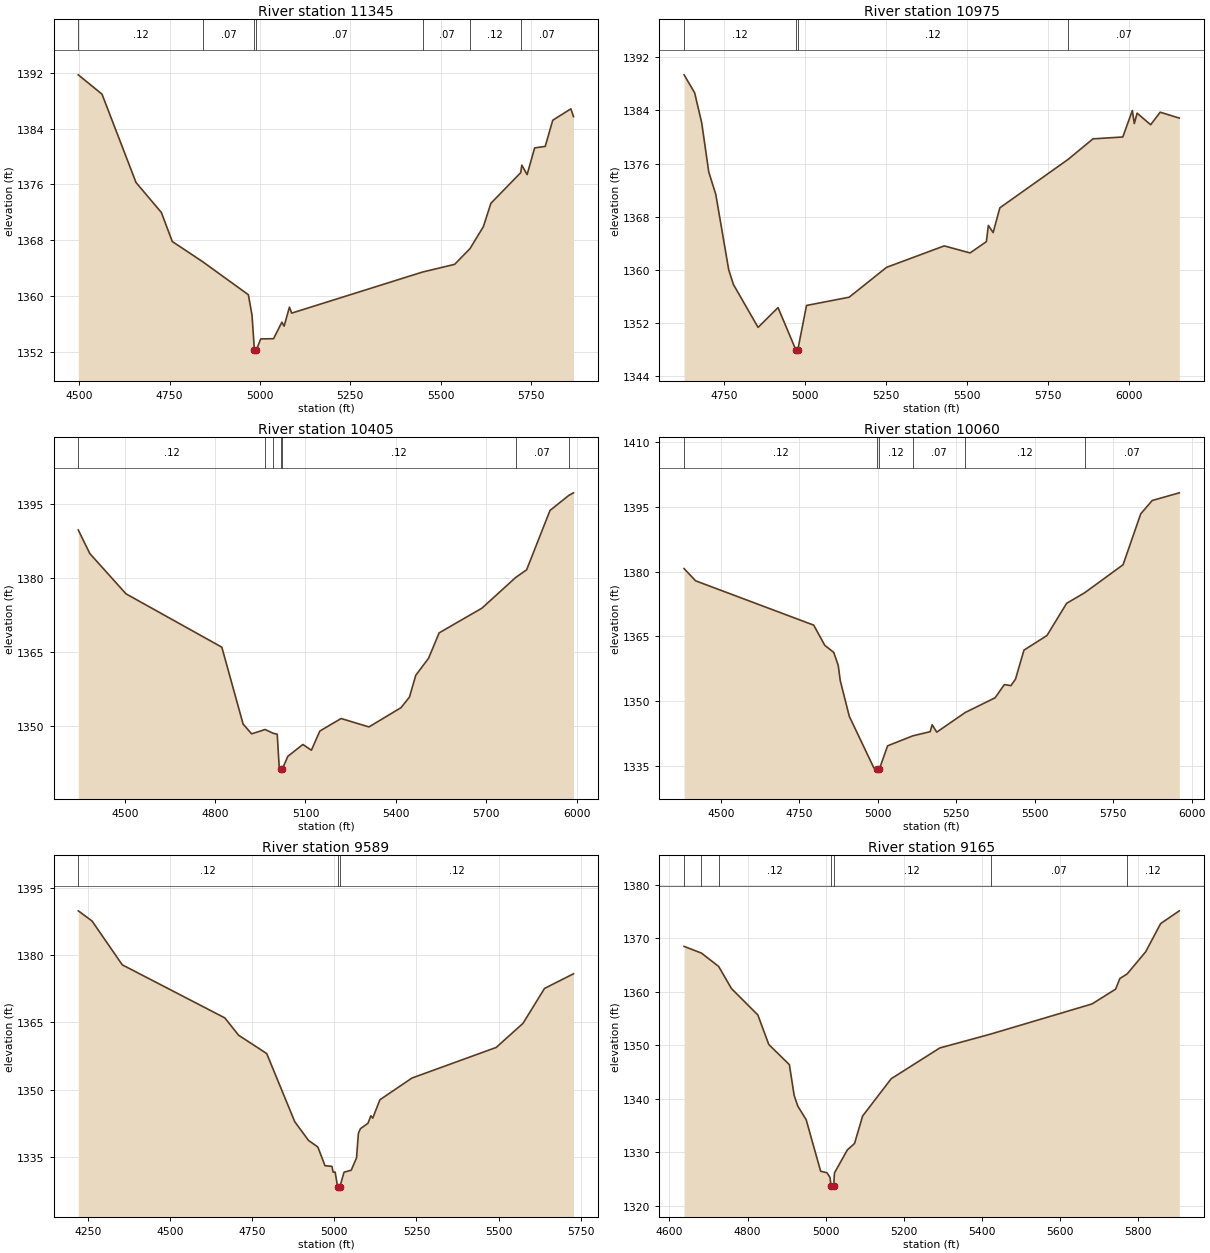
Type RM Length L Ch R = 1,11345,370,370,370
BEGIN DESCRIPTION:
VIOLET CREEK 25.0
END DESCRIPTION:
XS GIS Cut Line= 3
      2046275.72     13887785.64      2046768.80     13887743.97
      2047474.99     13887225.01
#Sta/Elev= 30
  4497.0 1391.71  4562.7 1388.93  4656.8 1376.26  4727.1 1371.95  4757.2 1367.79
  4841.7 1364.88  4967.9 1360.15  4978.0 1357.22  4984.5 1352.27  4985.0 1351.77
  4990.3 1352.27  5002.1 1353.81  5037.6 1353.84  5060.7 1356.21  5066.9 1355.64
  5081.6 1358.37  5087.8 1357.51  5450.4 1363.41  5539.1 1364.51  5581.6 1366.77
  5618.6 1369.92  5639.4 1373.27  5722.0 1377.67  5725.1 1378.75  5739.7 1377.39
  5760.6 1381.22  5789.9 1381.44  5810.7 1385.19  5860.9 1386.83  5868.2 1385.72
#Mann=7,-1,0
  4497.0    0.12       0  4841.7    0.07       0  4984.5    0.05       0
  4990.3    0.07       0  5450.4    0.07       0  5581.6    0.12       0
  5722.0    0.07       0
Bank Sta=4984.5,4990.3
Exp/Cntr=0.3,0.1

Type RM Length L Ch R = 1,10975,570,570,570
BEGIN DESCRIPTION:
VIOLET CREEK 24.0
END DESCRIPTION:
XS GIS Cut Line= 3
      2046825.00     13888375.01      2046975.00     13888025.00
      2047643.80     13887091.19
#Sta/Elev= 30
  4625.7 1389.35  4658.3 1386.65  4680.1 1382.13  4701.9 1374.74  4723.6 1371.36
  4763.5 1360.04  4778.0 1357.82  4854.2 1351.36  4915.8 1354.34  4970.8 1347.99
  4971.3 1347.49  4976.9 1347.99  5003.8 1354.66  5135.5 1355.90  5250.9 1360.39
  5429.1 1363.62  5508.9 1362.56  5559.3 1364.26  5565.4 1366.70  5580.1 1365.62
  5601.0 1369.35  5811.7 1376.63  5888.5 1379.72  5980.6 1380.00  6010.1 1383.98
  6016.2 1382.02  6024.8 1383.59  6066.6 1381.84  6096.1 1383.73  6155.1 1382.84
#Mann=4,-1,0
  4625.7    0.12       0  4970.8    0.05       0  4976.9    0.12       0
  5811.7    0.07       0
Bank Sta=4970.8,4976.9
Exp/Cntr=0.3,0.1

Type RM Length L Ch R = 1,10405,345,345,345
BEGIN DESCRIPTION:
VIOLET CREEK 23.0
END DESCRIPTION:
XS GIS Cut Line= 3
      2046949.33     13888723.16      2047407.68     13888250.91
      2048074.98     13887525.03
#Sta/Elev= 30
  4345.8 1389.71  4384.0 1384.94  4504.1 1376.76  4822.3 1365.93  4893.0 1350.32
  4921.3 1348.34  4966.3 1349.22  4992.3 1348.46  5006.2 1348.26  5013.0 1341.43
  5017.3 1341.27  5017.8 1340.77  5023.6 1341.27  5041.4 1343.77  5091.3 1346.18
  5119.7 1345.02  5147.8 1348.91  5218.3 1351.45  5310.8 1349.74  5416.9 1353.64
  5445.2 1355.79  5466.2 1360.23  5508.7 1363.68  5543.9 1368.84  5685.7 1373.84
  5798.0 1380.08  5834.3 1381.64  5911.9 1393.69  5974.1 1396.73  5989.9 1397.26
#Mann=7,-1,0
  4345.8    0.12       0  4966.3    0.07       0  4992.3    0.12       0
  5017.3    0.05       0  5023.6    0.12       0  5798.0    0.07       0
  5974.1    0.12       0
Bank Sta=5017.3,5023.6
Exp/Cntr=0.3,0.1

Type RM Length L Ch R = 1,10060,471,471,471
BEGIN DESCRIPTION:
VIOLET CREEK 22.0
END DESCRIPTION:
XS GIS Cut Line= 3
      2047154.18     13888865.52      2047625.00     13888475.00
      2048195.88     13887695.36
#Sta/Elev= 30
  4382.7 1380.72  4419.5 1377.88  4795.8 1367.59  4831.0 1362.91  4859.6 1361.26
  4873.9 1358.25  4880.4 1354.69  4909.1 1346.43  4987.2 1334.48  4998.4 1334.20
  4998.9 1333.70  5005.1 1334.20  5031.1 1339.57  5111.9 1341.90  5166.9 1342.86
  5173.1 1344.47  5187.8 1342.75  5278.6 1347.31  5373.8 1350.73  5403.2 1353.80
  5424.0 1353.55  5438.7 1355.04  5465.7 1361.79  5539.0 1365.18  5601.7 1372.66
  5658.7 1375.09  5781.5 1381.61  5837.8 1393.43  5874.4 1396.53  5960.7 1398.31
#Mann=6,-1,0
  4382.7    0.12       0  4998.4    0.05       0  5005.1    0.12       0
  5111.9    0.07       0  5278.6    0.12       0  5658.7    0.07       0
Bank Sta=4998.4,5005.1
Exp/Cntr=0.3,0.1

Type RM Length L Ch R = 1,9589,424,424,424
BEGIN DESCRIPTION:
VIOLET CREEK 21.0
END DESCRIPTION:
XS GIS Cut Line= 3
      2047390.31     13889289.12      2047975.00     13888775.00
      2048324.33     13888136.37
#Sta/Elev= 30
  4221.4 1389.82  4263.2 1387.56  4355.2 1377.81  4667.1 1366.01  4709.2 1362.15
  4794.6 1358.08  4879.9 1342.92  4921.7 1338.77  4950.2 1337.29  4972.0 1333.13
  4992.9 1333.00  4996.6 1331.71  5002.8 1331.71  5010.3 1328.43  5010.8 1327.93
  5017.1 1328.43  5029.8 1331.69  5051.7 1332.14  5067.8 1334.87  5073.5 1340.36
  5079.8 1341.38  5102.6 1342.58  5111.4 1344.23  5117.1 1343.72  5138.9 1347.80
  5236.6 1352.64  5492.7 1359.44  5574.3 1364.80  5639.7 1372.56  5727.9 1375.82
#Mann=3,-1,0
  4221.4    0.12       0  5010.3    0.05       0  5017.1    0.12       0
Bank Sta=5010.3,5017.1
Exp/Cntr=0.3,0.1

Type RM Length L Ch R = 1,9165,467,467,467
BEGIN DESCRIPTION:
VIOLET CREEK 20.0
END DESCRIPTION:
XS GIS Cut Line= 3
      2047862.55     13889309.94      2048175.00     13889125.00
      2048435.15     13888258.90
#Sta/Elev= 30
  4637.4 1368.47  4681.8 1367.22  4725.8 1364.73  4758.7 1360.58  4826.2 1355.65
  4854.2 1350.13  4906.9 1346.36  4919.1 1340.61  4928.4 1338.61  4949.8 1336.08
  4986.9 1326.44  5003.1 1326.15  5010.9 1325.28  5013.6 1323.59  5014.1 1323.09
  5020.4 1323.59  5022.2 1326.11  5055.3 1330.43  5073.6 1331.62  5094.4 1336.77
  5167.5 1343.73  5291.8 1349.48  5421.7 1352.07  5681.4 1357.71  5741.8 1360.48
  5752.7 1362.47  5771.3 1363.32  5818.7 1367.46  5857.0 1372.73  5904.8 1375.12
#Mann=7,-1,0
  4637.4    0.12       0  4681.8   0.035       0  4725.8    0.12       0
  5013.6    0.05       0  5020.4    0.12       0  5421.7    0.07       0
  5771.3    0.12       0
Bank Sta=5013.6,5020.4
Exp/Cntr=0.3,0.1

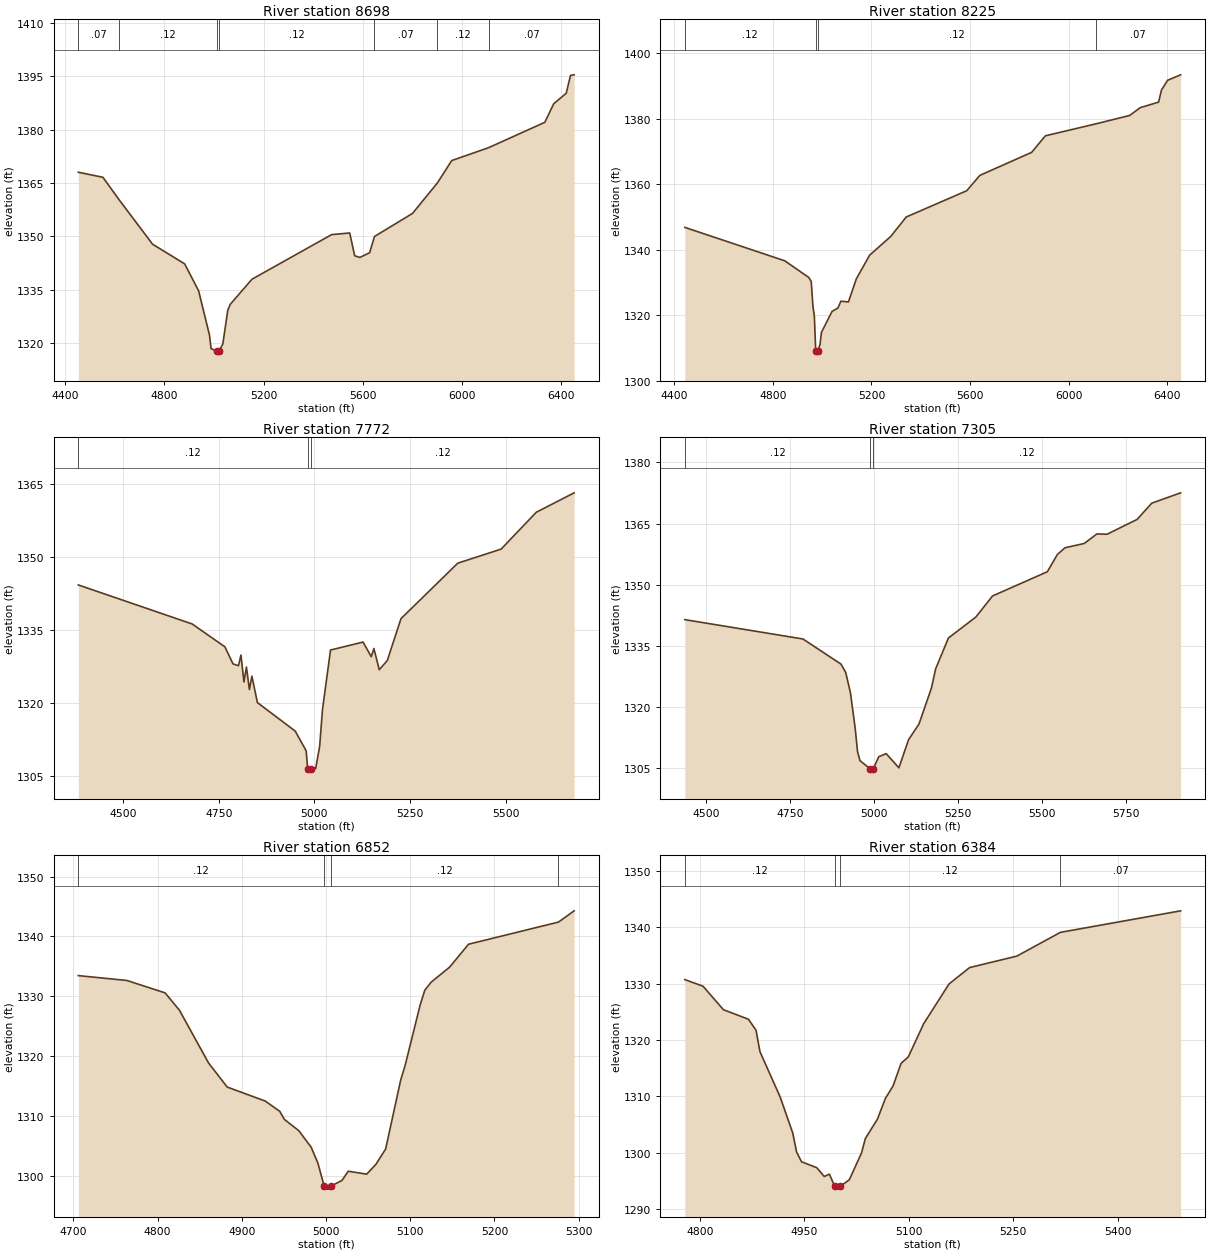
Type RM Length L Ch R = 1,8698,473,473,473
BEGIN DESCRIPTION:
VIOLET CREEK 19.0
END DESCRIPTION:
XS GIS Cut Line= 3
      2048202.84     13889862.01      2048525.00     13889425.00
      2048661.16     13887973.09
#Sta/Elev= 30
  4452.5 1368.03  4551.6 1366.62  4617.4 1360.26  4752.1 1347.78  4881.6 1342.25
  4938.0 1334.65  4981.9 1322.19  4988.1 1318.41  5012.1 1317.62  5012.6 1317.12
  5019.0 1317.62  5035.6 1319.65  5055.7 1329.19  5065.7 1330.86  5153.6 1337.93
  5474.9 1350.48  5547.8 1350.94  5567.9 1344.52  5588.8 1344.06  5628.2 1345.38
  5647.8 1349.95  5801.3 1356.44  5901.8 1365.03  5959.6 1371.32  6108.6 1374.95
  6335.2 1382.08  6371.4 1387.33  6421.7 1390.26  6439.0 1395.29  6453.7 1395.45
#Mann=7,-1,0
  4452.5    0.07       0  4617.4    0.12       0  5012.1    0.05       0
  5019.0    0.12       0  5647.8    0.07       0  5901.8    0.12       0
  6108.6    0.07       0
Bank Sta=5012.1,5019
Exp/Cntr=0.3,0.1

Type RM Length L Ch R = 1,8225,453,453,453
BEGIN DESCRIPTION:
VIOLET CREEK 18.0
END DESCRIPTION:
XS GIS Cut Line= 3
      2048688.93     13890129.39      2048925.00     13889625.00
      2049428.53     13888261.29
#Sta/Elev= 30
  4443.2 1346.86  4848.9 1336.64  4945.8 1331.56  4955.9 1330.34  4963.1 1322.53
  4968.6 1319.72  4974.2 1308.95  4974.7 1308.45  4981.8 1308.95  4991.4 1311.07
  4997.3 1314.78  5040.4 1321.21  5064.1 1322.22  5076.2 1324.32  5106.7 1324.08
  5138.7 1331.12  5192.5 1338.35  5278.5 1344.10  5341.2 1350.03  5586.4 1358.05
  5639.7 1362.74  5849.7 1369.77  5905.2 1374.82  6109.3 1378.46  6247.3 1381.04
  6290.0 1383.42  6364.6 1385.12  6376.0 1388.78  6401.1 1391.79  6453.8 1393.45
#Mann=4,-1,0
  4443.2    0.12       0  4974.2    0.05       0  4981.8    0.12       0
  6109.3    0.07       0
Bank Sta=4974.2,4981.8
Exp/Cntr=0.3,0.1

Type RM Length L Ch R = 1,7772,467,467,467
BEGIN DESCRIPTION:
VIOLET CREEK 17.0
END DESCRIPTION:
XS GIS Cut Line= 3
      2048800.04     13890219.67      2049275.00     13889825.00
      2049775.77     13889365.47
#Sta/Elev= 30
  4382.4 1344.31  4680.3 1336.28  4765.9 1331.58  4787.1 1328.07  4801.4 1327.70
  4807.9 1329.89  4815.7 1324.36  4822.2 1327.42  4830.0 1322.79  4836.5 1325.55
  4850.9 1320.11  4949.8 1314.25  4978.5 1310.18  4982.4 1306.51  4982.9 1306.01
  4990.1 1306.51  5003.3 1306.52  5013.8 1311.15  5021.2 1318.70  5042.2 1330.92
  5127.3 1332.56  5148.8 1329.54  5155.6 1331.24  5169.8 1326.87  5190.8 1328.77
  5226.5 1337.37  5375.1 1348.79  5488.5 1351.68  5580.5 1359.26  5679.6 1363.26
#Mann=3,-1,0
  4382.4    0.12       0  4982.4    0.05       0  4990.1    0.12       0
Bank Sta=4982.4,4990.1
Exp/Cntr=0.3,0.1

Type RM Length L Ch R = 1,7305,453,453,453
BEGIN DESCRIPTION:
VIOLET CREEK 16.0
END DESCRIPTION:
XS GIS Cut Line= 3
      2049116.02     13890563.41      2049525.00     13890175.00
      2049959.78     13889372.43
#Sta/Elev= 30
  4436.2 1341.42  4788.1 1336.67  4901.3 1330.51  4915.5 1328.45  4929.6 1323.46
  4943.8 1314.69  4950.7 1309.02  4957.9 1306.81  4989.2 1304.73  4989.7 1304.23
  4997.1 1304.73  5014.0 1307.77  5035.9 1308.53  5073.9 1305.04  5102.6 1311.93
  5133.9 1315.82  5170.8 1324.63  5183.3 1329.33  5221.3 1336.90  5303.1 1342.06
  5352.8 1347.23  5516.1 1353.18  5546.1 1357.44  5568.9 1359.07  5625.7 1360.11
  5663.5 1362.45  5694.0 1362.39  5783.4 1366.02  5827.1 1370.01  5913.0 1372.55
#Mann=3,-1,0
  4436.2    0.12       0  4989.2    0.05       0  4997.1    0.12       0
Bank Sta=4989.2,4997.1
Exp/Cntr=0.3,0.1

Type RM Length L Ch R = 1,6852,468,468,468
BEGIN DESCRIPTION:
VIOLET CREEK 15.0
END DESCRIPTION:
XS GIS Cut Line= 3
      2049796.56     13890594.70      2049925.00     13890325.00
      2050043.10     13890059.94
#Sta/Elev= 30
  4705.8 1333.45  4763.4 1332.64  4808.8 1330.57  4825.9 1327.67  4860.5 1318.85
  4882.7 1314.83  4927.8 1312.50  4945.0 1310.79  4950.5 1309.44  4967.7 1307.55
  4982.4 1304.77  4990.4 1302.11  4997.8 1298.29  4998.3 1297.79  5005.3 1297.79
  5005.8 1298.29  5018.9 1299.24  5026.4 1300.78  5048.3 1300.29  5059.3 1301.94
  5070.8 1304.49  5088.6 1315.96  5094.0 1318.48  5111.8 1328.55  5117.3 1331.01
  5124.9 1332.36  5146.8 1334.87  5169.2 1338.69  5276.1 1342.39  5294.7 1344.27
#Mann=4,-1,0
  4705.8    0.12       0  4997.8    0.05       0  5005.8    0.12       0
  5276.1    0.07       0
Bank Sta=4997.8,5005.8
Exp/Cntr=0.3,0.1

Type RM Length L Ch R = 1,6384,456,456,456
BEGIN DESCRIPTION:
VIOLET CREEK 14.0
END DESCRIPTION:
XS GIS Cut Line= 3
      2050070.89     13890712.72      2050275.00     13890625.00
      2050479.86     13890179.61
#Sta/Elev= 30
  4778.1 1330.72  4804.3 1329.54  4833.6 1325.38  4869.6 1323.68  4880.5 1321.72
  4886.1 1317.93  4915.1 1309.91  4933.2 1303.52  4938.7 1300.15  4945.8 1298.41
  4967.7 1297.36  4978.5 1295.80  4985.8 1296.22  4993.5 1294.06  4994.0 1293.56
  5001.6 1294.06  5014.5 1295.22  5032.0 1299.97  5037.5 1302.52  5054.9 1305.98
  5066.3 1309.64  5077.3 1311.85  5088.9 1315.87  5099.3 1317.02  5121.3 1322.89
  5157.8 1329.95  5187.4 1332.85  5255.2 1334.88  5317.7 1339.09  5490.5 1342.91
#Mann=4,-1,0
  4778.1    0.12       0  4993.5    0.05       0  5001.6    0.12       0
  5317.7    0.07       0
Bank Sta=4993.5,5001.6
Exp/Cntr=0.3,0.1

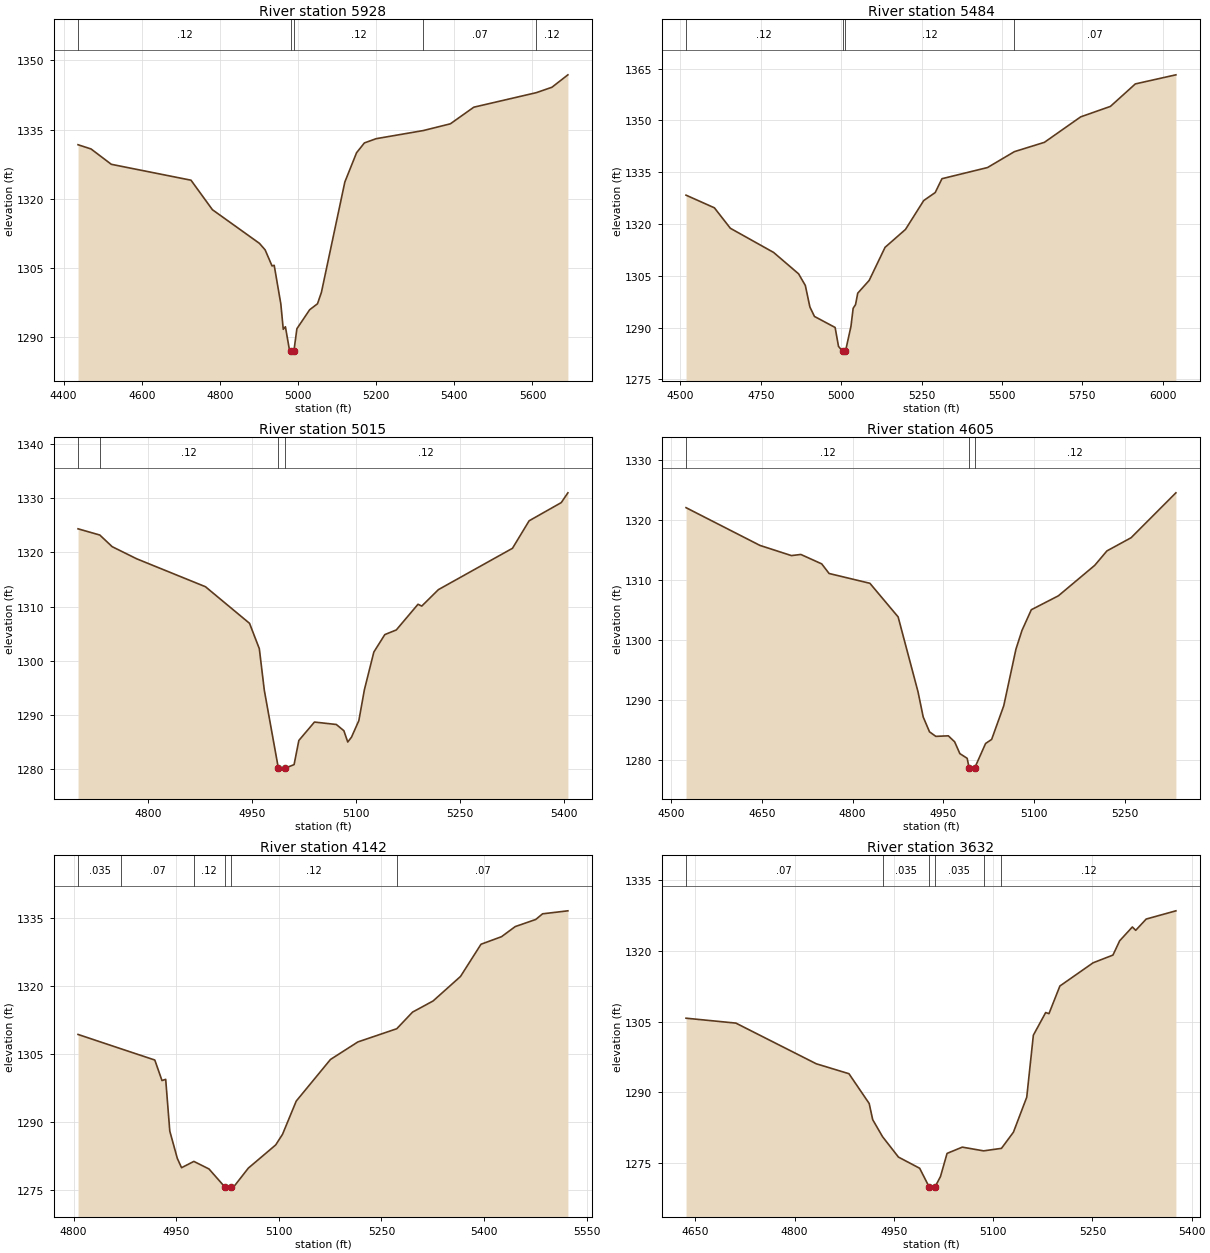
Type RM Length L Ch R = 1,5928,444,444,444
BEGIN DESCRIPTION:
VIOLET CREEK 13.0
END DESCRIPTION:
XS GIS Cut Line= 3
      2050445.90     13891289.07      2050675.00     13890775.00
      2050678.52     13890084.22
#Sta/Elev= 30
  4437.1 1331.73  4470.3 1330.82  4522.3 1327.49  4726.2 1324.05  4781.0 1317.66
  4901.4 1310.37  4915.9 1308.96  4933.6 1305.48  4939.1 1305.62  4956.1 1297.24
  4962.3 1291.76  4967.8 1292.31  4978.0 1287.36  4981.5 1287.10  4982.0 1286.60
  4989.6 1287.10  4997.2 1291.89  5029.9 1296.00  5049.9 1297.29  5059.9 1299.75
  5119.9 1323.66  5149.9 1330.00  5169.9 1332.12  5199.9 1333.04  5320.6 1334.80
  5389.9 1336.26  5449.9 1339.86  5610.0 1343.01  5649.9 1344.18  5690.7 1346.87
#Mann=5,-1,0
  4437.1    0.12       0  4981.5    0.05       0  4989.6    0.12       0
  5320.6    0.07       0  5610.0    0.12       0
Bank Sta=4981.5,4989.6
Exp/Cntr=0.3,0.1

Type RM Length L Ch R = 1,5484,469,469,469
BEGIN DESCRIPTION:
VIOLET CREEK 12.0
END DESCRIPTION:
XS GIS Cut Line= 3
      2050706.29     13891330.78      2051025.00     13890975.00
      2051734.05     13890205.80
#Sta/Elev= 30
  4517.4 1328.34  4605.7 1324.67  4655.3 1318.75  4789.8 1311.76  4867.6 1305.56
  4888.5 1302.20  4902.7 1295.97  4916.9 1293.23  4981.2 1290.04  4991.7 1284.57
  5004.5 1283.11  5005.0 1282.61  5013.3 1283.11  5030.5 1290.39  5037.3 1295.60
  5044.7 1296.65  5051.5 1299.96  5087.2 1303.67  5136.5 1313.23  5200.1 1318.42
  5256.8 1326.78  5292.5 1329.09  5313.5 1333.10  5455.2 1336.33  5538.8 1340.93
  5632.2 1343.63  5745.0 1351.00  5837.5 1354.03  5915.1 1360.54  6041.2 1363.17
#Mann=4,-1,0
  4517.4    0.12       0  5004.5    0.05       0  5013.3    0.12       0
  5538.8    0.07       0
Bank Sta=5004.5,5013.3
Exp/Cntr=0.3,0.1

Type RM Length L Ch R = 1,5015,410,410,410
BEGIN DESCRIPTION:
VIOLET CREEK 11.0
END DESCRIPTION:
XS GIS Cut Line= 3
      2051119.48     13891539.12      2051325.00     13891325.00
      2051480.30     13890946.09
#Sta/Elev= 30
  4698.9 1324.36  4730.3 1323.21  4748.1 1321.06  4783.6 1318.81  4882.6 1313.66
  4946.2 1306.89  4960.3 1302.20  4967.5 1294.51  4987.8 1280.08  4988.3 1279.58
  4996.6 1280.08  5010.4 1280.78  5017.3 1285.25  5039.8 1288.65  5071.3 1288.20
  5082.2 1287.05  5087.8 1284.96  5093.2 1285.86  5103.8 1288.92  5111.8 1294.63
  5125.4 1301.58  5141.2 1304.81  5157.8 1305.67  5189.1 1310.42  5194.5 1310.08
  5218.5 1313.12  5325.3 1320.76  5349.3 1325.84  5395.6 1329.20  5405.2 1331.01
#Mann=4,-1,0
  4698.9    0.07       0  4730.3    0.12       0  4987.8    0.05       0
  4996.6    0.12       0
Bank Sta=4987.8,4996.6
Exp/Cntr=0.3,0.1

Type RM Length L Ch R = 1,4605,463,463,463
BEGIN DESCRIPTION:
VIOLET CREEK 10.0
END DESCRIPTION:
XS GIS Cut Line= 3
      2051550.06     13891882.82      2051675.00     13891425.00
      2051692.41     13891091.22
#Sta/Elev= 30
  4525.0 1322.09  4647.1 1315.78  4699.0 1314.08  4714.6 1314.27  4749.1 1312.69
  4761.2 1311.09  4828.6 1309.45  4875.2 1303.83  4908.0 1291.33  4916.6 1287.11
  4927.0 1284.63  4937.4 1283.87  4958.1 1283.96  4968.5 1282.96  4977.1 1280.99
  4989.2 1280.20  4992.5 1278.56  4993.0 1278.06  5001.5 1278.56  5019.6 1282.68
  5029.6 1283.36  5049.6 1288.99  5069.7 1298.44  5079.7 1301.58  5095.1 1305.03
  5139.8 1307.36  5199.8 1312.45  5219.9 1314.86  5259.9 1317.07  5333.8 1324.57
#Mann=3,-1,0
  4525.0    0.12       0  4992.5    0.05       0  5001.5    0.12       0
Bank Sta=4992.5,5001.5
Exp/Cntr=0.3,0.1

Type RM Length L Ch R = 1,4142,510,510,510
BEGIN DESCRIPTION:
VIOLET CREEK 9.0
END DESCRIPTION:
XS GIS Cut Line= 3
      2051997.95     13891747.47      2052075.00     13891575.00
      2052077.81     13891048.00
#Sta/Elev= 30
  4806.6 1309.38  4869.6 1306.20  4918.8 1303.73  4929.3 1299.20  4934.7 1299.47
  4940.7 1288.04  4951.7 1282.01  4957.9 1279.96  4975.9 1281.35  4998.0 1279.68
  5021.0 1275.73  5021.5 1275.23  5030.0 1275.73  5035.5 1276.00  5055.5 1279.87
  5095.5 1284.99  5105.5 1287.35  5125.5 1294.67  5175.5 1303.85  5215.5 1307.72
  5272.4 1310.64  5295.5 1314.31  5325.5 1316.77  5365.5 1322.17  5395.5 1329.29
  5425.5 1330.96  5445.5 1333.19  5475.5 1334.76  5485.5 1336.01  5522.5 1336.67
#Mann=6,-1,0
  4806.6   0.035       0  4869.6    0.07       0  4975.9    0.12       0
  5021.0    0.05       0  5030.0    0.12       0  5272.4    0.07       0
Bank Sta=5021,5030
Exp/Cntr=0.3,0.1

Type RM Length L Ch R = 1,3632,391,391,391
BEGIN DESCRIPTION:
VIOLET CREEK 8.0
END DESCRIPTION:
XS GIS Cut Line= 3
      2052411.17     13891865.47      2052543.10     13891514.80
      2052515.32     13891150.22
#Sta/Elev= 30
  4635.9 1305.71  4711.2 1304.67  4832.7 1296.03  4882.1 1293.92  4912.7 1287.59
  4918.0 1284.16  4932.9 1280.54  4956.9 1276.21  4989.0 1273.83  5003.2 1269.90
  5003.7 1269.40  5012.3 1269.90  5020.4 1272.06  5030.4 1276.99  5053.4 1278.32
  5085.6 1277.53  5112.6 1278.06  5130.7 1281.50  5150.8 1288.93  5160.8 1302.10
  5179.4 1306.91  5184.4 1306.68  5200.9 1312.55  5251.1 1317.48  5281.1 1319.12
  5291.2 1322.15  5310.4 1325.09  5315.5 1324.38  5331.3 1326.77  5376.2 1328.52
#Mann=6,-1,0
  4635.9    0.07       0  4932.9   0.035       0  5003.2   0.035       0
  5012.3   0.035       0  5085.6    0.07       0  5112.6    0.12       0
Bank Sta=5003.2,5012.3
Exp/Cntr=0.3,0.1