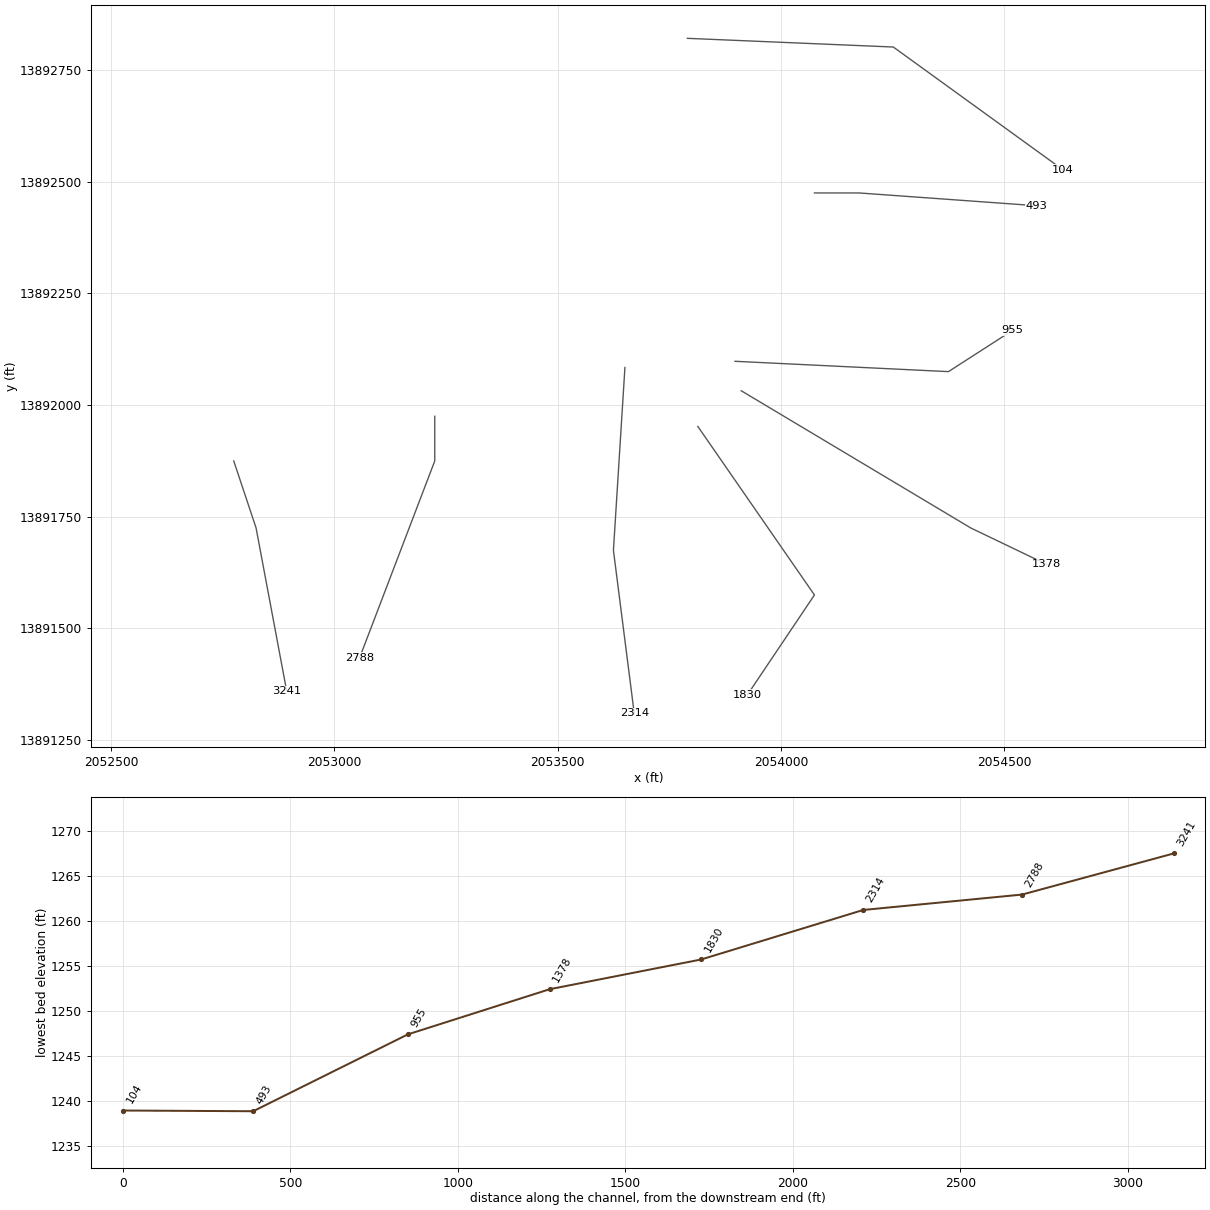
HEC-RAS study VIOLET CREEK.prj: VIOLET CREEK Base Level Engineering

--- VIOLET CREEK.g01 (geometry) --- (continued)

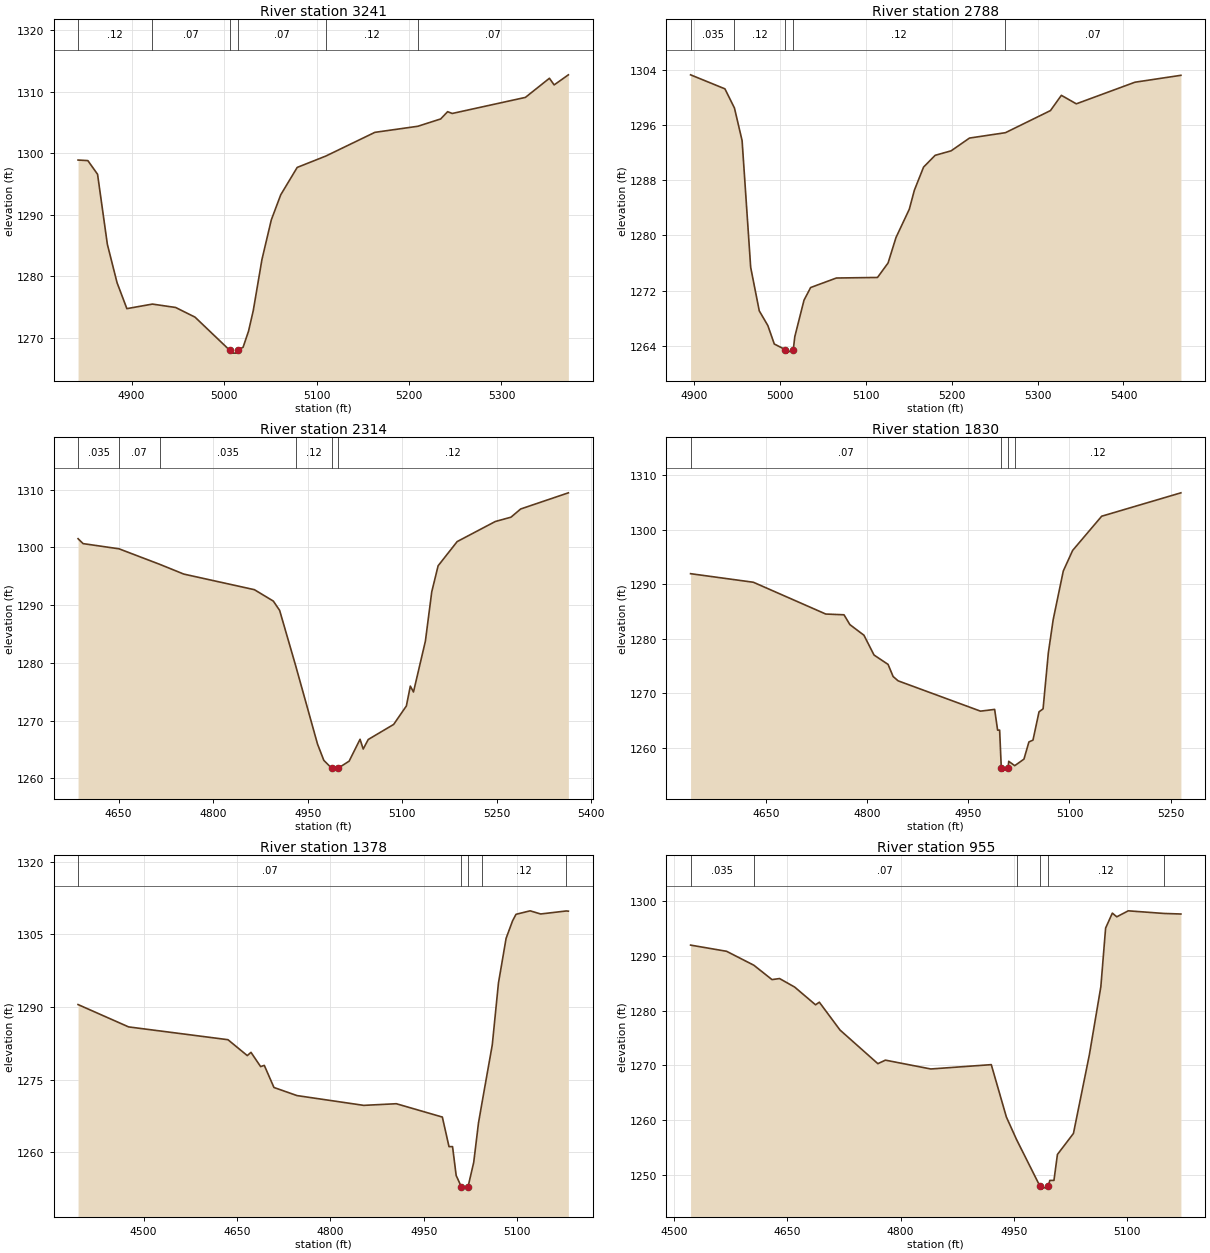
Type RM Length L Ch R = 1,3241,453,453,453
BEGIN DESCRIPTION:
VIOLET CREEK 7.0
END DESCRIPTION:
XS GIS Cut Line= 3
      2052774.99     13891875.04      2052825.00     13891725.00
      2052893.67     13891359.25
#Sta/Elev= 30
  4842.1 1298.90  4852.7 1298.81  4863.2 1296.59  4873.8 1285.20  4884.3 1278.96
  4894.9 1274.75  4922.5 1275.49  4947.6 1274.94  4968.6 1273.37  5005.9 1268.02
  5006.4 1267.52  5014.5 1267.52  5015.0 1268.02  5020.6 1268.48  5026.5 1271.10
  5031.6 1274.44  5041.0 1282.75  5051.1 1289.17  5061.3 1293.25  5079.1 1297.70
  5110.1 1299.55  5163.1 1303.40  5209.6 1304.39  5234.3 1305.58  5241.8 1306.76
  5246.8 1306.47  5325.9 1309.08  5351.9 1312.19  5357.0 1311.11  5372.4 1312.75
#Mann=6,-1,0
  4842.1    0.12       0  4922.5    0.07       0  5005.9    0.05       0
  5015.0    0.07       0  5110.1    0.12       0  5209.6    0.07       0
Bank Sta=5005.9,5015
Exp/Cntr=0.3,0.1

Type RM Length L Ch R = 1,2788,474,474,474
BEGIN DESCRIPTION:
VIOLET CREEK 6.0
END DESCRIPTION:
XS GIS Cut Line= 3
      2053225.00     13891975.00      2053225.00     13891875.00
      2053057.00     13891434.98
#Sta/Elev= 30
  4895.9 1303.26  4935.9 1301.23  4947.0 1298.45  4955.9 1293.73  4965.9 1275.37
  4975.9 1269.07  4985.9 1266.94  4993.4 1264.27  5006.3 1263.45  5006.8 1262.95
  5015.5 1263.45  5017.3 1265.35  5028.0 1270.62  5035.7 1272.45  5065.7 1273.83
  5113.6 1273.91  5125.9 1276.01  5135.1 1279.69  5150.6 1283.79  5156.5 1286.54
  5167.2 1289.89  5180.7 1291.60  5199.3 1292.25  5220.7 1294.10  5262.6 1294.88
  5315.0 1298.08  5327.7 1300.29  5345.1 1299.06  5413.4 1302.19  5466.9 1303.19
#Mann=5,-1,0
  4895.9   0.035       0  4947.0    0.12       0  5006.3    0.05       0
  5015.5    0.12       0  5262.6    0.07       0
Bank Sta=5006.3,5015.5
Exp/Cntr=0.3,0.1

Type RM Length L Ch R = 1,2314,484,484,484
BEGIN DESCRIPTION:
VIOLET CREEK 5.0
END DESCRIPTION:
XS GIS Cut Line= 3
      2053650.74     13892084.26      2053625.00     13891675.00
      2053671.58     13891309.93
#Sta/Elev= 30
  4585.6 1301.51  4593.6 1300.66  4650.6 1299.76  4715.0 1297.08  4753.4 1295.38
  4865.4 1292.68  4895.5 1290.70  4905.5 1289.09  4930.8 1279.56  4965.6 1265.93
  4975.6 1263.11  4988.1 1261.74  4988.6 1261.24  4998.2 1261.74  5015.8 1262.97
  5033.1 1266.76  5038.1 1265.07  5046.1 1266.72  5086.4 1269.33  5106.6 1272.53
  5112.9 1275.97  5117.9 1274.95  5136.8 1283.77  5146.9 1292.32  5157.0 1296.82
  5187.2 1301.01  5247.7 1304.49  5272.6 1305.24  5288.0 1306.66  5363.7 1309.46
#Mann=6,-1,0
  4585.6   0.035       0  4650.6    0.07       0  4715.0   0.035       0
  4930.8    0.12       0  4988.1    0.05       0  4998.2    0.12       0
Bank Sta=4988.1,4998.2
Exp/Cntr=0.3,0.1

Type RM Length L Ch R = 1,1830,452,452,452
BEGIN DESCRIPTION:
VIOLET CREEK 4.0
END DESCRIPTION:
XS GIS Cut Line= 3
      2053813.94     13891952.30      2054075.00     13891575.00
      2053925.03     13891351.58
#Sta/Elev= 30
  4537.5 1291.95  4630.7 1290.38  4738.2 1284.55  4765.3 1284.41  4774.0 1282.61
  4794.9 1280.66  4809.8 1277.04  4830.7 1275.31  4838.2 1273.09  4845.6 1272.30
  4967.9 1266.74  4988.9 1267.06  4993.3 1263.26  4996.3 1263.26  4998.8 1256.24
  4999.3 1255.74  5008.9 1256.24  5009.8 1257.54  5018.7 1256.74  5032.4 1257.94
  5039.8 1261.10  5045.8 1261.42  5054.8 1266.62  5060.8 1267.16  5068.6 1277.42
  5075.8 1283.52  5090.8 1292.44  5104.7 1296.22  5147.8 1302.49  5265.4 1306.78
#Mann=4,-1,0
  4537.5    0.07       0  4998.8    0.05       0  5008.9    0.07       0
  5018.7    0.12       0
Bank Sta=4998.8,5008.9
Exp/Cntr=0.3,0.1

Type RM Length L Ch R = 1,1378,423,423,423
BEGIN DESCRIPTION:
VIOLET CREEK 3.0
END DESCRIPTION:
XS GIS Cut Line= 3
      2053911.16     13892032.16      2054425.00     13891725.00
      2054595.15     13891643.29
#Sta/Elev= 30
  4394.7 1290.52  4475.9 1285.91  4635.4 1283.27  4666.5 1279.99  4672.4 1280.66
  4687.9 1277.72  4693.8 1277.97  4709.3 1273.41  4746.3 1271.74  4853.5 1269.72
  4905.8 1270.06  4979.7 1267.31  4990.4 1261.21  4996.1 1261.21  5001.9 1255.26
  5010.1 1252.94  5010.6 1252.44  5021.0 1252.94  5030.1 1257.96  5037.7 1266.06
  5043.9 1270.62  5059.9 1282.21  5069.8 1294.95  5082.1 1304.19  5092.5 1307.80
  5098.0 1309.14  5120.7 1309.86  5137.6 1309.21  5178.7 1309.83  5182.1 1309.79
#Mann=5,-1,0
  4394.7    0.07       0  5010.1    0.05       0  5021.0    0.07       0
  5043.9    0.12       0  5178.7    0.07       0
Bank Sta=5010.1,5021
Exp/Cntr=0.3,0.1

Type RM Length L Ch R = 1,955,462,462,462
BEGIN DESCRIPTION:
VIOLET CREEK 2.0
END DESCRIPTION:
XS GIS Cut Line= 3
      2053897.31     13892098.13      2054375.00     13892075.00
      2054518.82     13892167.60
#Sta/Elev= 30
  4521.8 1291.93  4569.5 1290.80  4605.6 1288.26  4629.6 1285.64  4639.6 1285.83
  4659.6 1284.28  4687.3 1281.04  4692.3 1281.52  4719.7 1276.44  4769.8 1270.31
  4779.8 1270.95  4839.9 1269.34  4920.0 1270.13  4940.0 1260.58  4953.4 1256.49
  4984.6 1247.93  4985.1 1247.43  4995.5 1247.93  4997.5 1249.02  5003.0 1249.02
  5007.6 1253.75  5028.8 1257.58  5049.9 1271.94  5065.1 1284.34  5071.4 1295.03
  5080.3 1297.76  5086.2 1297.09  5101.4 1298.18  5148.7 1297.70  5171.1 1297.60
#Mann=6,-1,0
  4521.8   0.035       0  4605.6    0.07       0  4953.4    0.12       0
  4984.6    0.05       0  4995.5    0.12       0  5148.7    0.07       0
Bank Sta=4984.6,4995.5
Exp/Cntr=0.3,0.1

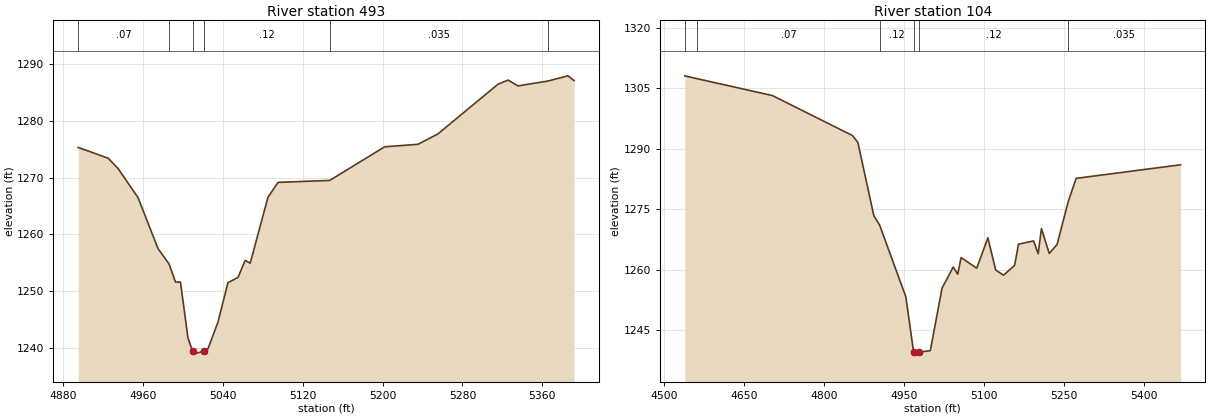
Type RM Length L Ch R = 1,493,389,389,389
BEGIN DESCRIPTION:
VIOLET CREEK 1.0
END DESCRIPTION:
XS GIS Cut Line= 3
      2054075.00     13892475.00      2054175.00     13892475.00
      2054571.07     13892446.48
#Sta/Elev= 30
  4894.8 1275.33  4924.8 1273.43  4934.8 1271.60  4954.8 1266.47  4974.8 1257.50
  4985.9 1254.78  4992.3 1251.59  4997.3 1251.59  5004.8 1241.80  5009.4 1239.39
  5009.9 1238.89  5020.4 1239.39  5024.9 1239.84  5034.9 1244.52  5044.9 1251.50
  5055.0 1252.41  5062.2 1255.42  5067.2 1254.91  5085.0 1266.52  5095.1 1269.17
  5146.9 1269.51  5202.0 1275.44  5235.4 1275.88  5255.5 1277.72  5315.6 1286.47
  5325.7 1287.20  5335.7 1286.17  5365.6 1287.03  5385.8 1287.95  5391.9 1287.10
#Mann=6,-1,0
  4894.8    0.07       0  4985.9    0.12       0  5009.4    0.05       0
  5020.4    0.12       0  5146.9   0.035       0  5365.6    0.12       0
Bank Sta=5009.4,5020.4
Exp/Cntr=0.3,0.1

Type RM Length L Ch R = 1,104,0,0,0
BEGIN DESCRIPTION:
VIOLET CREEK 0.0
END DESCRIPTION:
XS GIS Cut Line= 3
      2053790.52     13892821.14      2054251.61     13892801.69
      2054631.38     13892526.82
#Sta/Elev= 30
  4538.5 1308.13  4561.8 1307.42  4703.1 1303.22  4853.3 1293.28  4863.3 1291.58
  4893.3 1273.35  4904.2 1271.01  4953.3 1253.21  4967.9 1239.47  4968.4 1238.97
  4978.9 1239.47  4999.2 1239.83  5021.3 1255.40  5042.2 1260.60  5050.7 1258.83
  5056.9 1262.96  5086.3 1260.33  5107.2 1267.87  5121.9 1259.87  5136.6 1258.59
  5157.4 1261.03  5164.7 1266.30  5193.0 1267.10  5201.5 1263.93  5207.7 1270.16
  5222.4 1263.97  5237.1 1266.25  5257.4 1276.61  5272.7 1282.65  5468.8 1286.02
#Mann=6,-1,0
  4538.5    0.12       0  4561.8    0.07       0  4904.2    0.12       0
  4967.9    0.05       0  4978.9    0.12       0  5257.4   0.035       0
Bank Sta=4967.9,4978.9
Exp/Cntr=0.3,0.1

Chan Stop Cuts=-1