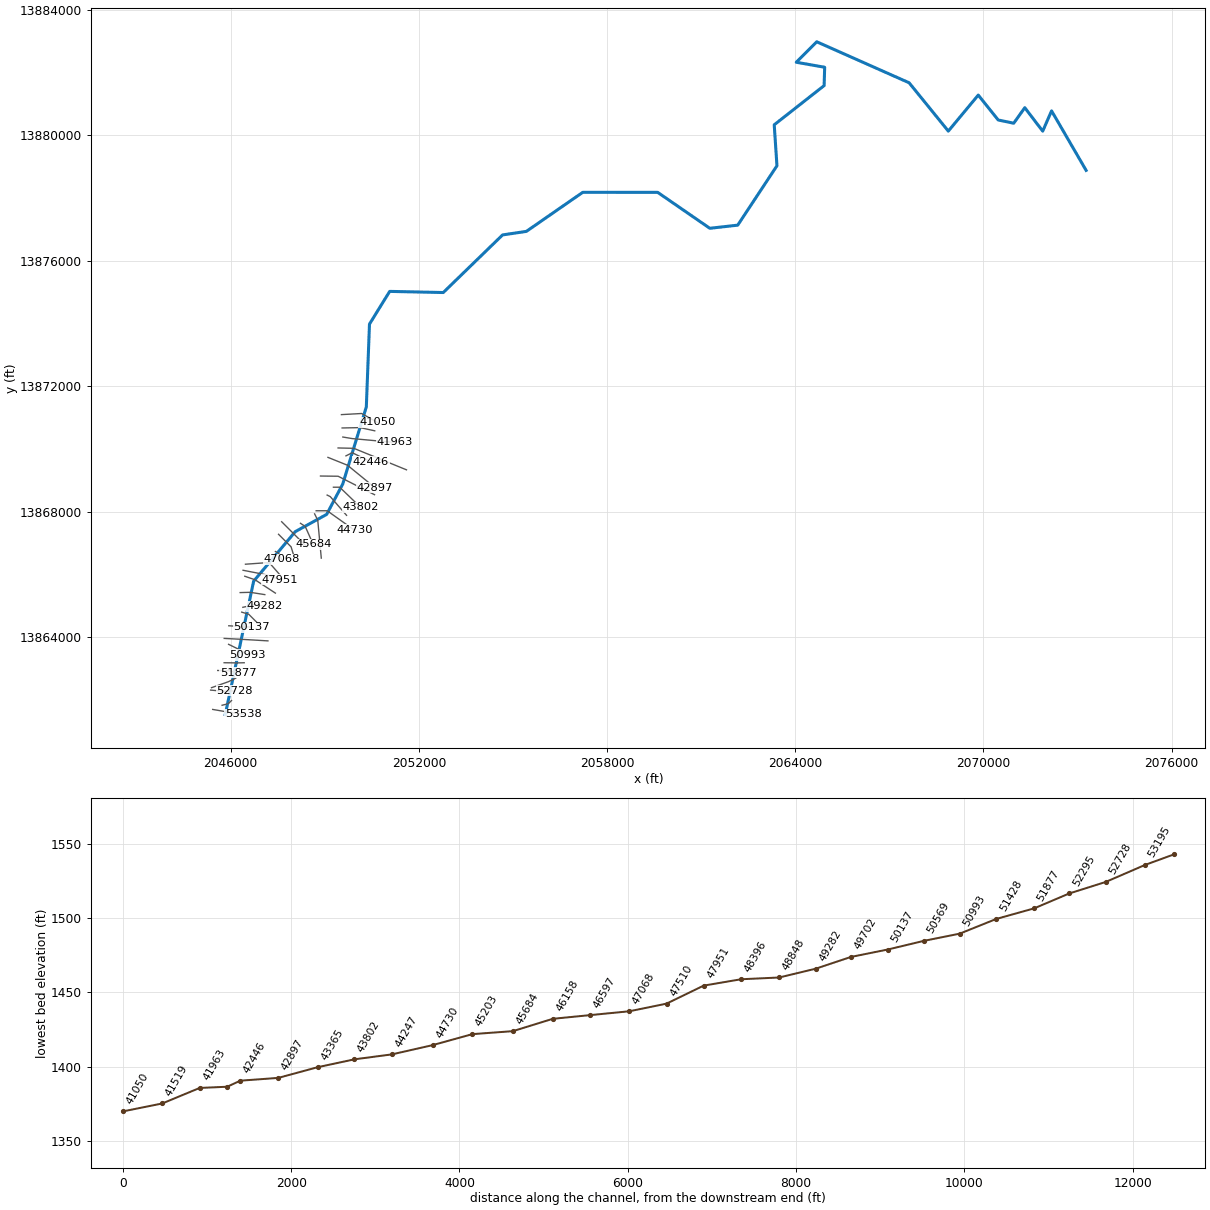
--- WASP CREEK.prj (project) ---

Proj Title=WASP CREEK Base Level Engineering
Current Plan=p01
Default Exp/Contr=0.3,0.1
English Units
Geom File=g01
Flow File=f01
Plan File=p01
Y Axis Title=Elevation
X Axis Title(PF)=Main Channel Distance
X Axis Title(XS)=Station
BEGIN DESCRIPTION:
WASP CREEK
END DESCRIPTION:
DSS Export Rating Curves= 0
DSS Export Rating Curve Sorted= 0
DSS Export Volume Flow Curves= 0
DXF OffsetX= 0
DXF OffsetY= 0
DXF ScaleX= 1
DXF ScaleY= 10

--- WASP CREEK.p01 (plan) ---

Plan Title=Multiple Run
Short Identifier=Multiple
Geom File=g01
Flow File=f01
Subcritical Flow
K Sum by GR= 0
Std Step Tol= 0.01
Critical Tol= 0.01
Num of Std Step Trials= 20
Max Error Tol= 0.3
Flow Tol Ratio= 0.001
Split Flow NTrial= 30
Split Flow Tol= 0.02
Split Flow Ratio= 0.02
Log Output Level= 0
Friction Slope Method= 1
Unsteady Friction Slope Method= 2
Unsteady Bridges Friction Slope Method= 1
Parabolic Critical Depth
Global Vel Dist=  1 , 1 , 1
Global Log Level= 0
CheckData=True
Encroach Param= -1, 0, 0, 0
BEGIN DESCRIPTION:
Multiple Run
END DESCRIPTION:

--- WASP CREEK.f01 (steady flow) ---

Flow Title=Multiple
Program Version=4.10
Number of Profiles= 7
Profile Names=10-year,25-year,50-year,1pct_min,100-year,1pct_plu,500-year
River Rch & RM=WASP CREEK,Reach-1         ,53538
     991    1678    2336    1580    3152    6289    5666
River Rch & RM=WASP CREEK,Reach-1         ,50993
    1505    2603    3670    2509    5006    9988    9204
River Rch & RM=WASP CREEK,Reach-1         ,46597
    2384    4225    6054    4199    8377   16715   15867
River Rch & RM=WASP CREEK,Reach-1         ,43365
    2707    4811    6909    4797    9571   19096   18173
River Rch & RM=WASP CREEK,Reach-1         ,39709
    3334    5984    8648    6039   12049   24041   23150
River Rch & RM=WASP CREEK,Reach-1         ,37896
    4725    8594   12531    8816   17591   35098   34317
River Rch & RM=WASP CREEK,Reach-1         ,32918
    4709    8537   12419    8715   17389   34697   33754
River Rch & RM=WASP CREEK,Reach-1         ,29341
    5808   10600   15490   10912   21772   43440   42580
River Rch & RM=WASP CREEK,Reach-1         ,25737
    6310   11521   16838   11858   23661   47209   46250
River Rch & RM=WASP CREEK,Reach-1         ,18884
    6819   12503   18321   12931   25802   51481   50679
River Rch & RM=WASP CREEK,Reach-1         ,13868
    7125   13008   19009   13377   26691   53255   52092
River Rch & RM=WASP CREEK,Reach-1         ,6574
    7468   13627   19907   14001   27935   55738   54455
Boundary for River Rch & Prof#=WASP CREEK,Reach-1         , 1
Up Type= 0
Dn Type= 3
Dn Slope=0.002
Boundary for River Rch & Prof#=WASP CREEK,Reach-1         , 2
Up Type= 0
Dn Type= 3
Dn Slope=0.002
Boundary for River Rch & Prof#=WASP CREEK,Reach-1         , 3
Up Type= 0
Dn Type= 3
Dn Slope=0.002
Boundary for River Rch & Prof#=WASP CREEK,Reach-1         , 4
Up Type= 0
Dn Type= 3
Dn Slope=0.002
Boundary for River Rch & Prof#=WASP CREEK,Reach-1         , 5
Up Type= 0
Dn Type= 3
Dn Slope=0.002
Boundary for River Rch & Prof#=WASP CREEK,Reach-1         , 6
Up Type= 0
Dn Type= 3
Dn Slope=0.002
Boundary for River Rch & Prof#=WASP CREEK,Reach-1         , 7
Up Type= 0
Dn Type= 3
Dn Slope=0.002
DSS Import GetInterval= 0
DSS Import GetPeak= 0
DSS Import FillOption= 0

--- WASP CREEK.g01 (geometry) ---

Geom Title=Existing Conditions
Program Version=4.10

River Reach=WASP CREEK      ,Reach-1
Reach XY= 30
        2045825.       13861525.      2046730.71     13865777.58
      2048057.95     13867358.87      2049058.57     13867908.23
       2049571.9     13868876.65      2050323.95     13871335.44
        2050425.       13873975.      2051068.81     13875017.17
      2052777.29      13874980.8      2054668.81     13876817.19
      2055427.29     13876930.11        2057225.       13878175.
      2059614.56     13878173.95      2061276.25     13877028.45
      2062166.52     13877128.49      2063416.93     13879021.69
      2063330.09      13880327.3      2064921.25     13881576.55
      2064938.73     13882161.84      2064032.65     13882321.31
       2064685.5      13882973.8      2067631.17     13881667.24
      2068881.03     13880126.61      2069835.64     13881274.45
      2070472.32     13880480.42      2070966.72     13880378.06
      2071319.03     13880872.86      2071891.02     13880125.16
      2072173.41     13880771.33        2073275.       13878875.

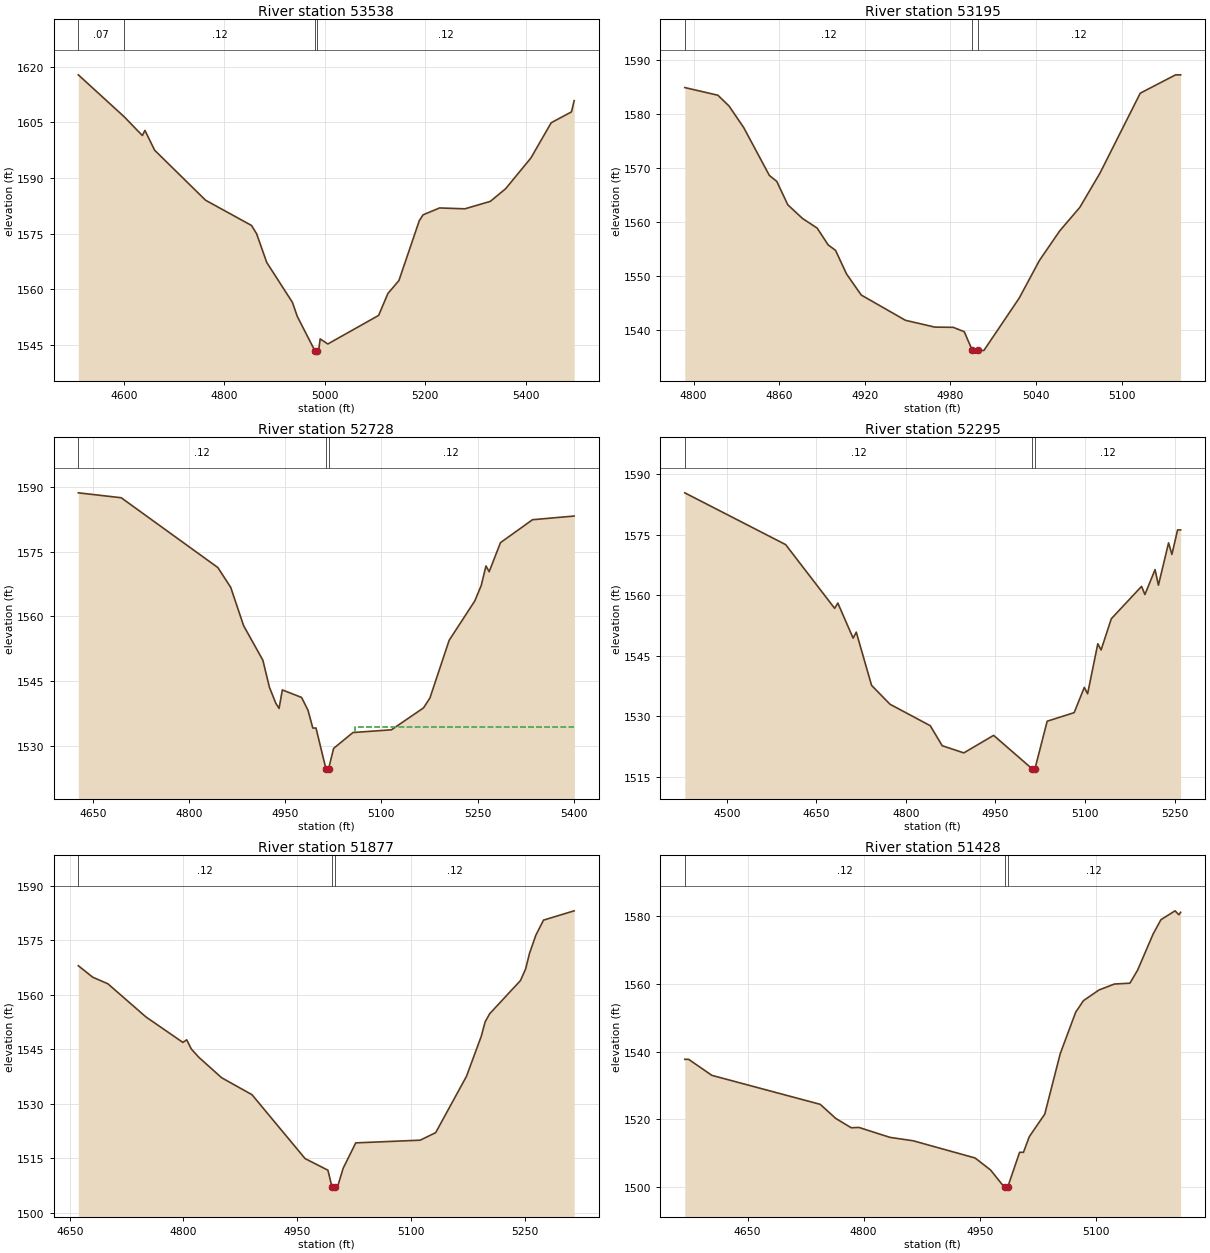
Type RM Length L Ch R = 1 ,53538   ,343,343,343
BEGIN DESCRIPTION:
WASP CREEK 103.0
END DESCRIPTION:
XS GIS Cut Line= 3
      2045425.35     13861691.93      2045893.81     13861610.84
      2046400.21     13861536.87
#Sta/Elev= 30
  4509.5 1617.79  4600.7 1606.49    4637 1601.42  4642.1 1602.81  4661.4 1597.47
  4762.9 1583.97  4854.2 1577.18  4864.4 1574.96  4884.7 1567.18  4935.8 1556.42
  4945.5 1552.63    4981 1543.24  4981.2 1542.74    4985 1543.24  4987.8 1543.24
    4991 1546.58  5006.3 1545.21  5107.4 1552.91  5125.8 1558.81  5147.8 1562.31
  5188.3 1578.44  5195.8 1580.03  5228.7 1581.89  5279.2 1581.66  5329.7 1583.66
  5360.1 1587.05  5410.7 1595.39    5451 1604.87  5491.4  1607.8  5496.7 1610.82
#Mann= 4 ,-1 , 0
  4509.5     .07       0  4600.7     .12       0    4981     .05       0
    4985     .12       0
Bank Sta=4981,4985
XS Rating Curve= 0 ,0
Exp/Cntr=0.3,0.1

Type RM Length L Ch R = 1 ,53195   ,467,467,467
BEGIN DESCRIPTION:
WASP CREEK 102.0
END DESCRIPTION:
XS GIS Cut Line= 3
      2045724.96     13861824.99        2045925.       13861875.
      2046024.99     13861974.99
#Sta/Elev= 30
  4793.8 1584.85    4817 1583.43  4824.8 1581.44  4835.1 1577.44  4853.1 1568.57
  4858.3 1567.47    4866 1563.14  4876.3 1560.61  4886.6 1558.82  4894.3 1555.71
  4899.5 1554.69  4907.2 1550.32  4917.5 1546.42  4948.5 1541.74  4969.1 1540.48
    4982 1540.44  4989.7 1539.63  4995.4 1536.16  4995.7 1535.66  4999.2 1535.66
  4999.4 1536.16  5003.5 1536.16  5028.3 1545.88  5042.4 1552.82  5056.6 1558.29
  5070.7 1562.65  5084.9 1569.02  5113.1 1583.81  5137.9 1587.21  5141.4 1587.21
#Mann= 3 ,-1 , 0
  4793.8     .12       0  4995.4     .05       0  4999.4     .12       0
Bank Sta=4995.4,4999.4
XS Rating Curve= 0 ,0
Exp/Cntr=0.3,0.1

Type RM Length L Ch R = 1 ,52728   ,433,433,433
BEGIN DESCRIPTION:
WASP CREEK 101.0
END DESCRIPTION:
XS GIS Cut Line= 3
      2045358.38     13862308.48        2045725.       13862275.
      2046129.89      13862282.5
#Sta/Elev= 30
  4627.6 1588.61  4694.5 1587.47  4845.1 1571.33  4865.2 1566.74  4885.3 1557.88
  4915.4 1549.86  4925.5 1543.65  4935.5 1539.93  4940.6 1538.73  4945.7 1543.01
  4975.7 1541.27  4985.7 1538.31  4993.2 1534.19  4998.2 1534.19  5013.7 1524.72
    5014 1524.22  5017.7 1524.72  5025.7 1529.49  5055.8 1533.15  5115.8 1533.78
  5165.8 1538.85  5175.8 1541.14  5205.8 1554.49  5245.8 1563.61  5255.8 1567.17
  5263.2 1571.69  5268.2 1570.36  5285.8 1577.08  5335.8 1582.39  5400.7 1583.24
#Mann= 3 ,-1 , 0
  4627.6     .12       0  5013.7     .05       0  5017.7     .12       0
#XS Ineff= 2 , 0
       0                 5059.33       0 1534.34
Permanent Ineff=
       F       F
Bank Sta=5013.7,5017.7
XS Rating Curve= 0 ,0
Exp/Cntr=0.3,0.1

Type RM Length L Ch R = 1 ,52295   ,418,418,418
BEGIN DESCRIPTION:
WASP CREEK 100.0
END DESCRIPTION:
XS GIS Cut Line= 3
      2045387.42     13862384.88        2045925.       13862575.
      2046159.24     13862688.28
#Sta/Elev= 30
  4429.7 1585.34  4598.6 1572.53  4680.7 1556.75    4686 1558.07  4711.6 1549.39
  4716.9 1550.87  4742.5  1537.7  4773.4 1533.03  4840.8 1527.72  4860.8 1522.77
    4897 1520.99  4946.9 1525.33    5012 1516.98  5012.2 1516.48    5016 1516.98
  5036.6 1528.83  5081.8 1530.95  5098.8  1537.2  5104.3 1535.61  5121.4 1547.99
  5126.9 1546.46    5144 1554.18  5194.7  1562.2  5200.3 1560.17  5217.3 1566.35
  5222.9 1562.48  5239.9 1572.96  5245.5  1570.1    5255 1576.16  5260.1 1576.16
#Mann= 3 ,-1 , 0
  4429.7     .12       0    5012     .05       0    5016     .12       0
Bank Sta=5012,5016
XS Rating Curve= 0 ,0
Exp/Cntr=0.3,0.1

Type RM Length L Ch R = 1 ,51877   ,449,449,449
BEGIN DESCRIPTION:
WASP CREEK 99.0
END DESCRIPTION:
XS GIS Cut Line= 3
      2045586.05     13862933.59        2045925.       13862925.
      2046234.71     13862868.92
#Sta/Elev= 30
  4661.4 1568.03  4680.4 1564.86  4700.4 1563.05  4750.4 1553.94  4799.3 1546.89
  4804.3 1547.61  4810.4 1545.07  4820.4 1542.77  4850.4 1537.15  4890.4 1532.48
  4960.4 1514.87  4990.5 1511.67    4996 1506.95  4996.2 1506.45    5000 1506.95
    5003 1506.95  5010.6  1512.2  5027.2  1519.2  5112.2 1519.94  5132.6 1522.02
  5173.2 1537.54  5192.7 1548.57  5197.8 1552.54  5203.7 1554.77  5244.4 1563.94
  5251.2 1567.13  5256.3 1571.42  5264.7 1576.45  5274.8  1580.6  5315.2 1583.16
#Mann= 3 ,-1 , 0
  4661.4     .12       0    4996     .05       0    5000     .12       0
Bank Sta=4996,5000
XS Rating Curve= 0 ,0
Exp/Cntr=0.3,0.1

Type RM Length L Ch R = 1 ,51428   ,435,435,435
BEGIN DESCRIPTION:
WASP CREEK 98.0
END DESCRIPTION:
XS GIS Cut Line= 3
      2045790.03     13863180.36        2046225.       13863175.
      2046430.44      13863180.1
#Sta/Elev= 30
    4569 1537.73    4574 1537.73    4604 1532.99    4744 1524.42    4764 1520.26
    4784  1517.5    4794 1517.59    4834 1514.66    4864 1513.65    4944 1508.56
    4964 1505.01    4982 1499.85  4982.2 1499.35    4986 1499.85  5001.5 1510.24
  5006.5 1510.24    5014 1514.86    5034 1521.54    5054 1539.42    5074  1551.7
    5084 1555.09    5104 1558.24    5124    1560    5144 1560.25    5154 1564.15
  5174.1 1574.86  5184.1 1579.03  5202.3 1581.65  5207.3 1580.48  5209.5 1581.22
#Mann= 3 ,-1 , 0
    4569     .12       0    4982     .05       0    4986     .12       0
Bank Sta=4982,4986
XS Rating Curve= 0 ,0
Exp/Cntr=0.3,0.1

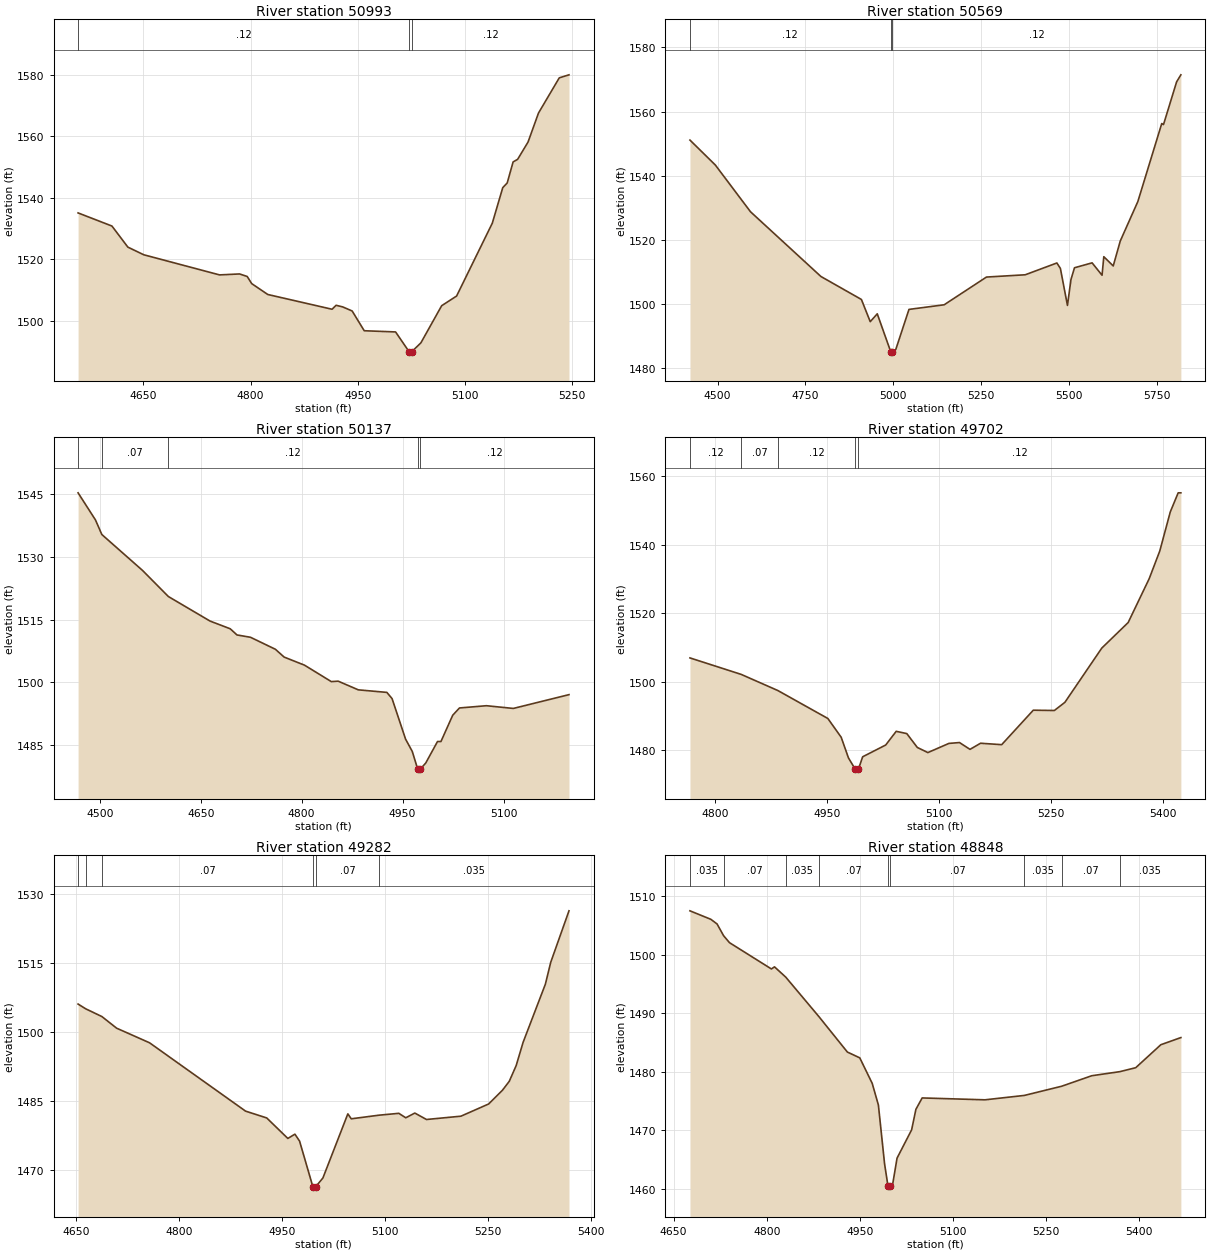
Type RM Length L Ch R = 1 ,50993   ,424,424,424
BEGIN DESCRIPTION:
WASP CREEK 97.0
END DESCRIPTION:
XS GIS Cut Line= 3
      2045932.43     13863767.15        2046325.       13863575.
      2046525.02     13863424.98
#Sta/Elev= 30
  4558.5 1535.05  4605.9 1530.78  4628.2 1523.92  4650.4 1521.44  4756.5 1514.89
  4784.5  1515.2  4795.2 1514.38  4801.5 1512.06    4824 1508.52    4914 1503.72
  4919.6 1505.01  4928.8 1504.49  4942.1 1503.16    4959 1496.73  5002.9 1496.34
  5021.7 1489.95  5021.9 1489.45  5025.7 1489.95  5038.3 1492.79  5067.4 1504.87
  5088.3 1508.02  5138.3 1531.73  5152.9 1543.27  5159.1 1544.78  5167.4 1551.64
  5173.7 1552.47  5188.3  1558.1  5202.9 1567.52    5232 1578.98  5245.6 1579.96
#Mann= 3 ,-1 , 0
  4558.5     .12       0  5021.7     .05       0  5025.7     .12       0
Bank Sta=5021.7,5025.7
XS Rating Curve= 0 ,0
Exp/Cntr=0.3,0.1

Type RM Length L Ch R = 1 ,50569   ,432,432,432
BEGIN DESCRIPTION:
WASP CREEK 96.0
END DESCRIPTION:
XS GIS Cut Line= 3
       2045792.9     13863955.59        2046375.       13863925.
      2047187.08     13863876.95
#Sta/Elev= 30
  4421.6 1551.09  4493.8 1543.31  4593.9 1528.72  4794.2 1508.53  4909.3 1501.37
  4934.4 1494.44  4954.4 1496.89  4992.5 1485.13  4992.7 1484.63  4996.5 1485.13
    5007 1485.75  5044.6 1498.27  5144.7 1499.71    5265 1508.36  5375.2 1509.07
  5465.3 1512.75  5475.3 1511.06  5495.4 1499.52  5505.4 1507.59  5515.4 1511.26
  5565.5 1512.79  5593.8 1508.93  5598.8 1514.71  5625.6 1511.83  5645.6  1519.6
  5695.7 1531.94  5763.6 1556.25  5768.6 1555.93  5805.9 1569.26    5818 1571.45
#Mann= 3 ,-1 , 0
  4421.6     .12       0  4992.5     .05       0  4996.5     .12       0
Bank Sta=4992.5,4996.5
XS Rating Curve= 0 ,0
Exp/Cntr=0.3,0.1

Type RM Length L Ch R = 1 ,50137   ,435,435,435
BEGIN DESCRIPTION:
WASP CREEK 95.0
END DESCRIPTION:
XS GIS Cut Line= 3
      2045939.29     13864358.32        2046475.       13864325.
       2046667.6     13864315.22
#Sta/Elev= 30
  4467.7  1545.4  4493.5 1538.92    4503 1535.42  4563.6  1526.8  4601.9 1520.57
  4663.8  1514.7  4693.8 1512.85  4703.9 1511.37  4723.9 1510.82  4760.9 1507.95
    4774 1506.07  4804.1 1504.15  4844.1  1500.2  4854.2 1500.31  4884.2 1498.23
  4926.6 1497.62  4934.3 1496.15  4954.4 1486.44  4964.4 1483.48  4972.4 1479.27
  4972.6 1478.77  4976.4 1479.27  4984.4 1480.71  5001.9 1485.86    5007 1485.86
  5024.5 1492.15  5034.5 1493.89  5074.5 1494.43  5114.6 1493.78  5197.3 1497.08
#Mann= 5 ,-1 , 0
  4467.7     .12       0    4503     .07       0  4601.9     .12       0
  4972.4     .05       0  4976.4     .12       0
Bank Sta=4972.4,4976.4
XS Rating Curve= 0 ,0
Exp/Cntr=0.3,0.1

Type RM Length L Ch R = 1 ,49702   ,420,420,420
BEGIN DESCRIPTION:
WASP CREEK 94.0
END DESCRIPTION:
XS GIS Cut Line= 3
      2046350.84      13864793.2        2046575.       13864725.
      2046875.02     13864424.98
#Sta/Elev= 30
    4766  1506.9  4834.8 1502.08    4884 1497.36    4951  1489.2  4968.9 1483.71
  4978.7 1477.65  4987.9 1474.32  4988.1 1473.82  4991.9 1474.32  4997.7 1478.01
  5028.6 1481.45  5042.7 1485.45  5056.9 1484.79    5071 1480.74  5085.2 1479.24
  5113.4 1481.92  5127.6 1482.17  5141.7 1480.18  5155.9 1481.97  5184.2 1481.55
  5226.6 1491.62  5254.9 1491.54    5269 1493.92  5318.5 1509.77  5353.9 1517.24
  5382.1 1530.05  5396.3 1538.14  5410.4 1549.56    5421 1555.14  5424.6 1555.14
#Mann= 5 ,-1 , 0
    4766     .12       0  4834.8     .07       0    4884     .12       0
  4987.9     .05       0  4991.9     .12       0
Bank Sta=4987.9,4991.9
XS Rating Curve= 0 ,0
Exp/Cntr=0.3,0.1

Type RM Length L Ch R = 1 ,49282   ,434,434,434
BEGIN DESCRIPTION:
WASP CREEK 93.0
END DESCRIPTION:
XS GIS Cut Line= 3
      2046387.27     13864946.86        2046725.       13865025.
      2047091.48     13864986.08
#Sta/Elev= 30
  4653.3 1506.13  4664.1 1505.12    4688 1503.41  4709.5 1500.88  4757.4 1497.71
  4897.3 1482.85  4928.1 1481.37  4958.9 1476.91  4969.2 1477.84    4976 1476.33
  4995.4 1466.39  4995.6 1465.89  4999.4 1466.39    5010 1468.32  5046.3 1482.25
  5051.3 1481.18  5091.9 1481.97  5120.6 1482.37  5130.7  1481.4  5143.9 1482.43
  5160.9 1481.03  5211.1 1481.75  5251.4  1484.4  5271.5 1487.38  5281.5 1489.33
  5291.6 1492.77  5301.6 1497.79  5334.1 1510.45  5341.9 1515.21  5368.5  1526.4
#Mann= 6 ,-1 , 0
  4653.3     .07       0  4664.1    .035       0    4688     .07       0
  4995.4     .05       0  4999.4     .07       0  5091.9    .035       0
Bank Sta=4995.4,4999.4
XS Rating Curve= 0 ,0
Exp/Cntr=0.3,0.1

Type RM Length L Ch R = 1 ,48848   ,452,452,452
BEGIN DESCRIPTION:
WASP CREEK 92.0
END DESCRIPTION:
XS GIS Cut Line= 3
      2046301.34     13865416.47        2046625.       13865425.
      2047086.89     13865351.37
#Sta/Elev= 30
  4676.3 1507.47    4710 1506.02    4720 1505.23  4730.5 1503.23    4740 1502.04
  4807.6 1497.55  4812.6 1497.91  4830.7 1496.16  4883.9 1489.46  4930.1 1483.37
  4950.1 1482.38  4970.1 1478.04  4980.1 1474.34  4990.1 1464.28  4995.6 1460.48
  4995.8 1459.98  4999.6 1460.48  5002.6 1460.48  5010.2 1465.27  5033.7  1470.1
  5040.6  1473.6  5050.7 1475.54    5152 1475.22  5215.5 1475.97  5275.7 1477.54
  5324.1 1479.33  5369.6 1480.03    5395  1480.7  5435.5 1484.62  5467.8 1485.84
#Mann= 9 ,-1 , 0
  4676.3    .035       0  4730.5     .07       0  4830.7    .035       0
  4883.9     .07       0  4995.6     .05       0  4999.6     .07       0
  5215.5    .035       0  5275.7     .07       0  5369.6    .035       0
Bank Sta=4995.6,4999.6
XS Rating Curve= 0 ,0
Exp/Cntr=0.3,0.1

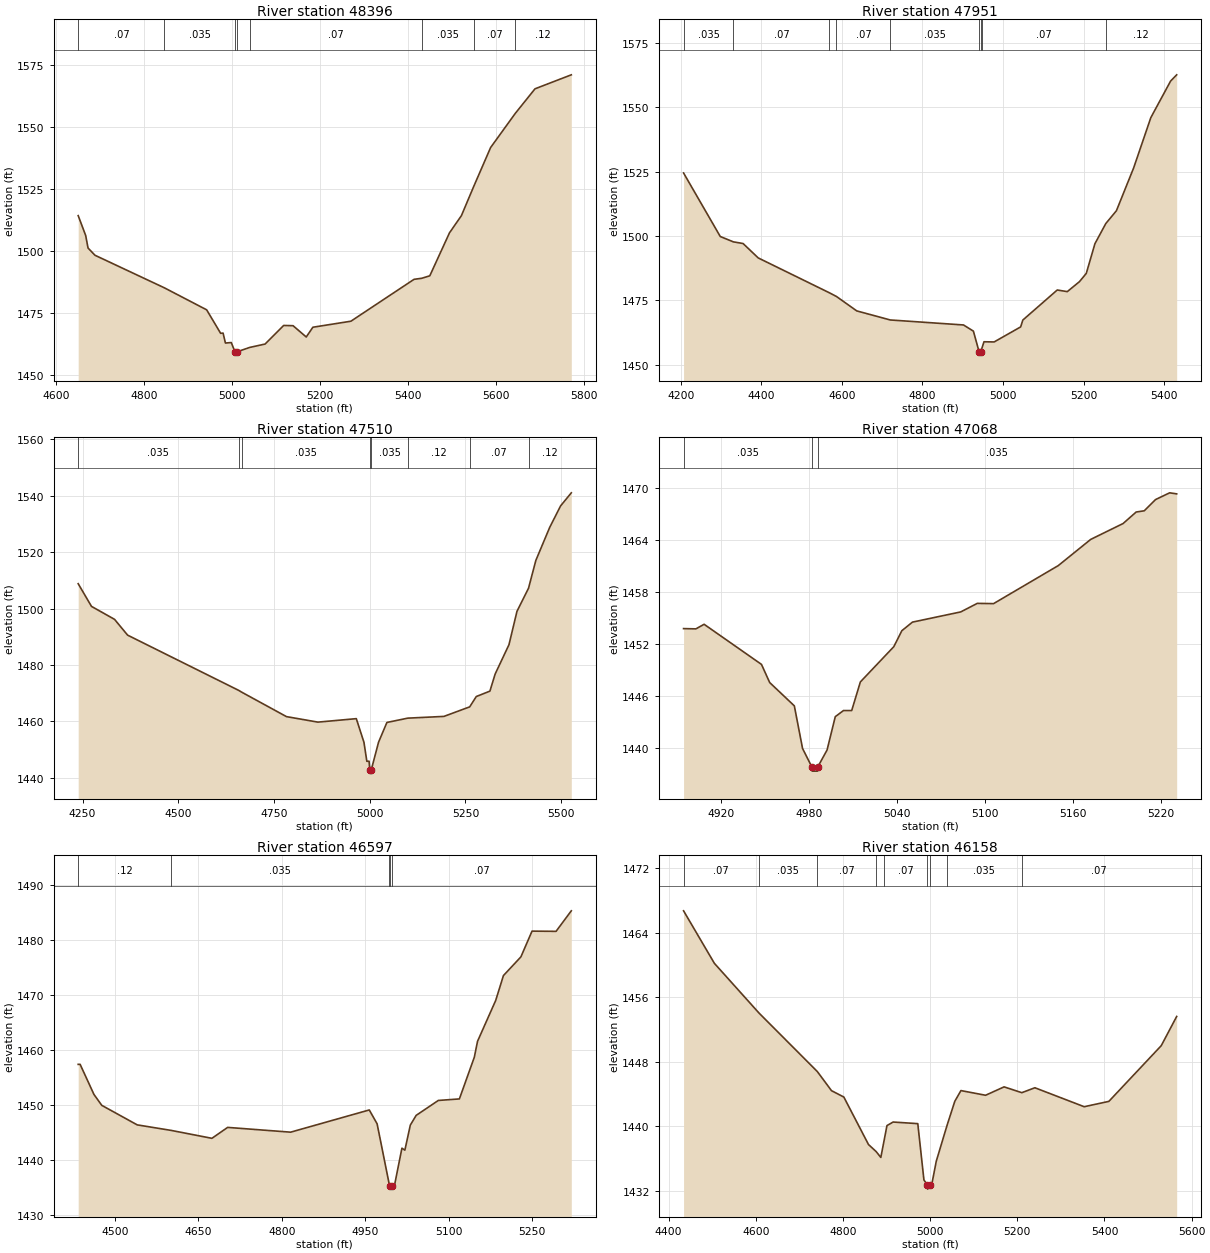
Type RM Length L Ch R = 1 ,48396   ,445,445,445
BEGIN DESCRIPTION:
WASP CREEK 91.0
END DESCRIPTION:
XS GIS Cut Line= 3
      2046448.89      13865937.3        2046775.       13865825.
      2047424.05     13865400.03
#Sta/Elev= 30
  4650.3 1514.34  4667.3 1506.33  4672.7 1501.25  4688.5 1498.33  4846.4 1485.16
  4942.3 1476.29    4974 1466.81  4979.6 1466.89  4984.9 1462.88  4998.2 1463.07
  5006.7  1459.3    5007  1458.8  5010.7  1459.3  5040.3 1461.11  5075.1 1462.47
  5117.3 1469.98  5138.6 1469.88  5168.6 1465.32  5183.7 1469.26  5270.1 1471.69
  5413.6 1488.61  5430.9 1489.03  5449.4 1490.03  5494.2  1507.4  5521.3 1514.35
  5548.8 1525.95  5587.7 1541.87  5643.7 1555.64  5688.5 1565.57    5771 1571.22
#Mann= 8 ,-1 , 0
  4650.3     .07       0  4846.4    .035       0  5006.7    .035       0
  5010.7    .035       0  5040.3     .07       0  5430.9    .035       0
  5548.8     .07       0  5643.7     .12       0
Bank Sta=5006.7,5010.7
XS Rating Curve= 0 ,0
Exp/Cntr=0.3,0.1

Type RM Length L Ch R = 1 ,47951   ,441,441,441
BEGIN DESCRIPTION:
WASP CREEK 90.0
END DESCRIPTION:
XS GIS Cut Line= 3
      2046393.24     13866128.02        2047175.       13865975.
        2047575.       13865825.
#Sta/Elev= 30
  4207.1 1524.44  4298.2 1499.78  4330.7 1497.71  4354.8 1497.06  4392.3 1491.48
  4568.9 1477.95  4586.6  1476.5  4636.9 1470.91  4720.1 1467.39  4901.8 1465.45
  4926.4 1463.06  4940.6 1455.02  4940.8 1454.52  4944.6 1455.02  4946.8 1456.08
  4952.7 1458.93  4977.9 1458.86  5043.7  1464.7  5049.1 1467.36  5134.5 1479.02
  5159.4 1478.39  5189.7 1482.27  5206.6 1485.48    5228 1496.98  5254.9 1504.79
  5281.4  1509.8  5324.1  1526.4  5366.8 1545.94  5415.8 1560.11  5430.9 1562.54
#Mann= 9 ,-1 , 0
  4207.1    .035       0  4330.7     .07       0  4568.9    .035       0
  4586.6     .07       0  4720.1    .035       0  4940.6     .05       0
  4944.6    .035       0  4946.8     .07       0  5254.9     .12       0
Bank Sta=4940.6,4944.6
XS Rating Curve= 0 ,0
Exp/Cntr=0.3,0.1

Type RM Length L Ch R = 1 ,47510   ,442,442,442
BEGIN DESCRIPTION:
WASP CREEK 89.0
END DESCRIPTION:
XS GIS Cut Line= 3
      2046470.39     13866320.81        2047225.       13866375.
      2047575.03     13865974.97
#Sta/Elev= 30
  4238.5 1508.84  4273.2  1500.8  4333.4 1496.21  4367.6  1490.6  4657.7 1471.03
    4666 1470.36  4782.6 1461.72  4864.7 1459.77    4965    1461    4985  1452.6
  4992.5  1445.9  4998.4  1445.9  5000.2  1442.9  5000.4  1442.4  5004.2  1442.9
  5023.1 1452.65  5044.9 1459.65  5099.4 1461.18  5193.9  1461.8  5261.2 1465.18
  5278.4 1468.84    5314 1470.76  5327.7 1476.82  5363.8 1487.22  5384.7 1499.04
  5414.9 1507.25    5434  1517.1  5470.1 1528.77  5498.6 1536.41  5526.6 1541.05
#Mann= 8 ,-1 , 0
  4238.5    .035       0  4657.7     .07       0    4666    .035       0
  5000.2    .035       0  5004.2    .035       0  5099.4     .12       0
  5261.2     .07       0  5414.9     .12       0
Bank Sta=5000.2,5004.2
XS Rating Curve= 0 ,0
Exp/Cntr=0.3,0.1

Type RM Length L Ch R = 1 ,47068   ,471,471,471
BEGIN DESCRIPTION:
WASP CREEK 88.0
END DESCRIPTION:
XS GIS Cut Line= 3
      2047424.99     13866725.01        2047525.       13866675.
      2047620.36       13866472.
#Sta/Elev= 30
  4894.6 1453.76    4903 1453.73  4908.6 1454.26  4947.7 1449.62  4953.3 1447.52
  4970.1 1444.82  4975.7 1439.89    4982 1437.77  4982.3 1437.27  4985.9 1437.27
  4986.1 1437.77  4992.4 1439.71    4998 1443.57  5003.6 1444.28  5009.2 1444.28
  5015.1 1447.59  5037.9 1451.67  5043.4 1453.52  5050.6 1454.51  5083.5 1455.69
  5094.8 1456.68  5105.9 1456.65    5150 1461.05  5172.1 1464.08  5194.2 1465.92
  5203.1 1467.25  5208.6 1467.39  5216.3 1468.69  5225.9 1469.47  5230.7 1469.35
#Mann= 3 ,-1 , 0
  4894.6    .035       0    4982    .035       0  4986.1    .035       0
Bank Sta=4982,4986.1
XS Rating Curve= 0 ,0
Exp/Cntr=0.3,0.1

Type RM Length L Ch R = 1 ,46597   ,439,439,439
BEGIN DESCRIPTION:
WASP CREEK 87.0
END DESCRIPTION:
XS GIS Cut Line= 3
      2047524.99     13867275.01        2047925.       13866875.
      2048019.51     13866568.44
#Sta/Elev= 30
    4434  1457.4  4437.5  1457.4  4462.3 1451.92  4476.4 1449.93  4540.1 1446.37
  4601.3 1445.36  4674.4 1443.92  4702.7 1445.91  4815.9 1445.04  4957.3 1449.09
  4971.4 1446.56  4993.2 1435.55  4994.1 1435.16  4994.4 1434.66  4998.2 1435.16
  5002.3 1435.16    5016 1442.12  5021.3 1441.76  5031.1 1446.33  5041.6  1448.1
  5081.4 1450.82  5119.3  1451.1  5146.2 1458.71  5151.9 1461.59  5184.6 1469.05
  5198.5 1473.58  5229.9 1476.99  5249.9 1481.68  5293.1 1481.64  5320.5 1485.38
#Mann= 5 ,-1 , 0
    4434     .12       0  4601.3    .035       0  4993.2     .07       0
  4994.1     .05       0  4998.2     .07       0
Bank Sta=4994.1,4998.2
XS Rating Curve= 0 ,0
Exp/Cntr=0.3,0.1

Type RM Length L Ch R = 1 ,46158   ,474,474,474
BEGIN DESCRIPTION:
WASP CREEK 86.0
END DESCRIPTION:
XS GIS Cut Line= 3
        2047625.       13867675.        2048025.       13867275.
      2048425.02     13866874.98
#Sta/Elev= 30
  4434.3 1466.71    4505  1460.2  4607.3 1454.04  4741.2 1446.78  4773.7 1444.41
    4802 1443.62  4858.6 1437.73  4876.1 1436.86  4886.9 1436.13    4895  1438.4
    4901 1440.08  4915.1 1440.52  4971.7 1440.32  4985.8 1433.34  4993.9  1432.7
  4994.3  1432.2  4999.1  1432.7  5003.5  1432.7  5014.1 1435.66  5038.8  1440.1
  5056.6 1443.09  5070.7 1444.42  5127.3 1443.84  5169.7 1444.88  5210.4 1444.16
  5240.4 1444.77  5353.5 1442.42  5410.1 1443.08  5530.3 1449.99  5565.7 1453.61
#Mann= 9 ,-1 , 0
  4434.3     .07       0  4607.3    .035       0  4741.2     .07       0
  4876.1     .12       0    4895     .07       0  4993.9     .05       0
  4999.1     .07       0  5038.8    .035       0  5210.4     .07       0
Bank Sta=4993.9,4999.1
XS Rating Curve= 0 ,0
Exp/Cntr=0.3,0.1

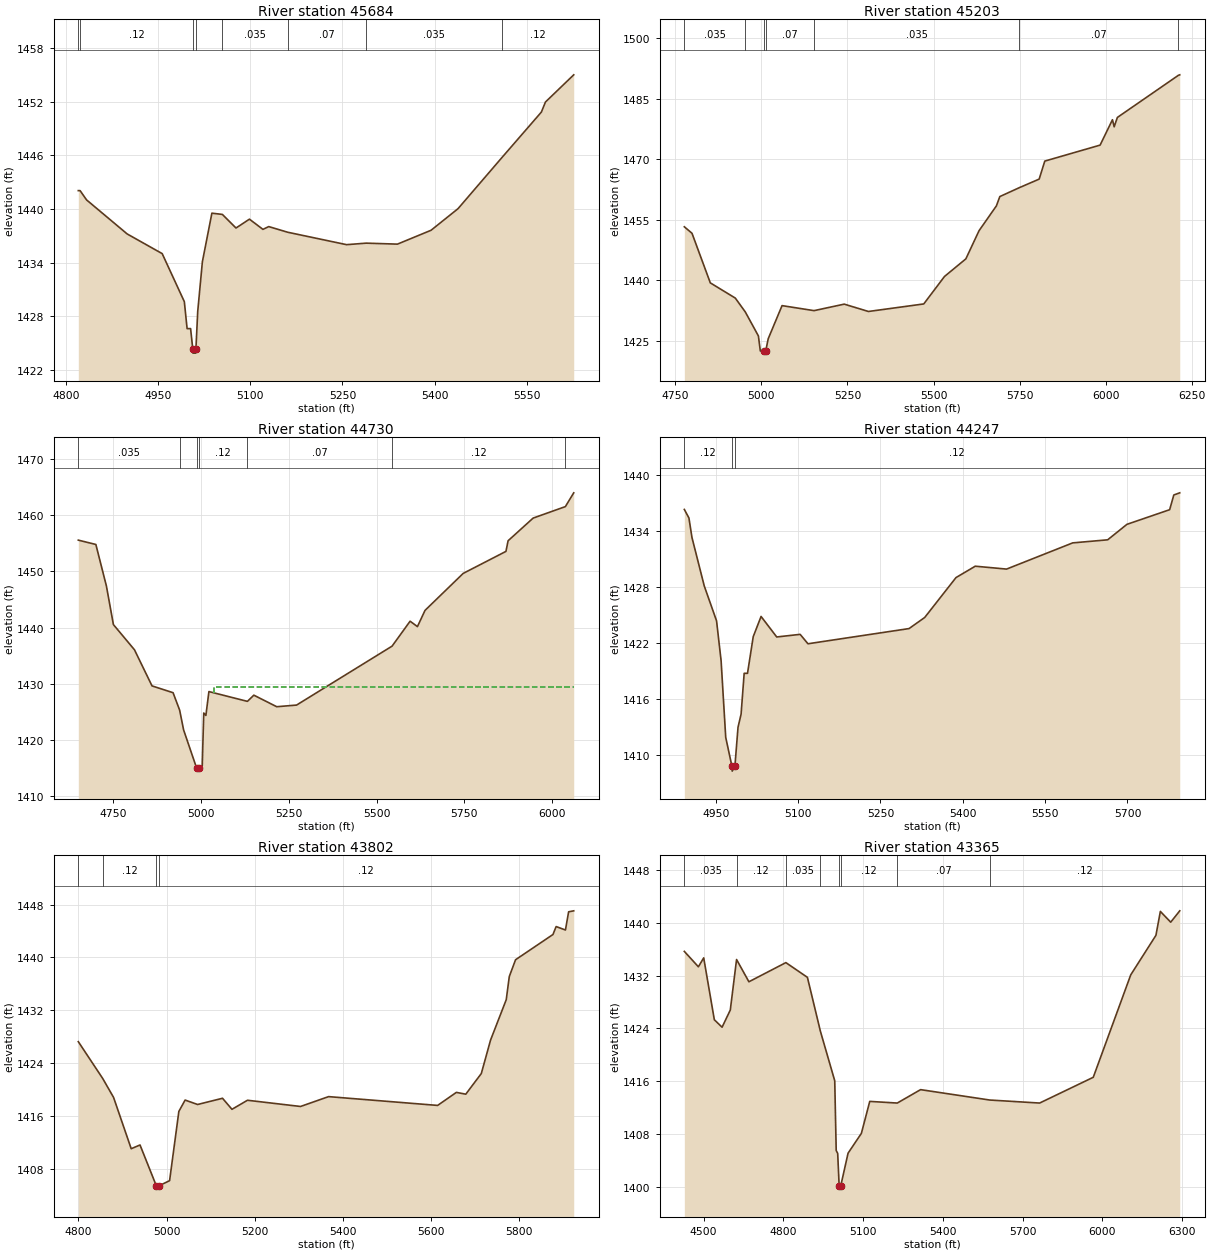
Type RM Length L Ch R = 1 ,45684   ,481,481,481
BEGIN DESCRIPTION:
WASP CREEK 85.0
END DESCRIPTION:
XS GIS Cut Line= 3
      2048225.01     13867624.99        2048375.       13867525.
      2048632.03     13866952.95
#Sta/Elev= 30
  4819.5 1442.06  4822.4 1442.06    4833 1441.02  4899.1 1437.22  4956.2 1435.02
  4992.3 1429.65  4996.8 1426.64  5002.5 1426.64    5006  1424.4  5006.4  1423.9
  5010.8  1423.9  5011.2  1424.4  5014.1 1428.55  5021.7 1434.11  5037.2 1439.54
  5054.3  1439.4  5076.5 1437.88  5098.4 1438.87  5120.4 1437.73  5129.9 1438.04
  5160.7 1437.41  5256.7 1436.02  5288.7 1436.19  5339.6 1436.08  5394.4 1437.63
  5438.3 1440.04  5509.7 1445.74  5574.2 1450.84  5580.8 1451.96  5626.9    1455
#Mann= 8 ,-1 , 0
  4819.5    .035       0  4822.4     .12       0    5006     .05       0
  5011.2     .12       0  5054.3    .035       0  5160.7     .07       0
  5288.7    .035       0  5509.7     .12       0
Bank Sta=5006,5011.2
XS Rating Curve= 0 ,0
Exp/Cntr=0.3,0.1

Type RM Length L Ch R = 1 ,45203   ,473,473,473
BEGIN DESCRIPTION:
WASP CREEK 84.0
END DESCRIPTION:
XS GIS Cut Line= 3
      2048675.01     13867924.99        2048775.       13867725.
      2048888.12     13866514.57
#Sta/Elev= 30
    4776 1453.21  4798.3  1451.6  4851.5 1439.31  4924.1 1435.54  4953.1 1432.11
  4991.2 1426.16  4996.8 1422.43    5007  1422.4  5007.4  1421.9  5012.3  1422.4
  5019.7 1425.46  5059.9 1433.67  5152.9 1432.43  5240.6 1434.04  5310.9 1432.22
  5471.6 1434.09  5531.9  1440.9  5593.9 1445.26  5632.3 1452.25  5682.6 1458.39
  5692.6  1460.7  5748.9 1462.89  5806.9 1465.03  5823.2 1469.49  5983.9 1473.45
  6019.8 1479.74  6024.8 1477.99  6034.1 1480.31  6211.2 1490.74  6215.3 1490.87
#Mann= 7 ,-1 , 0
    4776    .035       0  4953.1     .07       0    5007     .05       0
  5012.3     .07       0  5152.9    .035       0  5748.9     .07       0
  6211.2    .035       0
Bank Sta=5007,5012.3
XS Rating Curve= 0 ,0
Exp/Cntr=0.3,0.1

Type RM Length L Ch R = 1 ,44730   ,483,483,483
BEGIN DESCRIPTION:
WASP CREEK 83.0
END DESCRIPTION:
XS GIS Cut Line= 3
      2048725.01       13868025.        2049075.       13868025.
      2049940.44     13867410.34
#Sta/Elev= 30
  4649.9 1455.55  4699.9 1454.78  4729.9 1447.41  4749.9 1440.54  4809.9 1436.06
  4859.9 1429.64  4919.9 1428.43  4938.6 1425.33  4949.9 1421.82  4987.2 1414.99
  4987.6 1414.49  4992.5 1414.99    5003 1415.47  5007.3 1424.82  5013.4 1424.39
    5022 1428.63  5131.7 1426.89    5150 1427.99  5215.2 1425.94  5271.7 1426.23
  5543.9 1436.71  5595.2 1441.14  5616.1 1440.18  5637.7 1443.06  5746.5 1449.64
  5868.3 1453.55  5874.4 1455.44  5945.8 1459.47  6037.6 1461.51  6061.4 1463.96
#Mann= 7 ,-1 , 0
  4649.9    .035       0  4938.6     .12       0  4987.2     .05       0
  4992.5     .12       0  5131.7     .07       0  5543.9     .12       0
  6037.6    .035       0
#XS Ineff= 2 , 0
                         5035.86         1429.45
Permanent Ineff=
       F       F
Bank Sta=4987.2,4992.5
XS Rating Curve= 0 ,0
Exp/Cntr=0.3,0.1

Type RM Length L Ch R = 1 ,44247   ,445,445,445
BEGIN DESCRIPTION:
WASP CREEK 82.0
END DESCRIPTION:
XS GIS Cut Line= 3
      2049075.03     13868524.98        2049175.       13868475.
       2049694.3     13867878.69
#Sta/Elev= 30
  4892.8 1436.36  4901.2 1435.44  4906.7 1433.35  4929.1 1428.15  4951.5 1424.41
  4959.8 1420.13  4968.2 1411.91  4979.6 1408.79    4980 1408.29  4984.9 1408.79
  4990.6 1412.99  4996.2  1414.4  5001.8 1418.78  5007.9 1418.78  5018.3 1422.71
  5032.6 1424.88  5061.1 1422.68  5103.8 1422.96    5118 1421.95  5302.2 1423.58
  5330.7 1424.77  5387.7 1429.05  5422.8 1430.27  5479.8 1429.96  5600.3 1432.77
    5664  1433.1  5699.1 1434.76  5776.9 1436.33  5784.5 1437.91  5795.3 1438.14
#Mann= 3 ,-1 , 0
  4892.8     .12       0  4979.6     .05       0  4984.9     .12       0
Bank Sta=4979.6,4984.9
XS Rating Curve= 0 ,0
Exp/Cntr=0.3,0.1

Type RM Length L Ch R = 1 ,43802   ,437,437,437
BEGIN DESCRIPTION:
WASP CREEK 81.0
END DESCRIPTION:
XS GIS Cut Line= 3
      2049275.02       13868775.        2049475.       13868775.
       2050141.2      13868134.7
#Sta/Elev= 30
  4799.8 1427.26  4855.3 1421.68  4879.8 1418.83  4919.8 1411.07  4939.8 1411.64
  4976.8 1405.46  4977.3 1404.96  4982.8 1405.46  5006.9 1406.24  5027.9 1416.71
  5042.1 1418.43  5070.4 1417.76    5127  1418.7  5148.4 1417.03  5183.6  1418.4
    5304 1417.46  5367.6 1418.95    5615 1417.62  5657.5 1419.59  5678.9 1419.32
  5714.1 1422.44  5735.2 1427.52  5770.7 1433.61  5777.6 1437.11  5791.8 1439.65
  5876.7 1443.47  5883.9 1444.67    5905 1444.15  5912.2  1446.9  5923.8 1447.05
#Mann= 4 ,-1 , 0
  4799.8    .035       0  4855.3     .12       0  4976.8     .05       0
  4982.8     .12       0
Bank Sta=4976.8,4982.8
XS Rating Curve= 0 ,0
Exp/Cntr=0.3,0.1

Type RM Length L Ch R = 1 ,43365   ,468,468,468
BEGIN DESCRIPTION:
WASP CREEK 80.0
END DESCRIPTION:
XS GIS Cut Line= 3
      2048862.07     13869131.75        2049425.       13869125.
      2050585.19     13868537.12
#Sta/Elev= 30
  4427.8 1435.66  4480.7 1433.33  4500.7 1434.68  4540.7 1425.31  4569.8 1424.18
  4600.7 1426.78  4624.3 1434.43  4670.7 1431.06  4809.8 1433.96  4890.8 1431.73
  4939.4 1423.61  4993.6 1416.07  4999.1 1405.51  5004.7 1405.08  5010.2 1400.17
  5010.7 1399.67  5016.2 1400.17  5043.7 1405.11  5093.8 1408.11  5125.3 1412.95
  5228.8  1412.7  5316.5 1414.73    5576 1413.16  5764.3  1412.7  5966.1  1416.6
  6107.1 1432.11  6201.8 1438.09  6218.5 1441.71  6257.4 1440.08  6291.4  1441.8
#Mann= 8 ,-1 , 0
  4427.8    .035       0  4624.3     .12       0  4809.8    .035       0
  4939.4     .12       0  5010.2     .05       0  5016.2     .12       0
  5228.8     .07       0    5576     .12       0
Bank Sta=5010.2,5016.2
XS Rating Curve= 0 ,0
Exp/Cntr=0.3,0.1

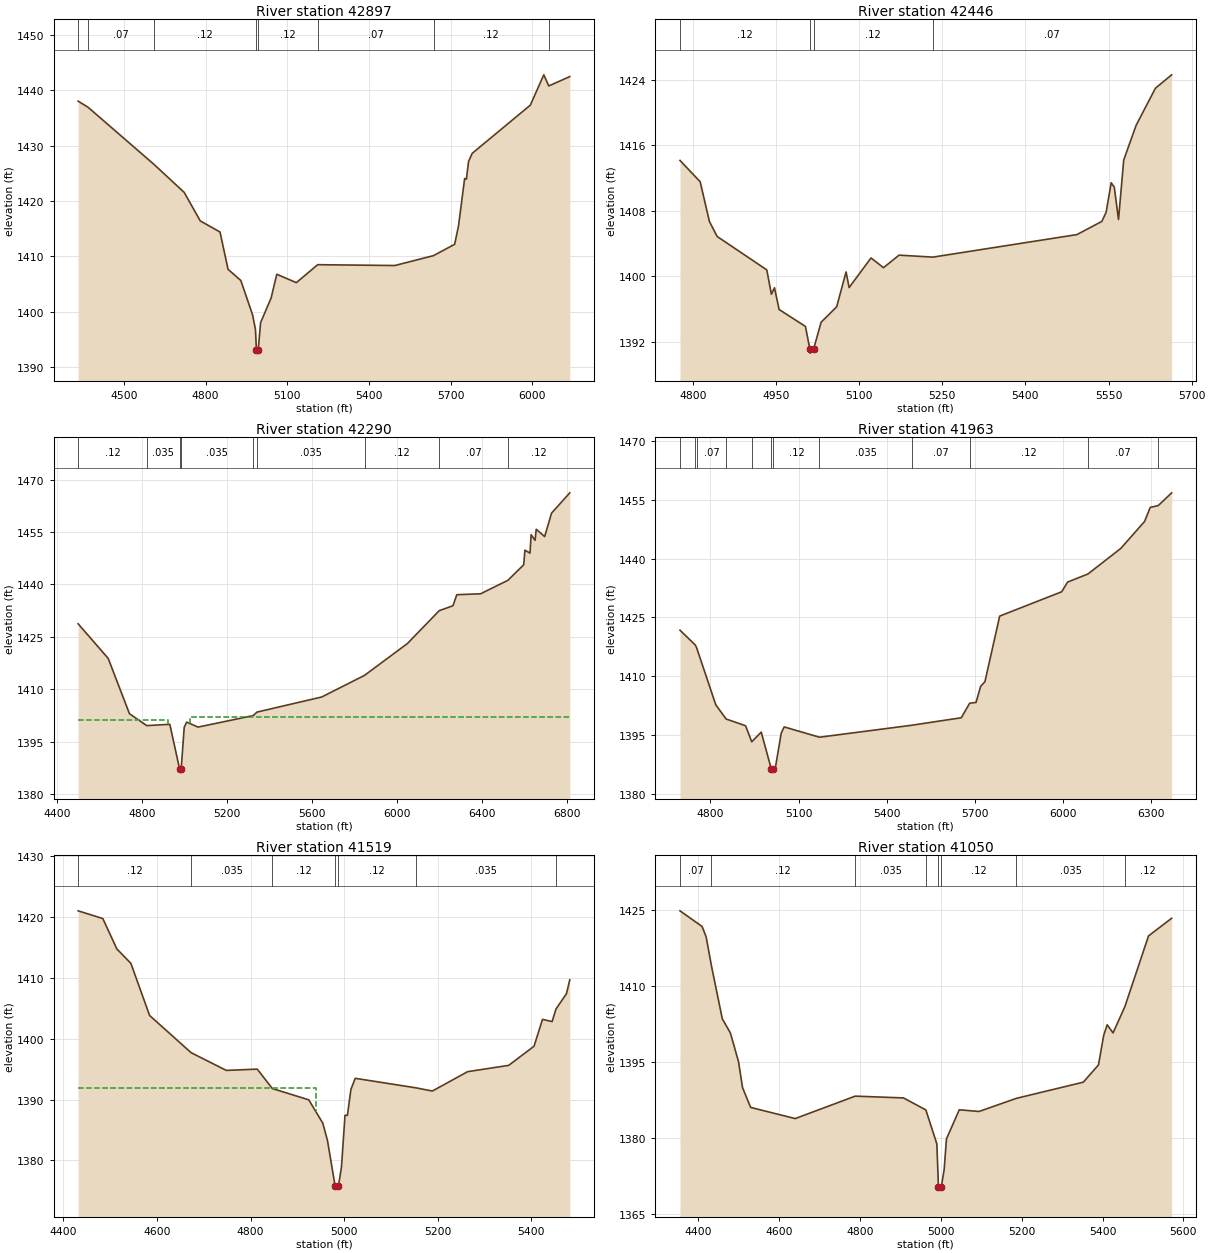
Type RM Length L Ch R = 1 ,42897   ,451,451,451
BEGIN DESCRIPTION:
WASP CREEK 79.0
END DESCRIPTION:
XS GIS Cut Line= 3
      2049100.78     13869726.37        2049725.       13869475.
       2050602.5      13868758.5
#Sta/Elev= 30
  4331.6 1438.07  4367.9 1436.97  4609.1 1426.68  4721.2 1421.56  4780.3  1416.4
  4852.8 1414.39  4882.3 1407.64  4929.1 1405.63  4972.2 1399.44    4983 1396.75
  4986.6 1392.98  4987.1 1392.48  4992.9 1392.98  5001.8 1397.99  5040.4 1402.45
  5061.3 1406.75  5133.1 1405.23  5211.6 1408.48  5495.1 1408.33  5636.9 1410.12
  5714.6 1412.17  5728.9 1415.54  5751.2 1424.07  5757.7 1423.95  5765.6 1427.15
  5779.1 1428.63  5992.4 1437.34    6042 1442.83  6060.3 1440.82  6137.4 1442.51
#Mann= 8 ,-1 , 0
  4331.6    .035       0  4367.9     .07       0  4609.1     .12       0
  4986.6     .05       0  4992.9     .12       0  5211.6     .07       0
  5636.9     .12       0  6060.3     .07       0
Bank Sta=4986.6,4992.9
XS Rating Curve= 0 ,0
Exp/Cntr=0.3,0.1

Type RM Length L Ch R = 1 ,42446   ,156,156,156
BEGIN DESCRIPTION:
WASP CREEK 78.0
END DESCRIPTION:
XS GIS Cut Line= 3
      2049674.97     13869774.98        2049875.       13869875.
      2050471.19     13869583.69
#Sta/Elev= 30
  4776.7 1414.14  4813.1 1411.54  4829.8 1406.68  4843.8 1404.85  4933.3 1400.77
  4941.6  1397.8  4947.2 1398.58  4955.6 1395.93  5003.1 1393.86    5011  1391.1
  5011.5  1390.6  5017.8  1391.1  5031.3 1394.37  5059.4 1396.26  5076.4 1400.52
  5081.9 1398.61  5121.4 1402.23  5143.9 1401.04    5172 1402.57  5233.1 1402.33
  5492.9 1405.08  5537.9 1406.69  5545.7 1407.82  5554.8 1411.42  5560.4 1410.87
    5568 1406.93  5577.4 1414.19  5599.9 1418.45  5634.7 1422.97  5663.9  1424.6
#Mann= 4 ,-1 , 0
  4776.7     .12       0    5011     .05       0  5017.8     .12       0
  5233.1     .07       0
Bank Sta=5011,5017.8
XS Rating Curve= 0 ,0
Exp/Cntr=0.3,0.1

Type RM Length L Ch R = 1 ,42290   ,327,327,327
BEGIN DESCRIPTION:
WASP CREEK 77.5
END DESCRIPTION:
XS GIS Cut Line= 3
      2049423.19     13870026.67      2049925.45     13870014.81
      2051604.52      13869329.6
#Sta/Elev= 30
  4497.6 1428.73  4639.4  1418.8  4739.5 1402.97  4820.8 1399.56  4929.5 1399.94
  4976.1 1387.03  4976.6 1386.53  4982.9 1387.03  4997.3 1399.07  5008.8 1400.57
  5062.3 1399.14  5322.2 1402.43  5340.4 1403.44    5645 1407.76  5846.7 1413.95
  6048.7 1423.07  6198.7 1432.49  6263.2 1433.89  6281.3 1437.05  6393.6 1437.32
  6522.1 1441.18  6596.7 1445.64  6602.1 1449.81  6626.1 1448.96  6631.5 1454.23
  6650.1 1452.64  6655.5  1455.8  6695.2  1453.7  6727.6 1460.41  6813.5 1466.23
#Mann= 9 ,-1 , 0
  4497.6     .12       0  4820.8    .035       0  4976.1    .035       0
  4982.9    .035       0  5322.2     .07       0  5340.4    .035       0
  5846.7     .12       0  6198.7     .07       0  6522.1     .12       0
#XS Ineff= 2 , 0
       0 4921.53 1401.24 5024.88       0 1402.14
Permanent Ineff=
       F       F
Bank Sta=4976.1,4982.9
XS Rating Curve= 0 ,0
Exp/Cntr=0.3,0.1

Type RM Length L Ch R = 1 ,41963   ,444,444,444
BEGIN DESCRIPTION:
WASP CREEK 77.0
END DESCRIPTION:
XS GIS Cut Line= 3
      2049574.98       13870375.        2049875.       13870325.
      2051237.53     13870201.27
#Sta/Elev= 30
  4696.7 1421.71  4748.7 1417.93  4753.2 1417.24  4818.4 1402.66  4853.6 1399.03
  4919.8 1397.31  4940.7 1393.21    4973 1395.68  5007.4 1386.22  5007.9 1385.72
  5014.3 1386.22  5020.9  1386.5    5041 1395.43  5051.1 1397.01  5171.1 1394.38
  5486.2 1397.45  5653.5 1399.35  5681.8 1403.05  5703.7 1403.27  5719.2 1407.35
  5733.9 1408.57  5784.1 1425.31  5994.9 1431.52    6015    1434  6084.2 1436.06
  6195.8 1442.58  6276.8 1449.47  6296.2 1453.07  6323.5 1453.54    6369 1456.79
#Mann= 12 ,-1 , 0
  4696.7     .12       0  4748.7    .035       0  4753.2     .07       0
  4853.6    .035       0  4940.7     .12       0  5007.4     .05       0
  5014.3     .12       0  5171.1    .035       0  5486.2     .07       0
  5681.8     .12       0  6084.2     .07       0  6323.5     .12       0
Bank Sta=5007.4,5014.3
XS Rating Curve= 0 ,0
Exp/Cntr=0.3,0.1

Type RM Length L Ch R = 1 ,41519   ,469,469,469
BEGIN DESCRIPTION:
WASP CREEK 76.0
END DESCRIPTION:
XS GIS Cut Line= 3
      2049552.21     13870663.87        2050125.       13870675.
      2050591.92     13870573.14
#Sta/Elev= 30
  4431.4    1421  4484.2 1419.73  4514.2 1414.74  4544.2 1412.37  4584.2 1403.81
  4672.9  1397.7  4748.1 1394.79  4814.3    1395  4846.5 1391.81  4924.3 1389.96
  4954.3 1386.13  4964.3 1383.29  4980.7 1375.79  4981.2 1375.29  4987.8 1375.79
  4994.3 1378.97  5001.8 1387.41  5006.9 1387.41  5014.5 1391.69  5023.7 1393.49
  5153.9 1391.92  5188.5  1391.4  5263.8 1394.58  5351.7 1395.62  5405.8 1398.76
  5423.9 1403.17  5444.4 1402.81  5452.7 1404.87  5475.1 1407.39  5482.2 1409.67
#Mann= 7 ,-1 , 0
  4431.4     .12       0  4672.9    .035       0  4846.5     .12       0
  4980.7     .05       0  4987.8     .12       0  5153.9    .035       0
  5452.7     .12       0
#XS Ineff= 2 , 0
       0 4939.71 1391.87               0
Permanent Ineff=
       F       F
Bank Sta=4980.7,4987.8
XS Rating Curve= 0 ,0
Exp/Cntr=0.3,0.1

Type RM Length L Ch R = 1 ,41050   ,455,455,455
BEGIN DESCRIPTION:
WASP CREEK 75.0
END DESCRIPTION:
XS GIS Cut Line= 3
      2049530.45     13871089.22        2050175.       13871125.
      2050670.99     13870842.38
#Sta/Elev= 30
  4354.5 1424.77  4409.1 1421.69  4419.2 1419.64  4432.2 1413.98  4459.2 1403.48
  4479.2 1400.71  4499.3 1395.04  4509.3 1389.92  4529.3 1386.04  4639.5 1383.84
    4788 1388.26  4907.4 1387.91  4962.8 1385.54    4990 1378.84  4993.9 1370.44
  4994.4 1369.94  5001.1 1370.44    5008 1373.75  5013.7 1379.82  5045.4 1385.57
  5094.4 1385.24  5186.5 1387.82  5352.3 1391.01  5389.8  1394.4  5402.9 1400.28
  5411.4 1402.31  5425.9 1400.72  5455.1 1405.88  5513.7 1419.83  5570.9 1423.31
#Mann= 8 ,-1 , 0
  4354.5     .07       0  4432.2     .12       0    4788    .035       0
  4962.8     .12       0  4993.9     .05       0  5001.1     .12       0
  5186.5    .035       0  5455.1     .12       0
Bank Sta=4993.9,5001.1
XS Rating Curve= 0 ,0
Exp/Cntr=0.3,0.1