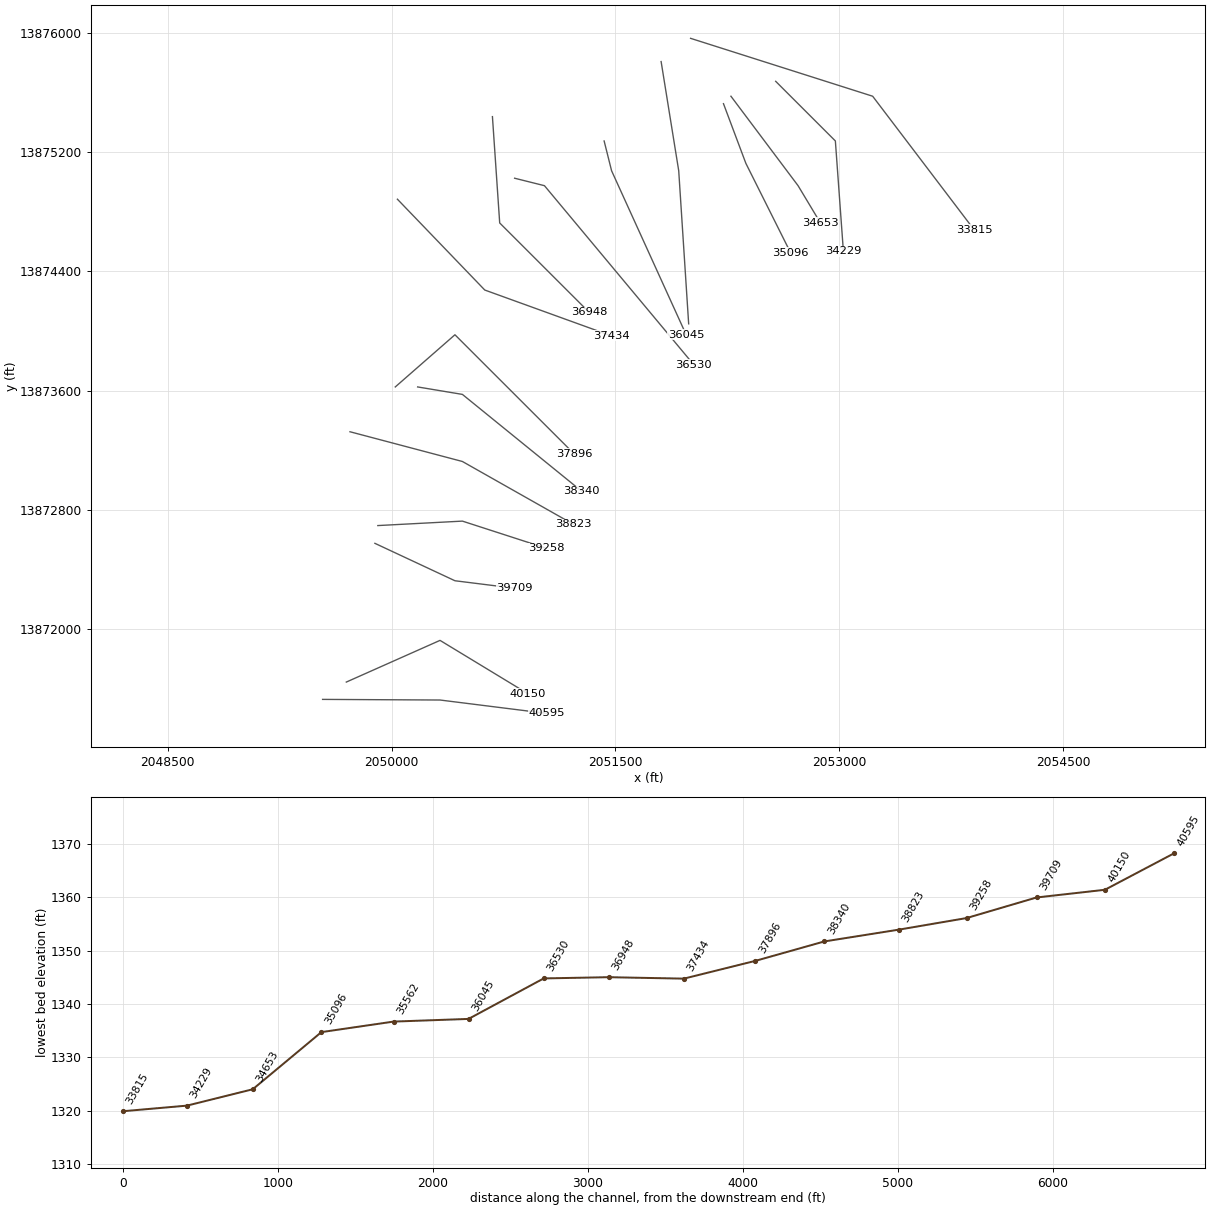
HEC-RAS study WASP CREEK.prj: WASP CREEK Base Level Engineering

--- WASP CREEK.g01 (geometry) --- (continued)

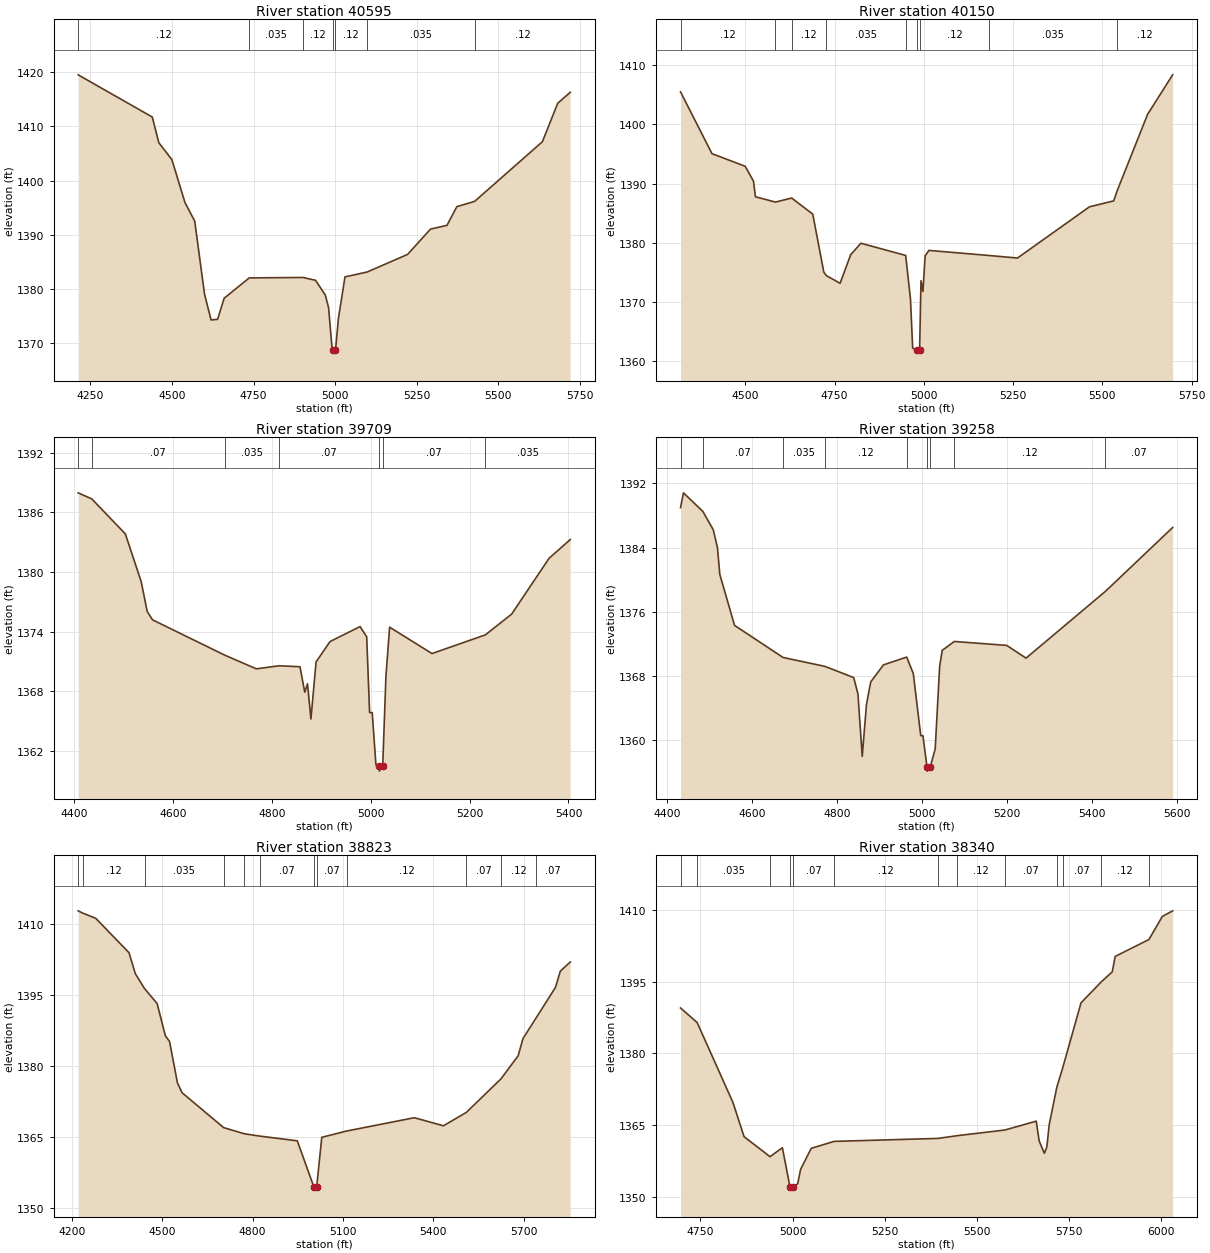
Type RM Length L Ch R = 1 ,40595   ,445,445,445
BEGIN DESCRIPTION:
WASP CREEK 74.0
END DESCRIPTION:
XS GIS Cut Line= 3
      2049537.92     13871529.17        2050325.       13871525.
      2051039.62     13871435.39
#Sta/Elev= 30
  4212.8 1419.49  4439.9 1411.71  4459.9 1406.97  4499.9 1403.86  4539.9 1395.96
  4569.9 1392.51  4599.9 1379.06  4619.9  1374.3  4639.9 1374.41  4659.9 1378.29
  4736.8 1382.05    4901 1382.13  4939.9 1381.61  4969.9 1378.89  4979.9 1376.56
  4989.9 1369.49  4993.8 1368.68  4994.3 1368.18    5001 1368.68    5010 1374.55
  5030.1 1382.24  5097.7 1383.13  5221.6 1386.37  5292.2 1391.05  5342.5 1391.74
  5372.8 1395.19  5427.2 1396.16  5634.8 1407.16  5681.6 1414.24  5720.1 1416.27
#Mann= 7 ,-1 , 0
  4212.8     .12       0  4736.8    .035       0    4901     .12       0
  4993.8     .05       0    5001     .12       0  5097.7    .035       0
  5427.2     .12       0
Bank Sta=4993.8,5001
XS Rating Curve= 0 ,0
Exp/Cntr=0.3,0.1

Type RM Length L Ch R = 1 ,40150   ,441,441,441
BEGIN DESCRIPTION:
WASP CREEK 73.0
END DESCRIPTION:
XS GIS Cut Line= 3
      2049696.81     13871645.36        2050325.       13871925.
      2050914.98     13871566.67
#Sta/Elev= 30
  4318.9 1405.47    4407 1395.04    4500 1392.91  4523.2 1390.39  4528.7 1387.76
  4584.8 1386.87  4630.1 1387.55  4689.1 1384.84  4720.1 1375.04  4727.3 1374.45
  4765.7 1373.16  4795.3 1377.98    4824 1379.92  4949.3 1377.86  4962.7 1370.52
  4968.9 1362.22    4981 1361.87  4981.5 1361.37  4988.3 1361.87  4992.2 1373.59
  4997.6 1371.77  5003.8 1377.78  5014.3 1378.71  5183.1 1377.85  5262.3 1377.42
  5463.9 1386.07  5531.7 1387.07    5542 1388.86  5626.6 1401.67  5696.8 1408.35
#Mann= 9 ,-1 , 0
  4318.9     .12       0  4584.8    .035       0  4630.1     .12       0
  4727.3    .035       0  4949.3     .12       0    4981     .05       0
  4988.3     .12       0  5183.1    .035       0    5542     .12       0
Bank Sta=4981,4988.3
XS Rating Curve= 0 ,0
Exp/Cntr=0.3,0.1

Type RM Length L Ch R = 1 ,39709   ,451,451,451
BEGIN DESCRIPTION:
WASP CREEK 72.0
END DESCRIPTION:
XS GIS Cut Line= 3
      2049888.46     13872575.99        2050425.       13872325.
      2050825.04     13872274.99
#Sta/Elev= 30
  4408.1 1387.98  4435.6 1387.37  4503.6 1383.84  4535.7 1379.02  4547.8 1376.02
  4558.6 1375.18  4704.6 1371.62  4768.6 1370.24  4815.1 1370.55  4856.9 1370.45
  4866.5 1367.89  4872.1 1368.73    4879 1365.19  4889.4 1370.94  4917.7 1372.99
  4978.4  1374.5  4991.8 1373.47  4997.7 1365.83    5003 1365.83  5010.5 1360.57
  5016.9 1360.43  5017.4 1359.93  5024.2 1360.43  5030.7 1369.48  5038.2 1374.44
  5123.9 1371.78  5231.8 1373.66  5285.1 1375.76  5360.7 1381.38  5403.6 1383.27
#Mann= 7 ,-1 , 0
  4408.1    .035       0  4435.6     .07       0  4704.6    .035       0
  4815.1     .07       0  5016.9     .05       0  5024.2     .07       0
  5231.8    .035       0
Bank Sta=5016.9,5024.2
XS Rating Curve= 0 ,0
Exp/Cntr=0.3,0.1

Type RM Length L Ch R = 1 ,39258   ,435,435,435
BEGIN DESCRIPTION:
WASP CREEK 71.0
END DESCRIPTION:
XS GIS Cut Line= 3
       2049908.1     13872695.12        2050475.       13872725.
      2051036.52     13872543.22
#Sta/Elev= 30
    4432 1388.98  4438.9 1390.83  4484.5 1388.51    4509 1386.22    4519 1383.95
  4524.4 1380.65  4559.1 1374.28  4673.3 1370.27  4771.8 1369.16  4839.5 1367.76
  4849.5  1365.7  4859.5 1357.92  4869.5 1364.41  4879.5 1367.22  4909.6 1369.35
  4964.2 1370.32  4979.7 1368.26  4997.2 1360.51  5002.3 1360.51    5012 1356.58
  5012.5 1356.08  5019.4 1356.58  5031.2 1358.84  5041.7 1369.17  5047.7 1371.16
  5076.2 1372.27  5199.4 1371.78    5245 1370.19  5431.8 1378.53  5589.9  1386.5
#Mann= 9 ,-1 , 0
    4432    .035       0  4484.5     .07       0  4673.3    .035       0
  4771.8     .12       0  4964.2     .07       0    5012     .05       0
  5019.4     .07       0  5076.2     .12       0  5431.8     .07       0
Bank Sta=5012,5019.4
XS Rating Curve= 0 ,0
Exp/Cntr=0.3,0.1

Type RM Length L Ch R = 1 ,38823   ,483,483,483
BEGIN DESCRIPTION:
WASP CREEK 70.0
END DESCRIPTION:
XS GIS Cut Line= 3
      2049721.46     13873324.46        2050475.       13873125.
      2051218.84      13872703.8
#Sta/Elev= 30
  4220.4  1412.8  4235.2 1412.33  4278.9 1411.22  4389.3 1403.94  4410.3 1399.51
  4440.8 1396.36  4482.7 1393.19    4510 1386.36    4524 1385.15  4550.2 1376.39
  4565.4 1374.32  4703.7 1366.93  4771.9 1365.64  4823.3 1365.14  4948.2 1364.14
    5003 1354.42  5003.5 1353.92  5012.6 1354.42  5029.5 1364.88  5111.9 1366.21
  5336.8 1369.03  5433.5 1367.32  5509.7 1370.16  5624.5 1377.24  5681.7 1382.14
  5697.6 1385.77  5741.9  1390.2  5805.8 1396.63  5821.7 1400.04  5854.7 1401.97
#Mann= 12 ,-1 , 0
  4220.4     .07       0  4235.2     .12       0  4440.8    .035       0
  4703.7     .07       0  4771.9     .12       0  4823.3     .07       0
    5003     .05       0  5012.6     .07       0  5111.9     .12       0
  5509.7     .07       0  5624.5     .12       0  5741.9     .07       0
Bank Sta=5003,5012.6
XS Rating Curve= 0 ,0
Exp/Cntr=0.3,0.1

Type RM Length L Ch R = 1 ,38340   ,444,444,444
BEGIN DESCRIPTION:
WASP CREEK 69.0
END DESCRIPTION:
XS GIS Cut Line= 3
      2050174.96     13873625.01        2050475.       13873575.
      2051275.04     13872924.97
#Sta/Elev= 30
  4695.9 1389.49  4740.8 1386.48  4837.9 1369.82  4868.3 1362.64  4938.7 1358.47
  4972.2 1360.34  4992.7  1352.2  4993.2  1351.7  5002.3  1352.2  5013.7 1352.83
  5021.6 1355.81  5050.4 1360.21  5112.6 1361.66  5394.6 1362.28  5445.4 1362.84
  5575.7 1364.03  5660.9 1365.88  5668.8 1361.75    5683 1359.17  5689.7 1360.54
  5696.1 1365.18  5716.7 1372.97  5732.7 1377.01  5782.3 1390.55  5836.2 1394.86
  5867.1 1397.03    5875 1400.25  5966.5 1403.77  6002.9 1408.58  6030.9 1409.76
#Mann= 13 ,-1 , 0
  4695.9     .07       0  4740.8    .035       0  4938.7     .07       0
  4992.7     .05       0  5002.3     .07       0  5112.6     .12       0
  5394.6     .07       0  5445.4     .12       0  5575.7     .07       0
  5716.7     .12       0  5732.7     .07       0  5836.2     .12       0
  5966.5     .07       0
Bank Sta=4992.7,5002.3
XS Rating Curve= 0 ,0
Exp/Cntr=0.3,0.1

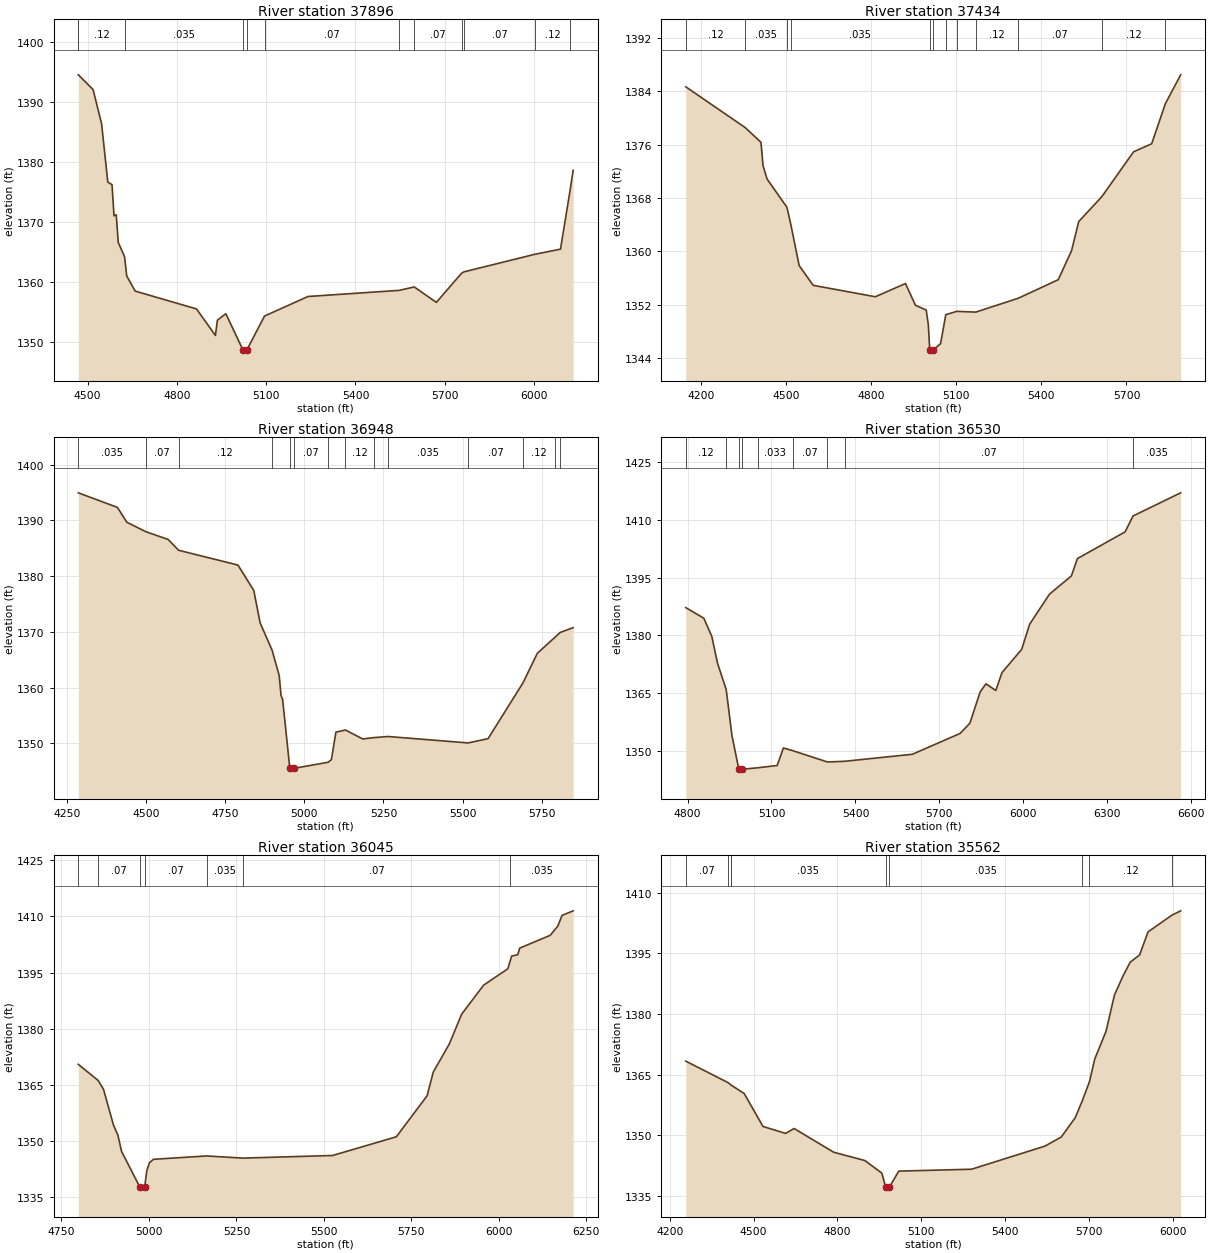
Type RM Length L Ch R = 1 ,37896   ,462,462,462
BEGIN DESCRIPTION:
WASP CREEK 68.0
END DESCRIPTION:
XS GIS Cut Line= 3
      2050025.01       13873625.        2050425.       13873975.
      2051225.02     13873174.98
#Sta/Elev= 30
  4468.5 1394.46  4469.1 1394.46  4518.3 1391.99  4546.8 1386.31  4567.7 1376.58
  4581.9 1376.15  4588.6 1370.95  4596.1 1371.13  4602.8 1366.52    4624 1364.15
  4631.3 1360.93  4659.7 1358.41  4865.7 1355.44  4929.3 1351.02  4935.9 1353.55
  4964.4 1354.64    5022 1348.57  5022.5 1348.07  5034.6 1348.57  5094.3 1354.25
  5240.4 1357.51  5546.6 1358.53  5597.5  1359.1  5671.8 1356.53  5756.7  1361.4
  5764.7 1361.62  6002.3 1364.54  6088.9  1365.4    6122 1375.47  6131.4 1378.55
#Mann= 12 ,-1 , 0
  4468.5     .07       0  4469.1     .12       0    4624    .035       0
    5022    .035       0  5034.6    .035       0  5094.3     .07       0
  5546.6     .12       0  5597.5     .07       0  5756.7     .12       0
  5764.7     .07       0  6002.3     .12       0    6122     .07       0
Bank Sta=5022,5034.6
XS Rating Curve= 0 ,0
Exp/Cntr=0.3,0.1

Type RM Length L Ch R = 1 ,37434   ,486,486,486
BEGIN DESCRIPTION:
WASP CREEK 67.0
END DESCRIPTION:
XS GIS Cut Line= 3
      2050039.37     13874884.25        2050625.       13874275.
      2051471.01     13873968.77
#Sta/Elev= 30
  4146.4 1384.65  4355.9 1378.54  4411.4 1376.34  4418.7 1372.81  4432.8 1370.85
  4502.9  1366.6  4516.3  1364.1    4546 1357.87  4595.4  1354.9  4814.6 1353.19
  4920.9 1355.17  4956.1 1351.92  4994.1 1351.19  5001.5 1348.97  5006.4 1345.24
  5006.9 1344.74  5019.1 1345.24  5044.6 1346.15  5063.1  1350.5  5101.7    1351
  5169.1 1350.89  5318.3 1352.96  5459.4 1355.74  5506.4 1360.08  5531.8 1364.46
  5612.9 1368.17  5725.3 1374.92  5789.1 1376.12  5837.3 1382.13  5891.2 1386.45
#Mann= 12 ,-1 , 0
  4146.4     .12       0  4355.9    .035       0  4502.9     .07       0
  4516.3    .035       0  5006.4    .035       0  5019.1    .035       0
  5063.1     .12       0  5101.7     .07       0  5169.1     .12       0
  5318.3     .07       0  5612.9     .12       0  5837.3     .07       0
Bank Sta=5006.4,5019.1
XS Rating Curve= 0 ,0
Exp/Cntr=0.3,0.1

Type RM Length L Ch R = 1 ,36948   ,418,418,418
BEGIN DESCRIPTION:
WASP CREEK 66.0
END DESCRIPTION:
XS GIS Cut Line= 3
      2050676.31     13875438.21        2050725.       13874725.
        2051325.       13874125.
#Sta/Elev= 30
  4285.8 1394.95  4409.3 1392.34  4439.4 1389.66  4499.1 1387.98  4569.7 1386.58
  4602.8 1384.64  4790.2 1381.99  4840.3 1377.43  4860.3 1371.61    4898 1366.73
  4920.5 1362.18  4926.4 1358.59  4931.4 1357.86  4954.1 1345.51  4954.6 1345.01
    4967 1345.51  5075.3  1346.6  5085.5 1347.08  5099.7    1352  5129.8 1352.39
  5184.5 1350.78  5219.1 1351.02  5264.7 1351.22  5517.5 1350.07  5580.5 1350.84
  5690.9 1360.87  5736.1 1366.16  5790.3 1368.95  5807.7 1369.88  5849.2 1370.76
#Mann= 14 ,-1 , 0
  4285.8    .035       0  4499.1     .07       0  4602.8     .12       0
    4898     .07       0  4954.1     .05       0    4967     .07       0
  5075.3    .033       0  5129.8     .12       0  5219.1     .07       0
  5264.7    .035       0  5517.5     .07       0  5690.9     .12       0
  5790.3     .07       0  5807.7     .12       0
Bank Sta=4954.1,4967
XS Rating Curve= 0 ,0
Exp/Cntr=0.3,0.1

Type RM Length L Ch R = 1 ,36530   ,485,485,485
BEGIN DESCRIPTION:
WASP CREEK 65.0
END DESCRIPTION:
XS GIS Cut Line= 3
      2050825.02       13875025.        2051025.       13874975.
      2052025.01     13873774.99
#Sta/Elev= 30
  4793.9 1387.19  4858.3 1384.44  4886.7 1379.76  4907.3 1372.75  4938.2 1365.97
  4958.8 1353.99  4983.3 1345.28  4983.8 1344.78  4996.2 1345.28  5050.4 1345.64
  5120.4 1346.24  5142.6 1350.79  5175.2 1350.11  5300.1 1347.15  5362.6 1347.34
  5603.4 1349.15  5773.9 1354.55    5809 1357.22  5845.5 1365.29  5866.3 1367.43
  5901.5 1365.69  5923.6 1370.34  5993.9 1376.35  6022.5 1382.89  6093.5  1390.7
  6171.6 1395.41  6193.1 1399.91  6363.6 1406.84  6391.8 1410.96  6562.1 1416.97
#Mann= 9 ,-1 , 0
  4793.9     .12       0  4938.2     .07       0  4983.3     .05       0
  4996.2     .07       0  5050.4    .033       0  5175.2     .07       0
  5300.1    .035       0  5362.6     .07       0  6391.8    .035       0
Bank Sta=4983.3,4996.2
XS Rating Curve= 0 ,0
Exp/Cntr=0.3,0.1

Type RM Length L Ch R = 1 ,36045   ,483,483,483
BEGIN DESCRIPTION:
WASP CREEK 64.0
END DESCRIPTION:
XS GIS Cut Line= 3
      2051425.01     13875274.96        2051475.       13875075.
      2051974.99     13873975.02
#Sta/Elev= 30
  4798.1  1370.5  4854.8  1366.2  4870.2 1363.84  4898.6 1354.32  4911.4 1351.58
  4921.8 1347.26  4974.3  1337.7  4974.8  1337.2  4987.7  1337.7  4993.9 1342.08
  5001.6 1344.25    5013 1345.16  5164.7 1346.05  5268.8 1345.48  5524.9 1346.17
  5707.2 1351.17  5795.1 1362.11  5812.7 1368.42  5858.8 1375.98    5894 1383.91
  5956.6 1391.62  6025.8    1396  6032.5 1398.06  6036.8 1399.39  6054.3 1399.76
  6059.8 1401.51  6146.6 1404.91  6168.6 1407.36  6180.7 1410.24  6212.5 1411.46
#Mann= 7 ,-1 , 0
  4798.1    .035       0  4854.8     .07       0  4974.3     .05       0
  4987.7     .07       0  5164.7    .035       0  5268.8     .07       0
  6032.5    .035       0
Bank Sta=4974.3,4987.7
XS Rating Curve= 0 ,0
Exp/Cntr=0.3,0.1

Type RM Length L Ch R = 1 ,35562   ,466,466,466
BEGIN DESCRIPTION:
WASP CREEK 63.0
END DESCRIPTION:
XS GIS Cut Line= 3
      2051806.99     13875807.57        2051925.       13875075.
      2051991.66     13874048.47
#Sta/Elev= 30
  4257.6 1368.34  4409.5 1363.01  4418.2 1362.52  4419.9 1362.42  4466.5 1360.34
  4533.7  1352.2  4614.7 1350.48  4645.1 1351.69  4786.9 1345.82  4898.3 1343.77
  4959.1 1340.65  4972.7  1337.2  4973.2  1336.7  4986.1  1337.2  5019.7 1341.15
  5280.2 1341.62  5542.8 1347.34  5600.9 1349.57    5651 1354.36  5675.8 1358.47
  5701.9 1363.25  5721.1 1368.92  5761.2  1375.7  5791.3 1384.67  5821.3  1389.3
  5847.4 1392.78  5881.5 1394.62  5911.5  1400.3  5996.9 1404.43  6028.3 1405.51
#Mann= 9 ,-1 , 0
  4257.6     .07       0  4409.5    .035       0  4418.2     .07       0
  4419.9    .035       0  4972.7    .035       0  4986.1    .035       0
  5675.8     .07       0  5701.9     .12       0  5996.9    .035       0
Bank Sta=4972.7,4986.1
XS Rating Curve= 0 ,0
Exp/Cntr=0.3,0.1

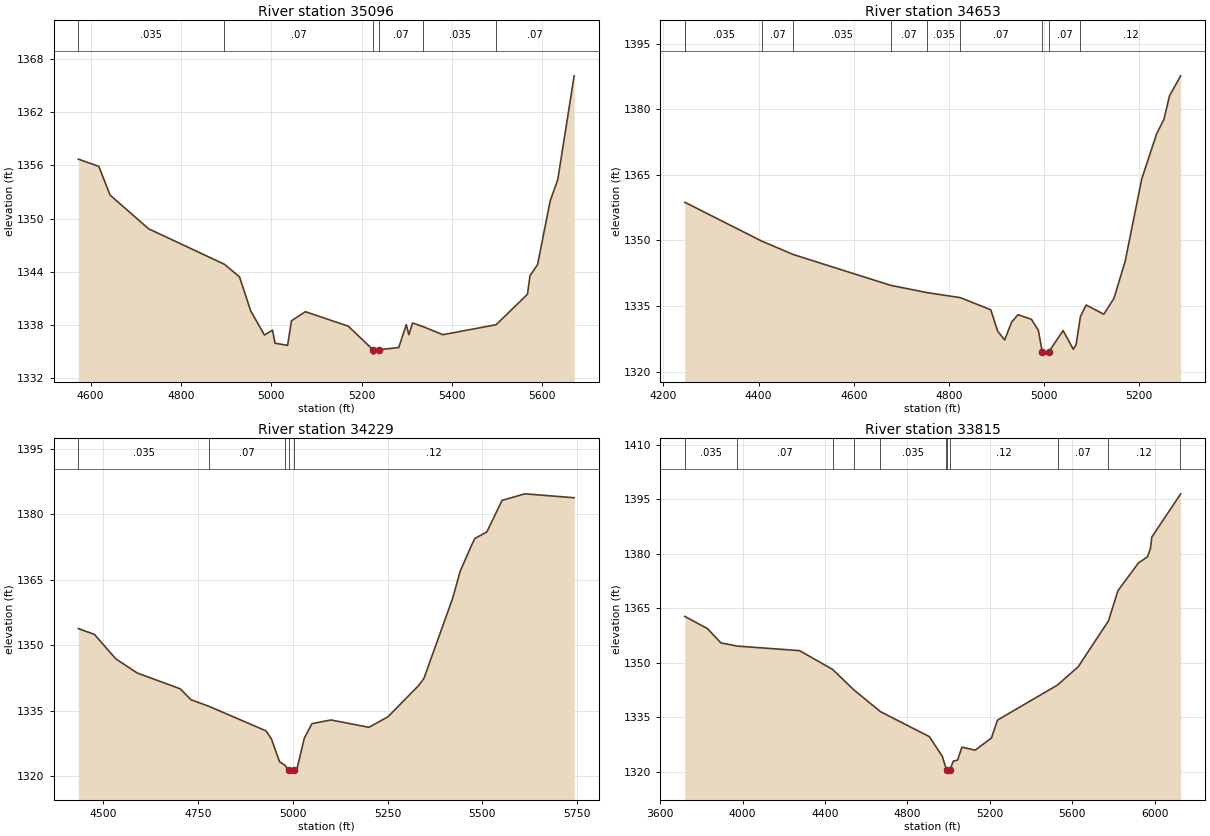
Type RM Length L Ch R = 1 ,35096   ,443,443,443
BEGIN DESCRIPTION:
WASP CREEK 62.0
END DESCRIPTION:
XS GIS Cut Line= 3
        2052225.       13875525.        2052375.       13875125.
      2052674.99     13874525.02
#Sta/Elev= 30
  4572.9 1356.69  4618.3 1355.87  4643.2 1352.64  4728.7 1348.84  4896.4 1344.85
  4929.8 1343.43  4954.7 1339.59    4985 1336.88  5002.9 1337.43  5008.5 1335.96
  5036.4 1335.72  5044.8 1338.48  5075.6 1339.51  5170.6 1337.88  5225.3 1335.23
  5225.8 1334.73  5238.8 1335.23  5282.4 1335.47  5299.2 1338.05  5304.8 1336.92
  5313.2 1338.24  5336.6 1337.82  5380.2 1336.92    5498 1338.04  5567.5 1341.47
  5573.1 1343.55  5589.9 1344.81  5617.8 1351.98  5634.6 1354.38  5670.9 1366.07
#Mann= 6 ,-1 , 0
  4572.9    .035       0  4896.4     .07       0  5225.3     .05       0
  5238.8     .07       0  5336.6    .035       0    5498     .07       0
Bank Sta=5225.3,5238.8
XS Rating Curve= 0 ,0
Exp/Cntr=0.3,0.1

Type RM Length L Ch R = 1 ,34653   ,424,424,424
BEGIN DESCRIPTION:
WASP CREEK 61.0
END DESCRIPTION:
XS GIS Cut Line= 3
      2052274.98     13875575.03        2052725.       13874975.
      2052875.01     13874724.99
#Sta/Elev= 30
  4245.1  1358.7  4245.8  1358.7  4407.1 1349.84  4473.3 1346.78  4677.3 1339.76
  4753.9 1338.09  4823.8 1336.94  4887.8 1334.17  4902.4 1329.27    4917 1327.27
  4931.6 1331.33  4945.1 1333.04  4973.3 1331.98  4987.8 1329.48  4996.1 1324.53
  4996.6 1324.03  5009.7 1324.53  5039.8 1329.43  5061.2 1325.14  5067.1 1326.17
  5076.2 1332.63  5088.4 1335.25  5125.4 1333.15  5146.7 1336.79  5170.1  1345.2
  5205.1  1364.1  5236.1 1374.32  5251.7 1377.71  5263.4 1383.06  5286.7 1387.63
#Mann= 10 ,-1 , 0
  4245.1     .07       0  4245.8    .035       0  4407.1     .07       0
  4473.3    .035       0  4677.3     .07       0  4753.9    .035       0
  4823.8     .07       0  4996.1     .05       0  5009.7     .07       0
  5076.2     .12       0
Bank Sta=4996.1,5009.7
XS Rating Curve= 0 ,0
Exp/Cntr=0.3,0.1

Type RM Length L Ch R = 1 ,34229   ,414,414,414
BEGIN DESCRIPTION:
WASP CREEK 60.0
END DESCRIPTION:
XS GIS Cut Line= 3
      2052574.97     13875675.03        2052975.       13875275.
      2053028.74     13874535.38
#Sta/Elev= 30
  4434.7 1353.86  4477.2 1352.52  4533.7 1346.91  4590.3 1343.67  4703.4 1340.06
  4731.7 1337.55  4778.4 1336.07  4929.7 1330.42  4943.9 1328.55  4965.1 1323.37
  4978.6 1322.59  4990.1 1321.47  4990.6 1320.97  5003.7 1321.47  5010.5 1321.48
  5030.5 1328.73  5050.6 1332.07  5100.7 1332.92    5201 1331.24  5251.1 1333.65
  5331.3 1340.75  5345.9 1342.44  5421.5 1360.75  5441.6 1367.02  5471.7 1372.98
    5480 1374.49  5511.8    1376  5551.9 1383.23    5612 1384.73    5742 1383.83
#Mann= 5 ,-1 , 0
  4434.7    .035       0  4778.4     .07       0  4978.6     .12       0
  4990.1     .05       0  5003.7     .12       0
Bank Sta=4990.1,5003.7
XS Rating Curve= 0 ,0
Exp/Cntr=0.3,0.1

Type RM Length L Ch R = 1 ,33815   ,426,426,426
BEGIN DESCRIPTION:
WASP CREEK 59.0
END DESCRIPTION:
XS GIS Cut Line= 3
      2052004.48     13875963.34        2053225.       13875575.
      2053904.98     13874679.28
#Sta/Elev= 30
  3719.7 1362.79    3830 1359.41  3894.5 1355.51  3972.6 1354.62  4276.4 1353.36
  4436.6  1348.2  4539.7 1342.57    4669 1336.56  4906.1 1329.69    4969 1324.27
  4988.2 1320.71  4990.8 1320.42  4991.3 1319.92  5004.9 1320.42  5022.3 1322.95
  5043.2 1323.24    5064  1326.8  5128.4 1325.96  5207.5 1329.33  5236.6 1334.24
  5527.8 1343.89  5628.3 1348.93    5775 1361.55    5821 1369.86  5920.9 1377.53
  5964.5 1379.19    5979 1381.54  5985.3 1384.63  6121.9 1396.22  6125.1 1396.52
#Mann= 11 ,-1 , 0
  3719.7    .035       0  3972.6     .07       0  4436.6    .035       0
  4539.7     .07       0    4669    .035       0  4988.2     .12       0
  4990.8     .05       0  5004.9     .12       0  5527.8     .07       0
    5775     .12       0  6121.9     .07       0
Bank Sta=4990.8,5004.9
XS Rating Curve= 0 ,0
Exp/Cntr=0.3,0.1