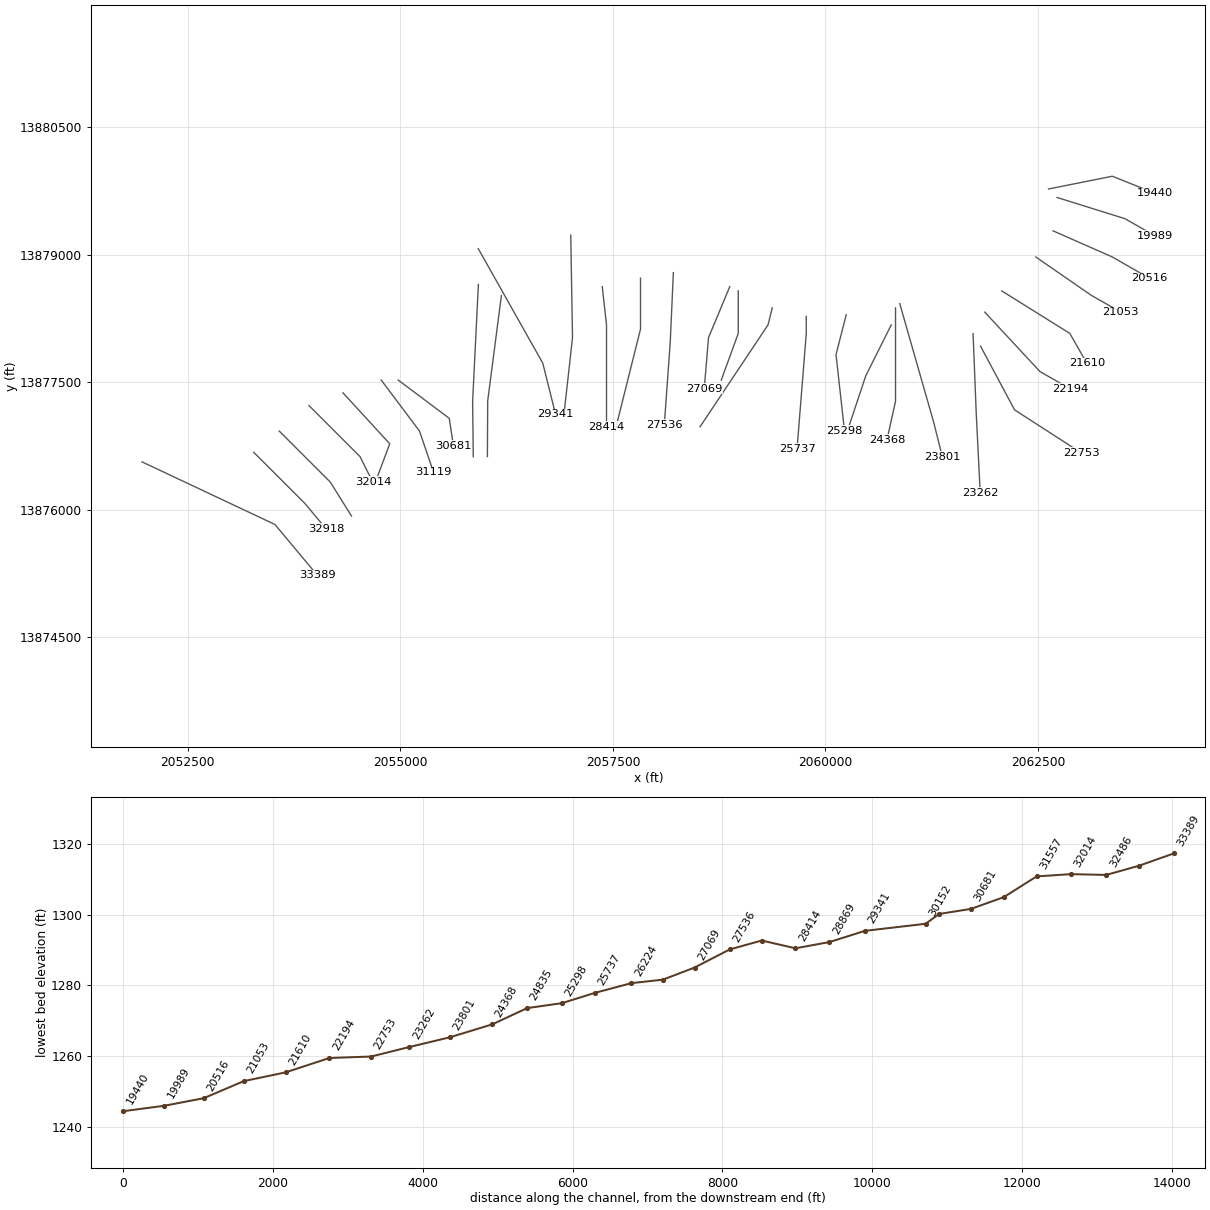
HEC-RAS study WASP CREEK.prj: WASP CREEK Base Level Engineering

--- WASP CREEK.g01 (geometry) --- (continued)

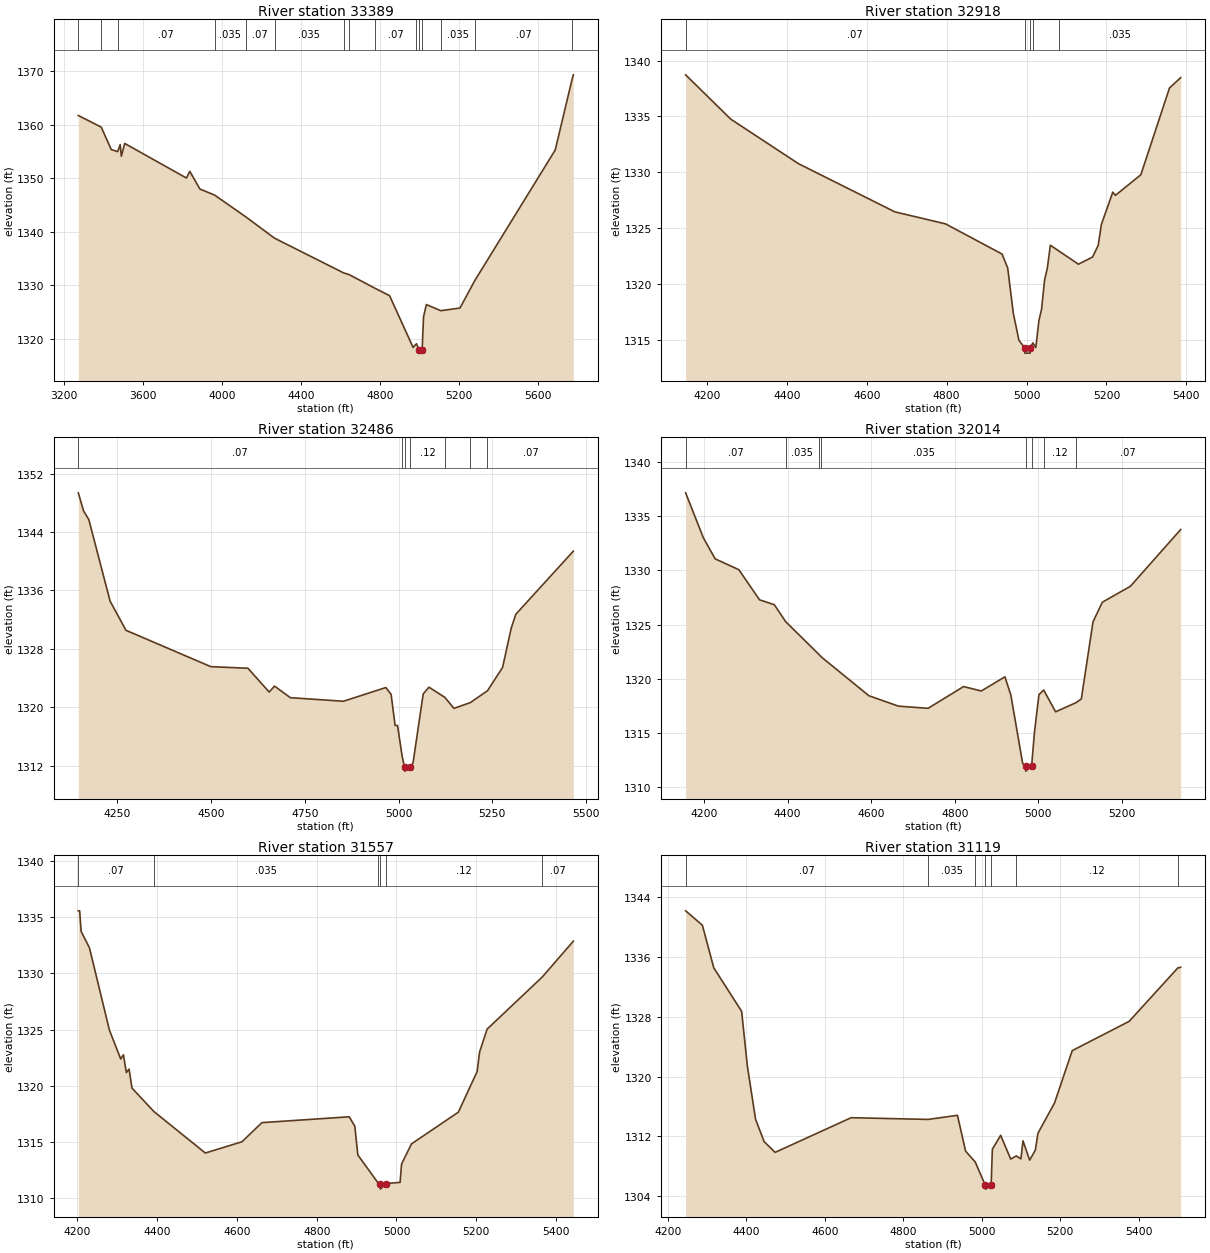
Type RM Length L Ch R = 1 ,33389   ,471,471,471
BEGIN DESCRIPTION:
WASP CREEK 58.0
END DESCRIPTION:
XS GIS Cut Line= 3
      2051961.01     13876562.32        2053525.       13875825.
        2054025.       13875225.
#Sta/Elev= 30
  3270.9 1361.69  3387.1 1359.52  3438.1 1355.33  3470.4 1354.95  3483.6 1356.25
  3489.1 1354.08  3506.4 1356.47  3819.1 1350.02  3836.4 1351.26  3887.5 1347.96
  3961.7 1346.84  4120.6 1342.76  4265.8 1338.79  4616.1 1332.31  4643.6    1332
  4776.4 1329.42  4849.1 1328.06  4968.6 1318.39  4985.6 1319.08    5000 1317.83
  5000.5 1317.33  5014.3 1317.83  5021.5  1324.1  5035.8  1326.4  5108.9 1325.25
  5206.3 1325.75  5281.5 1330.88  5689.2 1355.24  5774.4  1368.4    5781 1369.28
#Mann= 15 ,-1 , 0
  3270.9     .07       0  3387.1    .035       0  3470.4     .07       0
  3961.7    .035       0  4120.6     .07       0  4265.8    .035       0
  4616.1     .07       0  4643.6    .035       0  4776.4     .07       0
  4985.6     .12       0    5000     .05       0  5014.3     .12       0
  5108.9    .035       0  5281.5     .07       0  5774.4     .12       0
Bank Sta=5000,5014.3
XS Rating Curve= 0 ,0
Exp/Cntr=0.3,0.1

Type RM Length L Ch R = 1 ,32918   ,432,432,432
BEGIN DESCRIPTION:
WASP CREEK 57.0
END DESCRIPTION:
XS GIS Cut Line= 3
      2053275.03     13876674.97        2053875.       13876075.
        2054125.       13875775.
#Sta/Elev= 30
  4146.7 1338.72  4259.8 1334.75  4429.5 1330.76  4669.9 1326.46  4797.2 1325.38
  4938.6 1322.68  4952.8 1321.43  4966.9 1317.36    4981 1314.95  4995.1 1314.31
  4995.6 1313.81    5009 1313.81  5009.5 1314.31  5015.8 1314.73  5023.2 1314.31
    5031 1316.74  5037.5 1317.72  5045.3  1320.4  5051.8 1321.37  5059.6 1323.47
  5080.9 1322.95  5129.9 1321.77  5165.1 1322.41  5179.4 1323.46  5187.2 1325.32
  5215.8 1328.22  5222.3 1327.93  5286.1 1329.78  5357.7 1337.54  5385.7 1338.47
#Mann= 5 ,-1 , 0
  4146.7     .07       0  4995.1     .05       0  5009.5     .07       0
  5015.8     .12       0  5080.9    .035       0
Bank Sta=4995.1,5009.5
XS Rating Curve= 0 ,0
Exp/Cntr=0.3,0.1

Type RM Length L Ch R = 1 ,32486   ,472,472,472
BEGIN DESCRIPTION:
WASP CREEK 56.0
END DESCRIPTION:
XS GIS Cut Line= 3
      2053575.03     13876924.97        2054175.       13876325.
      2054425.01     13875924.98
#Sta/Elev= 30
  4145.9 1349.37    4160 1346.89  4174.1 1345.69  4230.7 1334.54  4273.1 1330.54
  4499.4 1325.56  4598.4 1325.34    4655 1322.08  4669.1  1322.9  4711.5 1321.31
    4853 1320.82  4966.1  1322.7  4980.2 1321.76  4990.8  1317.5  4997.3  1317.5
  5009.5 1313.32    5016 1311.75  5016.5 1311.25  5030.5 1311.75  5038.6 1312.36
  5065.7 1321.82  5081.1 1322.75  5123.3 1321.36  5147.7 1319.85  5191.2 1320.63
  5237.2 1322.26  5277.4 1325.45  5300.4 1330.82  5312.8 1332.74  5466.1 1341.38
#Mann= 7 ,-1 , 0
  4145.9     .07       0  5009.5     .12       0    5016     .05       0
  5030.5     .12       0  5123.3     .07       0  5191.2    .035       0
  5237.2     .07       0
Bank Sta=5016,5030.5
XS Rating Curve= 0 ,0
Exp/Cntr=0.3,0.1

Type RM Length L Ch R = 1 ,32014   ,457,457,457
BEGIN DESCRIPTION:
WASP CREEK 55.0
END DESCRIPTION:
XS GIS Cut Line= 3
      2053925.02     13877224.98        2054525.       13876625.
      2054674.99     13876325.01
#Sta/Elev= 30
  4156.3 1337.17  4198.7 1333.02    4227 1331.07  4283.6 1330.07  4333.1 1327.29
  4368.4 1326.84  4395.6 1325.27  4474.8 1322.26  4481.2    1322  4594.7 1318.43
  4665.4 1317.47  4736.1 1317.27    4821 1319.28  4863.4 1318.87  4919.9 1320.18
  4934.1 1318.49  4962.4 1312.17  4969.3 1311.97  4969.8 1311.47  4983.8 1311.97
  4990.7 1315.11  5001.3 1318.53  5012.6 1318.96  5041.1 1316.95  5089.3 1317.78
  5102.6 1318.13  5130.6 1325.26  5152.9 1327.07    5220 1328.54  5340.2 1333.78
#Mann= 8 ,-1 , 0
  4156.3     .07       0  4395.6    .035       0  4474.8     .07       0
  4481.2    .035       0  4969.3    .035       0  4983.8    .035       0
  5012.6     .12       0  5089.3     .07       0
Bank Sta=4969.3,4983.8
XS Rating Curve= 0 ,0
Exp/Cntr=0.3,0.1

Type RM Length L Ch R = 1 ,31557   ,438,438,438
BEGIN DESCRIPTION:
WASP CREEK 54.0
END DESCRIPTION:
XS GIS Cut Line= 3
      2054325.01     13877374.99        2054875.       13876775.
      2054725.01     13876375.02
#Sta/Elev= 30
  4202.3 1335.57  4205.7 1335.57  4209.4 1333.74  4230.3 1332.28  4280.3 1324.97
  4308.7  1322.4  4315.4 1322.77  4322.8 1321.19  4329.6  1321.5    4337 1319.81
  4391.8 1317.73  4520.8 1314.04  4612.6 1315.04  4662.6 1316.74  4881.5 1317.26
  4895.7 1316.41  4903.1 1313.87  4954.1 1311.37  4959.3 1311.33  4959.8 1310.83
  4973.9 1311.33  5009.1 1311.43  5012.8 1313.06  5037.6 1314.85  5155.1 1317.67
  5202.2 1321.28  5208.5 1323.03  5227.2 1325.05  5365.6 1329.69  5443.4 1332.87
#Mann= 6 ,-1 , 0
  4202.3     .07       0  4391.8    .035       0  4954.1     .12       0
  4959.3     .05       0  4973.9     .12       0  5365.6     .07       0
Bank Sta=4959.3,4973.9
XS Rating Curve= 0 ,0
Exp/Cntr=0.3,0.1

Type RM Length L Ch R = 1 ,31119   ,438,438,438
BEGIN DESCRIPTION:
WASP CREEK 53.0
END DESCRIPTION:
XS GIS Cut Line= 3
      2054775.02     13877524.97        2055225.       13876925.
      2055389.86     13876440.76
#Sta/Elev= 30
  4245.5 1342.14  4288.2 1340.22  4317.3 1334.52  4388.2 1328.72  4402.8 1321.42
  4423.6 1314.33  4445.5 1311.32  4473.6 1309.88  4667.3 1314.51  4863.4 1314.28
  4938.2 1314.83    4959 1310.04  4983.6 1308.59  5009.2 1305.47  5009.7 1304.97
    5024 1305.47  5027.2  1310.3  5048.3 1312.16  5073.9 1308.98  5088.2 1309.41
  5099.9 1309.01  5105.2 1311.42  5122.2 1308.85  5136.6 1310.17  5143.4 1312.44
  5185.6 1316.48  5230.7 1323.47  5375.8 1327.38  5499.5  1334.5    5507  1334.6
#Mann= 7 ,-1 , 0
  4245.5     .07       0  4863.4    .035       0  4983.6     .07       0
  5009.2     .05       0    5024     .07       0  5088.2     .12       0
  5499.5    .035       0
Bank Sta=5009.2,5024
XS Rating Curve= 0 ,0
Exp/Cntr=0.3,0.1

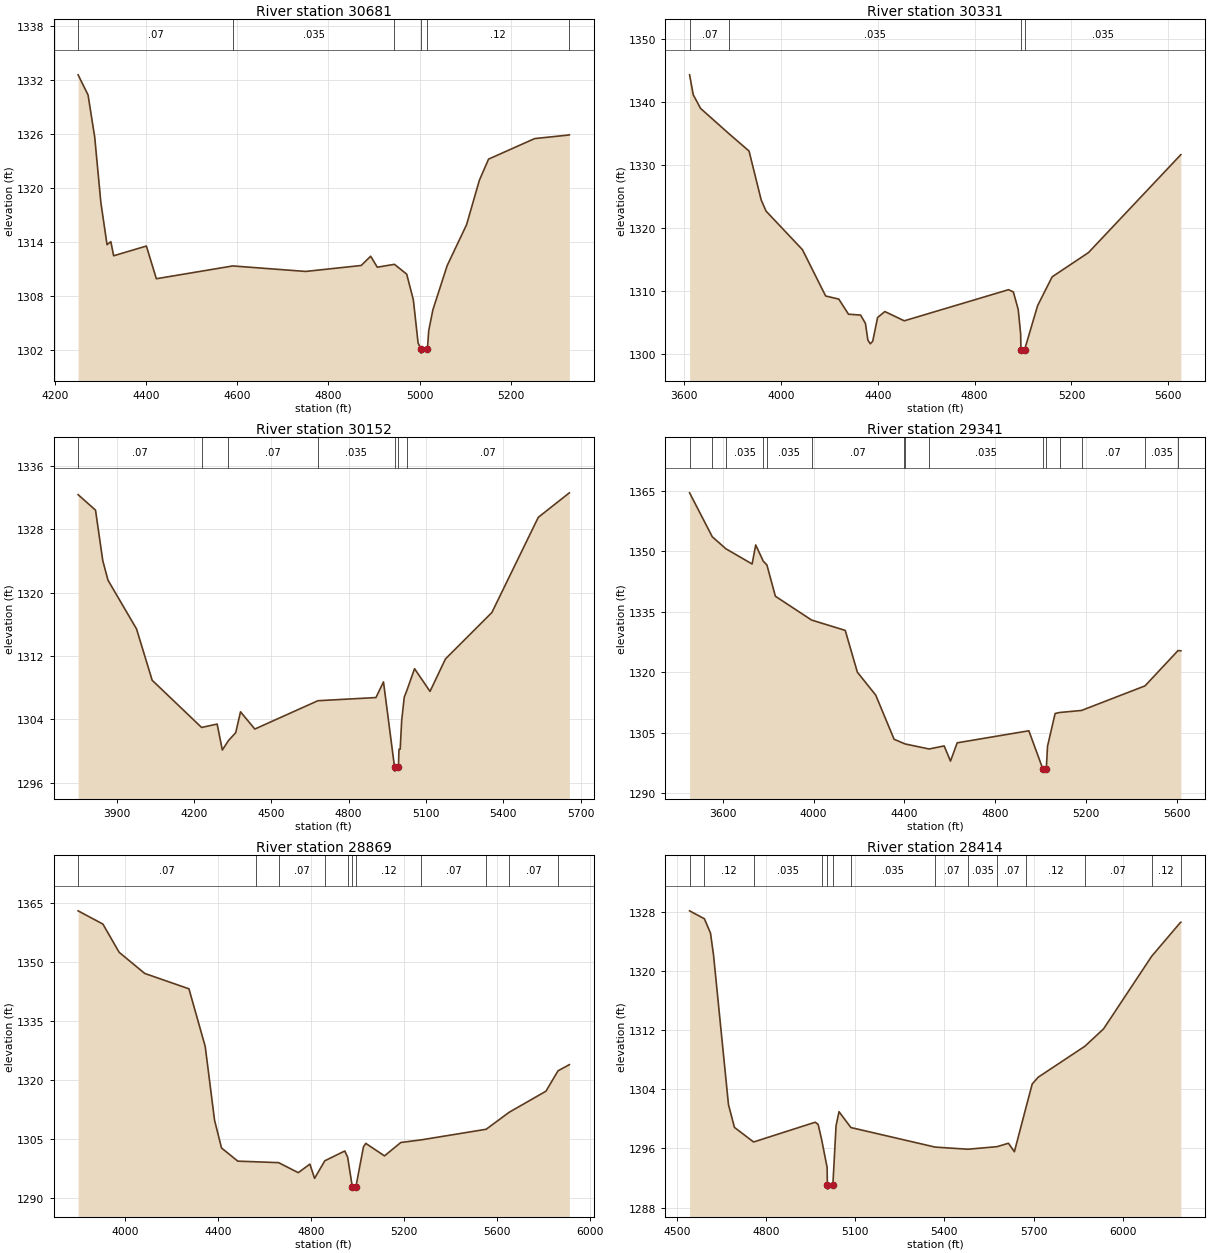
Type RM Length L Ch R = 1 ,30681   ,426,426,426
BEGIN DESCRIPTION:
WASP CREEK 52.0
END DESCRIPTION:
XS GIS Cut Line= 3
      2054974.98     13877525.01        2055575.       13877075.
      2055624.14     13876749.51
#Sta/Elev= 30
    4250 1332.55  4271.9 1330.31  4286.5 1325.63    4300 1318.37  4313.6 1313.69
  4321.9 1314.03  4328.1 1312.46    4400 1313.54  4421.9 1309.91  4589.7 1311.33
    4750 1310.72  4871.9 1311.38  4892.7 1312.41  4907.3 1311.19  4944.9 1311.51
  4971.9 1310.42  4986.5 1307.56  4996.9 1302.78  5002.7 1302.15  5003.2 1301.65
  5017.5 1302.15  5020.2 1304.13  5029.4 1306.46  5060.7 1311.36  5103.4 1315.91
  5131.5 1320.84  5151.7 1323.19  5252.9 1325.47  5328.4 1325.87  5329.2 1325.89
#Mann= 6 ,-1 , 0
    4250     .07       0  4589.7    .035       0  4944.9     .12       0
  5002.7     .05       0  5017.5     .12       0  5328.4    .035       0
Bank Sta=5002.7,5017.5
XS Rating Curve= 0 ,0
Exp/Cntr=0.3,0.1

Type RM Length L Ch R = 1 ,30331   ,179,179,179
BEGIN DESCRIPTION:
WASP CREEK 51.0
END DESCRIPTION:
XS GIS Cut Line= 3
      2055917.74     13878650.22      2055849.88     13877275.29
       2055857.6     13876623.64
#Sta/Elev= 30
  3623.4 1344.39  3638.6 1341.22  3668.7 1339.06  3787.3    1335  3868.9 1332.29
    3919 1324.53    3939 1322.76  4089.2 1316.64  4185.2 1309.28  4239.4 1308.79
  4279.4 1306.39  4329.5 1306.25  4349.5 1304.92  4359.5 1302.28  4369.5 1301.69
  4379.5  1302.1  4399.6 1305.86  4429.6 1306.81  4509.7 1305.34  4940.2 1310.28
  4960.2 1309.92  4980.3 1307.12  4990.3 1303.25  4991.4 1300.71  4991.9 1300.21
  5006.2 1300.71  5060.3 1307.75  5120.3 1312.32  5270.3 1316.17  5651.7 1331.72
#Mann= 4 ,-1 , 0
  3623.4     .07       0  3787.3    .035       0  4991.4    .035       0
  5006.2    .035       0
Bank Sta=4991.4,5006.2
XS Rating Curve= 0 ,0
Exp/Cntr=0.3,0.1

Type RM Length L Ch R = 1 ,30152   ,811,811,811
BEGIN DESCRIPTION:
WASP CREEK 50.0
END DESCRIPTION:
XS GIS Cut Line= 3
      2056188.34      13878519.9      2056027.35     13877280.71
      2056023.76     13876624.42
#Sta/Elev= 30
  3750.4 1332.39    3818 1330.43  3846.1 1324.05  3866.3 1321.58  3977.2 1315.41
  4037.7 1308.93  4229.5 1302.96  4289.8 1303.39    4310 1300.11  4333.5 1301.29
  4361.9  1302.3  4380.5 1304.94    4436 1302.76  4680.7 1306.34  4905.9 1306.74
  4935.2 1308.72  4978.1 1297.94  4978.6 1297.44  4993.1 1297.94  4995.3 1300.21
    5000 1300.21  5005.7 1303.81  5015.7 1306.78    5026 1307.65  5055.7 1310.39
  5115.7 1307.52  5175.7 1311.63  5355.7 1317.49  5535.7 1329.52  5656.3 1332.62
#Mann= 7 ,-1 , 0
  3750.4     .07       0  4229.5    .035       0  4333.5     .07       0
  4680.7    .035       0  4978.1    .035       0  4993.1    .035       0
    5026     .07       0
Bank Sta=4978.1,4993.1
XS Rating Curve= 0 ,0
Exp/Cntr=0.3,0.1

Type RM Length L Ch R = 1 ,29341   ,472,472,472
BEGIN DESCRIPTION:
WASP CREEK 49.0
END DESCRIPTION:
XS GIS Cut Line= 3
      2055916.22     13879072.56        2056675.       13877725.
      2056825.01     13877124.96
#Sta/Elev= 30
  3453.5 1364.55  3553.6 1353.63  3613.4 1350.66    3729 1346.88  3744.9 1351.61
  3778.2 1347.58  3794.3 1346.63  3831.6 1338.87    3991 1332.96  4139.4 1330.39
  4192.9 1320.01  4273.9 1314.31  4354.8 1303.35  4398.2 1302.31    4404 1302.18
  4509.2 1300.94  4575.4  1301.7  4603.3 1297.93  4632.8 1302.47  4948.7 1305.46
  5010.5 1295.94    5011 1295.44  5025.5 1295.94  5030.9 1301.61  5064.4 1309.75
  5084.2    1310  5180.9 1310.51  5460.5 1316.61    5606 1325.37  5618.5 1325.33
#Mann= 15 ,-1 , 0
  3453.5    .035       0  3553.6     .07       0  3613.4    .035       0
  3778.2     .07       0  3794.3    .035       0    3991     .07       0
  4398.2     .12       0    4404     .07       0  4509.2    .035       0
  5010.5    .035       0  5025.5    .035       0  5084.2     .12       0
  5180.9     .07       0  5460.5    .035       0    5606     .12       0
Bank Sta=5010.5,5025.5
XS Rating Curve= 0 ,0
Exp/Cntr=0.3,0.1

Type RM Length L Ch R = 1 ,28869   ,455,455,455
BEGIN DESCRIPTION:
WASP CREEK 48.0
END DESCRIPTION:
XS GIS Cut Line= 3
      2057004.44     13879231.56        2057025.       13878025.
        2056925.     13877124.98
#Sta/Elev= 30
    3798  1362.9  3904.6 1359.54  3974.6 1352.37  4084.6 1347.01  4274.6 1343.11
  4344.6 1328.48  4384.6 1309.81  4414.7 1302.72  4484.7 1299.38  4563.8 1299.21
  4660.1    1299  4744.7 1296.46  4794.7 1298.63  4814.7 1295.01  4858.8 1299.47
  4944.7 1301.96  4957.1 1300.38  4977.2 1292.78  4977.7 1292.28  4992.2 1292.78
  5024.9 1302.99  5034.9 1303.89  5115.4 1300.72  5185.8 1304.12  5273.4 1304.78
  5552.6 1307.47  5651.9  1311.8  5809.7 1317.13  5861.6 1322.31  5910.3 1323.87
#Mann= 11 ,-1 , 0
    3798     .07       0  4563.8    .035       0  4660.1     .07       0
  4858.8    .035       0  4957.1     .12       0  4977.2     .05       0
  4992.2     .12       0  5273.4     .07       0  5552.6     .12       0
  5651.9     .07       0  5861.6     .12       0
Bank Sta=4977.2,4992.2
XS Rating Curve= 0 ,0
Exp/Cntr=0.3,0.1

Type RM Length L Ch R = 1 ,28414   ,449,449,449
BEGIN DESCRIPTION:
WASP CREEK 47.0
END DESCRIPTION:
XS GIS Cut Line= 3
        2057375.     13878624.97        2057425.       13878175.
        2057425.     13876975.04
#Sta/Elev= 30
  4542.7 1328.11  4592.5 1327.04  4613.1 1325.09  4623.2 1322.14  4673.5 1301.93
  4693.6 1298.85    4758 1296.88  4965.3 1299.55  4975.3 1299.24    4987 1297.19
  5005.4 1293.44  5006.2 1291.01  5006.7 1290.51  5024.6 1291.01  5035.4 1299.08
  5045.4 1300.97  5085.4 1298.83  5368.5 1296.19  5478.9  1295.9  5577.3 1296.25
  5615.4 1296.71  5635.4 1295.56  5675.7 1301.74  5695.4 1304.72  5715.4 1305.63
  5872.4 1309.81  5935.4 1312.16  6097.2 1321.97  6194.6 1326.57  6195.4 1326.57
#Mann= 14 ,-1 , 0
  4542.7     .07       0  4592.5     .12       0    4758    .035       0
    4987     .07       0  5006.2     .05       0  5024.6     .07       0
  5085.4    .035       0  5368.5     .07       0  5478.9    .035       0
  5577.3     .07       0  5675.7     .12       0  5872.4     .07       0
  6097.2     .12       0  6194.6     .07       0
Bank Sta=5006.2,5024.6
XS Rating Curve= 0 ,0
Exp/Cntr=0.3,0.1

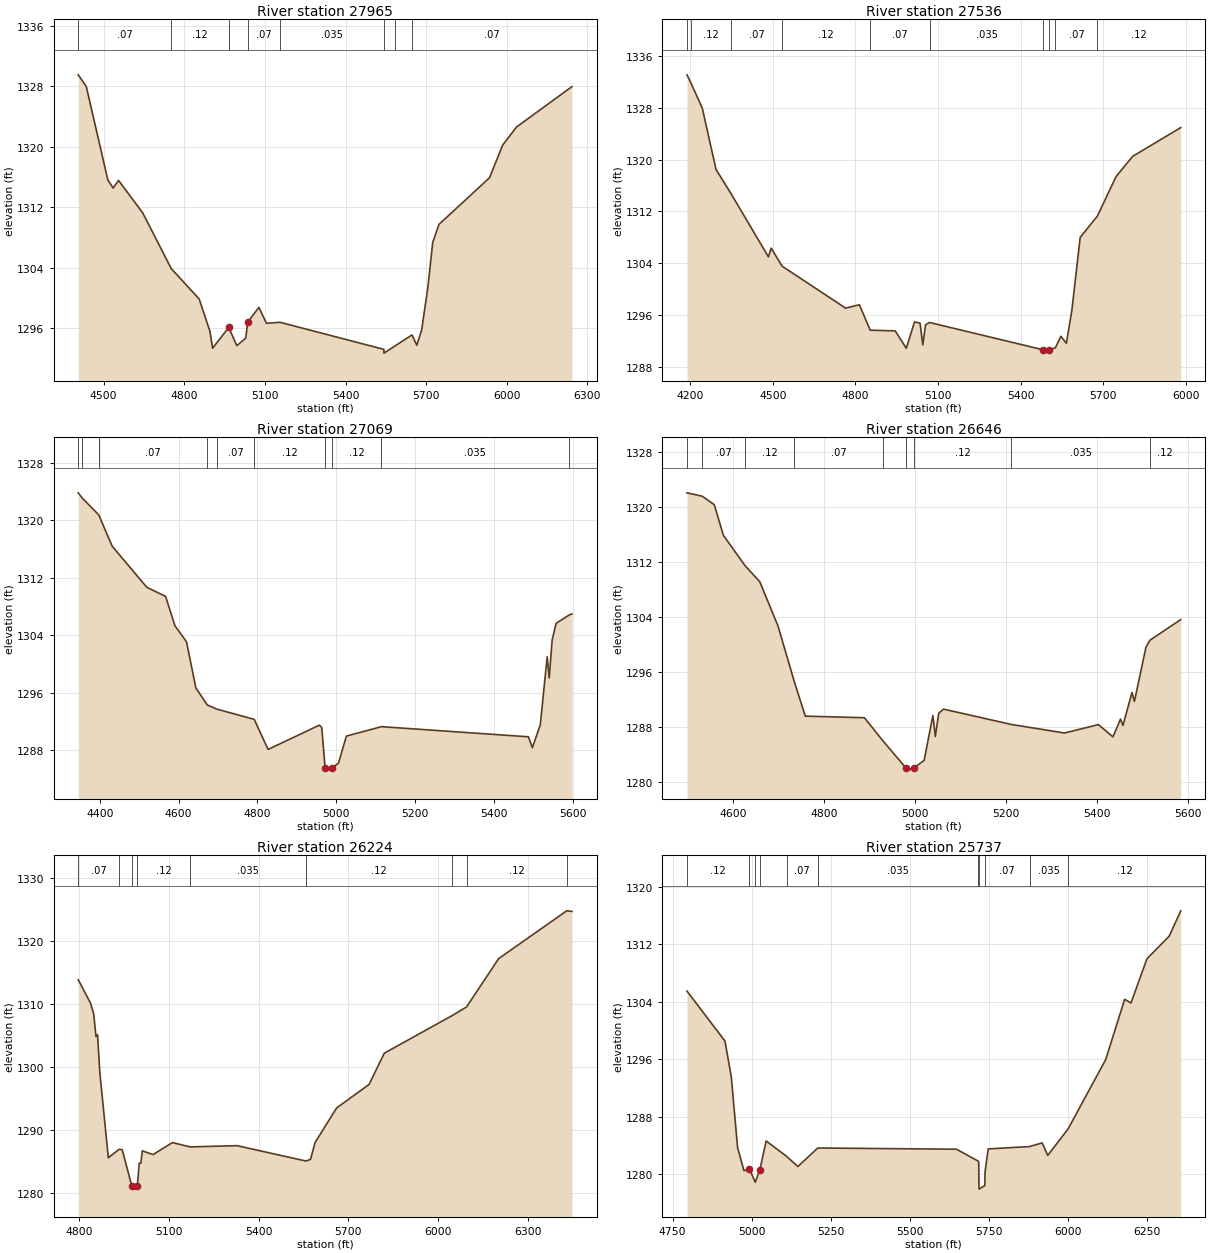
Type RM Length L Ch R = 1 ,27965   ,429,429,429
BEGIN DESCRIPTION:
WASP CREEK 46.0
END DESCRIPTION:
XS GIS Cut Line= 3
        2057825.     13878724.95        2057825.       13878125.
        2057525.     13876924.98
#Sta/Elev= 30
  4405.3 1329.51  4435.3 1327.97  4515.3 1315.63  4535.3 1314.53  4555.3 1315.55
  4645.3 1311.25  4751.4 1303.89  4855.3 1299.87  4895.3 1295.59  4905.3 1293.36
  4965.3 1296.11  4995.3 1293.69  5028.4 1294.69  5036.2 1296.83  5077.4 1298.76
  5105.8 1296.65  5155.7 1296.79  5542.4 1293.21  5542.9 1292.71  5583.1 1293.64
  5647.1 1295.12  5664.9 1293.75    5683 1295.76  5706.2 1301.41  5724.2 1307.35
  5747.4 1309.73  5935.5  1315.9  5984.5 1320.22    6036 1322.61  6242.2 1327.95
#Mann= 8 ,-1 , 0
  4405.3     .07       0  4751.4     .12       0  4965.3    .035       0
  5036.2     .07       0  5155.7    .035       0  5542.4     .05       0
  5583.1    .035       0  5647.1     .07       0
Bank Sta=4965.3,5036.2
XS Rating Curve= 0 ,0
Exp/Cntr=0.3,0.1

Type RM Length L Ch R = 1 ,27536   ,467,467,467
BEGIN DESCRIPTION:
WASP CREEK 45.0
END DESCRIPTION:
XS GIS Cut Line= 3
      2058211.47     13878790.42        2058175.       13877975.
      2058105.08     13877000.84
#Sta/Elev= 30
  4188.2 1333.05    4202 1331.83  4243.7 1327.92  4293.7 1318.46  4347.5 1314.79
  4483.9 1305.01  4493.9 1306.35  4533.5 1303.58  4764.2 1297.11  4814.2 1297.63
  4853.6 1293.71  4944.4 1293.61  4984.4 1290.93  5014.5 1294.99  5034.5  1294.8
  5044.5 1291.44  5054.6 1294.54  5069.1  1294.9  5482.7 1290.68  5483.2 1290.18
  5501.2 1290.68    5526    1291  5545.8 1292.77  5565.9  1291.7  5585.9  1296.8
    5616 1308.01  5678.6  1311.3  5746.3 1317.38  5806.5 1320.49  5981.1 1324.92
#Mann= 10 ,-1 , 0
  4188.2     .07       0    4202     .12       0  4347.5     .07       0
  4533.5     .12       0  4853.6     .07       0  5069.1    .035       0
  5482.7     .05       0  5501.2    .035       0    5526     .07       0
  5678.6     .12       0
Bank Sta=5482.7,5501.2
XS Rating Curve= 0 ,0
Exp/Cntr=0.3,0.1

Type RM Length L Ch R = 1 ,27069   ,423,423,423
BEGIN DESCRIPTION:
WASP CREEK 44.0
END DESCRIPTION:
XS GIS Cut Line= 3
      2058874.99     13878624.98        2058625.       13878025.
        2058575.     13877424.96
#Sta/Elev= 30
  4345.5 1323.83    4356 1323.08  4397.5 1320.76  4431.6  1316.4  4519.4 1310.68
    4567 1309.41  4590.9 1305.31  4620.1 1303.09  4643.9 1296.65  4672.9 1294.29
  4696.6 1293.72  4791.8 1292.29    4827  1288.1    4957 1291.48    4963 1291.16
  4971.6 1285.58  4972.1 1285.08  4990.1 1285.58  5005.5 1286.18  5025.6 1289.96
  5114.5 1291.27  5487.2 1289.86  5497.2 1288.34  5517.3 1291.53  5534.8    1301
  5539.9 1298.06  5547.4 1303.34  5557.4 1305.66  5590.5 1306.82  5597.6 1306.97
#Mann= 10 ,-1 , 0
  4345.5     .07       0    4356    .035       0  4397.5     .07       0
  4672.9     .12       0  4696.6     .07       0  4791.8     .12       0
  4971.6     .05       0  4990.1     .12       0  5114.5    .035       0
  5590.5     .07       0
Bank Sta=4971.6,4990.1
XS Rating Curve= 0 ,0
Exp/Cntr=0.3,0.1

Type RM Length L Ch R = 1 ,26646   ,422,422,422
BEGIN DESCRIPTION:
WASP CREEK 43.0
END DESCRIPTION:
XS GIS Cut Line= 3
        2058975.     13878574.95        2058975.       13878075.
        2058775.     13877524.99
#Sta/Elev= 30
  4499.5 1322.09    4533  1321.6  4559.5 1320.36  4579.5 1315.91  4627.4 1311.48
  4659.5 1309.17  4699.5 1302.74  4735.4 1294.64  4759.5 1289.64  4889.5 1289.41
  4929.7 1286.09  4980.2 1282.15  4980.7 1281.65  4998.7 1282.15  5020.7 1283.21
    5040 1289.74  5045.3 1286.67  5052.7 1290.05  5063.3 1290.66  5212.5 1288.43
  5329.3 1287.19  5403.8 1288.41  5435.7 1286.63  5452.3 1289.21  5457.7 1288.28
  5477.6 1293.08  5482.9 1291.78  5508.2 1299.63  5516.9 1300.66  5584.7 1303.67
#Mann= 9 ,-1 , 0
  4499.5    .035       0    4533     .07       0  4627.4     .12       0
  4735.4     .07       0  4929.7     .12       0  4980.2     .05       0
  4998.7     .12       0  5212.5    .035       0  5516.9     .12       0
Bank Sta=4980.2,4998.7
XS Rating Curve= 0 ,0
Exp/Cntr=0.3,0.1

Type RM Length L Ch R = 1 ,26224   ,487,487,487
BEGIN DESCRIPTION:
WASP CREEK 42.0
END DESCRIPTION:
XS GIS Cut Line= 3
      2059375.01     13878375.03        2059325.       13878175.
        2058525.     13876975.01
#Sta/Elev= 30
    4798 1313.92  4839.3 1310.18  4849.6 1308.52  4857.3 1304.88  4862.5  1305.2
  4870.2 1299.13  4898.5 1285.64  4934.3 1286.98  4944.9 1286.92  4976.9 1281.16
  4977.4 1280.66  4995.4 1281.16  5001.6 1284.78  5007.2 1284.78  5011.7 1286.74
  5047.8 1286.15  5112.4 1288.05  5171.7 1287.37  5328.7 1287.56  5558.5 1285.12
  5573.6  1285.4  5588.6 1288.05  5660.7 1293.55  5768.9 1297.28  5819.9 1302.25
  6047.1 1308.24  6094.4 1309.59  6201.5 1317.26  6428.8 1324.86  6446.4 1324.77
#Mann= 9 ,-1 , 0
    4798     .07       0  4934.3     .12       0  4976.9     .05       0
  4995.4     .12       0  5171.7    .035       0  5558.5     .12       0
  6047.1     .07       0  6094.4     .12       0  6428.8     .07       0
Bank Sta=4976.9,4995.4
XS Rating Curve= 0 ,0
Exp/Cntr=0.3,0.1

Type RM Length L Ch R = 1 ,25737   ,439,439,439
BEGIN DESCRIPTION:
WASP CREEK 41.0
END DESCRIPTION:
XS GIS Cut Line= 3
        2059775.       13878275.        2059775.       13878075.
      2059666.75     13876718.31
#Sta/Elev= 30
  4795.4  1305.5  4915.4 1298.54  4935.4 1293.57  4955.4 1283.68  4975.4 1280.49
  4992.9 1280.72  5011.1 1278.86  5025.5 1280.56  5045.6 1284.62    5110 1282.49
  5145.9 1281.06  5208.9 1283.64  5647.5 1283.47  5716.7 1281.79  5717.7 1281.67
  5718.5 1278.41    5719 1277.91    5737 1278.41  5737.8 1280.33  5747.8 1283.51
  5878.3 1283.84  5918.3 1284.35  5935.9 1282.61  6000.4 1286.31    6119 1295.94
  6179.1 1304.35  6199.2 1303.84  6249.4 1309.99  6320.1 1313.16  6356.4 1316.68
#Mann= 11 ,-1 , 0
  4795.4     .12       0  4992.9    .035       0  5011.1    .035       0
  5025.5     .07       0    5110     .07       0  5208.9    .035       0
  5716.7     .07       0  5718.5     .05       0    5737     .07       0
  5878.3    .035       0  6000.4     .12       0
Bank Sta=4992.9,5025.5
XS Rating Curve= 0 ,0
Exp/Cntr=0.3,0.1

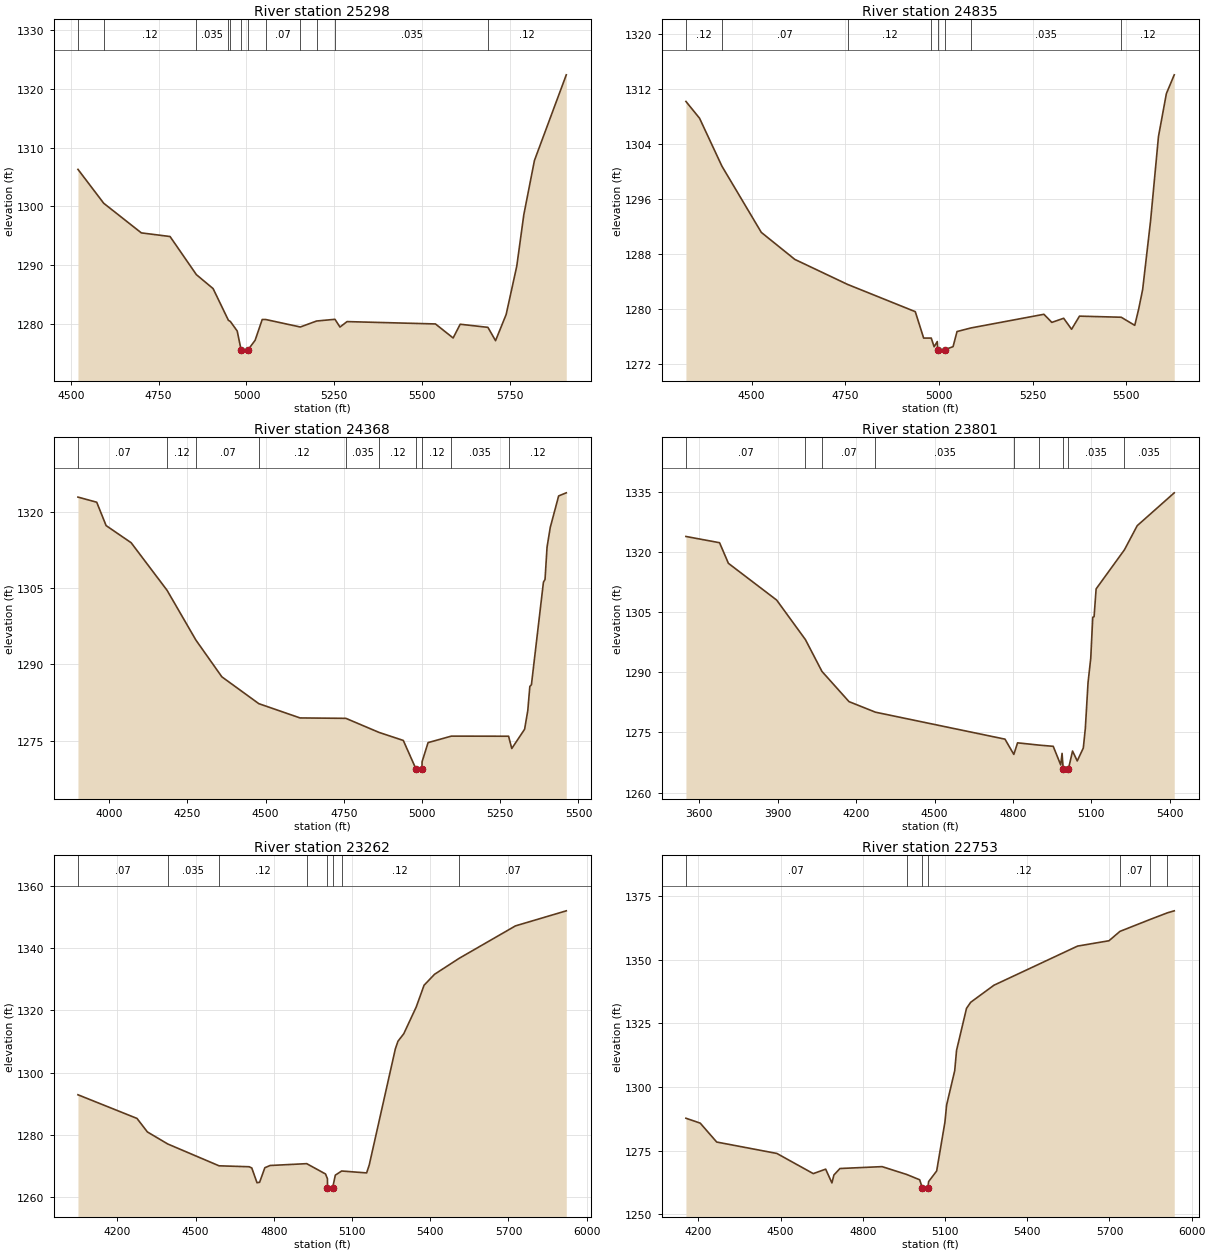
Type RM Length L Ch R = 1 ,25298   ,463,463,463
BEGIN DESCRIPTION:
WASP CREEK 40.0
END DESCRIPTION:
XS GIS Cut Line= 3
      2060244.88     13878294.05        2060125.       13877825.
        2060225.     13876924.96
#Sta/Elev= 30
  4520.5  1306.3  4593.9 1300.52  4700.9 1295.48  4782.6 1294.86  4857.5 1288.37
  4905.1 1285.99  4948.7 1280.59  4954.2 1280.39  4973.7 1278.77    4985  1275.5
  4985.5    1275  5003.7  1275.5  5024.7 1277.19  5044.9 1280.73  5054.6 1280.73
  5153.3 1279.45  5199.7 1280.47  5251.9 1280.76  5266.2 1279.44  5286.3 1280.37
  5537.9 1279.97  5588.2 1277.58  5608.3 1279.92  5687.2 1279.39  5708.9 1277.12
  5739.1 1281.58  5769.3 1289.81  5789.4 1298.59  5819.6 1307.81  5910.2  1322.4
#Mann= 12 ,-1 , 0
  4520.5     .07       0  4593.9     .12       0  4857.5    .035       0
  4948.7     .07       0  4954.2    .035       0    4985    .035       0
  5003.7    .035       0  5054.6     .07       0  5153.3    .035       0
  5199.7     .07       0  5251.9    .035       0  5687.2     .12       0
Bank Sta=4985,5003.7
XS Rating Curve= 0 ,0
Exp/Cntr=0.3,0.1

Type RM Length L Ch R = 1 ,24835   ,467,467,467
BEGIN DESCRIPTION:
WASP CREEK 39.0
END DESCRIPTION:
XS GIS Cut Line= 3
      2060774.98     13878174.97        2060475.       13877575.
      2060275.01     13876975.04
#Sta/Elev= 30
  4324.6 1310.22  4360.9 1307.78  4420.7  1300.8  4525.8 1291.17  4615.3 1287.24
  4755.8 1283.61  4936.7 1279.64    4959  1275.8  4979.3  1275.8    4987 1274.54
  4995.4 1275.29  4996.6 1274.11  4997.1 1273.61  5015.3 1274.11  5037.5 1274.55
  5048.1 1276.75    5085 1277.27    5280 1279.26  5301.1 1278.08  5332.7 1278.68
  5353.8 1277.08  5374.9 1278.99  5486.3 1278.83  5522.4 1277.65    5533 1280.05
  5543.5 1282.87  5564.6 1292.84  5585.7 1305.12  5606.8 1311.36  5627.8 1314.09
#Mann= 8 ,-1 , 0
  4324.6     .12       0  4420.7     .07       0  4755.8     .12       0
  4979.3     .07       0  4996.6     .05       0  5015.3     .07       0
    5085    .035       0  5486.3     .12       0
Bank Sta=4996.6,5015.3
XS Rating Curve= 0 ,0
Exp/Cntr=0.3,0.1

Type RM Length L Ch R = 1 ,24368   ,567,567,567
BEGIN DESCRIPTION:
WASP CREEK 38.0
END DESCRIPTION:
XS GIS Cut Line= 3
        2060825.       13878375.        2060825.       13877275.
        2060725.     13876824.98
#Sta/Elev= 30
    3900 1322.95    3960 1321.94    3990 1317.34    4070 1313.97  4184.9  1304.6
  4276.9 1294.82    4360 1287.57  4478.2 1282.29    4610 1279.48  4756.5  1279.4
  4862.5 1276.63    4940 1275.05    4980 1269.51  4980.5 1269.01  4999.9 1269.51
    5000 1270.85  5019.2 1274.62  5093.6  1275.9  5276.6 1275.88  5286.8 1273.46
  5327.8 1277.26    5338 1280.95  5344.5 1285.68  5349.6 1286.02    5388 1306.21
  5393.1 1306.74  5399.5 1313.08  5409.8 1316.99  5436.6 1323.18    5461 1323.79
#Mann= 10 ,-1 , 0
    3900     .07       0  4184.9     .12       0  4276.9     .07       0
  4478.2     .12       0  4756.5    .035       0  4862.5     .12       0
    4980     .05       0  4999.9     .12       0  5093.6    .035       0
  5276.6     .12       0
Bank Sta=4980,4999.9
XS Rating Curve= 0 ,0
Exp/Cntr=0.3,0.1

Type RM Length L Ch R = 1 ,23801   ,539,539,539
BEGIN DESCRIPTION:
WASP CREEK 37.0
END DESCRIPTION:
XS GIS Cut Line= 3
      2060875.01     13878424.97        2061275.       13877025.
        2061375.       13876625.
#Sta/Elev= 30
  3548.9 1323.91  3677.6 1322.35  3711.4 1317.21    3896 1308.04  4006.1 1298.17
  4069.3 1290.24  4172.9 1282.69    4274 1280.06  4769.6 1273.33  4803.4 1269.52
  4817.7 1272.41  4900.4 1271.84  4954.2 1271.54  4982.8  1266.9    4988 1269.78
  4992.3 1265.85  4992.8 1265.35  5012.3 1265.85  5028.1 1270.36  5046.1  1267.9
  5069.3 1271.12    5077    1276  5087.4 1287.46  5097.7 1293.49  5105.4 1303.74
  5110.5  1303.9  5118.3 1310.83  5226.5 1320.57  5275.5  1326.6  5417.2  1334.8
#Mann= 9 ,-1 , 0
  3548.9     .07       0  4006.1     .12       0  4069.3     .07       0
    4274    .035       0  4803.4     .12       0  4900.4    .035       0
  4992.3    .035       0  5012.3    .035       0  5226.5    .035       0
Bank Sta=4992.3,5012.3
XS Rating Curve= 0 ,0
Exp/Cntr=0.3,0.1

Type RM Length L Ch R = 1 ,23262   ,509,509,509
BEGIN DESCRIPTION:
WASP CREEK 36.0
END DESCRIPTION:
XS GIS Cut Line= 3
      2061737.43     13878071.18        2061775.       13877125.
      2061821.28     13876200.28
#Sta/Elev= 30
  4048.9 1292.92  4275.3 1285.32  4315.3 1280.97  4393.3 1277.11    4590  1270.1
  4705.6  1269.8  4715.6  1269.4  4735.6 1264.67  4745.6 1264.81  4765.6 1269.48
  4785.7  1270.2  4926.2 1270.79  4998.3 1267.48  5005.8 1265.93  5005.9 1263.11
  5006.4 1262.61  5025.9 1263.11  5035.9 1267.09  5060.2 1268.43    5156 1267.82
    5166 1270.37  5266.2 1307.67  5276.2 1310.11  5298.6 1312.54  5346.3 1321.13
  5376.3  1328.1  5416.4 1331.61  5510.4 1336.72  5726.7 1347.16  5921.7    1352
#Mann= 8 ,-1 , 0
  4048.9     .07       0  4393.3    .035       0    4590     .12       0
  4926.2     .07       0  5005.9     .05       0  5025.9     .07       0
  5060.2     .12       0  5510.4     .07       0
Bank Sta=5005.9,5025.9
XS Rating Curve= 0 ,0
Exp/Cntr=0.3,0.1

Type RM Length L Ch R = 1 ,22753   ,559,559,559
BEGIN DESCRIPTION:
WASP CREEK 35.0
END DESCRIPTION:
XS GIS Cut Line= 3
      2061824.99     13877925.02        2062225.       13877175.
      2063008.02     13876669.57
#Sta/Elev= 30
  4154.5 1287.75  4206.6 1285.84  4266.8 1278.41  4486.4 1273.93  4619.2 1266.02
  4664.5 1267.77  4687.2 1262.37  4694.6 1265.48  4716.6 1268.02  4870.3 1268.76
    4960 1265.69  5007.5  1263.6  5017.2 1260.43  5017.7 1259.93  5037.4 1260.43
  5040.2  1262.9  5069.5 1267.05  5099.7 1286.25  5105.8 1292.93  5135.4 1306.43
  5142.1  1314.4  5178.4 1330.87  5193.6 1333.25  5278.3 1339.94  5583.6 1355.31
  5698.4 1357.41  5738.3 1361.08  5848.8 1365.78  5911.4 1368.36  5936.5 1369.15
#Mann= 7 ,-1 , 0
  4154.5     .07       0    4960     .12       0  5017.2     .05       0
  5037.4     .12       0  5738.3     .07       0  5848.8    .035       0
  5911.4     .07       0
Bank Sta=5017.2,5037.4
XS Rating Curve= 0 ,0
Exp/Cntr=0.3,0.1

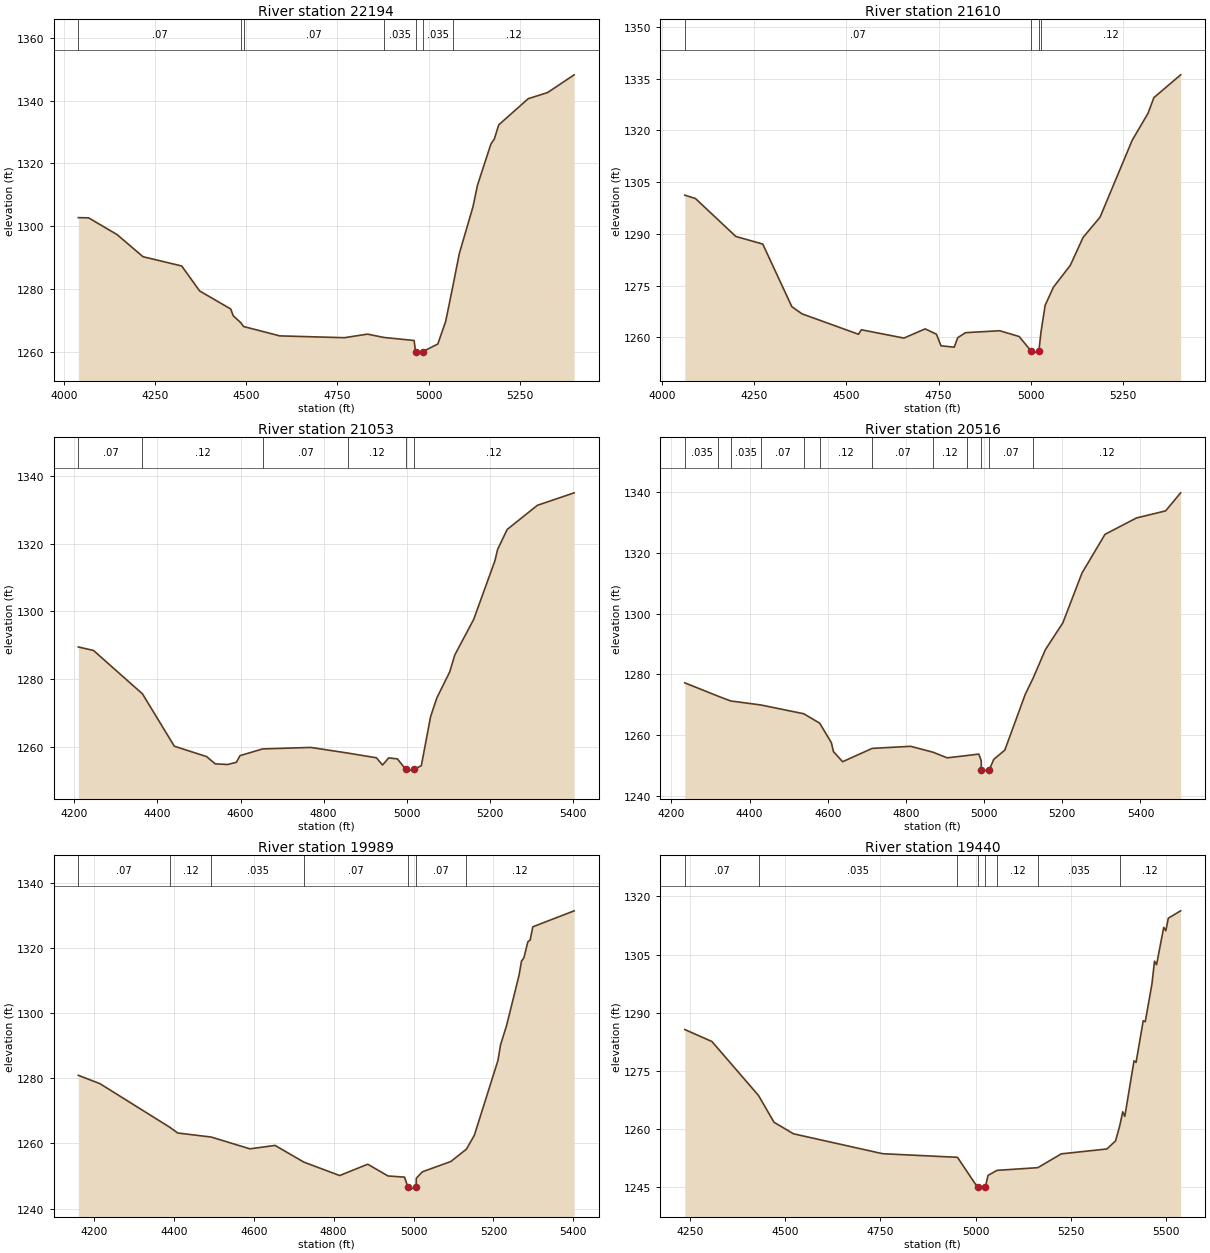
Type RM Length L Ch R = 1 ,22194   ,584,584,584
BEGIN DESCRIPTION:
WASP CREEK 34.0
END DESCRIPTION:
XS GIS Cut Line= 3
      2061874.97     13878325.03        2062525.       13877625.
        2062875.       13877425.
#Sta/Elev= 30
  4040.1  1302.7  4068.2 1302.65  4146.4 1297.29  4217.3 1290.25  4323.3 1287.29
  4372.6 1279.32  4457.7 1273.57  4464.5 1271.41  4485.4 1269.19  4492.8 1267.99
    4592    1265  4768.9 1264.42  4832.4 1265.56  4877.1  1264.5    4960 1263.53
    4964    1260  4964.5  1259.5  4984.2    1260  5024.9  1262.4  5046.5 1269.61
  5067.6 1281.66  5083.9 1291.27  5121.4 1306.21  5133.6 1313.03  5170.3 1326.14
  5179.7 1327.77  5191.9 1332.29  5272.5 1340.63  5325.8  1342.6  5398.5 1348.25
#Mann= 7 ,-1 , 0
  4040.1     .07       0  4485.4    .035       0  4492.8     .07       0
  4877.1    .035       0    4964    .035       0  4984.2    .035       0
  5067.6     .12       0
Bank Sta=4964,4984.2
XS Rating Curve= 0 ,0
Exp/Cntr=0.3,0.1

Type RM Length L Ch R = 1 ,21610   ,557,557,557
BEGIN DESCRIPTION:
WASP CREEK 33.0
END DESCRIPTION:
XS GIS Cut Line= 3
      2062074.98     13878575.01        2062875.       13878075.
      2063074.98     13877725.03
#Sta/Elev= 30
    4061 1301.22  4089.9 1300.25  4199.6 1289.25  4272.7 1287.05  4351.7  1268.9
  4379.4 1266.82  4532.7 1260.91  4540.4 1262.21    4656  1259.8  4713.7 1262.47
  4744.4 1260.92  4756.8 1257.56  4792.7 1257.17  4802.2 1259.91  4823.4 1261.37
    4916 1261.93    4969 1260.26  5002.2 1255.94  5002.7 1255.44  5022.5 1255.94
  5028.2 1261.49  5039.7 1269.32    5062 1274.53  5108.1 1280.92  5142.6 1288.97
  5188.7 1294.84  5275.8 1317.09    5319 1324.94  5334.8 1329.47  5407.5 1336.09
#Mann= 4 ,-1 , 0
    4061     .07       0  5002.2     .05       0  5022.5     .07       0
  5028.2     .12       0
Bank Sta=5002.2,5022.5
XS Rating Curve= 0 ,0
Exp/Cntr=0.3,0.1

Type RM Length L Ch R = 1 ,21053   ,537,537,537
BEGIN DESCRIPTION:
WASP CREEK 32.0
END DESCRIPTION:
XS GIS Cut Line= 3
      2062475.02     13878974.98        2063125.       13878525.
      2063475.04     13878324.98
#Sta/Elev= 30
  4209.5 1289.54    4246 1288.51  4363.9 1275.73  4440.6 1260.31  4518.3 1257.25
  4539.2 1255.11  4568.9 1254.92  4589.9 1255.56  4598.7 1257.53  4653.3 1259.51
    4769 1259.95  4859.1 1258.27  4927.1  1256.9  4941.9 1254.78  4956.8 1256.87
  4977.7 1256.57  4997.8 1253.47  4998.3 1252.97  5018.1 1253.47  5035.3 1254.59
  5057.6 1269.04  5072.7 1274.55  5103.7 1282.23  5115.9  1287.2  5161.3 1297.65
  5212.4  1314.9  5218.9 1318.27  5241.9 1324.14  5314.6 1331.25  5403.2 1334.93
#Mann= 6 ,-1 , 0
  4209.5     .07       0  4363.9     .12       0  4653.3     .07       0
  4859.1     .12       0  4997.8     .05       0  5018.1     .12       0
Bank Sta=4997.8,5018.1
XS Rating Curve= 0 ,0
Exp/Cntr=0.3,0.1

Type RM Length L Ch R = 1 ,20516   ,527,527,527
BEGIN DESCRIPTION:
WASP CREEK 31.0
END DESCRIPTION:
XS GIS Cut Line= 3
      2062678.56     13879281.99        2063375.       13878975.
      2063814.88      13878721.9
#Sta/Elev= 30
  4234.1  1277.2  4320.1 1272.77  4351.3 1271.24  4429.3  1269.9  4538.5 1267.02
  4579.2 1263.93  4609.1  1257.5  4614.5 1254.55  4637.9 1251.23  4713.6 1255.62
  4812.1  1256.3  4869.2 1254.36  4905.4 1252.51  4955.3 1253.25  4986.3 1253.75
  4992.5 1251.56  4992.9 1248.63  4993.4 1248.13  5013.2 1248.63  5024.7 1252.02
  5052.9 1255.05  5105.1  1273.4  5125.1  1278.7  5156.7 1288.14  5201.4 1296.96
  5250.3 1313.34  5309.2  1326.1  5389.7 1331.49  5464.4 1333.83  5502.7 1339.77
#Mann= 12 ,-1 , 0
  4234.1    .035       0  4320.1     .07       0  4351.3    .035       0
  4429.3     .07       0  4538.5    .035       0  4579.2     .12       0
  4713.6     .07       0  4869.2     .12       0  4955.3     .07       0
  4992.9     .05       0  5013.2     .07       0  5125.1     .12       0
Bank Sta=4992.9,5013.2
XS Rating Curve= 0 ,0
Exp/Cntr=0.3,0.1

Type RM Length L Ch R = 1 ,19989   ,549,549,549
BEGIN DESCRIPTION:
WASP CREEK 30.0
END DESCRIPTION:
XS GIS Cut Line= 3
      2062724.96     13879675.01        2063525.       13879425.
      2063874.99     13879225.01
#Sta/Elev= 30
  4160.9 1280.91  4214.9 1278.36  4389.5 1265.01  4409.8 1263.22  4493.8 1261.97
  4590.5 1258.36  4653.4 1259.41  4725.8 1254.27  4815.2 1250.17  4885.4 1253.64
  4936.2 1250.04  4977.6 1249.68  4986.3  1246.5  4986.8    1246  5006.7  1246.5
    5007 1249.33  5022.1 1251.31  5093.4 1254.47  5132.4 1258.25  5152.4 1262.54
  5211.5  1285.5  5217.9 1290.27    5233 1296.18    5264 1311.49  5270.5 1315.99
  5276.2  1316.9  5286.3 1321.88  5292.1  1322.4  5298.6 1326.46  5402.2 1331.37
#Mann= 7 ,-1 , 0
  4160.9     .07       0  4389.5     .12       0  4493.8    .035       0
  4725.8     .07       0  4986.3     .05       0  5006.7     .07       0
  5132.4     .12       0
Bank Sta=4986.3,5006.7
XS Rating Curve= 0 ,0
Exp/Cntr=0.3,0.1

Type RM Length L Ch R = 1 ,19440   ,556,556,556
BEGIN DESCRIPTION:
WASP CREEK 29.0
END DESCRIPTION:
XS GIS Cut Line= 3
      2062625.04     13879775.01        2063375.       13879925.
      2063874.98     13879725.01
#Sta/Elev= 30
  4235.6 1285.64  4306.9 1282.55  4429.4 1268.62  4470.1 1261.72  4521.1 1258.74
  4755.7  1253.6  4952.3 1252.67    5005 1244.96  5005.5 1244.46  5025.5 1244.96
  5032.7    1248  5056.1  1249.3  5163.6    1250  5225.2 1253.56  5345.1 1254.82
  5367.9 1256.92  5378.5 1260.68  5386.8 1264.41  5392.2 1263.23  5416.4 1277.57
  5421.8 1277.16  5440.6 1287.92    5446 1287.66  5463.5  1297.4  5470.3 1303.28
  5475.6 1302.36  5494.5 1312.01  5499.9 1311.13  5506.6 1314.37  5538.9 1316.27
#Mann= 8 ,-1 , 0
  4235.6     .07       0  4429.4    .035       0  4952.3     .07       0
    5005     .05       0  5025.5     .07       0  5056.1     .12       0
  5163.6    .035       0  5378.5     .12       0
Bank Sta=5005,5025.5
XS Rating Curve= 0 ,0
Exp/Cntr=0.3,0.1