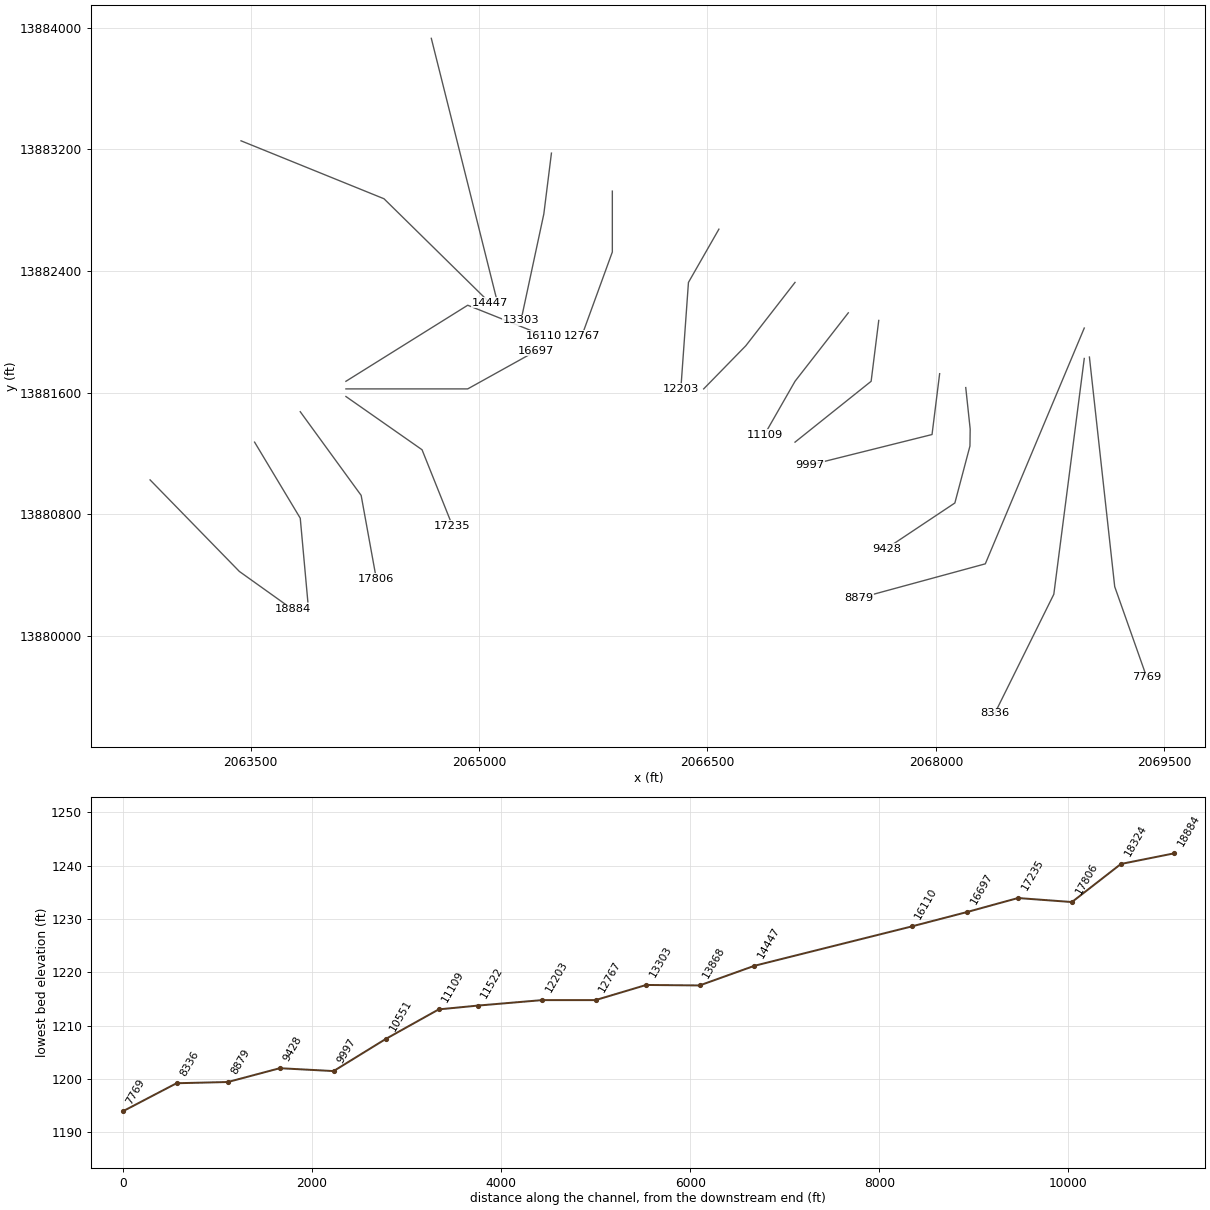
HEC-RAS study WASP CREEK.prj: WASP CREEK Base Level Engineering

--- WASP CREEK.g01 (geometry) --- (continued)

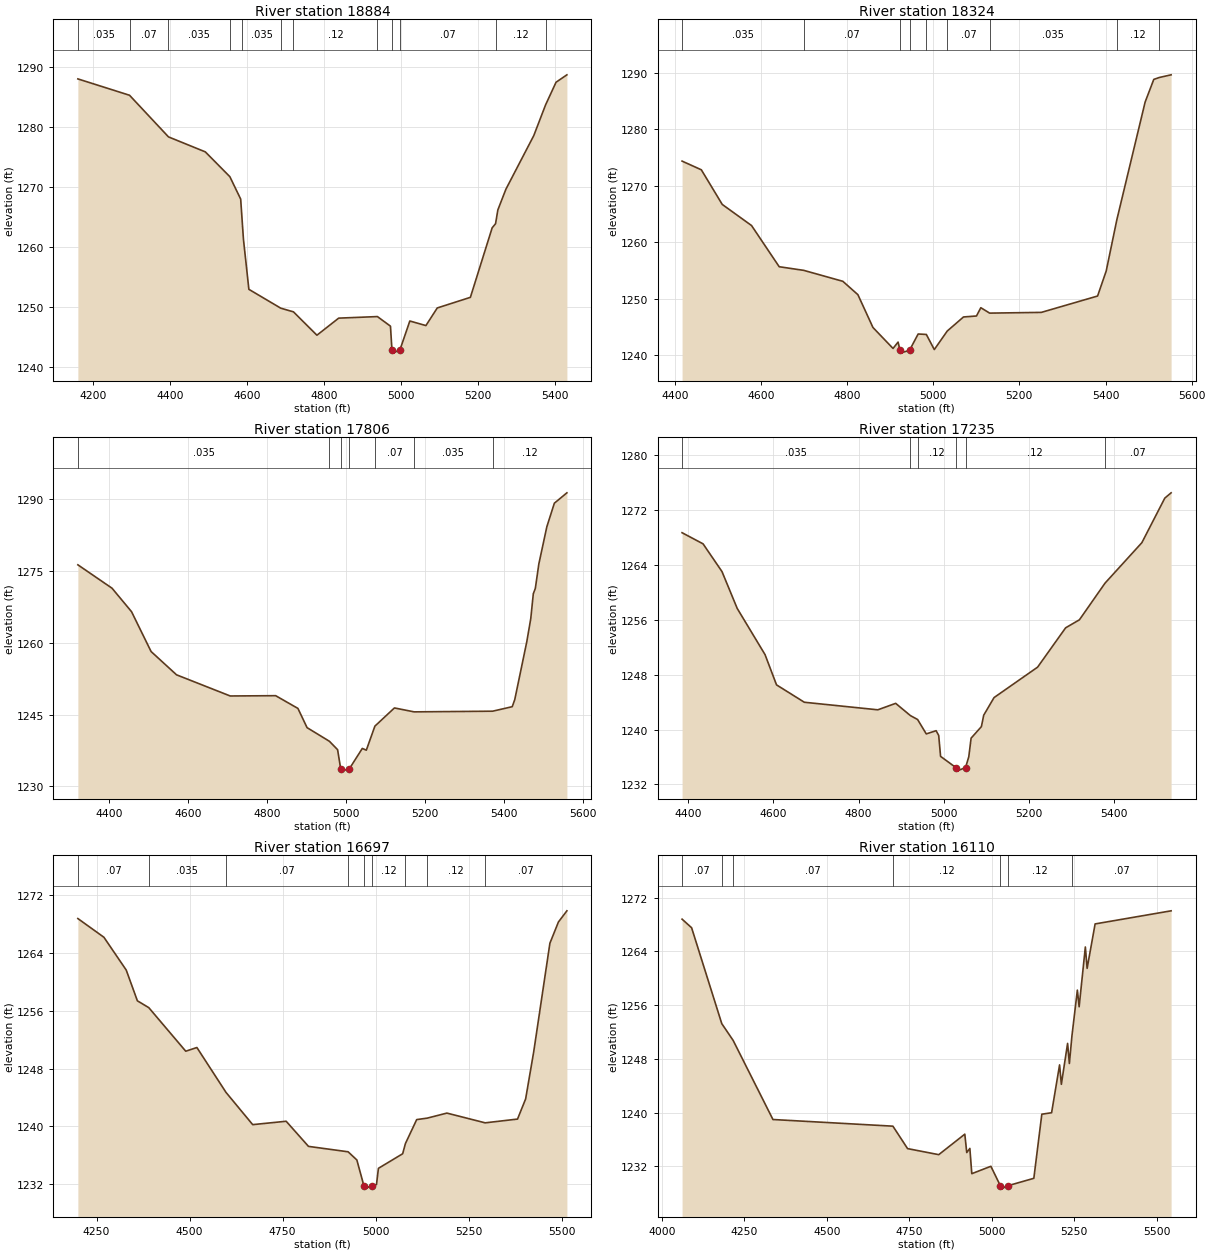
Type RM Length L Ch R = 1 ,18884   ,560,560,560
BEGIN DESCRIPTION:
WASP CREEK 28.0
END DESCRIPTION:
XS GIS Cut Line= 3
       2062838.6     13881026.75        2063425.       13880425.
      2063774.97     13880175.02
#Sta/Elev= 30
    4160 1288.08  4294.2 1285.35  4395.4  1278.4  4491.1  1275.9  4554.8 1271.76
  4582.9 1268.02  4586.6 1264.58  4590.1 1261.32  4604.2 1252.96  4687.1 1249.81
    4720  1249.2    4781  1245.3  4837.5 1248.15  4938.1 1248.41    4972 1246.81
  4975.9 1242.81  4976.4 1242.31  4996.4 1242.81  5022.3 1247.67  5064.1 1246.91
  5093.6 1249.85  5179.6 1251.62  5236.2 1263.23    5245 1263.91  5250.9  1266.2
  5271.8 1269.66  5344.3 1278.62  5374.9 1283.74  5402.1 1287.52  5430.3 1288.76
#Mann= 12 ,-1 , 0
    4160    .035       0  4294.2     .07       0  4395.4    .035       0
  4554.8     .07       0  4586.6    .035       0  4687.1     .07       0
    4720     .12       0  4938.1     .07       0  4975.9     .05       0
  4996.4     .07       0    5245     .12       0  5374.9     .07       0
Bank Sta=4975.9,4996.4
XS Rating Curve= 0 ,0
Exp/Cntr=0.3,0.1

Type RM Length L Ch R = 1 ,18324   ,518,518,518
BEGIN DESCRIPTION:
WASP CREEK 27.0
END DESCRIPTION:
XS GIS Cut Line= 3
        2063525.       13881275.        2063825.       13880775.
        2063875.     13880224.97
#Sta/Elev= 30
  4416.9 1274.36  4461.6 1272.82  4510.2 1266.68  4578.2 1262.94  4642.4 1255.64
  4699.3    1255  4790.1 1253.06  4825.1 1250.69  4860.1 1244.87  4906.7 1241.16
  4918.4 1242.29  4922.9 1240.83  4923.4 1240.33    4945 1240.83    4965 1243.72
    4984 1243.64  5002.5 1240.96  5032.5 1244.24  5070.3 1246.74  5100.4 1246.91
  5110.5 1248.38    5131 1247.42    5251 1247.55  5381.6 1250.45  5401.6 1254.88
  5426.5 1264.03    5492 1284.83  5512.1 1288.84    5525 1289.18  5552.3 1289.65
#Mann= 9 ,-1 , 0
  4416.9    .035       0  4699.3     .07       0  4922.9     .05       0
    4945     .07       0    4984     .12       0  5032.5     .07       0
    5131    .035       0  5426.5     .12       0    5525    .035       0
Bank Sta=4922.9,4945
XS Rating Curve= 0 ,0
Exp/Cntr=0.3,0.1

Type RM Length L Ch R = 1 ,17806   ,571,571,571
BEGIN DESCRIPTION:
WASP CREEK 26.0
END DESCRIPTION:
XS GIS Cut Line= 3
      2063824.99     13881475.01        2064225.       13880925.
        2064325.     13880375.01
#Sta/Elev= 30
  4320.3 1276.29  4406.9  1271.4  4456.3  1266.5  4505.8 1258.18  4570.3 1253.31
  4706.3 1248.89  4821.5 1248.95  4877.9 1246.29  4901.1 1242.27  4957.6 1239.43
  4978.4 1237.67  4986.2 1233.69  4986.7 1233.19  5008.3 1233.69    5041 1237.93
  5051.2 1237.57  5072.9 1242.59  5122.4 1246.39  5172.3 1245.57  5371.2 1245.71
  5420.9 1246.65  5427.3 1248.13  5457.8 1260.23  5467.9 1265.08  5474.3 1270.26
  5479.4 1271.35  5488.3 1276.47  5508.6 1284.25  5527.6 1289.16  5559.4 1291.33
#Mann= 7 ,-1 , 0
  4320.3    .035       0  4957.6     .12       0  4986.2     .05       0
  5008.3     .12       0  5072.9     .07       0  5172.3    .035       0
  5371.2     .12       0
Bank Sta=4986.2,5008.3
XS Rating Curve= 0 ,0
Exp/Cntr=0.3,0.1

Type RM Length L Ch R = 1 ,17235   ,538,538,538
BEGIN DESCRIPTION:
WASP CREEK 25.0
END DESCRIPTION:
XS GIS Cut Line= 3
      2064124.98     13881575.01        2064625.       13881225.
      2064825.01     13880724.97
#Sta/Elev= 30
  4385.5 1268.66  4434.8 1267.04  4479.3    1263    4515 1257.64  4580.4 1250.91
  4607.4  1246.5  4672.8 1243.97  4845.4 1242.87  4887.3 1243.81  4922.1 1242.02
  4938.8 1241.46  4959.2 1239.36  4982.3 1239.83  4988.4 1239.14  4992.8 1236.09
  5029.2 1234.44  5029.7 1233.94  5051.4 1234.44  5059.1 1236.04  5064.5 1238.74
  5088.7 1240.42  5094.1 1242.08  5118.4 1244.65  5220.7 1249.08  5286.6 1254.81
    5319 1255.98  5379.2 1261.32  5465.7 1267.21  5519.6  1273.7  5534.4 1274.47
#Mann= 6 ,-1 , 0
  4385.5    .035       0  4922.1     .07       0  4938.8     .12       0
  5029.2     .05       0  5051.4     .12       0  5379.2     .07       0
Bank Sta=5029.2,5051.4
XS Rating Curve= 0 ,0
Exp/Cntr=0.3,0.1

Type RM Length L Ch R = 1 ,16697   ,587,587,587
BEGIN DESCRIPTION:
WASP CREEK 24.0
END DESCRIPTION:
XS GIS Cut Line= 3
      2064125.05       13881625.        2064925.       13881625.
      2065374.97     13881874.98
#Sta/Elev= 30
  4199.6 1268.79  4269.6  1266.2  4329.6 1261.66  4359.6  1257.4  4390.3 1256.45
  4489.6 1250.42  4519.6 1250.93  4597.8 1244.72  4669.6 1240.25  4759.6 1240.72
  4819.6 1237.24  4926.1 1236.49  4949.6 1235.36  4968.4 1231.82  4968.9 1231.32
  4990.7 1231.82  5002.4 1231.95  5007.6  1234.2  5072.8 1236.22  5080.1 1237.62
  5110.5 1240.95  5138.7 1241.15  5191.7 1241.85  5294.6  1240.5  5381.6 1241.02
  5403.4 1243.82  5425.1 1250.34  5468.6 1265.37  5491.5 1268.31  5514.3 1269.86
#Mann= 9 ,-1 , 0
  4199.6     .07       0  4390.3    .035       0  4597.8     .07       0
  4926.1     .12       0  4968.4     .05       0  4990.7     .12       0
  5080.1     .07       0  5138.7     .12       0  5294.6     .07       0
Bank Sta=4968.4,4990.7
XS Rating Curve= 0 ,0
Exp/Cntr=0.3,0.1

Type RM Length L Ch R = 1 ,16110   ,1663,1663,1663
BEGIN DESCRIPTION:
WASP CREEK 23.0
END DESCRIPTION:
XS GIS Cut Line= 3
      2064124.96     13881674.98        2064925.       13882175.
      2065425.04     13881974.99
#Sta/Elev= 30
  4061.2 1268.79  4090.1 1267.51  4181.5 1253.24  4215.9 1250.75  4336.6 1238.97
  4700.1 1237.98  4744.6 1234.64    4839 1233.74    4918 1236.79  4923.9 1234.05
  4933.3 1234.67  4939.2 1230.91    4997 1232.01  5025.8 1229.11  5026.3 1228.61
  5048.1 1229.11  5127.2 1230.22  5151.4 1239.76    5181 1239.98  5205.2  1247.1
  5210.6 1244.21  5229.5  1250.3  5234.9 1247.31  5242.7 1251.43  5259.1 1258.23
  5264.5 1255.75  5283.3 1264.65  5288.7 1261.47  5312.9 1268.08  5543.2 1270.03
#Mann= 7 ,-1 , 0
  4061.2     .07       0  4181.5     .12       0  4215.9     .07       0
  4700.1     .12       0  5025.8     .05       0  5048.1     .12       0
  5242.7     .07       0
Bank Sta=5025.8,5048.1
XS Rating Curve= 0 ,0
Exp/Cntr=0.3,0.1

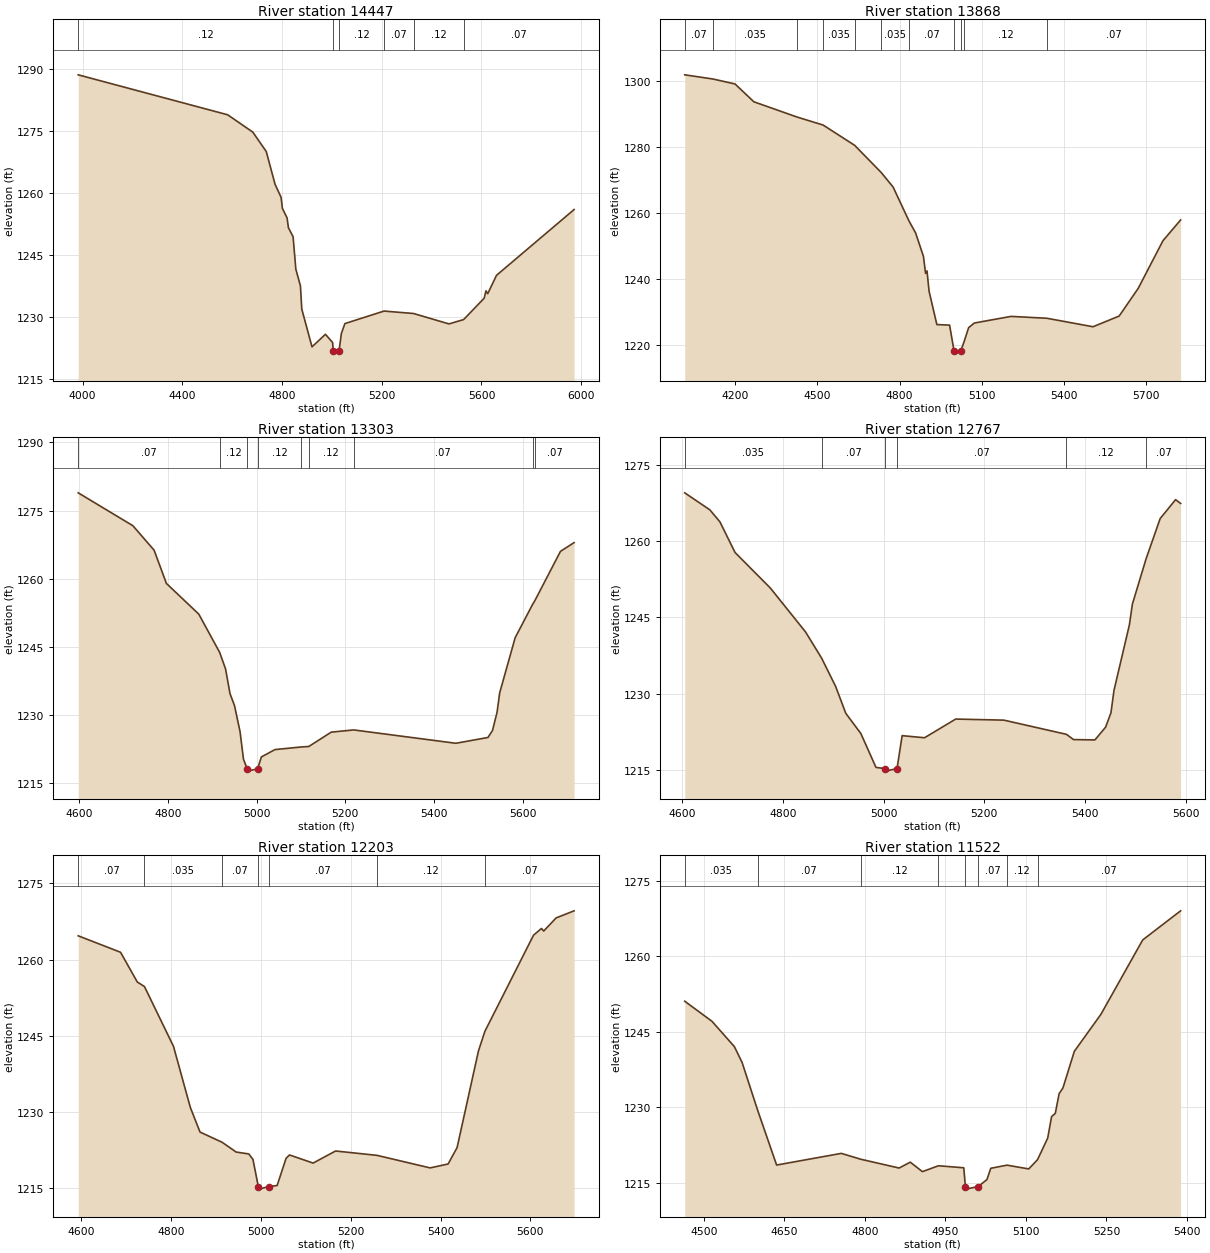
Type RM Length L Ch R = 1 ,14447   ,579,579,579
BEGIN DESCRIPTION:
WASP CREEK 22.0
END DESCRIPTION:
XS GIS Cut Line= 3
      2063435.88     13883255.87        2064375.       13882875.
      2065070.62     13882190.55
#Sta/Elev= 30
  3982.3 1288.66  4581.8 1278.98  4682.8 1274.78  4736.7 1270.08    4772 1262.13
  4796.1 1258.99  4801.5 1256.29  4820.2 1253.99  4825.6 1251.61  4844.3 1249.43
  4855.4 1241.56  4873.8 1237.53  4879.2  1231.9  4920.2 1222.75  4974.1 1225.79
  5002.8 1223.81  5005.4 1221.73  5005.9 1221.23  5028.5 1221.73  5038.1 1226.01
  5052.2 1228.39  5209.2 1231.42  5327.7 1230.83  5469.5 1228.31  5528.5 1229.36
    5611 1234.54    5618 1236.32  5625.1 1235.63  5660.4 1240.08  5971.6 1256.02
#Mann= 6 ,-1 , 0
  3982.3     .12       0  5005.4     .05       0  5028.5     .12       0
  5209.2     .07       0  5327.7     .12       0  5528.5     .07       0
Bank Sta=5005.4,5028.5
XS Rating Curve= 0 ,0
Exp/Cntr=0.3,0.1

Type RM Length L Ch R = 1 ,13868   ,565,565,565
BEGIN DESCRIPTION:
WASP CREEK 21.0
END DESCRIPTION:
XS GIS Cut Line= 3
      2064685.86     13883929.49        2064925.       13882975.
        2065125.     13882175.02
#Sta/Elev= 30
  4016.4 1301.78  4118.9 1300.52  4199.7 1299.02  4268.5 1293.62  4425.8 1289.01
  4521.1 1286.58  4636.2 1280.44  4733.5 1272.17  4776.4 1267.81  4834.1 1257.59
  4858.8 1253.86    4887 1246.84  4894.8 1241.69    4900 1242.44  4907.6 1236.26
    4936 1226.19  4982.4 1226.03    4999 1218.05  4999.5 1217.55  5022.5 1218.05
  5035.4 1221.05  5051.9 1225.27  5072.6 1226.66  5206.6 1228.67  5337.3  1228.1
  5505.5 1225.53  5600.8 1228.77  5670.4 1237.16  5760.6 1251.57    5825 1257.86
#Mann= 11 ,-1 , 0
  4016.4     .07       0  4118.9    .035       0  4425.8     .07       0
  4521.1    .035       0  4636.2     .07       0  4733.5    .035       0
  4834.1     .07       0    4999     .05       0  5022.5     .07       0
  5035.4     .12       0  5337.3     .07       0
Bank Sta=4999,5022.5
XS Rating Curve= 0 ,0
Exp/Cntr=0.3,0.1

Type RM Length L Ch R = 1 ,13303   ,536,536,536
BEGIN DESCRIPTION:
WASP CREEK 20.0
END DESCRIPTION:
XS GIS Cut Line= 3
        2065475.     13883174.98        2065425.       13882775.
        2065275.     13882074.98
#Sta/Elev= 30
  4597.2  1278.9  4720.6 1271.66  4768.5 1266.27  4796.2 1258.96  4869.3  1252.2
  4916.4 1243.78  4929.7 1240.14  4939.8 1234.68  4949.9 1232.07  4962.5 1226.28
  4970.1 1220.29  4978.4 1218.14  4978.9 1217.64    5002 1218.14  5010.5 1220.76
  5041.2 1222.38  5100.8 1222.96  5117.5 1223.06  5168.2 1226.22  5218.8 1226.71
  5449.4 1223.77  5521.9 1225.05  5532.1 1226.59  5542.3 1230.56  5548.3 1234.88
  5583.2    1247  5622.5 1254.33  5627.7 1255.17  5685.5 1266.02  5716.2 1267.94
#Mann= 9 ,-1 , 0
  4597.2     .07       0  4916.4     .12       0  4978.4     .05       0
    5002     .12       0  5100.8     .07       0  5117.5     .12       0
  5218.8     .07       0  5622.5     .12       0  5627.7     .07       0
Bank Sta=4978.4,5002
XS Rating Curve= 0 ,0
Exp/Cntr=0.3,0.1

Type RM Length L Ch R = 1 ,12767   ,564,564,564
BEGIN DESCRIPTION:
WASP CREEK 19.0
END DESCRIPTION:
XS GIS Cut Line= 3
        2065875.     13882925.04        2065875.       13882525.
      2065674.99     13881974.98
#Sta/Elev= 30
    4605 1269.49    4655 1266.14    4675 1263.77    4705 1257.76    4775 1250.79
    4845 1242.16  4877.1 1236.98    4905 1231.41    4925 1226.16    4955 1222.18
    4985 1215.53  5003.2  1215.3  5003.7  1214.8  5026.8  1215.3    5037 1221.77
  5081.5 1221.36  5143.4 1225.03  5239.1 1224.82  5363.5 1222.03  5377.5    1221
    5420 1220.93  5441.3 1223.45  5451.9 1226.27  5457.9 1230.67  5488.5 1243.54
  5494.5 1247.63  5521.8 1256.56  5549.7 1264.44  5580.3 1268.15  5590.3 1267.41
#Mann= 6 ,-1 , 0
    4605    .035       0  4877.1     .07       0  5003.2     .05       0
  5026.8     .07       0  5363.5     .12       0  5521.8     .07       0
Bank Sta=5003.2,5026.8
XS Rating Curve= 0 ,0
Exp/Cntr=0.3,0.1

Type RM Length L Ch R = 1 ,12203   ,681,681,681
BEGIN DESCRIPTION:
WASP CREEK 18.0
END DESCRIPTION:
XS GIS Cut Line= 3
      2066574.99     13882674.98        2066375.       13882325.
        2066325.     13881624.98
#Sta/Elev= 30
  4592.7 1264.69    4687 1261.45  4724.4 1255.59  4740.3  1254.7    4805 1242.92
  4842.5  1230.9  4864.1 1226.04  4913.3 1224.03  4944.7  1222.1  4972.8 1221.73
  4982.1 1220.64    4994  1215.3  4994.5  1214.8  5017.6  1215.3  5035.9 1215.51
  5055.9 1220.88  5063.5 1221.53  5116.1 1219.93  5166.2 1222.31  5258.5 1221.45
  5376.8 1218.98  5416.9 1219.75  5436.9 1222.98  5484.5 1242.01  5498.9 1245.89
  5607.3 1264.82  5624.9 1266.13  5629.9 1265.63  5657.5 1268.21  5697.6 1269.61
#Mann= 7 ,-1 , 0
  4592.7     .07       0  4740.3    .035       0  4913.3     .07       0
    4994     .05       0  5017.6     .07       0  5258.5     .12       0
  5498.9     .07       0
Bank Sta=4994,5017.6
XS Rating Curve= 0 ,0
Exp/Cntr=0.3,0.1

Type RM Length L Ch R = 1 ,11522   ,413,413,413
BEGIN DESCRIPTION:
WASP CREEK 17.0
END DESCRIPTION:
XS GIS Cut Line= 3
      2067075.02     13882325.03      2066751.83     13881908.66
      2066475.03     13881625.03
#Sta/Elev= 30
  4464.7 1251.09  4515.4  1247.1  4557.1 1242.08  4571.5 1238.93  4600.6  1229.4
  4635.8 1218.55  4756.2 1220.87  4792.7  1219.7  4863.9 1217.96  4884.7 1219.12
  4907.3 1217.24  4937.1 1218.41  4984.3 1218.01  4987.3 1214.27  4987.8 1213.77
    5011 1214.27  5027.4 1215.66  5034.6 1217.91  5064.8 1218.53  5105.3 1217.78
  5121.7 1219.63  5140.6 1223.91  5147.8 1228.17  5154.7 1228.81  5161.9 1232.74
  5168.9 1233.84  5190.2 1241.14  5239.6 1248.47  5317.5 1263.26  5388.1 1269.04
#Mann= 8 ,-1 , 0
  4464.7    .035       0  4600.6     .07       0  4792.7     .12       0
  4937.1     .07       0  4987.3     .05       0    5011     .07       0
  5064.8     .12       0  5121.7     .07       0
Bank Sta=4987.3,5011
XS Rating Curve= 0 ,0
Exp/Cntr=0.3,0.1

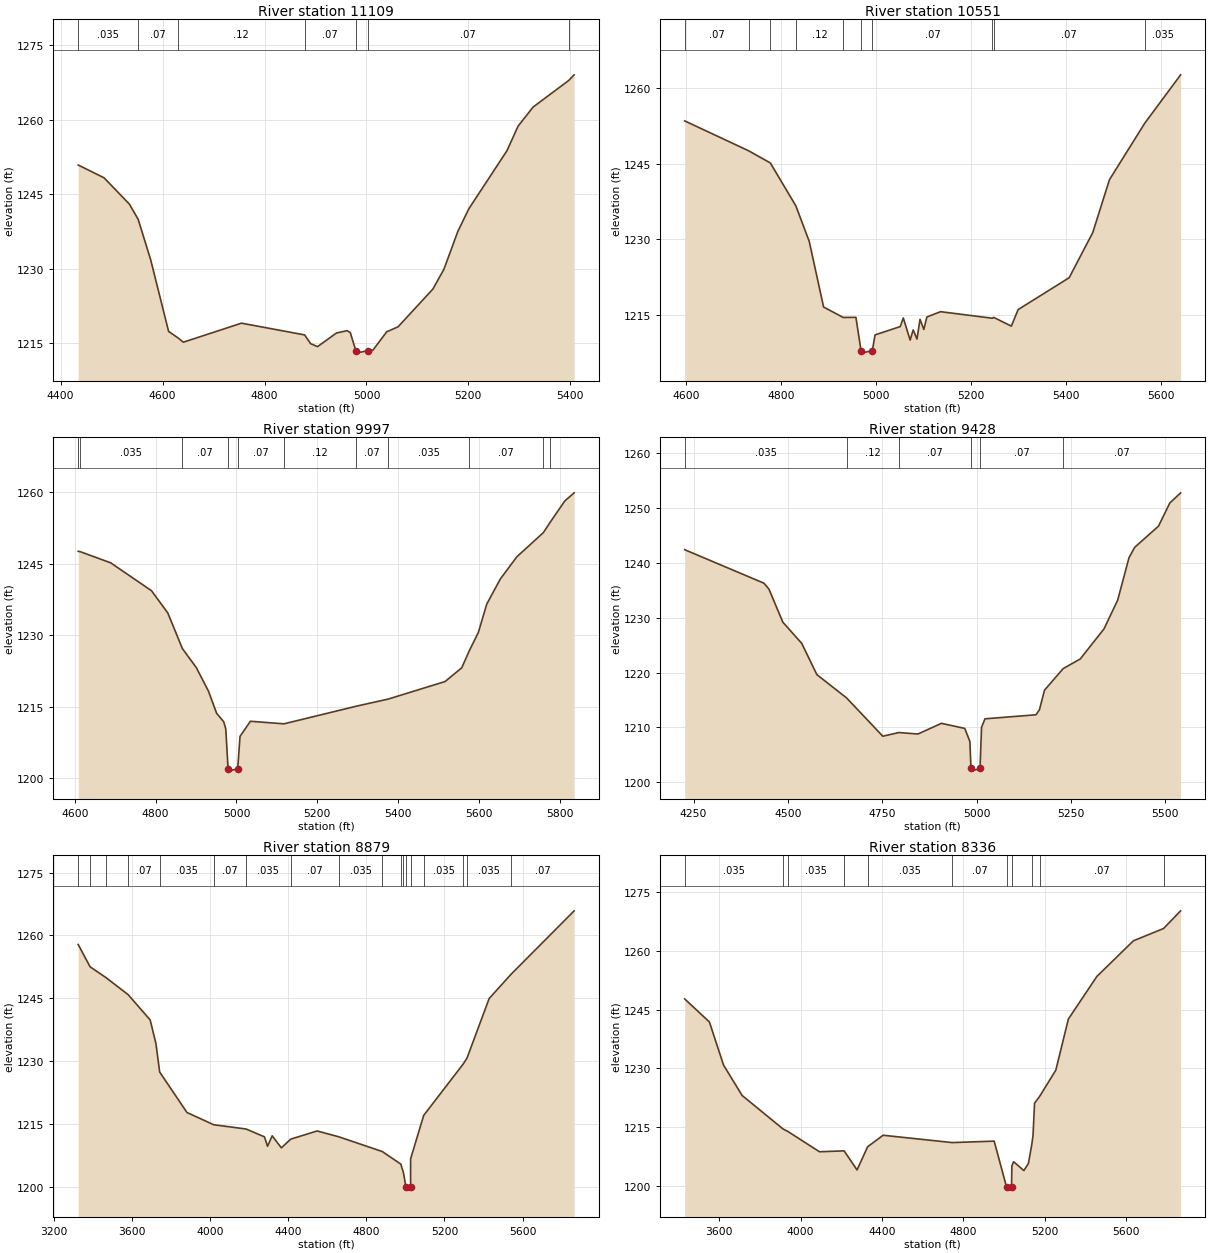
Type RM Length L Ch R = 1 ,11109   ,558,558,558
BEGIN DESCRIPTION:
WASP CREEK 16.0
END DESCRIPTION:
XS GIS Cut Line= 3
      2067425.01     13882125.01        2067075.       13881675.
      2066875.01     13881325.01
#Sta/Elev= 30
  4434.4 1250.92  4485.1 1248.35  4534.9 1243.04  4552.1 1239.98  4576.5 1231.89
  4611.8 1217.43  4630.4 1216.11  4640.7 1215.26  4754.8 1219.09  4878.6 1216.73
  4890.5 1214.96  4904.1 1214.37  4941.2 1217.11    4962 1217.58  4968.3  1217.2
  4979.1 1213.56  4979.6 1213.06  5002.8 1213.56  5012.4 1213.62  5039.8 1217.35
  5062.1 1218.36  5130.5 1225.97  5152.1 1229.95  5179.4 1237.56    5201 1242.12
  5275.9 1253.82  5297.5 1258.73    5327 1262.58  5396.8 1267.92  5407.6 1269.07
#Mann= 7 ,-1 , 0
  4434.4    .035       0  4552.1     .07       0  4630.4     .12       0
  4878.6     .07       0  4979.1     .05       0  5002.8     .07       0
  5396.8    .035       0
Bank Sta=4979.1,5002.8
XS Rating Curve= 0 ,0
Exp/Cntr=0.3,0.1

Type RM Length L Ch R = 1 ,10551   ,554,554,554
BEGIN DESCRIPTION:
WASP CREEK 15.0
END DESCRIPTION:
XS GIS Cut Line= 3
      2067625.01     13882075.04        2067575.       13881675.
      2067074.97     13881274.98
#Sta/Elev= 30
  4597.7 1253.43  4732.1 1247.53  4777.9 1245.12  4831.7 1236.63  4859.8 1229.61
    4890 1216.65  4931.2 1214.59    4958 1214.61  4968.8 1208.04  4969.3 1207.54
  4992.5 1208.04  4998.3 1211.14  5051.3 1212.79  5057.7 1214.49  5072.1 1210.12
  5078.5 1212.13  5086.5 1210.32  5092.9 1214.22  5100.9 1212.21  5107.3 1214.68
  5136.1 1215.73  5245.3 1214.43  5247.7 1214.61    5285 1212.88  5299.4 1216.15
  5406.7 1222.44  5456.3 1231.35  5491.5 1241.81  5565.7 1252.96  5641.2 1262.53
#Mann= 10 ,-1 , 0
  4597.7     .07       0  4732.1    .035       0  4777.9     .07       0
  4831.7     .12       0  4931.2     .07       0  4968.8     .05       0
  4992.5     .07       0  5245.3     .12       0  5247.7     .07       0
  5565.7    .035       0
Bank Sta=4968.8,4992.5
XS Rating Curve= 0 ,0
Exp/Cntr=0.3,0.1

Type RM Length L Ch R = 1 ,9997    ,569,569,569
BEGIN DESCRIPTION:
WASP CREEK 14.0
END DESCRIPTION:
XS GIS Cut Line= 3
        2068025.     13881724.99        2067975.       13881325.
      2067175.02     13881125.01
#Sta/Elev= 30
  4608.3  1247.6  4613.6 1247.51  4688.9 1245.17  4789.7 1239.33    4830 1234.68
  4866.2 1227.19  4900.5 1223.23  4930.8 1218.26  4950.9 1213.63  4968.6 1211.83
  4973.6 1210.31  4979.3 1201.99  4979.8 1201.49  5003.1 1201.99  5008.9 1208.78
  5034.6 1211.95  5117.6 1211.41  5296.8 1215.11  5375.7  1216.6  5516.5 1220.28
  5557.7 1223.16  5575.7  1226.6  5598.9 1230.59  5619.6 1236.51  5653.1 1241.77
  5694.3 1246.46  5759.6  1251.5  5777.4 1253.78  5812.8 1258.15    5836 1259.86
#Mann= 11 ,-1 , 0
  4608.3     .07       0  4613.6    .035       0  4866.2     .07       0
  4979.3     .05       0  5003.1     .07       0  5117.6     .12       0
  5296.8     .07       0  5375.7    .035       0  5575.7     .07       0
  5759.6    .035       0  5777.4     .07       0
Bank Sta=4979.3,5003.1
XS Rating Curve= 0 ,0
Exp/Cntr=0.3,0.1

Type RM Length L Ch R = 1 ,9428    ,549,549,549
BEGIN DESCRIPTION:
WASP CREEK 13.0
END DESCRIPTION:
XS GIS Cut Line= 5
       2068196.5     13881633.67       2068225.6     13881360.94
       2068224.1      13881249.4        2068125.       13880875.
      2067674.97     13880574.98
#Sta/Elev= 30
  4226.6 1242.38  4436.5 1236.28  4449.8 1235.21  4486.7 1229.17  4536.8  1225.3
  4576.8 1219.62  4655.6 1215.37  4751.5 1208.39    4794 1209.06  4844.6 1208.79
  4906.9 1210.74  4968.7 1209.81  4982.2 1207.44  4985.2 1202.53  4985.7 1202.03
  5009.1 1202.53  5013.2 1210.03  5022.3 1211.56  5157.5  1212.3  5166.5 1213.21
    5180 1216.78  5229.4 1220.71  5274.7 1222.47  5337.7 1227.96  5373.8 1233.18
  5403.8 1240.91  5418.9 1242.81    5482 1246.67    5512 1250.89  5540.6 1252.74
#Mann= 6 ,-1 , 0
  4226.6    .035       0  4655.6     .12       0    4794     .07       0
  4985.2    .035       0  5009.1     .07       0  5229.4     .07       0
Bank Sta=4985.2,5009.1
XS Rating Curve= 0 ,0
Exp/Cntr=0.3,0.1

Type RM Length L Ch R = 1 ,8879    ,543,543,543
BEGIN DESCRIPTION:
WASP CREEK 12.0
END DESCRIPTION:
XS GIS Cut Line= 3
        2068975.       13882025.        2068325.       13880475.
       2067494.9     13880248.94
#Sta/Elev= 30
  3323.5 1257.82  3384.5  1252.5  3465.6 1249.93  3579.3 1245.86  3692.2 1239.82
  3721.8 1234.17  3740.9 1227.39  3880.7 1217.73  4018.1  1214.8  4183.5 1213.79
  4277.7 1211.92  4293.6 1209.67  4317.4 1212.16  4364.5 1209.29  4412.7 1211.38
  4547.6 1213.32  4659.4 1211.92  4881.7 1208.41  4976.4 1205.41  4989.8 1203.37
  5002.7 1199.94  5003.2 1199.44  5026.6 1199.94  5026.7 1206.67  5093.6 1217.03
  5296.2  1229.3  5315.9 1230.75  5429.2 1244.94  5540.3 1250.67  5864.6 1265.86
#Mann= 18 ,-1 , 0
  3323.5    .035       0  3384.5     .07       0  3465.6    .035       0
  3579.3     .07       0  3740.9    .035       0  4018.1     .07       0
  4183.5    .035       0  4412.7     .07       0  4659.4    .035       0
  4881.7     .12       0  4976.4    .035       0  4989.8     .07       0
  5002.7     .05       0  5026.6     .07       0  5093.6    .035       0
  5296.2     .07       0  5315.9    .035       0  5540.3     .07       0
Bank Sta=5002.7,5026.6
XS Rating Curve= 0 ,0
Exp/Cntr=0.3,0.1

Type RM Length L Ch R = 1 ,8336    ,567,567,567
BEGIN DESCRIPTION:
WASP CREEK 11.0
END DESCRIPTION:
XS GIS Cut Line= 3
        2068975.     13881824.97        2068775.       13880275.
      2068387.24     13879491.97
#Sta/Elev= 30
  3430.8 1247.72  3552.4 1241.83  3621.7 1230.85  3713.1 1223.09  3914.4 1214.54
  3937.4 1213.93  4093.1 1208.74  4214.2 1208.97  4277.7  1204.1  4329.6 1210.01
  4405.7 1212.95  4744.9 1211.08  4951.4 1211.45  5012.4 1199.71  5012.9 1199.21
  5036.6 1199.71  5038.3 1205.11  5046.9  1206.2  5097.3 1203.94  5119.7 1205.78
  5136.1 1210.58  5142.2 1212.85  5149.8 1221.13  5175.4 1222.91  5254.3 1229.56
    5316 1242.59  5456.1 1253.46  5635.5 1262.54  5783.6 1265.67  5867.4 1270.18
#Mann= 11 ,-1 , 0
  3430.8    .035       0  3914.4     .07       0  3937.4    .035       0
  4214.2     .07       0  4329.6    .035       0  4744.9     .07       0
  5012.4     .05       0  5036.6     .07       0  5136.1    .035       0
  5175.4     .07       0  5783.6    .035       0
Bank Sta=5012.4,5036.6
XS Rating Curve= 0 ,0
Exp/Cntr=0.3,0.1

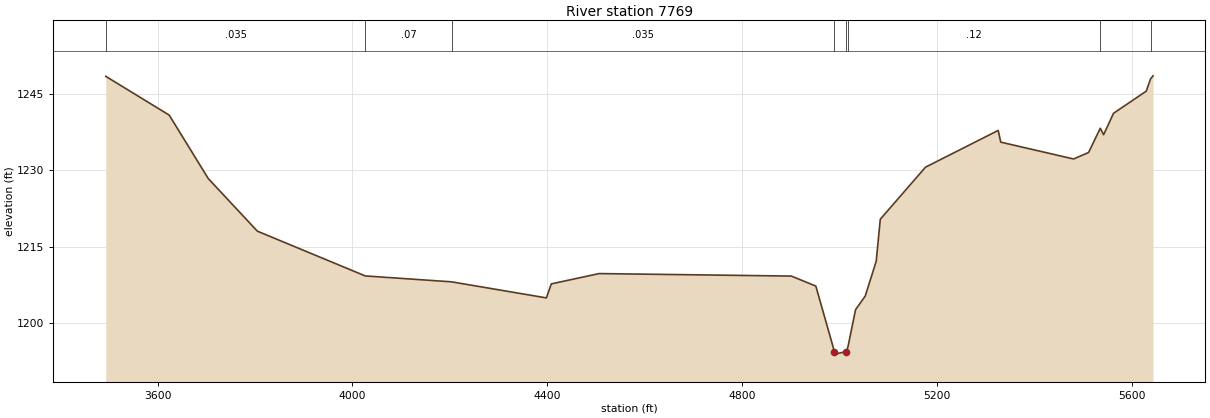
Type RM Length L Ch R = 1 ,7769    ,1195,1195,1195
BEGIN DESCRIPTION:
WASP CREEK 10.0
END DESCRIPTION:
XS GIS Cut Line= 3
      2069008.86     13881834.39        2069175.       13880325.
      2069385.43     13879728.95
#Sta/Elev= 30
  3493.5 1248.45  3623.7 1240.85  3704.1 1228.38  3804.8 1218.08  4026.3  1209.3
  4203.6 1208.14  4398.3 1204.99  4408.4 1207.74  4506.6 1209.76  4901.3 1209.27
  4951.6 1207.31  4989.8 1194.46  4990.3 1193.96    5014 1194.46  5017.6 1195.39
  5033.2 1202.68  5053.1 1205.36  5075.6 1212.17    5084 1220.42  5176.8 1230.63
  5326.1 1237.84  5331.4 1235.54  5480.8 1232.24  5511.7 1233.51  5535.7 1238.26
  5542.6    1237  5562.9  1241.2  5630.1 1245.54  5638.9 1247.94  5644.1 1248.55
#Mann= 8 ,-1 , 0
  3493.5    .035       0  4026.3     .07       0  4203.6    .035       0
  4989.8    .035       0    5014    .035       0  5017.6     .12       0
  5535.7     .07       0  5638.9     .12       0
Bank Sta=4989.8,5014
XS Rating Curve= 0 ,0
Exp/Cntr=0.3,0.1