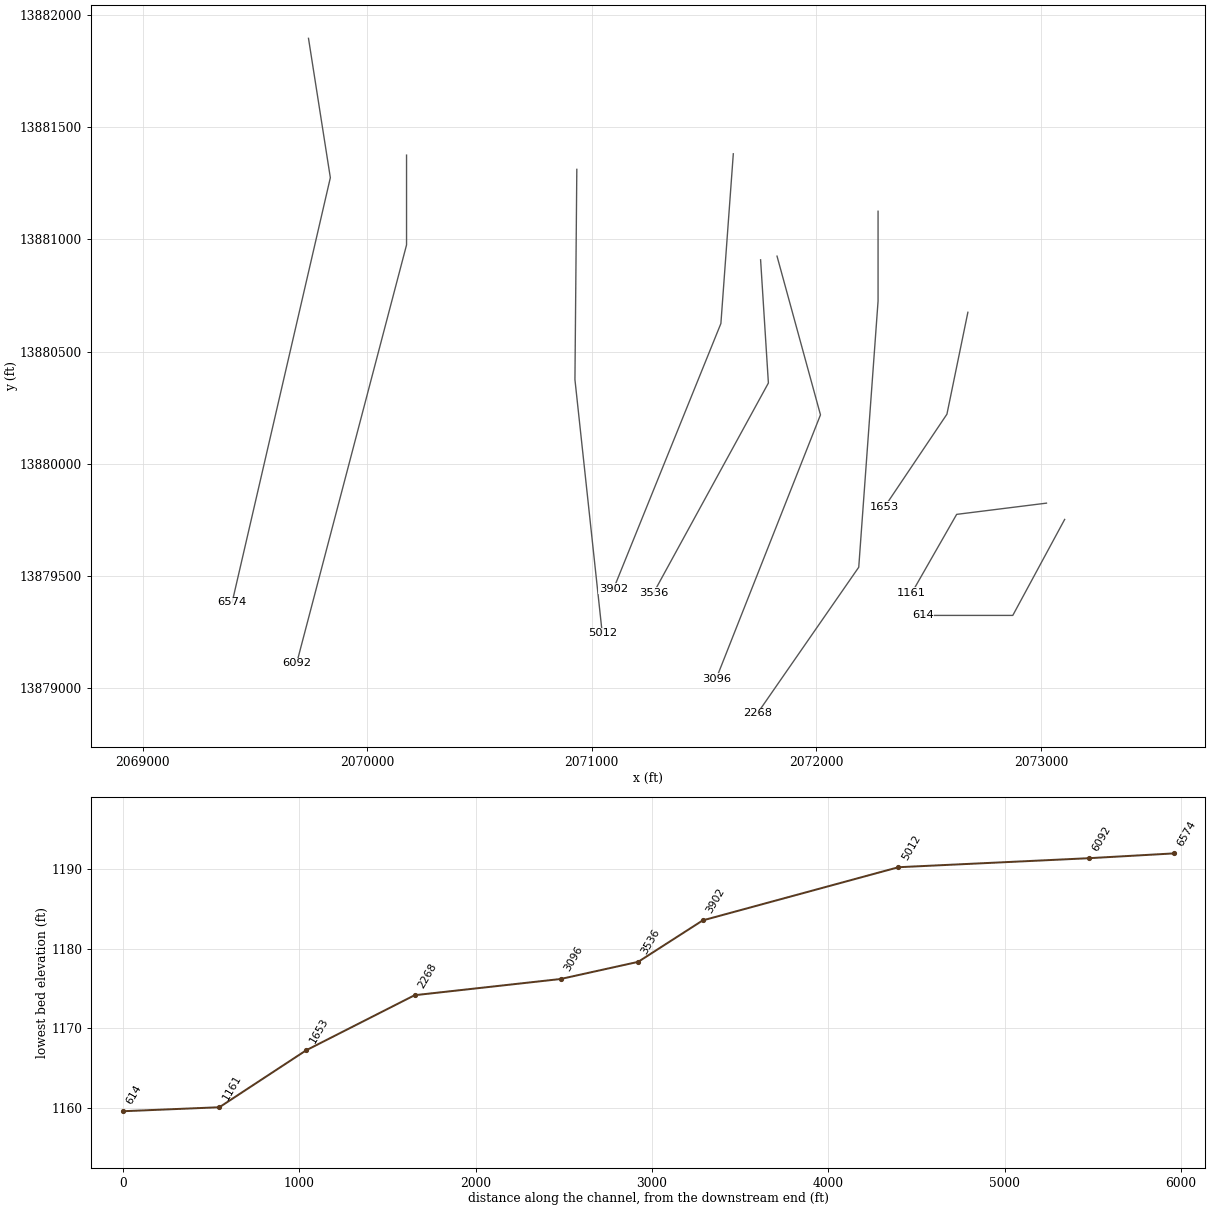
HEC-RAS study WASP CREEK.prj: WASP CREEK Base Level Engineering

--- WASP CREEK.g01 (geometry) --- (continued)

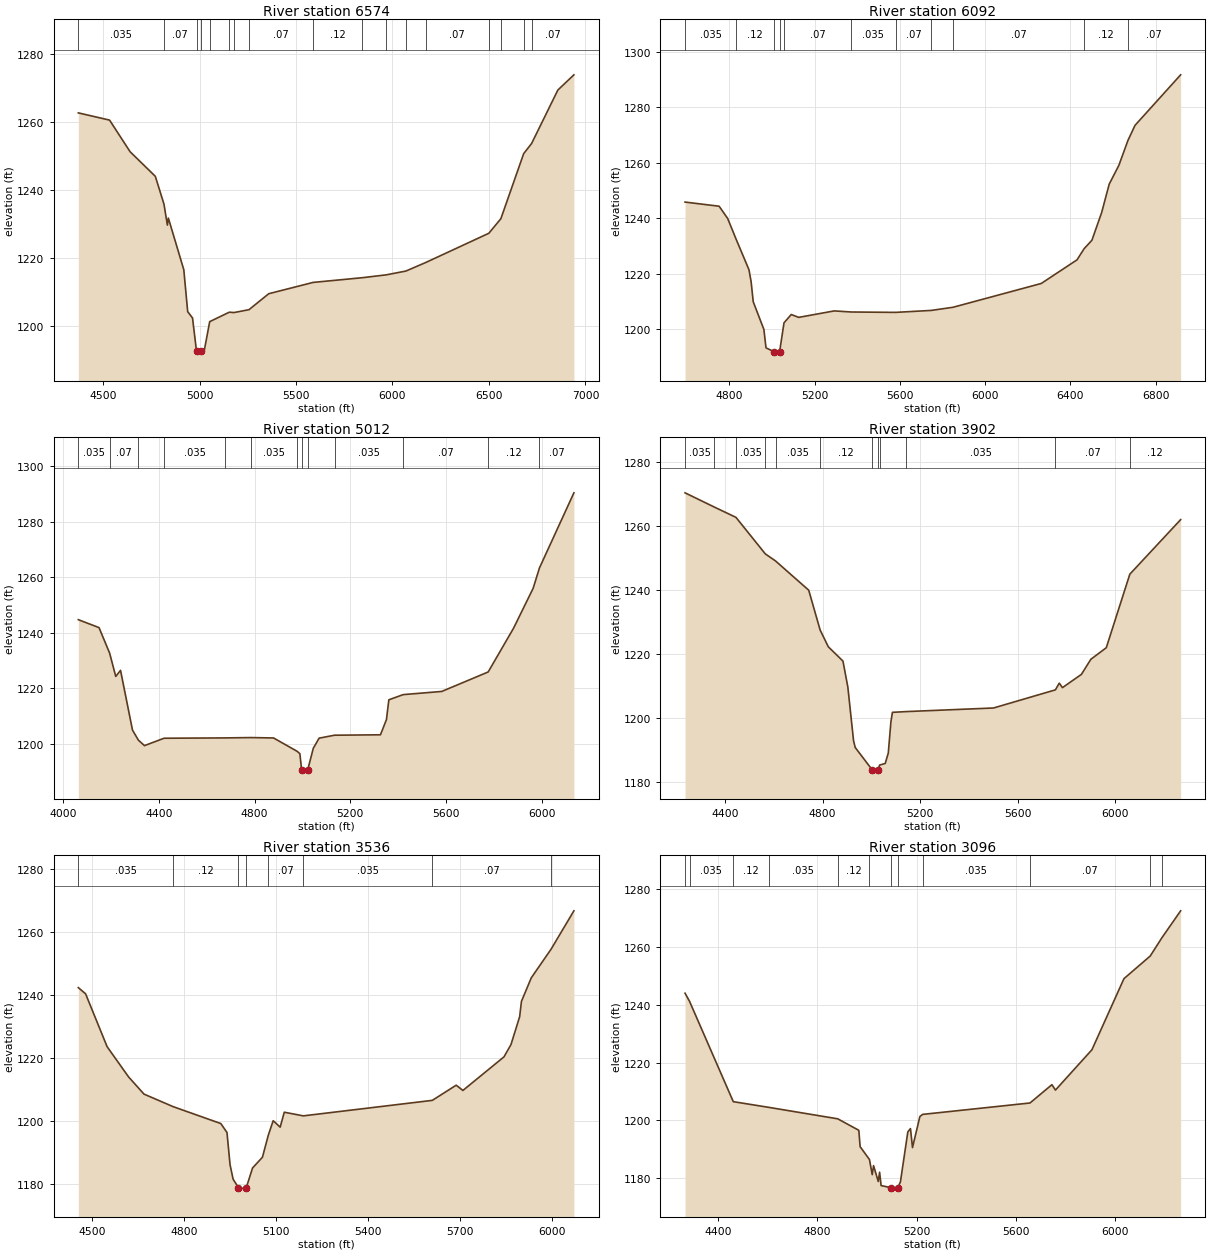
Type RM Length L Ch R = 1 ,6574    ,482,482,482
BEGIN DESCRIPTION:
WASP CREEK 9.5
END DESCRIPTION:
XS GIS Cut Line= 3
      2069738.34     13881895.07      2069835.64     13881274.45
      2069398.45     13879384.05
#Sta/Elev= 30
  4371.8 1262.68  4533.8 1260.55  4640.4 1251.22  4770.8    1244  4815.7 1235.81
  4833.4 1229.62  4838.5 1231.69  4918.5 1216.48  4938.7 1204.12  4963.8 1202.26
  4984.4 1192.41  4984.9 1191.91  5009.9 1192.41  5025.1 1192.83  5052.7 1201.18
  5154.4 1203.97  5178.3 1203.86  5256.1  1204.7  5358.7 1209.41  5588.7 1212.74
  5844.3 1214.13    5968 1214.97  6069.7 1216.09  6171.4 1218.58  6499.3 1227.21
  6561.8 1231.51  6679.9 1250.67    6721 1253.66  6857.2 1269.41  6940.3 1273.89
#Mann= 17 ,-1 , 0
  4371.8    .035       0  4815.7     .07       0  4984.4     .05       0
  5009.9     .07       0  5052.7     .12       0  5154.4    .035       0
  5178.3     .12       0  5256.1     .07       0  5588.7     .12       0
  5844.3     .07       0    5968     .12       0  6069.7    .035       0
  6171.4     .07       0  6499.3     .12       0  6561.8     .07       0
  6679.9     .12       0    6721     .07       0
Bank Sta=4984.4,5009.9
XS Rating Curve= 0 ,0
Exp/Cntr=0.3,0.1

Type RM Length L Ch R = 1 ,6092    ,1080,1080,1080
BEGIN DESCRIPTION:
WASP CREEK 9.0
END DESCRIPTION:
XS GIS Cut Line= 3
        2070175.     13881374.98        2070175.       13880975.
       2069685.7     13879112.27
#Sta/Elev= 30
  4591.7 1245.81  4751.7 1244.31  4791.7  1239.9  4831.1 1232.47  4891.7  1221.4
  4901.7 1217.15  4911.7 1209.84  4961.7 1199.86  4971.7 1193.21    5010 1191.81
  5010.5 1191.31  5035.5 1191.81  5056.1 1202.23    5090 1205.24  5125.2 1204.21
  5291.8 1206.54  5371.9 1206.15  5579.7 1206.01  5747.2 1206.72  5849.7 1207.86
  6263.4 1216.44  6431.2 1224.96    6465 1229.02  6501.2 1232.03  6547.1 1242.07
  6582.3 1252.26  6627.8 1259.08  6670.1 1268.01  6703.4 1273.48  6917.6 1291.72
#Mann= 11 ,-1 , 0
  4591.7    .035       0  4831.1     .12       0    5010     .05       0
  5035.5     .12       0  5056.1     .07       0  5371.9    .035       0
  5579.7     .07       0  5747.2    .035       0  5849.7     .07       0
    6465     .12       0  6670.1     .07       0
Bank Sta=5010,5035.5
XS Rating Curve= 0 ,0
Exp/Cntr=0.3,0.1

Type RM Length L Ch R = 1 ,5012    ,1110,1110,1110
BEGIN DESCRIPTION:
WASP CREEK 8.0
END DESCRIPTION:
XS GIS Cut Line= 3
      2070933.36     13881311.58        2070925.       13880375.
      2071046.57     13879245.54
#Sta/Elev= 30
  4062.8 1244.71  4149.4 1241.85  4193.7 1232.68  4219.4 1224.27  4239.4 1226.47
  4289.4 1204.95  4313.8 1201.36  4339.4 1199.36  4421.5 1202.02    4678 1202.14
  4784.4 1202.26  4879.4 1202.12  4978.2  1197.3  4989.4 1196.45  4996.7 1190.68
  4997.2 1190.18  5022.3 1190.68  5045.4 1198.38  5069.8 1202.05  5134.2 1203.11
  5326.4 1203.26  5351.4 1208.74  5361.5 1215.86  5421.7 1217.73  5582.8 1218.87
  5776.9 1225.88  5883.3 1241.68    5965 1256.02  5991.4 1263.35  6135.4 1290.38
#Mann= 13 ,-1 , 0
  4062.8    .035       0  4193.7     .07       0  4313.8     .12       0
  4421.5    .035       0    4678     .07       0  4784.4    .035       0
  4978.2     .07       0  4996.7     .05       0  5022.3     .07       0
  5134.2    .035       0  5421.7     .07       0  5776.9     .12       0
  5991.4     .07       0
Bank Sta=4996.7,5022.3
XS Rating Curve= 0 ,0
Exp/Cntr=0.3,0.1

Type RM Length L Ch R = 1 ,3902    ,366,366,366
BEGIN DESCRIPTION:
WASP CREEK 7.0
END DESCRIPTION:
XS GIS Cut Line= 3
       2071630.3     13881380.85        2071575.       13880625.
      2071097.15     13879443.65
#Sta/Elev= 30
  4236.1  1270.4  4354.7 1266.01  4444.9 1262.74  4565.2 1251.34  4607.2 1249.13
  4743.3    1240  4790.1 1227.56  4823.5 1222.34  4883.7 1217.87  4903.7 1209.75
  4927.1 1193.01  4933.8 1190.91  5002.6 1184.02  5003.1 1183.52  5028.5 1184.02
  5033.8  1185.4    5057 1185.92  5069.5 1189.17  5080.3 1198.96  5086.5 1201.87
  5141.2  1202.1    5501 1203.23  5754.8 1208.89  5770.6 1210.99  5783.7 1209.58
  5861.5 1213.73  5900.1 1218.43  5963.4 1222.04  6059.9 1244.99  6268.3 1262.03
#Mann= 12 ,-1 , 0
  4236.1    .035       0  4354.7     .12       0  4444.9    .035       0
  4565.2     .07       0  4607.2    .035       0  4790.1     .12       0
  5002.6     .05       0  5028.5     .12       0  5033.8     .07       0
  5141.2    .035       0  5754.8     .07       0  6059.9     .12       0
Bank Sta=5002.6,5028.5
XS Rating Curve= 0 ,0
Exp/Cntr=0.3,0.1

Type RM Length L Ch R = 1 ,3536    ,440,440,440
BEGIN DESCRIPTION:
WASP CREEK 6.0
END DESCRIPTION:
XS GIS Cut Line= 3
      2071751.83     13880908.69      2071786.55     13880360.05
      2071274.99     13879424.97
#Sta/Elev= 30
  4454.7  1242.3  4478.4 1240.35  4548.6 1223.55  4618.7 1213.94  4668.8  1208.5
    4764 1204.51  4919.3 1199.15  4939.4 1196.29  4949.4 1186.06  4959.4 1181.47
  4976.5 1178.83    4977 1178.33  5002.4 1178.83  5022.7 1185.05  5054.9 1188.45
  5074.1 1195.47    5090 1200.05  5112.8    1198  5126.1 1202.75  5188.1 1201.59
  5608.7 1206.51  5686.6 1211.33  5708.4 1209.66  5842.3 1220.32  5865.1 1224.21
  5893.4 1233.06  5899.3 1237.95  5931.3 1245.41  5995.8  1254.5  6070.3 1266.69
#Mann= 8 ,-1 , 0
  4454.7    .035       0    4764     .12       0  4976.5     .05       0
  5002.4     .12       0  5074.1     .07       0  5188.1    .035       0
  5608.7     .07       0  5995.8    .035       0
Bank Sta=4976.5,5002.4
XS Rating Curve= 0 ,0
Exp/Cntr=0.3,0.1

Type RM Length L Ch R = 1 ,3096    ,828,828,828
BEGIN DESCRIPTION:
WASP CREEK 5.0
END DESCRIPTION:
XS GIS Cut Line= 3
      2071824.99     13880925.03      2072018.51     13880218.24
        2071554.     13879042.58
#Sta/Elev= 30
  4267.2 1244.03  4285.2 1241.24  4461.6 1206.47  4605.2 1204.49  4882.4 1200.53
  4967.4 1196.55  4972.6  1190.9  5010.3 1186.42  5021.4  1181.2  5026.8 1184.32
  5045.7 1178.83  5051.1 1182.04  5057.2 1177.41    5098 1176.68  5098.5 1176.18
    5124 1176.68    5135 1178.66  5164.8 1195.99  5175.5 1197.15  5183.7 1190.58
  5213.4 1201.32  5224.5 1202.06  5657.1 1206.01  5745.4 1212.35  5759.7 1210.48
  5906.7 1224.45  6035.7 1249.07  6141.7 1256.92  6188.2 1263.18  6264.1 1272.56
#Mann= 12 ,-1 , 0
  4267.2     .12       0  4285.2    .035       0  4461.6     .12       0
  4605.2    .035       0  4882.4     .12       0  5010.3     .12       0
    5098     .05       0    5124     .12       0  5224.5    .035       0
  5657.1     .07       0  6141.7    .035       0  6188.2     .07       0
Bank Sta=5098,5124
XS Rating Curve= 0 ,0
Exp/Cntr=0.3,0.1

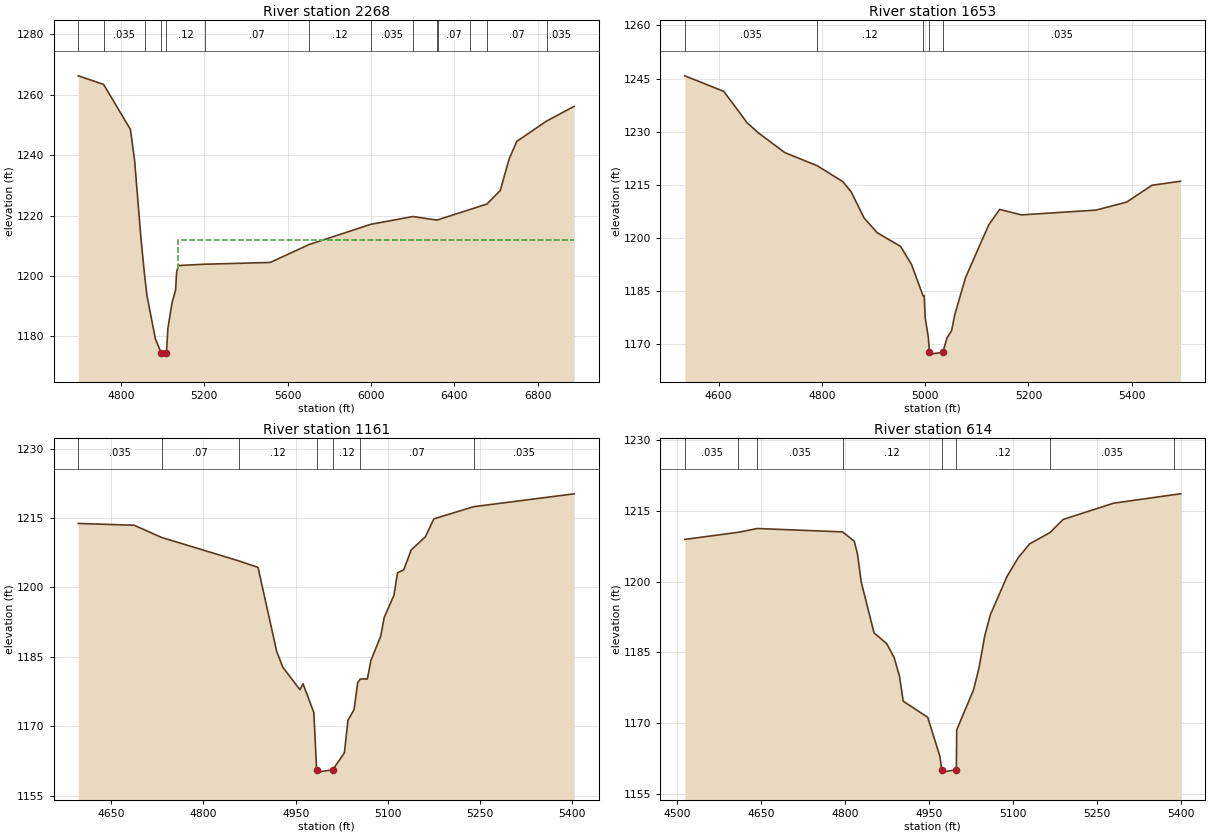
Type RM Length L Ch R = 1 ,2268    ,615,615,615
BEGIN DESCRIPTION:
WASP CREEK 4.0
END DESCRIPTION:
XS GIS Cut Line= 4
        2072275.     13881125.02        2072275.       13880725.
      2072188.92     13879539.52      2071737.64     13878888.69
#Sta/Elev= 30
  4595.4 1266.31  4716.7 1263.47  4845.4 1248.57  4865.4  1238.4  4895.4 1213.04
  4913.5 1200.27  4925.4 1193.35  4965.4 1179.22  4992.4 1174.65  4992.9 1174.15
  5018.4 1174.65  5025.5 1182.71  5045.6 1191.23  5062.5 1195.41  5067.5 1201.33
  5075.6  1203.5  5201.9 1203.92  5516.8 1204.51  5703.9 1210.46  5999.9 1217.14
  6201.6 1219.71  6315.7 1218.56  6322.5 1218.65  6476.8 1222.07  6557.2 1223.85
  6621.2 1228.34  6664.1 1238.83  6700.6 1244.61  6843.8 1251.33    6976 1256.22
#Mann= 14 ,-1 , 0
  4595.4     .07       0  4716.7    .035       0  4913.5     .12       0
  4992.4     .05       0  5018.4     .12       0  5201.9     .07       0
  5703.9     .12       0  5999.9    .035       0  6201.6     .12       0
  6315.7    .035       0  6322.5     .07       0  6476.8    .035       0
  6557.2     .07       0  6843.8    .035       0
#XS Ineff= 2 , 0
       0                 5071.77       0 1212.05
Permanent Ineff=
       F       F
Bank Sta=4992.4,5018.4
XS Rating Curve= 0 ,0
Exp/Cntr=0.3,0.1

Type RM Length L Ch R = 1 ,1653    ,492,492,492
BEGIN DESCRIPTION:
WASP CREEK 3.0
END DESCRIPTION:
XS GIS Cut Line= 3
        2072675.     13880675.02      2072581.69     13880221.16
       2072304.6     13879808.99
#Sta/Elev= 30
  4534.7 1245.76  4610.2 1241.37  4655.5  1232.5  4677.6 1229.62  4728.7 1224.07
  4790.8 1220.42    4841 1215.88  4856.9    1213  4881.8 1205.66  4907.2 1201.51
  4952.5 1197.64  4973.7 1192.53  4995.9 1183.75  4998.1 1183.75  5000.3 1177.39
  5006.3 1171.86  5008.3 1167.75  5008.8 1167.25  5034.3 1167.75  5042.3 1171.81
  5051.3 1173.89  5057.3 1178.31  5078.3 1188.86  5123.2 1203.72  5144.3 1208.08
  5186.3 1206.53  5330.8 1207.88  5390.2 1210.14  5439.3 1214.89  5494.7 1216.03
#Mann= 5 ,-1 , 0
  4534.7    .035       0  4790.8     .12       0  4995.9    .035       0
  5008.3    .035       0  5034.3    .035       0
Bank Sta=5008.3,5034.3
XS Rating Curve= 0 ,0
Exp/Cntr=0.3,0.1

Type RM Length L Ch R = 1 ,1161    ,547,547,547
BEGIN DESCRIPTION:
WASP CREEK 2.0
END DESCRIPTION:
XS GIS Cut Line= 3
      2073024.97       13879825.        2072625.       13879775.
        2072425.       13879425.
#Sta/Elev= 30
  4596.6 1213.82  4687.3 1213.44    4732  1210.8  4857.7 1205.73  4888.8 1204.32
  4919.1  1186.2  4929.1 1182.79  4956.9 1177.92  4961.9 1179.21  4979.5    1173
  4984.1 1160.62  4984.6 1160.12  5010.2 1160.62  5029.2 1164.28    5035 1171.31
    5045 1173.64  5050.8 1179.45  5055.1 1180.23  5066.6 1180.25  5072.4 1184.27
  5088.2 1189.45    5094 1193.53  5109.8 1198.34  5115.6 1203.17  5125.7  1203.8
  5137.9 1208.12  5160.9 1210.94  5174.6 1214.81  5239.3 1217.44  5402.8 1220.22
#Mann= 7 ,-1 , 0
  4596.6    .035       0    4732     .07       0  4857.7     .12       0
  4984.1     .05       0  5010.2     .12       0  5055.1     .07       0
  5239.3    .035       0
Bank Sta=4984.1,5010.2
XS Rating Curve= 0 ,0
Exp/Cntr=0.3,0.1

Type RM Length L Ch R = 1 ,614     ,0,0,0
BEGIN DESCRIPTION:
WASP CREEK 1.0
END DESCRIPTION:
XS GIS Cut Line= 3
        2073106.     13879752.42        2072875.       13879325.
      2072475.05       13879325.
#Sta/Elev= 30
  4513.8 1208.96  4609.7 1210.47  4643.5 1211.27  4795.7 1210.55  4816.5 1208.58
  4822.2 1205.92  4829.1 1199.87  4851.9 1189.14  4874.6 1186.85  4887.8 1183.91
  4897.3 1179.99    4904 1174.66  4947.8 1171.24  4969.7 1162.91  4972.8 1160.12
  4973.3 1159.62  4998.9 1160.12  4999.6 1168.58  5029.6 1177.05  5039.6  1181.8
  5049.6 1188.48  5059.6 1192.95  5089.6 1201.15  5109.6 1205.09  5129.6 1207.99
  5166.1  1210.4  5189.6 1213.18  5279.6 1216.63  5387.3 1218.43  5399.6 1218.62
#Mann= 8 ,-1 , 0
  4513.8    .035       0  4609.7     .07       0  4643.5    .035       0
  4795.7     .12       0  4972.8     .05       0  4998.9     .12       0
  5166.1    .035       0  5387.3     .07       0
Bank Sta=4972.8,4998.9
XS Rating Curve= 0 ,0
Exp/Cntr=0.3,0.1

Chan Stop Cuts=-1
Use User Specified Reach Order=0
Composite Channel Slope=5