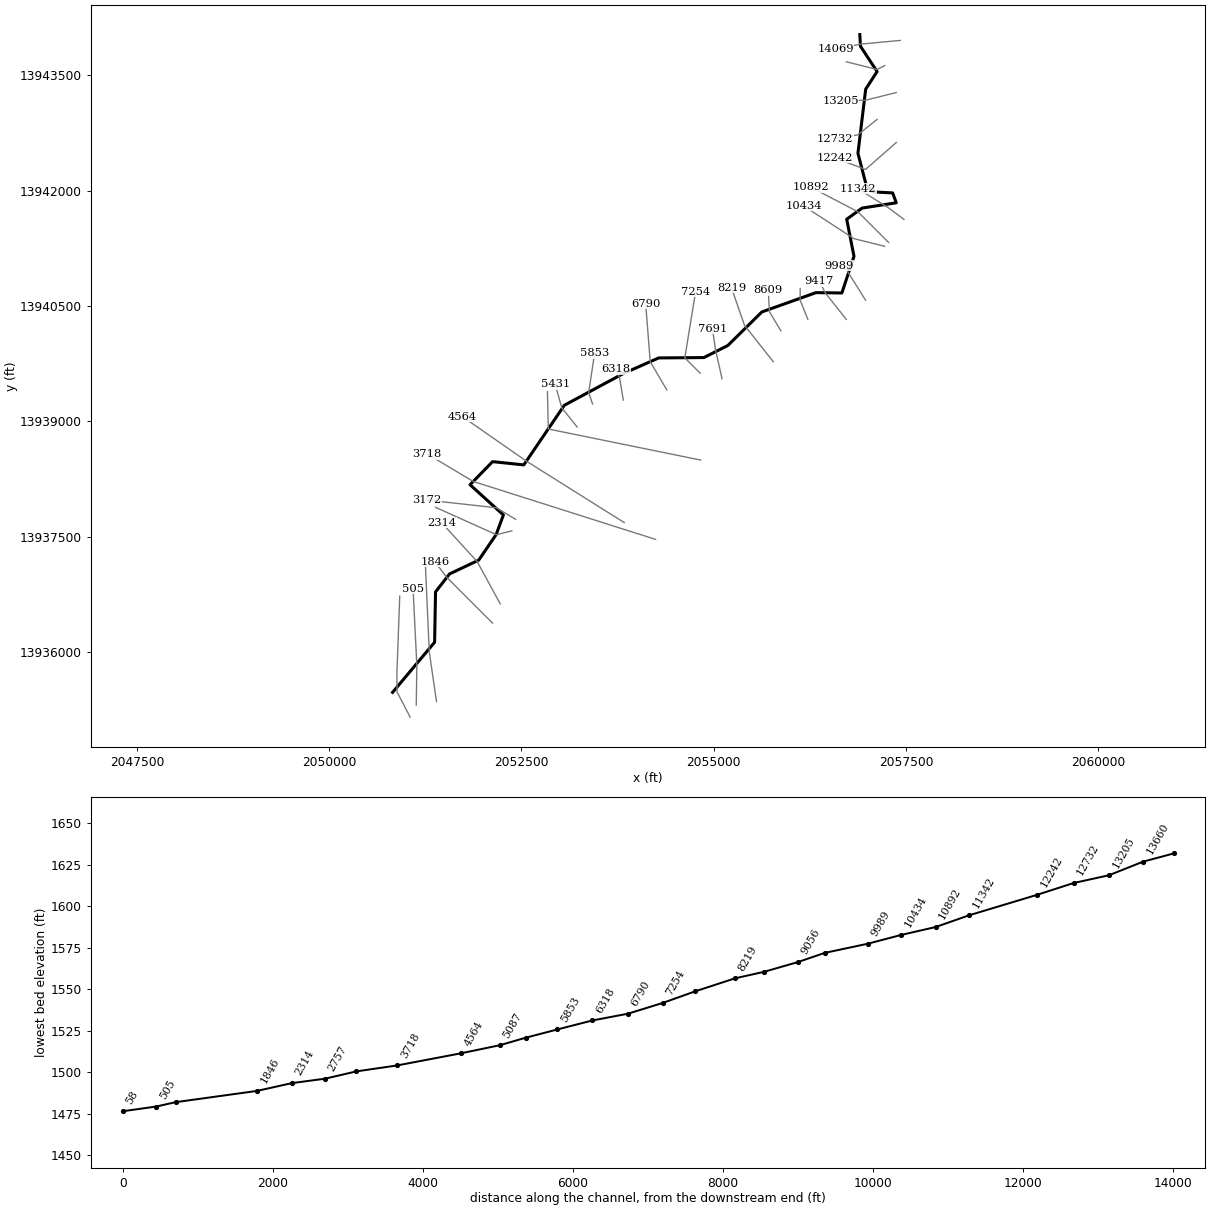
--- WENZEL CREEK.prj (project) ---

Proj Title=WENZEL CREEK Base Level Engineering
Current Plan=p01
Default Exp/Contr=0.3,0.1
English Units
Geom File=g01
Flow File=f01
Plan File=p01
BEGIN DESCRIPTION:
WENZEL CREEK
END DESCRIPTION:

--- WENZEL CREEK.p01 (plan) ---

Plan Title=Multiple Run
Short Identifier=Multiple
Geom File=g01
Flow File=f01
Subcritical Flow
K Sum by GR= 0
Std Step Tol= 0.01
Critical Tol= 0.01
Num of Std Step Trials= 20
Max Error Tol= 0.3
Flow Tol Ratio= 0.001
Split Flow NTrial= 30
Split Flow Tol= 0.02
Split Flow Ratio= 0.02
Log Output Level= 0
Friction Slope Method= 1
Unsteady Friction Slope Method= 2
Unsteady Bridges Friction Slope Method= 1
Parabolic Critical Depth
Global Vel Dist=  1 , 1 , 1
Global Log Level= 0
CheckData=True
Encroach Param= -1, 0, 0, 0
BEGIN DESCRIPTION:
Multiple Run
END DESCRIPTION:

--- WENZEL CREEK.f01 (steady flow) ---

Flow Title=Multiple
Number of Profiles=7
Profile Names=10-year,25-year,50-year,1pct_min,100-year,1pct_plu,500-year
River Rch & RM= WENZEL CREEK,Reach-1,14069
    1134    1957    2755    1882    3756    7493    6922
River Rch & RM= WENZEL CREEK,Reach-1,11342
    1777    3146    4503    3124    6233   12436   11848
River Rch & RM= WENZEL CREEK,Reach-1,9989
    2273    4060    5846    4074    8129   16220   15603
River Rch & RM= WENZEL CREEK,Reach-1,3718
    3584    6525    9518    6709   13386   26709   26291
Boundary for River Rch & Prof#=WENZEL CREEK,Reach-1,1
Up Type=0
Dn Type=3
Dn Slope=0.005
Boundary for River Rch & Prof#=WENZEL CREEK,Reach-1,2
Up Type=0
Dn Type=3
Dn Slope=0.005
Boundary for River Rch & Prof#=WENZEL CREEK,Reach-1,3
Up Type=0
Dn Type=3
Dn Slope=0.005
Boundary for River Rch & Prof#=WENZEL CREEK,Reach-1,4
Up Type=0
Dn Type=3
Dn Slope=0.005
Boundary for River Rch & Prof#=WENZEL CREEK,Reach-1,5
Up Type=0
Dn Type=3
Dn Slope=0.005
Boundary for River Rch & Prof#=WENZEL CREEK,Reach-1,6
Up Type=0
Dn Type=3
Dn Slope=0.005
Boundary for River Rch & Prof#=WENZEL CREEK,Reach-1,7
Up Type=0
Dn Type=3
Dn Slope=0.005

--- WENZEL CREEK.g01 (geometry) ---

Geom Title=Existing Conditions

River Reach=WENZEL CREEK,Reach-1
Reach XY= 30
      2056900.71     13944028.65      2056909.20     13943876.53
      2057125.40     13943547.80      2056977.06     13943319.14
      2056876.36     13942484.65      2056985.48     13942065.15
      2057071.58     13941982.81      2057327.66     13941969.67
      2057375.02     13941841.16      2056930.93     13941772.75
      2056730.08     13941627.31      2056825.02     13941144.99
      2056667.32     13940668.47      2056330.86     13940672.94
      2055626.47     13940421.45      2055184.79     13939985.52
      2054873.53     13939828.55      2054285.50     13939823.80
      2053826.58     13939621.17      2053058.33     13939208.35
      2052531.17     13938432.76      2052125.00     13938475.00
      2051831.98     13938174.79      2052265.89     13937781.73
      2052171.38     13937526.50      2051945.13     13937194.77
      2051565.19     13937014.49      2051383.16     13936781.05
      2051371.25     13936126.55      2050825.00     13935475.00

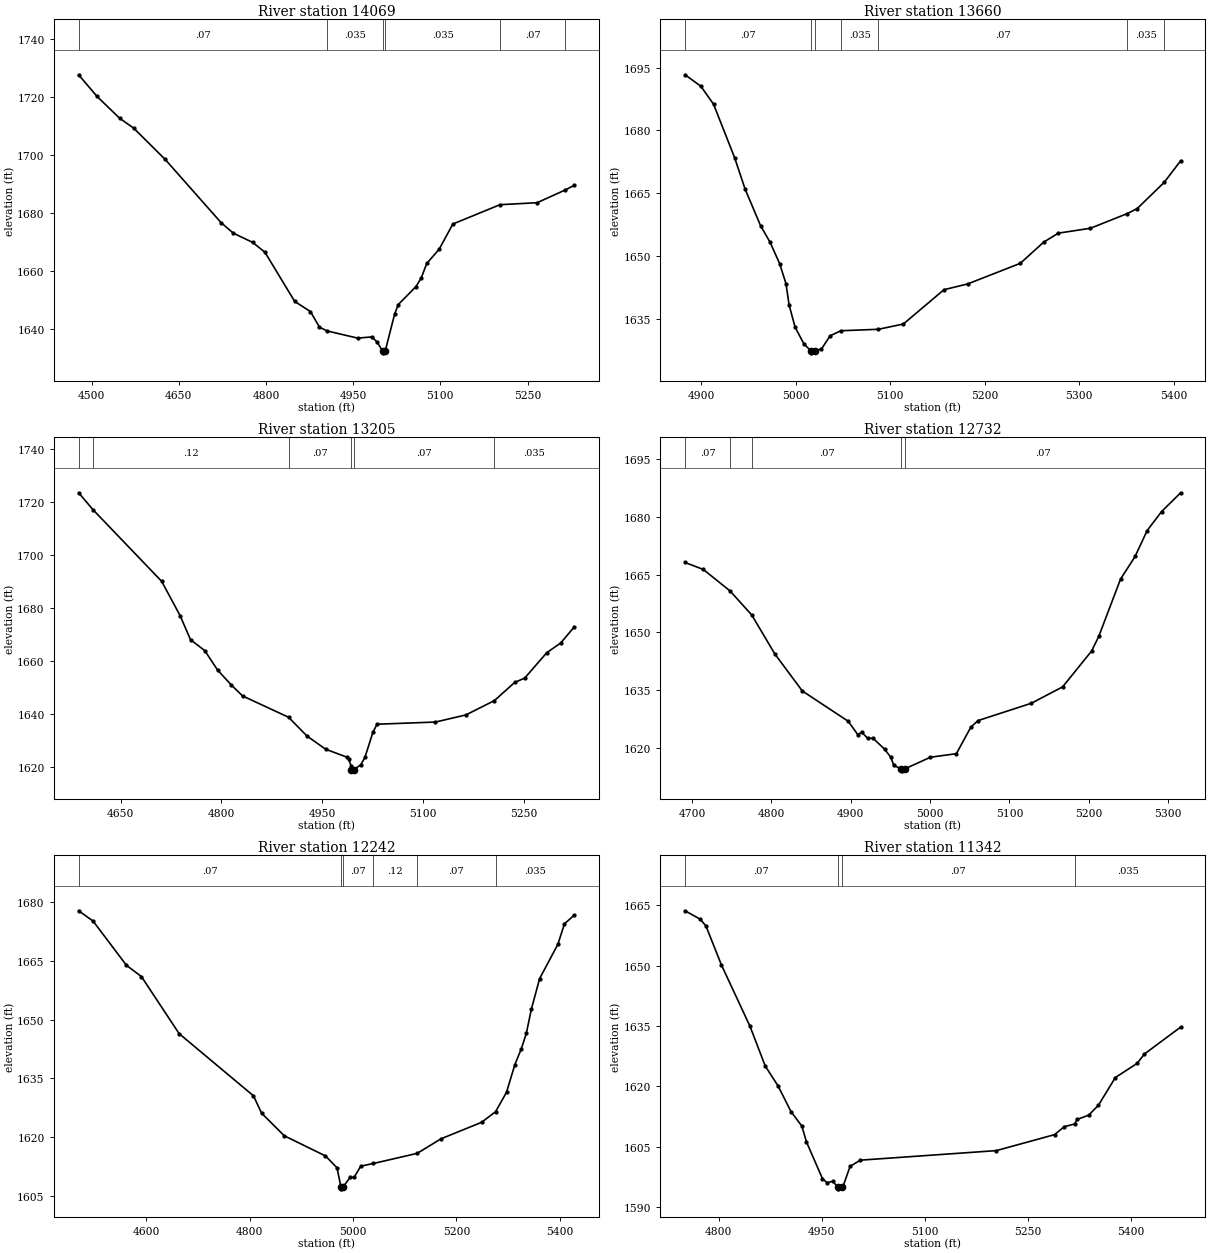
Type RM Length L Ch R = 1,14069,409,409,409
BEGIN DESCRIPTION:
WENZEL CREEK 29.0
END DESCRIPTION:
XS GIS Cut Line= 3
      2057427.77     13943952.99      2056902.57     13943903.81
      2056584.23     13943837.36
#Sta/Elev= 30
  4477.6 1727.76  4508.9 1720.37  4548.1 1712.76  4572.2 1709.36  4626.4 1698.57
  4722.8 1676.70  4743.9 1673.07  4777.1 1669.89  4798.1 1666.52  4849.4 1649.52
  4876.5 1646.02  4891.9 1640.66  4904.9 1639.34  4957.8 1636.85  4981.9 1637.27
  4990.9 1635.58  5001.0 1632.27  5001.3 1631.77  5005.0 1632.27  5021.4 1645.17
  5027.5 1648.41  5058.2 1654.66  5067.4 1657.76  5076.6 1662.62  5098.0 1667.54
  5121.5 1676.23  5202.6 1682.91  5266.6 1683.60  5315.0 1688.00  5330.3 1689.60
#Mann=6,-1,0
  4477.6    0.07       0  4904.9   0.035       0  5001.0   0.035       0
  5005.0   0.035       0  5202.6    0.07       0  5315.0   0.035       0
Bank Sta=5001,5005
Exp/Cntr=0.3,0.1

Type RM Length L Ch R = 1,13660,455,455,455
BEGIN DESCRIPTION:
WENZEL CREEK 28.0
END DESCRIPTION:
XS GIS Cut Line= 3
      2057225.02     13943625.01      2057125.00     13943575.00
      2056725.04     13943674.99
#Sta/Elev= 30
  4883.2 1693.28  4899.9 1690.53  4913.3 1686.24  4935.6 1673.45  4946.8 1665.88
  4963.0 1657.23  4973.1 1653.25  4983.2 1648.14  4989.9 1643.35  4993.2 1638.27
  4999.5 1632.98  5008.8 1628.99  5016.1 1627.33  5016.3 1626.83  5020.1 1627.33
  5027.4 1627.74  5036.6 1630.90  5047.9 1632.11  5087.6 1632.46  5114.0 1633.71
  5157.0 1641.92  5182.0 1643.29  5237.7 1648.22  5262.4 1653.27  5277.9 1655.43
  5311.9 1656.60  5350.9 1660.11  5361.3 1661.30  5389.8 1667.54  5407.3 1672.72
#Mann=7,-1,0
  4883.2    0.07       0  5016.1    0.05       0  5020.1    0.07       0
  5047.9   0.035       0  5087.6    0.07       0  5350.9   0.035       0
  5389.8    0.07       0
Bank Sta=5016.1,5020.1
Exp/Cntr=0.3,0.1

Type RM Length L Ch R = 1,13205,473,473,473
BEGIN DESCRIPTION:
WENZEL CREEK 27.0
END DESCRIPTION:
XS GIS Cut Line= 3
      2057374.95     13943274.99      2056975.00     13943175.00
      2056650.72     13943169.03
#Sta/Elev= 30
  4587.7 1723.37  4609.0 1717.01  4711.1 1690.02  4738.5 1677.11  4754.0 1668.02
  4775.1 1663.95  4794.2 1656.61  4814.7 1650.96  4831.3 1646.86  4899.7 1638.82
  4927.2 1631.73  4955.0 1626.76  4985.9 1623.84  4989.0 1623.11  4992.8 1620.43
  4993.2 1619.13  4993.5 1618.63  4997.3 1619.13  5007.3 1620.96  5013.3 1623.74
  5025.3 1633.26  5031.3 1636.19  5118.1 1637.01  5163.4 1639.70  5205.8 1645.10
  5236.0 1651.97  5250.7 1653.54  5283.4 1663.09  5304.4 1666.81  5324.3 1672.81
#Mann=6,-1,0
  4587.7    0.07       0  4609.0    0.12       0  4899.7    0.07       0
  4993.2    0.05       0  4997.3    0.07       0  5205.8   0.035       0
Bank Sta=4993.2,4997.3
Exp/Cntr=0.3,0.1

Type RM Length L Ch R = 1,12732,490,490,490
BEGIN DESCRIPTION:
WENZEL CREEK 26.0
END DESCRIPTION:
XS GIS Cut Line= 3
      2057124.97     13942924.98      2056875.00     13942725.00
      2056574.96     13942674.99
#Sta/Elev= 30
  4691.4 1668.15  4714.4 1666.33  4748.0 1660.75  4775.4 1654.48  4804.5 1644.33
  4839.1 1634.71  4896.8 1626.85  4909.0 1623.35  4913.8 1624.01  4921.4 1622.40
  4928.2 1622.41  4942.9 1619.53  4950.5 1617.47  4954.4 1615.32  4963.9 1614.43
  4964.1 1613.93  4968.0 1614.43  5000.5 1617.47  5033.2 1618.40  5051.4 1625.30
  5060.5 1627.01  5127.5 1631.51  5167.0 1635.78  5203.5 1645.10  5212.6 1648.94
  5240.0 1663.83  5258.3 1669.71  5273.5 1676.45  5291.7 1681.40  5315.7 1686.29
#Mann=5,-1,0
  4691.4    0.07       0  4748.0    0.12       0  4775.4    0.07       0
  4963.9    0.05       0  4968.0    0.07       0
Bank Sta=4963.9,4968
Exp/Cntr=0.3,0.1

Type RM Length L Ch R = 1,12242,900,900,900
BEGIN DESCRIPTION:
WENZEL CREEK 25.0
END DESCRIPTION:
XS GIS Cut Line= 3
      2057375.03     13942625.02      2056975.00     13942275.00
      2056575.04     13942424.99
#Sta/Elev= 30
  4469.0 1677.76  4496.9 1675.14  4561.6 1663.83  4590.4 1660.98  4663.5 1646.39
  4807.3 1630.52  4823.0 1626.09  4866.8 1620.33  4946.6 1615.18  4968.9 1612.15
  4976.4 1607.28  4976.7 1606.78  4980.5 1607.28  4994.4 1609.71  5002.0 1609.71
  5014.8 1612.57  5039.2 1613.25  5124.0 1615.84  5170.2 1619.56  5248.7 1623.77
  5275.7 1626.48  5296.8 1631.43  5312.8 1638.42  5325.6 1642.59  5335.2 1646.50
  5344.8 1652.60  5360.9 1660.46  5396.1 1669.17  5408.9 1674.43  5427.7 1676.63
#Mann=6,-1,0
  4469.0    0.07       0  4976.4    0.05       0  4980.5    0.07       0
  5039.2    0.12       0  5124.0    0.07       0  5275.7   0.035       0
Bank Sta=4976.4,4980.5
Exp/Cntr=0.3,0.1

Type RM Length L Ch R = 1,11342,450,450,450
BEGIN DESCRIPTION:
WENZEL CREEK 24.0
END DESCRIPTION:
XS GIS Cut Line= 3
      2057474.97     13941625.02      2057275.00     13941775.00
      2056874.96     13942025.02
#Sta/Elev= 30
  4750.9 1663.59  4773.0 1661.48  4781.3 1659.81  4803.8 1650.14  4845.5 1634.87
  4867.6 1625.04  4886.2 1620.12  4905.1 1613.73  4921.0 1610.11  4927.6 1606.22
  4951.0 1597.05  4957.6 1596.07  4966.0 1596.41  4973.0 1595.04  4973.5 1594.54
  4978.9 1595.04  4981.0 1595.19  4991.2 1600.12  5006.0 1601.66  5204.1 1604.03
  5289.0 1608.00  5303.2 1609.98  5318.3 1610.65  5321.9 1611.78  5338.6 1612.83
  5352.7 1615.25  5377.5 1622.18  5409.3 1625.70  5419.9 1628.03  5472.6 1634.70
#Mann=4,-1,0
  4750.9    0.07       0  4973.0    0.05       0  4978.9    0.07       0
  5318.3   0.035       0
Bank Sta=4973,4978.9
Exp/Cntr=0.3,0.1

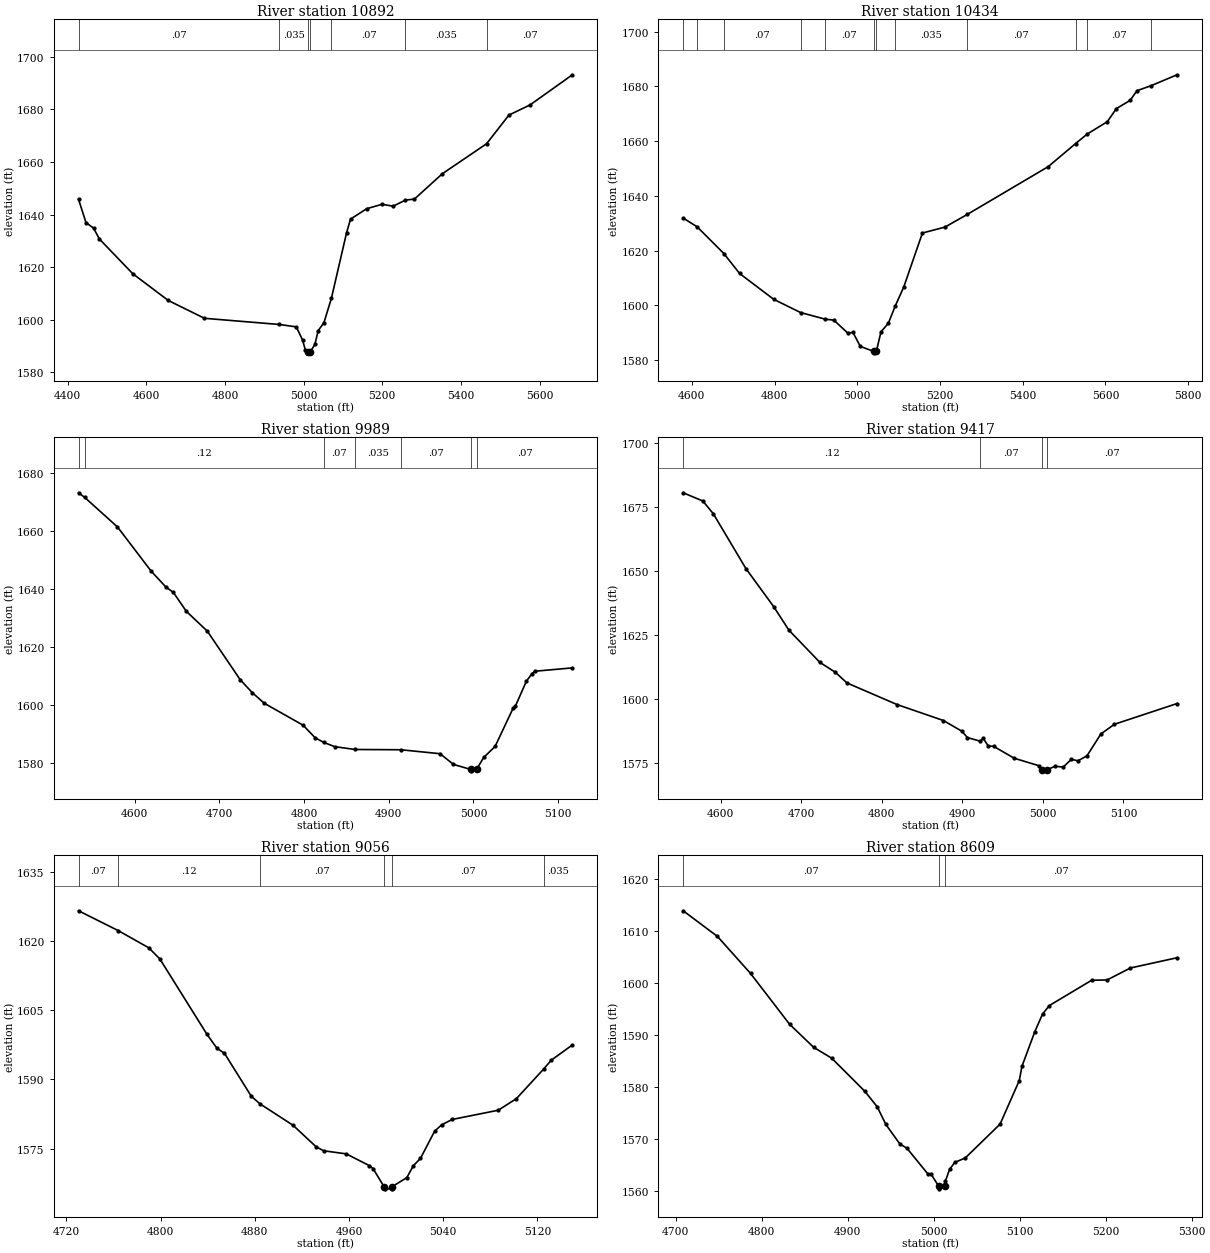
Type RM Length L Ch R = 1,10892,458,458,458
BEGIN DESCRIPTION:
WENZEL CREEK 23.0
END DESCRIPTION:
XS GIS Cut Line= 3
      2057275.00     13941325.00      2056875.00     13941725.00
      2056263.59     13942043.98
#Sta/Elev= 30
  4428.0 1645.78  4446.9 1636.93  4466.3 1634.80  4480.9 1630.71  4565.7 1617.51
  4656.0 1607.33  4748.1 1600.55  4938.3 1598.20  4981.5 1597.29  4997.5 1592.24
  5004.6 1588.46  5011.5 1587.92  5012.0 1587.42  5017.4 1587.92  5028.9 1590.69
  5037.1 1595.87  5051.6 1598.82  5070.7 1608.15  5109.2 1633.02  5119.3 1638.25
  5160.3 1642.20  5199.2 1643.88  5227.6 1643.17  5259.0 1645.48  5281.7 1645.87
  5352.8 1655.51  5465.1 1666.90  5522.0 1677.81  5575.4 1681.64  5683.3 1693.12
#Mann=7,-1,0
  4428.0    0.07       0  4938.3   0.035       0  5011.5   0.035       0
  5017.4   0.035       0  5070.7    0.07       0  5259.0   0.035       0
  5465.1    0.07       0
Bank Sta=5011.5,5017.4
Exp/Cntr=0.3,0.1

Type RM Length L Ch R = 1,10434,445,445,445
BEGIN DESCRIPTION:
WENZEL CREEK 22.0
END DESCRIPTION:
XS GIS Cut Line= 3
      2057225.01     13941275.00      2056825.00     13941375.00
      2056169.34     13941800.79
#Sta/Elev= 30
  4579.0 1631.92  4612.6 1628.75  4677.4 1618.96  4715.5 1611.67  4797.9 1602.24
  4862.8 1597.41  4921.9 1595.00  4943.3 1594.62  4977.3 1589.87  4989.6 1590.14
  5007.3 1585.03  5040.1 1583.18  5040.5 1582.68  5046.0 1583.18  5057.3 1590.34
  5075.2 1593.51  5091.8 1599.80  5112.4 1606.75  5157.5 1626.46  5212.1 1628.63
  5265.8 1633.24  5461.5 1650.70  5527.7 1659.13  5556.1 1662.64  5604.6 1667.14
  5626.4 1671.92  5659.8 1674.93  5676.2 1678.46  5710.8 1680.32  5773.1 1684.28
#Mann=12,-1,0
  4579.0    0.07       0  4612.6   0.035       0  4677.4    0.07       0
  4862.8   0.035       0  4921.9    0.07       0  5040.1    0.05       0
  5046.0    0.07       0  5091.8   0.035       0  5265.8    0.07       0
  5527.7   0.035       0  5556.1    0.07       0  5710.8   0.035       0
Bank Sta=5040.1,5046
Exp/Cntr=0.3,0.1

Type RM Length L Ch R = 1,9989,572,572,572
BEGIN DESCRIPTION:
WENZEL CREEK 21.0
END DESCRIPTION:
XS GIS Cut Line= 3
      2056974.98     13940575.03      2056725.00     13940975.00
      2056624.97     13941025.01
#Sta/Elev= 30
  4533.5 1673.12  4540.7 1671.54  4579.5 1661.36  4619.4 1646.10  4636.8 1640.64
  4645.5 1638.83  4660.9 1632.29  4685.7 1625.46  4724.6 1608.71  4738.7 1604.33
  4752.9 1600.65  4798.9 1593.07  4813.0 1588.77  4823.0 1587.20  4836.1 1585.71
  4860.3 1584.73  4914.3 1584.64  4960.6 1583.28  4976.5 1579.59  4996.7 1577.88
  4997.2 1577.38  5003.7 1577.88  5012.3 1582.02  5025.7 1585.80  5047.2 1599.10
  5049.5 1599.58  5062.6 1608.22  5069.3 1610.87  5072.7 1611.68  5117.0 1612.83
#Mann=7,-1,0
  4533.5    0.07       0  4540.7    0.12       0  4823.0    0.07       0
  4860.3   0.035       0  4914.3    0.07       0  4996.7    0.05       0
  5003.7    0.07       0
Bank Sta=4996.7,5003.7
Exp/Cntr=0.3,0.1

Type RM Length L Ch R = 1,9417,361,361,361
BEGIN DESCRIPTION:
WENZEL CREEK 20.0
END DESCRIPTION:
XS GIS Cut Line= 3
      2056725.03     13940324.96      2056449.37     13940672.50
      2056374.98     13940825.04
#Sta/Elev= 30
  4553.3 1680.49  4577.7 1677.28  4590.7 1672.32  4631.2 1650.90  4665.8 1635.98
  4684.6 1626.83  4723.2 1614.22  4742.2 1610.41  4756.7 1606.22  4818.9 1597.78
  4876.4 1591.55  4899.3 1587.39  4906.4 1584.87  4921.9 1583.50  4926.1 1584.53
  4932.3 1581.53  4938.7 1581.49  4964.4 1576.81  4995.1 1573.89  4998.5 1572.39
  4999.0 1571.89  5005.5 1572.39  5015.3 1573.68  5025.3 1573.35  5035.4 1576.40
  5043.5 1575.81  5054.7 1577.74  5072.1 1586.30  5088.8 1590.07  5166.6 1598.17
#Mann=4,-1,0
  4553.3    0.12       0  4921.9    0.07       0  4998.5    0.05       0
  5005.5    0.07       0
Bank Sta=4998.5,5005.5
Exp/Cntr=0.3,0.1

Type RM Length L Ch R = 1,9056,447,447,447
BEGIN DESCRIPTION:
WENZEL CREEK 19.0
END DESCRIPTION:
XS GIS Cut Line= 3
      2056225.00     13940324.99      2056125.00     13940575.00
      2056125.00     13940725.03
#Sta/Elev= 30
  4730.4 1626.50  4764.0 1622.22  4790.0 1618.49  4799.4 1616.09  4839.1 1599.89
  4847.9 1596.74  4854.3 1595.65  4877.0 1586.38  4884.3 1584.74  4912.5 1580.08
  4931.9 1575.47  4938.4 1574.56  4957.7 1573.89  4977.1 1571.37  4980.4 1570.72
  4989.7 1566.82  4990.2 1566.32  4996.3 1566.32  4996.8 1566.82  5009.1 1568.74
  5014.7 1571.34  5020.7 1572.91  5032.7 1578.79  5038.7 1580.18  5047.7 1581.34
  5086.7 1583.33  5102.1 1585.83  5125.3 1592.25  5131.7 1594.15  5149.7 1597.47
#Mann=6,-1,0
  4730.4    0.07       0  4764.0    0.12       0  4884.3    0.07       0
  4989.7    0.05       0  4996.8    0.07       0  5125.3   0.035       0
Bank Sta=4989.7,4996.8
Exp/Cntr=0.3,0.1

Type RM Length L Ch R = 1,8609,390,390,390
BEGIN DESCRIPTION:
WENZEL CREEK 18.0
END DESCRIPTION:
XS GIS Cut Line= 3
      2055875.02     13940174.97      2055725.00     13940425.00
      2055709.78     13940707.21
#Sta/Elev= 30
  4708.8 1613.96  4748.6 1609.04  4787.1 1601.92  4832.5 1592.15  4860.5 1587.71
  4881.5 1585.62  4920.0 1579.26  4934.4 1576.28  4944.5 1572.87  4960.6 1569.16
  4969.0 1568.30  4993.3 1563.37  4997.0 1563.34  5005.9 1561.00  5006.4 1560.50
  5013.1 1561.00  5013.8 1562.03  5018.5 1564.22  5024.5 1565.57  5036.9 1566.45
  5077.3 1572.95  5099.6 1581.32  5102.7 1584.05  5117.6 1590.69  5126.6 1594.09
  5134.5 1595.73  5183.7 1600.60  5201.7 1600.66  5228.8 1602.96  5283.0 1604.93
#Mann=3,-1,0
  4708.8    0.07       0  5005.9    0.05       0  5013.1    0.07       0
Bank Sta=5005.9,5013.1
Exp/Cntr=0.3,0.1

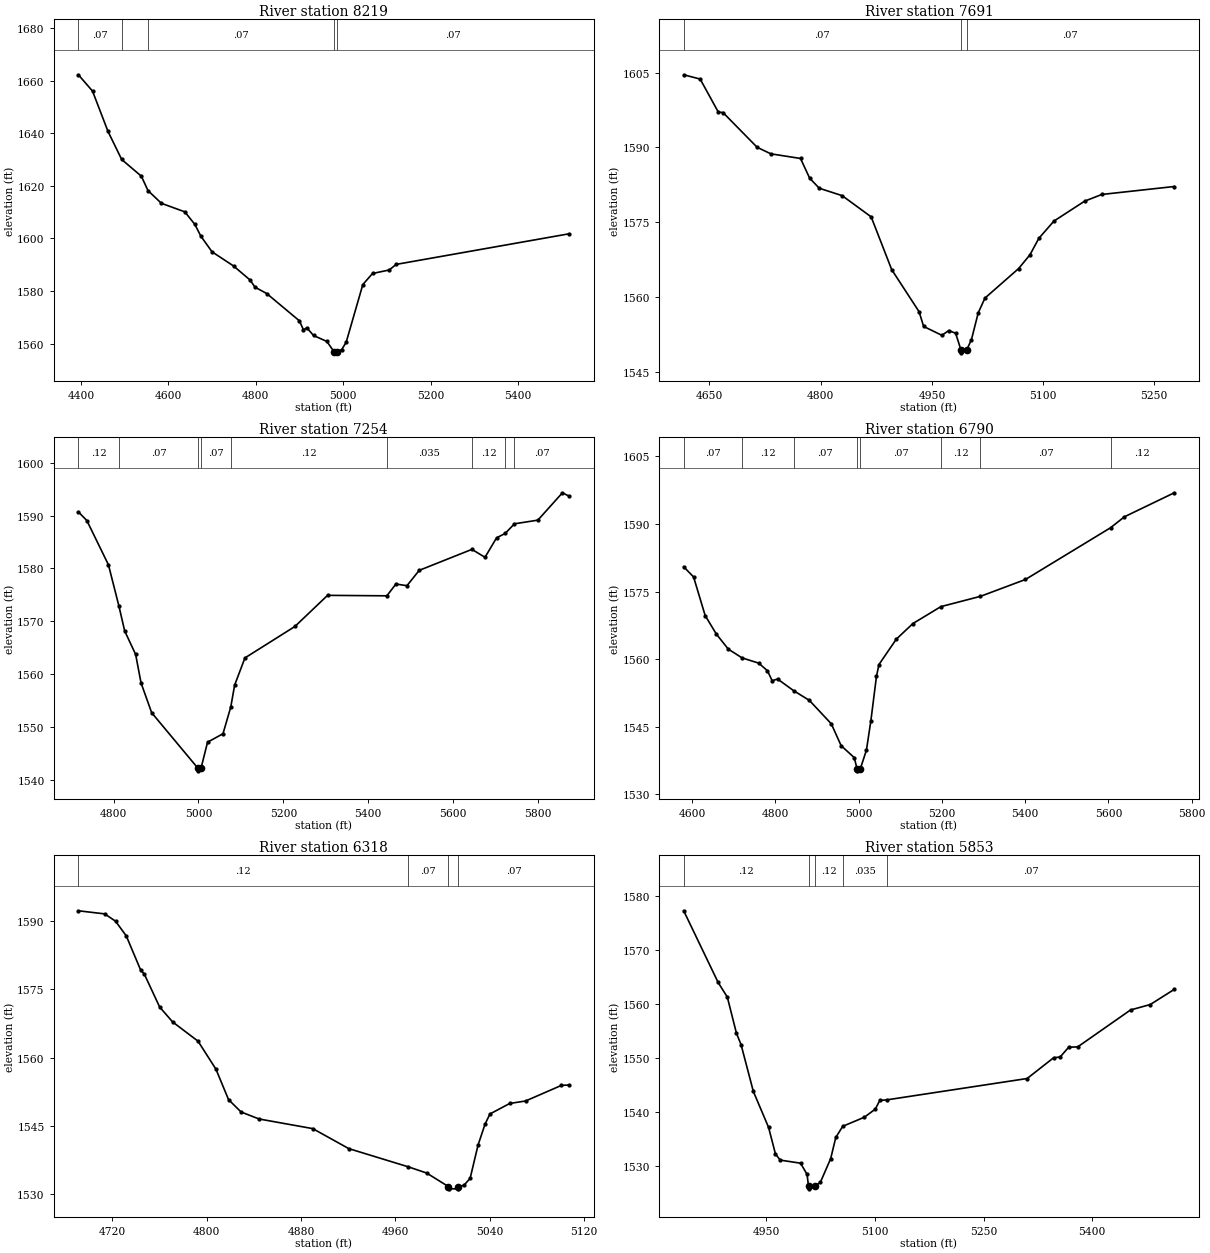
Type RM Length L Ch R = 1,8219,528,528,528
BEGIN DESCRIPTION:
WENZEL CREEK 17.0
END DESCRIPTION:
XS GIS Cut Line= 3
      2055774.97     13939775.03      2055400.75     13940248.89
      2055230.62     13940738.47
#Sta/Elev= 30
  4394.3 1662.18  4426.6 1655.99  4461.9 1640.71  4493.3 1630.01  4538.3 1623.65
  4553.5 1618.19  4584.2 1613.35  4637.7 1610.11  4660.7 1605.33  4674.4 1600.87
  4700.0 1594.92  4749.1 1589.55  4786.8 1584.24  4798.2 1581.49  4825.0 1579.08
  4899.9 1568.69  4909.1 1565.26  4916.8 1566.07  4932.1 1563.13  4962.8 1560.85
  4978.6 1557.04  4979.1 1556.54  4985.8 1557.04  4996.7 1557.80  5006.8 1560.57
  5044.9 1582.49  5067.1 1586.69  5105.3 1588.02  5121.1 1590.14  5516.4 1601.76
#Mann=5,-1,0
  4394.3    0.07       0  4493.3   0.035       0  4553.5    0.07       0
  4978.6    0.05       0  4985.8    0.07       0
Bank Sta=4978.6,4985.8
Exp/Cntr=0.3,0.1

Type RM Length L Ch R = 1,7691,437,437,437
BEGIN DESCRIPTION:
WENZEL CREEK 16.0
END DESCRIPTION:
XS GIS Cut Line= 3
      2055109.10     13939554.41      2055025.00     13939925.00
      2054984.08     13940203.80
#Sta/Elev= 30
  4615.2 1604.60  4637.4 1603.74  4662.0 1597.08  4668.2 1597.02  4714.3 1590.03
  4732.8 1588.72  4772.8 1587.79  4785.1 1583.84  4798.1 1581.81  4829.0 1580.32
  4868.1 1576.06  4895.8 1565.46  4932.7 1557.02  4938.9 1554.05  4963.5 1552.27
  4972.7 1553.22  4982.0 1552.70  4989.4 1549.25  4989.9 1548.75  4996.7 1549.25
  5003.4 1551.42  5012.5 1556.78  5021.6 1559.75  5067.0 1565.68  5082.2 1568.42
  5094.3 1571.75  5114.6 1575.21  5156.0 1579.21  5179.2 1580.56  5277.0 1582.16
#Mann=3,-1,0
  4615.2    0.07       0  4989.4    0.05       0  4996.7    0.07       0
Bank Sta=4989.4,4996.7
Exp/Cntr=0.3,0.1

Type RM Length L Ch R = 1,7254,464,464,464
BEGIN DESCRIPTION:
WENZEL CREEK 15.0
END DESCRIPTION:
XS GIS Cut Line= 3
      2054824.99     13939625.01      2054625.00     13939825.00
      2054765.33     13940686.32
#Sta/Elev= 30
  4717.2 1590.70  4737.1 1589.07  4788.0 1580.69  4812.9 1572.81  4826.2 1568.18
  4852.1 1563.72  4864.8 1558.33  4889.8 1552.70  4998.7 1542.20  4999.2 1541.70
  5006.1 1542.20  5021.4 1547.12  5057.8 1548.72  5076.2 1553.81  5085.2 1557.92
  5109.5 1563.07  5227.2 1569.02  5304.1 1574.91  5443.8 1574.82  5465.0 1577.05
  5491.1 1576.74  5520.0 1579.64  5644.1 1583.61  5674.9 1582.11  5702.2 1585.80
  5722.4 1586.62  5744.3 1588.45  5799.4 1589.14  5857.3 1594.32  5872.7 1593.69
#Mann=9,-1,0
  4717.2    0.12       0  4812.9    0.07       0  4998.7    0.05       0
  5006.1    0.07       0  5076.2    0.12       0  5443.8   0.035       0
  5644.1    0.12       0  5722.4   0.035       0  5744.3    0.07       0
Bank Sta=4998.7,5006.1
Exp/Cntr=0.3,0.1

Type RM Length L Ch R = 1,6790,472,472,472
BEGIN DESCRIPTION:
WENZEL CREEK 14.0
END DESCRIPTION:
XS GIS Cut Line= 3
      2054390.33     13939408.62      2054175.00     13939775.00
      2054116.04     13940526.62
#Sta/Elev= 30
  4579.4 1580.48  4603.1 1578.24  4631.0 1569.67  4657.7 1565.58  4686.6 1562.22
  4719.6 1560.28  4759.7 1559.11  4780.6 1557.43  4792.0 1555.20  4804.9 1555.59
  4843.5 1553.01  4881.5 1550.84  4934.1 1545.65  4957.8 1540.79  4989.4 1538.14
  4995.7 1535.72  4996.2 1535.22  5004.0 1535.72  5018.5 1539.81  5029.1 1546.27
  5042.6 1556.16  5048.6 1558.80  5090.4 1564.44  5130.3 1567.90  5197.3 1571.64
  5292.6 1573.93  5400.7 1577.67  5605.1 1589.14  5638.4 1591.57  5758.3 1596.90
#Mann=8,-1,0
  4579.4    0.07       0  4719.6    0.12       0  4843.5    0.07       0
  4995.7    0.05       0  5004.0    0.07       0  5197.3    0.12       0
  5292.6    0.07       0  5605.1    0.12       0
Bank Sta=4995.7,5004
Exp/Cntr=0.3,0.1

Type RM Length L Ch R = 1,6318,465,465,465
BEGIN DESCRIPTION:
WENZEL CREEK 13.0
END DESCRIPTION:
XS GIS Cut Line= 3
      2053824.99     13939275.04      2053775.00     13939575.00
      2053725.00     13939675.00
#Sta/Elev= 30
  4691.3 1592.27  4713.6 1591.59  4722.8 1589.98  4731.9 1586.75  4744.1 1579.24
  4747.1 1578.41  4760.2 1571.12  4771.2 1567.85  4792.7 1563.63  4807.9 1557.48
  4818.6 1550.78  4829.2 1548.07  4844.4 1546.53  4890.0 1544.41  4920.5 1540.02
  4970.8 1536.03  4986.5 1534.66  5005.0 1531.68  5005.5 1531.18  5012.8 1531.18
  5013.3 1531.68  5018.1 1531.95  5023.4 1533.48  5030.1 1540.78  5036.0 1545.36
  5040.2 1547.63  5057.0 1549.94  5070.4 1550.48  5100.8 1553.91  5107.2 1553.99
#Mann=4,-1,0
  4691.3    0.12       0  4970.8    0.07       0  5005.0    0.05       0
  5013.3    0.07       0
Bank Sta=5005,5013.3
Exp/Cntr=0.3,0.1

Type RM Length L Ch R = 1,5853,422,422,422
BEGIN DESCRIPTION:
WENZEL CREEK 12.0
END DESCRIPTION:
XS GIS Cut Line= 3
      2053425.01     13939224.98      2053375.00     13939375.00
      2053452.84     13939887.80
#Sta/Elev= 30
  4836.4 1577.27  4883.9 1564.00  4896.6 1561.28  4909.2 1554.58  4915.5 1552.50
  4932.5 1543.81  4953.5 1537.16  4963.0 1532.23  4969.6 1531.10  4997.6 1530.53
  5006.6 1528.45  5008.6 1526.28  5009.1 1525.78  5017.0 1526.28  5024.9 1526.97
  5039.2 1531.39  5046.2 1535.29  5055.8 1537.36  5085.6 1539.04  5100.8 1540.55
  5106.9 1542.15  5116.8 1542.26  5310.2 1546.21  5346.8 1550.06  5355.7 1550.19
  5367.5 1552.00  5380.0 1552.07  5452.8 1558.90  5480.1 1559.91  5513.2 1562.72
#Mann=5,-1,0
  4836.4    0.12       0  5008.6    0.05       0  5017.0    0.12       0
  5055.8   0.035       0  5116.8    0.07       0
Bank Sta=5008.6,5017
Exp/Cntr=0.3,0.1

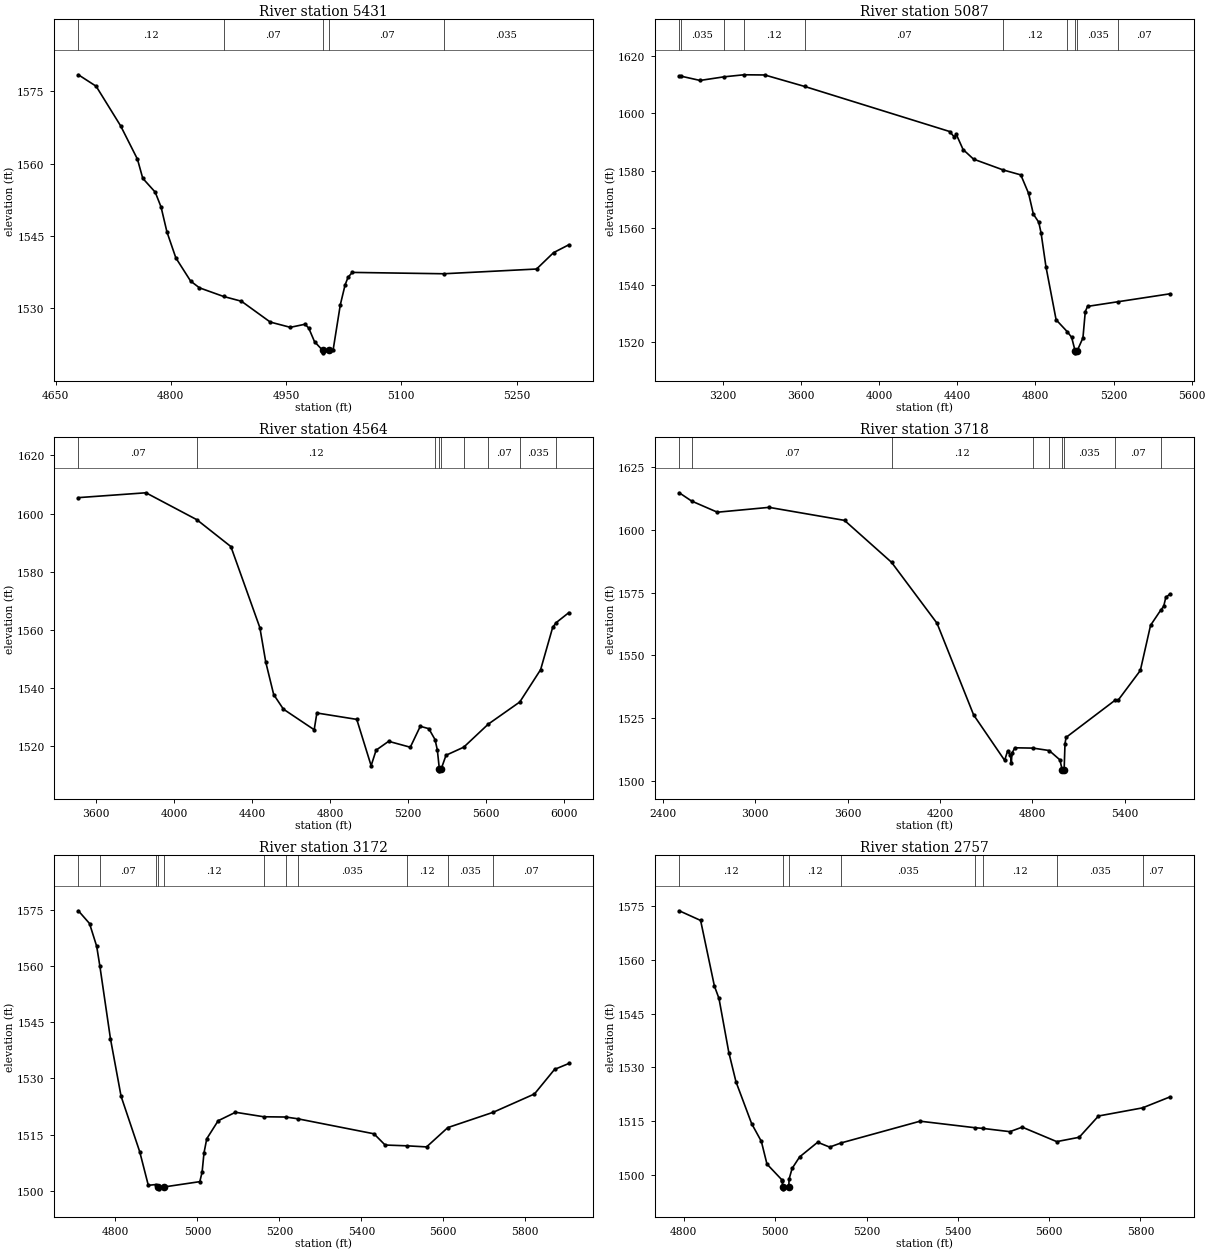
Type RM Length L Ch R = 1,5431,344,344,344
BEGIN DESCRIPTION:
WENZEL CREEK 11.0
END DESCRIPTION:
XS GIS Cut Line= 3
      2053224.99     13938925.01      2053025.00     13939175.00
      2052938.95     13939481.51
#Sta/Elev= 30
  4679.6 1578.37  4702.7 1576.00  4734.6 1567.80  4756.5 1560.90  4763.4 1556.94
  4779.6 1554.08  4787.2 1551.02  4794.9 1545.84  4806.5 1540.46  4825.7 1535.67
  4837.2 1534.27  4868.6 1532.48  4891.9 1531.49  4929.4 1527.18  4955.5 1526.09
  4974.7 1526.73  4979.5 1525.93  4987.0 1523.13  4997.7 1521.31  4998.2 1520.81
  5006.1 1521.31  5011.2 1521.36  5020.6 1530.76  5026.8 1534.86  5030.7 1536.46
  5036.2 1537.46  5155.4 1537.18  5276.1 1538.16  5298.2 1541.55  5318.1 1543.18
#Mann=5,-1,0
  4679.6    0.12       0  4868.6    0.07       0  4997.7    0.05       0
  5006.1    0.07       0  5155.4   0.035       0
Bank Sta=4997.7,5006.1
Exp/Cntr=0.3,0.1

Type RM Length L Ch R = 1,5087,523,523,523
BEGIN DESCRIPTION:
WENZEL CREEK 10.0
END DESCRIPTION:
XS GIS Cut Line= 3
      2054831.26     13938495.43      2052849.63     13938899.63
      2052838.61     13939386.97
#Sta/Elev= 30
  2977.7 1613.05  2984.4 1613.00  3084.1 1611.47  3207.5 1612.74  3308.8 1613.45
  3415.2 1613.38  3619.1 1609.38  4361.3 1593.63  4385.8 1591.66  4394.9 1592.72
  4430.3 1587.33  4483.7 1583.98  4635.7 1580.19  4725.6 1578.47  4765.4 1572.02
  4789.9 1564.76  4817.5 1561.93  4829.3 1558.22  4854.2 1546.44  4906.3 1527.85
  4964.4 1523.61  4985.9 1521.69  5004.2 1516.80  5004.7 1516.30  5012.7 1516.80
  5043.6 1521.52  5055.6 1530.70  5067.1 1532.53  5224.4 1534.17  5487.6 1536.91
#Mann=10,-1,0
  2977.7    0.07       0  2984.4   0.035       0  3207.5    0.07       0
  3308.8    0.12       0  3619.1    0.07       0  4635.7    0.12       0
  4964.4   0.035       0  5004.2   0.035       0  5012.7   0.035       0
  5224.4    0.07       0
Bank Sta=5004.2,5012.7
Exp/Cntr=0.3,0.1

Type RM Length L Ch R = 1,4564,846,846,846
BEGIN DESCRIPTION:
WENZEL CREEK 9.0
END DESCRIPTION:
XS GIS Cut Line= 3
      2053838.09     13937681.83      2052575.00     13938475.00
      2051733.82     13939059.50
#Sta/Elev= 30
  3508.8 1605.47  3855.3 1607.14  4116.6 1597.86  4291.1 1588.61  4439.8 1560.68
  4470.1 1548.79  4510.7 1537.64  4560.4 1532.63  4718.4 1525.53  4732.2 1531.30
  4936.8 1529.10  5010.5 1513.15  5036.1 1518.51  5100.3 1521.55  5211.4 1519.51
  5262.6 1526.72  5306.4 1525.90  5338.4 1522.13  5350.2 1518.54  5360.6 1511.88
  5361.1 1511.38  5369.1 1511.88  5394.7 1516.75  5485.5 1519.53  5611.1 1527.45
  5773.1 1535.10  5879.9 1546.23  5941.8 1560.80  5960.4 1562.46  6024.6 1565.86
#Mann=9,-1,0
  3508.8    0.07       0  4116.6    0.12       0  5338.4    0.07       0
  5360.6    0.05       0  5369.1    0.07       0  5485.5    0.12       0
  5611.1    0.07       0  5773.1   0.035       0  5960.4    0.07       0
Bank Sta=5360.6,5369.1
Exp/Cntr=0.3,0.1

Type RM Length L Ch R = 1,3718,546,546,546
BEGIN DESCRIPTION:
WENZEL CREEK 8.0
END DESCRIPTION:
XS GIS Cut Line= 3
      2054244.49     13937464.17      2051872.98     13938217.64
      2051274.96     13938575.02
#Sta/Elev= 30
  2507.3 1614.71  2587.6 1611.42  2754.7 1606.98  3090.6 1608.91  3580.5 1603.73
  3886.0 1587.05  4181.3 1562.82  4419.1 1526.34  4620.4 1508.28  4639.3 1511.94
  4658.1 1510.29  4664.4 1507.35  4667.6 1511.04  4686.4 1513.28  4805.0 1513.15
  4909.5 1512.19  4979.2 1508.48  4993.9 1504.61  4994.4 1504.11  5006.8 1504.61
  5012.4 1514.90  5019.3 1517.41  5336.1 1532.12  5357.1 1532.18  5501.6 1544.03
  5568.0 1562.00  5634.3 1568.05  5653.2 1569.53  5667.1 1573.11  5692.3 1574.35
#Mann=9,-1,0
  2507.3    0.12       0  2587.6    0.07       0  3886.0    0.12       0
  4805.0    0.07       0  4909.5   0.035       0  4993.9   0.035       0
  5006.8   0.035       0  5336.1    0.07       0  5634.3   0.035       0
Bank Sta=4993.9,5006.8
Exp/Cntr=0.3,0.1

Type RM Length L Ch R = 1,3172,415,415,415
BEGIN DESCRIPTION:
WENZEL CREEK 7.0
END DESCRIPTION:
XS GIS Cut Line= 3
      2052424.97     13937725.02      2052175.00     13937875.00
      2051274.95     13937975.01
#Sta/Elev= 30
  4709.4 1574.78  4736.6 1571.38  4754.1 1565.29  4761.9 1559.97  4787.7 1540.60
  4813.6 1525.25  4859.1 1510.43  4880.1 1501.45  4897.9 1501.65  4904.8 1501.01
  4905.3 1500.51  4918.3 1501.01  5005.8 1502.43  5011.4 1504.98  5016.0 1510.10
  5022.8 1513.90  5050.6 1518.70  5092.9 1520.96  5161.9 1519.76  5216.1 1519.69
  5244.9 1519.22  5430.9 1515.21  5458.1 1512.21  5511.6 1512.00  5559.3 1511.71
  5611.1 1516.87  5721.7 1520.95  5822.6 1525.85  5871.6 1532.41  5906.5 1533.99
#Mann=11,-1,0
  4709.4    0.12       0  4761.9    0.07       0  4897.9    0.12       0
  4904.8    0.05       0  4918.3    0.12       0  5161.9   0.035       0
  5216.1    0.07       0  5244.9   0.035       0  5511.6    0.12       0
  5611.1   0.035       0  5721.7    0.07       0
Bank Sta=4904.8,4918.3
Exp/Cntr=0.3,0.1

Type RM Length L Ch R = 1,2757,443,443,443
BEGIN DESCRIPTION:
WENZEL CREEK 6.0
END DESCRIPTION:
XS GIS Cut Line= 3
      2052375.01     13937575.00      2052175.00     13937525.00
      2051383.37     13937880.84
#Sta/Elev= 30
  4789.9 1573.74  4836.7 1571.04  4866.9 1552.73  4876.9 1549.28  4898.5 1534.17
  4914.2 1525.99  4948.5 1514.31  4969.7 1509.38  4982.0 1503.04  5014.0 1498.73
  5015.8 1498.23  5016.3 1496.63  5016.8 1496.13  5029.8 1496.63  5030.4 1498.83
  5037.1 1501.83  5053.5 1505.04  5093.0 1509.13  5119.3 1507.78  5144.0 1508.93
  5317.3 1515.01  5436.8 1513.20  5455.3 1512.99  5514.0 1512.09  5541.0 1513.35
  5616.6 1509.31  5665.8 1510.52  5708.0 1516.46  5804.5 1518.73  5864.0 1521.76
#Mann=8,-1,0
  4789.9    0.12       0  5016.3    0.05       0  5029.8    0.12       0
  5144.0   0.035       0  5436.8    0.07       0  5455.3    0.12       0
  5616.6   0.035       0  5804.5    0.07       0
Bank Sta=5016.3,5029.8
Exp/Cntr=0.3,0.1

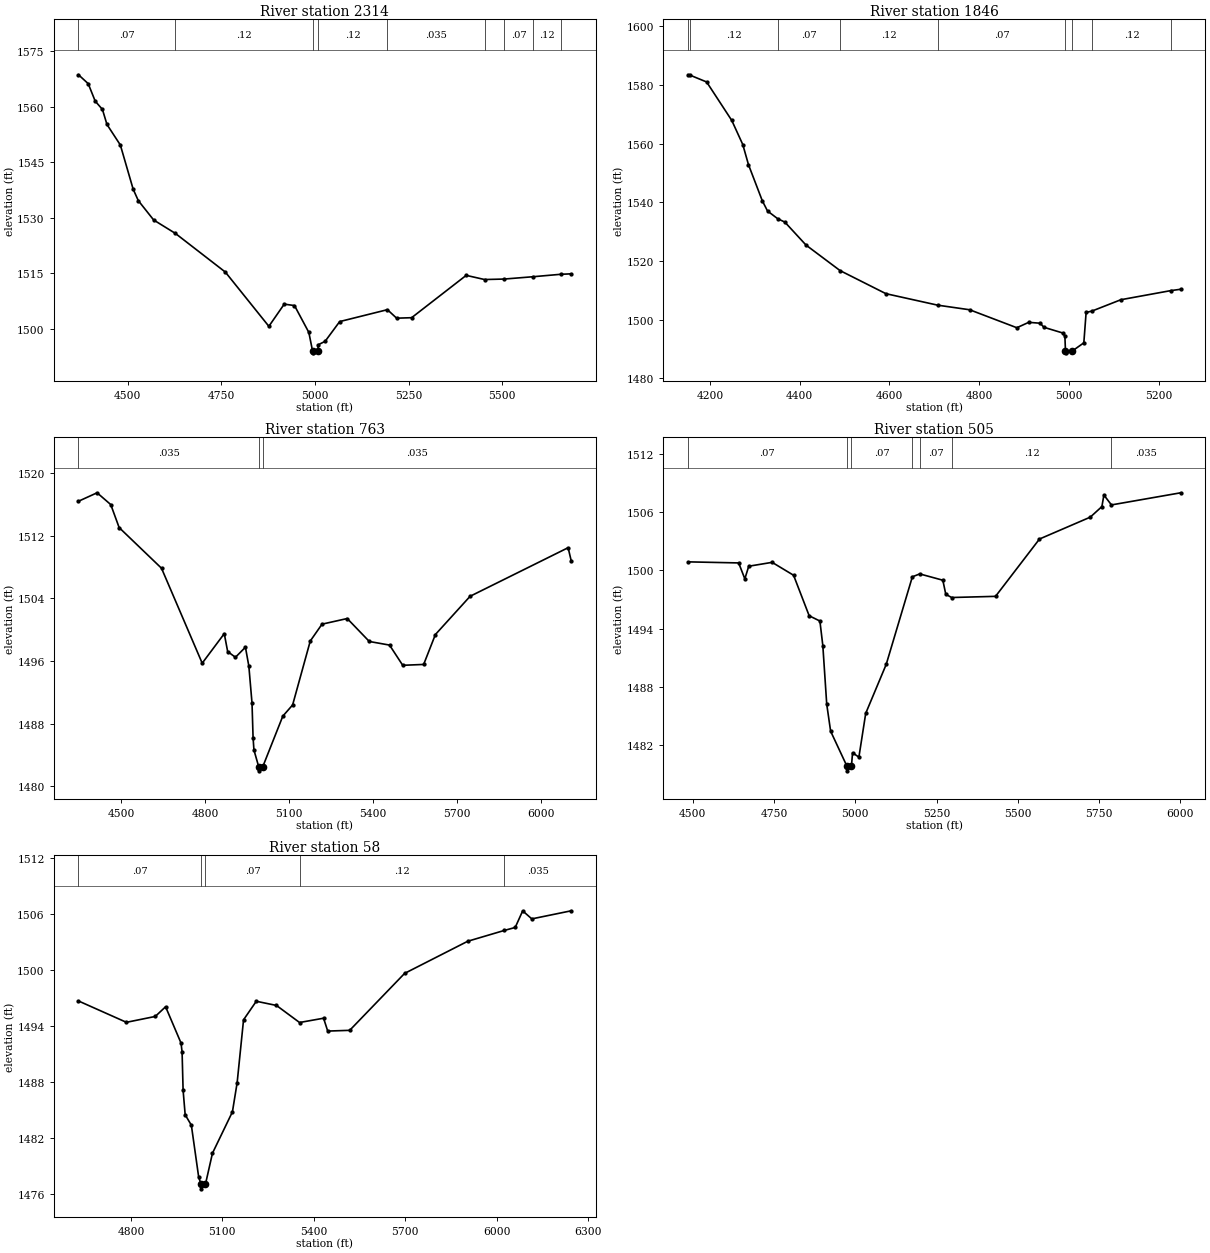
Type RM Length L Ch R = 1,2314,468,468,468
BEGIN DESCRIPTION:
WENZEL CREEK 5.0
END DESCRIPTION:
XS GIS Cut Line= 3
      2052225.00     13936625.00      2051925.00     13937175.00
      2051459.76     13937682.94
#Sta/Elev= 30
  4368.8 1568.64  4394.7 1566.24  4413.4 1561.51  4432.7 1559.27  4444.8 1555.20
  4480.5 1549.65  4514.7 1537.71  4528.4 1534.62  4569.4 1529.38  4627.4 1525.75
  4760.7 1515.30  4876.9 1500.63  4917.9 1506.63  4945.3 1506.24  4983.6 1498.98
  4993.5 1493.96  4994.0 1493.46  5007.1 1493.96  5009.2 1495.67  5027.0 1496.57
  5065.9 1501.91  5193.3 1505.13  5217.9 1502.83  5257.9 1502.96  5403.6 1514.41
  5452.6 1513.28  5505.0 1513.41  5582.3 1514.04  5656.1 1514.70  5684.1 1514.82
#Mann=9,-1,0
  4368.8    0.07       0  4627.4    0.12       0  4993.5    0.05       0
  5007.1    0.12       0  5193.3   0.035       0  5452.6    0.12       0
  5505.0    0.07       0  5582.3    0.12       0  5656.1   0.035       0
Bank Sta=4993.5,5007.1
Exp/Cntr=0.3,0.1

Type RM Length L Ch R = 1,1846,1083,1083,1083
BEGIN DESCRIPTION:
WENZEL CREEK 4.0
END DESCRIPTION:
XS GIS Cut Line= 3
      2052125.01     13936374.99      2051525.00     13936975.00
      2051375.02     13937174.97
#Sta/Elev= 30
  4151.0 1583.46  4155.6 1583.33  4192.6 1581.01  4248.7 1567.89  4273.2 1559.69
  4285.9 1552.83  4316.6 1540.58  4328.3 1537.06  4350.9 1534.44  4367.0 1533.27
  4414.2 1525.44  4490.1 1516.75  4592.3 1508.89  4707.6 1504.98  4779.0 1503.41
  4884.1 1497.29  4910.5 1499.13  4936.0 1498.83  4944.5 1497.44  4986.9 1495.48
  4991.2 1494.38  4992.5 1489.24  4993.0 1488.74  5006.5 1489.24  5033.4 1492.15
  5038.5 1502.49  5051.7 1502.98  5115.9 1506.83  5227.4 1509.94  5249.5 1510.40
#Mann=9,-1,0
  4151.0    0.07       0  4155.6    0.12       0  4350.9    0.07       0
  4490.1    0.12       0  4707.6    0.07       0  4992.5    0.05       0
  5006.5    0.07       0  5051.7    0.12       0  5227.4    0.07       0
Bank Sta=4992.5,5006.5
Exp/Cntr=0.3,0.1

Type RM Length L Ch R = 1,763,258,258,258
BEGIN DESCRIPTION:
WENZEL CREEK 3.0
END DESCRIPTION:
XS GIS Cut Line= 3
      2051395.62     13935355.31      2051301.94     13936001.55
      2051252.46     13937109.45
#Sta/Elev= 30
  4347.0 1516.39  4413.5 1517.47  4462.4 1515.96  4492.3 1513.03  4643.8 1507.84
  4789.3 1495.72  4868.2 1499.49  4880.3 1497.21  4908.1 1496.47  4943.9 1497.76
  4956.1 1495.34  4967.4 1490.63  4971.2 1486.22  4974.3 1484.64  4991.5 1482.48
  4992.0 1481.98  5005.6 1482.48  5077.5 1488.96  5112.6 1490.39  5175.7 1498.55
  5217.7 1500.70  5307.8 1501.42  5386.8 1498.49  5459.1 1498.03  5506.3 1495.45
  5581.1 1495.56  5623.1 1499.38  5747.2 1504.26  6097.6 1510.46  6109.0 1508.74
#Mann=3,-1,0
  4347.0   0.035       0  4991.5   0.035       0  5005.6   0.035       0
Bank Sta=4991.5,5005.6
Exp/Cntr=0.3,0.1

Type RM Length L Ch R = 1,505,447,447,447
BEGIN DESCRIPTION:
WENZEL CREEK 2.0
END DESCRIPTION:
XS GIS Cut Line= 3
      2051132.26     13935309.12      2051140.29     13935824.16
      2051090.75     13936824.33
#Sta/Elev= 30
  4484.9 1500.86  4640.9 1500.75  4659.9 1499.11  4671.9 1500.41  4743.9 1500.81
  4809.9 1499.48  4857.9 1495.31  4890.9 1494.77  4899.9 1492.24  4911.9 1486.21
  4923.9 1483.43  4973.8 1479.85  4974.3 1479.35  4988.0 1479.85  4991.4 1481.21
  5010.9 1480.76  5031.9 1485.27  5095.0 1490.31  5175.4 1499.32  5198.1 1499.62
  5269.2 1498.97  5278.3 1497.52  5296.4 1497.19  5431.4 1497.31  5566.6 1503.21
  5722.8 1505.46  5758.7 1506.55  5764.8 1507.74  5788.0 1506.72  6001.4 1507.97
#Mann=7,-1,0
  4484.9    0.07       0  4973.8    0.05       0  4988.0    0.07       0
  5175.4    0.12       0  5198.1    0.07       0  5296.4    0.12       0
  5788.0   0.035       0
Bank Sta=4973.8,4988
Exp/Cntr=0.3,0.1

Type RM Length L Ch R = 1,58,0,0,0
BEGIN DESCRIPTION:
WENZEL CREEK 1.0
END DESCRIPTION:
XS GIS Cut Line= 4
      2051053.22     13935152.64      2050881.63     13935482.59
      2050880.74     13935717.15      2050917.80     13936726.51
#Sta/Elev= 30
  4628.1 1496.68  4785.3 1494.39  4879.9 1495.02  4913.8 1496.06  4964.5 1492.16
  4967.9 1491.21  4971.2 1487.12  4978.0 1484.47  4998.3 1483.35  5022.5 1477.74
  5030.4 1477.02  5030.9 1476.52  5044.6 1477.02  5067.5 1480.34  5133.0 1484.78
  5148.5 1487.91  5169.5 1494.66  5211.3 1496.65  5277.5 1496.20  5353.2 1494.37
  5432.0 1494.83  5445.6 1493.45  5517.7 1493.53  5697.8 1499.64  5904.9 1503.09
  6024.8 1504.25  6060.6 1504.57  6085.1 1506.35  6115.1 1505.49  6244.6 1506.36
#Mann=5,-1,0
  4628.1    0.07       0  5030.4    0.05       0  5044.6    0.07       0
  5353.2    0.12       0  6024.8   0.035       0
Bank Sta=5030.4,5044.6
Exp/Cntr=0.3,0.1

Chan Stop Cuts=-1