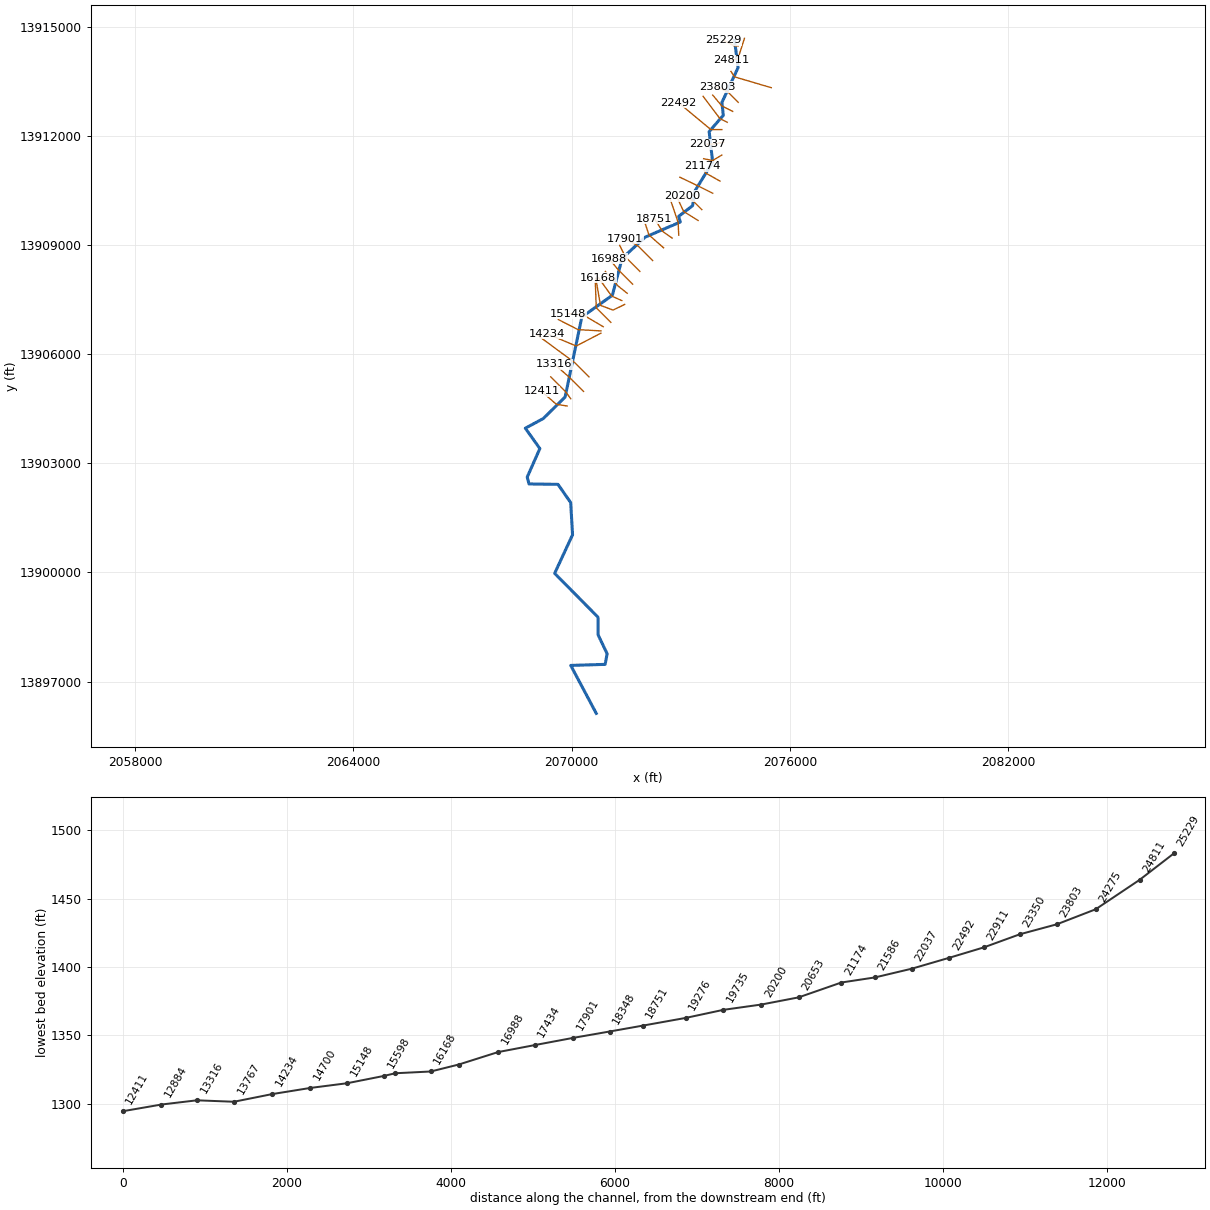
--- WERNER CREEK.prj (project) ---

Proj Title=WERNER CREEK Base Level Engineering
Current Plan=p01
Default Exp/Contr=0.3,0.1
English Units
Geom File=g01
Flow File=f01
Plan File=p01
Y Axis Title=Elevation
X Axis Title(PF)=Main Channel Distance
X Axis Title(XS)=Station
BEGIN DESCRIPTION:
WERNER CREEK
END DESCRIPTION:
DSS Export Rating Curves= 0
DSS Export Rating Curve Sorted= 0
DSS Export Volume Flow Curves= 0
DXF OffsetX= 0
DXF OffsetY= 0
DXF ScaleX= 1
DXF ScaleY= 10

--- WERNER CREEK.p01 (plan) ---

Plan Title=Multiple Run
Short Identifier=Multiple
Geom File=g01
Flow File=f01
Subcritical Flow
K Sum by GR= 0
Std Step Tol= 0.01
Critical Tol= 0.01
Num of Std Step Trials= 20
Max Error Tol= 0.3
Flow Tol Ratio= 0.001
Split Flow NTrial= 30
Split Flow Tol= 0.02
Split Flow Ratio= 0.02
Log Output Level= 0
Friction Slope Method= 1
Unsteady Friction Slope Method= 2
Unsteady Bridges Friction Slope Method= 1
Parabolic Critical Depth
Global Vel Dist=  1 , 1 , 1
Global Log Level= 0
CheckData=True
Encroach Param= -1, 0, 0, 0
BEGIN DESCRIPTION:
Multiple Run
END DESCRIPTION:

--- WERNER CREEK.f01 (steady flow) ---

Flow Title=Multiple
Program Version=4.10
Number of Profiles= 7
Profile Names=10-year,25-year,50-year,1pct_min,100-year,1pct_plu,500-year
River Rch & RM=WERNER CREEK,Reach-1         ,25229
     851    1458    2045    1397    2788    5563    5126
River Rch & RM=WERNER CREEK,Reach-1         ,23803
    1630    2883    4130    2873    5733   11438   10941
River Rch & RM=WERNER CREEK,Reach-1         ,20653
    2015    3575    5130    3566    7115   14197   13543
River Rch & RM=WERNER CREEK,Reach-1         ,17901
    2140    3798    5450    3787    7555   15074   14367
River Rch & RM=WERNER CREEK,Reach-1         ,15148
    2834    5089    7358    5144   10264   20479   19775
River Rch & RM=WERNER CREEK,Reach-1         ,11563
    3609    6522    9468    6638   13245   26427   25665
River Rch & RM=WERNER CREEK,Reach-1         ,4278
    5272    9674   14188   10037   20027   39958   39519
Boundary for River Rch & Prof#=WERNER CREEK,Reach-1         , 1
Up Type= 0
Dn Type= 3
Dn Slope=0.005
Boundary for River Rch & Prof#=WERNER CREEK,Reach-1         , 2
Up Type= 0
Dn Type= 3
Dn Slope=0.005
Boundary for River Rch & Prof#=WERNER CREEK,Reach-1         , 3
Up Type= 0
Dn Type= 3
Dn Slope=0.005
Boundary for River Rch & Prof#=WERNER CREEK,Reach-1         , 4
Up Type= 0
Dn Type= 3
Dn Slope=0.005
Boundary for River Rch & Prof#=WERNER CREEK,Reach-1         , 5
Up Type= 0
Dn Type= 3
Dn Slope=0.005
Boundary for River Rch & Prof#=WERNER CREEK,Reach-1         , 6
Up Type= 0
Dn Type= 3
Dn Slope=0.005
Boundary for River Rch & Prof#=WERNER CREEK,Reach-1         , 7
Up Type= 0
Dn Type= 3
Dn Slope=0.005
DSS Import GetInterval= 0
DSS Import GetPeak= 0
DSS Import FillOption= 0

--- WERNER CREEK.g01 (geometry) ---

Geom Title=Existing Conditions
Program Version=4.10

River Reach=WERNER CREEK    ,Reach-1
Reach XY= 30
        2074475.       13914625.      2074572.93     13913880.86
      2074127.36     13912919.48      2074166.02     13912568.34
      2073777.24     13912119.07      2073873.64     13911284.65
      2073378.61      13910473.5      2073321.44     13910083.15
      2072938.42     13909788.33      2072985.54     13909635.52
      2072018.85     13909217.09      2071385.63       13908635.
      2071116.86     13907618.94      2070278.75     13907023.45
      2069819.53     13904822.55      2069219.42     13904230.58
      2068725.97     13903964.71      2069125.06     13903405.01
      2068777.26     13902619.44       2068828.5     13902432.79
       2069623.5     13902421.39      2069972.62     13901919.47
      2070023.64     13901034.65      2069532.32      13899974.9
        2070723.     13898769.18      2070727.38     13898280.53
      2070973.78      13897764.5      2070919.29     13897472.41
      2069974.24     13897443.33        2070675.       13896125.

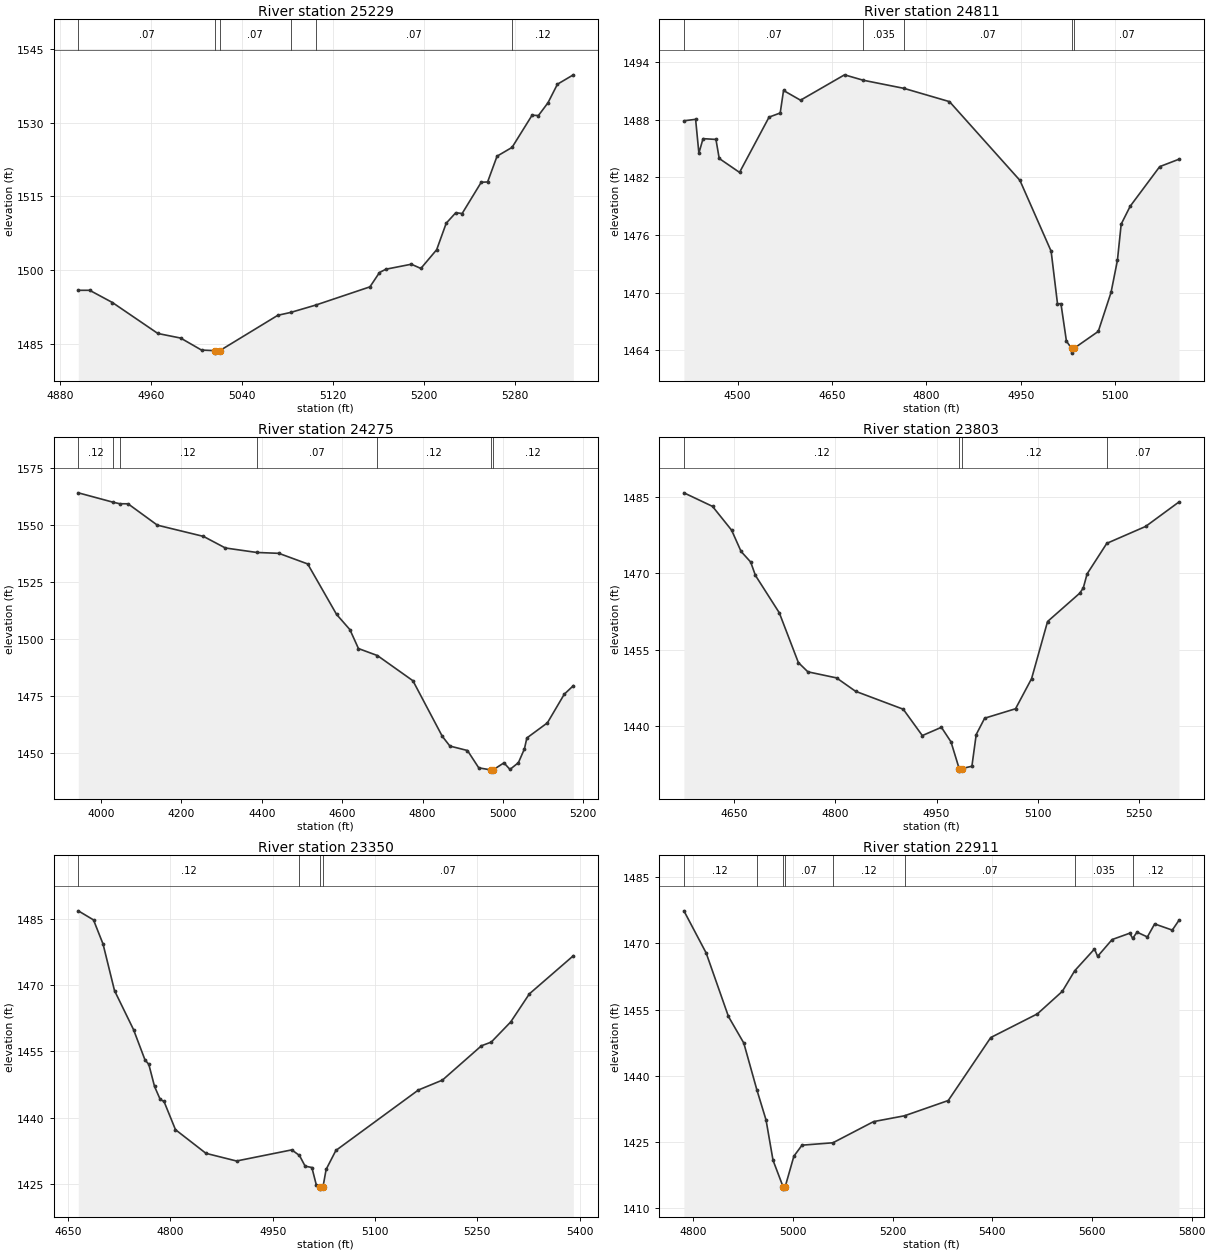
Type RM Length L Ch R = 1 ,25229   ,418,418,418
BEGIN DESCRIPTION:
WERNER CREEK 55.0
END DESCRIPTION:
XS GIS Cut Line= 3
      2074575.01       13914475.        2074475.       13914475.
      2074175.02     13914624.99
#Sta/Elev= 30
  4895.9 1495.86  4905.9 1495.86  4925.9 1493.37  4965.9 1487.06  4985.9 1486.13
  5004.3 1483.68  5016.3 1483.56  5016.5 1483.06  5020.3 1483.56  5071.4 1490.77
  5082.7 1491.35  5104.6 1492.84  5152.4 1496.56  5160.8 1499.48  5166.4 1500.15
  5188.8 1501.17  5197.2 1500.31  5211.1 1504.13  5219.5 1509.53  5227.9 1511.66
  5233.5  1511.5  5250.3 1517.87  5255.9 1517.93  5264.2 1523.18  5277.4 1524.97
    5295 1531.52  5300.6 1531.46    5309 1534.06  5317.3 1537.84  5331.3 1539.75
#Mann= 6 ,-1 , 0
  4895.9     .07       0  5016.3     .05       0  5020.3     .07       0
  5082.7    .035       0  5104.6     .07       0  5277.4     .12       0
Bank Sta=5016.3,5020.3
XS Rating Curve= 0 ,0
Exp/Cntr=0.3,0.1

Type RM Length L Ch R = 1 ,24811   ,536,536,536
BEGIN DESCRIPTION:
WERNER CREEK 54.0
END DESCRIPTION:
XS GIS Cut Line= 3
      2074746.78     13914684.01      2074567.08     13914116.26
      2074378.53     13914085.26
#Sta/Elev= 30
  4414.8 1487.89  4433.4 1488.04  4438.6 1484.52  4445.2 1486.03  4465.7 1485.95
  4470.9 1483.97  4503.2 1482.52  4550.1 1488.27  4567.8  1488.7  4573.1 1491.04
  4600.1 1490.03    4670 1492.67  4699.6 1492.11  4764.6 1491.26  4836.8 1489.88
  4948.7 1481.69  4998.3 1474.32  5008.4 1468.86  5013.9 1468.86  5022.6 1464.97
  5030.7 1464.22  5030.9 1463.72  5034.7 1464.22  5073.2 1465.98  5093.5 1470.04
  5103.6 1473.36  5109.6 1477.14  5123.9    1479  5170.8 1483.12  5201.4 1483.89
#Mann= 5 ,-1 , 0
  4414.8     .07       0  4699.6    .035       0  4764.6     .07       0
  5030.7     .05       0  5034.7     .07       0
Bank Sta=5030.7,5034.7
XS Rating Curve= 0 ,0
Exp/Cntr=0.3,0.1

Type RM Length L Ch R = 1 ,24275   ,472,472,472
BEGIN DESCRIPTION:
WERNER CREEK 53.0
END DESCRIPTION:
XS GIS Cut Line= 3
      2075483.71      13913327.2        2074475.       13913625.
      2074375.02     13913774.98
#Sta/Elev= 30
  3943.4 1564.14  4030.9 1559.98  4046.6 1559.36  4067.2 1559.33  4140.2 1549.97
  4254.9 1545.05  4309.3 1539.98  4387.5 1538.01  4442.5 1537.63  4514.3 1532.98
  4586.1 1510.88  4619.4 1504.18  4640.6 1495.91  4687.8 1492.84  4776.2  1481.8
  4849.2 1457.47  4868.2 1453.18  4911.9 1451.23    4940 1443.64  4971.3  1442.7
  4971.5  1442.2  4975.3  1442.7  5002.7 1445.83  5017.7 1442.94  5038.7 1445.91
  5053.7 1451.96  5059.7 1456.73  5110.8 1463.35  5152.9 1475.92  5175.4 1479.64
#Mann= 7 ,-1 , 0
  3943.4     .12       0  4030.9     .07       0  4046.6     .12       0
  4387.5     .07       0  4687.8     .12       0  4971.3     .05       0
  4975.3     .12       0
Bank Sta=4971.3,4975.3
XS Rating Curve= 0 ,0
Exp/Cntr=0.3,0.1

Type RM Length L Ch R = 1 ,23803   ,453,453,453
BEGIN DESCRIPTION:
WERNER CREEK 52.0
END DESCRIPTION:
XS GIS Cut Line= 3
      2074574.98     13912925.02        2074275.       13913225.
      2073989.51     13913345.19
#Sta/Elev= 30
  4575.4 1485.73  4617.8 1483.08  4646.1 1478.42  4660.2 1474.25  4674.4 1472.18
  4681.4 1469.57  4716.8 1462.25  4745.1  1452.5  4759.2 1450.69  4801.7  1449.5
  4829.9 1446.88  4900.6 1443.37  4928.9 1438.21  4957.2 1439.83  4971.4 1436.98
  4983.5 1431.75  4983.8 1431.25  4987.5 1431.75  5002.4 1432.21  5008.8 1438.42
  5021.3 1441.61  5067.1 1443.46  5090.9 1449.36  5114.6 1460.54  5162.1 1466.06
  5167.5 1467.08  5173.2 1469.86  5202.4 1475.84    5260 1479.15  5309.4 1483.94
#Mann= 4 ,-1 , 0
  4575.4     .12       0  4983.5     .05       0  4987.5     .12       0
  5202.4     .07       0
Bank Sta=4983.5,4987.5
XS Rating Curve= 0 ,0
Exp/Cntr=0.3,0.1

Type RM Length L Ch R = 1 ,23350   ,439,439,439
BEGIN DESCRIPTION:
WERNER CREEK 51.0
END DESCRIPTION:
XS GIS Cut Line= 3
      2074424.96     13912675.02        2074125.       13912825.
      2073874.99     13913125.01
#Sta/Elev= 30
    4665 1486.75  4687.3  1484.7  4701.3 1479.25  4718.1 1468.74    4746 1459.93
  4762.8 1453.09  4768.4 1452.09  4776.8  1447.1  4785.1 1444.17  4790.7 1443.71
  4807.5 1437.34  4852.2    1432    4897 1430.27    4978 1432.78  4989.3 1431.52
  4997.6 1429.11  5007.5  1428.8    5014 1424.87  5019.8 1424.42  5020.1 1423.92
  5023.8 1424.42  5028.4 1428.37  5042.7 1432.65  5163.7  1446.3  5198.9 1448.53
  5256.2 1456.29  5270.5 1457.11  5299.1 1461.67  5326.4    1468  5390.9 1476.61
#Mann= 4 ,-1 , 0
    4665     .12       0  4989.3     .07       0  5019.8     .05       0
  5023.8     .07       0
Bank Sta=5019.8,5023.8
XS Rating Curve= 0 ,0
Exp/Cntr=0.3,0.1

Type RM Length L Ch R = 1 ,22911   ,419,419,419
BEGIN DESCRIPTION:
WERNER CREEK 50.0
END DESCRIPTION:
XS GIS Cut Line= 3
      2074274.98     13912375.01        2074075.       13912475.
      2073611.44      13913090.1
#Sta/Elev= 30
  4780.8  1477.4  4825.5 1467.84  4870.2 1453.46    4901 1447.44  4927.2 1436.86
  4945.7    1430  4959.7 1420.88    4980 1414.84  4980.3 1414.34    4984 1414.84
  5001.6 1421.81  5017.9  1424.3  5079.9 1424.84  5161.6 1429.64  5223.7 1430.96
  5311.5 1434.42  5396.8 1448.69  5490.5 1454.06  5540.5 1459.16  5565.3 1463.82
    5605 1468.75  5611.3 1467.08  5640.4 1470.89  5675.8 1472.33  5681.7 1471.16
  5690.4 1472.57  5711.2 1471.48  5725.8 1474.43  5761.2 1473.03  5774.6 1475.26
#Mann= 8 ,-1 , 0
  4780.8     .12       0  4927.2     .07       0    4980     .05       0
    4984     .07       0  5079.9     .12       0  5223.7     .07       0
  5565.3    .035       0  5681.7     .12       0
Bank Sta=4980,4984
XS Rating Curve= 0 ,0
Exp/Cntr=0.3,0.1

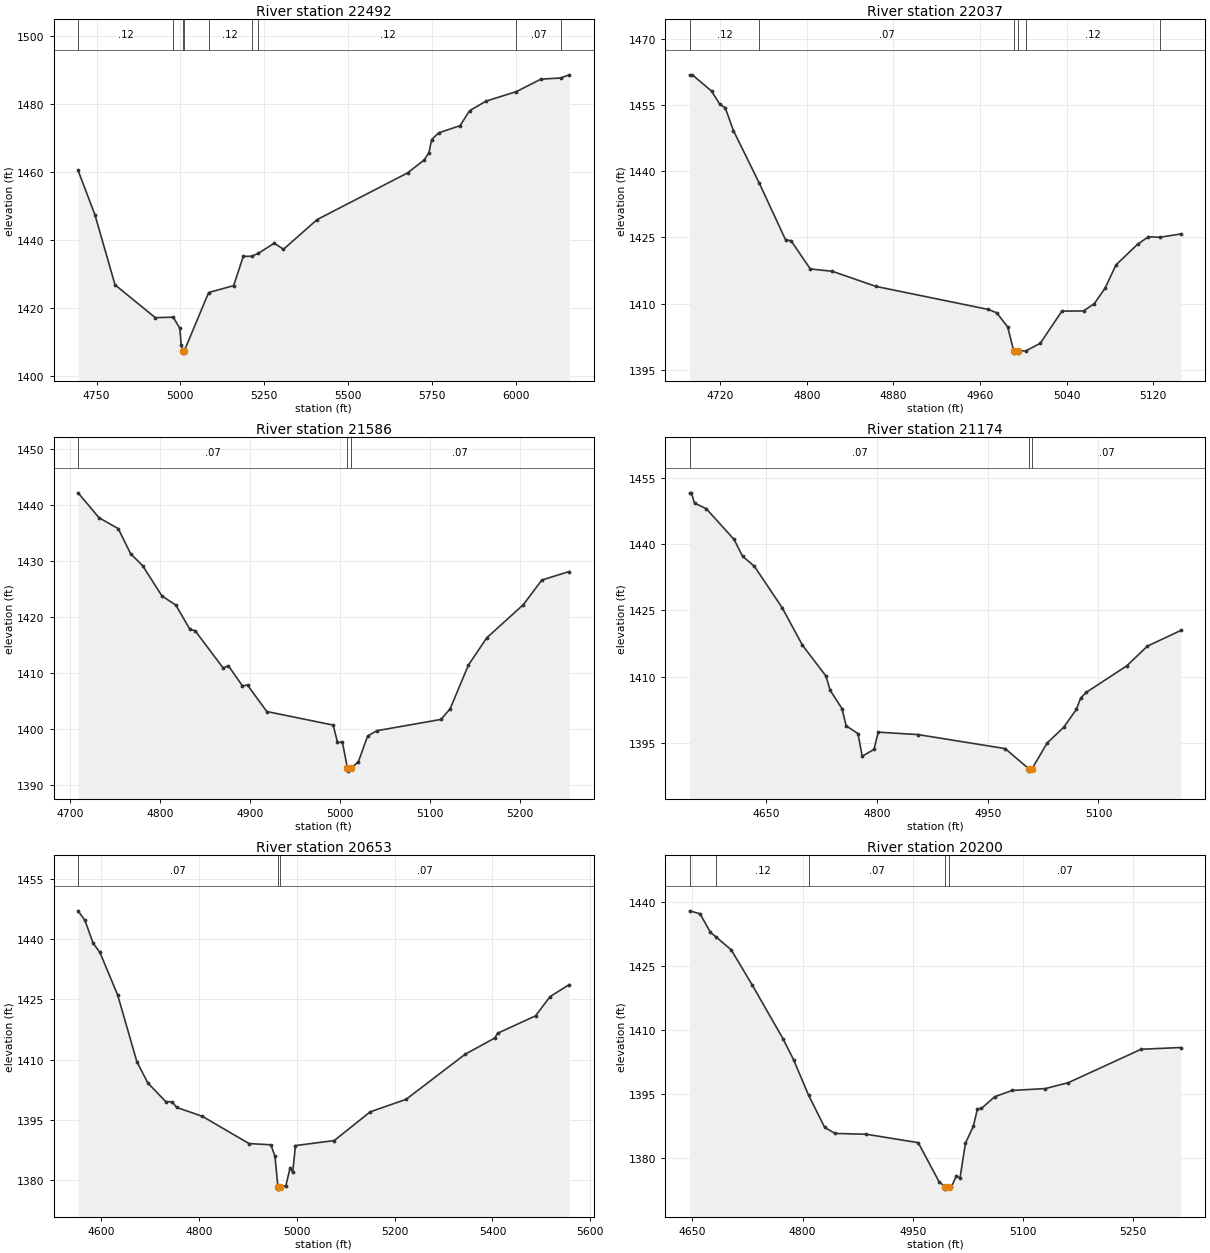
Type RM Length L Ch R = 1 ,22492   ,455,455,455
BEGIN DESCRIPTION:
WERNER CREEK 49.0
END DESCRIPTION:
XS GIS Cut Line= 3
      2074125.02       13912175.        2073825.       13912175.
      2072929.51     13912917.97
#Sta/Elev= 30
  4695.1 1460.54  4745.1 1447.55  4805.1 1426.89  4925.1 1417.22  4978.7 1417.36
  4998.4 1414.04  5002.3 1409.16  5006.8 1407.28    5007 1406.78  5010.8 1407.28
  5084.1 1424.62  5158.6 1426.65  5187.2 1435.25  5212.5 1435.31  5232.6 1436.18
  5279.7 1439.16    5307 1437.34  5407.3 1446.09  5676.8 1459.83  5726.3 1463.64
  5740.6 1465.82  5748.5 1469.63  5769.3 1471.61  5833.1 1473.73  5861.8 1478.17
  5911.2 1480.98  6001.3 1483.77    6074 1487.42  6132.7 1487.77  6158.7  1488.7
#Mann= 9 ,-1 , 0
  4695.1     .12       0  4978.7     .07       0  5006.8     .05       0
  5010.8     .07       0  5084.1     .12       0  5212.5    .035       0
  5232.6     .12       0  6001.3     .07       0  6132.7    .035       0
Bank Sta=5006.8,5010.8
XS Rating Curve= 0 ,0
Exp/Cntr=0.3,0.1

Type RM Length L Ch R = 1 ,22037   ,451,451,451
BEGIN DESCRIPTION:
WERNER CREEK 48.0
END DESCRIPTION:
XS GIS Cut Line= 3
      2074174.99       13911825.        2073875.       13911775.
      2073725.03       13911775.
#Sta/Elev= 30
  4691.6 1461.79  4694.1 1461.79  4711.9  1458.1  4719.5 1455.11  4724.5 1454.34
  4732.1 1449.16  4755.9 1437.32  4780.3 1424.45  4785.4 1424.25  4803.1 1417.88
  4823.4 1417.35  4863.9 1413.92  4967.8 1408.71  4975.5 1407.94  4985.6 1404.75
  4991.2 1399.33  4991.4 1398.83  4994.9 1398.83  4995.2 1399.33  5002.4 1399.34
  5015.7 1401.05  5035.7 1408.33  5055.7 1408.38  5065.7 1410.02  5075.7 1413.55
  5085.7 1418.78  5105.7 1423.46  5115.7 1425.15  5126.6 1425.05  5145.7 1425.79
#Mann= 6 ,-1 , 0
  4691.6     .12       0  4755.9     .07       0  4991.2     .05       0
  4995.2     .07       0  5002.4     .12       0  5126.6     .07       0
Bank Sta=4991.2,4995.2
XS Rating Curve= 0 ,0
Exp/Cntr=0.3,0.1

Type RM Length L Ch R = 1 ,21586   ,412,412,412
BEGIN DESCRIPTION:
WERNER CREEK 47.0
END DESCRIPTION:
XS GIS Cut Line= 3
        2074125.       13911475.        2073875.       13911325.
        2073625.       13911375.
#Sta/Elev= 30
  4708.9  1442.2  4732.2 1437.74  4753.6 1435.79  4767.2 1431.34  4780.8 1429.14
  4802.2 1423.74  4817.7  1422.1  4833.3 1417.77  4839.1 1417.53  4870.2 1410.87
  4876.1 1411.25  4891.6 1407.69  4897.4  1407.8  4918.8 1403.07  4992.7 1400.64
  4997.5 1397.56    5003 1397.56  5008.6  1392.9  5008.9  1392.4  5012.6  1392.9
  5020.8 1394.11    5031 1398.68  5041.2 1399.63  5112.6 1401.65  5122.8 1403.55
  5143.2 1411.39  5163.6 1416.26  5204.4 1422.21  5224.8 1426.59  5255.4 1428.12
#Mann= 3 ,-1 , 0
  4708.9     .07       0  5008.6     .05       0  5012.6     .07       0
Bank Sta=5008.6,5012.6
XS Rating Curve= 0 ,0
Exp/Cntr=0.3,0.1

Type RM Length L Ch R = 1 ,21174   ,521,521,521
BEGIN DESCRIPTION:
WERNER CREEK 46.0
END DESCRIPTION:
XS GIS Cut Line= 3
      2074077.48     13910757.76      2073681.66     13910979.97
      2073590.04     13911170.13
#Sta/Elev= 30
  4546.5 1451.58  4548.8 1451.58  4553.1 1449.25    4569 1447.99  4606.7 1441.03
  4618.1 1437.24  4634.1 1434.98  4671.7 1425.62  4699.1 1417.15    4731 1410.17
  4736.7 1406.96  4752.7 1402.79  4758.4 1398.91  4774.4 1397.14  4780.1 1392.03
  4796.1 1393.57  4801.8 1397.47  4855.4 1396.93  4973.7 1393.75  5005.9 1389.16
  5006.2 1388.66  5009.9 1389.16  5030.5 1395.02  5053.1 1398.61  5070.2 1402.67
  5075.8 1405.17  5083.7  1406.5  5138.1 1412.44  5166.2 1416.92  5211.5 1420.47
#Mann= 3 ,-1 , 0
  4546.5     .07       0  5005.9     .05       0  5009.9     .07       0
Bank Sta=5005.9,5009.9
XS Rating Curve= 0 ,0
Exp/Cntr=0.3,0.1

Type RM Length L Ch R = 1 ,20653   ,453,453,453
BEGIN DESCRIPTION:
WERNER CREEK 45.0
END DESCRIPTION:
XS GIS Cut Line= 3
      2073874.99     13910425.01        2073475.       13910625.
      2072972.72     13910865.98
#Sta/Elev= 30
  4552.8 1446.98  4566.8 1444.61  4583.5 1438.93  4597.5 1436.62  4633.8 1426.01
    4673 1409.46  4695.3 1404.21  4731.7 1399.57  4745.6 1399.47    4754 1398.12
  4807.1 1395.88  4902.2 1389.12  4946.9 1388.81  4955.3 1385.98  4961.4 1378.29
  4961.7 1377.79    4966 1378.29  4977.6 1378.65    4986 1382.97  4991.6    1382
  4997.2 1388.62  5076.5 1389.87    5150    1397  5223.5 1400.12  5343.8 1411.29
  5404.7 1415.36  5410.4 1416.54    5488 1420.86  5517.9 1425.67  5557.1 1428.65
#Mann= 3 ,-1 , 0
  4552.8     .07       0  4961.4     .05       0    4966     .07       0
Bank Sta=4961.4,4966
XS Rating Curve= 0 ,0
Exp/Cntr=0.3,0.1

Type RM Length L Ch R = 1 ,20200   ,465,465,465
BEGIN DESCRIPTION:
WERNER CREEK 44.0
END DESCRIPTION:
XS GIS Cut Line= 3
      2073574.98     13909975.02        2073325.       13910225.
      2073035.28     13910348.59
#Sta/Elev= 30
  4646.4 1438.03  4660.5 1437.34  4674.7 1432.97  4682.6 1431.85  4702.9 1428.87
  4731.2 1420.69  4773.6 1407.89  4787.8 1403.02  4808.3 1394.64  4830.2 1387.08
  4844.4 1385.67  4886.8 1385.48  4957.5  1383.5  4985.8 1374.32    4994 1373.07
  4994.3 1372.57  4998.7 1373.07  5002.6 1373.07    5009 1375.57  5014.4 1375.25
  5021.7 1383.35  5032.5 1387.36  5038.1 1391.47  5043.5 1391.55  5061.7 1394.32
  5085.3 1395.78  5130.4 1396.22  5161.6  1397.6  5260.8 1405.47  5314.9 1405.88
#Mann= 5 ,-1 , 0
  4646.4     .07       0  4682.6     .12       0  4808.3     .07       0
    4994     .05       0  4998.7     .07       0
Bank Sta=4994,4998.7
XS Rating Curve= 0 ,0
Exp/Cntr=0.3,0.1

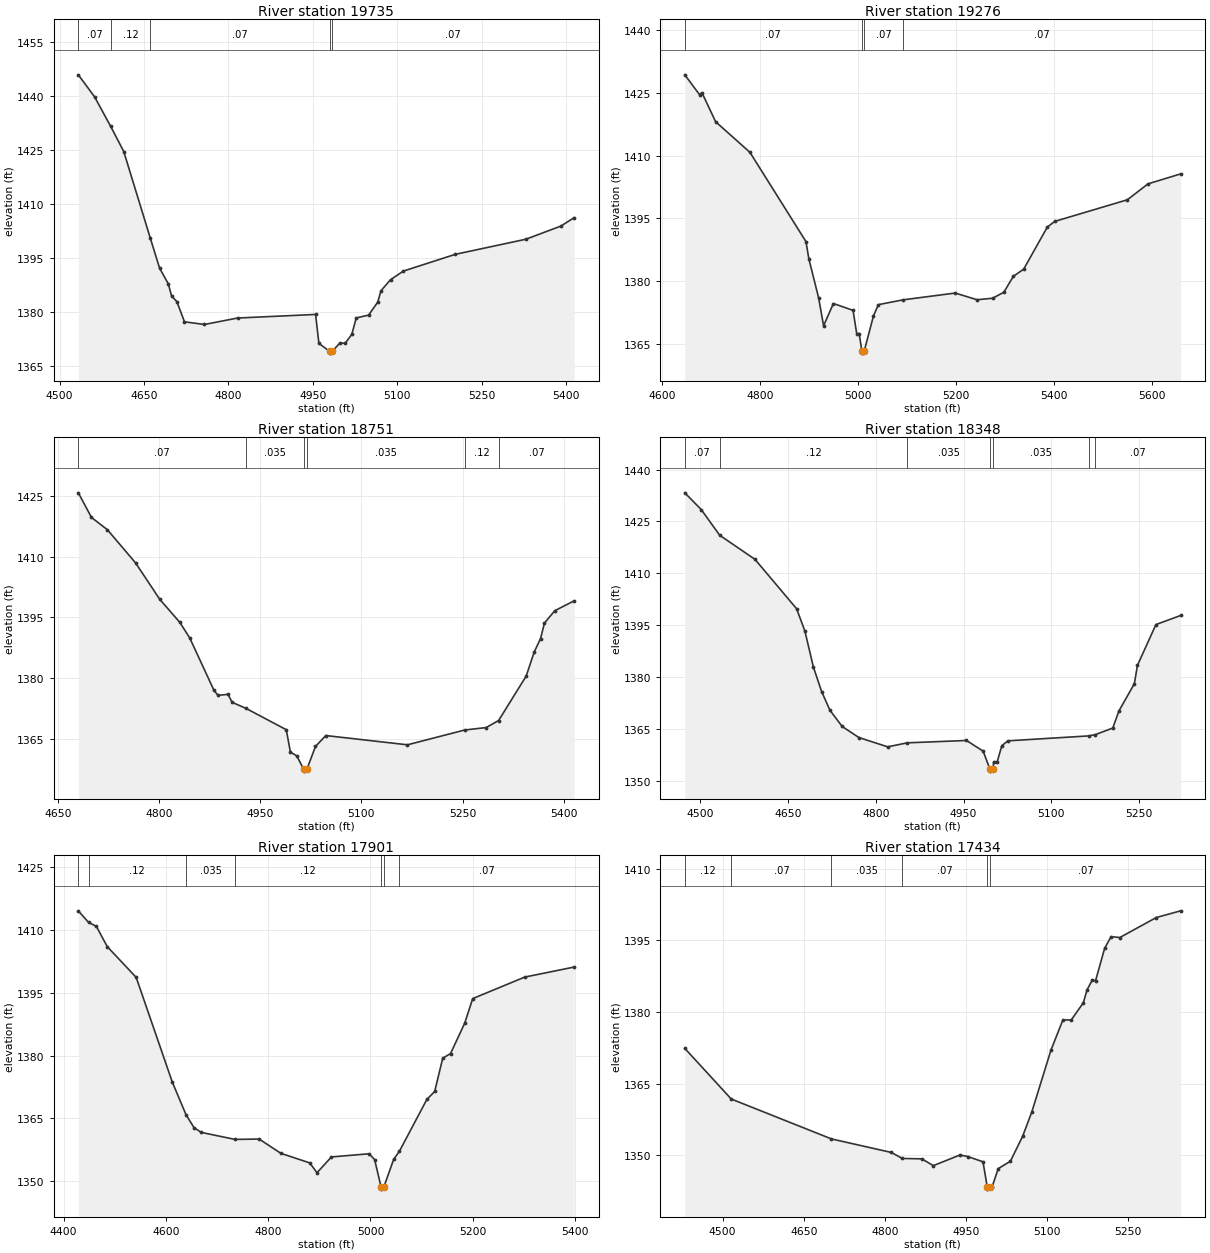
Type RM Length L Ch R = 1 ,19735   ,459,459,459
BEGIN DESCRIPTION:
WERNER CREEK 43.0
END DESCRIPTION:
XS GIS Cut Line= 3
      2073474.97     13909675.02        2073075.       13909925.
      2072903.32     13910296.49
#Sta/Elev= 30
  4533.4 1445.81  4562.3  1439.7  4590.9 1431.51  4614.1 1424.55  4661.2 1400.57
  4677.8 1392.21  4693.2 1387.88    4699 1384.55  4708.5 1382.93    4722 1377.35
  4757.4 1376.61  4816.4  1378.4  4954.9 1379.39  4960.8 1371.38  4979.7 1369.17
    4980 1368.67  4984.5 1369.17  4997.4 1371.35  5007.8 1371.48  5019.3 1373.87
  5027.1 1378.42  5049.1 1379.21  5065.2 1382.77  5071.2 1385.98  5088.1 1389.03
    5111 1391.42  5202.8 1396.04  5328.5 1400.24  5390.6 1403.88  5414.3 1406.22
#Mann= 5 ,-1 , 0
  4533.4     .07       0  4590.9     .12       0  4661.2     .07       0
  4979.7     .05       0  4984.5     .07       0
Bank Sta=4979.7,4984.5
XS Rating Curve= 0 ,0
Exp/Cntr=0.3,0.1

Type RM Length L Ch R = 1 ,19276   ,525,525,525
BEGIN DESCRIPTION:
WERNER CREEK 42.0
END DESCRIPTION:
XS GIS Cut Line= 3
       2072941.5      13909272.2        2072925.       13909625.
      2072712.34     13910247.91
#Sta/Elev= 30
  4646.8 1429.29  4676.8 1424.56  4681.8 1425.01  4709.7 1418.08  4779.7 1410.76
  4893.9 1389.44  4899.9 1385.29  4919.9 1375.92  4929.9  1369.3  4949.9 1374.63
    4990 1372.99  4997.5 1367.42  5002.6 1367.42  5007.9 1363.27  5008.3 1362.77
  5012.8 1363.27  5031.7 1371.69  5041.7 1374.36  5092.3 1375.51  5198.3 1377.13
    5243 1375.53  5274.7 1375.89  5297.6 1377.32    5317 1381.13  5338.1 1382.85
  5386.3  1392.9  5401.5 1394.26  5549.5 1399.42  5591.7 1403.23  5658.2 1405.61
#Mann= 4 ,-1 , 0
  4646.8     .07       0  5007.9     .05       0  5012.8     .07       0
  5092.3     .07       0
Bank Sta=5007.9,5012.8
XS Rating Curve= 0 ,0
Exp/Cntr=0.3,0.1

Type RM Length L Ch R = 1 ,18751   ,403,403,403
BEGIN DESCRIPTION:
WERNER CREEK 41.0
END DESCRIPTION:
XS GIS Cut Line= 3
      2072760.98     13909192.33      2072497.06     13909376.38
        2072275.       13909725.
#Sta/Elev= 30
  4680.3 1425.73  4699.8 1419.66  4723.4 1416.63  4765.2 1408.45    4801 1399.48
  4830.7 1393.81  4845.5 1389.94  4881.3 1377.07  4887.4  1375.8  4902.2 1376.05
  4908.3 1374.08  4928.9 1372.59  4988.6 1367.33  4994.7 1361.81  5004.2 1360.89
  5014.2 1357.62  5014.6 1357.12  5019.2 1357.62  5031.9  1363.2  5047.2 1365.89
  5168.2 1363.61  5253.2 1367.26    5285 1367.86  5303.4  1369.6  5344.3 1380.55
  5356.1 1386.46  5365.5 1389.77  5371.4 1393.62  5386.6 1396.66  5415.4 1399.11
#Mann= 6 ,-1 , 0
  4680.3     .07       0  4928.9    .035       0  5014.2    .035       0
  5019.2    .035       0  5253.2     .12       0  5303.4     .07       0
Bank Sta=5014.2,5019.2
XS Rating Curve= 0 ,0
Exp/Cntr=0.3,0.1

Type RM Length L Ch R = 1 ,18348   ,447,447,447
BEGIN DESCRIPTION:
WERNER CREEK 40.0
END DESCRIPTION:
XS GIS Cut Line= 3
      2072524.96     13908925.03        2072125.       13909275.
        2072025.     13909575.01
#Sta/Elev= 30
  4473.3 1433.28  4501.3 1428.46    4533 1421.01  4593.3 1414.05  4664.5 1399.76
  4678.7 1393.28    4693 1383.01  4707.2 1375.83  4721.4 1370.45  4742.3 1365.75
  4770.8 1362.55  4820.2 1359.85  4853.8 1361.01  4954.9 1361.69  4983.4  1358.6
  4995.1 1353.33  4995.5 1352.83  5000.1 1353.33  5001.4 1355.54  5007.4 1355.54
  5015.3 1360.18  5025.8 1361.59  5163.7 1363.01    5175 1363.37    5205 1365.28
  5215.6 1370.25  5241.9 1378.09  5247.2 1383.42  5278.8  1395.2    5321 1397.82
#Mann= 7 ,-1 , 0
  4473.3     .07       0    4533     .12       0  4853.8    .035       0
  4995.1    .035       0  5000.1    .035       0  5163.7     .12       0
    5175     .07       0
Bank Sta=4995.1,5000.1
XS Rating Curve= 0 ,0
Exp/Cntr=0.3,0.1

Type RM Length L Ch R = 1 ,17901   ,467,467,467
BEGIN DESCRIPTION:
WERNER CREEK 39.0
END DESCRIPTION:
XS GIS Cut Line= 3
      2072224.97     13908575.03        2071825.       13908975.
      2071476.25     13909178.45
#Sta/Elev= 30
  4428.8 1414.52  4448.7 1411.77  4464.1 1410.81  4485.3 1405.99  4541.9 1398.65
  4612.6 1373.65  4639.4 1365.88    4655  1362.8  4669.2 1361.68  4735.4    1360
  4782.3  1360.1  4824.7 1356.69  4881.3  1354.4  4895.4 1352.06  4923.7 1355.83
  4997.3 1356.58  5008.1 1355.19  5020.7 1348.65  5021.1 1348.15  5026.1 1348.65
  5045.3 1355.24  5056.7 1357.22  5110.2 1369.54  5125.5 1371.44  5141.2 1379.36
  5156.5 1380.48  5184.2 1387.72  5199.9 1393.59  5301.6 1398.72  5398.2 1401.11
#Mann= 7 ,-1 , 0
  4428.8     .07       0  4448.7     .12       0  4639.4    .035       0
  4735.4     .12       0  5020.7     .05       0  5026.1     .12       0
  5056.7     .07       0
Bank Sta=5020.7,5026.1
XS Rating Curve= 0 ,0
Exp/Cntr=0.3,0.1

Type RM Length L Ch R = 1 ,17434   ,446,446,446
BEGIN DESCRIPTION:
WERNER CREEK 38.0
END DESCRIPTION:
XS GIS Cut Line= 3
      2071874.97     13908275.03        2071475.       13908675.
      2071320.24     13908990.43
#Sta/Elev= 30
    4430 1372.38  4515.9 1361.77  4701.2 1353.41  4811.8 1350.58  4832.3 1349.32
  4868.4 1349.23  4889.6 1347.81  4939.1 1350.05  4953.2 1349.72  4981.5 1348.62
  4989.3 1343.39  4989.8 1342.89  4994.9 1343.39  4998.4 1343.39  5009.7 1347.19
  5032.2 1348.74  5054.7 1353.93  5071.6 1358.99    5107 1371.95  5129.3 1378.35
  5144.6 1378.32  5167.1 1381.94  5173.9 1384.63    5184 1386.79  5189.6 1386.52
  5206.5 1393.36  5218.4 1395.79  5234.6 1395.61    5302  1399.8    5347  1401.2
#Mann= 6 ,-1 , 0
    4430     .12       0  4515.9     .07       0  4701.2    .035       0
  4832.3     .07       0  4989.3     .05       0  4994.9     .07       0
Bank Sta=4989.3,4994.9
XS Rating Curve= 0 ,0
Exp/Cntr=0.3,0.1

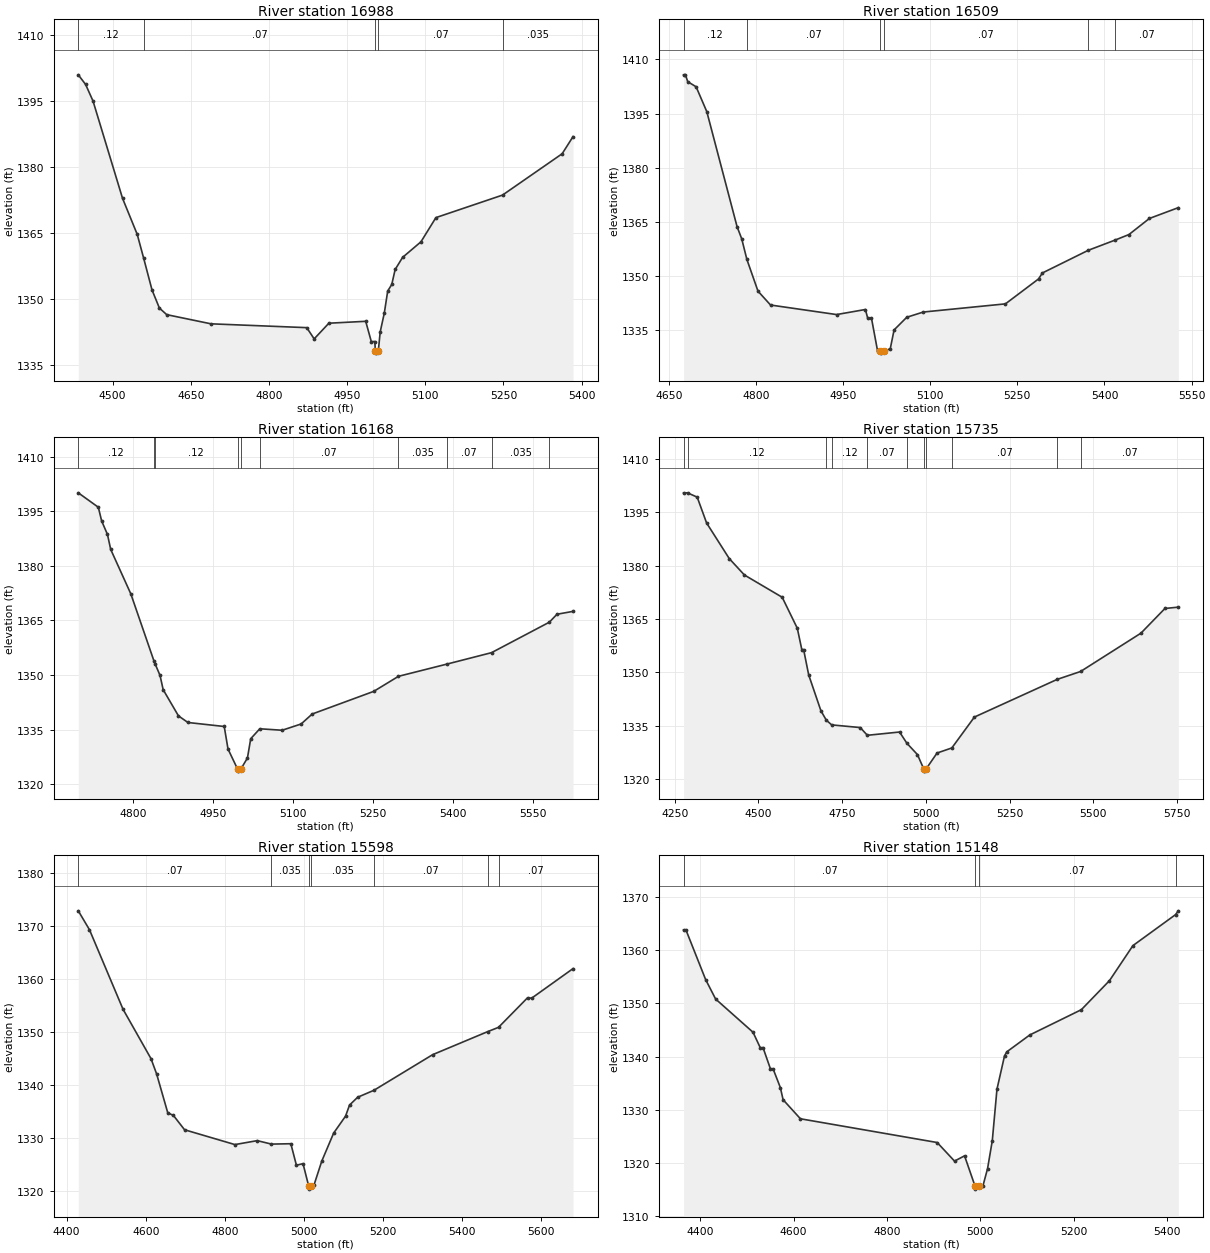
Type RM Length L Ch R = 1 ,16988   ,479,479,479
BEGIN DESCRIPTION:
WERNER CREEK 37.0
END DESCRIPTION:
XS GIS Cut Line= 3
        2071675.       13907925.        2071275.       13908325.
      2071030.34     13908620.46
#Sta/Elev= 30
  4434.3 1400.94  4448.4 1398.75  4462.6 1394.99  4519.2 1372.92  4547.4 1364.74
  4559.5 1359.44  4575.7 1352.16  4589.9 1348.02    4604 1346.52  4688.9 1344.44
  4872.7 1343.57  4886.9 1341.02  4915.1 1344.58  4985.8 1345.01  4996.5 1340.42
  5003.2 1340.42  5004.4 1338.29  5004.8 1337.79    5010 1338.29  5013.6  1342.6
  5021.5 1346.89    5028 1351.88  5035.8 1353.37  5042.3 1356.77  5056.6 1359.52
  5091.8 1363.05  5120.5 1368.54  5248.3 1373.65  5362.7 1383.03  5383.6 1386.92
#Mann= 5 ,-1 , 0
  4434.3     .12       0  4559.5     .07       0  5004.4     .05       0
    5010     .07       0  5248.3    .035       0
Bank Sta=5004.4,5010
XS Rating Curve= 0 ,0
Exp/Cntr=0.3,0.1

Type RM Length L Ch R = 1 ,16509   ,341,341,341
BEGIN DESCRIPTION:
WERNER CREEK 36.0
END DESCRIPTION:
XS GIS Cut Line= 3
      2071525.02     13907674.98        2071275.       13907875.
      2070924.99     13908275.01
#Sta/Elev= 30
  4675.4  1405.7  4678.6  1405.7  4682.6  1403.8    4697 1402.39  4715.4 1395.51
  4767.5 1363.69  4775.5 1360.33  4784.4 1354.62  4803.5 1345.85  4825.1 1342.01
  4938.8 1339.37  4988.4 1340.77  4992.4 1338.35  4998.9 1338.35  5009.3 1329.38
  5014.1  1329.2  5014.5  1328.7  5019.8  1329.2  5031.2 1329.91  5037.8 1335.12
  5059.6 1338.62  5088.1 1340.07  5229.5 1342.33  5286.5 1349.23  5293.1 1350.88
  5372.2 1357.16  5417.5 1359.93  5442.1 1361.51  5477.3 1365.96  5527.1 1368.95
#Mann= 6 ,-1 , 0
  4675.4     .12       0  4784.4     .07       0  5014.1     .05       0
  5019.8     .07       0  5372.2    .035       0  5417.5     .07       0
Bank Sta=5014.1,5019.8
XS Rating Curve= 0 ,0
Exp/Cntr=0.3,0.1

Type RM Length L Ch R = 1 ,16168   ,433,433,433
BEGIN DESCRIPTION:
WERNER CREEK 35.0
END DESCRIPTION:
XS GIS Cut Line= 3
      2071374.99       13907475.      2071098.71     13907598.18
      2070733.19     13908105.52
#Sta/Elev= 30
  4697.5 1400.04  4735.1 1396.08  4741.3 1392.32  4752.2 1388.62  4758.3  1384.5
    4796  1372.3  4839.6 1353.78  4841.4 1353.12  4850.8 1349.89  4856.7 1345.97
  4885.4 1338.77  4903.1 1336.96  4971.2 1335.86  4978.3 1329.67  4996.4  1324.1
  4996.9  1323.6  5002.1  1324.1  5014.7  1327.2  5020.9 1332.51  5037.9 1335.23
  5079.8 1334.83  5115.4 1336.55  5136.2 1339.29  5251.6 1345.51  5297.9 1349.64
  5388.3 1352.98  5472.5 1356.14  5580.9 1364.51  5595.2 1366.69  5625.3 1367.48
#Mann= 10 ,-1 , 0
  4697.5     .12       0  4839.6     .07       0  4841.4     .12       0
  4996.4     .05       0  5002.1     .12       0  5037.9     .07       0
  5297.9    .035       0  5388.3     .07       0  5472.5    .035       0
  5580.9     .07       0
Bank Sta=4996.4,5002.1
XS Rating Curve= 0 ,0
Exp/Cntr=0.3,0.1

Type RM Length L Ch R = 1 ,15735   ,137,137,137
BEGIN DESCRIPTION:
WERNER CREEK 34.5
END DESCRIPTION:
XS GIS Cut Line= 4
      2071456.13     13907367.99      2071136.96     13907213.14
      2070791.49      13907342.1      2070662.36     13908084.86
#Sta/Elev= 30
  4276.5 1400.44  4288.4 1400.43  4317.2 1399.23  4345.3 1391.97    4413 1381.97
  4458.2 1377.37    4571 1371.12  4616.1 1362.42  4629.6 1356.42    4635 1356.42
  4650.1 1349.33  4686.7 1339.24  4702.9 1336.59  4718.9 1335.29  4804.1 1334.54
  4825.3 1332.37  4921.5 1333.29  4943.3 1330.14  4974.9 1326.95  4994.2 1322.81
  4994.6 1322.31  4999.9 1322.81  5033.4 1327.39  5077.6 1328.82    5145 1337.49
  5392.3 1348.07    5462 1350.28  5642.4 1361.05  5713.9 1367.97  5753.9 1368.35
#Mann= 11 ,-1 , 0
  4276.5     .07       0  4288.4     .12       0  4702.9     .07       0
  4718.9     .12       0  4825.3     .07       0  4943.3     .12       0
  4994.2     .05       0  4999.9     .12       0  5077.6     .07       0
  5392.3    .035       0    5462     .07       0
Bank Sta=4994.2,4999.9
XS Rating Curve= 0 ,0
Exp/Cntr=0.3,0.1

Type RM Length L Ch R = 1 ,15598   ,450,450,450
BEGIN DESCRIPTION:
WERNER CREEK 34.0
END DESCRIPTION:
XS GIS Cut Line= 3
        2071075.       13906875.        2070675.       13907275.
      2070649.83     13907959.76
#Sta/Elev= 30
  4429.4 1372.79  4457.7 1369.23  4542.5 1354.26  4613.2 1344.96  4627.4 1342.09
  4655.7 1334.74  4669.8 1334.27  4698.1 1331.56  4825.4 1328.77  4881.9 1329.51
  4917.8 1328.86  4966.8 1328.93  4980.9 1324.88  4997.6 1325.18  5012.2 1320.88
  5012.7 1320.38  5017.9 1320.88  5025.1 1321.09  5045.1 1325.67  5075.1 1330.94
  5105.2 1334.13  5115.2 1336.21  5135.7 1337.68  5177.1    1339  5325.3  1345.7
  5464.2 1350.03  5491.9 1350.85  5565.5 1356.43  5575.5 1356.33  5680.3 1361.91
#Mann= 7 ,-1 , 0
  4429.4     .07       0  4917.8    .035       0  5012.2    .035       0
  5017.9    .035       0  5177.1     .07       0  5464.2    .035       0
  5491.9     .07       0
Bank Sta=5012.2,5017.9
XS Rating Curve= 0 ,0
Exp/Cntr=0.3,0.1

Type RM Length L Ch R = 1 ,15148   ,448,448,448
BEGIN DESCRIPTION:
WERNER CREEK 33.0
END DESCRIPTION:
XS GIS Cut Line= 3
       2070868.6     13906754.85        2070325.       13907075.
       2069898.2     13907112.33
#Sta/Elev= 30
  4364.4 1363.86  4369.4 1363.86  4411.6  1354.5    4433 1350.83  4513.1 1344.57
  4528.7 1341.64  4534.5 1341.68  4550.2 1337.72    4556 1337.69  4571.6 1334.15
  4577.5 1331.86  4614.6 1328.27  4907.4  1323.8  4944.5  1320.3    4966 1321.29
  4988.7 1315.52  4989.2 1315.02    4996 1315.52  5005.3 1315.61  5015.3  1318.9
  5025.4 1324.15  5035.4 1333.84  5051.6 1340.13  5056.6 1340.89  5105.7 1344.06
  5216.1 1348.82  5276.3 1354.29  5326.5 1360.89  5417.7 1366.72  5423.7 1367.44
#Mann= 4 ,-1 , 0
  4364.4     .07       0  4988.7     .05       0    4996     .07       0
  5417.7     .12       0
Bank Sta=4988.7,4996
XS Rating Curve= 0 ,0
Exp/Cntr=0.3,0.1

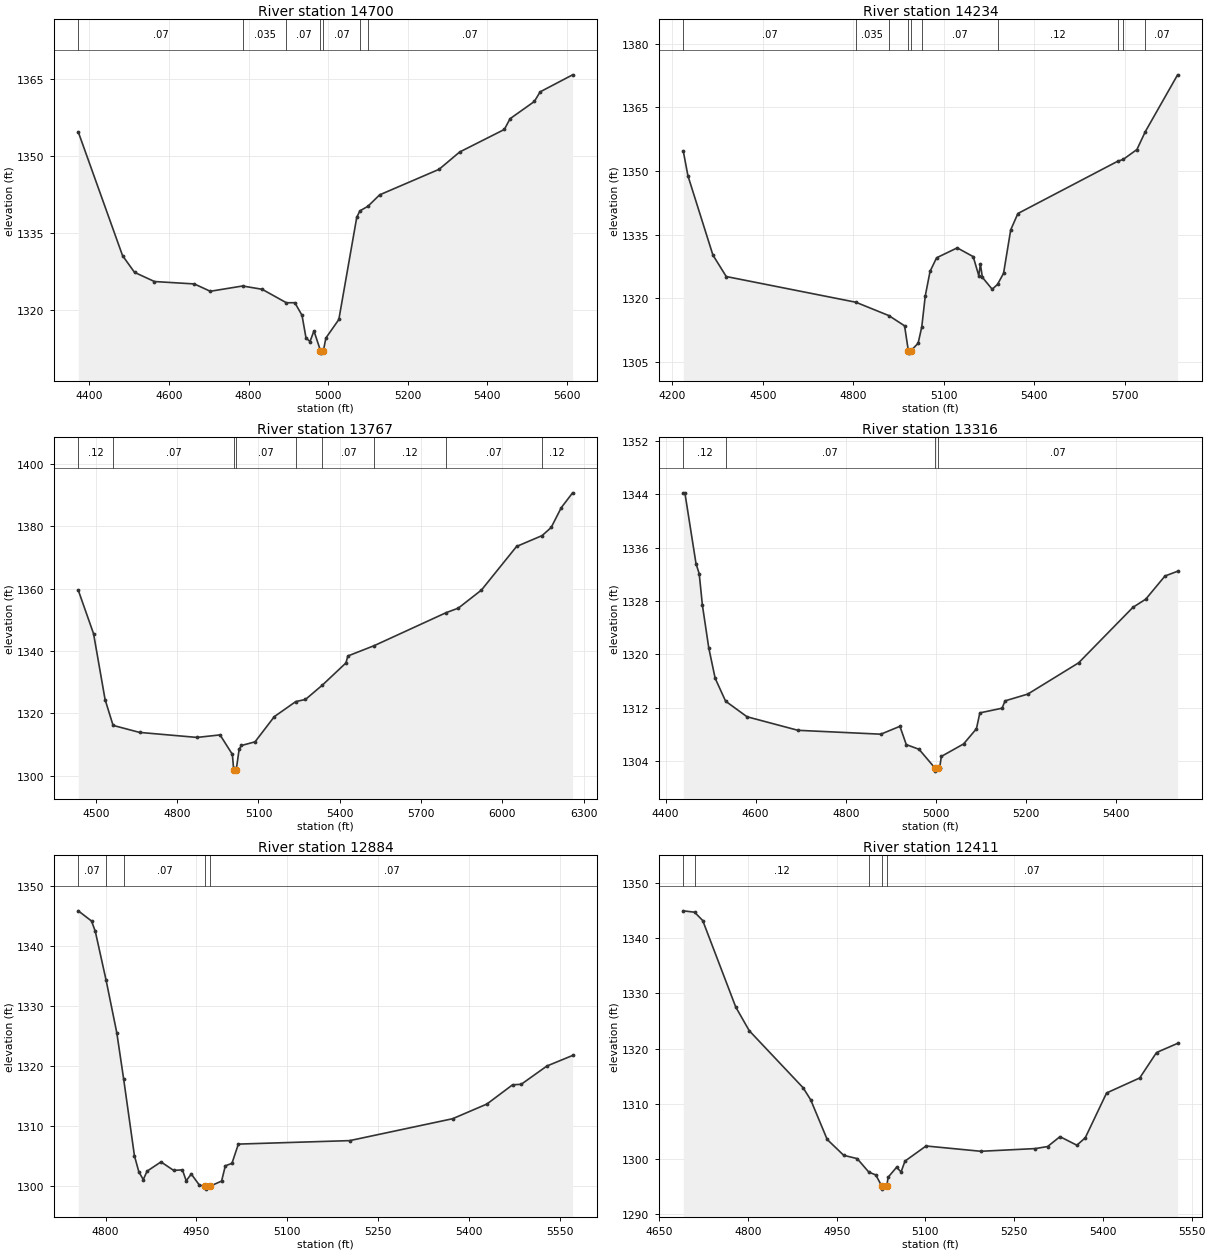
Type RM Length L Ch R = 1 ,14700   ,466,466,466
BEGIN DESCRIPTION:
WERNER CREEK 32.0
END DESCRIPTION:
XS GIS Cut Line= 3
       2070806.1     13906640.27        2070175.       13906675.
      2069632.44     13906952.79
#Sta/Elev= 30
  4372.4 1354.71  4483.7 1330.58  4513.7 1327.33  4563.8 1325.54  4663.9 1325.07
    4704 1323.64  4785.1 1324.67  4834.2 1324.03  4895.2  1321.4  4916.4 1321.41
  4934.4 1318.95  4944.4 1314.56  4954.4 1313.83  4964.4 1315.91  4980.7 1312.08
  4981.2 1311.58  4988.1 1312.08  4994.4 1314.53  5026.9 1318.14  5071.9 1338.06
  5079.8 1339.32  5099.9 1340.21  5129.4 1342.44  5278.7 1347.42  5330.3 1350.79
  5442.6 1355.19  5456.9 1357.28  5517.9 1360.64  5532.5 1362.52    5614 1365.84
#Mann= 7 ,-1 , 0
  4372.4     .07       0  4785.1    .035       0  4895.2     .07       0
  4980.7     .05       0  4988.1     .07       0  5079.8     .12       0
  5099.9     .07       0
Bank Sta=4980.7,4988.1
XS Rating Curve= 0 ,0
Exp/Cntr=0.3,0.1

Type RM Length L Ch R = 1 ,14234   ,467,467,467
BEGIN DESCRIPTION:
WERNER CREEK 31.0
END DESCRIPTION:
XS GIS Cut Line= 3
      2070802.59     13906577.76        2070125.       13906225.
      2069318.22     13906563.16
#Sta/Elev= 30
  4236.1 1354.74  4251.6  1348.9  4334.4  1330.2  4378.6 1325.14  4808.2 1319.08
  4917.6 1315.93  4969.7 1313.52  4982.4 1307.58  4982.9 1307.08  4989.8 1307.58
  5014.6  1309.4  5026.7 1313.24  5038.4 1320.58  5054.2 1326.36  5075.9 1329.56
  5144.3  1331.9  5197.3 1329.83  5215.7 1325.35  5221.1 1328.06  5227.7 1324.95
  5260.2 1322.14  5277.8 1323.28  5297.9 1325.91  5321.6 1336.15  5345.4    1340
  5676.4 1352.33  5694.2 1352.74    5740 1355.09  5767.8 1359.31  5874.8  1372.7
#Mann= 10 ,-1 , 0
  4236.1     .07       0  4808.2    .035       0  4917.6     .12       0
  4982.4     .05       0  4989.8     .12       0  5026.7     .07       0
  5277.8     .12       0  5676.4     .07       0  5694.2     .12       0
  5767.8     .07       0
Bank Sta=4982.4,4989.8
XS Rating Curve= 0 ,0
Exp/Cntr=0.3,0.1

Type RM Length L Ch R = 1 ,13767   ,451,451,451
BEGIN DESCRIPTION:
WERNER CREEK 30.0
END DESCRIPTION:
XS GIS Cut Line= 3
      2070474.97     13905375.03        2070075.       13905775.
      2069061.31     13906520.93
#Sta/Elev= 30
  4434.9 1359.51  4491.4 1345.54  4533.9 1324.42  4563.4 1316.14  4661.1 1313.89
  4873.3 1312.28  4958.1 1313.09  5003.6 1306.85  5007.9 1302.46  5010.1 1301.97
  5010.6 1301.47    5018 1301.97  5028.7 1308.53  5037.2 1309.69  5087.3 1310.87
  5158.3 1318.94  5237.6 1323.78  5273.2 1324.45  5335.9 1329.07  5422.7 1336.17
  5429.8  1338.4  5527.7 1341.74    5792 1352.28  5837.2 1353.74  5922.8 1359.55
  6052.4 1373.53  6146.7 1377.02    6180 1379.61  6217.3 1385.97  6259.1 1390.73
#Mann= 9 ,-1 , 0
  4434.9     .12       0  4563.4     .07       0  5010.1     .05       0
    5018     .07       0  5237.6     .12       0  5335.9     .07       0
  5527.7     .12       0    5792     .07       0  6146.7     .12       0
Bank Sta=5010.1,5018
XS Rating Curve= 0 ,0
Exp/Cntr=0.3,0.1

Type RM Length L Ch R = 1 ,13316   ,432,432,432
BEGIN DESCRIPTION:
WERNER CREEK 29.0
END DESCRIPTION:
XS GIS Cut Line= 3
      2070325.03     13904974.97        2069925.       13905375.
      2069525.03     13905724.98
#Sta/Elev= 30
  4439.3 1344.19  4442.9 1344.19  4467.6 1333.59  4474.7 1332.08  4481.8 1327.36
  4495.9 1320.98  4510.1 1316.43  4533.3    1313  4580.8 1310.67  4693.9 1308.64
  4877.8 1308.06  4920.2 1309.24  4934.3  1306.5  4962.6  1305.8  4997.5 1303.03
    4998 1302.53  5005.5 1303.03  5008.4 1303.03  5012.1 1304.73  5061.5  1306.6
    5090 1308.87  5097.6 1311.25  5146.9 1311.95  5153.6 1313.05  5203.9 1314.06
  5316.8 1318.74  5437.4 1327.05  5465.8 1328.27  5508.5 1331.74  5536.5 1332.45
#Mann= 4 ,-1 , 0
  4439.3     .12       0  4533.3     .07       0  4997.5     .05       0
  5005.5     .07       0
Bank Sta=4997.5,5005.5
XS Rating Curve= 0 ,0
Exp/Cntr=0.3,0.1

Type RM Length L Ch R = 1 ,12884   ,473,473,473
BEGIN DESCRIPTION:
WERNER CREEK 28.0
END DESCRIPTION:
XS GIS Cut Line= 3
      2069975.01     13904774.98        2069825.       13904975.
        2069425.       13905375.
#Sta/Elev= 30
  4754.9 1345.86  4776.8 1344.16    4783 1342.44  4800.9 1334.26  4818.5 1325.52
  4829.9 1317.75  4847.6 1305.02  4854.9 1302.32  4862.2 1301.04  4868.5 1302.45
  4891.4 1303.99  4912.2 1302.58  4926.8 1302.66    4933 1300.84  4941.4 1301.97
  4954.9  1300.1  4964.4 1299.95  4964.9 1299.45  4972.5 1299.95  4991.4 1300.79
  4997.6 1303.34  5008.5 1303.75  5019.1 1306.96  5202.9 1307.54  5372.6 1311.19
  5429.2 1313.64  5471.6 1316.85  5485.8 1316.93  5528.2 1319.98  5570.6 1321.74
#Mann= 5 ,-1 , 0
  4754.9     .07       0  4800.9     .12       0  4829.9     .07       0
  4964.4     .05       0  4972.5     .07       0
Bank Sta=4964.4,4972.5
XS Rating Curve= 0 ,0
Exp/Cntr=0.3,0.1

Type RM Length L Ch R = 1 ,12411   ,417,417,417
BEGIN DESCRIPTION:
WERNER CREEK 27.0
END DESCRIPTION:
XS GIS Cut Line= 3
      2069874.98       13904575.        2069575.       13904625.
      2069175.02     13904974.98
#Sta/Elev= 30
  4690.7 1344.98  4709.8 1344.73  4723.6 1343.22  4779.4 1327.55  4802.2 1323.26
  4893.4  1312.9  4906.1 1310.73    4934 1303.54  4961.9 1300.67  4984.7 1300.07
  5004.4 1297.62  5016.2 1297.11  5026.4 1295.04  5026.9 1294.54  5034.5 1295.04
  5037.1 1296.71  5051.3  1298.5  5058.9 1297.66  5065.5 1299.62  5101.1 1302.36
  5193.7  1301.4  5285.7 1301.89  5306.6 1302.26  5327.5 1304.05    5356  1302.5
  5370.2 1303.84  5406.3 1311.97  5462.3 1314.69  5490.7  1319.3  5526.3 1320.96
#Mann= 5 ,-1 , 0
  4690.7     .07       0  4709.8     .12       0  5004.4     .07       0
  5026.4     .05       0  5034.5     .07       0
Bank Sta=5026.4,5034.5
XS Rating Curve= 0 ,0
Exp/Cntr=0.3,0.1