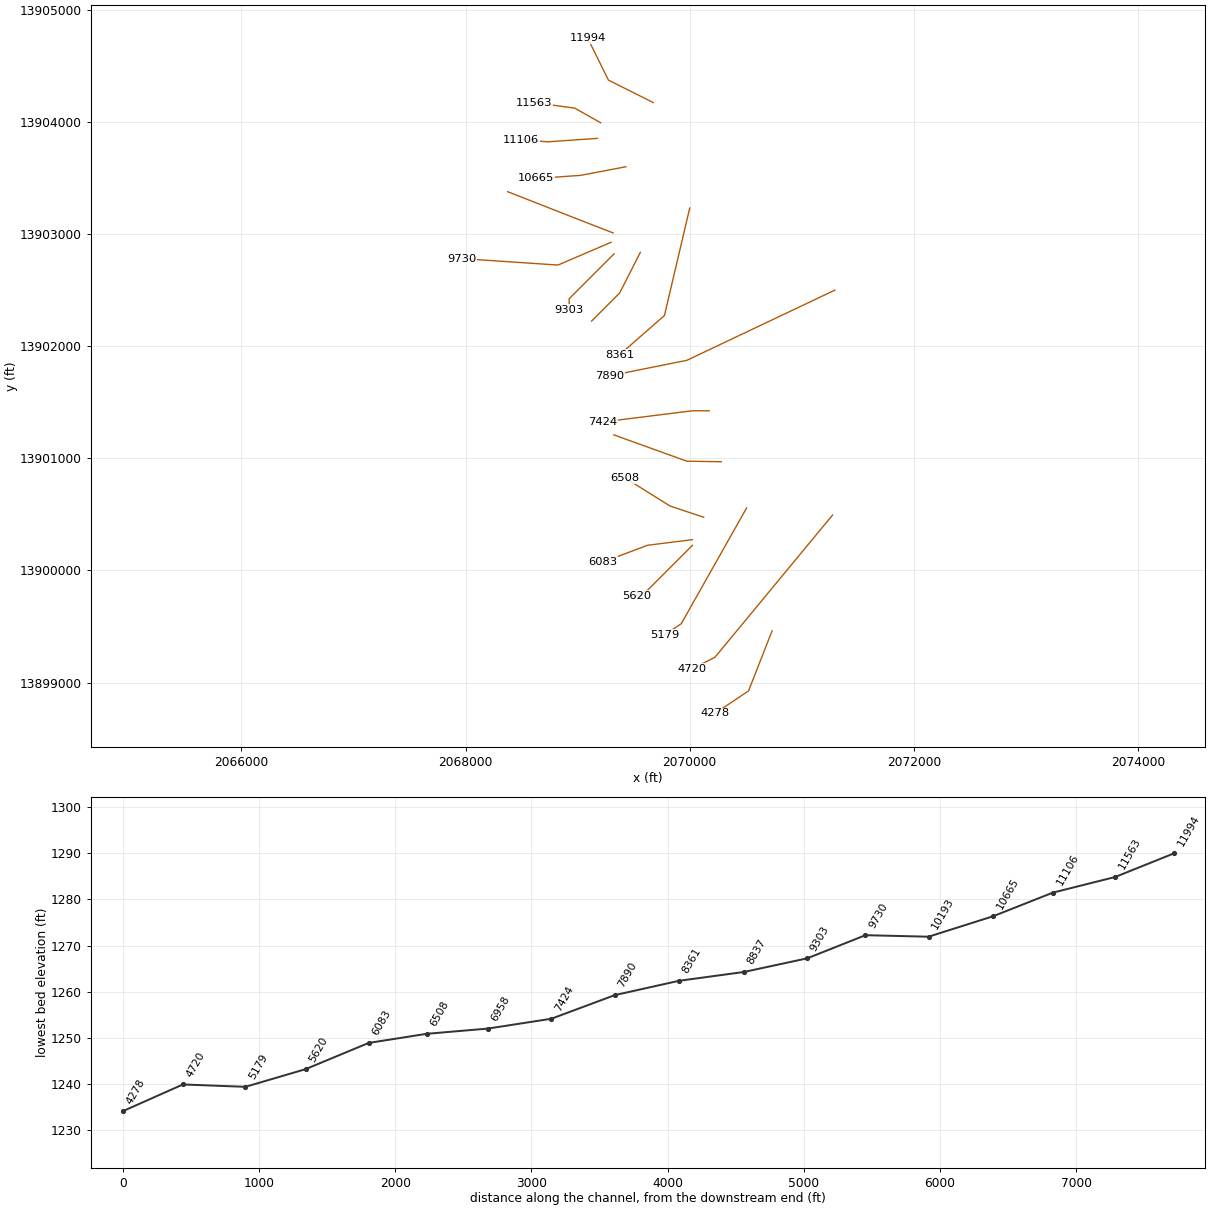
HEC-RAS study WERNER CREEK.prj: WERNER CREEK Base Level Engineering

--- WERNER CREEK.g01 (geometry) --- (continued)

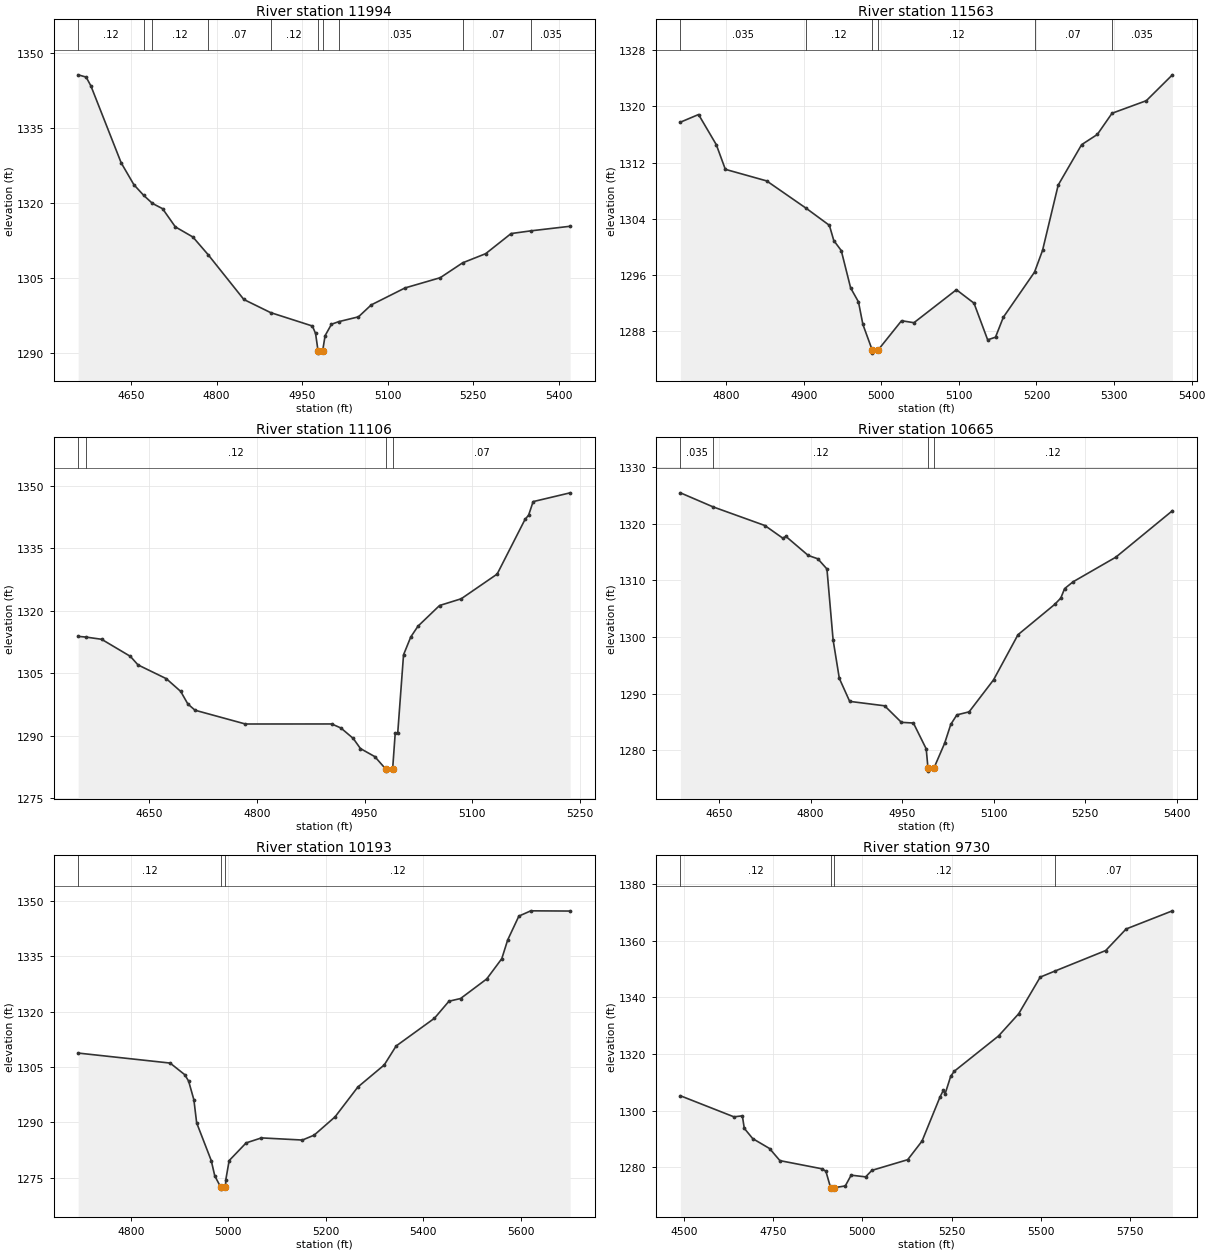
Type RM Length L Ch R = 1 ,11994   ,431,431,431
BEGIN DESCRIPTION:
WERNER CREEK 26.0
END DESCRIPTION:
XS GIS Cut Line= 3
        2069675.       13904175.        2069275.       13904375.
      2069090.82     13904747.88
#Sta/Elev= 30
  4557.1 1345.72  4571.1 1345.27  4579.5  1343.5  4632.6  1328.1  4654.9 1323.72
  4671.9 1321.61  4687.4 1319.98  4705.2 1318.92  4727.6 1315.28  4758.4 1313.25
    4785 1309.73  4847.8 1300.74  4894.6 1298.12    4968 1295.43  4973.6 1293.94
  4977.9  1290.5  4978.4    1290  4986.1  1290.5  4990.3 1293.49  5001.5 1295.78
  5013.9 1296.29  5048.9 1297.27  5071.2 1299.65  5130.5 1303.05  5192.3  1305.1
  5231.6 1308.08    5272 1309.91  5316.6 1313.94  5351.1 1314.48  5420.2  1315.4
#Mann= 10 ,-1 , 0
  4557.1     .12       0  4671.9     .07       0  4687.4     .12       0
    4785     .07       0  4894.6     .12       0  4977.9     .05       0
  4986.1     .12       0  5013.9    .035       0  5231.6     .07       0
  5351.1    .035       0
Bank Sta=4977.9,4986.1
XS Rating Curve= 0 ,0
Exp/Cntr=0.3,0.1

Type RM Length L Ch R = 1 ,11563   ,457,457,457
BEGIN DESCRIPTION:
WERNER CREEK 25.0
END DESCRIPTION:
XS GIS Cut Line= 3
       2069205.4     13903994.44        2068975.       13904125.
       2068609.1     13904174.87
#Sta/Elev= 30
  4741.1 1317.75  4764.5 1318.84  4787.4 1314.54    4799 1311.04  4852.3 1309.39
  4903.4 1305.48  4933.1 1303.07  4938.8  1300.9  4948.4 1299.48  4960.5 1294.16
  4970.6 1292.17  4976.3 1288.96  4988.1 1285.38  4988.6 1284.88  4996.3 1285.38
  5026.1 1289.49  5042.1 1289.21  5096.8  1293.9  5119.5 1291.99  5137.1 1286.77
  5147.2 1287.15  5157.3 1289.99  5197.5 1296.41  5207.8 1299.49    5228  1308.8
  5258.2 1314.55  5278.4    1316  5297.4 1319.02  5341.6 1320.81  5375.2 1324.49
#Mann= 6 ,-1 , 0
  4741.1    .035       0  4903.4     .12       0  4988.1     .05       0
  4996.3     .12       0  5197.5     .07       0  5297.4    .035       0
Bank Sta=4988.1,4996.3
XS Rating Curve= 0 ,0
Exp/Cntr=0.3,0.1

Type RM Length L Ch R = 1 ,11106   ,441,441,441
BEGIN DESCRIPTION:
WERNER CREEK 24.0
END DESCRIPTION:
XS GIS Cut Line= 3
      2069177.62     13903855.55      2068733.17      13903824.3
      2068493.62     13903845.13
#Sta/Elev= 30
  4550.7 1313.86  4561.2  1313.7  4583.4 1313.16  4623.5 1309.06  4634.2    1307
  4673.6  1303.7  4693.7 1300.64  4703.7 1297.61  4713.7 1296.12  4783.9 1292.81
  4904.2 1292.82  4917.1 1291.85  4934.3 1289.34  4944.3 1286.91  4964.3 1284.98
  4979.6 1281.99  4980.1 1281.49  4989.2 1281.99  4992.8 1290.63  4996.3 1290.63
  5004.4 1309.44  5014.5 1313.72  5024.5  1316.3  5054.6 1321.27  5084.8 1322.89
  5134.9 1328.82  5173.8 1341.96  5178.8 1342.98  5185.1 1346.23  5236.7 1348.34
#Mann= 4 ,-1 , 0
  4550.7    .035       0  4561.2     .12       0  4979.6     .05       0
  4989.2     .07       0
Bank Sta=4979.6,4989.2
XS Rating Curve= 0 ,0
Exp/Cntr=0.3,0.1

Type RM Length L Ch R = 1 ,10665   ,472,472,472
BEGIN DESCRIPTION:
WERNER CREEK 23.0
END DESCRIPTION:
XS GIS Cut Line= 3
      2069431.05     13903602.07        2069025.       13903525.
      2068632.43     13903497.91
#Sta/Elev= 30
  4586.4 1325.46    4640 1322.98  4724.9 1319.69  4754.4 1317.45  4759.4 1317.77
  4796.1  1314.4  4811.7 1313.82  4826.7 1312.02  4836.8  1299.5    4847 1292.71
    4864 1288.65  4921.3 1287.87  4948.8 1284.95  4968.5 1284.83  4989.5 1280.26
  4992.4 1276.84  4992.9 1276.34    5002 1276.84  5019.7 1281.26  5029.8  1284.6
  5039.8 1286.27  5059.8  1286.8  5099.9 1292.45    5140 1300.42  5200.2 1305.77
  5210.2 1306.89  5216.4 1308.55  5230.2 1309.75  5300.4  1314.1  5393.2  1322.3
#Mann= 4 ,-1 , 0
  4586.4    .035       0    4640     .12       0  4992.4     .05       0
    5002     .12       0
Bank Sta=4992.4,5002
XS Rating Curve= 0 ,0
Exp/Cntr=0.3,0.1

Type RM Length L Ch R = 1 ,10193   ,463,463,463
BEGIN DESCRIPTION:
WERNER CREEK 22.0
END DESCRIPTION:
XS GIS Cut Line= 3
      2069316.54     13903011.79        2069025.       13903125.
      2068375.56     13903379.84
#Sta/Elev= 30
  4691.4 1308.76  4880.3 1306.05  4910.2 1302.92  4918.3 1301.17  4929.1  1296.1
  4934.8 1289.86  4964.7 1279.67    4972 1275.51  4984.3 1272.42  4984.8 1271.92
    4994 1272.42  4994.6 1274.41  5001.5 1279.64  5036.4 1284.44  5067.9 1285.79
  5151.9 1285.21    5176 1286.53    5219 1291.49  5265.8 1299.56    5320 1305.54
  5344.4 1310.67  5423.1 1318.18  5452.9 1322.79  5476.8 1323.53  5530.5 1328.83
  5561.4 1334.31  5573.5 1339.38  5596.5 1345.84    5621 1347.27  5701.8 1347.21
#Mann= 3 ,-1 , 0
  4691.4     .12       0  4984.3     .05       0    4994     .12       0
Bank Sta=4984.3,4994
XS Rating Curve= 0 ,0
Exp/Cntr=0.3,0.1

Type RM Length L Ch R = 1 ,9730    ,427,427,427
BEGIN DESCRIPTION:
WERNER CREEK 21.0
END DESCRIPTION:
XS GIS Cut Line= 3
      2069299.14     13902928.47        2068825.       13902725.
      2067965.79     13902782.64
#Sta/Elev= 30
  4490.6 1305.23  4640.4 1297.79    4664 1298.14  4669.4 1293.73    4693  1290.1
  4740.1  1286.6  4769.1 1282.32  4886.9 1279.43  4897.8 1278.56    4911 1272.75
  4911.5 1272.25  4920.9 1272.75  4952.1 1273.38  4968.5 1277.18  5009.1 1276.58
  5026.6 1278.88  5126.8 1282.65  5166.9 1289.22    5217 1304.74  5226.4 1307.12
  5231.4 1305.86  5247.1  1312.1  5257.1 1313.89  5381.2 1326.38  5437.5 1334.22
  5497.7 1347.15  5537.9 1349.24    5681 1356.54  5738.2 1364.16  5867.7 1370.57
#Mann= 4 ,-1 , 0
  4490.6     .12       0    4911     .05       0  4920.9     .12       0
  5537.9     .07       0
Bank Sta=4911,4920.9
XS Rating Curve= 0 ,0
Exp/Cntr=0.3,0.1

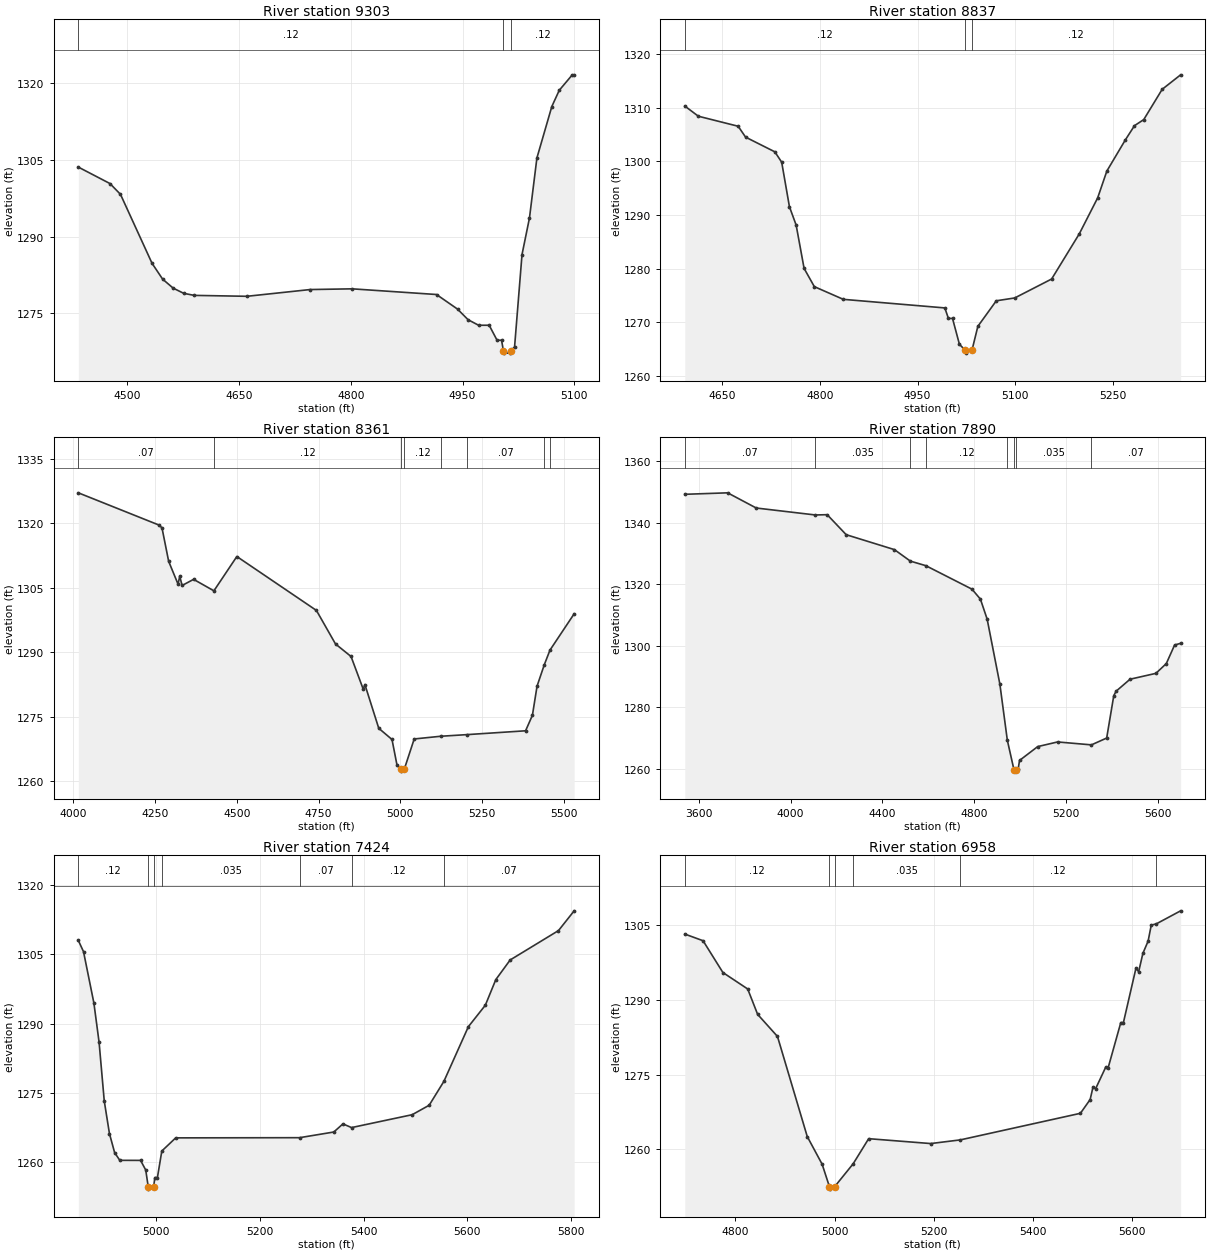
Type RM Length L Ch R = 1 ,9303    ,466,466,466
BEGIN DESCRIPTION:
WERNER CREEK 20.0
END DESCRIPTION:
XS GIS Cut Line= 3
      2069325.02     13902825.02        2068925.       13902425.
        2068925.     13902325.02
#Sta/Elev= 30
  4434.1  1303.6  4476.6 1300.38  4490.7 1298.27  4533.1 1284.78  4547.3 1281.69
  4561.4 1279.94  4575.6 1278.92  4589.7 1278.52  4660.4 1278.34  4745.3 1279.66
  4801.8  1279.8    4915 1278.69  4943.2 1275.84  4957.4 1273.76  4971.5 1272.68
  4985.7 1272.68  4996.3 1269.75  5002.3 1269.75  5004.8 1267.73  5005.3 1267.23
  5014.3 1267.23  5014.8 1267.73  5019.8 1268.44  5029.8 1286.51  5039.8 1293.65
  5049.8 1305.39  5069.8 1315.44  5079.8 1318.62  5097.3 1321.64  5099.8 1321.64
#Mann= 3 ,-1 , 0
  4434.1     .12       0  5004.8     .05       0  5014.8     .12       0
Bank Sta=5004.8,5014.8
XS Rating Curve= 0 ,0
Exp/Cntr=0.3,0.1

Type RM Length L Ch R = 1 ,8837    ,476,476,476
BEGIN DESCRIPTION:
WERNER CREEK 19.0
END DESCRIPTION:
XS GIS Cut Line= 3
      2069559.56      13902838.2        2069375.       13902475.
      2069124.97     13902224.97
#Sta/Elev= 30
  4592.7 1310.34  4613.5 1308.44  4674.6 1306.57    4686 1304.54  4730.9  1301.8
  4741.4 1299.87  4753.3 1291.56  4763.6 1288.14  4775.8 1280.06  4791.5 1276.66
    4836 1274.29  4991.8 1272.69  4997.3 1270.73  5003.6 1270.73  5014.2 1265.91
  5023.4 1264.76  5023.9 1264.26  5033.4 1264.76  5042.5 1269.26  5070.8 1274.02
  5099.1 1274.55  5155.7 1278.08  5198.1 1286.49  5226.4 1293.22  5240.5 1298.22
  5268.8 1304.01  5282.9 1306.68  5297.1 1307.81  5325.4 1313.46  5353.7 1316.16
#Mann= 3 ,-1 , 0
  4592.7     .12       0  5023.4     .05       0  5033.4     .12       0
Bank Sta=5023.4,5033.4
XS Rating Curve= 0 ,0
Exp/Cntr=0.3,0.1

Type RM Length L Ch R = 1 ,8361    ,471,471,471
BEGIN DESCRIPTION:
WERNER CREEK 18.0
END DESCRIPTION:
XS GIS Cut Line= 3
      2070000.52     13903233.99        2069775.       13902275.
      2069374.97     13901924.97
#Sta/Elev= 30
  4014.9 1327.07  4260.4 1319.61  4270.7 1318.96  4291.2 1311.14  4319.9 1305.83
  4325.1 1307.68  4332.3 1305.52  4367.5 1306.95  4429.6 1304.28  4499.8 1312.26
  4743.2 1299.72  4801.6 1291.92  4849.1 1289.01  4886.4  1281.4  4891.5 1282.48
  4933.9 1272.31  4974.4 1269.71  4989.8 1263.71  5002.2 1262.85  5002.7 1262.35
  5012.2 1262.85  5042.3 1269.83  5123.4 1270.46    5204 1270.84    5383 1271.73
  5403.9 1275.33  5418.1 1282.11  5440.3  1287.1  5457.6 1290.49  5531.6 1298.94
#Mann= 8 ,-1 , 0
  4014.9     .07       0  4429.6     .12       0  5002.2     .05       0
  5012.2     .12       0  5123.4    .035       0    5204     .07       0
  5440.3     .12       0  5457.6     .07       0
Bank Sta=5002.2,5012.2
XS Rating Curve= 0 ,0
Exp/Cntr=0.3,0.1

Type RM Length L Ch R = 1 ,7890    ,466,466,466
BEGIN DESCRIPTION:
WERNER CREEK 17.0
END DESCRIPTION:
XS GIS Cut Line= 3
      2071295.71      13902501.4        2069975.       13901875.
      2069289.35     13901737.62
#Sta/Elev= 30
  3538.7 1349.27  3725.4 1349.75  3850.1 1344.81  4107.5 1342.55  4159.3 1342.64
  4242.2 1336.13  4452.3 1331.28  4521.8 1327.54  4589.5 1326.05  4790.1 1318.43
  4827.1 1315.18  4856.5 1308.66  4911.9 1287.54  4944.4  1269.3  4973.1 1259.74
  4973.6 1259.24  4983.5 1259.74  4991.8 1260.03  4997.7 1262.72  5076.8 1267.22
  5163.6 1268.73    5311 1267.78  5377.4    1270  5408.4  1283.8  5418.6 1285.24
  5479.3 1289.13    5592 1291.04  5637.3 1294.22  5673.5 1300.26  5699.7  1300.8
#Mann= 8 ,-1 , 0
  3538.7     .07       0  4107.5    .035       0  4521.8     .07       0
  4589.5     .12       0  4944.4    .035       0  4973.1    .035       0
  4983.5    .035       0    5311     .07       0
Bank Sta=4973.1,4983.5
XS Rating Curve= 0 ,0
Exp/Cntr=0.3,0.1

Type RM Length L Ch R = 1 ,7424    ,466,466,466
BEGIN DESCRIPTION:
WERNER CREEK 16.0
END DESCRIPTION:
XS GIS Cut Line= 3
      2070175.02       13901425.        2070025.       13901425.
      2069225.05     13901325.01
#Sta/Elev= 30
    4850 1308.01    4860 1305.58    4880 1294.45    4890 1285.97    4900 1273.21
    4910 1266.15    4920 1262.02    4930 1260.35    4970 1260.34    4980 1258.25
  4984.8 1254.61  4985.3 1254.11  4995.3 1254.61  4997.5 1256.61  5002.5 1256.61
    5011 1262.37  5037.8 1265.22  5276.7 1265.26  5342.7 1266.49  5360.3 1268.25
  5376.9 1267.45  5493.8 1270.24  5526.6 1272.29    5555 1277.47  5602.2 1289.32
  5634.9 1293.97  5655.1 1299.52  5682.8 1303.78    5776 1310.15  5806.2 1314.43
#Mann= 7 ,-1 , 0
    4850     .12       0  4984.8     .05       0  4995.3     .12       0
    5011    .035       0  5276.7     .07       0  5376.9     .12       0
    5555     .07       0
Bank Sta=4984.8,4995.3
XS Rating Curve= 0 ,0
Exp/Cntr=0.3,0.1

Type RM Length L Ch R = 1 ,6958    ,450,450,450
BEGIN DESCRIPTION:
WERNER CREEK 15.0
END DESCRIPTION:
XS GIS Cut Line= 3
      2070281.77     13900970.13        2069975.       13900975.
       2069323.4     13901209.73
#Sta/Elev= 30
  4698.2 1303.25    4735 1301.91    4775 1295.52    4825 1292.21    4845 1287.11
    4885 1282.67    4945 1262.55    4975 1256.99  4989.7 1252.48  4990.2 1251.98
  5000.3 1252.48  5037.6 1257.08  5068.8 1262.12  5193.9 1261.14  5253.7 1261.88
  5495.6 1267.22  5515.2 1269.98  5520.9 1272.44  5526.3 1272.17  5546.3 1276.43
  5551.6  1276.4    5577 1285.45  5582.3 1285.46  5607.7 1296.45    5613 1295.66
  5621.5 1299.36  5632.1 1301.84  5638.4 1305.05  5648.4 1305.29  5697.6 1307.92
#Mann= 6 ,-1 , 0
  4698.2     .12       0  4989.7     .05       0  5000.3     .12       0
  5037.6    .035       0  5253.7     .12       0  5648.4     .07       0
Bank Sta=4989.7,5000.3
XS Rating Curve= 0 ,0
Exp/Cntr=0.3,0.1

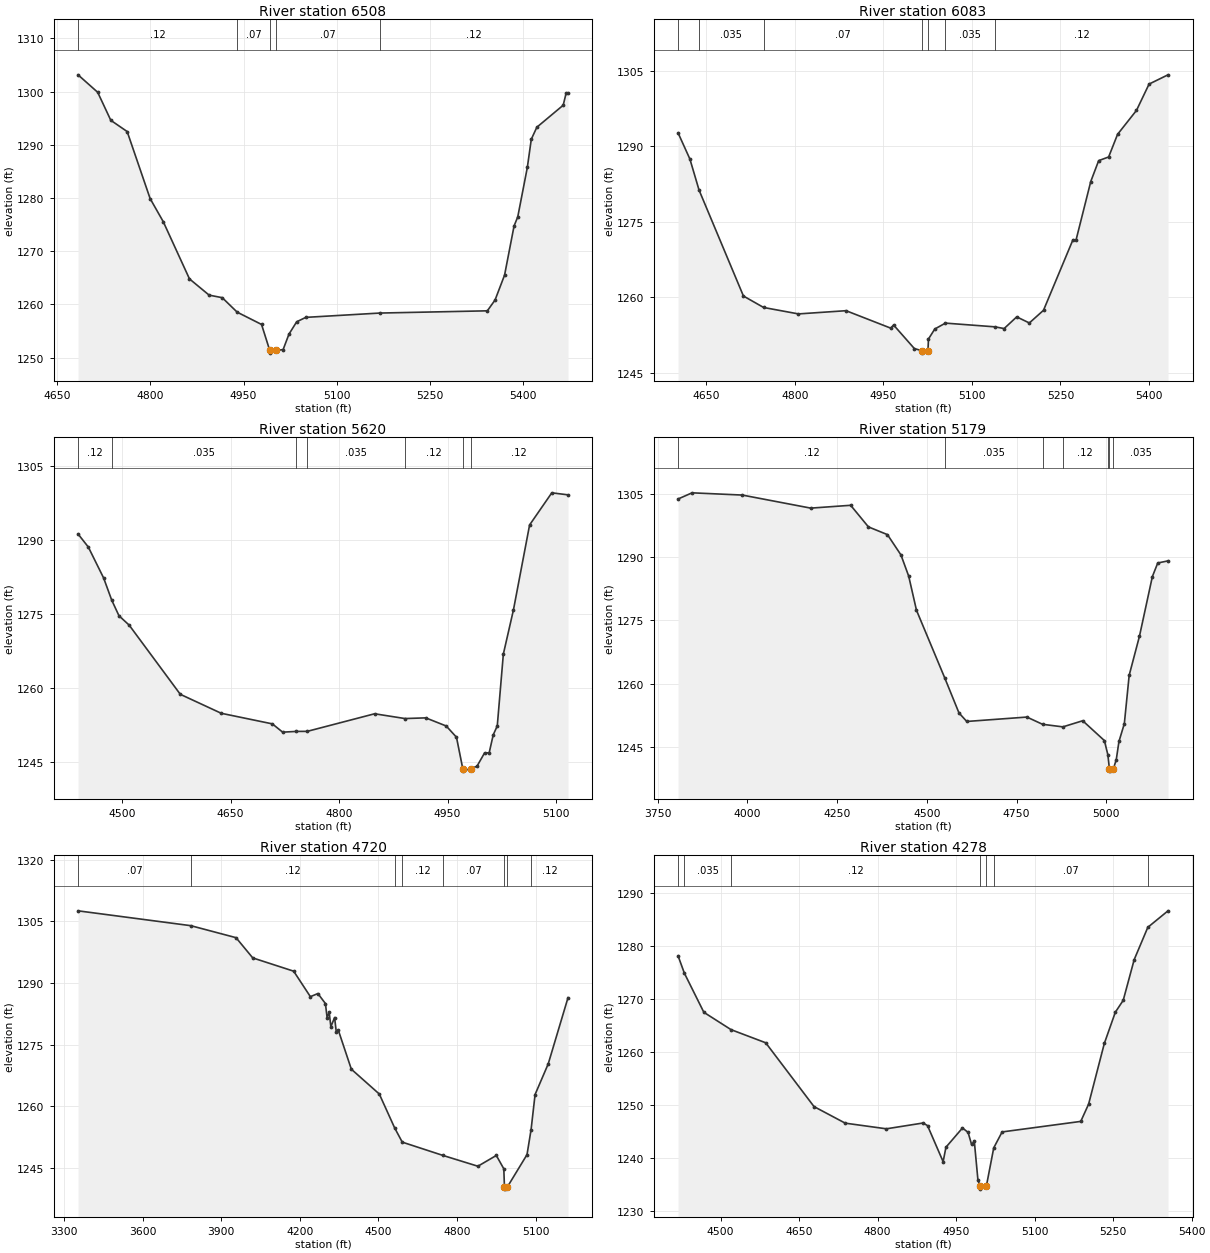
Type RM Length L Ch R = 1 ,6508    ,425,425,425
BEGIN DESCRIPTION:
WERNER CREEK 14.0
END DESCRIPTION:
XS GIS Cut Line= 3
      2070124.99       13900475.        2069825.       13900575.
      2069425.01     13900824.99
#Sta/Elev= 30
  4683.8 1303.14  4715.4 1299.86  4736.5 1294.59  4762.8 1292.48  4799.7 1279.89
  4820.8 1275.55    4863 1264.79  4894.6 1261.74  4915.7 1261.26  4939.7 1258.54
  4978.9 1256.23  4992.1 1251.34  4992.6 1250.84  5002.7 1251.34  5013.6 1251.51
    5023 1254.41  5035.4 1256.73  5050.1 1257.56  5168.9 1258.37    5342 1258.79
  5354.4 1260.82  5369.7  1265.5    5385 1274.75  5390.9 1276.44  5406.3 1285.73
  5412.7 1291.04  5421.6 1293.29    5464 1297.43  5468.8 1299.75  5471.7 1299.75
#Mann= 5 ,-1 , 0
  4683.8     .12       0  4939.7     .07       0  4992.1     .05       0
  5002.7     .07       0  5168.9     .12       0
Bank Sta=4992.1,5002.7
XS Rating Curve= 0 ,0
Exp/Cntr=0.3,0.1

Type RM Length L Ch R = 1 ,6083    ,463,463,463
BEGIN DESCRIPTION:
WERNER CREEK 13.0
END DESCRIPTION:
XS GIS Cut Line= 3
      2070024.96     13900274.99        2069625.       13900225.
      2069224.97     13900074.99
#Sta/Elev= 30
    4602 1292.68  4622.1 1287.46  4637.6 1281.29  4712.8 1260.22    4747 1257.94
    4806 1256.66  4886.7  1257.3  4962.2 1253.84  4967.3 1254.45  5002.5 1249.76
  5014.8 1249.36  5015.3 1248.86  5025.5 1249.36  5026.4 1251.68  5037.1 1253.66
  5055.1 1254.83  5138.9 1254.09  5154.6 1253.75  5175.9 1256.07  5197.3 1254.86
  5221.3 1257.38  5271.2 1271.41  5276.5 1271.38  5301.4    1283  5314.8 1287.15
  5331.7 1287.88  5346.8 1292.38  5378.9 1297.15  5400.2 1302.38  5432.3 1304.22
#Mann= 7 ,-1 , 0
    4602     .12       0  4637.6    .035       0    4747     .07       0
  5014.8     .05       0  5025.5     .07       0  5055.1    .035       0
  5138.9     .12       0
Bank Sta=5014.8,5025.5
XS Rating Curve= 0 ,0
Exp/Cntr=0.3,0.1

Type RM Length L Ch R = 1 ,5620    ,441,441,441
BEGIN DESCRIPTION:
WERNER CREEK 12.0
END DESCRIPTION:
XS GIS Cut Line= 3
      2070025.01     13900225.01        2069625.       13899825.
        2069525.       13899775.
#Sta/Elev= 30
  4439.1  1291.3  4453.3 1288.65  4474.5 1282.36  4485.6  1277.9  4495.7  1274.7
  4509.8  1272.8  4580.5 1258.76  4637.1 1254.91  4707.8 1252.76    4722 1251.08
  4741.1 1251.23    4756 1251.24  4849.2 1254.81  4891.2 1253.84  4919.9 1253.98
  4948.2 1252.33  4962.4 1250.05  4971.1 1243.67  4971.6 1243.17  4981.9 1243.67
  4990.7 1244.15  5001.3 1246.88  5007.6 1246.88  5013.2 1250.53  5018.8 1252.34
  5027.2 1266.92  5041.1 1275.84  5063.5 1293.13  5094.2 1299.65  5116.6 1299.24
#Mann= 7 ,-1 , 0
  4439.1     .12       0  4485.6    .035       0  4741.1     .07       0
    4756    .035       0  4891.2     .12       0  4971.1     .05       0
  4981.9     .12       0
Bank Sta=4971.1,4981.9
XS Rating Curve= 0 ,0
Exp/Cntr=0.3,0.1

Type RM Length L Ch R = 1 ,5179    ,459,459,459
BEGIN DESCRIPTION:
WERNER CREEK 11.0
END DESCRIPTION:
XS GIS Cut Line= 3
      2070507.49     13900556.97        2069925.       13899525.
      2069774.99       13899425.
#Sta/Elev= 30
  3806.6 1303.72  3845.6 1305.18  3985.7 1304.65  4176.3 1301.56  4287.6 1302.23
  4337.1 1297.12  4390.1 1295.29  4427.7 1290.49  4449.3 1285.47    4471  1277.4
  4550.1 1261.32  4589.4 1253.11  4611.1 1251.09  4778.6 1252.13  4822.3 1250.42
  4878.9 1249.81  4934.2 1251.26  4994.6 1246.57  5004.3  1243.2  5008.7 1239.84
  5009.2 1239.34  5019.5 1239.84  5027.7 1242.05  5035.2 1246.35  5050.2 1250.57
  5063.7 1262.02  5092.3 1271.24  5128.3 1285.36  5143.3 1288.58  5171.9 1289.08
#Mann= 7 ,-1 , 0
  3806.6     .12       0  4550.1    .035       0  4822.3     .07       0
  4878.9     .12       0  5004.3    .035       0  5008.7     .05       0
  5019.5    .035       0
Bank Sta=5008.7,5019.5
XS Rating Curve= 0 ,0
Exp/Cntr=0.3,0.1

Type RM Length L Ch R = 1 ,4720    ,442,442,442
BEGIN DESCRIPTION:
WERNER CREEK 10.0
END DESCRIPTION:
XS GIS Cut Line= 3
      2071274.84     13900494.45        2070225.       13899225.
      2070025.03     13899125.01
#Sta/Elev= 30
  3352.9 1307.54  3783.3 1303.93  3956.2 1301.01    4020 1296.09  4176.3 1292.86
  4240.1 1286.66  4268.8 1287.42  4297.5 1284.99    4304 1281.54  4311.8 1282.89
  4318.3 1279.35  4332.6 1281.59  4339.1    1278    4347 1278.47  4396.5 1269.02
  4503.3 1262.98  4561.8 1254.75  4590.9 1251.28  4746.6 1248.04  4879.7 1245.42
  4950.1 1248.04  4978.7 1244.79  4981.2 1240.35  4981.7 1239.85    4992 1240.35
  5067.3 1248.24  5082.8  1254.3  5098.1 1262.86  5148.4 1270.33  5223.8 1286.41
#Mann= 8 ,-1 , 0
  3352.9     .07       0  3783.3     .12       0  4561.8     .07       0
  4590.9     .12       0  4746.6     .07       0  4981.2     .05       0
    4992     .07       0  5082.8     .12       0
Bank Sta=4981.2,4992
XS Rating Curve= 0 ,0
Exp/Cntr=0.3,0.1

Type RM Length L Ch R = 1 ,4278    ,457,457,457
BEGIN DESCRIPTION:
WERNER CREEK 9.0
END DESCRIPTION:
XS GIS Cut Line= 3
      2070735.28      13899460.9        2070525.       13898925.
      2070225.03     13898725.02
#Sta/Elev= 30
  4418.6 1278.14  4430.7 1274.85  4467.9 1267.46  4519.9 1264.18  4586.1  1261.7
  4678.4 1249.64    4738 1246.51  4816.7 1245.44  4886.9 1246.54  4895.3 1246.04
  4925.1 1239.23  4930.5 1241.96  4962.1  1245.6  4972.8 1244.76  4979.4  1242.5
  4984.7 1243.08  4991.6 1235.77  4995.9 1234.54  4996.4 1234.04  5007.6 1234.54
  5021.8 1241.84  5037.8 1244.85  5188.1 1246.84  5203.1 1250.11  5233.1 1261.57
  5254.2 1267.49  5269.2 1269.72  5290.2 1277.42  5316.2 1283.52  5354.8 1286.64
#Mann= 7 ,-1 , 0
  4418.6     .12       0  4430.7    .035       0  4519.9     .12       0
  4995.9     .05       0  5007.6     .12       0  5021.8     .07       0
  5316.2    .035       0
Bank Sta=4995.9,5007.6
XS Rating Curve= 0 ,0
Exp/Cntr=0.3,0.1