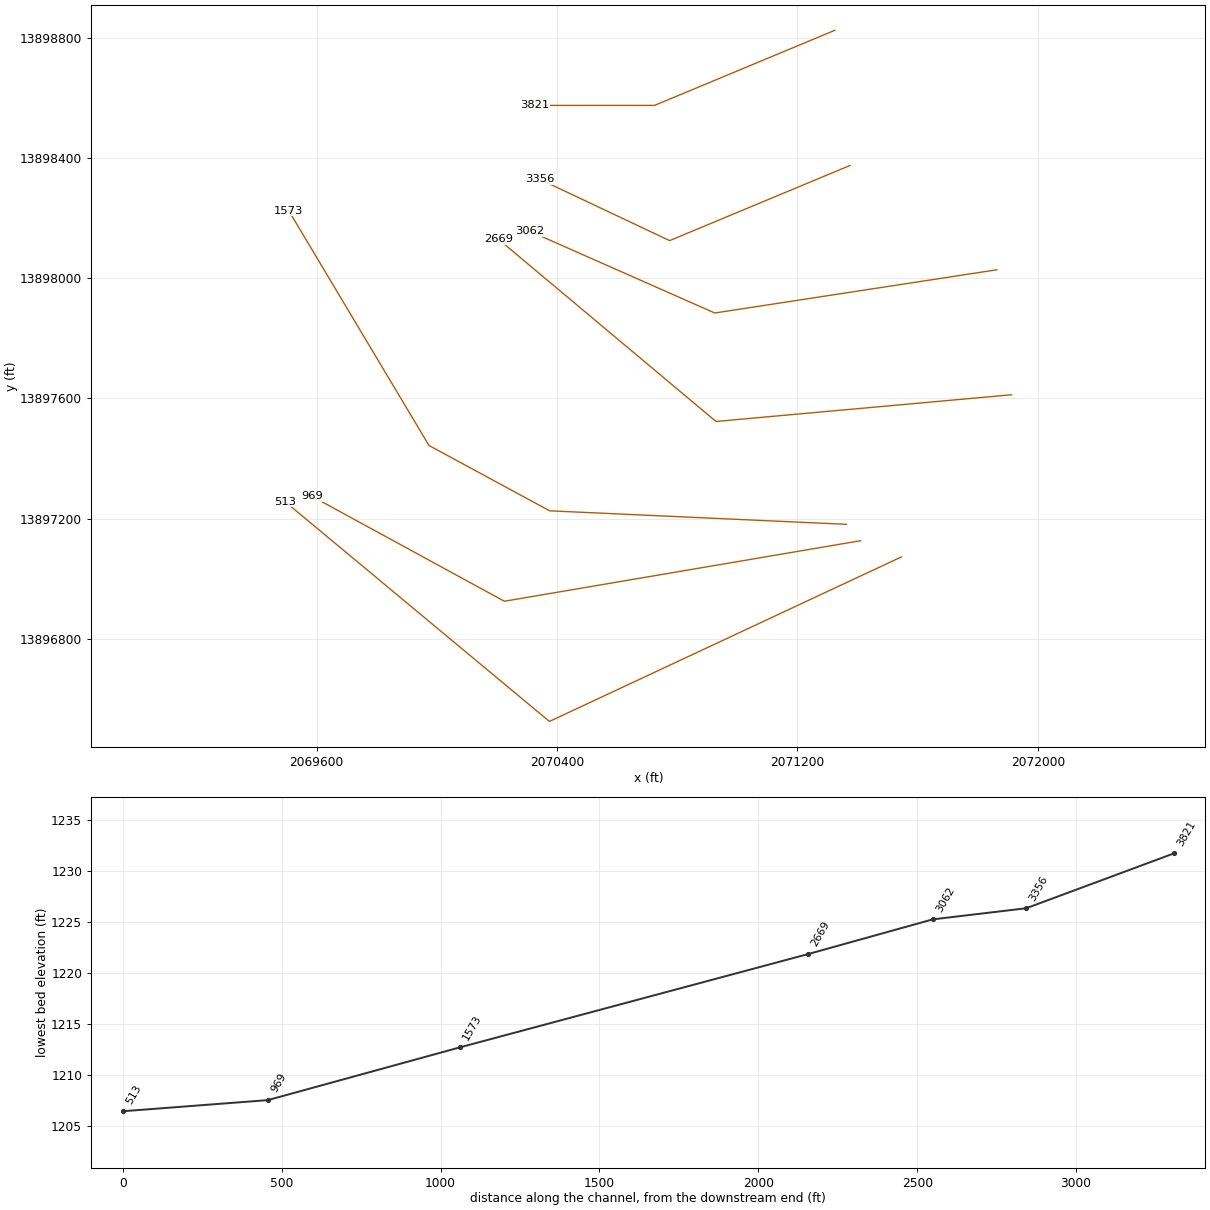
HEC-RAS study WERNER CREEK.prj: WERNER CREEK Base Level Engineering

--- WERNER CREEK.g01 (geometry) --- (continued)

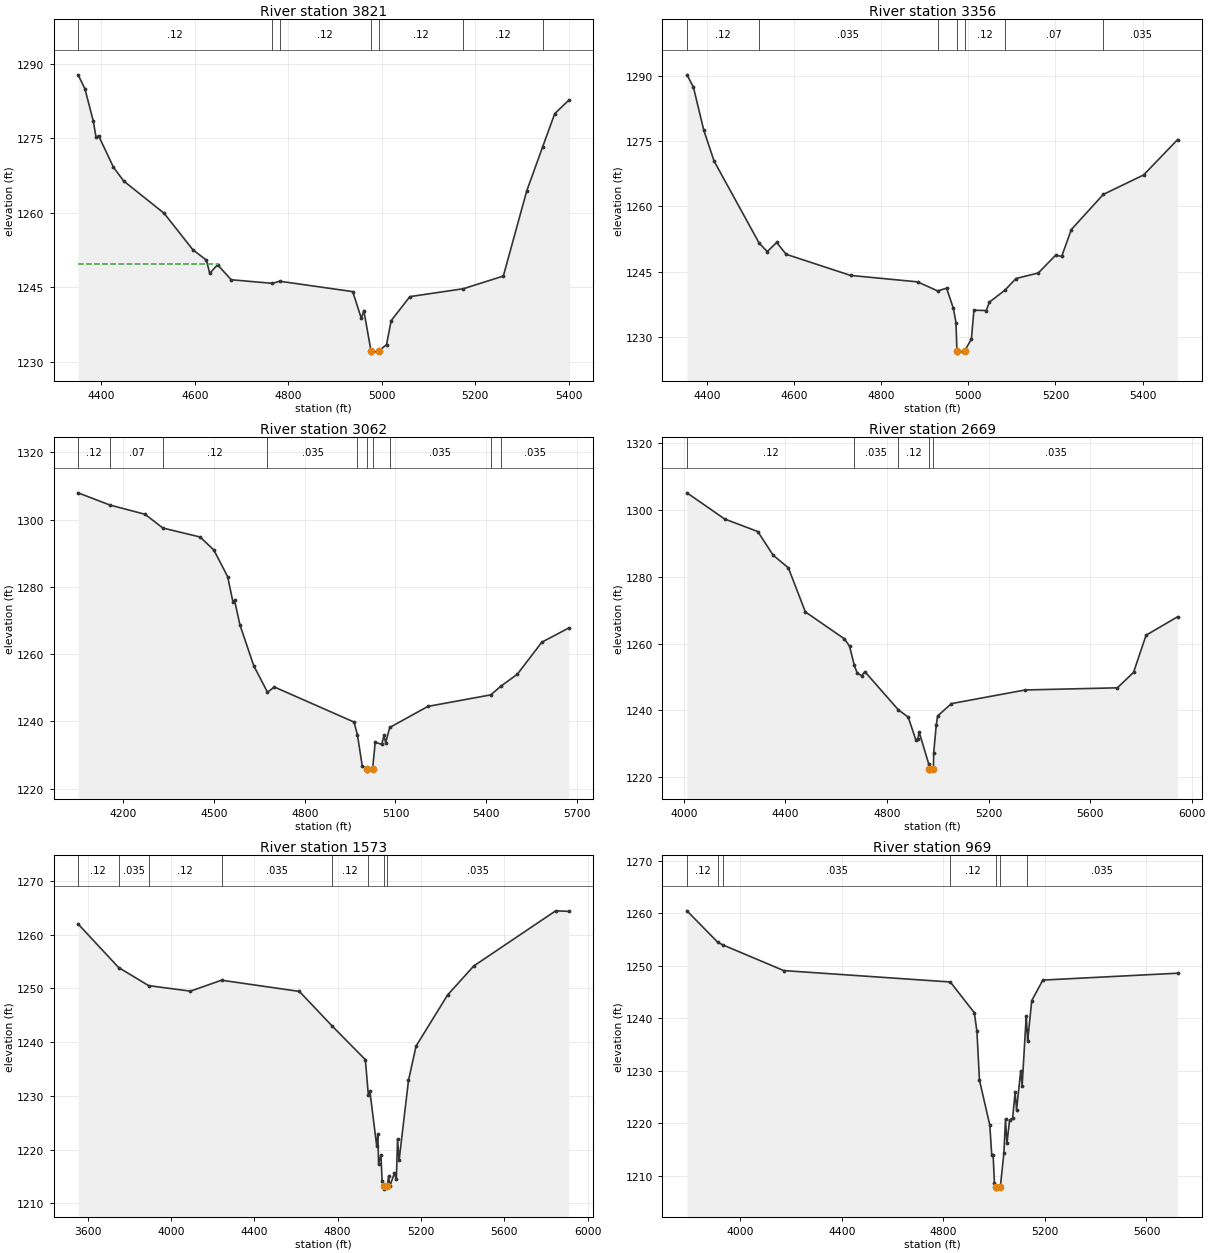
Type RM Length L Ch R = 1 ,3821    ,465,465,465
BEGIN DESCRIPTION:
WERNER CREEK 8.0
END DESCRIPTION:
XS GIS Cut Line= 3
      2071324.99       13898825.        2070725.       13898575.
      2070324.99       13898575.
#Sta/Elev= 30
    4350 1287.79  4364.6 1284.99  4382.5 1278.49  4388.5 1275.19  4393.9 1275.51
  4425.8 1269.15  4447.5  1266.4  4534.2 1259.87  4595.4 1252.56  4624.6 1250.43
  4631.7 1247.79  4648.5 1249.51  4677.7 1246.48  4765.7 1245.76  4781.5 1246.18
  4937.7 1244.09  4956.1  1238.7  4961.5 1240.28  4976.7 1232.19  4977.2 1231.69
  4994.1 1232.19    5010 1233.39    5020 1238.24    5060 1243.08  5174.3 1244.67
    5260 1247.23    5310 1264.37  5343.9 1273.22    5370 1279.97    5400 1282.67
#Mann= 7 ,-1 , 0
    4350     .12       0  4765.7    .035       0  4781.5     .12       0
  4976.7     .05       0  4994.1     .12       0  5174.3     .12       0
  5343.9    .035       0
#XS Ineff= 2 , 0
       0    4649  1249.7               0
Permanent Ineff=
       F       F
Bank Sta=4976.7,4994.1
XS Rating Curve= 0 ,0
Exp/Cntr=0.3,0.1

Type RM Length L Ch R = 1 ,3356    ,294,294,294
BEGIN DESCRIPTION:
WERNER CREEK 7.0
END DESCRIPTION:
XS GIS Cut Line= 3
      2071375.04     13898375.02        2070775.       13898125.
      2070344.26     13898328.43
#Sta/Elev= 30
  4354.1 1290.23  4368.8 1287.43  4392.6 1277.53  4416.4 1270.41  4519.6 1251.61
  4538.3 1249.63    4560 1251.73  4581.6 1249.02  4729.5 1244.16  4883.3 1242.68
  4929.6  1240.6    4950 1241.22  4965.7 1236.57  4971.6 1233.31  4973.8 1226.81
  4974.3 1226.31  4991.2 1226.81  5006.9 1229.49  5012.8 1236.17  5041.1 1236.09
  5048.4 1238.04  5083.3 1240.71  5109.4 1243.45  5160.4 1244.71  5200.4 1248.79
  5214.3 1248.54  5236.4  1254.7  5309.8 1262.76  5402.3 1267.23  5480.5 1275.37
#Mann= 7 ,-1 , 0
  4354.1     .12       0  4519.6    .035       0  4929.6     .12       0
  4973.8     .05       0  4991.2     .12       0  5083.3     .07       0
  5309.8    .035       0
Bank Sta=4973.8,4991.2
XS Rating Curve= 0 ,0
Exp/Cntr=0.3,0.1

Type RM Length L Ch R = 1 ,3062    ,393,393,393
BEGIN DESCRIPTION:
WERNER CREEK 6.0
END DESCRIPTION:
XS GIS Cut Line= 3
      2071864.11       13898028.      2070925.16     13897884.16
      2070309.32     13898156.32
#Sta/Elev= 30
  4050.1 1307.93  4155.5  1304.3  4271.8 1301.55  4330.4 1297.47  4453.9  1294.8
  4499.3 1290.93  4544.9 1283.01  4562.6 1275.44  4567.7 1276.02  4585.4 1268.72
  4631.1 1256.57  4676.6 1248.68  4699.5 1250.22  4963.1  1239.8  4974.3 1235.94
  4990.1 1226.79  5006.8 1225.72  5007.3 1225.22  5024.2 1225.72    5033 1233.74
  5054.8 1233.22  5062.1 1235.86  5067.6 1233.63  5080.9 1238.19  5207.4 1244.46
  5415.1 1247.88  5449.4  1250.5  5503.1 1254.02  5584.3 1263.55  5673.3 1267.76
#Mann= 10 ,-1 , 0
  4050.1     .12       0  4155.5     .07       0  4330.4     .12       0
  4676.6    .035       0  4974.3     .12       0  5006.8     .05       0
  5024.2     .12       0  5080.9    .035       0  5415.1     .07       0
  5449.4    .035       0
Bank Sta=5006.8,5024.2
XS Rating Curve= 0 ,0
Exp/Cntr=0.3,0.1

Type RM Length L Ch R = 1 ,2669    ,1096,1096,1096
BEGIN DESCRIPTION:
WERNER CREEK 5.0
END DESCRIPTION:
XS GIS Cut Line= 3
      2071912.73     13897612.11      2070929.23     13897523.22
      2070204.83     13898130.07
#Sta/Elev= 30
  4012.5 1305.09  4160.8 1297.26  4291.4 1293.51  4351.6 1286.45  4411.8 1282.64
  4478.7 1269.47  4632.7 1261.38  4652.8  1259.2  4671.2 1253.55  4682.9 1251.19
  4700.3 1250.35  4713.1 1251.58  4845.2 1240.13  4883.8 1237.98  4913.9 1231.13
  4921.8 1231.37  4926.8 1233.54  4964.1 1224.09  4965.4 1222.31  4965.9 1221.81
  4982.9 1222.31  4984.2 1227.28  4994.2 1235.61  4999.6 1238.33  5054.2 1242.02
  5344.7  1246.1  5707.4 1246.74  5771.1 1251.34  5820.6 1262.49    5945 1268.01
#Mann= 5 ,-1 , 0
  4012.5     .12       0  4671.2    .035       0  4845.2     .12       0
  4965.4    .035       0  4982.9    .035       0
Bank Sta=4965.4,4982.9
XS Rating Curve= 0 ,0
Exp/Cntr=0.3,0.1

Type RM Length L Ch R = 1 ,1573    ,604,604,604
BEGIN DESCRIPTION:
WERNER CREEK 3.0
END DESCRIPTION:
XS GIS Cut Line= 4
      2071363.62     13897180.89       2070375.7     13897225.91
      2069974.24     13897443.33      2069507.85     13898224.15
#Sta/Elev= 30
  3554.5 1262.01    3749  1253.9  3893.2 1250.53  4093.7  1249.5    4243 1251.54
  4616.6 1249.45  4774.3    1243  4933.3 1236.75  4947.7 1230.13  4955.2 1230.85
  4987.5 1220.75  4993.2 1222.84  4996.7 1217.37    5008 1219.04  5013.8 1214.08
  5020.6 1213.16  5021.1 1212.66  5038.2 1213.16    5045 1215.08  5050.8 1213.23
  5072.2 1215.57    5082 1214.49  5087.8 1221.99  5095.1 1217.99  5140.3 1232.88
  5176.7 1239.28  5328.1  1248.8  5453.6 1254.19  5846.6 1264.45  5909.5 1264.35
#Mann= 8 ,-1 , 0
  3554.5     .12       0    3749    .035       0  3893.2     .12       0
    4243    .035       0  4774.3     .12       0  4947.7    .035       0
  5020.6    .035       0  5038.2    .035       0
Bank Sta=5020.6,5038.2
XS Rating Curve= 0 ,0
Exp/Cntr=0.3,0.1

Type RM Length L Ch R = 1 ,969     ,456,456,456
BEGIN DESCRIPTION:
WERNER CREEK 2.0
END DESCRIPTION:
XS GIS Cut Line= 3
      2071410.64     13897126.49        2070225.       13896925.
      2069584.33     13897274.43
#Sta/Elev= 30
  3790.4 1260.45  3911.8 1254.46  3932.4 1253.95  4171.4 1249.08  4827.5 1246.91
    4922 1241.06  4932.2 1237.55  4942.3 1228.21  4982.9 1219.69  4990.5 1214.05
  4995.9 1214.05  5001.1 1208.73    5007 1207.99  5007.5 1207.49  5024.6 1207.99
  5038.6 1214.42  5044.8 1220.82  5050.5 1216.22  5060.9 1220.61  5072.8    1221
  5082.7 1225.93  5088.4 1222.61  5104.6 1229.95  5110.3 1227.19  5126.4 1240.42
  5129.7 1237.73  5132.1 1235.77  5148.2 1243.37  5191.9 1247.27  5722.8 1248.58
#Mann= 7 ,-1 , 0
  3790.4     .12       0  3911.8     .07       0  3932.4    .035       0
  4827.5     .12       0    5007     .05       0  5024.6     .12       0
  5129.7    .035       0
Bank Sta=5007,5024.6
XS Rating Curve= 0 ,0
Exp/Cntr=0.3,0.1

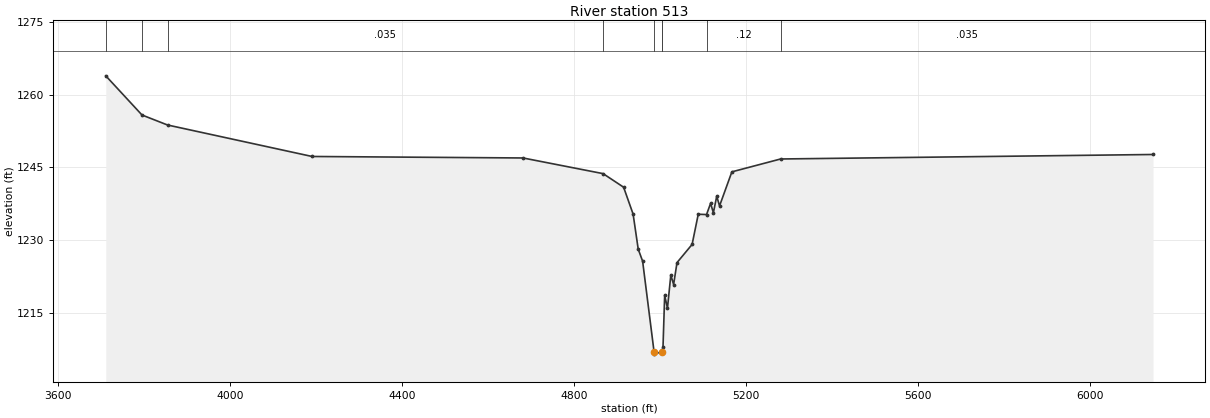
Type RM Length L Ch R = 1 ,513     ,0,0,0
BEGIN DESCRIPTION:
WERNER CREEK 1.0
END DESCRIPTION:
XS GIS Cut Line= 3
      2071546.11     13897072.47        2070375.       13896525.
      2069496.07     13897255.78
#Sta/Elev= 30
  3711.4 1263.96  3795.6 1255.86    3855 1253.79  4191.2 1247.28  4681.9 1246.97
  4868.1 1243.73  4915.8 1240.92  4937.9 1235.36  4949.8  1228.1    4960 1225.63
  4986.6  1206.9  4987.1  1206.4  5004.3  1206.9  5004.7 1207.02  5007.4  1207.8
  5011.3 1218.56  5017.8 1215.91  5025.6 1222.75  5032.1  1220.8    5040 1225.33
  5075.1 1229.09  5089.4 1235.33  5108.7 1235.27  5118.1 1237.58  5124.6 1235.64
  5132.4 1239.06  5138.9 1237.05  5167.6  1244.1  5280.9 1246.76  6147.2 1247.69
#Mann= 9 ,-1 , 0
  3711.4     .12       0  3795.6     .07       0    3855    .035       0
  4868.1     .12       0  4986.6     .05       0  5004.3     .12       0
  5004.7     .12       0  5108.7     .12       0  5280.9    .035       0
Bank Sta=4986.6,5004.3
XS Rating Curve= 0 ,0
Exp/Cntr=0.3,0.1

Chan Stop Cuts=-1
Use User Specified Reach Order=0
Composite Channel Slope=5