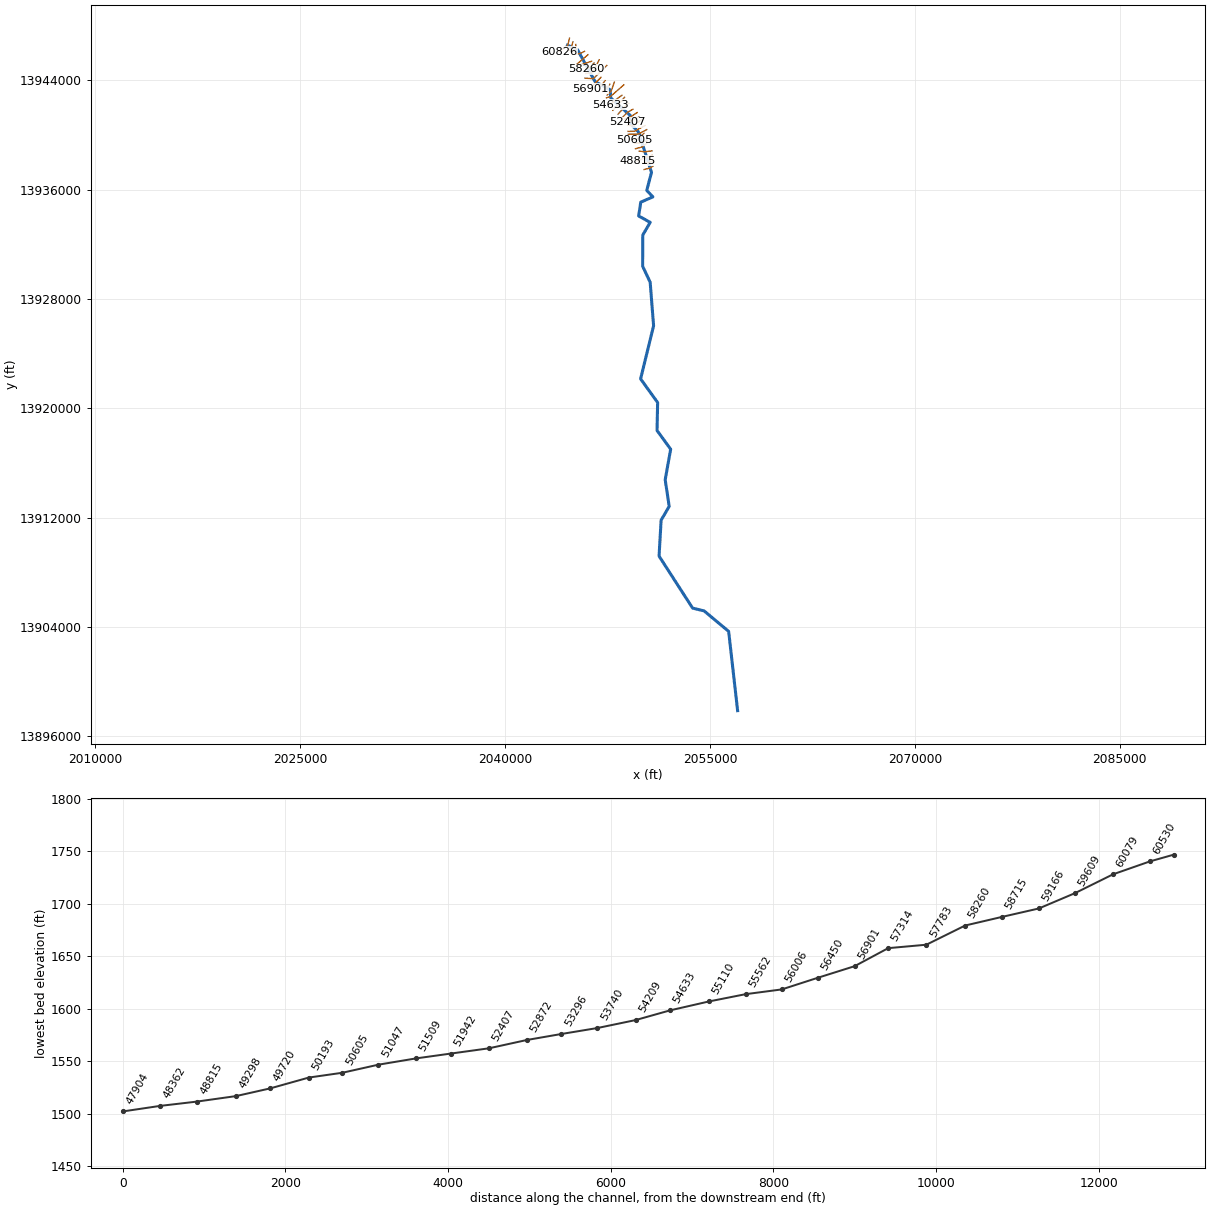
--- WEST SISTER CREEK.prj (project) ---

Proj Title=WEST SISTER CREEK Base Level Engineering
Current Plan=p01
Default Exp/Contr=0.3,0.1
English Units
Geom File=g01
Flow File=f01
Plan File=p01
Y Axis Title=Elevation
X Axis Title(PF)=Main Channel Distance
X Axis Title(XS)=Station
BEGIN DESCRIPTION:
WEST SISTER CREEK
END DESCRIPTION:
DSS Export Rating Curves= 0
DSS Export Rating Curve Sorted= 0
DSS Export Volume Flow Curves= 0
DXF OffsetX= 0
DXF OffsetY= 0
DXF ScaleX= 1
DXF ScaleY= 10

--- WEST SISTER CREEK.p01 (plan) ---

Plan Title=Multiple Run
Short Identifier=Multiple
Geom File=g01
Flow File=f01
Subcritical Flow
K Sum by GR= 0
Std Step Tol= 0.01
Critical Tol= 0.01
Num of Std Step Trials= 20
Max Error Tol= 0.3
Flow Tol Ratio= 0.001
Split Flow NTrial= 30
Split Flow Tol= 0.02
Split Flow Ratio= 0.02
Log Output Level= 0
Friction Slope Method= 1
Unsteady Friction Slope Method= 2
Unsteady Bridges Friction Slope Method= 1
Parabolic Critical Depth
Global Vel Dist=  1 , 1 , 1
Global Log Level= 0
CheckData=True
Encroach Param= -1, 0, 0, 0
BEGIN DESCRIPTION:
Multiple Run
END DESCRIPTION:

--- WEST SISTER CREEK.f01 (steady flow) ---

Flow Title=Multiple
Program Version=4.10
Number of Profiles= 7
Profile Names=10-year,25-year,50-year,1pct_min,100-year,1pct_plu,500-year
River Rch & RM=WEST SISTER CREE,Reach-1         ,60826
     299     477     638     417     833    1661    1398
River Rch & RM=WEST SISTER CREE,Reach-1         ,60530
     916    1576    2216    1514    3020    6027    5564
River Rch & RM=WEST SISTER CREE,Reach-1         ,56450
    1158    2017    2857    1965    3921    7824    7325
River Rch & RM=WEST SISTER CREE,Reach-1         ,53740
    1487    2599    3690    2538    5065   10106    9469
River Rch & RM=WEST SISTER CREE,Reach-1         ,45167
    4262    7788   11387    8040   16041   32007   31609
River Rch & RM=WEST SISTER CREE,Reach-1         ,37461
    6332   11754   17371   12386   24713   49309   49658
River Rch & RM=WEST SISTER CREE,Reach-1         ,36901
    6920   12862   19026   13574   27083   54038   54481
River Rch & RM=WEST SISTER CREE,Reach-1         ,33987
    7372   13684   20229   14421   28773   57410   57764
River Rch & RM=WEST SISTER CREE,Reach-1         ,31734
    7427   13756   20303   14449   28829   57522   57678
River Rch & RM=WEST SISTER CREE,Reach-1         ,26774
    7353   13594   20039   14241   28415   56695   56693
River Rch & RM=WEST SISTER CREE,Reach-1         ,24514
    7641   14124   20817   14790   29510   58880   58843
River Rch & RM=WEST SISTER CREE,Reach-1         ,20863
    9797   18182   26880   19148   38206   76230   76534
River Rch & RM=WEST SISTER CREE,Reach-1         ,18931
   12515   23342   34611   24685   49252   98271   98727
River Rch & RM=WEST SISTER CREE,Reach-1         ,11804
   13952   26090   38756   27685   55239  110216  111069
River Rch & RM=WEST SISTER CREE,Reach-1         ,9026
   13953   26035   38616   27541   54951  109641  110128
River Rch & RM=WEST SISTER CREE,Reach-1         ,5153
   19831   37307   55661   39908   79628  158878  161217
Boundary for River Rch & Prof#=WEST SISTER CREE,Reach-1         , 1
Up Type= 0
Dn Type= 1
Dn Known WS=1258.18
Boundary for River Rch & Prof#=WEST SISTER CREE,Reach-1         , 2
Up Type= 0
Dn Type= 1
Dn Known WS=1267.81
Boundary for River Rch & Prof#=WEST SISTER CREE,Reach-1         , 3
Up Type= 0
Dn Type= 1
Dn Known WS=1274.75
Boundary for River Rch & Prof#=WEST SISTER CREE,Reach-1         , 4
Up Type= 0
Dn Type= 1
Dn Known WS=1269.06
Boundary for River Rch & Prof#=WEST SISTER CREE,Reach-1         , 5
Up Type= 0
Dn Type= 1
Dn Known WS=1279.62
Boundary for River Rch & Prof#=WEST SISTER CREE,Reach-1         , 6
Up Type= 0
Dn Type= 1
Dn Known WS=1284.67
Boundary for River Rch & Prof#=WEST SISTER CREE,Reach-1         , 7
Up Type= 0
Dn Type= 1
Dn Known WS=1284.8
DSS Import GetInterval= 0
DSS Import GetPeak= 0
DSS Import FillOption= 0

--- WEST SISTER CREEK.g01 (geometry) ---

Geom Title=Existing Conditions
Program Version=4.10

River Reach=WEST SISTER CREE,Reach-1
Reach XY= 30
        2044575.       13946575.      2045308.36     13946241.71
      2046588.61     13943910.97      2047698.47     13943301.99
      2047735.48      13942715.2      2049167.14     13941431.17
      2049078.67     13940926.58      2049771.57     13940223.78
      2050722.83     13937269.56      2050374.54      13935947.9
        2050825.       13935475.      2049935.47     13935084.83
      2049782.56       13934075.      2050624.75     13933609.78
      2050083.04     13932678.32       2050074.8     13930399.92
        2050625.       13929225.      2050875.45     13926038.82
       2049924.6     13922156.65      2051171.47     13920423.55
      2051127.35     13918380.52      2052124.94     13917006.66
        2051725.       13914775.      2052017.41     13912825.01
      2051425.65     13911814.36       2051276.2     13909184.59
      2053730.58     13905380.58        2054575.       13905175.
      2056369.48     13903677.43        2057025.       13897875.

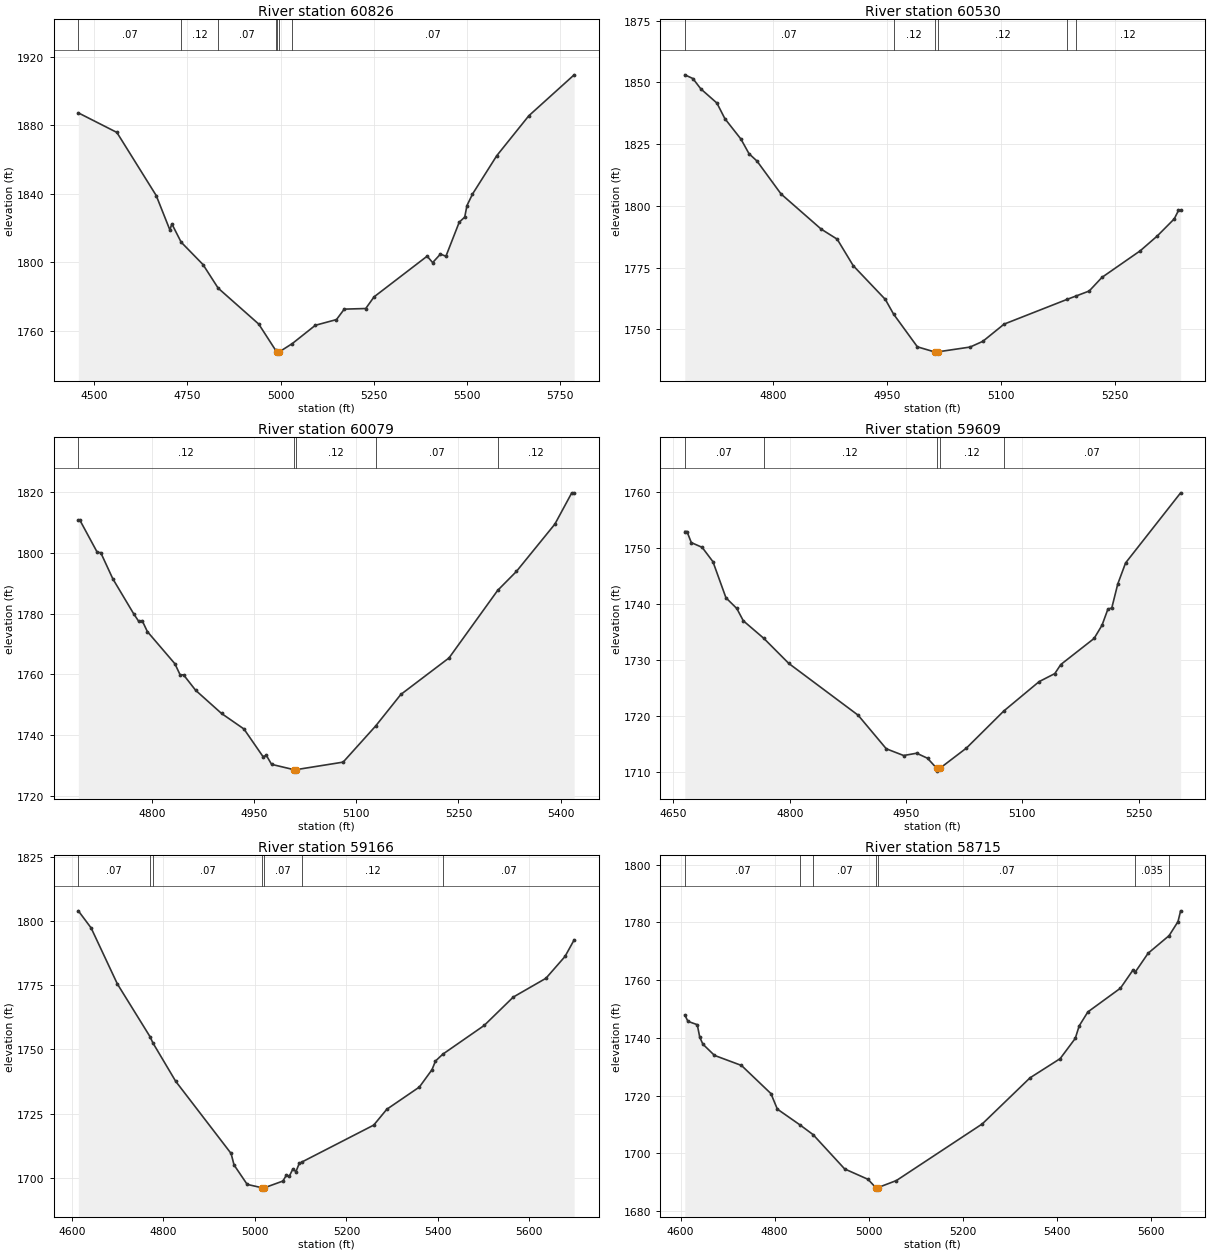
Type RM Length L Ch R = 1 ,60826   ,296,296,296
BEGIN DESCRIPTION:
WEST SISTER CREEK 119.0
END DESCRIPTION:
XS GIS Cut Line= 3
      2044718.59     13947085.53      2044590.97     13946558.15
      2043949.96     13946100.01
#Sta/Elev= 30
  4457.4 1887.31  4560.8 1875.88  4666.4 1838.99  4703.1 1818.87  4708.3 1822.46
  4733.3 1811.75  4791.9 1798.67  4832.6 1784.88  4941.5 1763.88  4986.5 1748.69
    4991  1747.4  4991.2  1746.9    4995  1747.4  5031.7 1752.51  5093.4 1763.17
  5150.1 1766.51    5171 1772.61  5228.6 1772.97  5250.9 1779.77  5393.4 1803.56
  5408.2 1799.79  5429.1 1804.79  5443.8  1803.5  5479.5 1823.42  5494.2 1826.38
  5500.3 1833.14  5515.1 1839.84  5580.2 1862.28  5666.2 1885.61  5787.9 1909.54
#Mann= 7 ,-1 , 0
  4457.4     .07       0  4733.3     .12       0  4832.6     .07       0
  4986.5     .12       0    4991     .05       0    4995     .12       0
  5031.7     .07       0
Bank Sta=4991,4995
XS Rating Curve= 0 ,0
Exp/Cntr=0.3,0.1

Type RM Length L Ch R = 1 ,60530   ,451,451,451
BEGIN DESCRIPTION:
WEST SISTER CREEK 118.0
END DESCRIPTION:
XS GIS Cut Line= 3
      2044975.01     13946825.04        2044875.       13946525.
      2044724.99     13946224.98
#Sta/Elev= 30
  4684.2 1853.02  4694.8 1851.53  4705.3 1847.32  4726.4  1841.6  4736.9 1835.27
    4758 1827.01  4768.6 1821.11  4779.1 1818.12  4810.7 1804.81  4863.4  1790.6
  4884.5 1786.51  4905.6 1775.78  4947.8 1762.12  4958.6  1756.2  4989.9 1742.95
  5012.4  1740.9  5012.7  1740.4  5016.4  1740.9  5059.2 1742.86  5075.9 1745.17
  5103.9 1752.14  5186.9 1762.18  5198.2 1763.49  5215.7 1765.53  5232.5 1771.05
  5282.8 1781.81  5305.1 1787.78  5327.5 1794.72  5333.1 1798.14  5335.9 1798.14
#Mann= 6 ,-1 , 0
  4684.2     .07       0  4958.6     .12       0  5012.4     .05       0
  5016.4     .12       0  5186.9     .07       0  5198.2     .12       0
Bank Sta=5012.4,5016.4
XS Rating Curve= 0 ,0
Exp/Cntr=0.3,0.1

Type RM Length L Ch R = 1 ,60079   ,470,470,470
BEGIN DESCRIPTION:
WEST SISTER CREEK 117.0
END DESCRIPTION:
XS GIS Cut Line= 3
        2045175.       13946625.        2045225.       13946325.
        2044925.       13946025.
#Sta/Elev= 30
  4691.6  1810.6  4694.1  1810.6  4719.5 1800.08  4724.5 1800.03  4742.3  1791.4
  4772.7 1779.99  4780.3 1777.43  4785.4 1777.65    4793 1774.06  4833.5 1763.47
  4841.1 1759.85  4846.2 1759.83  4863.9 1754.76    4902 1747.13  4934.9 1742.03
  4962.8 1732.98  4967.9 1733.31  4975.5  1730.4  5007.9 1728.67  5008.1 1728.17
  5011.9 1728.67  5080.6 1731.13  5128.4 1743.02  5165.4 1753.39  5236.2  1765.4
  5307.6  1787.6  5335.1 1793.82  5391.7 1809.41  5416.5 1819.69    5420 1819.69
#Mann= 5 ,-1 , 0
  4691.6     .12       0  5007.9     .05       0  5011.9     .12       0
  5128.4     .07       0  5307.6     .12       0
Bank Sta=5007.9,5011.9
XS Rating Curve= 0 ,0
Exp/Cntr=0.3,0.1

Type RM Length L Ch R = 1 ,59609   ,443,443,443
BEGIN DESCRIPTION:
WEST SISTER CREEK 116.0
END DESCRIPTION:
XS GIS Cut Line= 3
        2045825.       13946125.        2045525.       13945975.
      2045224.95     13945924.99
#Sta/Elev= 30
  4664.6 1752.97  4667.4 1752.97    4673 1750.99    4687 1750.14  4700.9 1747.58
  4717.7 1741.13  4731.7 1739.22  4740.1 1737.02  4766.5 1733.89  4798.8  1729.4
  4888.2 1720.16  4924.5 1714.16  4946.9 1712.96  4963.7 1713.37  4977.7 1712.47
  4989.6 1710.67  4989.9 1710.17  4993.6 1710.67  5027.9 1714.29  5076.1 1720.91
  5121.7 1726.16  5141.9 1727.59  5149.6 1729.21  5192.6 1733.87  5202.8 1736.23
  5210.4 1739.11  5215.4 1739.32  5223.1 1743.59  5233.2 1747.36  5304.2 1759.88
#Mann= 5 ,-1 , 0
  4664.6     .07       0  4766.5     .12       0  4989.6     .05       0
  4993.6     .12       0  5076.1     .07       0
Bank Sta=4989.6,4993.6
XS Rating Curve= 0 ,0
Exp/Cntr=0.3,0.1

Type RM Length L Ch R = 1 ,59166   ,451,451,451
BEGIN DESCRIPTION:
WEST SISTER CREEK 115.0
END DESCRIPTION:
XS GIS Cut Line= 3
      2046075.01     13945875.01        2045775.       13945625.
      2045249.01     13945173.39
#Sta/Elev= 30
  4614.1 1803.94  4642.1 1797.26  4699.4 1775.49  4771.1 1754.87    4777 1752.56
  4826.9  1737.6    4948  1709.5  4954.5 1705.01  4983.2 1697.46  5016.4 1696.12
  5016.6 1695.62  5020.4 1696.12  5061.2 1698.76  5068.8 1701.03  5075.4  1700.7
  5083.1 1703.47  5089.7  1702.4  5096.9 1705.61  5103.5 1706.24  5259.8 1720.54
  5288.3 1726.69  5359.6 1735.36  5387.1 1742.09  5394.8 1745.48  5410.8 1748.15
  5501.2 1759.32  5564.9 1770.38  5636.2 1777.68  5677.9 1786.18  5697.9 1792.64
#Mann= 7 ,-1 , 0
  4614.1     .07       0  4771.1     .12       0    4777     .07       0
  5016.4     .05       0  5020.4     .07       0  5103.5     .12       0
  5410.8     .07       0
Bank Sta=5016.4,5020.4
XS Rating Curve= 0 ,0
Exp/Cntr=0.3,0.1

Type RM Length L Ch R = 1 ,58715   ,455,455,455
BEGIN DESCRIPTION:
WEST SISTER CREEK 114.0
END DESCRIPTION:
XS GIS Cut Line= 3
      2046341.31     13945399.82        2045975.       13945275.
      2045339.66      13945070.3
#Sta/Elev= 30
  4608.9 1747.95  4615.6 1745.73  4635.4 1744.57  4640.7 1740.25  4647.3 1737.84
    4672 1733.94  4729.4 1730.46  4792.1 1720.71  4805.7 1715.34  4853.6  1709.9
  4881.7 1706.51  4948.9 1694.62  4998.5 1691.03  5015.2 1688.13  5015.4 1687.63
  5019.2 1688.13  5058.9  1690.6  5241.6 1710.22  5343.1 1726.17  5407.2 1732.82
  5439.3 1739.82  5447.7 1744.17  5466.1 1748.99  5535.4 1757.21  5562.3 1763.55
  5567.2 1762.87  5594.3 1769.32  5638.9 1775.41  5657.8 1780.26  5663.4    1784
#Mann= 7 ,-1 , 0
  4608.9     .07       0  4853.6     .12       0  4881.7     .07       0
  5015.2     .05       0  5019.2     .07       0  5567.2    .035       0
  5638.9     .07       0
Bank Sta=5015.2,5019.2
XS Rating Curve= 0 ,0
Exp/Cntr=0.3,0.1

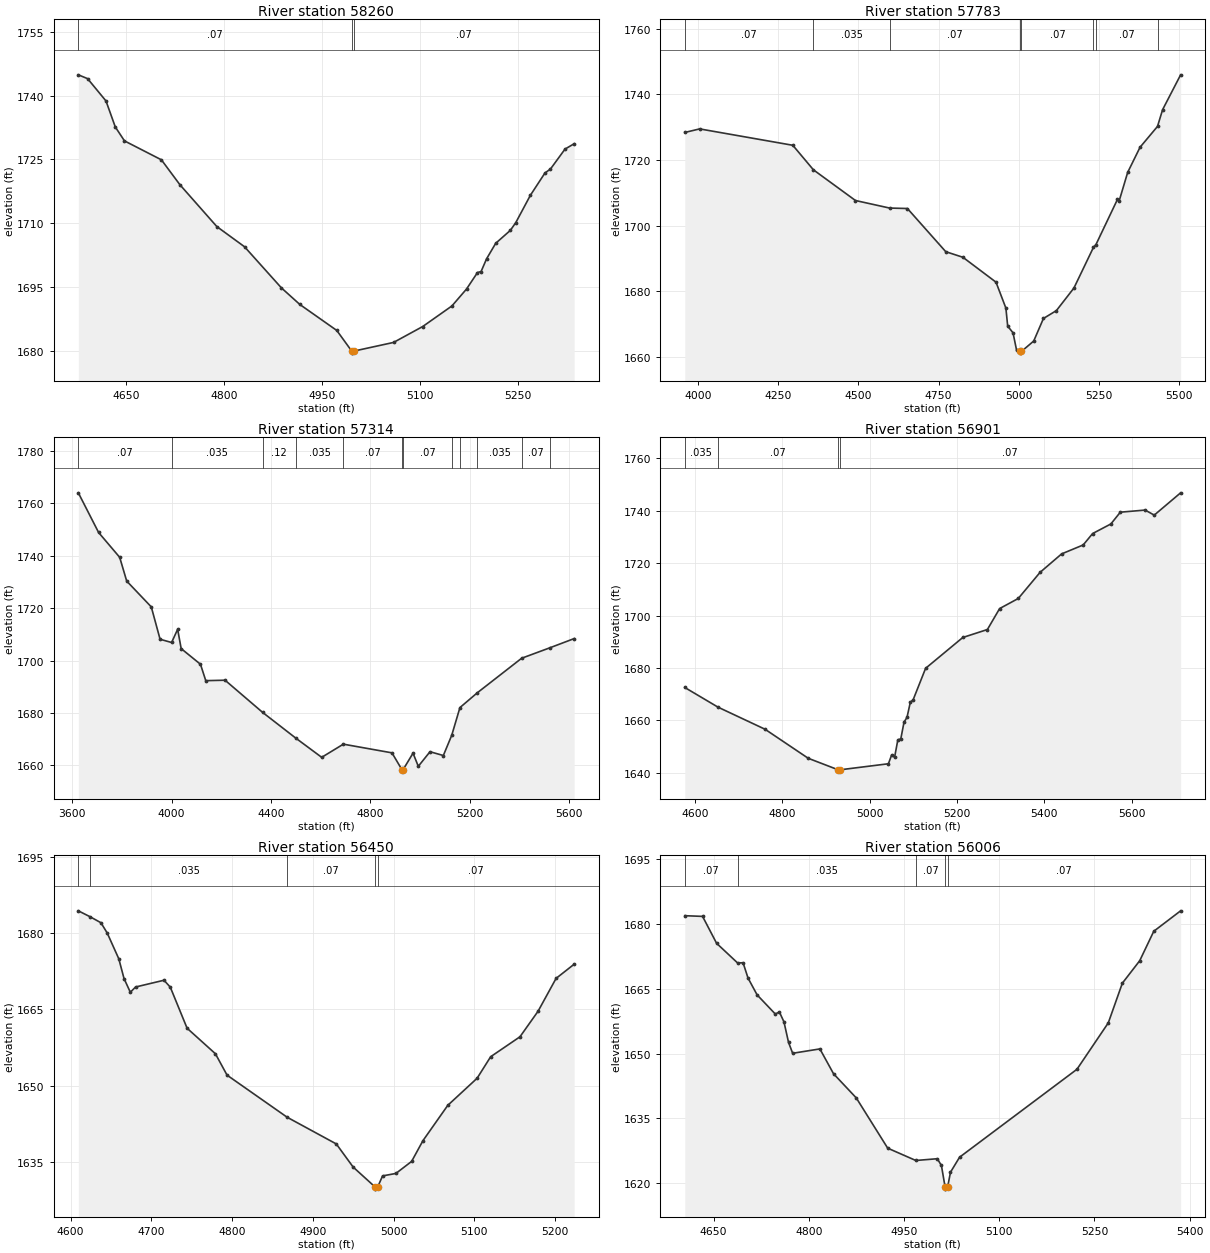
Type RM Length L Ch R = 1 ,58260   ,477,477,477
BEGIN DESCRIPTION:
WEST SISTER CREEK 113.0
END DESCRIPTION:
XS GIS Cut Line= 3
      2046525.02     13945275.02        2046225.       13944975.
        2045925.       13944825.
#Sta/Elev= 30
  4576.2 1744.94  4590.4 1744.04  4618.6 1738.78  4632.8 1732.67  4646.9 1729.38
  4703.5 1724.92  4731.8 1719.06  4788.4  1709.2  4830.8 1704.45  4887.4 1694.75
  4915.6 1690.85  4972.2 1684.73    4995 1679.89  4995.2 1679.39    4999 1679.89
  5059.2 1681.91  5103.9 1685.66  5148.6  1690.5    5171 1694.49  5187.8 1698.37
  5193.3 1698.61  5201.7  1701.6  5215.7 1705.26  5238.1  1708.3  5246.5 1710.14
  5268.8 1716.56  5291.2 1721.83  5299.6 1722.75  5321.9 1727.45  5335.9 1728.71
#Mann= 3 ,-1 , 0
  4576.2     .07       0    4995     .05       0    4999     .07       0
Bank Sta=4995,4999
XS Rating Curve= 0 ,0
Exp/Cntr=0.3,0.1

Type RM Length L Ch R = 1 ,57783   ,469,469,469
BEGIN DESCRIPTION:
WEST SISTER CREEK 112.0
END DESCRIPTION:
XS GIS Cut Line= 3
      2046890.35     13945502.38        2046425.       13944575.
       2045921.6     13944502.36
#Sta/Elev= 30
  3958.4 1728.36  4004.8 1729.44  4295.2 1724.45  4359.5 1716.97  4490.6 1707.62
    4597 1705.32  4652.6 1705.18  4772.2 1692.02  4825.7 1690.32  4928.9 1682.73
  4959.7 1674.83  4965.3 1669.35    4982 1667.29  4993.2 1661.93  5004.1 1661.61
  5004.3 1661.11  5008.1 1661.61  5046.5  1664.8  5076.8 1671.67  5117.2 1674.07
  5171.9 1680.95  5232.7 1693.32  5240.6  1694.2  5307.6 1707.95  5312.7 1707.42
  5339.5 1716.19    5378 1723.84  5432.5  1730.2  5448.4  1735.3  5504.6 1745.92
#Mann= 8 ,-1 , 0
  3958.4     .07       0  4359.5    .035       0    4597     .07       0
  5004.1     .05       0  5008.1     .07       0  5232.7    .035       0
  5240.6     .07       0  5432.5    .035       0
Bank Sta=5004.1,5008.1
XS Rating Curve= 0 ,0
Exp/Cntr=0.3,0.1

Type RM Length L Ch R = 1 ,57314   ,413,413,413
BEGIN DESCRIPTION:
WEST SISTER CREEK 111.0
END DESCRIPTION:
XS GIS Cut Line= 3
      2047452.82     13945092.62        2046475.       13944125.
      2045855.57     13944158.61
#Sta/Elev= 30
  3624.3 1763.94  3705.9 1748.82  3790.8 1739.35    3819  1730.3    3918 1720.45
  3953.4 1708.11  3999.8 1706.88  4024.1 1711.91  4038.3 1704.55    4116 1698.58
  4137.3 1692.33    4215  1692.5  4366.2 1680.23  4500.7 1670.35    4604  1663.1
  4691.2 1668.12  4886.9 1664.81  4927.3 1658.34  4927.5 1657.84  4931.3 1658.34
  4971.7 1664.69  4992.9 1659.67    5040 1665.24  5093.7 1663.79  5127.5 1671.51
  5160.5 1682.07  5230.7 1687.73    5409 1700.88  5523.1 1704.88  5620.3 1708.37
#Mann= 12 ,-1 , 0
  3624.3     .07       0  3999.8    .035       0  4366.2     .12       0
  4500.7    .035       0  4691.2     .07       0  4927.3     .05       0
  4931.3     .07       0  5127.5    .035       0  5160.5     .07       0
  5230.7    .035       0    5409     .07       0  5523.1    .035       0
Bank Sta=4927.3,4931.3
XS Rating Curve= 0 ,0
Exp/Cntr=0.3,0.1

Type RM Length L Ch R = 1 ,56901   ,451,451,451
BEGIN DESCRIPTION:
WEST SISTER CREEK 110.0
END DESCRIPTION:
XS GIS Cut Line= 3
      2047024.98     13944224.98        2046725.       13943925.
      2046248.98     13943395.84
#Sta/Elev= 30
  4576.4 1672.57  4652.6 1665.06  4760.2 1656.65  4859.2 1645.57  4927.9 1641.17
  4928.2 1640.67  4931.9 1641.17  5042.9 1643.48  5050.3 1646.83  5057.1 1645.99
  5064.5 1652.59  5071.3 1652.98  5078.7 1659.37  5085.5 1661.16    5093 1666.86
  5099.7 1667.94  5128.1 1679.88  5213.3 1691.64  5269.7 1694.68  5297.7 1702.67
  5340.4 1706.52  5390.4 1716.49  5439.8 1723.53  5489.1 1726.93  5510.8 1731.29
  5552.6 1734.95  5574.3 1739.44  5631.1 1740.24    5652 1738.32  5712.4 1746.82
#Mann= 4 ,-1 , 0
  4576.4    .035       0  4652.6     .07       0  4927.9     .05       0
  4931.9     .07       0
Bank Sta=4927.9,4931.9
XS Rating Curve= 0 ,0
Exp/Cntr=0.3,0.1

Type RM Length L Ch R = 1 ,56450   ,444,444,444
BEGIN DESCRIPTION:
WEST SISTER CREEK 109.0
END DESCRIPTION:
XS GIS Cut Line= 3
      2047324.98     13943974.97        2047075.       13943675.
      2046874.99     13943574.99
#Sta/Elev= 30
  4609.5 1684.36  4623.9 1683.21  4637.5 1682.02  4645.3 1679.99  4659.6 1674.94
  4666.1 1671.05  4673.9 1668.36  4680.4 1669.39  4715.6 1670.72  4723.4 1669.36
  4744.2 1661.29  4779.3 1656.27  4793.7 1652.07  4868.1  1643.8    4929 1638.55
  4949.9    1634  4976.5 1630.17  4976.7 1629.67  4980.5 1630.17  4986.3 1632.27
  5002.8 1632.75  5022.3 1635.12  5036.3 1639.19  5067.1 1646.14  5103.4 1651.46
  5120.2 1655.69  5156.5 1659.61  5178.9 1664.63  5201.2 1671.08  5223.6 1673.87
#Mann= 5 ,-1 , 0
  4609.5     .07       0  4623.9    .035       0  4868.1     .07       0
  4976.5     .05       0  4980.5     .07       0
Bank Sta=4976.5,4980.5
XS Rating Curve= 0 ,0
Exp/Cntr=0.3,0.1

Type RM Length L Ch R = 1 ,56006   ,444,444,444
BEGIN DESCRIPTION:
WEST SISTER CREEK 108.0
END DESCRIPTION:
XS GIS Cut Line= 3
      2047674.99     13943724.99        2047425.       13943425.
      2047125.01     13943175.01
#Sta/Elev= 30
  4604.7 1681.96  4632.7  1681.8  4654.8 1675.56  4687.9    1671  4696.5 1671.05
  4704.3  1667.5  4718.6  1663.6  4747.2 1659.17  4753.7 1659.63  4760.9 1657.34
  4768.1 1652.59  4774.6 1650.06  4817.5 1651.07    4839 1645.31  4874.8 1639.71
  4924.3 1628.06  4968.6  1625.2  5002.4 1625.61  5008.9 1624.05  5014.7 1619.06
  5014.9 1618.56  5018.7 1619.06  5023.2 1622.48  5037.5 1625.96  5222.4 1646.35
  5271.8 1657.12  5293.9 1666.31  5321.3 1671.53  5343.4 1678.35  5385.7 1683.09
#Mann= 5 ,-1 , 0
  4604.7     .07       0  4687.9    .035       0  4968.6     .07       0
  5014.7     .05       0  5018.7     .07       0
Bank Sta=5014.7,5018.7
XS Rating Curve= 0 ,0
Exp/Cntr=0.3,0.1

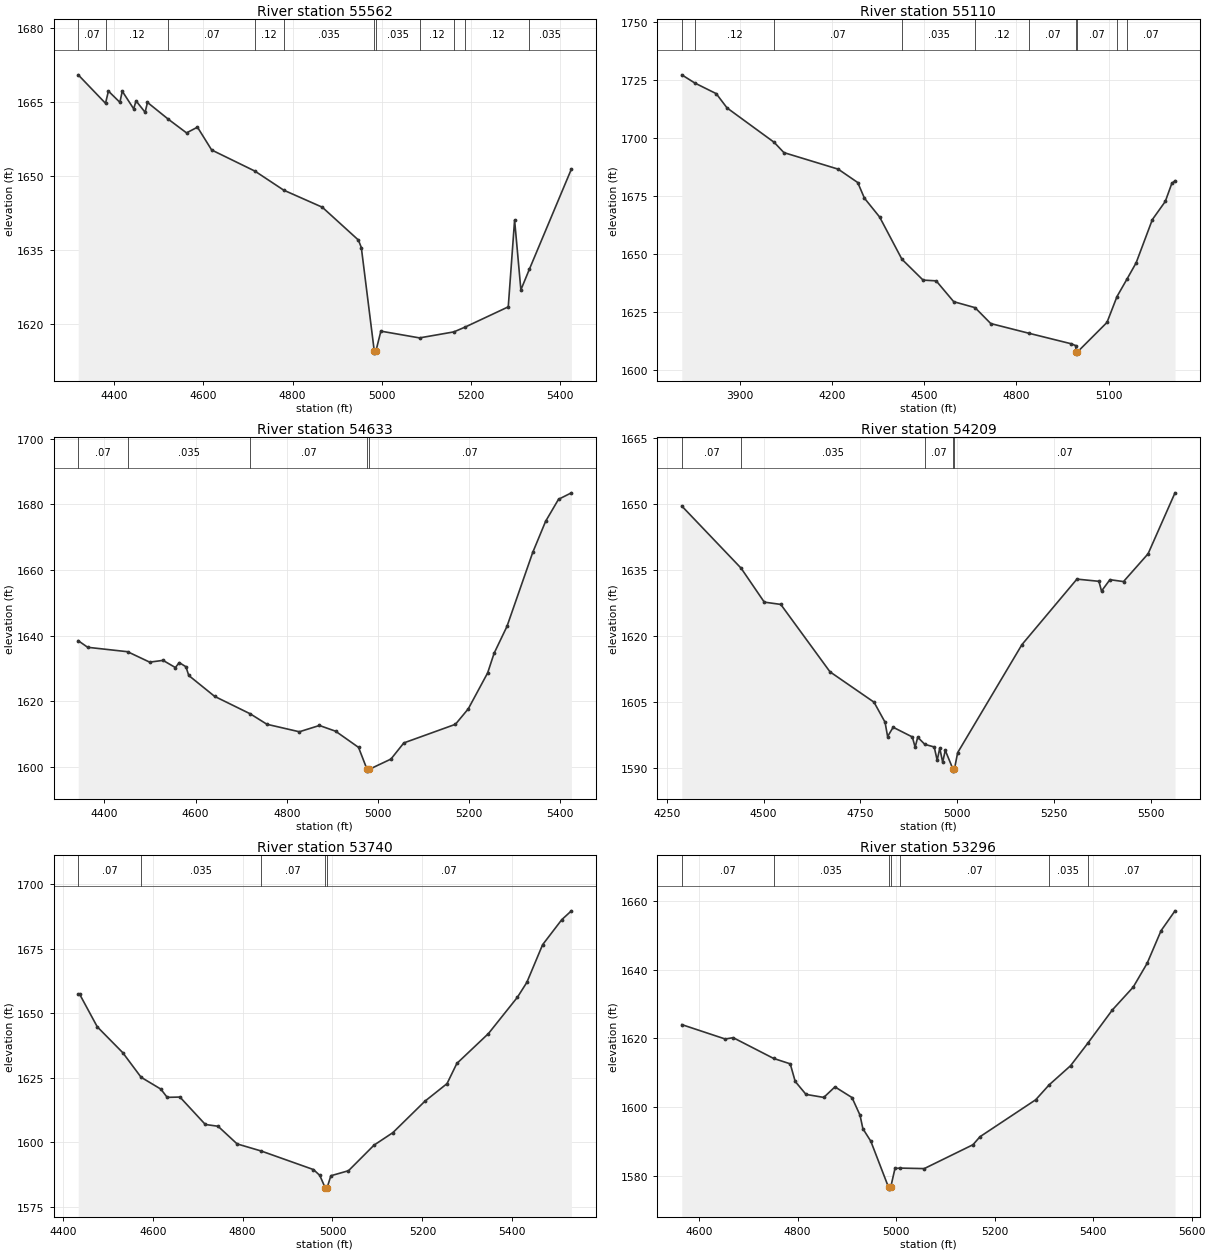
Type RM Length L Ch R = 1 ,55562   ,452,452,452
BEGIN DESCRIPTION:
WEST SISTER CREEK 107.0
END DESCRIPTION:
XS GIS Cut Line= 3
      2048001.45     13943866.94        2047775.       13943225.
      2047474.98     13942924.98
#Sta/Elev= 30
  4319.7 1670.51  4380.9 1664.73  4387.4 1667.21  4413.1 1664.93  4418.4 1667.19
    4444 1663.61  4449.3 1665.23  4469.6 1662.91  4474.9 1664.91  4521.5 1661.51
  4562.4 1658.73  4586.9 1659.89  4618.7 1655.26  4715.7 1650.97  4780.1 1647.11
  4866.5 1643.65  4947.4 1636.99    4954 1635.47  4982.9 1614.54  4983.2 1614.04
  4986.9 1614.54  4997.8  1618.5  5084.4 1617.13  5161.4 1618.35  5186.9 1619.34
  5283.2 1623.43  5297.4 1641.04  5311.5 1626.88  5330.4 1631.04  5424.7  1651.4
#Mann= 11 ,-1 , 0
  4319.7     .07       0  4380.9     .12       0  4521.5     .07       0
  4715.7     .12       0  4780.1    .035       0  4982.9    .035       0
  4986.9    .035       0  5084.4     .12       0  5161.4     .07       0
  5186.9     .12       0  5330.4    .035       0
Bank Sta=4982.9,4986.9
XS Rating Curve= 0 ,0
Exp/Cntr=0.3,0.1

Type RM Length L Ch R = 1 ,55110   ,477,477,477
BEGIN DESCRIPTION:
WEST SISTER CREEK 106.0
END DESCRIPTION:
XS GIS Cut Line= 3
      2048695.86     13943672.47        2047725.       13942825.
      2047425.03     13942725.01
#Sta/Elev= 30
  3711.2 1727.12  3753.4  1723.6  3823.3    1719  3858.4 1712.85  4011.6 1698.03
  4043.5 1693.57  4220.1 1686.44  4283.7 1680.67  4305.5 1673.92  4354.9  1665.8
  4427.5 1647.58  4496.3 1638.59    4539 1638.26    4596 1629.28  4665.5  1626.7
  4716.6 1619.84  4840.4 1615.67  4978.5 1611.12  4992.8 1610.34  4994.6 1607.59
  4994.8 1607.09  4998.6 1607.59  5094.8 1620.34  5127.4 1631.51  5160.1 1639.09
  5189.6 1646.03  5242.4 1664.69  5284.5 1672.52  5305.6 1680.25  5316.1 1681.43
#Mann= 10 ,-1 , 0
  3711.2     .07       0  3753.4     .12       0  4011.6     .07       0
  4427.5    .035       0  4665.5     .12       0  4840.4     .07       0
  4994.6     .05       0  4998.6     .07       0  5127.4    .035       0
  5160.1     .07       0
Bank Sta=4994.6,4998.6
XS Rating Curve= 0 ,0
Exp/Cntr=0.3,0.1

Type RM Length L Ch R = 1 ,54633   ,424,424,424
BEGIN DESCRIPTION:
WEST SISTER CREEK 105.0
END DESCRIPTION:
XS GIS Cut Line= 3
      2048557.02      13942912.1        2048025.       13942525.
      2047725.01     13942225.01
#Sta/Elev= 30
  4342.3 1638.43  4363.1 1636.41  4450.7 1635.06  4499.1 1631.88  4528.5 1632.42
  4555.5 1630.23    4564 1631.74  4578.7 1630.47  4584.9 1627.81  4641.6 1621.44
  4719.9  1616.1  4756.4 1612.92  4827.5 1610.63  4871.6 1612.55  4907.1  1610.8
  4957.4 1605.87  4976.2 1599.12  4976.5 1598.62  4980.2 1599.12  5028.5  1602.3
  5056.8 1607.23    5170 1612.91  5198.2 1617.63  5240.7  1628.6  5254.8 1634.57
  5283.1 1642.79  5339.7 1665.39  5367.9 1674.86  5396.2 1681.58  5424.5 1683.55
#Mann= 5 ,-1 , 0
  4342.3     .07       0  4450.7    .035       0  4719.9     .07       0
  4976.2     .05       0  4980.2     .07       0
Bank Sta=4976.2,4980.2
XS Rating Curve= 0 ,0
Exp/Cntr=0.3,0.1

Type RM Length L Ch R = 1 ,54209   ,469,469,469
BEGIN DESCRIPTION:
WEST SISTER CREEK 104.0
END DESCRIPTION:
XS GIS Cut Line= 3
      2048751.46     13942759.32        2048275.       13942225.
      2047900.75     13941811.38
#Sta/Elev= 30
  4288.6 1649.62  4441.7  1635.5  4501.6 1627.78  4544.2 1627.26  4671.3 1611.94
    4785 1605.04  4813.5 1600.49  4820.1 1597.23  4834.4 1599.34  4883.9 1597.14
  4891.2 1594.82  4897.9 1597.08  4916.2 1595.45  4940.5 1594.86  4948.1 1591.84
  4954.8 1594.58  4962.3 1591.39    4969  1594.1  4988.7 1589.87  4988.9 1589.37
  4992.7 1589.87  5001.1 1593.58    5167 1618.12    5309 1633.01  5365.8 1632.51
  5372.5 1630.29  5394.2 1632.88  5429.3 1632.45  5492.8 1638.77  5562.3 1652.62
#Mann= 5 ,-1 , 0
  4288.6     .07       0  4441.7    .035       0  4916.2     .07       0
  4988.7     .05       0  4992.7     .07       0
Bank Sta=4988.7,4992.7
XS Rating Curve= 0 ,0
Exp/Cntr=0.3,0.1

Type RM Length L Ch R = 1 ,53740   ,444,444,444
BEGIN DESCRIPTION:
WEST SISTER CREEK 103.0
END DESCRIPTION:
XS GIS Cut Line= 3
        2049025.       13942325.        2048625.       13941925.
      2048274.99     13941524.99
#Sta/Elev= 30
  4434.3 1657.32  4437.8 1657.32  4476.7 1644.78  4533.3 1634.77  4574.2 1625.21
  4618.1 1620.61  4632.3 1617.41  4660.6 1617.53  4717.1 1606.89  4745.4  1606.2
  4787.8 1599.35    4841 1596.62  4957.6  1589.4  4971.7 1587.15  4983.8 1582.31
    4984 1581.81  4987.9 1582.31  4996.4    1587  5035.6 1588.95  5092.5 1598.89
  5134.3 1603.72  5205.5  1615.9  5254.8 1622.74  5276.6 1630.56  5346.9 1642.15
  5411.4 1656.25  5432.3    1662  5467.4 1676.62  5510.1 1686.35  5531.5 1689.77
#Mann= 5 ,-1 , 0
  4434.3     .07       0  4574.2    .035       0    4841     .07       0
  4983.8     .05       0  4987.9     .07       0
Bank Sta=4983.8,4987.9
XS Rating Curve= 0 ,0
Exp/Cntr=0.3,0.1

Type RM Length L Ch R = 1 ,53296   ,424,424,424
BEGIN DESCRIPTION:
WEST SISTER CREEK 102.0
END DESCRIPTION:
XS GIS Cut Line= 3
       2049359.1     13941880.84        2048975.       13941675.
      2048574.98     13941274.98
#Sta/Elev= 30
  4564.7 1624.04  4652.8 1619.85  4669.1 1620.23  4751.1 1614.19  4784.9 1612.61
    4795 1607.48  4816.9 1603.71    4853 1602.83  4875.7  1605.9  4910.3 1602.79
  4926.6 1597.65  4932.4 1593.72  4948.5 1590.07  4984.6 1576.61  4984.9 1576.11
  4988.8 1576.61  4997.6 1582.14  5007.9 1582.24    5057 1582.09    5156 1589.05
  5170.2 1591.38  5283.3 1602.14  5310.5 1606.47    5354 1612.05  5388.9 1618.58
  5438.9  1628.3  5481.3 1634.96  5509.6  1641.9  5537.9 1651.41  5566.2 1657.19
#Mann= 7 ,-1 , 0
  4564.7     .07       0  4751.1    .035       0  4984.6    .035       0
  4988.8    .035       0  5007.9     .07       0  5310.5    .035       0
  5388.9     .07       0
Bank Sta=4984.6,4988.8
XS Rating Curve= 0 ,0
Exp/Cntr=0.3,0.1

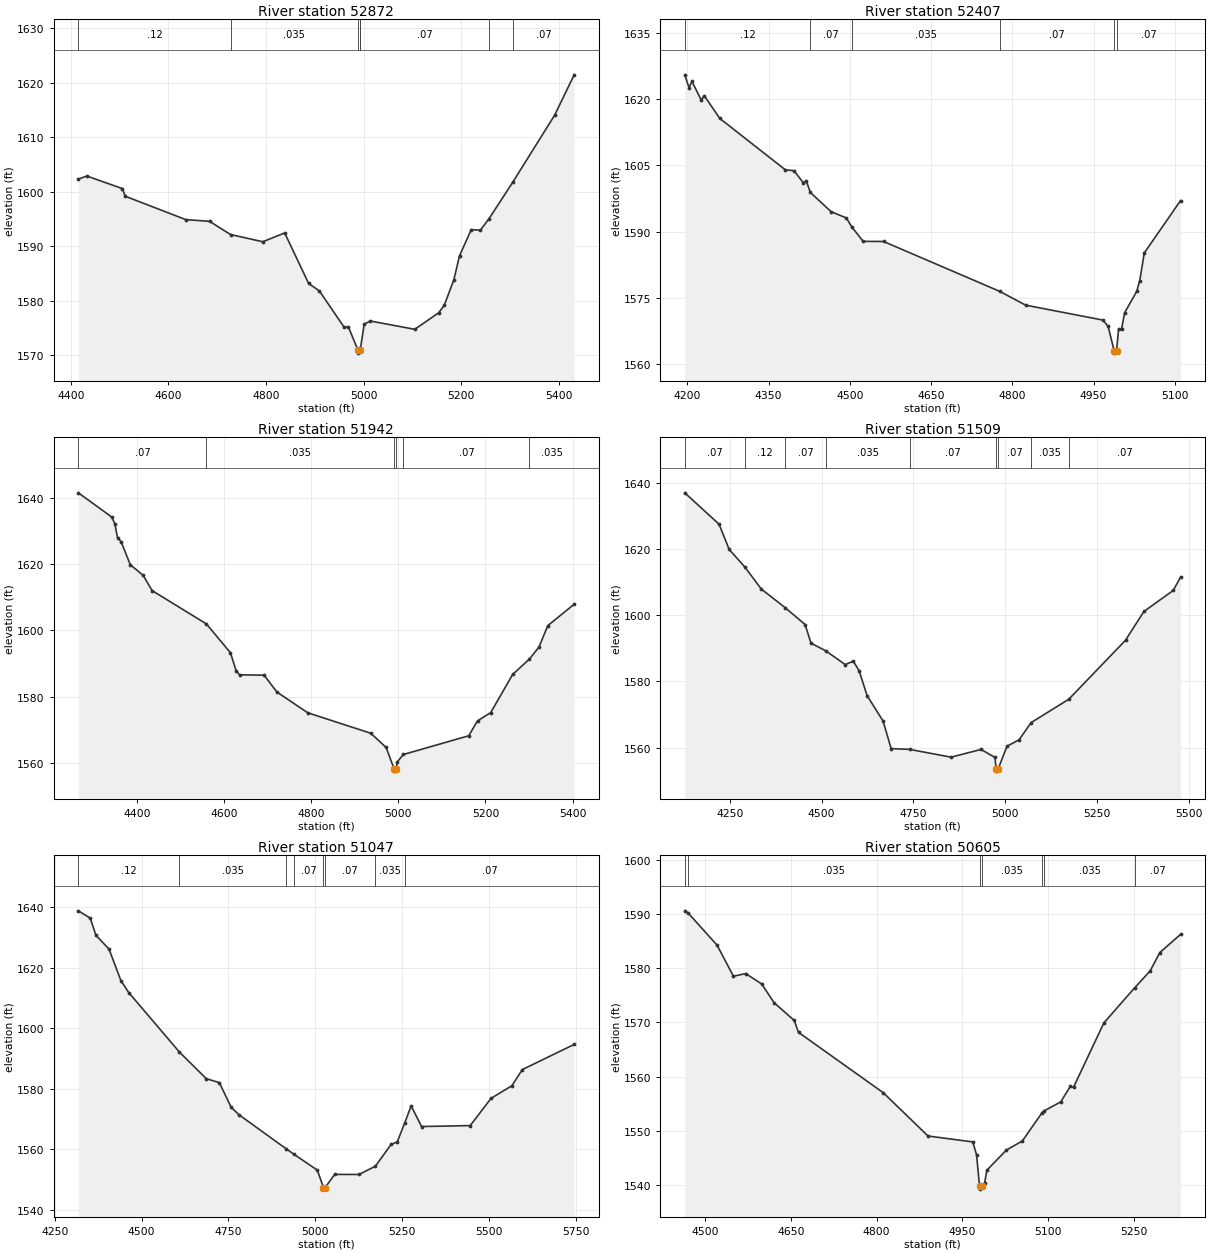
Type RM Length L Ch R = 1 ,52872   ,465,465,465
BEGIN DESCRIPTION:
WEST SISTER CREEK 101.0
END DESCRIPTION:
XS GIS Cut Line= 3
      2049671.59     13941641.25        2049175.       13941325.
      2048775.04     13941175.02
#Sta/Elev= 30
  4415.3 1602.34  4432.6 1602.91  4505.4 1600.61  4511.4  1599.2  4635.8  1594.9
  4684.1  1594.6  4727.2 1592.17  4793.3 1590.85  4838.1 1592.47  4887.2 1583.19
  4909.2 1581.83    4960 1575.15  4968.5 1575.25  4988.4 1570.91  4988.7 1570.41
  4992.6 1570.91  4993.4 1571.27  5001.1 1575.75  5013.8  1576.3  5104.6 1574.78
  5153.6 1577.81  5165.1  1579.2  5184.7 1583.87  5196.3 1588.27  5220.3 1593.07
    5239 1592.96  5256.8 1595.08  5305.1 1601.73  5391.2 1614.07  5431.2 1621.48
#Mann= 7 ,-1 , 0
  4415.3     .12       0  4727.2    .035       0  4988.4     .05       0
  4992.6    .035       0  4993.4     .07       0  5256.8    .035       0
  5305.1     .07       0
Bank Sta=4988.4,4992.6
XS Rating Curve= 0 ,0
Exp/Cntr=0.3,0.1

Type RM Length L Ch R = 1 ,52407   ,465,465,465
BEGIN DESCRIPTION:
WEST SISTER CREEK 100.0
END DESCRIPTION:
XS GIS Cut Line= 3
       2049803.5     13941314.84        2049075.       13940975.
      2048974.97     13940924.99
#Sta/Elev= 30
  4195.2 1625.52  4202.9 1622.63  4208.4 1624.02  4225.7 1619.78  4231.2 1620.79
  4259.7 1615.66  4381.1 1603.99  4396.8 1603.82  4414.1 1601.07  4419.6 1601.49
  4427.1 1598.88  4465.4 1594.53  4493.7  1593.1  4503.4 1591.09  4524.6 1587.81
  4562.3 1587.78  4776.5  1576.5  4824.8 1573.36  4967.5 1569.98    4977 1568.55
  4988.2    1563  4988.5  1562.5  4992.6    1563  4996.3 1567.98  5001.9 1567.98
  5007.5 1571.66  5029.8 1576.49  5035.4  1578.9  5043.8 1585.19  5110.9 1597.06
#Mann= 6 ,-1 , 0
  4195.2     .12       0  4427.1     .07       0  4503.4    .035       0
  4776.5     .07       0  4988.2     .05       0  4992.6     .07       0
Bank Sta=4988.2,4992.6
XS Rating Curve= 0 ,0
Exp/Cntr=0.3,0.1

Type RM Length L Ch R = 1 ,51942   ,433,433,433
BEGIN DESCRIPTION:
WEST SISTER CREEK 99.0
END DESCRIPTION:
XS GIS Cut Line= 3
      2049966.77     13941110.03        2049375.       13940675.
      2048974.98       13940725.
#Sta/Elev= 30
    4266 1641.51  4342.7  1634.2  4349.7 1632.21  4355.9 1627.98  4364.3 1626.74
  4385.2  1619.8  4414.5 1616.64  4435.3    1612  4559.7 1601.97  4615.1 1593.24
  4628.1 1587.81  4635.9  1586.6  4692.3 1586.48  4721.6  1581.4  4792.6 1575.12
  4936.8 1568.97  4972.3 1564.67  4990.9 1558.03  4991.2 1557.53  4995.4 1558.03
  4997.4 1560.25  5011.8 1562.55  5161.7  1568.2  5181.9  1572.7  5212.1 1575.18
  5262.5  1586.7  5301.1 1591.37    5323 1594.99  5343.1 1601.43  5403.6 1607.89
#Mann= 6 ,-1 , 0
    4266     .07       0  4559.7    .035       0  4990.9    .035       0
  4995.4    .035       0  5011.8     .07       0  5301.1    .035       0
Bank Sta=4990.9,4995.4
XS Rating Curve= 0 ,0
Exp/Cntr=0.3,0.1

Type RM Length L Ch R = 1 ,51509   ,462,462,462
BEGIN DESCRIPTION:
WEST SISTER CREEK 98.0
END DESCRIPTION:
XS GIS Cut Line= 3
      2050248.01     13940696.82        2049475.       13940275.
      2049004.89     13940266.25
#Sta/Elev= 30
  4127.2 1636.99  4220.5 1627.51    4248 1619.91  4290.2 1614.64  4335.7  1607.9
  4400.6 1602.28  4454.9 1597.19  4471.1 1591.54  4511.1 1589.25  4564.1 1585.08
  4586.3 1586.08  4602.1 1583.22  4623.9 1575.68  4667.5 1567.98  4689.4 1559.67
  4739.4 1559.45  4852.6 1557.09  4934.3 1559.43  4972.2    1557  4975.7 1553.37
    4976 1552.87  4980.2 1553.37    5005 1560.41  5037.8 1562.33  5070.7 1567.54
  5173.4  1574.6  5327.9 1592.44  5377.9 1601.12  5457.9 1607.49    5478 1611.54
#Mann= 9 ,-1 , 0
  4127.2     .07       0  4290.2     .12       0  4400.6     .07       0
  4511.1    .035       0  4739.4     .07       0  4975.7     .05       0
  4980.2     .07       0  5070.7    .035       0  5173.4     .07       0
Bank Sta=4975.7,4980.2
XS Rating Curve= 0 ,0
Exp/Cntr=0.3,0.1

Type RM Length L Ch R = 1 ,51047   ,442,442,442
BEGIN DESCRIPTION:
WEST SISTER CREEK 97.0
END DESCRIPTION:
XS GIS Cut Line= 3
        2050373.     13940394.73        2049775.       13940075.
       2049025.8     13940057.92
#Sta/Elev= 30
  4317.8 1638.84  4352.1 1636.43  4368.4 1630.77  4406.2 1626.18  4440.3  1615.8
  4462.9 1611.84    4609 1592.16  4686.2 1583.39  4723.8 1582.08  4757.8 1573.95
  4780.5 1571.45  4915.9 1560.25  4938.9 1558.39  5005.9 1553.17  5023.6  1547.4
    5024  1546.9  5028.2  1547.4  5055.9 1551.76  5125.9 1551.74  5173.2 1554.48
  5218.1 1561.65    5236 1562.51  5257.7  1568.8    5276 1574.41    5306 1567.58
    5446 1567.89    5506 1576.88  5566.1 1581.07  5596.1  1586.4  5745.3  1594.7
#Mann= 8 ,-1 , 0
  4317.8     .12       0    4609    .035       0  4915.9     .12       0
  4938.9     .07       0  5023.6     .05       0  5028.2     .07       0
  5173.2    .035       0  5257.7     .07       0
Bank Sta=5023.6,5028.2
XS Rating Curve= 0 ,0
Exp/Cntr=0.3,0.1

Type RM Length L Ch R = 1 ,50605   ,412,412,412
BEGIN DESCRIPTION:
WEST SISTER CREEK 96.0
END DESCRIPTION:
XS GIS Cut Line= 3
      2050175.04     13940125.03        2049775.       13939775.
      2049474.97     13939624.99
#Sta/Elev= 30
  4464.5 1590.62  4470.4 1590.21    4521 1584.27  4549.5 1578.54  4570.9 1579.03
  4598.9 1577.12  4620.7 1573.64  4655.8 1570.38  4663.4 1568.17  4811.5 1557.03
  4889.8 1549.03  4968.1 1547.94  4974.7 1545.55  4979.9 1539.72  4980.3 1539.22
  4984.6 1539.72  4988.9 1540.44  4992.7 1542.71  5026.8 1546.43  5054.8 1548.12
  5088.8 1553.27  5093.1 1553.69  5121.8 1555.33  5138.6 1558.19  5144.2 1558.03
  5197.3 1569.92  5251.1  1576.4  5278.4 1579.55  5295.1 1582.91  5331.5 1586.28
#Mann= 7 ,-1 , 0
  4464.5     .07       0  4470.4    .035       0  4979.9    .035       0
  4984.6    .035       0  5088.8     .07       0  5093.1    .035       0
  5251.1     .07       0
Bank Sta=4979.9,4984.6
XS Rating Curve= 0 ,0
Exp/Cntr=0.3,0.1

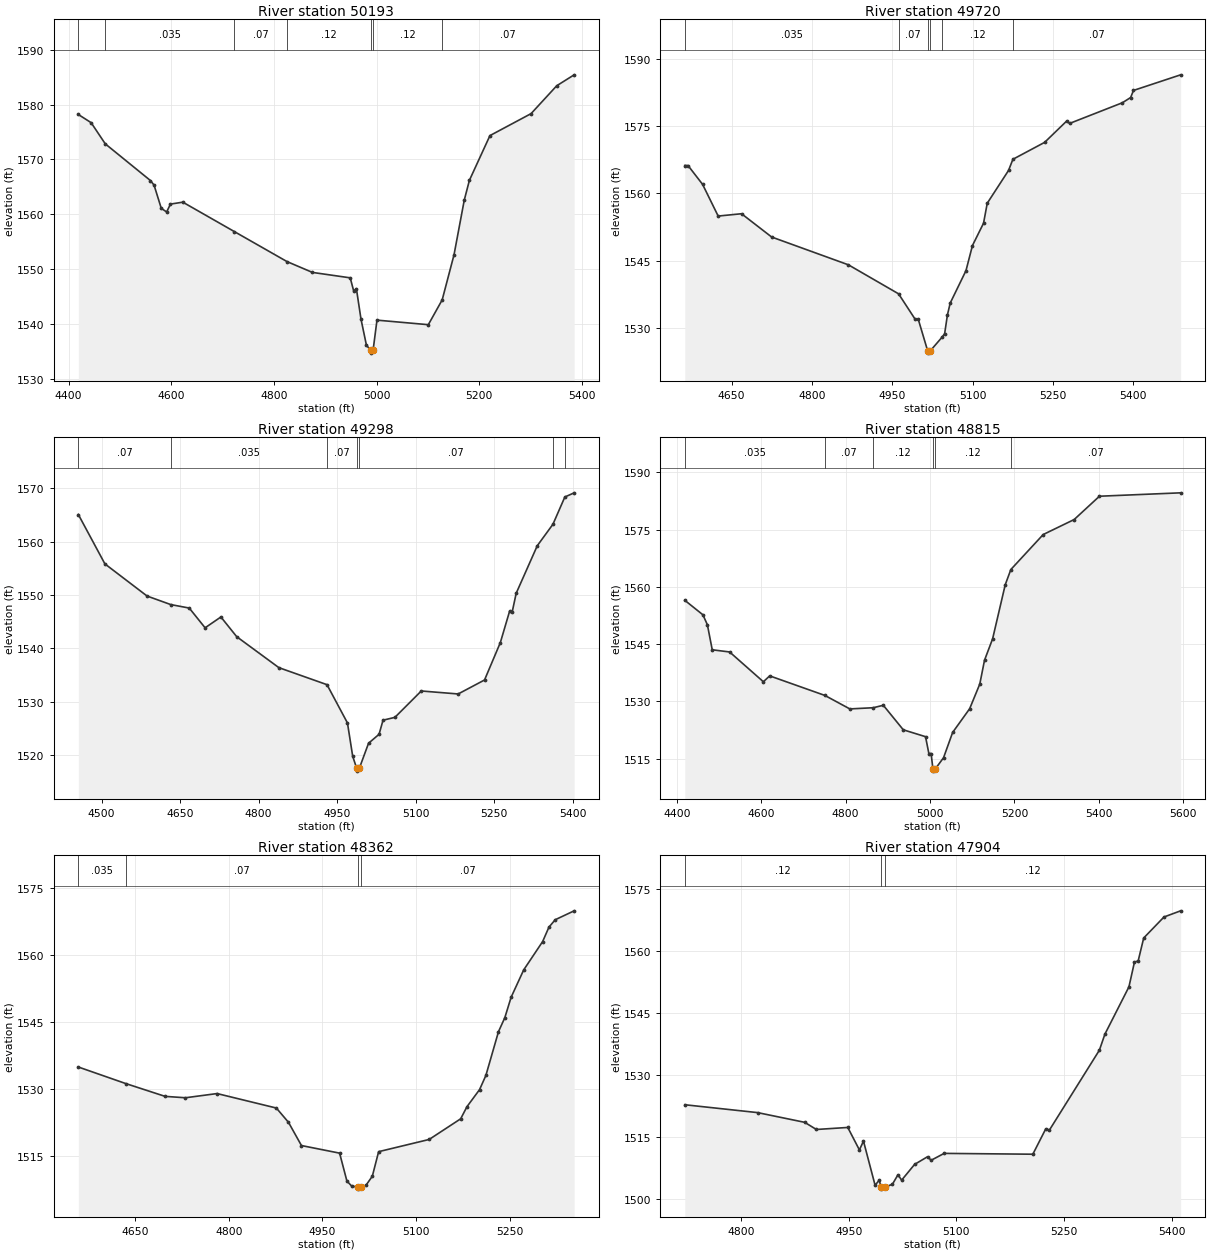
Type RM Length L Ch R = 1 ,50193   ,473,473,473
BEGIN DESCRIPTION:
WEST SISTER CREEK 95.0
END DESCRIPTION:
XS GIS Cut Line= 3
      2050428.56     13939596.12      2049883.39     13939419.03
      2049491.07     13939412.08
#Sta/Elev= 30
    4419 1578.21  4443.9 1576.72  4471.5 1572.85  4559.4 1566.16  4566.5 1565.32
  4580.5 1561.09    4591 1560.42  4598.4 1561.86  4622.5 1562.21  4722.7 1556.85
  4825.3 1551.37  4874.9 1549.39  4948.5  1548.4  4955.2 1546.01  4960.5 1546.43
  4969.5 1540.85    4980 1536.13  4988.3 1535.16  4988.6 1534.66    4993 1535.16
  5000.6 1540.68  5100.6 1539.85  5127.6 1544.38  5150.6 1552.59  5170.6 1562.59
  5180.6  1566.2  5220.6 1574.36  5300.7 1578.37  5350.7 1583.46  5384.6 1585.45
#Mann= 7 ,-1 , 0
    4419     .12       0  4471.5    .035       0  4722.7     .07       0
  4825.3     .12       0  4988.3     .05       0    4993     .12       0
  5127.6     .07       0
Bank Sta=4988.3,4993
XS Rating Curve= 0 ,0
Exp/Cntr=0.3,0.1

Type RM Length L Ch R = 1 ,49720   ,422,422,422
BEGIN DESCRIPTION:
WEST SISTER CREEK 94.0
END DESCRIPTION:
XS GIS Cut Line= 3
      2050369.52     13939387.79        2050025.       13939125.
      2049550.07     13938995.42
#Sta/Elev= 30
  4562.5 1566.22  4568.5 1566.22  4595.7 1562.02  4624.8 1554.95  4668.4 1555.47
  4724.6 1550.28  4867.9 1544.08  4961.6 1537.61  4992.7 1531.91  4998.4 1531.91
  5015.9 1524.89  5016.2 1524.39  5020.7 1524.89  5043.3 1528.02  5047.6 1528.75
  5052.8 1532.93    5058 1535.56  5087.4 1542.78  5099.5 1548.38  5120.2 1553.36
  5127.1 1557.81  5166.8 1565.11    5175 1567.61  5234.2 1571.38  5275.6 1576.16
  5280.8  1575.6  5379.3 1580.21  5394.8 1581.38  5400.1 1582.96  5488.1 1586.44
#Mann= 6 ,-1 , 0
  4562.5    .035       0  4961.6     .07       0  5015.9     .05       0
  5020.7     .07       0  5043.3     .12       0    5175     .07       0
Bank Sta=5015.9,5020.7
XS Rating Curve= 0 ,0
Exp/Cntr=0.3,0.1

Type RM Length L Ch R = 1 ,49298   ,483,483,483
BEGIN DESCRIPTION:
WEST SISTER CREEK 93.0
END DESCRIPTION:
XS GIS Cut Line= 3
      2050765.38     13938842.64        2050225.       13938775.
      2049825.01       13938825.
#Sta/Elev= 30
  4455.4 1565.07  4506.2 1555.82  4586.8  1549.8  4632.1  1548.2  4667.4 1547.55
  4697.7 1543.85  4727.9 1545.88  4758.1 1542.19  4838.7 1536.39  4930.7  1533.2
  4969.8 1526.03  4979.8  1519.8  4987.5 1517.51  4987.8 1517.01  4992.4 1517.51
  5010.1 1522.23  5030.2 1523.91  5037.8 1526.55  5060.5 1527.08  5110.9 1532.02
  5181.4 1531.46  5231.8 1534.08    5262 1541.08  5279.7 1546.96  5284.7 1546.83
  5292.3 1550.32  5332.6 1559.22  5362.6 1563.25  5385.3 1568.35  5403.1 1569.13
#Mann= 7 ,-1 , 0
  4455.4     .07       0  4632.1    .035       0  4930.7     .07       0
  4987.5     .05       0  4992.4     .07       0  5362.6     .12       0
  5385.3     .07       0
Bank Sta=4987.5,4992.4
XS Rating Curve= 0 ,0
Exp/Cntr=0.3,0.1

Type RM Length L Ch R = 1 ,48815   ,453,453,453
BEGIN DESCRIPTION:
WEST SISTER CREEK 92.0
END DESCRIPTION:
XS GIS Cut Line= 3
      2050775.71     13938509.29        2050225.       13938325.
      2049671.63     13938110.02
#Sta/Elev= 30
  4419.1 1556.48    4462 1552.68  4472.6 1550.07  4484.1 1543.52  4525.3 1542.95
  4605.2 1535.15  4620.2 1536.69  4750.9 1531.57    4810 1528.04  4865.4 1528.35
  4889.3 1528.99  4936.6 1522.57  4989.3 1520.77  4997.2 1516.35  5002.5 1516.35
  5006.9 1512.25  5007.3 1511.75  5011.9 1512.25    5032 1515.27  5053.5 1521.88
  5093.8 1528.09  5117.8 1534.55    5129 1540.79  5148.2  1546.4  5178.1 1560.56
  5191.4 1564.54    5268  1573.7  5341.4 1577.63  5401.2 1583.73  5593.5 1584.62
#Mann= 6 ,-1 , 0
  4419.1    .035       0  4750.9     .07       0  4865.4     .12       0
  5006.9     .05       0  5011.9     .12       0  5191.4     .07       0
Bank Sta=5006.9,5011.9
XS Rating Curve= 0 ,0
Exp/Cntr=0.3,0.1

Type RM Length L Ch R = 1 ,48362   ,458,458,458
BEGIN DESCRIPTION:
WEST SISTER CREEK 91.0
END DESCRIPTION:
XS GIS Cut Line= 3
      2050848.67     13938096.11        2050425.       13937975.
      2050074.99       13937925.
#Sta/Elev= 30
    4559 1534.96  4634.9 1531.26    4698 1528.39  4730.6 1528.08  4781.2 1529.02
  4876.2 1525.78  4895.6 1522.59  4916.4 1517.39  4977.5 1515.69  4989.2 1509.45
    4997  1508.3  5007.2 1508.14  5007.6 1507.64  5012.3 1508.14  5019.8 1508.52
  5029.9 1510.52    5040 1516.02  5120.9 1518.75  5171.4 1523.37  5181.5 1526.08
  5201.7 1529.91  5211.8 1533.07    5232 1542.87  5242.1 1545.98  5252.2 1550.56
  5272.4 1556.69  5302.7 1563.02  5312.8 1566.25  5322.9 1567.91  5353.2  1569.9
#Mann= 4 ,-1 , 0
    4559    .035       0  4634.9     .07       0  5007.2     .05       0
  5012.3     .07       0
Bank Sta=5007.2,5012.3
XS Rating Curve= 0 ,0
Exp/Cntr=0.3,0.1

Type RM Length L Ch R = 1 ,47904   ,441,441,441
BEGIN DESCRIPTION:
WEST SISTER CREEK 90.0
END DESCRIPTION:
XS GIS Cut Line= 3
      2050820.93     13937707.24        2050575.       13937575.
      2050175.03     13937475.01
#Sta/Elev= 30
  4721.2 1522.77  4822.7 1520.87  4888.4 1518.52  4904.7 1516.79  4948.5 1517.28
  4964.7 1511.85  4970.4 1513.98  4986.6  1503.3  4992.3 1504.53    4995 1502.87
  4995.4 1502.37  5000.1 1502.87  5010.7 1503.53  5018.5 1505.85  5023.6 1504.54
  5041.7 1508.35  5059.7  1510.2  5064.8 1509.35  5082.9 1511.01  5206.6 1510.81
  5224.6 1516.94  5229.8 1516.67  5299.4 1535.96  5307.1 1539.84  5340.6 1551.26
  5348.3 1557.25  5353.5 1557.54  5361.2 1563.08  5389.5 1568.16  5412.7 1569.65
#Mann= 3 ,-1 , 0
  4721.2     .12       0    4995     .05       0  5000.1     .12       0
Bank Sta=4995,5000.1
XS Rating Curve= 0 ,0
Exp/Cntr=0.3,0.1