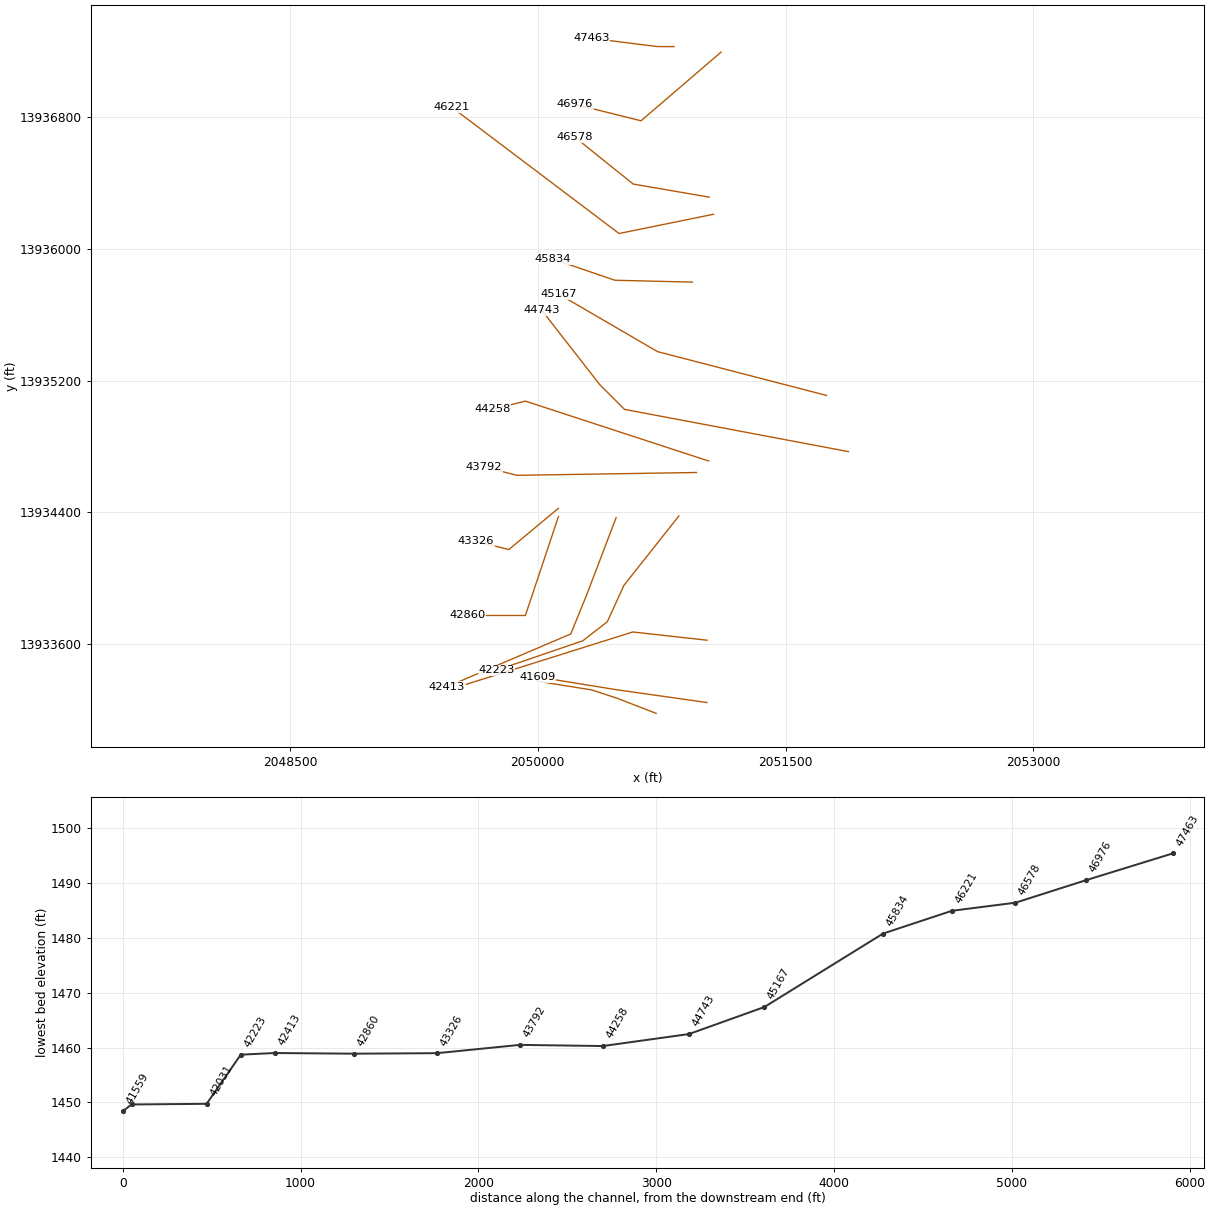
HEC-RAS study WEST SISTER CREEK.prj: WEST SISTER CREEK Base Level Engineering

--- WEST SISTER CREEK.g01 (geometry) --- (continued)

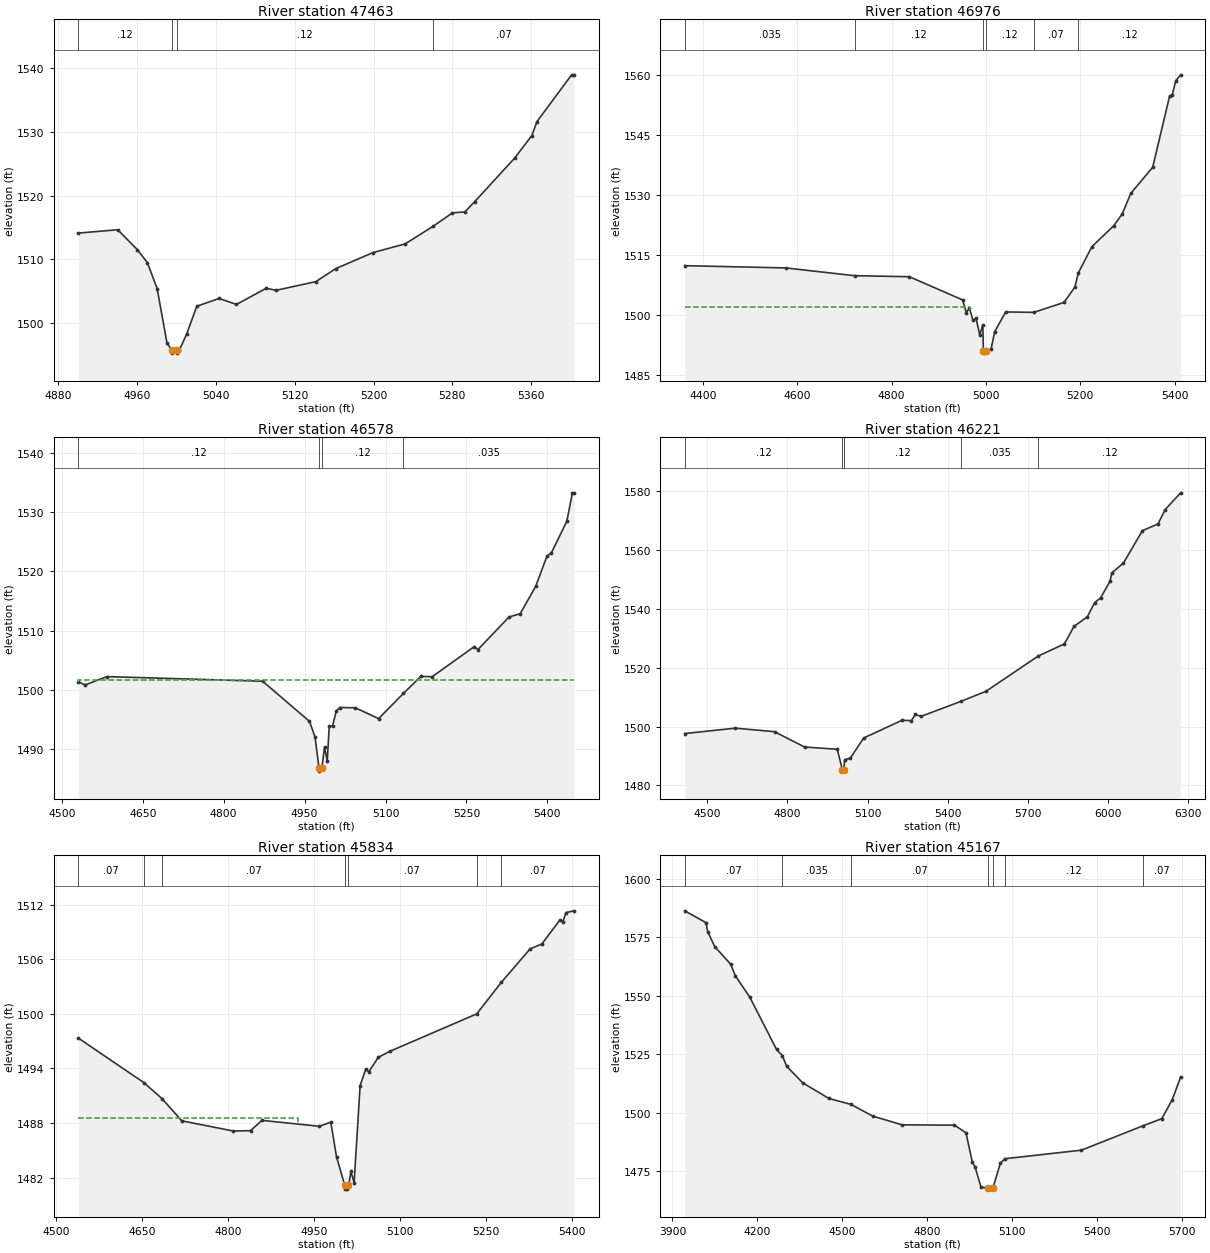
Type RM Length L Ch R = 1 ,47463   ,487,487,487
BEGIN DESCRIPTION:
WEST SISTER CREEK 89.0
END DESCRIPTION:
XS GIS Cut Line= 3
      2050825.04       13937225.        2050725.       13937225.
      2050324.95     13937275.01
#Sta/Elev= 30
  4900.4 1514.14  4940.4 1514.66  4960.4 1511.52  4970.4 1509.52  4980.4 1505.44
  4990.4 1496.86  4995.3 1495.81  4995.7 1495.31  5000.1 1495.31  5000.5 1495.81
    5003 1495.81  5010.5 1498.36  5020.6 1502.67  5043.3 1503.88  5060.9 1502.95
  5091.1 1505.48  5101.2 1505.16  5141.5 1506.53  5161.7 1508.57  5199.5 1511.08
  5232.2 1512.45  5260.3 1515.19  5280.1 1517.31  5292.7 1517.46  5302.8 1519.09
  5343.1 1525.88  5360.7 1529.44  5365.8 1531.61    5401 1538.96  5403.6 1538.96
#Mann= 4 ,-1 , 0
  4900.4     .12       0  4995.3     .05       0  5000.5     .12       0
  5260.3     .07       0
Bank Sta=4995.3,5000.5
XS Rating Curve= 0 ,0
Exp/Cntr=0.3,0.1

Type RM Length L Ch R = 1 ,46976   ,398,398,398
BEGIN DESCRIPTION:
WEST SISTER CREEK 88.0
END DESCRIPTION:
XS GIS Cut Line= 3
       2051109.6     13937191.71        2050625.       13936775.
      2050225.04     13936874.99
#Sta/Elev= 30
  4361.3  1512.3  4575.2 1511.74  4721.3  1509.8  4837.5 1509.54  4950.5 1503.74
  4958.2 1500.53  4964.8 1501.74  4972.4 1498.63    4979 1499.12  4986.7 1495.01
  4993.3 1497.52  4994.5 1490.95  4994.9 1490.45  4999.7 1490.95  5010.7 1491.44
  5018.5 1495.83  5041.7 1500.74  5101.4 1500.64  5165.4 1503.12  5188.5 1506.96
  5195.7 1510.47  5224.6 1517.06    5271  1522.3    5289 1525.25  5307.1 1530.38
  5353.5  1536.9  5389.5 1554.76  5394.7  1554.9  5402.4  1558.5  5412.7 1559.99
#Mann= 6 ,-1 , 0
  4361.3    .035       0  4721.3     .12       0  4994.5     .05       0
  4999.7     .12       0  5101.4     .07       0  5195.7     .12       0
#XS Ineff= 2 , 0
       0 4966.15 1501.98               0
Permanent Ineff=
       F       F
Bank Sta=4994.5,4999.7
XS Rating Curve= 0 ,0
Exp/Cntr=0.3,0.1

Type RM Length L Ch R = 1 ,46578   ,357,357,357
BEGIN DESCRIPTION:
WEST SISTER CREEK 87.0
END DESCRIPTION:
XS GIS Cut Line= 3
      2051037.17     13936312.05      2050577.84     13936391.25
      2050224.99       13936675.
#Sta/Elev= 30
  4530.7 1501.41  4543.1 1500.86  4583.6 1502.27  4872.3 1501.49  4959.1 1494.72
  4969.3 1492.11  4976.8 1486.84  4977.2 1486.34    4982 1486.84    4987 1490.43
    4992 1488.05  4995.7 1493.91  5001.8 1493.91  5008.8 1496.49  5015.2 1497.06
    5044 1497.02  5087.2 1495.19  5133.3 1499.45  5165.6 1502.31  5186.4 1502.25
  5264.8 1507.34  5271.2 1506.82  5328.8 1512.31  5349.6 1512.87  5378.4 1517.49
  5399.2 1522.57  5407.2 1523.08    5436 1528.45  5446.4 1533.24  5449.6 1533.24
#Mann= 4 ,-1 , 0
  4530.7     .12       0  4976.8     .05       0    4982     .12       0
  5133.3    .035       0
#XS Ineff= 2 , 0
       0 4257.32 1501.66               0
Permanent Ineff=
       F       F
Bank Sta=4976.8,4982
XS Rating Curve= 0 ,0
Exp/Cntr=0.3,0.1

Type RM Length L Ch R = 1 ,46221   ,387,387,387
BEGIN DESCRIPTION:
WEST SISTER CREEK 86.0
END DESCRIPTION:
XS GIS Cut Line= 3
      2051063.68     13936208.14      2050492.07     13936091.43
      2049478.42     13936858.04
#Sta/Elev= 30
  4416.6 1497.62  4605.7 1499.44  4752.1 1498.24  4864.3 1493.05  4986.8 1492.28
  5005.8 1485.37  5006.2 1484.87  5011.1 1485.37  5014.7 1488.73  5035.5 1489.24
  5085.4 1496.09    5229 1502.11  5264.4    1502  5278.9 1504.08  5299.8 1503.43
  5450.8 1508.57  5543.2 1511.95  5738.6 1523.91  5836.4 1528.02    5872 1533.93
  5921.9 1537.18  5949.2 1541.99  5971.9 1543.65  6007.3 1549.33  6013.5  1552.1
  6057.2 1555.42    6128 1566.41  6186.2 1568.67  6213.3 1573.55  6270.9 1579.23
#Mann= 5 ,-1 , 0
  4416.6     .12       0  5005.8     .05       0  5011.1     .12       0
  5450.8    .035       0  5738.6     .12       0
#XS Ineff= 2 , 0
       0 4706.44 1497.55               0
Permanent Ineff=
       F       F
Bank Sta=5005.8,5011.1
XS Rating Curve= 0 ,0
Exp/Cntr=0.3,0.1

Type RM Length L Ch R = 1 ,45834   ,667,667,667
BEGIN DESCRIPTION:
WEST SISTER CREEK 85.0
END DESCRIPTION:
XS GIS Cut Line= 3
      2050935.44     13935796.61      2050466.73     13935807.92
      2050091.68     13935936.41
#Sta/Elev= 30
  4538.7 1497.34  4653.1 1492.44  4684.9 1490.67  4719.2 1488.24  4809.2 1487.12
  4839.2 1487.16  4859.2 1488.29  4959.3 1487.64  4979.3 1488.09  4989.3 1484.27
  5003.3 1481.23  5003.7 1480.73  5008.2 1480.73  5008.6 1481.23  5010.8 1481.23
  5014.3 1482.67    5020 1481.44  5030.5 1492.12  5040.3 1493.91  5045.6 1493.63
  5062.2 1495.22  5083.4 1495.91    5234    1500  5276.8 1503.46  5327.2 1507.15
  5347.6 1507.68  5379.2 1510.33  5384.4 1510.14  5389.9 1511.14    5404 1511.33
#Mann= 7 ,-1 , 0
  4538.7     .07       0  4653.1     .12       0  4684.9     .07       0
  5003.3     .05       0  5008.6     .07       0    5234    .035       0
  5276.8     .07       0
#XS Ineff= 2 , 0
       0 4921.34 1488.54               0
Permanent Ineff=
       F       F
Bank Sta=5003.3,5008.6
XS Rating Curve= 0 ,0
Exp/Cntr=0.3,0.1

Type RM Length L Ch R = 1 ,45167   ,424,424,424
BEGIN DESCRIPTION:
WEST SISTER CREEK 84.0
END DESCRIPTION:
XS GIS Cut Line= 3
      2051747.49     13935109.53        2050725.       13935375.
      2050125.01     13935724.99
#Sta/Elev= 30
  3943.9  1586.2  4018.8 1581.14  4024.7 1577.35  4049.8 1570.89  4105.8 1563.42
  4122.1 1558.54  4173.8 1549.24    4268 1526.99  4288.2 1524.41  4303.4 1519.89
  4359.7 1512.81  4452.7 1506.08  4530.8 1503.55  4607.7 1498.55    4711 1494.83
  4896.3 1494.68  4936.9 1491.42    4959 1479.07  4969.3 1476.71    4990 1468.19
  5014.9 1467.87  5015.4 1467.37    5032 1467.87  5058.2 1478.35  5073.9 1480.35
  5344.7 1484.01  5562.9 1494.45  5628.3 1497.45  5665.6 1505.61  5694.9 1515.26
#Mann= 7 ,-1 , 0
  3943.9     .07       0  4288.2    .035       0  4530.8     .07       0
  5014.9     .05       0    5032     .07       0  5073.9     .12       0
  5562.9     .07       0
Bank Sta=5014.9,5032
XS Rating Curve= 0 ,0
Exp/Cntr=0.3,0.1

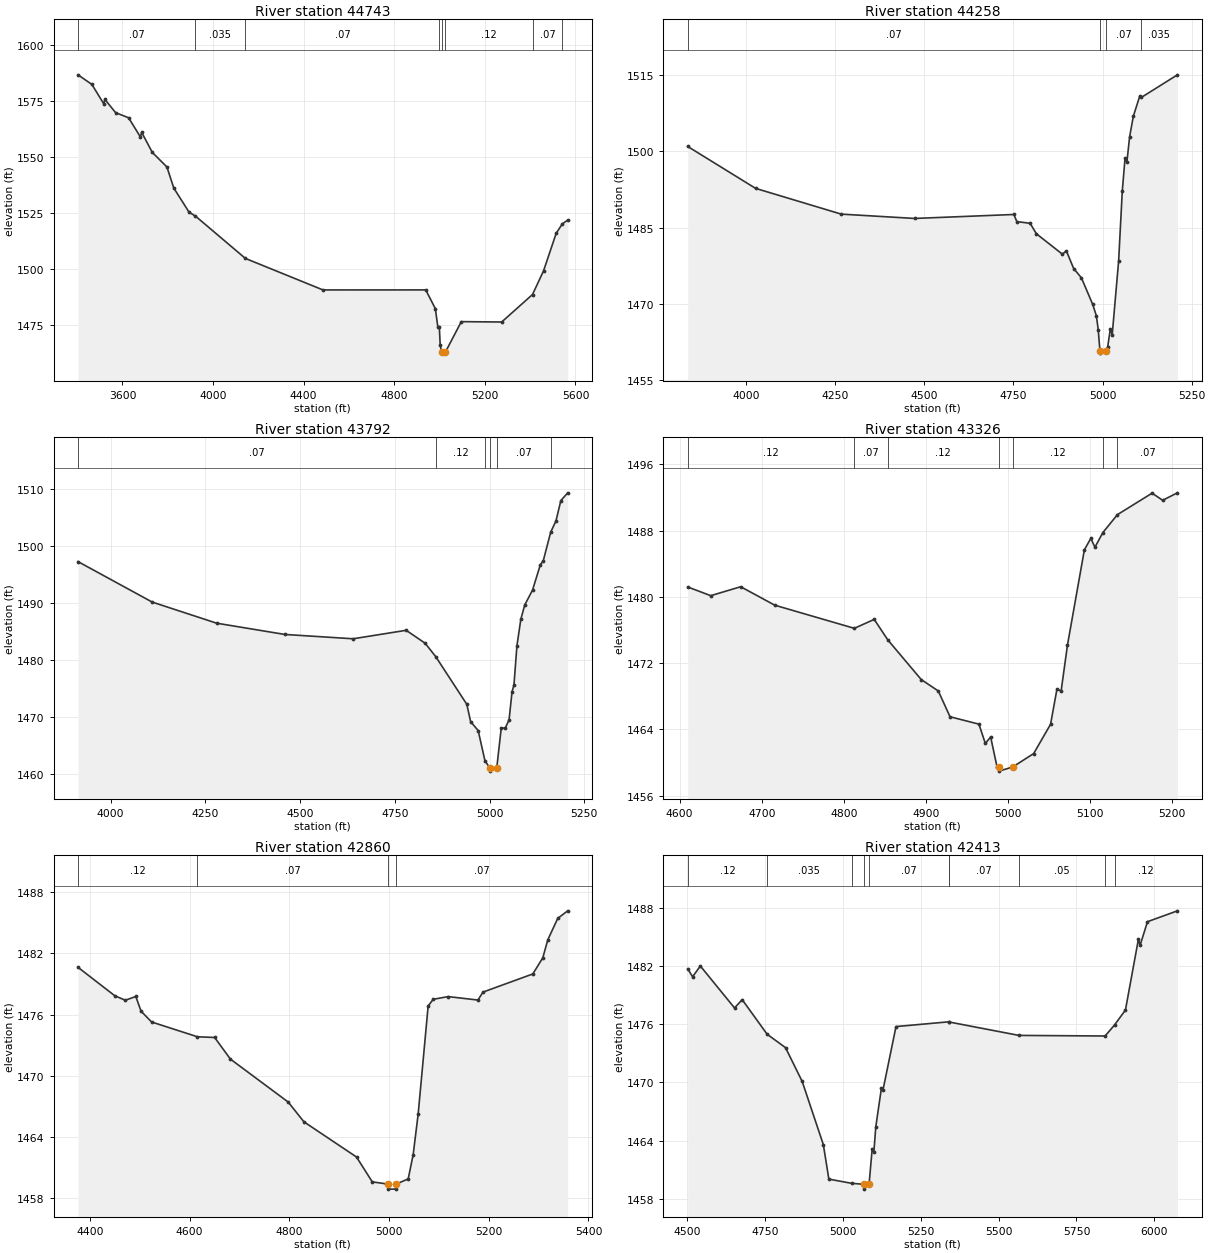
Type RM Length L Ch R = 1 ,44743   ,485,485,485
BEGIN DESCRIPTION:
WEST SISTER CREEK 83.0
END DESCRIPTION:
XS GIS Cut Line= 4
      2051880.54     13934768.72        2050525.       13935025.
        2050375.       13935175.      2050024.99     13935625.02
#Sta/Elev= 30
    3404 1586.73  3465.2 1582.44  3517.5  1573.8  3522.6 1575.74  3569.9 1569.85
  3627.3 1567.55  3679.7 1558.93  3684.8 1561.09    3732 1552.07  3796.4 1545.59
  3826.9 1536.14  3894.2 1525.39  3922.4 1523.65  4142.9 1504.74  4485.4 1490.67
  4939.1 1490.68  4981.5  1482.3  4992.2 1474.33    4999 1474.12  5002.9 1466.03
  5008.9 1462.95  5009.4 1462.45    5026 1462.95  5096.1 1476.51  5274.4 1476.35
  5410.4 1488.63    5459 1499.15  5515.1 1516.01  5542.3  1520.2  5565.8 1521.86
#Mann= 8 ,-1 , 0
    3404     .07       0  3922.4    .035       0  4142.9     .07       0
    4999     .12       0  5008.9     .05       0    5026     .12       0
  5410.4     .07       0  5542.3    .035       0
Bank Sta=5008.9,5026
XS Rating Curve= 0 ,0
Exp/Cntr=0.3,0.1

Type RM Length L Ch R = 1 ,44258   ,466,466,466
BEGIN DESCRIPTION:
WEST SISTER CREEK 82.0
END DESCRIPTION:
XS GIS Cut Line= 3
       2051034.1     13934711.82        2049925.       13935075.
        2049725.       13935025.
#Sta/Elev= 30
  3836.8 1500.96  4027.1 1492.71  4267.3 1487.64    4473 1486.79  4751.3 1487.57
  4759.7 1486.16  4796.8 1485.84  4814.4 1483.78  4887.1 1479.77  4898.6 1480.39
    4919 1476.93  4940.7  1475.1  4972.3 1469.88  4982.7 1467.62  4987.9 1464.87
  4992.6 1460.77  4993.1 1460.27  5009.8 1460.77  5014.2  1461.4  5021.9 1465.07
    5027 1463.83  5045.1 1478.41  5055.4 1492.24  5063.1 1498.65  5068.3 1497.92
    5076  1502.9  5086.3  1506.9  5104.3 1510.88  5108.8 1510.62    5210 1515.07
#Mann= 4 ,-1 , 0
  3836.8     .07       0  4992.6     .05       0  5009.8     .07       0
  5108.8    .035       0
Bank Sta=4992.6,5009.8
XS Rating Curve= 0 ,0
Exp/Cntr=0.3,0.1

Type RM Length L Ch R = 1 ,43792   ,466,466,466
BEGIN DESCRIPTION:
WEST SISTER CREEK 81.0
END DESCRIPTION:
XS GIS Cut Line= 3
      2050960.66     13934642.14        2049875.       13934625.
      2049674.95     13934675.01
#Sta/Elev= 30
  3914.2  1497.3  4109.9 1490.19  4279.9 1486.48  4459.9  1484.5    4640 1483.74
    4780 1485.23    4830 1482.96  4858.1 1480.59    4940 1472.22    4950 1469.19
    4970  1467.6  4987.9 1462.28  5001.7 1460.98  5002.2 1460.48  5018.9 1460.98
  5030.9 1468.08  5041.2 1468.02  5051.5  1469.5  5059.3 1474.41  5064.4 1475.63
  5072.2 1482.51  5082.5 1487.16  5092.8 1489.68  5113.4  1492.3    5134 1496.75
  5141.7 1497.45  5161.3 1502.48  5175.2 1504.45  5188.1 1508.03  5206.2 1509.39
#Mann= 6 ,-1 , 0
  3914.2     .07       0  4858.1     .12       0  4987.9     .07       0
  5001.7     .05       0  5018.9     .07       0  5161.3    .035       0
Bank Sta=5001.7,5018.9
XS Rating Curve= 0 ,0
Exp/Cntr=0.3,0.1

Type RM Length L Ch R = 1 ,43326   ,466,466,466
BEGIN DESCRIPTION:
WEST SISTER CREEK 80.0
END DESCRIPTION:
XS GIS Cut Line= 3
      2050125.04     13934425.03        2049825.       13934175.
      2049625.01       13934225.
#Sta/Elev= 30
  4609.9 1481.19  4637.9 1480.14  4674.4 1481.22    4716 1478.99  4812.9  1476.2
  4837.1 1477.28  4853.7  1474.8  4894.4 1470.02  4915.2 1468.64  4929.5 1465.53
  4964.7 1464.64  4972.5 1462.31    4979 1463.09  4986.8 1459.47  4988.6 1459.47
  4989.1 1458.97  5005.9 1459.47  5031.4 1461.09    5052 1464.62  5059.7 1468.82
  5064.9 1468.66  5072.6 1474.18  5093.2 1485.67    5101 1487.05  5106.1 1485.99
  5115.7 1487.75  5133.5 1489.92  5175.7 1492.51  5188.6 1491.65  5206.6 1492.55
#Mann= 7 ,-1 , 0
  4609.9     .12       0  4812.9     .07       0  4853.7     .12       0
  4988.6     .05       0  5005.9     .12       0  5115.7    .035       0
  5133.5     .07       0
Bank Sta=4988.6,5005.9
XS Rating Curve= 0 ,0
Exp/Cntr=0.3,0.1

Type RM Length L Ch R = 1 ,42860   ,447,447,447
BEGIN DESCRIPTION:
WEST SISTER CREEK 79.0
END DESCRIPTION:
XS GIS Cut Line= 3
        2050125.     13934374.99        2049925.       13933775.
      2049575.04       13933775.
#Sta/Elev= 30
    4376 1480.63  4449.8 1477.84  4470.9  1477.4  4491.9 1477.77  4502.5 1476.33
  4523.6 1475.27  4615.5 1473.82  4650.1 1473.75  4681.7 1471.63  4797.6 1467.42
  4829.2 1465.48  4934.7 1462.03  4966.3 1459.59  4997.2 1459.38  4997.7 1458.88
    5014 1458.88  5014.5 1459.38  5038.4 1459.88  5048.4 1462.27  5058.4 1466.25
  5078.4 1476.83  5088.4 1477.49  5118.4 1477.76  5178.4 1477.42  5188.4  1478.2
  5288.4 1479.98  5308.4 1481.56  5318.4 1483.32  5338.4 1485.43  5358.4 1486.17
#Mann= 4 ,-1 , 0
    4376     .12       0  4615.5     .07       0  4997.2     .05       0
  5014.5     .07       0
Bank Sta=4997.2,5014.5
XS Rating Curve= 0 ,0
Exp/Cntr=0.3,0.1

Type RM Length L Ch R = 1 ,42413   ,190,190,190
BEGIN DESCRIPTION:
WEST SISTER CREEK 78.0
END DESCRIPTION:
XS GIS Cut Line= 4
      2050474.11     13934368.34      2050296.59     13933901.67
      2050199.88     13933663.17      2049450.51     13933342.63
#Sta/Elev= 30
  4502.3 1481.68  4517.9 1480.87  4542.7 1481.98  4652.4 1477.66  4677.1 1478.51
  4757.1 1474.95  4816.1 1473.57  4869.6 1470.09  4937.5 1463.58  4955.2 1460.03
    5028  1459.6  5066.9  1459.5  5067.4    1459  5084.3  1459.5  5094.3 1463.16
  5099.7 1462.83  5105.9 1465.43  5123.8 1469.38  5129.2 1469.25  5170.7 1475.74
  5340.2 1476.23  5341.3 1476.21  5565.4 1474.83  5841.8 1474.77    5872  1475.9
  5907.1 1477.44  5948.8 1484.74  5954.2 1484.11  5977.8 1486.54    6074 1487.66
#Mann= 10 ,-1 , 0
  4502.3     .12       0  4757.1    .035       0    5028     .07       0
  5066.9    .035       0  5084.3     .07       0  5340.2     .05       0
  5341.3     .07       0  5565.4     .05       0  5841.8     .07       0
    5872     .12       0
Bank Sta=5066.9,5084.3
XS Rating Curve= 0 ,0
Exp/Cntr=0.3,0.1

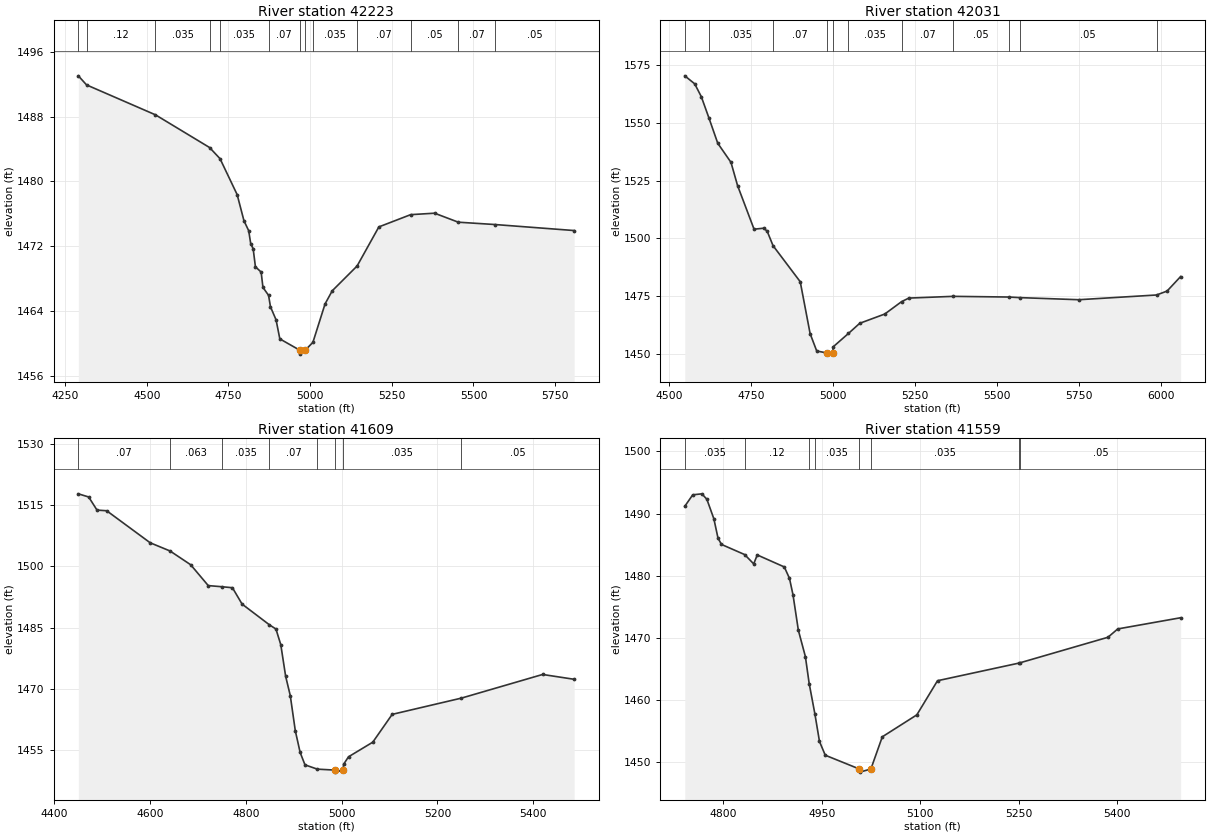
Type RM Length L Ch R = 1 ,42223   ,192,192,192
BEGIN DESCRIPTION:
WEST SISTER CREEK 77.5
END DESCRIPTION:
XS GIS Cut Line= 5
      2050853.79     13934378.39      2050521.06     13933957.31
      2050420.84     13933736.86      2050271.81     13933621.32
      2049751.37     13933443.15
#Sta/Elev= 30
  4290.7 1493.02  4315.9  1491.9  4526.8 1488.21  4692.3 1484.18  4724.4  1482.8
  4776.8 1478.37  4797.6 1475.15  4812.1 1473.92  4818.5 1472.27  4825.7 1471.72
  4832.7 1469.47  4850.2 1468.82  4855.7 1466.93  4872.9 1465.95  4878.8 1464.53
  4895.8 1462.94  4907.4 1460.58  4967.8  1459.2  4968.3  1458.7  4985.3  1459.2
  5008.6 1460.15  5045.8 1464.89  5067.8 1466.51  5143.9 1469.57  5210.5 1474.39
  5307.8  1475.9    5381 1476.08  5453.6 1474.97  5566.4 1474.68  5808.2 1473.94
#Mann= 13 ,-1 , 0
  4290.7     .07       0  4315.9     .12       0  4526.8    .035       0
  4692.3     .07       0  4724.4    .035       0  4872.9     .07       0
  4967.8     .05       0  4985.3     .07       0  5008.6    .035       0
  5143.9     .07       0  5307.8     .05       0  5453.6     .07       0
  5566.4     .05       0
Bank Sta=4967.8,4985.3
XS Rating Curve= 0 ,0
Exp/Cntr=0.3,0.1

Type RM Length L Ch R = 1 ,42031   ,422,422,422
BEGIN DESCRIPTION:
WEST SISTER CREEK 77.0
END DESCRIPTION:
XS GIS Cut Line= 3
      2051025.03       13933625.        2050575.       13933675.
      2049563.97     13933356.53
#Sta/Elev= 30
  4547.3 1570.47  4577.5    1567  4597.6 1561.46  4620.9 1552.21  4647.9 1541.21
  4688.2 1532.94  4708.3 1522.86  4758.6 1503.95  4788.8 1504.39  4798.9 1502.98
  4816.5 1496.81  4899.5 1481.16  4929.7 1458.63  4949.8 1451.12  4981.3 1450.26
  4981.8 1449.76  4998.8 1450.26  5000.1 1452.94  5046.6 1458.73    5081 1463.13
  5157.4 1467.15  5208.5  1472.5  5230.8 1474.07    5366 1474.82  5536.4 1474.52
  5569.6 1474.27  5749.4 1473.36  5986.7 1475.41  6018.8 1477.12  6060.1 1483.41
#Mann= 11 ,-1 , 0
  4547.3     .12       0  4620.9    .035       0  4816.5     .07       0
  4981.3     .05       0  4998.8     .07       0  5046.6    .035       0
  5208.5     .07       0    5366     .05       0  5536.4     .07       0
  5569.6     .05       0  5986.7     .12       0
Bank Sta=4981.3,4998.8
XS Rating Curve= 0 ,0
Exp/Cntr=0.3,0.1

Type RM Length L Ch R = 1 ,41609   ,50,50,50
BEGIN DESCRIPTION:
WEST SISTER CREEK 76.0
END DESCRIPTION:
XS GIS Cut Line= 3
      2051023.64     13933247.28        2050475.       13933325.
      2049999.95     13933402.18
#Sta/Elev= 30
    4450 1517.72  4471.6 1516.95    4489 1513.74  4509.2 1513.58  4600.1 1505.74
  4641.5 1503.74  4684.6 1500.37  4721.3 1495.27  4749.1    1495  4771.8 1494.75
    4792 1490.74  4849.1 1485.67  4862.7 1484.64  4872.8  1480.8  4882.9  1473.1
  4892.6 1468.35  4903.1 1459.75  4913.2 1454.45  4923.3 1451.42  4949.1 1450.37
  4985.3 1450.14  4985.8 1449.64  5002.8 1450.14  5004.1 1451.59  5014.2 1453.39
  5064.9 1456.97  5105.4 1463.77  5250.1 1467.75  5419.5 1473.53  5485.4 1472.35
#Mann= 8 ,-1 , 0
    4450     .07       0  4641.5    .063       0  4749.1    .035       0
  4849.1     .07       0  4949.1    .035       0  4985.3    .035       0
  5002.8    .035       0  5250.1     .05       0
Bank Sta=4985.3,5002.8
XS Rating Curve= 0 ,0
Exp/Cntr=0.3,0.1

Type RM Length L Ch R = 1 ,41559   ,375,375,375
BEGIN DESCRIPTION:
WEST SISTER CREEK 75.5
END DESCRIPTION:
XS GIS Cut Line= 4
      2050716.29     13933181.36        2050475.       13933275.
      2050325.53     13933323.72      2049990.44     13933377.48
#Sta/Elev= 30
  4741.2 1491.17  4753.3 1493.01  4767.2 1493.17  4774.8  1492.3  4785.5 1489.15
  4791.8 1486.04  4797.1 1485.03  4832.4  1483.4  4846.2  1481.9  4851.6 1483.34
  4892.8 1481.41  4900.7 1479.57  4906.1  1476.9  4914.2 1471.23  4924.9    1467
  4930.7 1462.66  4939.4 1457.77  4946.4 1453.34  4955.2 1451.13  5007.2 1448.91
  5007.7 1448.41  5024.7 1448.91  5042.1 1454.09  5094.7 1457.62  5126.2 1463.11
  5250.9 1465.96  5252.1    1466  5385.9  1470.1  5400.8 1471.44  5496.6 1473.24
#Mann= 8 ,-1 , 0
  4741.2    .035       0  4832.4     .12       0  4930.7     .07       0
  4939.4    .035       0  5007.2    .035       0  5024.7    .035       0
  5250.9     .07       0  5252.1     .05       0
Bank Sta=5007.2,5024.7
XS Rating Curve= 0 ,0
Exp/Cntr=0.3,0.1