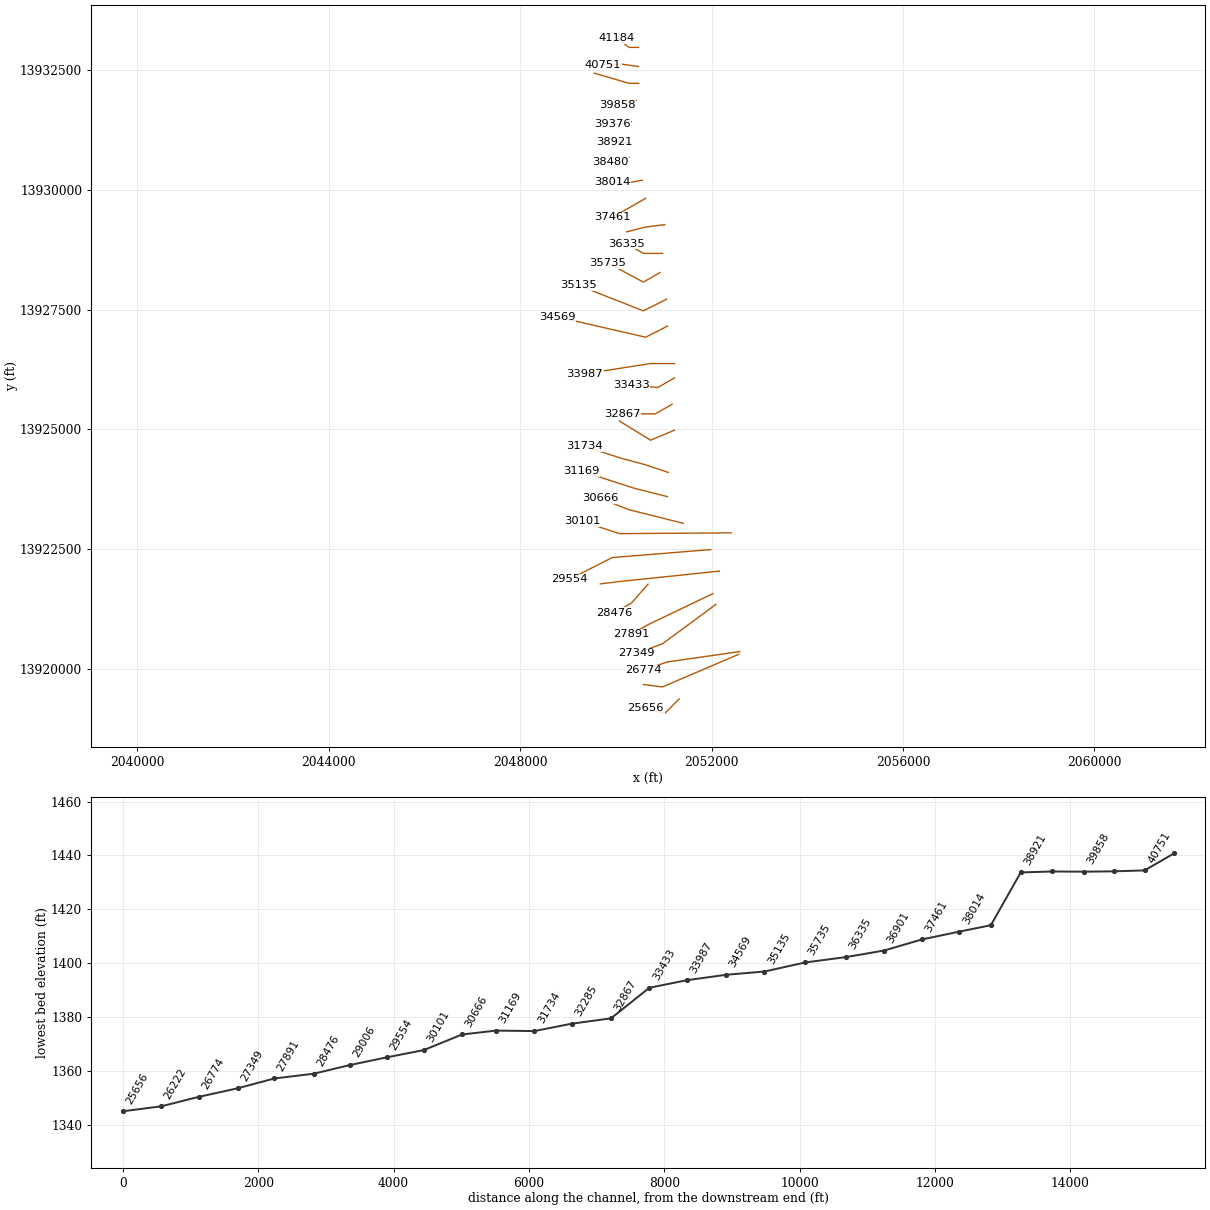
HEC-RAS study WEST SISTER CREEK.prj: WEST SISTER CREEK Base Level Engineering

--- WEST SISTER CREEK.g01 (geometry) --- (continued)

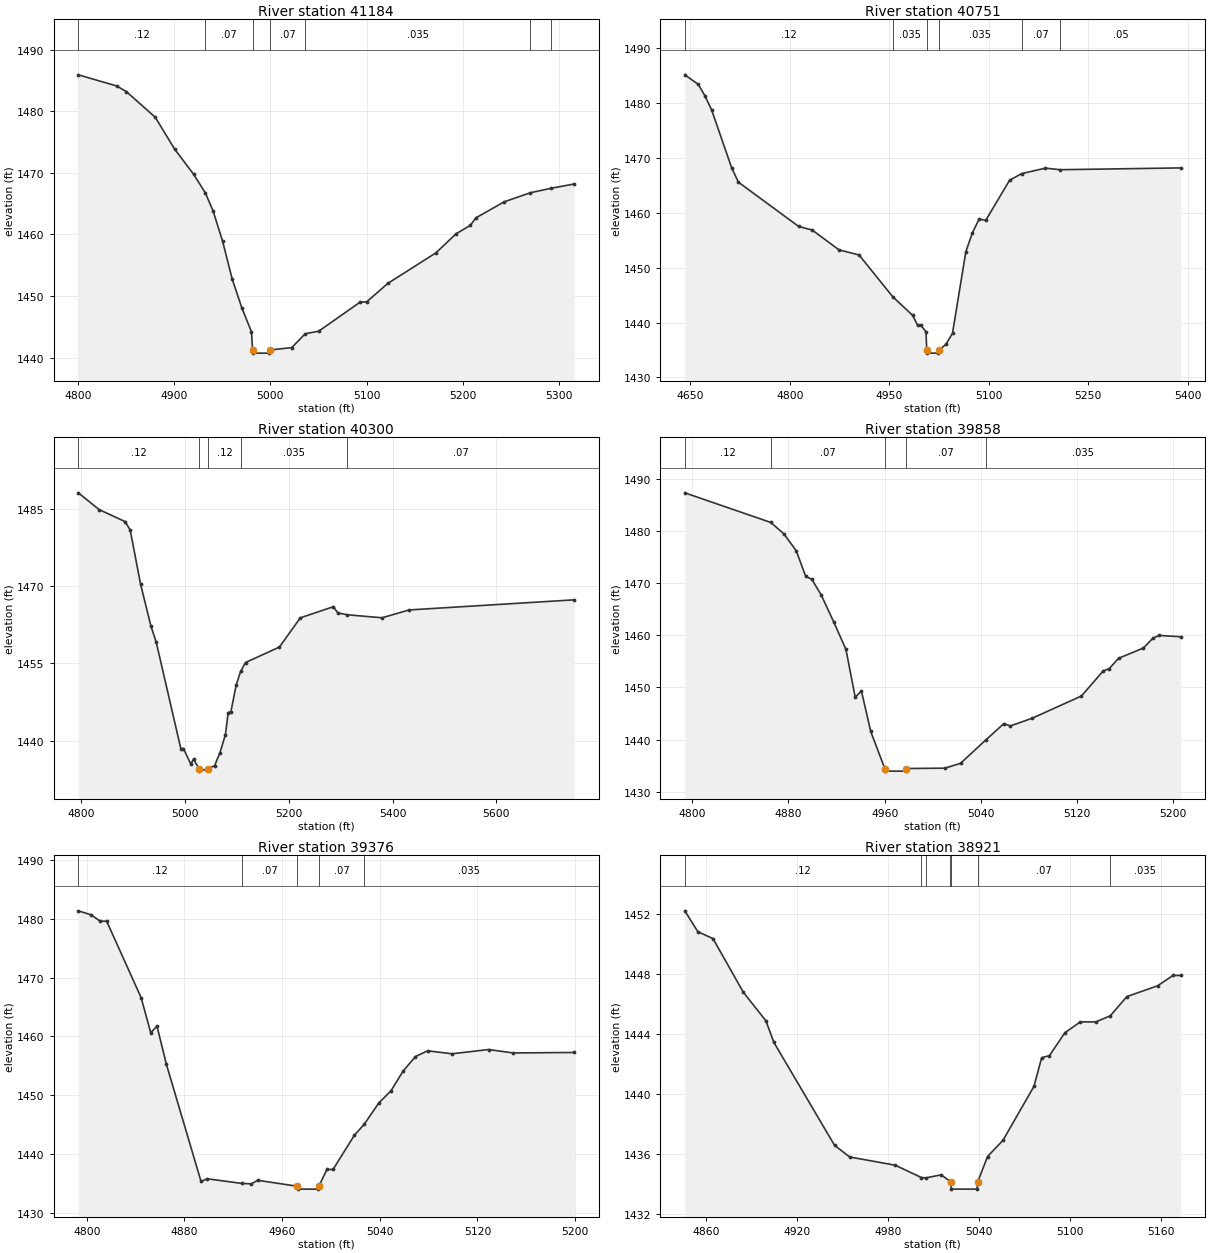
Type RM Length L Ch R = 1 ,41184   ,433,433,433
BEGIN DESCRIPTION:
WEST SISTER CREEK 75.0
END DESCRIPTION:
XS GIS Cut Line= 3
      2050474.99       13932975.        2050275.       13932975.
      2050022.35     13933163.98
#Sta/Elev= 30
  4800.3 1485.89  4840.3 1484.08  4850.3 1483.16  4880.3    1479  4900.3 1473.86
  4920.3 1469.72  4932.3 1466.74  4940.3 1463.84  4950.3 1458.88  4960.3 1452.72
  4970.3 1448.07  4980.3 1444.18  4981.5 1441.22    4982 1440.72  4998.6 1440.72
  4999.1 1441.22  5022.2 1441.62  5036.2 1443.87  5050.2 1444.28    5093 1448.97
  5100.2 1449.06  5122.2 1452.05  5172.2 1457.01  5193.1  1460.1  5207.7 1461.44
  5213.9  1462.7  5243.1 1465.28  5270.2 1466.75  5291.6 1467.47  5315.8 1468.17
#Mann= 7 ,-1 , 0
  4800.3     .12       0  4932.3     .07       0  4981.5     .05       0
  4999.1     .07       0  5036.2    .035       0  5270.2     .07       0
  5291.6     .05       0
Bank Sta=4981.5,4999.1
XS Rating Curve= 0 ,0
Exp/Cntr=0.3,0.1

Type RM Length L Ch R = 1 ,40751   ,451,451,451
BEGIN DESCRIPTION:
WEST SISTER CREEK 74.0
END DESCRIPTION:
XS GIS Cut Line= 3
      2050474.96     13932575.01        2050125.       13932625.
      2049731.47     13932610.62
#Sta/Elev= 30
  4641.8 1485.17    4662 1483.44  4672.1 1481.36  4682.2 1478.79  4712.5 1468.19
  4722.6  1465.6  4813.5 1457.52  4833.7 1456.88  4874.1 1453.27  4904.4 1452.33
  4955.5 1444.67  4985.2 1441.32  4992.8 1439.49  4997.8 1439.49  5005.3 1438.32
  5006.5 1434.93    5007 1434.43  5023.7 1434.43  5024.2 1434.93  5035.3 1436.01
  5045.3 1438.06  5065.4 1452.94  5075.4  1456.4  5085.4 1458.87  5095.4 1458.64
  5131.3 1465.95  5149.3 1467.15  5185.4 1468.16  5207.4 1467.87  5389.1  1468.2
#Mann= 6 ,-1 , 0
  4641.8     .12       0  4955.5    .035       0  5006.5    .035       0
  5024.2    .035       0  5149.3     .07       0  5207.4     .05       0
Bank Sta=5006.5,5024.2
XS Rating Curve= 0 ,0
Exp/Cntr=0.3,0.1

Type RM Length L Ch R = 1 ,40300   ,442,442,442
BEGIN DESCRIPTION:
WEST SISTER CREEK 73.0
END DESCRIPTION:
XS GIS Cut Line= 3
      2050475.03       13932225.        2050275.       13932225.
      2049549.64     13932436.89
#Sta/Elev= 30
  4794.4 1488.07  4834.4 1484.82  4884.4  1482.5  4894.4 1480.85  4914.4 1470.34
  4934.4 1462.18  4944.4 1459.15  4991.9 1438.46    4997 1438.46  5011.2 1435.45
  5016.4 1436.38  5027.2 1434.58  5027.7 1434.08  5044.9 1434.58  5056.9 1435.11
  5067.4 1437.67  5077.8 1441.11  5083.3 1445.44  5088.5 1445.61  5098.6 1450.76
  5107.2 1453.41  5116.7 1455.15    5182 1458.15  5222.3 1463.82  5286.1 1465.98
  5294.5 1464.77    5313 1464.41  5379.9 1463.83    5432 1465.35  5750.1 1467.31
#Mann= 5 ,-1 , 0
  4794.4     .12       0  5027.2     .05       0  5044.9     .12       0
  5107.2    .035       0    5313     .07       0
Bank Sta=5027.2,5044.9
XS Rating Curve= 0 ,0
Exp/Cntr=0.3,0.1

Type RM Length L Ch R = 1 ,39858   ,482,482,482
BEGIN DESCRIPTION:
WEST SISTER CREEK 72.0
END DESCRIPTION:
XS GIS Cut Line= 3
      2050424.97     13931874.99        2050225.       13931825.
      2050024.98     13931774.99
#Sta/Elev= 30
  4793.8 1487.32  4865.4 1481.63  4876.2 1479.45  4886.5  1476.2  4894.3 1471.31
  4899.4 1470.74  4907.2 1467.74  4917.5 1462.64  4927.8 1457.28  4935.5 1448.13
  4940.7 1449.31  4948.4 1441.55  4960.1 1434.45  4960.6 1433.95  4977.4 1433.95
  4977.9 1434.45  5010.2 1434.52  5023.1 1435.45  5044.3 1439.97  5059.2 1443.08
  5064.3  1442.6  5082.4 1444.07  5123.6 1448.35  5141.7 1453.15  5146.8 1453.62
  5154.5 1455.59  5175.2 1457.56  5182.9 1459.41    5188 1459.98  5206.1 1459.72
#Mann= 5 ,-1 , 0
  4793.8     .12       0  4865.4     .07       0  4960.1     .05       0
  4977.9     .07       0  5044.3    .035       0
Bank Sta=4960.1,4977.9
XS Rating Curve= 0 ,0
Exp/Cntr=0.3,0.1

Type RM Length L Ch R = 1 ,39376   ,455,455,455
BEGIN DESCRIPTION:
WEST SISTER CREEK 71.0
END DESCRIPTION:
XS GIS Cut Line= 3
      2050324.99       13931425.        2050125.       13931375.
      2049925.05       13931375.
#Sta/Elev= 30
  4793.1 1481.37  4803.4  1480.7  4811.1  1479.6  4816.3 1479.61  4844.6 1466.56
  4852.4 1460.61  4857.5 1461.77  4865.2 1455.27  4893.6 1435.33  4898.7 1435.78
    4927 1434.99  4934.8 1434.92    4940 1435.52  4972.3 1434.52  4972.8 1434.02
  4989.6 1434.02  4990.1 1434.52  4996.7 1437.36  5001.7 1437.36  5019.2 1443.19
  5027.2 1445.04  5039.2 1448.68  5049.2 1450.76  5059.2 1454.13  5069.2 1456.57
  5079.2 1457.55  5099.2 1457.05  5129.2 1457.77  5149.2 1457.19  5199.2 1457.27
#Mann= 5 ,-1 , 0
  4793.1     .12       0    4927     .07       0  4972.3     .05       0
  4990.1     .07       0  5027.2    .035       0
Bank Sta=4972.3,4990.1
XS Rating Curve= 0 ,0
Exp/Cntr=0.3,0.1

Type RM Length L Ch R = 1 ,38921   ,441,441,441
BEGIN DESCRIPTION:
WEST SISTER CREEK 70.0
END DESCRIPTION:
XS GIS Cut Line= 3
       2050283.6     13930982.53        2050125.       13930975.
      2049960.14     13931007.95
#Sta/Elev= 30
  4846.2 1452.19  4854.8  1450.8  4864.8 1450.34  4884.8 1446.77  4899.7 1444.87
  4904.9 1443.44  4944.9 1436.59  4954.9 1435.81    4985 1435.26  5002.2 1434.44
  5005.2 1434.42  5015.2 1434.62  5020.9 1434.21  5021.5 1434.17    5022 1433.67
  5038.9 1433.67  5039.4 1434.17  5045.8 1435.84    5056 1436.92  5076.4 1440.51
  5081.5 1442.42  5086.6 1442.55  5096.8 1444.08    5107  1444.8  5117.2  1444.8
  5126.7  1445.2  5137.6 1446.48  5157.9  1447.2  5168.1 1447.89  5173.1 1447.89
#Mann= 7 ,-1 , 0
  4846.2     .12       0  5002.2     .07       0  5005.2     .12       0
  5020.9     .07       0  5021.5     .05       0  5039.4     .07       0
  5126.7    .035       0
Bank Sta=5021.5,5039.4
XS Rating Curve= 0 ,0
Exp/Cntr=0.3,0.1

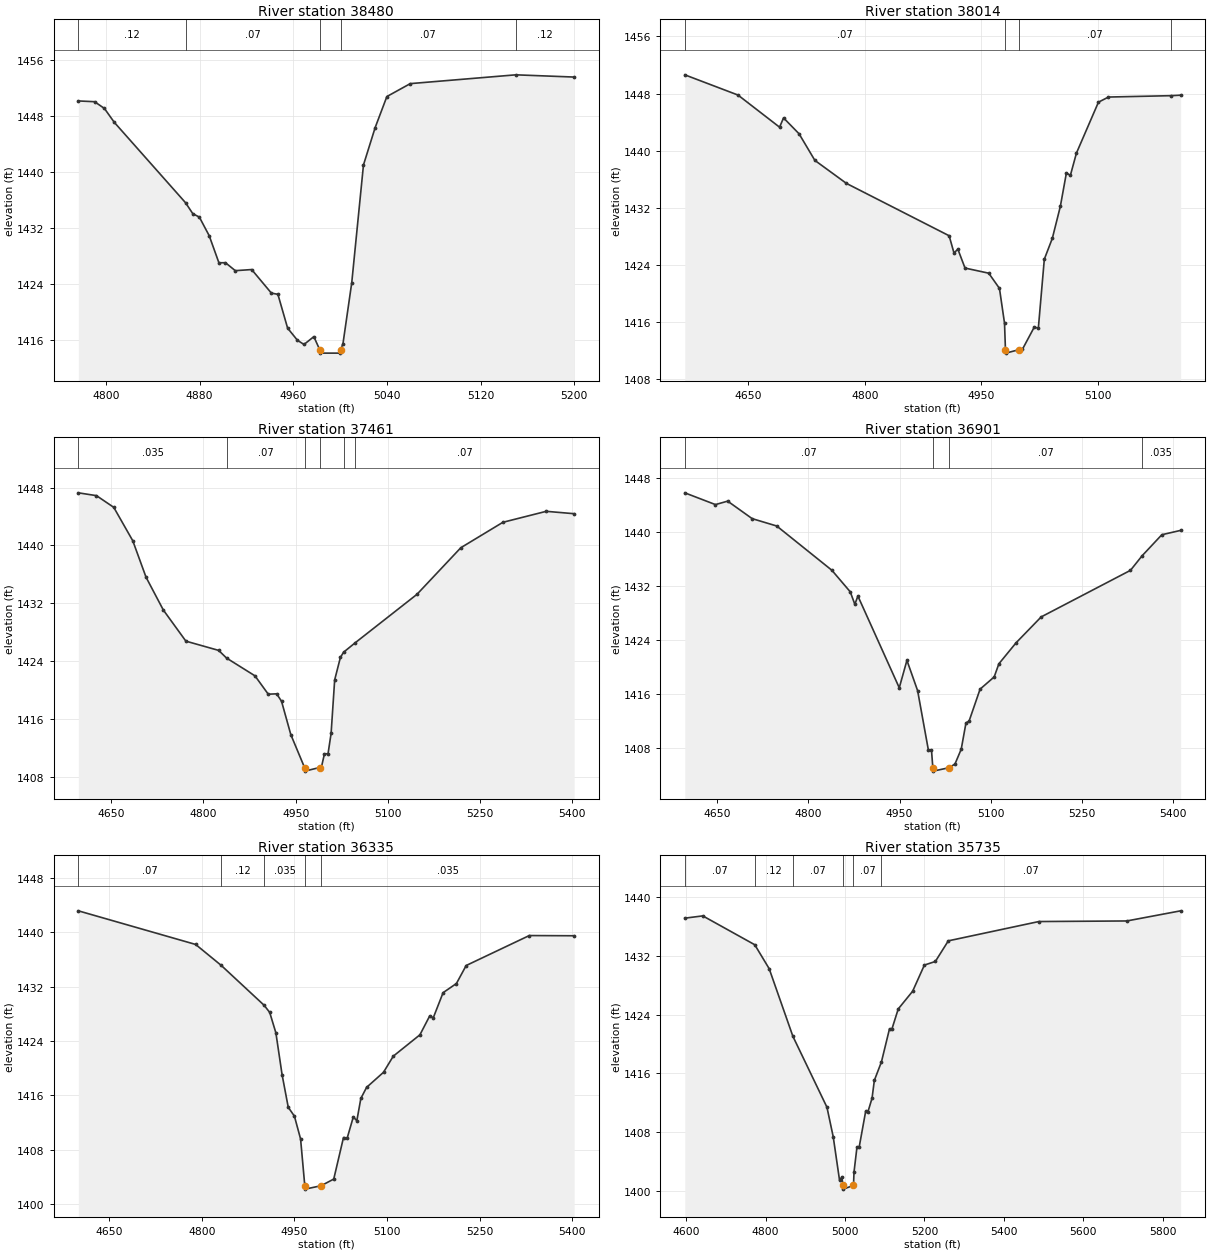
Type RM Length L Ch R = 1 ,38480   ,466,466,466
BEGIN DESCRIPTION:
WEST SISTER CREEK 69.0
END DESCRIPTION:
XS GIS Cut Line= 3
      2050274.96     13930674.98        2050075.       13930575.
      2049874.96       13930575.
#Sta/Elev= 30
  4776.4 1450.18  4790.3 1450.07  4798.7  1449.1  4807.1 1447.12    4868  1435.6
  4874.2 1434.03  4879.8 1433.54  4888.2 1430.88  4896.5    1427  4902.1 1427.01
  4910.5 1425.87  4924.5 1426.03  4941.3 1422.66  4946.9 1422.48  4955.2 1417.64
  4963.6  1415.9  4969.2  1415.3  4977.6 1416.42  4982.6 1414.56  4983.1 1414.06
    5000 1414.06  5000.5 1414.56  5002.5 1415.42    5010 1424.16    5020 1441.01
    5030 1446.37    5040 1450.81    5060 1452.66  5150.2 1453.92    5200  1453.6
#Mann= 5 ,-1 , 0
  4776.4     .12       0    4868     .07       0  4982.6     .05       0
  5000.5     .07       0  5150.2     .12       0
Bank Sta=4982.6,5000.5
XS Rating Curve= 0 ,0
Exp/Cntr=0.3,0.1

Type RM Length L Ch R = 1 ,38014   ,553,553,553
BEGIN DESCRIPTION:
WEST SISTER CREEK 68.0
END DESCRIPTION:
XS GIS Cut Line= 3
      2050549.62     13930201.76        2050125.       13930125.
      2049924.96     13930175.01
#Sta/Elev= 30
  4568.5 1450.63  4636.9  1447.8  4690.4  1443.3  4695.5  1444.6  4715.5 1442.37
  4735.8 1438.65  4776.4 1435.43  4908.5  1428.1  4914.7 1425.69  4919.7 1426.22
  4928.9 1423.58  4959.4 1422.86  4973.2 1420.73  4979.7 1415.87  4980.9 1412.17
  4981.4 1411.67  4998.8 1412.17  5002.6 1412.18    5018 1415.32  5023.2 1415.16
  5030.9 1424.82  5041.2 1427.74  5051.5 1432.21  5059.3  1436.9  5064.4 1436.55
  5072.2 1439.67  5100.5  1446.8  5113.4 1447.52  5193.5 1447.71  5206.2 1447.78
#Mann= 4 ,-1 , 0
  4568.5     .07       0  4980.9    .035       0  4998.8     .07       0
  5193.5     .07       0
Bank Sta=4980.9,4998.8
XS Rating Curve= 0 ,0
Exp/Cntr=0.3,0.1

Type RM Length L Ch R = 1 ,37461   ,560,560,560
BEGIN DESCRIPTION:
WEST SISTER CREEK 67.0
END DESCRIPTION:
XS GIS Cut Line= 3
      2050624.97     13929824.98        2050275.       13929625.
      2049924.99       13929425.
#Sta/Elev= 30
  4596.6 1447.29  4626.1  1446.9  4654.2 1445.28  4685.1 1440.66  4706.7 1435.61
  4734.8 1431.07  4771.5 1426.76  4824.8 1425.48  4837.6 1424.42  4883.8 1421.96
  4905.4 1419.42  4919.1 1419.47    4927 1418.44  4942.1 1413.82  4964.4 1409.27
  4964.9 1408.77  4988.8 1409.27  4991.8  1409.3  4996.8 1411.17  5002.6 1411.17
  5007.6 1413.99  5013.4  1421.4  5022.7  1424.5  5027.9 1425.23    5047 1426.55
  5147.2 1433.24  5218.5 1439.69  5286.9 1443.21  5357.4 1444.73  5402.8  1444.4
#Mann= 6 ,-1 , 0
  4596.6    .035       0  4837.6     .07       0  4964.4     .05       0
  4988.8     .07       0  5027.9     .12       0    5047     .07       0
Bank Sta=4964.4,4988.8
XS Rating Curve= 0 ,0
Exp/Cntr=0.3,0.1

Type RM Length L Ch R = 1 ,36901   ,566,566,566
BEGIN DESCRIPTION:
WEST SISTER CREEK 66.0
END DESCRIPTION:
XS GIS Cut Line= 3
      2051024.99       13929275.        2050625.       13929225.
      2050225.01       13929125.
#Sta/Elev= 30
  4596.9 1445.82  4647.3 1444.08  4667.4 1444.59  4707.7    1442  4748.1 1440.91
  4838.8 1434.36    4869 1431.17  4876.5 1429.33  4881.6 1430.54  4949.6 1416.97
  4962.2 1421.03  4979.8 1416.54  4997.5 1407.75  5002.6 1407.75  5004.8 1405.14
  5005.3 1404.64  5031.2 1405.14  5041.2 1405.69  5051.5 1407.89  5059.3 1411.77
  5064.4 1412.04  5082.5 1416.77  5105.7 1418.58  5113.4 1420.52  5141.7 1423.63
    5183 1427.46  5329.8 1434.35    5349 1436.51  5381.4 1439.62  5412.3 1440.26
#Mann= 4 ,-1 , 0
  4596.9     .07       0  5004.8     .05       0  5031.2     .07       0
    5349    .035       0
Bank Sta=5004.8,5031.2
XS Rating Curve= 0 ,0
Exp/Cntr=0.3,0.1

Type RM Length L Ch R = 1 ,36335   ,600,600,600
BEGIN DESCRIPTION:
WEST SISTER CREEK 65.0
END DESCRIPTION:
XS GIS Cut Line= 3
        2050975.       13928675.        2050575.       13928675.
      2050225.01     13928874.99
#Sta/Elev= 30
  4599.9 1443.17  4789.9 1438.22  4831.3 1435.14  4900.9 1429.26  4909.9 1428.21
  4919.9  1425.2  4929.9 1419.06  4939.9 1414.25  4949.9 1412.94  4959.9 1409.58
  4966.7  1402.7  4967.2  1402.2  4993.1  1402.7  5013.6 1403.68  5029.4  1409.8
  5035.2 1409.66  5045.3 1412.83    5051 1412.27  5057.5 1415.55  5066.8 1417.18
  5094.2  1419.4    5110 1421.77  5153.2 1424.92  5169.1 1427.71  5174.8 1427.42
  5190.7 1431.12  5212.3 1432.47  5228.1 1435.12  5330.3 1439.53    5403  1439.5
#Mann= 5 ,-1 , 0
  4599.9     .07       0  4831.3     .12       0  4900.9    .035       0
  4966.7    .035       0  4993.1    .035       0
Bank Sta=4966.7,4993.1
XS Rating Curve= 0 ,0
Exp/Cntr=0.3,0.1

Type RM Length L Ch R = 1 ,35735   ,600,600,600
BEGIN DESCRIPTION:
WEST SISTER CREEK 64.0
END DESCRIPTION:
XS GIS Cut Line= 3
      2050924.99     13928274.99        2050575.       13928075.
      2049830.54     13928473.92
#Sta/Elev= 30
  4596.9 1437.13  4642.2 1437.44  4772.9 1433.51  4809.2 1430.25  4868.9 1421.03
  4954.6 1411.37  4970.5 1407.31  4986.3 1401.42  4992.1 1401.86  4994.9 1400.71
  4995.4 1400.21  5021.4 1400.71  5022.7 1402.53  5030.1 1405.91  5035.7 1405.93
    5052  1410.8  5057.7 1410.73  5068.1  1412.6  5073.9 1415.03  5091.7 1417.54
  5112.1 1422.07  5117.8 1421.97    5134 1424.76  5170.2 1427.17  5199.8 1430.74
  5227.4 1431.23    5260 1434.04  5487.8 1436.67  5709.2 1436.75  5844.6 1438.13
#Mann= 6 ,-1 , 0
  4596.9     .07       0  4772.9     .12       0  4868.9     .07       0
  4994.9     .05       0  5021.4     .07       0  5091.7     .07       0
Bank Sta=4994.9,5021.4
XS Rating Curve= 0 ,0
Exp/Cntr=0.3,0.1

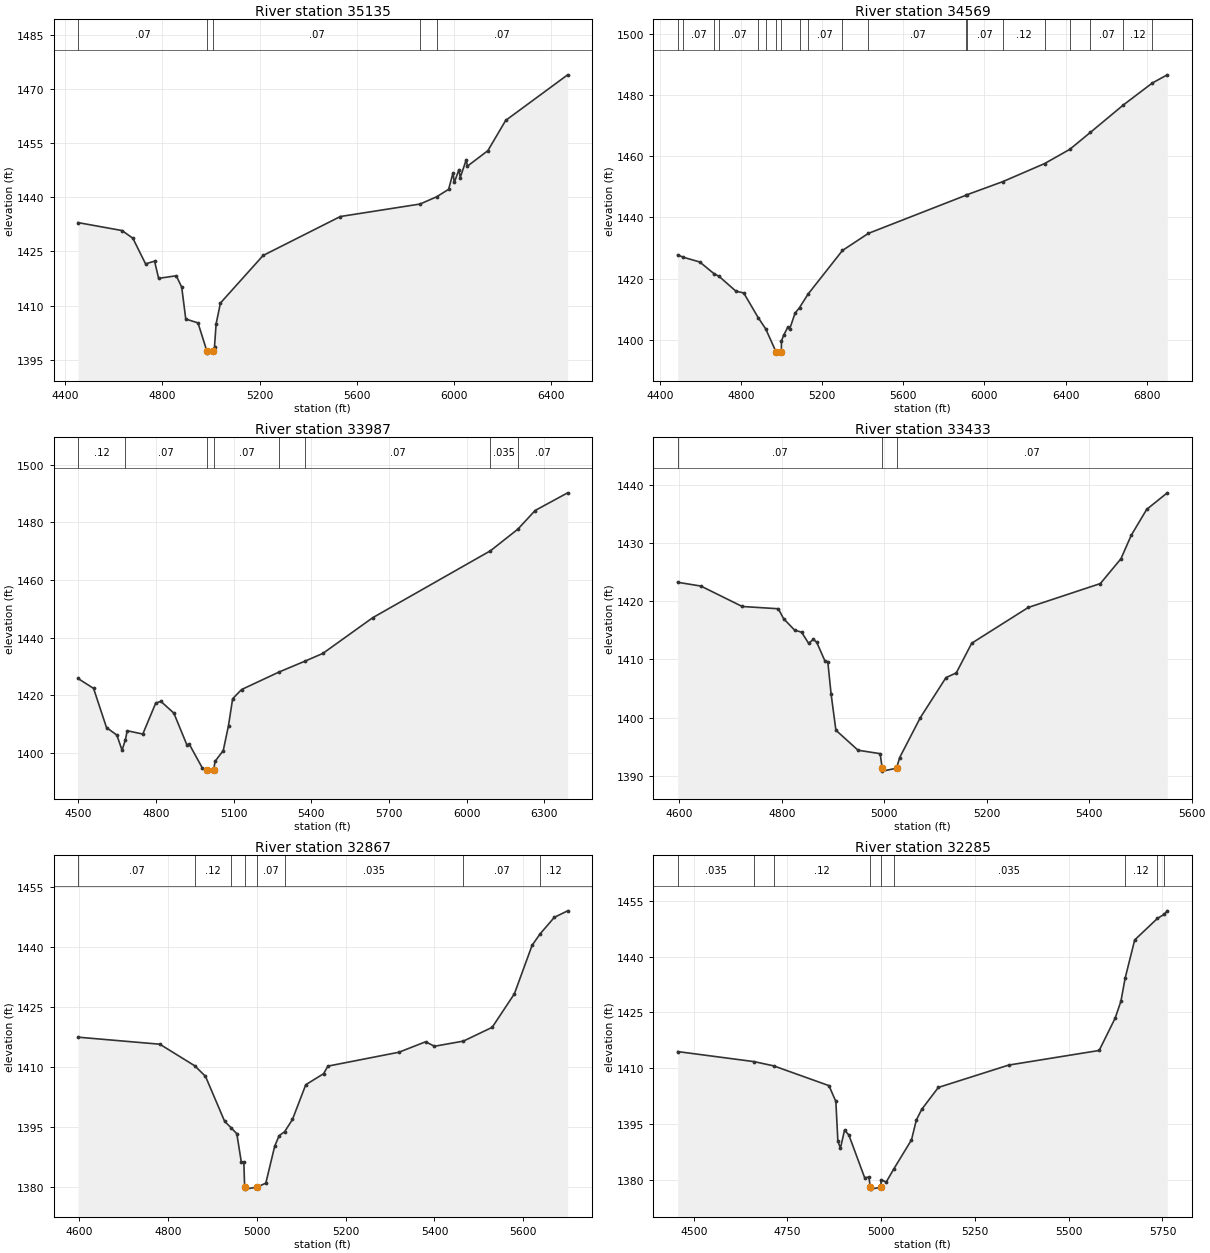
Type RM Length L Ch R = 1 ,35135   ,566,566,566
BEGIN DESCRIPTION:
WEST SISTER CREEK 63.0
END DESCRIPTION:
XS GIS Cut Line= 3
      2051063.17     13927720.41        2050575.       13927475.
      2049209.55      13928011.9
#Sta/Elev= 30
  4453.2 1432.99    4634 1430.79  4678.7 1428.66    4731 1421.57    4768 1422.31
  4784.7 1417.55  4857.3 1418.27  4879.6 1415.12  4896.3 1406.29  4946.6 1405.22
  4983.5 1397.35    4984 1396.85  5010.1 1397.35  5014.5 1398.59  5021.1 1404.93
  5038.9 1410.72  5214.5 1423.89    5532 1434.67    5860 1438.13  5927.9 1440.13
  5977.4  1442.2  5995.3 1446.73  6000.7 1444.09  6019.7 1447.65  6025.1 1445.45
  6049.5 1450.33  6054.8 1448.62  6138.8 1452.91    6212 1461.28  6466.8  1473.9
#Mann= 5 ,-1 , 0
  4453.2     .07       0  4983.5     .05       0  5010.1     .07       0
    5860    .035       0  5927.9     .07       0
Bank Sta=4983.5,5010.1
XS Rating Curve= 0 ,0
Exp/Cntr=0.3,0.1

Type RM Length L Ch R = 1 ,34569   ,582,582,582
BEGIN DESCRIPTION:
WEST SISTER CREEK 62.0
END DESCRIPTION:
XS GIS Cut Line= 3
      2051080.52     13927157.91        2050625.       13926925.
      2048771.57      13927348.9
#Sta/Elev= 30
    4488 1427.73  4515.2 1426.96  4597.1  1425.4  4667.2 1421.58  4692.1 1420.71
    4775 1415.88  4813.6 1415.29  4885.2  1407.2  4922.1 1403.54  4972.2 1396.14
  4972.7 1395.64  4999.1 1396.14  4999.6 1399.58  5009.9 1401.42  5030.4 1404.05
  5040.6 1403.62  5066.6  1408.7  5088.5  1410.5  5130.6 1414.91  5300.1 1429.16
  5427.8 1434.74  5910.6 1447.24  5915.3  1447.4  6090.6 1451.65    6296 1457.53
  6420.5 1462.19  6522.3 1467.74  6684.5 1476.68  6827.9 1483.88  6900.9 1486.52
#Mann= 20 ,-1 , 0
    4488     .07       0  4515.2     .07       0  4667.2    .035       0
  4692.1     .07       0  4885.2    .035       0  4922.1     .07       0
  4972.2     .05       0  4999.1     .07       0  5088.5    .035       0
  5130.6     .07       0  5300.1    .035       0  5427.8     .07       0
  5910.6     .12       0  5915.3     .07       0  6090.6     .12       0
    6296     .07       0  6420.5    .035       0  6522.3     .07       0
  6684.5     .12       0  6827.9     .07       0
Bank Sta=4972.2,4999.1
XS Rating Curve= 0 ,0
Exp/Cntr=0.3,0.1

Type RM Length L Ch R = 1 ,33987   ,554,554,554
BEGIN DESCRIPTION:
WEST SISTER CREEK 61.0
END DESCRIPTION:
XS GIS Cut Line= 3
      2051224.98       13926375.        2050725.       13926375.
      2049351.39      13926161.4
#Sta/Elev= 30
  4499.7 1425.79  4559.7 1422.35  4609.7 1408.74  4649.7 1406.13  4669.7 1400.87
  4682.4 1404.46  4689.7 1407.64  4749.7 1406.49  4799.7 1417.26  4819.7 1417.84
  4869.7 1413.76  4919.7 1402.79  4929.7 1402.88  4979.7  1394.7  4996.2 1394.12
  4996.7 1393.62  5023.4 1394.12  5028.6    1397  5060.4 1400.78  5080.6 1409.45
  5096.6 1418.76  5131.2 1421.96  5276.8 1428.08  5376.1 1431.82    5445  1434.5
  5637.2 1446.89    6092 1470.15  6197.7 1477.65  6264.2 1484.12  6389.8 1490.26
#Mann= 8 ,-1 , 0
  4499.7     .12       0  4682.4     .07       0  4996.2     .05       0
  5023.4     .07       0  5276.8     .12       0  5376.1     .07       0
    6092    .035       0  6197.7     .07       0
Bank Sta=4996.2,5023.4
XS Rating Curve= 0 ,0
Exp/Cntr=0.3,0.1

Type RM Length L Ch R = 1 ,33433   ,566,566,566
BEGIN DESCRIPTION:
WEST SISTER CREEK 60.0
END DESCRIPTION:
XS GIS Cut Line= 3
      2051224.99     13926074.99        2050875.       13925875.
      2050324.97       13925925.
#Sta/Elev= 30
    4597 1423.25  4642.3  1422.6    4723 1419.09  4793.5  1418.7  4803.6 1417.01
  4825.2 1415.03  4838.9 1414.67  4852.5 1412.77  4861.9 1413.44  4868.4 1412.93
  4884.2 1409.77    4890 1409.59  4896.4 1404.05  4905.8 1397.83    4949 1394.39
  4992.2  1393.8  4996.1  1391.3  4996.6  1390.8  5024.1  1391.3  5030.2 1393.13
  5070.4 1399.97  5120.6 1406.87  5140.7 1407.68  5170.8 1412.78  5281.3 1418.93
  5421.8 1423.03    5462 1427.29  5482.1 1431.33  5512.2 1435.77  5552.4 1438.62
#Mann= 3 ,-1 , 0
    4597     .07       0  4996.1     .05       0  5024.1     .07       0
Bank Sta=4996.1,5024.1
XS Rating Curve= 0 ,0
Exp/Cntr=0.3,0.1

Type RM Length L Ch R = 1 ,32867   ,582,582,582
BEGIN DESCRIPTION:
WEST SISTER CREEK 59.0
END DESCRIPTION:
XS GIS Cut Line= 3
        2051175.       13925525.        2050825.       13925325.
      2050125.01       13925325.
#Sta/Elev= 30
  4596.9 1417.42  4781.2 1415.66    4860 1410.26  4884.1 1407.63  4927.3 1396.37
  4941.3 1394.84  4954.7 1393.28  4964.7 1386.27  4970.5 1386.16  4972.3 1379.95
  4972.8 1379.45  5000.4 1379.95    5020 1380.95    5040 1390.17    5050 1392.81
  5062.4  1393.8    5080 1396.85    5110 1405.54    5150 1408.28    5160 1410.19
    5320 1413.66    5380 1416.27    5400 1415.15  5465.2 1416.44    5530 1419.88
    5580 1428.25    5620 1440.39  5638.2 1443.26    5670 1447.36    5700 1448.99
#Mann= 8 ,-1 , 0
  4596.9     .07       0    4860     .12       0  4941.3     .07       0
  4972.3     .05       0  5000.4     .07       0  5062.4    .035       0
  5465.2     .07       0  5638.2     .12       0
Bank Sta=4972.3,5000.4
XS Rating Curve= 0 ,0
Exp/Cntr=0.3,0.1

Type RM Length L Ch R = 1 ,32285   ,551,551,551
BEGIN DESCRIPTION:
WEST SISTER CREEK 58.0
END DESCRIPTION:
XS GIS Cut Line= 3
      2051225.52     13924984.32        2050725.       13924775.
      2050075.04     13925174.98
#Sta/Elev= 30
  4457.1 1414.48  4661.3 1411.77  4713.3 1410.63  4860.6 1405.31    4879 1401.05
  4884.4 1390.33  4891.2 1388.48  4902.1 1393.32  4913.6 1392.04  4955.8 1380.53
  4967.1  1380.7  4970.9 1377.96  4971.4 1377.46  4999.1 1377.96  4999.6    1380
  5013.2 1379.35  5033.3 1382.86  5080.7 1390.72  5093.6 1396.05  5107.9 1398.92
  5152.3 1404.83  5340.1 1410.85  5581.2 1414.78  5623.8 1423.48  5639.2 1428.02
  5650.4 1434.22  5675.9 1444.52  5736.6 1450.32  5755.1 1451.45  5762.8 1452.36
#Mann= 9 ,-1 , 0
  4457.1    .035       0  4661.3     .07       0  4713.3     .12       0
  4970.9     .05       0  4999.1     .12       0  5033.3    .035       0
  5650.4     .12       0  5736.6    .035       0  5755.1     .07       0
Bank Sta=4970.9,4999.1
XS Rating Curve= 0 ,0
Exp/Cntr=0.3,0.1

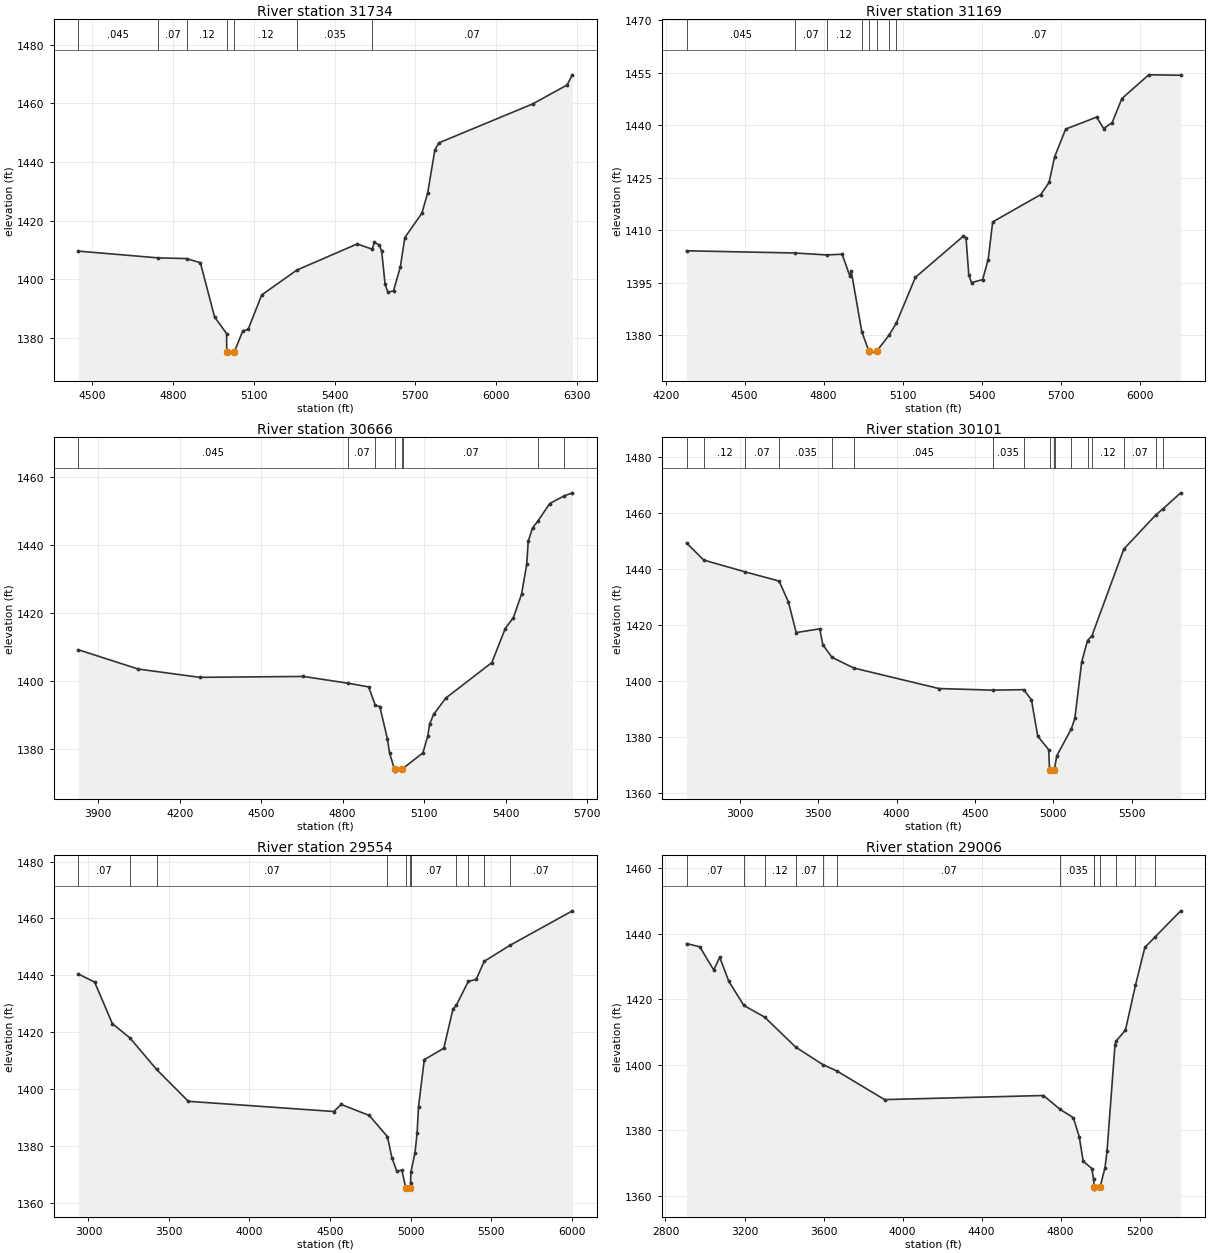
Type RM Length L Ch R = 1 ,31734   ,565,565,565
BEGIN DESCRIPTION:
WEST SISTER CREEK 57.0
END DESCRIPTION:
XS GIS Cut Line= 4
      2051096.03     13924103.03        2050575.       13924275.
      2050127.25     13924393.41      2049342.37     13924646.49
#Sta/Elev= 30
  4447.1 1409.55  4744.7 1407.24  4849.6    1407    4901 1405.59  4953.7  1387.1
  4998.4 1381.38    4999 1375.22  4999.5 1374.72  5027.7 1375.22  5058.7 1382.34
  5078.5 1382.81  5128.9 1394.58  5259.6 1403.08    5484    1412  5539.4 1410.21
  5548.1 1412.62  5566.4 1411.52  5574.9  1409.5  5587.4 1398.34  5597.9  1395.5
  5618.9 1396.01  5644.2 1404.14  5660.9 1414.19    5724 1422.45  5745.7 1429.34
  5772.5 1444.08    5787  1446.5  6135.5 1459.78  6263.8 1466.26  6283.6 1469.74
#Mann= 7 ,-1 , 0
  4447.1    .045       0  4744.7     .07       0  4849.6     .12       0
    4999     .05       0  5027.7     .12       0  5259.6    .035       0
  5539.4     .07       0
Bank Sta=4999,5027.7
XS Rating Curve= 0 ,0
Exp/Cntr=0.3,0.1

Type RM Length L Ch R = 1 ,31169   ,503,503,503
BEGIN DESCRIPTION:
WEST SISTER CREEK 56.0
END DESCRIPTION:
XS GIS Cut Line= 3
      2051077.57     13923596.63        2050375.       13923775.
      2049279.43     13924129.31
#Sta/Elev= 30
  4279.4 1404.12  4690.6 1403.49  4812.1 1402.93  4870.1 1403.15  4899.3 1396.93
  4904.5 1398.38  4944.7 1381.04  4971.9  1375.4  4972.4  1374.9  5000.8  1375.4
  5048.2 1380.03  5075.6 1383.44  5148.3 1396.54  5330.1 1408.28  5340.4 1407.87
  5351.1 1397.15  5361.6 1395.02  5403.6 1395.91  5424.7 1401.63  5441.7 1412.36
  5624.3 1420.17  5655.9 1423.64  5676.9 1430.95  5718.9 1438.87  5836.4 1442.28
  5863.1 1439.03  5895.2 1440.69  5932.4 1447.59  6034.2 1454.36  6155.7 1454.24
#Mann= 8 ,-1 , 0
  4279.4    .045       0  4690.6     .07       0  4812.1     .12       0
  4944.7     .07       0  4971.9     .05       0  5000.8     .07       0
  5048.2    .035       0  5075.6     .07       0
Bank Sta=4971.9,5000.8
XS Rating Curve= 0 ,0
Exp/Cntr=0.3,0.1

Type RM Length L Ch R = 1 ,30666   ,565,565,565
BEGIN DESCRIPTION:
WEST SISTER CREEK 55.0
END DESCRIPTION:
XS GIS Cut Line= 3
      2051409.43     13923039.84        2050275.       13923325.
      2049668.15     13923558.37
#Sta/Elev= 30
  3826.1 1409.16  4047.2 1403.47  4273.4 1401.04  4655.6  1401.3  4817.9 1399.33
  4895.6 1398.23  4920.3 1392.78  4936.7 1392.45  4964.9  1382.9  4972.7 1378.78
    4991 1373.95  4991.5 1373.45  5019.9 1373.95  5023.9 1374.36  5095.5 1378.83
  5113.7 1383.85  5120.1 1387.28  5135.1 1390.16  5180.1 1394.96  5349.4 1405.38
  5398.7 1415.39  5428.7 1418.61  5458.7 1425.48  5477.9 1434.29  5483.3 1441.04
  5499.4    1445  5518.8 1446.98  5562.6 1452.17  5614.8 1454.38    5646 1455.31
#Mann= 8 ,-1 , 0
  3826.1    .045       0  4817.9     .07       0  4920.3    .035       0
    4991    .035       0  5019.9    .035       0  5023.9     .07       0
  5518.8    .035       0  5614.8     .07       0
Bank Sta=4991,5019.9
XS Rating Curve= 0 ,0
Exp/Cntr=0.3,0.1

Type RM Length L Ch R = 1 ,30101   ,547,547,547
BEGIN DESCRIPTION:
WEST SISTER CREEK 54.0
END DESCRIPTION:
XS GIS Cut Line= 3
      2052414.03     13922840.83        2050075.       13922825.
      2049303.64     13923078.08
#Sta/Elev= 30
  2660.9 1449.24    2770 1443.15  3036.3 1438.89  3250.8 1435.63  3309.9 1428.22
  3359.9 1417.21  3509.9 1418.54  3529.9 1412.83  3588.1 1408.36  3726.2 1404.54
    4270 1397.19  4613.2 1396.62  4810.4 1396.79    4860 1393.19    4900 1380.17
    4970 1375.32  4975.5 1368.15    4976 1367.65  5004.4 1368.15    5008 1368.76
  5021.2 1373.13  5112.8 1382.56  5136.8 1386.48  5180.3 1406.69  5217.6 1414.37
  5245.1 1415.98  5449.2 1447.09    5653 1459.28  5700.1 1461.52  5811.8 1467.19
#Mann= 17 ,-1 , 0
  2660.9     .07       0    2770     .12       0  3036.3     .07       0
  3250.8    .035       0  3588.1     .07       0  3726.2    .045       0
  4613.2    .035       0  4810.4     .07       0  4975.5     .05       0
  5004.4     .07       0    5008     .12       0  5112.8    .035       0
  5217.6     .07       0  5245.1     .12       0  5449.2     .07       0
    5653     .12       0  5700.1     .07       0
Bank Sta=4975.5,5004.4
XS Rating Curve= 0 ,0
Exp/Cntr=0.3,0.1

Type RM Length L Ch R = 1 ,29554   ,548,548,548
BEGIN DESCRIPTION:
WEST SISTER CREEK 53.0
END DESCRIPTION:
XS GIS Cut Line= 3
      2051986.42     13922492.13        2049925.       13922325.
      2049032.84     13921872.35
#Sta/Elev= 30
  2936.6 1440.53  3038.3 1437.67  3148.7 1423.05  3257.6 1418.05    3423 1406.99
  3620.3  1395.8  4523.2 1392.22    4570 1394.69  4743.9 1390.82  4856.7 1383.39
  4884.4 1375.98  4914.5 1371.32  4946.3  1371.6  4970.2 1365.46  4970.7 1364.96
  4999.2 1365.46  5000.1 1367.03  5002.3 1370.86  5027.2 1377.55    5041 1384.61
  5049.6 1393.85  5085.5 1410.43  5206.6 1414.42  5263.6 1428.15  5284.8 1429.55
  5358.3 1437.88  5408.3 1438.64  5457.5 1444.95  5617.7 1450.58  6005.2 1462.69
#Mann= 11 ,-1 , 0
  2936.6     .07       0  3257.6     .12       0    3423     .07       0
  4856.7     .12       0  4970.2     .05       0  4999.2     .12       0
  5000.1     .07       0  5284.8     .12       0  5358.3     .07       0
  5457.5     .12       0  5617.7     .07       0
Bank Sta=4970.2,4999.2
XS Rating Curve= 0 ,0
Exp/Cntr=0.3,0.1

Type RM Length L Ch R = 1 ,29006   ,530,530,530
BEGIN DESCRIPTION:
WEST SISTER CREEK 52.0
END DESCRIPTION:
XS GIS Cut Line= 3
      2052161.82     13922042.12        2050075.       13921825.
        2049675.       13921775.
#Sta/Elev= 30
  2906.7 1436.94  2973.9 1435.94  3044.3 1428.87  3074.4 1432.79  3120.1 1425.47
  3196.5 1418.08  3301.7 1414.53  3458.8 1405.39  3596.5 1400.04  3667.2 1398.11
  3908.9 1389.37  4713.2 1390.62  4797.8 1386.38  4864.4 1383.85  4894.2 1378.08
  4914.3  1370.6    4958 1368.36  4966.6 1365.15  4970.2 1362.58  4970.7 1362.08
  4999.2 1362.58  5024.9 1368.67    5035 1373.74  5075.3 1406.07    5080 1407.14
  5128.2 1410.57    5179 1424.26  5226.5 1435.77  5277.9 1438.94  5407.9 1446.92
#Mann= 13 ,-1 , 0
  2906.7     .07       0  3196.5    .035       0  3301.7     .12       0
  3458.8     .07       0  3596.5     .12       0  3667.2     .07       0
  4797.8    .035       0  4966.6     .07       0  4970.2     .05       0
  4999.2     .07       0    5080    .035       0    5179     .07       0
  5277.9     .12       0
Bank Sta=4970.2,4999.2
XS Rating Curve= 0 ,0
Exp/Cntr=0.3,0.1

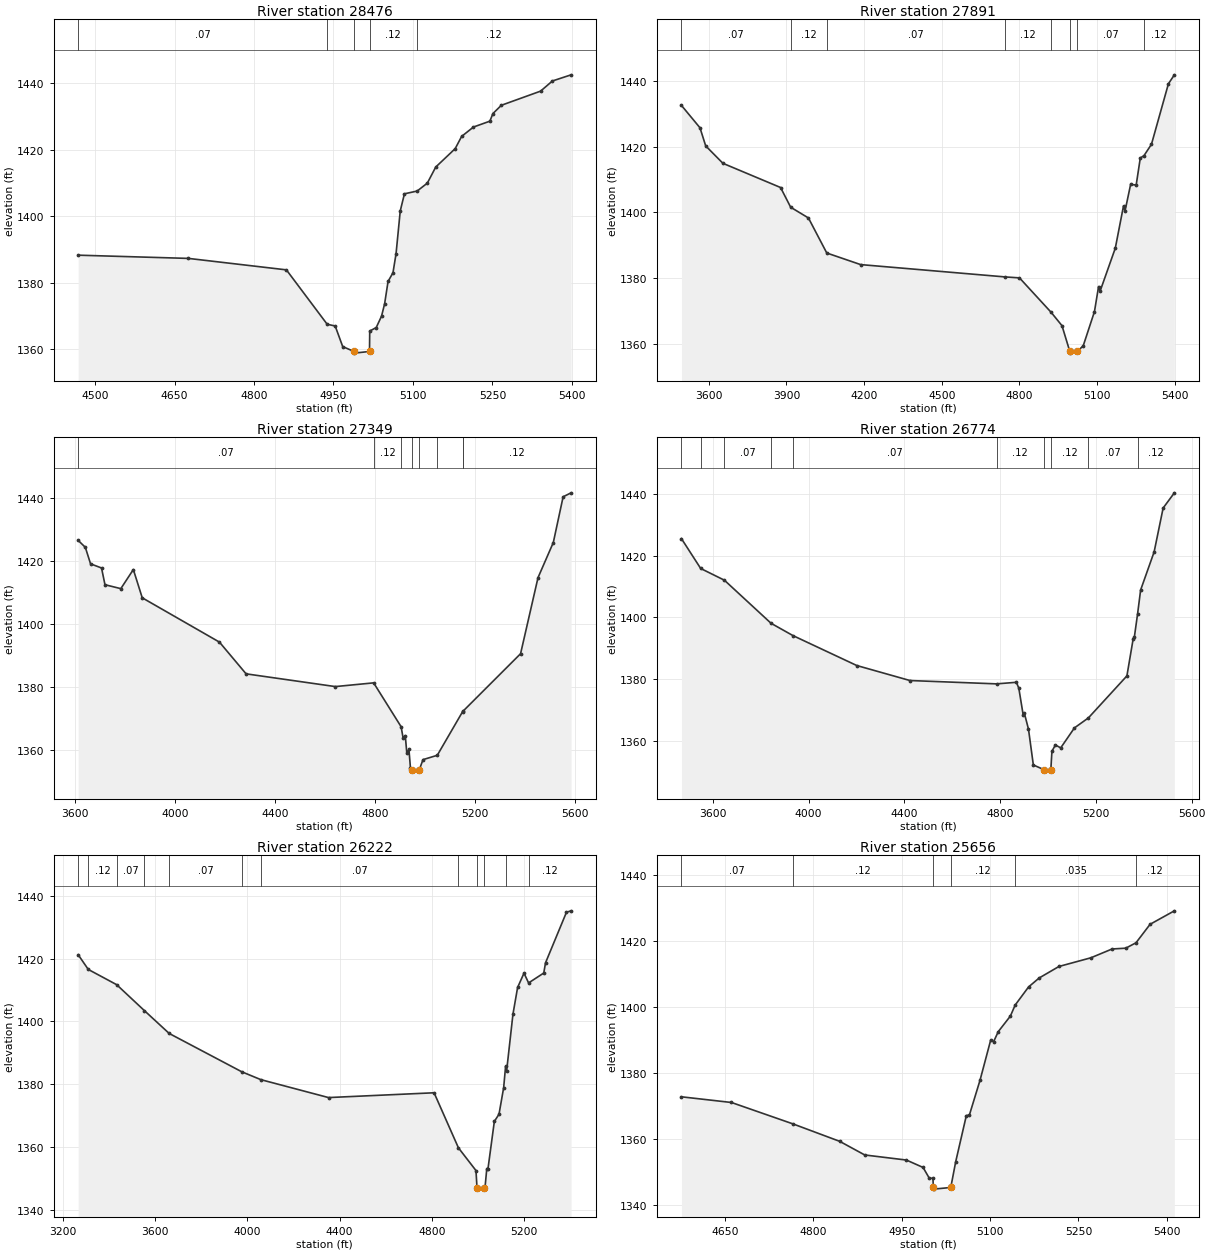
Type RM Length L Ch R = 1 ,28476   ,585,585,585
BEGIN DESCRIPTION:
WEST SISTER CREEK 51.0
END DESCRIPTION:
XS GIS Cut Line= 3
      2050673.43     13921770.76        2050325.       13921375.
        2049975.       13921175.
#Sta/Elev= 30
  4468.1  1388.3  4676.2 1387.33  4861.1 1383.89  4938.1 1367.55  4953.2 1367.03
  4967.4 1360.84  4988.7 1359.38  4989.2 1358.88    5018 1359.38  5018.4 1365.51
  5030.7 1366.57  5040.7 1369.99  5046.5 1373.69    5053 1380.41  5062.3 1383.03
  5068.1 1388.76    5076 1401.59  5083.9 1406.73    5108 1407.57  5127.1 1409.94
    5143 1414.77  5179.7  1420.3  5191.9 1423.98  5214.2 1426.79  5245.2 1428.55
  5250.9 1430.83  5266.8 1433.32  5340.9 1437.57  5363.2 1440.62  5398.5 1442.47
#Mann= 5 ,-1 , 0
  4468.1     .07       0  4938.1     .12       0  4988.7     .05       0
    5018     .12       0    5108     .12       0
Bank Sta=4988.7,5018
XS Rating Curve= 0 ,0
Exp/Cntr=0.3,0.1

Type RM Length L Ch R = 1 ,27891   ,542,542,542
BEGIN DESCRIPTION:
WEST SISTER CREEK 50.0
END DESCRIPTION:
XS GIS Cut Line= 3
      2052029.55     13921573.37        2050675.       13920925.
      2050325.03     13920725.02
#Sta/Elev= 30
  3494.3 1432.59  3565.9 1425.77    3588 1420.25  3654.6 1414.94  3877.3 1407.57
  3916.4 1401.56    3985 1398.29  4055.9 1387.61  4186.7 1384.08  4745.4 1380.32
  4800.6 1380.03  4922.6 1369.56  4964.8 1365.47  4995.1  1357.6  4995.6  1357.1
  5024.4  1357.6  5047.1 1359.38  5090.3 1369.75  5106.2 1377.39  5111.9 1375.93
  5170.9  1389.1  5202.6 1401.99  5208.4 1400.39    5230 1408.49  5251.6 1408.34
  5267.4 1416.55  5281.9 1417.31  5310.6 1420.74  5376.1 1439.18  5399.1 1441.91
#Mann= 8 ,-1 , 0
  3494.3     .07       0  3916.4     .12       0  4055.9     .07       0
  4745.4     .12       0  4922.6     .07       0  4995.1     .05       0
  5024.4     .07       0  5281.9     .12       0
Bank Sta=4995.1,5024.4
XS Rating Curve= 0 ,0
Exp/Cntr=0.3,0.1

Type RM Length L Ch R = 1 ,27349   ,575,575,575
BEGIN DESCRIPTION:
WEST SISTER CREEK 49.0
END DESCRIPTION:
XS GIS Cut Line= 3
       2052091.3     13921348.27        2050975.       13920525.
      2050424.98     13920324.99
#Sta/Elev= 30
    3612 1426.59  3640.6 1424.39  3661.5 1419.16  3705.4 1417.85  3719.2 1412.54
  3782.6  1411.3  3832.7 1417.35  3868.3 1408.39  4177.3 1394.34  4283.8 1384.29
  4640.9 1380.25  4794.2 1381.43  4904.1 1367.53  4912.3 1363.88  4920.8 1364.71
    4927 1359.09  4935.4 1360.35  4941.6 1354.33  4947.8 1353.95  4948.3 1353.45
  4977.2 1353.95  4991.7 1357.09  5048.8 1358.47  5150.5 1372.34  5152.9 1372.53
  5382.1 1390.67  5451.9 1414.78  5513.1 1425.91  5552.4 1440.42  5584.3 1441.67
#Mann= 8 ,-1 , 0
    3612     .07       0  4794.2     .12       0  4904.1     .07       0
  4947.8     .05       0  4977.2     .07       0  5048.8     .12       0
  5150.5     .07       0  5152.9     .12       0
Bank Sta=4947.8,4977.2
XS Rating Curve= 0 ,0
Exp/Cntr=0.3,0.1

Type RM Length L Ch R = 1 ,26774   ,552,552,552
BEGIN DESCRIPTION:
WEST SISTER CREEK 48.0
END DESCRIPTION:
XS GIS Cut Line= 3
      2052589.86      13920362.2      2051074.49     13920145.78
      2050575.02     13919975.01
#Sta/Elev= 30
  3469.2 1425.53  3549.5 1415.87  3648.6 1412.07  3843.3 1398.13  3934.9 1394.14
  4201.4 1384.45  4423.6 1379.59  4785.4 1378.51  4868.1 1379.02  4878.2 1377.09
  4896.4 1368.45  4901.4 1368.98  4918.6 1363.83  4938.8 1352.26  4982.4 1350.76
  4982.9 1350.26  5011.9 1350.76  5016.5 1356.73  5031.1 1358.72  5053.1 1357.79
  5110.5 1364.26  5168.6 1367.48  5329.6 1381.09  5355.6 1393.01  5360.9 1393.76
  5374.1 1401.11  5386.9  1408.9  5443.3 1421.24  5480.9 1435.44  5527.8 1440.36
#Mann= 10 ,-1 , 0
  3469.2     .07       0  3549.5     .12       0  3648.6     .07       0
  3843.3    .035       0  3934.9     .07       0  4785.4     .12       0
  4982.4     .05       0  5011.9     .12       0  5168.6     .07       0
  5374.1     .12       0
Bank Sta=4982.4,5011.9
XS Rating Curve= 0 ,0
Exp/Cntr=0.3,0.1

Type RM Length L Ch R = 1 ,26222   ,566,566,566
BEGIN DESCRIPTION:
WEST SISTER CREEK 47.0
END DESCRIPTION:
XS GIS Cut Line= 3
      2052568.47     13920305.77        2050975.       13919625.
      2050575.01       13919675.
#Sta/Elev= 30
  3267.2  1421.2    3311 1416.53  3433.8  1411.7  3554.3 1403.44  3661.6  1396.2
    3976 1384.03  4058.8 1381.53  4351.9 1375.84  4809.4 1377.36  4914.9 1359.87
  4990.9 1352.66  4995.3 1347.26  4995.8 1346.76  5024.8 1347.26  5030.2 1347.37
  5037.8  1353.3  5042.8 1353.17  5070.5 1368.27  5090.7 1370.55  5110.9 1379.01
  5119.2 1385.73  5123.4 1384.12  5151.2 1402.35  5171.3 1410.81    5199 1415.36
  5218.9 1412.25  5284.7  1415.4  5292.3 1418.65    5383  1434.7  5403.1 1435.15
#Mann= 12 ,-1 , 0
  3267.2     .07       0    3311     .12       0  3433.8     .07       0
  3554.3    .035       0  3661.6     .07       0    3976    .035       0
  4058.8     .07       0  4914.9     .12       0  4995.3     .05       0
  5024.8     .12       0  5119.2    .035       0  5218.9     .12       0
Bank Sta=4995.3,5024.8
XS Rating Curve= 0 ,0
Exp/Cntr=0.3,0.1

Type RM Length L Ch R = 1 ,25656   ,582,582,582
BEGIN DESCRIPTION:
WEST SISTER CREEK 46.0
END DESCRIPTION:
XS GIS Cut Line= 3
      2051325.01     13919375.01        2051025.       13919075.
      2050624.98       13919175.
#Sta/Elev= 30
  4576.3  1372.9  4661.2 1371.18    4765 1364.73    4845  1359.4  4887.4 1355.28
  4958.1 1353.74  4986.4  1351.5    4997 1348.22  5003.1 1348.22  5003.9 1345.43
  5004.4 1344.93  5033.4 1345.43  5041.8 1353.26  5059.8  1367.2    5065 1367.38
    5083 1377.89  5101.1 1390.05  5106.2 1389.63    5114 1392.64  5134.6 1397.37
  5142.7  1400.7  5165.5  1406.2  5183.5 1408.91    5217 1412.39  5271.2 1415.02
  5307.2 1417.69  5330.4 1417.93  5347.8 1419.57  5371.7 1425.17  5412.9 1429.25
#Mann= 6 ,-1 , 0
  4576.3     .07       0    4765     .12       0  5003.9     .05       0
  5033.4     .12       0  5142.7    .035       0  5347.8     .12       0
Bank Sta=5003.9,5033.4
XS Rating Curve= 0 ,0
Exp/Cntr=0.3,0.1