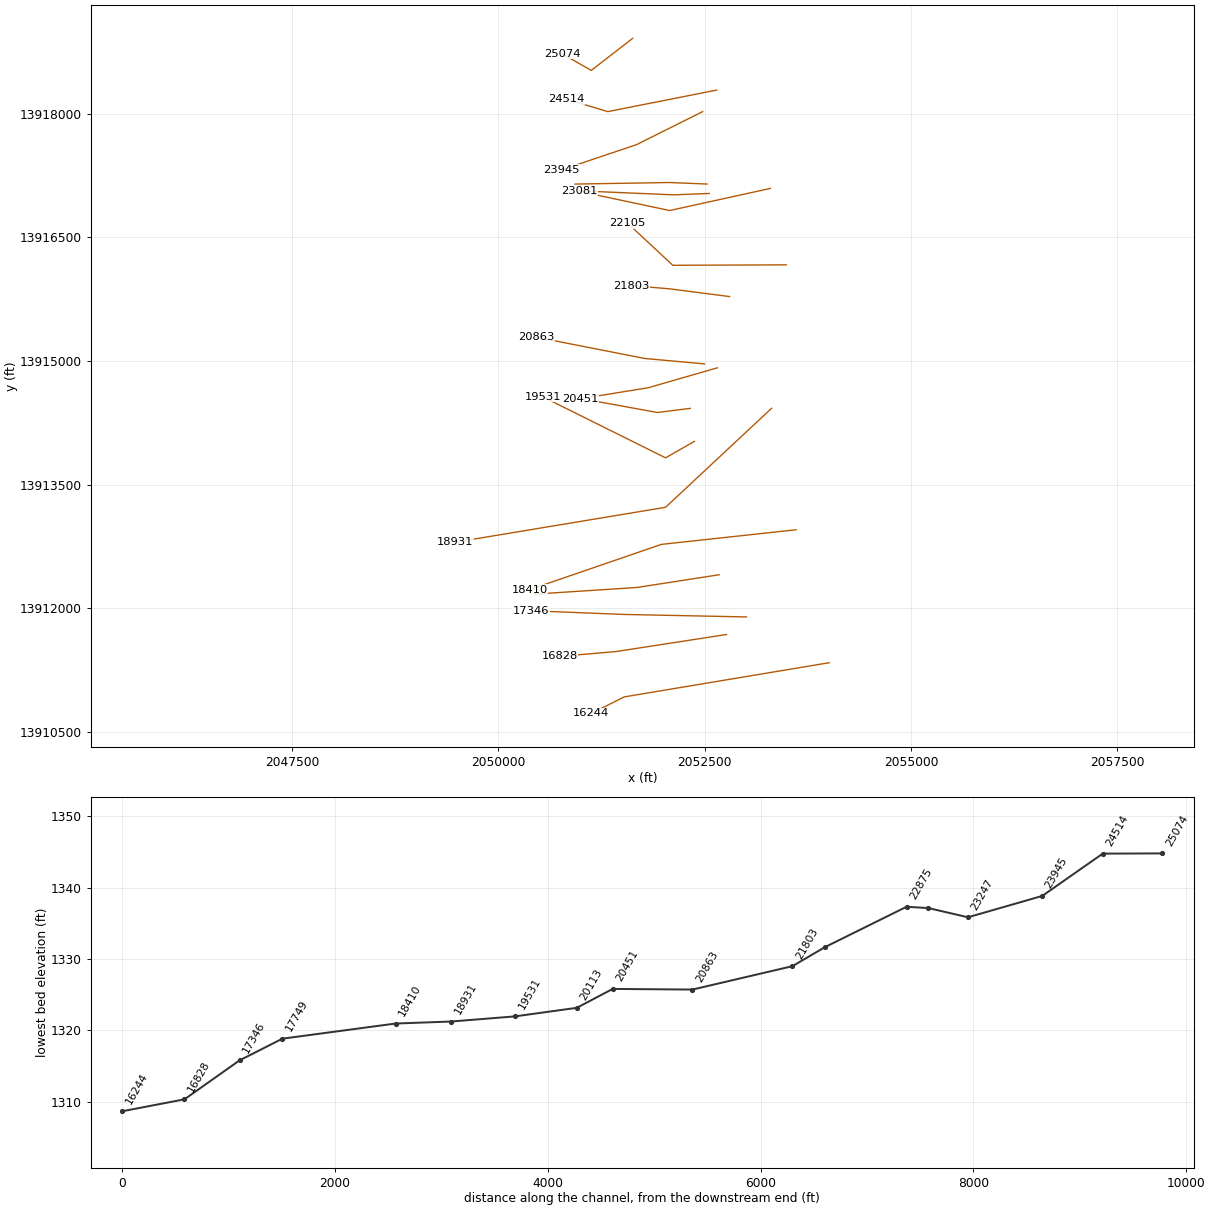
HEC-RAS study WEST SISTER CREEK.prj: WEST SISTER CREEK Base Level Engineering

--- WEST SISTER CREEK.g01 (geometry) --- (continued)

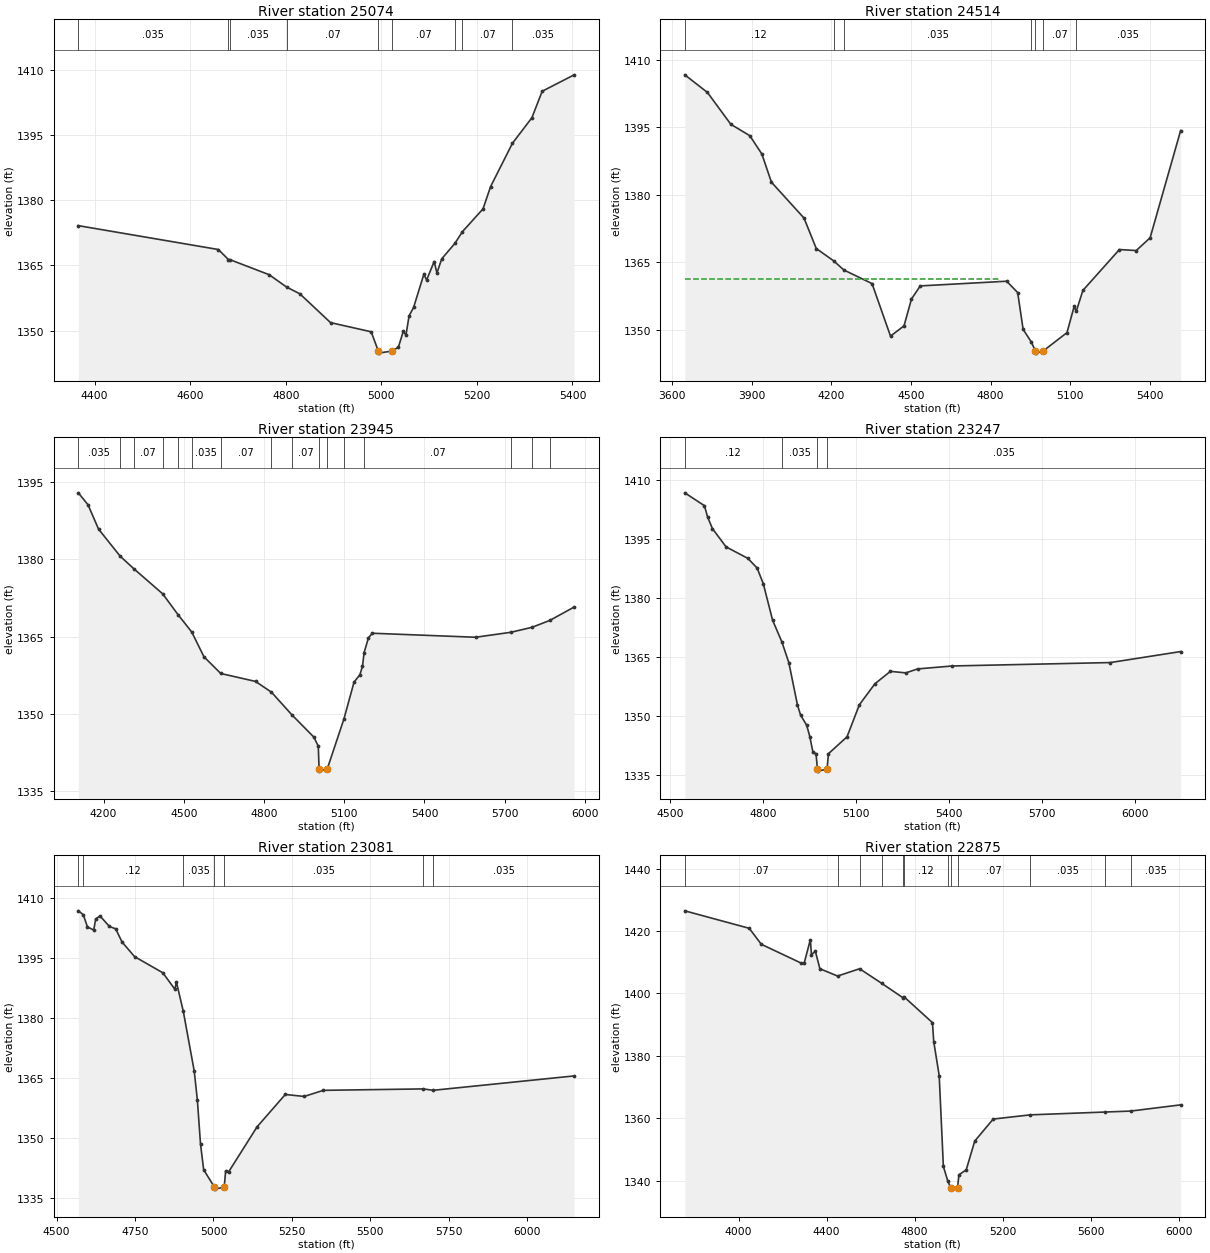
Type RM Length L Ch R = 1 ,25074   ,560,560,560
BEGIN DESCRIPTION:
WEST SISTER CREEK 45.0
END DESCRIPTION:
XS GIS Cut Line= 3
      2051626.54     13918913.98        2051125.       13918525.
      2050775.02     13918724.99
#Sta/Elev= 30
  4365.8 1374.14  4658.8 1368.65  4680.1 1366.33  4682.8 1366.33  4765.1 1362.86
  4801.9    1360  4829.4 1358.46  4893.7 1351.83  4978.8 1349.72  4993.6 1345.31
  4994.1 1344.81  5023.3 1345.31  5035.8 1346.21  5045.9  1349.8  5051.6 1348.99
  5058.1 1353.39  5067.5 1355.31    5089 1362.95  5094.8 1361.64  5110.6 1365.88
  5116.4 1363.25  5126.5 1366.52  5153.9 1370.05  5169.8 1372.76  5212.9 1378.01
  5228.7 1383.13  5274.4 1393.09  5315.1 1398.96  5336.7 1405.06  5403.6 1408.84
#Mann= 9 ,-1 , 0
  4365.8    .035       0  4680.1     .07       0  4682.8    .035       0
  4801.9     .07       0  4993.6     .05       0  5023.3     .07       0
  5153.9     .12       0  5169.8     .07       0  5274.4    .035       0
Bank Sta=4993.6,5023.3
XS Rating Curve= 0 ,0
Exp/Cntr=0.3,0.1

Type RM Length L Ch R = 1 ,24514   ,569,569,569
BEGIN DESCRIPTION:
WEST SISTER CREEK 44.0
END DESCRIPTION:
XS GIS Cut Line= 3
      2052645.13      13918286.3        2051325.       13918025.
      2050824.96     13918175.01
#Sta/Elev= 30
  3648.1 1406.71  3733.5 1402.78  3821.5  1395.7  3892.9 1393.17  3938.4 1389.09
  3974.4 1382.82  4097.2 1374.83  4143.4 1368.06  4208.7 1365.32  4247.3 1363.28
  4353.4 1360.26    4423 1348.57  4473.9 1350.84    4502 1356.82  4535.1 1359.74
  4860.7 1360.78  4902.1 1358.25  4922.5 1350.09  4953.2 1347.27  4968.8 1345.28
  4969.3 1344.78  4998.5 1345.28  5087.8 1349.34  5114.8 1355.17  5122.7 1354.07
  5147.8 1358.74  5285.3 1367.83  5348.8 1367.61    5401 1370.45  5515.9  1394.3
#Mann= 7 ,-1 , 0
  3648.1     .12       0  4208.7     .07       0  4247.3    .035       0
  4953.2     .07       0  4968.8     .05       0  4998.5     .07       0
  5122.7    .035       0
#XS Ineff= 2 , 0
       0 4830.53  1361.2               0
Permanent Ineff=
       F       F
Bank Sta=4968.8,4998.5
XS Rating Curve= 0 ,0
Exp/Cntr=0.3,0.1

Type RM Length L Ch R = 1 ,23945   ,698,698,698
BEGIN DESCRIPTION:
WEST SISTER CREEK 43.0
END DESCRIPTION:
XS GIS Cut Line= 3
        2052475.       13918025.        2051675.       13917625.
      2050765.95     13917318.67
#Sta/Elev= 30
  4105.9 1392.92  4142.2 1390.59  4181.4 1385.88  4262.3 1380.61  4312.8  1378.2
  4421.4 1373.29  4478.9 1369.23  4529.9 1365.88  4575.5 1361.07  4638.4 1357.82
  4768.3 1356.28  4827.9 1354.19  4903.9 1349.81  4986.4 1345.46    5003  1343.7
  5005.9 1339.35  5006.4 1338.85    5037 1339.35  5098.9 1348.99  5136.7 1356.15
  5158.6 1357.58  5168.2 1359.22  5174.3 1361.87  5190.3 1364.72    5205 1365.64
  5591.3 1364.86  5722.2 1365.82  5801.4 1366.78  5868.6 1368.13  5959.6 1370.73
#Mann= 16 ,-1 , 0
  4105.9    .035       0  4262.3     .12       0  4312.8     .07       0
  4421.4    .035       0  4478.9     .07       0  4529.9    .035       0
  4638.4     .07       0  4827.9    .035       0  4903.9     .07       0
  5005.9     .05       0    5037     .07       0  5098.9    .035       0
  5174.3     .07       0  5722.2    .035       0  5801.4     .07       0
  5868.6    .035       0
Bank Sta=5005.9,5037
XS Rating Curve= 0 ,0
Exp/Cntr=0.3,0.1

Type RM Length L Ch R = 1 ,23247   ,372,372,372
BEGIN DESCRIPTION:
WEST SISTER CREEK 42.0
END DESCRIPTION:
XS GIS Cut Line= 3
      2052528.31      13917146.3      2052074.89     13917164.95
      2050928.15     13917146.05
#Sta/Elev= 30
  4546.2 1406.76  4609.6 1403.48  4619.6 1400.65  4635.3 1397.66  4679.6 1392.98
  4749.7 1390.07  4779.7  1387.6  4799.7 1383.58  4829.7 1374.29  4859.4 1368.83
  4882.1 1363.49  4909.8 1352.76  4919.8 1350.18  4939.8 1347.52  4949.8 1344.65
  4959.9 1340.67  4969.9 1340.32  4974.3 1336.36  4974.8 1335.86  5005.4 1336.36
  5009.9  1340.3  5069.9  1344.6  5109.9 1352.78  5159.9 1358.11  5209.9 1361.28
  5259.9 1360.89  5297.8  1361.9  5409.9 1362.65    5920 1363.52  6146.9 1366.32
#Mann= 4 ,-1 , 0
  4546.2     .12       0  4859.4    .035       0  4974.3    .035       0
  5005.4    .035       0
Bank Sta=4974.3,5005.4
XS Rating Curve= 0 ,0
Exp/Cntr=0.3,0.1

Type RM Length L Ch R = 1 ,23081   ,206,206,206
BEGIN DESCRIPTION:
WEST SISTER CREEK 41.5
END DESCRIPTION:
XS GIS Cut Line= 3
       2052554.1     13917032.22      2052123.73     13917015.29
      2050975.27     13917064.12
#Sta/Elev= 30
  4569.3 1406.82  4585.1 1405.86  4598.4 1402.78  4618.4 1402.02  4624.6 1404.79
  4638.5 1405.52  4668.5  1402.9  4688.5  1402.3  4708.5 1399.02  4748.5 1395.36
  4838.6 1391.31  4876.9  1387.2  4881.9 1388.98  4903.9 1381.63  4938.7 1366.69
  4948.7 1359.45  4958.7 1348.43  4968.7 1342.01  5003.1 1337.65  5003.6 1337.15
  5034.3 1337.65  5038.8 1341.75  5048.8 1341.53  5138.9 1352.74  5228.9 1360.85
    5289 1360.35  5350.2 1361.88  5668.8 1362.24  5700.1 1361.89  6149.5 1365.49
#Mann= 7 ,-1 , 0
  4569.3     .07       0  4585.1     .12       0  4903.9    .035       0
  5003.1    .035       0  5034.3    .035       0  5668.8     .07       0
  5700.1    .035       0
Bank Sta=5003.1,5034.3
XS Rating Curve= 0 ,0
Exp/Cntr=0.3,0.1

Type RM Length L Ch R = 1 ,22875   ,770,770,770
BEGIN DESCRIPTION:
WEST SISTER CREEK 41.0
END DESCRIPTION:
XS GIS Cut Line= 3
      2053294.77     13917093.17        2052075.       13916825.
      2051091.53     13917033.85
#Sta/Elev= 30
  3755.2 1426.46  4048.1 1420.86  4103.1 1415.74  4282.2 1409.79  4297.6 1409.63
    4326 1417.21  4331.1  1412.4  4348.8 1413.53  4369.3 1407.92  4449.8 1405.57
    4550 1407.91  4650.3 1403.25  4746.1 1398.67  4750.5 1399.02  4881.2 1390.65
    4887  1384.6  4911.9 1373.65  4930.8 1344.63    4951 1339.85  4964.1 1337.83
  4964.6 1337.33  4995.3 1337.83  5001.5 1341.91  5034.8 1343.52  5073.4 1352.72
  5157.4 1359.77  5326.4 1361.12  5665.3 1362.02  5782.6 1362.33  6009.5 1364.32
#Mann= 12 ,-1 , 0
  3755.2     .07       0  4449.8     .12       0    4550    .035       0
  4650.3     .12       0  4746.1     .07       0  4750.5     .12       0
    4951     .07       0  4964.1     .05       0  4995.3     .07       0
  5326.4    .035       0  5665.3     .07       0  5782.6    .035       0
Bank Sta=4964.1,4995.3
XS Rating Curve= 0 ,0
Exp/Cntr=0.3,0.1

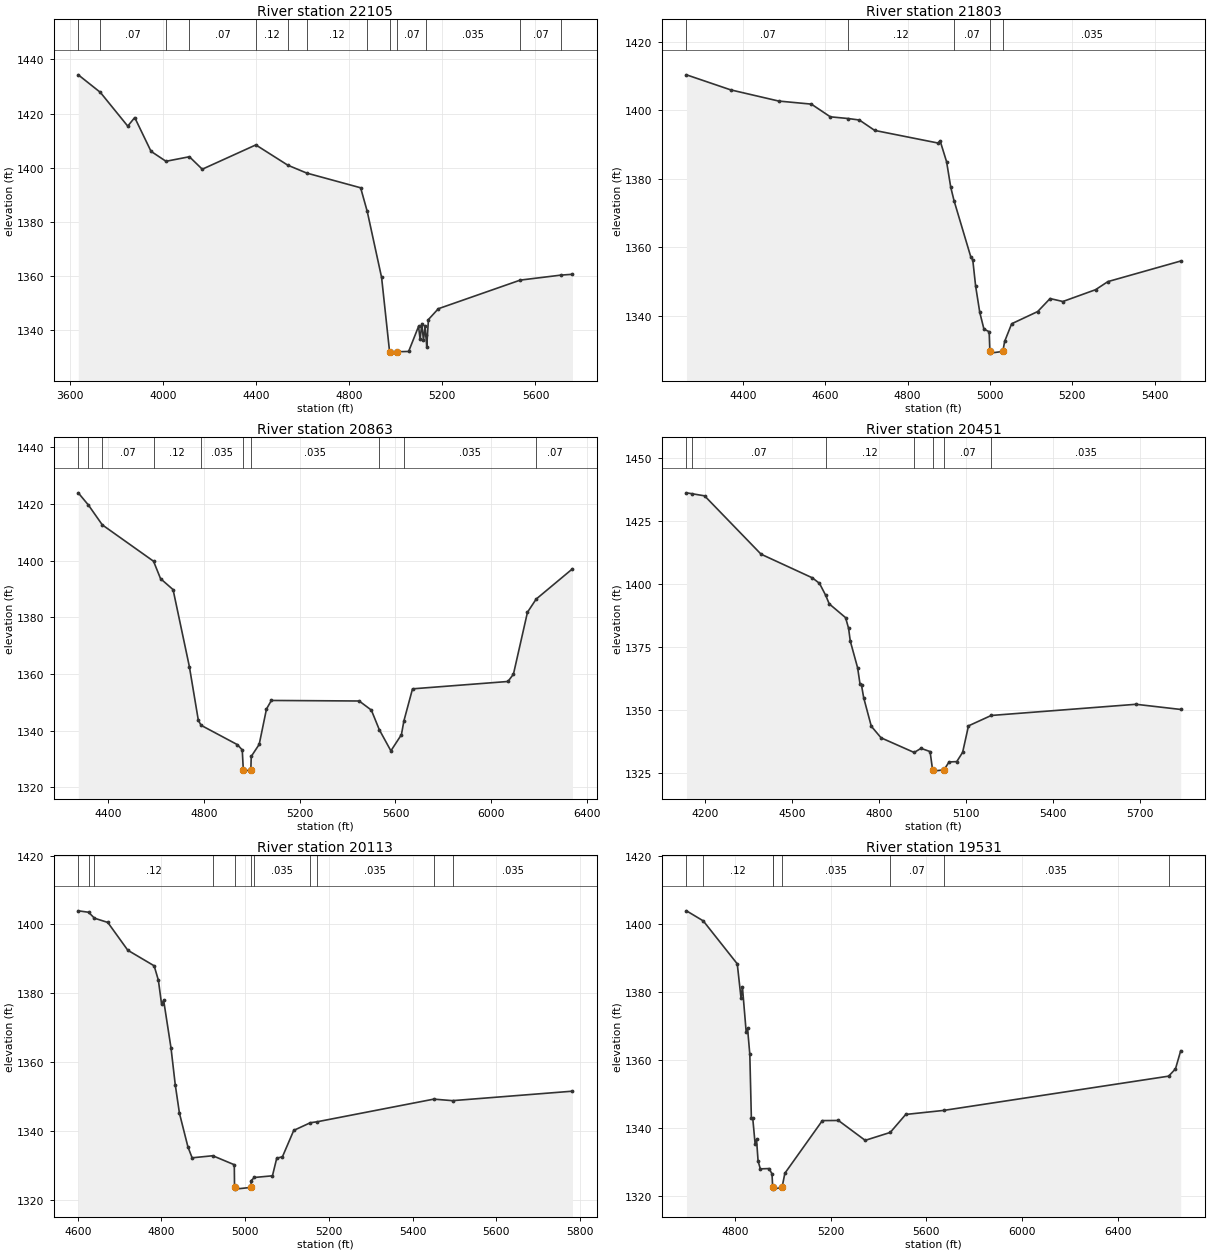
Type RM Length L Ch R = 1 ,22105   ,302,302,302
BEGIN DESCRIPTION:
WEST SISTER CREEK 40.0
END DESCRIPTION:
XS GIS Cut Line= 3
      2053487.52     13916166.09      2052112.51     13916160.88
      2051566.35     13916670.63
#Sta/Elev= 30
  3636.8 1434.26  3731.5 1427.81  3849.3 1415.35  3879.3 1418.51  3949.3 1406.05
  4013.6 1402.38    4114 1404.06  4169.3 1399.46  4399.3 1408.42  4536.8 1400.93
  4617.7 1398.04  4849.3 1392.61  4877.7 1383.87  4939.3 1359.54  4973.6 1332.15
  4974.1 1331.65    5005 1332.15  5055.4 1332.27  5097.9 1341.49  5104.7 1336.76
  5112.1 1342.53  5118.9 1336.48  5126.2 1341.51  5129.3 1338.18  5133.1 1334.09
  5140.4 1344.04  5182.9 1348.02  5534.5 1358.57  5708.9 1360.41  5758.9 1360.72
#Mann= 13 ,-1 , 0
  3636.8     .12       0  3731.5     .07       0  4013.6    .035       0
    4114     .07       0  4399.3     .12       0  4536.8     .07       0
  4617.7     .12       0  4877.7     .07       0  4973.6     .05       0
    5005     .07       0  5129.3    .035       0  5534.5     .07       0
  5708.9    .035       0
Bank Sta=4973.6,5005
XS Rating Curve= 0 ,0
Exp/Cntr=0.3,0.1

Type RM Length L Ch R = 1 ,21803   ,940,940,940
BEGIN DESCRIPTION:
WEST SISTER CREEK 39.0
END DESCRIPTION:
XS GIS Cut Line= 3
      2052801.48     13915781.27        2052075.       13915875.
      2051608.97     13915914.52
#Sta/Elev= 30
  4263.1 1410.41  4370.5 1406.01    4487 1402.74  4566.4 1401.84  4612.4 1398.13
  4656.4 1397.62    4683 1397.19  4720.2 1394.15    4874 1390.46    4879 1391.13
  4894.8 1384.97  4904.9 1377.51  4912.8 1373.63  4953.4 1357.22  4958.4 1356.23
  4965.3 1348.59  4975.4  1340.9  4985.5 1336.02  4998.1 1335.29  4999.9 1329.51
  5000.4 1329.01  5031.4 1329.51  5035.7 1332.42  5052.8  1337.6    5116 1341.17
  5146.1 1344.97  5177.2 1344.11  5256.5 1347.56  5286.5 1349.93  5463.3 1355.95
#Mann= 5 ,-1 , 0
  4263.1     .07       0  4656.4     .12       0  4912.8     .07       0
  4999.9     .05       0  5031.4    .035       0
Bank Sta=4999.9,5031.4
XS Rating Curve= 0 ,0
Exp/Cntr=0.3,0.1

Type RM Length L Ch R = 1 ,20863   ,750,750,750
BEGIN DESCRIPTION:
WEST SISTER CREEK 38.0
END DESCRIPTION:
XS GIS Cut Line= 3
      2052497.54     13914964.47      2051774.91     13915030.04
      2050460.37     13915287.97
#Sta/Elev= 30
  4274.4 1423.98  4317.1 1419.64    4375 1412.66    4589 1399.83  4618.3 1393.68
  4670.6 1389.81  4738.8  1362.6  4776.1 1343.72  4787.5 1341.92  4939.7 1335.06
  4959.7  1333.2  4964.1 1326.23  4964.6 1325.73  4995.6 1326.23  4997.2 1330.91
  5030.5 1335.17    5061 1347.68  5081.4 1350.68  5448.3 1350.49  5499.2 1347.27
  5532.3 1340.37  5580.8 1332.89  5624.8  1338.6  5635.2 1343.48  5671.2 1354.78
  6069.9 1357.38  6092.9 1359.96  6151.5 1381.82  6187.8 1386.46  6339.6 1397.15
#Mann= 10 ,-1 , 0
  4274.4     .07       0  4317.1    .035       0    4375     .07       0
    4589     .12       0  4787.5    .035       0  4964.1    .035       0
  4995.6    .035       0  5532.3     .07       0  5635.2    .035       0
  6187.8     .07       0
#XS Ineff= 2 , 0
       0                 5361.64       0 1350.25
Permanent Ineff=
       F       F
Bank Sta=4964.1,4995.6
XS Rating Curve= 0 ,0
Exp/Cntr=0.3,0.1

Type RM Length L Ch R = 1 ,20451   ,338,338,338
BEGIN DESCRIPTION:
WEST SISTER CREEK 37.0
END DESCRIPTION:
XS GIS Cut Line= 3
       2052652.1     13914916.74      2051815.71     13914675.43
      2050992.71     13914541.68
#Sta/Elev= 30
  4136.9 1436.11  4157.4 1435.73  4199.4 1434.91  4394.1 1411.79    4571 1402.42
  4595.6 1400.23  4617.1 1395.46  4629.2  1392.1  4685.5 1386.65  4695.9 1382.42
  4701.7 1377.39  4727.1 1366.75  4735.4 1360.29  4740.6 1359.82  4747.9 1354.95
  4774.2 1343.62  4807.9 1339.02  4922.1 1333.21  4945.7 1334.85  4976.9 1333.57
  4985.6 1326.32  4986.6 1325.82  5024.8 1326.32  5042.4 1329.46  5068.9 1329.59
  5089.2 1333.27  5109.4 1343.76  5187.9 1347.88  5686.9 1352.31  5841.2 1350.26
#Mann= 7 ,-1 , 0
  4136.9     .12       0  4157.4     .07       0  4617.1     .12       0
  4922.1     .07       0  4985.6     .05       0  5024.8     .07       0
  5187.9    .035       0
Bank Sta=4985.6,5024.8
XS Rating Curve= 0 ,0
Exp/Cntr=0.3,0.1

Type RM Length L Ch R = 1 ,20113   ,582,582,582
BEGIN DESCRIPTION:
WEST SISTER CREEK 36.0
END DESCRIPTION:
XS GIS Cut Line= 3
      2052325.03       13914425.        2051925.       13914375.
      2051159.74     13914514.98
#Sta/Elev= 30
  4601.2 1403.95  4625.8 1403.54    4640 1401.81  4671.8 1400.58  4719.6 1392.51
  4782.6 1387.99  4792.7  1383.8  4800.3 1376.88  4805.3 1377.97  4822.9 1364.12
    4833 1353.47  4843.1 1345.15  4863.3 1335.43  4873.3 1332.26  4922.7 1332.86
  4974.1 1330.25  4974.7 1323.67  4975.7 1323.17  5013.9 1323.67  5014.5 1325.64
    5022 1326.55  5065.3 1327.04  5075.5 1332.13  5089.2 1332.57  5116.2 1340.22
  5155.8 1342.44    5172 1342.72  5450.8 1349.29  5495.6 1348.85  5782.3  1351.6
#Mann= 11 ,-1 , 0
  4601.2     .07       0  4625.8    .035       0    4640     .12       0
  4922.7     .07       0  4974.7     .05       0  5013.9     .07       0
    5022    .035       0  5155.8     .07       0    5172    .035       0
  5450.8     .07       0  5495.6    .035       0
Bank Sta=4974.7,5013.9
XS Rating Curve= 0 ,0
Exp/Cntr=0.3,0.1

Type RM Length L Ch R = 1 ,19531   ,600,600,600
BEGIN DESCRIPTION:
WEST SISTER CREEK 35.0
END DESCRIPTION:
XS GIS Cut Line= 3
        2052375.       13914025.        2052025.       13913825.
      2050535.35     13914566.27
#Sta/Elev= 30
  4596.9 1403.85  4667.1 1400.89  4809.3 1388.25  4825.1 1378.15  4830.8 1381.48
  4846.7 1368.14  4852.4 1369.23  4861.8 1361.62  4868.3  1342.8    4874 1342.89
  4884.1 1335.16  4889.9 1336.59  4896.4 1330.23  4905.7 1327.93  4942.4 1328.02
  4954.7 1326.45  4957.3 1322.62  4957.4 1322.47  4958.4 1321.97  4996.6 1322.47
  5008.4 1326.64  5165.2 1342.13  5232.3 1342.17  5344.3 1336.32  5449.1 1338.65
  5513.8 1343.94  5672.8 1345.13  6613.5 1355.21    6642 1357.35  6663.9 1362.68
#Mann= 8 ,-1 , 0
  4596.9    .035       0  4667.1     .12       0  4957.3    .035       0
  4957.4    .035       0  4996.6    .035       0  5449.1     .07       0
  5672.8    .035       0  6613.5     .07       0
Bank Sta=4957.4,4996.6
XS Rating Curve= 0 ,0
Exp/Cntr=0.3,0.1

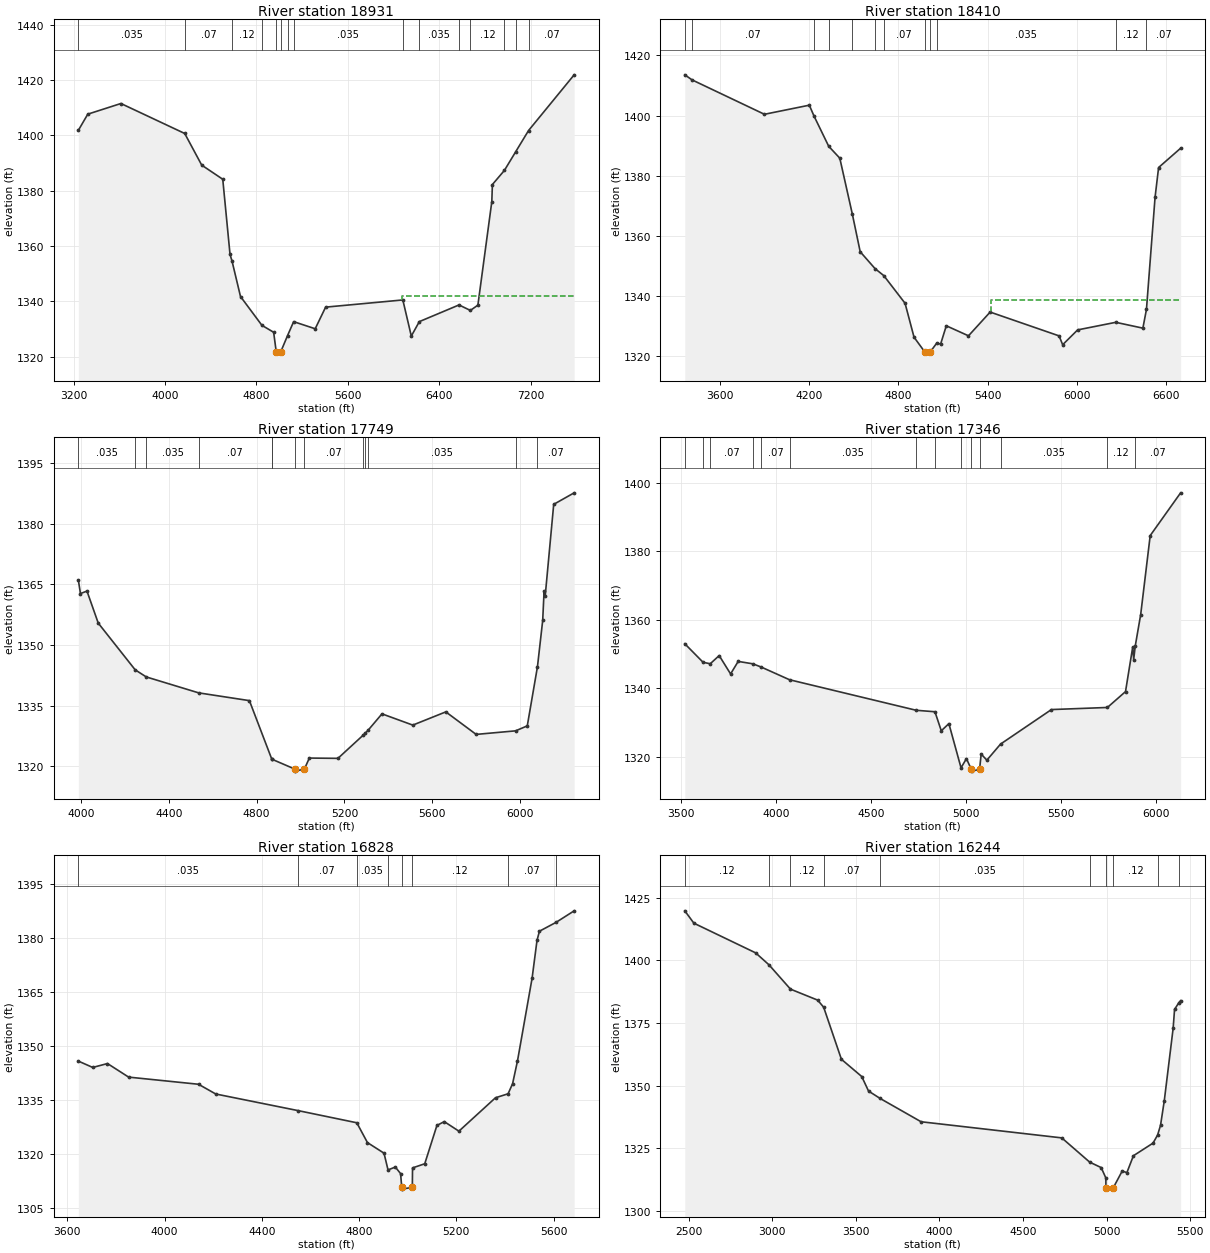
Type RM Length L Ch R = 1 ,18931   ,521,521,521
BEGIN DESCRIPTION:
WEST SISTER CREEK 34.0
END DESCRIPTION:
XS GIS Cut Line= 3
      2053310.46     13914426.54        2052025.       13913225.
      2049478.48      13912801.9
#Sta/Elev= 30
  3240.9  1401.8  3323.7 1407.66  3613.8 1411.51  4172.4 1400.67  4321.2 1389.23
  4505.4 1384.12  4568.9 1356.99  4587.2 1354.42  4660.7 1341.72  4848.1 1331.31
  4950.9 1328.79  4973.5 1321.75  4974.5 1321.25  5013.3 1321.75  5072.8 1327.61
    5126 1332.63  5314.7 1330.06    5406 1337.88    6082 1340.48  6156.1 1327.42
  6226.3 1332.64  6573.8 1338.67  6673.2 1336.69  6739.1  1338.6    6861 1376.05
    6866 1382.21  6971.4 1387.33  7070.8 1394.12  7182.7 1401.74  7581.9 1421.88
#Mann= 15 ,-1 , 0
  3240.9    .035       0  4172.4     .07       0  4587.2     .12       0
  4848.1    .035       0  4973.5    .035       0  5013.3    .035       0
  5072.8     .07       0    5126    .035       0    6082     .07       0
  6226.3    .035       0  6573.8     .07       0  6673.2     .12       0
  6971.4     .07       0  7070.8    .035       0  7182.7     .07       0
#XS Ineff= 2 , 0
       0                 6071.01       0 1342.03
Permanent Ineff=
       F       F
Bank Sta=4973.5,5013.3
XS Rating Curve= 0 ,0
Exp/Cntr=0.3,0.1

Type RM Length L Ch R = 1 ,18410   ,1064,1064,1064
BEGIN DESCRIPTION:
WEST SISTER CREEK 33.0
END DESCRIPTION:
XS GIS Cut Line= 3
      2053607.34     13912952.55        2051975.       13912775.
      2050374.96     13912224.99
#Sta/Elev= 30
  3363.2 1413.56    3412 1411.88  3898.7 1400.43  4200.4 1403.46  4232.1 1399.84
  4330.9 1389.78  4405.4 1385.83  4489.8 1367.21  4542.5 1354.71  4642.5 1349.08
  4701.1 1346.76  4844.2 1337.56  4904.6 1326.27  4975.2 1321.47  4976.2 1320.97
    5015 1321.47  5057.8 1324.34  5083.3 1323.98  5121.5 1330.07  5270.7 1326.73
  5416.4 1334.63  5879.7 1326.71    5904 1323.77  6004.7  1328.7    6261 1331.22
  6443.3 1329.28  6467.3 1335.49  6525.2 1372.79    6549 1382.72  6697.1 1389.14
#Mann= 12 ,-1 , 0
  3363.2    .035       0    3412     .07       0  4232.1    .035       0
  4330.9     .12       0  4489.8     .07       0  4642.5    .035       0
  4701.1     .07       0  4975.2     .05       0    5015     .07       0
  5057.8    .035       0    6261     .12       0  6467.3     .07       0
#XS Ineff= 2 , 0
       0                 5418.74       0 1338.78
Permanent Ineff=
       F       F
Bank Sta=4975.2,5015
XS Rating Curve= 0 ,0
Exp/Cntr=0.3,0.1

Type RM Length L Ch R = 1 ,17749   ,403,403,403
BEGIN DESCRIPTION:
WEST SISTER CREEK 32.0
END DESCRIPTION:
XS GIS Cut Line= 3
      2052674.54     13912406.69      2051678.21     13912252.32
      2050432.07     13912171.19
#Sta/Elev= 30
  3988.6 1366.11  3998.3 1362.75  4027.9 1363.37  4079.2 1355.45  4247.3  1343.9
  4297.8 1342.14  4536.4  1338.2  4767.3 1336.28  4869.7 1321.74  4871.4 1321.76
  4974.2 1319.35  4975.2 1318.85  5017.6 1319.35  5040.1 1322.08  5170.4 1322.01
  5284.8 1327.72    5294  1328.2    5308 1328.98  5370.8 1333.01  5511.1 1330.23
  5661.4  1333.5  5799.4 1327.93    5979 1328.81  6032.2 1330.04  6078.6 1344.68
  6102.4 1356.11  6108.7 1363.31  6113.7 1362.11  6152.5 1384.81  6245.6 1387.66
#Mann= 13 ,-1 , 0
  3988.6    .035       0  4247.3     .07       0  4297.8    .035       0
  4536.4     .07       0  4869.7     .12       0  4871.4     .07       0
  4974.2     .05       0  5017.6     .07       0  5284.8    .035       0
    5294     .07       0    5308    .035       0    5979     .12       0
  6078.6     .07       0
Bank Sta=4974.2,5017.6
XS Rating Curve= 0 ,0
Exp/Cntr=0.3,0.1

Type RM Length L Ch R = 1 ,17346   ,518,518,518
BEGIN DESCRIPTION:
WEST SISTER CREEK 31.0
END DESCRIPTION:
XS GIS Cut Line= 3
      2053006.21     13911894.97        2051525.       13911925.
       2050394.8     13911969.89
#Sta/Elev= 30
  3518.8 1352.97  3615.3 1347.55    3653 1347.14    3700 1349.52  3760.1 1344.16
  3800.1 1347.82  3877.8 1347.11  3922.4 1346.15  4070.6 1342.47  4738.2 1333.56
  4836.9 1333.13  4870.3 1327.57  4910.3 1329.67  4974.3 1316.78  5002.8 1319.46
  5028.7 1316.31  5029.7 1315.81  5072.1 1316.31  5080.4 1320.79  5110.4 1319.01
  5182.6  1323.7  5450.7 1333.77  5745.6 1334.38    5841 1339.01  5879.1 1352.06
  5884.1 1348.37  5892.2 1352.27    5921  1361.5  5971.1 1384.53  6131.4    1397
#Mann= 14 ,-1 , 0
  3518.8     .07       0  3615.3    .035       0    3653     .07       0
  3877.8    .035       0  3922.4     .07       0  4070.6    .035       0
  4738.2     .07       0  4836.9     .12       0  4974.3     .07       0
  5028.7     .05       0  5072.1     .07       0  5182.6    .035       0
  5745.6     .12       0  5892.2     .07       0
Bank Sta=5028.7,5072.1
XS Rating Curve= 0 ,0
Exp/Cntr=0.3,0.1

Type RM Length L Ch R = 1 ,16828   ,584,584,584
BEGIN DESCRIPTION:
WEST SISTER CREEK 30.0
END DESCRIPTION:
XS GIS Cut Line= 3
      2052763.54     13911681.71        2051425.       13911475.
      2050742.74     13911416.09
#Sta/Elev= 30
  3645.5 1345.83  3704.7 1344.07  3765.4 1345.15  3852.4 1341.39  4139.8 1339.41
  4210.7 1336.71  4547.7 1332.13  4790.7 1328.74  4834.5 1323.25  4902.7 1320.31
  4919.2 1315.67  4949.3 1316.47  4970.9 1314.64  4975.6 1310.85  4976.6 1310.35
  5019.2 1310.85    5020 1316.23  5070.2 1317.38  5120.3    1328  5150.5 1329.06
  5210.7 1326.41  5361.2 1335.67    5413 1336.77  5431.5 1339.57  5451.6 1345.86
  5511.8 1368.83  5531.9 1379.27  5541.9 1381.82  5610.4 1384.28  5684.7 1387.47
#Mann= 8 ,-1 , 0
  3645.5    .035       0  4547.7     .07       0  4790.7    .035       0
  4919.2     .12       0  4975.6     .05       0  5019.2     .12       0
    5413     .07       0  5610.4    .035       0
Bank Sta=4975.6,5019.2
XS Rating Curve= 0 ,0
Exp/Cntr=0.3,0.1

Type RM Length L Ch R = 1 ,16244   ,548,548,548
BEGIN DESCRIPTION:
WEST SISTER CREEK 29.0
END DESCRIPTION:
XS GIS Cut Line= 3
      2054008.91     13911339.67        2051525.       13910925.
        2051125.       13910725.
#Sta/Elev= 30
  2477.6  1419.8  2531.8 1414.87  2901.5 1403.01  2981.1 1398.24  3109.7 1388.53
  3272.4 1384.14  3308.2  1381.3  3414.3 1360.52    3536 1353.63  3576.5 1347.84
  3646.3 1344.87  3890.8 1335.58  4732.3 1329.14  4899.2 1319.46    4968 1317.28
  4995.9 1313.13  4996.4 1309.18  4997.4 1308.68    5040 1309.18  5093.7 1315.91
  5121.7 1315.27  5160.8 1322.01  5278.2 1327.06  5305.5  1330.3  5322.9 1334.15
  5345.3 1343.93  5398.4 1372.91  5406.8 1380.43    5433 1383.18  5443.1 1383.92
#Mann= 10 ,-1 , 0
  2477.6     .12       0  2981.1     .07       0  3109.7     .12       0
  3308.2     .07       0  3646.3    .035       0  4899.2     .12       0
  4996.4     .05       0    5040     .12       0  5305.5     .07       0
    5433    .035       0
Bank Sta=4996.4,5040
XS Rating Curve= 0 ,0
Exp/Cntr=0.3,0.1