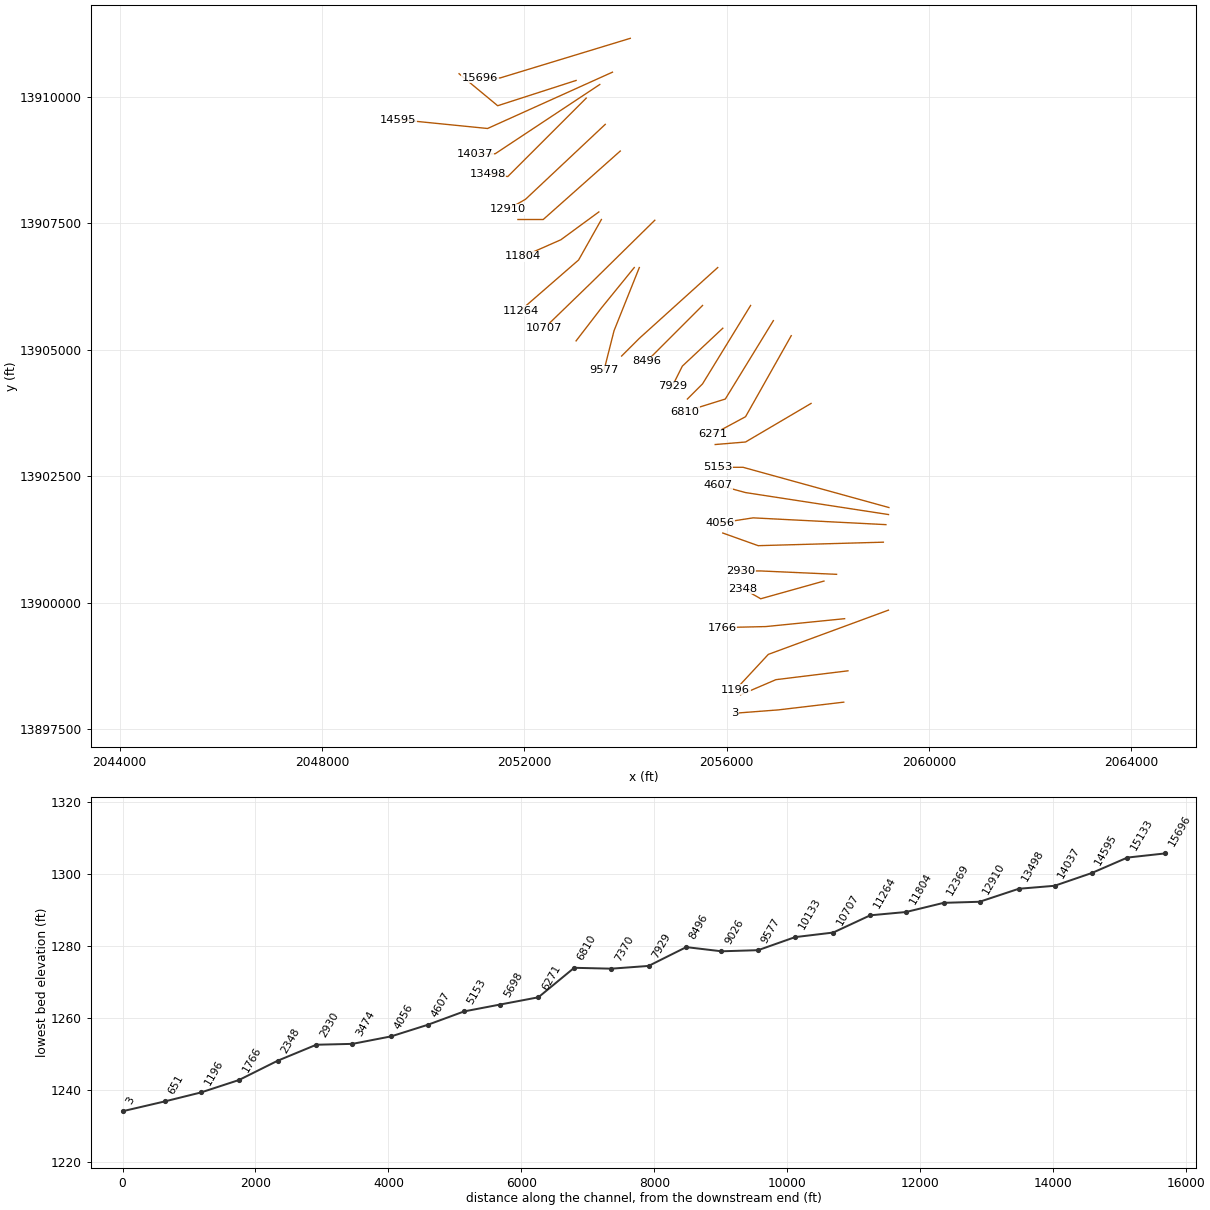
HEC-RAS study WEST SISTER CREEK.prj: WEST SISTER CREEK Base Level Engineering

--- WEST SISTER CREEK.g01 (geometry) --- (continued)

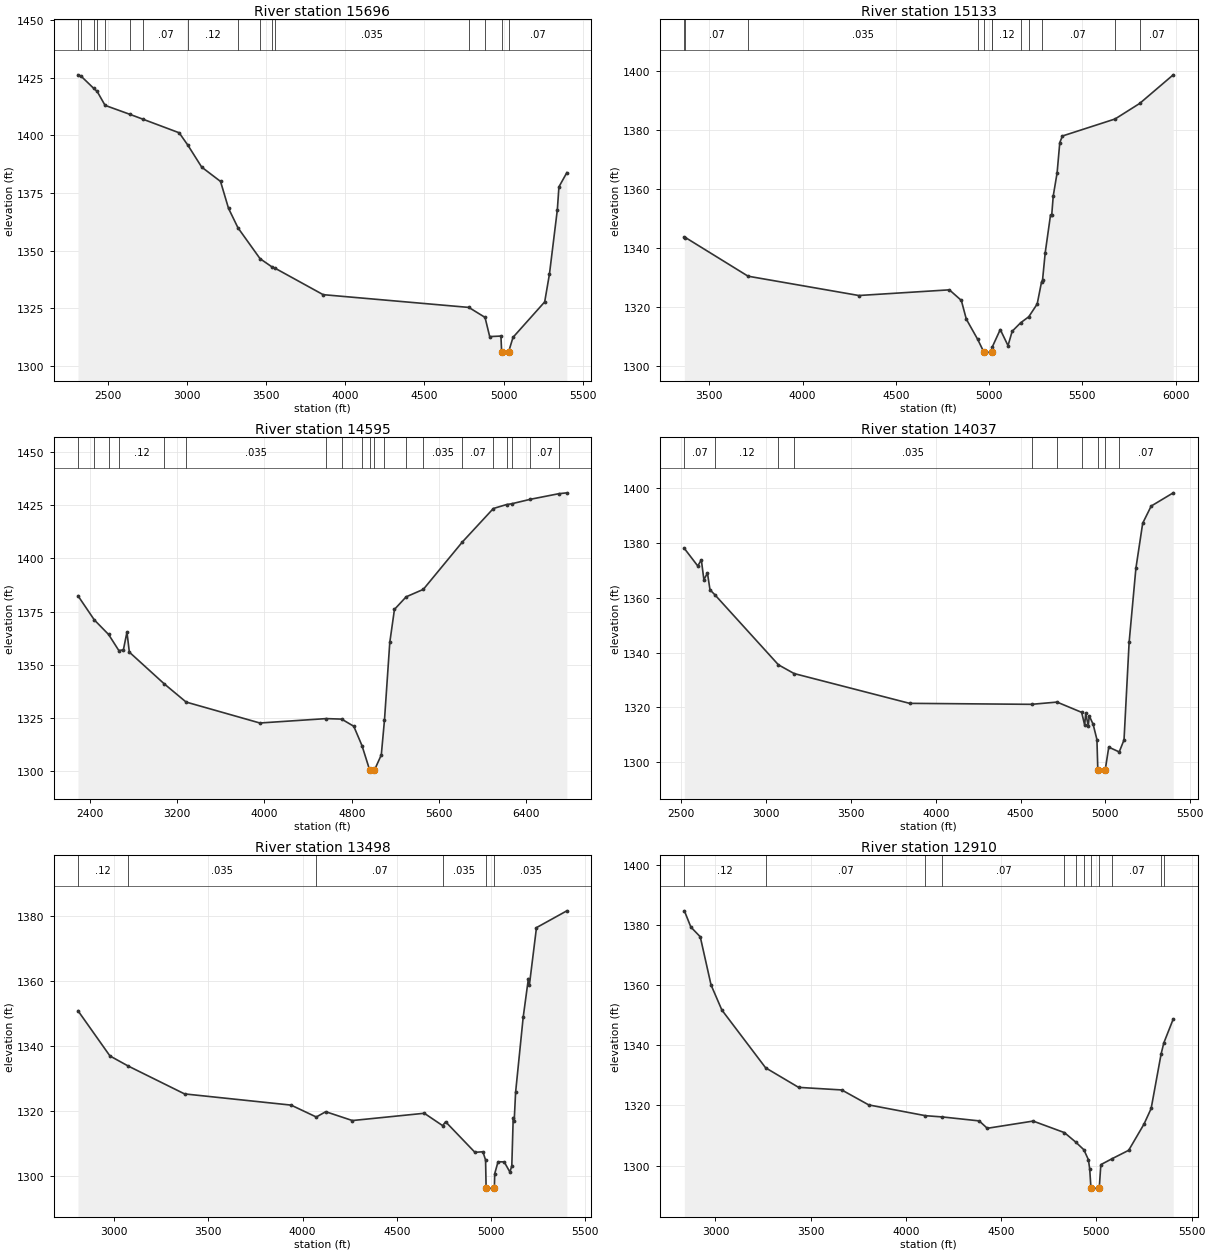
Type RM Length L Ch R = 1 ,15696   ,563,563,563
BEGIN DESCRIPTION:
WEST SISTER CREEK 28.0
END DESCRIPTION:
XS GIS Cut Line= 3
      2054096.34       13911158.        2051525.       13910375.
      2051125.01       13910375.
#Sta/Elev= 30
  2312.1 1426.28  2331.2 1425.73  2411.2 1420.43  2433.3 1419.07  2483.2 1413.04
  2637.5 1409.21  2723.3 1407.02  2951.2 1401.15  3006.4 1395.75  3093.5 1386.27
  3212.5 1380.05    3263 1368.38  3322.6 1359.95  3462.2 1346.56  3538.9 1342.92
  3556.1 1342.46  3860.6 1330.96    4781 1325.43  4883.1 1321.11  4912.7 1312.78
  4983.6 1313.01  4988.2 1306.11  4989.2 1305.61  5031.9 1306.11    5060 1312.46
    5260 1327.82    5290 1339.84    5340  1367.8    5350 1377.71    5400 1383.88
#Mann= 16 ,-1 , 0
  2312.1     .12       0  2331.2     .07       0  2411.2    .035       0
  2433.3     .07       0  2483.2    .035       0  2637.5     .12       0
  2723.3     .07       0  3006.4     .12       0  3322.6     .07       0
  3462.2    .035       0  3538.9     .07       0  3556.1    .035       0
    4781     .07       0  4883.1     .12       0  4988.2     .05       0
  5031.9     .07       0
Bank Sta=4988.2,5031.9
XS Rating Curve= 0 ,0
Exp/Cntr=0.3,0.1

Type RM Length L Ch R = 1 ,15133   ,538,538,538
BEGIN DESCRIPTION:
WEST SISTER CREEK 27.0
END DESCRIPTION:
XS GIS Cut Line= 3
      2053025.02     13910325.01        2051475.       13909825.
      2050711.48     13910457.75
#Sta/Elev= 30
  3366.5 1343.79  3372.2 1343.63    3708 1330.53  4301.7 1323.99  4786.9 1325.91
    4851 1322.33  4877.7 1315.99  4938.4 1309.17  4970.7 1304.97  4971.7 1304.47
  5014.4 1304.97  5017.9  1306.7  5059.7 1312.46  5101.3 1307.01  5123.5 1311.87
  5168.7 1314.74  5212.5 1316.79  5257.6 1321.11  5280.8 1328.55  5286.2 1329.13
  5300.6 1338.47  5329.2 1351.31  5335.7 1351.34  5343.6  1357.7  5364.4 1365.54
  5378.7 1375.79    5393 1378.03    5675 1383.79  5806.9 1389.05  5986.8 1398.75
#Mann= 12 ,-1 , 0
  3366.5     .12       0  3372.2     .07       0    3708    .035       0
  4938.4     .07       0  4970.7     .05       0  5014.4     .07       0
  5017.9     .12       0  5168.7     .07       0  5212.5     .12       0
  5280.8     .07       0    5675    .035       0  5806.9     .07       0
Bank Sta=4970.7,5014.4
XS Rating Curve= 0 ,0
Exp/Cntr=0.3,0.1

Type RM Length L Ch R = 1 ,14595   ,558,558,558
BEGIN DESCRIPTION:
WEST SISTER CREEK 26.0
END DESCRIPTION:
XS GIS Cut Line= 3
      2053743.94      13910488.9        2051275.       13909375.
      2049513.51     13909551.51
#Sta/Elev= 30
  2291.3  1382.4  2440.7  1371.1  2571.8 1364.25  2665.6 1356.72  2707.3 1357.05
  2739.9 1365.36  2761.9 1355.97  3080.6 1341.14    3282 1332.56  3957.7 1322.74
  4565.1  1324.8    4707 1324.56  4818.2  1321.2  4893.5  1312.1  4963.7 1300.67
  4964.7 1300.17  5007.5 1300.67  5070.2 1307.76  5099.5 1324.19    5148 1360.55
  5190.8 1376.02  5298.2 1381.92  5455.1  1385.4  5813.2 1407.64  6096.9 1423.33
  6217.5 1425.18  6264.6 1425.55  6437.1 1427.66  6694.4 1430.25  6770.2 1430.68
#Mann= 20 ,-1 , 0
  2291.3     .12       0  2440.7     .12       0  2571.8     .07       0
  2665.6     .12       0  3080.6     .07       0    3282    .035       0
  4565.1    .035       0    4707     .07       0  4893.5     .12       0
  4963.7     .05       0  5007.5     .12       0  5099.5    .035       0
  5298.2     .07       0  5455.1    .035       0  5813.2     .07       0
  6096.9     .12       0  6217.5     .07       0  6264.6     .12       0
  6437.1     .07       0  6694.4     .12       0
Bank Sta=4963.7,5007.5
XS Rating Curve= 0 ,0
Exp/Cntr=0.3,0.1

Type RM Length L Ch R = 1 ,14037   ,539,539,539
BEGIN DESCRIPTION:
WEST SISTER CREEK 25.0
END DESCRIPTION:
XS GIS Cut Line= 3
      2053493.63     13910245.04        2051425.       13908875.
      2051024.97       13908875.
#Sta/Elev= 30
  2518.4 1378.05  2597.3 1371.64  2618.4 1373.88  2633.4 1366.64  2654.5 1369.04
  2669.5 1362.92  2696.9  1361.2  3072.7 1335.51  3165.2 1332.31  3845.8 1321.42
  4564.3 1321.06  4714.7 1321.88  4859.9 1318.13  4877.7 1313.44  4883.7 1317.82
  4898.8 1313.23  4904.8 1316.85  4927.6 1313.74  4949.9 1308.18  4955.1 1297.14
  4956.1 1296.64  4998.9 1297.14  5019.6 1305.41  5081.3 1303.66  5109.6 1308.06
  5139.6 1343.69  5179.6  1370.8  5219.6 1387.26  5269.6 1393.54  5399.6 1398.38
#Mann= 10 ,-1 , 0
  2518.4     .07       0  2696.9     .12       0  3072.7     .07       0
  3165.2    .035       0  4564.3     .07       0  4714.7    .035       0
  4859.9     .12       0  4955.1     .05       0  4998.9     .12       0
  5081.3     .07       0
Bank Sta=4955.1,4998.9
XS Rating Curve= 0 ,0
Exp/Cntr=0.3,0.1

Type RM Length L Ch R = 1 ,13498   ,588,588,588
BEGIN DESCRIPTION:
WEST SISTER CREEK 24.0
END DESCRIPTION:
XS GIS Cut Line= 3
      2053224.98     13909974.98        2051675.       13908425.
      2051275.01       13908475.
#Sta/Elev= 30
    2808 1350.72  2977.7  1336.8  3074.9 1333.69  3373.7 1325.12  3939.3 1321.67
    4073 1318.01  4123.2 1319.64  4264.6 1316.92  4646.4 1319.16  4743.6 1315.36
  4759.6 1316.54  4915.1 1307.14  4957.6 1307.31  4971.7 1304.75  4974.5 1296.31
  4975.5 1295.81  5018.4 1296.31  5020.2 1300.57  5037.8 1304.23  5070.5 1304.19
  5100.8 1301.07  5110.9 1302.96  5118.4 1317.84  5123.5 1316.63    5131 1325.57
  5171.3  1348.7    5199 1360.61  5204.1 1358.58  5241.9  1376.3  5403.1 1381.47
#Mann= 6 ,-1 , 0
    2808     .12       0  3074.9    .035       0    4073     .07       0
  4743.6    .035       0  4974.5    .035       0  5018.4    .035       0
Bank Sta=4974.5,5018.4
XS Rating Curve= 0 ,0
Exp/Cntr=0.3,0.1

Type RM Length L Ch R = 1 ,12910   ,541,541,541
BEGIN DESCRIPTION:
WEST SISTER CREEK 23.0
END DESCRIPTION:
XS GIS Cut Line= 3
      2053601.25     13909456.68        2052025.       13907975.
      2051675.03     13907775.02
#Sta/Elev= 30
  2836.9 1384.67    2871 1379.28  2920.3 1376.04    2977 1360.04  3033.6 1351.73
  3263.5 1332.51  3436.6 1326.02  3663.2 1325.16  3804.8 1320.19  4102.4 1316.61
  4191.7 1316.19  4384.6 1314.88  4427.1 1312.42  4667.8 1314.82  4831.9 1310.99
    4891 1307.86  4934.3 1305.28    4958 1301.97  4964.8 1298.92  4971.2 1292.71
  4972.2 1292.21  5015.1 1292.71  5023.3 1300.35  5083.6 1302.36  5169.4 1305.11
    5250 1313.83  5287.4    1319  5339.6 1337.09  5353.7 1340.76  5403.3 1348.72
#Mann= 12 ,-1 , 0
  2836.9     .12       0  3263.5     .07       0  4102.4    .035       0
  4191.7     .07       0  4831.9    .035       0    4891     .07       0
  4934.3     .12       0  4971.2     .05       0  5015.1     .12       0
  5083.6     .07       0  5339.6    .035       0  5353.7     .07       0
Bank Sta=4971.2,5015.1
XS Rating Curve= 0 ,0
Exp/Cntr=0.3,0.1

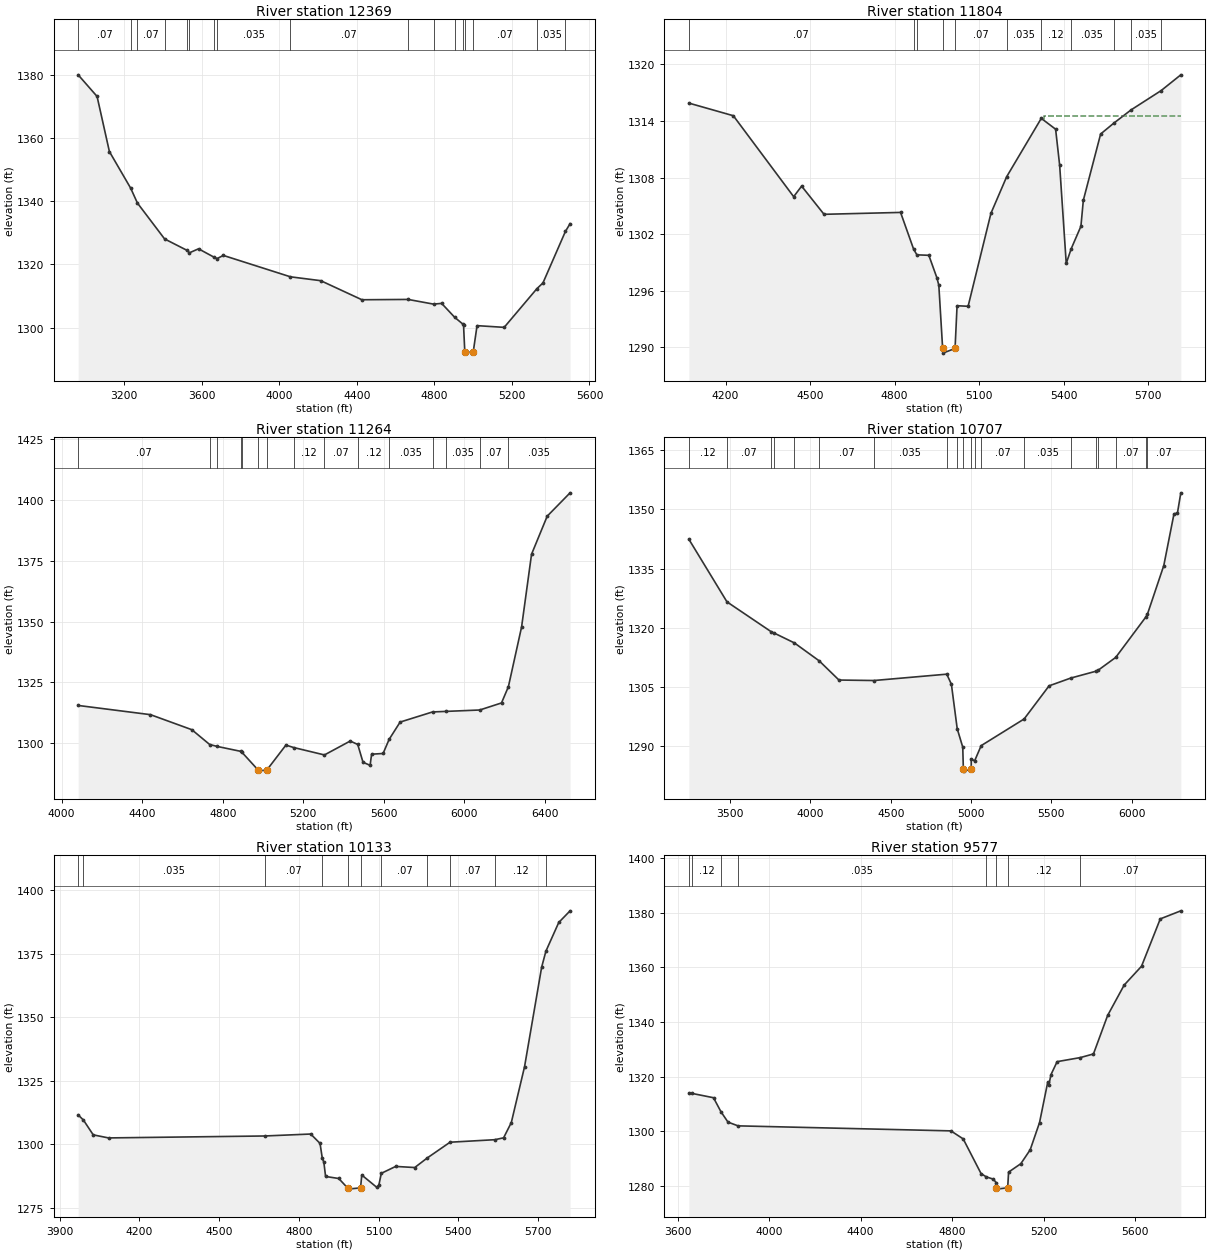
Type RM Length L Ch R = 1 ,12369   ,565,565,565
BEGIN DESCRIPTION:
WEST SISTER CREEK 22.0
END DESCRIPTION:
XS GIS Cut Line= 3
      2053898.31     13908929.16        2052375.       13907575.
      2051874.99       13907575.
#Sta/Elev= 30
  2961.8 1379.92  3059.5 1373.09  3123.1 1355.65    3233 1344.06  3267.6 1339.38
  3407.8 1328.03  3524.2 1324.39  3536.1 1323.64    3583  1324.9  3664.5  1322.2
  3679.3 1321.83    3711 1322.81  4057.4 1316.04  4213.5 1314.82  4425.9 1308.79
  4664.3 1308.89  4795.3 1307.41  4837.3 1307.64  4904.7 1303.23  4947.8 1301.04
  4950.2 1300.93  4956.7 1292.41  4957.7 1291.91  5000.6 1292.41    5020  1300.6
    5160 1300.06  5328.7 1312.29    5360  1314.1    5476  1330.4    5500 1332.85
#Mann= 17 ,-1 , 0
  2961.8     .07       0    3233    .035       0  3267.6     .07       0
  3407.8    .035       0  3524.2     .07       0  3536.1    .035       0
  3664.5     .07       0  3679.3    .035       0  4057.4     .07       0
  4664.3    .035       0  4795.3     .07       0  4904.7     .12       0
  4947.8     .07       0  4956.7     .05       0  5000.6     .07       0
  5328.7    .035       0    5476     .07       0
Bank Sta=4956.7,5000.6
XS Rating Curve= 0 ,0
Exp/Cntr=0.3,0.1

Type RM Length L Ch R = 1 ,11804   ,540,540,540
BEGIN DESCRIPTION:
WEST SISTER CREEK 21.0
END DESCRIPTION:
XS GIS Cut Line= 3
      2053475.02     13907725.01        2052725.       13907175.
      2051978.39     13906845.64
#Sta/Elev= 30
  4069.9  1315.9  4227.7 1314.56  4441.9 1305.97  4470.1 1307.09  4549.6  1304.1
  4821.3  1304.3  4867.5 1300.41  4879.2  1299.8  4921.6 1299.75  4950.4 1297.35
  4957.1 1296.56  4970.6 1289.87  4971.6 1289.37  5014.7 1289.87  5021.8  1294.4
    5061 1294.34  5142.1 1304.21  5197.9 1308.09  5320.7 1314.28  5371.6 1313.13
    5386 1309.29  5409.3 1298.89    5427 1300.45  5461.4 1302.83    5470 1305.59
  5531.4 1312.62  5577.2 1313.75  5639.5 1315.18  5745.8 1317.22    5816  1318.9
#Mann= 11 ,-1 , 0
  4069.9     .07       0  4867.5    .035       0  4879.2     .07       0
  4970.6     .05       0  5014.7     .07       0  5197.9    .035       0
  5320.7     .12       0    5427    .035       0  5577.2     .07       0
  5639.5    .035       0  5745.8     .07       0
#XS Ineff= 2 , 0
       0                 5329.43       0 1314.48
Permanent Ineff=
       F       F
Bank Sta=4970.6,5014.7
XS Rating Curve= 0 ,0
Exp/Cntr=0.3,0.1

Type RM Length L Ch R = 1 ,11264   ,557,557,557
BEGIN DESCRIPTION:
WEST SISTER CREEK 20.0
END DESCRIPTION:
XS GIS Cut Line= 3
      2053524.98     13907574.96        2053075.       13906775.
      2051925.01     13905775.01
#Sta/Elev= 30
  4082.4 1315.47  4441.5 1311.68  4646.8 1305.49  4735.3  1299.4  4773.4  1298.6
  4888.3 1296.61    4894 1296.33  4975.3 1288.95  4976.3 1288.45  5019.5 1288.95
  5113.7 1299.16  5152.1 1298.16    5305 1295.11  5432.7 1300.82  5470.2 1299.43
  5496.4  1292.1  5531.5 1290.83  5539.1 1295.42  5596.1 1295.71  5625.9  1301.5
  5680.6 1308.63  5841.5  1312.8  5906.9 1313.02  6075.7  1313.6  6183.8  1316.5
    6218 1323.18  6283.5 1347.77  6332.9 1377.68  6410.7 1393.35  6524.2 1402.95
#Mann= 15 ,-1 , 0
  4082.4     .07       0  4735.3    .035       0  4773.4     .07       0
  4888.3    .035       0    4894     .07       0  4975.3     .05       0
  5019.5     .07       0  5152.1     .12       0    5305     .07       0
  5470.2     .12       0  5625.9    .035       0  5841.5     .07       0
  5906.9    .035       0  6075.7     .07       0    6218    .035       0
Bank Sta=4975.3,5019.5
XS Rating Curve= 0 ,0
Exp/Cntr=0.3,0.1

Type RM Length L Ch R = 1 ,10707   ,574,574,574
BEGIN DESCRIPTION:
WEST SISTER CREEK 19.0
END DESCRIPTION:
XS GIS Cut Line= 3
      2054580.95      13907560.6        2053325.       13906325.
      2052390.27     13905419.72
#Sta/Elev= 30
  3243.2 1342.45  3480.4 1326.58  3755.5 1319.02  3775.7 1318.64  3900.3 1316.17
  4055.1 1311.61  4177.7 1306.76  4395.8 1306.64    4849 1308.25  4877.8 1305.69
    4914 1294.42  4948.5 1289.75  4952.3 1284.17  4953.3 1283.67  5001.3 1284.17
  5001.5 1286.79  5022.1 1286.24  5063.2 1290.13  5330.6 1296.89    5486 1305.29
    5621 1307.26  5776.5 1308.98  5789.6 1309.19    5901  1312.5  6088.7 1322.75
  6098.5 1323.47  6200.3 1335.79  6263.8  1348.9  6285.2 1349.08  6306.3 1354.22
#Mann= 20 ,-1 , 0
  3243.2     .12       0  3480.4     .07       0  3755.5    .035       0
  3775.7     .07       0  3900.3     .12       0  4055.1     .07       0
  4395.8    .035       0    4849     .12       0    4914     .07       0
  4952.3     .05       0  5001.3     .07       0  5022.1     .12       0
  5063.2     .07       0  5330.6    .035       0    5621     .07       0
  5776.5    .035       0  5789.6     .12       0    5901     .07       0
  6088.7     .12       0  6098.5     .07       0
Bank Sta=4952.3,5001.3
XS Rating Curve= 0 ,0
Exp/Cntr=0.3,0.1

Type RM Length L Ch R = 1 ,10133   ,556,556,556
BEGIN DESCRIPTION:
WEST SISTER CREEK 18.0
END DESCRIPTION:
XS GIS Cut Line= 3
      2054175.02     13906625.03        2053525.       13905825.
      2053024.98     13905174.98
#Sta/Elev= 30
  3969.2 1311.61  3989.2 1309.55    4026 1303.74  4083.5 1302.54  4670.6  1303.3
  4844.2 1304.07  4879.3 1300.39  4887.8 1294.57  4893.7 1292.97  4900.2 1287.38
  4949.7 1286.58  4982.7  1282.9  4983.7  1282.4  5031.8  1282.9  5036.3 1287.95
  5092.4 1283.14  5100.6 1283.99    5110 1288.62    5164 1291.33  5235.6 1290.89
  5282.9 1294.67  5368.5 1300.85    5537 1301.84    5570 1302.58    5599 1308.59
  5648.8 1330.56  5713.1 1369.68  5729.2    1376  5777.5 1387.27  5820.1 1391.85
#Mann= 11 ,-1 , 0
  3969.2     .12       0  3989.2    .035       0  4670.6     .07       0
  4887.8     .12       0  4982.7     .05       0  5031.8     .12       0
    5110     .07       0  5282.9    .035       0  5368.5     .07       0
    5537     .12       0  5729.2     .07       0
Bank Sta=4982.7,5031.8
XS Rating Curve= 0 ,0
Exp/Cntr=0.3,0.1

Type RM Length L Ch R = 1 ,9577    ,551,551,551
BEGIN DESCRIPTION:
WEST SISTER CREEK 17.0
END DESCRIPTION:
XS GIS Cut Line= 3
        2054275.     13906624.99        2053775.       13905375.
      2053577.44     13904594.91
#Sta/Elev= 30
  3648.8 1313.89  3661.9 1313.84  3756.5 1312.25    3789 1307.13  3819.8 1303.32
  3863.7 1301.95  4794.5 1300.11  4848.3 1297.17  4926.4 1284.47  4949.1 1283.27
  4980.3 1282.42  4992.4 1281.15  4993.6 1279.28  4994.6 1278.78  5042.8 1279.28
  5046.7 1285.01  5100.2 1288.09  5141.2 1293.18  5182.1 1303.16    5218 1317.99
  5223.1 1317.09  5232.3 1320.75    5259 1325.46  5360.3 1326.95  5417.8 1328.28
  5479.9  1342.4  5552.1  1353.5    5628  1360.4    5710 1377.74  5799.8 1380.69
#Mann= 8 ,-1 , 0
  3648.8    .035       0  3661.9     .12       0    3789     .07       0
  3863.7    .035       0  4949.1     .12       0  4993.6     .05       0
  5042.8     .12       0  5360.3     .07       0
Bank Sta=4993.6,5042.8
XS Rating Curve= 0 ,0
Exp/Cntr=0.3,0.1

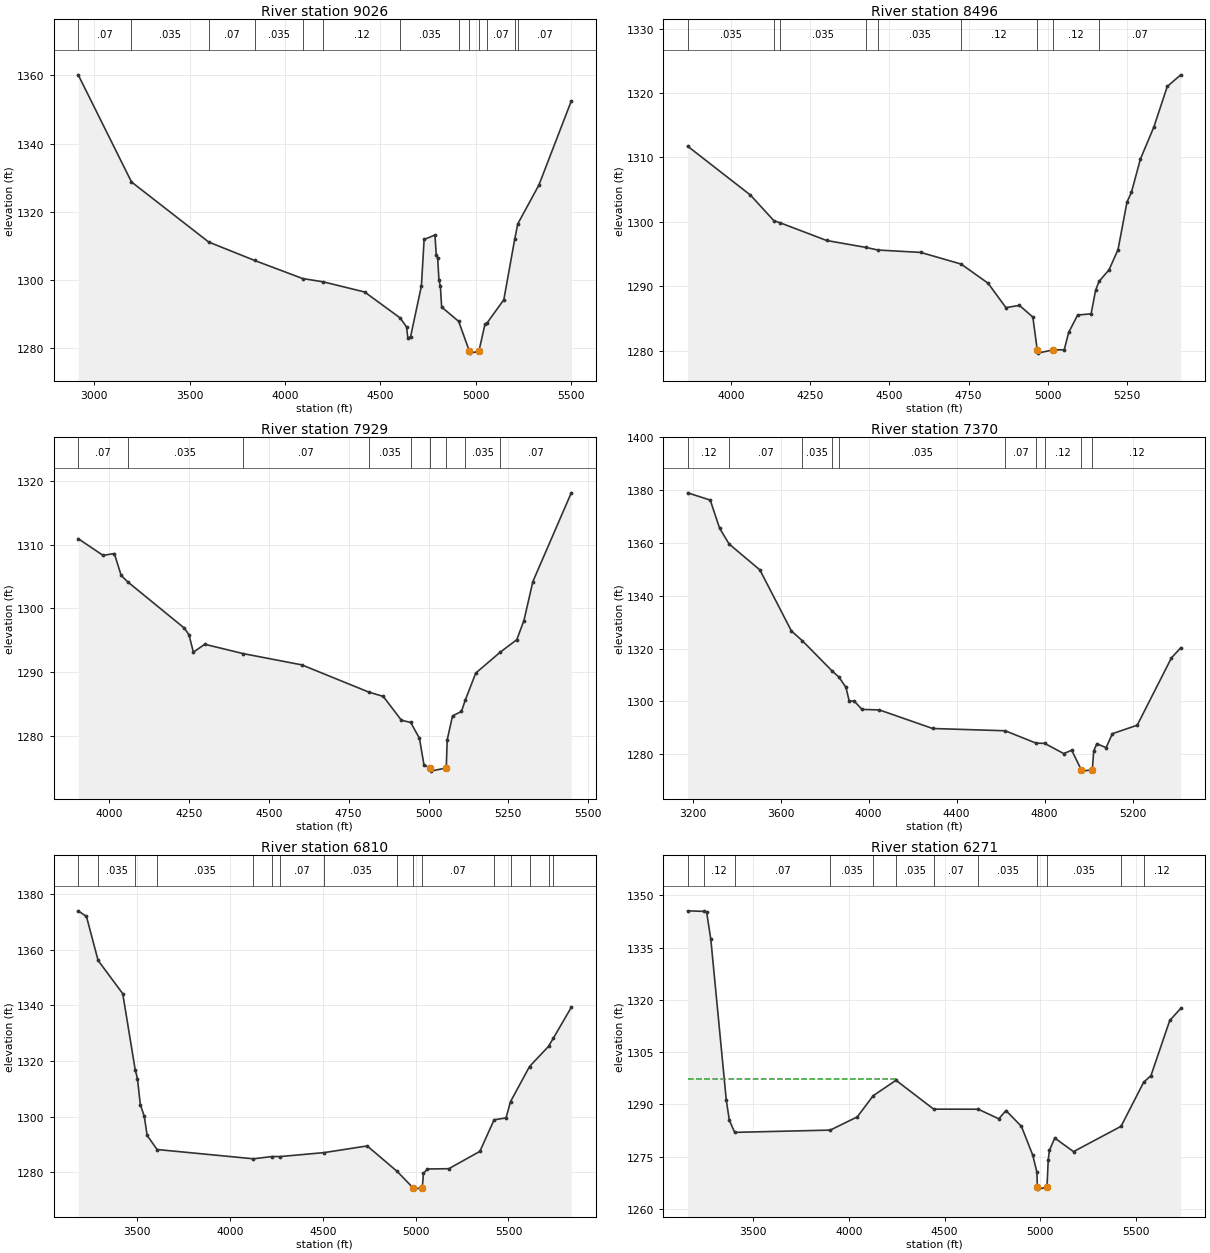
Type RM Length L Ch R = 1 ,9026    ,530,530,530
BEGIN DESCRIPTION:
WEST SISTER CREEK 16.0
END DESCRIPTION:
XS GIS Cut Line= 3
      2055824.99     13906624.99        2054275.       13905225.
      2053925.02     13904875.02
#Sta/Elev= 30
  2916.1 1360.18  3195.3 1328.73  3600.1 1311.08  3840.6 1305.68    4092 1300.37
  4200.1  1299.4    4417 1296.42  4603.5 1288.78  4636.7 1286.12  4643.4  1282.9
  4657.6 1283.26  4714.4 1298.19  4728.6 1311.84  4785.4 1313.15  4792.2 1307.34
  4799.6 1306.31  4806.4 1299.94  4813.8 1298.12  4820.5    1292  4909.6  1287.8
  4966.3 1278.97  4967.3 1278.47  5015.5 1278.97  5047.2 1286.89  5059.7 1287.43
  5146.2 1294.15  5203.4 1311.92  5219.1 1316.39    5330 1327.82  5499.7 1352.49
#Mann= 13 ,-1 , 0
  2916.1     .07       0  3195.3    .035       0  3600.1     .07       0
  3840.6    .035       0    4092     .07       0  4200.1     .12       0
  4603.5    .035       0  4909.6     .12       0  4966.3     .05       0
  5015.5     .12       0  5059.7     .07       0  5203.4     .12       0
  5219.1     .07       0
Bank Sta=4966.3,5015.5
XS Rating Curve= 0 ,0
Exp/Cntr=0.3,0.1

Type RM Length L Ch R = 1 ,8496    ,567,567,567
BEGIN DESCRIPTION:
WEST SISTER CREEK 15.0
END DESCRIPTION:
XS GIS Cut Line= 3
      2055525.02     13905875.02        2054725.       13905075.
      2054424.98     13904774.98
#Sta/Elev= 30
  3863.8 1311.74  4061.8 1304.16  4136.2 1300.16  4155.4 1299.86  4302.2 1297.11
  4425.8 1296.04    4464 1295.63  4599.2 1295.26  4726.5 1293.45  4811.4 1290.49
  4867.9 1286.69  4910.4 1287.04  4952.8 1285.23  4966.7 1280.13  4967.7 1279.63
  5016.7 1280.13  5051.8 1280.15  5065.9 1282.85  5094.2 1285.54  5136.6 1285.73
  5150.8 1289.37  5161.5 1290.75  5193.2 1292.56  5221.5 1295.68  5249.8 1303.06
  5263.9  1304.6  5292.2 1309.75  5334.6 1314.72    5377 1321.02  5419.5 1322.82
#Mann= 9 ,-1 , 0
  3863.8    .035       0  4136.2     .07       0  4155.4    .035       0
  4425.8     .12       0    4464    .035       0  4726.5     .12       0
  4966.7     .05       0  5016.7     .12       0  5161.5     .07       0
Bank Sta=4966.7,5016.7
XS Rating Curve= 0 ,0
Exp/Cntr=0.3,0.1

Type RM Length L Ch R = 1 ,7929    ,559,559,559
BEGIN DESCRIPTION:
WEST SISTER CREEK 14.0
END DESCRIPTION:
XS GIS Cut Line= 3
      2055924.99     13905424.99        2055125.       13904675.
      2054924.99     13904274.99
#Sta/Elev= 30
  3903.2 1310.97  3981.1 1308.34  4016.3 1308.63  4037.7  1305.2  4058.1 1304.18
  4235.6  1296.9  4249.8 1295.87  4263.9 1293.13  4299.6 1294.36  4419.2  1292.9
  4603.4 1291.12  4813.1 1286.84  4858.4 1286.16    4915 1282.42  4944.3 1282.06
  4971.7 1279.57  4985.8 1275.38  5005.5 1274.91  5006.5 1274.41  5055.6 1274.91
  5058.5 1279.32  5075.2  1283.1  5103.2  1283.8  5114.8 1285.54  5147.9 1289.83
  5224.3 1293.11  5276.5 1295.09  5298.8  1298.1  5326.8 1304.23    5447 1318.18
#Mann= 9 ,-1 , 0
  3903.2     .07       0  4058.1    .035       0  4419.2     .07       0
  4813.1    .035       0  4944.3     .12       0  5005.5     .05       0
  5055.6     .12       0  5114.8    .035       0  5224.3     .07       0
Bank Sta=5005.5,5055.6
XS Rating Curve= 0 ,0
Exp/Cntr=0.3,0.1

Type RM Length L Ch R = 1 ,7370    ,560,560,560
BEGIN DESCRIPTION:
WEST SISTER CREEK 13.0
END DESCRIPTION:
XS GIS Cut Line= 3
        2056475.     13905874.99        2055525.       13904325.
      2055225.02     13904025.02
#Sta/Elev= 30
    3177 1378.95  3279.5 1376.21  3322.1 1365.57  3365.4 1359.59  3505.4 1349.78
  3648.9 1326.65  3698.2    1323  3832.7 1311.64  3864.8 1309.22  3896.5 1305.38
  3911.9 1300.07  3933.2 1300.24  3969.9 1297.01  4049.2  1296.8  4290.9 1289.78
    4621 1288.92  4760.6 1284.26  4800.4 1284.15  4886.6 1280.31  4923.4 1281.53
  4966.9 1274.15  4967.9 1273.65  5017.1 1274.15  5023.2 1281.21  5037.4 1284.01
  5079.8 1282.54  5108.1 1287.81  5221.2 1291.03  5376.8 1316.51  5419.2 1320.32
#Mann= 10 ,-1 , 0
    3177     .12       0  3365.4     .07       0  3698.2    .035       0
  3832.7     .07       0  3864.8    .035       0    4621     .07       0
  4760.6    .035       0  4800.4     .12       0  4966.9     .05       0
  5017.1     .12       0
Bank Sta=4966.9,5017.1
XS Rating Curve= 0 ,0
Exp/Cntr=0.3,0.1

Type RM Length L Ch R = 1 ,6810    ,539,539,539
BEGIN DESCRIPTION:
WEST SISTER CREEK 12.0
END DESCRIPTION:
XS GIS Cut Line= 3
      2056925.03     13905575.04        2055975.       13904025.
      2055174.97     13903774.99
#Sta/Elev= 30
  3182.2 1374.06  3226.7 1372.03  3289.4  1356.2  3422.1 1344.26  3489.5 1316.76
  3501.4 1313.69  3516.8 1304.32  3538.1 1300.14  3553.6 1293.22  3607.1 1288.15
  4126.1 1284.81  4227.1 1285.63  4269.8 1285.61  4507.3 1287.04  4739.1 1289.44
  4900.7 1280.25  4985.6 1274.39  4986.6 1273.89  5035.8 1274.39  5042.1 1279.54
  5063.1 1281.14  5178.3 1281.24    5346 1287.48  5422.6 1298.84  5486.9 1299.52
  5511.2  1305.4  5613.5 1318.02  5715.8 1325.27  5741.9 1328.24  5838.4 1339.32
#Mann= 16 ,-1 , 0
  3182.2     .07       0  3289.4    .035       0  3489.5     .12       0
  3607.1    .035       0  4126.1     .07       0  4227.1    .035       0
  4269.8     .07       0  4507.3    .035       0  4900.7     .07       0
  4985.6     .05       0  5035.8     .07       0  5422.6     .07       0
  5511.2     .12       0  5613.5     .07       0  5715.8     .12       0
  5741.9     .07       0
Bank Sta=4985.6,5035.8
XS Rating Curve= 0 ,0
Exp/Cntr=0.3,0.1

Type RM Length L Ch R = 1 ,6271    ,573,573,573
BEGIN DESCRIPTION:
WEST SISTER CREEK 11.0
END DESCRIPTION:
XS GIS Cut Line= 3
      2057278.27     13905277.38        2056375.       13903675.
      2055724.98     13903324.99
#Sta/Elev= 30
  3156.6 1345.53  3240.2 1345.37  3255.9 1345.08  3277.6 1337.33  3358.5 1291.19
  3374.4 1285.47  3402.2 1281.99  3901.8 1282.64  4043.2 1286.43  4126.4  1292.5
  4245.6 1296.93  4442.7 1288.65  4675.7 1288.63  4782.9 1285.88  4820.5 1288.25
  4901.4 1283.71  4960.7 1275.42  4982.3 1270.56  4984.7 1266.21  4985.7 1265.71
  5034.9 1266.21  5041.5 1274.16    5048 1276.86  5075.5 1280.36  5173.7 1276.47
  5422.2 1283.73  5540.4 1296.37  5578.5 1298.27  5676.7 1314.08  5734.3 1317.56
#Mann= 12 ,-1 , 0
  3156.6     .07       0  3240.2     .12       0  3402.2     .07       0
  3901.8    .035       0  4126.4     .07       0  4245.6    .035       0
  4442.7     .07       0  4675.7    .035       0  4984.7    .035       0
  5034.9    .035       0  5422.2    .035       0  5540.4     .12       0
#XS Ineff= 2 , 0
       0 4243.06 1297.35               0
Permanent Ineff=
       F       F
Bank Sta=4984.7,5034.9
XS Rating Curve= 0 ,0
Exp/Cntr=0.3,0.1

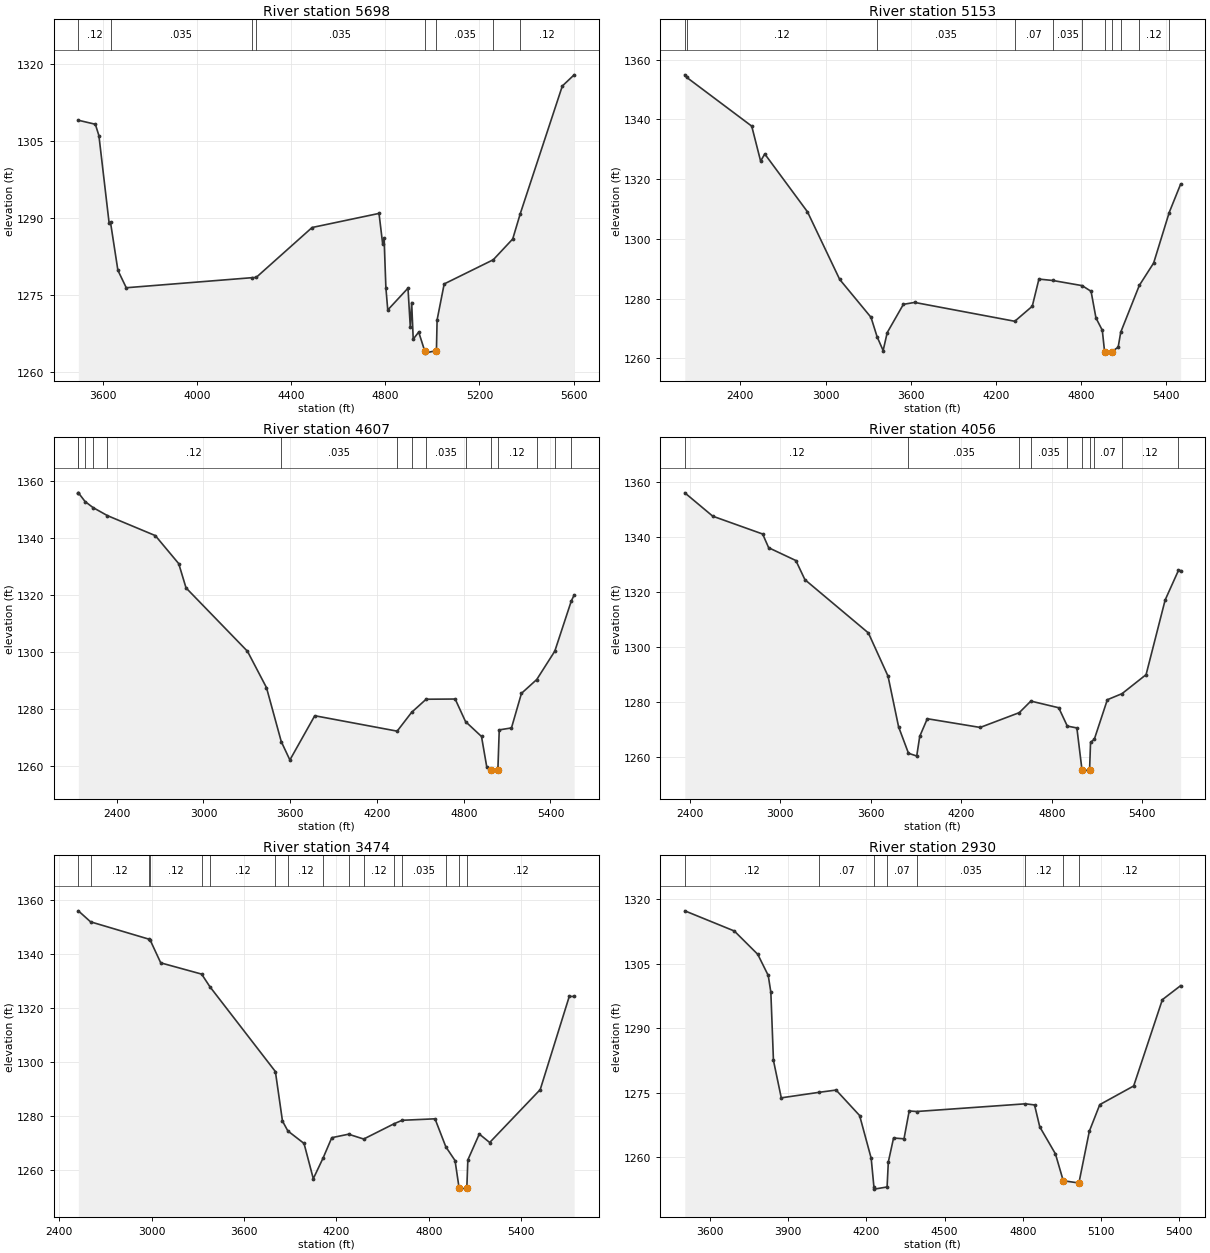
Type RM Length L Ch R = 1 ,5698    ,545,545,545
BEGIN DESCRIPTION:
WEST SISTER CREEK 10.0
END DESCRIPTION:
XS GIS Cut Line= 3
      2057670.33     13903937.88        2056375.       13903175.
      2055774.97       13903125.
#Sta/Elev= 30
  3496.7 1308.98    3569  1308.2  3584.1 1305.99  3627.6 1288.93  3633.3 1289.15
  3664.7 1279.81  3700.2 1276.42  4235.2 1278.38  4251.8 1278.42  4489.3 1288.13
  4773.5 1290.87  4789.2 1284.85    4795    1286  4802.7 1276.39  4810.6  1272.1
  4896.5 1276.34  4906.3  1268.8  4912.1 1273.55  4918.7 1266.43    4942  1267.8
    4967 1264.21    4968 1263.71  5017.3 1264.21  5020.1 1270.16  5050.2 1277.16
  5258.6 1281.86  5341.2  1285.9  5373.5 1290.85  5551.9 1315.64  5602.1 1317.81
#Mann= 8 ,-1 , 0
  3496.7     .12       0  3633.3    .035       0  4235.2     .07       0
  4251.8    .035       0    4967     .05       0  5017.3    .035       0
  5258.6    .035       0  5373.5     .12       0
Bank Sta=4967,5017.3
XS Rating Curve= 0 ,0
Exp/Cntr=0.3,0.1

Type RM Length L Ch R = 1 ,5153    ,546,546,546
BEGIN DESCRIPTION:
WEST SISTER CREEK 9.0
END DESCRIPTION:
XS GIS Cut Line= 3
       2059209.3     13901879.24        2056325.       13902675.
      2055824.96       13902675.
#Sta/Elev= 30
  2008.3 1354.93    2022 1354.07  2479.6 1337.76  2542.3 1326.06  2571.5 1328.45
  2872.3 1309.08  3099.2 1286.46  3319.8 1273.77  3362.7 1267.26  3405.2 1262.65
  3433.9 1268.65  3547.8 1278.12  3626.9 1278.76  4332.3 1272.45  4455.5 1277.48
  4502.4 1286.57  4600.3  1286.1  4806.6 1284.38  4869.7 1282.48  4904.1 1273.57
  4948.8 1269.43  4964.8 1262.29  4965.8 1261.79  5015.1 1262.29  5060.4 1263.76
  5078.7 1268.81  5209.5 1284.46  5310.4 1291.95  5419.9 1308.84  5500.4 1318.35
#Mann= 11 ,-1 , 0
  2008.3     .07       0    2022     .12       0  3362.7    .035       0
  4332.3     .07       0  4600.3    .035       0  4806.6     .12       0
  4964.8     .05       0  5015.1     .12       0  5078.7     .07       0
  5209.5     .12       0  5419.9     .07       0
Bank Sta=4964.8,5015.1
XS Rating Curve= 0 ,0
Exp/Cntr=0.3,0.1

Type RM Length L Ch R = 1 ,4607    ,551,551,551
BEGIN DESCRIPTION:
WEST SISTER CREEK 8.0
END DESCRIPTION:
XS GIS Cut Line= 3
      2059201.32     13901740.48        2056375.       13902175.
      2055825.01       13902325.
#Sta/Elev= 30
  2134.4 1355.74  2135.2 1355.72  2181.1 1352.68  2235.5 1350.59  2335.7 1347.74
  2666.9 1340.73  2828.8 1330.89  2879.4 1322.38  3304.3 1300.14  3435.8 1287.39
  3538.1 1268.44  3597.7 1261.99  3769.7 1277.52  4339.7 1272.11  4439.9 1278.72
  4540.1 1283.31    4741 1283.38  4812.7 1275.46  4923.1 1270.24  4959.8 1259.45
  4986.1 1258.58  4987.1 1258.08  5036.4 1258.58  5045.8 1272.55  5130.4 1273.24
  5199.5 1285.37  5305.3 1290.23  5430.1 1300.18  5543.7 1317.71    5564  1319.9
#Mann= 15 ,-1 , 0
  2134.4     .12       0  2135.2     .07       0  2181.1     .12       0
  2235.5     .07       0  2335.7     .12       0  3538.1    .035       0
  4339.7     .12       0  4439.9     .07       0  4540.1    .035       0
  4812.7     .12       0  4986.1     .05       0  5036.4     .12       0
  5305.3    .035       0  5430.1     .12       0  5543.7     .07       0
Bank Sta=4986.1,5036.4
XS Rating Curve= 0 ,0
Exp/Cntr=0.3,0.1

Type RM Length L Ch R = 1 ,4056    ,582,582,582
BEGIN DESCRIPTION:
WEST SISTER CREEK 7.0
END DESCRIPTION:
XS GIS Cut Line= 3
      2059150.21     13901540.88        2056525.       13901675.
      2055874.98       13901575.
#Sta/Elev= 30
    2367 1356.09  2552.4 1347.59  2882.9 1341.11  2922.9 1336.12  3103.2 1331.46
  3163.2  1324.5  3583.8 1305.13    3714 1289.41  3784.1 1270.96  3849.6 1261.36
  3904.2 1260.37  3924.2 1267.53  3974.3 1273.93  4324.8 1270.76  4583.9 1276.14
  4660.7 1280.34  4845.4 1277.92  4902.2 1271.25  4965.6 1270.58  4999.5 1255.37
  5000.5 1254.87  5049.9 1255.37  5056.3 1265.32  5081.3 1266.47  5167.6 1280.84
    5265 1283.05  5424.4 1289.96  5550.8 1317.13  5638.7 1327.85  5653.3 1327.81
#Mann= 10 ,-1 , 0
    2367     .12       0  3849.6    .035       0  4583.9     .07       0
  4660.7    .035       0  4902.2     .12       0  4999.5     .05       0
  5049.9     .12       0  5081.3     .07       0    5265     .12       0
  5638.7     .07       0
Bank Sta=4999.5,5049.9
XS Rating Curve= 0 ,0
Exp/Cntr=0.3,0.1

Type RM Length L Ch R = 1 ,3474    ,544,544,544
BEGIN DESCRIPTION:
WEST SISTER CREEK 6.0
END DESCRIPTION:
XS GIS Cut Line= 3
      2059099.76      13901193.9        2056625.       13901125.
      2055925.02     13901374.99
#Sta/Elev= 30
  2524.2 1356.01  2603.6 1351.93  2986.2 1345.44  2989.5 1345.29  3059.2 1336.71
  3324.7 1332.54  3377.6 1327.92  3803.5  1296.4  3849.5 1278.05  3884.3 1274.38
  3989.5 1269.73  4049.6 1256.66  4113.7 1264.39  4169.6 1271.87  4278.4 1273.16
  4376.9 1271.37  4573.9 1277.03    4626 1278.32  4839.9 1278.87  4910.1 1268.48
  4969.9 1263.38    4996 1253.29    4997 1252.79  5046.4 1253.29    5053 1263.62
  5127.3 1273.22  5194.8 1270.08  5522.9 1289.71  5711.4 1324.25  5743.2 1324.26
#Mann= 16 ,-1 , 0
  2524.2     .07       0  2603.6     .12       0  2986.2     .07       0
  2989.5     .12       0  3324.7     .07       0  3377.6     .12       0
  3803.5     .07       0  3884.3     .12       0  4113.7    .035       0
  4278.4     .07       0  4376.9     .12       0  4573.9     .07       0
    4626    .035       0  4910.1     .12       0    4996     .05       0
  5046.4     .12       0
Bank Sta=4996,5046.4
XS Rating Curve= 0 ,0
Exp/Cntr=0.3,0.1

Type RM Length L Ch R = 1 ,2930    ,582,582,582
BEGIN DESCRIPTION:
WEST SISTER CREEK 5.0
END DESCRIPTION:
XS GIS Cut Line= 3
      2058174.56     13900558.26        2056675.       13900625.
      2056275.05       13900625.
#Sta/Elev= 30
  3503.7 1317.27  3693.5 1312.58  3783.5 1307.15  3823.6 1302.24  3833.6 1298.35
  3843.6 1282.48  3873.6 1273.78  4019.3 1275.07  4083.8 1275.59  4173.9 1269.67
  4218.3 1259.73  4228.8 1253.05  4229.8 1252.55  4279.3 1253.05    4284 1258.86
  4304.1 1264.44  4344.1 1264.25  4364.1 1270.73  4392.5  1270.6  4809.7 1272.39
  4844.6 1272.13  4864.6 1267.04  4924.7 1260.75  4954.7  1254.5  5014.7 1253.98
  5054.7 1266.01  5094.7  1272.2  5224.7 1276.54  5334.7 1296.61  5404.7 1299.87
#Mann= 8 ,-1 , 0
  3503.7     .12       0  4019.3     .07       0  4228.8     .05       0
  4279.3     .07       0  4392.5    .035       0  4809.7     .12       0
  4954.7    .035       0  5014.7     .12       0
Bank Sta=4954.7,5014.7
XS Rating Curve= 0 ,0
Exp/Cntr=0.3,0.1

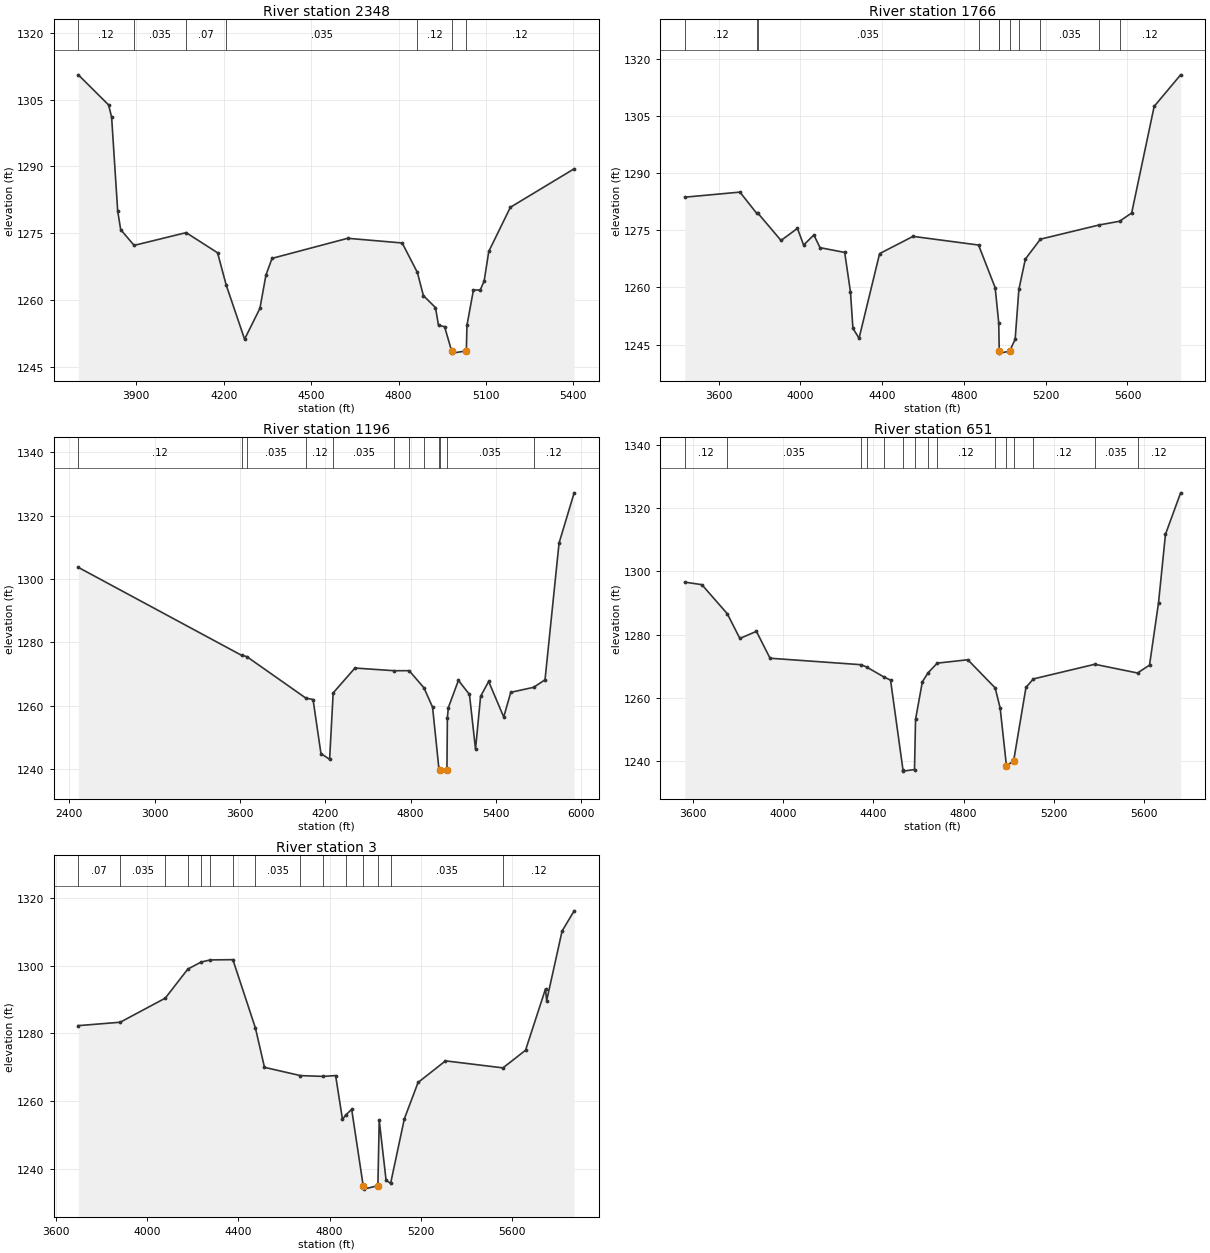
Type RM Length L Ch R = 1 ,2348    ,582,582,582
BEGIN DESCRIPTION:
WEST SISTER CREEK 4.0
END DESCRIPTION:
XS GIS Cut Line= 3
      2057924.96     13900424.99        2056675.       13900075.
      2056325.04     13900274.98
#Sta/Elev= 30
  3701.5 1310.54  3805.3 1303.79  3815.7 1301.06  3836.5 1280.02  3846.8 1275.82
  3892.9 1272.28  4071.3 1275.14  4179.2 1270.62  4208.5 1263.45  4271.9 1251.24
  4324.5 1258.16  4345.3 1265.66  4366.1 1269.37  4625.7 1273.87  4812.6 1272.82
  4864.7 1266.21  4885.3 1261.01  4926.8 1258.33  4937.2 1254.34    4958 1254.05
  4982.2 1248.61  4983.2 1248.11  5032.7 1248.61  5034.8 1254.34  5057.1 1262.29
  5080.2 1262.25  5093.8 1264.29  5109.7 1270.93  5183.8 1280.83  5402.6 1289.46
#Mann= 7 ,-1 , 0
  3701.5     .12       0  3892.9    .035       0  4071.3     .07       0
  4208.5    .035       0  4864.7     .12       0  4982.2     .05       0
  5032.7     .12       0
Bank Sta=4982.2,5032.7
XS Rating Curve= 0 ,0
Exp/Cntr=0.3,0.1

Type RM Length L Ch R = 1 ,1766    ,570,570,570
BEGIN DESCRIPTION:
WEST SISTER CREEK 3.0
END DESCRIPTION:
XS GIS Cut Line= 3
      2058333.39     13899681.11        2056775.       13899525.
      2055915.61     13899505.55
#Sta/Elev= 30
  3434.2 1283.69  3703.9 1285.02  3785.1 1279.52  3791.9 1279.49  3904.9 1272.33
  3985.3  1275.5  4015.5 1271.13  4065.7 1273.77  4095.9 1270.44  4216.5 1269.19
  4244.8 1258.78  4256.7 1249.25  4286.8 1246.67  4387.3 1268.88    4551  1273.4
  4871.4 1271.13  4952.7 1259.93  4970.1 1250.72  4972.6 1243.26  4973.6 1242.76
  5023.1 1243.26  5050.4 1246.38  5068.7 1259.49  5100.4 1267.45    5174 1272.67
  5462.8 1276.41  5561.3 1277.37  5620.5 1279.55  5730.6 1307.52    5860  1315.8
#Mann= 11 ,-1 , 0
  3434.2     .12       0  3785.1     .07       0  3791.9    .035       0
  4871.4     .12       0  4970.1     .12       0  4972.6     .05       0
  5023.1     .12       0  5068.7     .07       0    5174    .035       0
  5462.8     .07       0  5561.3     .12       0
Bank Sta=4972.6,5023.1
XS Rating Curve= 0 ,0
Exp/Cntr=0.3,0.1

Type RM Length L Ch R = 1 ,1196    ,545,545,545
BEGIN DESCRIPTION:
WEST SISTER CREEK 2.0
END DESCRIPTION:
XS GIS Cut Line= 3
      2059200.03     13899850.01        2056825.       13898975.
      2056175.03     13898275.03
#Sta/Elev= 30
  2464.2 1303.67  3611.9  1275.9    3648 1275.51  4063.5  1262.4  4114.6 1261.94
  4170.1 1244.88    4231 1243.04    4256 1264.02  4409.2 1271.88  4686.6 1271.03
  4790.4 1271.05  4894.3 1265.64  4954.9 1259.52  4999.1 1240.28  5005.5 1239.82
  5006.5 1239.32    5056 1239.82  5059.1 1256.17  5065.9 1259.39  5136.7 1267.98
  5214.4 1263.54  5256.9 1246.24  5292.6 1262.94  5349.3 1267.64  5455.3 1256.41
  5504.7 1264.21  5665.4 1265.79  5745.6 1268.16  5844.3 1311.36  5950.5 1327.22
#Mann= 12 ,-1 , 0
  2464.2     .12       0  3611.9     .07       0    3648    .035       0
  4063.5     .12       0    4256    .035       0  4686.6     .07       0
  4790.4     .12       0  4894.3     .12       0  4999.1    .035       0
  5005.5    .035       0    5056    .035       0  5665.4     .12       0
Bank Sta=5005.5,5056
XS Rating Curve= 0 ,0
Exp/Cntr=0.3,0.1

Type RM Length L Ch R = 1 ,651     ,636,636,636
BEGIN DESCRIPTION:
WEST SISTER CREEK 1.0
END DESCRIPTION:
XS GIS Cut Line= 3
      2058399.99       13898650.        2056975.       13898475.
      2056274.98     13898174.99
#Sta/Elev= 30
  3564.3 1296.61  3639.9 1295.81  3752.7 1286.61  3808.3 1278.79  3881.7 1281.04
  3942.1 1272.54  4346.2 1270.49  4370.4 1269.74  4445.2 1266.68  4476.1 1265.61
    4531 1237.33    4532 1236.83  4582.3 1237.33  4586.9  1253.2  4617.1 1265.11
    4643 1267.98    4683 1270.99  4818.6 1272.06  4939.8 1263.14  4961.9 1256.76
  4989.9 1238.38  5021.8 1240.16  5076.2  1263.3  5108.8 1265.99  5381.3 1270.63
  5570.5 1267.87  5623.8 1270.37  5663.7 1290.11  5694.5 1311.75  5761.6 1324.86
#Mann= 15 ,-1 , 0
  3564.3     .12       0  3752.7    .035       0  4346.2     .12       0
  4370.4     .12       0  4445.2     .12       0    4531     .05       0
  4582.3     .12       0    4643     .12       0    4683     .12       0
  4939.8     .12       0  4989.9    .035       0  5021.8     .12       0
  5108.8     .12       0  5381.3    .035       0  5570.5     .12       0
Bank Sta=4989.9,5021.8
XS Rating Curve= 0 ,0
Exp/Cntr=0.3,0.1

Type RM Length L Ch R = 1 ,3       ,0,0,0
BEGIN DESCRIPTION:
WEST SISTER CREEK 0.0
END DESCRIPTION:
XS GIS Cut Line= 3
      2058315.99     13898030.51      2057022.73     13897877.28
      2056152.18     13897810.58
#Sta/Elev= 30
  3697.7 1282.32  3881.3 1283.32  4079.1 1290.42    4178 1298.99  4236.1 1301.07
  4276.8  1301.7  4375.7 1301.78  4474.6 1281.63  4514.4 1270.02  4672.4 1267.58
  4771.3 1267.35  4826.5 1267.59  4856.7 1254.64  4870.2 1255.92    4897 1257.63
  4947.5  1235.1    4949  1234.1    5012  1235.1  5017.8 1254.45  5047.9 1236.75
  5067.8 1235.79  5128.1 1254.85  5188.3 1265.56  5308.6 1271.93  5560.8 1269.86
  5659.7 1275.06  5747.4 1293.16  5752.4 1289.69  5820.1 1310.21  5873.1 1316.18
#Mann= 15 ,-1 , 0
  3697.7     .07       0  3881.3    .035       0  4079.1     .07       0
    4178     .12       0  4236.1     .07       0  4276.8     .12       0
  4375.7     .07       0  4474.6    .035       0  4672.4     .12       0
  4771.3     .12       0  4870.2     .12       0  4947.5     .05       0
    5012     .12       0  5067.8    .035       0  5560.8     .12       0
Bank Sta=4947.5,5012
XS Rating Curve= 0 ,0
Exp/Cntr=0.3,0.1

Chan Stop Cuts=-1
Use User Specified Reach Order=0
Composite Channel Slope=5