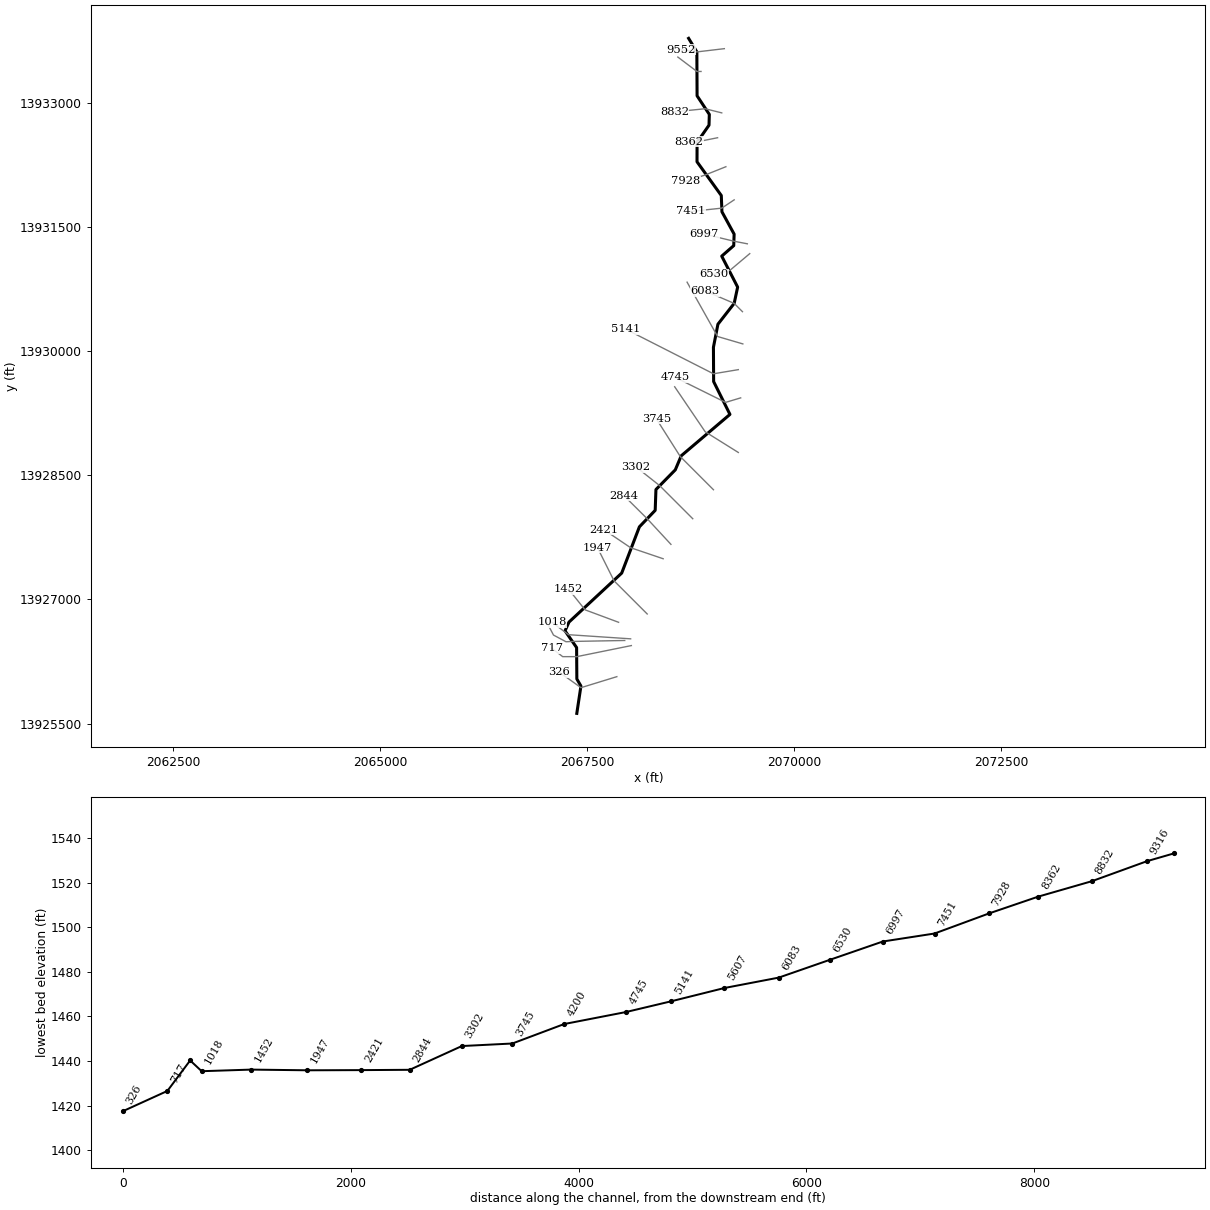
--- WILLIE CREEK.prj (project) ---

Proj Title=WILLIE CREEK Base Level Engineering
Current Plan=p01
Default Exp/Contr=0.3,0.1
English Units
Geom File=g01
Flow File=f01
Plan File=p01
BEGIN DESCRIPTION:
WILLIE CREEK
END DESCRIPTION:

--- WILLIE CREEK.p01 (plan) ---

Plan Title=Multiple Run
Short Identifier=Multiple
Geom File=g01
Flow File=f01
Subcritical Flow
K Sum by GR= 0
Std Step Tol= 0.01
Critical Tol= 0.01
Num of Std Step Trials= 20
Max Error Tol= 0.3
Flow Tol Ratio= 0.001
Split Flow NTrial= 30
Split Flow Tol= 0.02
Split Flow Ratio= 0.02
Log Output Level= 0
Friction Slope Method= 1
Unsteady Friction Slope Method= 2
Unsteady Bridges Friction Slope Method= 1
Parabolic Critical Depth
Global Vel Dist=  1 , 1 , 1
Global Log Level= 0
CheckData=True
Encroach Param= -1, 0, 0, 0
BEGIN DESCRIPTION:
Multiple Run
END DESCRIPTION:

--- WILLIE CREEK.f01 (steady flow) ---

Flow Title=Multiple
Number of Profiles=7
Profile Names=10-year,25-year,50-year,1pct_min,100-year,1pct_plu,500-year
River Rch & RM= WILLIE CREEK,Reach-1,9552
    1243    2167    3072    2115    4220    8419    7892
River Rch & RM= WILLIE CREEK,Reach-1,6083
    2502    4503    6523    4575    9129   18215   17739
River Rch & RM= WILLIE CREEK,Reach-1,4200
    2803    5055    7330    5144   10263   20477   19960
Boundary for River Rch & Prof#=WILLIE CREEK,Reach-1,1
Up Type=0
Dn Type=3
Dn Slope=0.005
Boundary for River Rch & Prof#=WILLIE CREEK,Reach-1,2
Up Type=0
Dn Type=3
Dn Slope=0.005
Boundary for River Rch & Prof#=WILLIE CREEK,Reach-1,3
Up Type=0
Dn Type=3
Dn Slope=0.005
Boundary for River Rch & Prof#=WILLIE CREEK,Reach-1,4
Up Type=0
Dn Type=3
Dn Slope=0.005
Boundary for River Rch & Prof#=WILLIE CREEK,Reach-1,5
Up Type=0
Dn Type=3
Dn Slope=0.005
Boundary for River Rch & Prof#=WILLIE CREEK,Reach-1,6
Up Type=0
Dn Type=3
Dn Slope=0.005
Boundary for River Rch & Prof#=WILLIE CREEK,Reach-1,7
Up Type=0
Dn Type=3
Dn Slope=0.005

--- WILLIE CREEK.g01 (geometry) ---

Geom Title=Existing Conditions

River Reach=WILLIE CREEK,Reach-1
Reach XY= 30
      2068725.00     13933775.00      2068824.46     13933611.14
      2068827.24     13933080.93      2068974.93     13932856.77
      2068971.26     13932726.56      2068827.18     13932519.55
      2068826.36     13932284.65      2069119.54     13931877.45
      2069127.26     13931680.94      2069274.47     13931411.13
      2069269.65     13931272.30      2069124.60     13931145.27
      2069316.93     13930771.70      2069275.00     13930575.00
      2069078.75     13930323.45      2069024.64     13930045.15
      2069027.06     13929630.86      2069224.04     13929234.61
      2068635.76     13928734.68      2068564.24     13928565.32
      2068330.46     13928327.45      2068321.46     13928076.46
      2068130.83     13927877.30      2067917.14     13927318.83
      2067280.80     13926727.30      2067232.78     13926621.60
      2067372.65     13926419.48      2067375.52     13926040.22
      2067424.93     13925954.97      2067375.00     13925625.00

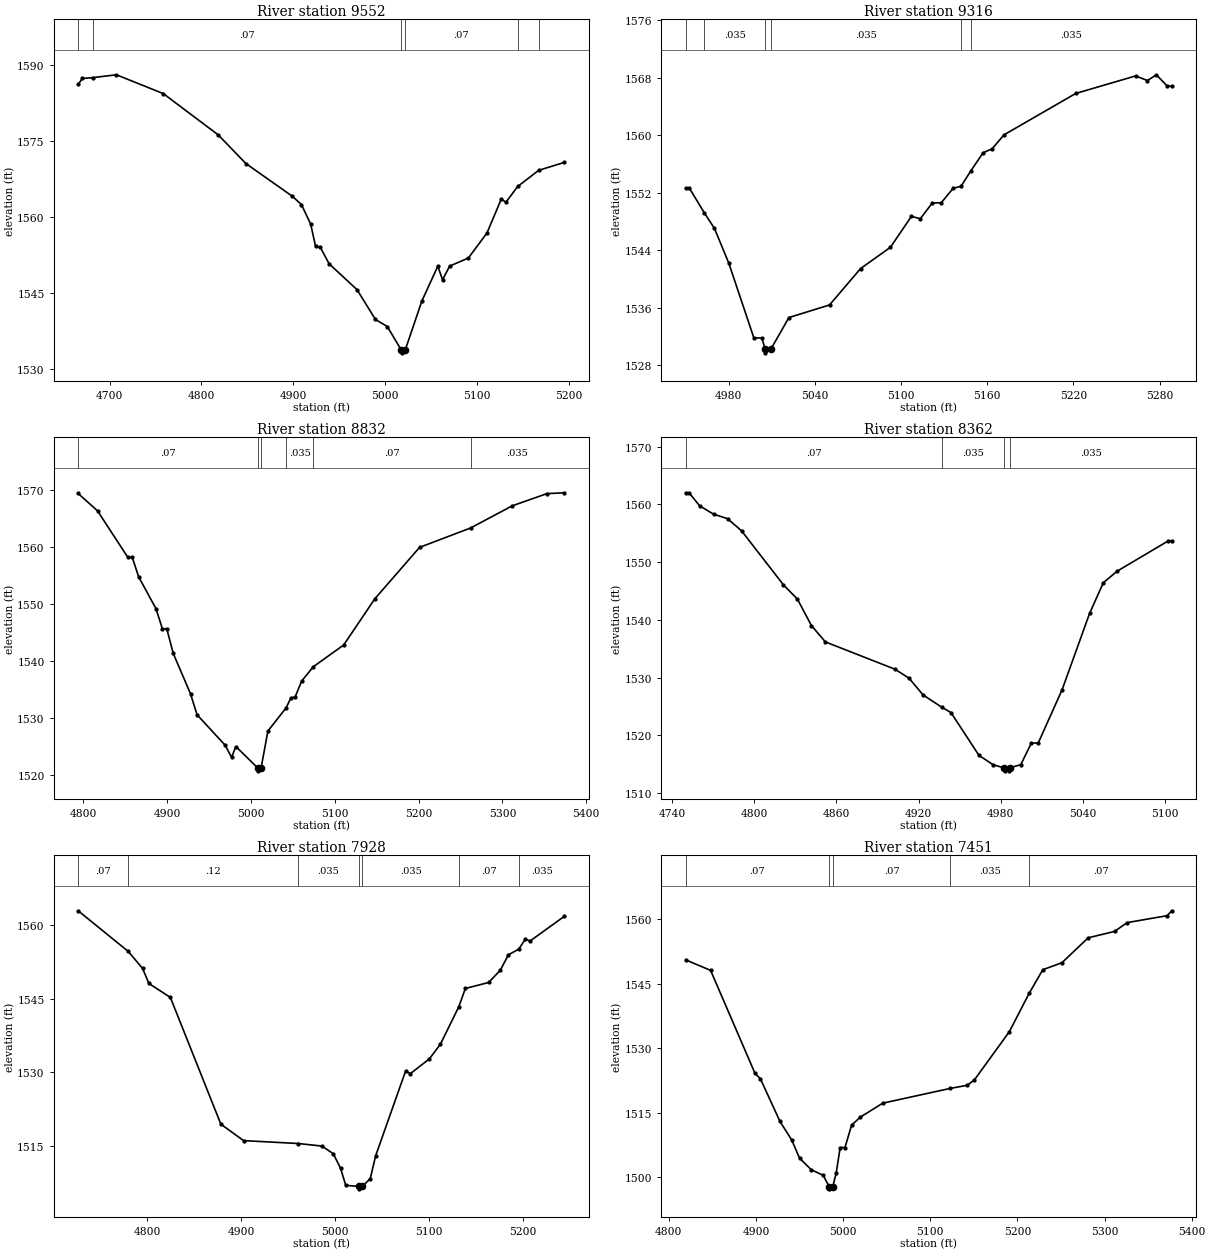
Type RM Length L Ch R = 1,9552,236,236,236
BEGIN DESCRIPTION:
WILLIE CREEK 21.0
END DESCRIPTION:
XS GIS Cut Line= 3
      2069156.36     13933650.34      2068824.46     13933611.14
      2068631.73     13933640.10
#Sta/Elev= 30
  4665.8 1586.12  4670.4 1587.29  4681.9 1587.46  4707.4 1588.02  4758.4 1584.32
  4818.2 1576.19  4848.4 1570.53  4898.8 1564.11  4908.8 1562.46  4918.9 1558.61
  4924.2 1554.22  4929.2 1554.09  4939.0 1550.78  4969.3 1545.70  4989.4 1539.82
  5002.3 1538.43  5017.7 1533.75  5017.9 1533.25  5021.7 1533.75  5039.9 1543.45
  5057.3 1550.33  5062.4 1547.64  5070.2 1550.34  5090.5 1551.92  5110.7 1556.83
  5126.4 1563.55  5131.4 1562.90  5144.2 1566.02  5167.1 1569.20  5194.9 1570.76
#Mann=6,-1,0
  4665.8   0.035       0  4681.9    0.07       0  5017.7    0.05       0
  5021.7    0.07       0  5144.2   0.035       0  5167.1    0.07       0
Bank Sta=5017.7,5021.7
Exp/Cntr=0.3,0.1

Type RM Length L Ch R = 1,9316,484,484,484
BEGIN DESCRIPTION:
WILLIE CREEK 20.0
END DESCRIPTION:
XS GIS Cut Line= 3
      2068875.01     13933375.00      2068825.00     13933375.00
      2068594.89     13933548.99
#Sta/Elev= 30
  4950.0 1552.69  4952.5 1552.69  4963.0 1549.22  4970.0 1547.08  4980.0 1542.25
  4997.5 1531.83  5003.1 1531.83  5005.3 1530.26  5005.5 1529.76  5009.3 1530.26
  5021.9 1534.67  5050.2 1536.42  5071.8 1541.48  5092.6 1544.44  5107.2 1548.74
  5113.4 1548.41  5121.7 1550.59  5128.0 1550.64  5136.3 1552.65  5141.7 1552.91
  5148.4 1555.01  5157.1 1557.58  5163.4 1558.14  5171.7 1560.08  5221.6 1565.83
  5263.3 1568.27  5271.6 1567.63  5277.8 1568.43  5285.3 1566.86  5288.5 1566.86
#Mann=6,-1,0
  4950.0    0.07       0  4963.0   0.035       0  5005.3   0.035       0
  5009.3   0.035       0  5141.7    0.07       0  5148.4   0.035       0
Bank Sta=5005.3,5009.3
Exp/Cntr=0.3,0.1

Type RM Length L Ch R = 1,8832,470,470,470
BEGIN DESCRIPTION:
WILLIE CREEK 19.0
END DESCRIPTION:
XS GIS Cut Line= 3
      2069125.03     13932874.99      2068925.00     13932925.00
      2068553.27     13932887.54
#Sta/Elev= 30
  4793.9 1569.33  4817.1 1566.27  4853.2 1558.13  4858.4 1558.15  4866.1 1554.72
  4886.7 1549.17  4894.4 1545.62  4899.6 1545.65  4907.3 1541.33  4927.9 1534.26
  4935.7 1530.59  4969.2 1525.26  4976.9 1523.13  4982.0 1525.03  5008.1 1521.27
  5008.4 1520.77  5012.1 1521.27  5020.2 1527.73  5042.0 1531.81  5047.6 1533.53
  5052.7 1533.70  5060.4 1536.47  5074.5 1539.01  5110.6 1542.80  5147.7 1550.88
  5201.1 1559.89  5261.9 1563.28  5311.7 1567.17  5353.0 1569.30  5373.7 1569.45
#Mann=6,-1,0
  4793.9    0.07       0  5008.1    0.05       0  5012.1    0.07       0
  5042.0   0.035       0  5074.5    0.07       0  5261.9   0.035       0
Bank Sta=5008.1,5012.1
Exp/Cntr=0.3,0.1

Type RM Length L Ch R = 1,8362,434,434,434
BEGIN DESCRIPTION:
WILLIE CREEK 18.0
END DESCRIPTION:
XS GIS Cut Line= 3
      2069074.98     13932575.00      2068825.00     13932525.00
      2068725.03     13932525.00
#Sta/Elev= 30
  4749.9 1562.03  4752.4 1562.03  4760.1 1559.77  4770.3 1558.32  4780.5 1557.54
  4790.7 1555.44  4821.3 1546.07  4831.5 1543.60  4841.7 1539.03  4851.9 1536.19
  4902.8 1531.45  4913.0 1529.90  4923.2 1527.01  4936.8 1524.88  4943.6 1523.95
  4964.0 1516.54  4974.2 1514.93  4982.4 1514.35  4982.7 1513.85  4986.2 1513.85
  4986.4 1514.35  4994.6 1514.93  5002.3 1518.67  5007.3 1518.67  5024.8 1527.94
  5044.8 1541.13  5054.8 1546.43  5064.8 1548.43  5102.3 1553.70  5104.8 1553.70
#Mann=4,-1,0
  4749.9    0.07       0  4936.8   0.035       0  4982.4   0.035       0
  4986.4   0.035       0
Bank Sta=4982.4,4986.4
Exp/Cntr=0.3,0.1

Type RM Length L Ch R = 1,7928,477,477,477
BEGIN DESCRIPTION:
WILLIE CREEK 17.0
END DESCRIPTION:
XS GIS Cut Line= 3
      2069174.97     13932224.99      2068925.00     13932125.00
      2068688.42     13932047.75
#Sta/Elev= 30
  4726.2 1562.89  4779.5 1554.63  4794.8 1551.17  4801.6 1548.09  4824.5 1545.24
  4878.3 1519.44  4902.5 1516.09  4960.8 1515.50  4986.0 1514.98  4998.1 1513.42
  5005.9 1510.46  5011.4 1506.98  5025.0 1506.77  5025.2 1506.27  5029.0 1506.77
  5037.5 1508.33  5043.3 1513.01  5075.1 1530.21  5080.4 1529.74  5100.6 1532.75
  5112.3 1535.72  5131.9 1543.34  5138.9 1547.07  5163.7 1548.29  5176.1 1550.77
  5184.8 1553.92  5195.8 1555.08  5202.7 1557.08  5208.0 1556.75  5244.3 1561.75
#Mann=7,-1,0
  4726.2    0.07       0  4779.5    0.12       0  4960.8   0.035       0
  5025.0   0.035       0  5029.0   0.035       0  5131.9    0.07       0
  5195.8   0.035       0
Bank Sta=5025,5029
Exp/Cntr=0.3,0.1

Type RM Length L Ch R = 1,7451,454,454,454
BEGIN DESCRIPTION:
WILLIE CREEK 16.0
END DESCRIPTION:
XS GIS Cut Line= 3
      2069275.02     13931825.01      2069125.00     13931725.00
      2068749.68     13931684.44
#Sta/Elev= 30
  4819.3 1550.53  4847.9 1548.09  4898.9 1524.11  4905.0 1522.89  4927.5 1512.95
  4941.0 1508.63  4950.0 1504.39  4963.5 1501.71  4977.1 1500.42  4984.0 1497.77
  4984.3 1497.27  4988.1 1497.77  4992.1 1501.05  4996.6 1506.88  5002.1 1506.88
  5009.7 1512.08  5019.7 1513.95  5045.5 1517.20  5123.1 1520.64  5142.3 1521.35
  5150.5 1522.58  5190.7 1533.82  5213.6 1542.80  5229.1 1548.24  5251.1 1549.87
  5281.2 1555.67  5311.4 1557.14  5325.9 1559.20  5371.8 1560.81  5377.1 1561.95
#Mann=5,-1,0
  4819.3    0.07       0  4984.0    0.05       0  4988.1    0.07       0
  5123.1   0.035       0  5213.6    0.07       0
Bank Sta=4984,4988.1
Exp/Cntr=0.3,0.1

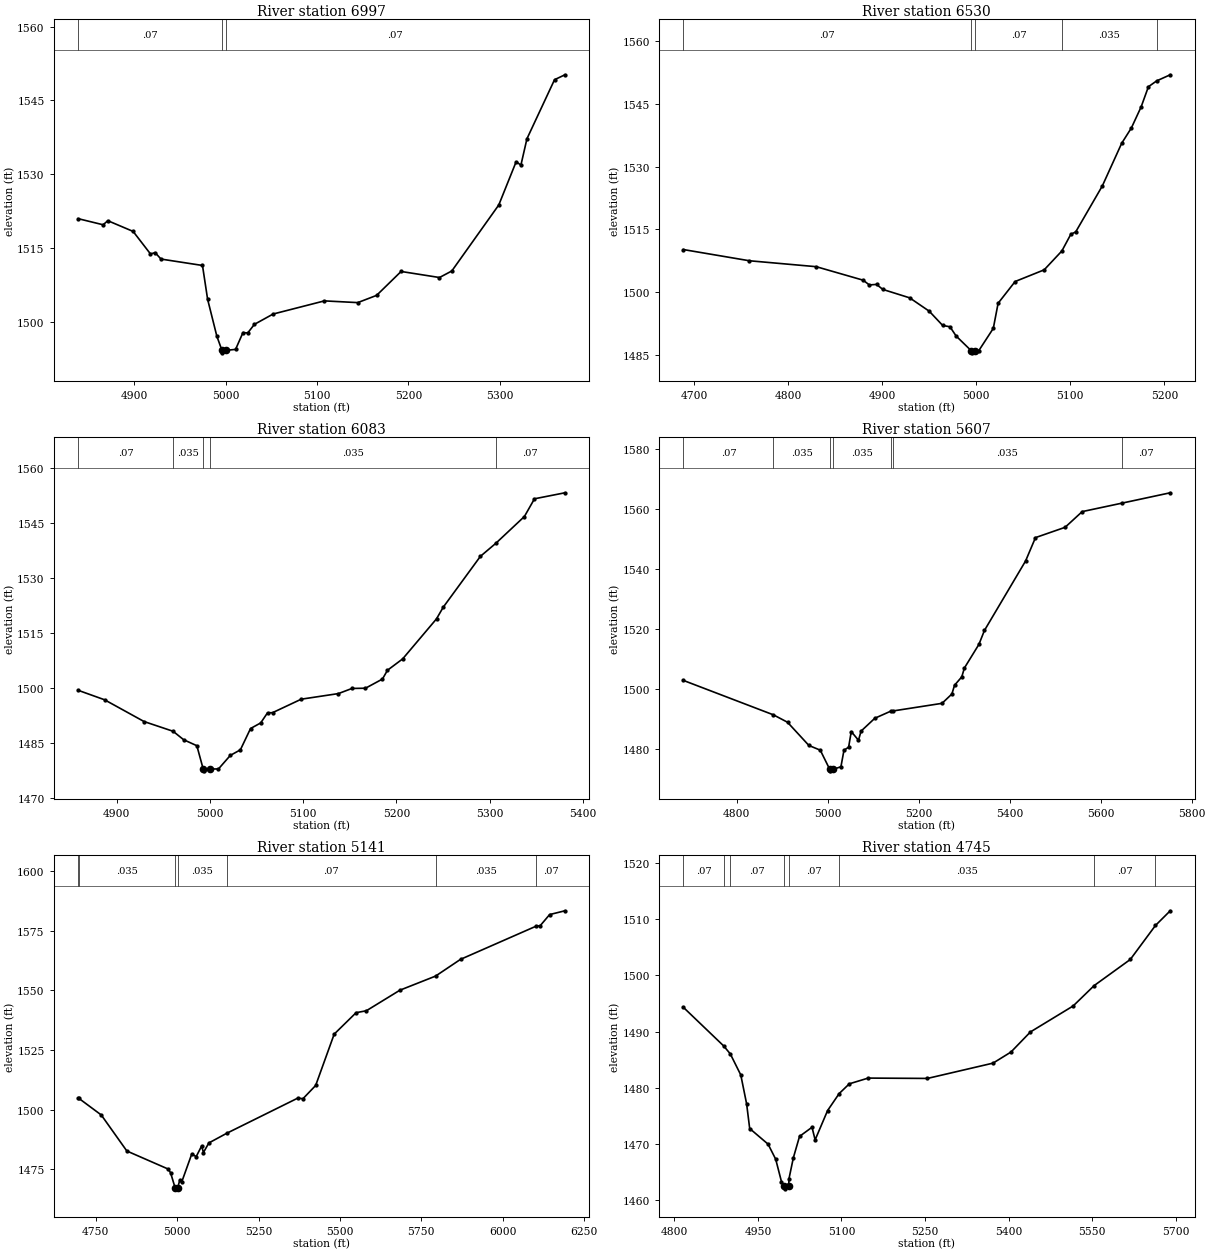
Type RM Length L Ch R = 1,6997,467,467,467
BEGIN DESCRIPTION:
WILLIE CREEK 15.0
END DESCRIPTION:
XS GIS Cut Line= 3
      2069433.98     13931294.29      2069275.00     13931325.00
      2068914.59     13931411.62
#Sta/Elev= 30
  4838.6 1520.95  4865.9 1519.71  4871.0 1520.54  4898.7 1518.36  4917.7 1513.78
  4922.8 1514.05  4929.2 1512.74  4974.6 1511.44  4980.2 1504.57  4990.3 1497.07
  4995.9 1494.18  4996.2 1493.68  5000.0 1494.18  5010.8 1494.38  5018.9 1497.80
  5024.1 1497.72  5031.4 1499.47  5051.9 1501.57  5108.0 1504.24  5144.5 1503.89
  5165.1 1505.36  5191.9 1510.22  5233.9 1508.99  5247.4 1510.32  5298.8 1523.74
  5317.8 1532.53  5323.0 1531.83  5329.6 1537.19  5359.8 1549.20  5371.2 1550.20
#Mann=3,-1,0
  4838.6    0.07       0  4995.9    0.05       0  5000.0    0.07       0
Bank Sta=4995.9,5000
Exp/Cntr=0.3,0.1

Type RM Length L Ch R = 1,6530,447,447,447
BEGIN DESCRIPTION:
WILLIE CREEK 14.0
END DESCRIPTION:
XS GIS Cut Line= 3
      2069462.96     13931175.74      2069225.00     13930975.00
      2069024.98     13930924.99
#Sta/Elev= 30
  4688.7 1510.15  4758.8 1507.47  4829.9 1506.05  4879.7 1502.82  4886.3 1501.68
  4894.0 1501.81  4900.6 1500.61  4929.2 1498.59  4950.0 1495.39  4964.3 1491.97
  4972.0 1491.67  4978.6 1489.44  4994.7 1485.92  4995.0 1485.42  4998.8 1485.92
  5002.6 1485.92  5018.1 1491.28  5023.2 1497.29  5041.3 1502.50  5072.2 1505.30
  5091.0 1509.82  5100.5 1513.81  5105.7 1514.38  5134.0 1525.39  5154.6 1535.61
  5164.9 1539.28  5175.3 1544.34  5183.0 1549.15  5191.8 1550.55  5206.2 1552.01
#Mann=5,-1,0
  4688.7    0.07       0  4994.7    0.05       0  4998.8    0.07       0
  5091.0   0.035       0  5191.8    0.07       0
Bank Sta=4994.7,4998.8
Exp/Cntr=0.3,0.1

Type RM Length L Ch R = 1,6083,476,476,476
BEGIN DESCRIPTION:
WILLIE CREEK 13.0
END DESCRIPTION:
XS GIS Cut Line= 3
      2069374.98     13930475.02      2069275.00     13930575.00
      2068924.99     13930725.00
#Sta/Elev= 30
  4858.6 1499.42  4886.9 1496.84  4929.3 1490.90  4960.4 1488.25  4971.7 1485.95
  4985.9 1484.31  4992.7 1477.96  4993.2 1477.46  5000.3 1477.96  5009.1 1477.98
  5021.8 1481.67  5032.6 1483.19  5043.5 1489.00  5054.4 1490.53  5061.7 1493.28
  5067.1 1493.32  5097.9 1497.00  5137.8 1498.53  5152.3 1499.93  5166.8 1499.99
  5185.0 1502.49  5190.4 1504.89  5206.7 1507.99  5243.0 1518.91  5250.2 1522.08
  5290.1 1535.96  5306.5 1539.48  5337.3 1546.82  5348.1 1551.65  5380.8 1553.29
#Mann=5,-1,0
  4858.6    0.07       0  4960.4   0.035       0  4992.7   0.035       0
  5000.3   0.035       0  5306.5    0.07       0
Bank Sta=4992.7,5000.3
Exp/Cntr=0.3,0.1

Type RM Length L Ch R = 1,5607,466,466,466
BEGIN DESCRIPTION:
WILLIE CREEK 12.0
END DESCRIPTION:
XS GIS Cut Line= 3
      2069379.59     13930085.68      2069075.00     13930175.00
      2068706.60     13930831.13
#Sta/Elev= 30
  4683.0 1502.90  4880.8 1491.44  4911.7 1488.98  4958.7 1481.25  4983.7 1479.68
  5004.5 1473.30  5005.0 1472.80  5012.2 1473.30  5029.1 1474.17  5035.8 1479.67
  5046.0 1480.68  5051.8 1485.87  5067.7 1482.99  5073.4 1486.03  5103.6 1490.31
  5138.8 1492.68  5143.1 1492.73  5251.4 1495.28  5273.0 1498.39  5278.8 1501.30
  5294.7 1504.09  5300.5 1507.05  5332.4 1514.91  5344.5 1519.54  5435.0 1542.69
  5456.7 1550.46  5521.8 1553.89  5559.4 1559.12  5646.5 1561.93  5752.9 1565.39
#Mann=7,-1,0
  4683.0    0.07       0  4880.8   0.035       0  5004.5   0.035       0
  5012.2   0.035       0  5138.8    0.07       0  5143.1   0.035       0
  5646.5    0.07       0
Bank Sta=5004.5,5012.2
Exp/Cntr=0.3,0.1

Type RM Length L Ch R = 1,5141,396,396,396
BEGIN DESCRIPTION:
WILLIE CREEK 11.0
END DESCRIPTION:
XS GIS Cut Line= 3
      2069324.97     13929775.00      2069025.00     13929725.00
      2067962.99     13930264.94
#Sta/Elev= 30
  4695.8 1504.79  4697.2 1504.79  4766.7 1497.77  4845.3 1482.69  4972.0 1475.15
  4979.6 1473.60  4993.4 1467.35  4993.9 1466.85  5001.3 1467.35  5008.2 1470.56
  5013.8 1469.69  5044.8 1481.47  5058.3 1480.33  5075.0 1484.78  5080.6 1482.06
  5097.2 1486.06  5152.0 1490.10  5370.1 1504.81  5386.5 1504.60  5425.4 1510.13
  5482.3 1531.62  5549.6 1540.60  5581.1 1541.40  5684.2 1550.01  5793.7 1555.91
  5870.4 1562.92  6102.4 1576.80  6115.2 1577.01  6144.2 1581.67  6191.3 1583.26
#Mann=7,-1,0
  4695.8    0.07       0  4697.2   0.035       0  4993.4   0.035       0
  5001.3   0.035       0  5152.0    0.07       0  5793.7   0.035       0
  6102.4    0.07       0
Bank Sta=4993.4,5001.3
Exp/Cntr=0.3,0.1

Type RM Length L Ch R = 1,4745,545,545,545
BEGIN DESCRIPTION:
WILLIE CREEK 10.0
END DESCRIPTION:
XS GIS Cut Line= 3
      2069353.58     13929434.24      2069171.28     13929379.55
      2068558.83     13929683.37
#Sta/Elev= 30
  4816.3 1494.30  4888.5 1487.45  4900.4 1486.03  4919.2 1482.29  4929.7 1477.14
  4935.2 1472.76  4968.2 1469.98  4981.9 1467.30  4992.3 1463.29  4997.3 1462.53
  4997.8 1462.03  5005.2 1462.53  5005.8 1463.85  5013.6 1467.55  5024.7 1471.36
  5047.1 1472.98  5052.7 1470.74  5075.1 1475.96  5095.9 1478.98  5114.1 1480.71
  5147.9 1481.73  5254.4 1481.67  5372.1 1484.39  5404.3 1486.36  5439.3 1489.94
  5516.0 1494.56  5553.8 1498.19  5618.6 1502.83  5663.8 1508.88  5690.3 1511.49
#Mann=8,-1,0
  4816.3    0.07       0  4888.5   0.035       0  4900.4    0.07       0
  4997.3    0.05       0  5005.2    0.07       0  5095.9   0.035       0
  5553.8    0.07       0  5663.8   0.035       0
Bank Sta=4997.3,5005.2
Exp/Cntr=0.3,0.1

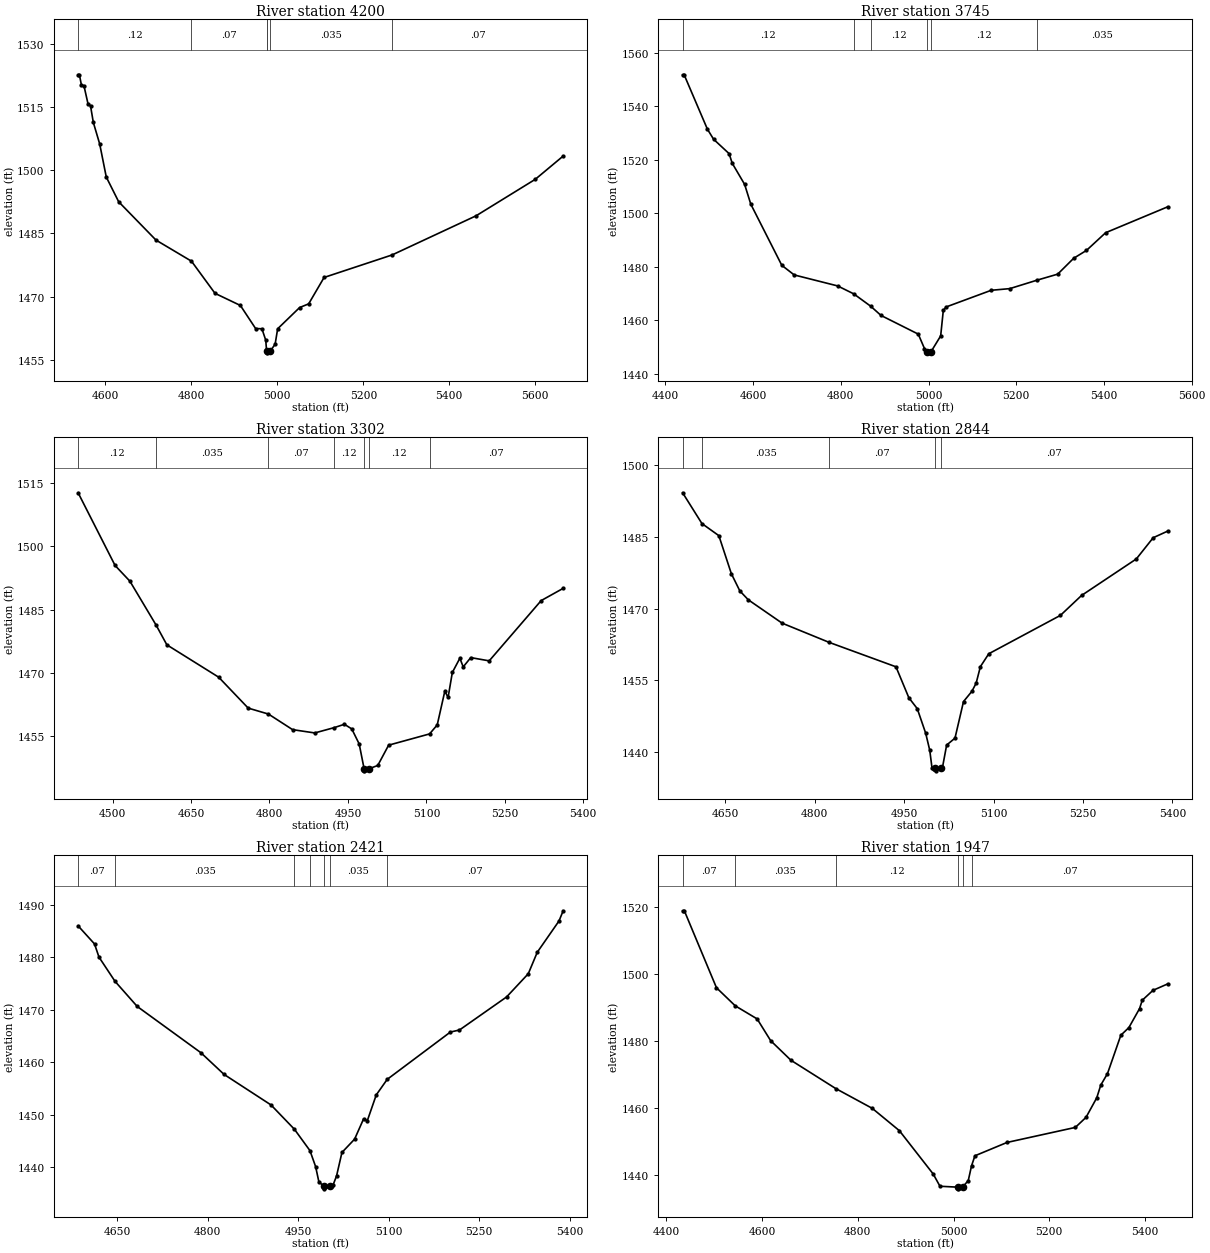
Type RM Length L Ch R = 1,4200,455,455,455
BEGIN DESCRIPTION:
WILLIE CREEK 9.0
END DESCRIPTION:
XS GIS Cut Line= 3
      2069325.04     13928774.98      2068925.00     13929025.00
      2068556.71     13929568.29
#Sta/Elev= 30
  4536.7 1522.70  4539.7 1522.70  4544.4 1520.27  4550.3 1520.09  4559.7 1515.81
  4565.6 1515.30  4572.1 1511.37  4586.9 1506.26  4602.2 1498.40  4631.1 1492.51
  4717.8 1483.41  4800.4 1478.39  4855.1 1470.75  4914.1 1467.87  4949.5 1462.39
  4964.2 1462.33  4973.1 1459.61  4974.9 1457.24  4975.0 1457.11  4975.5 1456.61
  4984.1 1457.11  4994.9 1458.66  5000.8 1462.33  5051.9 1467.38  5072.9 1468.25
  5108.8 1474.53  5267.0 1479.88  5462.2 1489.18  5599.9 1497.85  5664.8 1503.38
#Mann=6,-1,0
  4536.7    0.12       0  4800.4    0.07       0  4974.9   0.035       0
  4975.0   0.035       0  4984.1   0.035       0  5267.0    0.07       0
Bank Sta=4975,4984.1
Exp/Cntr=0.3,0.1

Type RM Length L Ch R = 1,3745,443,443,443
BEGIN DESCRIPTION:
WILLIE CREEK 8.0
END DESCRIPTION:
XS GIS Cut Line= 3
      2069024.98     13928325.02      2068625.00     13928725.00
      2068335.41     13929181.42
#Sta/Elev= 30
  4439.1 1551.71  4442.6 1551.71  4495.6 1531.40  4509.8 1527.62  4545.1 1522.26
  4552.2 1518.68  4580.5 1510.78  4594.6 1503.38  4665.3 1480.55  4693.6 1476.96
  4792.6 1472.86  4829.2 1469.91  4868.0 1465.28  4891.6 1461.83  4976.5 1454.86
  4990.6 1449.49  4996.6 1448.37  4997.1 1447.87  5005.9 1448.37  5027.6 1454.19
  5033.6 1463.72  5040.3 1465.02  5142.9 1471.23  5185.2 1471.85  5248.0 1475.04
  5294.5 1477.26  5330.9 1483.18  5360.1 1486.12  5403.8 1492.73  5545.3 1502.40
#Mann=6,-1,0
  4439.1    0.12       0  4829.2    0.07       0  4868.0    0.12       0
  4996.6    0.05       0  5005.9    0.12       0  5248.0   0.035       0
Bank Sta=4996.6,5005.9
Exp/Cntr=0.3,0.1

Type RM Length L Ch R = 1,3302,458,458,458
BEGIN DESCRIPTION:
WILLIE CREEK 7.0
END DESCRIPTION:
XS GIS Cut Line= 3
      2068774.97     13927975.03      2068375.00     13928375.00
      2068091.40     13928599.58
#Sta/Elev= 30
  4434.1 1512.69  4504.8 1495.44  4533.1 1491.72  4582.9 1481.37  4603.8 1476.62
  4702.8 1468.95  4759.3 1461.61  4798.0 1460.20  4844.2 1456.50  4886.6 1455.72
  4924.0 1456.99  4943.2 1457.77  4957.3 1456.68  4971.5 1453.11  4980.9 1447.23
  4981.4 1446.73  4990.3 1447.23  5007.0 1448.00  5027.8 1452.82  5106.1 1455.49
  5120.7 1457.62  5135.2 1465.61  5141.5 1464.15  5149.6 1470.07  5164.0 1473.44
  5170.4 1471.39  5184.8 1473.59  5220.1 1472.82  5319.4 1487.11  5361.5 1490.02
#Mann=7,-1,0
  4434.1    0.12       0  4582.9   0.035       0  4798.0    0.07       0
  4924.0    0.12       0  4980.9    0.05       0  4990.3    0.12       0
  5106.1    0.07       0
Bank Sta=4980.9,4990.3
Exp/Cntr=0.3,0.1

Type RM Length L Ch R = 1,2844,423,423,423
BEGIN DESCRIPTION:
WILLIE CREEK 6.0
END DESCRIPTION:
XS GIS Cut Line= 3
      2068511.52     13927665.58      2068225.00     13927975.00
      2067946.79     13928251.15
#Sta/Elev= 30
  4578.3 1494.22  4610.7 1487.78  4639.1 1485.25  4660.1 1477.28  4674.3 1473.69
  4688.5 1471.83  4745.2 1466.95  4824.1 1462.93  4936.2 1457.82  4957.8 1451.35
  4971.9 1449.07  4986.1 1443.91  4992.9 1440.34  4996.6 1436.71  5002.3 1436.56
  5002.8 1436.06  5011.8 1436.56  5014.1 1436.69  5021.2 1441.45  5035.2 1442.90
  5049.5 1450.55  5063.6 1452.70  5070.7 1454.40  5077.8 1457.85  5091.9 1460.55
  5212.1 1468.58  5247.5 1472.74  5339.4 1480.38  5367.7 1484.82  5392.0 1486.20
#Mann=5,-1,0
  4578.3    0.07       0  4610.7   0.035       0  4824.1    0.07       0
  5002.3    0.05       0  5011.8    0.07       0
Bank Sta=5002.3,5011.8
Exp/Cntr=0.3,0.1

Type RM Length L Ch R = 1,2421,474,474,474
BEGIN DESCRIPTION:
WILLIE CREEK 5.0
END DESCRIPTION:
XS GIS Cut Line= 3
      2068417.79     13927491.94      2068025.00     13927625.00
      2067702.48     13927842.65
#Sta/Elev= 30
  4585.3 1485.96  4612.5 1482.52  4619.9 1480.01  4646.5 1475.40  4683.3 1470.62
  4788.8 1461.82  4827.2 1457.69  4905.0 1451.88  4943.8 1447.25  4969.5 1443.19
  4978.9 1440.14  4984.3 1437.24  4992.6 1436.42  4993.1 1435.92  5002.2 1436.42
  5007.5 1436.57  5013.5 1438.34  5022.5 1442.84  5043.5 1445.38  5058.4 1449.24
  5064.5 1448.87  5079.4 1453.80  5097.5 1456.75  5202.3 1465.76  5217.2 1466.14
  5295.3 1472.43  5331.3 1476.85  5346.2 1480.94  5382.2 1486.89  5389.1 1488.83
#Mann=7,-1,0
  4585.3    0.07       0  4646.5   0.035       0  4943.8    0.07       0
  4969.5   0.035       0  4992.6   0.035       0  5002.2   0.035       0
  5097.5    0.07       0
Bank Sta=4992.6,5002.2
Exp/Cntr=0.3,0.1

Type RM Length L Ch R = 1,1947,495,495,495
BEGIN DESCRIPTION:
WILLIE CREEK 4.0
END DESCRIPTION:
XS GIS Cut Line= 3
      2068225.02     13926824.98      2067825.00     13927225.00
      2067625.01     13927624.97
#Sta/Elev= 30
  4434.3 1518.95  4437.9 1518.95  4505.0 1495.94  4544.2 1490.54  4589.9 1486.63
  4618.2 1480.12  4660.6 1474.26  4754.0 1465.82  4830.3 1459.90  4886.9 1453.23
  4957.6 1440.27  4971.7 1436.61  5009.2 1436.34  5009.7 1435.84  5018.8 1436.34
  5030.8 1438.32  5037.6 1442.71  5044.7 1445.72  5111.8 1449.71  5254.4 1454.20
  5276.7 1457.21  5299.1 1463.05  5307.5 1466.85  5321.5 1470.28  5349.4 1481.75
  5366.2 1484.04  5388.5 1489.72  5394.1 1492.21  5416.5 1495.17  5447.2 1497.09
#Mann=6,-1,0
  4434.3    0.07       0  4544.2   0.035       0  4754.0    0.12       0
  5009.2    0.05       0  5018.8    0.12       0  5037.6    0.07       0
Bank Sta=5009.2,5018.8
Exp/Cntr=0.3,0.1

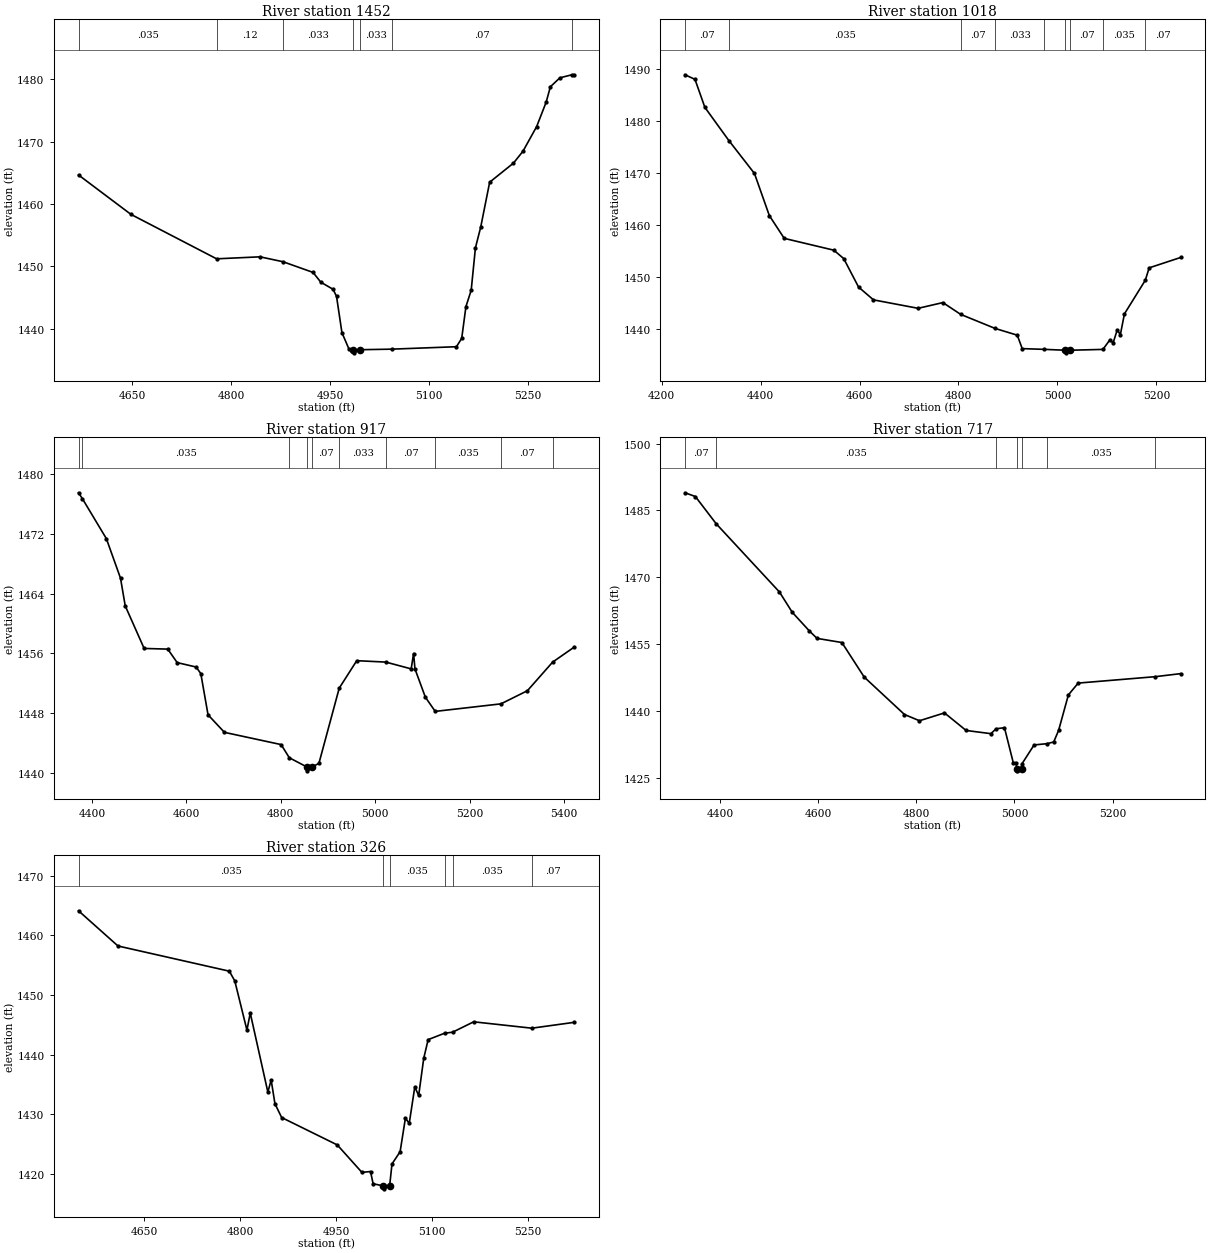
Type RM Length L Ch R = 1,1452,434,434,434
BEGIN DESCRIPTION:
WILLIE CREEK 3.0
END DESCRIPTION:
XS GIS Cut Line= 3
      2067879.58     13926724.58      2067475.00     13926875.00
      2067275.00     13927125.00
#Sta/Elev= 30
  4568.6 1464.66  4648.2 1458.34  4778.1 1451.22  4844.0 1451.54  4878.9 1450.75
  4924.4 1449.04  4936.2 1447.47  4954.7 1446.34  4960.0 1445.21  4968.2 1439.39
  4978.9 1436.75  4985.5 1436.65  4986.0 1436.15  4995.2 1436.65  5043.4 1436.74
  5141.9 1437.13  5149.9 1438.47  5156.3 1443.56  5164.3 1446.19  5170.7 1452.98
  5178.7 1456.29  5192.3 1463.50  5228.4 1466.56  5242.8 1468.46  5263.6 1472.42
  5278.0 1476.33  5284.4 1478.80  5298.8 1480.23  5317.0 1480.72  5320.4 1480.72
#Mann=7,-1,0
  4568.6   0.035       0  4778.1    0.12       0  4878.9   0.033       0
  4985.5   0.033       0  4995.2   0.033       0  5043.4    0.07       0
  5317.0   0.035       0
Bank Sta=4985.5,4995.2
Exp/Cntr=0.3,0.1

Type RM Length L Ch R = 1,1018,101,101,101
BEGIN DESCRIPTION:
WILLIE CREEK 2.0
END DESCRIPTION:
XS GIS Cut Line= 3
      2068025.01     13926525.00      2067275.00     13926575.00
      2067074.98     13926725.01
#Sta/Elev= 30
  4247.3 1488.82  4267.4 1487.94  4287.4 1482.56  4335.8 1476.20  4387.6 1469.87
  4417.7 1461.78  4447.8 1457.41  4548.0 1455.14  4568.0 1453.53  4598.1 1448.05
  4628.2 1445.60  4718.4 1443.98  4768.5 1445.08  4804.3 1442.82  4873.9 1440.12
  4918.8 1438.82  4928.8 1436.24  4972.9 1436.10  5016.0 1435.93  5016.5 1435.43
  5025.7 1435.93  5091.9 1436.09  5106.3 1437.96  5112.5 1437.31  5120.9 1439.86
  5127.1 1438.89  5135.4 1442.91  5177.6 1449.37  5185.4 1451.75  5249.0 1453.74
#Mann=9,-1,0
  4247.3    0.07       0  4335.8   0.035       0  4804.3    0.07       0
  4873.9   0.033       0  4972.9    0.07       0  5016.0    0.05       0
  5025.7    0.07       0  5091.9   0.035       0  5177.6    0.07       0
Bank Sta=5016,5025.7
Exp/Cntr=0.3,0.1

Type RM Length L Ch R = 1,917,200,200,200
BEGIN DESCRIPTION:
WILLIE CREEK 1.5
END DESCRIPTION:
XS GIS Cut Line= 5
      2067953.86     13926505.07      2067325.67     13926493.46
      2067244.74     13926489.77      2067093.53     13926570.59
      2067014.82     13926719.40
#Sta/Elev= 30
  4371.7 1477.54  4379.9 1476.75  4430.6 1471.40  4460.6 1466.09  4470.6 1462.38
  4510.6 1456.67  4560.6 1456.58  4580.6 1454.77  4620.6 1454.18  4630.6 1453.30
  4645.9 1447.77  4680.6 1445.42  4800.6 1443.78  4818.0 1442.01  4855.8 1440.76
  4856.3 1440.26  4865.5 1440.76  4880.6 1441.26  4923.6 1451.35  4960.7 1455.03
  5022.2 1454.84  5075.9 1453.93  5081.0 1455.99  5083.9 1453.93  5105.9 1450.14
  5126.8 1448.23  5265.9 1449.24  5321.9 1451.00  5375.4 1454.84  5420.8 1456.84
#Mann=10,-1,0
  4371.7    0.07       0  4379.9   0.035       0  4818.0    0.07       0
  4855.8   0.033       0  4865.5    0.07       0  4923.6   0.033       0
  5022.2    0.07       0  5126.8   0.035       0  5265.9    0.07       0
  5375.4   0.035       0
Bank Sta=4855.8,4865.5
Exp/Cntr=0.3,0.1

Type RM Length L Ch R = 1,717,391,391,391
BEGIN DESCRIPTION:
WILLIE CREEK 1.0
END DESCRIPTION:
XS GIS Cut Line= 4
      2068033.74     13926443.57      2067375.04     13926310.02
      2067204.65     13926309.83      2067071.52     13926413.29
#Sta/Elev= 30
  4327.9 1488.95  4349.0 1488.11  4391.6 1481.98  4520.5 1466.69  4546.6 1462.14
  4581.7 1457.93  4597.2 1456.28  4647.9 1455.35  4693.5 1447.59  4775.6 1439.20
  4806.2 1437.80  4857.2 1439.56  4901.3 1435.62  4951.9 1434.90  4962.5 1436.00
  4979.6 1436.24  4997.5 1428.41  5002.5 1428.41  5005.1 1427.06  5005.6 1426.56
  5014.8 1427.06  5014.9 1428.07  5040.0 1432.37  5065.9 1432.65  5080.0 1433.03
  5090.0 1435.62  5110.0 1443.60  5130.0 1446.25  5287.4 1447.69  5339.0 1448.37
#Mann=7,-1,0
  4327.9    0.07       0  4391.6   0.035       0  4962.5    0.07       0
  5005.1    0.05       0  5014.8    0.07       0  5065.9   0.035       0
  5287.4    0.12       0
Bank Sta=5005.1,5014.8
Exp/Cntr=0.3,0.1

Type RM Length L Ch R = 1,326,0,0,0
BEGIN DESCRIPTION:
WILLIE CREEK 0.0
END DESCRIPTION:
XS GIS Cut Line= 3
      2067858.56     13926068.28      2067425.45     13925935.19
      2067163.84     13926122.41
#Sta/Elev= 30
  4546.9 1464.13  4608.6 1458.22  4782.7 1453.99  4791.2 1452.36  4810.2 1444.10
  4815.4 1446.96  4842.9 1433.70  4848.1 1435.71  4854.0 1431.74  4864.5 1429.42
  4951.5 1424.82  4990.0 1420.21  5003.4 1420.36  5007.5 1418.30  5023.5 1417.95
  5024.0 1417.45  5033.3 1417.95  5037.0 1421.63  5049.7 1423.68  5057.9 1429.28
  5064.0 1428.47  5072.6 1434.55  5078.7 1433.13  5086.6 1439.35  5093.5 1442.50
  5119.4 1443.58  5131.6 1443.74  5164.7 1445.49  5255.6 1444.42  5321.7 1445.40
#Mann=6,-1,0
  4546.9   0.035       0  5023.5   0.035       0  5033.3   0.035       0
  5119.4    0.07       0  5131.6   0.035       0  5255.6    0.07       0
Bank Sta=5023.5,5033.3
Exp/Cntr=0.3,0.1

Chan Stop Cuts=-1