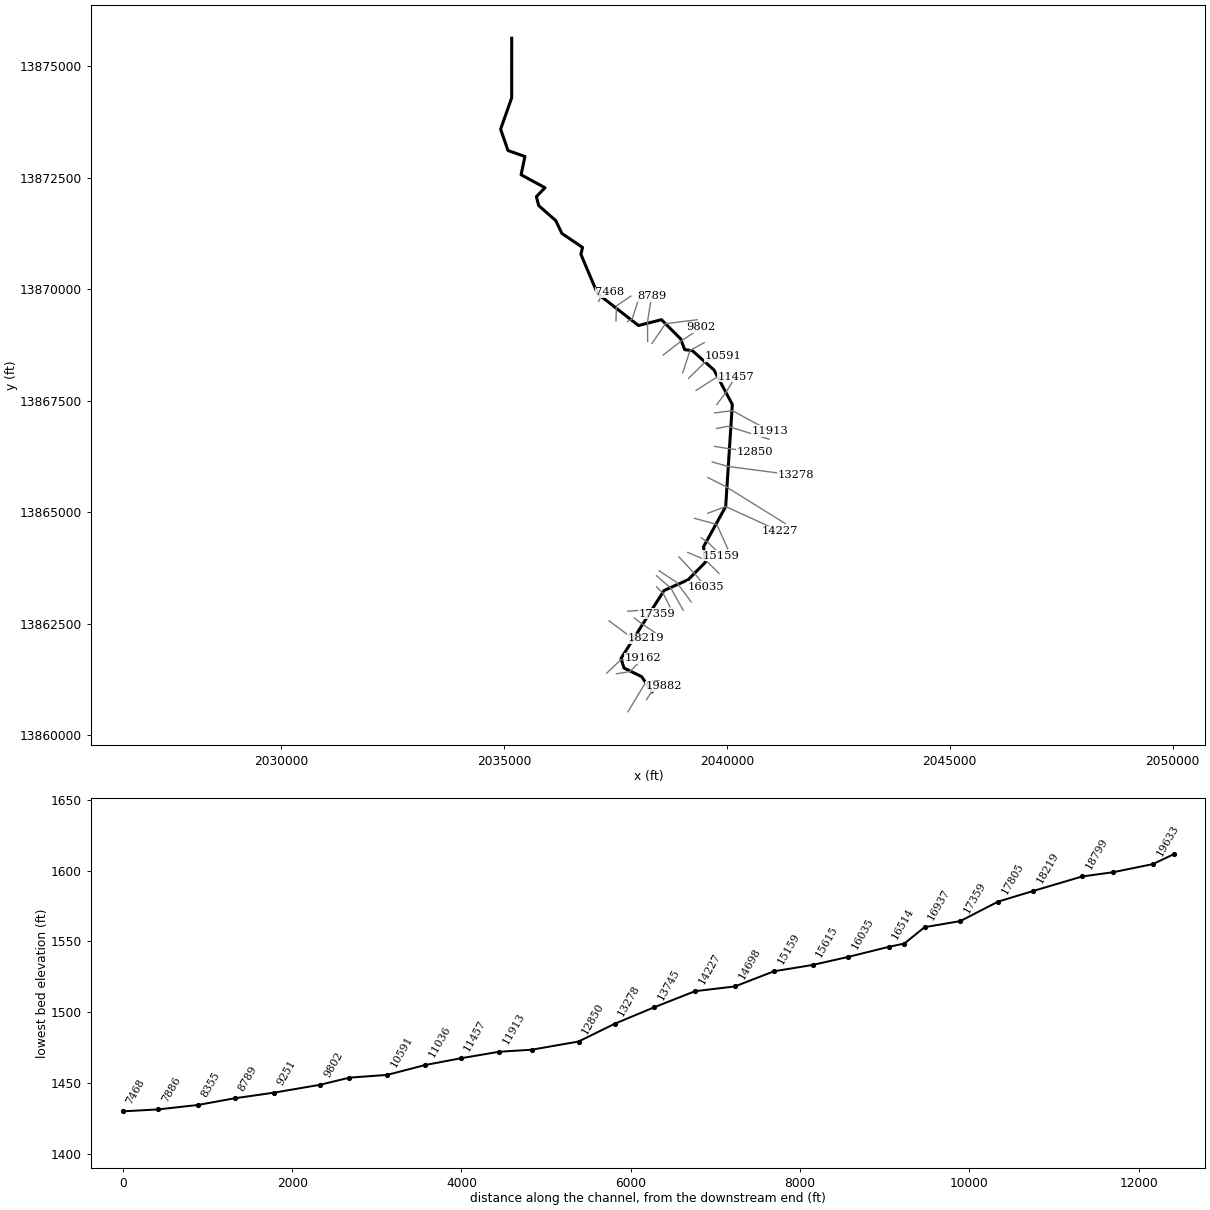
--- ZINKE CREEK.prj (project) ---

Proj Title=ZINKE CREEK Base Level Engineering
Current Plan=p01
Default Exp/Contr=0.3,0.1
English Units
Geom File=g01
Flow File=f01
Plan File=p01
Y Axis Title=Elevation
X Axis Title(PF)=Main Channel Distance
X Axis Title(XS)=Station
BEGIN DESCRIPTION:
ZINKE CREEK
END DESCRIPTION:
DSS Export Rating Curves= 0
DSS Export Rating Curve Sorted= 0
DSS Export Volume Flow Curves= 0
DXF OffsetX= 0
DXF OffsetY= 0
DXF ScaleX= 1
DXF ScaleY= 10

--- ZINKE CREEK.p01 (plan) ---

Plan Title=Multiple Run
Short Identifier=Multiple
Geom File=g01
Flow File=f01
Subcritical Flow
K Sum by GR= 0
Std Step Tol= 0.01
Critical Tol= 0.01
Num of Std Step Trials= 20
Max Error Tol= 0.3
Flow Tol Ratio= 0.001
Split Flow NTrial= 30
Split Flow Tol= 0.02
Split Flow Ratio= 0.02
Log Output Level= 0
Friction Slope Method= 1
Unsteady Friction Slope Method= 2
Unsteady Bridges Friction Slope Method= 1
Parabolic Critical Depth
Global Vel Dist=  1 , 1 , 1
Global Log Level= 0
CheckData=True
Encroach Param= -1, 0, 0, 0
BEGIN DESCRIPTION:
Multiple Run
END DESCRIPTION:

--- ZINKE CREEK.f01 (steady flow) ---

Flow Title=Multiple
Program Version=4.10
Number of Profiles= 7
Profile Names=10-year,25-year,50-year,1pct_min,100-year,1pct_plu,500-year
River Rch & RM=ZINKE CREEK,Reach-1         ,19882
     587     965    1315     874    1745    3481    3023
River Rch & RM=ZINKE CREEK,Reach-1         ,19633
    1210    2086    2938    2009    4008    7998    7372
River Rch & RM=ZINKE CREEK,Reach-1         ,17359
    1383    2393    3376    2310    4608    9195    8490
River Rch & RM=ZINKE CREEK,Reach-1         ,14227
    2574    4587    6597    4588    9155   18266   17453
River Rch & RM=ZINKE CREEK,Reach-1         ,8789
    2951    5269    7586    5276   10528   21006   20079
River Rch & RM=ZINKE CREEK,Reach-1         ,3807
    4458    8106   11813    8307   16575   33072   32317
Boundary for River Rch & Prof#=ZINKE CREEK,Reach-1         , 1
Up Type= 0
Dn Type= 3
Dn Slope=0.005
Boundary for River Rch & Prof#=ZINKE CREEK,Reach-1         , 2
Up Type= 0
Dn Type= 3
Dn Slope=0.005
Boundary for River Rch & Prof#=ZINKE CREEK,Reach-1         , 3
Up Type= 0
Dn Type= 3
Dn Slope=0.005
Boundary for River Rch & Prof#=ZINKE CREEK,Reach-1         , 4
Up Type= 0
Dn Type= 3
Dn Slope=0.005
Boundary for River Rch & Prof#=ZINKE CREEK,Reach-1         , 5
Up Type= 0
Dn Type= 3
Dn Slope=0.005
Boundary for River Rch & Prof#=ZINKE CREEK,Reach-1         , 6
Up Type= 0
Dn Type= 3
Dn Slope=0.005
Boundary for River Rch & Prof#=ZINKE CREEK,Reach-1         , 7
Up Type= 0
Dn Type= 3
Dn Slope=0.005
DSS Import GetInterval= 0
DSS Import GetPeak= 0
DSS Import FillOption= 0

--- ZINKE CREEK.g01 (geometry) ---

Geom Title=Existing Conditions
Program Version=4.10

River Reach=ZINKE CREEK     ,Reach-1
Reach XY= 30
        2038325.       13860975.      2038088.24     13861311.39
      2037694.47     13861504.46      2037626.82     13861718.88
      2038591.45     13863242.13      2039131.19     13863482.81
      2039521.25     13863876.55      2039478.47      13864223.5
        2039975.       13865125.      2040123.78      13867414.5
      2039711.38     13868188.21      2039231.19     13868617.18
      2039054.45     13868644.44      2038964.48     13868884.79
      2038534.82     13869314.54      2038018.26     13869184.13
      2037098.01     13869901.53      2036727.17     13870780.98
      2036763.91     13870935.08      2036301.48     13871247.99
      2036161.38     13871538.22      2035780.83      13871872.7
      2035728.37     13872073.72      2035921.91     13872273.36
      2035385.05       13872565.      2035471.57     13872973.78
      2035091.41     13873108.07       2034926.1     13873585.55
      2035174.48     13874290.22        2035175.       13875625.

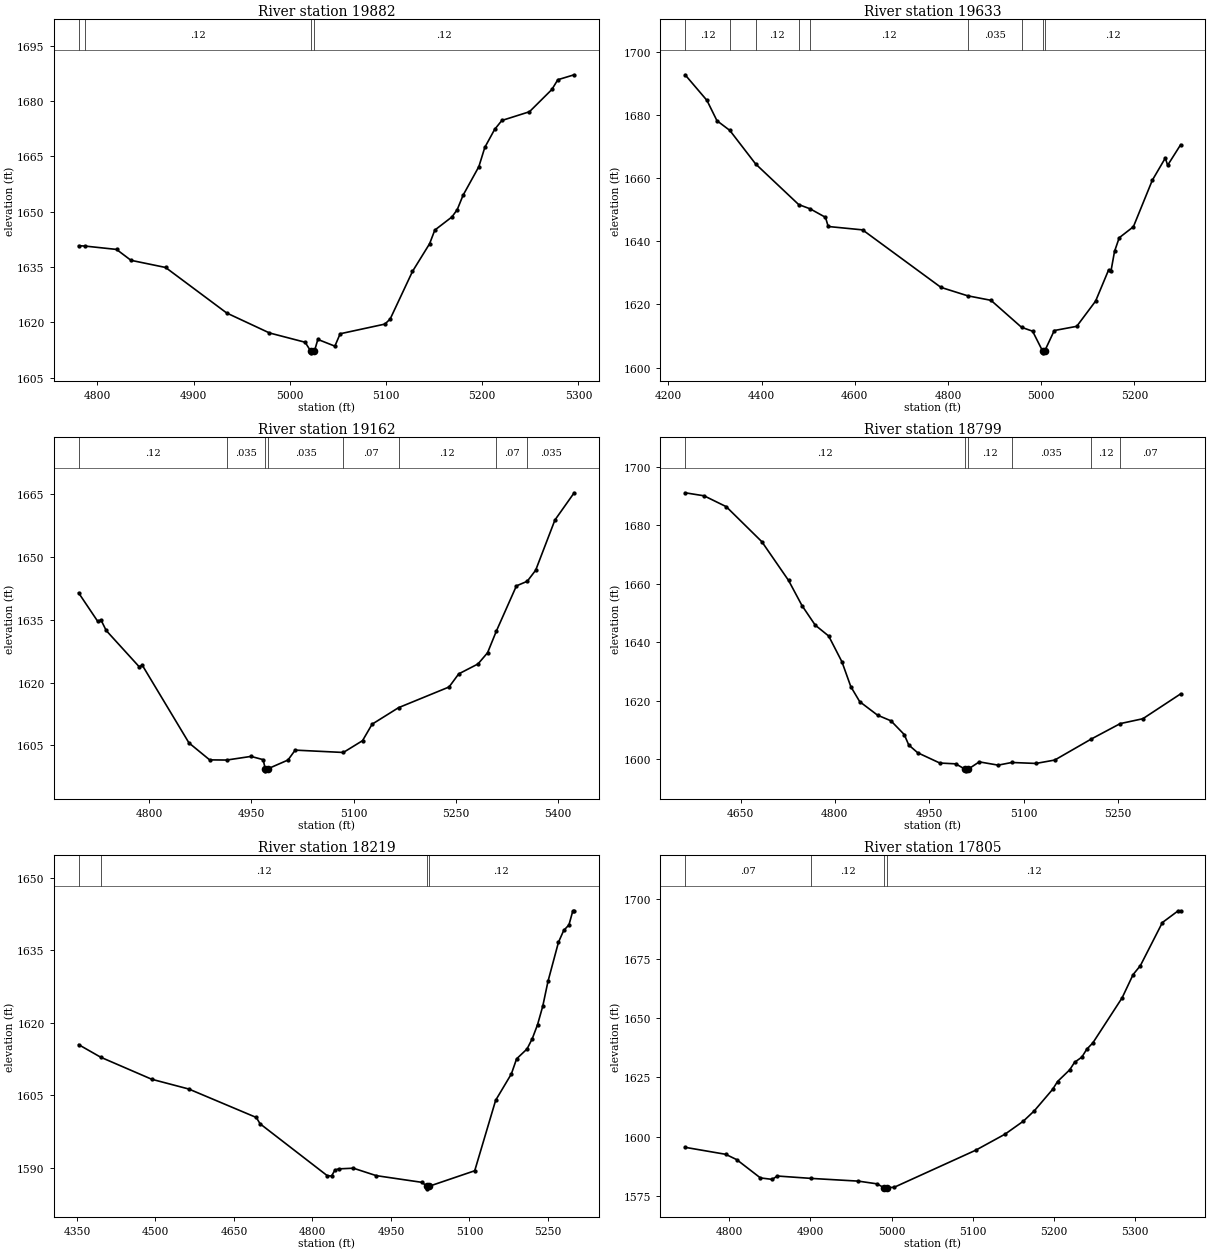
Type RM Length L Ch R = 1 ,19882   ,249,249,249
BEGIN DESCRIPTION:
ZINKE CREEK 44.0
END DESCRIPTION:
XS GIS Cut Line= 3
      2038198.24     13860797.05       2038320.5     13860979.47
      2038590.52     13861099.76
#Sta/Elev= 30
  4780.4 1640.75  4787.1 1640.65  4819.8 1639.74  4834.8 1636.79  4870.8 1634.85
  4934.4  1622.5  4978.8  1617.1  5015.9 1614.58  5021.6 1612.21  5021.9 1611.71
  5025.6 1612.21  5029.1 1615.35  5046.8 1613.52  5052.3 1616.88  5098.8  1619.5
  5104.3 1620.88  5127.5 1633.78  5145.3 1641.29  5150.7 1644.98  5168.5 1648.54
    5174 1650.52  5180.1 1654.43  5196.5 1662.18  5202.7  1667.4  5212.9 1672.27
  5220.4 1674.69  5249.1 1677.06  5272.4 1683.09  5278.6 1685.74  5295.6 1687.08
#Mann= 4 ,-1 , 0
  4780.4    .035       0  4787.1     .12       0  5021.6     .05       0
  5025.6     .12       0
Bank Sta=5021.6,5025.6
XS Rating Curve= 0 ,0
Exp/Cntr=0.3,0.1

Type RM Length L Ch R = 1 ,19633   ,471,471,471
BEGIN DESCRIPTION:
ZINKE CREEK 43.0
END DESCRIPTION:
XS GIS Cut Line= 3
      2037782.59     13860524.87        2038175.       13861175.
      2038474.98       13861225.
#Sta/Elev= 30
  4235.9 1692.66  4282.8 1684.55  4304.3 1678.12  4331.8 1675.06  4387.3 1664.43
  4479.6 1651.59  4504.4 1650.22  4537.2 1647.54    4543 1644.64  4616.8 1643.57
    4785 1625.37  4842.2 1622.71  4892.4 1621.27  4957.9 1612.74  4981.7  1611.5
  5003.4 1605.15  5003.7 1604.65  5007.4 1605.15  5028.2 1611.71  5076.4 1613.04
  5116.9 1621.03  5144.8 1630.89  5149.9 1630.51  5157.5 1636.75  5167.6 1641.08
    5198 1644.56  5238.6 1659.28  5266.5 1666.31  5271.5 1664.02  5299.4 1670.52
#Mann= 9 ,-1 , 0
  4235.9     .12       0  4331.8    .035       0  4387.3     .12       0
  4479.6    .035       0  4504.4     .12       0  4842.2    .035       0
  4957.9     .12       0  5003.4     .05       0  5007.4     .12       0
Bank Sta=5003.4,5007.4
XS Rating Curve= 0 ,0
Exp/Cntr=0.3,0.1

Type RM Length L Ch R = 1 ,19162   ,363,363,363
BEGIN DESCRIPTION:
ZINKE CREEK 42.0
END DESCRIPTION:
XS GIS Cut Line= 3
      2037525.01       13861375.        2037825.       13861425.
        2038125.       13861725.
#Sta/Elev= 30
  4695.9 1641.44  4723.8 1634.68  4728.8 1634.96  4736.4 1632.46  4784.6 1623.85
  4789.7  1624.1  4858.1 1605.59  4888.5 1601.54  4913.6  1601.5  4949.3 1602.37
  4967.1 1601.59  4970.2 1599.42  4970.4 1598.92  4974.2 1599.42  5003.6  1601.5
  5014.2 1603.87    5085 1603.31  5113.2 1606.13  5127.3 1610.07  5166.2 1614.02
  5240.4 1618.96  5254.6 1622.09  5282.9 1624.46    5297 1627.14  5309.8 1632.27
  5339.4 1643.12  5355.3 1644.22  5367.7 1646.86    5396 1658.86  5424.3 1665.37
#Mann= 8 ,-1 , 0
  4695.9     .12       0  4913.6    .035       0  4970.2    .035       0
  4974.2    .035       0    5085     .07       0  5166.2     .12       0
  5309.8     .07       0  5355.3    .035       0
Bank Sta=4970.2,4974.2
XS Rating Curve= 0 ,0
Exp/Cntr=0.3,0.1

Type RM Length L Ch R = 1 ,18799   ,580,580,580
BEGIN DESCRIPTION:
ZINKE CREEK 41.0
END DESCRIPTION:
XS GIS Cut Line= 3
       2037307.9     13861389.42      2037617.68     13861688.09
      2037975.03       13861675.
#Sta/Elev= 30
  4561.9 1691.09  4592.1 1690.05  4627.3 1686.34  4683.9 1674.35  4726.4 1661.09
  4747.7 1652.51  4768.8 1645.79  4790.2 1642.07  4811.3 1633.23  4825.4 1624.74
  4839.6 1619.59  4867.9 1614.98  4889.2 1613.05  4910.3 1608.36  4917.5 1604.78
  4931.7 1602.12  4966.9  1598.6  4992.2 1598.32  5007.5 1596.43  5007.8 1595.93
  5011.5 1596.43  5029.6    1599  5059.6 1597.88  5081.4 1598.79  5119.6 1598.46
  5149.6 1599.62  5207.5 1606.79  5253.7 1612.09  5289.7 1613.76  5349.8 1622.27
#Mann= 6 ,-1 , 0
  4561.9     .12       0  5007.5     .05       0  5011.5     .12       0
  5081.4    .035       0  5207.5     .12       0  5253.7     .07       0
Bank Sta=5007.5,5011.5
XS Rating Curve= 0 ,0
Exp/Cntr=0.3,0.1

Type RM Length L Ch R = 1 ,18219   ,414,414,414
BEGIN DESCRIPTION:
ZINKE CREEK 40.0
END DESCRIPTION:
XS GIS Cut Line= 3
      2037357.91     13862563.45        2037875.       13862175.
      2038174.96       13862175.
#Sta/Elev= 30
  4353.3 1615.49  4395.6 1612.88  4492.9 1608.33  4563.7 1606.31  4692.8 1600.42
  4699.9 1599.12  4828.2 1588.39  4836.5 1588.31  4842.8 1589.52    4850 1589.79
  4878.2 1589.93  4921.9 1588.39    5010 1586.99    5018 1586.16  5018.3 1585.66
    5022 1586.16    5110  1589.4    5150 1603.98    5180 1609.43    5190 1612.55
    5210  1614.6    5220 1616.74    5230 1619.61    5240 1623.45    5250 1628.59
    5270 1636.67    5280 1639.11    5290 1640.26  5297.5 1643.18    5300 1643.18
#Mann= 4 ,-1 , 0
  4353.3     .07       0  4395.6     .12       0    5018     .05       0
    5022     .12       0
Bank Sta=5018,5022
XS Rating Curve= 0 ,0
Exp/Cntr=0.3,0.1

Type RM Length L Ch R = 1 ,17805   ,446,446,446
BEGIN DESCRIPTION:
ZINKE CREEK 39.0
END DESCRIPTION:
XS GIS Cut Line= 3
      2037924.96     13862625.03        2038125.       13862475.
        2038425.       13862275.
#Sta/Elev= 30
  4745.5  1595.6  4795.5 1592.66  4809.1 1590.42  4838.3 1582.73  4852.8 1582.12
  4859.1 1583.53  4901.2 1582.52  4959.1 1581.38    4982 1580.24  4990.4 1578.64
  4990.7 1578.14  4994.4 1578.64  5003.1 1578.79  5103.7  1594.4  5139.8 1601.15
  5162.3  1606.6  5175.8 1610.95  5198.4 1619.99  5204.4 1623.26  5219.4 1628.19
  5225.4 1631.34  5234.4 1633.55  5240.4 1636.85  5247.9  1639.5    5284 1658.47
  5297.5 1668.22  5306.5 1672.01  5333.6 1690.12  5353.1 1695.07  5356.1 1695.07
#Mann= 4 ,-1 , 0
  4745.5     .07       0  4901.2     .12       0  4990.4     .05       0
  4994.4     .12       0
Bank Sta=4990.4,4994.4
XS Rating Curve= 0 ,0
Exp/Cntr=0.3,0.1

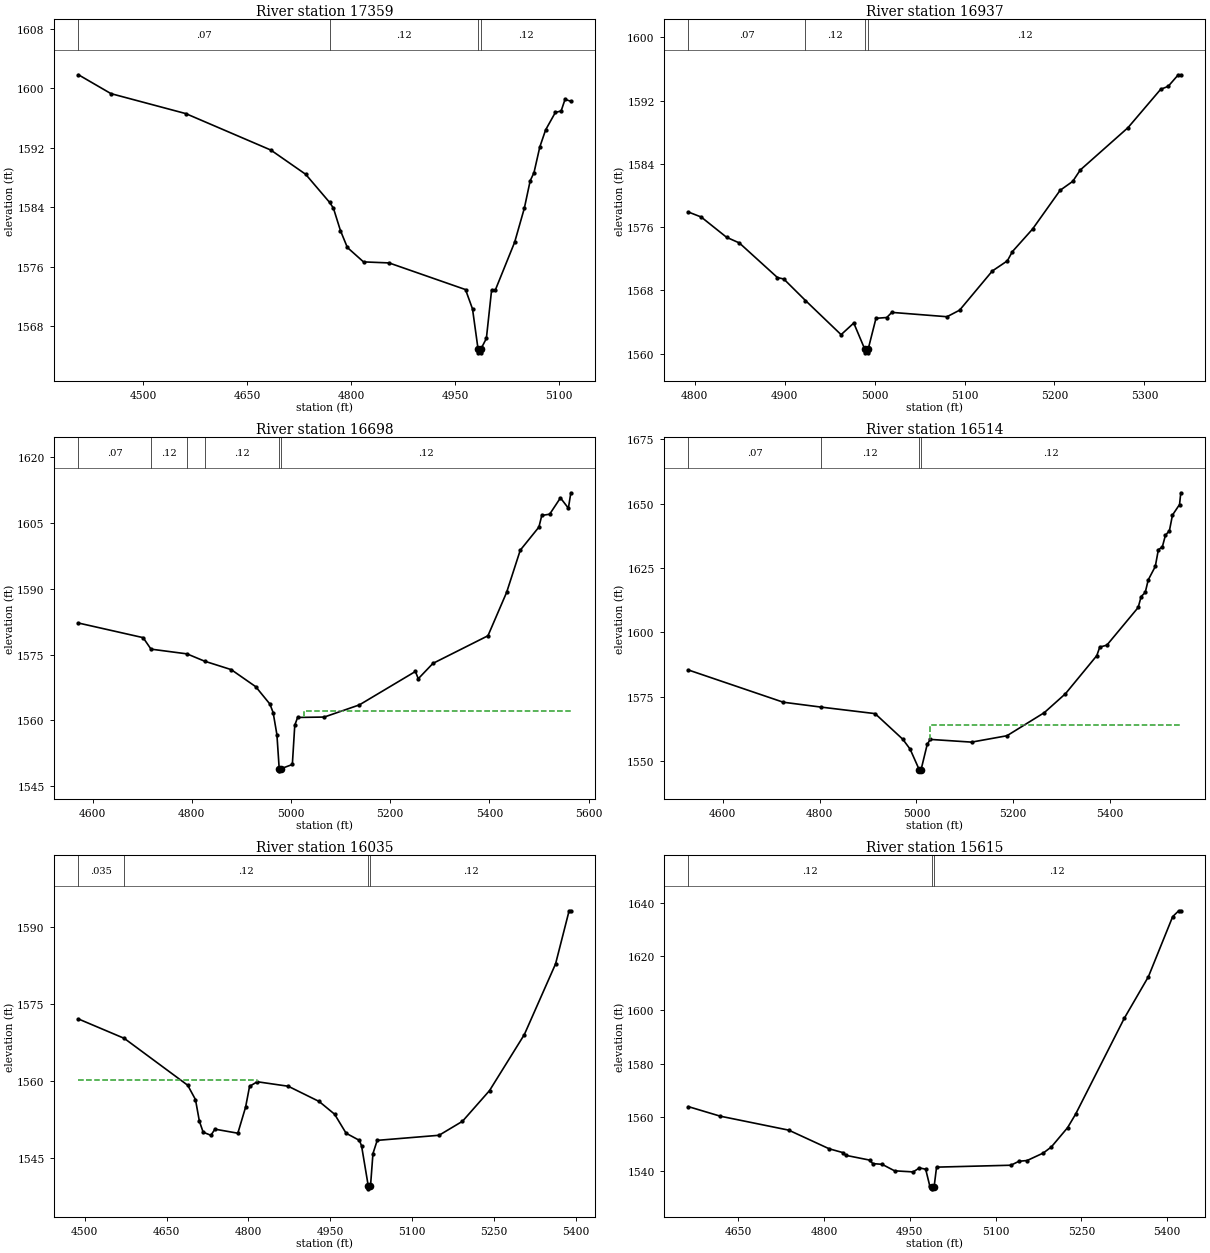
Type RM Length L Ch R = 1 ,17359   ,422,422,422
BEGIN DESCRIPTION:
ZINKE CREEK 38.0
END DESCRIPTION:
XS GIS Cut Line= 3
      2037778.24     13862777.49        2038375.       13862825.
      2038425.02     13862724.96
#Sta/Elev= 30
  4406.3 1601.84  4453.2  1599.3  4561.2 1596.61  4683.9  1591.7  4734.1 1588.44
  4768.7 1584.65  4774.2 1583.87  4784.3 1580.86  4794.3 1578.58  4817.6 1576.64
  4854.5  1576.5  4964.8 1572.91  4974.9  1570.3  4982.9 1564.89  4983.1 1564.39
  4986.6 1564.39  4986.9 1564.89  4994.9 1566.33  5002.4 1572.82  5007.7 1572.82
  5035.7 1579.29  5049.7 1583.88  5058.1 1587.56  5063.6 1588.66    5072 1592.12
  5080.4 1594.42  5094.4 1596.76  5102.8 1596.97  5108.4 1598.53  5116.8 1598.27
#Mann= 4 ,-1 , 0
  4406.3     .07       0  4768.7     .12       0  4982.9     .05       0
  4986.9     .12       0
Bank Sta=4982.9,4986.9
XS Rating Curve= 0 ,0
Exp/Cntr=0.3,0.1

Type RM Length L Ch R = 1 ,16937   ,239,239,239
BEGIN DESCRIPTION:
ZINKE CREEK 37.0
END DESCRIPTION:
XS GIS Cut Line= 3
      2038424.97     13863325.03        2038575.       13863175.
        2038725.     13862874.99
#Sta/Elev= 30
  4792.9 1577.91  4807.1 1577.28  4835.4 1574.71  4849.5    1574  4891.9 1569.62
    4899 1569.43  4923.1 1566.71  4962.7 1562.39  4976.8 1563.86  4988.9 1560.59
  4989.2 1560.09  4992.7 1560.09  4992.9 1560.59  5001.5 1564.46  5013.5 1564.56
  5019.1 1565.21  5080.5 1564.66  5094.5 1565.49  5130.9 1570.45  5147.6 1571.73
  5153.2  1572.9  5175.6 1575.75  5206.3 1580.66  5220.3 1581.79  5228.7 1583.23
  5281.8 1588.59  5318.1 1593.44  5326.5 1593.82  5337.7 1595.28  5340.5 1595.28
#Mann= 4 ,-1 , 0
  4792.9     .07       0  4923.1     .12       0  4988.9     .05       0
  4992.9     .12       0
Bank Sta=4988.9,4992.9
XS Rating Curve= 0 ,0
Exp/Cntr=0.3,0.1

Type RM Length L Ch R = 1 ,16698   ,184,184,184
BEGIN DESCRIPTION:
ZINKE CREEK 36.5
END DESCRIPTION:
XS GIS Cut Line= 3
      2038421.39     13863575.17      2038745.15     13863294.63
      2039020.62     13862802.36
#Sta/Elev= 30
  4571.6  1582.2  4701.9 1578.87  4717.8 1576.25  4790.4 1575.17  4825.7 1573.51
  4879.5 1571.58  4928.9 1567.69  4957.4 1563.74    4964 1561.79  4971.6 1556.76
  4976.2 1549.01  4976.5 1548.51  4980.2 1549.01  5002.7 1549.96  5007.6 1558.91
  5013.3 1560.68    5067 1560.77  5137.8 1563.54  5250.8 1571.16  5256.5  1569.5
  5286.1    1573    5397  1579.3  5434.6 1589.18  5462.1  1598.8  5499.7 1604.07
  5505.5 1606.72  5521.4 1607.01  5543.1 1610.73  5559.1 1608.38  5564.1 1611.89
#Mann= 6 ,-1 , 0
  4571.6     .07       0  4717.8     .12       0  4790.4     .07       0
  4825.7     .12       0  4976.2     .05       0  4980.2     .12       0
#XS Ineff= 2 , 0
       0                 5026.81       0 1562.16
Permanent Ineff=
       F       F
Bank Sta=4976.2,4980.2
XS Rating Curve= 0 ,0
Exp/Cntr=0.3,0.1

Type RM Length L Ch R = 1 ,16514   ,479,479,479
BEGIN DESCRIPTION:
ZINKE CREEK 36.0
END DESCRIPTION:
XS GIS Cut Line= 3
      2038481.42      13863684.6        2038875.       13863425.
      2039200.95     13862987.07
#Sta/Elev= 30
  4528.8 1585.41  4724.8 1572.88  4802.1    1571  4914.5 1568.45  4971.7  1558.5
  4986.8 1554.68  5005.6 1546.71  5005.8 1546.21  5009.6 1546.71  5022.2 1556.47
  5028.4 1558.43  5113.9 1557.37    5187 1559.85  5264.1 1568.82  5307.9 1576.19
  5372.6 1590.98  5378.8 1594.31  5393.4 1595.06  5458.1  1609.7  5464.3 1613.97
  5472.7 1615.53  5478.9 1620.42  5493.5 1625.65  5499.8 1632.13  5508.1 1633.29
  5514.4 1637.75  5522.7 1639.57    5529 1645.63  5543.6 1649.72  5546.2 1654.29
#Mann= 4 ,-1 , 0
  4528.8     .07       0  4802.1     .12       0  5005.6     .05       0
  5009.6     .12       0
#XS Ineff= 2 , 0
       0                  5027.7       0    1564
Permanent Ineff=
       F       F
Bank Sta=5005.6,5009.6
XS Rating Curve= 0 ,0
Exp/Cntr=0.3,0.1

Type RM Length L Ch R = 1 ,16035   ,420,420,420
BEGIN DESCRIPTION:
ZINKE CREEK 35.0
END DESCRIPTION:
XS GIS Cut Line= 3
      2038924.13     13863997.08        2039275.       13863625.
      2039524.98     13863325.03
#Sta/Elev= 30
  4488.6 1572.09  4572.4 1568.33  4688.7 1559.21  4702.9 1556.43  4710.1 1552.21
    4717 1550.09  4731.2 1549.48  4738.5 1550.68  4780.5 1549.89  4794.7 1554.95
    4802    1559  4816.1 1559.89  4872.8 1559.02  4929.4 1556.06  4957.7 1553.59
  4978.8 1549.89  5003.3 1548.49  5007.2  1547.4  5019.5 1539.58  5019.8 1539.08
  5023.5 1539.58    5028 1545.93  5035.8  1548.5  5149.1 1549.49    5192 1552.21
  5241.5 1558.17  5305.3 1569.06  5362.5  1582.8  5387.3 1593.12  5390.5 1593.12
#Mann= 4 ,-1 , 0
  4488.6    .035       0  4572.4     .12       0  5019.5     .05       0
  5023.5     .12       0
#XS Ineff= 2 , 0
       0  4815.4  1560.3               0
Permanent Ineff=
       F       F
Bank Sta=5019.5,5023.5
XS Rating Curve= 0 ,0
Exp/Cntr=0.3,0.1

Type RM Length L Ch R = 1 ,15615   ,456,456,456
BEGIN DESCRIPTION:
ZINKE CREEK 34.0
END DESCRIPTION:
XS GIS Cut Line= 3
      2039123.77     13864096.93        2039525.       13863925.
      2039825.02     13863624.98
#Sta/Elev= 30
  4562.9 1564.01  4618.6 1560.46  4738.3 1555.26    4809 1548.32  4832.6 1546.92
    4838 1545.89  4879.7 1544.11  4885.2  1542.8  4901.5 1542.54  4923.3 1540.12
  4955.9 1539.71  4966.8 1541.22  4977.7  1540.7  4984.9 1534.45  4988.3 1533.91
  4988.6 1533.41  4992.3 1533.91  4996.7 1541.49  5126.7  1542.2  5140.8 1543.68
    5155 1543.95  5183.3 1546.74  5197.4 1549.01  5225.7 1556.16  5239.8 1561.21
  5324.7 1596.83  5367.1  1612.4  5409.5 1634.75  5420.1 1636.93  5423.7 1636.93
#Mann= 3 ,-1 , 0
  4562.9     .12       0  4988.3     .05       0  4992.3     .12       0
Bank Sta=4988.3,4992.3
XS Rating Curve= 0 ,0
Exp/Cntr=0.3,0.1

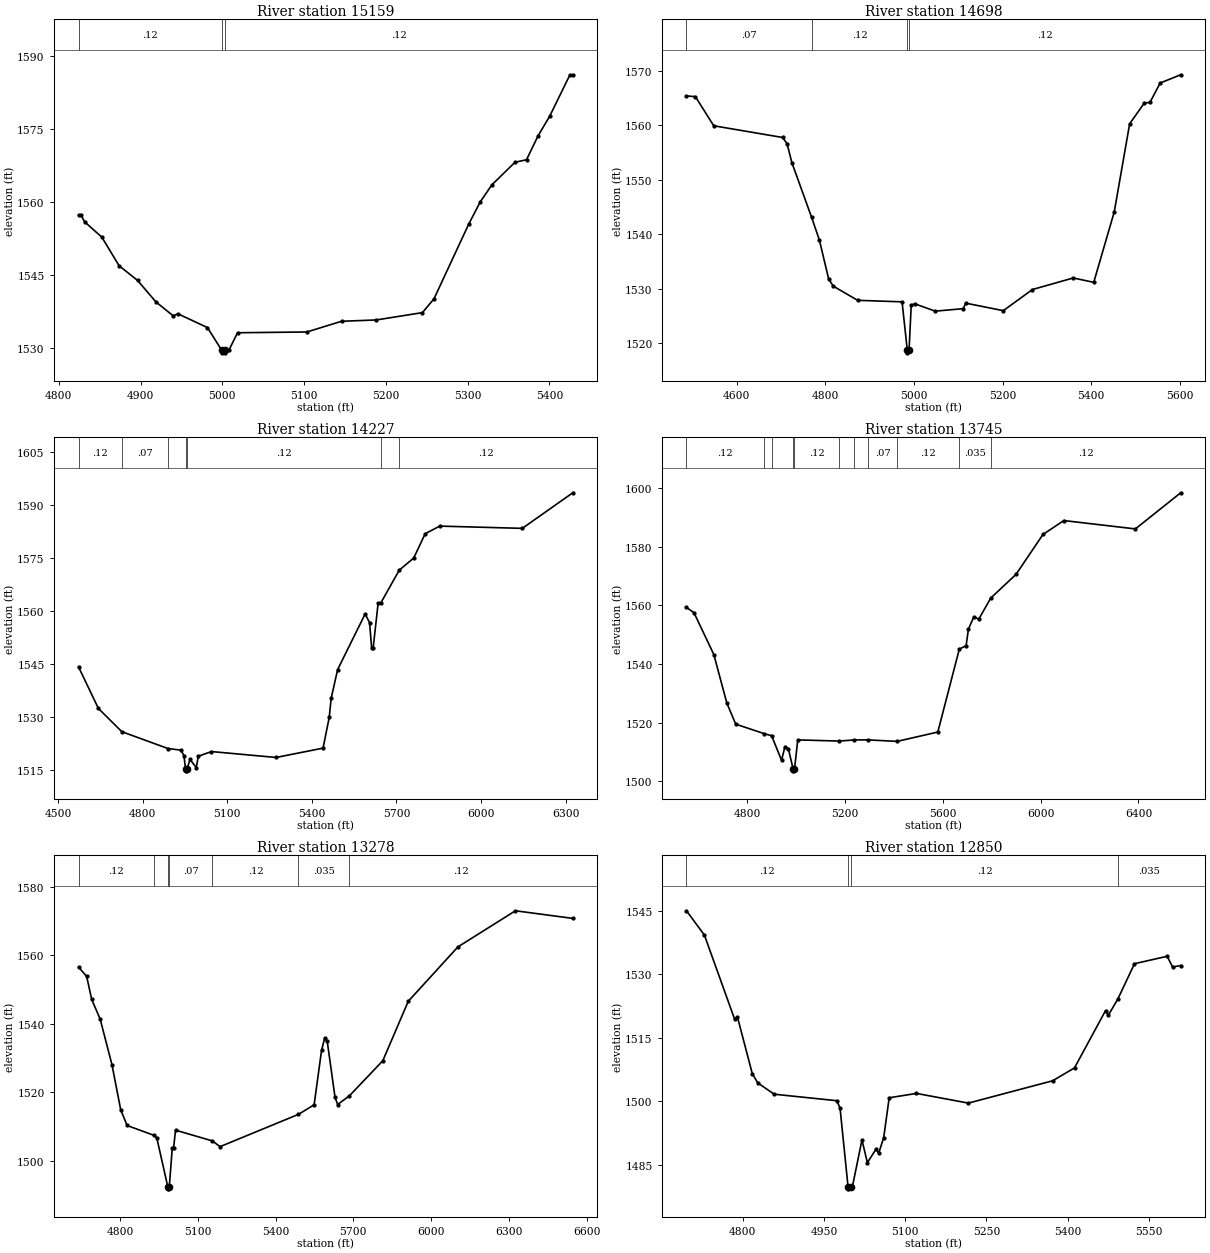
Type RM Length L Ch R = 1 ,15159   ,461,461,461
BEGIN DESCRIPTION:
ZINKE CREEK 33.0
END DESCRIPTION:
XS GIS Cut Line= 3
      2039425.04     13864424.98        2039575.       13864325.
        2039875.       13864025.
#Sta/Elev= 30
  4824.2 1557.24  4827.2 1557.24  4831.7 1555.87  4852.7 1552.73  4873.7 1546.87
  4896.3 1543.85  4918.8 1539.42  4939.8 1536.58  4945.8 1536.97  4981.9 1534.14
  4999.4 1529.45  4999.7 1528.95  5003.2 1528.95  5003.4 1529.45    5008 1529.45
  5018.6 1533.08  5103.4 1533.24  5145.9 1535.44  5188.3 1535.71  5244.8 1537.22
    5259 1540.08  5301.4 1555.41  5315.6 1560.01  5329.7 1563.48    5358 1568.13
  5372.1 1568.65  5386.3 1573.59  5400.4 1577.58  5425.2 1586.12  5428.7 1586.12
#Mann= 3 ,-1 , 0
  4824.2     .12       0  4999.4     .05       0  5003.4     .12       0
Bank Sta=4999.4,5003.4
XS Rating Curve= 0 ,0
Exp/Cntr=0.3,0.1

Type RM Length L Ch R = 1 ,14698   ,471,471,471
BEGIN DESCRIPTION:
ZINKE CREEK 32.0
END DESCRIPTION:
XS GIS Cut Line= 3
      2039275.63     13864860.84        2039775.       13864725.
      2040019.93     13864179.91
#Sta/Elev= 30
  4486.7 1565.39  4506.8 1565.26  4548.2 1559.91  4703.7 1557.76  4713.7  1556.6
  4724.4 1553.17    4769 1543.11  4786.6 1538.93  4807.3 1531.86  4817.7 1530.49
  4872.8 1527.88  4973.1  1527.6  4984.9 1518.74  4985.2 1518.24  4988.9 1518.74
  4993.8 1526.99  5001.6 1527.24  5048.1 1525.89  5111.2 1526.35  5116.7 1527.36
  5201.5 1525.98  5267.3 1529.86  5359.3 1531.98  5405.6 1531.18  5451.9 1544.12
  5486.6 1560.27  5519.5 1564.07  5532.4  1564.2  5555.5 1567.76  5601.8 1569.27
#Mann= 4 ,-1 , 0
  4486.7     .07       0    4769     .12       0  4984.9     .05       0
  4988.9     .12       0
Bank Sta=4984.9,4988.9
XS Rating Curve= 0 ,0
Exp/Cntr=0.3,0.1

Type RM Length L Ch R = 1 ,14227   ,482,482,482
BEGIN DESCRIPTION:
ZINKE CREEK 31.0
END DESCRIPTION:
XS GIS Cut Line= 3
        2039575.       13864975.        2039975.       13865125.
       2041180.5     13864574.62
#Sta/Elev= 30
  4572.8 1544.26  4643.1 1532.53  4726.1 1525.96  4889.7  1521.2  4935.9 1520.74
  4946.6 1519.18    4952 1515.39  4952.4 1514.89  4957.3 1515.39    4968 1518.11
  4990.2 1515.81  4997.3 1519.01    5044 1520.34  5273.1 1518.67  5439.7 1521.31
  5461.7 1530.05  5468.4 1535.35  5491.4 1543.53    5589 1559.25  5604.6  1556.8
    5612 1549.62  5617.5 1549.72  5635.1 1562.36  5645.2 1562.46    5710 1571.64
  5761.2 1575.06  5801.8 1581.92  5853.4 1584.08  6146.2 1583.44  6325.2  1593.5
#Mann= 7 ,-1 , 0
  4572.8     .12       0  4726.1     .07       0  4889.7     .12       0
    4952     .05       0  4957.3     .12       0  5645.2    .035       0
    5710     .12       0
Bank Sta=4952,4957.3
XS Rating Curve= 0 ,0
Exp/Cntr=0.3,0.1

Type RM Length L Ch R = 1 ,13745   ,467,467,467
BEGIN DESCRIPTION:
ZINKE CREEK 30.0
END DESCRIPTION:
XS GIS Cut Line= 3
      2039574.97     13865775.02        2039975.       13865575.
      2041310.65     13864744.02
#Sta/Elev= 30
  4552.3 1559.26  4583.1 1557.42  4664.1 1543.18  4717.2 1526.63  4753.6 1519.45
  4870.7 1516.19  4900.3 1515.51  4940.9 1507.13  4954.8 1511.79  4968.8 1511.09
  4988.5 1504.03  4988.9 1503.53  4993.8 1504.03  5007.2 1514.08  5176.7 1513.68
    5238 1514.07  5295.1 1514.08  5413.4 1513.57  5579.7 1516.76  5667.6 1545.04
  5695.4 1546.21  5704.9 1551.86  5726.1  1555.9  5747.4  1555.3    5796 1562.42
  5899.6 1570.53  6009.4 1584.11  6094.9 1588.86  6387.2 1586.01  6572.6 1598.33
#Mann= 11 ,-1 , 0
  4552.3     .12       0  4870.7     .07       0  4900.3     .12       0
  4988.5     .05       0  4993.8     .12       0  5176.7     .07       0
    5238     .12       0  5295.1     .07       0  5413.4     .12       0
  5667.6    .035       0    5796     .12       0
Bank Sta=4988.5,4993.8
XS Rating Curve= 0 ,0
Exp/Cntr=0.3,0.1

Type RM Length L Ch R = 1 ,13278   ,428,428,428
BEGIN DESCRIPTION:
ZINKE CREEK 29.0
END DESCRIPTION:
XS GIS Cut Line= 3
      2039674.95     13866125.01        2040025.       13866025.
      2041554.34     13865824.37
#Sta/Elev= 30
  4640.1 1556.53  4671.3 1553.81  4690.8  1547.1  4723.4 1541.37  4768.9 1528.08
  4802.7 1514.92  4827.4 1510.34    4930  1507.5  4941.8 1506.74  4984.6 1492.37
    4985 1491.87    4990 1492.37  5001.6 1503.81  5006.7 1503.81  5014.2 1508.98
  5156.7 1505.84  5185.7 1504.17  5488.5 1513.59  5548.8 1516.38  5577.4 1532.21
  5589.1 1535.74  5599.2 1534.98  5629.5 1518.53  5639.6 1516.46    5685    1519
  5813.7 1529.22  5911.9 1546.55  6103.5 1562.42  6325.4 1572.95  6546.6 1570.73
#Mann= 7 ,-1 , 0
  4640.1     .12       0    4930     .07       0  4984.6     .05       0
    4990     .07       0  5156.7     .12       0  5488.5    .035       0
    5685     .12       0
Bank Sta=4984.6,4990
XS Rating Curve= 0 ,0
Exp/Cntr=0.3,0.1

Type RM Length L Ch R = 1 ,12850   ,555,555,555
BEGIN DESCRIPTION:
ZINKE CREEK 28.0
END DESCRIPTION:
XS GIS Cut Line= 3
      2039725.04     13866474.99      2040024.98     13866425.52
      2040629.86     13866353.88
#Sta/Elev= 30
    4696 1545.01  4729.1 1539.27  4785.1 1519.33  4790.2 1519.88  4817.6 1506.51
  4827.7 1504.33  4858.1 1501.66  4973.6 1500.13  4979.7 1498.41  4994.5  1479.8
    4995  1479.3  5000.4  1479.8  5002.5  1479.8  5020.2 1490.86  5030.2 1485.49
  5046.1 1488.65  5051.2 1487.73  5060.4 1491.43  5070.5 1500.82  5120.9 1501.85
  5216.8 1499.56  5372.6 1504.84  5412.9 1507.89  5470.2 1521.41  5475.2 1520.29
  5493.2 1524.22  5523.7  1532.5  5584.1 1534.26  5594.1 1531.72  5609.1 1532.07
#Mann= 4 ,-1 , 0
    4696     .12       0  4994.5     .05       0  5000.4     .12       0
  5493.2    .035       0
Bank Sta=4994.5,5000.4
XS Rating Curve= 0 ,0
Exp/Cntr=0.3,0.1

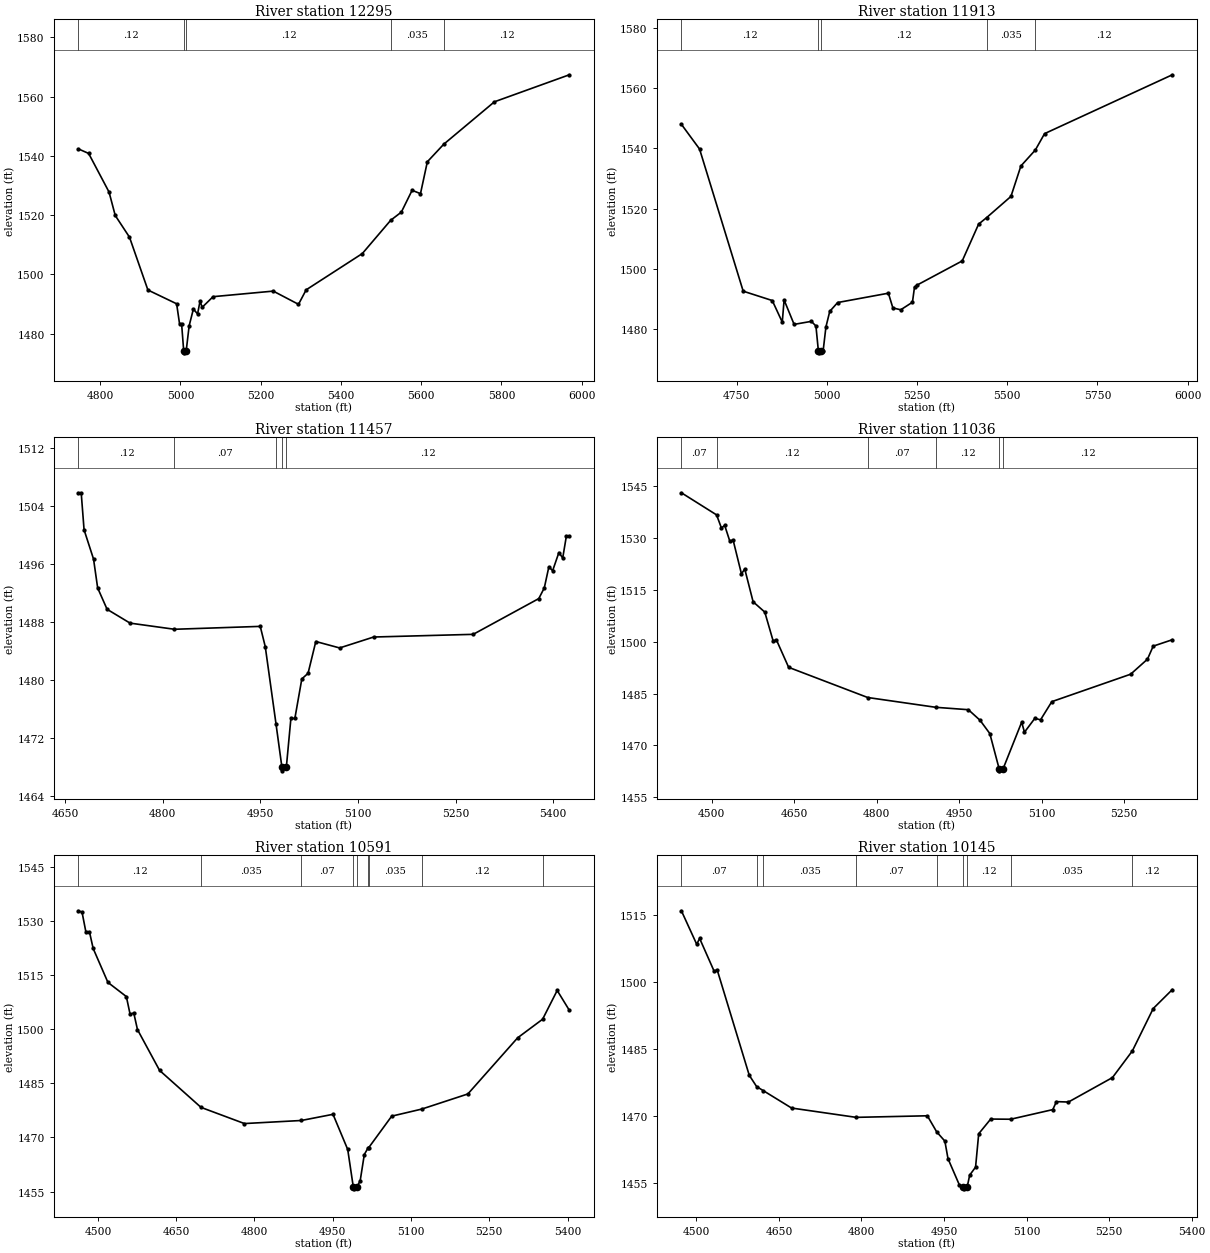
Type RM Length L Ch R = 1 ,12295   ,382,382,382
BEGIN DESCRIPTION:
ZINKE CREEK 27.0
END DESCRIPTION:
XS GIS Cut Line= 3
      2039774.98       13866875.      2040024.21     13866924.99
      2040948.89     13866634.27
#Sta/Elev= 30
  4745.8 1542.34  4771.3 1540.82  4822.2 1527.77  4837.6 1519.87  4873.1 1512.55
    4919 1494.71  4990.6 1490.06  4997.9 1483.27    5003 1483.27  5008.3    1474
  5008.8  1473.5  5014.3    1474  5021.8 1482.62  5032.3 1488.28  5042.8 1486.64
    5049 1490.99  5054.2 1488.86  5081.4 1492.46  5231.4 1494.34  5294.3 1489.88
  5313.4 1494.77  5453.4 1507.02  5524.2 1518.27  5550.6    1521  5577.4 1528.37
  5598.3 1527.24  5615.4    1538  5656.3 1543.93  5782.6 1558.25  5969.3 1567.37
#Mann= 5 ,-1 , 0
  4745.8     .12       0  5008.3     .05       0  5014.3     .12       0
  5524.2    .035       0  5656.3     .12       0
Bank Sta=5008.3,5014.3
XS Rating Curve= 0 ,0
Exp/Cntr=0.3,0.1

Type RM Length L Ch R = 1 ,11913   ,456,456,456
BEGIN DESCRIPTION:
ZINKE CREEK 26.0
END DESCRIPTION:
XS GIS Cut Line= 3
      2039725.03       13867225.        2040125.       13867275.
      2040967.11     13866819.06
#Sta/Elev= 30
  4596.8 1547.96  4647.2 1539.74  4768.1 1492.56  4848.7 1489.45  4876.4 1482.29
  4881.5 1489.64  4909.2 1481.54  4957.1 1482.54  4969.7    1481  4976.6 1472.59
  4977.1 1472.09  4982.9 1472.59  4989.8 1472.86  4997.4 1480.68    5008 1485.85
  5029.9 1488.79  5170.5 1491.89    5183 1486.99  5204.8 1486.39  5237.2 1488.89
  5242.9  1493.9  5250.1 1494.59  5375.2 1502.61  5420.6 1514.82  5442.7 1516.97
  5510.2 1524.02  5537.8 1534.13  5577.8 1539.42  5603.4 1544.86  5957.5  1564.4
#Mann= 5 ,-1 , 0
  4596.8     .12       0  4976.6     .05       0  4982.9     .12       0
  5442.7    .035       0  5577.8     .12       0
Bank Sta=4976.6,4982.9
XS Rating Curve= 0 ,0
Exp/Cntr=0.3,0.1

Type RM Length L Ch R = 1 ,11457   ,421,421,421
BEGIN DESCRIPTION:
ZINKE CREEK 25.0
END DESCRIPTION:
XS GIS Cut Line= 3
       2039774.8     13867412.92        2039975.       13867675.
       2040195.8     13868037.91
#Sta/Elev= 30
  4670.2 1505.87  4674.5 1505.87  4678.9 1500.76  4693.5  1496.7  4699.8 1492.72
  4714.3 1489.77  4749.6 1487.86  4817.9 1487.01  4949.7 1487.41  4957.4 1484.61
  4973.9 1473.95    4983 1467.95  4983.5 1467.45  4989.8 1467.95  4996.8 1474.69
  5002.9 1474.69  5013.6 1480.15  5023.2 1480.93  5035.1 1485.32  5071.7 1484.43
    5124 1485.94    5277 1486.31  5377.8 1491.25  5386.3 1492.73  5393.3 1495.64
  5399.1  1495.1  5408.7 1497.61  5414.6 1496.86  5420.2 1499.88  5424.8 1499.88
#Mann= 5 ,-1 , 0
  4670.2     .12       0  4817.9     .07       0  4973.9     .12       0
    4983     .05       0  4989.8     .12       0
Bank Sta=4983,4989.8
XS Rating Curve= 0 ,0
Exp/Cntr=0.3,0.1

Type RM Length L Ch R = 1 ,11036   ,445,445,445
BEGIN DESCRIPTION:
ZINKE CREEK 24.0
END DESCRIPTION:
XS GIS Cut Line= 3
       2039310.4     13867729.76        2039775.       13868025.
        2040109.     13868098.68
#Sta/Elev= 30
  4444.9 1543.12  4508.9 1536.72  4517.7 1532.92  4523.6 1533.69    4533 1529.08
  4538.9 1529.46  4554.1 1519.65  4560.1 1521.06  4575.3 1511.58  4596.5  1508.6
  4611.7 1500.25  4617.7 1500.53  4639.9 1492.61  4783.6 1483.88  4907.6 1481.04
  4966.6 1480.35  4987.8  1477.3  5005.6 1473.45  5022.7 1463.16  5023.2 1462.66
  5029.5 1463.16  5063.5 1476.74  5068.6 1473.84  5087.5 1477.86  5097.8 1477.42
  5118.3 1482.68  5261.6 1490.62  5292.2 1494.97  5302.6 1498.74  5337.4  1500.6
#Mann= 6 ,-1 , 0
  4444.9     .07       0  4508.9     .12       0  4783.6     .07       0
  4907.6     .12       0  5022.7     .05       0  5029.5     .12       0
Bank Sta=5022.7,5029.5
XS Rating Curve= 0 ,0
Exp/Cntr=0.3,0.1

Type RM Length L Ch R = 1 ,10591   ,446,446,446
BEGIN DESCRIPTION:
ZINKE CREEK 23.0
END DESCRIPTION:
XS GIS Cut Line= 3
      2039141.11     13867998.85        2039525.       13868375.
      2039909.34     13868497.98
#Sta/Elev= 30
  4462.5 1532.75  4469.5 1532.36  4476.7 1526.99  4483.7 1526.91  4490.8 1522.31
  4519.1 1512.91  4554.4 1508.99  4561.6 1504.08  4568.6 1504.46  4575.7 1499.85
  4618.1 1488.54  4697.5  1478.3  4780.7 1473.82  4889.8 1474.67  4950.5 1476.38
  4978.7 1466.64  4989.4 1456.24  4989.9 1455.74  4996.3 1456.24  5002.6    1458
  5010.5 1465.25  5018.1 1467.18    5019 1467.16    5063 1475.87  5120.6 1477.83
    5209 1482.02  5304.4 1497.57  5352.2 1502.71  5380.2 1510.68  5403.5 1505.18
#Mann= 9 ,-1 , 0
  4462.5     .12       0  4697.5    .035       0  4889.8     .07       0
  4989.4     .05       0  4996.3     .07       0  5018.1     .12       0
    5019    .035       0  5120.6     .12       0  5352.2     .07       0
Bank Sta=4989.4,4996.3
XS Rating Curve= 0 ,0
Exp/Cntr=0.3,0.1

Type RM Length L Ch R = 1 ,10145   ,343,343,343
BEGIN DESCRIPTION:
ZINKE CREEK 22.0
END DESCRIPTION:
XS GIS Cut Line= 3
      2039010.92     13868124.75        2039175.       13868625.
      2039495.41     13868800.92
#Sta/Elev= 30
  4472.8 1515.87  4500.7 1508.38  4505.9 1509.71  4532.5 1502.32  4537.7 1502.73
  4596.1 1479.15  4609.5 1476.62  4621.9 1475.69    4673 1471.83  4790.3 1469.75
  4919.7  1470.1  4936.7  1466.5  4951.5 1464.45  4957.2 1460.53  4978.1 1454.59
  4985.2 1454.29  4985.7 1453.79  4992.2 1454.29  4996.6 1456.85  5007.3 1458.64
    5013 1466.09  5034.8 1469.37  5071.1 1469.33  5147.6 1471.48  5154.2 1473.26
    5176 1473.17    5256 1478.63  5292.2 1484.59  5330.1 1494.05  5364.8 1498.28
#Mann= 9 ,-1 , 0
  4472.8     .07       0  4609.5     .12       0  4621.9    .035       0
  4790.3     .07       0  4936.7     .12       0  4985.2     .05       0
  4992.2     .12       0  5071.1    .035       0  5292.2     .12       0
Bank Sta=4985.2,4992.2
XS Rating Curve= 0 ,0
Exp/Cntr=0.3,0.1

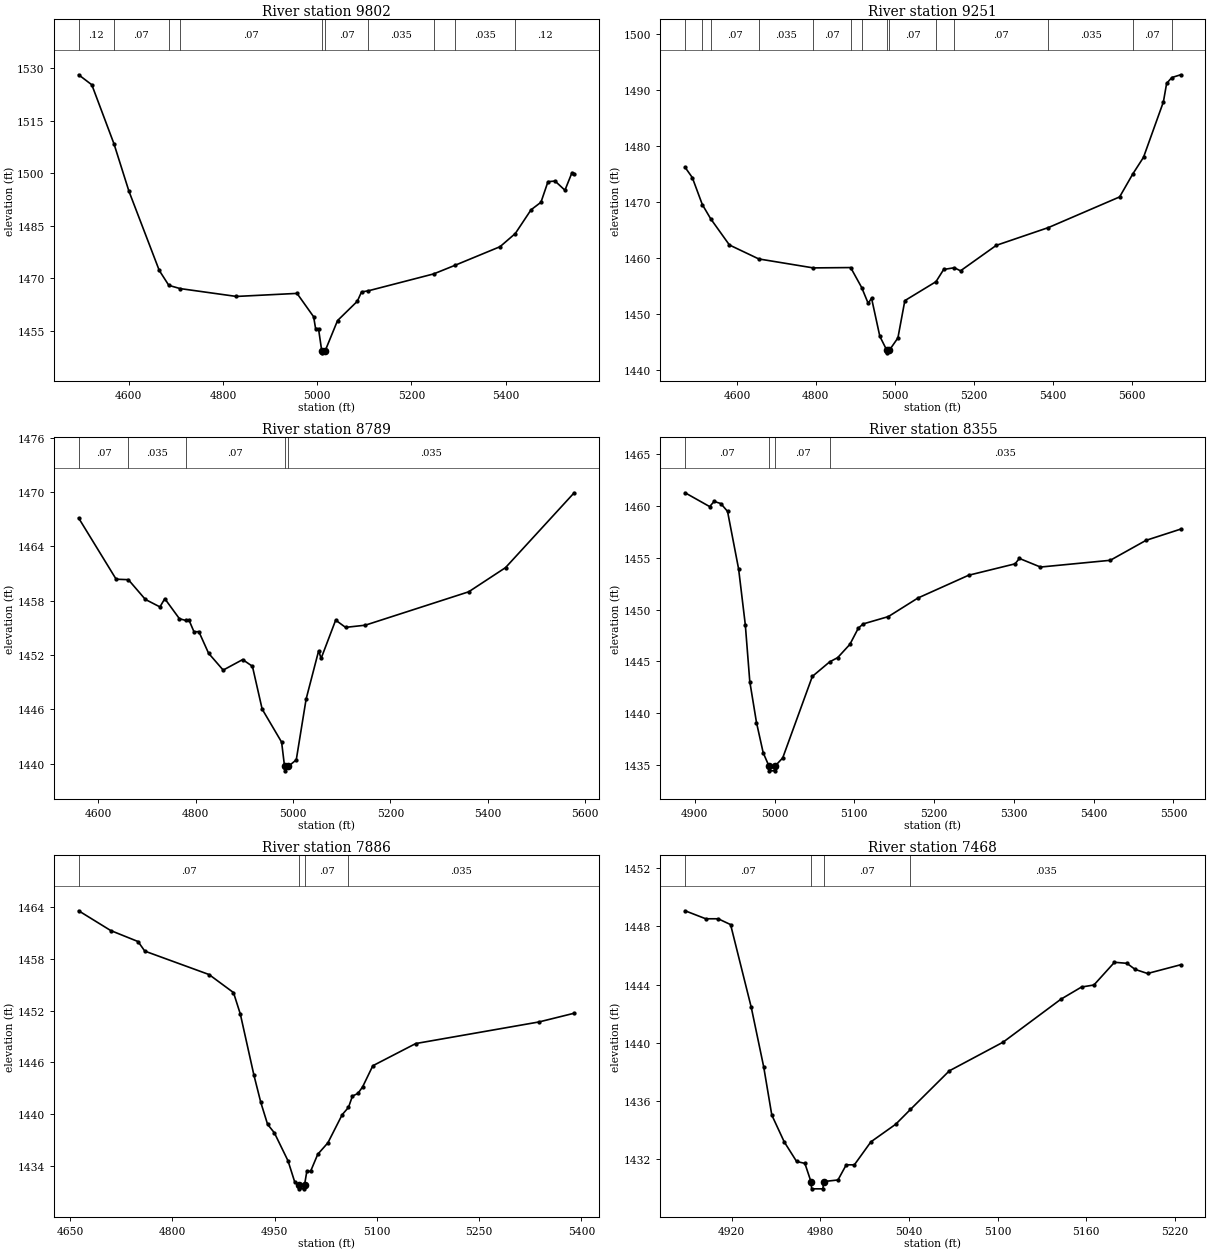
Type RM Length L Ch R = 1 ,9802    ,551,551,551
BEGIN DESCRIPTION:
ZINKE CREEK 21.0
END DESCRIPTION:
XS GIS Cut Line= 3
      2038575.04     13868525.03      2038975.17     13868835.07
      2039427.36      13869140.2
#Sta/Elev= 30
  4493.8 1528.08  4521.8 1525.22  4568.8  1508.4  4600.6 1494.87  4664.9  1472.3
  4685.2 1468.04  4709.2 1467.12  4828.7 1464.88  4957.3 1465.75  4992.6 1459.07
  4996.7 1455.71  5002.9 1455.71  5009.8  1449.3  5010.3  1448.8  5016.8  1449.3
  5043.3    1458  5085.3 1463.51  5094.2 1466.17  5108.1 1466.47  5247.2  1471.3
  5291.7 1473.71  5388.1 1479.06  5420.5 1482.81    5454 1489.59    5475 1491.73
  5489.9  1497.6  5504.9 1497.78  5525.9 1495.16  5540.9 1500.19  5545.5  1499.9
#Mann= 10 ,-1 , 0
  4493.8     .12       0  4568.8     .07       0  4685.2     .12       0
  4709.2     .07       0  5009.8     .05       0  5016.8     .07       0
  5108.1    .035       0  5247.2     .07       0  5291.7    .035       0
  5420.5     .12       0
Bank Sta=5009.8,5016.8
XS Rating Curve= 0 ,0
Exp/Cntr=0.3,0.1

Type RM Length L Ch R = 1 ,9251    ,462,462,462
BEGIN DESCRIPTION:
ZINKE CREEK 20.0
END DESCRIPTION:
XS GIS Cut Line= 3
      2038321.43     13868782.41        2038625.       13869225.
      2039338.37     13869314.01
#Sta/Elev= 30
  4468.7 1476.26  4486.9 1474.44  4512.3 1469.62  4533.5 1467.08    4581  1462.4
  4655.4 1459.91  4793.4 1458.31  4888.2 1458.37  4916.1 1454.81  4932.6 1451.98
  4941.1 1452.91  4962.1  1446.1  4979.5 1443.65    4980 1443.15  4986.6 1443.65
  5007.9 1445.81  5025.5 1452.47  5104.4 1455.85  5123.9 1458.03  5150.8 1458.34
  5166.6 1457.79  5257.3 1462.34  5389.3 1465.51  5569.7 1470.98    5603 1475.07
  5630.2 1478.05  5680.6 1487.94  5688.8 1491.24    5702 1492.29  5724.3 1492.78
#Mann= 14 ,-1 , 0
  4468.7     .07       0  4512.3     .12       0  4533.5     .07       0
  4655.4    .035       0  4793.4     .07       0  4888.2    .035       0
  4916.1     .07       0  4979.5     .05       0  4986.6     .07       0
  5104.4    .035       0  5150.8     .07       0  5389.3    .035       0
    5603     .07       0    5702     .12       0
Bank Sta=4979.5,4986.6
XS Rating Curve= 0 ,0
Exp/Cntr=0.3,0.1

Type RM Length L Ch R = 1 ,8789    ,434,434,434
BEGIN DESCRIPTION:
ZINKE CREEK 19.0
END DESCRIPTION:
XS GIS Cut Line= 3
      2038225.32     13868827.87      2038220.66     13869261.98
      2038312.13     13869839.14
#Sta/Elev= 30
  4559.2 1467.14  4636.3 1460.38  4661.4 1460.33  4696.3 1458.15  4726.3 1457.32
  4736.3 1458.23  4766.3 1456.02  4779.7 1455.82  4786.3 1455.83  4796.3 1454.57
  4806.3 1454.59  4826.3  1452.2  4856.3 1450.34  4896.3  1451.5  4916.4 1450.76
  4936.4 1446.03  4976.4 1442.38  4982.4 1439.71  4982.9 1439.21  4990.3 1439.71
  5006.5 1440.42  5026.8 1447.15  5052.5 1452.47  5057.6 1451.63  5087.5 1455.86
  5107.8 1455.06  5148.3  1455.3  5360.9 1458.99  5436.6 1461.66  5577.7 1469.93
#Mann= 5 ,-1 , 0
  4559.2     .07       0  4661.4    .035       0  4779.7     .07       0
  4982.4    .035       0  4990.3    .035       0
Bank Sta=4982.4,4990.3
XS Rating Curve= 0 ,0
Exp/Cntr=0.3,0.1

Type RM Length L Ch R = 1 ,8355    ,469,469,469
BEGIN DESCRIPTION:
ZINKE CREEK 18.0
END DESCRIPTION:
XS GIS Cut Line= 3
      2037774.96     13869274.98        2037875.       13869325.
      2038034.36     13869808.78
#Sta/Elev= 30
  4887.9 1461.24  4918.7 1459.91  4924.3 1460.41  4932.7  1460.2  4941.1 1459.45
    4955  1453.9  4963.4 1448.52    4969 1443.06  4977.4 1439.12  4985.8 1436.21
  4992.8 1434.97  4993.3 1434.47  5000.7 1434.47  5001.2 1434.97  5010.3 1435.72
  5047.4 1443.56  5069.1 1444.96  5079.2 1445.37  5094.5 1446.65    5105  1448.2
    5111 1448.61  5142.7 1449.32  5179.8 1451.11  5243.3  1453.3  5301.6  1454.4
  5306.9 1454.92  5333.4 1454.09  5420.9 1454.74  5465.7 1456.66  5509.1 1457.74
#Mann= 4 ,-1 , 0
  4887.9     .07       0  4992.8     .05       0  5001.2     .07       0
  5069.1    .035       0
Bank Sta=4992.8,5001.2
XS Rating Curve= 0 ,0
Exp/Cntr=0.3,0.1

Type RM Length L Ch R = 1 ,7886    ,418,418,418
BEGIN DESCRIPTION:
ZINKE CREEK 17.0
END DESCRIPTION:
XS GIS Cut Line= 3
      2037513.51     13869287.94        2037525.       13869625.
      2037847.75     13869843.49
#Sta/Elev= 30
  4662.5 1463.55  4709.6 1461.26  4749.6 1459.99  4759.6 1458.88  4853.8 1456.17
  4889.7 1454.08  4899.7  1451.6  4919.7 1444.51  4929.7 1441.38  4939.7 1438.83
  4949.7 1437.84  4969.7  1434.6  4979.7 1432.11  4985.5 1431.86    4986 1431.36
  4993.5 1431.36    4994 1431.86  4997.3 1433.39  5002.8 1433.39  5013.3 1435.36
  5028.2 1436.69  5049.2 1439.95  5058.4 1440.79  5064.2  1442.1  5072.2  1442.4
  5079.1 1443.16  5094.1 1445.61  5157.1 1448.18  5337.9 1450.68  5389.5 1451.69
#Mann= 4 ,-1 , 0
  4662.5     .07       0  4985.5     .05       0    4994     .07       0
  5058.4    .035       0
Bank Sta=4985.5,4994
XS Rating Curve= 0 ,0
Exp/Cntr=0.3,0.1

Type RM Length L Ch R = 1 ,7468    ,423,423,423
BEGIN DESCRIPTION:
ZINKE CREEK 16.0
END DESCRIPTION:
XS GIS Cut Line= 3
      2037124.98     13869724.96        2037175.       13869825.
      2037375.04     13869925.02
#Sta/Elev= 30
  4888.4 1449.07  4902.4 1448.52  4910.8 1448.52  4919.2 1448.12  4933.2 1442.43
  4941.6 1438.35  4947.1 1435.03  4955.5 1433.19  4963.9 1431.84  4969.5 1431.71
  4973.6 1430.46  4974.1 1429.96  4981.7 1429.96  4982.2 1430.46  4991.9 1430.57
  4997.5 1431.61    5003 1431.61  5014.2 1433.19    5031  1434.4    5041 1435.42
  5067.3 1438.07  5103.7 1440.04  5142.8 1442.99  5156.8 1443.83  5165.2 1443.97
  5179.1 1445.53  5187.5 1445.46  5193.1 1445.04  5201.5 1444.76  5223.9 1445.36
#Mann= 4 ,-1 , 0
  4888.4     .07       0  4973.6     .05       0  4982.2     .07       0
    5041    .035       0
Bank Sta=4973.6,4982.2
XS Rating Curve= 0 ,0
Exp/Cntr=0.3,0.1