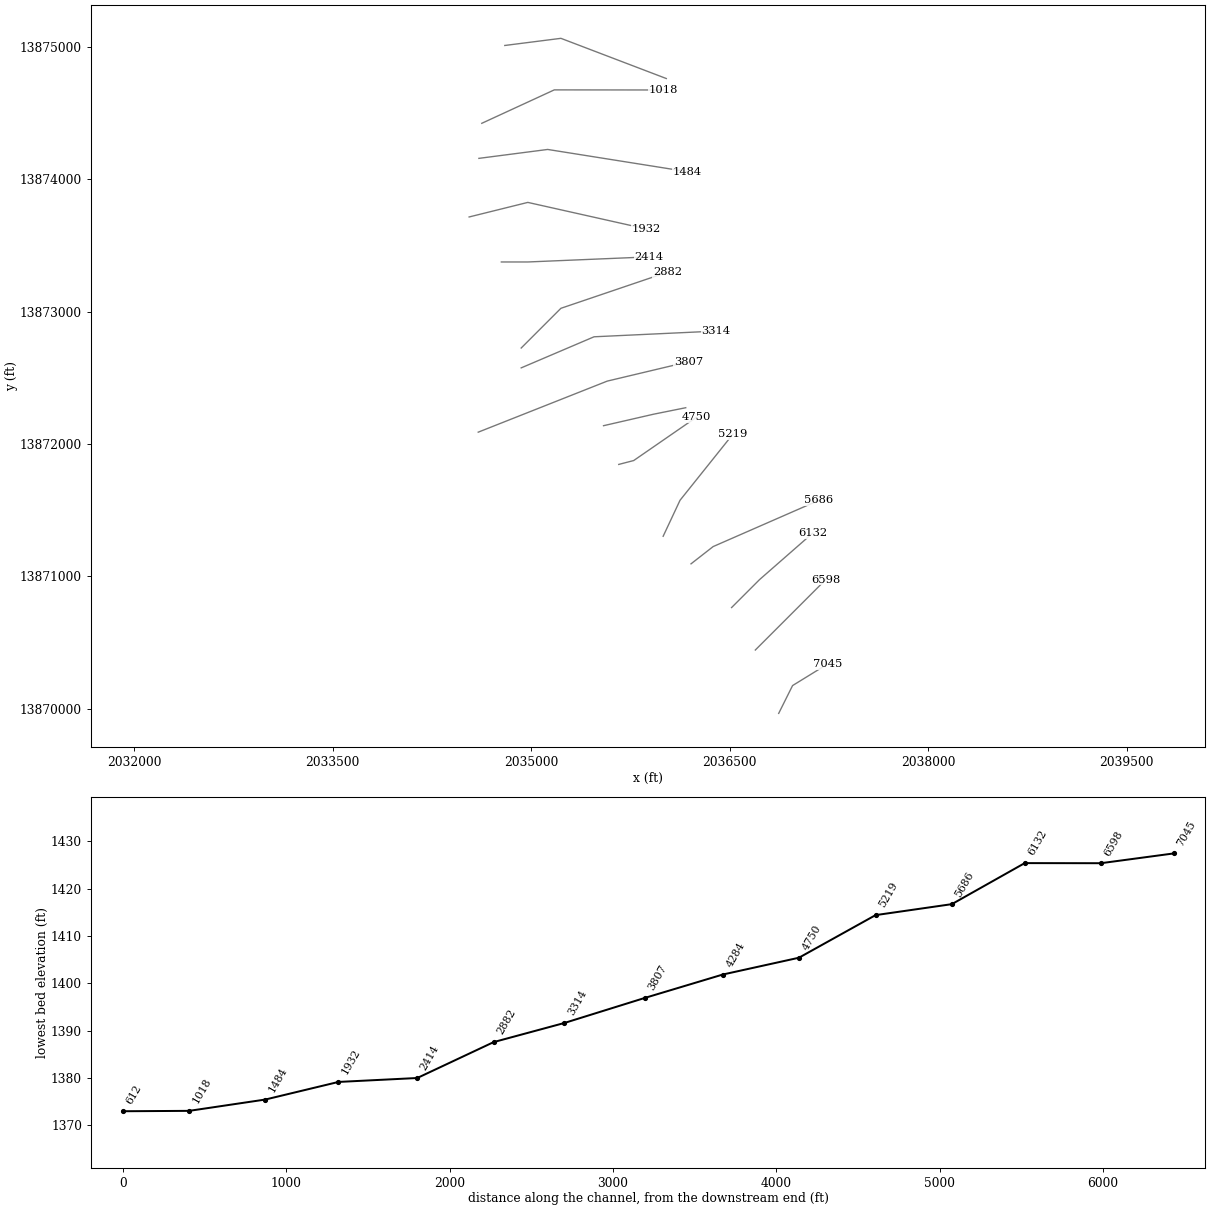
HEC-RAS study ZINKE CREEK.prj: ZINKE CREEK Base Level Engineering

--- ZINKE CREEK.g01 (geometry) --- (continued)

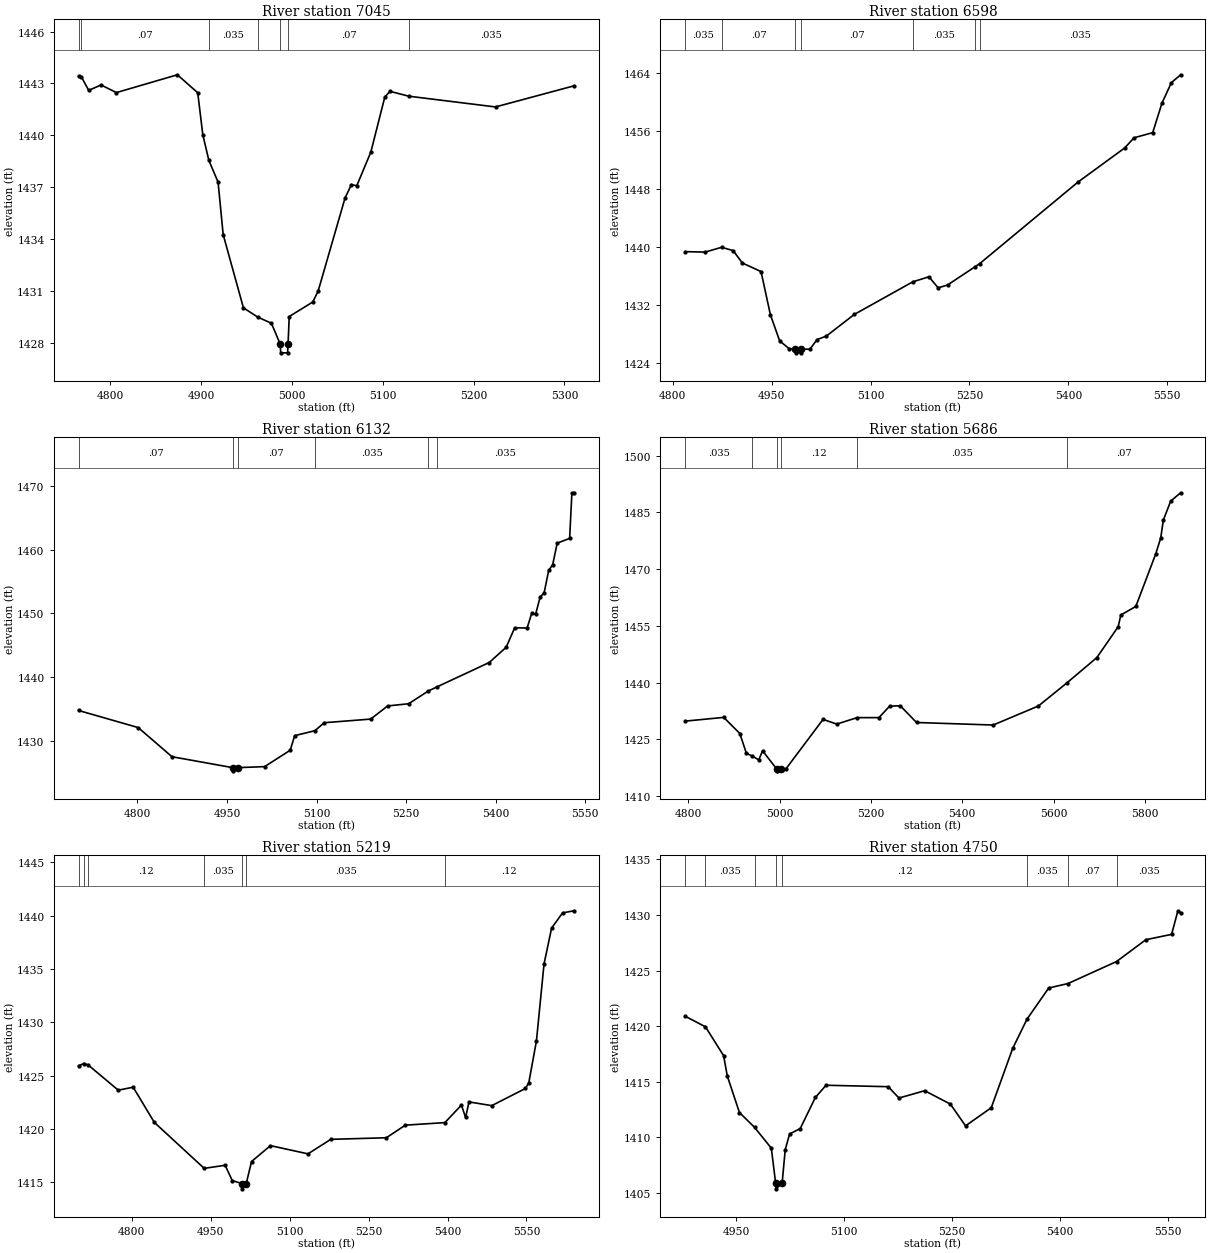
Type RM Length L Ch R = 1 ,7045    ,447,447,447
BEGIN DESCRIPTION:
ZINKE CREEK 15.0
END DESCRIPTION:
XS GIS Cut Line= 3
      2036870.22       13869965.        2036975.       13870175.
      2037239.49     13870337.67
#Sta/Elev= 30
  4765.3 1443.42  4768.6 1443.37  4776.5  1442.6  4790.2 1442.91    4807 1442.47
  4874.1  1443.5  4896.5 1442.46  4902.1 1440.03  4908.7 1438.56  4918.9 1437.29
  4924.5 1434.26  4946.8 1430.02  4962.5 1429.49  4977.6 1429.13  4987.3 1427.92
  4987.8 1427.42  4995.4 1427.42  4995.9 1427.92  4997.2 1429.52  5023.1 1430.36
    5029 1430.99  5058.7 1436.39  5065.7 1437.15  5071.5 1437.08    5087 1439.03
  5102.4 1442.22  5108.2 1442.54  5128.9 1442.26  5224.2 1441.64  5310.5 1442.86
#Mann= 7 ,-1 , 0
  4765.3    .035       0  4768.6     .07       0  4908.7    .035       0
  4962.5     .07       0  4987.3     .05       0  4995.9     .07       0
  5128.9    .035       0
Bank Sta=4987.3,4995.9
XS Rating Curve= 0 ,0
Exp/Cntr=0.3,0.1

Type RM Length L Ch R = 1 ,6598    ,466,466,466
BEGIN DESCRIPTION:
ZINKE CREEK 14.0
END DESCRIPTION:
XS GIS Cut Line= 3
      2036693.66     13870443.67        2036825.       13870575.
      2037224.99     13870974.99
#Sta/Elev= 30
  4818.9 1439.32  4849.1 1439.26  4874.1 1439.92  4891.5 1439.47  4905.6 1437.75
  4933.9 1436.57  4948.1 1430.61  4962.2 1426.99  4976.4 1425.94  4986.1 1425.85
  4986.6 1425.35  4994.3 1425.35  4994.8 1425.85  5008.2 1425.86  5018.8 1427.18
  5032.9 1427.66  5075.3 1430.65  5164.2 1435.16  5188.5 1435.85  5202.6 1434.32
  5216.8 1434.72  5258.7 1437.25  5265.7 1437.68  5414.8 1448.94  5485.5 1453.64
  5499.6 1455.04  5527.9 1455.75    5542 1459.83  5556.2 1462.65  5570.3 1463.74
#Mann= 7 ,-1 , 0
  4818.9    .035       0  4874.1     .07       0  4986.1     .05       0
  4994.8     .07       0  5164.2    .035       0  5258.7     .07       0
  5265.7    .035       0
Bank Sta=4986.1,4994.8
XS Rating Curve= 0 ,0
Exp/Cntr=0.3,0.1

Type RM Length L Ch R = 1 ,6132    ,446,446,446
BEGIN DESCRIPTION:
ZINKE CREEK 13.0
END DESCRIPTION:
XS GIS Cut Line= 3
      2036514.32     13870764.32        2036725.       13870975.
      2037125.04     13871325.03
#Sta/Elev= 30
  4701.5 1434.82  4801.5 1432.14    4858 1427.58  4959.7 1425.87  4960.2 1425.37
  4968.4 1425.87  5013.2 1426.03  5055.9 1428.59  5063.5 1430.88  5097.3 1431.65
  5112.9  1432.9  5190.7 1433.47  5219.2 1435.53  5254.3 1435.87  5286.9 1437.85
    5301 1438.48  5389.1 1442.32  5417.5  1444.7  5431.8 1447.76  5452.6 1447.72
  5460.2    1450  5466.9 1449.89  5474.5  1452.6  5481.1 1453.22  5488.7 1456.74
  5495.4 1457.63    5503 1461.01  5523.8 1461.75  5527.6 1468.89    5531 1468.89
#Mann= 6 ,-1 , 0
  4701.5     .07       0  4959.7     .05       0  4968.4     .07       0
  5097.3    .035       0  5286.9     .07       0    5301    .035       0
Bank Sta=4959.7,4968.4
XS Rating Curve= 0 ,0
Exp/Cntr=0.3,0.1

Type RM Length L Ch R = 1 ,5686    ,467,467,467
BEGIN DESCRIPTION:
ZINKE CREEK 12.0
END DESCRIPTION:
XS GIS Cut Line= 3
      2036207.92     13871094.69        2036375.       13871225.
        2037175.       13871575.
#Sta/Elev= 30
  4793.3 1429.84  4877.6 1430.83  4912.9 1426.57  4927.4  1421.3  4939.3 1420.67
  4954.5  1419.6  4962.7    1422  4993.6  1417.2  4994.1  1416.7  5002.3  1417.2
  5014.2 1417.27  5095.2  1430.3  5125.3 1429.06  5169.6 1430.76  5217.6 1430.77
    5241  1433.8  5264.4  1433.9  5299.9 1429.48  5467.9 1428.81  5566.9 1433.85
    5629 1439.92  5694.8 1446.63  5741.6  1454.8  5747.4 1457.89  5780.2 1460.16
  5823.8 1474.03  5834.7 1478.23  5840.6 1483.02  5856.6 1488.01  5878.4 1490.21
#Mann= 6 ,-1 , 0
  4793.3    .035       0  4939.3     .12       0  4993.6     .05       0
  5002.3     .12       0  5169.6    .035       0    5629     .07       0
Bank Sta=4993.6,5002.3
XS Rating Curve= 0 ,0
Exp/Cntr=0.3,0.1

Type RM Length L Ch R = 1 ,5219    ,469,469,469
BEGIN DESCRIPTION:
ZINKE CREEK 11.0
END DESCRIPTION:
XS GIS Cut Line= 3
      2035997.35     13871302.88        2036125.       13871575.
      2036525.01     13872075.01
#Sta/Elev= 30
  4699.2 1425.92  4709.6 1426.13  4717.7 1425.99  4774.7 1423.63    4803 1423.91
  4843.2 1420.61  4937.9  1416.3  4977.7 1416.59  4991.1 1415.16    5009 1414.88
  5009.5 1414.38  5017.8 1414.88  5027.8 1416.94  5063.8 1418.43    5135 1417.66
  5178.3 1419.02  5283.9 1419.17  5319.9 1420.35    5395 1420.59  5426.4 1422.23
  5434.4 1421.07  5440.8 1422.53    5484 1422.18    5548 1423.79  5554.4 1424.33
  5568.9 1428.25  5583.3 1435.46  5597.7 1438.83  5618.5 1440.25  5640.1 1440.45
#Mann= 7 ,-1 , 0
  4699.2     .12       0  4709.6    .035       0  4717.7     .12       0
  4937.9    .035       0    5009    .035       0  5017.8    .035       0
    5395     .12       0
Bank Sta=5009,5017.8
XS Rating Curve= 0 ,0
Exp/Cntr=0.3,0.1

Type RM Length L Ch R = 1 ,4750    ,466,466,466
BEGIN DESCRIPTION:
ZINKE CREEK 10.0
END DESCRIPTION:
XS GIS Cut Line= 3
      2035661.99     13871845.64        2035775.       13871875.
      2036246.01     13872200.14
#Sta/Elev= 30
  4878.8 1420.89    4907 1419.94  4932.2 1417.35  4937.3 1415.53  4954.2 1412.24
  4975.2 1410.91  4998.6 1409.03  5004.6 1405.88  5005.1 1405.38  5013.6 1405.88
  5017.9  1408.9    5024 1410.31  5038.8  1410.8  5059.8 1413.59  5074.7 1414.69
  5161.2 1414.56  5176.1 1413.54  5211.9  1414.2  5247.7 1412.99  5268.7 1411.04
  5304.5 1412.67  5334.3    1418  5354.2 1420.63  5384.4 1423.43  5411.2 1423.83
  5478.8 1425.81  5519.5 1427.77  5555.3 1428.25  5564.1 1430.37  5567.9  1430.2
#Mann= 8 ,-1 , 0
  4878.8     .07       0    4907    .035       0  4975.2     .12       0
  5004.6     .05       0  5013.6     .12       0  5354.2    .035       0
  5411.2     .07       0  5478.8    .035       0
Bank Sta=5004.6,5013.6
XS Rating Curve= 0 ,0
Exp/Cntr=0.3,0.1

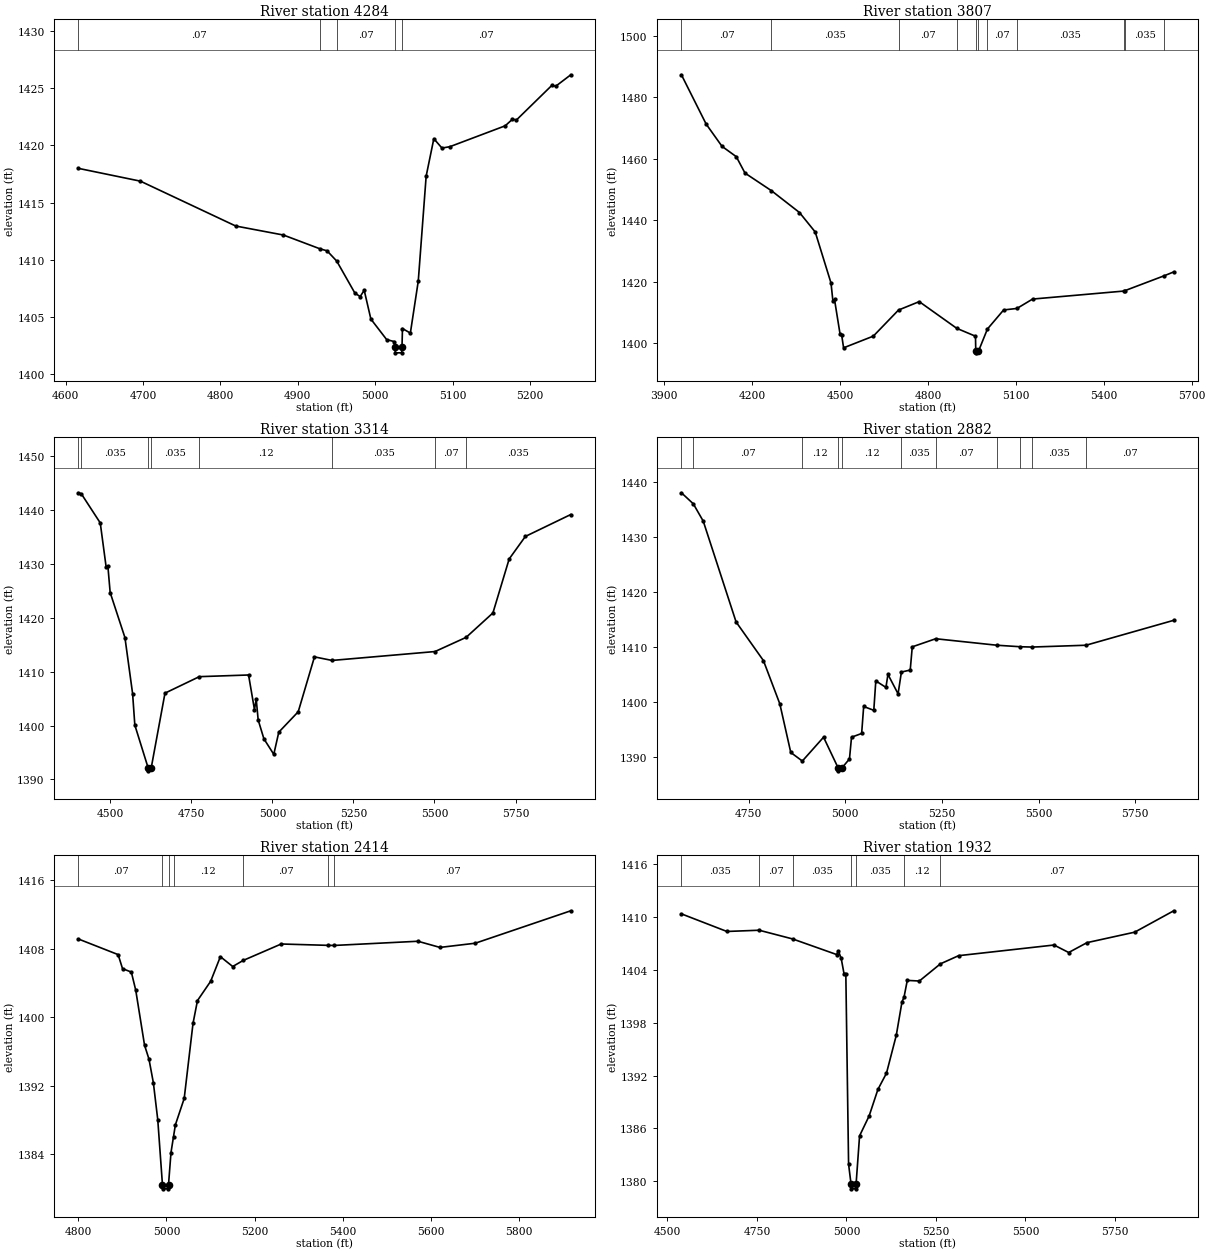
Type RM Length L Ch R = 1 ,4284    ,477,477,477
BEGIN DESCRIPTION:
ZINKE CREEK 9.0
END DESCRIPTION:
XS GIS Cut Line= 3
      2035547.01     13872138.17        2035925.       13872225.
      2036168.07     13872274.03
#Sta/Elev= 30
  4616.7 1417.99  4696.7 1416.87  4819.8 1412.94  4881.4 1412.15  4928.7 1410.94
  4937.7 1410.77  4950.2 1409.87  4973.7 1407.06  4980.5 1406.76  4985.7 1407.31
  4994.3 1404.79  5014.7 1402.99  5024.8 1402.81  5025.4 1402.33  5025.9 1401.83
    5034 1401.83  5034.5 1402.33  5035.1 1403.96  5045.3 1403.56  5055.5 1408.11
  5065.7 1417.31  5075.6 1420.59  5086.1 1419.77  5096.3 1419.89  5167.8 1421.72
  5177.2  1422.3  5182.3 1422.23    5228 1425.26  5233.1 1425.19  5252.5 1426.19
#Mann= 5 ,-1 , 0
  4616.7     .07       0  4928.7     .12       0  4950.2     .07       0
  5025.4     .05       0  5034.5     .07       0
Bank Sta=5025.4,5034.5
XS Rating Curve= 0 ,0
Exp/Cntr=0.3,0.1

Type RM Length L Ch R = 1 ,3807    ,493,493,493
BEGIN DESCRIPTION:
ZINKE CREEK 8.0
END DESCRIPTION:
XS GIS Cut Line= 3
      2034600.42      13872089.3        2035575.       13872475.
      2036189.72     13872621.24
#Sta/Elev= 30
  3958.9 1487.28  4043.4 1471.24  4097.5 1464.01  4146.1 1460.66  4175.9 1455.32
  4266.2 1449.59  4361.7 1442.51  4415.5 1436.17  4469.3 1419.61  4475.9  1413.7
  4481.3 1414.23  4500.2 1403.02  4505.6 1402.75  4512.3 1398.52  4613.7 1402.32
  4699.7  1410.8  4770.4 1413.54  4898.4 1404.86  4962.4 1402.29  4963.3 1397.39
  4963.8 1396.89  4972.4 1397.39  5003.1 1404.63  5058.4 1410.83  5103.8 1411.32
  5157.2 1414.37  5468.3 1416.97  5472.7 1417.12  5606.5 1421.95  5638.9  1423.2
#Mann= 11 ,-1 , 0
  3958.9     .07       0  4266.2    .035       0  4699.7     .07       0
  4898.4     .12       0  4963.3     .05       0  4972.4     .12       0
  5003.1     .07       0  5103.8    .035       0  5468.3     .07       0
  5472.7    .035       0  5606.5     .07       0
Bank Sta=4963.3,4972.4
XS Rating Curve= 0 ,0
Exp/Cntr=0.3,0.1

Type RM Length L Ch R = 1 ,3314    ,432,432,432
BEGIN DESCRIPTION:
ZINKE CREEK 7.0
END DESCRIPTION:
XS GIS Cut Line= 3
      2034925.03     13872575.01      2035475.44     13872809.82
      2036395.03      13872852.9
#Sta/Elev= 30
  4401.6 1443.17  4410.4 1442.98  4468.8 1437.58  4486.9 1429.43  4492.4 1429.51
  4499.4 1424.66    4545  1416.3  4568.6 1405.92  4575.5 1400.07  4616.8 1392.09
  4617.3 1391.59  4625.9 1392.09  4668.5    1406  4774.4 1409.06  4926.4 1409.37
  4944.6 1402.95    4950 1404.89    4956 1401.04  4973.7 1397.53  5004.2 1394.65
  5019.6 1398.76  5079.6 1402.55  5129.7 1412.73  5183.9 1412.07  5501.7 1413.72
  5597.6 1416.35  5680.3 1420.88  5730.4 1430.89  5780.4 1435.07  5920.6 1439.14
#Mann= 8 ,-1 , 0
  4401.6     .07       0  4410.4    .035       0  4616.8     .05       0
  4625.9    .035       0  4774.4     .12       0  5183.9    .035       0
  5501.7     .07       0  5597.6    .035       0
Bank Sta=4616.8,4625.9
XS Rating Curve= 0 ,0
Exp/Cntr=0.3,0.1

Type RM Length L Ch R = 1 ,2882    ,468,468,468
BEGIN DESCRIPTION:
ZINKE CREEK 6.0
END DESCRIPTION:
XS GIS Cut Line= 3
      2034925.03     13872725.03        2035225.       13873025.
      2036029.01     13873297.64
#Sta/Elev= 30
  4576.3 1438.08  4607.1 1436.07  4632.8 1432.92  4717.7 1414.61  4788.4 1407.59
  4830.8 1399.73  4859.1  1390.9    4889 1389.34  4943.9 1393.67  4981.8 1388.06
  4982.3 1387.56    4991 1388.06  5010.9 1389.72  5016.2 1393.67  5042.4 1394.35
  5047.6 1399.25  5073.8 1398.56    5079  1403.9  5105.2 1402.72  5110.4 1405.08
  5136.6 1401.55  5145.2 1405.51    5168 1405.87  5173.3 1410.09  5233.9 1411.56
  5392.3 1410.38    5452 1410.11  5482.5 1410.05  5622.6 1410.38  5849.5 1414.91
#Mann= 11 ,-1 , 0
  4576.3    .035       0  4607.1     .07       0    4889     .12       0
  4981.8     .05       0    4991     .12       0  5145.2    .035       0
  5233.9     .07       0  5392.3    .035       0    5452     .07       0
  5482.5    .035       0  5622.6     .07       0
Bank Sta=4981.8,4991
XS Rating Curve= 0 ,0
Exp/Cntr=0.3,0.1

Type RM Length L Ch R = 1 ,2414    ,482,482,482
BEGIN DESCRIPTION:
ZINKE CREEK 5.0
END DESCRIPTION:
XS GIS Cut Line= 3
        2034775.       13873375.        2034975.       13873375.
       2035891.7     13873413.54
#Sta/Elev= 30
  4800.4 1409.15  4890.4 1407.33  4900.4 1405.69  4920.4 1405.29  4930.4 1403.17
  4950.4 1396.74  4960.4 1395.13  4970.4 1392.36  4980.4 1388.03    4991 1380.47
  4991.5 1379.97  5004.3 1379.97  5004.8 1380.47  5010.4 1384.21  5016.1 1386.06
  5020.4 1387.45  5040.4 1390.53  5060.4  1399.3  5070.5 1401.96  5100.5 1404.22
  5122.5 1407.09  5150.5 1405.94  5174.3 1406.65  5260.6 1408.57  5367.7 1408.41
  5380.7  1408.4  5570.9 1408.89  5620.9 1408.17    5701 1408.66  5917.9 1412.45
#Mann= 7 ,-1 , 0
  4800.4     .07       0    4991     .05       0  5004.8     .07       0
  5016.1     .12       0  5174.3     .07       0  5367.7    .035       0
  5380.7     .07       0
Bank Sta=4991,5004.8
XS Rating Curve= 0 ,0
Exp/Cntr=0.3,0.1

Type RM Length L Ch R = 1 ,1932    ,448,448,448
BEGIN DESCRIPTION:
ZINKE CREEK 4.0
END DESCRIPTION:
XS GIS Cut Line= 3
       2034531.7     13873714.99        2034975.       13873825.
      2035871.44     13873624.18
#Sta/Elev= 30
    4539 1410.38    4666 1408.38  4756.2 1408.52  4849.7 1407.53  4972.5 1405.76
  4977.6 1406.16  4985.4 1405.31  4993.2  1403.6  4998.3  1403.6    5006 1381.94
    5013 1379.64  5013.5 1379.14  5026.4 1379.14  5026.9 1379.64  5036.7 1385.16
  5063.4 1387.42    5088 1390.44  5111.9 1392.28  5139.2 1396.57  5155.2 1400.38
  5160.8  1400.9    5170 1402.82  5203.7 1402.75  5262.5  1404.7  5313.4 1405.63
  5579.9 1406.84  5620.9 1405.99  5672.1 1407.11  5805.3  1408.3  5914.4 1410.73
#Mann= 7 ,-1 , 0
    4539    .035       0  4756.2     .07       0  4849.7    .035       0
    5013    .035       0  5026.9    .035       0  5160.8     .12       0
  5262.5     .07       0
Bank Sta=5013,5026.9
XS Rating Curve= 0 ,0
Exp/Cntr=0.3,0.1

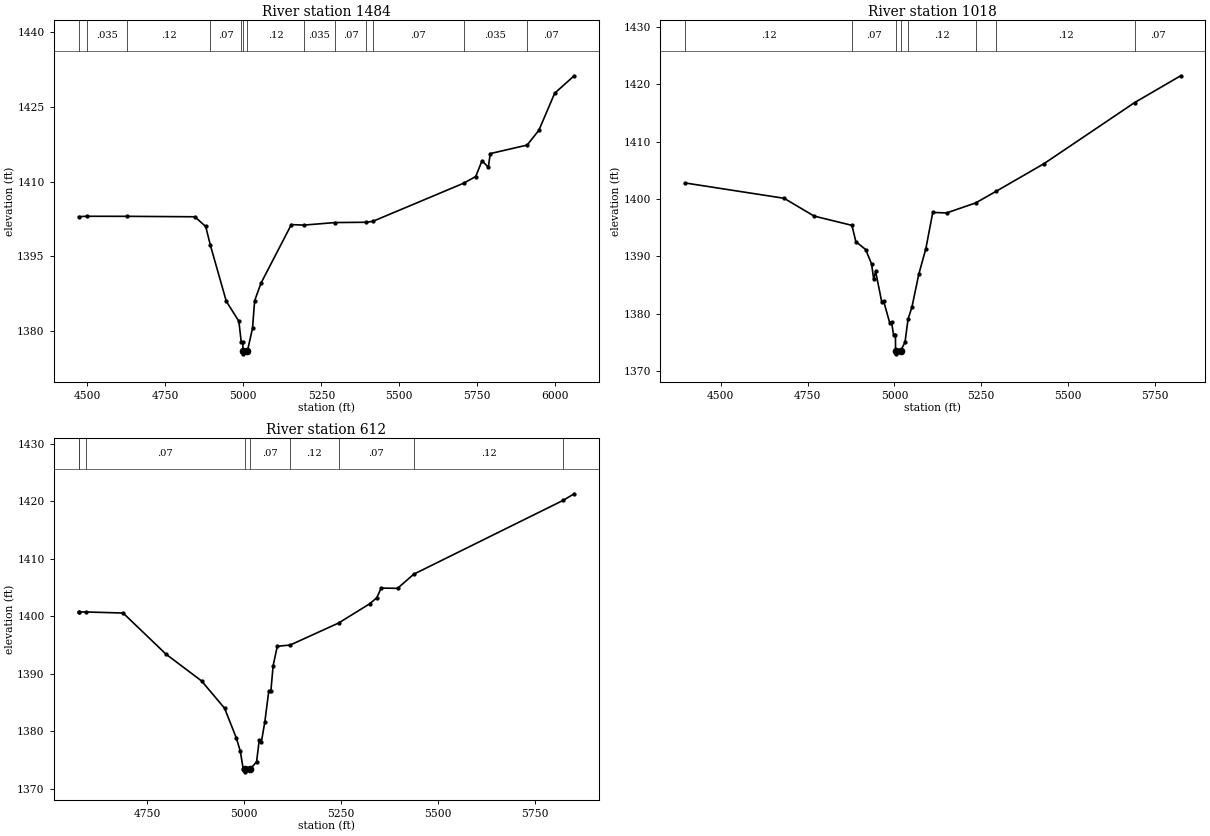
Type RM Length L Ch R = 1 ,1484    ,466,466,466
BEGIN DESCRIPTION:
ZINKE CREEK 3.0
END DESCRIPTION:
XS GIS Cut Line= 3
      2034605.53     13874157.71        2035125.       13874225.
       2036176.7     13874057.88
#Sta/Elev= 30
  4471.9 1402.96  4498.3 1403.03  4625.6 1403.02  4844.5 1402.93  4879.3 1400.98
  4894.2 1397.24  4945.3 1385.97  4985.6 1381.96  4993.2  1377.8  4998.2  1377.8
  4998.9 1375.92  4999.4 1375.42  5012.8 1375.92  5029.4 1380.57  5036.2 1386.09
  5056.5  1389.6  5153.8 1401.36  5193.7 1401.26    5294 1401.77  5394.3 1401.83
  5415.3 1402.02  5706.3 1409.67    5745 1411.01  5765.2 1414.18  5785.5 1412.85
  5791.4 1415.61  5909.7 1417.32  5947.5  1420.3  5998.1 1427.73  6060.6 1431.23
#Mann= 13 ,-1 , 0
  4471.9     .12       0  4498.3    .035       0  4625.6     .12       0
  4894.2     .07       0  4993.2     .12       0  4998.9     .05       0
  5012.8     .12       0  5193.7    .035       0    5294     .07       0
  5394.3    .035       0  5415.3     .07       0  5706.3    .035       0
  5909.7     .07       0
Bank Sta=4998.9,5012.8
XS Rating Curve= 0 ,0
Exp/Cntr=0.3,0.1

Type RM Length L Ch R = 1 ,1018    ,406,406,406
BEGIN DESCRIPTION:
ZINKE CREEK 2.0
END DESCRIPTION:
XS GIS Cut Line= 3
       2034627.2     13874422.45        2035175.       13874675.
      2035998.78      13874674.2
#Sta/Elev= 30
  4397.2 1402.81  4682.3 1400.14  4768.6 1397.04  4877.7 1395.42  4888.9 1392.58
  4917.3  1391.2  4934.3 1388.68  4940.3 1386.02  4945.8 1387.41  4963.2 1382.15
  4968.7 1382.26  4986.2 1378.49  4991.7 1378.58  4997.7 1376.24  5002.9 1376.24
  5003.3 1373.53  5003.8 1373.03  5017.5 1373.53  5030.4 1375.04  5039.3 1379.09
  5050.4 1381.18  5070.4 1386.97  5090.4 1391.33  5110.4 1397.67  5150.4 1397.59
  5233.9 1399.33  5293.8 1401.39  5430.4 1406.16  5691.7 1416.82  5824.2 1421.49
#Mann= 8 ,-1 , 0
  4397.2     .12       0  4877.7     .07       0  5003.3     .05       0
  5017.5     .07       0  5039.3     .12       0  5233.9     .07       0
  5293.8     .12       0  5691.7     .07       0
Bank Sta=5003.3,5017.5
XS Rating Curve= 0 ,0
Exp/Cntr=0.3,0.1

Type RM Length L Ch R = 1 ,612     ,0,0,0
BEGIN DESCRIPTION:
ZINKE CREEK 1.0
END DESCRIPTION:
XS GIS Cut Line= 3
      2034801.15     13875010.48      2035225.03      13875064.4
       2036021.2     13874760.77
#Sta/Elev= 30
  4572.7 1400.77  4573.9 1400.77  4590.7 1400.77  4687.5 1400.58  4798.4 1393.42
    4890 1388.77  4949.6 1384.01  4979.8 1378.84  4989.9 1376.59  4997.5 1373.51
  5001.7 1373.45  5002.2 1372.95  5015.9 1373.45  5032.1 1374.69  5038.9 1378.41
  5044.3 1378.06  5053.5 1381.67  5063.6    1387    5069 1386.99  5074.9 1391.43
  5085.6  1394.8  5118.8 1395.01  5244.1 1398.85  5323.7 1402.17  5342.4 1403.23
  5353.8 1404.92    5396 1404.88    5438 1407.34  5824.1  1420.2  5852.1 1421.33
#Mann= 9 ,-1 , 0
  4572.7    .035       0  4573.9     .12       0  4590.7     .07       0
  5001.7     .05       0  5015.9     .07       0  5118.8     .12       0
  5244.1     .07       0    5438     .12       0  5824.1     .07       0
Bank Sta=5001.7,5015.9
XS Rating Curve= 0 ,0
Exp/Cntr=0.3,0.1

Chan Stop Cuts=-1
Use User Specified Reach Order=0
Composite Channel Slope=5