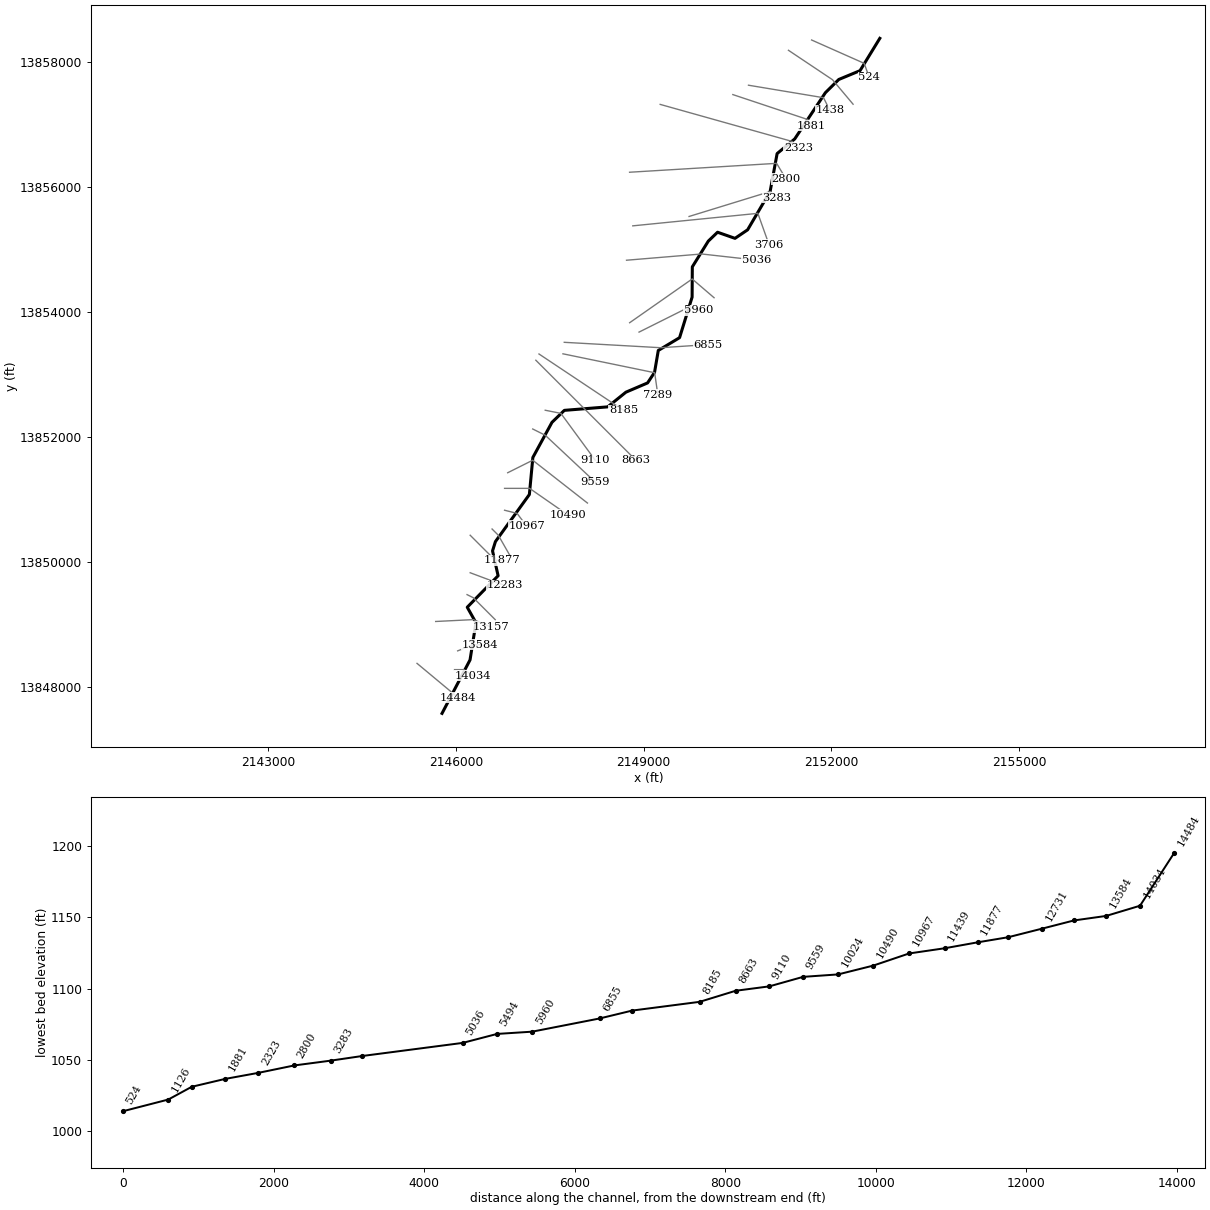
--- Ahern Creek.prj (project) ---

Proj Title=Ahern Creek Base Level Engineering
Current Plan=p01
Default Exp/Contr=0.3,0.1
English Units
Geom File=g01
Flow File=f01
Plan File=p01
Y Axis Title=Elevation
X Axis Title(PF)=Main Channel Distance
X Axis Title(XS)=Station
BEGIN DESCRIPTION:
Ahern Creek
END DESCRIPTION:
DSS Export Rating Curves= 0
DSS Export Rating Curve Sorted= 0
DSS Export Volume Flow Curves= 0
DXF OffsetX= 0
DXF OffsetY= 0
DXF ScaleX= 1
DXF ScaleY= 10

--- Ahern Creek.p01 (plan) ---

Plan Title=Multiple Run
Short Identifier=Multiple
Geom File=g01
Flow File=f01
Subcritical Flow
K Sum by GR= 0
Std Step Tol= 0.01
Critical Tol= 0.01
Num of Std Step Trials= 20
Max Error Tol= 0.3
Flow Tol Ratio= 0.001
Split Flow NTrial= 30
Split Flow Tol= 0.02
Split Flow Ratio= 0.02
Log Output Level= 0
Friction Slope Method= 1
Unsteady Friction Slope Method= 2
Unsteady Bridges Friction Slope Method= 1
Parabolic Critical Depth
Global Vel Dist=  1 , 1 , 1
Global Log Level= 0
CheckData=True
Encroach Param= -1, 0, 0, 0
BEGIN DESCRIPTION:
Multiple Run
END DESCRIPTION:

--- Ahern Creek.f01 (steady flow) ---

Flow Title=Multiple
Number of Profiles=7
Profile Names=10-year,25-year,50-year,1pct_min,100-year,1pct_plu,500-year
River Rch & RM= Ahern Creek,Reach-1,14484
    1310    2273    3210    2197    4384    8748    8096
River Rch & RM= Ahern Creek,Reach-1,12731
    1943    3425    4886    3372    6728   13423   12636
River Rch & RM= Ahern Creek,Reach-1,3706
    2375    4219    6052    4195    8370   16700   15866
Boundary for River Rch & Prof#=Ahern Creek,Reach-1,1
Up Type=0
Dn Type=3
Dn Slope=0.005
Boundary for River Rch & Prof#=Ahern Creek,Reach-1,2
Up Type=0
Dn Type=3
Dn Slope=0.005
Boundary for River Rch & Prof#=Ahern Creek,Reach-1,3
Up Type=0
Dn Type=3
Dn Slope=0.005
Boundary for River Rch & Prof#=Ahern Creek,Reach-1,4
Up Type=0
Dn Type=3
Dn Slope=0.005
Boundary for River Rch & Prof#=Ahern Creek,Reach-1,5
Up Type=0
Dn Type=3
Dn Slope=0.005
Boundary for River Rch & Prof#=Ahern Creek,Reach-1,6
Up Type=0
Dn Type=3
Dn Slope=0.005
Boundary for River Rch & Prof#=Ahern Creek,Reach-1,7
Up Type=0
Dn Type=3
Dn Slope=0.005

--- Ahern Creek.g01 (geometry) ---

Geom Title=Existing Conditions
Program Version=4.10

River Reach=Ahern Creek     ,Reach-1
Reach XY= 30
        2145775.       13847575.      2146222.82     13848430.45
      2146317.47     13849025.01      2146178.11     13849273.35
      2146671.63     13849776.73      2146582.56       13850175.
      2146628.82     13850323.41      2147171.45     13851076.47
      2147227.36     13851669.48      2147532.86     13852231.17
      2147730.86     13852422.93      2148423.45     13852478.75
        2148715.     13852713.76      2149061.38     13852861.76
      2149172.81     13853030.45      2149232.81     13853381.21
      2149573.17     13853585.89      2149773.62     13854234.66
      2149777.06     13854719.15      2150032.86     13855131.17
      2150180.48     13855272.92      2150459.61     13855175.07
      2150661.38     13855311.76      2151021.45     13855926.47
      2151132.82     13856531.19      2151414.24      13856765.3
      2151904.62     13857505.16      2152118.94     13857716.86
      2152458.55     13857857.87        2152775.       13858375.

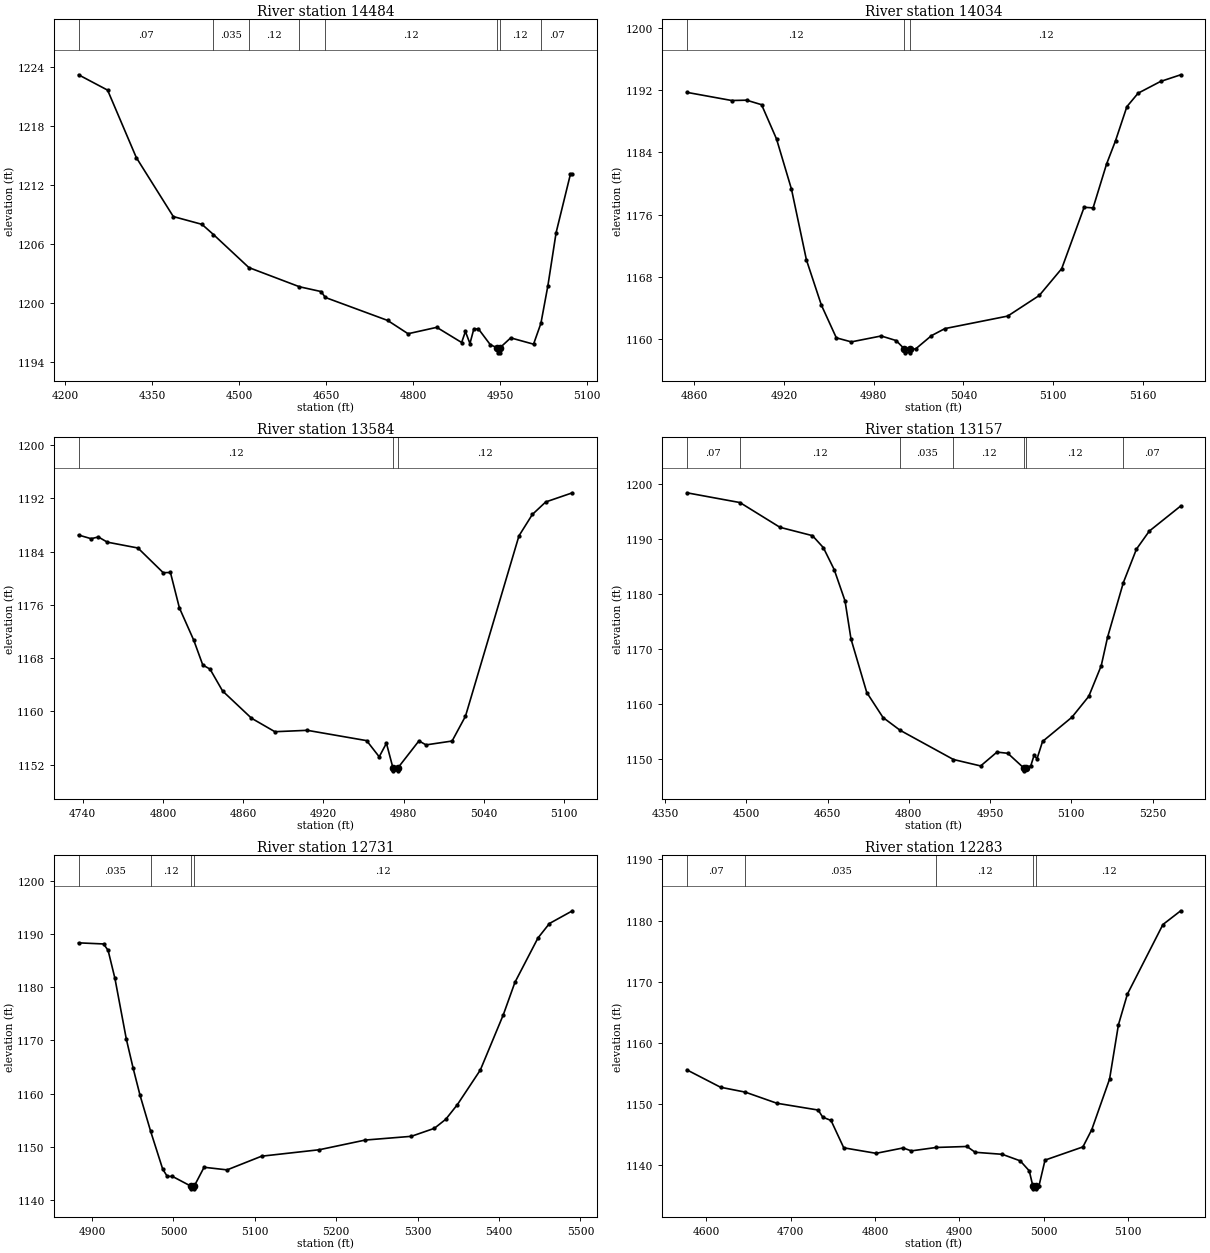
Type RM Length L Ch R = 1 ,14484   ,450,450,450
BEGIN DESCRIPTION:
Ahern Creek 28.0
END DESCRIPTION:
XS GIS Cut Line= 3
        2145375.       13848375.        2145975.       13847875.
      2146024.98     13847825.02
#Sta/Elev= 30
  4223.3 1223.18  4273.4 1221.62  4322.9 1214.77  4386.7 1208.78  4436.1 1207.99
    4456 1206.95    4517  1203.6  4604.3 1201.65  4641.8 1201.16  4648.6 1200.57
  4756.3 1198.23  4791.5 1196.88    4841 1197.53  4883.9 1195.99  4890.4 1197.11
  4898.2 1195.88  4904.7 1197.32  4912.6 1197.39  4933.4 1195.76  4945.7 1195.44
  4945.9 1194.94  4949.4 1194.94  4949.7 1195.44  4968.5 1196.46  5007.9 1195.82
  5020.6 1197.94  5032.6 1201.75  5046.8 1207.15  5071.5 1213.09    5075 1213.09
#Mann= 8 ,-1 , 0
  4223.3     .07       0    4456    .035       0    4517     .12       0
  4604.3     .07       0  4648.6     .12       0  4945.7     .05       0
  4949.7     .12       0  5020.6     .07       0
Bank Sta=4945.7,4949.7
XS Rating Curve= 0 ,0
Exp/Cntr=0.3,0.1

Type RM Length L Ch R = 1 ,14034   ,450,450,450
BEGIN DESCRIPTION:
Ahern Creek 27.0
END DESCRIPTION:
XS GIS Cut Line= 3
      2145974.96       13848275.        2146125.       13848275.
      2146274.99     13848175.01
#Sta/Elev= 30
    4855 1191.73    4885 1190.68    4895 1190.72    4905 1190.14    4915 1185.73
    4925 1179.27    4935 1170.17    4945 1164.35    4955 1160.14    4965 1159.62
    4985 1160.38    4995 1159.79  5000.5 1158.71  5000.8 1158.21  5004.3 1158.21
  5004.5 1158.71    5008 1158.71  5018.6 1160.42  5027.6 1161.33  5069.6 1162.94
  5090.7 1165.59  5105.7 1169.04  5120.7 1176.94  5126.7 1176.86  5135.7  1182.5
  5141.7  1185.5  5149.3 1189.89  5156.8 1191.62  5171.8 1193.13  5185.3 1193.99
#Mann= 3 ,-1 , 0
    4855     .12       0  5000.5     .05       0  5004.5     .12       0
Bank Sta=5000.5,5004.5
XS Rating Curve= 0 ,0
Exp/Cntr=0.3,0.1

Type RM Length L Ch R = 1 ,13584   ,427,427,427
BEGIN DESCRIPTION:
Ahern Creek 26.0
END DESCRIPTION:
XS GIS Cut Line= 3
      2146024.99       13848575.        2146275.       13848675.
      2146375.03       13848675.
#Sta/Elev= 30
  4736.9  1186.5  4746.3 1185.95  4751.7 1186.21  4758.4 1185.43  4781.3 1184.55
  4800.2 1180.84  4805.6 1180.87  4812.3 1175.55  4823.1 1170.66  4829.8 1166.96
  4835.2 1166.35  4844.6 1163.06  4866.2 1158.97  4883.7 1156.94  4907.9 1157.15
  4952.3  1155.6  4961.7 1153.17  4967.1 1155.21  4971.9 1151.56  4972.1 1151.06
  4975.6 1151.06  4975.9 1151.56  4991.4 1155.56  4996.7 1154.96  5016.2 1155.54
  5026.2 1159.27  5066.2 1186.38  5076.2 1189.59  5086.2 1191.47  5106.2 1192.85
#Mann= 3 ,-1 , 0
  4736.9     .12       0  4971.9     .05       0  4975.9     .12       0
Bank Sta=4971.9,4975.9
XS Rating Curve= 0 ,0
Exp/Cntr=0.3,0.1

Type RM Length L Ch R = 1 ,13157   ,426,426,426
BEGIN DESCRIPTION:
Ahern Creek 25.0
END DESCRIPTION:
XS GIS Cut Line= 3
      2145673.34     13849045.22        2146275.       13849075.
      2146560.46     13848956.45
#Sta/Elev= 30
  4390.3 1198.47  4488.4 1196.69  4562.2 1192.19  4622.2 1190.67  4642.3 1188.49
  4662.3  1184.5  4682.3  1178.8  4693.3 1171.88  4722.4 1162.14  4752.4 1157.59
  4783.9 1155.27  4882.4 1149.95  4932.6 1148.78  4962.7  1151.3  4982.7 1151.08
  5012.4 1148.39  5012.6 1147.89  5016.4 1148.39  5025.2 1148.83  5031.2 1150.73
  5036.6 1150.08  5046.8 1153.23    5101 1157.64  5132.1 1161.44  5155.1 1167.01
  5166.8  1172.2  5195.9 1182.12  5220.1 1188.22  5243.8  1191.5  5301.8 1196.07
#Mann= 7 ,-1 , 0
  4390.3     .07       0  4488.4     .12       0  4783.9    .035       0
  4882.4     .12       0  5012.4     .05       0  5016.4     .12       0
  5195.9     .07       0
Bank Sta=5012.4,5016.4
XS Rating Curve= 0 ,0
Exp/Cntr=0.3,0.1

Type RM Length L Ch R = 1 ,12731   ,448,448,448
BEGIN DESCRIPTION:
Ahern Creek 24.0
END DESCRIPTION:
XS GIS Cut Line= 3
        2146175.       13849475.        2146275.       13849425.
      2146625.02     13849074.98
#Sta/Elev= 30
  4883.4  1188.3  4914.1 1188.09  4919.7 1186.89  4928.1 1181.62  4942.1 1170.22
  4950.5 1164.74  4958.9  1159.7  4971.9 1152.95  4986.8  1145.8  4992.4 1144.45
  4998.7 1144.45  5021.5 1142.61  5021.7 1142.11  5025.2 1142.11  5025.5 1142.61
  5037.6 1146.16  5065.9 1145.67  5108.3 1148.24  5179.1 1149.45  5235.6 1151.27
  5292.2 1151.97  5320.5 1153.47  5334.6 1155.18  5348.8 1157.92    5377 1164.42
  5405.3 1174.82  5419.5 1180.88  5447.8 1189.21  5461.9 1191.93  5490.2 1194.32
#Mann= 4 ,-1 , 0
  4883.4    .035       0  4971.9     .12       0  5021.5     .05       0
  5025.5     .12       0
Bank Sta=5021.5,5025.5
XS Rating Curve= 0 ,0
Exp/Cntr=0.3,0.1

Type RM Length L Ch R = 1 ,12283   ,406,406,406
BEGIN DESCRIPTION:
Ahern Creek 23.0
END DESCRIPTION:
XS GIS Cut Line= 3
      2146225.01       13849825.        2146625.       13849675.
        2146775.       13849625.
#Sta/Elev= 30
  4576.9 1155.59  4616.9 1152.74  4646.2 1151.94  4683.7 1150.12  4732.6 1149.01
    4738 1147.84  4747.8 1147.31  4762.9 1142.83  4801.2 1141.93  4833.2 1142.81
    4843 1142.33  4872.5 1142.89  4908.9 1143.05  4918.6  1142.1  4950.7 1141.77
    4972  1140.7  4982.7 1139.07  4986.9 1136.62  4987.1 1136.12  4990.8 1136.12
  4991.1 1136.62  4994.3 1136.65  5001.4 1140.82  5046.3 1142.98  5056.8 1145.81
  5077.9 1154.08  5088.4 1162.97    5099 1167.97  5141.1 1179.36  5162.2 1181.61
#Mann= 5 ,-1 , 0
  4576.9     .07       0  4646.2    .035       0  4872.5     .12       0
  4986.9     .05       0  4991.1     .12       0
Bank Sta=4986.9,4991.1
XS Rating Curve= 0 ,0
Exp/Cntr=0.3,0.1

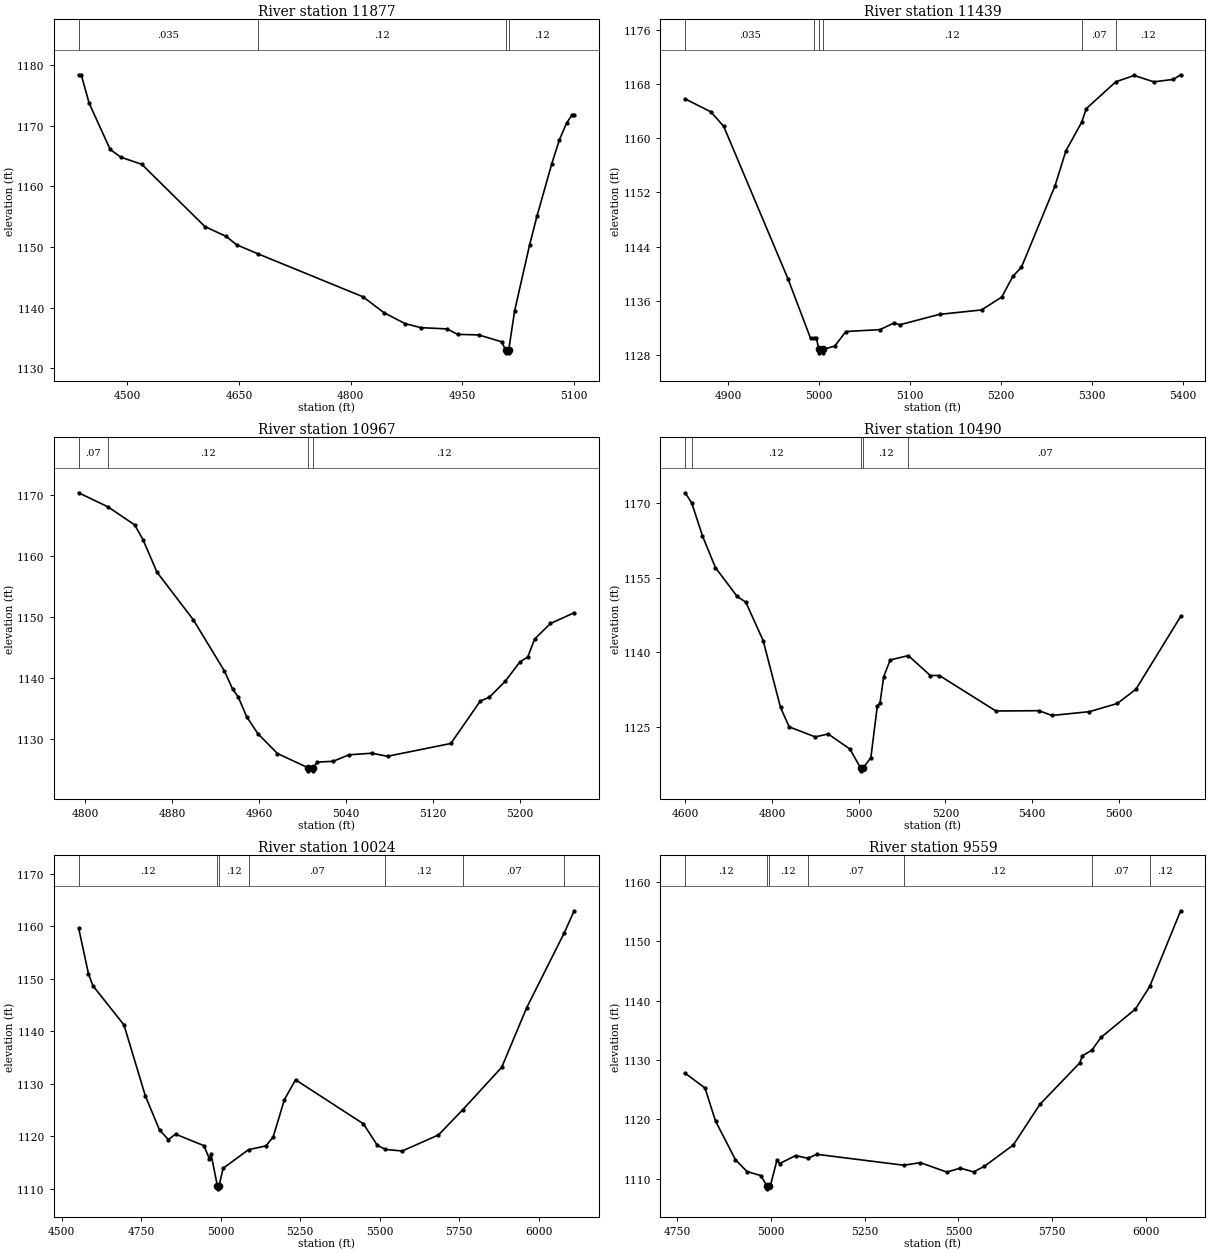
Type RM Length L Ch R = 1 ,11877   ,438,438,438
BEGIN DESCRIPTION:
Ahern Creek 22.0
END DESCRIPTION:
XS GIS Cut Line= 3
      2146224.99     13850425.01        2146625.       13850025.
        2146725.       13850025.
#Sta/Elev= 30
  4434.7 1178.44  4438.2 1178.44  4448.9 1173.72  4477.1 1166.11  4491.3 1164.84
  4519.6 1163.65  4604.4 1153.37  4632.7 1151.77  4646.8 1150.38  4675.2  1148.9
  4816.6 1141.79  4844.8 1139.17  4873.1 1137.36  4894.3 1136.69  4929.7 1136.48
  4943.8 1135.58  4972.1 1135.49  5002.9 1134.36  5008.2 1133.03  5008.5 1132.53
  5012.2 1132.53  5012.5 1133.03  5020.4 1139.46  5040.4 1150.28  5050.4  1155.1
  5070.4 1163.78  5080.4 1167.65  5090.4 1170.51  5097.9 1171.87  5100.4 1171.87
#Mann= 4 ,-1 , 0
  4434.7    .035       0  4675.2     .12       0  5008.2     .05       0
  5012.5     .12       0
Bank Sta=5008.2,5012.5
XS Rating Curve= 0 ,0
Exp/Cntr=0.3,0.1

Type RM Length L Ch R = 1 ,11439   ,472,472,472
BEGIN DESCRIPTION:
Ahern Creek 21.0
END DESCRIPTION:
XS GIS Cut Line= 3
      2146575.02     13850524.98        2146675.       13850425.
        2146875.     13850075.01
#Sta/Elev= 30
  4852.9 1165.79  4881.2 1163.88  4895.3 1161.75    4966 1139.26  4990.8 1130.49
  4994.6 1130.49  4997.2 1130.49    5000 1128.87  5000.3 1128.37  5004.1 1128.37
  5004.4 1128.87  5017.3 1129.37  5029.6 1131.51    5067 1131.79  5082.8 1132.79
  5088.6  1132.5  5132.5 1134.04  5178.6 1134.69  5200.9  1136.6  5213.1 1139.65
  5222.5 1140.99  5259.2 1152.92  5271.4 1158.16  5288.6 1162.33  5293.7 1164.35
  5326.2 1168.31  5346.3 1169.24  5367.9  1168.3  5389.5 1168.66  5397.4 1169.34
#Mann= 6 ,-1 , 0
  4852.9    .035       0  4994.6     .12       0    5000     .05       0
  5004.4     .12       0  5288.6     .07       0  5326.2     .12       0
Bank Sta=5000,5004.4
XS Rating Curve= 0 ,0
Exp/Cntr=0.3,0.1

Type RM Length L Ch R = 1 ,10967   ,477,477,477
BEGIN DESCRIPTION:
Ahern Creek 20.0
END DESCRIPTION:
XS GIS Cut Line= 3
      2146775.01       13850825.        2146975.       13850775.
      2147124.97     13850575.04
#Sta/Elev= 30
  4794.1 1170.33  4821.1 1168.02  4845.6 1165.07  4853.4 1162.63  4866.2 1157.31
  4899.7 1149.49  4928.1 1141.15  4935.8 1138.15    4941 1136.84  4948.7 1133.62
    4959 1130.83  4977.1 1127.56  5005.3 1125.22  5005.6 1124.72  5009.5 1124.72
  5009.8 1125.22  5013.8 1126.15  5028.4 1126.29    5043 1127.35  5063.8 1127.61
  5078.4 1127.11  5136.7 1129.21  5163.8 1136.17  5172.1 1136.79  5186.7  1139.4
  5200.2 1142.57  5207.5  1143.4  5213.8 1146.34  5228.4 1148.89  5250.2 1150.65
#Mann= 4 ,-1 , 0
  4794.1     .07       0  4821.1     .12       0  5005.3     .05       0
  5009.8     .12       0
Bank Sta=5005.3,5009.8
XS Rating Curve= 0 ,0
Exp/Cntr=0.3,0.1

Type RM Length L Ch R = 1 ,10490   ,466,466,466
BEGIN DESCRIPTION:
Ahern Creek 19.0
END DESCRIPTION:
XS GIS Cut Line= 3
      2146775.02       13851175.        2147175.       13851175.
      2147784.86     13850751.27
#Sta/Elev= 30
  4599.9 1172.13  4615.2 1170.09  4639.9 1163.47  4669.9 1157.07  4719.9 1151.28
  4739.9 1150.12  4779.9 1142.39  4819.9 1128.95  4839.9 1125.04  4899.9 1123.02
  4929.9  1123.6  4979.9 1120.57  5005.1 1116.69  5005.4 1116.19  5009.6 1116.69
  5028.2 1118.83  5043.1 1129.23  5049.2 1129.78  5057.9 1135.15  5072.8  1138.5
  5114.6 1139.38  5165.3 1135.37  5186.3 1135.37  5316.5 1128.23  5415.9 1128.29
  5445.6 1127.33    5532 1128.09  5596.5 1129.74  5639.4  1132.6  5742.5 1147.24
#Mann= 5 ,-1 , 0
  4599.9     .07       0  4615.2     .12       0  5005.1     .05       0
  5009.6     .12       0  5114.6     .07       0
Bank Sta=5005.1,5009.6
XS Rating Curve= 0 ,0
Exp/Cntr=0.3,0.1

Type RM Length L Ch R = 1 ,10024   ,465,465,465
BEGIN DESCRIPTION:
Ahern Creek 18.0
END DESCRIPTION:
XS GIS Cut Line= 3
      2146824.97     13851424.98        2147225.       13851625.
      2148100.11     13850940.13
#Sta/Elev= 30
  4553.1 1159.72  4583.9 1151.03  4597.9 1148.72  4695.7 1141.24  4762.8 1127.75
  4807.5 1121.22  4835.4  1119.4  4857.8 1120.44  4947.2 1118.24    4964 1115.79
  4969.6 1116.59  4989.7 1110.52    4990 1110.02  4994.3 1110.52  5007.6 1113.93
  5087.4 1117.48  5142.3  1118.2  5164.9 1119.88  5200.2 1127.01  5235.4 1130.79
  5448.9  1122.4  5492.2 1118.34  5517.7 1117.53  5570.9 1117.23  5684.8 1120.28
  5761.8 1125.13  5883.8 1133.18  5962.4 1144.54  6080.5 1158.79  6111.6 1162.99
#Mann= 7 ,-1 , 0
  4553.1     .12       0  4989.7     .05       0  4994.3     .12       0
  5087.4     .07       0  5517.7     .12       0  5761.8     .07       0
  6080.5     .12       0
Bank Sta=4989.7,4994.3
XS Rating Curve= 0 ,0
Exp/Cntr=0.3,0.1

Type RM Length L Ch R = 1 ,9559    ,449,449,449
BEGIN DESCRIPTION:
Ahern Creek 17.0
END DESCRIPTION:
XS GIS Cut Line= 3
      2147225.02     13852124.99        2147425.       13852025.
      2148225.02     13851274.98
#Sta/Elev= 30
  4771.7 1127.79  4824.8 1125.29  4852.7 1119.73  4905.8 1113.21  4936.6 1111.22
  4972.9 1110.54  4990.2  1108.8  4990.5  1108.3  4994.8  1108.8  4998.7  1108.8
  5016.5 1113.14  5023.4 1112.55  5065.9  1113.9  5098.5 1113.45  5122.5 1114.12
  5354.1 1112.28  5398.5 1112.71  5469.3 1111.12  5504.5 1111.79  5540.2 1111.16
  5568.5 1112.07  5646.2  1115.7    5717 1122.54    5823 1129.52  5830.3 1130.73
  5855.2 1131.65  5879.6 1133.81  5971.5  1138.6  6009.7 1142.43  6091.9 1155.16
#Mann= 7 ,-1 , 0
  4771.7     .12       0  4990.2     .05       0  4994.8     .12       0
  5098.5     .07       0  5354.1     .12       0  5855.2     .07       0
  6009.7     .12       0
Bank Sta=4990.2,4994.8
XS Rating Curve= 0 ,0
Exp/Cntr=0.3,0.1

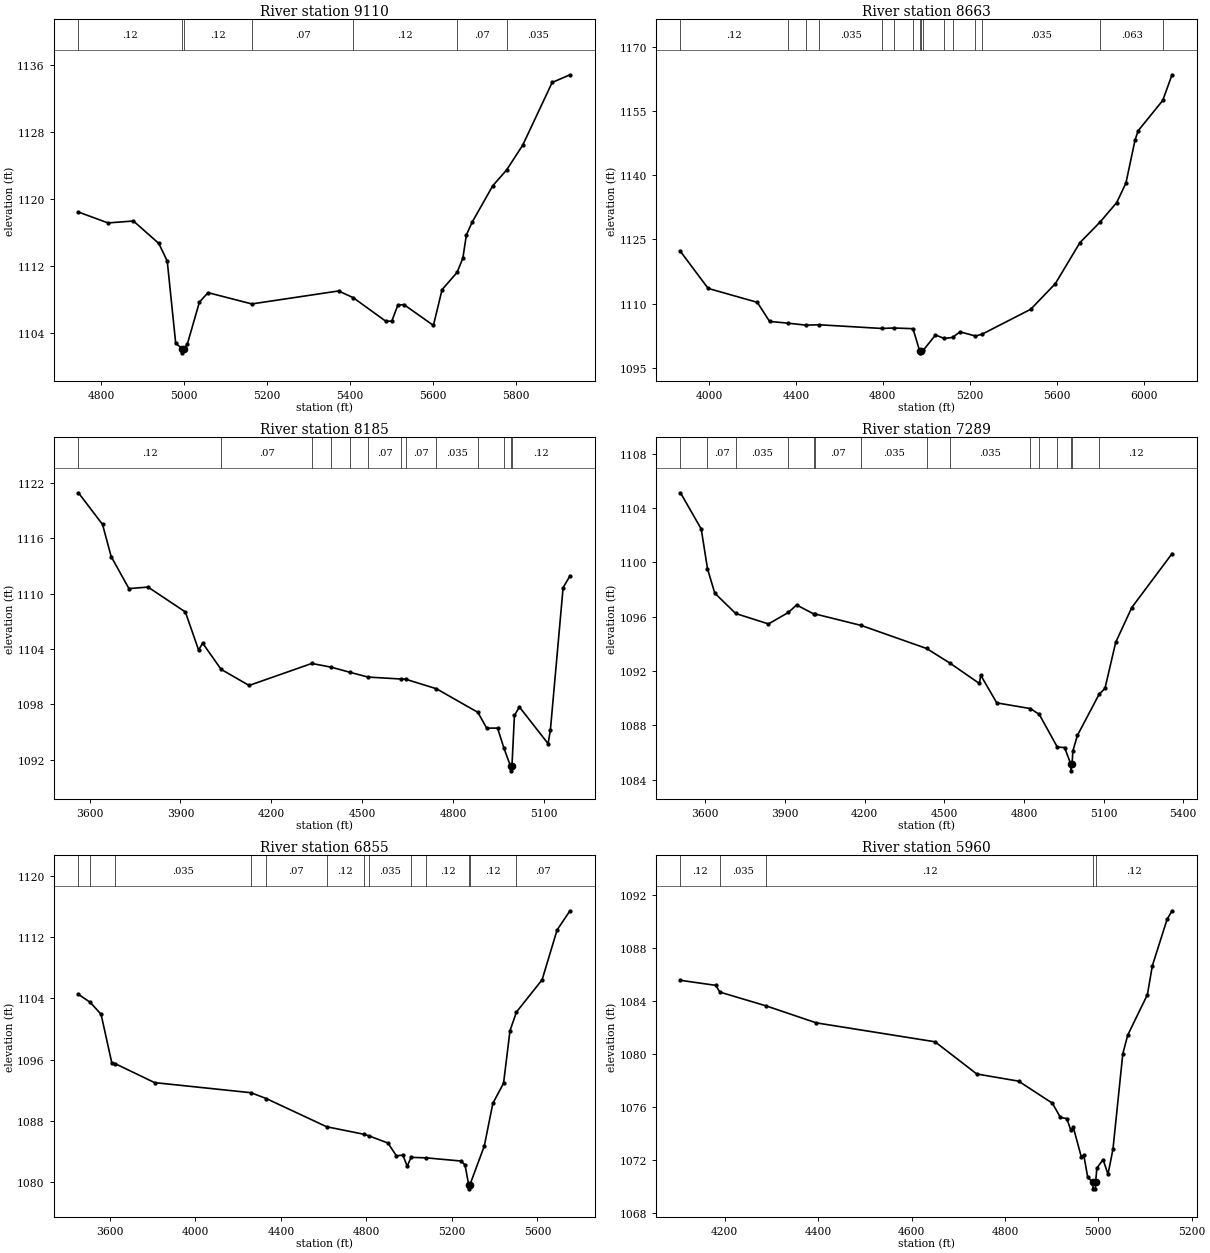
Type RM Length L Ch R = 1 ,9110    ,447,447,447
BEGIN DESCRIPTION:
Ahern Creek 16.0
END DESCRIPTION:
XS GIS Cut Line= 3
      2147425.02       13852425.        2147675.       13852375.
      2148225.01     13851624.99
#Sta/Elev= 30
  4745.4 1118.47  4816.8 1117.17    4878  1117.4  4939.1 1114.72  4959.5 1112.61
  4979.9 1102.78  4995.5 1102.13  4995.8 1101.63  5000.1 1102.13  5007.7 1102.63
    5037 1107.69  5057.8 1108.83  5163.4 1107.48  5372.4 1109.03  5407.5 1108.24
  5486.2 1105.42  5500.9 1105.42  5515.5 1107.34  5530.2  1107.4  5601.2 1104.91
  5622.1 1109.19  5658.2 1111.25  5672.2 1112.95  5680.7 1115.74  5694.8 1117.28
  5744.4 1121.62  5777.6  1123.5  5816.5 1126.47  5887.5 1133.97  5930.4 1134.89
#Mann= 7 ,-1 , 0
  4745.4     .12       0  4995.5     .05       0  5000.1     .12       0
  5163.4     .07       0  5407.5     .12       0  5658.2     .07       0
  5777.6    .035       0
Bank Sta=4995.5,5000.1
XS Rating Curve= 0 ,0
Exp/Cntr=0.3,0.1

Type RM Length L Ch R = 1 ,8663    ,478,478,478
BEGIN DESCRIPTION:
Ahern Creek 15.0
END DESCRIPTION:
XS GIS Cut Line= 3
      2147274.99     13853225.01        2148075.       13852425.
      2148875.03     13851624.97
#Sta/Elev= 30
  3868.4 1122.21  3995.7 1113.58    4222 1110.33  4278.5 1105.88  4363.8 1105.46
  4445.7 1105.01  4507.5 1105.09    4795 1104.23  4850.8 1104.34  4938.7 1104.18
  4969.2 1099.04  4969.5 1098.54  4973.8 1099.04  4985.9 1099.12  5042.2  1102.7
  5082.5 1101.91  5120.9 1102.13  5155.4 1103.44  5226.2 1102.47  5255.9 1102.87
  5480.6 1108.71  5593.8 1114.67  5706.9 1124.24  5801.1 1129.13  5876.6 1133.62
    5919 1138.17  5961.5 1148.34  5975.6  1150.4  6088.6 1157.47  6131.2 1163.45
#Mann= 16 ,-1 , 0
  3868.4     .12       0  4363.8    .035       0  4445.7     .07       0
  4507.5    .035       0    4795     .07       0  4850.8    .035       0
  4938.7     .07       0  4969.2    .035       0  4973.8     .07       0
  4985.9    .035       0  5082.5     .07       0  5120.9    .035       0
  5226.2     .12       0  5255.9    .035       0  5801.1    .063       0
  6088.6    .035       0
Bank Sta=4969.2,4973.8
XS Rating Curve= 0 ,0
Exp/Cntr=0.3,0.1

Type RM Length L Ch R = 1 ,8185    ,896,896,896
BEGIN DESCRIPTION:
Ahern Creek 14.0
END DESCRIPTION:
XS GIS Cut Line= 3
      2147325.03     13853324.98        2148525.       13852525.
      2148675.03     13852424.98
#Sta/Elev= 30
  3563.2 1120.96  3642.8 1117.52  3671.3 1114.03  3729.9 1110.56    3793 1110.72
  3916.2 1108.02  3959.8 1103.89  3973.3 1104.63  4034.1 1101.79  4126.5 1100.04
  4333.6 1102.43  4398.2 1102.02  4458.2 1101.48  4519.1 1100.95  4627.8 1100.74
  4643.1 1100.72  4745.1 1099.68  4881.8 1097.12  4910.7 1095.41  4946.8 1095.41
  4967.1  1093.3  4989.5 1091.27  4989.9 1090.77  4994.2 1091.27  5002.4 1096.79
  5018.9  1097.7  5113.6 1093.72  5121.1  1095.2  5163.1 1110.67  5185.7 1111.93
#Mann= 13 ,-1 , 0
  3563.2     .12       0  4034.1     .07       0  4333.6    .035       0
  4398.2     .07       0  4458.2    .035       0  4519.1     .07       0
  4627.8    .035       0  4643.1     .07       0  4745.1    .035       0
  4881.8     .07       0  4967.1     .12       0  4989.5     .05       0
  4994.2     .12       0
Bank Sta=4989.5,4994.2
XS Rating Curve= 0 ,0
Exp/Cntr=0.3,0.1

Type RM Length L Ch R = 1 ,7289    ,434,434,434
BEGIN DESCRIPTION:
Ahern Creek 13.0
END DESCRIPTION:
XS GIS Cut Line= 3
      2147708.53     13853327.63        2149175.       13853025.
        2149225.     13852675.02
#Sta/Elev= 30
  3506.6 1105.14  3584.7 1102.47  3608.2 1099.55  3635.7 1097.74  3714.5 1096.24
    3838 1095.47  3913.1 1096.32  3943.7 1096.87    4009  1096.2  4014.4  1096.2
    4187 1095.36  4433.3 1093.66  4520.6 1092.59  4632.1 1091.08  4637.2 1091.69
  4697.6 1089.65  4824.3 1089.23  4857.6  1088.8  4925.6 1086.39  4952.9 1086.36
  4976.3 1085.14  4976.7 1084.64  4981.3 1085.14  4983.9 1086.09  5001.4 1087.26
  5082.8 1090.28    5105 1090.72  5145.4 1094.11    5206 1096.68  5357.5 1100.65
#Mann= 15 ,-1 , 0
  3506.6     .12       0  3608.2     .07       0  3714.5    .035       0
  3913.1     .07       0    4009    .035       0  4014.4     .07       0
    4187    .035       0  4433.3     .07       0  4520.6    .035       0
  4824.3     .07       0  4857.6    .035       0  4925.6     .07       0
  4976.3     .05       0  4981.3     .07       0  5082.8     .12       0
Bank Sta=4976.3,4981.3
XS Rating Curve= 0 ,0
Exp/Cntr=0.3,0.1

Type RM Length L Ch R = 1 ,6855    ,895,895,895
BEGIN DESCRIPTION:
Ahern Creek 12.0
END DESCRIPTION:
XS GIS Cut Line= 3
      2147729.31     13853511.66        2149275.       13853425.
      2150025.02       13853475.
#Sta/Elev= 30
  3452.5 1104.52  3507.5 1103.48  3558.4 1101.92  3608.4 1095.59  3625.2 1095.45
  3808.7 1092.98  4260.1 1091.66  4330.9  1090.9  4613.8 1087.21  4787.4 1086.23
  4811.5 1086.02  4900.5 1085.08  4940.5  1083.4  4970.6  1083.5  4990.6 1082.06
  5009.2 1083.21  5080.2 1083.14  5241.1 1082.73  5261.2 1082.23  5278.7 1079.59
  5279.1 1079.09  5283.8 1079.59  5351.4 1084.68  5391.5 1090.27  5441.6  1092.9
  5471.7 1099.77    5502 1102.21    5622 1106.43  5692.1 1112.94  5752.3 1115.45
#Mann= 13 ,-1 , 0
  3452.5    .035       0  3507.5     .12       0  3625.2    .035       0
  4260.1     .12       0  4330.9     .07       0  4613.8     .12       0
  4787.4     .07       0  4811.5    .035       0  5009.2     .07       0
  5080.2     .12       0  5278.7    .035       0  5283.8     .12       0
    5502     .07       0
Bank Sta=5278.7,5283.8
XS Rating Curve= 0 ,0
Exp/Cntr=0.3,0.1

Type RM Length L Ch R = 1 ,5960    ,466,466,466
BEGIN DESCRIPTION:
Ahern Creek 11.0
END DESCRIPTION:
XS GIS Cut Line= 3
      2148924.98     13853674.99        2149725.       13854075.
      2149875.03     13854024.99
#Sta/Elev= 30
  4105.2 1085.57  4180.7 1085.19  4189.6 1084.68  4288.7 1083.64  4395.9 1082.36
  4650.3 1080.93  4739.7  1078.5  4829.1 1077.96  4901.8 1076.29  4918.6 1075.23
  4932.6 1075.13    4941 1074.26  4946.5 1074.47  4963.3 1072.27  4968.9 1072.37
  4977.3  1070.7  4988.3 1070.33  4988.8 1069.83  4993.7 1069.83  4994.2 1070.33
  4996.9  1071.4  5010.2 1072.04  5020.7 1070.93  5031.3 1072.81  5052.4 1080.02
  5062.9 1081.43  5105.1 1084.49  5115.6 1086.66  5147.2 1090.17  5157.8 1090.82
#Mann= 5 ,-1 , 0
  4105.2     .12       0  4189.6    .035       0  4288.7     .12       0
  4988.3     .05       0  4994.2     .12       0
Bank Sta=4988.3,4994.2
XS Rating Curve= 0 ,0
Exp/Cntr=0.3,0.1

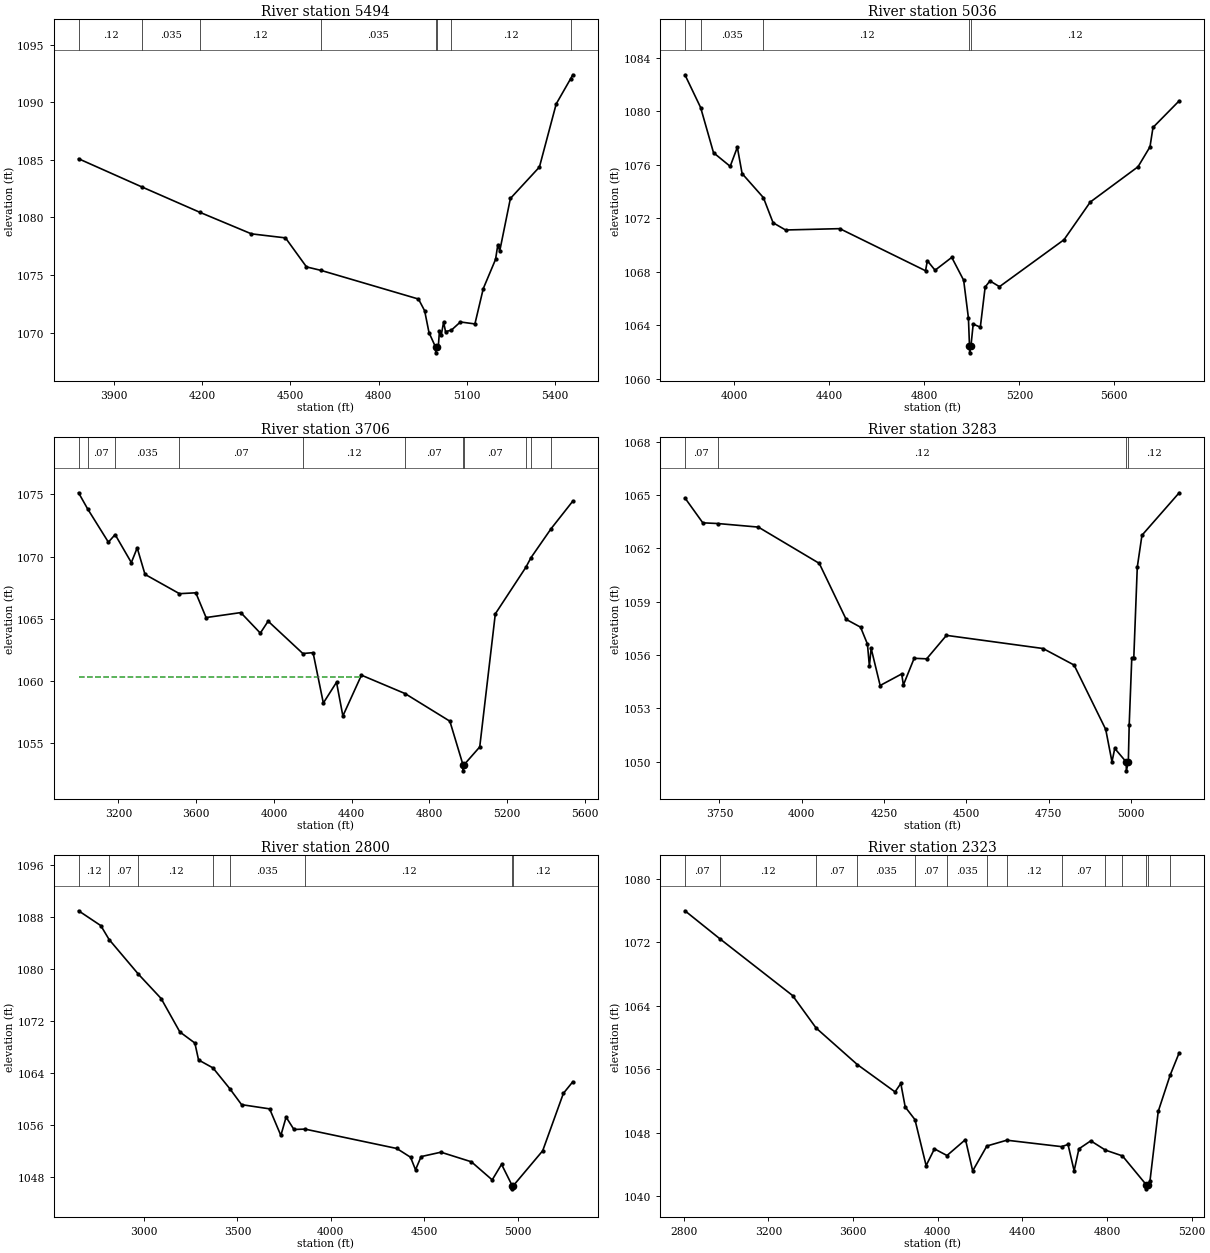
Type RM Length L Ch R = 1 ,5494    ,458,458,458
BEGIN DESCRIPTION:
Ahern Creek 10.0
END DESCRIPTION:
XS GIS Cut Line= 3
      2148775.02     13853825.02        2149775.       13854525.
      2150124.99       13854225.
#Sta/Elev= 30
  3779.4  1085.1  3996.9 1082.63  4191.2 1080.46  4367.5 1078.58  4483.4 1078.23
  4554.9 1075.71    4604 1075.41  4935.9 1072.92  4956.9  1071.9  4971.7 1070.01
    4994 1068.75  4994.5 1068.25    5000 1068.75  5003.3 1068.75  5007.2 1070.14
  5013.7 1069.84  5021.4 1070.92    5028 1070.09  5047.8 1070.22  5078.5 1070.93
  5127.9 1070.76  5156.4 1073.83  5198.1 1076.36  5205.8 1077.62  5212.4  1077.1
  5248.6 1081.65  5347.4 1084.38  5404.5 1089.86  5453.4 1092.04    5461 1092.39
#Mann= 8 ,-1 , 0
  3779.4     .12       0  3996.9    .035       0  4191.2     .12       0
    4604    .035       0    4994    .035       0    5000    .035       0
  5047.8     .12       0  5453.4    .035       0
Bank Sta=4994,5000
XS Rating Curve= 0 ,0
Exp/Cntr=0.3,0.1

Type RM Length L Ch R = 1 ,5036    ,1330,1330,1330
BEGIN DESCRIPTION:
Ahern Creek 9.0
END DESCRIPTION:
XS GIS Cut Line= 3
      2148725.02       13854825.        2149925.       13854925.
      2150797.23     13854827.49
#Sta/Elev= 30
  3791.3 1082.74  3857.4 1080.29  3911.7 1076.91  3981.9 1075.89    4012 1077.32
  4032.1 1075.35  4121.8 1073.55  4162.6 1071.67  4215.2 1071.13  4443.5 1071.23
  4804.8 1068.08  4812.3 1068.83  4844.9 1068.12  4915.2 1069.08  4965.3 1067.37
  4985.4 1064.54  4989.9 1062.44  4990.4 1061.94  4995.9 1062.44  5005.5 1064.09
  5035.5 1063.86  5055.8 1066.86  5075.9 1067.32  5116.2 1066.89  5387.9  1070.4
  5498.6 1073.22  5699.8 1075.86  5750.1 1077.35  5762.8  1078.8  5873.1 1080.79
#Mann= 5 ,-1 , 0
  3791.3     .07       0  3857.4    .035       0  4121.8     .12       0
  4989.9     .05       0  4995.9     .12       0
Bank Sta=4989.9,4995.9
XS Rating Curve= 0 ,0
Exp/Cntr=0.3,0.1

Type RM Length L Ch R = 1 ,3706    ,423,423,423
BEGIN DESCRIPTION:
Ahern Creek 8.0
END DESCRIPTION:
XS GIS Cut Line= 3
      2148824.96       13855375.        2150825.       13855575.
      2151003.66     13855074.13
#Sta/Elev= 30
  2995.3 1075.13  3041.7 1073.84  3148.6 1071.16  3183.3 1071.77  3266.7 1069.52
  3296.8  1070.7    3337 1068.57  3514.2 1067.02  3598.3 1067.09  3651.1  1065.1
  3829.5  1065.5    3930 1063.85  3970.2 1064.81  4148.7 1062.21  4201.3 1062.28
  4254.1 1058.23  4321.9  1059.9  4354.6 1057.19  4450.1 1060.47  4674.4 1058.99
  4904.8 1056.77    4972 1053.28  4972.5 1052.78  4978.4 1053.28  5058.4  1054.7
  5138.6  1065.4    5296 1069.15  5321.8 1069.91  5425.2 1072.24  5537.1 1074.46
#Mann= 11 ,-1 , 0
  2995.3    .035       0  3041.7     .07       0  3183.3    .035       0
  3514.2     .07       0  4148.7     .12       0  4674.4     .07       0
    4972     .05       0  4978.4     .07       0    5296    .035       0
  5321.8    .063       0  5425.2     .12       0
#XS Ineff= 2 , 0
       0  4442.5 1060.32               0
Permanent Ineff=
       F       F
Bank Sta=4972,4978.4
XS Rating Curve= 0 ,0
Exp/Cntr=0.3,0.1

Type RM Length L Ch R = 1 ,3283    ,483,483,483
BEGIN DESCRIPTION:
Ahern Creek 7.0
END DESCRIPTION:
XS GIS Cut Line= 3
      2149724.98     13855524.99        2151025.       13855925.
      2151125.01     13855824.99
#Sta/Elev= 30
  3645.1 1064.84  3699.4 1063.44  3745.2  1063.4  3868.1  1063.2  4053.2 1061.16
  4134.9 1058.01  4178.7 1057.57  4199.6 1056.62  4205.5 1055.37  4210.8 1056.38
  4238.2 1054.29  4303.6 1054.94  4308.8 1054.32  4341.5 1055.82  4379.5 1055.79
  4439.6 1057.11  4733.2 1056.37  4827.4 1055.44  4923.5 1051.82  4942.5    1050
    4951 1050.75  4985.7 1049.99  4986.2 1049.49  4992.2 1049.99  4994.8 1052.05
  5002.7 1055.85  5008.8 1055.85  5019.4 1060.95  5033.6 1062.74  5146.7 1065.13
#Mann= 4 ,-1 , 0
  3645.1     .07       0  3745.2     .12       0  4985.7     .05       0
  4992.2     .12       0
Bank Sta=4985.7,4992.2
XS Rating Curve= 0 ,0
Exp/Cntr=0.3,0.1

Type RM Length L Ch R = 1 ,2800    ,477,477,477
BEGIN DESCRIPTION:
Ahern Creek 6.0
END DESCRIPTION:
XS GIS Cut Line= 3
      2148773.52     13856232.65        2151125.       13856375.
      2151274.98     13856125.03
#Sta/Elev= 30
  2648.9    1089  2768.1 1086.71  2812.4 1084.57  2969.6 1079.22  3091.2 1075.47
  3191.4 1070.32  3271.8 1068.61  3291.6    1066    3369 1064.77  3458.7 1061.58
    3522 1059.11  3672.3 1058.46  3732.4 1054.36  3760.5 1057.19  3802.5 1055.28
  3861.6 1055.34  4353.5 1052.35  4427.1    1051  4453.7 1049.07  4483.7  1051.1
  4589.9 1051.78  4752.8  1050.3  4864.4 1047.51  4914.5 1049.91  4971.4 1046.63
  4971.9 1046.13  4977.9 1046.63  5134.9    1052  5245.7 1060.85  5296.2 1062.64
#Mann= 8 ,-1 , 0
  2648.9     .12       0  2812.4     .07       0  2969.6     .12       0
    3369     .07       0  3458.7    .035       0  3861.6     .12       0
  4971.4     .05       0  4977.9     .12       0
Bank Sta=4971.4,4977.9
XS Rating Curve= 0 ,0
Exp/Cntr=0.3,0.1

Type RM Length L Ch R = 1 ,2323    ,442,442,442
BEGIN DESCRIPTION:
Ahern Creek 5.0
END DESCRIPTION:
XS GIS Cut Line= 3
      2149263.05     13857318.15        2151375.       13856725.
      2151475.01     13856624.99
#Sta/Elev= 30
  2805.9 1075.98  2969.5 1072.48  3314.3  1065.3  3425.7  1061.2  3620.6 1056.59
  3798.7 1053.15  3825.8 1054.21  3846.6 1051.25  3892.7 1049.65  3945.4 1043.86
  3984.7 1045.97    4044 1045.13  4131.4 1047.14  4165.4 1043.19  4232.4 1046.33
  4326.7 1047.06  4585.2 1046.25  4615.8 1046.52  4644.7  1043.2  4667.2 1045.97
  4723.3 1046.98  4792.7 1045.81    4873 1045.08  4985.9 1041.43  4986.4 1040.93
  4992.5 1041.43  5003.1 1041.94    5042 1050.69  5097.9 1055.23    5141 1058.08
#Mann= 14 ,-1 , 0
  2805.9     .07       0  2969.5     .12       0  3425.7     .07       0
  3620.6    .035       0  3892.7     .07       0    4044    .035       0
  4232.4     .07       0  4326.7     .12       0  4585.2     .07       0
  4792.7     .12       0    4873     .07       0  4985.9     .05       0
  4992.5     .07       0  5097.9     .12       0
Bank Sta=4985.9,4992.5
XS Rating Curve= 0 ,0
Exp/Cntr=0.3,0.1

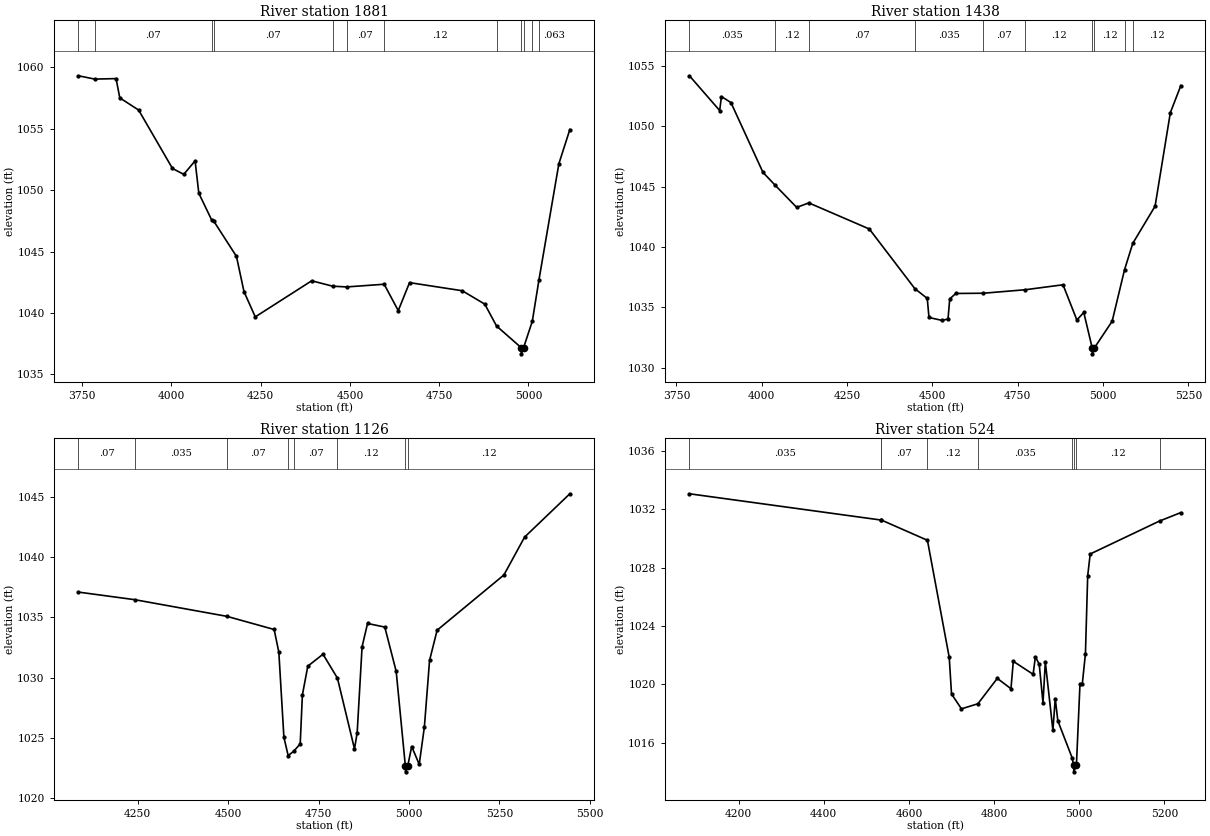
Type RM Length L Ch R = 1 ,1881    ,443,443,443
BEGIN DESCRIPTION:
Ahern Creek 4.0
END DESCRIPTION:
XS GIS Cut Line= 3
      2150425.01       13857475.        2151625.       13857075.
        2151675.       13856975.
#Sta/Elev= 30
  3739.4 1059.32  3785.2 1059.05  3844.8 1059.09  3855.3 1057.52    3908 1056.53
  4002.9 1051.77  4034.5 1051.29  4066.2 1052.39  4076.7 1049.75  4112.4 1047.59
  4119.2 1047.45  4182.1 1044.61  4203.2 1041.74  4234.8 1039.68  4392.9 1042.62
  4451.6 1042.18    4491 1042.12  4595.9 1042.34  4635.4 1040.19    4667 1042.47
  4814.6 1041.81  4877.8 1040.72  4910.7 1038.94  4979.9 1037.17  4980.4 1036.67
  4986.5 1037.17    5011 1039.33  5029.7 1042.72  5085.4 1052.16  5116.1 1054.94
#Mann= 12 ,-1 , 0
  3739.4    .035       0  3785.2     .07       0  4112.4     .12       0
  4119.2     .07       0  4451.6    .035       0    4491     .07       0
  4595.9     .12       0  4910.7     .07       0  4979.9     .05       0
  4986.5     .07       0    5011     .12       0  5029.7    .063       0
Bank Sta=4979.9,4986.5
XS Rating Curve= 0 ,0
Exp/Cntr=0.3,0.1

Type RM Length L Ch R = 1 ,1438    ,312,312,312
BEGIN DESCRIPTION:
Ahern Creek 3.0
END DESCRIPTION:
XS GIS Cut Line= 3
      2150674.98       13857625.        2151875.       13857425.
      2151975.01     13857224.98
#Sta/Elev= 30
  3787.9 1054.18  3876.6  1051.3  3881.7 1052.46  3909.6 1051.96  4003.4 1046.18
  4038.3 1045.14  4102.2 1043.28  4137.9 1043.65  4315.1 1041.49  4448.5 1036.55
  4484.9 1035.74    4490 1034.16    4528 1033.92  4545.7 1034.03  4550.8  1035.7
  4568.5 1036.15  4649.3 1036.17  4772.5 1036.46  4882.8 1036.87  4923.4 1033.95
  4943.6 1034.58  4968.2 1031.65  4968.7 1031.15  4974.9 1031.65  5026.8 1033.85
  5063.2 1038.13  5087.2  1040.3  5152.6 1043.38  5197.3 1051.12  5228.1 1053.37
#Mann= 10 ,-1 , 0
  3787.9    .035       0  4038.3     .12       0  4137.9     .07       0
  4448.5    .035       0  4649.3     .07       0  4772.5     .12       0
  4968.2     .05       0  4974.9     .12       0  5063.2     .07       0
  5087.2     .12       0
Bank Sta=4968.2,4974.9
XS Rating Curve= 0 ,0
Exp/Cntr=0.3,0.1

Type RM Length L Ch R = 1 ,1126    ,602,602,602
BEGIN DESCRIPTION:
Ahern Creek 2.0
END DESCRIPTION:
XS GIS Cut Line= 3
      2151314.28      13858183.6      2152018.56     13857712.69
      2152347.77     13857320.98
#Sta/Elev= 30
  4086.1 1037.09    4242 1036.46  4496.7 1035.08  4627.3 1033.99  4640.3 1032.11
  4654.3 1025.05  4666.1 1023.54  4681.3 1023.89  4699.4 1024.51  4705.4 1028.56
  4720.4 1030.95  4762.4 1031.94  4802.3 1029.96  4849.5 1024.09  4856.9 1025.43
  4870.5 1032.56  4885.6 1034.49  4933.3 1034.19  4964.8 1030.52  4990.1 1022.69
  4990.6 1022.19  4996.8 1022.69  5007.7 1024.29  5028.5 1022.81  5042.8 1025.92
  5057.1 1031.43    5078 1033.93  5262.7 1038.51  5319.9 1041.65    5445 1045.24
#Mann= 8 ,-1 , 0
  4086.1     .07       0    4242    .035       0  4496.7     .07       0
  4666.1    .035       0  4681.3     .07       0  4802.3     .12       0
  4990.1     .05       0  4996.8     .12       0
Bank Sta=4990.1,4996.8
XS Rating Curve= 0 ,0
Exp/Cntr=0.3,0.1

Type RM Length L Ch R = 1 ,524     ,0,0,0
BEGIN DESCRIPTION:
Ahern Creek 1.0
END DESCRIPTION:
XS GIS Cut Line= 3
      2151684.17     13858348.48        2152525.       13857975.
      2152604.35      13857754.7
#Sta/Elev= 30
  4084.5 1033.06  4534.2 1031.26  4535.2 1031.26  4643.5 1029.87  4694.7 1021.84
  4700.1 1019.33  4723.4 1018.31  4762.1 1018.66  4807.6  1020.4  4839.7 1019.69
  4845.2 1021.57  4891.7 1020.68  4897.1 1021.88  4906.1 1021.37  4914.9 1018.72
  4920.4 1021.52  4938.2 1016.84  4943.7 1019.01  4949.8 1017.49  4983.1 1014.97
  4986.8 1014.49  4987.3 1013.99  4993.5 1014.49  5001.8 1020.01  5007.2 1020.01
  5014.6 1022.08  5019.9 1027.43  5025.8 1028.93  5188.6 1031.19  5238.7 1031.77
#Mann= 9 ,-1 , 0
  4084.5    .035       0  4534.2     .12       0  4535.2     .07       0
  4643.5     .12       0  4762.1    .035       0  4983.1     .12       0
  4986.8     .05       0  4993.5     .12       0  5188.6     .07       0
Bank Sta=4986.8,4993.5
XS Rating Curve= 0 ,0
Exp/Cntr=0.3,0.1

Chan Stop Cuts=-1
Use User Specified Reach Order=0
Composite Channel Slope=5