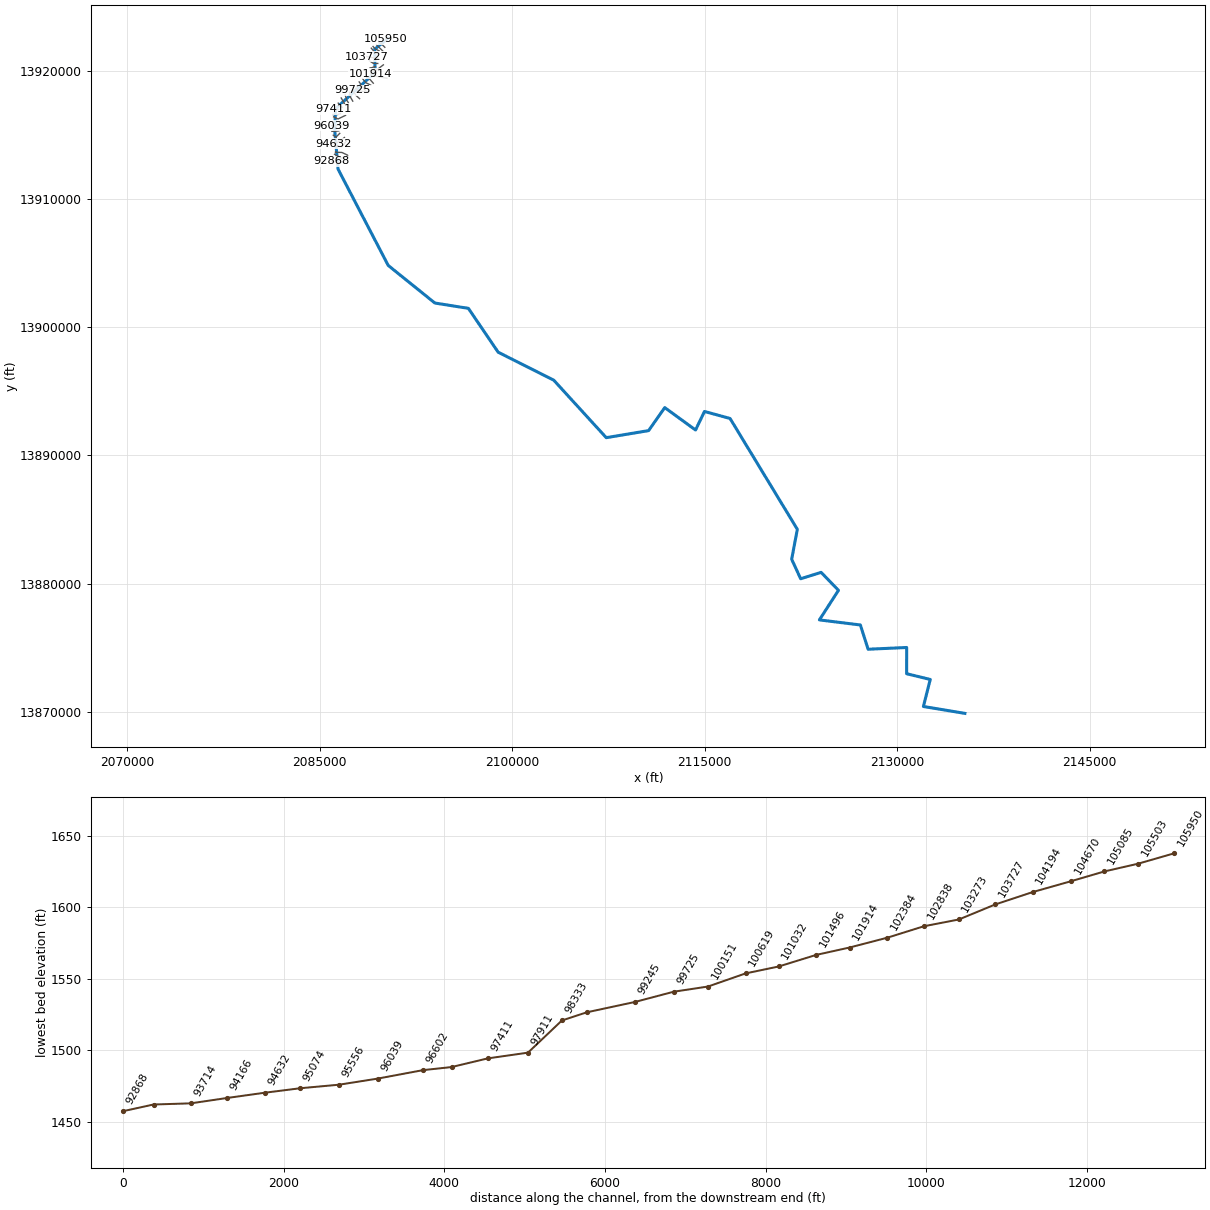
--- CURRY CREEK.prj (project) ---

Proj Title=CURRY CREEK Base Level Engineering
Current Plan=p01
Default Exp/Contr=0.3,0.1
English Units
Geom File=g01
Flow File=f01
Plan File=p01
Y Axis Title=Elevation
X Axis Title(PF)=Main Channel Distance
X Axis Title(XS)=Station
BEGIN DESCRIPTION:
CURRY CREEK
END DESCRIPTION:
DSS Export Rating Curves= 0
DSS Export Rating Curve Sorted= 0
DSS Export Volume Flow Curves= 0
DXF OffsetX= 0
DXF OffsetY= 0
DXF ScaleX= 1
DXF ScaleY= 10

--- CURRY CREEK.p01 (plan) ---

Plan Title=Multiple Run
Short Identifier=Multiple
Geom File=g01
Flow File=f01
Subcritical Flow
K Sum by GR= 0
Std Step Tol= 0.01
Critical Tol= 0.01
Num of Std Step Trials= 20
Max Error Tol= 0.3
Flow Tol Ratio= 0.001
Split Flow NTrial= 30
Split Flow Tol= 0.02
Split Flow Ratio= 0.02
Log Output Level= 0
Friction Slope Method= 1
Unsteady Friction Slope Method= 2
Unsteady Bridges Friction Slope Method= 1
Parabolic Critical Depth
Global Vel Dist=  1 , 1 , 1
Global Log Level= 0
CheckData=True
Encroach Param= -1, 0, 0, 0
BEGIN DESCRIPTION:
Multiple Run
END DESCRIPTION:

--- CURRY CREEK.f01 (steady flow) ---

Flow Title=Multiple
Program Version=4.10
Number of Profiles= 7
Profile Names=10-year,25-year,50-year,1pct_min,100-year,1pct_plu,500-year
River Rch & RM=CURRY CREEK,Reach-1         ,105950
    1166    2014    2836    1939    3870    7721    7139
River Rch & RM=CURRY CREEK,Reach-1         ,101496
    1352    2347    3318    2275    4539    9056    8422
River Rch & RM=CURRY CREEK,Reach-1         ,97411
    2401    4293    6189    4319    8618   17196   16581
River Rch & RM=CURRY CREEK,Reach-1         ,95074
    2928    5264    7616    5329   10633   21216   20566
River Rch & RM=CURRY CREEK,Reach-1         ,90449
    5025    9173   13402    9445   18846   37602   36904
River Rch & RM=CURRY CREEK,Reach-1         ,84537
    4314    7853   11455    8069   16099   32122   31560
River Rch & RM=CURRY CREEK,Reach-1         ,81930
    5555   10145   14828   10448   20846   41593   40804
River Rch & RM=CURRY CREEK,Reach-1         ,77880
    5516   10052   14668   10317   20585   41072   40151
River Rch & RM=CURRY CREEK,Reach-1         ,75041
    7213   13261   19468   13766   27467   54803   54143
River Rch & RM=CURRY CREEK,Reach-1         ,70424
    7448   13682   20074   14182   28297   56460   55684
River Rch & RM=CURRY CREEK,Reach-1         ,65745
    7714   14176   20805   14701   29333   58527   57743
River Rch & RM=CURRY CREEK,Reach-1         ,63117
   10421   19325   28540   20280   40463   80735   80527
River Rch & RM=CURRY CREEK,Reach-1         ,58495
   10540   19540   28850   20495   40892   81591   81334
River Rch & RM=CURRY CREEK,Reach-1         ,56385
   10560   19540   28813   20439   40781   81368   80880
River Rch & RM=CURRY CREEK,Reach-1         ,51369
   10511   19402   28560   20222   40348   80505   79724
River Rch & RM=CURRY CREEK,Reach-1         ,44095
   10655   19663   28942   20489   40880   81567   80745
River Rch & RM=CURRY CREEK,Reach-1         ,42459
   13193   24456   36109   25630   51139  102035  101518
River Rch & RM=CURRY CREEK,Reach-1         ,35301
   13428   24878   36718   26050   51977  103708  103084
River Rch & RM=CURRY CREEK,Reach-1         ,30878
   13195   24478   36150   25662   51202  102162  101699
River Rch & RM=CURRY CREEK,Reach-1         ,29749
   13754   25584   37856   26924   53721  107187  107107
River Rch & RM=CURRY CREEK,Reach-1         ,21977
   14171   26374   39039   27775   55418  110573  110560
River Rch & RM=CURRY CREEK,Reach-1         ,19762
   14188   26382   39028   27748   55365  110468  110307
River Rch & RM=CURRY CREEK,Reach-1         ,15918
   14185   26343   38936   27657   55182  110103  109732
River Rch & RM=CURRY CREEK,Reach-1         ,9750
   18057   33703   49995   35628   71088  141839  142237
River Rch & RM=CURRY CREEK,Reach-1         ,3515
   18075   33712   49985   35603   71037  141737  141986
Boundary for River Rch & Prof#=CURRY CREEK,Reach-1         , 1
Up Type= 0
Dn Type= 3
Dn Slope=0.004
Boundary for River Rch & Prof#=CURRY CREEK,Reach-1         , 2
Up Type= 0
Dn Type= 3
Dn Slope=0.004
Boundary for River Rch & Prof#=CURRY CREEK,Reach-1         , 3
Up Type= 0
Dn Type= 3
Dn Slope=0.004
Boundary for River Rch & Prof#=CURRY CREEK,Reach-1         , 4
Up Type= 0
Dn Type= 3
Dn Slope=0.004
Boundary for River Rch & Prof#=CURRY CREEK,Reach-1         , 5
Up Type= 0
Dn Type= 3
Dn Slope=0.004
Boundary for River Rch & Prof#=CURRY CREEK,Reach-1         , 6
Up Type= 0
Dn Type= 3
Dn Slope=0.004
Boundary for River Rch & Prof#=CURRY CREEK,Reach-1         , 7
Up Type= 0
Dn Type= 3
Dn Slope=0.004
DSS Import GetInterval= 0
DSS Import GetPeak= 0
DSS Import FillOption= 0

--- CURRY CREEK.g01 (geometry) ---

Geom Title=Existing Conditions
Program Version=4.10

River Reach=CURRY CREEK     ,Reach-1
Reach XY= 30
        2090325.       13922525.      2089282.59     13921678.35
       2089314.7      13919864.9      2086230.14     13917027.59
      2086174.18       13915325.      2086428.53     13912326.45
      2090338.62     13904811.79      2093972.57      13901880.4
      2096585.16     13901464.72      2098904.84     13898044.63
      2103234.68     13895864.24      2107326.53     13891378.75
      2110627.55     13891930.73      2111885.47     13893724.07
      2114285.51     13891976.22      2114980.85     13893422.95
        2116975.       13892875.      2122215.71     13884231.67
      2121775.03     13881895.05        2122475.       13880375.
      2124069.06     13880872.74      2125421.48     13879473.72
      2123935.48      13877165.2      2127127.45     13876769.53
      2127730.93     13874877.25      2130735.02     13875013.79
      2130732.81     13872968.81      2132572.95     13872519.16
      2132038.36     13870411.65        2135275.       13869875.

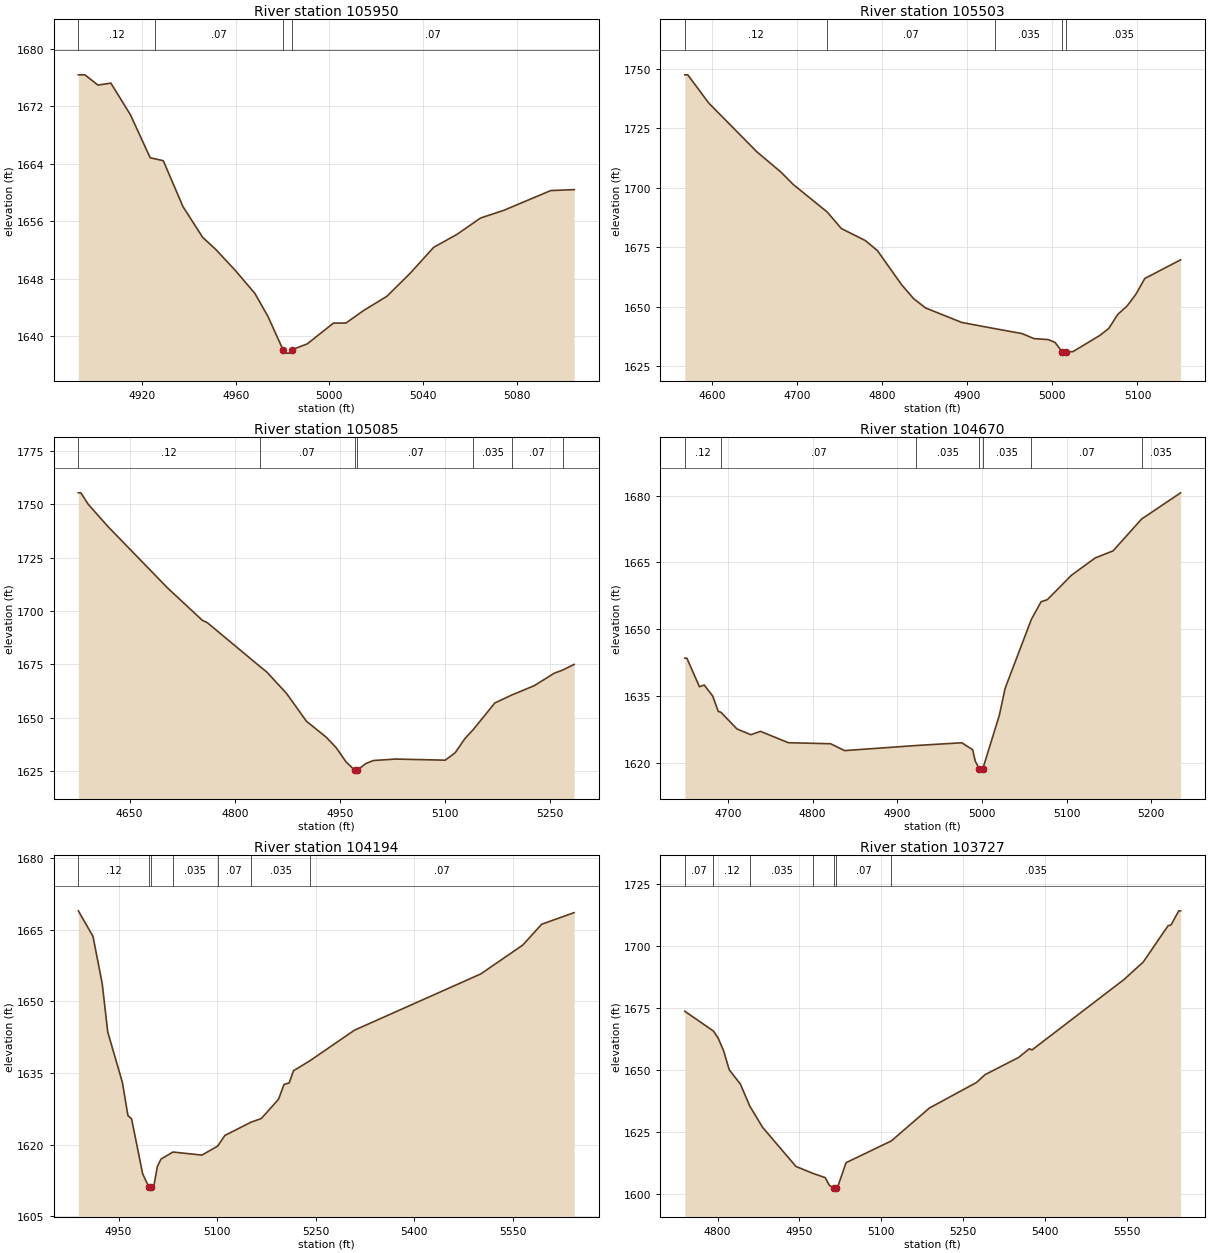
Type RM Length L Ch R = 1 ,105950  ,447,447,447
BEGIN DESCRIPTION:
CURRY CREEK 182.0
END DESCRIPTION:
XS GIS Cut Line= 3
      2090174.98     13922275.03        2090125.       13922375.
        2090125.     13922475.03
#Sta/Elev= 30
  4892.8 1676.35  4895.6 1676.35  4901.2 1674.92  4906.7  1675.2  4915.1 1670.77
  4923.5 1664.82  4925.6 1664.67  4929.1 1664.41  4937.5 1658.03  4945.9 1653.76
  4951.5 1652.08  4959.8 1649.18  4968.2 1645.97  4973.8 1642.76  4980.2 1638.16
  4980.5 1637.66    4984 1637.66  4984.2 1638.16  4990.6 1638.95  5001.8 1641.84
  5007.1 1641.84  5014.6 1643.57  5024.6 1645.56  5034.6 1648.78  5044.6 1652.37
  5054.6 1654.18  5064.6 1656.44  5074.6 1657.52  5094.6 1660.26  5104.6 1660.39
#Mann= 4 ,-1 , 0
  4892.8     .12       0  4925.6     .07       0  4980.2     .05       0
  4984.2     .07       0
Bank Sta=4980.2,4984.2
XS Rating Curve= 0 ,0
Exp/Cntr=0.3,0.1

Type RM Length L Ch R = 1 ,105503  ,418,418,418
BEGIN DESCRIPTION:
CURRY CREEK 181.0
END DESCRIPTION:
XS GIS Cut Line= 3
      2090074.97     13921825.03        2089775.       13922125.
      2089625.04     13922174.99
#Sta/Elev= 30
  4568.4 1747.38  4571.9 1747.38  4596.6 1735.49  4653.2 1714.98  4681.5 1706.45
  4695.6 1701.35  4735.8 1689.69  4752.2 1682.81  4780.5 1677.72  4794.6 1673.52
  4822.9 1659.23  4837.1 1653.34  4851.2 1649.41  4893.6 1643.33  4932.6 1640.71
  4964.3 1638.66  4978.5 1636.53  4995.3 1636.11  5003.2 1634.94  5011.7 1630.93
    5012 1630.43  5015.7 1630.93  5024.2 1631.05  5055.9 1637.88  5066.4 1640.85
    5077 1646.76  5087.5 1650.11    5098 1655.08  5108.6 1661.79  5150.7 1669.64
#Mann= 5 ,-1 , 0
  4568.4     .12       0  4735.8     .07       0  4932.6    .035       0
  5011.7    .035       0  5015.7    .035       0
Bank Sta=5011.7,5015.7
XS Rating Curve= 0 ,0
Exp/Cntr=0.3,0.1

Type RM Length L Ch R = 1 ,105085  ,415,415,415
BEGIN DESCRIPTION:
CURRY CREEK 180.0
END DESCRIPTION:
XS GIS Cut Line= 3
      2089925.03     13921524.97        2089625.       13921825.
      2089424.97     13922025.03
#Sta/Elev= 30
  4576.9 1755.29  4580.5 1755.29  4591.1 1749.89  4619.4 1739.44  4704.2 1710.76
  4753.7 1695.65  4760.8 1694.55  4835.6 1674.11  4845.6 1671.47  4873.9  1661.4
  4902.2 1648.42  4930.5 1640.92  4944.6 1636.06  4958.8 1629.34  4970.9 1625.55
  4971.2 1625.05  4974.9 1625.55  4987.1 1628.61  4997.7 1630.01  5029.5  1630.7
  5100.2 1630.18  5114.3 1633.62  5128.5 1640.36  5140.3 1644.54  5170.9 1656.93
    5195 1660.65  5227.5 1665.09  5255.8 1670.89  5267.5 1672.31  5284.1    1675
#Mann= 7 ,-1 , 0
  4576.9     .12       0  4835.6     .07       0  4970.9     .05       0
  4974.9     .07       0  5140.3    .035       0    5195     .07       0
  5267.5    .035       0
Bank Sta=4970.9,4974.9
XS Rating Curve= 0 ,0
Exp/Cntr=0.3,0.1

Type RM Length L Ch R = 1 ,104670  ,476,476,476
BEGIN DESCRIPTION:
CURRY CREEK 179.0
END DESCRIPTION:
XS GIS Cut Line= 3
      2089624.43     13921551.53      2089322.32     13921707.79
      2089155.62     13921888.38
#Sta/Elev= 30
  4648.9 1643.53  4651.4 1643.53  4666.2 1637.13  4671.9 1637.51    4682    1635
  4688.4  1631.6  4691.6 1631.41  4710.5 1627.67    4727 1626.37  4738.3 1627.13
  4771.3 1624.58  4821.2 1624.35  4837.7 1622.81  4922.1 1623.95  4976.2 1624.57
    4989 1623.02  4992.2 1620.41    4997 1618.71  4997.3 1618.21    5001 1618.71
  5020.6 1630.74  5027.4 1636.77  5058.4 1652.22  5069.9 1656.18  5077.3 1656.65
  5105.7 1662.11    5134 1666.02    5155 1667.59  5188.6 1674.71  5234.8  1680.6
#Mann= 7 ,-1 , 0
  4648.9     .12       0  4691.6     .07       0  4922.1    .035       0
    4997    .035       0    5001    .035       0  5058.4     .07       0
  5188.6    .035       0
Bank Sta=4997,5001
XS Rating Curve= 0 ,0
Exp/Cntr=0.3,0.1

Type RM Length L Ch R = 1 ,104194  ,467,467,467
BEGIN DESCRIPTION:
CURRY CREEK 178.0
END DESCRIPTION:
XS GIS Cut Line= 4
      2089574.98     13921275.01        2089475.       13921325.
      2089301.48     13921409.18      2089020.22     13921759.89
#Sta/Elev= 30
  4888.8 1669.02  4911.1 1663.67  4925.1 1653.77  4933.5 1643.64  4955.9 1632.98
  4964.2 1626.09  4969.8 1625.38  4986.6 1613.89  4995.8 1611.14    4996 1610.64
  4999.8 1611.14  5003.4 1611.14  5009.1 1615.42  5014.6 1616.95  5032.7 1618.42
  5076.8 1617.78  5100.7 1619.66  5111.7  1621.9  5151.4 1624.68  5167.1 1625.45
  5193.4  1629.5  5201.6 1632.59  5209.6 1632.93    5216 1635.46  5241.2 1637.58
  5308.8 1643.98  5500.8 1655.77  5564.8 1661.83  5593.6 1666.21    5643 1668.64
#Mann= 7 ,-1 , 0
  4888.8     .12       0  4995.8     .05       0  4999.8     .12       0
  5032.7    .035       0  5100.7     .07       0  5151.4    .035       0
  5241.2     .07       0
Bank Sta=4995.8,4999.8
XS Rating Curve= 0 ,0
Exp/Cntr=0.3,0.1

Type RM Length L Ch R = 1 ,103727  ,454,454,454
BEGIN DESCRIPTION:
CURRY CREEK 177.0
END DESCRIPTION:
XS GIS Cut Line= 3
      2089574.96     13920925.01        2089325.       13920975.
      2088683.38     13921103.64
#Sta/Elev= 30
  4739.9 1673.79  4792.4 1665.79    4801 1662.99  4811.2 1657.75  4821.4 1650.15
  4841.8 1644.39    4859 1635.53  4882.6  1626.9  4943.8 1611.11  4975.7 1608.25
  4997.4 1606.61    5005 1603.48  5013.2 1602.46  5013.4 1601.96  5017.2 1602.46
  5020.3 1602.86  5035.6 1612.63  5118.7 1621.43  5188.6 1634.72  5274.9 1645.03
  5290.6 1648.19  5351.8 1655.09  5371.7 1658.62  5376.8 1658.19  5545.6 1686.63
  5580.5 1693.63  5626.4 1708.37  5631.5 1708.59  5645.8 1714.33  5649.2 1714.33
#Mann= 7 ,-1 , 0
  4739.9     .07       0  4792.4     .12       0    4859    .035       0
  4975.7     .07       0  5013.2     .05       0  5017.2     .07       0
  5118.7    .035       0
Bank Sta=5013.2,5017.2
XS Rating Curve= 0 ,0
Exp/Cntr=0.3,0.1

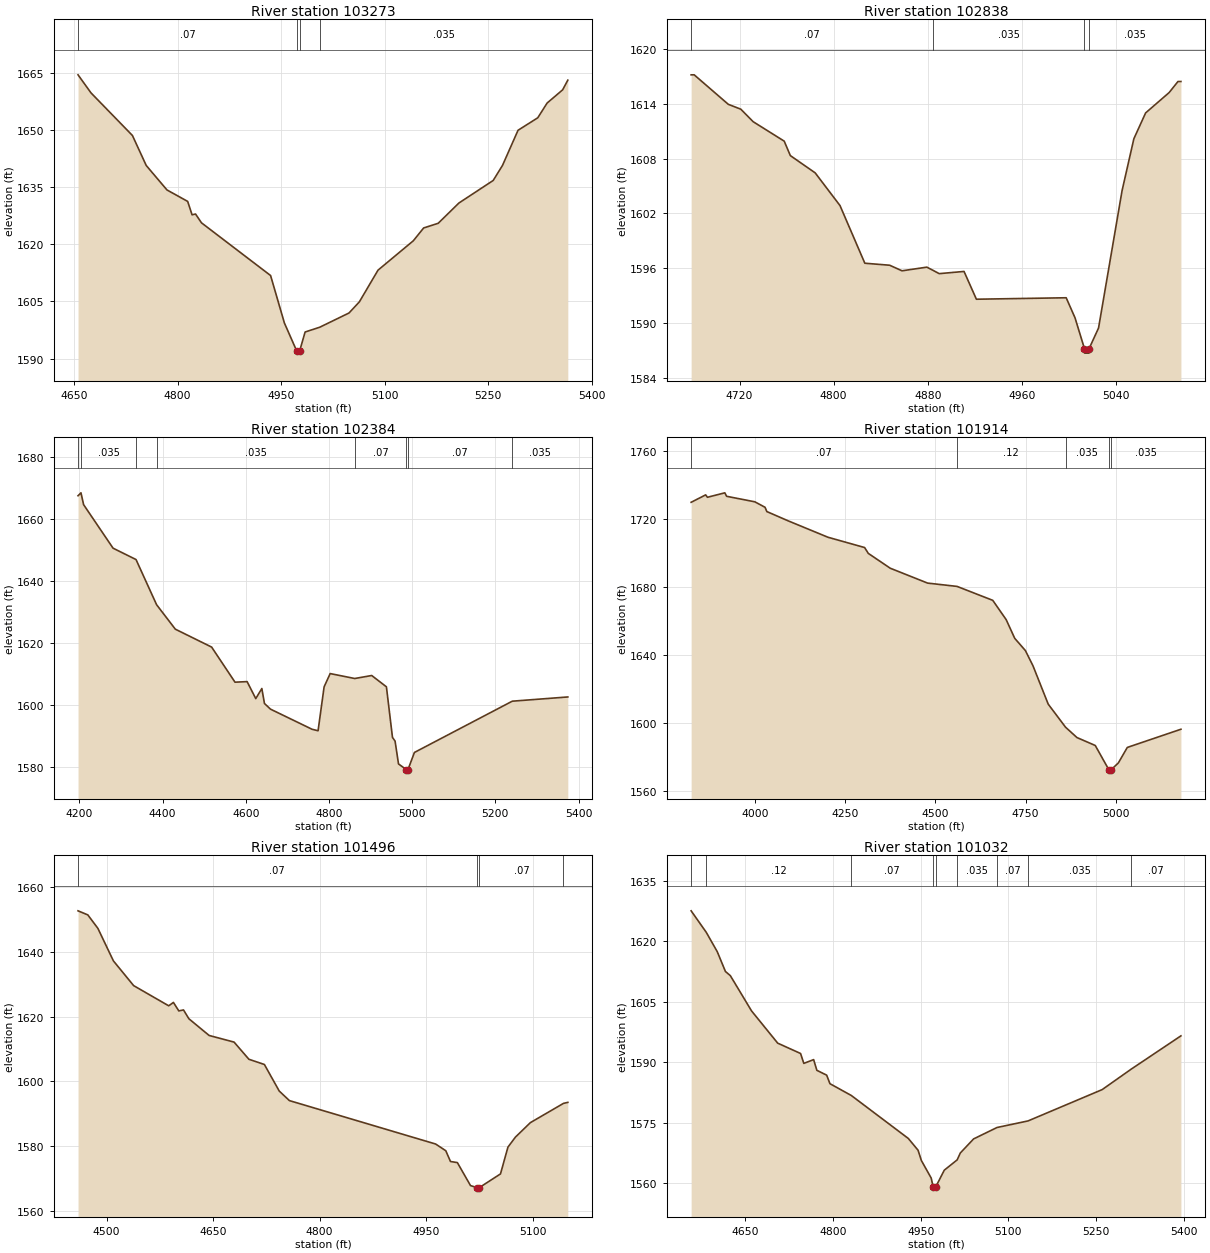
Type RM Length L Ch R = 1 ,103273  ,435,435,435
BEGIN DESCRIPTION:
CURRY CREEK 176.0
END DESCRIPTION:
XS GIS Cut Line= 3
      2089523.75     13920565.43        2089175.       13920575.
      2088875.03     13920774.98
#Sta/Elev= 30
  4655.8 1664.45  4674.6 1659.71  4734.6 1648.53  4754.6 1640.66  4784.6 1634.25
  4814.6 1631.24    4821 1627.72    4826 1627.93  4834.6 1625.62  4934.7 1611.79
  4954.7 1599.34  4972.7 1591.93  4972.9 1591.43  4976.7 1591.93  4984.7 1596.97
  5005.8 1598.22  5048.3 1601.96  5063.3 1604.89  5090.3  1613.2  5141.4  1620.9
  5156.4 1624.27  5177.5  1625.5  5207.5 1630.82  5257.1 1636.73  5270.6 1640.68
  5293.1  1649.9  5321.7 1653.18  5335.2 1657.04  5357.7 1660.51  5365.2 1663.05
#Mann= 4 ,-1 , 0
  4655.8     .07       0  4972.7     .05       0  4976.7     .07       0
  5005.8    .035       0
Bank Sta=4972.7,4976.7
XS Rating Curve= 0 ,0
Exp/Cntr=0.3,0.1

Type RM Length L Ch R = 1 ,102838  ,454,454,454
BEGIN DESCRIPTION:
CURRY CREEK 175.0
END DESCRIPTION:
XS GIS Cut Line= 3
        2089325.       13920325.        2089025.       13920225.
      2088925.03       13920225.
#Sta/Elev= 30
  4678.9 1617.16  4681.5 1617.16  4710.5 1613.93  4721.1  1613.4  4731.6 1612.03
    4758  1609.9  4763.2 1608.32  4784.3 1606.43  4805.4 1602.85  4826.5 1596.54
  4847.6 1596.32  4858.1 1595.71  4879.2 1596.11  4884.3 1595.77  4889.7  1595.4
  4910.8 1595.64  4921.3  1592.6  4997.6 1592.76  5005.1 1590.57  5013.1  1587.2
  5013.4  1586.7  5016.9  1586.7  5017.1  1587.2  5025.1 1589.45  5045.1 1604.49
  5055.1 1610.16  5065.1 1612.99  5085.1 1615.22  5092.6 1616.43  5095.1 1616.43
#Mann= 4 ,-1 , 0
  4678.9     .07       0  4884.3    .035       0  5013.1    .035       0
  5017.1    .035       0
Bank Sta=5013.1,5017.1
XS Rating Curve= 0 ,0
Exp/Cntr=0.3,0.1

Type RM Length L Ch R = 1 ,102384  ,470,470,470
BEGIN DESCRIPTION:
CURRY CREEK 174.0
END DESCRIPTION:
XS GIS Cut Line= 3
      2089961.17     13920457.76        2089325.       13919975.
      2088950.76     13920034.19
#Sta/Elev= 30
  4196.8 1667.38  4203.9 1668.32  4210.2 1664.51    4281  1650.5  4336.2 1646.84
  4385.7 1632.29  4430.7 1624.42    4518 1618.65  4574.2 1607.35  4603.3 1607.53
  4624.1 1602.06  4638.7 1605.31    4645 1600.49  4659.5 1598.67  4759.4 1592.19
  4773.9 1591.71  4788.4 1605.84    4803 1610.12    4862 1608.53  4902.8  1609.5
  4938.2 1605.86  4952.8 1589.56    4959 1588.38  4967.3 1581.02  4986.1 1579.21
  4986.4 1578.71  4990.1 1579.21  5005.5 1584.72  5240.8 1601.23  5374.3 1602.59
#Mann= 8 ,-1 , 0
  4196.8     .07       0  4203.9    .035       0  4336.2     .07       0
  4385.7    .035       0    4862     .07       0  4986.1     .05       0
  4990.1     .07       0  5240.8    .035       0
Bank Sta=4986.1,4990.1
XS Rating Curve= 0 ,0
Exp/Cntr=0.3,0.1

Type RM Length L Ch R = 1 ,101914  ,418,418,418
BEGIN DESCRIPTION:
CURRY CREEK 173.0
END DESCRIPTION:
XS GIS Cut Line= 3
      2090238.96     13919412.66        2089075.       13919625.
      2088964.69     13919763.33
#Sta/Elev= 30
  3821.5 1729.68  3861.8 1734.03  3866.8 1732.63    3915 1735.24  3920.1  1733.2
  3998.3 1729.97  4026.7 1726.76  4031.7 1724.24  4090.1 1718.86  4201.7 1709.14
  4303.2 1703.12  4313.4 1699.69  4374.4 1690.97  4478.2 1682.23  4559.8  1680.3
  4659.1 1672.11  4696.4 1660.76    4720 1649.83  4749.7 1642.62  4770.9 1633.62
  4813.1 1611.15  4861.2 1597.63  4892.9 1591.54  4943.7 1586.89  4982.3 1572.33
  4982.6 1571.83  4986.3 1572.33  5007.9 1576.66  5032.7 1585.74  5181.6 1596.42
#Mann= 5 ,-1 , 0
  3821.5     .07       0  4559.8     .12       0  4861.2    .035       0
  4982.3    .035       0  4986.3    .035       0
Bank Sta=4982.3,4986.3
XS Rating Curve= 0 ,0
Exp/Cntr=0.3,0.1

Type RM Length L Ch R = 1 ,101496  ,464,464,464
BEGIN DESCRIPTION:
CURRY CREEK 172.0
END DESCRIPTION:
XS GIS Cut Line= 3
        2089175.     13919024.99        2088825.       13919425.
      2088675.03     13919474.99
#Sta/Elev= 30
  4459.8 1652.77  4473.6 1651.51  4487.8 1647.33  4509.6 1637.28  4538.1 1629.62
  4587.5 1623.37  4594.1 1624.42  4601.7 1621.79  4608.3  1622.1  4615.9 1619.36
  4644.4 1614.19  4679.5 1612.14  4700.4 1606.82  4722.2 1605.21  4743.1 1596.99
  4757.4 1594.03  4963.3 1580.59  4977.6 1578.51  4984.2 1575.18  4993.9 1574.84
  5012.4 1567.73  5020.9 1567.13  5021.2 1566.63    5025 1567.13  5054.6 1571.34
  5065.1 1579.63  5075.6 1582.72  5096.7 1587.21  5143.3 1593.17  5149.4 1593.48
#Mann= 4 ,-1 , 0
  4459.8     .07       0  5020.9     .05       0    5025     .07       0
  5143.3    .035       0
Bank Sta=5020.9,5025
XS Rating Curve= 0 ,0
Exp/Cntr=0.3,0.1

Type RM Length L Ch R = 1 ,101032  ,413,413,413
BEGIN DESCRIPTION:
CURRY CREEK 171.0
END DESCRIPTION:
XS GIS Cut Line= 3
      2088975.02     13918874.99        2088575.       13919075.
      2088336.24     13919384.84
#Sta/Elev= 30
  4557.1 1627.53    4583  1622.2  4601.8 1617.41  4615.8  1612.5  4624.2 1611.47
  4660.5 1602.73  4705.3 1594.74  4744.4 1592.18    4750 1589.73  4766.8 1590.66
  4772.3 1588.01  4789.1 1586.81  4794.7  1584.7  4831.3 1581.77  4928.9 1571.12
  4945.6  1568.2  4951.2 1565.66    4968 1561.32  4971.5 1559.07  4971.8 1558.57
  4975.6 1559.07  4990.4 1563.26  5012.5 1565.82  5017.9 1567.53  5040.6 1571.01
  5080.7 1573.84  5133.8 1575.47  5260.7 1583.23  5310.3 1588.29  5395.5 1596.55
#Mann= 9 ,-1 , 0
  4557.1     .07       0    4583     .12       0  4831.3     .07       0
  4971.5     .05       0  4975.6     .07       0  5012.5    .035       0
  5080.7     .07       0  5133.8    .035       0  5310.3     .07       0
Bank Sta=4971.5,4975.6
XS Rating Curve= 0 ,0
Exp/Cntr=0.3,0.1

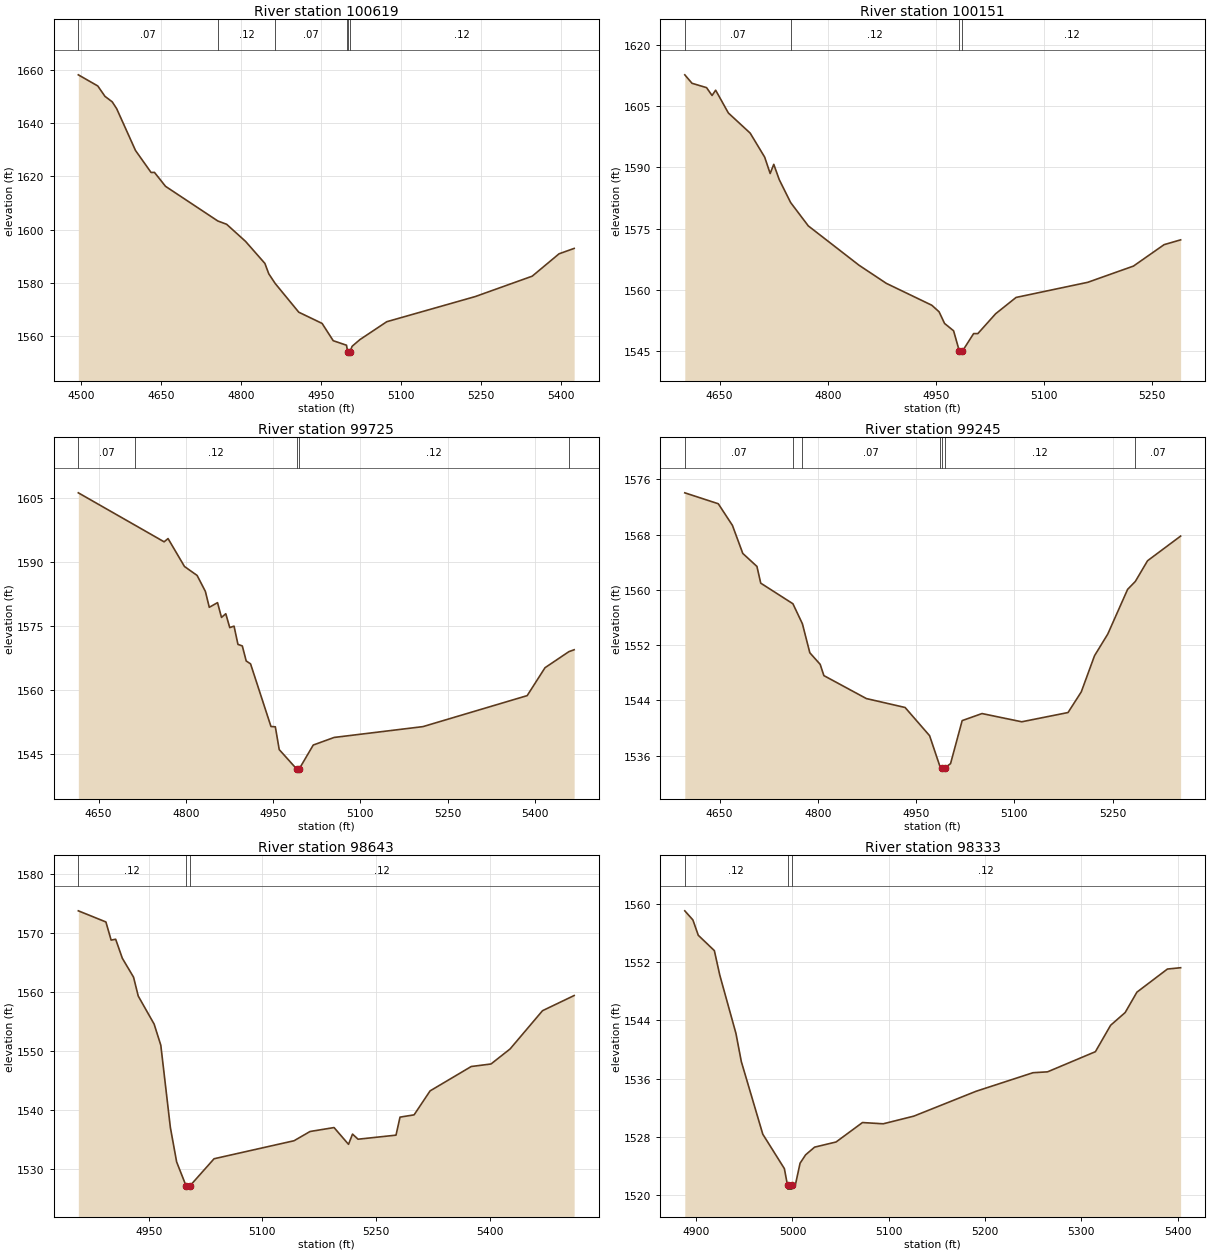
Type RM Length L Ch R = 1 ,100619  ,468,468,468
BEGIN DESCRIPTION:
CURRY CREEK 170.0
END DESCRIPTION:
XS GIS Cut Line= 3
      2088625.03     13918374.96        2088325.       13918775.
      2088074.98     13919125.03
#Sta/Elev= 30
  4494.3 1658.13  4530.8 1653.95  4544.3 1650.05  4557.9 1647.99  4566.2 1645.44
  4601.6 1629.73  4630.8 1621.49  4637.1 1621.53  4657.9 1616.29    4756 1603.29
  4772.5 1602.06  4807.9 1595.66  4844.3 1587.37  4851.6 1583.47  4863.7 1579.82
  4907.9 1569.06  4951.6 1564.86  4972.5 1558.37  4997.4 1556.68    4999 1554.88
  4999.6 1554.21  4999.9 1553.71  5003.9 1554.21  5007.9 1556.27  5022.6 1558.79
    5073  1565.5  5238.9 1574.93  5345.8 1582.58  5396.2 1590.98  5424.5    1593
#Mann= 6 ,-1 , 0
  4494.3     .07       0    4756     .12       0  4863.7     .07       0
    4999     .12       0  4999.6     .05       0  5003.9     .12       0
Bank Sta=4999.6,5003.9
XS Rating Curve= 0 ,0
Exp/Cntr=0.3,0.1

Type RM Length L Ch R = 1 ,100151  ,426,426,426
BEGIN DESCRIPTION:
CURRY CREEK 169.0
END DESCRIPTION:
XS GIS Cut Line= 3
      2088424.97       13918375.        2088025.       13918425.
      2087815.37     13918617.52
#Sta/Elev= 30
  4601.7 1612.69  4611.7 1610.62  4631.9 1609.55  4639.5 1607.63  4644.5 1608.93
  4662.1 1603.35  4692.4 1598.41  4712.5 1592.53  4720.1 1588.52  4725.1 1590.77
  4732.7 1587.02  4748.5 1581.41    4773 1575.69  4843.5 1566.04  4881.3 1561.61
  4944.3 1556.26  4954.4 1554.65    4962  1551.8  4974.5    1550  4982.5 1545.03
  4982.8 1544.53  4986.8 1545.03  5002.3 1549.32  5008.2 1549.32  5032.8 1554.17
  5061.2 1558.17  5160.5 1561.87    5224 1565.85  5266.5  1571.1  5289.4 1572.27
#Mann= 4 ,-1 , 0
  4601.7     .07       0  4748.5     .12       0  4982.5     .05       0
  4986.8     .12       0
Bank Sta=4982.5,4986.8
XS Rating Curve= 0 ,0
Exp/Cntr=0.3,0.1

Type RM Length L Ch R = 1 ,99725   ,480,480,480
BEGIN DESCRIPTION:
CURRY CREEK 168.0
END DESCRIPTION:
XS GIS Cut Line= 3
      2088107.06     13917818.89        2087825.       13918075.
      2087574.99     13918475.01
#Sta/Elev= 30
  4615.1  1606.2  4713.1 1598.57  4762.6 1594.71  4769.4 1595.47  4797.7 1588.91
  4819.4 1586.82  4833.6 1583.08  4840.3 1579.35  4854.5 1580.44  4861.3 1576.97
  4868.7 1577.84  4875.5 1574.59  4882.9 1574.93  4889.6 1570.65  4897.1 1570.29
  4903.8 1566.76  4911.3 1566.08  4946.4 1551.39  4953.9 1551.32  4960.6 1545.97
  4990.6 1541.42  4990.8 1540.92  4994.9 1541.42  5019.1 1547.04    5055 1548.82
  5207.8 1551.36    5387 1558.63  5417.7 1565.18  5458.7 1568.94  5467.8 1569.39
#Mann= 5 ,-1 , 0
  4615.1     .07       0  4713.1     .12       0  4990.6     .05       0
  4994.9     .12       0  5458.7     .07       0
Bank Sta=4990.6,4994.9
XS Rating Curve= 0 ,0
Exp/Cntr=0.3,0.1

Type RM Length L Ch R = 1 ,99245   ,602,602,602
BEGIN DESCRIPTION:
CURRY CREEK 167.0
END DESCRIPTION:
XS GIS Cut Line= 3
        2087575.     13917625.01        2087375.       13917975.
      2087324.99     13918325.04
#Sta/Elev= 30
    4597 1574.05  4648.1 1572.47  4669.7 1569.34  4685.5 1565.28  4707.1  1563.4
  4712.9 1560.98    4762    1558  4776.5  1555.1  4787.8 1550.91  4803.6 1549.23
  4809.3  1547.6  4874.1 1544.28  4933.2 1542.99  4970.6 1538.91  4986.6  1534.4
  4989.9 1534.28  4990.2 1533.78  4994.4 1534.28  5002.6 1534.87  5020.3 1541.09
  5050.6 1542.11  5111.2 1540.92  5181.9 1542.26  5202.1 1545.25  5222.3 1550.48
  5242.5 1553.61  5272.8 1560.08  5284.6 1561.23  5303.2 1564.22  5353.7 1567.79
#Mann= 7 ,-1 , 0
    4597     .07       0    4762     .12       0  4776.5     .07       0
  4986.6     .12       0  4989.9     .05       0  4994.4     .12       0
  5284.6     .07       0
Bank Sta=4989.9,4994.4
XS Rating Curve= 0 ,0
Exp/Cntr=0.3,0.1

Type RM Length L Ch R = 1 ,98643   ,310,310,310
BEGIN DESCRIPTION:
CURRY CREEK 166.0
END DESCRIPTION:
XS GIS Cut Line= 3
        2087225.     13917525.01      2087134.82     13917655.71
      2086974.98     13918125.05
#Sta/Elev= 30
    4857 1573.79  4893.4  1571.9  4900.3 1568.82  4906.3 1568.96  4915.1 1565.73
  4929.9 1562.52  4936.1 1559.31  4957.1 1554.54  4965.9 1550.95  4978.5 1536.99
  4986.8 1531.13  4999.4 1527.01  4999.7 1526.51    5004 1527.01  5036.2 1531.67
  5141.8 1534.73  5162.9  1536.3  5194.6 1536.97  5213.7 1534.12    5219 1535.86
  5226.3 1534.99  5276.4 1535.68  5281.7 1538.74  5300.3 1539.13  5321.4  1543.2
  5375.7 1547.34  5401.8 1547.77    5427 1550.32  5469.8 1556.82  5511.6  1559.4
#Mann= 3 ,-1 , 0
    4857     .12       0  4999.4     .05       0    5004     .12       0
Bank Sta=4999.4,5004
XS Rating Curve= 0 ,0
Exp/Cntr=0.3,0.1

Type RM Length L Ch R = 1 ,98333   ,422,422,422
BEGIN DESCRIPTION:
CURRY CREEK 165.0
END DESCRIPTION:
XS GIS Cut Line= 3
      2086924.99     13917425.02        2086875.       13917525.
        2086675.       13917875.
#Sta/Elev= 30
  4888.2 1559.05  4896.6  1557.8  4902.2 1555.69  4918.9 1553.58  4924.5 1550.23
  4941.3 1542.21  4946.9 1538.33  4969.2 1528.35  4991.6 1523.62  4994.9  1521.3
  4995.2  1520.8  4999.2  1520.8  4999.5  1521.3  5002.9  1521.3  5007.9 1524.36
  5013.7 1525.52    5023 1526.57  5045.3 1527.28  5072.7 1529.95  5094.3 1529.78
    5126 1530.83  5190.7 1534.25  5249.8  1536.8  5264.9 1536.92  5314.6 1539.69
  5330.4 1543.32  5345.5 1545.07  5357.7 1547.87  5389.4 1551.05  5403.1 1551.23
#Mann= 3 ,-1 , 0
  4888.2     .12       0  4994.9     .05       0  4999.5     .12       0
Bank Sta=4994.9,4999.5
XS Rating Curve= 0 ,0
Exp/Cntr=0.3,0.1

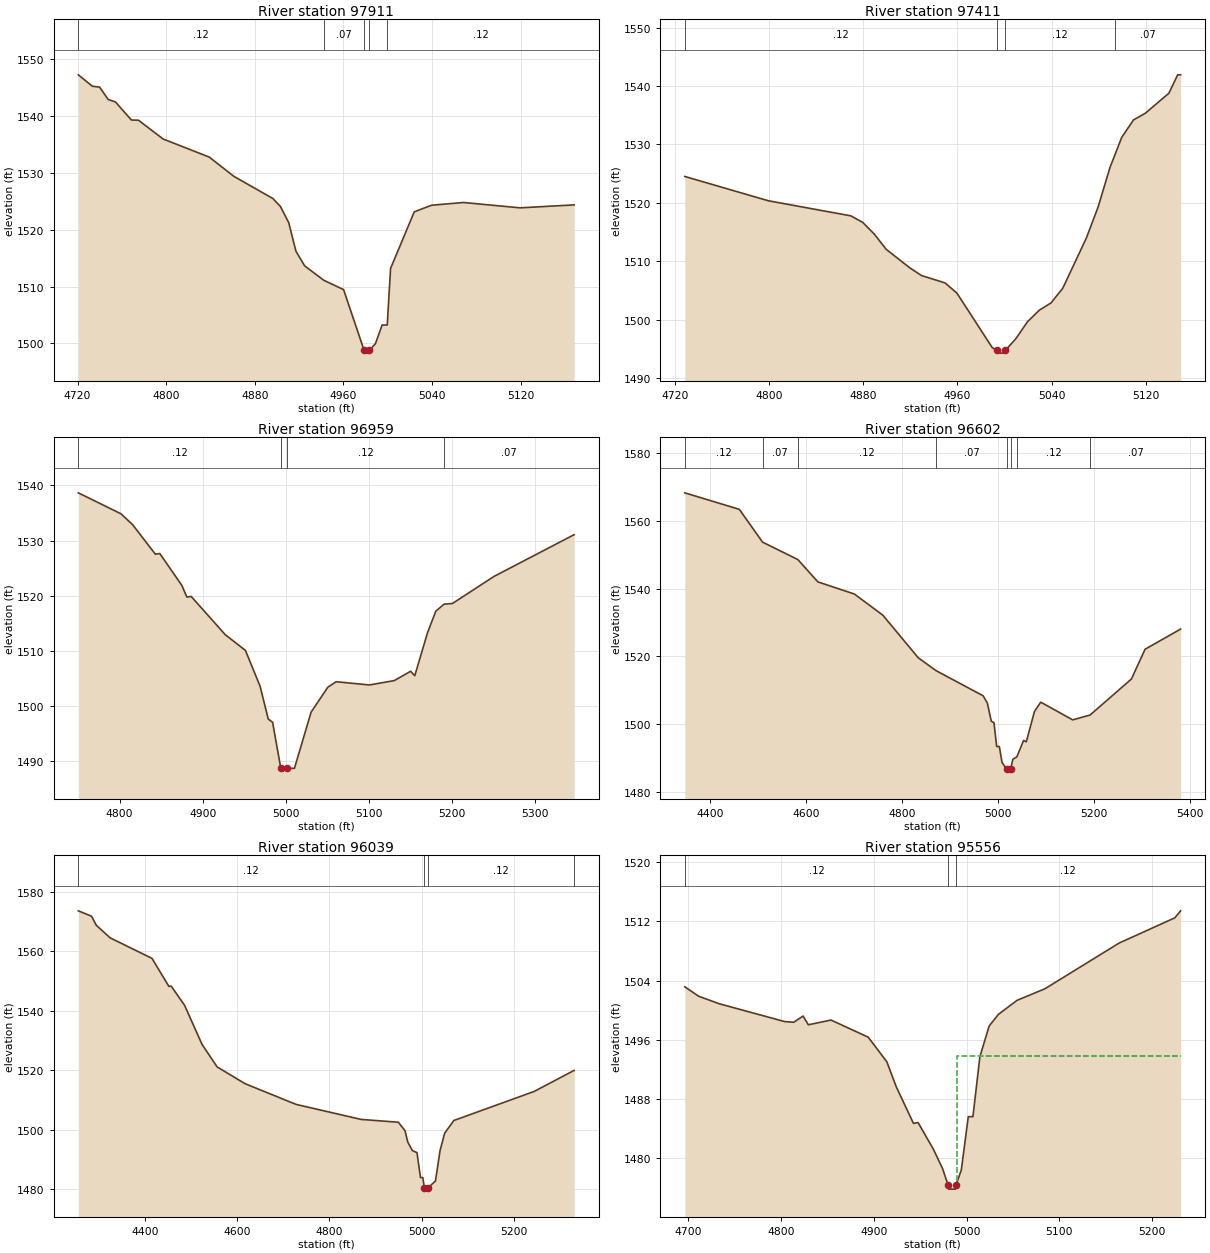
Type RM Length L Ch R = 1 ,97911   ,500,500,500
BEGIN DESCRIPTION:
CURRY CREEK 164.0
END DESCRIPTION:
XS GIS Cut Line= 3
      2086745.94     13917148.76      2086530.65     13917325.85
      2086444.34     13917470.84
#Sta/Elev= 30
  4720.7 1547.27  4733.4 1545.26  4739.9 1545.11  4747.7 1542.92  4754.2  1542.5
  4768.6 1539.32    4775 1539.28  4797.2 1535.98  4838.9 1532.79  4861.1  1529.4
  4896.3  1525.5  4903.2 1524.07  4910.6 1521.25  4917.1 1516.23    4925 1513.64
  4942.3 1511.11  4960.1 1509.47  4978.6 1498.79  4978.9 1498.29  4983.2 1498.79
  4988.8 1499.93  4994.9 1503.24  4999.2 1503.24  4999.5 1503.24  5002.5 1513.19
  5023.9 1523.16  5039.5 1524.32  5068.3  1524.8  5119.4 1523.86  5168.2 1524.38
#Mann= 5 ,-1 , 0
  4720.7     .12       0  4942.3     .07       0  4978.6     .05       0
  4983.2     .07       0  4999.2     .12       0
Bank Sta=4978.6,4983.2
XS Rating Curve= 0 ,0
Exp/Cntr=0.3,0.1

Type RM Length L Ch R = 1 ,97411   ,452,452,452
BEGIN DESCRIPTION:
CURRY CREEK 163.0
END DESCRIPTION:
XS GIS Cut Line= 3
      2086495.96      13916982.1        2086225.       13916975.
      2086075.05       13916975.
#Sta/Elev= 30
  4728.6 1524.52  4799.6 1520.36  4869.6 1517.78  4879.6 1516.67  4889.6 1514.64
  4899.6 1512.05  4919.6 1508.89  4929.6 1507.56  4949.6  1506.3  4959.6 1504.57
  4989.6 1495.24  4993.3 1494.78  4993.8 1494.28  5000.4 1494.28  5000.9 1494.78
  5009.6 1496.73  5019.6 1499.66  5029.6 1501.63  5039.6 1502.88  5049.6 1505.41
  5069.6    1514  5079.6 1519.33  5089.6 1526.05  5093.9 1528.27  5099.6 1531.22
  5109.6  1534.2  5119.6 1535.34  5139.6 1538.76  5147.1 1541.92  5149.6 1541.92
#Mann= 4 ,-1 , 0
  4728.6     .12       0  4993.3     .05       0  5000.9     .12       0
  5093.9     .07       0
Bank Sta=4993.3,5000.9
XS Rating Curve= 0 ,0
Exp/Cntr=0.3,0.1

Type RM Length L Ch R = 1 ,96959   ,357,357,357
BEGIN DESCRIPTION:
CURRY CREEK 162.0
END DESCRIPTION:
XS GIS Cut Line= 3
        2086614.     13916648.77        2086375.       13916575.
      2086028.61     13916586.22
#Sta/Elev= 30
  4750.3 1538.66  4801.6 1534.86  4815.6 1532.89    4843 1527.54  4848.3 1527.66
  4874.8  1521.9  4880.9 1519.77  4886.1 1519.88  4927.2 1512.93  4951.4  1510.1
    4969 1503.61  4978.9 1497.64  4984.1 1497.07    4994 1488.71  4994.5 1488.21
  5001.7 1488.71  5010.4 1488.72  5030.4 1498.89  5050.5 1503.41  5060.5 1504.42
  5100.5 1503.83  5130.5 1504.62  5150.2 1506.31  5155.2 1505.51  5170.5 1513.28
  5180.5 1517.21  5190.5 1518.48  5200.5  1518.6  5250.6 1523.51    5347 1531.08
#Mann= 4 ,-1 , 0
  4750.3     .12       0    4994     .05       0  5001.7     .12       0
  5190.5     .07       0
Bank Sta=4994,5001.7
XS Rating Curve= 0 ,0
Exp/Cntr=0.3,0.1

Type RM Length L Ch R = 1 ,96602   ,563,563,563
BEGIN DESCRIPTION:
CURRY CREEK 161.0
END DESCRIPTION:
XS GIS Cut Line= 3
      2087013.52     13916518.93      2086425.12     13916235.05
      2086082.76     13916402.23
#Sta/Elev= 30
  4346.7 1568.36  4460.5 1563.47  4508.9 1553.78  4582.5 1548.63  4624.3 1542.02
  4700.4 1538.43  4759.9 1532.16  4833.6 1519.58  4870.9 1515.75    4969 1508.33
  4977.9 1506.18    4986  1500.8  4991.6 1500.39  4997.3 1493.32  5002.8 1493.32
  5008.5  1488.6  5018.5 1486.54    5019 1486.04  5026.2 1486.54    5031 1489.54
  5039.3 1490.25  5053.5 1495.14  5059.1 1494.72  5076.1 1503.68  5089.2 1506.44
  5155.9  1501.2  5192.2 1502.64  5278.3 1513.28  5306.9  1522.1    5381 1528.06
#Mann= 8 ,-1 , 0
  4346.7     .12       0  4508.9     .07       0  4582.5     .12       0
  4870.9     .07       0  5018.5     .05       0  5026.2     .07       0
  5039.3     .12       0  5192.2     .07       0
Bank Sta=5018.5,5026.2
XS Rating Curve= 0 ,0
Exp/Cntr=0.3,0.1

Type RM Length L Ch R = 1 ,96039   ,483,483,483
BEGIN DESCRIPTION:
CURRY CREEK 160.0
END DESCRIPTION:
XS GIS Cut Line= 3
      2087013.48     13915827.11        2086275.       13915725.
      2085943.88     13915718.21
#Sta/Elev= 30
  4254.8  1573.6  4283.6 1571.78  4293.7 1568.77  4323.9 1564.52  4414.8 1557.63
  4451.4 1548.22  4456.5  1548.3  4485.5 1541.88  4523.3 1528.78  4556.1 1521.19
  4616.7 1515.55  4727.7 1508.58  4869.1 1503.53  4949.8 1502.59  4964.4 1499.68
    4970 1496.01  4980.1 1493.08  4990.2 1492.38  4997.8 1484.01  5002.8 1484.01
  5006.2 1480.62  5006.7 1480.12  5014.4 1480.62  5030.3 1482.84  5040.3 1493.08
  5050.3 1498.91  5070.3 1503.18  5244.8 1512.94  5331.3 1519.99  5331.5 1519.99
#Mann= 4 ,-1 , 0
  4254.8     .12       0  5006.2     .05       0  5014.4     .12       0
  5331.3     .07       0
Bank Sta=5006.2,5014.4
XS Rating Curve= 0 ,0
Exp/Cntr=0.3,0.1

Type RM Length L Ch R = 1 ,95556   ,482,482,482
BEGIN DESCRIPTION:
CURRY CREEK 159.0
END DESCRIPTION:
XS GIS Cut Line= 3
        2086482.     13915301.54        2086175.       13915275.
      2085948.69     13915270.32
#Sta/Elev= 30
  4696.2 1503.16  4711.2 1501.88  4733.3 1500.87  4803.6 1498.47  4813.6 1498.37
  4823.7 1499.21  4829.4 1498.03  4853.8 1498.67  4893.9 1496.36    4914 1493.04
    4924 1489.71  4942.7 1484.72  4947.7 1484.83  4964.2 1481.23  4974.2 1478.59
  4980.1 1476.35  4980.6 1475.85  4987.9 1475.85  4988.4 1476.35  4994.3 1478.44
  5001.8 1485.63  5006.8 1485.63  5014.3 1493.72  5024.3 1497.86  5034.3 1499.44
  5054.4 1501.33  5084.4 1502.89  5164.4 1509.06  5224.4 1512.46  5230.7 1513.41
#Mann= 3 ,-1 , 0
  4696.2     .12       0  4980.1     .05       0  4988.4     .12       0
#XS Ineff= 2 , 0
       0                    4990       0 1493.81
Permanent Ineff=
       F       F
Bank Sta=4980.1,4988.4
XS Rating Curve= 0 ,0
Exp/Cntr=0.3,0.1

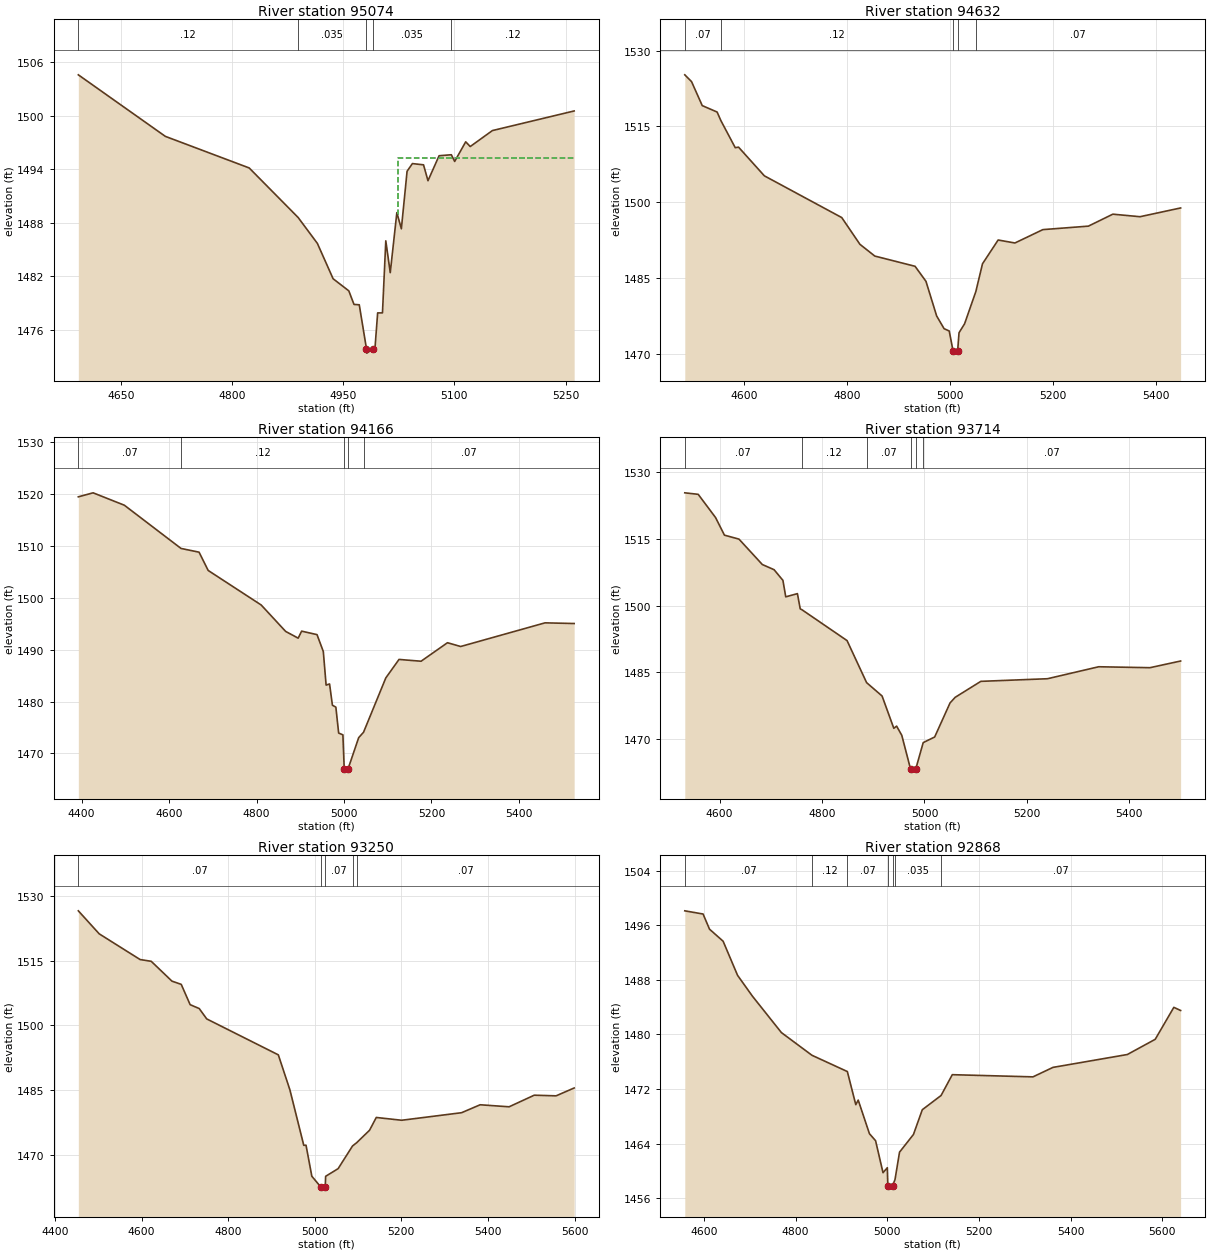
Type RM Length L Ch R = 1 ,95074   ,442,442,442
BEGIN DESCRIPTION:
CURRY CREEK 158.0
END DESCRIPTION:
XS GIS Cut Line= 3
      2086561.93     13915114.07        2086275.       13914825.
       2086058.4      13914971.7
#Sta/Elev= 30
  4592.7 1504.58  4710.1 1497.68  4823.2 1494.14  4889.3 1488.58  4915.2 1485.68
  4936.4 1481.72  4957.6 1480.36  4964.6 1478.84  4971.7  1478.8  4981.4 1473.88
  4981.9 1473.38  4990.4 1473.88  4992.9 1473.93  4996.5 1477.89    5003 1477.89
  5007.5 1485.97  5013.5  1482.4  5022.4 1489.13  5028.5 1487.32  5036.2 1493.77
  5043.4 1494.63  5058.4 1494.49  5064.4 1492.71  5079.4 1495.51  5095.9 1495.62
  5100.4 1494.87  5115.3 1497.07  5121.4 1496.54  5151.3 1498.33  5261.6 1500.53
#Mann= 5 ,-1 , 0
  4592.7     .12       0  4889.3    .035       0  4981.4    .035       0
  4990.4    .035       0  5095.9     .12       0
#XS Ineff= 2 , 0
       0                 5023.37       0  1495.2
Permanent Ineff=
       F       F
Bank Sta=4981.4,4990.4
XS Rating Curve= 0 ,0
Exp/Cntr=0.3,0.1

Type RM Length L Ch R = 1 ,94632   ,466,466,466
BEGIN DESCRIPTION:
CURRY CREEK 157.0
END DESCRIPTION:
XS GIS Cut Line= 3
      2086926.45      13914791.1        2086525.       13914475.
      2086108.54     13914298.71
#Sta/Elev= 30
  4484.5  1525.2  4497.6 1523.86  4518.4 1519.12  4547.3 1517.85  4554.5 1516.18
  4582.5 1510.81  4588.9 1510.92  4639.1 1505.25  4789.4 1497.01  4824.7 1491.73
  4853.6 1489.41  4931.8 1487.39    4953 1484.42  4973.8 1477.57  4988.2 1475.07
  4998.2 1474.61  5005.5 1470.74    5006 1470.24  5014.6 1470.74  5017.2 1474.26
    5028 1476.03  5049.9  1482.4  5062.8 1487.88  5093.2 1492.58  5125.8 1491.99
  5180.1 1494.63  5268.6 1495.32    5316 1497.68  5368.8 1497.18  5447.7 1498.91
#Mann= 5 ,-1 , 0
  4484.5     .07       0  4554.5     .12       0  5005.5     .05       0
  5014.6     .12       0  5049.9     .07       0
Bank Sta=5005.5,5014.6
XS Rating Curve= 0 ,0
Exp/Cntr=0.3,0.1

Type RM Length L Ch R = 1 ,94166   ,452,452,452
BEGIN DESCRIPTION:
CURRY CREEK 156.0
END DESCRIPTION:
XS GIS Cut Line= 3
      2087107.05     13914541.14        2086725.       13914075.
      2086197.29     13914138.35
#Sta/Elev= 30
  4392.4 1519.45  4426.2 1520.22  4497.7 1517.83  4627.3  1509.5  4668.6 1508.78
  4689.4 1505.26  4810.7  1498.6  4866.6 1493.51  4895.3 1492.21  4903.2 1493.56
  4938.4 1492.89  4952.8 1489.63  4959.2 1483.16  4967.1 1483.38  4973.6 1479.29
  4981.5 1478.91  4987.9 1473.92  4997.6 1473.57  5000.6 1467.08  5001.1 1466.58
  5009.7 1467.08  5033.7 1473.03  5044.8 1474.07  5095.8 1484.55    5126 1488.11
  5176.4 1487.76  5236.8 1491.33    5267  1490.6    5460 1495.16  5526.6 1495.03
#Mann= 5 ,-1 , 0
  4392.4     .07       0  4627.3     .12       0  5000.6     .05       0
  5009.7     .12       0  5044.8     .07       0
Bank Sta=5000.6,5009.7
XS Rating Curve= 0 ,0
Exp/Cntr=0.3,0.1

Type RM Length L Ch R = 1 ,93714   ,464,464,464
BEGIN DESCRIPTION:
CURRY CREEK 155.0
END DESCRIPTION:
XS GIS Cut Line= 3
      2087148.74     13913426.53        2086725.       13913625.
       2086225.1     13913641.82
#Sta/Elev= 30
  4532.1 1525.36  4558.3 1525.02  4592.2  1519.8  4609.5 1515.85  4637.9 1514.96
  4683.5 1509.25  4706.4 1508.09  4723.7 1505.69  4729.2 1501.99    4752 1502.71
  4757.5 1499.28  4760.5 1499.12  4848.9 1492.16  4887.1 1482.71  4917.3 1479.71
  4940.2 1472.45  4945.7 1472.94  4955.8 1470.87  4972.8 1463.33  4973.3 1462.83
  4983.1 1463.33  4997.6 1469.24    5020  1470.5    5050 1478.15  5060.1 1479.42
  5110.1    1483  5240.2 1483.59  5340.2 1486.28  5440.3 1486.07  5500.2 1487.57
#Mann= 6 ,-1 , 0
  4532.1     .07       0  4760.5     .12       0  4887.1     .07       0
  4972.8     .05       0  4983.1     .07       0  4997.6     .07       0
Bank Sta=4972.8,4983.1
XS Rating Curve= 0 ,0
Exp/Cntr=0.3,0.1

Type RM Length L Ch R = 1 ,93250   ,382,382,382
BEGIN DESCRIPTION:
CURRY CREEK 154.0
END DESCRIPTION:
XS GIS Cut Line= 3
      2087190.83     13913341.58        2086675.       13913175.
      2086155.66     13913482.09
#Sta/Elev= 30
  4453.8 1526.52    4502 1521.19  4596.5 1515.23  4622.2 1514.82  4670.1 1510.22
  4691.5 1509.48  4712.1 1504.77  4733.1 1503.87  4750.4 1501.47  4915.8 1493.14
  4942.6 1485.01  4974.6 1472.17  4979.8  1472.2  4993.2 1465.01  5013.9 1462.52
  5014.4 1462.02  5024.2 1462.52  5025.1 1464.99  5053.9 1466.76  5087.3 1472.03
    5097  1472.8  5126.5 1475.66  5142.1 1478.63  5200.7 1477.98  5339.1 1479.73
    5382 1481.57  5448.9  1481.1    5507 1483.79  5557.5 1483.64  5599.2 1485.46
#Mann= 5 ,-1 , 0
  4453.8     .07       0  5013.9     .05       0  5024.2     .07       0
  5087.3    .035       0    5097     .07       0
Bank Sta=5013.9,5024.2
XS Rating Curve= 0 ,0
Exp/Cntr=0.3,0.1

Type RM Length L Ch R = 1 ,92868   ,549,549,549
BEGIN DESCRIPTION:
CURRY CREEK 153.0
END DESCRIPTION:
XS GIS Cut Line= 3
      2086982.06     13912989.05      2086571.22     13912826.57
      2085940.42     13912933.48
#Sta/Elev= 30
  4558.2 1498.14  4598.1 1497.67  4612.1 1495.45  4641.8 1493.68  4673.3 1488.68
  4705.6 1485.63  4768.9 1480.28  4835.5 1476.95  4912.8 1474.56  4931.2  1469.7
  4936.5 1470.37  4960.9 1465.45  4974.4 1464.41  4990.6 1459.72    5000 1460.45
  5001.1 1457.81  5001.6 1457.31  5011.5 1457.81  5016.8 1458.72  5026.6 1462.73
    5057 1465.33  5076.3 1468.96  5117.3 1471.05  5141.7  1474.1  5317.7 1473.78
  5361.3 1475.17  5523.6 1477.06  5584.4 1479.29    5625 1483.98  5639.8 1483.52
#Mann= 7 ,-1 , 0
  4558.2     .07       0  4835.5     .12       0  4912.8     .07       0
  5001.1     .05       0  5011.5     .07       0  5016.8    .035       0
  5117.3     .07       0
Bank Sta=5001.1,5011.5
XS Rating Curve= 0 ,0
Exp/Cntr=0.3,0.1