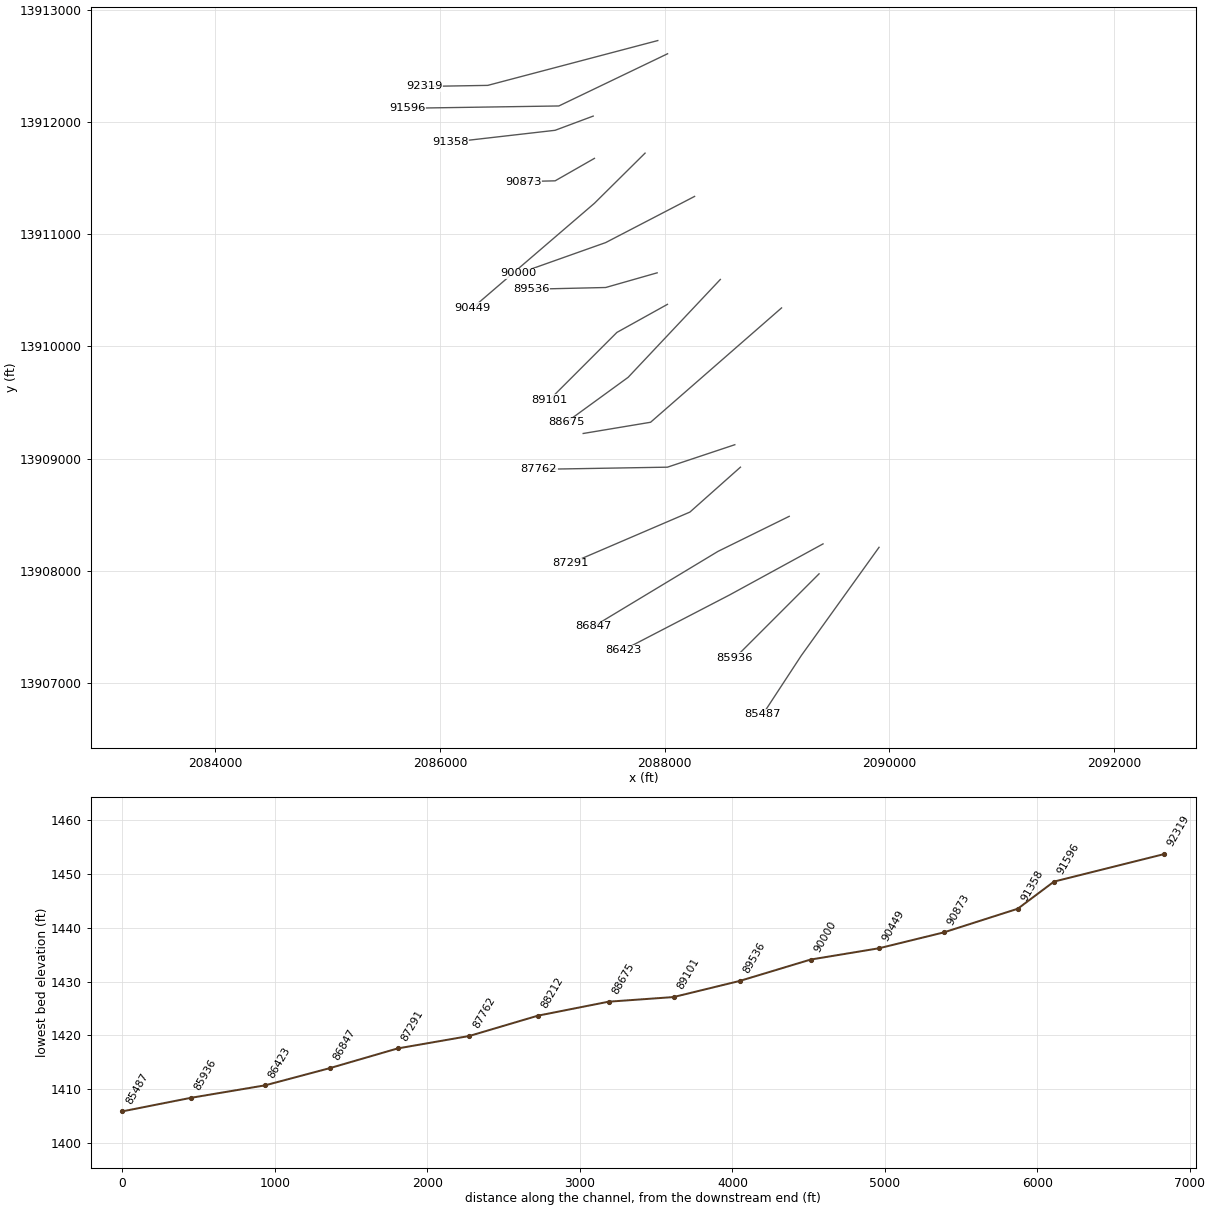
HEC-RAS study CURRY CREEK.prj: CURRY CREEK Base Level Engineering

--- CURRY CREEK.g01 (geometry) --- (continued)

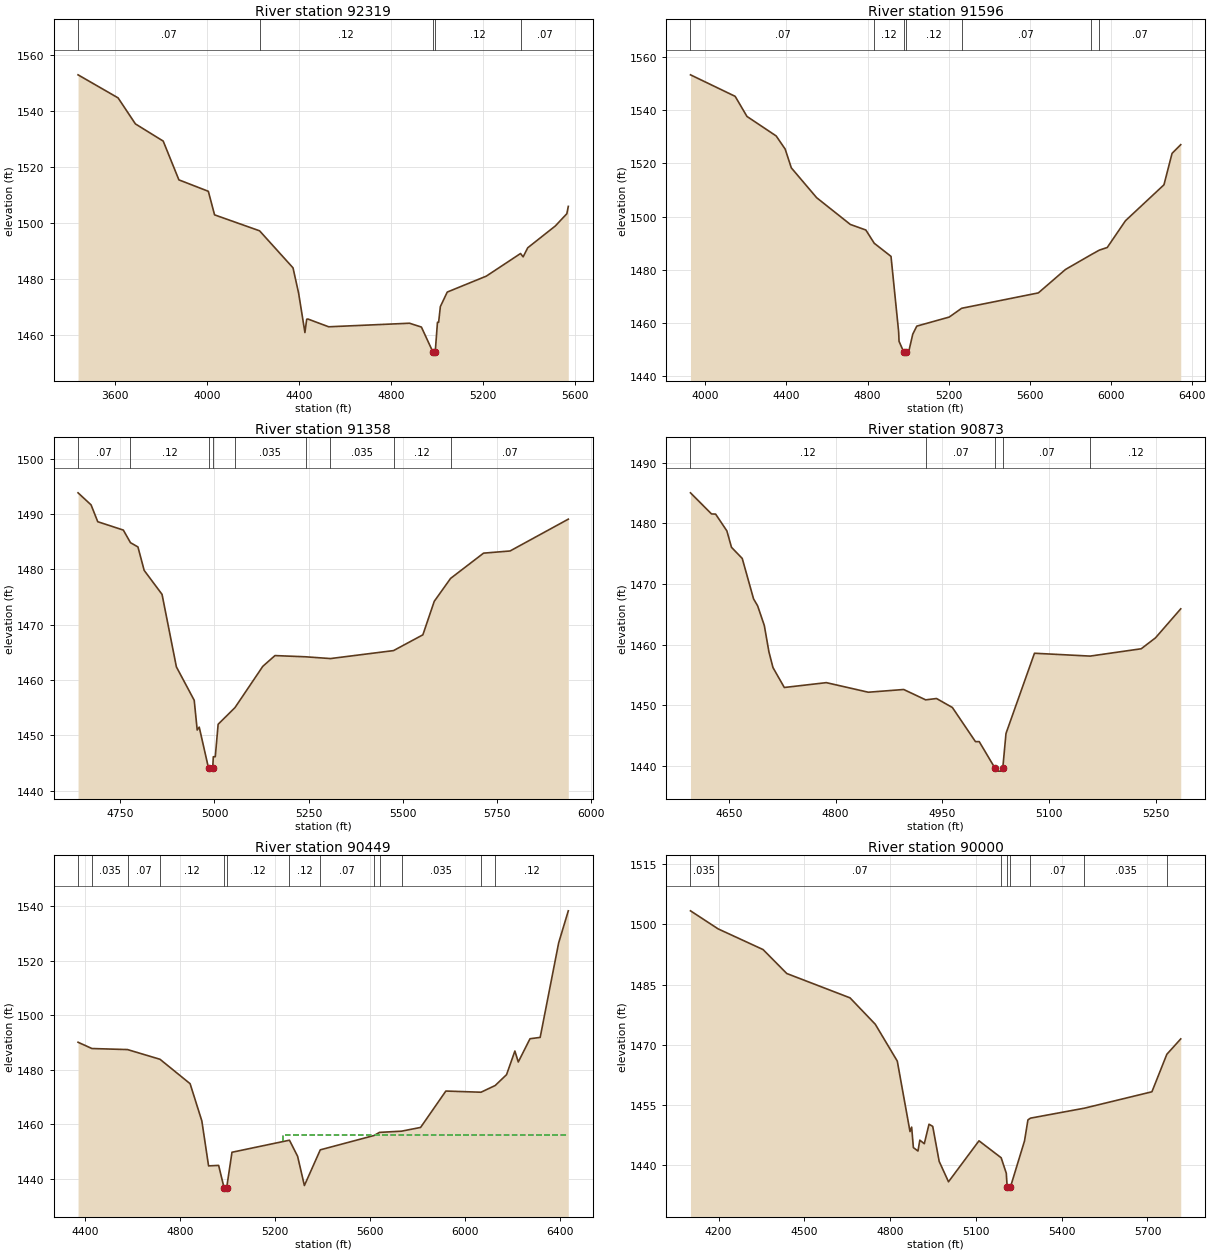
Type RM Length L Ch R = 1 ,92319   ,723,723,723
BEGIN DESCRIPTION:
CURRY CREEK 152.0
END DESCRIPTION:
XS GIS Cut Line= 3
      2087939.15     13912724.18        2086425.       13912325.
      2085858.57     13912315.46
#Sta/Elev= 30
    3438 1552.89  3612.1 1544.67  3687.5 1535.39  3808.4 1529.26  3876.6 1515.44
  4004.7 1511.36  4031.8 1502.96  4227.6 1497.27    4373 1484.07  4397.4 1475.04
  4424.8    1461  4432.5 1465.72  4437.7 1465.82  4528.2 1463.05  4879.8 1464.32
  4931.5 1462.95    4981 1454.16  4981.5 1453.66  4991.7 1454.16  5001.3 1464.66
  5006.4 1464.66  5013.9 1470.25  5043.9 1475.43  5213.9 1481.12  5362.7 1489.18
  5373.9 1487.98  5393.9 1491.22    5514    1499    5564 1503.37  5570.4 1505.98
#Mann= 5 ,-1 , 0
    3438     .07       0  4227.6     .12       0    4981     .05       0
  4991.7     .12       0  5362.7     .07       0
Bank Sta=4981,4991.7
XS Rating Curve= 0 ,0
Exp/Cntr=0.3,0.1

Type RM Length L Ch R = 1 ,91596   ,238,238,238
BEGIN DESCRIPTION:
CURRY CREEK 151.0
END DESCRIPTION:
XS GIS Cut Line= 3
      2088026.29     13912606.64      2087058.26     13912141.69
      2085712.11     13912121.42
#Sta/Elev= 30
  3926.1 1553.36  4146.6 1545.26  4204.9 1537.69  4349.1 1530.34  4393.5 1525.39
  4423.8 1518.33  4548.8 1507.09  4715.2 1497.01  4791.7 1494.92  4833.3 1489.92
    4916 1484.98  4953.7 1456.55  4955.7 1452.99  4978.4 1449.05  4978.9 1448.55
  4989.3 1449.05  5004.1 1449.32  5023.3 1455.68  5043.3 1458.72  5203.3 1462.13
  5264.7 1465.44  5643.3 1471.23  5777.3 1480.06  5902.8 1485.57  5944.3 1487.34
  5983.4 1488.33  6073.4 1498.41  6263.4 1511.94  6303.4 1523.78  6346.3 1527.06
#Mann= 7 ,-1 , 0
  3926.1     .07       0  4833.3     .12       0  4978.4     .05       0
  4989.3     .12       0  5264.7     .07       0  5902.8     .12       0
  5944.3     .07       0
Bank Sta=4978.4,4989.3
XS Rating Curve= 0 ,0
Exp/Cntr=0.3,0.1

Type RM Length L Ch R = 1 ,91358   ,485,485,485
BEGIN DESCRIPTION:
CURRY CREEK 150.0
END DESCRIPTION:
XS GIS Cut Line= 3
      2087363.95     13912051.53        2087025.       13911925.
      2086091.42     13911817.94
#Sta/Elev= 30
  4637.8  1493.8  4672.4 1491.62  4690.1 1488.58    4758 1487.07    4777 1484.79
  4796.8 1484.02  4813.3 1479.79  4860.8 1475.45  4898.9 1462.34  4946.2 1456.31
  4954.1 1450.94  4959.5 1451.46  4984.3 1444.01  4984.8 1443.51  4995.2 1444.01
  4996.9 1446.11  5002.1 1446.11  5009.7 1451.98  5054.3 1454.98  5128.3 1462.45
  5160.6 1464.39    5242 1464.17  5307.8 1463.85  5475.3 1465.29  5553.2 1468.14
  5583.4 1474.19  5626.7 1478.33  5714.3  1482.9  5784.7 1483.29  5939.3 1489.04
#Mann= 9 ,-1 , 0
  4637.8     .07       0    4777     .12       0  4984.3     .05       0
  4995.2     .12       0  5054.3    .035       0    5242     .07       0
  5307.8    .035       0  5475.3     .12       0  5626.7     .07       0
Bank Sta=4984.3,4995.2
XS Rating Curve= 0 ,0
Exp/Cntr=0.3,0.1

Type RM Length L Ch R = 1 ,90873   ,424,424,424
BEGIN DESCRIPTION:
CURRY CREEK 149.0
END DESCRIPTION:
XS GIS Cut Line= 3
      2087375.03     13911675.02        2087025.       13911475.
      2086739.52     13911468.22
#Sta/Elev= 30
  4596.2 1485.04  4625.7 1481.56  4631.5 1481.53  4647.3 1478.76  4653.8 1476.05
  4668.9 1474.21  4684.8 1467.54  4690.5  1466.4  4699.9 1463.15  4706.4 1458.79
  4712.1  1456.2    4728 1452.92    4787 1453.72    4846 1452.14  4895.7 1452.59
  4926.6 1450.88  4941.8  1451.1  4964.1 1449.62  4996.5 1443.99  5001.8 1443.99
  5023.9 1439.62  5024.4 1439.12  5034.4 1439.12  5034.9 1439.62  5039.4 1445.33
  5079.4 1458.57  5157.6  1458.1  5229.4 1459.31  5249.4 1461.11  5284.9  1465.9
#Mann= 5 ,-1 , 0
  4596.2     .12       0  4926.6     .07       0  5023.9     .05       0
  5034.9     .07       0  5157.6     .12       0
Bank Sta=5023.9,5034.9
XS Rating Curve= 0 ,0
Exp/Cntr=0.3,0.1

Type RM Length L Ch R = 1 ,90449   ,449,449,449
BEGIN DESCRIPTION:
CURRY CREEK 148.0
END DESCRIPTION:
XS GIS Cut Line= 3
       2087825.8      13911721.7        2087375.       13911275.
      2086289.79     13910343.04
#Sta/Elev= 30
  4370.2 1490.09  4428.7 1487.79  4578.7  1487.4  4715.4 1483.84  4842.2 1474.88
  4891.7 1461.19    4920 1444.71  4962.4 1444.89  4985.2 1436.68  4985.7 1436.18
  4996.2 1436.68  5018.6 1449.71  5260.7 1454.14  5295.1 1448.22  5323.6  1437.5
  5390.6  1450.6  5616.9 1455.86    5640 1457.01  5732.9 1457.45  5813.1 1458.83
  5919.5 1472.18  6067.6 1471.75  6127.3 1474.21  6175.2  1478.2  6210.3 1486.87
  6224.6 1482.85    6274 1491.38  6316.8 1491.87  6394.7 1526.58  6435.3 1538.33
#Mann= 13 ,-1 , 0
  4370.2     .07       0  4428.7    .035       0  4578.7     .07       0
  4715.4     .12       0  4985.2     .05       0  4996.2     .12       0
  5260.7     .12       0  5390.6     .07       0  5616.9    .035       0
    5640     .07       0  5732.9    .035       0  6067.6     .07       0
  6127.3     .12       0
#XS Ineff= 2 , 0
       0                 5235.36       0  1456.1
Permanent Ineff=
       F       F
Bank Sta=4985.2,4996.2
XS Rating Curve= 0 ,0
Exp/Cntr=0.3,0.1

Type RM Length L Ch R = 1 ,90000   ,464,464,464
BEGIN DESCRIPTION:
CURRY CREEK 147.0
END DESCRIPTION:
XS GIS Cut Line= 3
      2088266.76     13911336.26        2087475.       13910925.
      2086700.04     13910650.02
#Sta/Elev= 30
  4101.9 1503.38  4198.4 1498.89  4355.8 1493.73  4438.6 1487.77  4659.8 1481.71
  4748.2 1475.13  4825.1 1465.96  4869.6 1448.41  4875.3 1449.52  4881.4 1444.42
  4897.4 1443.57    4904 1446.28  4919.5 1445.38    4936 1450.24    4949 1449.71
  4971.6 1440.99  5004.2 1435.91  5110.8 1446.11  5188.4 1441.89  5206.3 1438.03
  5209.4 1434.58  5209.9 1434.08  5220.7 1434.58    5270 1446.07    5282 1451.32
  5290.7 1451.75  5479.7 1454.24  5715.6 1458.32  5767.7 1467.65  5816.4 1471.49
#Mann= 8 ,-1 , 0
  4101.9    .035       0  4198.4     .07       0  5188.4     .12       0
  5209.4     .05       0  5220.7     .12       0  5290.7     .07       0
  5479.7    .035       0  5767.7     .07       0
Bank Sta=5209.4,5220.7
XS Rating Curve= 0 ,0
Exp/Cntr=0.3,0.1

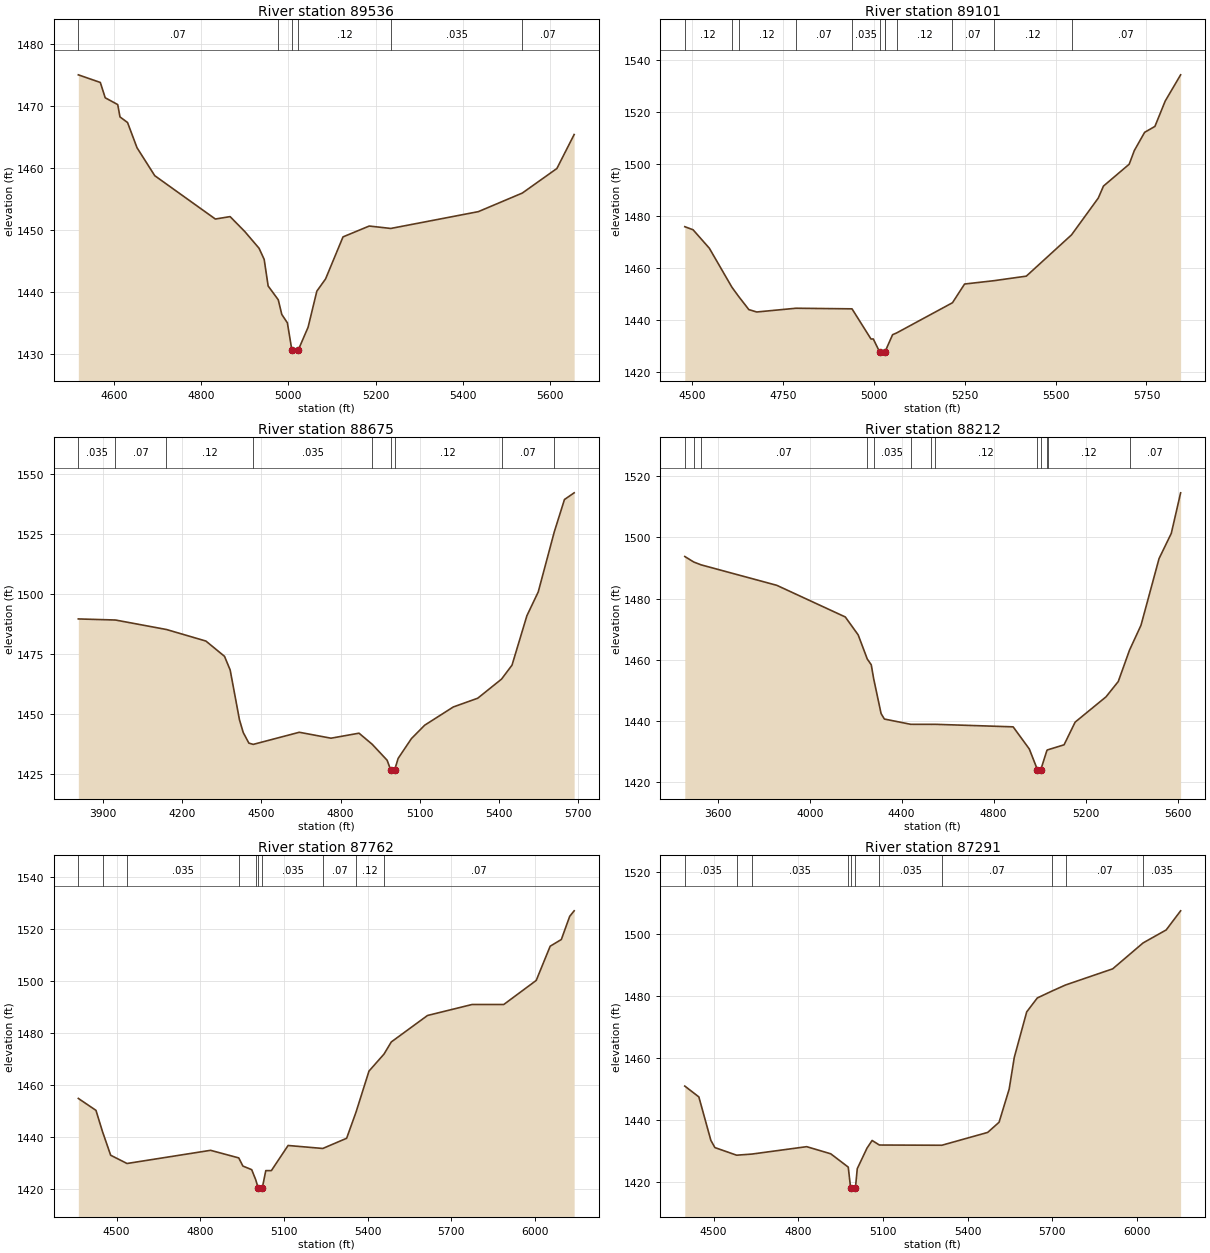
Type RM Length L Ch R = 1 ,89536   ,435,435,435
BEGIN DESCRIPTION:
CURRY CREEK 146.0
END DESCRIPTION:
XS GIS Cut Line= 3
      2087933.44     13910655.71        2087475.       13910525.
      2086815.39     13910509.88
#Sta/Elev= 30
  4518.8 1475.01  4569.2 1473.78  4580.4 1471.31  4609.1 1470.21  4614.3 1468.22
  4631.6 1467.32  4653.3 1463.25    4694 1458.74  4832.9 1451.75  4866.7 1452.14
  4900.5 1449.72  4933.1 1447.03  4944.8 1445.24  4953.9 1440.95  4977.1 1438.72
  4985.1 1436.37    4998    1435  5008.2 1430.62  5008.7 1430.12  5022.9 1430.62
  5045.5 1434.31  5065.5 1440.12  5085.5 1442.09  5125.5 1448.87  5185.6 1450.62
    5235 1450.23  5435.6 1452.94  5536.5 1455.94  5615.7  1459.9  5655.3 1465.38
#Mann= 6 ,-1 , 0
  4518.8     .07       0  4977.1     .12       0  5008.2     .05       0
  5022.9     .12       0    5235    .035       0  5536.5     .07       0
Bank Sta=5008.2,5022.9
XS Rating Curve= 0 ,0
Exp/Cntr=0.3,0.1

Type RM Length L Ch R = 1 ,89101   ,426,426,426
BEGIN DESCRIPTION:
CURRY CREEK 145.0
END DESCRIPTION:
XS GIS Cut Line= 3
      2088024.97     13910374.99        2087575.       13910125.
      2086974.99     13909524.99
#Sta/Elev= 30
  4480.7 1475.77  4503.5 1474.58  4548.2 1467.48  4610.1 1452.52  4628.4    1449
  4656.8 1443.87  4678.6 1442.95  4786.3 1444.39  4940.5 1444.16  4992.6 1432.56
    4999 1432.56  5016.3 1427.62  5016.8 1427.12  5031.2 1427.62  5031.4 1427.67
    5052 1434.21  5063.6 1434.92  5216.7 1446.51    5250 1453.71  5330.7 1454.99
  5419.7 1456.74  5544.1 1472.63  5617.7 1486.81  5631.8 1491.39  5702.6 1499.81
  5716.7 1505.07    5745 1512.07  5773.3 1514.35  5801.6 1524.11    5844  1534.2
#Mann= 12 ,-1 , 0
  4480.7     .12       0  4610.1     .07       0  4628.4     .12       0
  4786.3     .07       0  4940.5    .035       0  5016.3    .035       0
  5031.2    .035       0  5031.4     .07       0  5063.6     .12       0
  5216.7     .07       0  5330.7     .12       0  5544.1     .07       0
Bank Sta=5016.3,5031.2
XS Rating Curve= 0 ,0
Exp/Cntr=0.3,0.1

Type RM Length L Ch R = 1 ,88675   ,463,463,463
BEGIN DESCRIPTION:
CURRY CREEK 144.0
END DESCRIPTION:
XS GIS Cut Line= 3
      2088495.92     13910596.67        2087675.       13909725.
      2087125.04     13909325.03
#Sta/Elev= 30
  3807.3 1489.63  3947.9 1489.18    4141 1485.23  4290.4 1480.42  4360.8 1474.06
  4382.2 1468.38  4417.4 1447.67  4431.6 1442.36    4453 1437.93  4469.4 1437.39
    4644 1442.44  4764.1 1439.97  4870.1 1442.06  4920.2 1437.42  4976.6 1430.78
  4990.1 1426.76  4990.6 1426.26    5005 1426.76  5018.2 1431.55  5068.4 1439.79
  5118.7 1445.38  5227.2 1452.98  5319.6 1456.62  5409.8 1464.58  5449.4 1470.39
  5505.8 1490.98  5548.7 1500.88  5609.5  1525.9    5648 1539.36  5684.7 1542.14
#Mann= 9 ,-1 , 0
  3807.3    .035       0  3947.9     .07       0    4141     .12       0
  4469.4    .035       0  4920.2     .12       0  4990.1     .05       0
    5005     .12       0  5409.8     .07       0  5609.5     .12       0
Bank Sta=4990.1,5005
XS Rating Curve= 0 ,0
Exp/Cntr=0.3,0.1

Type RM Length L Ch R = 1 ,88212   ,450,450,450
BEGIN DESCRIPTION:
CURRY CREEK 143.0
END DESCRIPTION:
XS GIS Cut Line= 3
       2089041.1     13910343.24        2087875.       13909325.
      2087274.97       13909225.
#Sta/Elev= 30
  3456.8 1493.71    3496  1491.9    3528 1490.98  3856.8 1484.31  4154.8 1473.98
  4210.8 1468.14  4250.5 1460.25  4267.8 1458.36  4278.2 1453.83  4310.5 1442.45
  4324.8 1440.67  4439.1 1438.95  4528.1 1438.94  4545.4 1438.95  4884.8 1438.12
  4955.1  1430.9  4990.3 1424.17  4990.8 1423.67  5005.2 1424.17  5031.8 1430.45
  5034.4  1430.6  5106.3 1432.26  5154.4 1439.66  5288.8 1447.92    5342 1452.91
    5391 1463.17  5440.8 1471.26  5519.4 1493.03  5572.6 1501.26  5613.2 1514.49
#Mann= 13 ,-1 , 0
  3456.8     .07       0    3496    .035       0    3528     .07       0
  4250.5     .12       0  4278.2    .035       0  4439.1     .12       0
  4528.1    .035       0  4545.4     .12       0  4990.3     .05       0
  5005.2     .12       0  5031.8    .035       0  5034.4     .12       0
    5391     .07       0
Bank Sta=4990.3,5005.2
XS Rating Curve= 0 ,0
Exp/Cntr=0.3,0.1

Type RM Length L Ch R = 1 ,87762   ,471,471,471
BEGIN DESCRIPTION:
CURRY CREEK 142.0
END DESCRIPTION:
XS GIS Cut Line= 3
      2088625.04     13909125.01        2088025.       13908925.
      2086878.96     13908905.73
#Sta/Elev= 30
  4362.5 1454.79  4425.8  1450.2  4449.2 1442.03  4478.5 1432.94  4537.2 1429.76
  4836.9 1434.83    4938 1431.91  4952.8 1428.78  4984.5 1427.38    4999 1423.47
  5007.6  1420.4  5008.1  1419.9  5022.5  1420.4    5035 1427.02    5055 1427.02
    5115 1436.69  5239.4 1435.54    5325 1439.46  5358.9 1449.59  5405.1 1465.29
  5459.1 1471.86  5485.1 1476.51  5615.1  1486.7  5775.1 1490.93  5888.6 1490.92
  6005.1 1500.18  6055.2 1513.35  6095.2 1515.93  6125.2 1524.84  6141.2 1526.96
#Mann= 10 ,-1 , 0
  4362.5    .035       0  4449.2     .12       0  4537.2    .035       0
    4938     .07       0    4999    .035       0  5007.6    .035       0
  5022.5    .035       0  5239.4     .07       0  5358.9     .12       0
  5459.1     .07       0
Bank Sta=5007.6,5022.5
XS Rating Curve= 0 ,0
Exp/Cntr=0.3,0.1

Type RM Length L Ch R = 1 ,87291   ,444,444,444
BEGIN DESCRIPTION:
CURRY CREEK 141.0
END DESCRIPTION:
XS GIS Cut Line= 3
      2088675.01     13908925.01        2088225.       13908525.
      2087163.85     13908069.44
#Sta/Elev= 30
  4397.9 1450.83  4447.7 1447.34  4490.3 1433.31  4504.5 1430.99  4581.5 1428.53
  4635.4 1428.89  4829.8 1431.28  4915.1 1428.98  4977.1 1424.68  4985.3 1418.08
  4985.8 1417.58  5000.4 1418.08  5002.7 1418.11    5009 1424.17  5043.5 1430.81
  5061.6 1433.28  5087.5 1431.81  5308.8 1431.74  5471.2 1435.88  5511.5 1439.16
  5547.3 1449.86  5565.4 1460.09  5609.4 1474.77    5647 1479.27  5698.4 1481.47
  5746.9 1483.45  5914.1 1488.66  6021.9 1497.03  6103.6 1501.21  6154.8 1507.38
#Mann= 11 ,-1 , 0
  4397.9    .035       0  4581.5     .07       0  4635.4    .035       0
  4977.1     .07       0  4985.3     .05       0  5000.4     .07       0
  5087.5    .035       0  5308.8     .07       0  5698.4     .12       0
  5746.9     .07       0  6021.9    .035       0
Bank Sta=4985.3,5000.4
XS Rating Curve= 0 ,0
Exp/Cntr=0.3,0.1

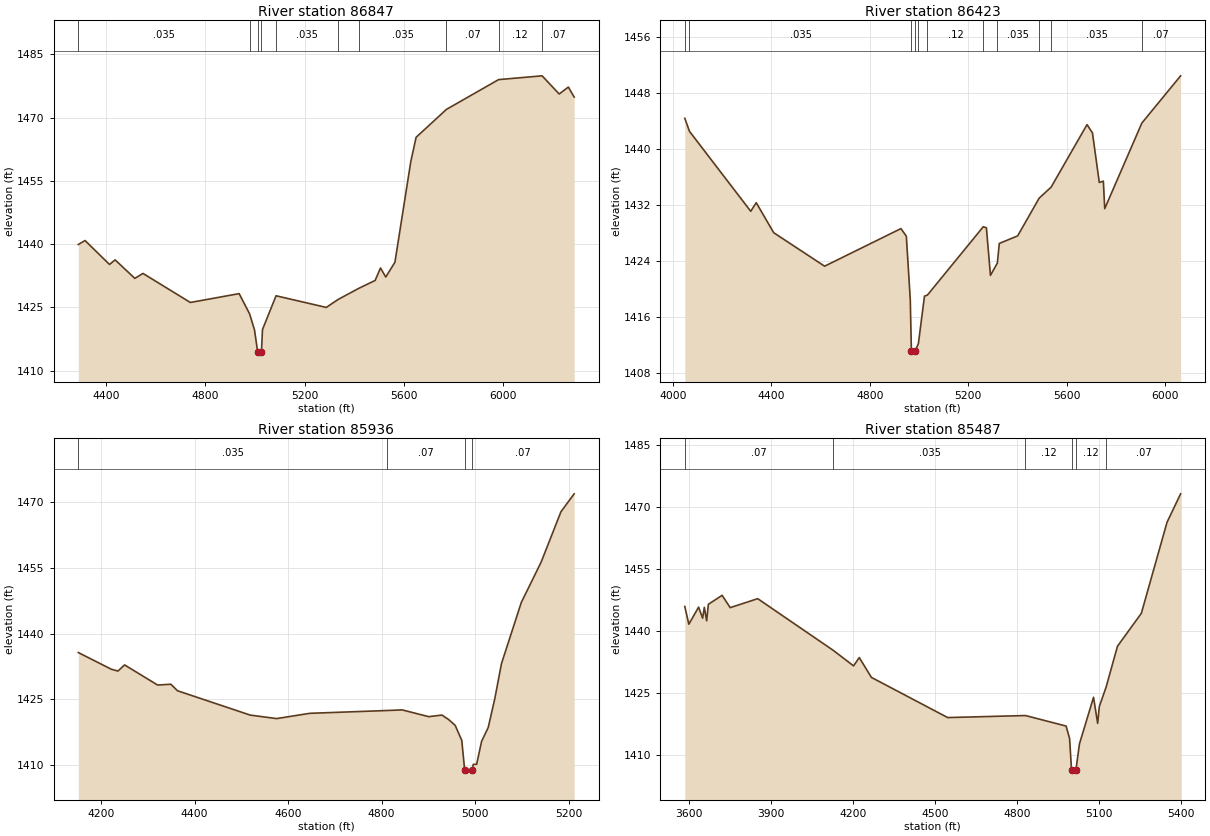
Type RM Length L Ch R = 1 ,86847   ,424,424,424
BEGIN DESCRIPTION:
CURRY CREEK 140.0
END DESCRIPTION:
XS GIS Cut Line= 3
      2089109.33     13908487.17        2088475.       13908175.
      2087369.75     13907508.01
#Sta/Elev= 30
  4288.6 1439.94  4315.7 1440.87  4414.3  1435.2  4436.7 1436.29  4516.3  1431.9
  4549.1 1433.07    4740 1426.18  4936.6 1428.28  4978.6  1423.5  4998.5 1419.67
  5011.3 1414.43  5011.8 1413.93  5026.4 1414.43  5030.6 1419.75  5085.3 1427.77
  5287.6 1425.01  5336.7 1426.94  5419.6 1429.56  5484.7 1431.41  5506.1 1434.36
  5527.4 1432.22  5564.3 1435.72  5628.4 1459.65  5649.7 1465.36  5771.9 1471.98
    5982 1479.04  6157.4 1479.94  6226.2 1475.63  6263.1 1477.27  6286.5  1474.9
#Mann= 10 ,-1 , 0
  4288.6    .035       0  4978.6     .07       0  5011.3     .05       0
  5026.4     .07       0  5085.3    .035       0  5336.7     .07       0
  5419.6    .035       0  5771.9     .07       0    5982     .12       0
  6157.4     .07       0
Bank Sta=5011.3,5026.4
XS Rating Curve= 0 ,0
Exp/Cntr=0.3,0.1

Type RM Length L Ch R = 1 ,86423   ,487,487,487
BEGIN DESCRIPTION:
CURRY CREEK 139.0
END DESCRIPTION:
XS GIS Cut Line= 3
      2089410.29     13908241.71      2088579.26     13907787.65
      2087630.81     13907295.55
#Sta/Elev= 30
  4048.2 1444.42  4067.3 1442.56  4316.3 1431.14  4338.6 1432.37  4409.7 1428.08
  4616.6  1423.3  4926.8 1428.67  4948.7 1427.59  4964.8  1418.5  4969.3 1411.24
  4969.8 1410.74  4985.2 1411.24  4997.7 1412.24  5022.5 1419.02  5034.6 1419.18
  5261.6 1428.94  5274.2 1428.78  5290.7 1421.99  5318.7 1423.74  5326.7 1426.55
  5401.3 1427.63  5488.7 1433.02  5537.3 1434.59  5683.2 1443.52  5705.4 1442.33
  5733.1 1435.26  5749.6 1435.45  5755.2 1431.52  5906.2 1443.75  6063.7 1450.49
#Mann= 11 ,-1 , 0
  4048.2     .07       0  4067.3    .035       0  4969.3     .05       0
  4985.2    .035       0  4997.7     .07       0  5034.6     .12       0
  5261.6     .07       0  5318.7    .035       0  5488.7     .12       0
  5537.3    .035       0  5906.2     .07       0
Bank Sta=4969.3,4985.2
XS Rating Curve= 0 ,0
Exp/Cntr=0.3,0.1

Type RM Length L Ch R = 1 ,85936   ,449,449,449
BEGIN DESCRIPTION:
CURRY CREEK 138.0
END DESCRIPTION:
XS GIS Cut Line= 3
      2089374.97     13907974.97        2088775.       13907375.
      2088625.01     13907225.01
#Sta/Elev= 30
  4151.3 1435.69    4222 1431.88  4236.1 1431.47  4250.2 1432.87    4321 1428.28
  4349.2 1428.47  4363.4 1426.98  4518.9 1421.43  4575.5 1420.63  4646.2 1421.83
    4811 1422.47  4844.2 1422.61  4900.8 1421.07  4929.1 1421.43  4943.2 1420.43
  4957.4 1419.09  4971.5 1415.66  4977.7 1408.92  4978.2 1408.42  4993.6 1408.92
  4996.2  1410.2  5003.3  1410.2  5013.9 1415.44  5028.1 1418.61  5042.2 1425.19
  5056.4 1433.16  5098.8  1447.1  5141.2  1456.3  5183.6 1467.79  5211.9 1471.89
#Mann= 4 ,-1 , 0
  4151.3    .035       0    4811     .07       0  4977.7     .05       0
  4993.6     .07       0
Bank Sta=4977.7,4993.6
XS Rating Curve= 0 ,0
Exp/Cntr=0.3,0.1

Type RM Length L Ch R = 1 ,85487   ,950,950,950
BEGIN DESCRIPTION:
CURRY CREEK 137.0
END DESCRIPTION:
XS GIS Cut Line= 3
      2089909.14     13908211.29      2089216.65     13907246.87
      2088875.02     13906725.03
#Sta/Elev= 30
  3586.2 1445.93    3601 1441.65  3636.6 1445.78  3651.3  1443.1  3657.5 1445.73
  3666.1 1442.47  3672.2 1446.45  3722.5 1448.63    3752 1445.65  3852.5 1447.82
  4129.3 1435.29  4202.6 1431.58  4223.5 1433.59  4267.7  1428.8  4546.4 1419.09
  4830.6 1419.58  4978.9 1417.04  4991.6 1414.05  4998.8 1406.41  4999.3 1405.91
  5014.7 1406.41  5027.8 1412.76  5079.1 1423.99  5094.2 1417.69  5100.2 1421.75
  5125.2 1426.49  5166.6 1436.33  5253.8 1444.29  5347.5 1466.27  5397.2 1473.15
#Mann= 6 ,-1 , 0
  3586.2     .07       0  4129.3    .035       0  4830.6     .12       0
  4998.8     .05       0  5014.7     .12       0  5125.2     .07       0
Bank Sta=4998.8,5014.7
XS Rating Curve= 0 ,0
Exp/Cntr=0.3,0.1