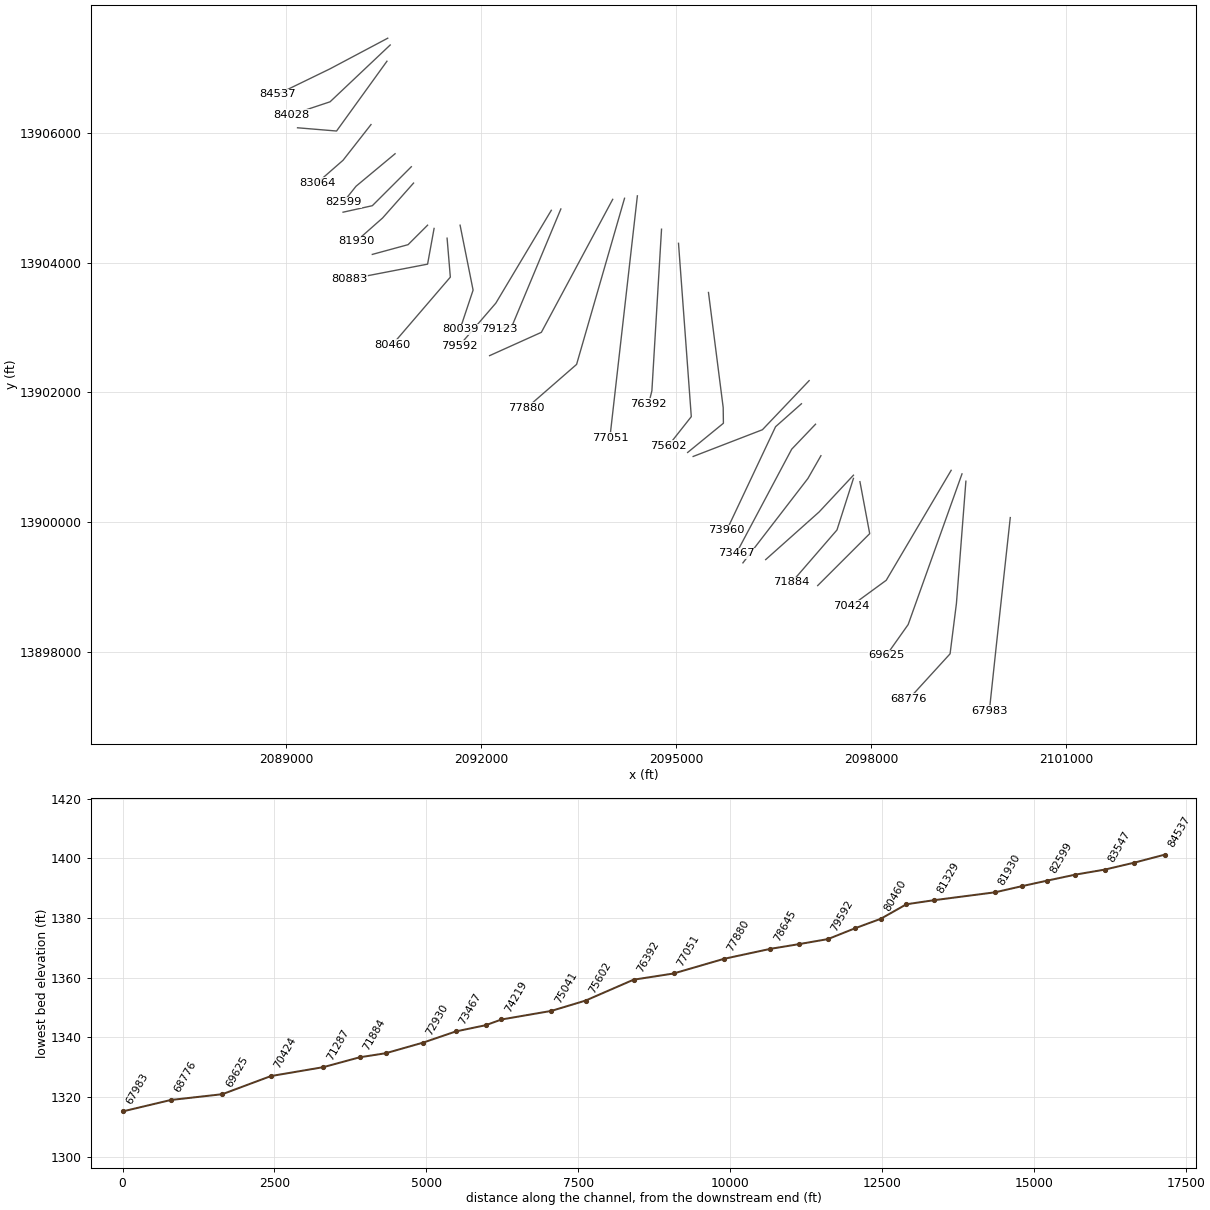
HEC-RAS study CURRY CREEK.prj: CURRY CREEK Base Level Engineering

--- CURRY CREEK.g01 (geometry) --- (continued)

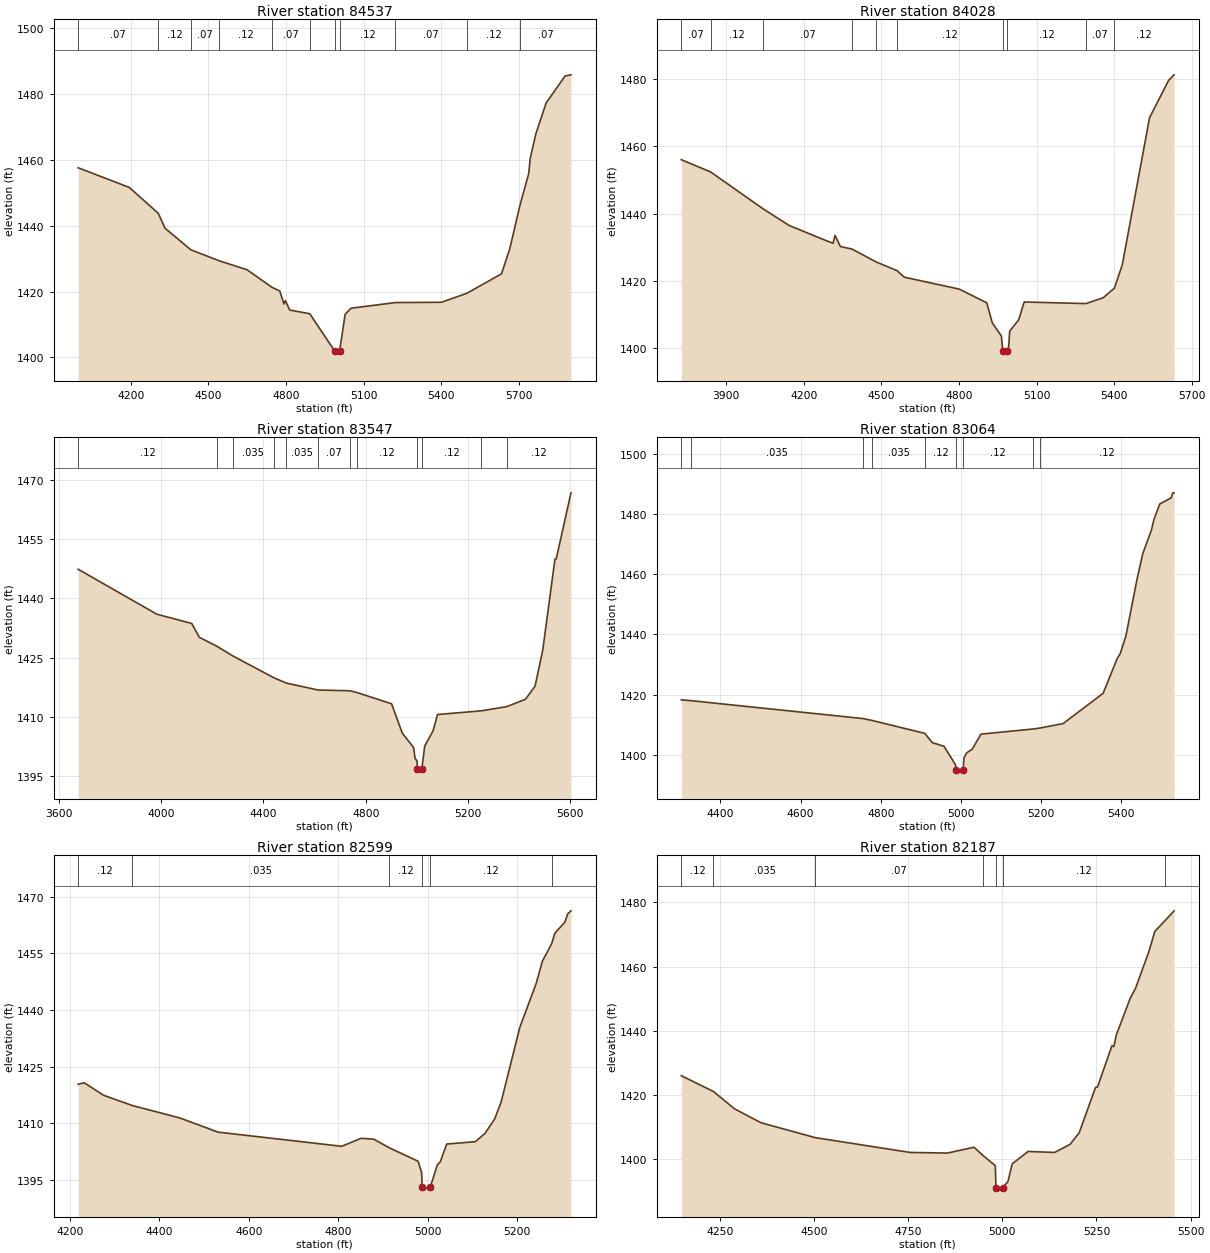
Type RM Length L Ch R = 1 ,84537   ,509,509,509
BEGIN DESCRIPTION:
CURRY CREEK 136.0
END DESCRIPTION:
XS GIS Cut Line= 3
      2090561.94     13907454.34      2089673.01      13906982.1
       2088863.4     13906588.05
#Sta/Elev= 30
  3995.8 1457.65  4193.7 1451.67  4305.9 1443.79    4332 1439.27  4431.8 1432.72
  4541.6 1429.37  4649.6 1426.64  4745.6 1421.32  4775.9  1420.2  4792.2 1416.26
  4797.8 1417.27  4814.2 1414.41    4892 1413.28  4989.7 1401.81  4990.2 1401.31
  5007.1 1401.81    5029 1413.13  5051.6 1414.95  5223.3 1416.68  5400.9 1416.76
  5499.5 1419.48  5634.1 1425.42  5665.9    1433  5705.7 1446.34  5739.1 1455.81
  5745.3 1460.57  5767.6 1468.14  5806.7 1477.34  5879.9 1485.54  5902.8  1485.9
#Mann= 11 ,-1 , 0
  3995.8     .07       0  4305.9     .12       0  4431.8     .07       0
  4541.6     .12       0  4745.6     .07       0    4892     .12       0
  4989.7     .05       0  5007.1     .12       0  5223.3     .07       0
  5499.5     .12       0  5705.7     .07       0
Bank Sta=4989.7,5007.1
XS Rating Curve= 0 ,0
Exp/Cntr=0.3,0.1

Type RM Length L Ch R = 1 ,84028   ,481,481,481
BEGIN DESCRIPTION:
CURRY CREEK 135.0
END DESCRIPTION:
XS GIS Cut Line= 3
      2090600.01     13907350.01        2089675.       13906475.
      2089074.95     13906274.98
#Sta/Elev= 30
  3726.3 1456.08  3839.5 1452.45  4041.8 1441.51  4143.8 1436.52  4292.3 1431.84
  4313.3 1431.25  4320.6 1433.58  4341.6 1430.26  4386.7 1429.52  4479.7 1425.68
    4560 1423.13  4589.2 1421.15  4801.6 1417.61  4907.6 1413.54    4929 1407.59
  4964.2 1403.68  4969.7 1399.09  4970.2 1398.59  4987.1 1399.09  4992.5 1400.61
  4996.2 1405.11  5031.2 1408.51  5052.3 1413.79  5290.9 1413.31    5358 1415.05
  5401.2  1417.9  5431.8 1424.85  5537.2 1468.57    5611 1479.67  5632.1  1481.3
#Mann= 10 ,-1 , 0
  3726.3     .07       0  3839.5     .12       0  4041.8     .07       0
  4386.7     .12       0  4479.7     .07       0    4560     .12       0
  4969.7     .05       0  4987.1     .12       0  5290.9     .07       0
  5401.2     .12       0
Bank Sta=4969.7,4987.1
XS Rating Curve= 0 ,0
Exp/Cntr=0.3,0.1

Type RM Length L Ch R = 1 ,83547   ,483,483,483
BEGIN DESCRIPTION:
CURRY CREEK 134.0
END DESCRIPTION:
XS GIS Cut Line= 3
      2090550.02     13907100.03        2089775.       13906025.
      2089174.96       13906075.
#Sta/Elev= 30
  3675.4 1447.32  3983.4 1435.95  4119.6 1433.61  4149.1 1430.13  4218.3 1427.84
  4279.6 1425.43  4441.2 1419.88  4489.7 1418.54  4613.7 1416.79  4737.7  1416.6
  4764.5 1416.18  4901.3  1413.3    4943  1405.9  4987.2 1402.26  4993.3 1399.45
  5000.7 1398.92    5002 1396.78  5002.5 1396.28  5019.4 1396.78  5030.8 1402.62
  5063.4 1406.47    5081 1410.59  5252.4 1411.53  5351.6 1412.59  5424.6 1414.44
  5462.3 1417.74  5492.4 1426.86    5540 1449.82  5545.1 1449.94  5602.8 1466.65
#Mann= 12 ,-1 , 0
  3675.4     .12       0  4218.3     .07       0  4279.6    .035       0
  4441.2     .12       0  4489.7    .035       0  4613.7     .07       0
  4737.7    .035       0  4764.5     .12       0    5002     .05       0
  5019.4     .12       0  5252.4     .07       0  5351.6     .12       0
Bank Sta=5002,5019.4
XS Rating Curve= 0 ,0
Exp/Cntr=0.3,0.1

Type RM Length L Ch R = 1 ,83064   ,465,465,465
BEGIN DESCRIPTION:
CURRY CREEK 133.0
END DESCRIPTION:
XS GIS Cut Line= 3
      2090304.96     13906124.47        2089875.       13905575.
        2089475.       13905225.
#Sta/Elev= 30
  4302.3 1418.26  4325.8 1417.99  4755.7 1412.04    4779 1411.39  4909.6 1407.13
  4928.6 1404.04  4957.5 1402.85  4986.4 1396.66    4988  1395.1  4988.5  1394.6
  5005.7  1395.1  5007.1 1398.85  5013.8 1400.64    5028 1401.89  5049.8 1406.88
  5180.1 1408.58  5197.1  1408.9  5254.8 1410.39  5354.5 1420.43  5389.6 1431.98
  5397.2 1433.59  5411.4 1439.53    5439 1458.26  5453.2  1466.7    5475 1474.63
  5481.7 1478.34  5495.9 1483.27  5524.4 1485.32  5528.2 1486.96  5531.5 1486.96
#Mann= 9 ,-1 , 0
  4302.3     .07       0  4325.8    .035       0  4755.7     .12       0
    4779    .035       0  4909.6     .12       0    4988     .05       0
  5005.7     .12       0  5180.1     .07       0  5197.1     .12       0
Bank Sta=4988,5005.7
XS Rating Curve= 0 ,0
Exp/Cntr=0.3,0.1

Type RM Length L Ch R = 1 ,82599   ,412,412,412
BEGIN DESCRIPTION:
CURRY CREEK 132.0
END DESCRIPTION:
XS GIS Cut Line= 3
      2090674.97     13905674.98        2090075.       13905175.
      2089875.03     13904925.03
#Sta/Elev= 30
  4218.8 1420.33  4232.4 1420.72  4275.4 1417.42  4339.8  1414.7  4445.9 1411.41
  4531.2 1407.66  4807.8 1403.91  4850.7 1406.02  4879.4 1405.79  4914.2  1403.5
  4978.3 1399.96  4986.1 1397.01  4987.6 1393.08  4988.1 1392.58  5005.4 1393.08
  5021.4 1399.02  5027.8 1399.78  5042.2  1404.5  5106.2 1405.13  5127.8 1407.33
  5149.5 1411.16  5163.9 1415.65  5205.5 1435.34  5242.3 1447.03  5255.9 1452.86
  5276.7 1457.49  5283.9 1460.28  5306.3 1463.23  5312.7 1465.42  5319.9 1466.21
#Mann= 6 ,-1 , 0
  4218.8     .12       0  4339.8    .035       0  4914.2     .12       0
  4987.6     .05       0  5005.4     .12       0  5276.7     .07       0
Bank Sta=4987.6,5005.4
XS Rating Curve= 0 ,0
Exp/Cntr=0.3,0.1

Type RM Length L Ch R = 1 ,82187   ,446,446,446
BEGIN DESCRIPTION:
CURRY CREEK 131.0
END DESCRIPTION:
XS GIS Cut Line= 3
      2090925.01     13905475.01        2090325.       13904875.
      2089875.02     13904775.01
#Sta/Elev= 30
  4146.8 1426.06  4232.3 1421.12  4288.2 1415.74    4359 1411.39  4503.2 1406.76
  4754.9 1402.16  4853.9 1401.97  4924.6 1403.78  4947.8 1401.28  4981.2 1398.05
  4982.9 1391.24  4983.4 1390.74  5000.7 1391.24  5014.6 1393.03  5026.1  1398.6
  5068.3 1402.47  5138.8 1402.16  5179.7 1404.67  5204.1 1408.27  5247.6 1422.43
  5252.7 1422.51  5291.1 1435.35  5296.3 1435.15  5302.7 1438.71  5339.8 1450.19
  5353.9 1453.27  5388.5 1464.42  5405.1 1470.98  5431.8 1474.27  5456.3 1477.38
#Mann= 7 ,-1 , 0
  4146.8     .12       0  4232.3    .035       0  4503.2     .07       0
  4947.8     .12       0  4982.9     .05       0  5000.7     .12       0
  5431.8     .07       0
Bank Sta=4982.9,5000.7
XS Rating Curve= 0 ,0
Exp/Cntr=0.3,0.1

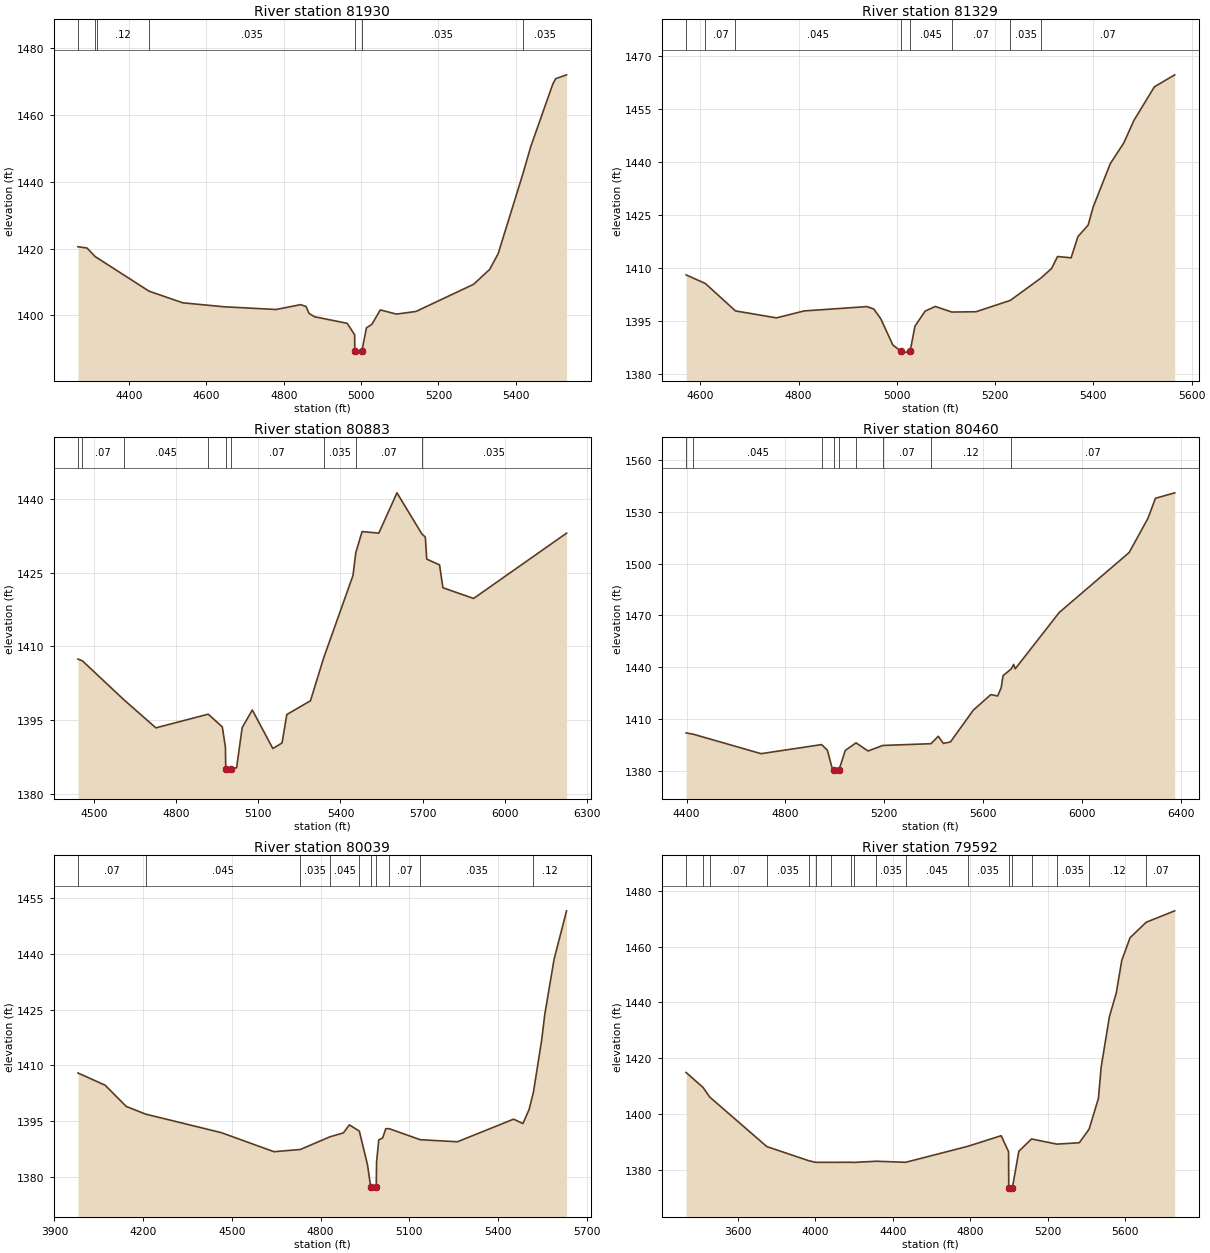
Type RM Length L Ch R = 1 ,81930   ,1013,1013,1013
BEGIN DESCRIPTION:
CURRY CREEK 130.0
END DESCRIPTION:
XS GIS Cut Line= 3
       2090959.1     13905223.48      2090483.29     13904686.12
      2090075.01     13904325.01
#Sta/Elev= 30
  4268.3 1420.54  4291.7 1420.14  4312.7 1417.59    4317 1417.27    4452 1407.22
  4539.3 1403.73  4645.5 1402.55  4780.2 1401.73  4843.7 1403.18  4857.9 1402.62
  4865.5 1400.57  4879.7 1399.56  4964.2 1397.59  4983.4 1394.13  4983.8 1389.16
  4984.3 1388.66  5001.9 1389.16  5013.8 1396.21    5028 1397.31  5049.7 1401.61
  5091.5 1400.35  5141.8 1401.14  5290.6 1409.26  5332.4 1413.74  5354.2 1418.43
  5417.7 1442.17  5438.7 1450.58  5495.6 1469.29  5503.1 1470.88  5531.1 1472.03
#Mann= 7 ,-1 , 0
  4268.3     .12       0  4312.7    .035       0    4317     .12       0
    4452    .035       0  4983.8     .05       0  5001.9    .035       0
  5417.7    .035       0
Bank Sta=4983.8,5001.9
XS Rating Curve= 0 ,0
Exp/Cntr=0.3,0.1

Type RM Length L Ch R = 1 ,81329   ,446,446,446
BEGIN DESCRIPTION:
CURRY CREEK 129.0
END DESCRIPTION:
XS GIS Cut Line= 3
      2091175.02     13904575.02        2090875.       13904275.
      2090324.98     13904124.99
#Sta/Elev= 30
  4571.1  1408.1  4610.1 1405.69  4671.6 1397.92    4755 1395.96  4811.5 1397.92
  4938.8 1399.14    4953 1398.48  4967.1 1395.76  4991.9 1388.28  5008.8 1386.49
  5009.3 1385.99    5027 1386.49  5036.9 1393.62  5057.6 1397.86  5078.3 1399.19
  5111.9  1397.6  5161.2 1397.69    5231  1400.9  5293.6 1407.24    5315 1409.93
  5327.1  1413.3  5354.7 1412.93  5368.5 1418.92  5389.3 1422.16  5399.6 1427.29
  5434.2 1439.48  5461.8 1445.38  5482.6 1451.78    5524 1461.24  5565.5 1464.65
#Mann= 8 ,-1 , 0
  4571.1    .045       0  4610.1     .07       0  4671.6    .045       0
  5008.8    .045       0    5027    .045       0  5111.9     .07       0
    5231    .035       0  5293.6     .07       0
Bank Sta=5008.8,5027
XS Rating Curve= 0 ,0
Exp/Cntr=0.3,0.1

Type RM Length L Ch R = 1 ,80883   ,423,423,423
BEGIN DESCRIPTION:
CURRY CREEK 128.0
END DESCRIPTION:
XS GIS Cut Line= 3
      2091275.01     13904525.04        2091175.       13903975.
      2089971.61     13903742.51
#Sta/Elev= 30
  4441.2 1407.43  4457.4 1407.08  4609.2 1399.15  4725.8 1393.45  4916.9 1396.23
  4968.5 1393.64  4979.9 1389.47    4981 1385.15  4981.5 1384.65  4999.2 1385.15
  5020.6 1385.32    5041  1393.5    5078 1397.08    5153 1389.25  5186.7 1390.38
    5204 1396.16  5290.4 1398.95  5338.6 1407.66  5445.8 1424.44  5456.1 1429.09
    5479 1433.36  5540.1 1433.05  5606.4 1441.24  5698.1 1432.82    5710 1432.26
  5715.1 1427.76  5761.9 1426.59  5774.3 1421.94  5886.3 1419.76  6225.9 1433.04
#Mann= 9 ,-1 , 0
  4441.2    .035       0  4457.4     .07       0  4609.2    .045       0
  4916.9     .07       0    4981     .05       0  4999.2     .07       0
  5338.6    .035       0  5456.1     .07       0  5698.1    .035       0
Bank Sta=4981,4999.2
XS Rating Curve= 0 ,0
Exp/Cntr=0.3,0.1

Type RM Length L Ch R = 1 ,80460   ,421,421,421
BEGIN DESCRIPTION:
CURRY CREEK 127.0
END DESCRIPTION:
XS GIS Cut Line= 3
        2091475.     13904375.01        2091525.       13903775.
       2090629.5     13902730.52
#Sta/Elev= 30
  4397.9  1401.9  4427.7 1401.13  4701.5 1389.88  4946.6 1395.14  4969.9 1391.88
    4990 1381.03  4997.8 1380.27  4998.3 1379.77  5016.5 1380.27  5042.2 1391.76
    5086 1396.16  5134.4 1391.42  5193.9 1394.64  5389.1 1395.66  5418.7 1399.95
  5439.6  1395.8  5468.1 1396.69  5560.3 1415.05  5631.6 1424.12  5659.1 1423.29
  5673.3 1428.03    5681 1435.05  5714.3 1439.04  5723.8 1441.59  5730.4 1439.06
  5908.2 1471.65  6191.4 1506.39  6267.5  1526.2  6297.8 1537.83  6375.8 1540.99
#Mann= 9 ,-1 , 0
  4397.9     .07       0  4427.7    .045       0  4946.6     .07       0
  4997.8     .05       0  5016.5     .07       0    5086    .035       0
  5193.9     .07       0  5389.1     .12       0  5714.3     .07       0
Bank Sta=4997.8,5016.5
XS Rating Curve= 0 ,0
Exp/Cntr=0.3,0.1

Type RM Length L Ch R = 1 ,80039   ,447,447,447
BEGIN DESCRIPTION:
CURRY CREEK 126.0
END DESCRIPTION:
XS GIS Cut Line= 3
      2091674.99     13904575.04        2091875.       13903575.
        2091675.       13902975.
#Sta/Elev= 30
  3979.7 1407.92  4071.5 1404.63  4142.9 1398.91  4208.1 1396.84  4464.2 1391.84
  4642.6  1386.7  4731.8  1387.3  4831.5 1390.71  4877.2 1391.76  4897.6 1393.93
  4931.2 1392.25  4958.8 1383.18  4969.8 1377.11  4970.3 1376.61  4988.5 1377.11
  4989.4 1383.84    4997  1389.9  5010.1 1390.39  5020.6 1392.91  5032.5  1392.9
  5137.3 1389.93  5263.1 1389.38  5452.8 1395.47  5484.4 1394.29  5505.5 1398.11
    5520 1402.78  5547.7 1416.73  5558.2 1423.64  5589.8 1438.59    5632 1451.63
#Mann= 10 ,-1 , 0
  3979.7     .07       0  4208.1    .045       0  4731.8    .035       0
  4831.5    .045       0  4931.2    .035       0  4969.8    .035       0
  4988.5    .035       0  5032.5     .07       0  5137.3    .035       0
    5520     .12       0
Bank Sta=4969.8,4988.5
XS Rating Curve= 0 ,0
Exp/Cntr=0.3,0.1

Type RM Length L Ch R = 1 ,79592   ,469,469,469
BEGIN DESCRIPTION:
CURRY CREEK 125.0
END DESCRIPTION:
XS GIS Cut Line= 3
      2093077.84     13904804.21        2092225.       13903375.
      2091662.89     13902720.86
#Sta/Elev= 30
  3330.9 1414.85  3418.9 1409.45  3452.8 1406.04  3748.5 1388.24  3965.1 1383.18
  4001.2 1382.59  4081.8 1382.59  4184.1 1382.62  4198.5 1382.56  4315.2 1382.99
  4466.2  1382.6  4787.1 1388.33  4960.2 1392.15  4998.5 1386.44  4999.6 1373.47
  5000.1 1372.97  5018.3 1373.47  5051.7 1386.56  5117.2 1390.98  5248.2 1389.13
  5364.4 1389.62  5415.2 1394.52  5463.2 1405.51  5477.5 1416.82  5520.3 1434.97
  5555.4 1443.33    5584 1455.09  5626.7 1463.21  5710.1 1468.78  5857.7 1472.88
#Mann= 18 ,-1 , 0
  3330.9     .07       0  3418.9     .12       0  3452.8     .07       0
  3748.5    .035       0  3965.1     .07       0  4001.2    .035       0
  4081.8     .07       0  4184.1    .035       0  4198.5     .07       0
  4315.2    .035       0  4466.2    .045       0  4787.1    .035       0
  4999.6    .035       0  5018.3    .035       0  5117.2     .07       0
  5248.2    .035       0  5415.2     .12       0  5710.1     .07       0
Bank Sta=4999.6,5018.3
XS Rating Curve= 0 ,0
Exp/Cntr=0.3,0.1

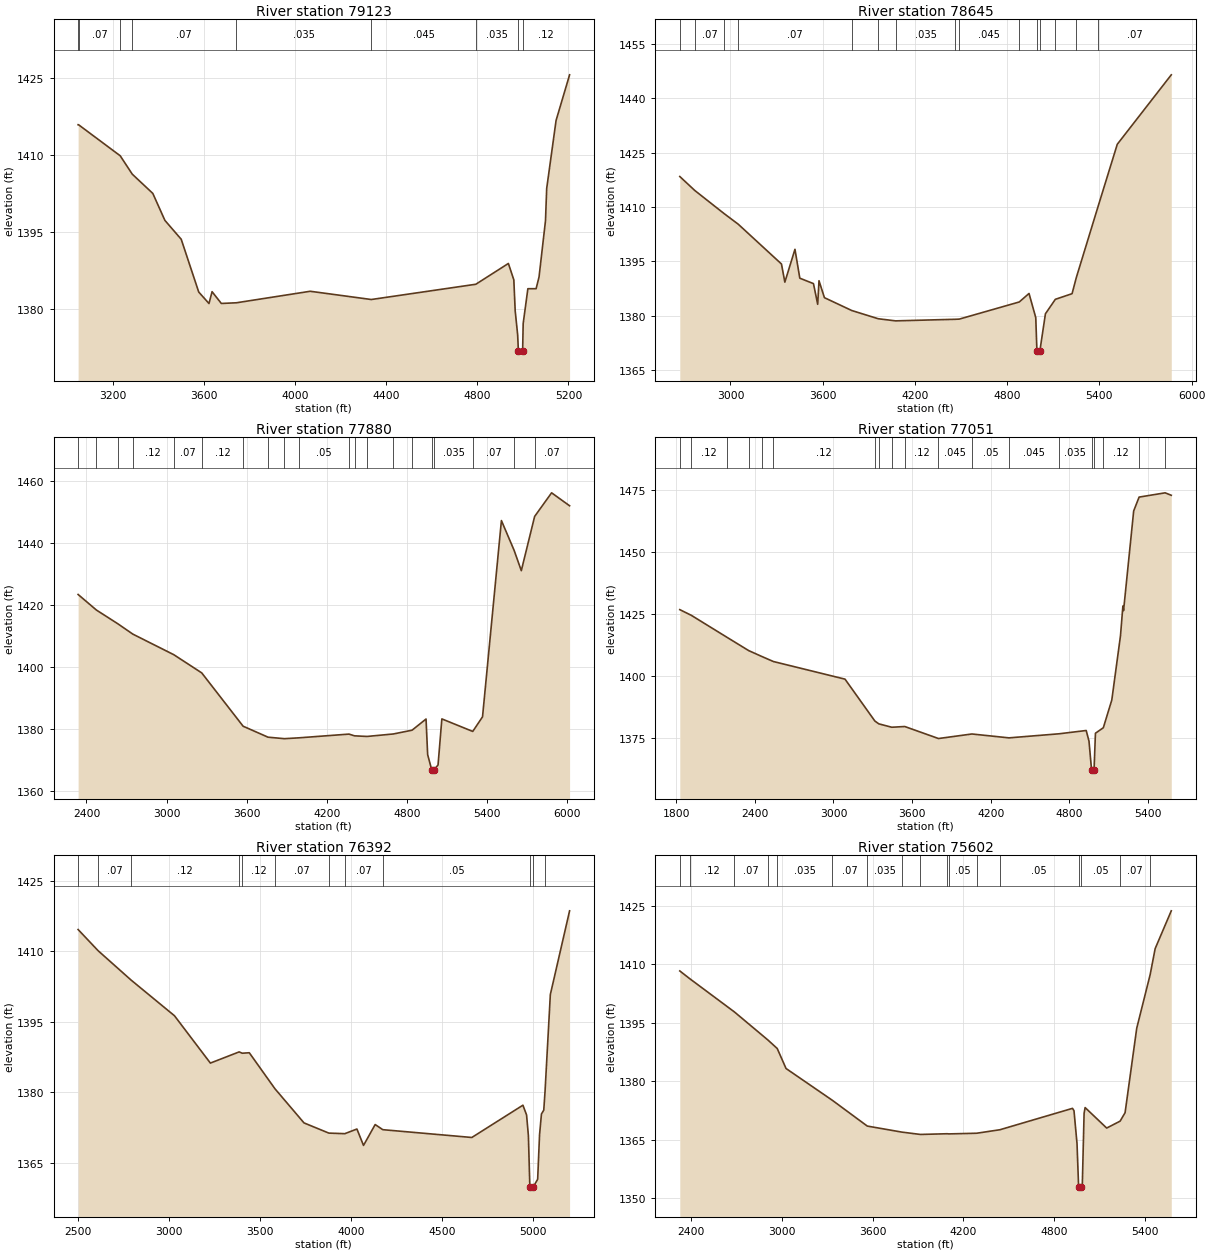
Type RM Length L Ch R = 1 ,79123   ,478,478,478
BEGIN DESCRIPTION:
CURRY CREEK 124.0
END DESCRIPTION:
XS GIS Cut Line= 3
        2093225.     13904825.01        2092475.       13903025.
      2092274.97     13902974.99
#Sta/Elev= 30
  3048.6 1415.91  3050.3 1415.91  3233.3 1409.84  3286.2 1406.25  3376.3 1402.49
  3429.4 1397.22  3500.9 1393.54  3577.8 1383.23  3622.8 1380.99  3636.3  1383.3
  3676.9    1381  3742.7 1381.13  4066.9 1383.38  4334.8 1381.77  4793.4 1384.75
  4936.3 1388.81  4960.2  1385.6  4966.1 1379.57  4976.9 1374.92  4980.1  1371.8
  4980.6  1371.3  4998.8  1371.8  5001.2 1377.09  5021.8 1383.88  5057.9 1383.88
  5070.8 1386.18  5099.1 1397.17  5104.3 1403.44  5145.5 1416.74  5204.8 1425.65
#Mann= 9 ,-1 , 0
  3048.6     .12       0  3050.3     .07       0  3233.3     .12       0
  3286.2     .07       0  3742.7    .035       0  4334.8    .045       0
  4793.4    .035       0  4980.1     .05       0  4998.8     .12       0
Bank Sta=4980.1,4998.8
XS Rating Curve= 0 ,0
Exp/Cntr=0.3,0.1

Type RM Length L Ch R = 1 ,78645   ,765,765,765
BEGIN DESCRIPTION:
CURRY CREEK 123.0
END DESCRIPTION:
XS GIS Cut Line= 3
      2094022.31     13904973.05        2092925.       13902925.
      2092128.93     13902565.91
#Sta/Elev= 30
  2670.6 1418.42  2767.8 1414.58  2958.6  1408.2  3051.1 1405.25    3332 1394.28
  3353.9 1389.28  3419.7 1398.34  3451.2 1390.37    3540 1388.87  3567.6 1383.16
    3576 1389.67  3611.4 1384.99    3789 1381.45    3961 1379.18  4073.9 1378.59
  4463.8 1379.03  4488.9 1379.08  4878.5  1383.8  4942.1 1386.15    4986 1379.49
  4993.6 1370.19  4994.1 1369.69  5012.3 1370.19  5048.9 1380.55  5113.4 1384.54
  5222.1 1386.09  5249.8 1390.55  5393.7 1410.49  5516.1 1427.31  5867.4 1446.48
#Mann= 15 ,-1 , 0
  2670.6     .12       0  2767.8     .07       0  2958.6    .035       0
  3051.1     .07       0    3789    .035       0    3961     .07       0
  4073.9    .035       0  4463.8     .05       0  4488.9    .045       0
  4878.5    .035       0  4993.6    .035       0  5012.3    .035       0
  5113.4     .07       0  5249.8    .035       0  5393.7     .07       0
Bank Sta=4993.6,5012.3
XS Rating Curve= 0 ,0
Exp/Cntr=0.3,0.1

Type RM Length L Ch R = 1 ,77880   ,829,829,829
BEGIN DESCRIPTION:
Curry Creek 122.1
END DESCRIPTION:
XS GIS Cut Line= 3
      2094204.29     13904989.47      2093466.82     13902431.04
      2092698.73     13901761.11
#Sta/Elev= 30
  2337.4  1423.4  2473.8 1418.39  2633.7 1413.97  2747.1  1410.6  3054.4 1403.94
  3263.5 1398.07  3573.4 1380.85  3760.3  1377.3  3883.2 1376.82  3993.3  1377.1
  4366.7  1378.3  4408.1 1377.74  4501.1 1377.54  4698.8 1378.34  4839.1 1379.56
  4943.8 1383.17  4955.9 1371.67  4985.8 1366.84  4986.3 1366.34  5004.8 1366.84
  5033.8 1368.33  5062.3 1383.21  5293.7 1379.16    5367 1383.88  5508.5 1447.27
  5603.9 1437.63  5657.5 1431.09  5757.4 1448.61  5884.4 1456.23  6019.2 1452.05
#Mann= 20 ,-1 , 0
  2337.4     .12       0  2473.8     .07       0  2633.7     .12       0
  2747.1     .12       0  3054.4     .07       0  3263.5     .12       0
  3573.4     .07       0  3760.3    .035       0  3883.2     .07       0
  3993.3     .05       0  4366.7    .045       0  4408.1     .05       0
  4501.1    .045       0  4698.8    .045       0  4839.1    .035       0
  4985.8    .035       0  5004.8    .035       0  5293.7     .07       0
  5603.9    .035       0  5757.4     .07       0
Bank Sta=4985.8,5004.8
XS Rating Curve= 0 ,0
Exp/Cntr=0.3,0.1

Type RM Length L Ch R = 1 ,77051   ,659,659,659
BEGIN DESCRIPTION:
Curry Creek 122.0
END DESCRIPTION:
XS GIS Cut Line= 2
      2094401.78     13905026.74      2093978.71     13901299.98
#Sta/Elev= 30
  1827.4 1426.77    1915 1424.48  2188.3 1415.55  2352.3 1410.22  2451.7 1407.85
  2541.8 1405.77  3088.3 1398.64    3316  1381.7  3345.7 1380.56  3445.1 1379.18
  3544.4 1379.47  3801.6 1374.61  4056.8 1376.45  4339.5 1374.88  4720.2 1376.52
  4928.9 1377.86  4950.1 1373.58  4969.8 1361.92  4970.3 1361.42  4988.8 1361.92
  4999.4 1376.76  5059.6 1378.98  5124.3 1390.22  5190.6 1416.25  5208.9 1428.24
  5213.9 1426.37  5291.2 1466.71  5332.6 1472.31  5531.3 1474.04  5578.1 1473.05
#Mann= 19 ,-1 , 0
  1827.4     .07       0    1915     .12       0  2188.3     .07       0
  2352.3     .12       0  2451.7     .07       0  2541.8     .12       0
    3316    .035       0  3345.7     .07       0  3445.1    .035       0
  3544.4     .12       0  3801.6    .045       0  4056.8     .05       0
  4339.5    .045       0  4720.2    .035       0  4969.8    .035       0
  4988.8    .035       0  5059.6     .12       0  5332.6     .07       0
  5531.3    .035       0
Bank Sta=4969.8,4988.8
XS Rating Curve= 0 ,0
Exp/Cntr=0.3,0.1

Type RM Length L Ch R = 1 ,76392   ,790,790,790
BEGIN DESCRIPTION:
CURRY CREEK 121.0
END DESCRIPTION:
XS GIS Cut Line= 3
      2094773.31      13904513.4        2094625.       13902025.
      2094574.99     13901824.97
#Sta/Elev= 30
  2501.8 1414.58  2611.5 1410.08  2792.9 1403.82  3031.1 1396.23  3228.1 1386.16
  3386.2 1388.54  3402.9 1388.26  3441.9 1388.36  3582.7  1380.7  3742.4 1373.43
  3878.8 1371.26  3966.3 1371.14  4032.9 1372.13  4069.1 1368.64  4133.1 1373.08
    4175 1371.99    4664 1370.33  4944.5  1377.2  4964.6 1375.12  4974.6 1370.68
  4982.6 1359.84  4983.1 1359.34  5001.6 1359.84  5025.5 1361.44  5035.8 1370.88
  5046.2 1375.32    5059 1376.16  5065.9 1380.08  5095.1 1400.75  5200.8 1418.56
#Mann= 12 ,-1 , 0
  2501.8    .035       0  2611.5     .07       0  2792.9     .12       0
  3386.2     .07       0  3402.9     .12       0  3582.7     .07       0
  3878.8    .035       0  3966.3     .07       0    4175     .05       0
  4982.6     .05       0  5001.6     .05       0  5065.9     .12       0
Bank Sta=4982.6,5001.6
XS Rating Curve= 0 ,0
Exp/Cntr=0.3,0.1

Type RM Length L Ch R = 1 ,75602   ,561,561,561
BEGIN DESCRIPTION:
CURRY CREEK 120.0
END DESCRIPTION:
XS GIS Cut Line= 3
      2095034.33     13904296.13      2095231.05     13901626.67
      2094875.02     13901175.02
#Sta/Elev= 30
  2323.3 1408.28  2388.1 1406.32  2684.5 1397.77  2907.1 1390.54  2967.9 1388.39
  3026.3 1383.26  3331.8 1375.13  3563.7  1368.5  3792.7 1366.95  3915.4 1366.35
    4092 1366.53  4103.8 1366.49  4287.4 1366.66  4441.5 1367.56  4921.5 1373.04
  4931.5 1372.44  4951.5 1363.99  4962.1 1352.83  4962.6 1352.33  4981.1 1352.83
  4986.2 1352.97  4998.3 1371.78  5005.1 1373.24  5147.8 1367.99  5236.5 1369.76
  5269.5 1371.93  5346.6  1393.6  5435.5 1407.35  5468.5    1414  5575.1 1423.69
#Mann= 17 ,-1 , 0
  2323.3     .07       0  2388.1     .12       0  2684.5     .07       0
  2907.1     .12       0  2967.9    .035       0  3331.8     .07       0
  3563.7    .035       0  3792.7     .07       0  3915.4     .05       0
    4092     .07       0  4103.8     .05       0  4287.4     .07       0
  4441.5     .05       0  4962.1     .05       0  4981.1     .05       0
  5236.5     .07       0  5435.5     .12       0
Bank Sta=4962.1,4981.1
XS Rating Curve= 0 ,0
Exp/Cntr=0.3,0.1

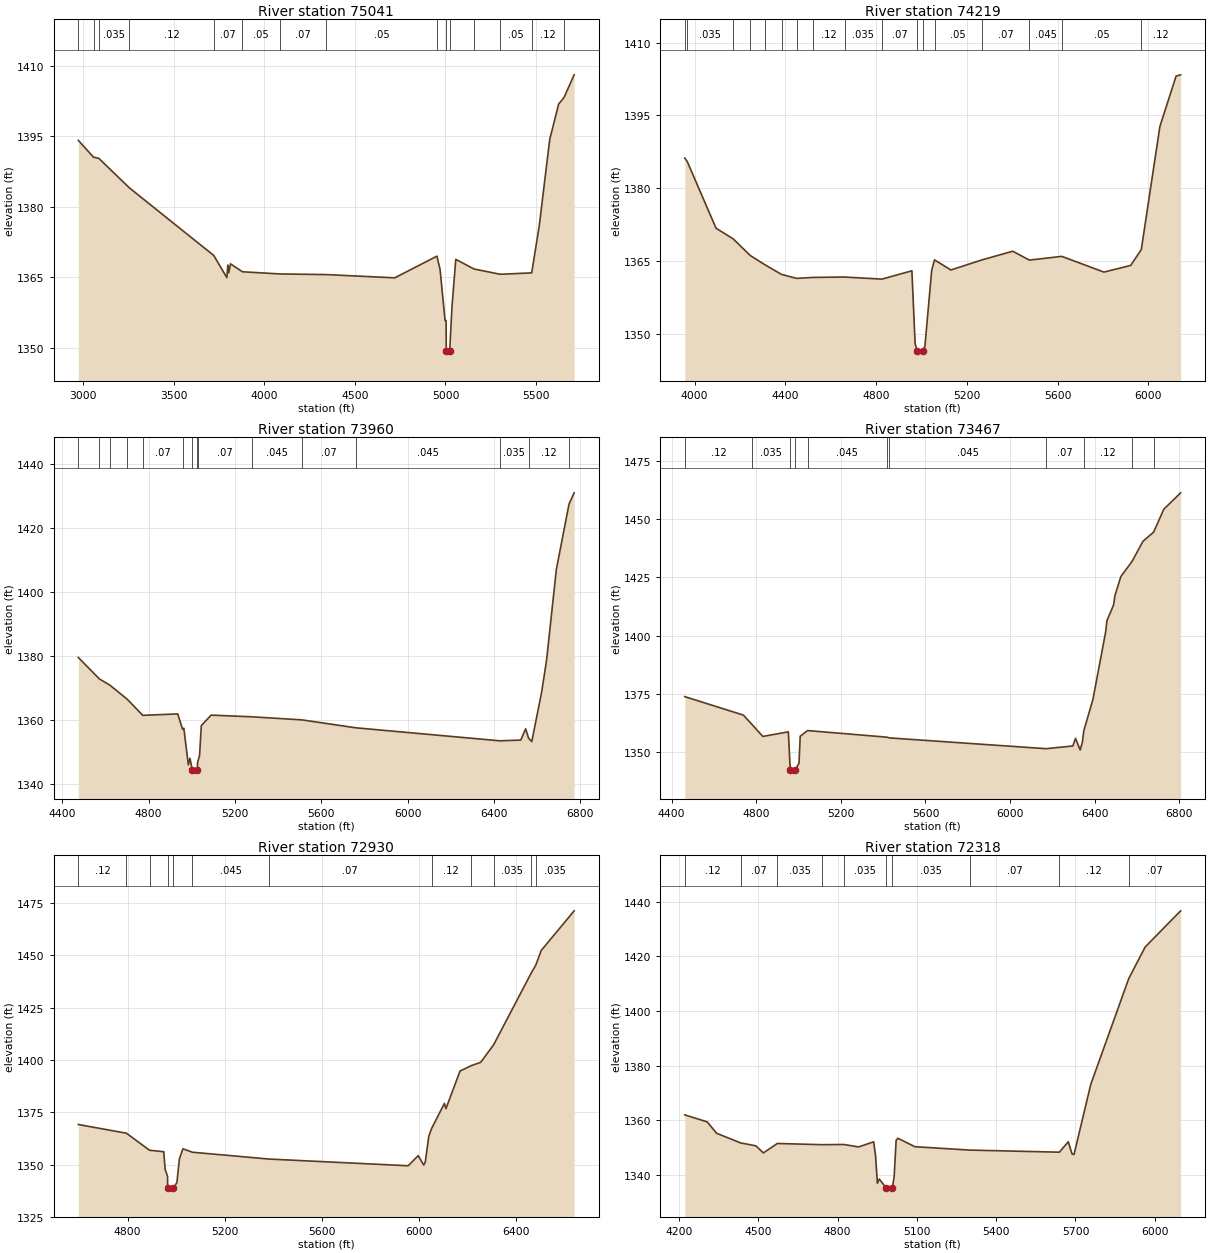
Type RM Length L Ch R = 1 ,75041   ,822,822,822
BEGIN DESCRIPTION:
CURRY CREEK 119.0
END DESCRIPTION:
XS GIS Cut Line= 4
      2095495.35     13903538.75      2095721.62     13901766.82
        2095725.       13901525.      2095174.99     13901074.99
#Sta/Elev= 30
  2972.2 1394.13  3056.1 1390.55  3085.7 1390.29  3254.3 1384.02  3720.2 1369.65
  3792.6 1364.94    3798  1367.6    3803 1365.94  3812.7 1367.87  3878.6 1366.18
  4084.9 1365.72  4342.7 1365.58    4720 1364.89  4952.9  1369.5  4970.4 1366.68
  4997.9 1355.82  5003.6 1355.82  5004.5 1349.38    5005 1348.88  5023.5 1349.38
  5036.2 1358.82  5057.1 1368.82  5157.8 1366.77  5302.3 1365.65  5476.5 1365.94
  5518.6 1376.07    5576 1394.31  5625.6 1401.86  5654.9 1403.23    5711 1408.06
#Mann= 15 ,-1 , 0
  2972.2    .035       0  3056.1     .07       0  3085.7    .035       0
  3254.3     .12       0  3720.2     .07       0  3878.6     .05       0
  4084.9     .07       0  4342.7     .05       0  4952.9     .07       0
  5004.5     .05       0  5023.5     .07       0  5157.8     .07       0
  5302.3     .05       0  5476.5     .12       0  5654.9     .07       0
Bank Sta=5004.5,5023.5
XS Rating Curve= 0 ,0
Exp/Cntr=0.3,0.1

Type RM Length L Ch R = 1 ,74219   ,259,259,259
BEGIN DESCRIPTION:
CURRY CREEK 118.0
END DESCRIPTION:
XS GIS Cut Line= 3
      2097043.68     13902181.05        2096325.       13901425.
      2095259.76     13901013.43
#Sta/Elev= 30
  3956.5 1386.18  3967.5 1385.45  4094.2 1371.73  4170.1 1369.52  4244.7 1366.12
  4309.9 1364.19  4383.2  1362.2  4449.7 1361.39  4521.8 1361.59  4660.4 1361.67
  4825.5 1361.24  4957.3 1362.96  4971.5 1347.96  4980.5 1346.49    4981 1345.99
  5004.5 1346.49  5014.6 1347.37  5044.6 1363.06  5057.2  1365.2  5129.1 1363.12
  5266.1  1365.2  5401.8 1366.99  5474.9 1365.16  5617.9 1365.93  5803.7 1362.69
  5921.6 1364.06  5968.3 1367.33  6050.2 1392.68  6121.6 1403.08  6141.6 1403.34
#Mann= 17 ,-1 , 0
  3956.5     .12       0  3967.5    .035       0  4170.1     .12       0
  4244.7    .035       0  4309.9     .07       0  4383.2    .035       0
  4449.7     .07       0  4521.8     .12       0  4660.4    .035       0
  4825.5     .07       0  4980.5     .05       0  5004.5     .07       0
  5057.2     .05       0  5266.1     .07       0  5474.9    .045       0
  5617.9     .05       0  5968.3     .12       0
Bank Sta=4980.5,5004.5
XS Rating Curve= 0 ,0
Exp/Cntr=0.3,0.1

Type RM Length L Ch R = 1 ,73960   ,493,493,493
BEGIN DESCRIPTION:
CURRY CREEK 117.0
END DESCRIPTION:
XS GIS Cut Line= 3
        2096925.       13901825.      2096527.18     13901471.68
      2095775.02     13899875.04
#Sta/Elev= 30
  4474.2 1379.61  4572.2 1372.88  4619.3 1371.01  4700.5 1366.58  4772.7 1361.52
  4934.6 1361.97  4957.2 1357.17    4963  1357.5  4983.9 1346.04  4991.4 1348.11
  5001.6 1344.58  5002.1 1344.08  5025.6 1344.58  5026.6 1346.78  5035.8 1348.96
  5043.9  1358.3  5089.5 1361.59  5279.7 1361.06  5510.1  1360.1  5759.1 1357.63
  6425.8 1353.56  6523.7 1353.78  6546.5 1357.31    6560 1354.38  6574.8 1353.31
  6620.4 1368.71  6643.2 1378.65  6688.7 1407.13  6747.3 1427.53  6771.2 1431.09
#Mann= 15 ,-1 , 0
  4474.2     .07       0  4572.2     .12       0  4619.3     .07       0
  4700.5     .12       0  4772.7     .07       0  4957.2    .035       0
  5001.6    .035       0  5025.6    .035       0  5026.6     .07       0
  5279.7    .045       0  5510.1     .07       0  5759.1    .045       0
  6425.8    .035       0    6560     .12       0  6747.3     .07       0
Bank Sta=5001.6,5025.6
XS Rating Curve= 0 ,0
Exp/Cntr=0.3,0.1

Type RM Length L Ch R = 1 ,73467   ,537,537,537
BEGIN DESCRIPTION:
CURRY CREEK 116.0
END DESCRIPTION:
XS GIS Cut Line= 3
      2097141.77     13901509.88        2096775.       13901125.
      2095925.01     13899525.02
#Sta/Elev= 30
  4462.4 1373.89  4739.4 1365.97  4781.7 1361.78  4831.3 1356.84  4951.8 1358.81
  4960.8 1342.48  4961.3 1341.98  4984.9 1342.48  5002.2 1345.41  5007.9 1356.92
  5042.6 1359.35  5417.2 1356.53  5429.7 1356.21  6170.2 1351.59  6296.3 1352.75
  6309.1 1356.01  6331.1 1351.03  6341.6 1354.45  6348.1 1359.24  6391.3 1372.68
  6451.6 1401.65  6457.3 1406.38  6488.8  1413.1  6495.6 1417.25  6523.2 1425.31
  6576.2 1431.78  6627.5 1440.39  6678.5 1444.38  6726.1 1454.14  6805.8 1461.18
#Mann= 11 ,-1 , 0
  4462.4     .12       0  4781.7    .035       0  4960.8    .035       0
  4984.9    .035       0  5042.6    .045       0  5417.2     .07       0
  5429.7    .045       0  6170.2     .07       0  6348.1     .12       0
  6576.2     .07       0  6678.5    .035       0
Bank Sta=4960.8,4984.9
XS Rating Curve= 0 ,0
Exp/Cntr=0.3,0.1

Type RM Length L Ch R = 1 ,72930   ,612,612,612
BEGIN DESCRIPTION:
CURRY CREEK 115.0
END DESCRIPTION:
XS GIS Cut Line= 3
      2097224.98     13901024.97        2097025.       13900675.
        2096025.       13899375.
#Sta/Elev= 30
  4596.7 1369.13  4794.9 1364.97  4890.2 1356.82  4948.7 1356.13  4954.4 1347.76
  4964.5 1344.28  4964.7 1338.74  4965.2 1338.24  4988.8 1338.74  5002.9 1341.39
  5013.3 1352.75  5027.8 1357.52  5066.5 1355.89    5382 1352.62  5955.8 1349.41
  5997.4 1354.24  6020.1 1349.78  6026.4 1351.16  6040.9 1363.51  6052.4 1367.22
  6105.3 1379.23  6111.6 1376.71  6169.6  1394.7  6214.1 1397.19  6254.8 1398.88
  6308.3 1407.29  6461.5 1441.22  6482.4 1445.51    6504  1452.3  6639.9 1471.29
#Mann= 12 ,-1 , 0
  4596.7     .12       0  4794.9     .07       0  4890.2    .035       0
  4964.7    .035       0  4988.8    .035       0  5066.5    .045       0
    5382     .07       0  6052.4     .12       0  6214.1     .07       0
  6308.3    .035       0  6461.5     .07       0  6482.4    .035       0
Bank Sta=4964.7,4988.8
XS Rating Curve= 0 ,0
Exp/Cntr=0.3,0.1

Type RM Length L Ch R = 1 ,72318   ,434,434,434
BEGIN DESCRIPTION:
CURRY CREEK 114.0
END DESCRIPTION:
XS GIS Cut Line= 3
        2097725.     13900724.99      2097197.32     13900159.18
      2096374.97     13899424.97
#Sta/Elev= 30
  4221.7  1361.9  4306.5 1359.34  4342.1 1355.16  4433.2 1351.62  4490.6 1350.56
    4519 1347.97  4571.9 1351.42  4740.3 1350.98  4823.6 1351.05  4879.5 1350.16
  4936.2 1352.03  4943.5 1347.04  4950.4 1336.83  4957.7 1338.39  4983.3 1335.19
  4983.8 1334.69  5007.4 1335.19  5013.9  1339.4  5021.4 1352.61  5028.1 1353.34
  5092.3 1350.24  5299.5    1349  5639.1 1348.23  5672.7 1352.05  5686.9 1347.59
  5694.4 1347.37  5757.9 1373.11  5901.7 1411.89  5963.6 1423.43  6097.8 1436.69
#Mann= 10 ,-1 , 0
  4221.7     .12       0  4433.2     .07       0  4571.9    .035       0
  4740.3     .07       0  4823.6    .035       0  4983.3    .045       0
  5007.4    .035       0  5299.5     .07       0  5639.1     .12       0
  5901.7     .07       0
Bank Sta=4983.3,5007.4
XS Rating Curve= 0 ,0
Exp/Cntr=0.3,0.1

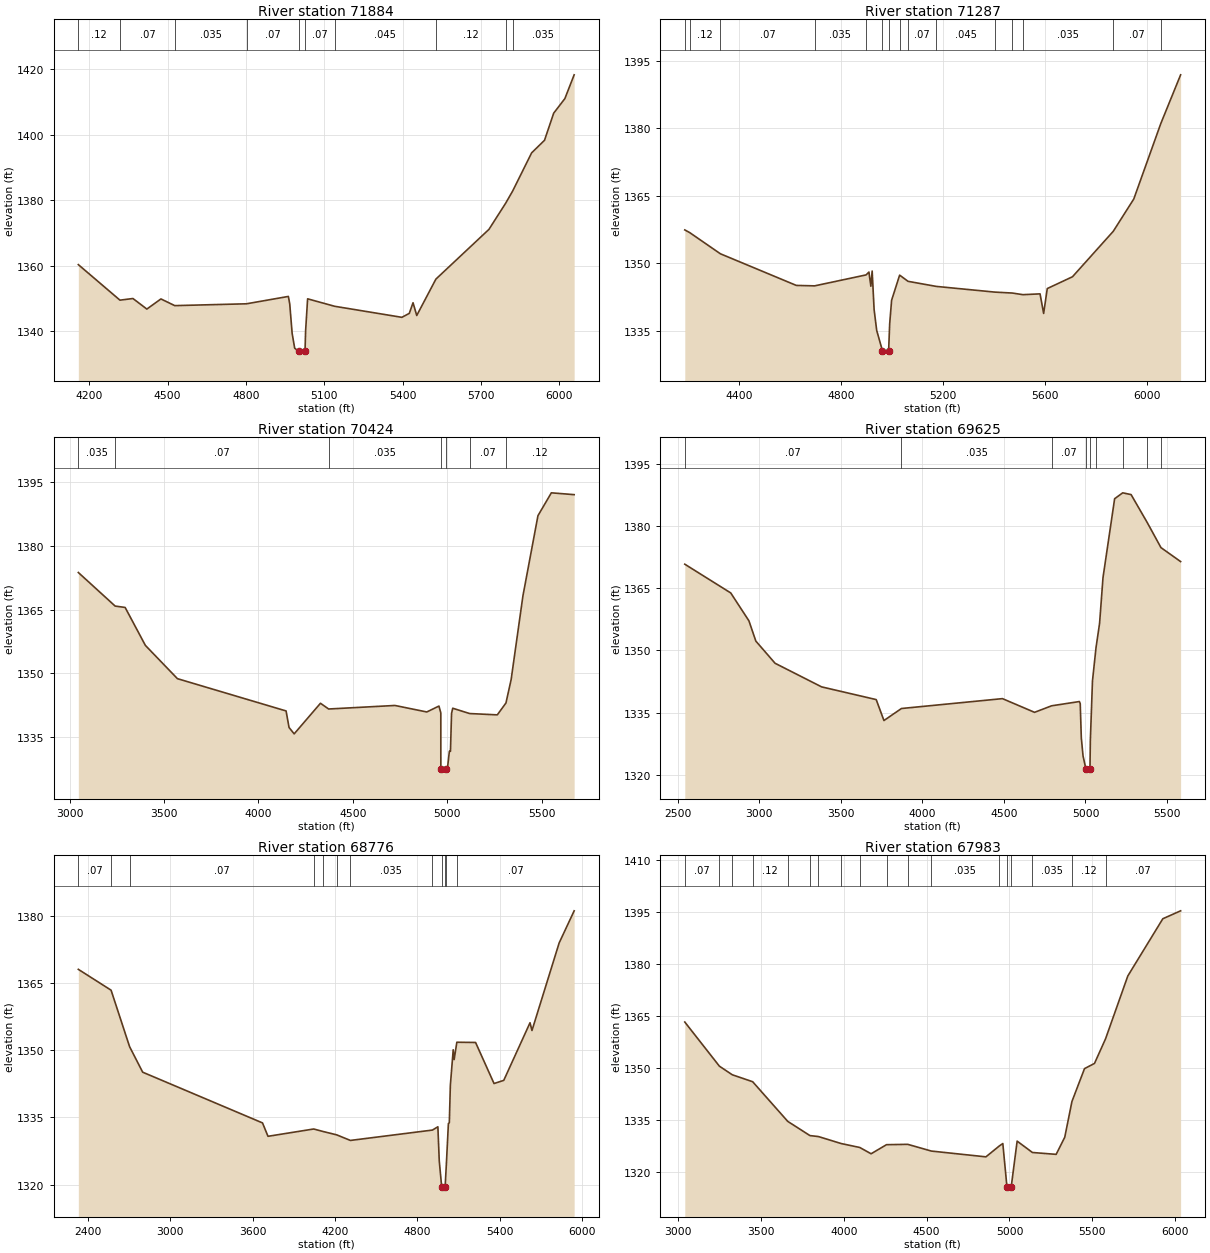
Type RM Length L Ch R = 1 ,71884   ,597,597,597
BEGIN DESCRIPTION:
CURRY CREEK 113.0
END DESCRIPTION:
XS GIS Cut Line= 3
        2097725.       13900675.      2097471.62      13899881.4
      2096774.99     13899074.99
#Sta/Elev= 30
  4157.9 1360.32  4317.3 1349.47  4367.1 1349.97  4420.3 1346.75  4474.2 1349.84
  4527.2  1347.8    4802 1348.36  4962.2 1350.61  4967.4 1348.37  4976.7 1339.31
  4986.4 1334.82  5001.9  1333.8  5002.4  1333.3    5026  1333.8  5028.2 1340.05
  5035.9 1349.88  5139.5  1347.6  5396.8 1344.23  5425.3 1345.44  5439.6 1348.68
  5453.8 1344.79  5527.2  1355.9  5730.3 1371.08  5794.2 1379.05    5821 1382.77
  5893.7 1394.43  5943.1 1398.28  5978.2 1406.55    6021    1411  6056.6 1418.26
#Mann= 10 ,-1 , 0
  4157.9     .12       0  4317.3     .07       0  4527.2    .035       0
    4802     .07       0  5001.9     .05       0    5026     .07       0
  5139.5    .045       0  5527.2     .12       0  5794.2     .07       0
    5821    .035       0
Bank Sta=5001.9,5026
XS Rating Curve= 0 ,0
Exp/Cntr=0.3,0.1

Type RM Length L Ch R = 1 ,71287   ,863,863,863
BEGIN DESCRIPTION:
CURRY CREEK 112.0
END DESCRIPTION:
XS GIS Cut Line= 3
        2097825.     13900625.02        2097975.       13899825.
      2097175.02     13899025.02
#Sta/Elev= 30
  4186.5 1357.42  4205.1 1356.85  4326.2 1352.11    4624 1345.07  4695.9 1344.97
  4897.8 1347.41  4908.9 1348.04  4916.5 1344.89  4921.6 1348.27  4929.2 1339.71
  4939.4 1335.05  4962.1  1330.5  4962.6    1330  4986.2  1330.5  4990.3 1336.49
  4997.9 1341.77  5029.4 1347.36  5062.4 1345.98  5173.1 1344.85  5403.2 1343.58
  5471.9 1343.37  5513.1 1343.01  5580.3 1343.19  5594.4 1338.83  5608.6 1344.37
  5707.6    1347  5867.6 1357.12    5948  1364.3    6054 1381.09  6131.8 1391.94
#Mann= 15 ,-1 , 0
  4186.5     .07       0  4205.1     .12       0  4326.2     .07       0
  4695.9    .035       0  4897.8     .07       0  4962.1     .05       0
  4986.2     .07       0  5029.4    .035       0  5062.4     .07       0
  5173.1    .045       0  5403.2    .035       0  5471.9    .045       0
  5513.1    .035       0  5867.6     .07       0    6054     .12       0
Bank Sta=4962.1,4986.2
XS Rating Curve= 0 ,0
Exp/Cntr=0.3,0.1

Type RM Length L Ch R = 1 ,70424   ,799,799,799
BEGIN DESCRIPTION:
Curry Creek 111.1
END DESCRIPTION:
XS GIS Cut Line= 3
      2099227.96      13900800.1      2098229.39     13899106.73
      2097696.03     13898716.06
#Sta/Elev= 30
  3045.9 1373.75    3241 1365.85  3293.8 1365.53  3401.1  1356.6  3570.9 1348.77
  4146.6 1341.17  4162.3 1337.28  4189.5 1335.78  4328.8 1342.98  4372.1 1341.63
  4723.5 1342.46  4892.2 1340.93  4956.5 1342.32  4966.4 1340.71  4966.5 1327.51
    4967 1327.01  4991.4 1327.51  5002.2  1327.9  5011.8 1331.68  5017.5 1331.68
  5023.3 1340.59  5029.6 1341.81  5119.1 1340.56  5265.7 1340.25  5311.6 1343.05
    5339 1348.55  5401.6 1368.28  5481.1 1387.12  5552.1  1392.5  5672.9 1392.07
#Mann= 7 ,-1 , 0
  3045.9    .035       0    3241     .07       0  4372.1    .035       0
  4966.5     .05       0  4991.4    .035       0  5119.1     .07       0
  5311.6     .12       0
Bank Sta=4966.5,4991.4
XS Rating Curve= 0 ,0
Exp/Cntr=0.3,0.1

Type RM Length L Ch R = 1 ,69625   ,849,849,849
BEGIN DESCRIPTION:
Curry Creek 111.0
END DESCRIPTION:
XS GIS Cut Line= 3
      2099394.63     13900745.34      2098566.56     13898424.77
      2098233.67     13897953.47
#Sta/Elev= 30
  2542.6 1370.77  2824.3 1363.85  2935.8 1357.14  2978.3 1352.25  3096.2 1346.91
  3381.8 1341.22  3716.5 1338.16    3764 1333.12  3871.3 1336.01  4490.9 1338.39
  4687.7 1335.09    4792 1336.66  4962.5 1337.69  4967.8 1337.18  4974.4 1328.98
    4985  1324.6  5002.6 1321.43  5003.1 1320.93  5027.5 1321.43  5029.9  1328.4
  5042.9 1342.66  5064.7  1350.7  5086.5 1356.53  5107.4 1367.53  5178.8 1386.54
  5228.4 1387.96  5279.8 1387.53  5379.2 1380.77  5462.8 1374.77  5583.5  1371.4
#Mann= 9 ,-1 , 0
  2542.6     .07       0  3871.3    .035       0    4792     .07       0
  5002.6     .05       0  5027.5     .07       0  5064.7     .12       0
  5228.4     .07       0  5379.2     .12       0  5462.8     .07       0
Bank Sta=5002.6,5027.5
XS Rating Curve= 0 ,0
Exp/Cntr=0.3,0.1

Type RM Length L Ch R = 1 ,68776   ,793,793,793
BEGIN DESCRIPTION:
Curry Creek 110.0
END DESCRIPTION:
XS GIS Cut Line= 4
      2099454.58     13900632.28      2099308.94     13898750.36
      2099211.25     13897974.27      2098577.05     13897278.62
#Sta/Elev= 30
  2330.9    1368  2569.4 1363.35  2704.3 1350.75  2799.6 1345.06  3672.2 1333.75
  3712.3 1330.76  4044.9 1332.39    4114 1331.83  4212.9 1331.08  4312.4 1329.84
  4909.5 1332.15  4949.5 1332.88  4959.6 1325.23  4977.3 1319.48  4977.8 1318.98
  5002.3 1319.48  5012.2 1325.08  5026.1 1333.61  5032.8 1333.77  5040.3 1342.11
  5061.2 1350.06    5068 1347.87  5087.6 1351.74  5224.1 1351.69  5358.5 1342.53
  5429.4 1343.24  5620.6 1356.09  5634.8 1354.36  5832.8 1373.89    5942 1381.05
#Mann= 12 ,-1 , 0
  2330.9     .07       0  2569.4     .12       0  2704.3     .07       0
  4044.9     .12       0    4114    .035       0  4212.9     .07       0
  4312.4    .035       0  4909.5     .07       0  4977.3     .05       0
  5002.3     .07       0  5012.2     .12       0  5087.6     .07       0
Bank Sta=4977.3,5002.3
XS Rating Curve= 0 ,0
Exp/Cntr=0.3,0.1

Type RM Length L Ch R = 1 ,67983   ,644,644,644
BEGIN DESCRIPTION:
Curry Creek 109.0
END DESCRIPTION:
XS GIS Cut Line= 3
      2100137.19     13900072.37        2099925.       13898125.
      2099815.55     13897098.32
#Sta/Elev= 30
  3041.1 1363.34  3249.8 1350.61  3327.5 1348.13  3450.6 1346.12  3662.3 1334.68
  3796.4 1330.58  3847.7  1330.3  3984.3 1328.29    4097 1327.15  4165.1 1325.34
    4258 1327.96  4386.2 1328.06  4528.7 1326.12  4857.8 1324.45  4938.9  1327.6
  4959.8 1328.29    4985 1315.64  4985.5 1315.14    5010 1315.64  5046.2 1328.99
  5138.3 1325.71  5281.6 1325.17  5333.5 1330.11  5376.7  1340.4  5452.6  1349.9
  5512.9  1351.4  5579.6  1358.5    5714 1376.64  5925.2 1393.14  6032.5 1395.42
#Mann= 18 ,-1 , 0
  3041.1     .07       0  3249.8    .035       0  3327.5     .07       0
  3450.6     .12       0  3662.3     .07       0  3796.4    .035       0
  3847.7     .07       0  3984.3    .035       0    4097     .07       0
    4258    .035       0  4386.2     .07       0  4528.7    .035       0
  4938.9     .07       0    4985     .05       0    5010     .07       0
  5138.3    .035       0  5376.7     .12       0  5579.6     .07       0
Bank Sta=4985,5010
XS Rating Curve= 0 ,0
Exp/Cntr=0.3,0.1