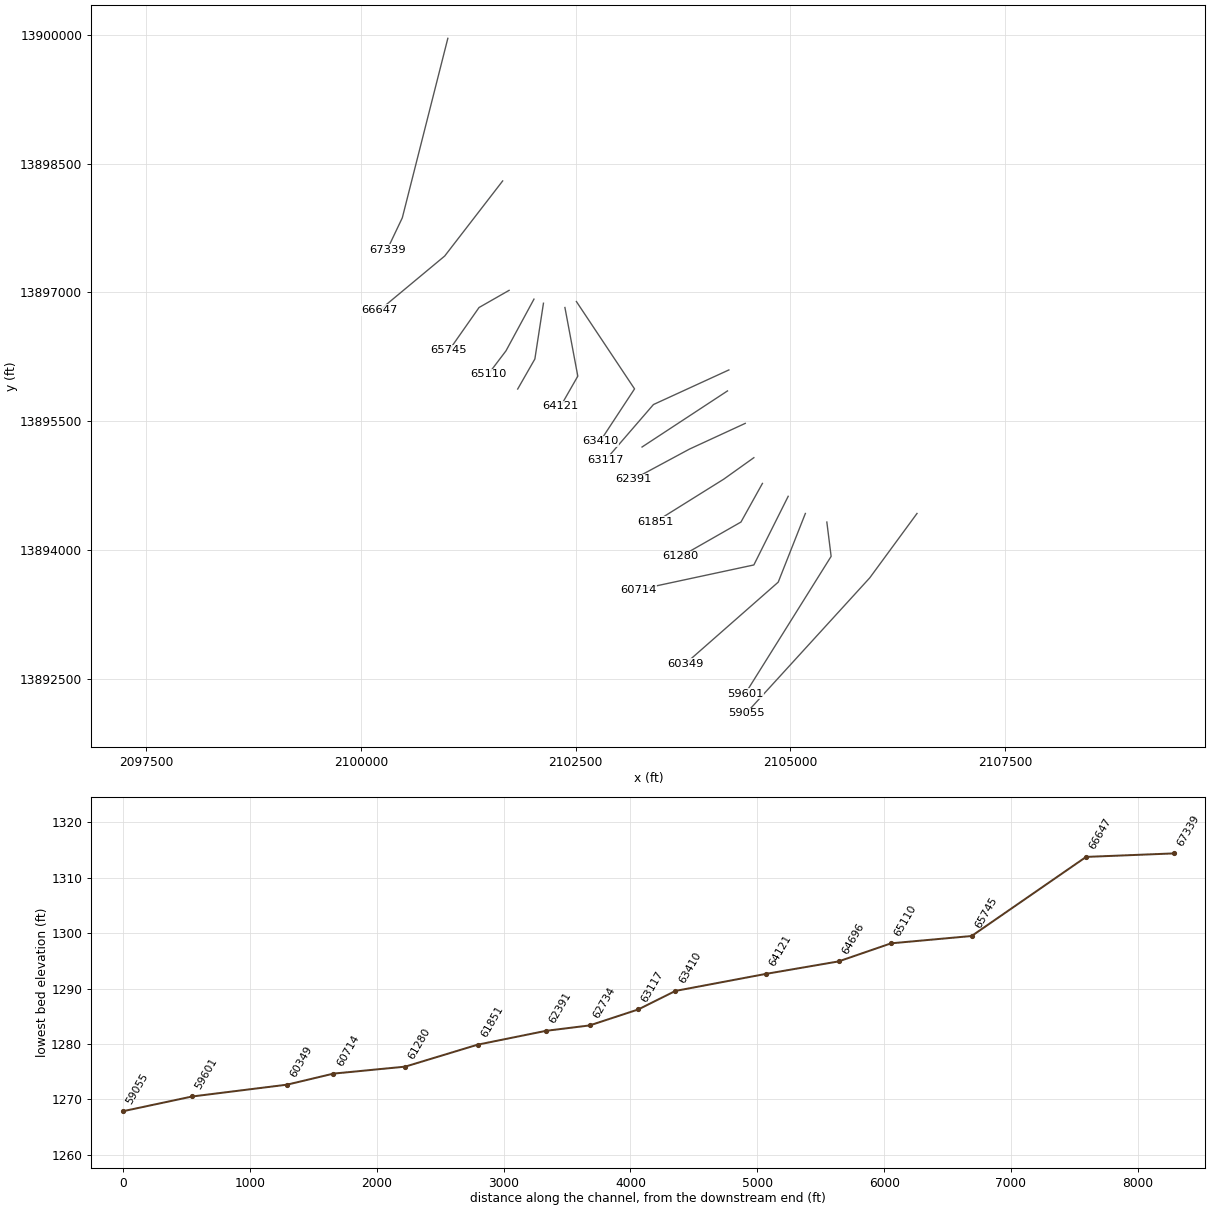
HEC-RAS study CURRY CREEK.prj: CURRY CREEK Base Level Engineering

--- CURRY CREEK.g01 (geometry) --- (continued)

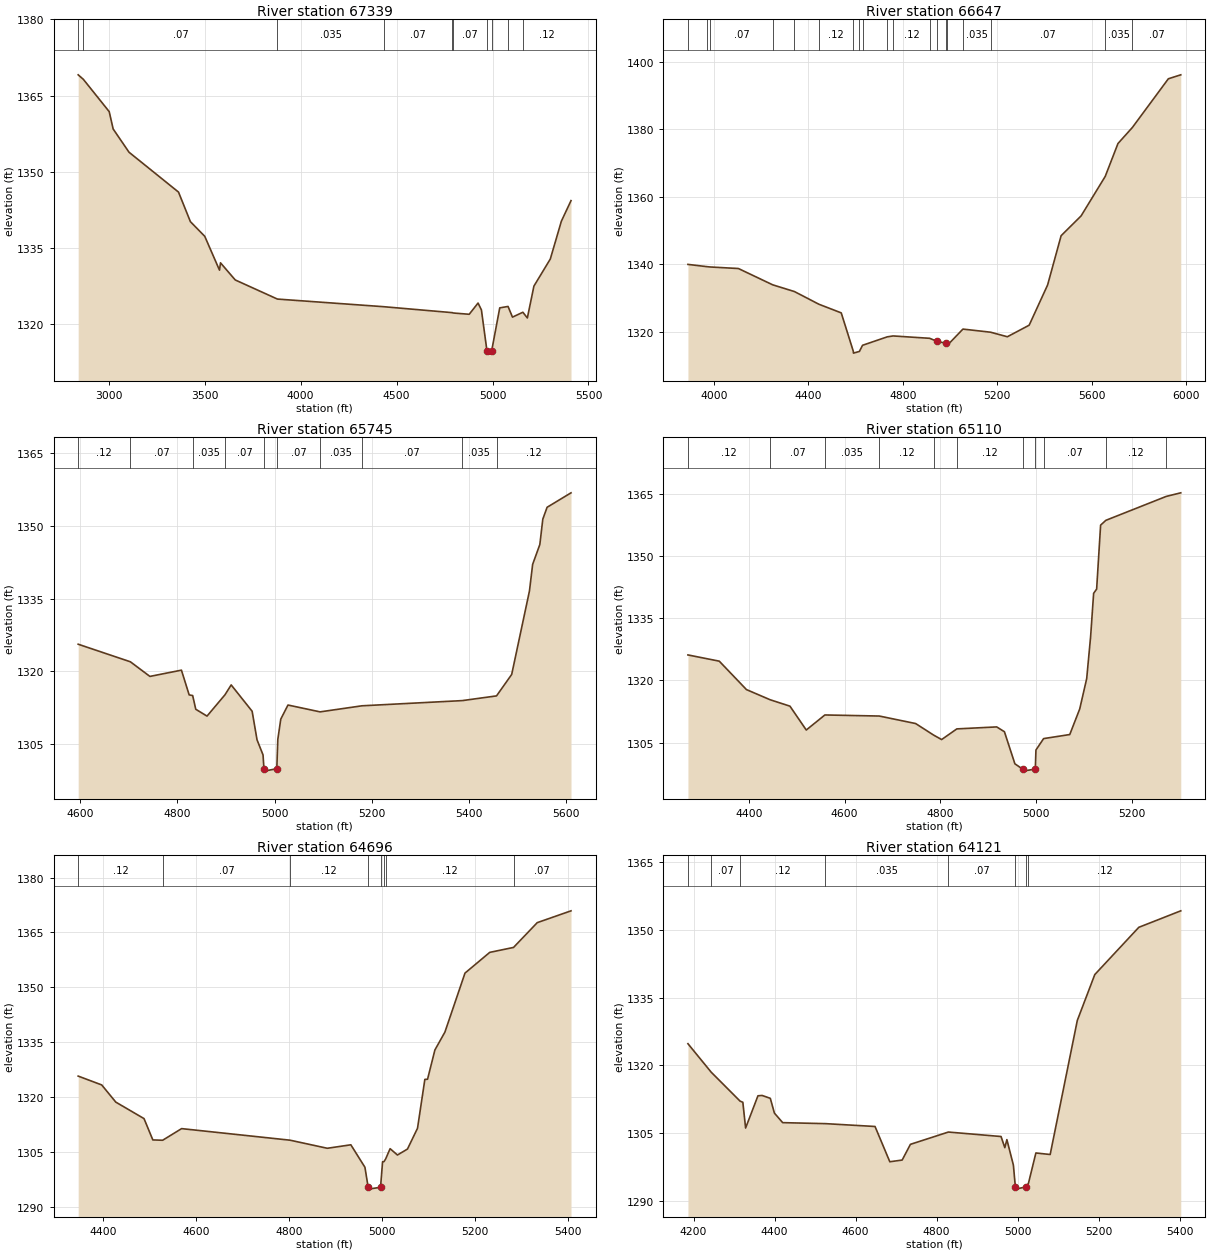
Type RM Length L Ch R = 1 ,67339   ,692,692,692
BEGIN DESCRIPTION:
Curry Creek 108.0
END DESCRIPTION:
XS GIS Cut Line= 3
      2101011.48     13899961.75      2100481.41     13897870.44
      2100305.05     13897499.58
#Sta/Elev= 30
  2840.9 1369.09  2867.7 1368.21  3002.6 1361.85  3023.2 1358.44  3105.8 1353.87
  3363.7 1346.03  3425.6 1340.22  3500.5 1337.33  3577.3 1330.68  3582.5 1332.12
  3659.3 1328.75  3879.2 1324.99  4432.8 1323.49  4790.4 1322.32  4795.5 1322.25
  4878.5    1322  4924.6 1324.21  4942.1 1322.86  4970.8 1314.86  4971.3 1314.36
  4995.8 1314.86  5037.6 1323.26  5080.9 1323.54    5104 1321.44  5158.2  1322.4
  5181.5 1321.28  5215.7 1327.54  5301.1 1332.87  5358.7  1340.3    5409 1344.35
#Mann= 10 ,-1 , 0
  2840.9     .12       0  2867.7     .07       0  3879.2    .035       0
  4432.8     .07       0  4790.4    .035       0  4795.5     .07       0
  4970.8     .05       0  4995.8     .07       0  5080.9    .035       0
  5158.2     .12       0
Bank Sta=4970.8,4995.8
XS Rating Curve= 0 ,0
Exp/Cntr=0.3,0.1

Type RM Length L Ch R = 1 ,66647   ,902,902,902
BEGIN DESCRIPTION:
Curry Creek 107.0
END DESCRIPTION:
XS GIS Cut Line= 3
      2101650.03     13898300.04        2100975.       13897425.
      2100219.57      13896796.4
#Sta/Elev= 30
  3889.5 1340.01  3970.3 1339.34  3982.7 1339.25  4103.3 1338.79  4248.6 1333.96
  4340.6 1331.97  4444.4 1328.21    4539 1325.65  4590.3 1314.23  4590.8 1313.73
  4615.9 1314.23  4629.2 1316.05  4733.8 1318.55  4758.6 1318.82  4913.7 1318.12
  4944.1 1317.22  4981.1 1316.69  4988.3 1316.04  5054.5 1320.85  5171.4 1319.93
  5242.7 1318.58  5335.1    1322  5413.2 1333.91  5470.5 1348.51  5555.1 1354.37
  5657.4 1366.08  5711.3 1375.81  5772.3 1380.56  5924.8 1394.99  5977.4 1396.16
#Mann= 19 ,-1 , 0
  3889.5     .07       0  3970.3     .12       0  3982.7     .07       0
  4248.6     .12       0  4340.6     .07       0  4444.4     .12       0
  4590.3     .05       0  4615.9     .12       0  4629.2     .07       0
  4733.8     .12       0  4758.6     .12       0  4913.7    .035       0
  4944.1    .035       0  4981.1     .07       0  4988.3     .07       0
  5054.5    .035       0  5171.4     .07       0  5657.4    .035       0
  5772.3     .07       0
Bank Sta=4944.1,4981.1
XS Rating Curve= 0 ,0
Exp/Cntr=0.3,0.1

Type RM Length L Ch R = 1 ,65745   ,635,635,635
BEGIN DESCRIPTION:
CURRY CREEK 106.0
END DESCRIPTION:
XS GIS Cut Line= 3
      2101724.98     13897024.99        2101375.       13896825.
      2101025.01     13896325.02
#Sta/Elev= 30
  4596.2  1325.6  4703.6 1321.98  4743.7 1318.97  4808.5 1320.26  4824.4 1315.17
  4831.6 1315.03    4838 1312.21  4861.1  1310.8    4898 1315.18  4910.8 1317.22
  4953.9  1311.8    4964 1305.91  4976.3 1302.81  4978.2 1299.97  4978.7 1299.47
  5004.6 1299.97  5006.7    1306  5012.8 1310.18  5027.6 1313.08  5093.6 1311.67
  5179.7 1312.92  5386.1 1313.99  5456.4 1314.96  5487.6 1319.37  5524.2 1336.59
  5530.7 1342.04  5545.5 1346.13  5551.6 1351.35  5560.4 1353.79  5609.6 1356.77
#Mann= 10 ,-1 , 0
  4596.2     .12       0  4703.6     .07       0  4831.6    .035       0
    4898     .07       0  4978.2     .05       0  5004.6     .07       0
  5093.6    .035       0  5179.7     .07       0  5386.1    .035       0
  5456.4     .12       0
Bank Sta=4978.2,5004.6
XS Rating Curve= 0 ,0
Exp/Cntr=0.3,0.1

Type RM Length L Ch R = 1 ,65110   ,414,414,414
BEGIN DESCRIPTION:
Curry Creek 105.0
END DESCRIPTION:
XS GIS Cut Line= 3
      2102014.49     13896922.58      2101688.45      13896319.8
      2101480.06     13896044.73
#Sta/Elev= 30
  4272.6 1326.16  4338.1 1324.66  4394.9 1317.81  4444.4 1315.36  4485.9 1313.81
    4520 1308.06  4558.9 1311.69  4672.7 1311.43  4748.7 1309.62  4786.4 1306.83
    4803 1305.76  4834.8 1308.33  4918.1 1308.81  4934.3 1307.65  4956.2 1299.91
  4972.3 1298.65  4972.8 1298.15  4998.9 1298.65  5000.2 1303.24  5016.2 1305.99
  5070.9 1306.97  5091.7 1313.13  5106.3 1320.45  5114.5 1330.56  5120.8 1341.01
  5127.1 1342.04  5135.4 1357.45  5146.4 1358.61  5272.7 1364.38    5303 1365.24
#Mann= 11 ,-1 , 0
  4272.6     .12       0  4444.4     .07       0  4558.9    .035       0
  4672.7     .12       0  4786.4     .07       0  4834.8     .12       0
  4972.3     .05       0  4998.9     .12       0  5016.2     .07       0
  5146.4     .12       0  5272.7     .07       0
Bank Sta=4972.3,4998.9
XS Rating Curve= 0 ,0
Exp/Cntr=0.3,0.1

Type RM Length L Ch R = 1 ,64696   ,575,575,575
BEGIN DESCRIPTION:
CURRY CREEK 104.0
END DESCRIPTION:
XS GIS Cut Line= 3
      2102125.01     13896875.04        2102025.       13896225.
        2101825.       13895875.
#Sta/Elev= 30
  4346.6 1325.77  4397.2 1323.36  4427.6 1318.66  4488.3 1314.16  4507.3 1308.33
  4528.4 1308.24  4569.2 1311.42  4802.6 1308.26  4882.9 1306.05  4933.5    1307
  4963.8 1300.87  4970.8 1295.39  4971.3 1294.89  4997.4 1295.39  5001.8 1302.37
  5004.6 1302.37  5008.4 1303.13    5018 1305.94  5033.8 1304.21  5055.4 1305.84
    5077 1311.52  5092.8 1324.87  5098.6 1324.91  5114.4  1332.9    5136  1337.8
  5179.2 1353.91  5232.5 1359.57  5283.7 1360.92  5334.7 1367.69  5407.4 1370.92
#Mann= 8 ,-1 , 0
  4346.6     .12       0  4528.4     .07       0  4802.6     .12       0
  4970.8     .05       0  4997.4     .12       0  5004.6     .07       0
  5008.4     .12       0  5283.7     .07       0
Bank Sta=4970.8,4997.4
XS Rating Curve= 0 ,0
Exp/Cntr=0.3,0.1

Type RM Length L Ch R = 1 ,64121   ,711,711,711
BEGIN DESCRIPTION:
CURRY CREEK 103.0
END DESCRIPTION:
XS GIS Cut Line= 3
      2102375.01     13896824.96        2102525.       13896025.
      2102325.01     13895675.01
#Sta/Elev= 30
  4186.1 1324.81  4243.4 1318.52  4314.9  1312.1  4321.7 1311.85  4328.5 1306.15
    4359 1313.28  4369.2 1313.36  4389.5 1312.72  4399.7 1309.44  4420.1 1307.34
  4525.7 1307.12  4648.1 1306.49  4684.6 1298.69  4715.1 1299.06  4735.5 1302.54
  4829.3 1305.26  4959.3 1304.27  4968.6 1301.81  4973.7 1303.58  4989.8 1297.94
  4994.6 1293.13  4995.1 1292.63  5021.2 1293.13    5027 1293.93  5045.3 1300.63
  5080.6 1300.29  5147.6 1329.95  5190.8 1340.11  5299.5 1350.56  5403.1 1354.21
#Mann= 8 ,-1 , 0
  4186.1     .12       0  4243.4     .07       0  4314.9     .12       0
  4525.7    .035       0  4829.3     .07       0  4994.6     .05       0
  5021.2     .07       0    5027     .12       0
Bank Sta=4994.6,5021.2
XS Rating Curve= 0 ,0
Exp/Cntr=0.3,0.1

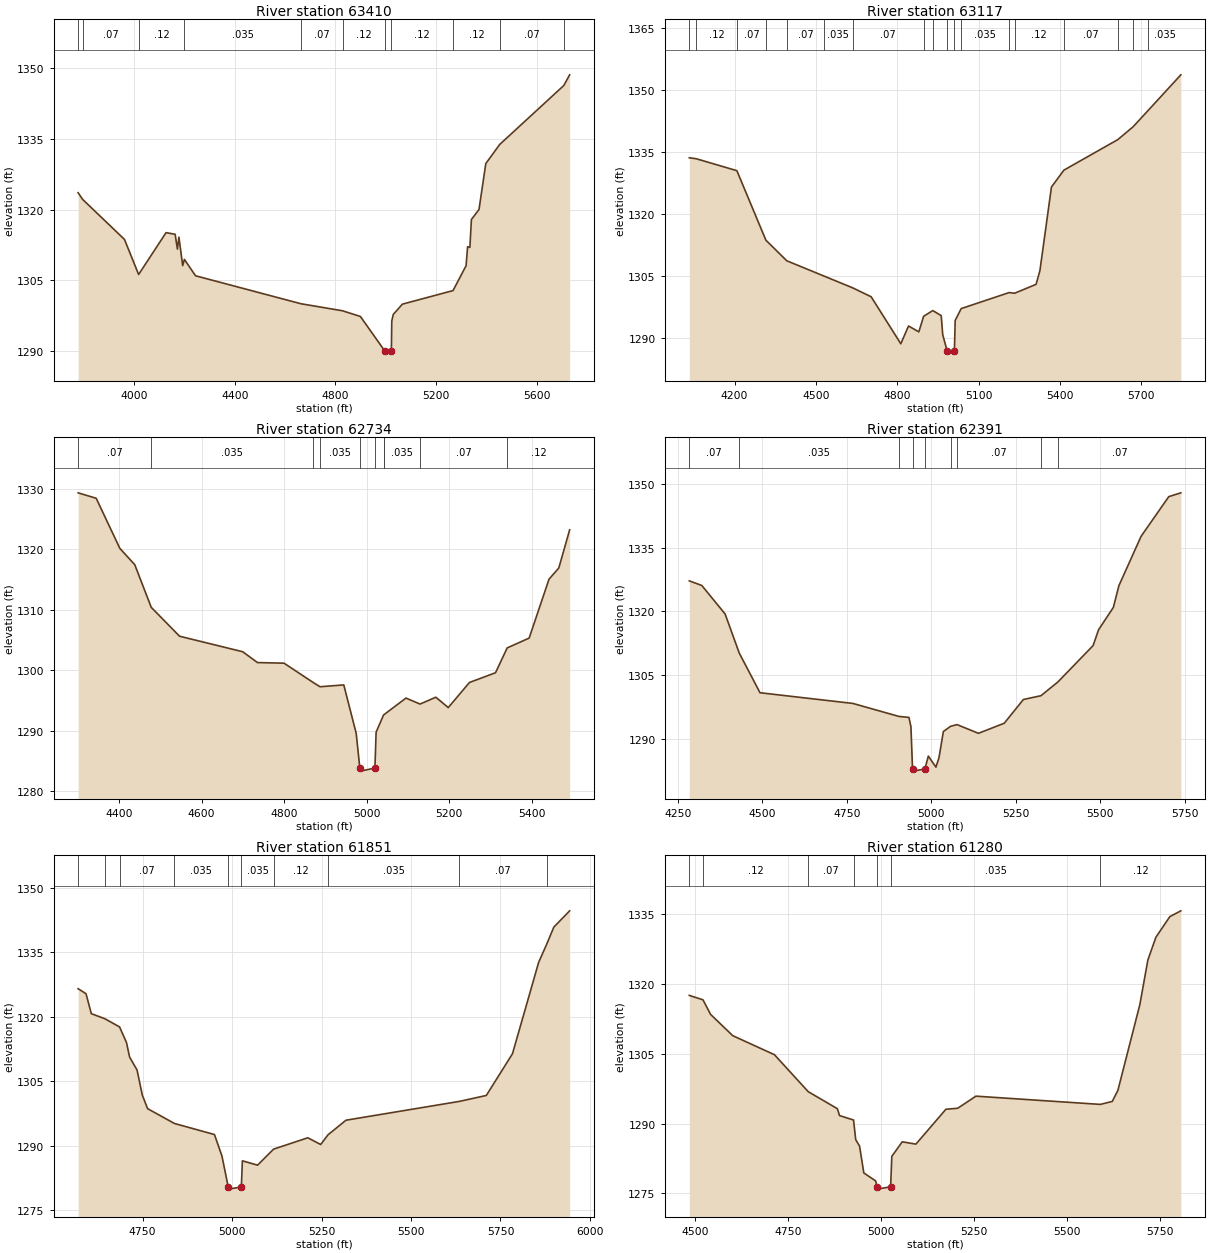
Type RM Length L Ch R = 1 ,63410   ,293,293,293
BEGIN DESCRIPTION:
Curry Creek 102.0
END DESCRIPTION:
XS GIS Cut Line= 3
      2102508.71     13896894.41      2103185.71     13895876.72
      2102784.48     13895265.43
#Sta/Elev= 30
  3777.7 1323.56  3795.6 1322.15  3961.9 1313.67  4018.2 1306.23  4127.2  1315.1
  4163.3 1314.75  4172.3 1311.61  4178.3 1314.14  4193.3 1308.12  4200.1 1309.43
  4244.4 1305.96  4663.5 1300.03  4828.7 1298.54  4899.7 1297.33  4995.9 1290.07
  4996.4 1289.57  5022.6 1290.07  5024.3  1296.4  5030.3 1297.77  5066.5 1299.95
  5267.7 1302.82  5319.6 1308.09  5325.6 1312.12  5334.7 1311.97  5340.7 1317.88
  5370.9    1320  5397.9 1329.73  5453.3 1333.79  5707.8 1346.27  5731.2 1348.54
#Mann= 11 ,-1 , 0
  3777.7     .12       0  3795.6     .07       0  4018.2     .12       0
  4200.1    .035       0  4663.5     .07       0  4828.7     .12       0
  4995.9     .05       0  5022.6     .12       0  5267.7     .12       0
  5453.3     .07       0  5707.8    .035       0
Bank Sta=4995.9,5022.6
XS Rating Curve= 0 ,0
Exp/Cntr=0.3,0.1

Type RM Length L Ch R = 1 ,63117   ,383,383,383
BEGIN DESCRIPTION:
Curry Creek 101.5
END DESCRIPTION:
XS GIS Cut Line= 3
      2104284.39      13896097.6      2103405.76     13895694.23
      2102852.82     13895053.81
#Sta/Elev= 30
  4033.2 1333.57  4058.6 1333.34  4208.7 1330.44  4315.6 1313.61  4392.7 1308.61
  4529.5 1304.92  4636.4 1302.03  4703.9 1299.89  4813.3  1288.5  4841.8 1292.81
  4879.8 1291.38  4897.4 1295.15  4931.2 1296.54  4962.3 1295.32  4967.8 1290.74
  4984.3 1286.73  4984.8 1286.23    5011 1286.73  5013.8 1294.13  5035.9 1297.02
  5213.1 1300.91    5233 1300.74  5312.2  1302.9  5326.4 1306.23  5368.9 1326.48
  5414.8 1330.57  5613.6 1337.97  5669.9 1341.07  5726.7 1345.12  5846.1 1353.67
#Mann= 18 ,-1 , 0
  4033.2     .07       0  4058.6     .12       0  4208.7     .07       0
  4315.6    .035       0  4392.7     .07       0  4529.5    .035       0
  4636.4     .07       0  4897.4    .035       0  4931.2     .07       0
  4984.3     .05       0    5011     .07       0  5035.9    .035       0
  5213.1     .07       0    5233     .12       0  5414.8     .07       0
  5613.6    .035       0  5669.9     .07       0  5726.7    .035       0
Bank Sta=4984.3,5011
XS Rating Curve= 0 ,0
Exp/Cntr=0.3,0.1

Type RM Length L Ch R = 1 ,62734   ,343,343,343
BEGIN DESCRIPTION:
Curry Creek 101.0
END DESCRIPTION:
XS GIS Cut Line= 2
      2104268.13     13895853.07      2103273.03     13895199.39
#Sta/Elev= 30
  4300.8 1329.29  4344.6 1328.39  4401.9 1320.12    4438 1317.43  4477.9 1310.39
  4546.5 1305.62  4699.4 1303.06  4735.3 1301.27  4799.6 1301.17    4870 1297.99
  4886.8 1297.28  4944.3 1297.58  4974.4 1289.58  4983.2 1283.85  4984.1 1283.35
  5019.7 1283.85  5022.6 1289.77  5040.5  1292.6  5041.7 1292.67  5094.9 1295.41
  5129.1 1294.42  5167.2 1295.55  5197.4 1293.84  5248.6 1297.98  5311.8 1299.59
  5340.1 1303.69  5393.3 1305.31  5441.4 1315.03  5465.1 1316.88  5491.4 1323.18
#Mann= 10 ,-1 , 0
  4300.8     .07       0  4477.9    .035       0    4870     .07       0
  4886.8    .035       0  4983.2    .035       0  5019.7    .035       0
  5040.5     .07       0  5041.7    .035       0  5129.1     .07       0
  5340.1     .12       0
Bank Sta=4983.2,5019.7
XS Rating Curve= 0 ,0
Exp/Cntr=0.3,0.1

Type RM Length L Ch R = 1 ,62391   ,540,540,540
BEGIN DESCRIPTION:
CURRY CREEK 100.0
END DESCRIPTION:
XS GIS Cut Line= 3
      2104474.97     13895474.99        2103825.       13895175.
        2103175.       13894825.
#Sta/Elev= 30
  4283.9 1327.16    4321 1326.07  4389.9 1319.36  4431.6 1310.18  4493.1 1300.83
    4768 1298.31  4903.7 1295.26  4933.7 1295.02  4939.6  1292.8  4944.3 1282.88
  4945.2 1282.38  4980.9 1282.88    4991 1285.92  5013.5 1283.32  5022.5 1285.53
  5035.5  1291.7  5056.7 1292.92  5075.9 1293.33  5139.3 1291.28  5215.6 1293.65
  5272.3 1299.24  5324.2 1300.13  5374.1 1303.35  5478.4 1311.92  5494.6 1315.64
  5538.4 1320.92  5554.7 1326.01  5620.4 1337.64  5702.3 1346.98    5738 1347.88
#Mann= 9 ,-1 , 0
  4283.9     .07       0  4431.6    .035       0  4903.7     .07       0
  4944.3     .05       0  4980.9     .07       0  5056.7    .035       0
  5075.9     .07       0  5324.2     .12       0  5374.1     .07       0
Bank Sta=4944.3,4980.9
XS Rating Curve= 0 ,0
Exp/Cntr=0.3,0.1

Type RM Length L Ch R = 1 ,61851   ,571,571,571
BEGIN DESCRIPTION:
CURRY CREEK 99.0
END DESCRIPTION:
XS GIS Cut Line= 3
      2104575.01     13895075.01        2104225.       13894825.
      2103425.03     13894325.02
#Sta/Elev= 30
  4569.9 1326.54    4592 1325.36  4606.8 1320.72  4644.2 1319.56  4685.7 1317.64
  4705.1    1314  4713.7 1310.63  4734.6 1307.61  4749.3 1301.76  4764.1 1298.61
  4838.9 1295.17  4950.9 1292.58  4971.8  1287.6  4989.4 1280.38  4990.3 1279.88
    5026 1280.38  5028.9 1286.47  5071.4 1285.46  5116.1 1289.19  5211.7 1291.83
  5247.7 1290.27  5268.1 1292.52  5318.4 1295.92  5635.1  1300.3  5710.5 1301.68
  5783.6 1311.39  5856.8 1332.67  5879.2 1336.88  5899.2 1340.87  5943.4 1344.66
#Mann= 10 ,-1 , 0
  4569.9     .07       0  4644.2     .12       0  4685.7     .07       0
  4838.9    .035       0  4989.4    .035       0    5026    .035       0
  5116.1     .12       0  5268.1    .035       0  5635.1     .07       0
  5879.2     .12       0
Bank Sta=4989.4,5026
XS Rating Curve= 0 ,0
Exp/Cntr=0.3,0.1

Type RM Length L Ch R = 1 ,61280   ,566,566,566
BEGIN DESCRIPTION:
CURRY CREEK 98.0
END DESCRIPTION:
XS GIS Cut Line= 3
      2104674.98     13894774.97        2104425.       13894325.
      2103724.98     13893924.99
#Sta/Elev= 30
  4485.4 1317.51  4522.1 1316.57  4542.6 1313.44  4602.1 1308.87  4714.2 1304.78
  4805.1 1296.84  4883.5 1293.18  4889.2 1291.71  4926.8 1290.76  4932.7 1286.53
    4943 1285.15  4954.4  1279.4  4986.4 1277.67  4989.8 1276.42  4990.6 1275.92
  5026.4 1276.42  5029.7 1282.96  5057.7 1286.08  5094.4 1285.58  5175.1 1293.07
  5206.7 1293.28  5255.7 1295.88  5590.1 1294.11  5622.1 1294.75  5637.2 1297.11
  5696.2 1315.52  5717.8 1325.11  5739.4    1330  5776.9 1334.43  5806.4 1335.67
#Mann= 7 ,-1 , 0
  4485.4     .07       0  4522.1     .12       0  4805.1     .07       0
  4926.8    .035       0  4989.8    .035       0  5026.4    .035       0
  5590.1     .12       0
Bank Sta=4989.8,5026.4
XS Rating Curve= 0 ,0
Exp/Cntr=0.3,0.1

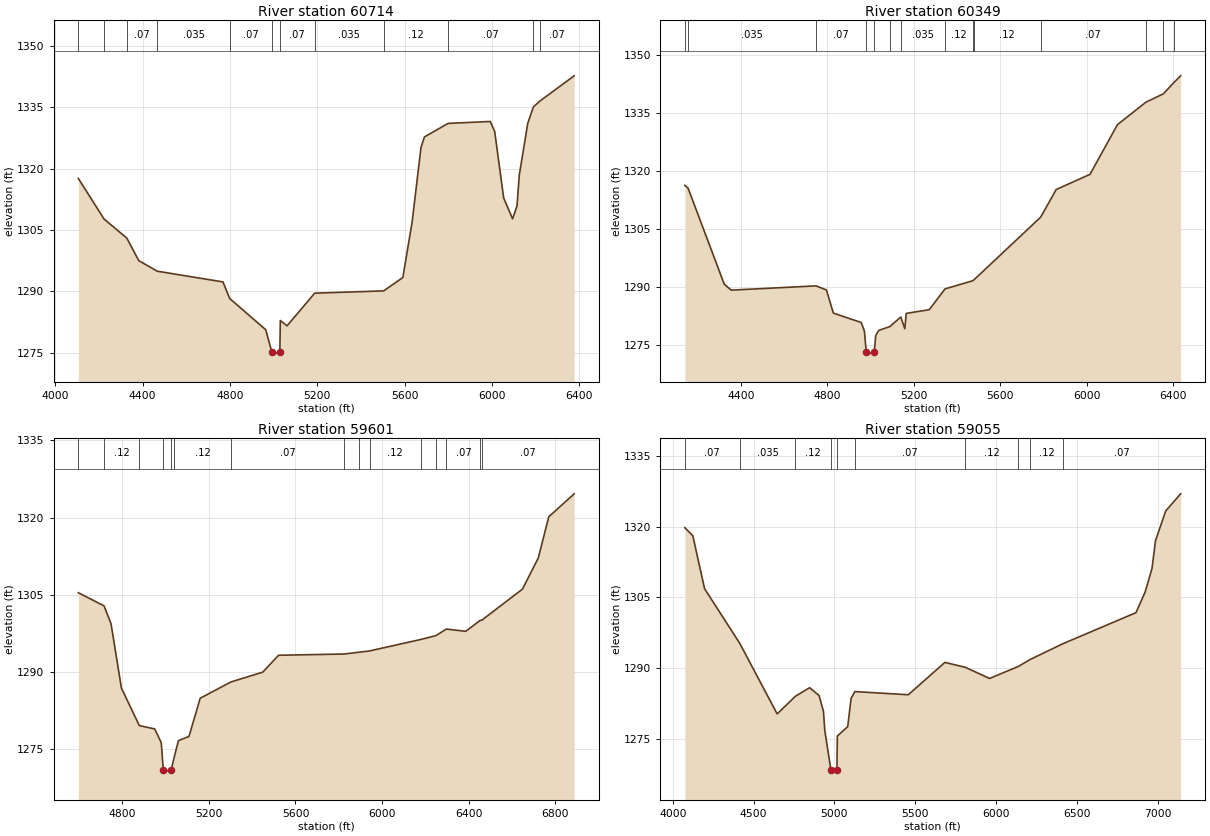
Type RM Length L Ch R = 1 ,60714   ,365,365,365
BEGIN DESCRIPTION:
CURRY CREEK 97.0
END DESCRIPTION:
XS GIS Cut Line= 3
      2104974.98     13894624.96        2104575.       13893825.
      2103229.25     13893536.07
#Sta/Elev= 30
  4105.3 1317.58  4223.2 1307.66  4327.5    1303    4382  1297.5  4466.8 1294.92
  4767.7  1292.3  4798.5 1288.25  4963.4 1280.63  4991.6 1275.16  4992.5 1274.66
  5028.2 1275.16  5030.4 1282.87  5061.1 1281.57  5187.9 1289.55  5503.8 1290.11
  5591.5 1293.38  5633.8 1306.84  5674.7 1325.16  5690.3 1327.72    5799 1331.03
  5991.8  1331.5  6012.2 1329.05  6053.2 1312.84  6094.1 1307.71  6114.3 1310.84
  6124.8  1318.4  6163.7 1331.06  6189.4 1335.04  6218.4 1336.46  6376.1 1342.65
#Mann= 12 ,-1 , 0
  4105.3     .07       0  4223.2    .035       0  4327.5     .07       0
  4466.8    .035       0  4798.5     .07       0  4991.6     .05       0
  5028.2     .07       0  5187.9    .035       0  5503.8     .12       0
    5799     .07       0  6189.4     .12       0  6218.4     .07       0
Bank Sta=4991.6,5028.2
XS Rating Curve= 0 ,0
Exp/Cntr=0.3,0.1

Type RM Length L Ch R = 1 ,60349   ,748,748,748
BEGIN DESCRIPTION:
CURRY CREEK 96.0
END DESCRIPTION:
XS GIS Cut Line= 3
      2105174.98     13894424.96      2104858.78     13893624.46
      2103780.63     13892676.53
#Sta/Elev= 30
  4139.4 1316.27  4154.5 1315.59  4322.1 1290.75  4354.4 1289.21  4747.2 1290.31
  4795.2 1289.27  4827.5 1283.28  4956.5 1280.84  4971.1 1278.64  4979.9 1273.17
  4980.8 1272.67    5017 1273.17  5023.5 1277.49  5037.8 1278.81  5089.1  1279.8
  5139.7 1282.27  5158.3 1279.24  5164.9  1283.2  5271.4 1284.15  5344.6 1289.53
  5472.4 1291.63  5478.9 1291.89  5787.6 1308.08  5859.5 1315.22    6016 1319.14
  6143.1 1331.98    6275  1337.8  6355.3 1339.94  6405.1 1342.91  6435.7 1344.61
#Mann= 14 ,-1 , 0
  4139.4     .07       0  4154.5    .035       0  4747.2     .07       0
  4979.9     .05       0    5017     .07       0  5089.1     .07       0
  5139.7    .035       0  5344.6     .12       0  5472.4     .07       0
  5478.9     .12       0  5787.6     .07       0    6275     .12       0
  6355.3     .07       0  6405.1     .12       0
Bank Sta=4979.9,5017
XS Rating Curve= 0 ,0
Exp/Cntr=0.3,0.1

Type RM Length L Ch R = 1 ,59601   ,546,546,546
BEGIN DESCRIPTION:
CURRY CREEK 95.0
END DESCRIPTION:
XS GIS Cut Line= 3
        2105425.     13894324.98        2105475.       13893925.
      2104474.99     13892324.99
#Sta/Elev= 30
  4597.3  1305.4    4716 1302.85  4748.4 1299.36  4796.3 1286.88  4878.9 1279.59
    4950 1278.93  4980.2 1276.27  4989.5 1271.04  4990.5 1270.54  5026.6 1271.04
    5039 1273.26  5059.4 1276.65  5108.3 1277.48  5160.2  1284.9    5302 1288.06
  5449.1 1289.97  5522.2 1293.25  5824.1 1293.49  5894.1 1293.84  5942.4 1294.09
  6178.9 1296.32  6248.5 1297.06  6297.2 1298.34  6386.6  1297.9    6454 1300.05
  6459.4 1300.02  6648.4  1306.1  6721.5 1312.15  6769.9 1320.15  6887.2 1324.62
#Mann= 15 ,-1 , 0
  4597.3    .035       0    4716     .12       0  4878.9    .035       0
  4989.5    .035       0  5026.6    .035       0    5039     .12       0
    5302     .07       0  5824.1     .12       0  5894.1     .07       0
  5942.4     .12       0  6178.9     .07       0  6248.5     .12       0
  6297.2     .07       0    6454     .12       0  6459.4     .07       0
Bank Sta=4989.5,5026.6
XS Rating Curve= 0 ,0
Exp/Cntr=0.3,0.1

Type RM Length L Ch R = 1 ,59055   ,560,560,560
BEGIN DESCRIPTION:
CURRY CREEK 94.0
END DESCRIPTION:
XS GIS Cut Line= 3
      2106474.98     13894424.97        2105925.       13893675.
      2104484.37      13892095.4
#Sta/Elev= 30
  4074.5 1319.79  4124.1 1318.08  4196.8 1306.83  4414.5 1295.23    4646 1280.24
  4759.3    1284  4846.7  1285.8  4905.3 1284.15  4932.4 1280.79  4940.8 1276.69
  4978.6 1268.38  4979.6 1267.88  5015.7 1268.38  5018.4 1275.54  5082.5 1277.54
  5103.5 1283.54  5126.7 1284.98  5457.5 1284.31  5683.9 1291.18  5810.2 1290.13
  5960.2 1287.77  6139.1 1290.33  6211.4 1291.79    6413 1295.13  6866.2 1301.74
    6923 1306.13  6965.5 1311.16  6986.5 1316.96    7050 1323.33  7142.4 1326.97
#Mann= 10 ,-1 , 0
  4074.5     .07       0  4414.5    .035       0  4759.3     .12       0
  4978.6     .05       0  5015.7     .12       0  5126.7     .07       0
  5810.2     .12       0  6139.1     .07       0  6211.4     .12       0
    6413     .07       0
Bank Sta=4978.6,5015.7
XS Rating Curve= 0 ,0
Exp/Cntr=0.3,0.1