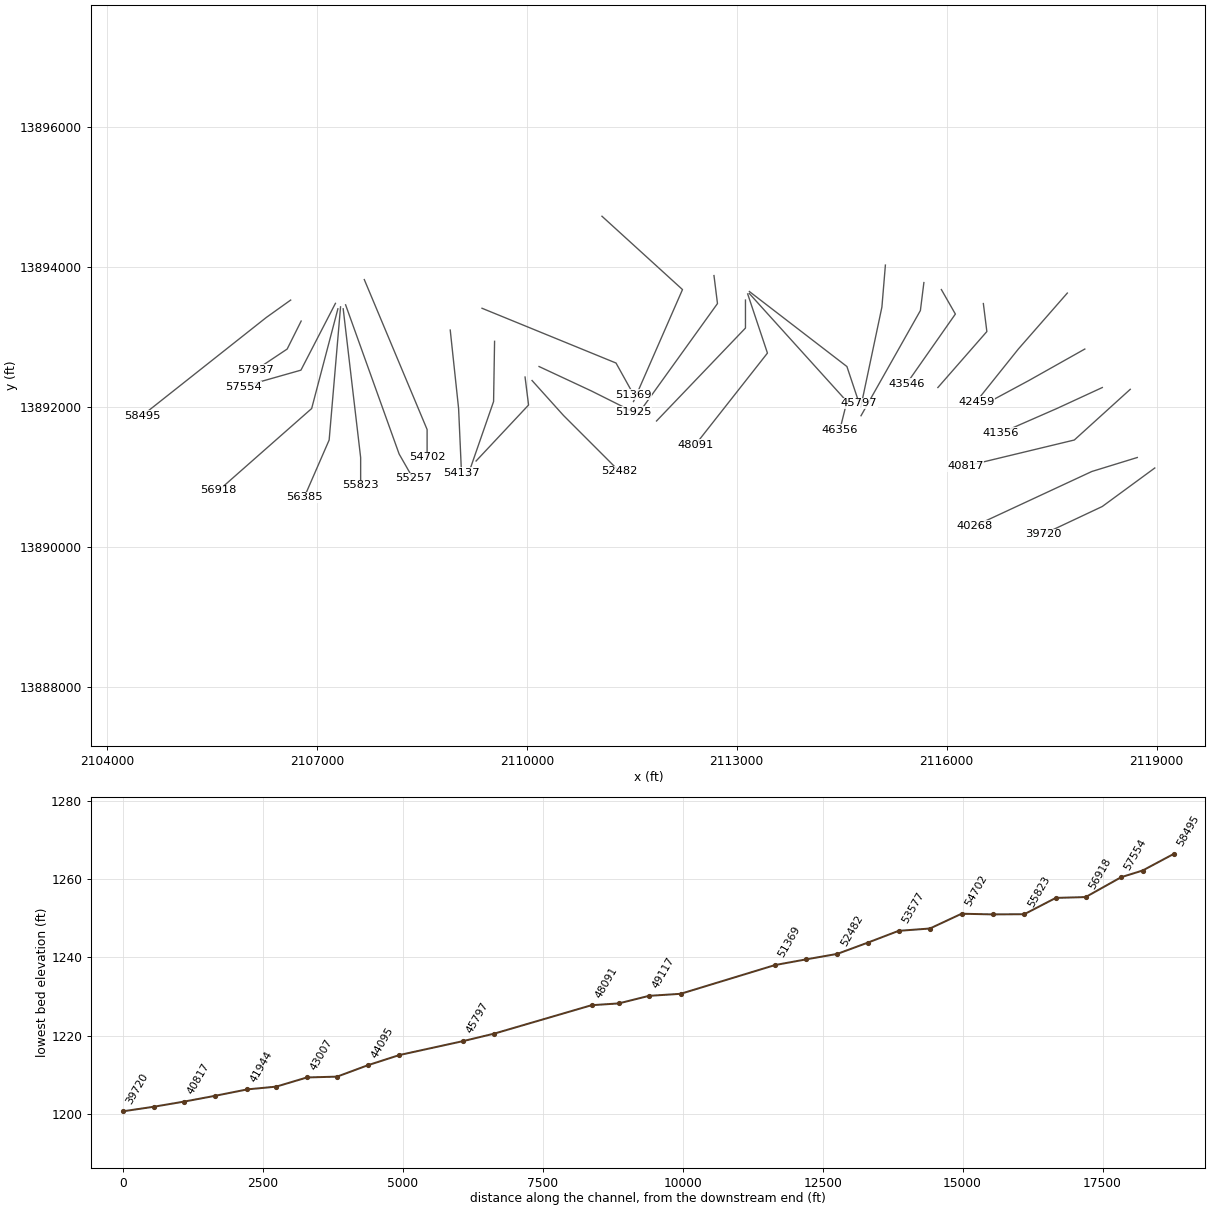
HEC-RAS study CURRY CREEK.prj: CURRY CREEK Base Level Engineering

--- CURRY CREEK.g01 (geometry) --- (continued)

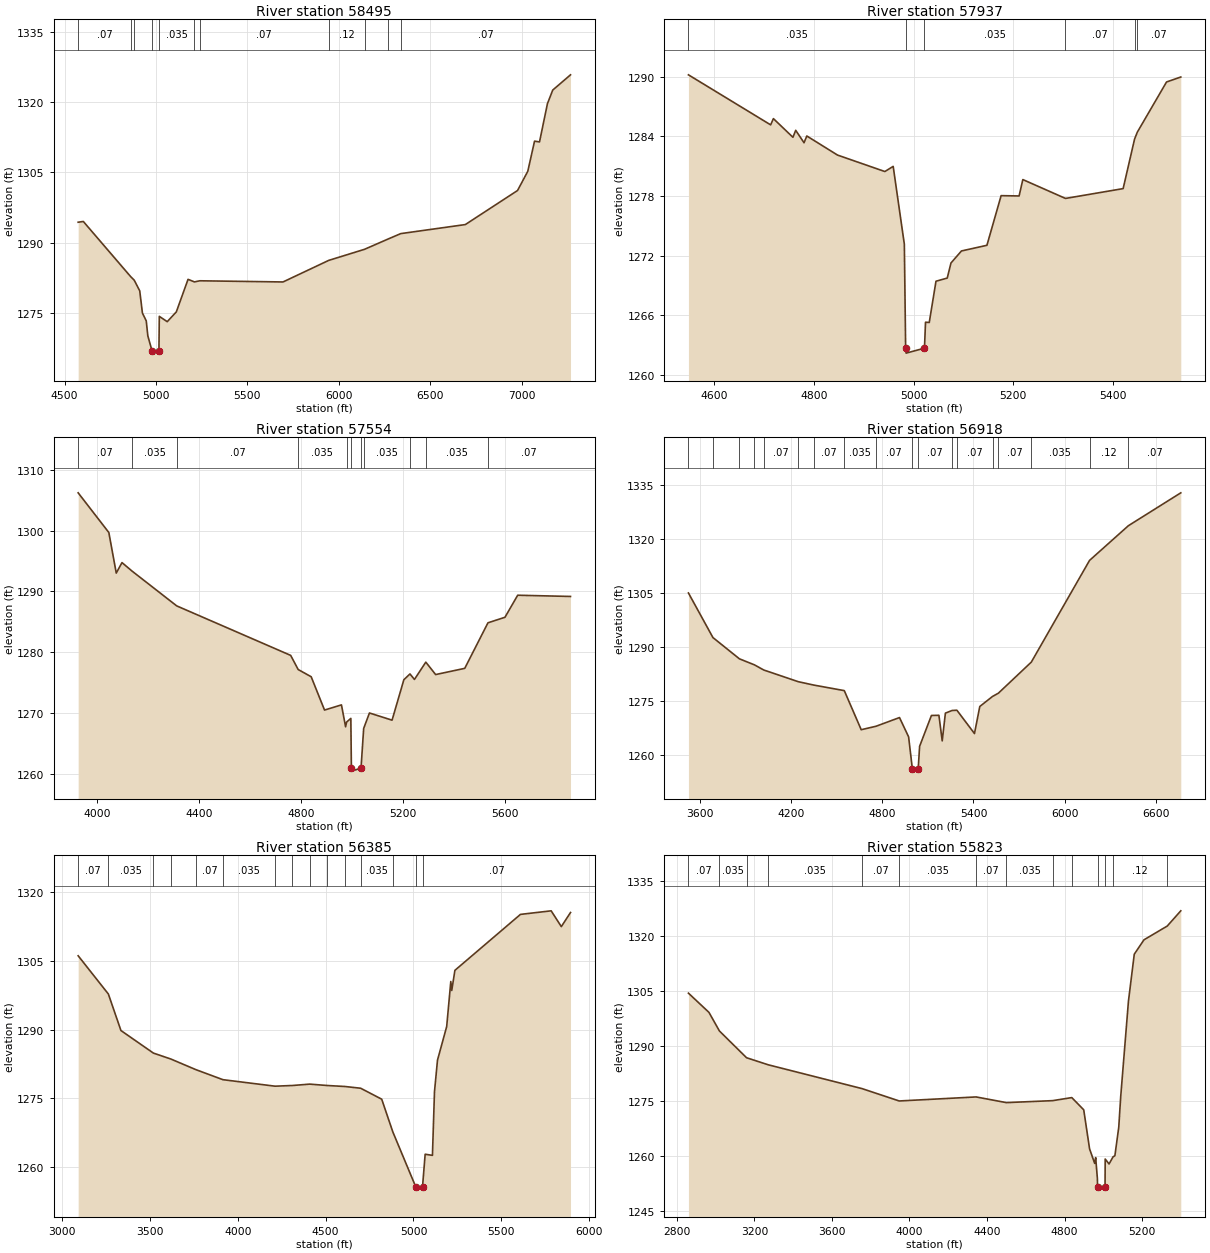
Type RM Length L Ch R = 1 ,58495   ,558,558,558
BEGIN DESCRIPTION:
CURRY CREEK 93.0
END DESCRIPTION:
XS GIS Cut Line= 3
      2106624.98     13893524.99        2106275.       13893275.
      2104500.94     13891871.82
#Sta/Elev= 30
  4574.6 1294.38  4602.8 1294.54  4861.5 1282.78    4881 1282.02  4911.3 1279.73
    4926 1274.99  4946.9 1273.32  4955.5 1270.14  4978.4 1266.94  4979.4 1266.44
  5016.2 1266.94  5018.3 1274.29  5061.6 1273.15  5111.3 1275.24  5175.4 1282.19
  5210.4 1281.64  5239.8 1281.88  5694.7 1281.63  5944.3 1286.23  6140.4  1288.6
  6271.3 1290.83  6338.5 1291.95  6691.6 1293.88    6977 1301.15    7033 1305.25
  7069.9 1311.68  7097.1 1311.52  7140.4 1319.68  7169.3 1322.58  7266.6 1325.84
#Mann= 11 ,-1 , 0
  4574.6     .07       0  4861.5     .12       0    4881     .07       0
  4978.4    .035       0  5016.2    .035       0  5210.4    .035       0
  5239.8     .07       0  5944.3     .12       0  6140.4     .07       0
  6271.3     .12       0  6338.5     .07       0
Bank Sta=4978.4,5016.2
XS Rating Curve= 0 ,0
Exp/Cntr=0.3,0.1

Type RM Length L Ch R = 1 ,57937   ,383,383,383
BEGIN DESCRIPTION:
CURRY CREEK 92.0
END DESCRIPTION:
XS GIS Cut Line= 3
      2106775.02     13893225.04        2106575.       13892825.
      2106124.99       13892525.
#Sta/Elev= 30
  4548.1 1290.21  4713.1 1285.17  4718.6  1285.8  4757.8 1283.92  4763.4 1284.62
  4780.1 1283.37  4785.7 1284.05  4847.2 1282.13  4942.3 1280.47    4959 1280.99
  4981.4 1273.15    4984 1262.68    4985 1262.18  5021.8 1262.68  5023.9 1265.29
  5031.4 1265.27  5044.9 1269.42  5067.5 1269.74    5075 1271.26    5096 1272.47
  5147.1 1273.04  5175.6 1278.04  5211.7 1278.01  5219.2 1279.66  5304.8 1277.76
  5420.5 1278.75  5443.4 1283.73  5448.9 1284.43  5507.6 1289.49  5536.2 1289.99
#Mann= 6 ,-1 , 0
  4548.1    .035       0    4984    .035       0  5021.8    .035       0
  5304.8     .07       0  5443.4     .12       0  5448.9     .07       0
Bank Sta=4984,5021.8
XS Rating Curve= 0 ,0
Exp/Cntr=0.3,0.1

Type RM Length L Ch R = 1 ,57554   ,636,636,636
BEGIN DESCRIPTION:
CURRY CREEK 91.0
END DESCRIPTION:
XS GIS Cut Line= 3
      2107264.83     13893477.91      2106771.66     13892523.28
      2105945.48     13892288.84
#Sta/Elev= 30
  3925.5 1306.19    4046 1299.67  4075.1 1293.01  4097.6 1294.73  4137.6 1293.32
  4312.5 1287.62    4760 1279.49  4789.4 1277.17  4840.5 1275.98  4892.9 1270.51
  4959.4 1271.36  4975.6 1267.76  4979.6 1268.54  4996.2 1269.14  4998.4 1260.98
  4999.4 1260.48  5036.2 1260.98  5046.6 1267.49  5069.3 1270.03  5158.1 1268.85
  5204.4 1275.49  5228.4 1276.44    5246 1275.54  5290.6 1278.38  5329.2 1276.34
  5443.5 1277.36  5534.6 1284.84  5601.4 1285.75  5651.4 1289.37  5858.8 1289.17
#Mann= 11 ,-1 , 0
  3925.5     .07       0  4137.6    .035       0  4312.5     .07       0
  4789.4    .035       0  4979.6     .07       0  4998.4     .05       0
  5036.2     .07       0  5046.6    .035       0  5228.4     .07       0
  5290.6    .035       0  5534.6     .07       0
Bank Sta=4998.4,5036.2
XS Rating Curve= 0 ,0
Exp/Cntr=0.3,0.1

Type RM Length L Ch R = 1 ,56918   ,533,533,533
BEGIN DESCRIPTION:
CURRY CREEK 90.0
END DESCRIPTION:
XS GIS Cut Line= 3
      2107300.01     13893400.04        2106925.       13891975.
      2105596.22     13890804.43
#Sta/Elev= 30
  3521.8 1304.93  3683.3 1292.53  3857.8 1286.62    3957 1284.94  4017.8 1283.52
  4245.7 1280.26  4348.3 1279.32  4548.8 1277.78  4660.3 1266.91  4758.4 1267.88
  4912.6 1270.29  4972.6 1264.93  4997.7  1255.9  4998.7  1255.4  5035.6  1255.9
  5045.2 1262.31    5123 1270.87  5172.3 1270.92  5194.1 1263.81    5215 1271.52
  5259.1 1272.26  5290.8 1272.33  5406.6 1265.85  5441.7 1273.37  5525.5 1276.16
  5564.2 1277.07  5781.2 1285.71  6164.9 1313.98  6420.6 1323.62  6766.2 1332.77
#Mann= 18 ,-1 , 0
  3521.8     .07       0  3683.3    .035       0  3857.8     .07       0
    3957    .035       0  4017.8     .07       0  4245.7    .035       0
  4348.3     .07       0  4548.8    .035       0  4758.4     .07       0
  4997.7     .05       0  5035.6     .07       0  5259.1    .035       0
  5290.8     .07       0  5525.5    .035       0  5564.2     .07       0
  5781.2    .035       0  6164.9     .12       0  6420.6     .07       0
Bank Sta=4997.7,5035.6
XS Rating Curve= 0 ,0
Exp/Cntr=0.3,0.1

Type RM Length L Ch R = 1 ,56385   ,562,562,562
BEGIN DESCRIPTION:
CURRY CREEK 89.0
END DESCRIPTION:
XS GIS Cut Line= 3
      2107337.88     13893427.82        2107175.       13891525.
      2106817.89     13890704.63
#Sta/Elev= 30
  3090.2 1306.17  3262.2 1297.82  3333.9 1289.84  3518.8 1284.91  3617.8 1283.62
  3760.3  1281.3  3914.8  1279.1  4211.7 1277.68  4310.7 1277.83  4409.7 1278.13
  4508.7 1277.83  4610.3 1277.61  4699.5 1277.23  4819.2 1274.84  4882.8 1267.67
  5013.2 1255.69  5014.2 1255.19  5051.7 1255.69  5066.7 1262.81  5108.2 1262.57
  5119.9  1276.5    5137 1283.37  5189.4 1290.72  5212.8 1300.55  5218.2 1298.59
  5236.2 1302.99  5609.5 1315.21  5784.5 1315.99  5842.3 1312.54  5894.7 1315.62
#Mann= 15 ,-1 , 0
  3090.2     .07       0  3262.2    .035       0  3518.8     .07       0
  3617.8    .035       0  3760.3     .07       0  3914.8    .035       0
  4211.7     .07       0  4310.7    .035       0  4409.7     .07       0
  4508.7    .035       0  4610.3     .07       0  4699.5    .035       0
  4882.8     .07       0  5013.2     .05       0  5051.7     .07       0
Bank Sta=5013.2,5051.7
XS Rating Curve= 0 ,0
Exp/Cntr=0.3,0.1

Type RM Length L Ch R = 1 ,55823   ,566,566,566
BEGIN DESCRIPTION:
CURRY CREEK 88.0
END DESCRIPTION:
XS GIS Cut Line= 3
      2107375.72     13893400.19        2107625.       13891275.
        2107625.     13890874.96
#Sta/Elev= 30
  2859.8 1304.43  2965.7 1299.19  3019.7 1294.12  3159.6 1286.83  3271.9  1284.9
  3754.5 1278.43  3947.2 1275.05  4343.8 1276.15    4500  1274.6  4738.6 1275.14
  4837.3 1275.97  4898.9 1272.64  4929.1 1261.98  4955.4 1258.05  4960.5 1259.62
  4969.4 1253.88  4970.2 1251.53  4971.2 1251.03  5008.8 1251.53  5009.6 1259.23
  5029.6 1257.88  5050.1 1259.83  5059.6 1260.13  5079.6 1267.89  5089.6  1276.2
  5129.6 1302.25  5159.6 1315.04  5209.6 1318.96  5329.6 1322.71  5399.6 1326.86
#Mann= 14 ,-1 , 0
  2859.8     .07       0  3019.7    .035       0  3159.6     .07       0
  3271.9    .035       0  3754.5     .07       0  3947.2    .035       0
  4343.8     .07       0    4500    .035       0  4738.6     .07       0
  4837.3    .035       0  4970.2    .035       0  5008.8    .035       0
  5050.1     .12       0  5329.6     .07       0
Bank Sta=4970.2,5008.8
XS Rating Curve= 0 ,0
Exp/Cntr=0.3,0.1

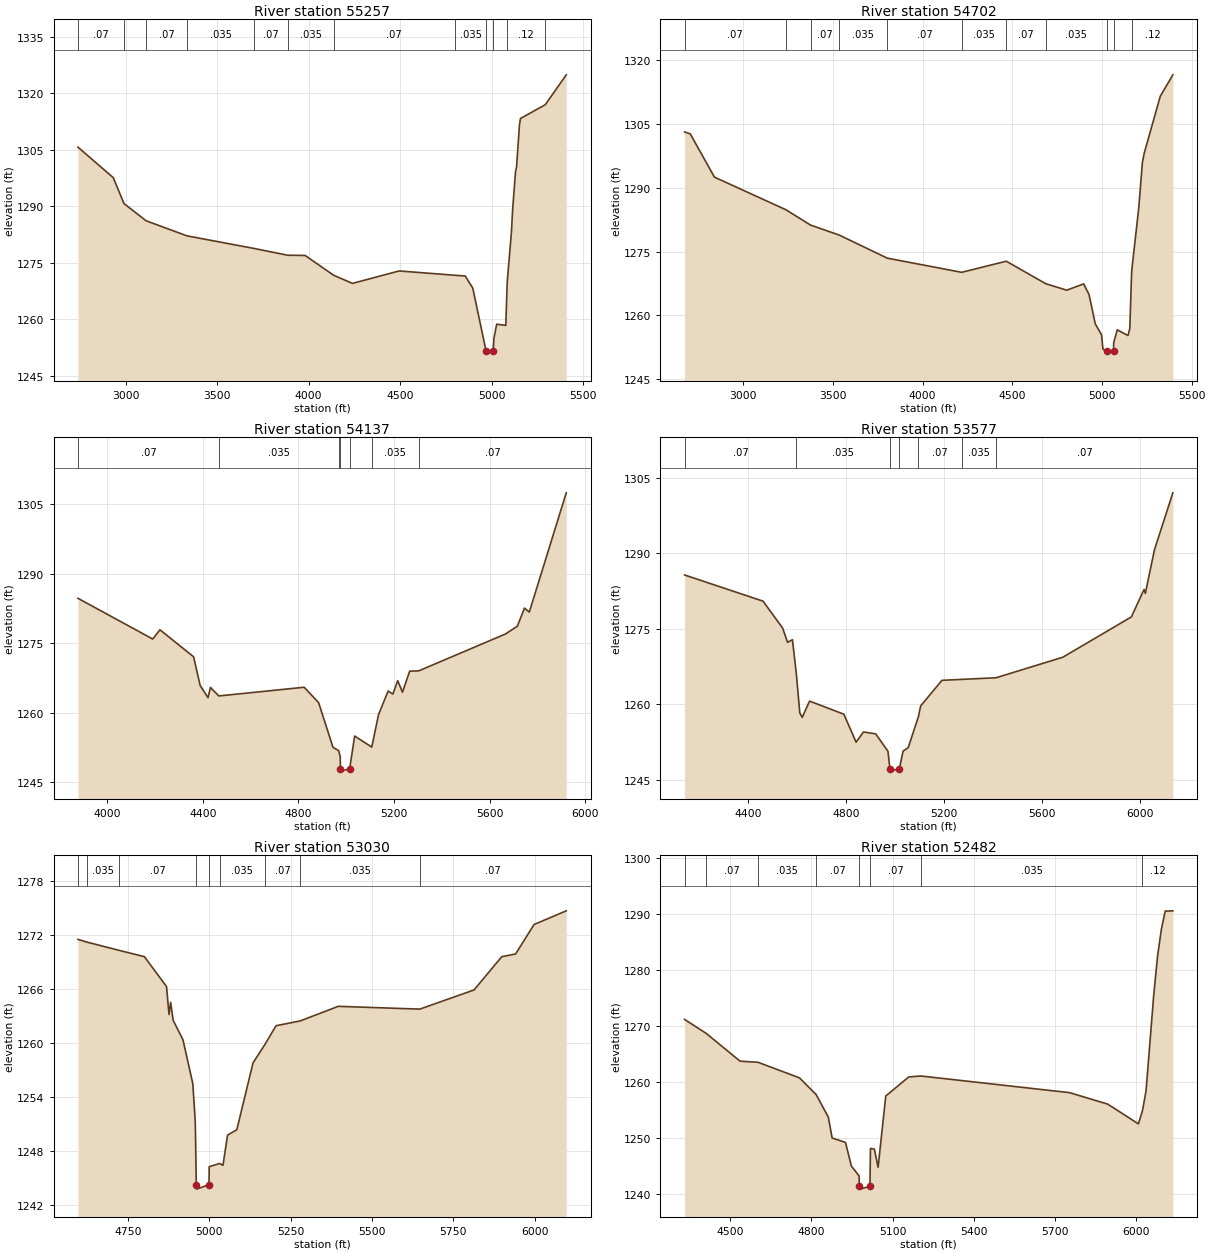
Type RM Length L Ch R = 1 ,55257   ,555,555,555
BEGIN DESCRIPTION:
CURRY CREEK 87.0
END DESCRIPTION:
XS GIS Cut Line= 3
      2107410.15      13893456.7        2108175.       13891325.
      2108375.01     13890974.98
#Sta/Elev= 30
  2739.4 1305.67  2932.4 1297.56    2991 1290.69  3111.7 1286.12  3334.5 1282.12
    3703 1278.76  3885.6 1276.97  3980.8 1276.91  4136.2 1271.66  4239.2 1269.49
  4494.2  1272.8  4798.7 1271.65  4855.4 1271.46  4896.6 1268.24  4969.5 1251.48
  4970.5 1250.98  5008.1 1251.48  5012.1 1254.89  5027.2 1258.66  5076.9 1258.35
  5081.3 1264.75  5084.8 1269.84  5107.8 1283.11  5114.3 1289.07  5130.1 1299.09
  5135.9 1300.44  5151.7 1311.58  5157.5 1313.29  5292.7 1316.93  5407.3 1324.87
#Mann= 12 ,-1 , 0
  2739.4     .07       0    2991    .035       0  3111.7     .07       0
  3334.5    .035       0    3703     .07       0  3885.6    .035       0
  4136.2     .07       0  4798.7    .035       0  4969.5    .035       0
  5008.1    .035       0  5081.3     .12       0  5292.7     .07       0
Bank Sta=4969.5,5008.1
XS Rating Curve= 0 ,0
Exp/Cntr=0.3,0.1

Type RM Length L Ch R = 1 ,54702   ,565,565,565
BEGIN DESCRIPTION:
CURRY CREEK 86.0
END DESCRIPTION:
XS GIS Cut Line= 3
      2107677.28     13893817.68        2108575.       13891675.
        2108575.     13891275.04
#Sta/Elev= 30
  2672.1 1303.13  2703.6 1302.69  2838.7 1292.51  3236.9 1284.85  3374.8 1281.24
  3534.2  1278.9  3802.6 1273.47  4217.3 1270.14  4466.3 1272.75  4686.1 1267.47
  4803.3 1265.94  4897.7 1267.42  4927.7 1264.92  4962.7 1258.02  4997.7 1255.44
  5005.2 1252.07  5025.9 1251.65  5026.9 1251.15  5064.5 1251.65  5065.2 1253.58
  5085.2 1256.62  5145.2 1255.28  5155.2 1256.98  5165.2 1270.07  5168.1 1271.39
  5205.2 1285.37  5225.2 1295.92  5235.2 1298.09  5325.2 1311.53  5395.2 1316.55
#Mann= 11 ,-1 , 0
  2672.1     .07       0  3236.9    .035       0  3374.8     .07       0
  3534.2    .035       0  3802.6     .07       0  4217.3    .035       0
  4466.3     .07       0  4686.1    .035       0  5025.9    .035       0
  5064.5    .035       0  5168.1     .12       0
Bank Sta=5025.9,5064.5
XS Rating Curve= 0 ,0
Exp/Cntr=0.3,0.1

Type RM Length L Ch R = 1 ,54137   ,560,560,560
BEGIN DESCRIPTION:
CURRY CREEK 85.0
END DESCRIPTION:
XS GIS Cut Line= 3
      2108905.57     13893096.11        2109025.       13891975.
      2109066.15     13891060.58
#Sta/Elev= 30
  3877.4 1284.67  4190.3 1275.88  4220.4 1277.88  4361.2 1272.05  4388.8 1265.84
  4421.6 1263.23  4431.6 1265.44  4466.9  1263.6  4823.8 1265.48  4884.2 1262.16
  4944.5  1252.5  4967.9 1251.81  4974.7 1250.48  4975.4 1247.88  4976.4 1247.38
  5014.1 1247.88  5034.9 1254.96  5106.6 1252.56    5135 1259.59    5175 1264.66
    5195 1264.02  5215.1  1266.9  5235.1 1264.41  5265.1 1268.94  5303.3 1269.02
  5665.5 1276.96  5715.6 1278.65  5745.6 1282.57  5765.6 1281.69  5920.2 1307.43
#Mann= 7 ,-1 , 0
  3877.4     .07       0  4466.9    .035       0  4967.9     .07       0
  4975.4     .05       0  5014.1     .07       0  5106.6    .035       0
  5303.3     .07       0
Bank Sta=4975.4,5014.1
XS Rating Curve= 0 ,0
Exp/Cntr=0.3,0.1

Type RM Length L Ch R = 1 ,53577   ,547,547,547
BEGIN DESCRIPTION:
CURRY CREEK 84.0
END DESCRIPTION:
XS GIS Cut Line= 3
      2109539.24     13892935.56        2109525.       13892075.
      2109152.97     13891004.16
#Sta/Elev= 30
  4139.4 1285.69    4460 1280.49    4540 1275.15    4560 1272.32    4580 1272.85
  4596.1 1266.01    4610 1258.34    4620 1257.45    4650 1260.67    4790 1258.07
  4840.1 1252.52  4870.1 1254.55  4920.1 1254.17  4970.1 1250.72  4978.2 1247.28
  4979.2 1246.78  5016.9 1247.28  5031.8 1250.73    5053 1251.46  5094.4 1257.57
  5103.7 1259.71  5190.6 1264.79  5272.4 1264.98  5411.5  1265.3  5684.3 1269.37
  5964.3 1277.37    6016 1282.81  6021.3 1282.04  6058.7 1290.71  6133.7 1301.98
#Mann= 7 ,-1 , 0
  4139.4     .07       0  4596.1    .035       0  4978.2    .035       0
  5016.9    .035       0  5094.4     .07       0  5272.4    .035       0
  5411.5     .07       0
Bank Sta=4978.2,5016.9
XS Rating Curve= 0 ,0
Exp/Cntr=0.3,0.1

Type RM Length L Ch R = 1 ,53030   ,548,548,548
BEGIN DESCRIPTION:
CURRY CREEK 83.0
END DESCRIPTION:
XS GIS Cut Line= 3
        2109975.       13892425.        2110025.       13892025.
        2109275.       13891225.
#Sta/Elev= 30
  4597.1 1271.51  4624.7 1271.21  4723.7 1270.29  4801.2 1269.59  4869.2 1266.27
  4876.8 1263.17  4881.8 1264.52  4889.4 1262.54  4919.6 1260.37  4949.8 1255.51
  4957.4 1251.31  4960.6 1244.29  4961.6 1243.79  4999.5 1244.29  5000.2 1246.28
  5032.4 1246.64  5042.5 1246.43  5056.6 1249.79    5085 1250.38  5134.8  1257.8
  5171.2 1259.84  5205.6 1261.93  5279.7 1262.46  5396.6 1264.08    5647 1263.77
  5813.7  1265.9  5898.7 1269.59  5941.2 1269.89  5997.9 1273.16  6096.8 1274.68
#Mann= 9 ,-1 , 0
  4597.1     .07       0  4624.7    .035       0  4723.7     .07       0
  4960.6     .05       0  4999.5     .07       0  5032.4    .035       0
  5171.2     .07       0  5279.7    .035       0    5647     .07       0
Bank Sta=4960.6,4999.5
XS Rating Curve= 0 ,0
Exp/Cntr=0.3,0.1

Type RM Length L Ch R = 1 ,52482   ,557,557,557
BEGIN DESCRIPTION:
CURRY CREEK 82.0
END DESCRIPTION:
XS GIS Cut Line= 3
      2110074.99     13892375.01        2110525.       13891875.
      2111325.03     13891074.97
#Sta/Elev= 30
  4331.7 1271.17  4410.8 1268.71  4536.9 1263.72  4602.7 1263.53  4756.6 1260.74
  4817.8 1257.77  4862.8 1253.75    4877 1250.02  4926.3 1249.23    4948 1245.02
  4976.4 1243.27  4977.8  1241.4  4978.8  1240.9  5016.7  1241.4  5018.5 1248.16
  5032.7 1248.05  5046.8  1244.8  5075.1 1257.51    5160 1260.91  5204.7 1261.08
  5753.9 1258.11  5895.3 1256.06  6008.5 1252.54  6023.6 1254.89  6036.8 1258.46
    6065 1275.44  6079.2  1282.4  6093.3 1287.23  6107.5 1290.49  6135.8 1290.54
#Mann= 8 ,-1 , 0
  4331.7    .035       0  4410.8     .07       0  4602.7    .035       0
  4817.8     .07       0  4977.8     .05       0  5016.7     .07       0
  5204.7    .035       0  6023.6     .12       0
Bank Sta=4977.8,5016.7
XS Rating Curve= 0 ,0
Exp/Cntr=0.3,0.1

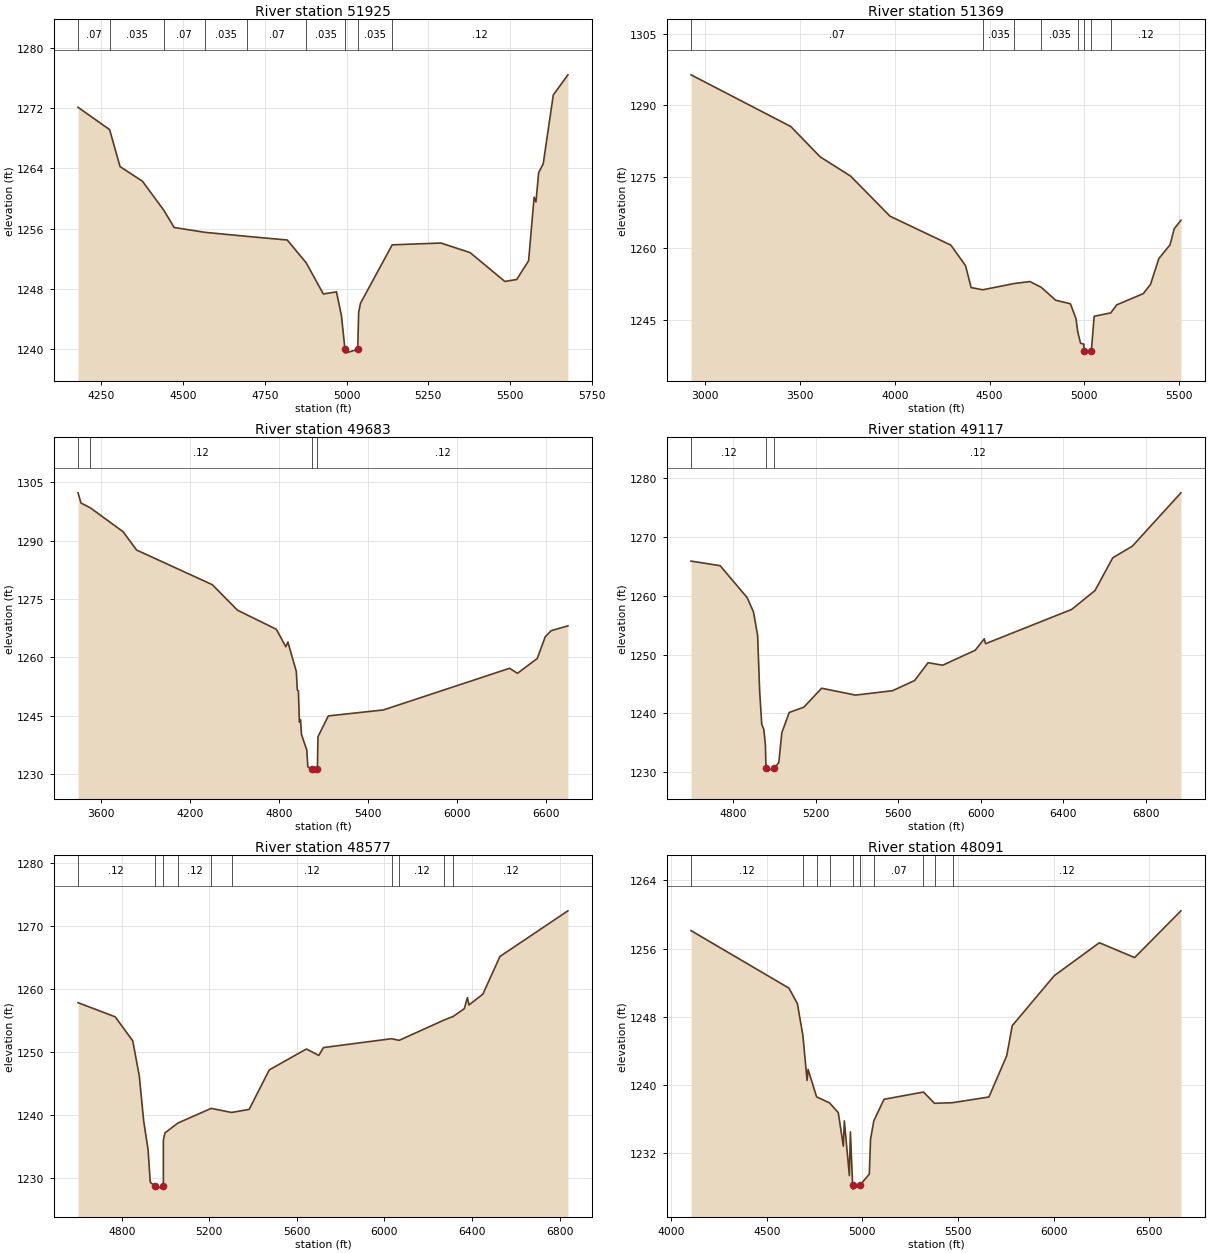
Type RM Length L Ch R = 1 ,51925   ,556,556,556
BEGIN DESCRIPTION:
CURRY CREEK 81.0
END DESCRIPTION:
XS GIS Cut Line= 3
      2110174.97     13892575.01        2110925.       13892225.
        2111525.       13891925.
#Sta/Elev= 30
  4178.6 1272.08  4275.2 1269.12  4307.1 1264.22  4375.7 1262.28  4440.9 1258.44
  4472.6 1256.15  4566.4 1255.51  4696.4 1254.97  4818.7 1254.49  4876.5 1251.47
    4929 1247.34  4969.2 1247.62  4984.2 1244.49  4995.2    1240  4996.2  1239.5
  5034.1    1240    5037 1244.89  5042.6 1246.11  5139.6 1253.85  5288.6 1254.09
    5378 1252.82  5484.2    1249  5520.6 1249.26  5556.9 1251.75  5573.7 1260.16
  5579.3 1259.54  5587.7 1263.41  5601.6 1264.59  5632.4 1273.72  5677.1 1276.38
#Mann= 9 ,-1 , 0
  4178.6     .07       0  4275.2    .035       0  4440.9     .07       0
  4566.4    .035       0  4696.4     .07       0  4876.5    .035       0
  4995.2    .035       0  5034.1    .035       0  5139.6     .12       0
Bank Sta=4995.2,5034.1
XS Rating Curve= 0 ,0
Exp/Cntr=0.3,0.1

Type RM Length L Ch R = 1 ,51369   ,1686,1686,1686
BEGIN DESCRIPTION:
CURRY CREEK 80.0
END DESCRIPTION:
XS GIS Cut Line= 3
      2109359.81      13893407.7        2111275.       13892625.
      2111524.99     13892175.03
#Sta/Elev= 30
  2925.2 1296.41  3451.3 1285.57  3606.2 1279.21  3766.5 1275.18  3974.9 1266.76
  4295.5  1260.7    4373 1256.39  4402.4  1251.8  4463.5 1251.33  4630.5 1252.65
  4712.2 1253.06  4772.3 1251.85  4848.5 1249.14    4926  1248.4  4955.4 1245.28
    4965 1242.46  4979.4 1240.14    4997 1239.92  4997.4 1238.55  4998.4 1238.05
  5036.6 1238.55  5051.3 1245.78  5138.9 1246.49  5170.3 1248.17    5311 1250.54
  5348.8  1252.5  5392.2 1257.86  5451.7 1260.78  5473.5 1264.13  5508.9 1265.92
#Mann= 8 ,-1 , 0
  2925.2     .07       0  4463.5    .035       0  4630.5     .07       0
  4772.3    .035       0    4965     .07       0  4997.4     .05       0
  5036.6     .07       0  5138.9     .12       0
Bank Sta=4997.4,5036.6
XS Rating Curve= 0 ,0
Exp/Cntr=0.3,0.1

Type RM Length L Ch R = 1 ,49683   ,566,566,566
BEGIN DESCRIPTION:
CURRY CREEK 79.0
END DESCRIPTION:
XS GIS Cut Line= 3
      2111074.23     13894722.78        2112225.       13893675.
      2111525.01     13892075.03
#Sta/Elev= 30
  3443.8 1302.28    3464 1299.65  3527.3 1298.41  3747.1 1292.29    3839 1287.56
  4349.1 1278.66  4518.7  1272.1  4780.9 1267.18  4844.4 1262.69  4858.6  1263.9
  4915.3 1256.37  4922.1 1251.58  4929.5 1251.32  4936.3 1243.31  4943.7 1243.95
  4950.5 1240.12  4986.3 1236.12    4993 1231.82  5018.1 1231.21  5019.1 1230.71
  5057.7 1231.21  5061.3 1239.55  5131.1 1244.91  5502.2 1246.44  6353.6 1257.16
  6406.2 1255.86  6539.5 1259.67  6593.7 1265.26  6633.1 1266.83  6746.5 1268.07
#Mann= 4 ,-1 , 0
  3443.8    .035       0  3527.3     .12       0  5018.1     .05       0
  5057.7     .12       0
Bank Sta=5018.1,5057.7
XS Rating Curve= 0 ,0
Exp/Cntr=0.3,0.1

Type RM Length L Ch R = 1 ,49117   ,540,540,540
BEGIN DESCRIPTION:
CURRY CREEK 78.0
END DESCRIPTION:
XS GIS Cut Line= 3
        2112675.     13893874.98        2112725.       13893475.
        2111575.     13891874.99
#Sta/Elev= 30
  4596.9 1265.94    4738 1265.16    4869 1259.71  4899.2 1257.31  4919.4 1253.31
  4929.4 1243.77  4939.5 1238.16  4949.6 1237.27  4957.2 1234.61    4960 1230.69
    4961 1230.19  4999.6 1230.69  5022.1 1231.63  5036.8 1236.73  5072.4 1240.17
  5143.6 1241.08  5229.6  1244.3  5394.1 1243.13  5573.3 1243.88  5680.1 1245.61
  5745.2 1248.64  5816.4 1248.22  5973.5 1250.76  6017.7 1252.71  6023.9 1251.88
  6440.8 1257.71  6554.2 1260.93  6640.2  1266.5  6734.7 1268.47  6970.4 1277.56
#Mann= 3 ,-1 , 0
  4596.9     .12       0    4960     .05       0  4999.6     .12       0
Bank Sta=4960,4999.6
XS Rating Curve= 0 ,0
Exp/Cntr=0.3,0.1

Type RM Length L Ch R = 1 ,48577   ,486,486,486
BEGIN DESCRIPTION:
CURRY CREEK 77.0
END DESCRIPTION:
XS GIS Cut Line= 3
        2113125.     13893525.01        2113125.       13893125.
      2111853.88     13891796.87
#Sta/Elev= 30
    4600 1257.86    4770 1255.61    4850  1251.8    4880  1246.2    4900 1239.07
    4920 1234.53    4930 1229.37  4950.2 1228.76  4951.2 1228.26  4989.8 1228.76
    4990 1236.06  4997.5  1237.2  5056.8 1238.76  5208.7 1241.08  5301.3 1240.43
    5382 1240.92  5473.8 1247.19  5643.6 1250.51  5700.2 1249.48  5721.3 1250.73
  6032.4 1252.14  6067.4 1251.88  6274.3 1255.13  6314.6 1255.68  6365.1 1256.91
  6379.2 1258.66  6386.2  1257.5    6450 1259.22  6527.7 1265.19  6838.4 1272.44
#Mann= 10 ,-1 , 0
    4600     .12       0  4950.2     .05       0  4989.8     .12       0
  5056.8     .12       0  5208.7    .035       0  5301.3     .12       0
  6032.4     .07       0  6067.4     .12       0  6274.3     .07       0
  6314.6     .12       0
Bank Sta=4950.2,4989.8
XS Rating Curve= 0 ,0
Exp/Cntr=0.3,0.1

Type RM Length L Ch R = 1 ,48091   ,1735,1735,1735
BEGIN DESCRIPTION:
Curry Creek 76.0
END DESCRIPTION:
XS GIS Cut Line= 3
      2113156.73     13893612.46      2113439.22     13892767.21
      2112406.65     13891454.57
#Sta/Elev= 30
  4104.1  1258.1    4616 1251.36  4660.2 1249.54  4688.7 1245.83  4710.8 1240.54
    4716 1241.83  4760.6 1238.61  4828.3 1237.91    4874 1236.76  4900.3 1232.84
  4905.6  1235.8  4931.9  1229.4  4937.2 1234.51  4948.9  1228.3  4949.9  1227.8
  4988.5  1228.3  5036.2 1229.56  5042.6 1233.64  5059.6  1235.8  5113.1 1238.33
  5319.4 1239.18    5377 1237.86  5471.6 1237.93  5661.6  1238.6  5754.7 1243.44
  5783.6 1246.96  6003.2 1252.82    6239 1256.68  6423.4 1254.94  6665.4 1260.42
#Mann= 10 ,-1 , 0
  4104.1     .12       0  4688.7     .07       0  4760.6    .035       0
  4828.3     .07       0  4948.9    .035       0  4988.5     .07       0
  5059.6     .07       0  5319.4     .12       0    5377     .07       0
  5471.6     .12       0
Bank Sta=4948.9,4988.5
XS Rating Curve= 0 ,0
Exp/Cntr=0.3,0.1

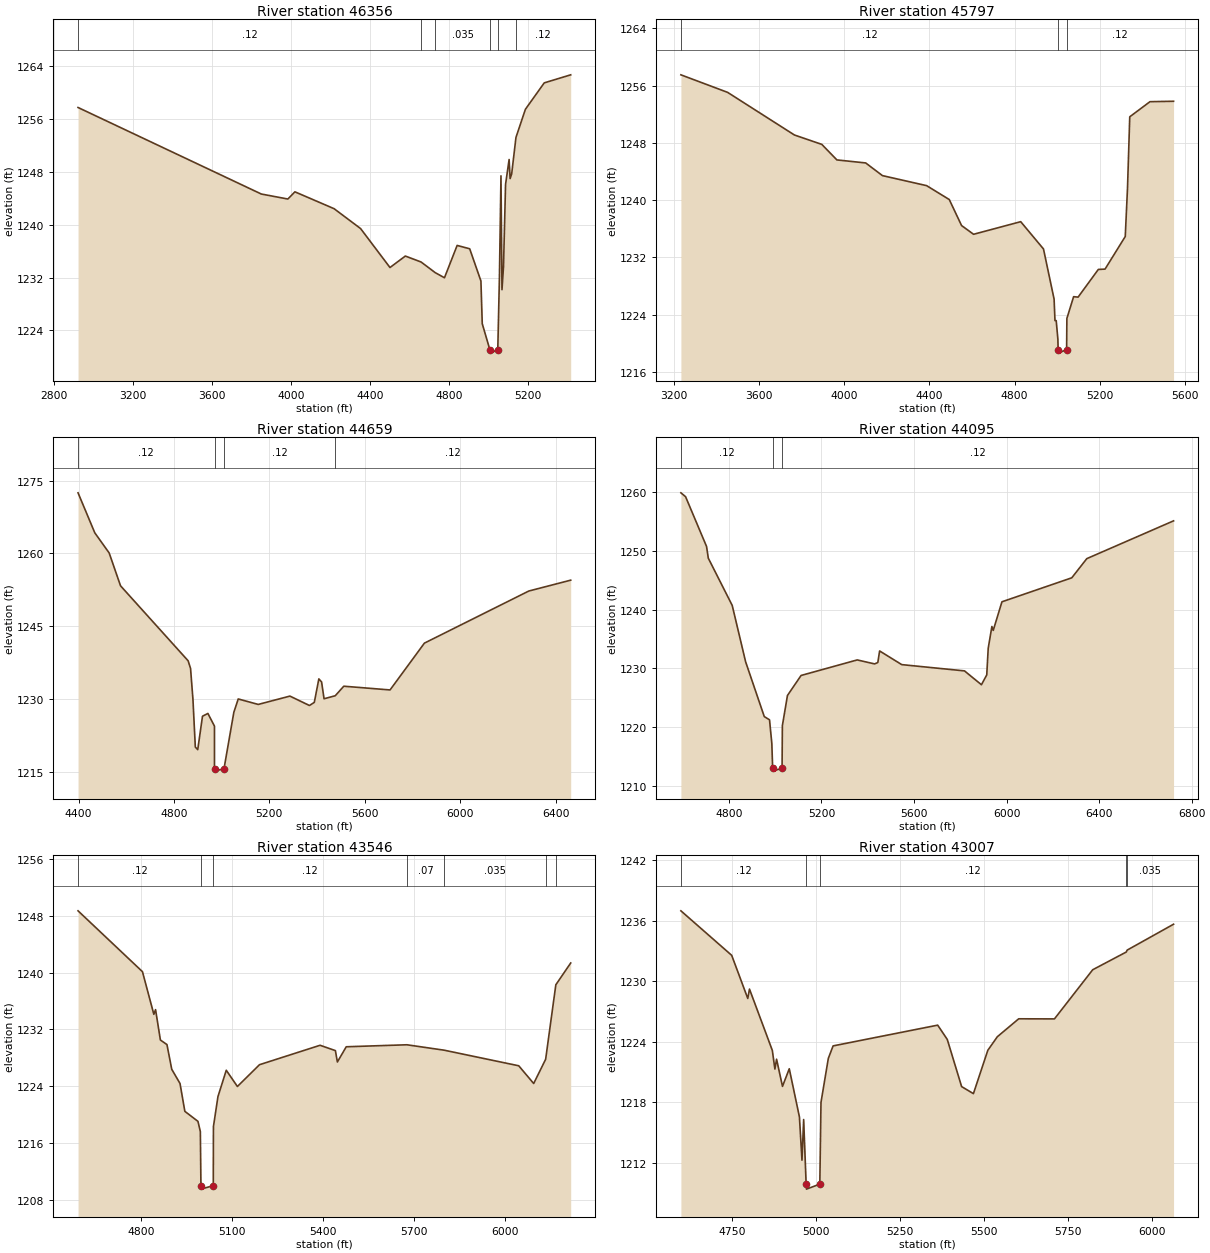
Type RM Length L Ch R = 1 ,46356   ,559,559,559
BEGIN DESCRIPTION:
CURRY CREEK 75.0
END DESCRIPTION:
XS GIS Cut Line= 3
      2113179.23     13893619.56        2114575.       13892075.
        2114475.       13891675.
#Sta/Elev= 30
  2923.1 1257.78  3850.7 1244.67  3985.3 1243.91    4021    1245  4219.1 1242.45
  4353.6 1239.43  4502.3 1233.53  4580.1 1235.27  4659.6 1234.37  4731.6 1232.75
  4778.1 1231.98  4842.3 1236.88  4905.9 1236.37  4962.7 1231.49  4969.4 1225.02
  5008.1 1221.06  5009.1 1220.56    5048 1221.06  5056.4 1232.15  5064.2 1247.42
  5069.3 1230.17    5077 1233.68  5087.4 1246.13  5105.4  1249.9  5110.5 1247.01
  5118.3  1247.7  5140.1 1253.25  5187.9 1257.51  5283.2 1261.51  5417.2 1262.73
#Mann= 6 ,-1 , 0
  2923.1     .12       0  4659.6     .07       0  4731.6    .035       0
  5008.1    .035       0    5048    .035       0  5140.1     .12       0
Bank Sta=5008.1,5048
XS Rating Curve= 0 ,0
Exp/Cntr=0.3,0.1

Type RM Length L Ch R = 1 ,45797   ,1138,1138,1138
BEGIN DESCRIPTION:
CURRY CREEK 74.0
END DESCRIPTION:
XS GIS Cut Line= 3
      2113180.81     13893647.29        2114575.       13892575.
      2114750.02     13892049.95
#Sta/Elev= 30
  3233.5 1257.49  3452.8 1255.04  3766.3 1249.09  3894.8 1247.78  3965.7 1245.61
  4100.7 1245.19  4179.5 1243.42  4386.8 1242.02  4493.1 1240.08  4550.8 1236.45
  4607.2 1235.23  4828.4 1236.99  4935.3 1233.18  4985.1 1226.18  4989.2 1223.18
    4995 1223.18  5002.9 1220.57    5004 1219.14    5005 1218.64  5043.9 1219.14
  5045.1 1223.48  5076.7 1226.52  5097.8 1226.46  5192.6 1230.32  5224.3 1230.37
  5319.1 1234.92  5329.7 1241.71  5340.2 1251.63  5435.1 1253.74  5545.8  1253.8
#Mann= 3 ,-1 , 0
  3233.5     .12       0    5004     .05       0  5043.9     .12       0
Bank Sta=5004,5043.9
XS Rating Curve= 0 ,0
Exp/Cntr=0.3,0.1

Type RM Length L Ch R = 1 ,44659   ,564,564,564
BEGIN DESCRIPTION:
CURRY CREEK 73.0
END DESCRIPTION:
XS GIS Cut Line= 3
        2115125.     13894025.02        2115075.       13893425.
      2114772.57     13891993.19
#Sta/Elev= 30
    4398  1272.5  4468.3 1264.24  4528.5 1260.09  4576.1 1253.32  4859.6 1237.84
  4869.7 1236.26  4879.7 1229.93  4889.7 1220.04  4899.8 1219.51  4919.8 1226.41
  4942.4 1226.98    4970 1224.36  4970.1 1215.58  4971.1 1215.08    5010 1215.58
  5051.2 1227.23  5069.6 1229.97  5153.4 1228.84  5286.3 1230.56  5368.1 1228.62
  5388.5 1229.26  5407.6 1234.11  5419.1 1233.48  5429.4 1230.01  5476.2 1230.63
  5512.2  1232.6  5706.1 1231.83  5850.2 1241.49  6287.9 1252.24  6463.5 1254.48
#Mann= 4 ,-1 , 0
    4398     .12       0  4970.1     .05       0    5010     .12       0
  5476.2     .12       0
Bank Sta=4970.1,5010
XS Rating Curve= 0 ,0
Exp/Cntr=0.3,0.1

Type RM Length L Ch R = 1 ,44095   ,549,549,549
BEGIN DESCRIPTION:
CURRY CREEK 72.0
END DESCRIPTION:
XS GIS Cut Line= 3
        2115675.     13893775.01        2115625.       13893375.
      2114776.59     13891871.94
#Sta/Elev= 30
  4592.7 1259.93  4612.9 1259.27  4703.6 1250.78  4711.1 1248.79  4814.4 1240.74
  4872.4 1231.12    4953 1221.78  4975.7 1221.23  4985.7 1217.18  4989.2 1212.98
  4990.2 1212.48  5029.9 1212.98  5031.2 1220.23  5053.2 1225.38  5112.1 1228.79
  5354.7 1231.44  5429.8 1230.76  5443.7    1231  5451.5 1232.97    5547 1230.64
  5818.3 1229.57  5891.5 1227.21  5914.5 1228.89  5920.8 1233.42  5936.7 1237.14
  5942.5 1236.47  5980.1 1241.35  6281.9 1245.44  6346.9 1248.71  6721.8 1255.15
#Mann= 3 ,-1 , 0
  4592.7     .12       0  4989.2     .05       0  5029.9     .12       0
Bank Sta=4989.2,5029.9
XS Rating Curve= 0 ,0
Exp/Cntr=0.3,0.1

Type RM Length L Ch R = 1 ,43546   ,539,539,539
BEGIN DESCRIPTION:
CURRY CREEK 71.0
END DESCRIPTION:
XS GIS Cut Line= 3
      2115925.01     13893674.98        2116125.       13893325.
      2115425.02     13892325.03
#Sta/Elev= 30
  4592.7 1248.67    4805 1240.12  4842.5 1234.13  4848.2 1234.79  4864.1 1230.52
  4885.7 1229.88  4901.5 1226.41  4928.8 1224.41  4944.7  1220.5  4987.9 1219.09
  4995.8 1217.65  4997.7 1210.07  4998.7 1209.57  5038.4 1210.07  5038.9 1218.35
  5053.8 1222.57  5081.2 1226.27  5117.9 1223.99  5190.7 1227.05  5390.3 1229.78
  5440.9 1229.03  5447.4 1227.43  5476.6 1229.57  5676.6 1229.85  5799.3 1229.09
  6045.1  1226.9  6094.4 1224.41  6133.8 1227.81  6167.4 1238.28  6216.4 1241.34
#Mann= 7 ,-1 , 0
  4592.7     .12       0  4997.7     .05       0  5038.4     .12       0
  5676.6     .07       0  5799.3    .035       0  6133.8     .07       0
  6167.4     .12       0
Bank Sta=4997.7,5038.4
XS Rating Curve= 0 ,0
Exp/Cntr=0.3,0.1

Type RM Length L Ch R = 1 ,43007   ,548,548,548
BEGIN DESCRIPTION:
CURRY CREEK 70.0
END DESCRIPTION:
XS GIS Cut Line= 3
        2116525.     13893474.99        2116575.       13893075.
      2115875.01     13892275.02
#Sta/Elev= 30
  4596.9 1236.99  4748.1 1232.57  4795.9 1228.29    4801 1229.22    4869 1223.13
  4876.6 1221.28  4881.6 1222.26  4899.2 1219.56  4919.4 1221.31  4949.6 1216.53
  4957.2 1212.23  4962.2 1216.27  4969.6 1209.86  4970.6 1209.36  5010.3 1209.86
  5013.8 1217.97  5035.6 1222.34  5049.8 1223.58  5361.1 1225.64  5389.6 1224.22
  5432.3 1219.54  5467.4 1218.84  5510.2 1223.14  5538.6 1224.49  5602.2 1226.27
  5708.5 1226.26  5822.4 1231.14  5922.3  1232.9    5925 1233.09    6063 1235.66
#Mann= 5 ,-1 , 0
  4596.9     .12       0  4969.6     .05       0  5010.3     .12       0
  5922.3     .07       0    5925    .035       0
Bank Sta=4969.6,5010.3
XS Rating Curve= 0 ,0
Exp/Cntr=0.3,0.1

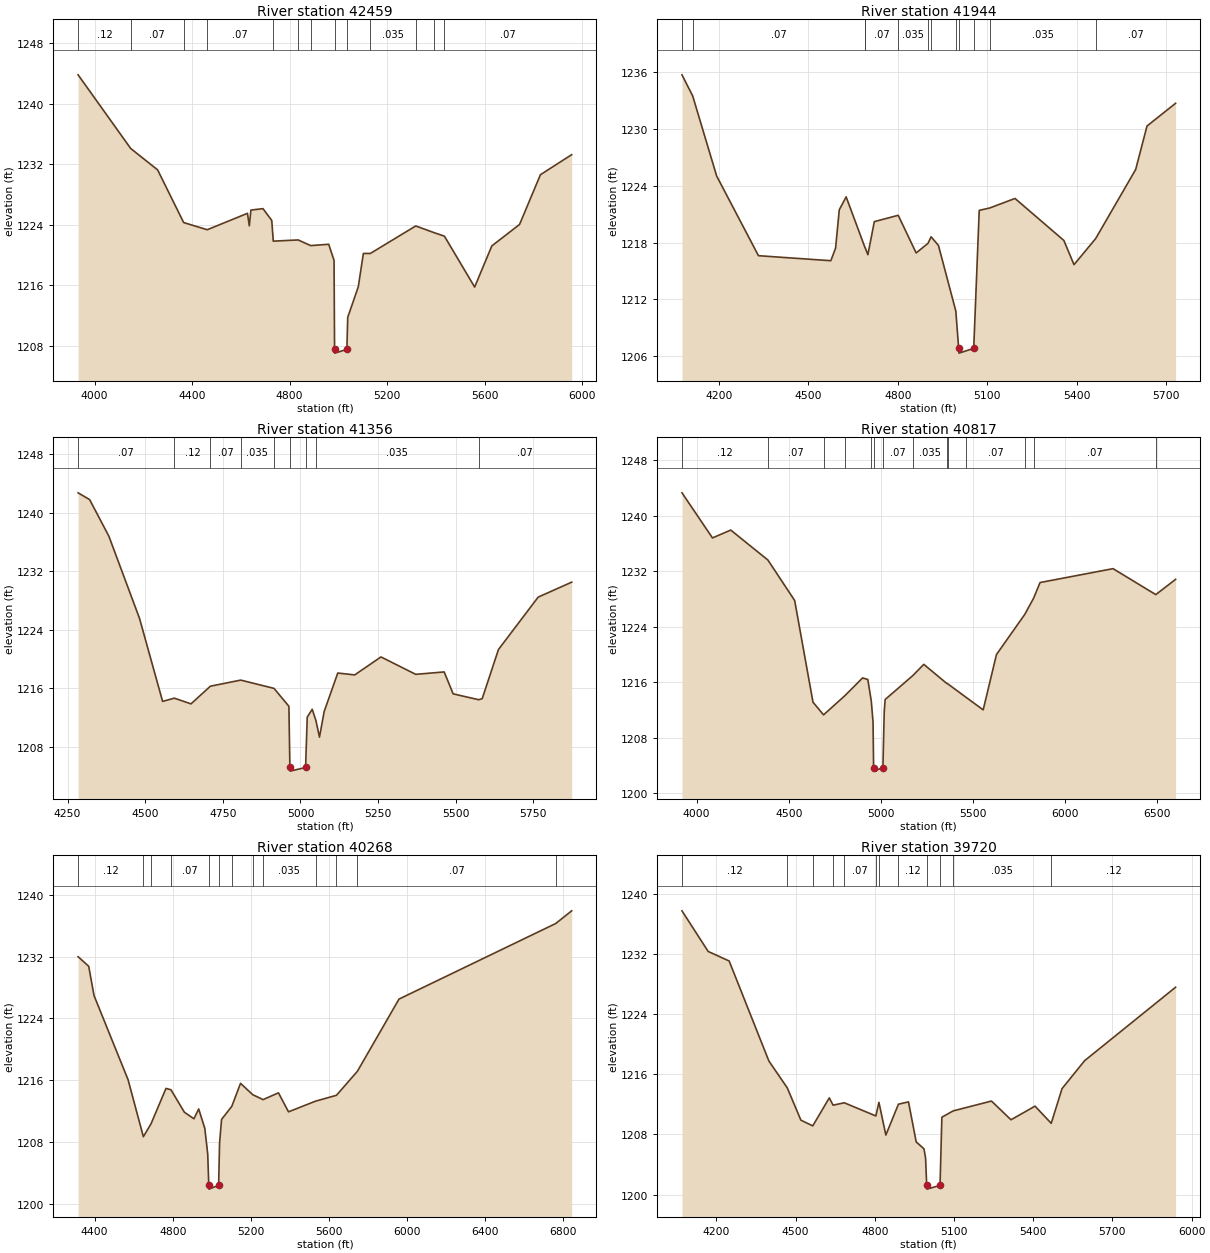
Type RM Length L Ch R = 1 ,42459   ,515,515,515
BEGIN DESCRIPTION:
CURRY CREEK 69.0
END DESCRIPTION:
XS GIS Cut Line= 3
        2117725.       13893625.        2117025.       13892825.
      2116424.99     13892074.99
#Sta/Elev= 30
  3932.7 1243.83  4148.3 1234.09  4258.7 1231.26  4365.5 1224.29  4462.2 1223.34
    4627 1225.51  4634.6 1223.86  4641.2 1225.94  4690.6 1226.13  4726.6 1224.57
  4732.9 1221.83  4834.9 1221.99  4886.3 1221.24  4960.1 1221.42    4982 1219.28
  4984.1 1207.52  4985.1 1207.02  5034.5 1207.52  5038.1 1211.75  5081.4  1215.8
  5102.2  1220.2  5130.6  1220.2  5316.9 1223.84  5393.4 1222.94  5434.5 1222.49
  5558.4 1215.76  5628.8  1221.2  5742.5 1224.04  5828.1 1230.62  5956.2 1233.27
#Mann= 13 ,-1 , 0
  3932.7     .12       0  4148.3     .07       0  4365.5    .035       0
  4462.2     .07       0  4732.9    .035       0  4834.9     .12       0
  4886.3     .07       0  4984.1     .05       0  5034.5     .07       0
  5130.6    .035       0  5316.9     .07       0  5393.4    .035       0
  5434.5     .07       0
Bank Sta=4984.1,5034.5
XS Rating Curve= 0 ,0
Exp/Cntr=0.3,0.1

Type RM Length L Ch R = 1 ,41944   ,588,588,588
BEGIN DESCRIPTION:
CURRY CREEK 68.0
END DESCRIPTION:
XS GIS Cut Line= 3
      2117975.04     13892825.02        2117175.       13892375.
      2116524.97     13892024.99
#Sta/Elev= 30
  4075.7 1235.74  4111.6 1233.51  4192.1 1225.04  4332.3 1216.62  4575.2 1216.09
  4591.1 1217.42  4603.5 1221.47  4626.5 1222.84  4689.5  1217.5  4690.1 1217.48
  4699.5 1216.73  4721.1 1220.22  4801.3 1220.89  4861.4 1216.91  4901.1 1217.92
  4911.6 1218.62  4936.3  1217.7  4994.6 1210.76  5004.1 1206.82  5005.1 1206.32
  5054.6 1206.82  5073.1 1221.41  5107.9 1221.66  5193.2 1222.67  5357.1 1218.23
  5391.1 1215.67  5463.8 1218.43    5598 1225.73  5636.1 1230.33  5731.9 1232.73
#Mann= 12 ,-1 , 0
  4075.7     .12       0  4111.6     .07       0  4689.5    .035       0
  4690.1     .07       0  4801.3    .035       0  4901.1     .07       0
  4911.6    .035       0  4994.6     .07       0  5004.1     .05       0
  5054.6     .07       0  5107.9    .035       0  5463.8     .07       0
Bank Sta=5004.1,5054.6
XS Rating Curve= 0 ,0
Exp/Cntr=0.3,0.1

Type RM Length L Ch R = 1 ,41356   ,539,539,539
BEGIN DESCRIPTION:
CURRY CREEK 67.0
END DESCRIPTION:
XS GIS Cut Line= 3
        2118225.       13892275.        2117575.       13891975.
      2116775.01       13891625.
#Sta/Elev= 30
  4284.1 1242.72  4321.3 1241.79  4383.2 1236.79  4481.9 1225.54  4556.2 1214.19
    4594 1214.63  4647.6 1213.85  4710.1 1216.27  4807.7  1217.1  4914.8 1215.97
  4962.8 1213.52    4966 1205.15    4967 1204.65  5016.5 1205.15  5021.8 1212.03
  5037.8 1213.11  5049.9 1211.55  5061.2  1209.3  5076.4 1212.81  5120.1 1218.07
  5174.6 1217.81  5259.2 1220.27  5371.1 1217.89  5462.7 1218.22  5491.6 1215.22
  5573.8 1214.42  5585.1 1214.56  5637.4 1221.28  5765.2 1228.45  5873.2  1230.5
#Mann= 9 ,-1 , 0
  4284.1     .07       0    4594     .12       0  4710.1     .07       0
  4807.7    .035       0  4914.8     .07       0    4966     .05       0
  5016.5     .07       0  5049.9    .035       0  5573.8     .07       0
Bank Sta=4966,5016.5
XS Rating Curve= 0 ,0
Exp/Cntr=0.3,0.1

Type RM Length L Ch R = 1 ,40817   ,549,549,549
BEGIN DESCRIPTION:
CURRY CREEK 66.0
END DESCRIPTION:
XS GIS Cut Line= 3
      2118624.36     13892249.43        2117825.       13891525.
      2116270.25     13891150.51
#Sta/Elev= 30
  3920.9 1243.32  4086.3 1236.82  4185.6 1237.95  4387.2 1233.63  4532.3  1227.8
  4631.7 1213.15  4689.1 1211.32  4805.8 1214.11  4900.7 1216.64  4929.1 1216.42
  4947.9 1213.33  4957.5 1210.29  4960.6 1203.71  4961.6 1203.21  5011.1 1203.71
  5018.1 1211.71  5023.2 1213.53  5173.7 1216.99  5232.8  1218.6  5357.4 1215.85
    5362 1215.81  5462.6 1213.84  5555.1 1212.04  5627.1 1220.01  5780.2 1225.78
  5828.2 1228.11  5863.7 1230.39  6259.6 1232.39  6491.7 1228.65  6598.9 1230.85
#Mann= 14 ,-1 , 0
  3920.9     .12       0  4387.2     .07       0  4689.1    .035       0
  4805.8     .12       0  4947.9     .07       0  4960.6     .05       0
  5011.1     .07       0  5173.7    .035       0  5357.4     .07       0
    5362    .035       0  5462.6     .07       0  5780.2    .035       0
  5828.2     .07       0  6491.7     .12       0
Bank Sta=4960.6,5011.1
XS Rating Curve= 0 ,0
Exp/Cntr=0.3,0.1

Type RM Length L Ch R = 1 ,40268   ,548,548,548
BEGIN DESCRIPTION:
CURRY CREEK 65.0
END DESCRIPTION:
XS GIS Cut Line= 3
      2118724.98     13891274.99        2118075.       13891075.
      2116400.44     13890296.33
#Sta/Elev= 30
  4315.4 1231.98  4369.7 1230.74  4397.1 1226.94  4571.1 1216.06  4649.5 1208.67
  4688.6 1210.33  4765.3 1214.92  4790.8 1214.75  4859.4 1211.84  4908.5 1210.99
  4932.7 1212.26  4964.1 1209.75  4979.1 1206.39  4984.4 1202.38  4985.4 1201.88
  5034.9 1202.38  5039.6 1207.84  5049.9 1210.91  5102.2  1212.6    5147 1215.58
  5209.4 1214.11  5262.3 1213.47  5341.1 1214.35  5392.5 1211.89  5530.9 1213.27
    5638 1214.03  5745.2 1217.14  5958.2 1226.49  6760.7 1236.28  6842.2 1237.92
#Mann= 13 ,-1 , 0
  4315.4     .12       0  4649.5     .07       0  4688.6    .035       0
  4790.8     .07       0  4984.4     .05       0  5034.9     .07       0
  5102.2    .035       0  5209.4     .07       0  5262.3    .035       0
  5530.9     .07       0    5638    .035       0  5745.2     .07       0
  6760.7    .035       0
Bank Sta=4984.4,5034.9
XS Rating Curve= 0 ,0
Exp/Cntr=0.3,0.1

Type RM Length L Ch R = 1 ,39720   ,543,543,543
BEGIN DESCRIPTION:
CURRY CREEK 64.0
END DESCRIPTION:
XS GIS Cut Line= 3
        2118975.       13891125.        2118225.       13890575.
      2117374.97     13890174.99
#Sta/Elev= 30
  4069.7 1237.72  4168.9 1232.32  4248.4 1231.05  4398.9 1217.75  4468.4 1214.19
  4520.1 1209.89    4565 1209.13  4627.7 1212.85    4642 1211.88  4684.5  1212.2
    4804 1210.45  4815.6 1212.26  4841.9 1207.91  4889.5 1212.01  4927.6 1212.32
  4956.9 1206.99  4986.2 1206.08  4992.4 1204.84  4996.6 1201.22  4997.6 1200.72
  5047.1 1201.22    5054 1210.28  5096.7 1211.12  5241.9 1212.43  5315.8 1209.94
    5407 1211.75  5468.2 1209.47  5509.2 1214.08  5594.8  1217.8  5939.2 1227.56
#Mann= 12 ,-1 , 0
  4069.7     .12       0  4468.4    .035       0    4565     .07       0
    4642    .035       0  4684.5     .07       0    4804     .12       0
  4815.6     .07       0  4889.5     .12       0  4996.6     .05       0
  5047.1     .12       0  5096.7    .035       0  5468.2     .12       0
Bank Sta=4996.6,5047.1
XS Rating Curve= 0 ,0
Exp/Cntr=0.3,0.1