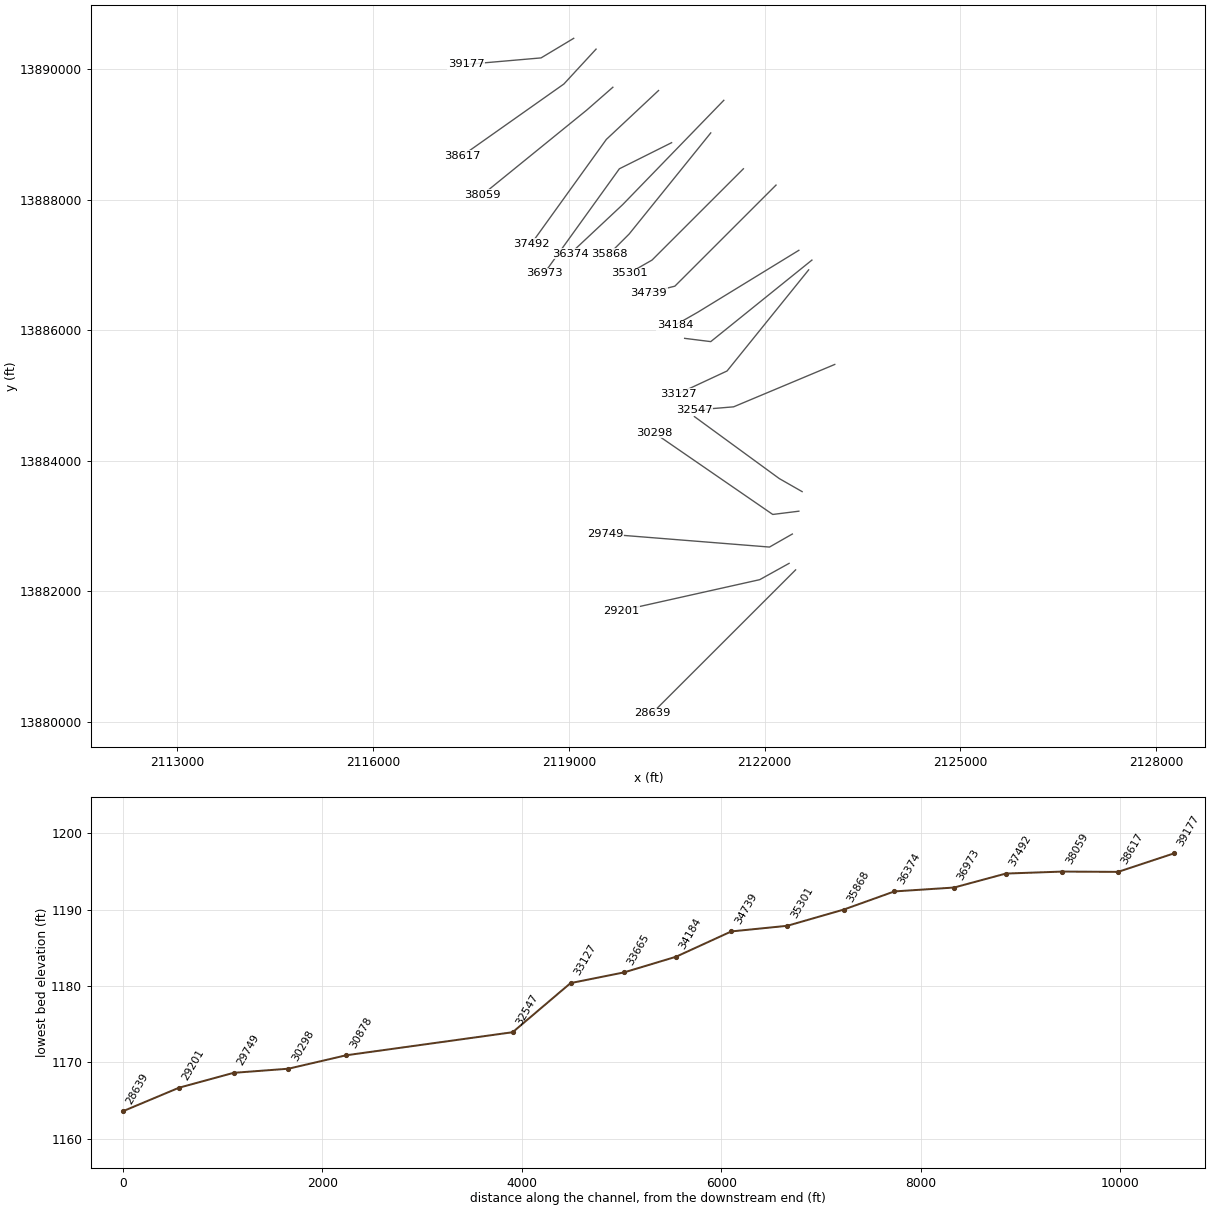
HEC-RAS study CURRY CREEK.prj: CURRY CREEK Base Level Engineering

--- CURRY CREEK.g01 (geometry) --- (continued)

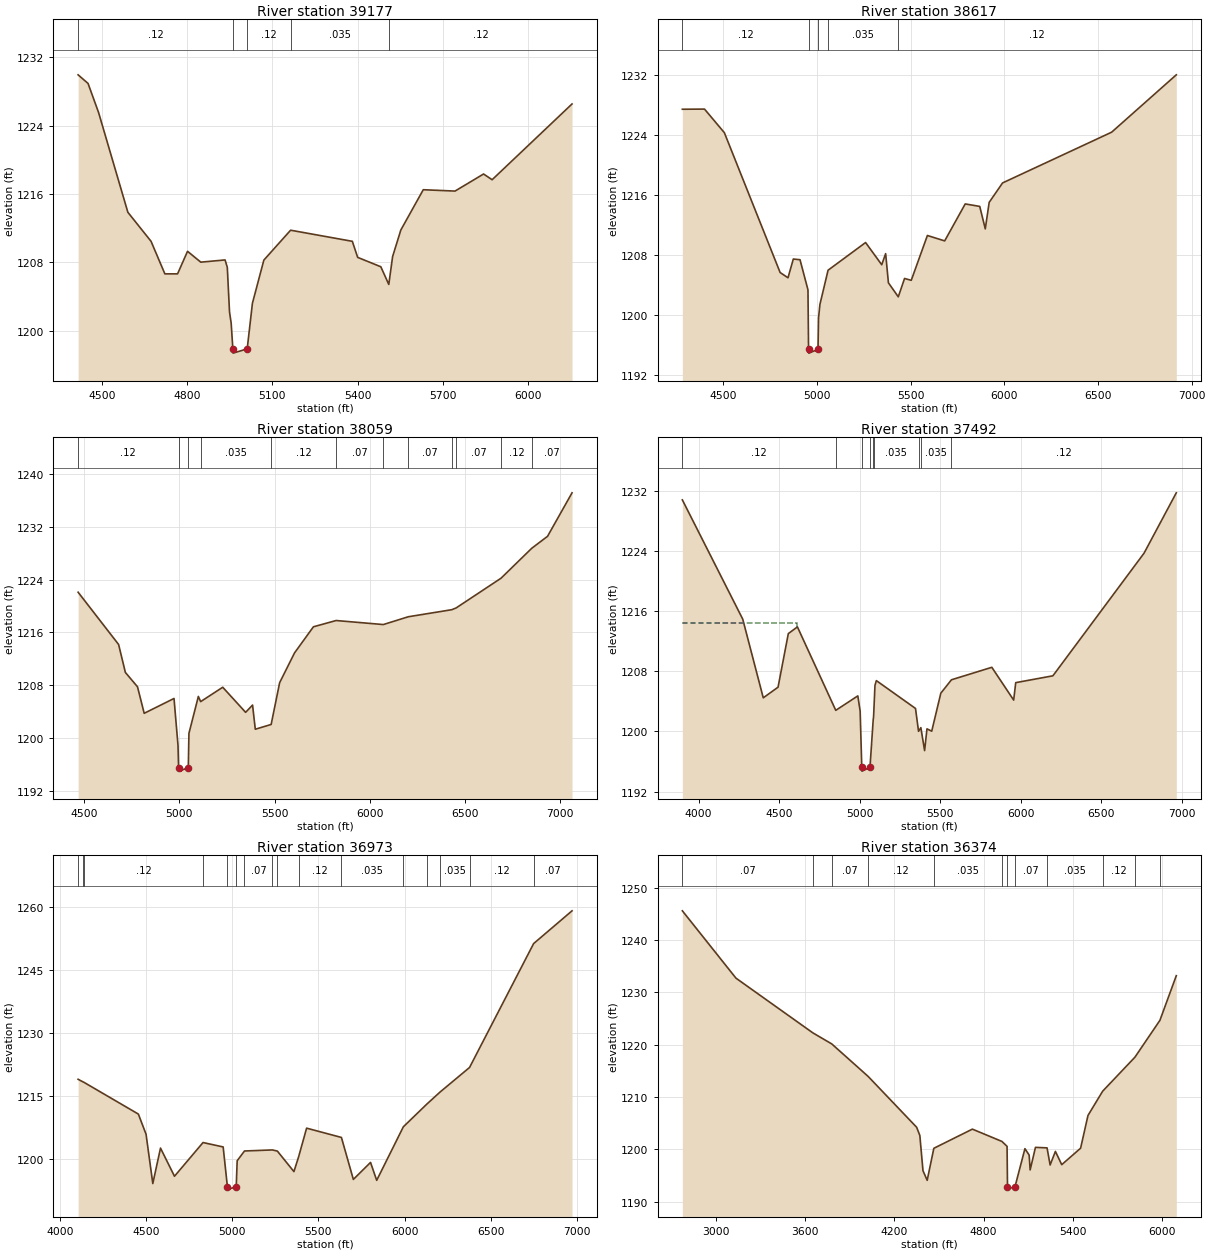
Type RM Length L Ch R = 1 ,39177   ,560,560,560
BEGIN DESCRIPTION:
CURRY CREEK 63.0
END DESCRIPTION:
XS GIS Cut Line= 3
      2119075.02     13890475.01        2118575.       13890175.
      2117424.96       13890075.
#Sta/Elev= 30
  4416.9 1229.95  4451.9 1228.94  4488.8 1225.55  4591.9 1213.86  4673.5 1210.46
  4722.1 1206.65  4766.8 1206.65  4801.8 1209.29  4848.4 1208.02  4933.9 1208.28
  4941.7 1207.41  4949.5 1202.19  4955.3 1200.89  4961.2 1197.87  4962.2 1197.37
  5011.7 1197.87  5030.1 1203.21  5070.3 1208.26  5164.4 1211.76  5381.5 1210.46
  5400.3 1208.58  5481.8 1207.48  5509.8 1205.41  5523.2 1208.67  5552.1 1211.78
  5631.1  1216.5  5742.8 1216.34  5843.2 1218.34  5873.3 1217.67  6154.4 1226.54
#Mann= 5 ,-1 , 0
  4416.9     .12       0  4961.2     .05       0  5011.7     .12       0
  5164.4    .035       0  5509.8     .12       0
Bank Sta=4961.2,5011.7
XS Rating Curve= 0 ,0
Exp/Cntr=0.3,0.1

Type RM Length L Ch R = 1 ,38617   ,558,558,558
BEGIN DESCRIPTION:
CURRY CREEK 62.0
END DESCRIPTION:
XS GIS Cut Line= 3
      2119417.69     13890309.65        2118925.       13889775.
      2117364.75     13888673.38
#Sta/Elev= 30
    4281 1227.48  4399.3  1227.5  4505.3 1224.35    4803  1205.7    4845    1205
  4873.4  1207.5  4909.1 1207.41  4951.6 1203.39  4954.7 1195.45  4955.7 1194.95
  5005.2 1195.45    5008 1199.62  5015.4 1201.45    5059 1206.01  5259.2  1209.7
  5345.4 1206.74  5366.3 1208.22  5381.1 1204.33  5433.8 1202.46  5467.3 1204.91
    5503 1204.66  5589.2 1210.64  5681.5 1209.92  5791.1 1214.85  5868.7 1214.52
  5898.2 1211.52  5919.1 1215.06  5990.5 1217.65    6573 1224.42    6918 1232.07
#Mann= 5 ,-1 , 0
    4281     .12       0  4954.7     .05       0  5005.2     .12       0
    5059    .035       0  5433.8     .12       0
Bank Sta=4954.7,5005.2
XS Rating Curve= 0 ,0
Exp/Cntr=0.3,0.1

Type RM Length L Ch R = 1 ,38059   ,567,567,567
BEGIN DESCRIPTION:
CURRY CREEK 61.0
END DESCRIPTION:
XS GIS Cut Line= 3
      2119674.98     13889724.98        2119275.       13889375.
      2117675.02     13888075.02
#Sta/Elev= 30
  4468.8  1222.1  4681.4 1214.18    4717 1209.94  4780.6 1207.77  4815.7 1203.75
  4972.3    1206  4993.2  1198.9  4996.4 1195.49  4997.4 1194.99  5047.2 1195.49
  5050.6 1200.71  5100.1 1206.31    5112 1205.52    5228  1207.7  5348.2  1203.9
  5384.6    1205    5399 1201.34  5482.2 1202.06  5526.8 1208.39  5605.1 1212.91
  5704.2 1216.86  5823.3 1217.81  6071.1  1217.2    6202 1218.38  6430.4 1219.45
  6453.5 1219.72    6689 1224.22  6850.4 1228.76  6933.2 1230.57  7061.8 1237.16
#Mann= 12 ,-1 , 0
  4468.8     .12       0  4996.4     .05       0  5047.2     .12       0
    5112    .035       0  5482.2     .12       0  5823.3     .07       0
  6071.1     .12       0    6202     .07       0  6430.4    .035       0
  6453.5     .07       0    6689     .12       0  6850.4     .07       0
Bank Sta=4996.4,5047.2
XS Rating Curve= 0 ,0
Exp/Cntr=0.3,0.1

Type RM Length L Ch R = 1 ,37492   ,519,519,519
BEGIN DESCRIPTION:
CURRY CREEK 60.0
END DESCRIPTION:
XS GIS Cut Line= 3
        2120375.       13889675.        2119575.       13888925.
        2118425.       13887325.
#Sta/Elev= 30
  3898.7 1230.78  4273.6 1214.93  4401.1 1204.47  4492.9 1205.89  4556.7 1213.01
  4613.1  1213.9  4851.3 1202.81  4988.2 1204.73  5002.7 1202.71  5012.8 1195.23
  5013.8 1194.73  5063.7 1195.23  5083.8 1201.58  5086.1 1201.96  5094.7 1206.13
  5103.3 1206.76  5346.4 1203.06  5365.2 1200.02  5379.6 1200.51  5402.9 1197.46
  5417.6 1200.35  5447.1 1200.04  5503.6 1205.09  5569.6 1206.87  5820.3 1208.53
  5955.9 1204.17  5968.8 1206.49  6199.6  1207.4  6765.6  1223.7  6965.7 1231.72
#Mann= 9 ,-1 , 0
  3898.7     .12       0  4851.3    .035       0  5012.8    .035       0
  5063.7    .035       0  5083.8     .12       0  5086.1    .035       0
  5365.2     .12       0  5379.6    .035       0  5569.6     .12       0
#XS Ineff= 2 , 0
       0  4612.1 1214.37               0
Permanent Ineff=
       F       F
Bank Sta=5012.8,5063.7
XS Rating Curve= 0 ,0
Exp/Cntr=0.3,0.1

Type RM Length L Ch R = 1 ,36973   ,599,599,599
BEGIN DESCRIPTION:
CURRY CREEK 59.0
END DESCRIPTION:
XS GIS Cut Line= 3
      2120574.97     13888874.99        2119775.       13888475.
        2118625.       13886875.
#Sta/Elev= 30
  4106.5 1219.02  4136.9 1218.36  4139.5 1218.32  4455.9 1210.75  4500.6 1205.95
  4539.7 1194.23  4584.4 1202.66  4665.5 1195.96  4831.1 1203.98  4947.8 1202.93
  4972.6  1193.4  4973.6  1192.9  5023.5  1193.4  5029.1 1199.65  5071.5 1201.97
  5233.4 1202.22  5262.1 1201.95  5358.2 1197.07    5386 1200.66  5431.8  1207.4
  5633.7 1205.19  5702.9 1195.21  5802.6 1199.25  5838.3 1194.99  5992.9 1207.72
  6129.2 1213.12  6205.1 1215.96  6376.9 1221.83  6748.5 1251.29  6971.3 1259.08
#Mann= 16 ,-1 , 0
  4106.5     .12       0  4136.9     .07       0  4139.5     .12       0
  4831.1     .07       0  4972.6     .05       0  5023.5     .07       0
  5071.5     .07       0  5233.4    .035       0  5262.1     .07       0
    5386     .12       0  5633.7    .035       0  5992.9     .12       0
  6129.2     .07       0  6205.1    .035       0  6376.9     .12       0
  6748.5     .07       0
Bank Sta=4972.6,5023.5
XS Rating Curve= 0 ,0
Exp/Cntr=0.3,0.1

Type RM Length L Ch R = 1 ,36374   ,506,506,506
BEGIN DESCRIPTION:
CURRY CREEK 58.0
END DESCRIPTION:
XS GIS Cut Line= 3
      2121374.99     13889524.99        2119825.       13887925.
      2119025.03     13887175.03
#Sta/Elev= 30
  2772.4 1245.55  3133.2 1232.69  3650.6 1222.24  3777.8 1220.13  4022.8 1213.92
  4349.4  1204.2  4370.7 1202.64  4391.8 1195.91  4420.1 1194.07  4464.9 1200.19
  4724.2 1203.85  4923.2  1201.5  4957.7 1200.56  4960.6 1192.89  4961.6 1192.39
  5011.5 1192.89    5078 1200.12  5106.3 1198.89  5113.1 1196.06  5148.8 1200.37
  5226.8 1200.27  5247.5    1197  5283.1  1199.6  5325.6 1197.06  5452.6 1200.21
  5502.4 1206.47  5601.2  1211.1  5818.2 1217.59  5986.4 1224.63  6096.6 1233.16
#Mann= 12 ,-1 , 0
  2772.4     .07       0  3650.6     .12       0  3777.8     .07       0
  4022.8     .12       0  4464.9    .035       0  4923.2     .07       0
  4960.6     .05       0  5011.5     .07       0  5226.8    .035       0
  5601.2     .12       0  5818.2     .07       0  5986.4     .12       0
Bank Sta=4960.6,5011.5
XS Rating Curve= 0 ,0
Exp/Cntr=0.3,0.1

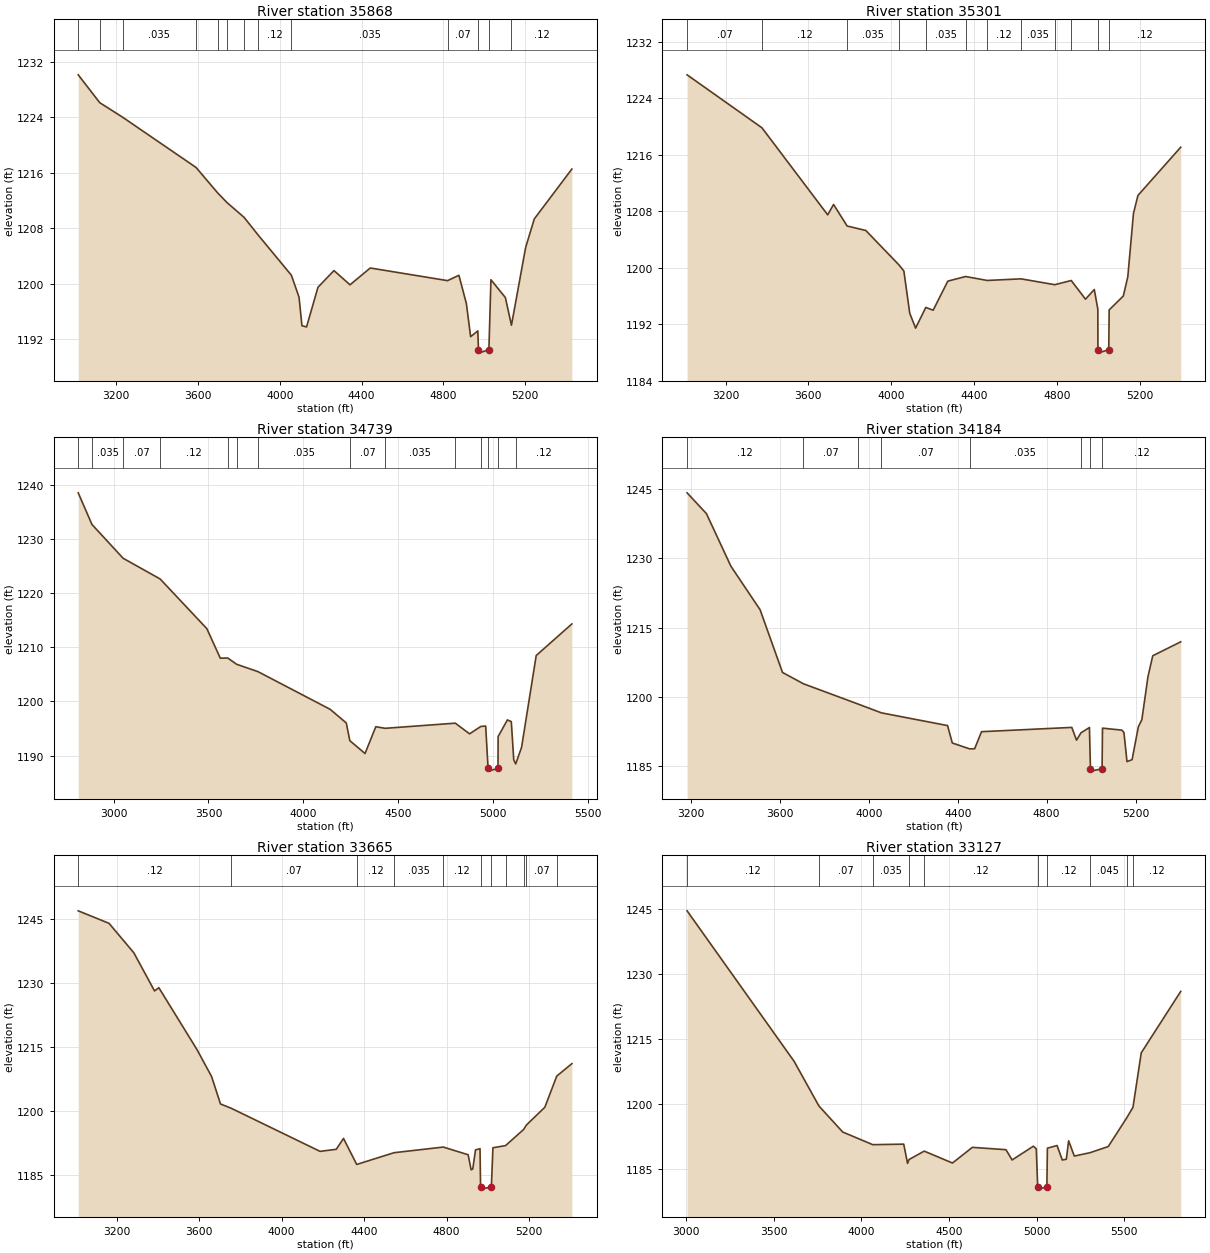
Type RM Length L Ch R = 1 ,35868   ,567,567,567
BEGIN DESCRIPTION:
CURRY CREEK 57.0
END DESCRIPTION:
XS GIS Cut Line= 3
      2121175.01     13889025.01        2119925.       13887475.
        2119625.       13887175.
#Sta/Elev= 30
  3013.8  1230.1  3119.1 1226.09  3231.3 1223.99  3590.4 1216.76    3696  1213.1
  3741.6 1211.71  3825.5 1209.57  3892.8 1207.08  4056.8 1201.24  4094.2 1198.09
  4108.6 1193.97    4131 1193.79    4187 1199.51  4265.3 1201.91  4343.7 1199.86
  4442.9 1202.28  4821.1 1200.46  4876.6 1201.23  4913.1 1197.16  4933.9 1192.39
  4969.1 1193.22  4972.4 1190.52  4973.4 1190.02  5023.3 1190.52  5033.3 1200.59
    5104 1198.02  5133.7 1194.04    5203 1205.22  5245.5 1209.35  5429.3 1216.53
#Mann= 13 ,-1 , 0
  3013.8    .035       0  3119.1     .07       0  3231.3    .035       0
  3590.4     .07       0    3696     .12       0  3741.6     .07       0
  3825.5    .035       0  3892.8     .12       0  4056.8    .035       0
  4821.1     .07       0  4972.4     .05       0  5023.3     .07       0
  5133.7     .12       0
Bank Sta=4972.4,5023.3
XS Rating Curve= 0 ,0
Exp/Cntr=0.3,0.1

Type RM Length L Ch R = 1 ,35301   ,562,562,562
BEGIN DESCRIPTION:
CURRY CREEK 56.0
END DESCRIPTION:
XS GIS Cut Line= 3
      2121674.99     13888474.99        2120275.       13887075.
        2119925.       13886875.
#Sta/Elev= 30
  3014.5  1227.3  3375.9  1219.8  3693.3 1207.47  3721.6 1208.94  3787.2 1205.89
  3877.2 1205.26  4038.1 1200.36    4061 1199.52  4089.3 1193.54  4117.6 1191.43
  4166.8 1194.36  4202.4 1193.97  4273.1 1198.08  4358.8 1198.74  4463.4 1198.18
  4626.5 1198.41  4789.2 1197.58    4869 1198.17  4937.8 1195.53  4980.2  1196.9
  4997.3 1194.12  4997.8 1188.39  4998.8 1187.89  5050.1 1188.39    5052 1194.01
  5120.4 1195.98    5142  1198.7  5169.3 1207.67  5190.9 1210.22  5397.5 1217.05
#Mann= 12 ,-1 , 0
  3014.5     .07       0  3375.9     .12       0  3787.2    .035       0
  4038.1     .07       0  4166.8    .035       0  4358.8     .07       0
  4463.4     .12       0  4626.5    .035       0  4789.2     .12       0
    4869     .12       0  4997.8     .05       0  5050.1     .12       0
Bank Sta=4997.8,5050.1
XS Rating Curve= 0 ,0
Exp/Cntr=0.3,0.1

Type RM Length L Ch R = 1 ,34739   ,555,555,555
BEGIN DESCRIPTION:
CURRY CREEK 55.0
END DESCRIPTION:
XS GIS Cut Line= 3
      2122174.99     13888224.99        2120625.       13886675.
      2120225.02     13886575.01
#Sta/Elev= 30
  2812.8  1238.5  2885.3 1232.66  3049.6 1226.43  3245.2  1222.6  3491.6 1213.43
  3562.3 1207.99  3601.9 1208.02  3648.2 1206.87    3761 1205.51  4142.1 1198.55
    4227 1196.04  4245.7 1192.77    4326  1190.4  4382.6 1195.34  4432.7 1195.05
    4802    1196  4877.5 1194.03  4937.2  1195.4  4962.4 1195.46  4975.1 1187.65
  4976.2 1187.15  5027.4 1187.65    5028 1193.52    5077  1196.6  5097.6 1196.28
  5110.5 1189.24  5120.7 1188.48  5151.7 1191.53    5229 1208.48  5417.1 1214.31
#Mann= 14 ,-1 , 0
  2812.8     .12       0  2885.3    .035       0  3049.6     .07       0
  3245.2     .12       0  3601.9    .035       0  3648.2     .07       0
    3761    .035       0  4245.7     .07       0  4432.7    .035       0
    4802     .12       0  4937.2     .12       0  4975.1     .05       0
  5027.4     .12       0  5120.7     .12       0
Bank Sta=4975.1,5027.4
XS Rating Curve= 0 ,0
Exp/Cntr=0.3,0.1

Type RM Length L Ch R = 1 ,34184   ,519,519,519
BEGIN DESCRIPTION:
CURRY CREEK 54.0
END DESCRIPTION:
XS GIS Cut Line= 3
      2122524.96     13887224.98        2120975.       13886275.
      2120625.03     13886075.02
#Sta/Elev= 30
  3182.5 1244.24  3269.5 1239.73  3379.7 1228.31  3510.9 1218.87  3611.8 1205.25
  3705.6  1202.8  3950.8 1198.41  4056.8 1196.48  4354.4 1193.72  4375.7 1189.94
  4453.9 1188.66  4476.3 1188.69  4507.2 1192.39  4913.4 1193.32  4934.7 1190.55
  4954.5 1192.13  4992.7  1193.3  4997.3 1184.33  4998.4 1183.83  5049.6 1184.33
  5051.5 1193.16  5138.6 1192.73    5148  1192.2  5161.7  1185.9  5184.7 1186.32
  5212.8 1193.45  5228.6    1195    5256  1204.3  5277.6 1208.87  5403.5  1211.9
#Mann= 8 ,-1 , 0
  3182.5     .12       0  3705.6     .07       0  3950.8     .12       0
  4056.8     .07       0  4453.9    .035       0  4954.5     .12       0
  4997.3     .05       0  5049.6     .12       0
Bank Sta=4997.3,5049.6
XS Rating Curve= 0 ,0
Exp/Cntr=0.3,0.1

Type RM Length L Ch R = 1 ,33665   ,538,538,538
BEGIN DESCRIPTION:
CURRY CREEK 53.0
END DESCRIPTION:
XS GIS Cut Line= 3
      2122724.99     13887074.99        2121175.       13885825.
      2120775.04       13885875.
#Sta/Elev= 30
  3013.6 1246.96  3163.1 1244.03  3283.4 1237.13  3383.8  1228.2  3404.6 1228.96
  3590.1 1214.43  3660.5 1208.15  3703.7 1201.73  3755.1 1200.74  4186.7 1190.63
  4265.1 1191.12  4300.3 1193.66  4364.3 1187.57  4545.6 1190.32  4784.4 1191.64
  4904.9 1189.84  4919.3 1186.31  4927.2 1186.51  4940.6 1190.98  4962.4 1191.26
  4965.1 1182.29  4966.1 1181.79  5017.4 1182.29    5025 1191.48  5086.2 1191.98
  5173.7 1195.75  5186.9 1196.77  5276.9 1200.97  5334.6 1208.26  5407.9 1211.17
#Mann= 11 ,-1 , 0
  3013.6     .12       0  3755.1     .07       0  4364.3     .12       0
  4545.6    .035       0  4784.4     .12       0  4965.1     .05       0
  5017.4     .12       0  5086.2    .035       0  5173.7     .12       0
  5186.9     .07       0  5334.6     .12       0
Bank Sta=4965.1,5017.4
XS Rating Curve= 0 ,0
Exp/Cntr=0.3,0.1

Type RM Length L Ch R = 1 ,33127   ,580,580,580
BEGIN DESCRIPTION:
CURRY CREEK 52.0
END DESCRIPTION:
XS GIS Cut Line= 3
      2122674.98     13886924.97        2121425.       13885375.
      2120675.04     13885025.02
#Sta/Elev= 30
  3004.7 1244.67  3616.4 1209.87  3757.5 1199.59  3893.1 1193.58  4064.8 1190.65
  4241.8 1190.77  4263.6 1186.32  4271.8 1187.21  4358.8 1189.16  4520.1 1186.41
  4633.6 1190.03  4825.5 1189.49  4860.7 1187.12  4982.3  1190.3  4998.7 1189.67
  5006.8 1180.88  5007.8 1180.38  5059.1 1180.88  5062.1 1189.84  5117.3 1190.45
  5147.2 1187.11  5170.1 1187.28  5183.5 1191.55  5215.8 1188.02  5305.9  1188.8
  5409.7 1190.22  5514.4  1196.8  5550.9 1199.29  5598.1 1211.87  5823.5 1226.06
#Mann= 10 ,-1 , 0
  3004.7     .12       0  3757.5     .07       0  4064.8    .035       0
  4271.8     .07       0  4358.8     .12       0  5006.8     .05       0
  5059.1     .12       0  5305.9    .045       0  5514.4    .035       0
  5550.9     .12       0
Bank Sta=5006.8,5059.1
XS Rating Curve= 0 ,0
Exp/Cntr=0.3,0.1

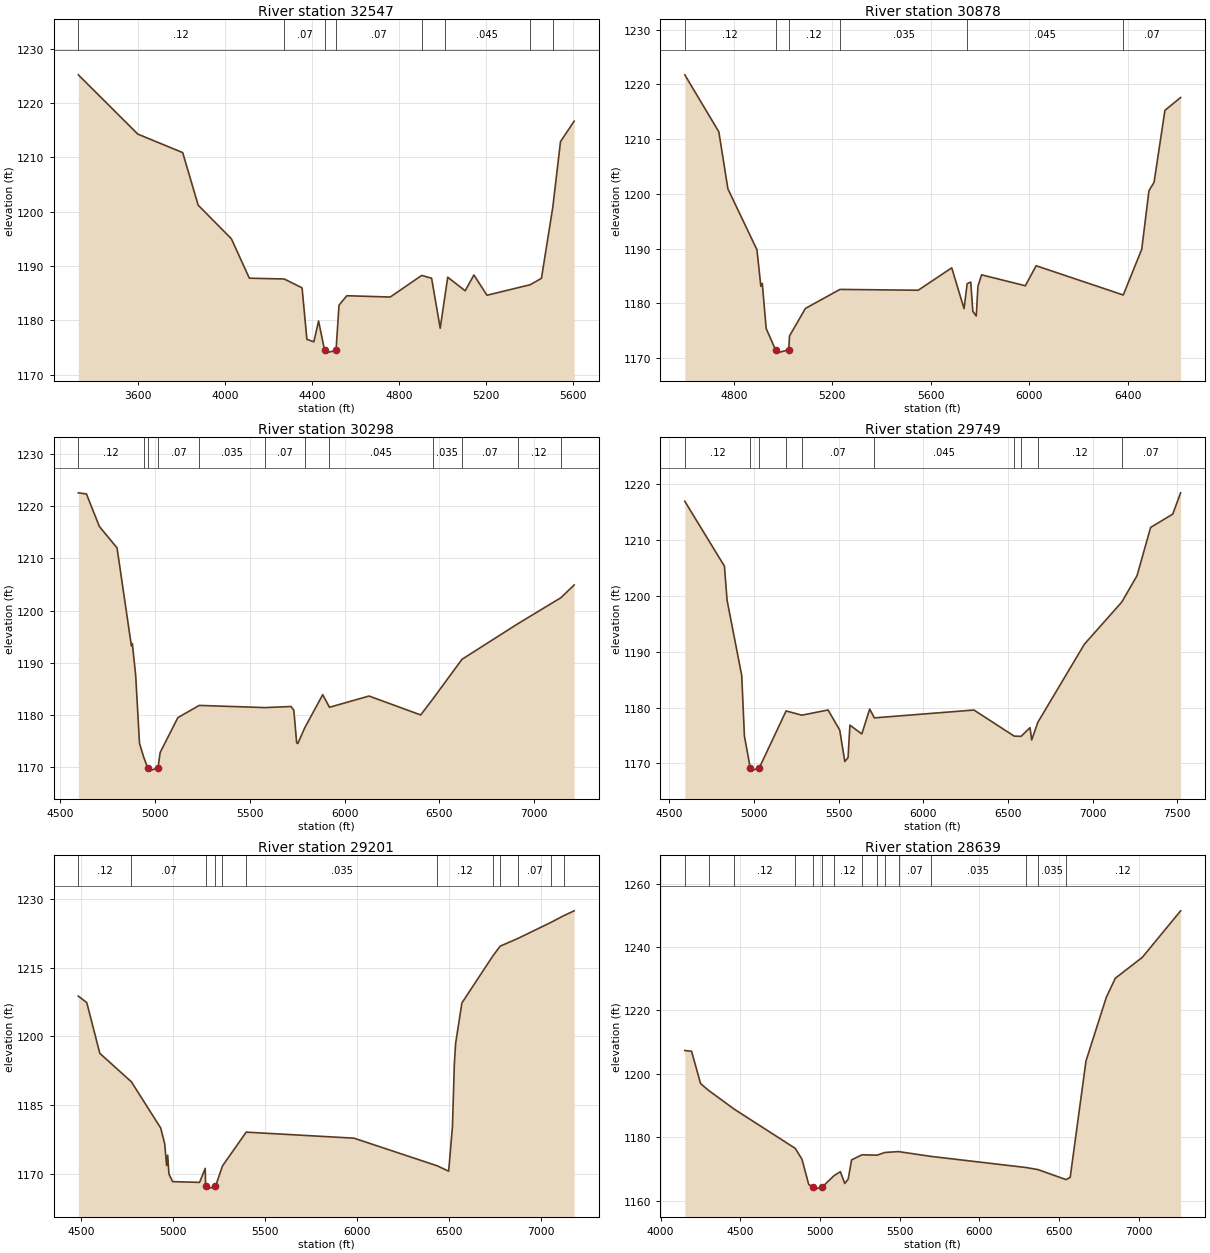
Type RM Length L Ch R = 1 ,32547   ,1669,1669,1669
BEGIN DESCRIPTION:
CURRY CREEK 51.0
END DESCRIPTION:
XS GIS Cut Line= 3
        2123075.       13885475.        2121525.       13884825.
      2120924.96       13884775.
#Sta/Elev= 30
  3323.4  1225.2  3597.4 1214.28  3803.9 1210.88  3875.2  1201.2  4028.2    1195
  4110.8 1187.75  4271.5  1187.6  4353.6 1185.97  4375.7 1176.49  4407.8 1176.03
  4429.5 1179.86  4457.5 1174.45  4458.5 1173.95  4509.9 1174.45  4523.7 1182.79
  4559.6 1184.52  4759.4 1184.28  4904.6 1188.26    4950 1187.74  4989.6 1178.53
  5009.7 1184.03  5024.2 1187.93  5104.5 1185.43  5144.7 1188.34  5204.9 1184.61
  5404.3 1186.55  5455.7 1187.73  5507.7 1200.75  5543.5 1212.91  5606.3 1216.66
#Mann= 8 ,-1 , 0
  3323.4     .12       0  4271.5     .07       0  4457.5    .035       0
  4509.9     .07       0  4904.6    .035       0  5009.7    .045       0
  5404.3    .035       0  5507.7     .12       0
Bank Sta=4457.5,4509.9
XS Rating Curve= 0 ,0
Exp/Cntr=0.3,0.1

Type RM Length L Ch R = 1 ,30878   ,580,580,580
BEGIN DESCRIPTION:
CURRY CREEK 50.0
END DESCRIPTION:
XS GIS Cut Line= 3
      2122575.03     13883524.98        2122225.       13883725.
      2120924.97     13884675.02
#Sta/Elev= 30
  4601.2 1221.73  4739.4 1211.33  4776.2 1200.92  4894.2  1189.8    4910 1183.13
  4915.8 1183.68  4931.6 1175.44  4969.6 1171.53  4970.7 1170.93  5023.3 1171.53
  5026.3 1174.06    5091 1179.09  5231.2 1182.56  5549.1 1182.41  5685.1  1186.5
  5735.1 1179.05  5747.7 1183.61  5762.3  1183.9  5770.8 1178.56  5784.6 1177.71
  5791.6 1183.15  5806.3 1185.22  5983.9 1183.23  6027.9 1186.88  6381.6 1181.54
  6456.6 1189.89  6485.9 1200.57  6506.7 1202.11  6550.7 1215.24  6614.5 1217.59
#Mann= 6 ,-1 , 0
  4601.2     .12       0  4969.6     .05       0  5023.3     .12       0
  5231.2    .035       0  5747.7    .045       0  6381.6     .07       0
Bank Sta=4969.6,5023.3
XS Rating Curve= 0 ,0
Exp/Cntr=0.3,0.1

Type RM Length L Ch R = 1 ,30298   ,549,549,549
BEGIN DESCRIPTION:
CURRY CREEK 49.0
END DESCRIPTION:
XS GIS Cut Line= 3
      2122525.02       13883225.        2122125.       13883175.
      2120304.35     13884429.43
#Sta/Elev= 30
  4595.9 1222.61  4638.8 1222.39  4706.8 1216.15    4800 1212.04  4875.6 1193.25
  4880.6 1193.67  4898.3 1187.57  4918.4 1174.51  4940.3 1171.88  4962.1 1169.77
  4963.2 1169.17  5015.8 1169.77  5027.4 1172.75  5120.5 1179.44  5233.3 1181.79
    5580 1181.37  5717.2 1181.58  5732.1 1180.85    5747 1174.62  5753.1 1174.46
  5789.5 1177.48  5884.3 1183.85  5920.1 1181.43  6128.4 1183.59  6400.9 1179.96
  6464.3 1182.99  6618.6 1190.64  6913.5 1197.48  7139.7 1202.46    7210 1204.92
#Mann= 12 ,-1 , 0
  4595.9     .12       0  4940.3     .07       0  4962.1     .05       0
  5015.8     .07       0  5233.3    .035       0    5580     .07       0
  5789.5    .035       0  5920.1    .045       0  6464.3    .035       0
  6618.6     .07       0  6913.5     .12       0  7139.7     .07       0
Bank Sta=4962.1,5015.8
XS Rating Curve= 0 ,0
Exp/Cntr=0.3,0.1

Type RM Length L Ch R = 1 ,29749   ,548,548,548
BEGIN DESCRIPTION:
CURRY CREEK 48.0
END DESCRIPTION:
XS GIS Cut Line= 3
      2122425.03     13882875.02        2122075.       13882675.
      2119558.48     13882876.19
#Sta/Elev= 30
  4592.4 1216.87  4826.4 1205.27  4842.2 1199.16  4928.6 1185.71  4944.4 1174.91
  4978.7 1169.23  4979.8 1168.63  5032.4 1169.23  5190.6 1179.39  5283.4 1178.63
  5438.4 1179.56  5507.2 1175.97  5537.3 1170.34  5556.3 1171.05  5567.4 1176.85
  5637.6 1175.28  5684.2 1179.73  5711.7 1178.15  6299.7 1179.55  6537.3 1174.89
  6578.1 1174.85  6630.7  1176.4  6640.8  1174.2  6677.2 1177.37  6951.8 1191.32
  7172.8 1198.86  7262.8 1203.58    7343  1212.2  7473.4 1214.57  7520.1 1218.38
#Mann= 10 ,-1 , 0
  4592.4     .12       0  4978.7     .05       0  5032.4     .12       0
  5190.6    .035       0  5283.4     .07       0  5711.7    .045       0
  6537.3    .035       0  6578.1    .045       0  6677.2     .12       0
  7172.8     .07       0
Bank Sta=4978.7,5032.4
XS Rating Curve= 0 ,0
Exp/Cntr=0.3,0.1

Type RM Length L Ch R = 1 ,29201   ,562,562,562
BEGIN DESCRIPTION:
CURRY CREEK 47.0
END DESCRIPTION:
XS GIS Cut Line= 3
      2122375.01     13882425.01        2121925.       13882175.
      2119800.04     13881700.01
#Sta/Elev= 30
  4485.7 1208.81  4531.5 1207.39  4602.4 1196.32  4773.8  1190.1    4933 1180.02
  4954.7 1176.55    4965 1171.82  4970.8  1174.1  4977.6 1170.01  4997.6 1168.32
    5144 1168.15  5174.7 1171.21  5176.7 1167.28  5177.8 1166.68  5230.4 1167.28
  5268.4 1171.74  5397.2 1179.12  5982.6  1177.8  6433.7 1171.78  6496.5  1170.6
    6517 1180.29  6527.3 1193.94  6534.3 1198.47  6568.3 1207.31  6734.6 1217.46
  6775.8  1219.7  6871.8 1221.38  7053.8 1224.93  7122.7 1226.39  7177.9 1227.42
#Mann= 12 ,-1 , 0
  4485.7     .12       0  4773.8     .07       0  5176.7     .05       0
  5230.4     .07       0  5268.4     .12       0  5397.2    .035       0
  6433.7     .12       0  6734.6     .07       0  6775.8     .12       0
  6871.8     .07       0  7053.8     .12       0  7122.7     .07       0
Bank Sta=5176.7,5230.4
XS Rating Curve= 0 ,0
Exp/Cntr=0.3,0.1

Type RM Length L Ch R = 1 ,28639   ,510,510,510
BEGIN DESCRIPTION:
CURRY CREEK 46.0
END DESCRIPTION:
XS GIS Cut Line= 3
      2122474.97     13882324.97        2121875.       13881725.
      2120275.02     13880125.02
#Sta/Elev= 30
  4151.5 1207.33  4193.9 1207.11  4250.5 1196.91  4300.4 1194.77  4462.4 1188.81
  4844.3 1176.47  4886.8 1173.02  4929.3 1165.04  4958.9  1164.2    4960  1163.6
  5012.7  1164.2    5087 1167.81  5127.3  1169.1  5155.5 1165.39  5176.8 1166.76
    5198 1172.83  5263.9 1174.44  5357.3 1174.31  5407.5 1175.17  5492.6 1175.44
  5694.2 1173.94  6293.8 1170.41  6367.8 1169.76  6543.4 1166.61  6569.8 1167.29
  6668.8 1204.02    6796 1224.06  6852.6 1230.13  7022.3 1236.73  7262.7 1251.41
#Mann= 15 ,-1 , 0
  4151.5     .12       0  4300.4     .07       0  4462.4     .12       0
  4844.3     .07       0  4958.9     .05       0  5012.7     .07       0
    5087     .12       0  5263.9    .035       0  5357.3     .07       0
  5407.5    .035       0  5492.6     .07       0  5694.2    .035       0
  6293.8     .07       0  6367.8    .035       0  6543.4     .12       0
Bank Sta=4958.9,5012.7
XS Rating Curve= 0 ,0
Exp/Cntr=0.3,0.1