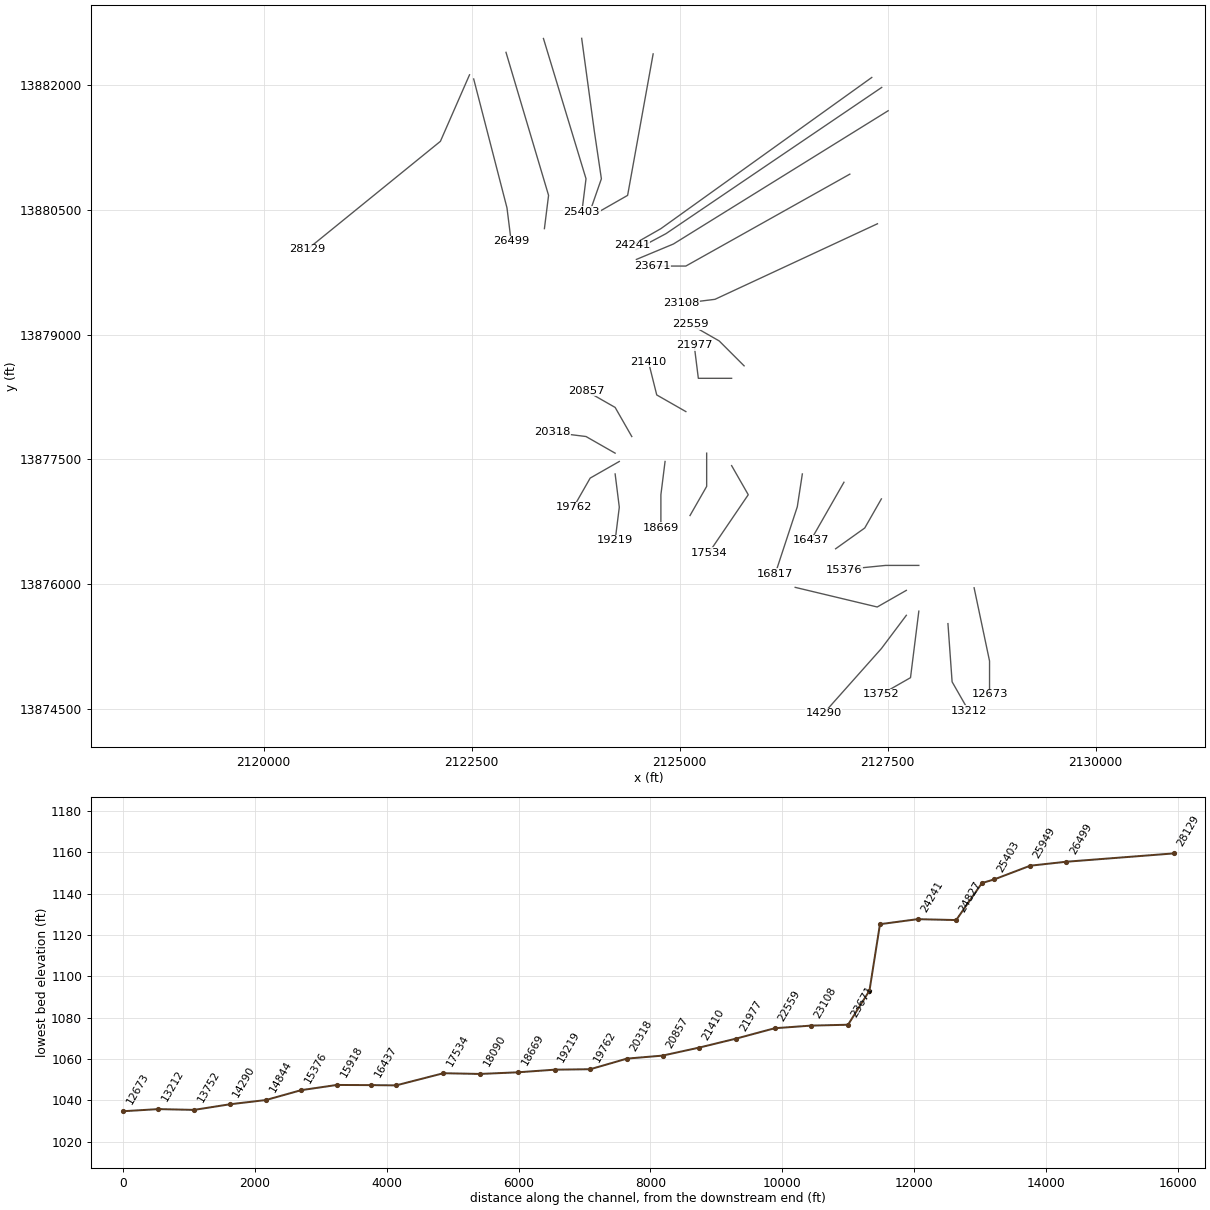
HEC-RAS study CURRY CREEK.prj: CURRY CREEK Base Level Engineering

--- CURRY CREEK.g01 (geometry) --- (continued)

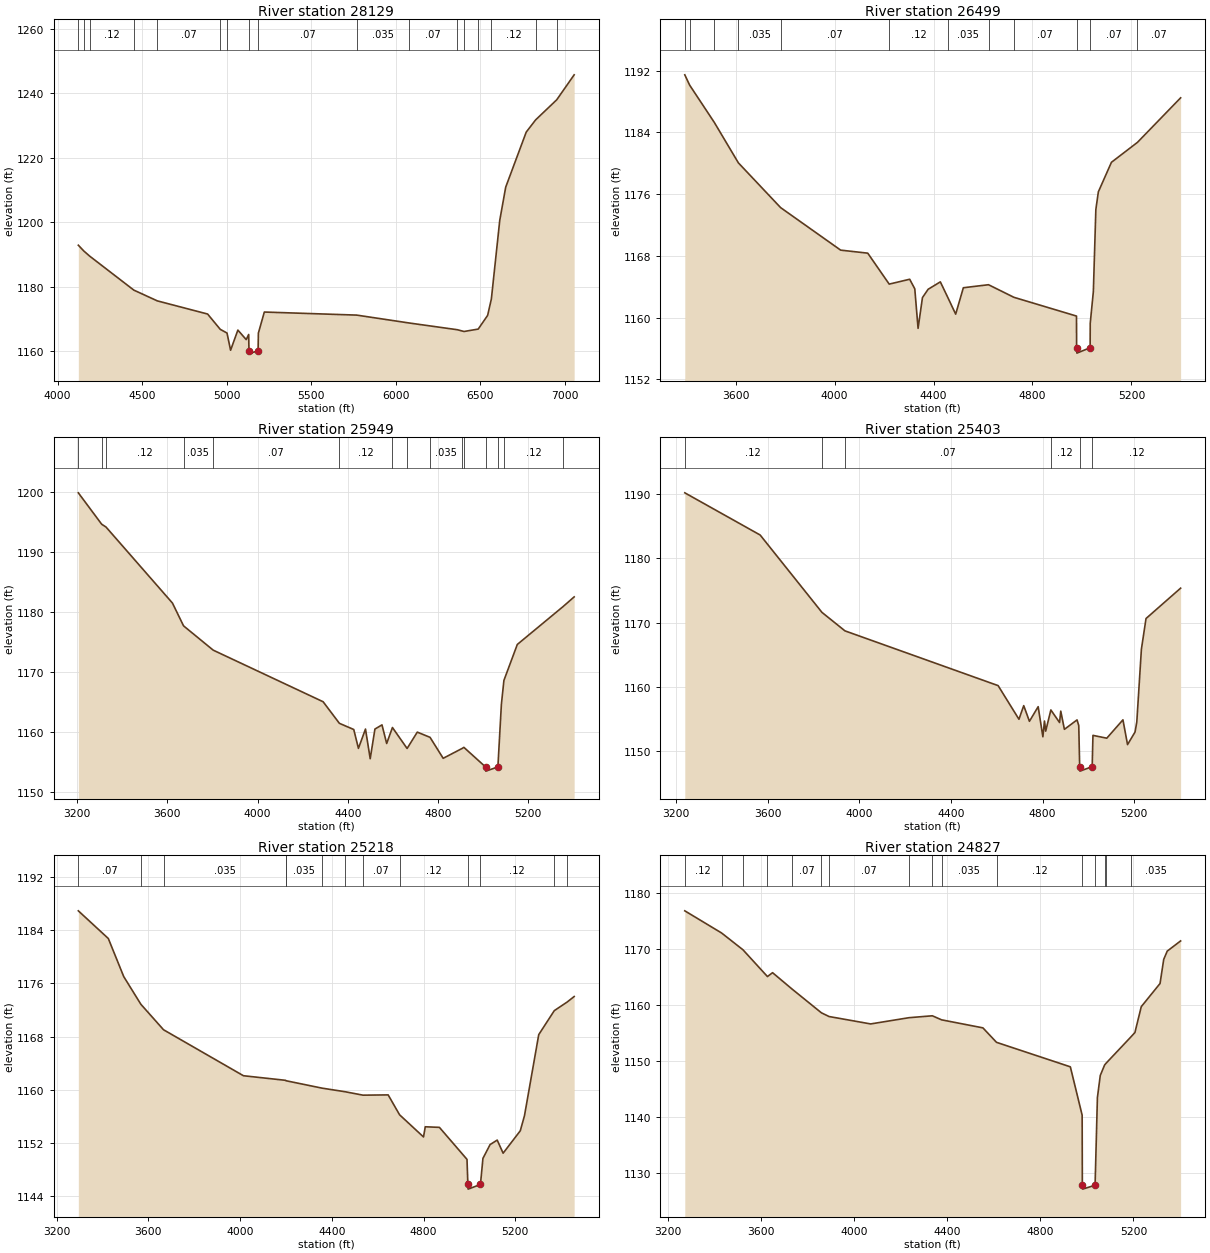
Type RM Length L Ch R = 1 ,28129   ,1630,1630,1630
BEGIN DESCRIPTION:
CURRY CREEK 45.0
END DESCRIPTION:
XS GIS Cut Line= 3
      2122474.98     13882124.96        2122125.       13881325.
      2120525.02     13880025.01
#Sta/Elev= 30
  4122.4  1192.9  4155.2 1191.09    4189 1189.54  4451.1 1178.97    4590 1175.64
  4887.6 1171.56  4962.4 1166.82  5002.4 1165.67  5023.6 1160.34  5066.7 1166.58
  5116.2 1163.63  5130.6 1165.23  5132.5 1160.04  5133.6 1159.44  5186.3 1160.04
  5188.1 1165.65  5223.3 1172.18  5769.7 1171.23  6080.9 1168.78  6365.2  1166.7
  6405.1 1166.15  6489.1 1166.89    6545 1171.14  6567.2 1176.27  6616.8 1200.64
    6652 1210.91  6773.4 1227.97  6828.9 1231.75  6954.1    1238  7057.1 1245.73
#Mann= 17 ,-1 , 0
  4122.4     .12       0  4155.2     .07       0    4189     .12       0
  4451.1    .035       0    4590     .07       0  4962.4     .12       0
  5002.4     .07       0  5132.5     .05       0  5186.3     .07       0
  5769.7    .035       0  6080.9     .07       0  6365.2    .035       0
  6405.1     .07       0  6489.1    .035       0  6567.2     .12       0
  6828.9     .07       0  6954.1     .12       0
Bank Sta=5132.5,5186.3
XS Rating Curve= 0 ,0
Exp/Cntr=0.3,0.1

Type RM Length L Ch R = 1 ,26499   ,550,550,550
BEGIN DESCRIPTION:
CURRY CREEK 44.0
END DESCRIPTION:
XS GIS Cut Line= 3
      2122524.99     13882075.04        2122925.       13880525.
        2122975.     13880125.03
#Sta/Elev= 30
  3394.8 1191.46  3414.5 1190.12  3514.2 1185.29  3611.3 1180.06    3782 1174.26
  4024.8 1168.75  4134.2 1168.36  4220.9 1164.35  4303.7 1164.98  4324.3 1163.74
  4337.6 1158.62  4355.3  1162.6  4378.2 1163.68  4427.6 1164.64  4458.8 1162.55
  4489.6 1160.46  4520.6 1163.88  4622.3 1164.27  4724.9 1162.64  4977.9 1160.21
  4978.3 1156.11  4979.5 1155.41    5033 1156.11  5033.4 1159.28    5046 1163.38
  5056.1 1174.01  5066.2  1176.3  5119.1 1180.13  5224.2 1182.71  5398.7 1188.48
#Mann= 12 ,-1 , 0
  3394.8     .12       0  3414.5     .07       0  3514.2     .12       0
  3611.3    .035       0    3782     .07       0  4220.9     .12       0
  4458.8    .035       0  4622.3     .12       0  4724.9     .07       0
  4978.3     .05       0    5033     .07       0  5224.2     .07       0
Bank Sta=4978.3,5033
XS Rating Curve= 0 ,0
Exp/Cntr=0.3,0.1

Type RM Length L Ch R = 1 ,25949   ,546,546,546
BEGIN DESCRIPTION:
CURRY CREEK 43.0
END DESCRIPTION:
XS GIS Cut Line= 3
      2122913.44     13882394.91        2123425.       13880675.
        2123375.     13880274.99
#Sta/Elev= 30
  3205.5 1199.93    3309 1194.69  3328.2 1194.22  3622.7 1181.53  3671.8 1177.73
  3803.3 1173.67  4290.4 1165.06  4362.5 1161.46  4426.2 1160.43  4446.9 1157.28
  4478.2  1160.5  4499.1 1155.55    4520  1160.5  4551.3  1161.2  4572.1 1158.09
  4597.6 1160.76  4662.6 1157.26  4707.8 1159.99  4764.3 1159.12  4822.5 1155.62
  4906.8 1157.27  4914.2 1157.45  5010.3 1154.18  5011.5 1153.48    5065 1154.18
  5080.5 1164.63  5091.7 1168.62    5151 1174.62  5354.4 1180.96    5403 1182.56
#Mann= 15 ,-1 , 0
  3205.5     .12       0    3309     .07       0  3328.2     .12       0
  3671.8    .035       0  3803.3     .07       0  4362.5     .12       0
  4597.6    .035       0  4662.6     .12       0  4764.3    .035       0
  4906.8     .07       0  4914.2    .035       0  5010.3    .035       0
    5065    .035       0  5091.7     .12       0  5354.4    .035       0
Bank Sta=5010.3,5065
XS Rating Curve= 0 ,0
Exp/Cntr=0.3,0.1

Type RM Length L Ch R = 1 ,25403   ,185,185,185
BEGIN DESCRIPTION:
CURRY CREEK 42.0
END DESCRIPTION:
XS GIS Cut Line= 3
      2123363.47     13882561.55        2123875.       13880875.
        2123825.     13880475.03
#Sta/Elev= 30
  3237.6  1190.2  3566.7 1183.63  3836.6 1171.58    3937  1168.7    4606 1160.17
    4697 1154.93  4717.9 1157.05  4742.8 1154.61  4780.9 1156.89  4801.5  1152.2
  4808.6 1154.65  4813.8 1153.08  4836.4 1156.38  4874.4 1154.42  4879.6  1156.2
  4895.5 1153.36  4950.7 1154.83  4958.2 1153.95  4962.2 1147.55  4963.4 1146.85
  5016.9 1147.55  5020.2 1152.42  5080.6 1151.98  5151.2 1154.84  5171.3 1150.98
  5204.1 1152.95  5211.7  1154.5  5231.8 1165.84    5252 1170.62  5403.1 1175.35
#Mann= 6 ,-1 , 0
  3237.6     .12       0  3836.6    .035       0    3937     .07       0
  4836.4     .12       0  4962.2     .05       0  5016.9     .12       0
Bank Sta=4962.2,5016.9
XS Rating Curve= 0 ,0
Exp/Cntr=0.3,0.1

Type RM Length L Ch R = 1 ,25218   ,391,391,391
BEGIN DESCRIPTION:
CURRY CREEK 41.5
END DESCRIPTION:
XS GIS Cut Line= 4
      2123822.89     13882563.52      2123975.04     13881445.95
      2124059.78     13880874.48      2123909.56     13880443.19
#Sta/Elev= 30
  3294.4 1186.91  3425.2 1182.75  3492.5 1177.02  3567.1 1172.87  3665.9 1169.04
  4014.4 1162.13  4198.4 1161.44  4199.8 1161.38    4358 1160.26  4456.9 1159.73
  4535.9 1159.21  4645.6 1159.25  4695.4 1156.26  4799.7 1152.93  4807.4 1154.46
  4869.1 1154.37  4989.4 1149.56  4993.2 1145.79  4994.4 1145.09    5048 1145.79
  5058.9 1149.71    5090 1151.78  5121.1 1152.46  5146.9 1150.49  5221.8 1153.86
  5240.1 1156.13  5302.3 1168.31  5370.1 1171.91    5426  1173.2  5456.7 1174.03
#Mann= 13 ,-1 , 0
  3294.4     .07       0  3567.1     .12       0  3665.9    .035       0
  4198.4     .07       0  4199.8    .035       0    4358     .07       0
  4456.9    .035       0  4535.9     .07       0  4695.4     .12       0
  4993.2     .05       0    5048     .12       0  5370.1    .035       0
    5426     .12       0
Bank Sta=4993.2,5048
XS Rating Curve= 0 ,0
Exp/Cntr=0.3,0.1

Type RM Length L Ch R = 1 ,24827   ,586,586,586
BEGIN DESCRIPTION:
CURRY CREEK 41.0
END DESCRIPTION:
XS GIS Cut Line= 3
      2124681.84     13882376.43        2124375.       13880675.
      2124024.99       13880475.
#Sta/Elev= 30
  3271.1 1176.76  3429.4 1172.81  3521.2 1169.82  3626.5 1165.05  3648.5 1165.74
  3732.4 1162.82  3858.6 1158.59  3891.3 1157.93  4070.3 1156.61    4235 1157.72
  4335.5 1158.06  4375.2 1157.34  4552.9 1155.91  4611.5 1153.33  4928.9 1148.97
  4979.7 1140.35  4980.5 1127.88  4981.7 1127.18  5035.3 1127.88  5045.3  1143.5
  5057.6 1147.43  5076.2 1149.29  5081.5 1149.56  5187.8 1154.23  5206.6 1155.08
  5233.9 1159.69  5314.6 1163.81  5330.4  1168.1  5345.5 1169.58  5403.1  1171.4
#Mann= 16 ,-1 , 0
  3271.1     .12       0  3429.4    .035       0  3521.2     .12       0
  3626.5    .035       0  3732.4     .07       0  3858.6    .035       0
  3891.3     .07       0    4235    .035       0  4335.5     .07       0
  4375.2    .035       0  4611.5     .12       0  4980.5     .05       0
  5035.3     .12       0  5076.2    .035       0  5081.5     .12       0
  5187.8    .035       0
Bank Sta=4980.5,5035.3
XS Rating Curve= 0 ,0
Exp/Cntr=0.3,0.1

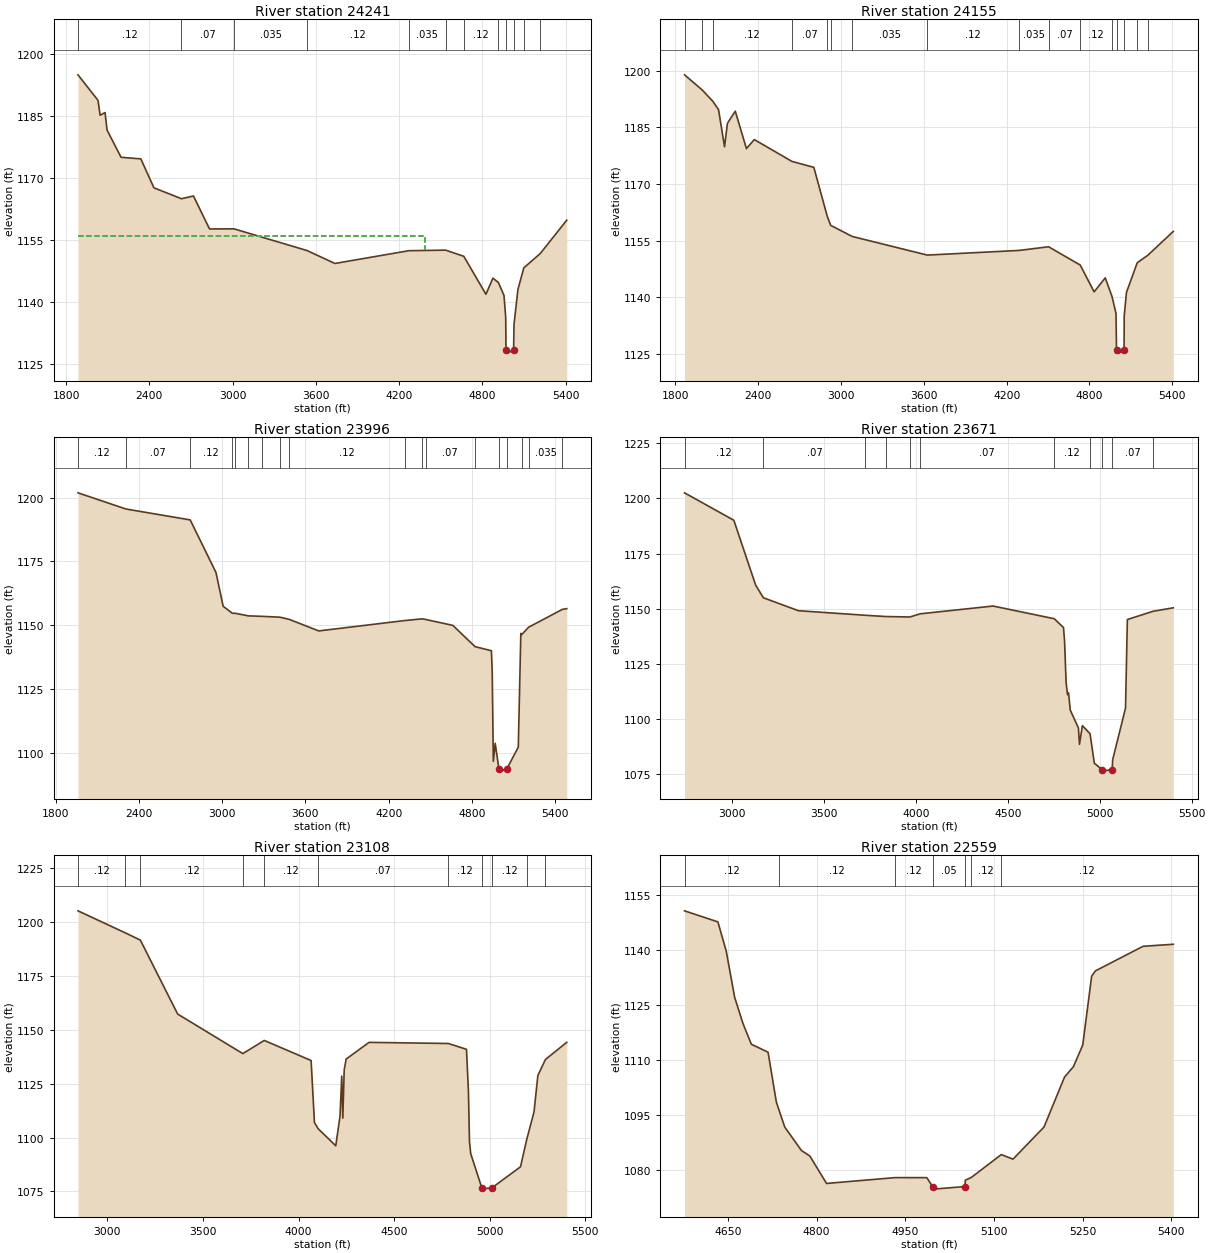
Type RM Length L Ch R = 1 ,24241   ,570,570,570
BEGIN DESCRIPTION:
CURRY CREEK 40.0
END DESCRIPTION:
XS GIS Cut Line= 3
      2127309.51     13882092.98        2124775.       13880275.
      2124425.01     13880075.01
#Sta/Elev= 30
  1885.4 1195.03  2030.1 1188.83  2044.9 1185.24  2080.5 1185.88  2095.2 1181.63
  2195.9 1175.05  2338.4 1174.67  2432.4 1167.67  2631.3 1165.01  2717.8 1165.68
  2833.3 1157.69  3009.6 1157.72  3535.1 1152.47  3736.9 1149.33  4269.3 1152.42
  4534.9 1152.56  4665.7 1151.07  4825.2 1141.87  4875.6 1145.78  4915.2  1144.7
  4955.3 1141.58  4967.7 1136.23  4969.7 1128.31  4970.9 1127.61  5024.5 1128.31
  5027.5  1134.6  5055.6 1143.01  5098.1 1148.27  5216.1 1151.72  5407.6 1159.82
#Mann= 12 ,-1 , 0
  1885.4     .12       0  2631.3     .07       0  3009.6    .035       0
  3535.1     .12       0  4269.3    .035       0  4534.9     .07       0
  4665.7     .12       0  4915.2     .07       0  4969.7     .05       0
  5024.5     .07       0  5098.1     .12       0  5216.1    .035       0
#XS Ineff= 2 , 0
       0 4384.33 1155.93               0
Permanent Ineff=
       F       F
Bank Sta=4969.7,5024.5
XS Rating Curve= 0 ,0
Exp/Cntr=0.3,0.1

Type RM Length L Ch R = 1 ,24155   ,159,159,159
BEGIN DESCRIPTION:
CURRY CREEK 39.2
END DESCRIPTION:
XS GIS Cut Line= 3
      2127428.99     13881973.25      2124836.07     13880214.66
      2124476.33     13880022.44
#Sta/Elev= 30
  1866.3 1198.96  1995.9  1194.9  2071.1 1191.95  2112.8 1189.73  2156.1 1179.89
  2177.1  1186.1    2234 1189.32  2314.8  1179.4  2371.7  1181.8  2644.1 1176.01
    2803 1174.43  2900.9 1161.37  2925.1 1159.06  3080.5 1156.12    3625 1151.17
  4291.6 1152.41  4503.4 1153.38  4732.9 1148.53  4833.5 1141.42  4914.3 1145.13
    4963 1140.21  4992.2 1135.69  4995.8 1125.88    4997 1125.18  5050.6 1125.88
  5051.6 1135.08  5067.9 1141.28  5145.9 1149.14  5222.3 1151.12  5407.2 1157.45
#Mann= 16 ,-1 , 0
  1866.3     .12       0  1995.9     .07       0  2071.1     .12       0
  2644.1     .07       0  2900.9     .12       0  2925.1     .07       0
  3080.5    .035       0    3625     .12       0  4291.6    .035       0
  4503.4     .07       0  4732.9     .12       0    4963     .07       0
  4995.8     .05       0  5050.6     .07       0  5145.9     .12       0
  5222.3    .035       0
Bank Sta=4995.8,5050.6
XS Rating Curve= 0 ,0
Exp/Cntr=0.3,0.1

Type RM Length L Ch R = 1 ,23996   ,325,325,325
BEGIN DESCRIPTION:
CURRY CREEK 39.1
END DESCRIPTION:
XS GIS Cut Line= 3
       2127506.5     13881692.76      2124925.45     13880090.19
       2124480.3     13879904.57
#Sta/Elev= 30
  1961.9 1201.83  2307.6  1195.5  2770.1 1191.25  2955.6 1170.73  3007.6 1157.49
  3074.7 1154.72  3092.1 1154.77  3188.5 1153.74  3288.3 1153.55  3416.2 1153.22
  3484.4 1152.35  3696.1 1147.85  4314.3  1151.9  4440.7 1152.57  4465.1 1152.34
  4662.1 1150.01  4821.9  1141.7  4939.6 1140.11  4945.5 1131.84  4953.4 1096.89
  4966.8 1103.93  4994.2 1093.75  4995.4 1093.05    5049 1093.75  5133.2 1102.43
  5151.6 1146.87  5157.4 1146.41  5207.6  1149.3  5451.3 1156.29  5482.3 1156.55
#Mann= 18 ,-1 , 0
  1961.9     .12       0  2307.6     .07       0  2770.1     .12       0
  3074.7     .07       0  3092.1     .12       0  3188.5    .035       0
  3288.3     .07       0  3416.2    .035       0  3484.4     .12       0
  4314.3    .035       0  4440.7     .12       0  4465.1     .07       0
  4821.9     .12       0  4994.2     .05       0    5049     .12       0
  5157.4     .12       0  5207.6    .035       0  5451.3     .07       0
Bank Sta=4994.2,5049
XS Rating Curve= 0 ,0
Exp/Cntr=0.3,0.1

Type RM Length L Ch R = 1 ,23671   ,563,563,563
BEGIN DESCRIPTION:
CURRY CREEK 39.0
END DESCRIPTION:
XS GIS Cut Line= 3
      2127045.83     13880930.35        2125075.       13879825.
      2124675.04       13879825.
#Sta/Elev= 30
  2740.6 1202.51    3009 1190.09  3127.7  1160.7  3169.8 1154.99  3360.7 1149.14
  3725.2 1147.07    3837  1146.5  3966.4  1146.3  4023.5 1147.74  4419.4 1151.26
  4752.1 1145.52  4802.8 1141.52  4808.5 1135.34  4816.8 1116.82  4824.5 1111.13
  4830.2 1111.92  4839.7 1104.11  4883.8  1096.1  4889.6 1088.65  4905.5 1097.11
  4947.2 1093.45  4970.6 1080.07  5012.8 1077.22    5014 1076.52  5067.6 1077.22
  5070.2 1081.66  5140.2 1105.06  5150.2 1145.14  5289.8 1148.88  5400.2 1150.45
#Mann= 11 ,-1 , 0
  2740.6     .12       0  3169.8     .07       0  3725.2     .12       0
    3837     .07       0  3966.4     .12       0  4023.5     .07       0
  4752.1     .12       0  4947.2     .07       0  5012.8     .05       0
  5067.6     .07       0  5289.8    .035       0
Bank Sta=5012.8,5067.6
XS Rating Curve= 0 ,0
Exp/Cntr=0.3,0.1

Type RM Length L Ch R = 1 ,23108   ,549,549,549
BEGIN DESCRIPTION:
CURRY CREEK 38.0
END DESCRIPTION:
XS GIS Cut Line= 3
      2127377.71     13880333.63        2125425.       13879425.
      2125024.98       13879375.
#Sta/Elev= 30
  2846.3 1205.27  3092.5  1195.1  3172.7 1191.67  3367.7 1157.36  3708.6    1139
  3820.9  1145.1  4065.9 1135.78  4083.3 1107.04  4102.3 1104.16  4194.9 1096.21
    4217 1109.93  4226.1 1128.57  4231.6 1109.02    4239  1131.4    4249 1136.45
  4368.9 1144.21    4784 1143.69  4878.7 1140.99  4888.8 1121.64  4894.3 1098.23
  4900.8 1092.58  4958.4 1076.79  4959.6 1076.09  5013.3 1076.79  5161.3 1086.45
  5192.9 1098.82  5231.9 1111.93    5252 1128.82  5291.8 1136.28  5403.2 1144.24
#Mann= 11 ,-1 , 0
  2846.3     .12       0  3092.5     .07       0  3172.7     .12       0
  3708.6     .07       0  3820.9     .12       0  4102.3     .07       0
    4784     .12       0  4958.4     .05       0  5013.3     .12       0
  5192.9     .12       0  5291.8     .12       0
#XS Ineff= 2 , 0
       0 4309.66 1139.67               0
Permanent Ineff=
       F       F
Bank Sta=4958.4,5013.3
XS Rating Curve= 0 ,0
Exp/Cntr=0.3,0.1

Type RM Length L Ch R = 1 ,22559   ,582,582,582
BEGIN DESCRIPTION:
CURRY CREEK 37.0
END DESCRIPTION:
XS GIS Cut Line= 3
      2125774.97     13878625.03        2125475.       13878925.
      2125125.03     13879124.98
#Sta/Elev= 30
  4576.4 1150.74  4632.9 1147.72  4647.1 1139.67  4661.2 1127.17  4675.4 1119.97
  4689.5 1114.35  4717.8 1112.18  4731.9 1098.52  4736.4 1096.37  4746.1 1091.74
  4774.4 1085.34  4788.5 1083.87  4816.8 1076.38  4932.7 1077.97  4986.5 1077.96
  4996.2 1075.53  4997.4 1074.83  5051.1 1075.53  5051.7 1077.28  5061.7    1078
  5112.5 1084.25  5132.4 1083.01  5184.9 1091.78  5219.5 1105.37  5234.6 1108.22
  5250.4 1114.11  5265.5 1132.93    5272 1134.37  5352.6 1141.07  5403.7 1141.62
#Mann= 7 ,-1 , 0
  4576.4     .12       0  4736.4     .12       0  4932.7     .12       0
  4996.2     .05       0  5051.1     .12       0  5061.7     .12       0
  5112.5     .12       0
Bank Sta=4996.2,5051.1
XS Rating Curve= 0 ,0
Exp/Cntr=0.3,0.1

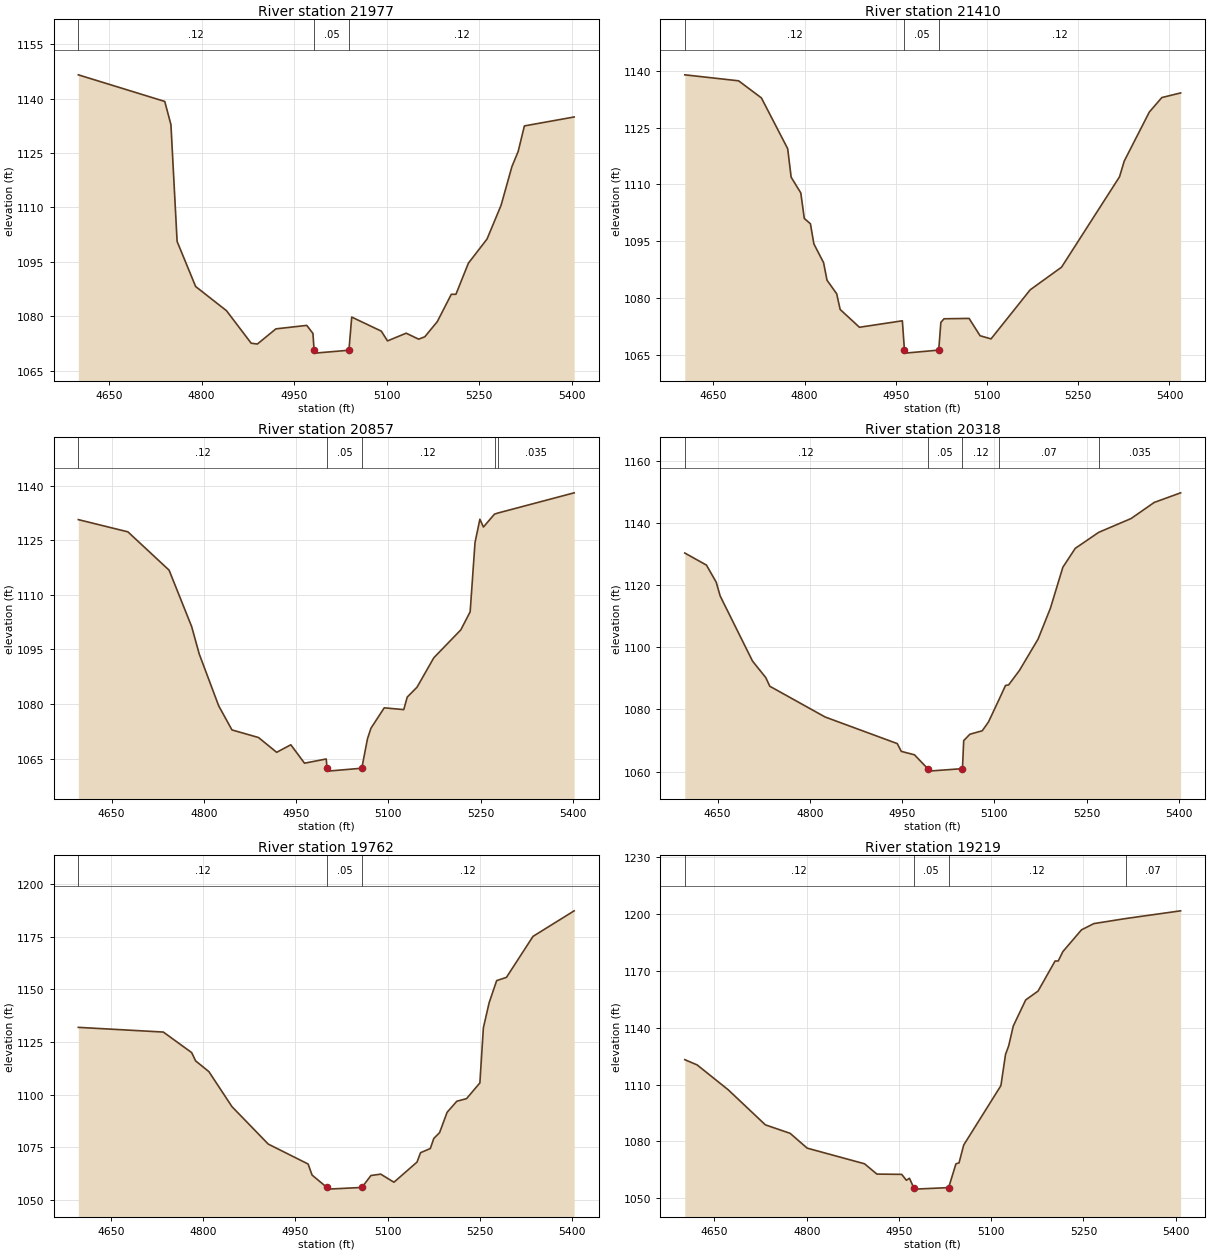
Type RM Length L Ch R = 1 ,21977   ,567,567,567
BEGIN DESCRIPTION:
CURRY CREEK 36.0
END DESCRIPTION:
XS GIS Cut Line= 3
        2125625.       13878475.        2125225.       13878475.
        2125175.     13878874.99
#Sta/Elev= 30
  4600.5 1146.57  4740.5 1139.23  4750.5 1132.83  4760.5 1100.63  4790.5  1088.2
  4840.5 1081.53  4880.5 1072.56  4890.5 1072.34  4920.5 1076.52  4970.5 1077.48
  4980.5 1075.26  4982.4 1070.63  4983.7 1069.83  5038.8 1070.63  5043.3 1079.77
  5091.2  1075.9  5101.3  1073.2  5131.5 1075.33  5151.7 1073.68  5161.7 1074.34
  5181.9 1078.51  5204.6 1086.05  5212.1 1086.05  5232.3 1094.63  5262.5  1101.3
  5285.2 1110.59  5302.8 1121.27  5312.9 1125.43    5323 1132.48  5403.6 1134.95
#Mann= 3 ,-1 , 0
  4600.5     .12       0  4982.4     .05       0  5038.8     .12       0
Bank Sta=4982.4,5038.8
XS Rating Curve= 0 ,0
Exp/Cntr=0.3,0.1

Type RM Length L Ch R = 1 ,21410   ,553,553,553
BEGIN DESCRIPTION:
CURRY CREEK 35.0
END DESCRIPTION:
XS GIS Cut Line= 3
      2125074.99       13878075.        2124725.       13878275.
        2124625.     13878674.99
#Sta/Elev= 30
  4602.9 1138.92  4691.4 1137.34  4728.9 1132.82  4772.1 1119.42  4777.8 1111.89
  4793.7 1107.72  4799.4    1101  4809.5 1099.59  4815.2 1094.26  4831.1 1089.34
  4836.8 1084.68  4852.7  1081.1  4858.4 1076.96  4890.1 1072.26  4960.7 1073.97
  4964.1 1066.23  4965.4 1065.43  5020.5 1066.23    5024 1073.54  5029.2  1074.5
  5070.4  1074.6  5088.5 1070.02  5106.5 1069.19  5170.9 1082.15  5222.5 1088.13
  5317.8 1111.99  5325.5 1116.12  5366.8 1129.09  5387.4 1132.92  5418.3 1134.14
#Mann= 3 ,-1 , 0
  4602.9     .12       0  4964.1     .05       0  5020.5     .12       0
Bank Sta=4964.1,5020.5
XS Rating Curve= 0 ,0
Exp/Cntr=0.3,0.1

Type RM Length L Ch R = 1 ,20857   ,539,539,539
BEGIN DESCRIPTION:
CURRY CREEK 34.0
END DESCRIPTION:
XS GIS Cut Line= 3
        2124425.       13877775.        2124225.       13878125.
      2123875.02     13878324.99
#Sta/Elev= 30
    4596 1130.67  4676.6 1127.31  4743.6 1116.78  4780.3 1101.27  4792.5  1093.8
  4824.2 1079.52  4845.8 1072.89    4889  1070.8  4918.5 1066.74  4941.5 1068.81
  4963.8 1063.75  4999.1 1064.91  5000.4 1062.37  5001.7 1061.57  5056.9 1062.37
  5066.1 1070.42  5071.8 1073.36  5093.4 1078.96  5125.1 1078.47  5130.8 1081.91
  5146.7 1084.63    5174 1092.71  5217.9 1100.38  5233.1 1105.34    5241 1124.37
  5248.9 1130.77  5254.7 1128.64  5272.7 1132.18  5278.7  1132.5  5402.2 1138.03
#Mann= 5 ,-1 , 0
    4596     .12       0  5000.4     .05       0  5056.9     .12       0
  5272.7     .07       0  5278.7    .035       0
Bank Sta=5000.4,5056.9
XS Rating Curve= 0 ,0
Exp/Cntr=0.3,0.1

Type RM Length L Ch R = 1 ,20318   ,556,556,556
BEGIN DESCRIPTION:
CURRY CREEK 33.0
END DESCRIPTION:
XS GIS Cut Line= 3
      2124224.96     13877575.02        2123875.       13877775.
      2123474.98       13877825.
#Sta/Elev= 30
  4596.6 1130.33  4631.8 1126.45  4647.7 1120.94  4654.1 1116.51  4706.7 1095.55
  4728.3 1090.22  4734.8 1087.45  4824.7 1077.55  4942.1 1068.98  4948.6 1066.48
  4970.1 1065.37  4991.6 1060.92  4992.8 1060.12  5048.1 1060.92  5050.1 1069.95
  5060.1 1071.99  5080.3 1073.12  5090.4 1075.96  5107.7 1083.24  5118.1 1087.71
  5123.1 1087.86  5140.8 1092.56    5171 1102.62  5191.1 1112.58  5211.3 1125.75
  5231.5 1131.84  5269.6 1136.99  5322.2 1141.43  5359.9 1146.62  5402.8 1149.71
#Mann= 5 ,-1 , 0
  4596.6     .12       0  4991.6     .05       0  5048.1     .12       0
  5107.7     .07       0  5269.6    .035       0
Bank Sta=4991.6,5048.1
XS Rating Curve= 0 ,0
Exp/Cntr=0.3,0.1

Type RM Length L Ch R = 1 ,19762   ,543,543,543
BEGIN DESCRIPTION:
CURRY CREEK 32.0
END DESCRIPTION:
XS GIS Cut Line= 3
      2124274.98     13877474.99        2123925.       13877275.
        2123725.     13876925.01
#Sta/Elev= 30
  4597.3 1131.98  4735.5 1129.75  4781.6 1119.97    4788 1116.03  4809.6 1110.91
  4847.1 1094.25  4906.1 1076.43  4970.9 1066.94  4977.4 1061.68  5001.5 1055.79
  5002.8 1054.99  5058.3 1055.79  5073.1 1061.47  5088.9 1062.13  5110.5 1058.28
    5148 1067.86  5153.7 1072.33  5169.6 1074.31  5175.3 1079.13  5184.7 1081.88
  5196.9 1091.55  5212.7 1096.81  5228.6 1098.07  5250.2 1105.54  5255.9 1131.79
  5265.3 1143.74  5277.5 1154.23  5293.4 1155.77  5336.6 1175.28  5403.5 1187.44
#Mann= 3 ,-1 , 0
  4597.3     .12       0  5001.5     .05       0  5058.3     .12       0
Bank Sta=5001.5,5058.3
XS Rating Curve= 0 ,0
Exp/Cntr=0.3,0.1

Type RM Length L Ch R = 1 ,19219   ,550,550,550
BEGIN DESCRIPTION:
CURRY CREEK 31.0
END DESCRIPTION:
XS GIS Cut Line= 3
        2124225.     13877324.99        2124275.       13876925.
        2124225.     13876525.02
#Sta/Elev= 30
  4601.8 1123.15  4621.9 1120.38  4672.3 1107.27  4732.8 1088.72  4773.1 1084.23
  4800.8 1076.41    4894 1068.16  4914.2  1062.7  4954.5 1062.56  4962.1 1059.45
  4967.1 1060.49    4974 1055.56  4975.3 1054.76  5030.8 1055.56  5042.7 1068.15
  5047.7 1068.62  5055.3 1078.06  5115.8 1109.45  5123.3 1125.95  5128.4 1130.41
  5135.9 1140.94  5156.1 1154.71  5176.2 1159.39  5203.9 1175.28    5209 1175.27
  5216.5 1180.23  5246.8 1191.73  5266.9 1195.03    5319 1197.72    5408 1201.78
#Mann= 4 ,-1 , 0
  4601.8     .12       0    4974     .05       0  5030.8     .12       0
    5319     .07       0
Bank Sta=4974,5030.8
XS Rating Curve= 0 ,0
Exp/Cntr=0.3,0.1

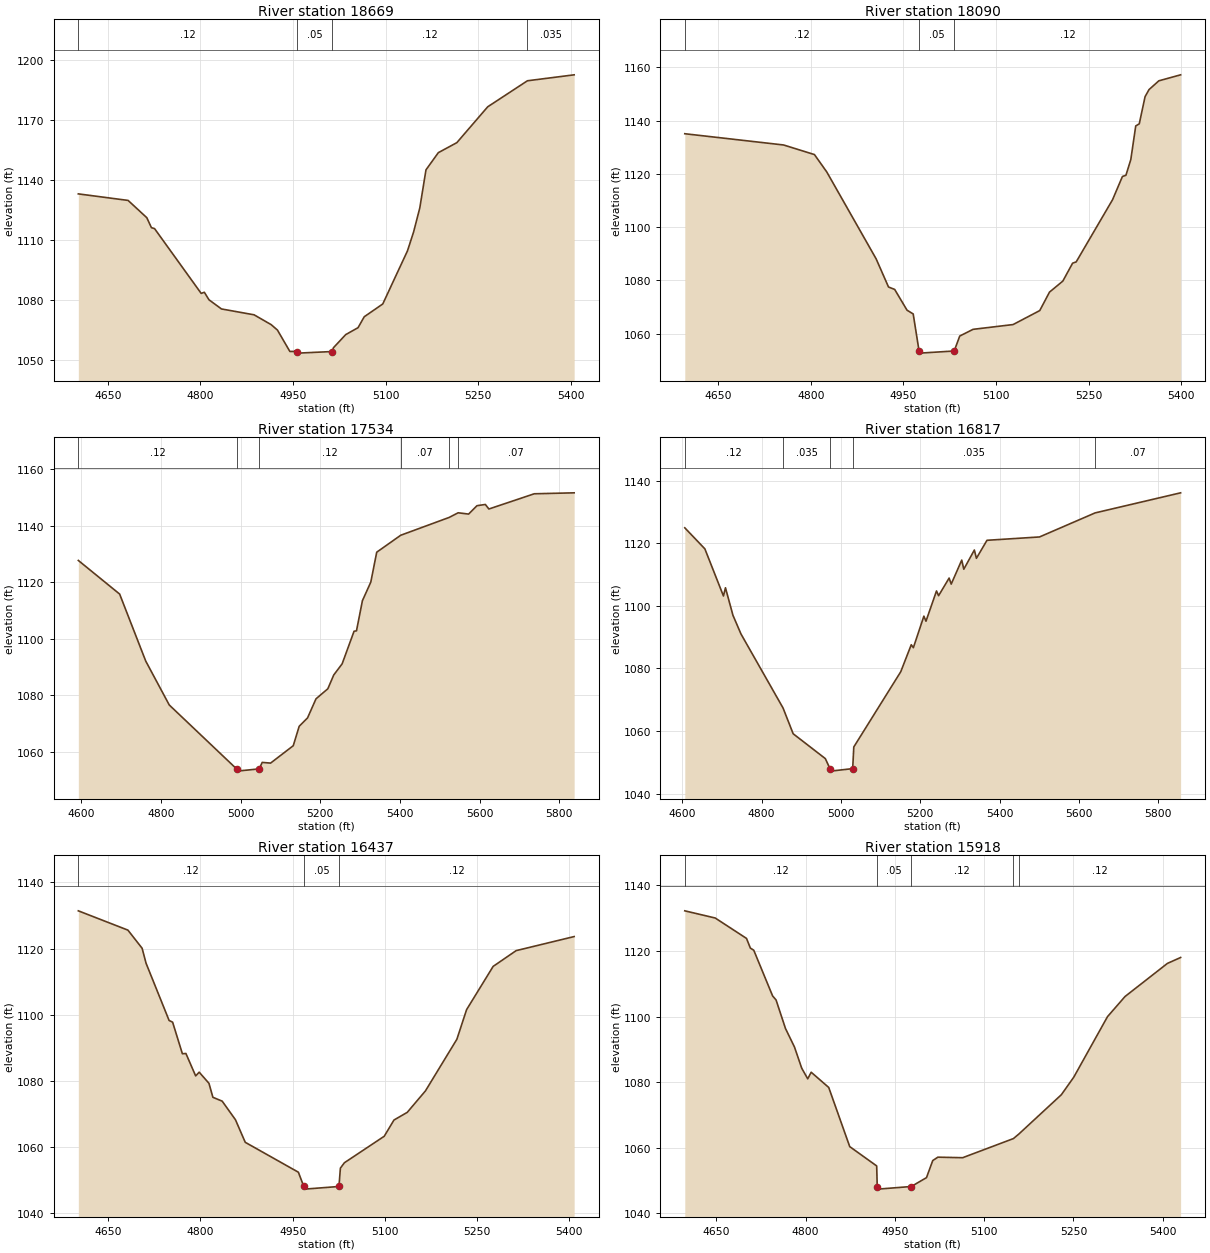
Type RM Length L Ch R = 1 ,18669   ,579,579,579
BEGIN DESCRIPTION:
CURRY CREEK 30.0
END DESCRIPTION:
XS GIS Cut Line= 3
        2124825.       13877475.        2124775.       13877075.
        2124775.     13876675.01
#Sta/Elev= 30
  4602.3 1133.19  4682.9 1129.92  4713.2 1121.28  4720.7 1116.29  4725.8  1115.8
  4801.3 1083.38  4806.4 1083.96  4813.9  1080.2  4834.1 1075.61    4887 1072.67
  4914.7 1067.74  4924.8 1065.04  4944.9 1054.35  4956.9  1054.3  4958.2  1053.5
  5013.7  1054.3  5015.4 1056.15  5035.4 1062.77  5055.4 1066.24  5065.4  1071.7
  5095.4  1078.1  5135.4 1104.66  5145.4 1114.19  5155.4 1126.19  5165.4 1145.22
  5185.4 1153.82  5215.4 1158.83  5265.4 1176.77  5329.7 1189.79  5405.4 1192.77
#Mann= 4 ,-1 , 0
  4602.3     .12       0  4956.9     .05       0  5013.7     .12       0
  5329.7    .035       0
Bank Sta=4956.9,5013.7
XS Rating Curve= 0 ,0
Exp/Cntr=0.3,0.1

Type RM Length L Ch R = 1 ,18090   ,556,556,556
BEGIN DESCRIPTION:
CURRY CREEK 29.0
END DESCRIPTION:
XS GIS Cut Line= 3
        2125325.     13877575.04        2125325.       13877175.
      2125124.98     13876824.96
#Sta/Elev= 30
  4595.8 1135.05  4755.8 1130.83  4805.8 1127.23  4825.8  1120.7  4905.8 1088.07
  4925.8 1077.52  4935.8 1076.61  4955.8 1068.82  4965.8  1067.4  4975.3  1053.5
  4976.6  1052.7  5032.2  1053.5  5041.2 1059.11  5062.8 1061.63  5127.6 1063.42
  5170.8 1068.67  5186.6  1075.6  5208.2 1079.74    5224 1086.46  5229.8 1086.93
  5288.8 1110.31  5304.7 1118.99  5310.4 1119.46  5318.3 1125.35  5326.3 1137.98
    5332 1138.76  5341.4 1148.95  5347.8 1151.61  5363.7 1154.91    5399 1157.16
#Mann= 3 ,-1 , 0
  4595.8     .12       0  4975.3     .05       0  5032.2     .12       0
Bank Sta=4975.3,5032.2
XS Rating Curve= 0 ,0
Exp/Cntr=0.3,0.1

Type RM Length L Ch R = 1 ,17534   ,717,717,717
BEGIN DESCRIPTION:
CURRY CREEK 28.0
END DESCRIPTION:
XS GIS Cut Line= 3
        2125625.       13877425.        2125825.       13877075.
      2125352.51     13876378.93
#Sta/Elev= 30
  4592.9 1127.67  4696.6 1115.76  4762.1 1092.02  4821.1 1076.48    4990 1053.85
  4991.3 1053.05  5046.9 1053.85  5054.4 1056.14  5075.4 1055.89  5132.3 1062.05
  5147.2 1068.93  5168.2 1071.91  5189.4 1078.66  5219.1 1082.22    5234 1087.12
    5255 1091.05  5284.9 1102.59    5291 1102.74  5305.9 1113.42  5326.9 1119.99
  5341.8 1130.59    5402 1136.59  5523.5  1142.9  5546.2 1144.55  5572.4 1144.09
  5593.4 1147.06  5614.4  1147.5  5623.3 1145.89  5737.1 1151.28  5837.3 1151.62
#Mann= 6 ,-1 , 0
  4592.9     .12       0    4990     .05       0  5046.9     .12       0
    5402     .07       0  5523.5    .035       0  5546.2     .07       0
Bank Sta=4990,5046.9
XS Rating Curve= 0 ,0
Exp/Cntr=0.3,0.1

Type RM Length L Ch R = 1 ,16817   ,380,380,380
BEGIN DESCRIPTION:
CURRY CREEK 27.0
END DESCRIPTION:
XS GIS Cut Line= 3
        2126475.     13877324.97      2126414.33     13876930.02
      2126148.69     13876122.68
#Sta/Elev= 30
  4606.6 1124.97  4657.2 1118.24    4704 1103.17  4709.1  1105.8    4728 1096.98
  4748.2 1091.02  4854.2 1067.36  4879.7 1059.12  4960.7 1051.18  4972.5 1047.97
  4973.9 1047.17  5029.7 1047.97  5032.5  1054.9  5150.8 1078.95  5177.3 1087.58
  5182.6 1086.65  5209.1 1096.72  5214.4 1095.11  5240.9 1104.78  5246.2 1103.27
  5272.7  1108.9    5278 1106.97  5304.5 1114.65  5309.7 1111.73  5336.3 1117.87
  5341.5 1115.22  5368.1 1120.98  5500.5 1122.05  5640.6 1129.74  5856.1 1136.16
#Mann= 5 ,-1 , 0
  4606.6     .12       0  4854.2    .035       0  4972.5     .05       0
  5029.7    .035       0  5640.6     .07       0
Bank Sta=4972.5,5029.7
XS Rating Curve= 0 ,0
Exp/Cntr=0.3,0.1

Type RM Length L Ch R = 1 ,16437   ,519,519,519
BEGIN DESCRIPTION:
CURRY CREEK 26.0
END DESCRIPTION:
XS GIS Cut Line= 3
        2126975.       13877225.        2126775.       13876875.
      2126575.01     13876525.02
#Sta/Elev= 30
  4601.5  1131.4  4682.1 1125.57  4705.2 1120.09  4711.6 1115.58  4749.1 1098.26
  4754.8 1097.75  4770.7  1088.2  4776.4 1088.29  4792.3  1081.5    4798 1082.64
  4813.9 1079.27  4820.3 1075.04  4835.4 1073.88    4857 1068.26  4872.9 1061.44
  4959.3  1052.4  4968.1 1048.09  4969.4 1047.29  5025.3 1048.09  5027.6 1053.63
  5034.1 1055.26  5098.9 1063.27  5114.7 1068.17  5136.3 1070.49  5165.9 1076.98
    5217 1092.58  5232.8 1101.53    5276 1114.61  5313.4 1119.37  5407.7 1123.62
#Mann= 3 ,-1 , 0
  4601.5     .12       0  4968.1     .05       0  5025.3     .12       0
Bank Sta=4968.1,5025.3
XS Rating Curve= 0 ,0
Exp/Cntr=0.3,0.1

Type RM Length L Ch R = 1 ,15918   ,542,542,542
BEGIN DESCRIPTION:
CURRY CREEK 25.0
END DESCRIPTION:
XS GIS Cut Line= 3
      2127425.01     13877025.02        2127225.       13876675.
      2126874.96     13876424.97
#Sta/Elev= 30
  4596.9 1132.22    4648 1130.03  4700.6 1123.81  4707.1 1120.86  4712.8 1120.21
  4744.5 1106.27  4750.3 1105.04  4766.1 1096.35  4781.2 1090.71  4793.4 1084.25
  4803.5    1081  4809.3 1083.01  4838.8 1078.37  4874.1 1060.33  4919.4 1054.44
  4920.3 1048.17  4921.6 1047.37  4977.5 1048.17  5003.1 1050.87  5013.6 1056.08
  5022.2 1057.11  5063.9 1056.95  5149.2 1062.78  5158.1 1064.13  5229.8 1076.16
  5250.7 1081.53  5307.3 1099.95  5336.8  1106.1    5408 1116.19  5430.2 1117.99
#Mann= 5 ,-1 , 0
  4596.9     .12       0  4920.3     .05       0  4977.5     .12       0
  5149.2     .07       0  5158.1     .12       0
Bank Sta=4920.3,4977.5
XS Rating Curve= 0 ,0
Exp/Cntr=0.3,0.1

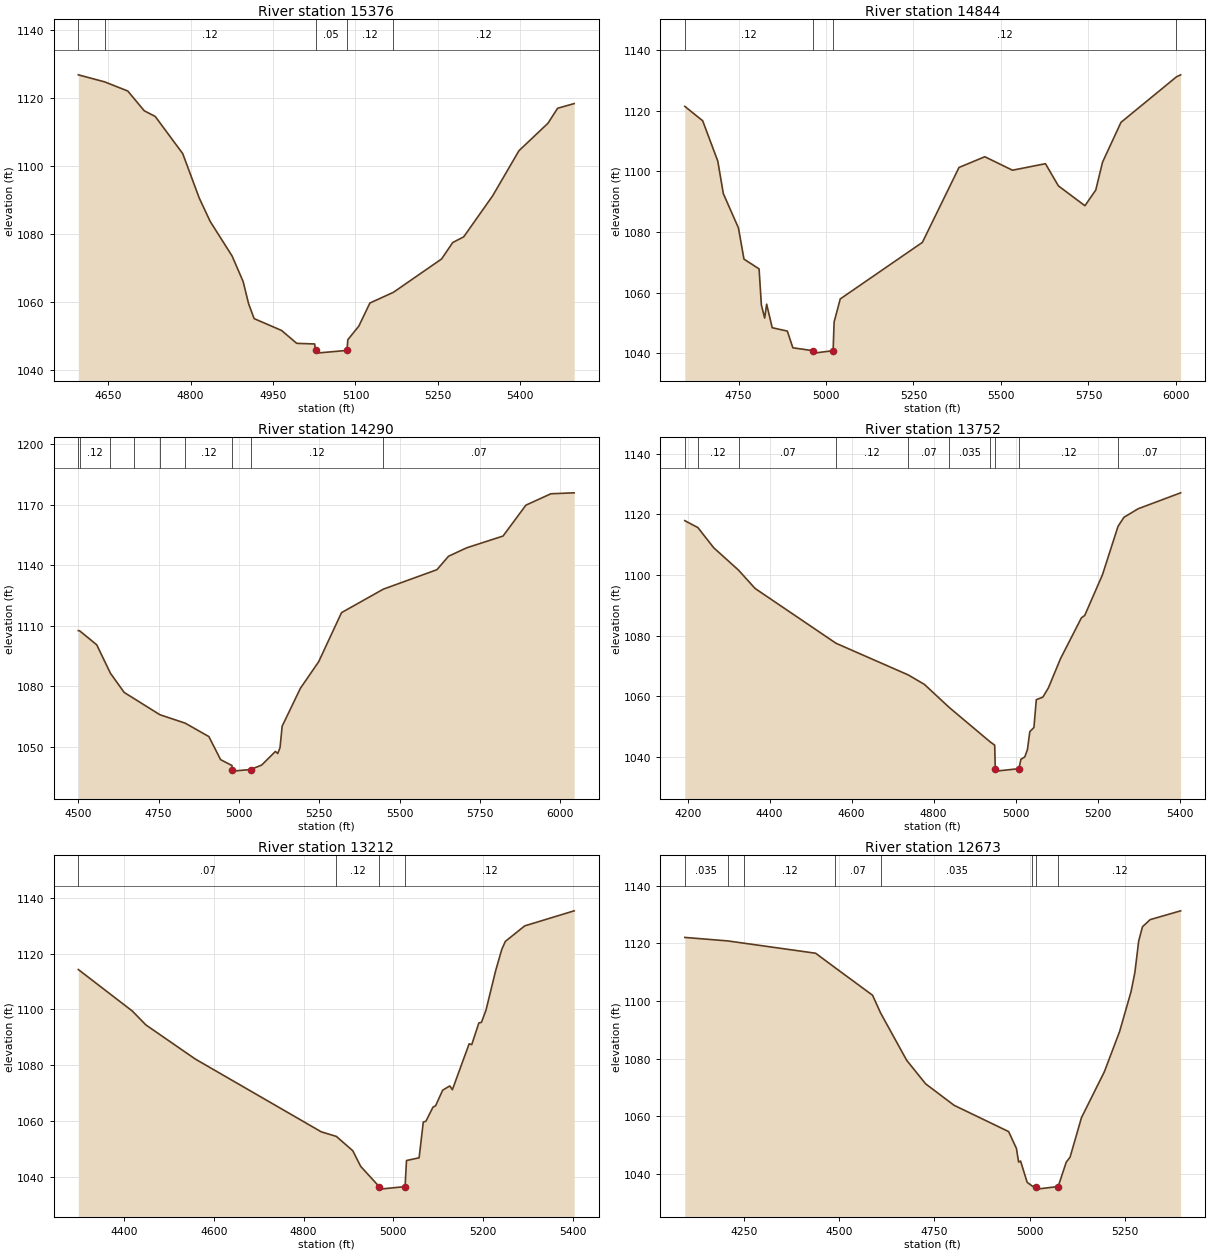
Type RM Length L Ch R = 1 ,15376   ,532,532,532
BEGIN DESCRIPTION:
CURRY CREEK 24.0
END DESCRIPTION:
XS GIS Cut Line= 3
      2127875.03       13876225.        2127475.       13876225.
      2126975.03       13876175.
#Sta/Elev= 30
  4595.6 1126.68  4643.5 1124.61  4685.6 1121.92  4715.6 1116.11  4735.6 1114.44
  4785.6 1103.52  4815.6 1090.48  4835.6 1083.58  4875.6 1073.38  4895.6 1065.89
  4905.6 1059.34  4915.6    1055  4965.6 1051.51  4993.1 1047.73  5025.8 1047.54
  5027.3 1045.65  5028.6 1044.85  5084.6 1045.65  5086.1 1048.79  5106.2 1052.81
  5126.3 1059.58    5169 1062.72  5256.9 1072.55    5277 1077.36  5297.1 1079.05
  5349.9 1091.14  5397.6 1104.36  5450.4 1112.44    5468 1116.85  5498.1 1118.22
#Mann= 5 ,-1 , 0
  4595.6     .07       0  4643.5     .12       0  5027.3     .05       0
  5084.6     .12       0    5169     .12       0
Bank Sta=5027.3,5084.6
XS Rating Curve= 0 ,0
Exp/Cntr=0.3,0.1

Type RM Length L Ch R = 1 ,14844   ,554,554,554
BEGIN DESCRIPTION:
CURRY CREEK 23.0
END DESCRIPTION:
XS GIS Cut Line= 3
      2127724.98     13875924.99        2127375.       13875725.
      2126389.16     13875961.06
#Sta/Elev= 30
  4596.5 1121.38  4647.6 1116.63  4690.8 1103.33  4706.6 1092.64  4749.8 1081.32
  4765.6 1071.06  4808.8 1067.83  4815.3 1055.95  4824.7 1051.65  4830.4 1056.22
  4846.3 1048.46  4889.5 1047.35  4905.3 1041.85    4963 1040.89  4964.4 1040.09
  5020.3 1040.89  5023.2 1050.36  5040.7 1057.94  5275.4 1076.57    5380 1101.24
  5453.8 1104.78  5532.8 1100.34  5627.1 1102.49    5664 1095.19  5739.9 1088.64
  5770.8 1093.81  5790.1 1102.96  5842.8  1116.1  6001.3 1131.09  6013.3 1131.76
#Mann= 4 ,-1 , 0
  4596.5     .12       0    4963     .05       0  5020.3     .12       0
  6001.3     .07       0
Bank Sta=4963,5020.3
XS Rating Curve= 0 ,0
Exp/Cntr=0.3,0.1

Type RM Length L Ch R = 1 ,14290   ,538,538,538
BEGIN DESCRIPTION:
CURRY CREEK 22.0
END DESCRIPTION:
XS GIS Cut Line= 3
      2127724.97     13875624.97        2127425.       13875225.
      2126732.06     13874445.67
#Sta/Elev= 30
  4500.1  1107.6  4503.9 1107.55  4557.3  1100.6  4600.1 1086.47  4642.8 1076.98
  4674.6 1073.83  4753.6 1065.96  4832.4 1061.78  4906.3 1055.11  4942.8 1043.68
  4978.2 1040.77  4978.4 1038.79  4979.7 1037.99    5036 1038.79  5070.7 1041.01
  5113.4 1047.76  5120.5 1046.69  5127.6 1049.57  5134.3 1060.25  5191.1 1079.04
    5248 1092.22  5319.1 1116.53  5449.3 1128.17  5615.9  1137.8  5651.9 1144.45
  5708.7 1148.66  5821.6 1154.47  5892.7 1169.77  5970.5 1175.43  6042.9 1175.89
#Mann= 9 ,-1 , 0
  4500.1     .07       0  4503.9     .12       0  4600.1     .07       0
  4674.6     .12       0  4753.6     .07       0  4832.4     .12       0
  4978.4     .05       0    5036     .12       0  5449.3     .07       0
Bank Sta=4978.4,5036
XS Rating Curve= 0 ,0
Exp/Cntr=0.3,0.1

Type RM Length L Ch R = 1 ,13752   ,540,540,540
BEGIN DESCRIPTION:
CURRY CREEK 21.0
END DESCRIPTION:
XS GIS Cut Line= 3
        2127875.     13875675.02        2127775.       13874875.
      2127424.96     13874674.98
#Sta/Elev= 30
  4193.1 1117.92  4225.1 1115.63  4263.7 1108.97  4324.4 1101.57  4364.4 1095.57
  4561.9 1077.48  4738.2 1067.03  4777.6  1063.9  4837.7 1056.35  4937.2 1045.03
    4949 1043.85  4950.4  1036.1  4951.7  1035.3    5008  1036.1    5013 1039.21
  5022.4 1039.98  5028.9 1042.44  5034.6  1048.3  5044.7 1049.71  5050.5 1058.88
  5066.3 1059.68    5080 1062.77  5109.5 1072.39  5160.6 1085.89  5168.5 1086.63
  5211.7 1100.02  5249.9 1116.06  5264.2 1119.02  5298.8 1121.84  5402.5  1127.1
#Mann= 10 ,-1 , 0
  4193.1     .07       0  4225.1     .12       0  4324.4     .07       0
  4561.9     .12       0  4738.2     .07       0  4837.7    .035       0
  4937.2     .12       0  4950.4     .05       0    5008     .12       0
  5249.9     .07       0
Bank Sta=4950.4,5008
XS Rating Curve= 0 ,0
Exp/Cntr=0.3,0.1

Type RM Length L Ch R = 1 ,13212   ,539,539,539
BEGIN DESCRIPTION:
CURRY CREEK 20.0
END DESCRIPTION:
XS GIS Cut Line= 3
        2128225.       13875525.        2128275.       13874825.
        2128475.       13874475.
#Sta/Elev= 30
  4298.1 1114.27  4418.4 1099.42  4448.5 1094.47  4558.8 1082.23  4839.5 1056.18
  4873.1 1054.55  4909.7 1049.42  4927.2 1043.85  4968.5 1036.58  4969.9 1035.68
  5026.2 1036.58  5029.4 1045.92  5057.5 1046.89  5066.8 1059.68  5072.6 1059.97
  5088.4 1065.02  5094.2 1065.51    5110  1071.1  5125.9 1072.61  5131.6 1071.26
    5169 1087.69  5174.8  1087.4  5190.6 1095.15  5196.4 1095.36  5206.5 1099.71
  5228.1 1113.89  5241.8 1121.53  5249.7 1124.35  5292.9  1129.9    5403 1135.28
#Mann= 4 ,-1 , 0
  4298.1     .07       0  4873.1     .12       0  4968.5     .05       0
  5026.2     .12       0
Bank Sta=4968.5,5026.2
XS Rating Curve= 0 ,0
Exp/Cntr=0.3,0.1

Type RM Length L Ch R = 1 ,12673   ,549,549,549
BEGIN DESCRIPTION:
CURRY CREEK 19.0
END DESCRIPTION:
XS GIS Cut Line= 3
      2128539.33     13875956.07        2128725.       13875075.
        2128725.     13874675.02
#Sta/Elev= 30
  4095.3 1122.09  4207.9 1120.88  4251.4 1120.07  4438.4  1116.6  4488.7 1111.66
  4587.8    1102    4609  1095.8  4677.2 1079.42  4726.9 1071.23  4801.5 1063.78
  4944.6 1054.64  4965.1 1048.78  4970.8 1044.04  4975.9 1044.42  4993.2 1037.02
  5006.9 1035.68  5016.9 1035.55  5018.2 1034.65  5074.6 1035.55  5095.7 1044.02
  5105.7 1045.74  5135.7 1059.51  5195.7 1075.43  5235.7 1089.42  5265.7 1103.26
  5275.7 1109.88  5285.7 1120.81  5295.7 1125.81  5315.7 1128.27  5395.7 1131.33
#Mann= 8 ,-1 , 0
  4095.3    .035       0  4207.9     .07       0  4251.4     .12       0
  4488.7     .07       0    4609    .035       0  5006.9     .12       0
  5016.9    .035       0  5074.6     .12       0
Bank Sta=5016.9,5074.6
XS Rating Curve= 0 ,0
Exp/Cntr=0.3,0.1