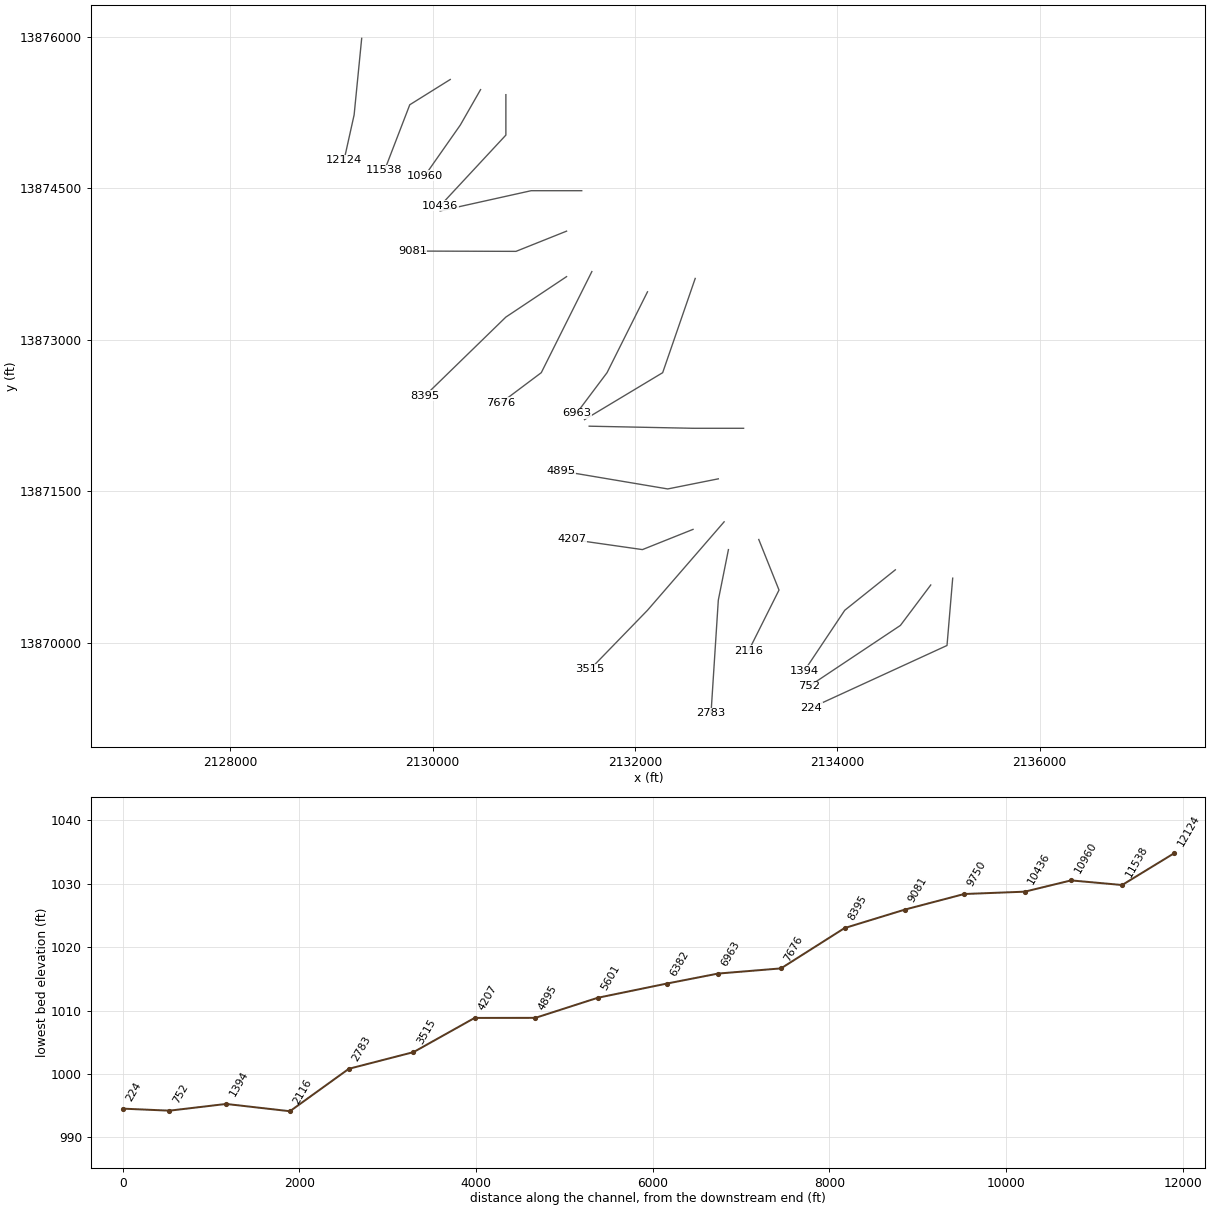
HEC-RAS study CURRY CREEK.prj: CURRY CREEK Base Level Engineering

--- CURRY CREEK.g01 (geometry) --- (continued)

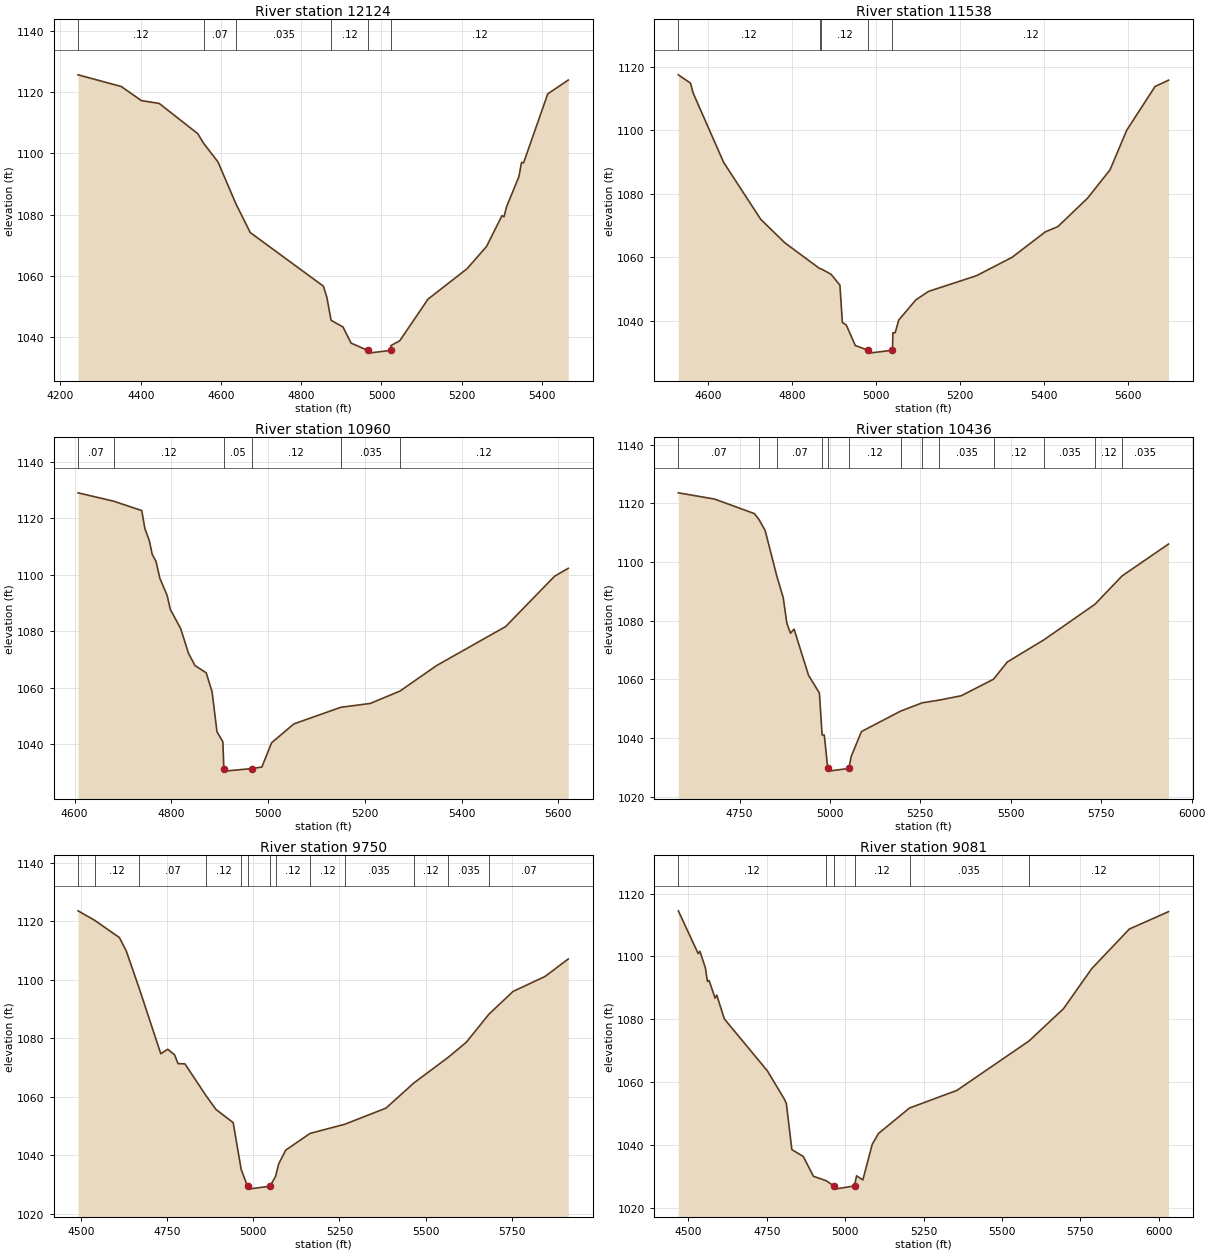
Type RM Length L Ch R = 1 ,12124   ,586,586,586
BEGIN DESCRIPTION:
CURRY CREEK 18.0
END DESCRIPTION:
XS GIS Cut Line= 3
      2129299.75     13875982.12        2129225.       13875225.
      2129124.99     13874774.98
#Sta/Elev= 30
  4243.8 1125.68  4351.4 1121.87  4401.7 1117.26  4445.9 1116.35    4542 1106.49
  4556.7 1103.34  4592.6 1097.23  4637.3 1083.56    4673 1074.18  4855.4 1056.66
  4863.9 1053.05  4874.5 1045.52  4904.1 1043.35  4924.2 1038.09  4965.6  1035.7
    4967  1034.8  5023.5  1035.7  5023.8 1037.27  5045.6 1038.84    5116 1052.42
  5213.3 1062.35    5262 1069.65  5300.4 1079.69  5305.5 1079.33  5311.9 1082.63
  5342.6 1092.42  5349.1 1097.06  5354.2 1096.93  5414.4 1119.44  5465.6 1123.98
#Mann= 6 ,-1 , 0
  4243.8     .12       0  4556.7     .07       0  4637.3    .035       0
  4874.5     .12       0  4965.6     .05       0  5023.5     .12       0
Bank Sta=4965.6,5023.5
XS Rating Curve= 0 ,0
Exp/Cntr=0.3,0.1

Type RM Length L Ch R = 1 ,11538   ,578,578,578
BEGIN DESCRIPTION:
CURRY CREEK 17.0
END DESCRIPTION:
XS GIS Cut Line= 3
      2130174.98     13875574.99        2129775.       13875325.
        2129525.     13874674.99
#Sta/Elev= 30
  4528.4 1117.49  4557.3 1114.88  4563.7 1111.74  4636.3 1089.93  4724.7 1071.97
  4782.5 1064.53    4865 1056.47  4869.1 1056.33  4892.2 1054.67  4913.4 1051.22
  4919.3 1039.49  4928.7 1038.64    4950 1032.22  4980.7 1030.71  4982.1 1029.81
  5038.7 1030.71  5039.7 1036.23  5045.1 1036.24  5053.6 1040.23  5094.4  1046.6
  5124.4 1049.25    5239 1054.21  5323.6 1059.99  5402.9 1068.01  5432.9 1069.69
  5503.6 1078.64  5557.2 1087.59  5596.8 1100.03  5664.3 1113.81  5696.5 1115.81
#Mann= 5 ,-1 , 0
  4528.4     .12       0    4865     .07       0  4869.1     .12       0
  4980.7     .05       0  5038.7     .12       0
Bank Sta=4980.7,5038.7
XS Rating Curve= 0 ,0
Exp/Cntr=0.3,0.1

Type RM Length L Ch R = 1 ,10960   ,524,524,524
BEGIN DESCRIPTION:
CURRY CREEK 16.0
END DESCRIPTION:
XS GIS Cut Line= 3
      2130474.98     13875474.97        2130275.       13875125.
        2129925.     13874625.01
#Sta/Elev= 30
  4607.2 1128.97  4680.6 1126.02  4738.9  1122.7  4745.4 1116.33  4754.7 1111.96
  4760.5 1107.23  4768.4 1104.71  4776.3 1098.77  4791.4 1092.67  4797.9 1087.76
  4819.5  1080.9  4835.4 1072.26    4849 1067.87  4872.1 1065.33  4884.3  1058.6
  4894.4 1044.47  4906.6  1040.9  4908.6 1031.44  4909.9 1030.54  4966.6 1031.44
  4987.2    1032  5007.4 1040.59  5053.4 1047.25  5150.3 1053.11  5211.3 1054.48
    5273 1058.88  5348.1 1067.85  5491.1 1081.66  5592.3 1099.47  5620.6 1102.27
#Mann= 6 ,-1 , 0
  4607.2     .07       0  4680.6     .12       0  4908.6     .05       0
  4966.6     .12       0  5150.3    .035       0    5273     .12       0
Bank Sta=4908.6,4966.6
XS Rating Curve= 0 ,0
Exp/Cntr=0.3,0.1

Type RM Length L Ch R = 1 ,10436   ,686,686,686
BEGIN DESCRIPTION:
CURRY CREEK 15.0
END DESCRIPTION:
XS GIS Cut Line= 3
        2130725.       13875425.        2130725.       13875025.
      2130075.03     13874325.03
#Sta/Elev= 30
  4580.9 1123.62  4680.9  1121.5  4790.9 1116.55  4803.4 1114.61  4820.9 1110.79
  4853.2 1095.21  4870.9 1087.87  4880.9 1079.16  4890.9 1075.76  4900.9 1077.15
  4940.9 1061.41  4970.9 1055.38  4978.4 1041.07  4979.4 1041.07  4984.3 1041.07
  4994.1 1029.66  4995.5 1028.76  5052.1 1029.66  5058.8 1033.79  5087.2 1042.26
  5195.5 1049.22  5255.1 1052.04  5302.4 1052.98    5363 1054.45  5452.3  1060.1
  5490.3 1065.96  5592.5 1073.59  5732.7 1085.64  5807.8 1095.31  5936.1 1106.17
#Mann= 13 ,-1 , 0
  4580.9     .07       0  4803.4     .12       0  4853.2     .07       0
  4979.4     .12       0  4994.1     .05       0  5052.1     .12       0
  5195.5     .12       0  5255.1     .12       0  5302.4    .035       0
  5452.3     .12       0  5592.5    .035       0  5732.7     .12       0
  5807.8    .035       0
Bank Sta=4994.1,5052.1
XS Rating Curve= 0 ,0
Exp/Cntr=0.3,0.1

Type RM Length L Ch R = 1 ,9750    ,669,669,669
BEGIN DESCRIPTION:
CURRY CREEK 14.0
END DESCRIPTION:
XS GIS Cut Line= 3
      2131474.97       13874475.        2130975.       13874475.
      2130075.02     13874275.01
#Sta/Elev= 30
    4492 1123.57    4540 1120.34    4612 1114.42    4632 1109.81  4669.5 1097.03
    4732 1074.69    4752 1076.23    4772 1074.33    4782  1071.3    4802 1071.24
  4863.4 1060.32    4892 1055.65    4942 1051.13  4965.2 1035.11  4983.5 1029.39
    4985 1028.39  5049.1 1029.39    5065 1032.78  5073.9 1037.01  5094.4 1041.73
  5165.2 1047.45  5265.5 1050.57  5385.1 1056.09  5466.1  1064.7  5566.3 1073.52
  5618.1 1078.61  5684.1 1088.26  5753.9 1096.01  5846.1 1101.09  5913.9  1107.1
#Mann= 13 ,-1 , 0
    4492     .07       0    4540     .12       0  4669.5     .07       0
  4863.4     .12       0  4965.2    .033       0  4983.5    .033       0
  5049.1    .033       0    5065     .12       0  5165.2     .12       0
  5265.5    .035       0  5466.1     .12       0  5566.3    .035       0
  5684.1     .07       0
Bank Sta=4983.5,5049.1
XS Rating Curve= 0 ,0
Exp/Cntr=0.3,0.1

Type RM Length L Ch R = 1 ,9081    ,686,686,686
BEGIN DESCRIPTION:
CURRY CREEK 13.0
END DESCRIPTION:
XS GIS Cut Line= 3
        2131325.       13874075.        2130825.       13873875.
      2129799.92     13873877.93
#Sta/Elev= 30
  4467.6 1114.53  4530.9 1100.92  4536.3 1101.66  4553.8 1096.41  4560.5 1092.05
  4565.9 1092.33  4584.7 1086.75  4590.1 1087.72  4614.3 1080.13  4751.7 1063.57
  4805.5 1054.64  4812.2 1053.14  4829.7 1038.52  4866.1 1036.34  4898.4 1030.04
  4939.7 1028.59  4963.9 1026.94  4965.4 1025.94  5029.5 1026.94  5036.1 1030.18
  5056.1 1028.88  5086.1 1040.22  5106.1 1043.67  5205.2 1051.77  5356.1 1057.37
  5586.5 1073.13  5696.1 1083.37  5786.1 1096.12  5906.1 1108.73  6031.2 1114.27
#Mann= 6 ,-1 , 0
  4467.6     .12       0  4939.7     .12       0  4963.9     .05       0
  5029.5     .12       0  5205.2    .035       0  5586.5     .12       0
Bank Sta=4963.9,5029.5
XS Rating Curve= 0 ,0
Exp/Cntr=0.3,0.1

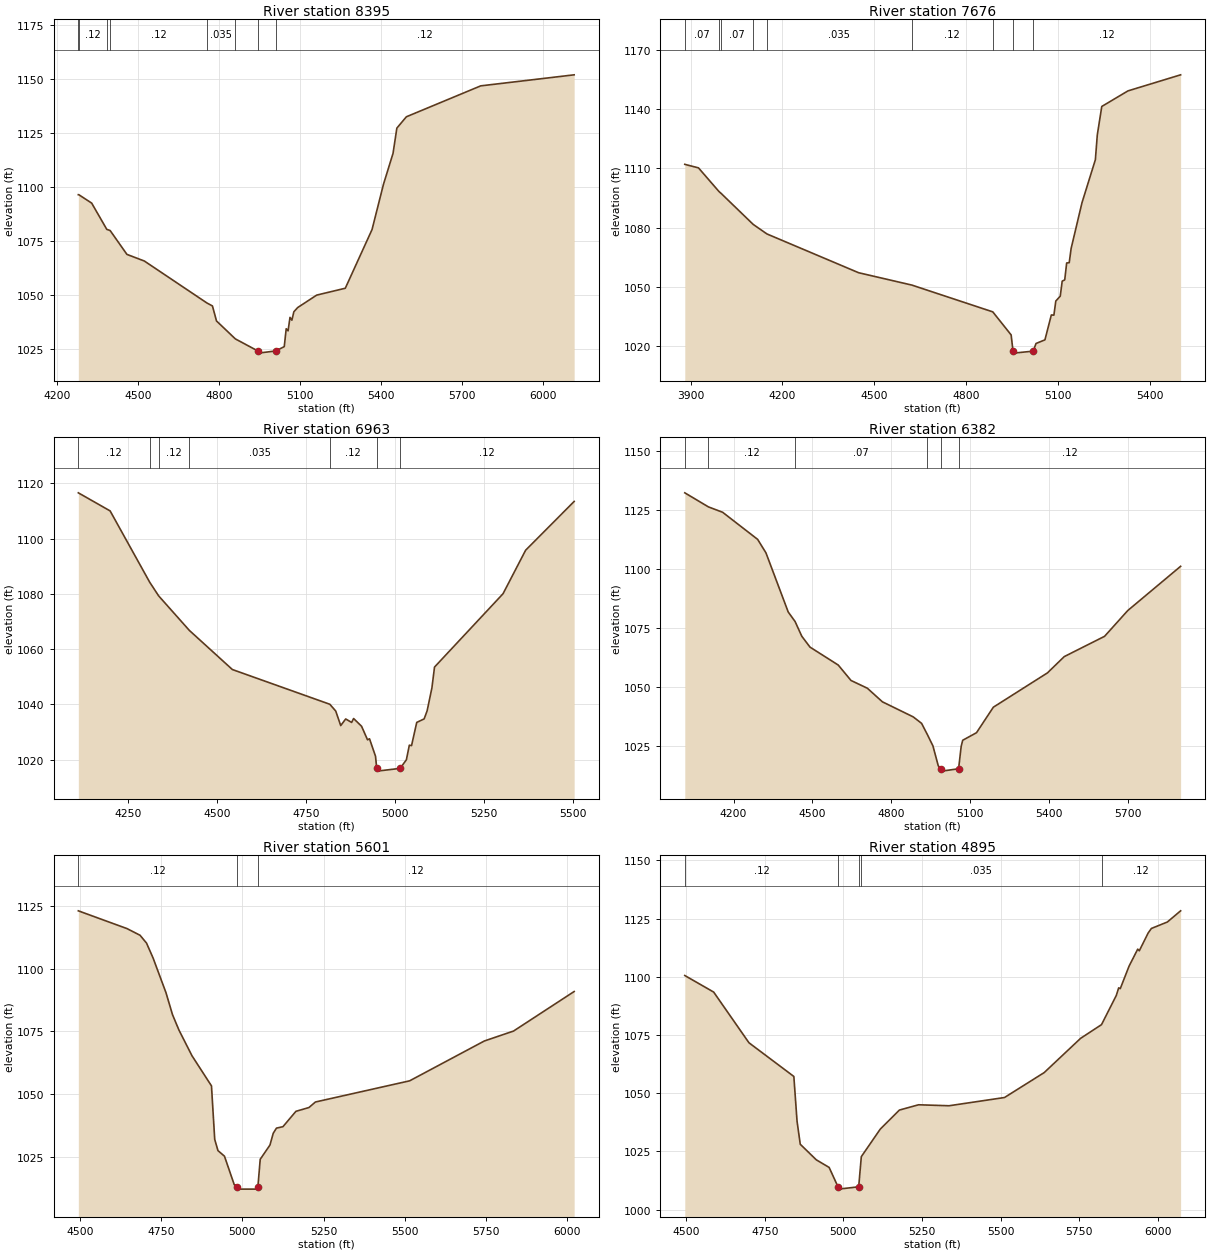
Type RM Length L Ch R = 1 ,8395    ,719,719,719
BEGIN DESCRIPTION:
CURRY CREEK 12.0
END DESCRIPTION:
XS GIS Cut Line= 3
      2131324.97     13873624.98        2130725.       13873225.
      2129924.76     13872445.65
#Sta/Elev= 30
  4278.8 1096.38  4280.6 1096.38  4328.3 1092.48  4384.3 1080.32  4396.7 1079.79
    4459 1068.73  4523.6 1065.66    4756 1046.19    4776 1044.85    4791 1037.91
  4860.9  1029.6  4944.5 1024.01    4946 1023.01  5010.2 1024.01  5042.2 1026.01
  5049.4  1034.3  5056.4 1033.33  5063.5 1039.56  5070.5 1038.26  5077.7 1042.14
  5091.8  1044.1  5162.5 1049.88  5268.5 1053.06  5367.6 1080.22    5410 1101.19
  5445.5 1115.54  5459.6 1127.21  5494.9 1132.46  5770.6 1146.78  6116.9 1151.89
#Mann= 8 ,-1 , 0
  4278.8    .035       0  4280.6     .12       0  4384.3    .035       0
  4396.7     .12       0    4756    .035       0  4860.9     .12       0
  4944.5     .05       0  5010.2     .12       0
Bank Sta=4944.5,5010.2
XS Rating Curve= 0 ,0
Exp/Cntr=0.3,0.1

Type RM Length L Ch R = 1 ,7676    ,713,713,713
BEGIN DESCRIPTION:
CURRY CREEK 11.0
END DESCRIPTION:
XS GIS Cut Line= 3
      2131575.01     13873675.02        2131075.       13872675.
      2130674.97     13872374.97
#Sta/Elev= 30
  3881.2 1112.05  3925.9 1110.26  3992.8  1098.3  3999.2 1097.44  4104.4  1081.7
  4149.3 1076.87  4448.6 1057.27  4622.1 1051.04  4886.3  1037.5  4946.2 1025.85
  4952.4 1017.65  4953.9 1016.65  5018.1 1017.65  5027.4 1021.52  5056.5 1023.36
  5077.4 1035.95  5085.7 1035.84    5092 1042.97  5106.5 1045.44  5112.8 1053.02
  5121.1 1053.67  5127.4  1062.2  5135.7 1062.34    5142 1069.55  5177.4 1092.64
  5221.1 1114.39  5227.4 1126.92    5242 1141.29  5327.4 1149.16  5499.3 1157.28
#Mann= 9 ,-1 , 0
  3881.2     .07       0  3992.8     .12       0  3999.2     .07       0
  4104.4     .12       0  4149.3    .035       0  4622.1     .12       0
  4886.3     .12       0  4952.4     .05       0  5018.1     .12       0
Bank Sta=4952.4,5018.1
XS Rating Curve= 0 ,0
Exp/Cntr=0.3,0.1

Type RM Length L Ch R = 1 ,6963    ,581,581,581
BEGIN DESCRIPTION:
CURRY CREEK 10.0
END DESCRIPTION:
XS GIS Cut Line= 3
      2132124.99     13873474.98        2131725.       13872675.
        2131425.       13872275.
#Sta/Elev= 30
  4109.9 1116.61  4199.3 1110.06  4310.4 1084.29  4335.6 1079.32  4422.1 1066.79
  4543.1 1052.62  4817.2 1040.04  4833.8 1037.59  4847.8 1032.33  4861.8 1034.72
  4878.5 1033.46  4884.1 1034.88  4906.5 1032.07  4923.2 1027.17  4928.8 1027.54
  4945.6 1021.25  4949.1 1016.83  4950.6 1015.83  5014.8 1016.83  5032.4 1019.92
  5040.8 1025.22    5047 1025.08  5061.6 1033.47  5082.4 1034.74  5090.8 1037.66
  5104.3    1046  5111.6 1053.51  5304.3 1080.07  5367.8 1095.82  5504.3 1113.49
#Mann= 7 ,-1 , 0
  4109.9     .12       0  4310.4     .07       0  4335.6     .12       0
  4422.1    .035       0  4817.2     .12       0  4949.1     .05       0
  5014.8     .12       0
Bank Sta=4949.1,5014.8
XS Rating Curve= 0 ,0
Exp/Cntr=0.3,0.1

Type RM Length L Ch R = 1 ,6382    ,781,781,781
BEGIN DESCRIPTION:
CURRY CREEK 9.0
END DESCRIPTION:
XS GIS Cut Line= 3
      2132596.63     13873607.12        2132275.       13872675.
       2131502.5     13872210.59
#Sta/Elev= 30
  4014.3  1132.2  4104.4 1126.23  4158.3 1123.96  4291.6 1112.47  4323.3 1106.74
    4408 1081.69  4434.1 1077.66  4459.7 1071.41  4490.9 1066.81  4598.4 1059.21
  4646.9 1052.68  4709.3 1049.38  4766.4 1043.63    4884 1037.23  4915.7 1034.49
  4937.8 1029.72  4958.8 1024.96  4979.2 1016.48  4990.8 1015.25  4992.3 1014.25
  5056.5 1015.25  5066.4 1024.76  5072.2 1027.33  5124.7 1030.53  5188.8 1041.34
  5394.7 1055.88  5458.8 1062.79  5612.3 1071.39  5700.4  1082.3  5901.7 1101.06
#Mann= 6 ,-1 , 0
  4014.3     .07       0  4104.4     .12       0  4434.1     .07       0
  4937.8     .12       0  4990.8     .05       0  5056.5     .12       0
Bank Sta=4990.8,5056.5
XS Rating Curve= 0 ,0
Exp/Cntr=0.3,0.1

Type RM Length L Ch R = 1 ,5601    ,706,706,706
BEGIN DESCRIPTION:
CURRY CREEK 8.0
END DESCRIPTION:
XS GIS Cut Line= 3
      2133075.05       13872125.        2132575.       13872125.
      2131548.46     13872145.75
#Sta/Elev= 30
  4494.8  1123.1  4644.8    1116  4684.8 1113.35  4704.8 1110.22  4724.8 1104.33
  4764.8 1090.39  4784.8 1081.65  4804.8 1075.46  4844.8 1065.25  4904.8 1053.22
  4914.8 1031.83  4924.8 1027.38  4944.8 1025.16  4974.8 1013.82    4982 1013.01
  4983.5 1012.01  5046.3 1012.01  5047.8 1013.01  5054.9 1023.92  5084.9 1029.61
  5094.9 1034.28  5104.9 1036.36  5124.9 1036.94  5164.9 1043.07  5204.9 1044.58
  5224.9 1046.79    5515 1055.24    5745 1071.14    5835 1075.11  6021.6 1090.89
#Mann= 3 ,-1 , 0
  4494.8     .12       0    4982     .05       0  5047.8     .12       0
Bank Sta=4982,5047.8
XS Rating Curve= 0 ,0
Exp/Cntr=0.3,0.1

Type RM Length L Ch R = 1 ,4895    ,688,688,688
BEGIN DESCRIPTION:
CURRY CREEK 7.0
END DESCRIPTION:
XS GIS Cut Line= 3
        2132825.       13871625.        2132325.       13871525.
      2131273.35     13871702.33
#Sta/Elev= 30
  4495.8 1100.57  4587.6 1093.46  4699.8 1071.69  4842.5 1057.22  4852.7    1038
  4862.9 1028.11  4913.9 1021.42  4954.7 1018.16  4982.9 1009.84  4984.4 1008.84
  5048.7 1009.84    5057 1022.78  5117.3 1034.62  5178.1 1042.79    5239 1045.06
  5335.9 1044.64  5512.3 1048.18  5638.4 1058.88  5754.3  1073.6  5820.7 1079.48
  5867.7 1092.01  5875.3 1095.28  5880.3 1094.93  5908.3  1104.6  5935.8 1111.89
  5940.8 1111.19  5969.1 1118.85  5979.3 1120.78    6030 1123.55  6072.2 1128.35
#Mann= 5 ,-1 , 0
  4495.8     .12       0  4982.9     .05       0  5048.7     .12       0
    5057    .035       0  5820.7     .12       0
Bank Sta=4982.9,5048.7
XS Rating Curve= 0 ,0
Exp/Cntr=0.3,0.1

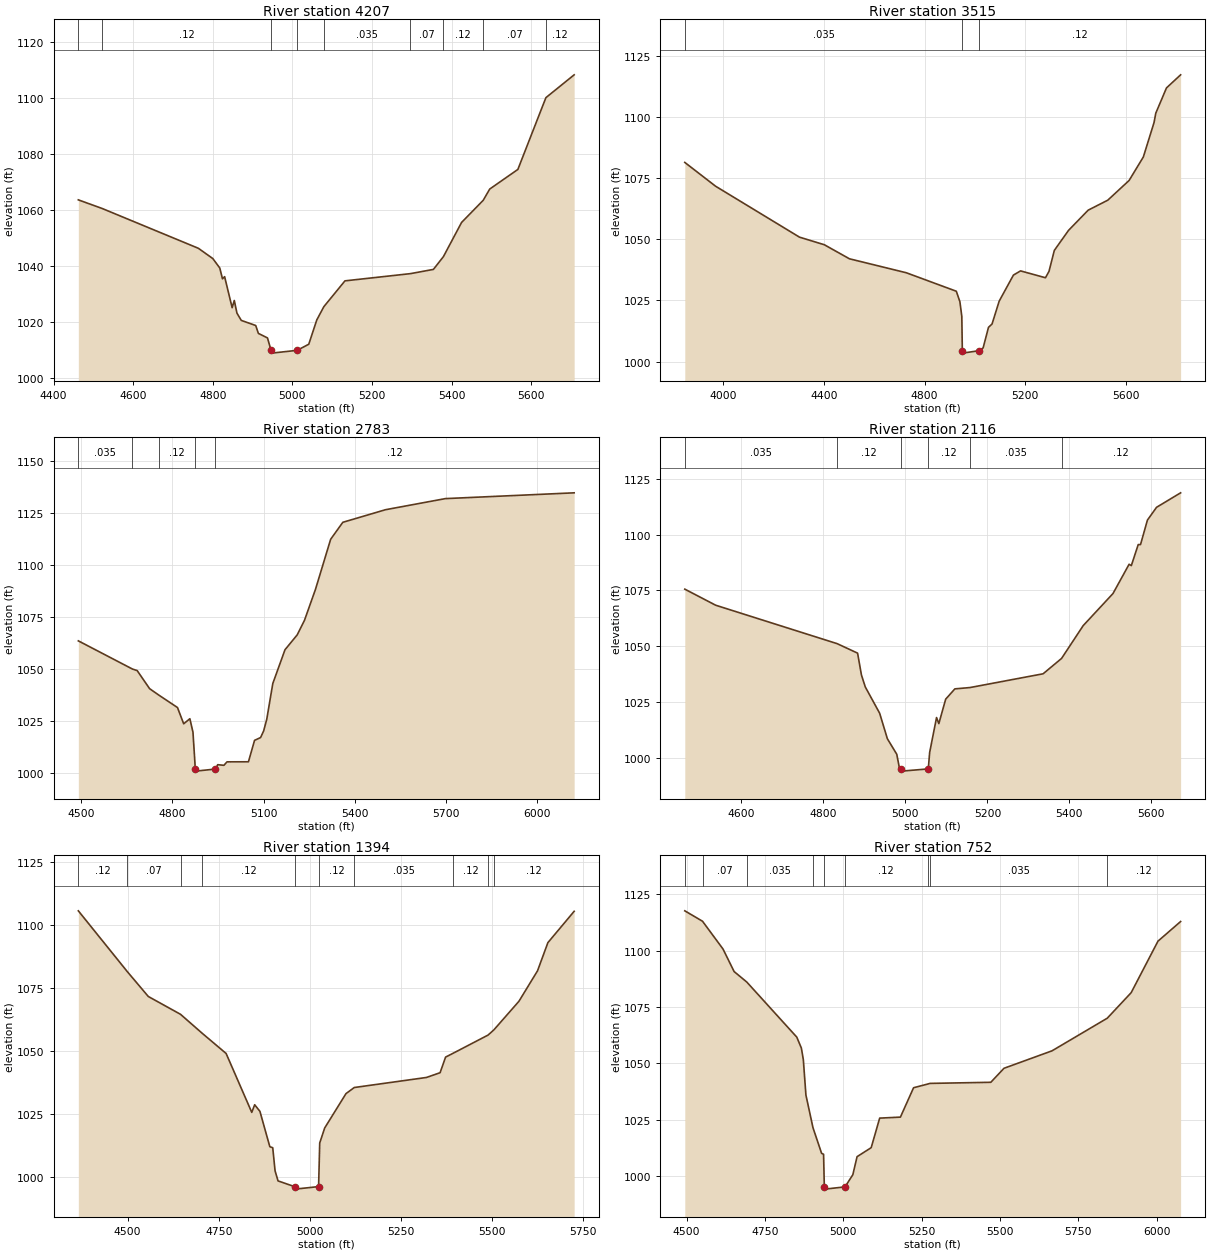
Type RM Length L Ch R = 1 ,4207    ,692,692,692
BEGIN DESCRIPTION:
CURRY CREEK 6.0
END DESCRIPTION:
XS GIS Cut Line= 3
      2132574.98     13871124.99        2132075.       13870925.
        2131375.       13871025.
#Sta/Elev= 30
  4462.2 1063.59    4522 1060.51  4763.7 1046.29  4800.1 1042.61  4817.6 1039.23
  4824.3 1035.39  4829.7 1036.14  4848.6 1025.07    4854 1027.64  4860.7 1023.12
  4871.5 1020.53  4907.8  1018.7  4914.5 1015.88  4937.4 1014.26  4946.3 1009.83
  4947.8 1008.83  5012.1 1009.83  5041.1 1012.01  5061.3 1020.71    5079 1025.43
    5132 1034.65  5296.6 1037.23  5354.2 1038.74  5379.4 1043.32    5425 1055.52
  5479.4 1063.44  5495.7 1067.45  5566.4 1074.46  5636.8  1100.1  5707.8 1108.26
#Mann= 9 ,-1 , 0
  4462.2    .035       0    4522     .12       0  4946.3     .05       0
  5012.1     .12       0    5079    .035       0  5296.6     .07       0
  5379.4     .12       0  5479.4     .07       0  5636.8     .12       0
Bank Sta=4946.3,5012.1
XS Rating Curve= 0 ,0
Exp/Cntr=0.3,0.1

Type RM Length L Ch R = 1 ,3515    ,732,732,732
BEGIN DESCRIPTION:
CURRY CREEK 5.0
END DESCRIPTION:
XS GIS Cut Line= 3
      2132882.45     13871199.75        2132125.       13870325.
      2131559.03     13869741.52
#Sta/Elev= 30
    3847 1081.51  3969.3 1071.77  4302.7 1050.91  4401.5  1047.8  4501.2 1042.05
  4727.2 1036.33  4925.7 1028.77    4940  1024.5  4947.6 1018.49  4949.7 1004.43
  4951.2 1003.43  5015.7 1004.43  5032.3 1005.55  5053.6 1013.98  5067.8 1015.36
  5096.1 1024.71  5152.7 1035.38    5181  1037.1    5280 1034.29  5294.1 1036.92
  5315.2 1045.49  5371.8  1053.7  5449.7 1061.96  5527.5 1066.04  5612.3 1074.12
  5668.9 1083.74  5711.4 1097.84  5718.3 1101.66  5760.8 1112.01    5817 1117.37
#Mann= 3 ,-1 , 0
    3847    .035       0  4949.7     .05       0  5015.7     .12       0
Bank Sta=4949.7,5015.7
XS Rating Curve= 0 ,0
Exp/Cntr=0.3,0.1

Type RM Length L Ch R = 1 ,2783    ,667,667,667
BEGIN DESCRIPTION:
CURRY CREEK 4.0
END DESCRIPTION:
XS GIS Cut Line= 3
        2132925.     13870925.02        2132825.       13870425.
      2132752.88     13869305.05
#Sta/Elev= 30
  4490.1 1063.38  4668.1 1049.85  4683.9 1049.08  4724.7 1040.42  4755.3  1037.3
  4816.5 1031.35  4836.9 1023.54  4857.3 1025.98  4867.5 1019.49  4875.2  1001.8
  4876.7  1000.8  4941.3  1001.8    4949 1003.89  4969.4 1003.59  4979.6 1005.26
  5050.1 1005.29  5070.2 1015.58  5090.2 1016.95  5100.2 1020.15  5110.3 1025.65
  5130.3  1042.9  5170.4 1059.11  5210.5 1066.23  5234.5 1073.23  5270.6 1088.04
  5320.7 1112.17  5360.8 1120.33  5501.1 1126.37  5698.3 1131.71  6122.3 1134.49
#Mann= 5 ,-1 , 0
  4490.1    .035       0  4668.1     .07       0  4755.3     .12       0
  4875.2     .05       0  4941.3     .12       0
Bank Sta=4875.2,4941.3
XS Rating Curve= 0 ,0
Exp/Cntr=0.3,0.1

Type RM Length L Ch R = 1 ,2116    ,722,722,722
BEGIN DESCRIPTION:
CURRY CREEK 3.0
END DESCRIPTION:
XS GIS Cut Line= 3
        2133225.     13871024.99        2133425.       13870525.
      2133125.01     13869925.03
#Sta/Elev= 30
  4461.9 1075.56  4537.3 1068.36  4833.5 1051.16  4883.3 1046.92  4892.7 1037.16
  4902.1 1031.79  4937.1 1020.03    4956 1008.59  4978.9 1001.65  4985.6  995.24
  4989.7   995.1  4991.2   994.1  5055.8   995.1  5059.1 1002.45  5075.9 1018.08
  5081.5 1015.37  5098.2 1026.32  5120.6 1030.92  5157.4 1031.51  5335.8 1037.67
  5380.8 1044.54  5433.6 1059.24  5506.3 1073.61  5545.5 1086.69    5551 1086.11
  5567.8 1095.51  5573.4 1095.51  5590.2 1106.46  5612.5  1112.2  5671.2 1118.68
#Mann= 6 ,-1 , 0
  4461.9    .035       0  4833.5     .12       0  4989.7     .05       0
  5055.8     .12       0  5157.4    .035       0  5380.8     .12       0
Bank Sta=4989.7,5055.8
XS Rating Curve= 0 ,0
Exp/Cntr=0.3,0.1

Type RM Length L Ch R = 1 ,1394    ,642,642,642
BEGIN DESCRIPTION:
CURRY CREEK 2.0
END DESCRIPTION:
XS GIS Cut Line= 3
      2134574.99     13870724.99        2134075.       13870325.
        2133675.     13869725.01
#Sta/Elev= 30
  4364.6 1105.49  4499.5 1081.33  4556.7 1071.56  4645.2  1064.5  4705.5 1056.89
  4770.4 1048.98  4840.8 1025.66  4848.8 1028.67  4863.2 1026.06  4890.4 1012.05
  4898.4 1011.65  4904.8 1002.49  4912.9  998.51  4958.2  996.25  4959.7  995.25
  5024.3  996.25  5027.4 1013.53    5041 1019.46  5099.5 1033.08  5122.3  1035.5
  5320.4 1039.48  5357.9 1041.36    5373 1047.55  5393.4 1049.05  5489.6 1056.27
  5505.3 1058.29  5574.3 1069.64  5625.4 1081.72  5653.9 1092.89    5726  1105.3
#Mann= 10 ,-1 , 0
  4364.6     .12       0  4499.5     .07       0  4645.2    .035       0
  4705.5     .12       0  4958.2     .05       0  5024.3     .12       0
  5122.3    .035       0  5393.4     .12       0  5489.6    .035       0
  5505.3     .12       0
Bank Sta=4958.2,5024.3
XS Rating Curve= 0 ,0
Exp/Cntr=0.3,0.1

Type RM Length L Ch R = 1 ,752     ,528,528,528
BEGIN DESCRIPTION:
CURRY CREEK 1.0
END DESCRIPTION:
XS GIS Cut Line= 3
      2134924.99     13870574.99        2134625.       13870175.
      2133724.96     13869574.98
#Sta/Elev= 30
  4494.3 1117.72  4550.8  1113.1  4616.2 1100.77  4651.6 1090.77  4692.2 1086.09
  4851.6 1061.65  4866.2 1056.79  4872.4  1051.7  4880.7 1035.94  4903.2 1021.47
  4930.7 1010.07    4937 1009.67  4939.4  995.19  4940.9  994.19  5005.5  995.19
  5030.3 1000.58  5043.9  1008.6  5088.9 1012.59    5116 1025.71  5182.1 1026.15
  5224.1 1039.19  5268.6 1040.81  5276.5 1041.12  5470.5 1041.61  5512.6 1047.83
  5665.8 1055.58    5842 1070.06  5918.2 1081.38  6003.8 1104.26    6076 1112.97
#Mann= 9 ,-1 , 0
  4494.3     .12       0  4550.8     .07       0  4692.2    .035       0
  4903.2     .12       0  4939.4     .05       0  5005.5     .12       0
  5268.6     .07       0  5276.5    .035       0    5842     .12       0
Bank Sta=4939.4,5005.5
XS Rating Curve= 0 ,0
Exp/Cntr=0.3,0.1

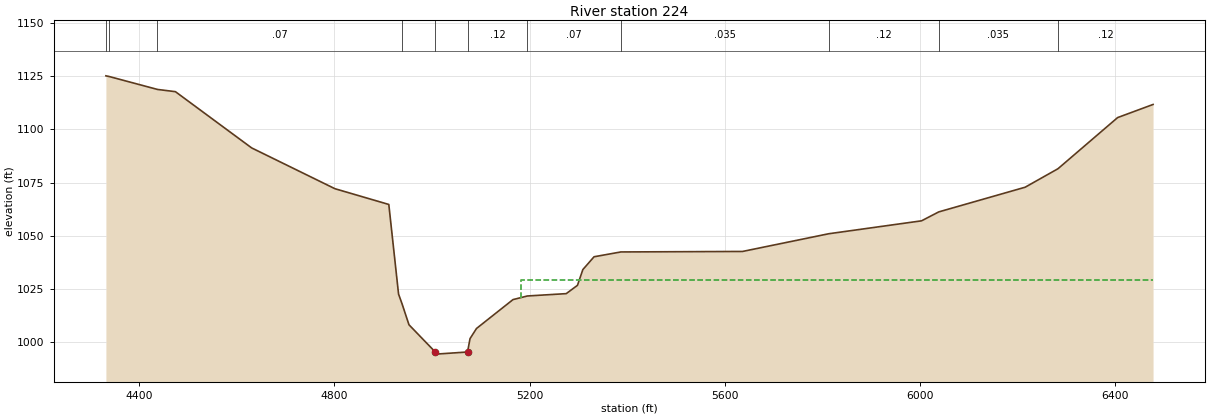
Type RM Length L Ch R = 1 ,224     ,0,0,0
BEGIN DESCRIPTION:
CURRY CREEK 0.0
END DESCRIPTION:
XS GIS Cut Line= 3
      2135141.94      13870642.5      2135085.69     13869976.67
      2133743.53     13869359.88
#Sta/Elev= 30
  4331.8 1125.08  4338.5 1124.76  4437.5 1118.69  4474.2 1117.65  4630.4 1091.26
    4801 1072.12  4911.4 1064.73  4931.4 1022.65  4938.4 1018.21  4952.7 1008.29
  5006.6  995.51  5008.1  994.51  5072.7  995.51  5077.8 1001.79  5091.1 1006.55
  5165.8 1020.09  5195.3 1021.79  5274.9 1022.89  5297.9 1026.79  5308.9 1034.16
  5331.9 1040.19  5386.9 1042.45  5636.1 1042.68  5812.5 1050.98  6002.8 1057.05
  6038.1 1061.24  6215.1 1072.82  6282.3 1081.49  6404.5 1105.49  6477.1 1111.64
#Mann= 11 ,-1 , 0
  4331.8    .035       0  4338.5     .12       0  4437.5     .07       0
  4938.4     .12       0  5006.6     .05       0  5072.7     .12       0
  5195.3     .07       0  5386.9    .035       0  5812.5     .12       0
  6038.1    .035       0  6282.3     .12       0
#XS Ineff= 2 , 0
       0                 5181.32       0 1029.13
Permanent Ineff=
       F       F
Bank Sta=5006.6,5072.7
XS Rating Curve= 0 ,0
Exp/Cntr=0.3,0.1

Chan Stop Cuts=-1
Use User Specified Reach Order=0
Composite Channel Slope=5