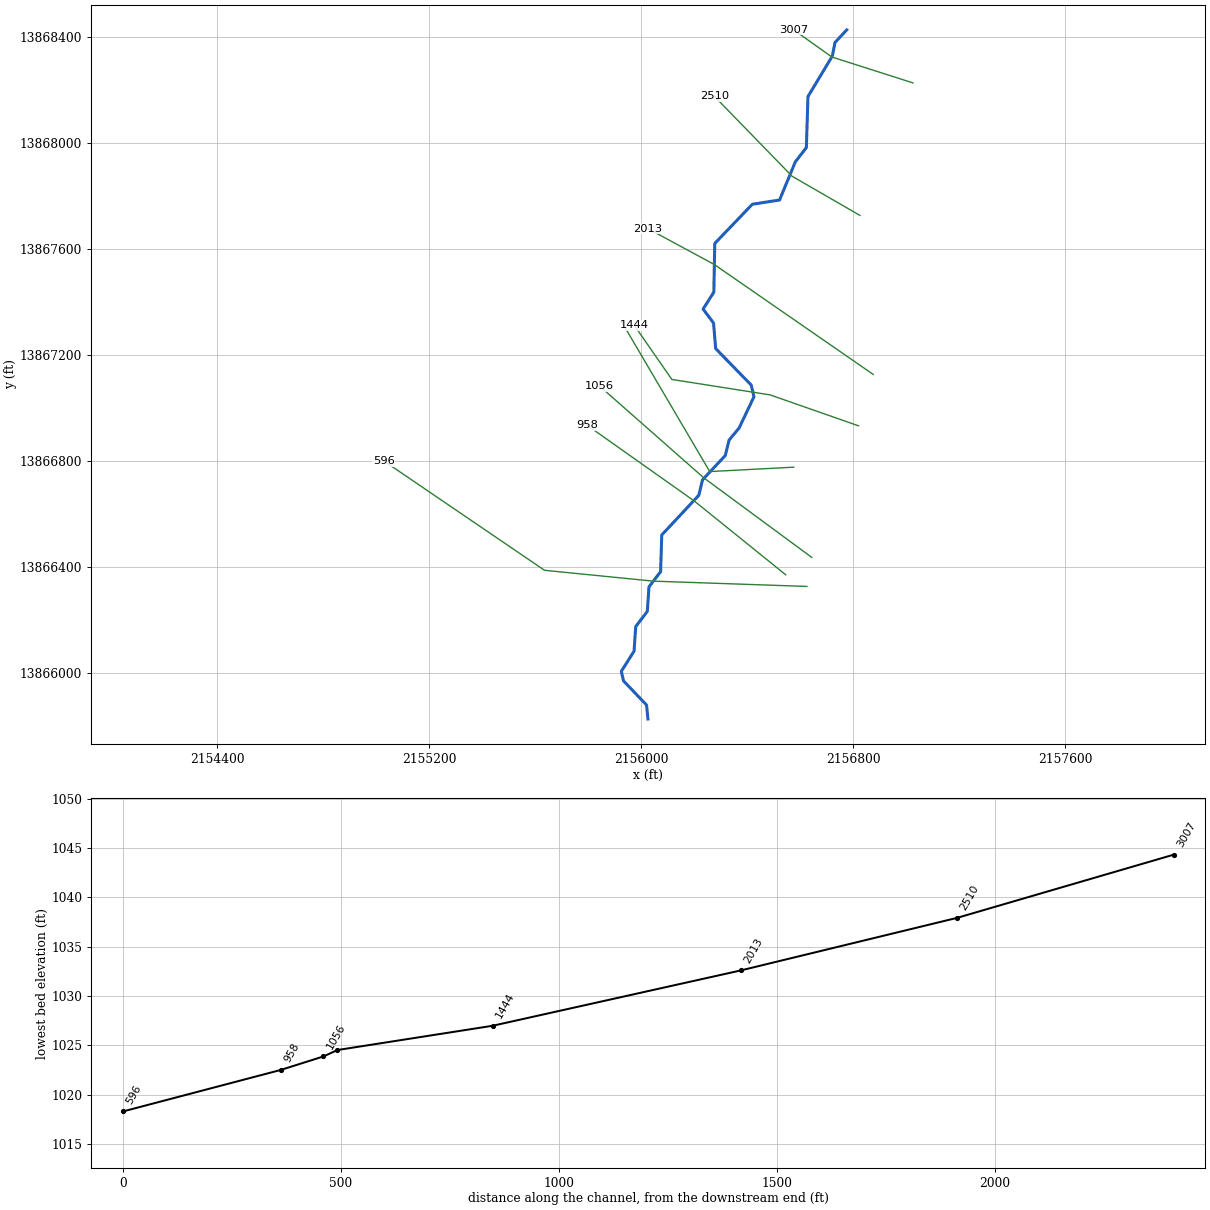
--- Cypress Tributary 1.prj (project) ---

Proj Title=Cypress Tributary 1 Base Level Engineering
Current Plan=p01
Default Exp/Contr=0.3,0.1
English Units
Geom File=g01
Flow File=f01
Plan File=p01
BEGIN DESCRIPTION:
Cypress Tributary 1
END DESCRIPTION:

--- Cypress Tributary 1.p01 (plan) ---

Plan Title=Multiple Run
Short Identifier=Multiple
Geom File=g01
Flow File=f01
Subcritical Flow
K Sum by GR= 0
Std Step Tol= 0.01
Critical Tol= 0.01
Num of Std Step Trials= 20
Max Error Tol= 0.3
Flow Tol Ratio= 0.001
Split Flow NTrial= 30
Split Flow Tol= 0.02
Split Flow Ratio= 0.02
Log Output Level= 0
Friction Slope Method= 1
Unsteady Friction Slope Method= 2
Unsteady Bridges Friction Slope Method= 1
Parabolic Critical Depth
Global Vel Dist=  1 , 1 , 1
Global Log Level= 0
CheckData=True
Encroach Param= -1, 0, 0, 0
BEGIN DESCRIPTION:
Multiple Run
END DESCRIPTION:

--- Cypress Tributary 1.f01 (steady flow) ---

Flow Title=Multiple
Number of Profiles=7
Profile Names=10-year,25-year,50-year,1pct_min,100-year,1pct_plu,500-year
River Rch & RM= Cypress Tributar,Reach-1,3007
     443     713     959     627    1251    2496    2102
River Rch & RM= Cypress Tributar,Reach-1,2510
     581     950    1289     850    1696    3383    2898
Boundary for River Rch & Prof#=Cypress Tributar,Reach-1,1
Up Type=0
Dn Type=3
Dn Slope=0.005
Boundary for River Rch & Prof#=Cypress Tributar,Reach-1,2
Up Type=0
Dn Type=3
Dn Slope=0.005
Boundary for River Rch & Prof#=Cypress Tributar,Reach-1,3
Up Type=0
Dn Type=3
Dn Slope=0.005
Boundary for River Rch & Prof#=Cypress Tributar,Reach-1,4
Up Type=0
Dn Type=3
Dn Slope=0.005
Boundary for River Rch & Prof#=Cypress Tributar,Reach-1,5
Up Type=0
Dn Type=3
Dn Slope=0.005
Boundary for River Rch & Prof#=Cypress Tributar,Reach-1,6
Up Type=0
Dn Type=3
Dn Slope=0.005
Boundary for River Rch & Prof#=Cypress Tributar,Reach-1,7
Up Type=0
Dn Type=3
Dn Slope=0.005

--- Cypress Tributary 1.g01 (geometry) ---

Geom Title=Existing Conditions

River Reach=Cypress Tributar,Reach-1
Reach XY= 30
      2156775.00     13868425.00      2156730.67     13868377.36
      2156720.96     13868326.67      2156628.75     13868173.45
      2156622.76     13867980.93      2156581.12     13867927.18
      2156521.62     13867783.15      2156418.88     13867767.12
      2156277.06     13867619.15      2156273.62     13867435.44
      2156233.08     13867371.70      2156272.44     13867319.10
      2156280.52     13867222.57      2156414.81     13867084.68
      2156424.98     13867040.41      2156368.92     13866922.80
      2156331.10     13866877.19      2156316.84     13866818.95
      2156230.87     13866727.28      2156216.84     13866668.95
      2156077.07     13866519.14      2156072.73     13866380.94
      2156028.86     13866323.40      2156022.65     13866230.97
      2155978.85     13866173.40      2155972.62     13866080.97
      2155924.64     13866004.79      2155932.48     13865968.94
      2156019.67     13865877.51      2156025.00     13865825.00

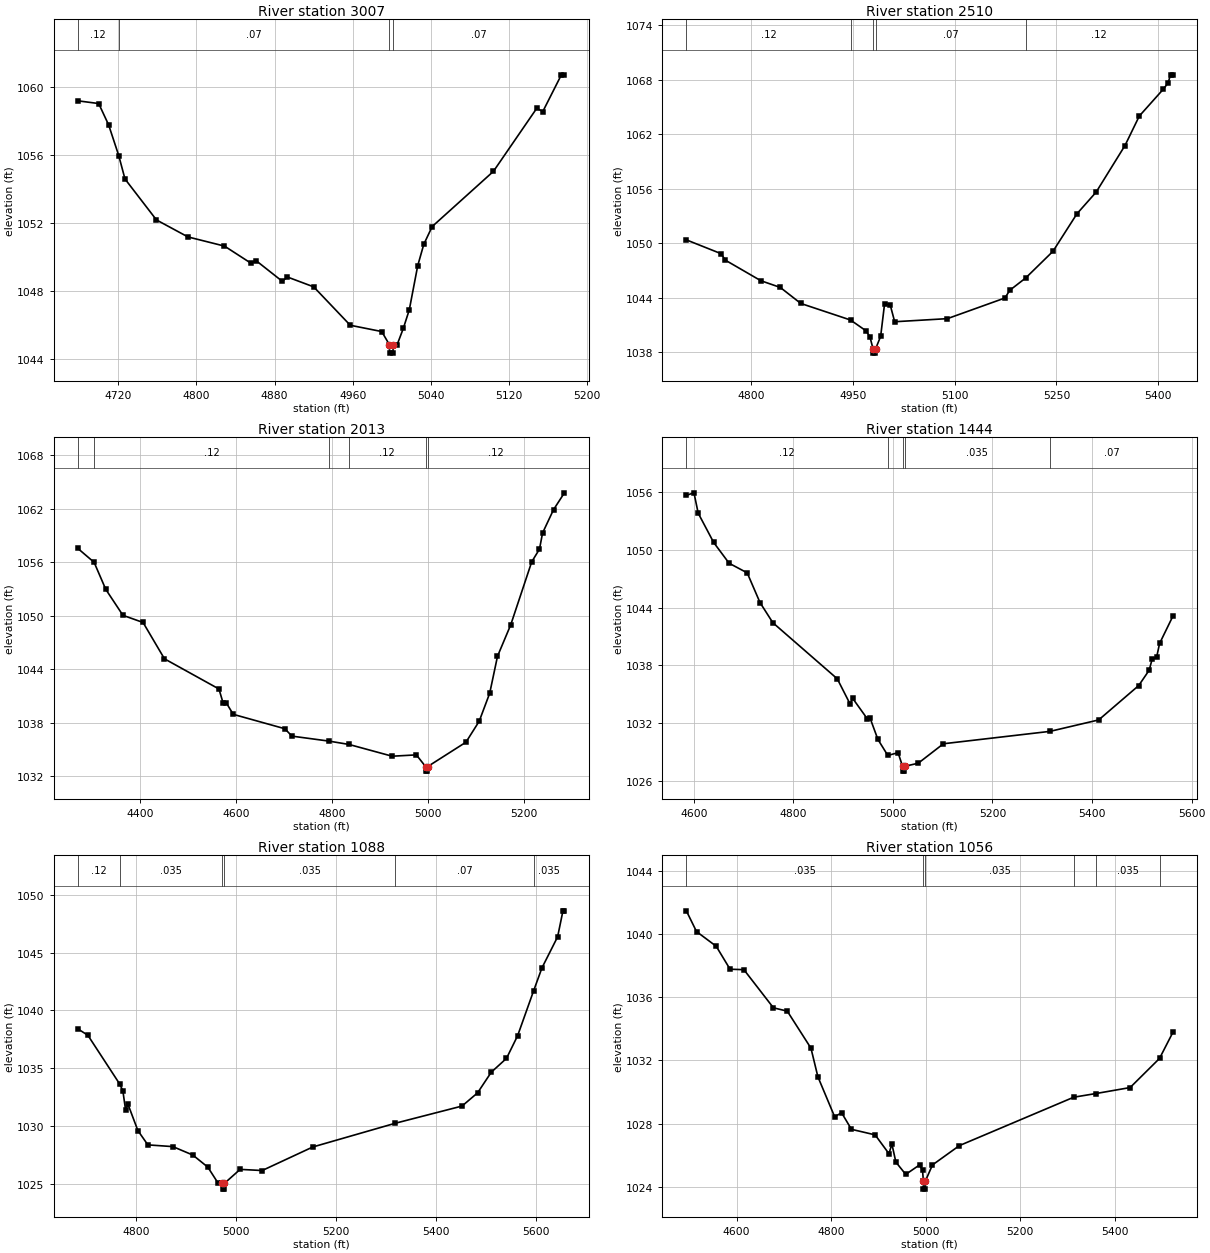
Type RM Length L Ch R = 1,3007,497,497,497
BEGIN DESCRIPTION:
Cypress Tributary 1 6.0
END DESCRIPTION:
XS GIS Cut Line= 3
      2157024.97     13868225.01      2156719.01     13868322.77
      2156575.01     13868425.00
#Sta/Elev= 30
  4678.8 1059.19  4700.1 1059.03  4710.3 1057.77  4720.6 1055.97  4727.0 1054.59
  4759.2 1052.18  4791.4 1051.18  4828.8 1050.64  4855.7 1049.64  4861.0 1049.79
  4887.9 1048.57  4893.2 1048.82  4920.1 1048.24  4957.5 1045.98  4989.7 1045.61
  4997.5 1044.84  4997.7 1044.34  5001.2 1044.34  5001.5 1044.84  5005.5 1044.84
  5011.8 1045.80  5017.9 1046.89  5026.5 1049.48  5032.7 1050.74  5041.3 1051.79
  5104.0 1055.04  5148.3 1058.75  5154.5 1058.56  5173.5 1060.72  5176.6 1060.72
#Mann=4,-1,0
  4678.8    0.12       0  4720.6    0.07       0  4997.5    0.05       0
  5001.5    0.07       0
Bank Sta=4997.5,5001.5
Exp/Cntr=0.3,0.1

Type RM Length L Ch R = 1,2510,497,497,497
BEGIN DESCRIPTION:
Cypress Tributary 1 5.0
END DESCRIPTION:
XS GIS Cut Line= 3
      2156824.97     13867725.02      2156568.94     13867872.76
      2156275.00     13868175.00
#Sta/Elev= 30
  4704.4 1050.38  4755.3 1048.87  4762.1 1048.14  4814.2 1045.89  4842.9 1045.15
  4873.1 1043.39  4946.4 1041.57  4969.3 1040.38  4975.1 1039.70  4979.5 1038.43
  4979.7 1037.93  4983.2 1037.93  4983.5 1038.43  4990.8 1039.77  4996.6 1043.35
  5005.0 1043.20  5011.5 1041.38  5089.2 1041.72  5174.0 1043.99  5181.2 1044.84
  5204.6 1046.19  5244.8 1049.12  5280.2 1053.25  5308.5 1055.63  5351.0 1060.75
  5372.1 1063.99  5407.6 1066.95  5414.5 1067.63  5418.1 1068.52  5421.6 1068.52
#Mann=5,-1,0
  4704.4    0.12       0  4946.4    0.07       0  4979.5    0.05       0
  4983.5    0.07       0  5204.6    0.12       0
Bank Sta=4979.5,4983.5
Exp/Cntr=0.3,0.1

Type RM Length L Ch R = 1,2013,569,569,569
BEGIN DESCRIPTION:
Cypress Tributary 1 4.0
END DESCRIPTION:
XS GIS Cut Line= 3
      2156874.96     13867125.03      2156274.89     13867540.04
      2156025.01     13867675.00
#Sta/Elev= 30
  4270.4 1057.53  4304.2 1055.98  4328.5 1052.95  4364.3 1050.04  4406.2 1049.24
  4450.8 1045.17  4564.3 1041.79  4573.1 1040.20  4579.2 1040.27  4594.1 1038.95
  4701.5 1037.34  4716.4 1036.51  4793.8 1035.95  4835.1 1035.58  4925.2 1034.26
  4975.6 1034.41  4994.9 1033.09  4995.1 1032.59  4998.6 1032.59  4998.9 1033.09
  5078.9 1035.83  5106.5 1038.18  5128.4 1041.32  5144.6 1045.45  5172.2 1048.98
  5215.9 1056.03  5232.1 1057.46  5238.5 1059.26  5261.3 1061.87  5284.0 1063.76
#Mann=6,-1,0
  4270.4    0.07       0  4304.2    0.12       0  4793.8    0.07       0
  4835.1    0.12       0  4994.9    0.05       0  4998.9    0.12       0
Bank Sta=4994.9,4998.9
Exp/Cntr=0.3,0.1

Type RM Length L Ch R = 1,1444,356,356,356
BEGIN DESCRIPTION:
Cypress Tributary 1 3.0
END DESCRIPTION:
XS GIS Cut Line= 4
      2156819.45     13866931.06      2156486.05     13867047.75
      2156115.15     13867106.09      2155973.53     13867310.18
#Sta/Elev= 30
  4585.2 1055.69  4600.5 1055.95  4609.0 1053.83  4640.1 1050.78  4671.1 1048.62
  4707.4 1047.62  4733.1 1044.53  4758.9 1042.43  4888.3 1036.59  4914.0 1033.97
  4919.3 1034.55  4948.7 1032.42  4953.8 1032.55  4969.9 1030.28  4989.8 1028.61
  5010.4 1028.90  5019.4 1027.48  5019.7 1026.98  5023.2 1026.98  5023.4 1027.48
  5050.8 1027.80  5101.5 1029.83  5315.6 1031.12  5413.3 1032.31  5493.7 1035.89
  5514.6 1037.48  5520.7 1038.64  5529.5 1038.81  5535.6 1040.27  5562.3 1043.11
#Mann=5,-1,0
  4585.2    0.12       0  4989.8   0.035       0  5019.4   0.035       0
  5023.4   0.035       0  5315.6    0.07       0
Bank Sta=5019.4,5023.4
Exp/Cntr=0.3,0.1

Type RM Length L Ch R = 1,1088,32,32,32
BEGIN DESCRIPTION:
Cypress Tributary 1 2.0
END DESCRIPTION:
XS GIS Cut Line= 3
      2156575.02     13866775.00      2156258.05     13866758.45
      2155924.99     13867325.01
#Sta/Elev= 30
  4682.6 1038.39  4702.6 1037.84  4766.2 1033.63  4772.7 1033.04  4778.1 1031.40
  4783.1 1031.85  4802.8 1029.59  4822.8 1028.35  4872.9 1028.20  4912.9 1027.47
  4943.0 1026.42  4963.0 1025.07  4972.2 1025.02  4972.4 1024.52  4975.9 1024.52
  4976.2 1025.02  5007.6 1026.23  5051.8 1026.13  5153.3 1028.17  5318.2 1030.22
  5452.1 1031.71  5483.2 1032.85  5510.7 1034.64  5541.2 1035.84  5563.5 1037.80
  5595.3 1041.66  5612.2 1043.67  5643.6 1046.36  5654.3 1048.61  5657.2 1048.61
#Mann=6,-1,0
  4682.6    0.12       0  4766.2   0.035       0  4972.2   0.035       0
  4976.2   0.035       0  5318.2    0.07       0  5595.3   0.035       0
Bank Sta=4972.2,4976.2
Exp/Cntr=0.3,0.1

Type RM Length L Ch R = 1,1056,98,98,98
BEGIN DESCRIPTION:
Cypress Tributary 1 1.2
END DESCRIPTION:
XS GIS Cut Line= 3
      2156643.42     13866434.36      2156235.80     13866734.67
      2155842.99     13867080.57
#Sta/Elev= 30
  4493.7 1041.46  4515.2 1040.15  4556.9 1039.22  4586.2 1037.77  4615.5 1037.74
  4678.0 1035.33  4707.3 1035.12  4757.4 1032.78  4772.1 1030.97  4807.6 1028.44
  4822.2 1028.70  4843.1 1027.65  4893.2 1027.30  4922.5 1026.11  4928.7 1026.72
  4937.1 1025.58  4958.0 1024.80  4987.2 1025.40  4993.5 1025.07  4995.4 1024.37
  4995.6 1023.87  4999.1 1023.87  4999.4 1024.37  5014.6 1025.40  5071.5 1026.62
  5313.6 1029.68  5360.2 1029.91  5432.9 1030.29  5495.1 1032.13  5523.4 1033.78
#Mann=6,-1,0
  4493.7   0.035       0  4995.4   0.035       0  4999.4   0.035       0
  5313.6    0.07       0  5360.2   0.035       0  5495.1   0.063       0
Bank Sta=4995.4,4999.4
Exp/Cntr=0.3,0.1

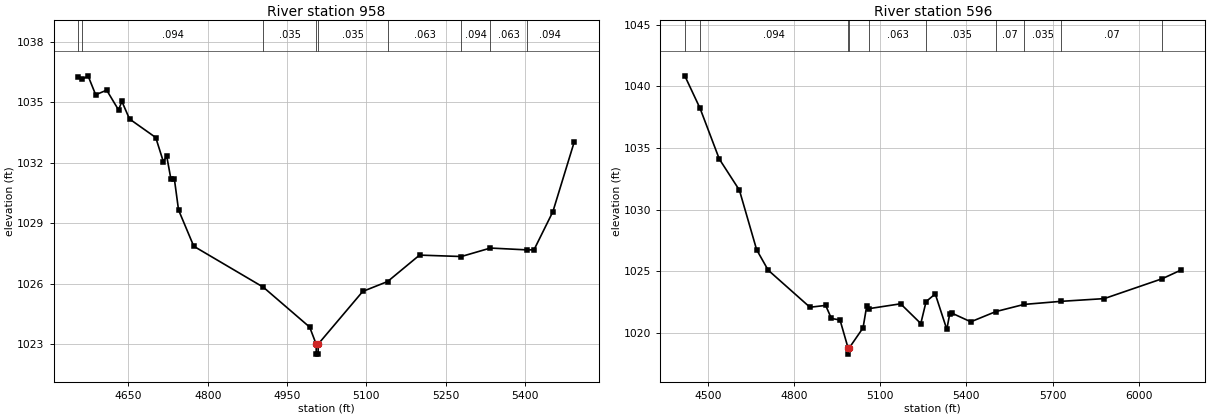
Type RM Length L Ch R = 1,958,362,362,362
BEGIN DESCRIPTION:
Cypress Tributary 1 1.1
END DESCRIPTION:
XS GIS Cut Line= 3
      2156544.91     13866368.91      2156198.70     13866648.18
      2155796.20     13866932.69
#Sta/Elev= 30
  4555.2 1036.24  4562.3 1036.12  4573.6 1036.30  4588.0 1035.36  4608.8 1035.59
  4631.2 1034.61  4637.6 1035.03  4652.0 1034.16  4701.6 1033.24  4715.9 1032.05
  4722.4 1032.31  4730.3 1031.18  4736.8 1031.19  4744.7 1029.65  4773.5 1027.85
  4905.0 1025.82  4992.7 1023.84  5004.9 1023.00  5005.2 1022.50  5008.7 1022.50
  5008.9 1023.00  5093.1 1025.61  5140.1 1026.10  5200.5 1027.41  5279.5 1027.34
  5334.5 1027.76  5402.9 1027.67  5416.9 1027.67  5452.6 1029.56  5492.9 1033.01
#Mann=9,-1,0
  4555.2   0.035       0  4562.3   0.094       0  4905.0   0.035       0
  5004.9   0.035       0  5008.9   0.035       0  5140.1   0.063       0
  5279.5   0.094       0  5334.5   0.063       0  5402.9   0.094       0
Bank Sta=5004.9,5008.9
Exp/Cntr=0.3,0.1

Type RM Length L Ch R = 1,596,0,0,0
BEGIN DESCRIPTION:
Cypress Tributary 1 1.0
END DESCRIPTION:
XS GIS Cut Line= 4
      2156624.97     13866325.00      2156045.12     13866344.95
      2155634.69     13866385.92      2155028.52     13866798.46
#Sta/Elev= 30
  4419.8 1040.85  4473.0 1038.21  4539.8 1034.11  4609.9 1031.58  4669.9 1026.75
  4709.9 1025.10  4855.5 1022.09  4910.1 1022.24  4930.1 1021.18  4960.1 1021.06
  4988.1 1018.79  4988.4 1018.29  4992.1 1018.79  5040.3 1020.42  5053.1 1022.21
  5061.8 1021.98  5171.0 1022.37  5241.3 1020.77  5259.7 1022.55  5291.6 1023.17
  5331.8 1020.30  5341.8 1021.53  5349.8 1021.61  5415.3 1020.91  5502.6 1021.74
  5600.8 1022.32  5730.0 1022.57  5879.8 1022.79  6081.2 1024.40  6145.7 1025.09
#Mann=10,-1,0
  4419.8   0.035       0  4473.0   0.094       0  4988.1    0.05       0
  4992.1   0.094       0  5061.8   0.063       0  5259.7   0.035       0
  5502.6    0.07       0  5600.8   0.035       0  5730.0    0.07       0
  6081.2   0.035       0
Bank Sta=4988.1,4992.1
Exp/Cntr=0.3,0.1

Chan Stop Cuts=-1