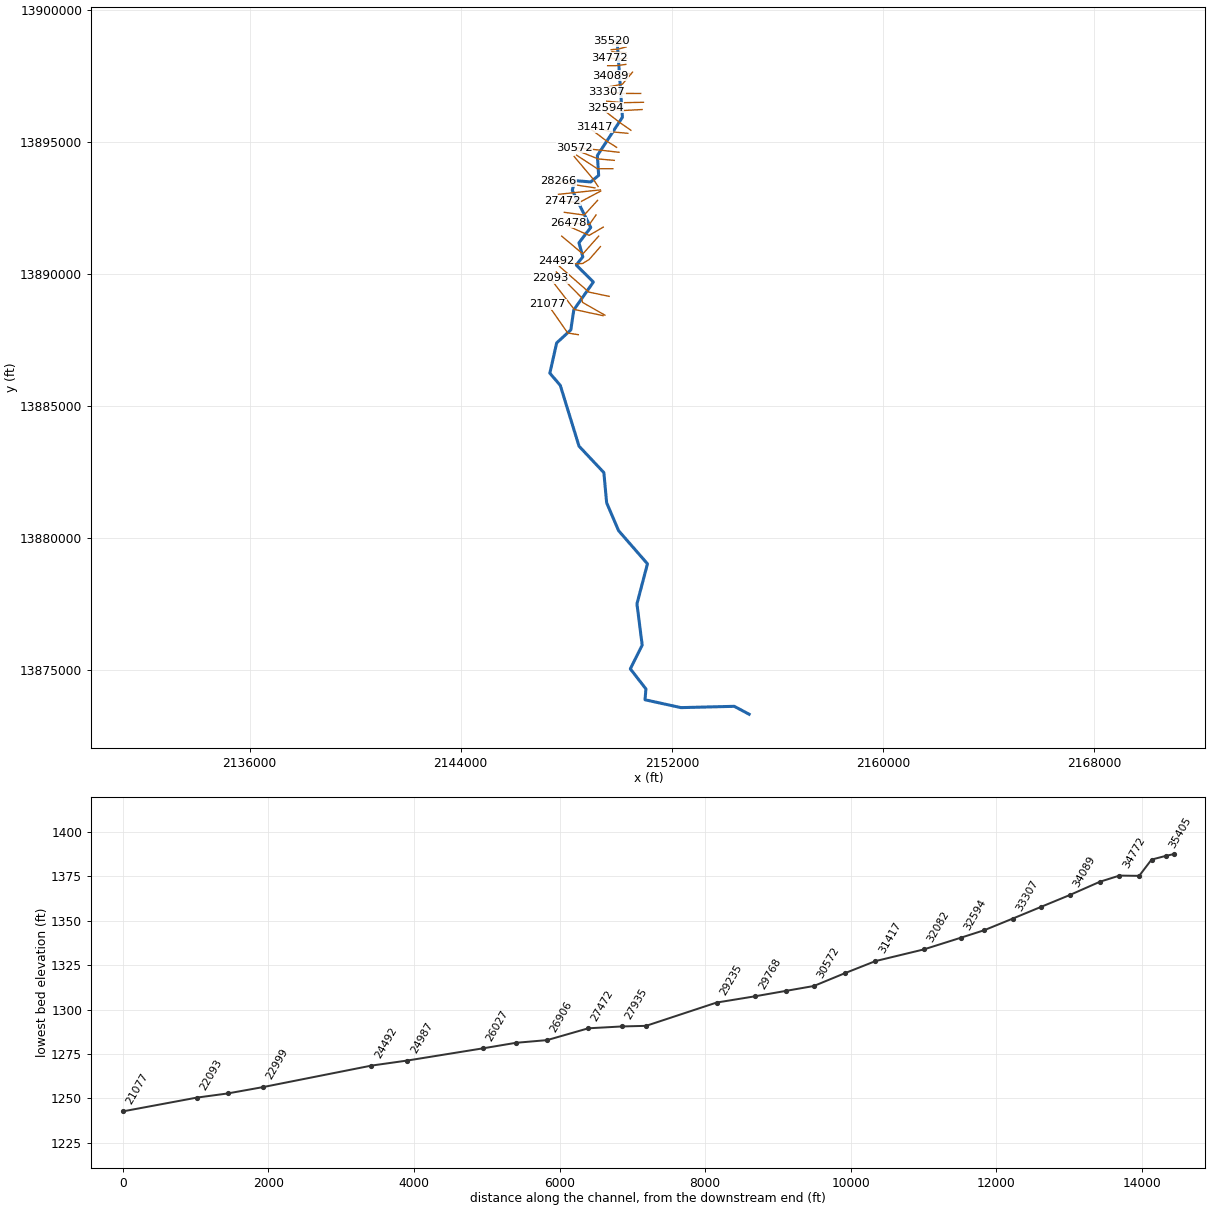
--- Cypress Tributary 2.prj (project) ---

Proj Title=Cypress Tributary 2 Base Level Engineering
Current Plan=p01
Default Exp/Contr=0.3,0.1
English Units
Geom File=g01
Flow File=f01
Plan File=p01
BEGIN DESCRIPTION:
Cypress Tributary 2
END DESCRIPTION:

--- Cypress Tributary 2.p01 (plan) ---

Plan Title=Multiple Run
Short Identifier=Multiple
Geom File=g01
Flow File=f01
Subcritical Flow
K Sum by GR= 0
Std Step Tol= 0.01
Critical Tol= 0.01
Num of Std Step Trials= 20
Max Error Tol= 0.3
Flow Tol Ratio= 0.001
Split Flow NTrial= 30
Split Flow Tol= 0.02
Split Flow Ratio= 0.02
Log Output Level= 0
Friction Slope Method= 1
Unsteady Friction Slope Method= 2
Unsteady Bridges Friction Slope Method= 1
Parabolic Critical Depth
Global Vel Dist=  1 , 1 , 1
Global Log Level= 0
CheckData=True
Encroach Param= -1, 0, 0, 0
BEGIN DESCRIPTION:
Multiple Run
END DESCRIPTION:

--- Cypress Tributary 2.f01 (steady flow) ---

Flow Title=Multiple
Number of Profiles=7
Profile Names=10-year,25-year,50-year,1pct_min,100-year,1pct_plu,500-year
River Rch & RM= Cypress Tributar,Reach-1,35520
     412     656     874     567    1131    2257    1869
River Rch & RM= Cypress Tributar,Reach-1,35213
    1186    2014    2804    1891    3773    7527    6755
River Rch & RM= Cypress Tributar,Reach-1,28266
    1729    2985    4198    2854    5695   11364   10380
River Rch & RM= Cypress Tributar,Reach-1,20136
    2230    3891    5512    3770    7522   15009   13879
River Rch & RM= Cypress Tributar,Reach-1,9474
    2992    5318    7627    5277   10530   21010   19893
River Rch & RM= Cypress Tributar,Reach-1,6044
    3293    5871    8435    5845   11662   23268   22095
River Rch & RM= Cypress Tributar,Reach-1,2715
    3371    6008    8630    5978   11927   23798   22582
Boundary for River Rch & Prof#=Cypress Tributar,Reach-1,1
Up Type=0
Dn Type=3
Dn Slope=0.005
Boundary for River Rch & Prof#=Cypress Tributar,Reach-1,2
Up Type=0
Dn Type=3
Dn Slope=0.005
Boundary for River Rch & Prof#=Cypress Tributar,Reach-1,3
Up Type=0
Dn Type=3
Dn Slope=0.005
Boundary for River Rch & Prof#=Cypress Tributar,Reach-1,4
Up Type=0
Dn Type=3
Dn Slope=0.005
Boundary for River Rch & Prof#=Cypress Tributar,Reach-1,5
Up Type=0
Dn Type=3
Dn Slope=0.005
Boundary for River Rch & Prof#=Cypress Tributar,Reach-1,6
Up Type=0
Dn Type=3
Dn Slope=0.005
Boundary for River Rch & Prof#=Cypress Tributar,Reach-1,7
Up Type=0
Dn Type=3
Dn Slope=0.005

--- Cypress Tributary 2.g01 (geometry) ---

Geom Title=Existing Conditions

River Reach=Cypress Tributar,Reach-1
Reach XY= 30
      2149925.00     13898825.00      2150125.00     13895925.00
      2149175.00     13894475.00      2149225.00     13893725.00
      2148925.00     13893475.00      2148325.00     13893525.00
      2148225.19     13893156.72      2148925.11     13891752.32
      2148478.67     13891173.42      2148624.51     13890640.22
      2148376.59     13890331.06      2149024.30     13889685.70
      2148284.01     13888632.02      2148169.48     13887872.57
      2147634.19     13887381.95      2147376.20     13886235.50
      2147771.87     13885773.37      2148480.85     13883472.71
      2149421.25     13882473.45      2149527.24     13881330.93
      2149980.52     13880272.57      2151073.27     13879019.37
      2150674.87     13877502.31      2150874.32     13875938.92
      2150424.28     13875043.27      2151015.43     13874281.55
      2150980.71     13873872.42      2152343.27     13873575.21
      2154361.09     13873624.33      2154925.00     13873325.00

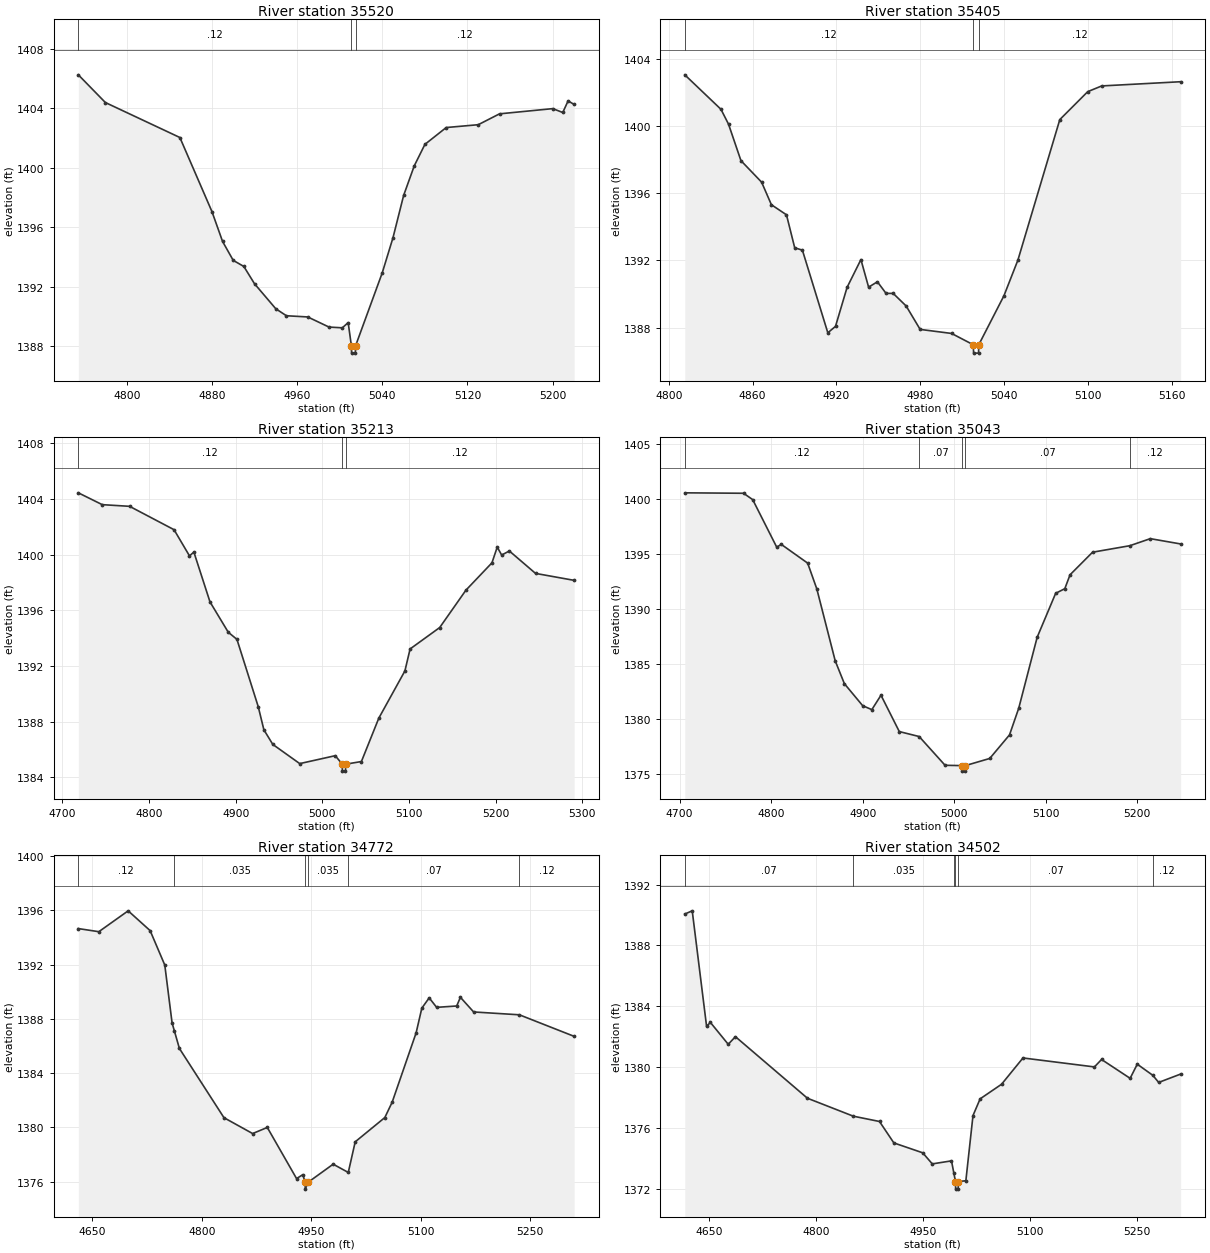
Type RM Length L Ch R = 1,35520,115,115,115
BEGIN DESCRIPTION:
Cypress Tributary 2 67.0
END DESCRIPTION:
XS GIS Cut Line= 3
      2150170.41     13898795.97      2149925.00     13898789.46
      2149704.97     13898800.31
#Sta/Elev= 30
  4754.5 1406.24  4779.9 1404.38  4849.9 1402.03  4880.0 1397.06  4890.0 1395.05
  4900.0 1393.78  4910.0 1393.37  4920.0 1392.21  4940.0 1390.53  4950.0 1390.06
  4970.0 1389.98  4990.0 1389.30  5002.5 1389.25  5008.0 1389.60  5011.0 1388.05
  5011.2 1387.55  5014.7 1387.55  5015.0 1388.05  5040.0 1392.94  5050.1 1395.30
  5060.1 1398.14  5070.1 1400.13  5080.1 1401.57  5100.1 1402.70  5130.2 1402.89
  5150.2 1403.62  5200.2 1403.97  5209.6 1403.71  5214.6 1404.49  5220.3 1404.25
#Mann=3,-1,0
  4754.5    0.12       0  5011.0    0.05       0  5015.0    0.12       0
Bank Sta=5011,5015
Exp/Cntr=0.3,0.1

Type RM Length L Ch R = 1,35405,192,192,192
BEGIN DESCRIPTION:
Cypress Tributary 2 66.0
END DESCRIPTION:
XS GIS Cut Line= 4
      2150102.06     13898730.86      2149968.62     13898674.44
      2149925.00     13898675.00      2149758.51     13898673.37
#Sta/Elev= 30
  4811.5 1403.03  4837.4 1400.98  4842.8 1400.10  4851.7 1397.93  4866.5 1396.65
  4873.5 1395.31  4884.3 1394.71  4890.2 1392.75  4895.7 1392.61  4913.9 1387.70
  4919.4 1388.08  4927.7 1390.40  4937.6 1392.05  4943.1 1390.41  4949.4 1390.73
  4955.6 1390.04  4960.7 1390.04  4970.0 1389.29  4980.0 1387.90  5002.5 1387.66
  5018.0 1386.99  5018.3 1386.49  5021.8 1386.49  5022.0 1386.99  5040.0 1389.90
  5050.0 1392.02  5080.0 1400.37  5100.0 1402.03  5110.0 1402.37  5166.5 1402.62
#Mann=3,-1,0
  4811.5    0.12       0  5018.0    0.05       0  5022.0    0.12       0
Bank Sta=5018,5022
Exp/Cntr=0.3,0.1

Type RM Length L Ch R = 1,35213,170,170,170
BEGIN DESCRIPTION:
Cypress Tributary 2 65.0
END DESCRIPTION:
XS GIS Cut Line= 3
      2150261.60     13898584.39      2149989.86     13898510.14
      2149700.59     13898481.30
#Sta/Elev= 30
  4718.3 1404.44  4745.9 1403.59  4777.5 1403.47  4828.8 1401.79  4846.6 1399.91
  4851.7 1400.18  4870.3 1396.60  4891.4 1394.42  4901.4 1393.91  4926.0 1389.07
  4932.5 1387.41  4942.8 1386.36  4973.9 1384.98  5014.9 1385.55  5023.0 1384.94
  5023.2 1384.44  5026.7 1384.44  5027.0 1384.94  5045.1 1385.13  5065.2 1388.25
  5095.3 1391.64  5101.3 1393.22  5135.5 1394.76  5165.7 1397.44  5195.8 1399.41
  5201.9 1400.54  5207.0 1399.97  5215.9 1400.26  5246.1 1398.65  5290.7 1398.15
#Mann=3,-1,0
  4718.3    0.12       0  5023.0    0.05       0  5027.0    0.12       0
Bank Sta=5023,5027
Exp/Cntr=0.3,0.1

Type RM Length L Ch R = 1,35043,271,271,271
BEGIN DESCRIPTION:
Cypress Tributary 2 64.0
END DESCRIPTION:
XS GIS Cut Line= 3
      2150269.20     13898367.37      2149975.00     13898375.00
      2149729.43     13898404.19
#Sta/Elev= 30
  4705.7 1400.55  4769.9 1400.51  4779.9 1399.93  4806.1 1395.62  4811.1 1395.87
  4839.9 1394.17  4849.9 1391.83  4870.0 1385.30  4880.0 1383.23  4900.0 1381.23
  4910.0 1380.87  4920.0 1382.18  4940.0 1378.88  4961.7 1378.43  4990.0 1375.82
  5008.1 1375.79  5008.3 1375.29  5011.8 1375.29  5012.1 1375.79  5038.8 1376.44
  5060.4 1378.58  5070.5 1381.01  5090.6 1387.44  5110.8 1391.43  5120.8 1391.85
  5126.5 1393.11  5151.1 1395.16  5191.8 1395.75  5214.2 1396.39  5247.3 1395.91
#Mann=5,-1,0
  4705.7    0.12       0  4961.7    0.07       0  5008.1    0.05       0
  5012.1    0.07       0  5191.8    0.12       0
Bank Sta=5008.1,5012.1
Exp/Cntr=0.3,0.1

Type RM Length L Ch R = 1,34772,270,270,270
BEGIN DESCRIPTION:
Cypress Tributary 2 63.0
END DESCRIPTION:
XS GIS Cut Line= 3
      2150293.02     13898156.86      2149925.00     13898125.00
      2149619.06     13898176.24
#Sta/Elev= 30
  4630.6 1394.66  4658.7 1394.43  4698.9 1395.97  4729.0 1394.51  4749.1 1391.97
  4759.1 1387.70  4762.2 1387.12  4769.1 1385.82  4830.2 1380.71  4869.5 1379.54
  4889.6 1379.99  4929.7 1376.22  4938.4 1376.51  4941.4 1375.94  4941.7 1375.44
  4945.4 1375.94  4979.9 1377.28  5000.6 1376.67  5010.1 1378.93  5050.7 1380.72
  5060.8 1381.86  5093.6 1386.97  5101.4 1388.79  5111.5 1389.55  5121.7 1388.85
  5149.2 1388.95  5154.3 1389.59  5172.4 1388.51  5235.1 1388.30  5310.2 1386.71
#Mann=6,-1,0
  4630.6    0.12       0  4762.2   0.035       0  4941.4   0.035       0
  4945.4   0.035       0  5000.6    0.07       0  5235.1    0.12       0
Bank Sta=4941.4,4945.4
Exp/Cntr=0.3,0.1

Type RM Length L Ch R = 1,34502,413,413,413
BEGIN DESCRIPTION:
Cypress Tributary 2 62.0
END DESCRIPTION:
XS GIS Cut Line= 3
      2150255.27     13897924.66      2149875.00     13897875.00
      2149564.30     13897876.05
#Sta/Elev= 30
  4616.5 1390.06  4626.9 1390.27  4647.0 1382.67  4652.3 1382.93  4677.3 1381.49
  4687.4 1381.99  4788.2 1377.94  4852.4 1376.76  4889.1 1376.41  4909.2 1375.00
  4949.6 1374.35  4963.0 1373.62  4989.9 1373.82  4993.1 1373.04  4995.5 1372.46
  4995.7 1371.96  4999.2 1371.96  4999.5 1372.46  5010.0 1372.51  5020.0 1376.80
  5030.0 1377.90  5060.0 1378.86  5090.0 1380.59  5190.0 1380.00  5200.0 1380.49
  5240.0 1379.25  5250.0 1380.18  5271.7 1379.45  5280.0 1378.98  5310.7 1379.53
#Mann=6,-1,0
  4616.5    0.07       0  4852.4   0.035       0  4993.1    0.07       0
  4995.5    0.05       0  4999.5    0.07       0  5271.7    0.12       0
Bank Sta=4995.5,4999.5
Exp/Cntr=0.3,0.1

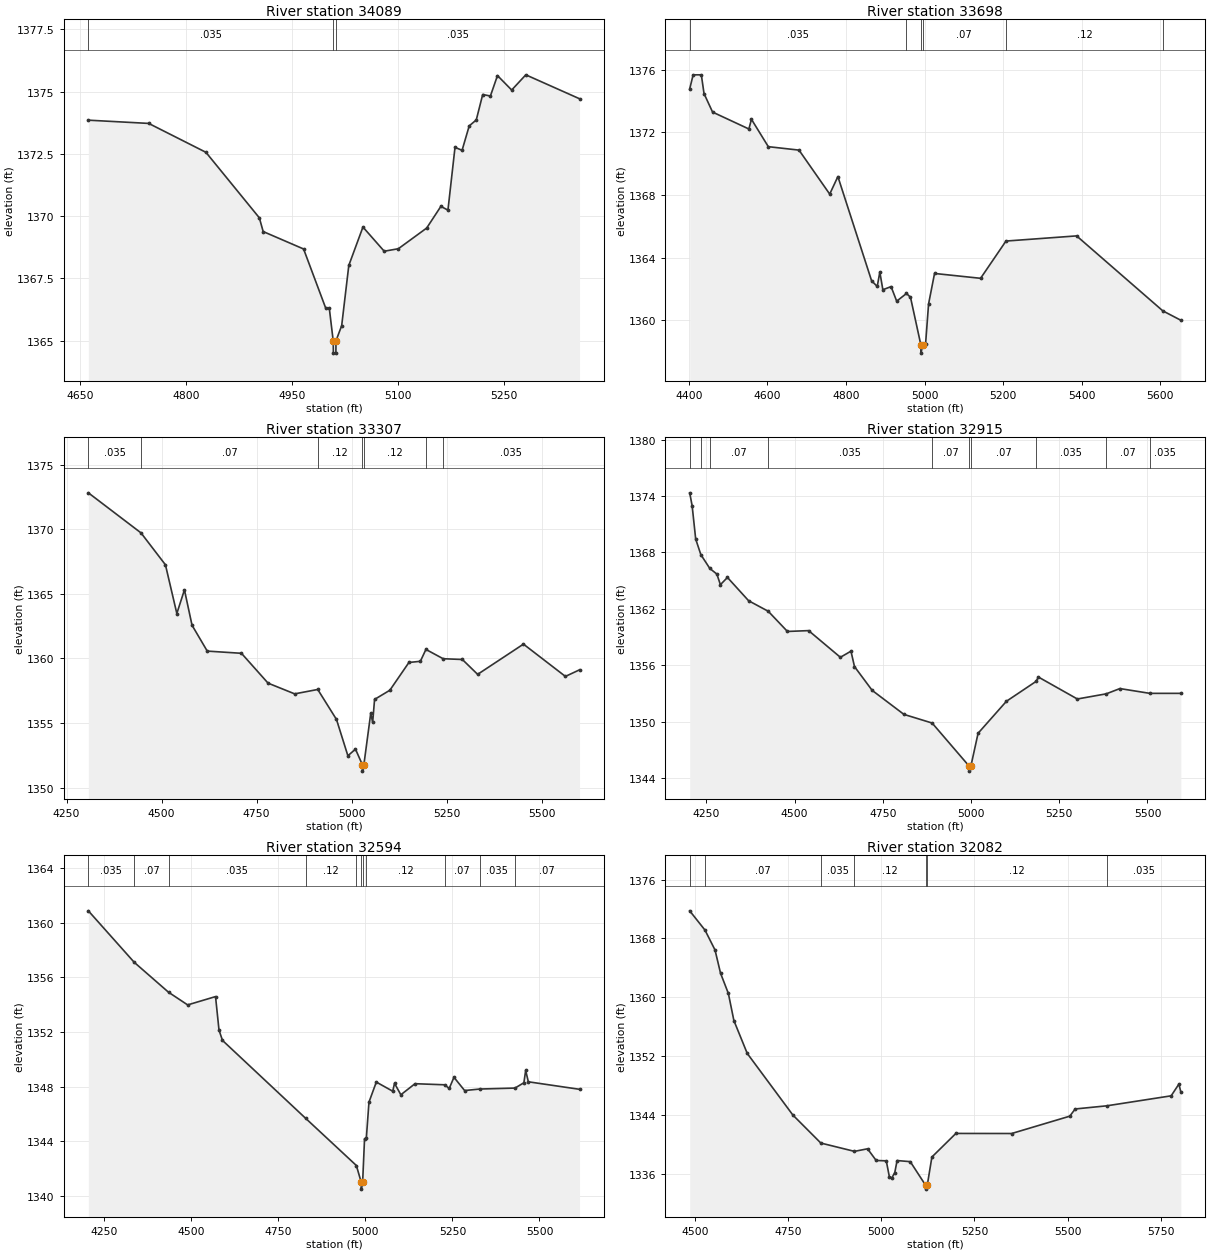
Type RM Length L Ch R = 1,34089,391,391,391
BEGIN DESCRIPTION:
Cypress Tributary 2 61.0
END DESCRIPTION:
XS GIS Cut Line= 3
      2150359.41     13897577.43      2150025.00     13897525.00
      2149669.20     13897501.10
#Sta/Elev= 30
  4661.5 1373.85  4746.9 1373.72  4827.9 1372.56  4903.5 1369.93  4908.9 1369.38
  4966.1 1368.68  4997.5 1366.30  5002.5 1366.30  5008.0 1365.00  5008.3 1364.50
  5011.8 1364.50  5012.0 1365.00  5020.0 1365.60  5030.1 1368.02  5050.1 1369.56
  5080.2 1368.59  5100.2 1368.69  5140.3 1369.52  5160.4 1370.39  5170.4 1370.24
  5180.4 1372.76  5190.4 1372.64  5200.5 1373.62  5210.5 1373.86  5219.6 1374.88
  5230.5 1374.82  5240.5 1375.64  5260.6 1375.06  5280.6 1375.67  5356.6 1374.71
#Mann=3,-1,0
  4661.5   0.035       0  5008.0   0.035       0  5012.0   0.035       0
Bank Sta=5008,5012
Exp/Cntr=0.3,0.1

Type RM Length L Ch R = 1,33698,391,391,391
BEGIN DESCRIPTION:
Cypress Tributary 2 60.0
END DESCRIPTION:
XS GIS Cut Line= 3
      2150508.75     13897632.98      2150125.00     13897175.00
      2149484.49     13897053.14
#Sta/Elev= 30
  4402.5 1374.78  4411.3 1375.68  4432.1 1375.68  4439.0 1374.48  4460.7 1373.30
  4553.1 1372.22  4559.6 1372.84  4602.5 1371.09  4680.6 1370.87  4758.7 1368.06
  4779.5 1369.18  4865.3 1362.52  4879.6 1362.16  4886.2 1363.08  4893.9 1361.95
  4914.8 1362.15  4929.1 1361.22  4954.0 1361.71  4964.2 1361.47  4990.8 1358.40
  4991.1 1357.90  4994.8 1358.40  5002.5 1358.46  5010.2 1361.04  5025.4 1362.99
  5142.5 1362.68  5207.1 1365.06  5386.8 1365.39  5606.1 1360.60  5652.0 1360.00
#Mann=6,-1,0
  4402.5   0.035       0  4954.0    0.07       0  4990.8    0.05       0
  4994.8    0.07       0  5207.1    0.12       0  5606.1   0.035       0
Bank Sta=4990.8,4994.8
Exp/Cntr=0.3,0.1

Type RM Length L Ch R = 1,33307,392,392,392
BEGIN DESCRIPTION:
Cypress Tributary 2 59.0
END DESCRIPTION:
XS GIS Cut Line= 3
      2150817.80     13896823.97      2150125.00     13896825.00
      2149528.07     13896879.34
#Sta/Elev= 30
  4307.2 1372.81  4445.7 1369.71  4510.0 1367.24  4540.0 1363.47  4560.0 1365.30
  4580.0 1362.56  4620.0 1360.56  4710.0 1360.39  4780.0 1358.08  4850.0 1357.25
  4910.7 1357.59  4960.0 1355.27  4990.0 1352.46  5010.0 1352.97  5028.1 1351.77
  5028.4 1351.27  5032.1 1351.77  5050.2 1355.76  5055.2 1355.04  5060.2 1356.82
  5100.4 1357.53  5150.6 1359.68  5180.7 1359.77  5195.3 1360.69  5240.6 1359.97
  5291.2 1359.91  5331.4 1358.76  5451.9 1361.10  5562.3 1358.60  5599.4 1359.11
#Mann=7,-1,0
  4307.2   0.035       0  4445.7    0.07       0  4910.7    0.12       0
  5028.1    0.05       0  5032.1    0.12       0  5195.3    0.07       0
  5240.6   0.035       0
Bank Sta=5028.1,5032.1
Exp/Cntr=0.3,0.1

Type RM Length L Ch R = 1,32915,321,321,321
BEGIN DESCRIPTION:
Cypress Tributary 2 58.0
END DESCRIPTION:
XS GIS Cut Line= 3
      2150921.95     13896490.63      2150125.00     13896475.00
      2149533.07     13896532.30
#Sta/Elev= 30
  4202.9 1374.35  4209.8 1372.99  4219.9 1369.43  4234.5 1367.77  4259.9 1366.30
  4279.9 1365.70  4289.9 1364.57  4309.9 1365.34  4369.9 1362.86  4425.5 1361.74
  4479.9 1359.59  4539.9 1359.68  4629.9 1356.84  4659.9 1357.49  4669.9 1355.85
  4719.9 1353.32  4810.0 1350.76  4889.9 1349.84  4995.5 1345.22  4995.7 1344.72
  4999.5 1345.22  5020.1 1348.75  5100.5 1352.16  5184.7 1354.28  5190.9 1354.74
  5301.4 1352.40  5383.3 1352.95  5422.0 1353.51  5506.8 1353.00  5594.7 1353.00
#Mann=10,-1,0
  4202.9    0.07       0  4234.5   0.035       0  4259.9    0.07       0
  4425.5   0.035       0  4889.9    0.07       0  4995.5    0.05       0
  4999.5    0.07       0  5184.7   0.035       0  5383.3    0.07       0
  5506.8   0.035       0
Bank Sta=4995.5,4999.5
Exp/Cntr=0.3,0.1

Type RM Length L Ch R = 1,32594,512,512,512
BEGIN DESCRIPTION:
Cypress Tributary 2 57.0
END DESCRIPTION:
XS GIS Cut Line= 3
      2150869.93     13896216.33      2150075.00     13896175.00
      2149470.60     13896289.24
#Sta/Elev= 30
  4204.0 1360.88  4335.8 1357.11  4434.3 1354.92  4489.3 1353.99  4569.4 1354.60
  4579.4 1352.14  4589.4 1351.39  4828.5 1345.68  4974.0 1342.23  4988.0 1341.00
  4988.2 1340.50  4992.0 1341.00  4997.5 1344.19  5002.6 1344.22  5010.2 1346.87
  5031.3 1348.34  5078.5 1347.67  5083.6 1348.25  5101.8 1347.41  5142.5 1348.22
  5227.9 1348.14  5240.7 1347.87  5254.4 1348.69  5285.0 1347.72  5328.8 1347.83
  5429.7 1347.90  5455.3 1348.29  5460.4 1349.19  5468.1 1348.36  5615.1 1347.81
#Mann=11,-1,0
  4204.0   0.035       0  4335.8    0.07       0  4434.3   0.035       0
  4828.5    0.12       0  4974.0    0.07       0  4988.0    0.05       0
  4992.0    0.07       0  5002.6    0.12       0  5227.9    0.07       0
  5328.8   0.035       0  5429.7    0.07       0
Bank Sta=4988,4992
Exp/Cntr=0.3,0.1

Type RM Length L Ch R = 1,32082,665,665,665
BEGIN DESCRIPTION:
Cypress Tributary 2 56.0
END DESCRIPTION:
XS GIS Cut Line= 3
      2150446.29     13895431.59      2150025.00     13895725.00
      2149388.64     13896215.24
#Sta/Elev= 30
  4486.6 1371.76  4527.7 1369.13  4554.5 1366.43  4569.3 1363.27  4590.3 1360.51
  4605.1 1356.82  4640.9 1352.35  4763.1 1343.97  4838.2 1340.15  4928.3 1339.02
  4963.4 1339.37  4986.5 1337.78  5013.6 1337.73  5021.8 1335.58  5028.1 1335.38
  5036.3 1336.11  5042.6 1337.77  5077.9 1337.62  5119.4 1334.38  5119.7 1333.88
  5123.4 1334.38  5135.9 1338.25  5200.2 1341.46  5349.7 1341.45  5505.5 1343.81
  5520.0 1344.79  5604.8 1345.22  5777.3 1346.58  5798.1 1348.18  5803.3 1347.09
#Mann=7,-1,0
  4486.6    0.12       0  4527.7    0.07       0  4838.2   0.035       0
  4928.3    0.12       0  5119.4    0.05       0  5123.4    0.12       0
  5604.8   0.035       0
Bank Sta=5119.4,5123.4
Exp/Cntr=0.3,0.1

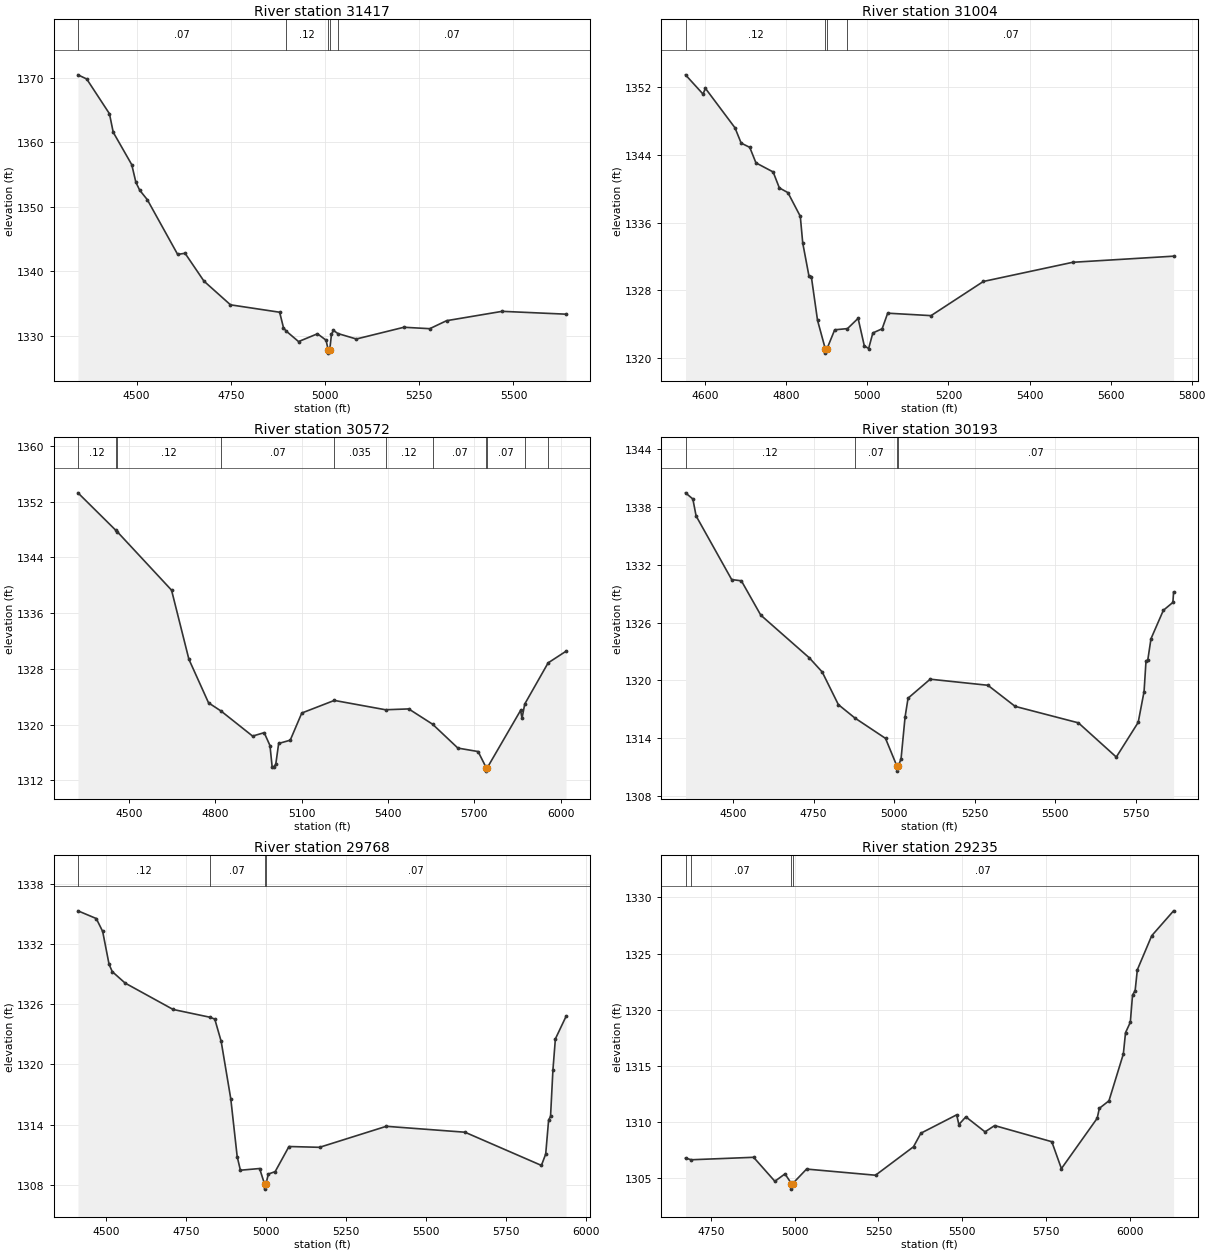
Type RM Length L Ch R = 1,31417,413,413,413
BEGIN DESCRIPTION:
Cypress Tributary 2 55.0
END DESCRIPTION:
XS GIS Cut Line= 3
      2150328.23     13895317.02      2149675.00     13895375.00
      2149058.73     13895545.81
#Sta/Elev= 30
  4344.2 1370.45  4367.5 1369.80  4427.8 1364.42  4437.8 1361.55  4487.0 1356.52
  4498.0 1353.78  4508.1 1352.56  4528.2 1351.10  4608.8 1342.61  4628.5 1342.78
  4678.7 1338.46  4749.0 1334.79  4879.5 1333.64  4889.6 1331.26  4896.1 1330.76
  4929.7 1329.09  4979.9 1330.30  5002.6 1329.31  5008.4 1327.80  5008.6 1327.30
  5012.4 1327.80  5017.1 1330.24  5022.3 1330.83  5033.9 1330.34  5083.0 1329.49
  5209.3 1331.31  5277.9 1331.09  5322.6 1332.33  5470.1 1333.78  5639.5 1333.34
#Mann=5,-1,0
  4344.2    0.07       0  4896.1    0.12       0  5008.4    0.05       0
  5012.4    0.12       0  5033.9    0.07       0
Bank Sta=5008.4,5012.4
Exp/Cntr=0.3,0.1

Type RM Length L Ch R = 1,31004,432,432,432
BEGIN DESCRIPTION:
Cypress Tributary 2 54.0
END DESCRIPTION:
XS GIS Cut Line= 3
      2149904.60     13894785.77      2149525.00     13895025.00
      2148922.09     13895480.12
#Sta/Elev= 30
  4551.3 1353.41  4594.5 1351.14  4600.4 1351.82  4673.4 1347.16  4688.6 1345.36
  4709.8 1344.86  4725.1 1343.03  4767.5 1341.96  4782.8 1340.08  4804.0 1339.52
  4834.5 1336.73  4840.5 1333.59  4855.8 1329.71  4861.7 1329.63  4877.0 1324.47
  4896.2 1321.10  4896.4 1320.60  4900.2 1321.10  4919.4 1323.35  4950.9 1323.49
  4977.1 1324.70  4992.4 1321.46  5003.1 1321.14  5013.5 1322.98  5036.4 1323.47
  5050.1 1325.31  5157.1 1325.02  5286.2 1329.05  5506.8 1331.31  5755.4 1332.03
#Mann=4,-1,0
  4551.3    0.12       0  4896.2    0.05       0  4900.2    0.12       0
  4950.9    0.07       0
Bank Sta=4896.2,4900.2
Exp/Cntr=0.3,0.1

Type RM Length L Ch R = 1,30572,379,379,379
BEGIN DESCRIPTION:
Cypress Tributary 2 53.0
END DESCRIPTION:
XS GIS Cut Line= 3
      2149998.34     13894598.27      2149325.00     13894675.00
      2148310.85     13894775.35
#Sta/Elev= 30
  4322.3 1353.26  4454.2 1347.87  4458.4 1347.70  4647.7 1339.29  4708.1 1329.36
  4776.4 1323.11  4819.7 1321.94  4929.5 1318.34  4969.8 1318.83  4989.9 1316.98
  4997.5 1313.91  5002.5 1313.91  5010.0 1314.28  5020.1 1317.28  5060.3 1317.75
  5100.5 1321.65  5213.6 1323.46  5391.6 1322.12  5472.3 1322.24  5555.1 1320.05
  5643.1 1316.62  5713.5 1316.12  5741.6 1313.81  5741.9 1313.31  5745.6 1313.81
  5861.2 1322.03  5866.2 1320.90  5875.6 1322.94  5956.9 1328.85  6019.1 1330.52
#Mann=11,-1,0
  4322.3    0.12       0  4454.2    0.07       0  4458.4    0.12       0
  4819.7    0.07       0  5213.6   0.035       0  5391.6    0.12       0
  5555.1    0.07       0  5741.6    0.05       0  5745.6    0.07       0
  5875.6    0.12       0  5956.9    0.07       0
Bank Sta=5741.6,5745.6
Exp/Cntr=0.3,0.1

Type RM Length L Ch R = 1,30193,425,425,425
BEGIN DESCRIPTION:
Cypress Tributary 2 52.0
END DESCRIPTION:
XS GIS Cut Line= 3
      2149817.75     13894292.72      2149210.15     13894344.80
      2148369.96     13894681.57
#Sta/Elev= 30
  4352.3 1339.47  4375.1 1338.83  4385.2 1337.07  4495.6 1330.47  4525.7 1330.34
  4585.9 1326.78  4736.5 1322.35  4776.6 1320.88  4826.8 1317.49  4878.2 1316.10
  4973.1 1313.99  5008.8 1311.09  5009.0 1310.59  5012.8 1311.09  5021.5 1311.90
  5033.8 1316.19  5043.1 1318.16  5111.8 1320.13  5290.9 1319.50  5375.5 1317.31
  5571.9 1315.60  5689.5 1312.05  5757.5 1315.65  5775.7 1318.85  5781.8 1322.05
  5787.1 1322.09  5797.2 1324.33  5835.6 1327.28  5865.2 1328.10  5867.3 1329.17
#Mann=4,-1,0
  4352.3    0.12       0  4878.2    0.07       0  5008.8    0.05       0
  5012.8    0.07       0
Bank Sta=5008.8,5012.8
Exp/Cntr=0.3,0.1

Type RM Length L Ch R = 1,29768,533,533,533
BEGIN DESCRIPTION:
Cypress Tributary 2 51.0
END DESCRIPTION:
XS GIS Cut Line= 3
      2149762.20     13893976.74      2149175.00     13893975.00
      2148390.72     13894487.16
#Sta/Elev= 30
  4412.8 1335.36  4470.0 1334.59  4490.0 1333.30  4510.0 1330.01  4520.0 1329.28
  4560.0 1328.14  4710.0 1325.50  4823.8 1324.73  4840.0 1324.54  4860.0 1322.31
  4890.0 1316.57  4910.0 1310.79  4920.0 1309.43  4980.0 1309.60  4995.5 1308.04
  4995.7 1307.54  4999.5 1308.04  5007.6 1309.05  5028.6 1309.29  5071.7 1311.80
  5167.2 1311.72  5375.6 1313.82  5621.1 1313.23  5859.9 1309.91  5873.3 1311.05
  5882.4 1314.45  5888.4 1314.81  5895.8 1319.43  5903.5 1322.56  5936.7 1324.80
#Mann=4,-1,0
  4412.8    0.12       0  4823.8    0.07       0  4995.5    0.05       0
  4999.5    0.07       0
Bank Sta=4995.5,4999.5
Exp/Cntr=0.3,0.1

Type RM Length L Ch R = 1,29235,969,969,969
BEGIN DESCRIPTION:
Cypress Tributary 2 50.0
END DESCRIPTION:
XS GIS Cut Line= 3
      2149203.23     13893303.11      2149025.00     13893575.00
      2148296.96     13894438.55
#Sta/Elev= 30
  4674.9 1306.75  4692.0 1306.60  4877.9 1306.82  4941.2 1304.68  4971.4 1305.34
  4990.5 1304.48  4990.7 1303.98  4994.5 1304.48  5035.7 1305.77  5241.2 1305.22
  5354.4 1307.76  5376.4 1308.97  5483.1 1310.61  5489.6 1309.74  5510.4 1310.43
  5567.6 1309.09  5596.2 1309.65  5766.6 1308.21  5795.2 1305.81  5901.8 1310.30
  5908.3 1311.19  5936.9 1311.86  5979.8 1316.04  5986.3 1317.94  6000.6 1318.87
  6007.2 1321.30  6014.9 1321.68  6021.5 1323.55  6064.4 1326.59  6129.5 1328.81
#Mann=4,-1,0
  4674.9    0.12       0  4692.0    0.07       0  4990.5    0.05       0
  4994.5    0.07       0
Bank Sta=4990.5,4994.5
Exp/Cntr=0.3,0.1

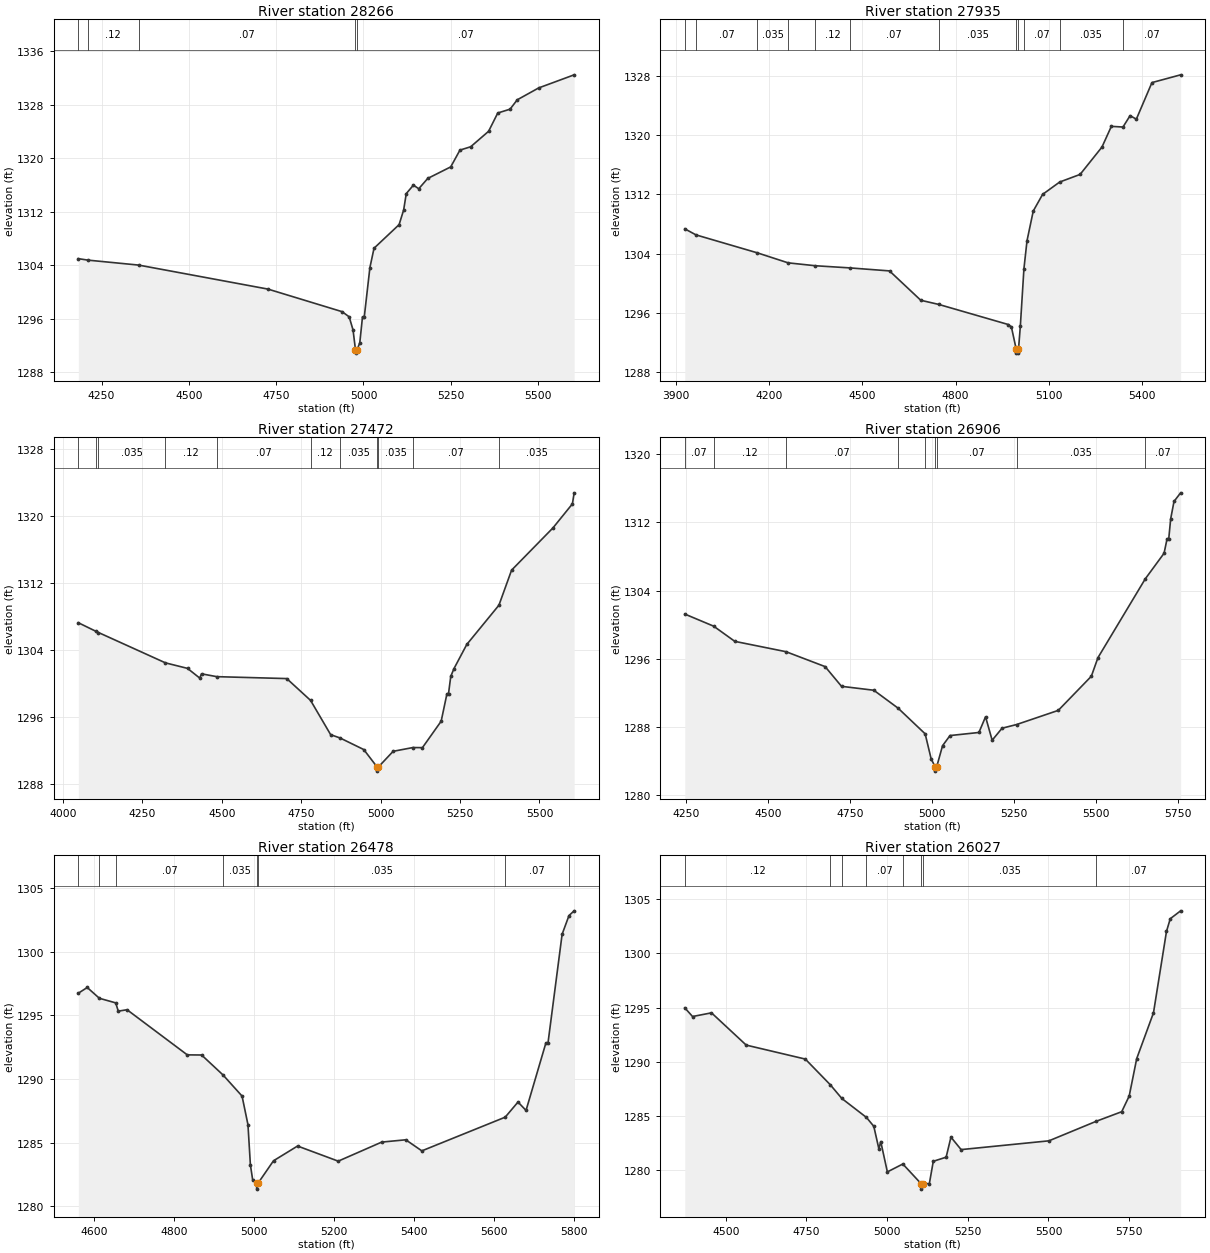
Type RM Length L Ch R = 1,28266,331,331,331
BEGIN DESCRIPTION:
Cypress Tributary 2 49.0
END DESCRIPTION:
XS GIS Cut Line= 3
      2149081.71     13893251.04      2148274.60     13893375.17
      2147685.90     13893507.98
#Sta/Elev= 30
  4183.4 1305.01  4211.1 1304.79  4356.1 1304.05  4726.4 1300.46  4938.9 1297.08
  4959.1 1296.31  4970.2 1294.35  4977.2 1291.38  4977.5 1290.88  4981.5 1291.38
  4989.5 1292.41  4997.3 1296.31  5002.4 1296.31  5018.5 1303.68  5030.3 1306.57
  5102.1 1310.10  5115.2 1312.30  5122.6 1314.74  5143.1 1316.01  5158.4 1315.47
  5184.1 1317.01  5250.0 1318.74  5276.4 1321.25  5307.1 1321.75  5358.4 1324.06
  5384.7 1326.80  5419.9 1327.37  5440.4 1328.77  5501.9 1330.55  5603.5 1332.51
#Mann=5,-1,0
  4183.4   0.035       0  4211.1    0.12       0  4356.1    0.07       0
  4977.2    0.05       0  4981.5    0.07       0
Bank Sta=4977.2,4981.5
Exp/Cntr=0.3,0.1

Type RM Length L Ch R = 1,27935,463,463,463
BEGIN DESCRIPTION:
Cypress Tributary 2 48.0
END DESCRIPTION:
XS GIS Cut Line= 3
      2149289.99     13893174.66      2148224.51     13893061.20
      2147703.22     13893007.99
#Sta/Elev= 30
  3928.5 1307.35  3964.6 1306.53  4162.2 1304.10  4261.0 1302.75  4348.2 1302.36
  4458.7 1302.07  4587.2 1301.66  4687.8 1297.69  4746.3 1297.12  4969.3 1294.41
  4979.4 1294.09  4995.1 1291.04  4995.4 1290.54  4999.1 1290.54  4999.4 1291.04
  5002.3 1291.04  5008.2 1294.18  5019.8 1301.96  5029.7 1305.74  5049.8 1309.76
  5079.9 1312.01  5134.8 1313.68  5200.5 1314.71  5270.9 1318.41  5301.1 1321.21
  5338.5 1321.12  5361.4 1322.66  5381.5 1322.18  5431.7 1327.13  5524.0 1328.18
#Mann=12,-1,0
  3928.5    0.12       0  3964.6    0.07       0  4162.2   0.035       0
  4261.0    0.07       0  4348.2    0.12       0  4458.7    0.07       0
  4746.3   0.035       0  4995.1   0.035       0  4999.4   0.035       0
  5019.8    0.07       0  5134.8   0.035       0  5338.5    0.07       0
Bank Sta=4995.1,4999.4
Exp/Cntr=0.3,0.1

Type RM Length L Ch R = 1,27472,566,566,566
BEGIN DESCRIPTION:
Cypress Tributary 2 47.0
END DESCRIPTION:
XS GIS Cut Line= 3
      2149304.21     13893130.81      2148464.24     13892684.68
      2147859.50     13892757.49
#Sta/Elev= 30
  4048.9 1307.25  4103.4 1306.24  4112.3 1306.08  4323.1 1302.45  4392.5 1301.79
  4430.9 1300.63  4436.5 1301.14  4484.6 1300.80  4704.7 1300.57  4779.7 1297.96
  4842.9 1293.86  4872.2 1293.47  4947.1 1292.08  4988.9 1290.00  4989.2 1289.50
  4993.2 1290.00  5039.5 1291.87  5101.6 1292.32  5131.7 1292.31  5190.6 1295.47
  5208.8 1298.75  5213.8 1298.78  5220.8 1300.83  5230.9 1301.76  5271.2 1304.65
  5372.4 1309.35  5412.2 1313.54  5542.3 1318.59  5603.6 1321.47  5609.1 1322.79
#Mann=11,-1,0
  4048.9    0.12       0  4103.4    0.07       0  4112.3   0.035       0
  4323.1    0.12       0  4484.6    0.07       0  4779.7    0.12       0
  4872.2   0.035       0  4988.9   0.035       0  4993.2   0.035       0
  5101.6    0.07       0  5372.4   0.035       0
Bank Sta=4988.9,4993.2
Exp/Cntr=0.3,0.1

Type RM Length L Ch R = 1,26906,428,428,428
BEGIN DESCRIPTION:
Cypress Tributary 2 46.0
END DESCRIPTION:
XS GIS Cut Line= 3
      2149185.27     13892780.09      2148677.49     13892222.84
      2147925.00     13892325.00
#Sta/Elev= 30
  4246.1 1301.26  4334.2 1299.84  4398.7 1298.06  4554.9 1296.85  4674.4 1295.10
  4724.4 1292.79  4823.0 1292.33  4897.1 1290.23  4979.7 1287.22  4998.1 1284.27
  5010.4 1283.35  5010.7 1282.85  5014.8 1283.35  5032.8 1285.83  5055.6 1287.02
  5143.8 1287.38  5164.0 1289.22  5184.2 1286.47  5214.4 1287.88  5258.7 1288.31
  5386.0 1289.97  5486.9 1293.97  5507.1 1296.15  5651.4 1305.38  5708.9 1308.39
  5718.1 1310.09  5723.2 1310.10  5729.1 1312.43  5739.2 1314.46  5759.4 1315.47
#Mann=9,-1,0
  4246.1    0.07       0  4334.2    0.12       0  4554.9    0.07       0
  4897.1    0.12       0  4979.7    0.07       0  5010.4    0.05       0
  5014.8    0.07       0  5258.7   0.035       0  5651.4    0.07       0
Bank Sta=5010.4,5014.8
Exp/Cntr=0.3,0.1

Type RM Length L Ch R = 1,26478,451,451,451
BEGIN DESCRIPTION:
Cypress Tributary 2 45.0
END DESCRIPTION:
XS GIS Cut Line= 3
      2149125.00     13892225.00      2148873.35     13891864.32
      2148074.95     13891925.00
#Sta/Elev= 30
  4560.2 1296.75  4582.5 1297.20  4612.9 1296.35  4653.7 1295.99  4660.1 1295.34
  4682.1 1295.45  4832.8 1291.90  4868.6 1291.89  4922.2 1290.32  4969.8 1288.66
  4984.6 1286.41  4990.7 1283.24  4996.5 1282.05  5006.1 1281.84  5006.5 1281.34
  5010.6 1281.84  5048.5 1283.57  5108.7 1284.73  5210.4 1283.54  5319.3 1285.04
  5379.4 1285.22  5419.6 1284.35  5628.2 1287.00  5660.2 1288.19  5680.3 1287.53
  5730.1 1292.85  5735.1 1292.80  5770.6 1301.39  5787.8 1302.86  5800.7 1303.23
#Mann=8,-1,0
  4560.2    0.07       0  4612.9    0.12       0  4653.7    0.07       0
  4922.2   0.035       0  5006.1   0.035       0  5010.6   0.035       0
  5628.2    0.07       0  5787.8   0.035       0
Bank Sta=5006.1,5010.6
Exp/Cntr=0.3,0.1

Type RM Length L Ch R = 1,26027,1040,1040,1040
BEGIN DESCRIPTION:
Cypress Tributary 2 44.0
END DESCRIPTION:
XS GIS Cut Line= 3
      2149397.60     13891763.92      2148862.39     13891452.00
      2148024.98     13891825.01
#Sta/Elev= 30
  4373.3 1294.98  4397.3 1294.18  4456.0 1294.52  4563.6 1291.54  4746.7 1290.25
  4824.0 1287.88  4859.9 1286.61  4936.1 1284.86  4958.9 1284.04  4974.6 1281.96
  4980.4 1282.63  5000.9 1279.83  5048.8 1280.56  5105.5 1278.74  5105.8 1278.24
  5110.0 1278.74  5131.0 1278.75  5143.2 1280.81  5183.0 1281.19  5197.9 1283.04
  5229.4 1281.89  5501.5 1282.70  5648.5 1284.51  5727.0 1285.39  5750.2 1286.84
  5773.5 1290.30  5825.4 1294.52  5865.7 1302.04  5877.4 1303.21  5909.5 1303.94
#Mann=8,-1,0
  4373.3    0.12       0  4824.0    0.07       0  4859.9    0.12       0
  4936.1    0.07       0  5048.8   0.035       0  5105.5    0.05       0
  5110.0   0.035       0  5648.5    0.07       0
Bank Sta=5105.5,5110
Exp/Cntr=0.3,0.1

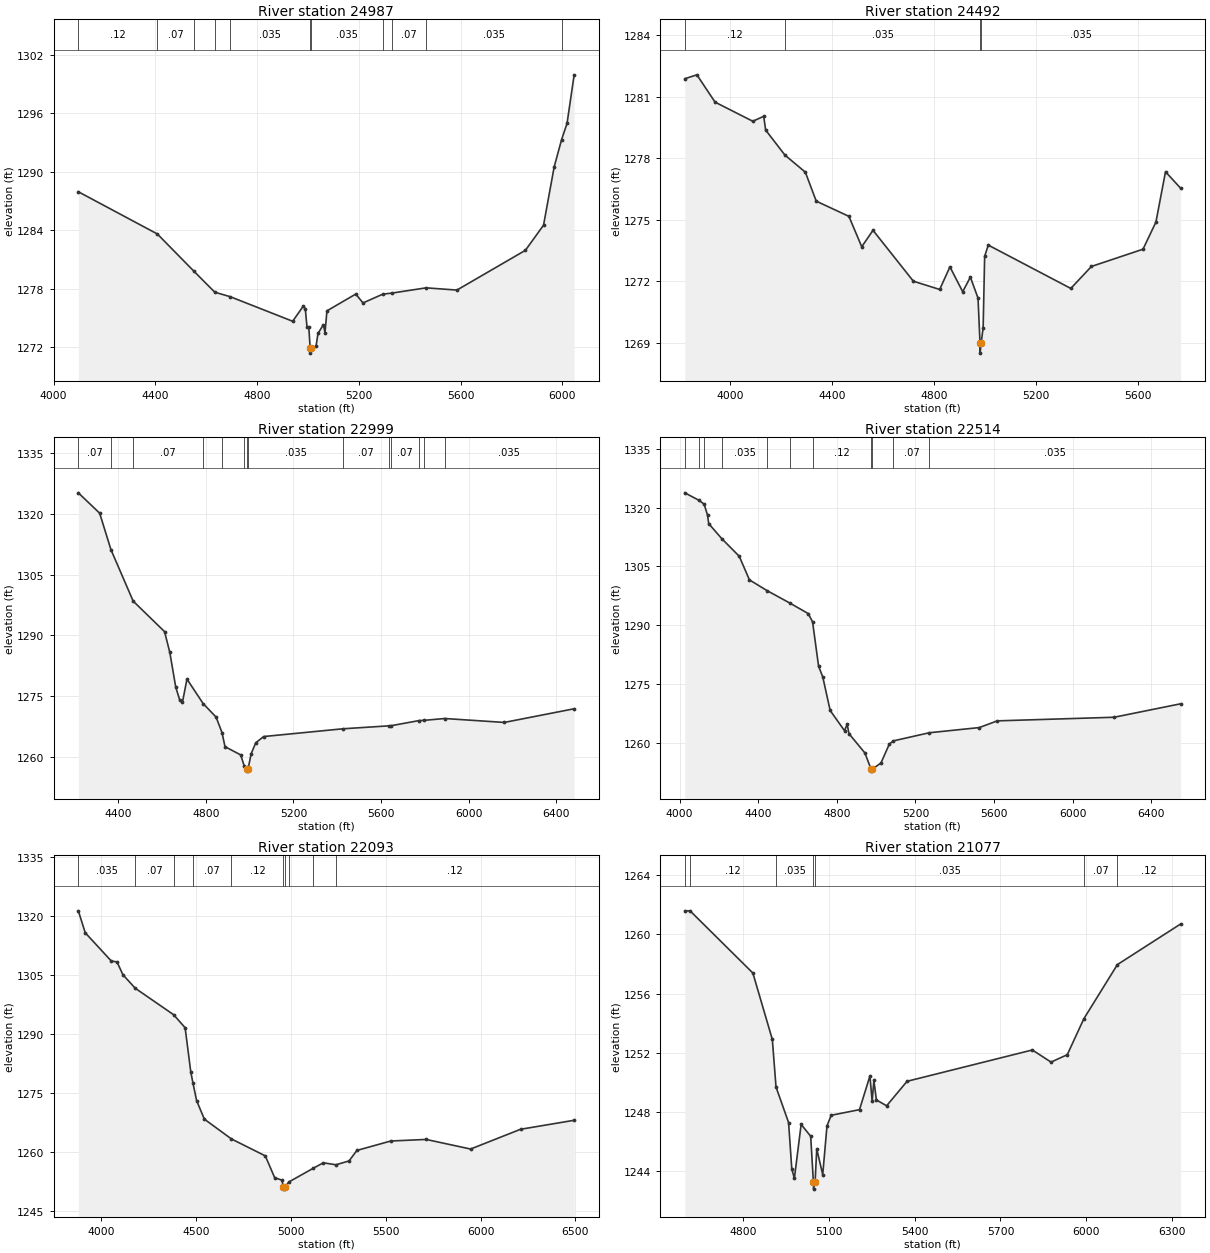
Type RM Length L Ch R = 1,24987,495,495,495
BEGIN DESCRIPTION:
Cypress Tributary 2 43.0
END DESCRIPTION:
XS GIS Cut Line= 3
      2149225.00     13891425.00      2148625.24     13890750.08
      2147824.96     13891425.03
#Sta/Elev= 30
  4097.1 1287.93  4407.7 1283.60  4551.1 1279.79  4633.8 1277.62  4694.5 1277.16
  4939.9 1274.64  4982.2 1276.21  4989.8 1275.89  4996.4 1274.02  5003.4 1274.02
  5008.8 1271.87  5009.2 1271.37  5013.4 1271.87  5032.0 1272.09  5039.6 1273.39
  5060.6 1274.28  5067.1 1273.48  5074.8 1275.71  5188.0 1277.43  5216.6 1276.52
  5294.2 1277.42  5329.6 1277.53  5464.7 1278.07  5585.9 1277.84  5855.1 1281.92
  5926.5 1284.50  5968.4 1290.49  5997.6 1293.29  6018.9 1294.94  6046.9 1299.93
#Mann=11,-1,0
  4097.1    0.12       0  4407.7    0.07       0  4551.1   0.035       0
  4633.8    0.07       0  4694.5   0.035       0  5008.8   0.035       0
  5013.4   0.035       0  5294.2   0.035       0  5329.6    0.07       0
  5464.7   0.035       0  5997.6    0.07       0
Bank Sta=5008.8,5013.4
Exp/Cntr=0.3,0.1

Type RM Length L Ch R = 1,24492,1493,1493,1493
BEGIN DESCRIPTION:
Cypress Tributary 2 42.0
END DESCRIPTION:
XS GIS Cut Line= 5
      2149290.75     13891026.22      2148869.80     13890542.51
      2148620.79     13890388.90      2148378.09     13890373.36
      2147619.19     13890488.57
#Sta/Elev= 30
  3823.0 1281.87  3870.4 1282.06  3941.7 1280.73  4089.7 1279.80  4132.5 1280.04
  4140.1 1279.37  4215.9 1278.15  4295.8 1277.32  4338.5 1275.91  4466.6 1275.17
  4516.9 1273.69  4561.1 1274.49  4719.6 1272.01  4822.7 1271.61  4862.8 1272.71
  4912.9 1271.50  4943.0 1272.21  4973.0 1271.19  4980.8 1269.01  4981.1 1268.51
  4985.4 1269.01  4993.1 1269.75  4999.0 1273.22  5013.2 1273.77  5336.9 1271.66
  5417.8 1272.73  5620.1 1273.57  5670.7 1274.89  5708.3 1277.34  5767.6 1276.54
#Mann=4,-1,0
  3823.0    0.12       0  4215.9   0.035       0  4980.8   0.035       0
  4985.4   0.035       0
Bank Sta=4980.8,4985.4
Exp/Cntr=0.3,0.1

Type RM Length L Ch R = 1,22999,485,485,485
BEGIN DESCRIPTION:
Cypress Tributary 2 41.0
END DESCRIPTION:
XS GIS Cut Line= 3
      2149620.28     13889144.72      2148855.08     13889304.97
      2147739.24     13890279.36
#Sta/Elev= 30
  4218.2 1325.20  4315.5 1320.17  4367.2 1311.13  4468.5 1298.43  4611.8 1290.88
  4635.8 1285.73  4662.9 1277.14  4680.6 1274.04  4693.6 1273.45  4714.0 1279.15
  4787.9 1273.09  4846.8 1269.76  4873.9 1265.94  4887.7 1262.44  4959.2 1260.40
  4975.2 1257.70  4986.9 1256.89  4987.4 1256.39  4992.8 1256.89  5007.2 1260.71
  5028.1 1263.40  5064.2 1264.94  5425.7 1266.86  5636.9 1267.59  5645.9 1267.62
  5773.7 1268.89  5797.6 1268.95  5890.5 1269.40  6162.4 1268.43  6481.4 1271.81
#Mann=14,-1,0
  4218.2    0.07       0  4367.2   0.035       0  4468.5    0.07       0
  4787.9    0.12       0  4873.9    0.07       0  4975.2   0.035       0
  4986.9   0.035       0  4992.8   0.035       0  5425.7    0.07       0
  5636.9   0.035       0  5645.9    0.07       0  5773.7   0.035       0
  5797.6    0.07       0  5890.5   0.035       0
Bank Sta=4986.9,4992.8
Exp/Cntr=0.3,0.1

Type RM Length L Ch R = 1,22514,421,421,421
BEGIN DESCRIPTION:
Cypress Tributary 2 40.0
END DESCRIPTION:
XS GIS Cut Line= 4
      2149460.58     13888432.91      2148615.15     13888914.94
      2148571.70     13889103.04      2147620.30     13890068.34
#Sta/Elev= 30
  4026.8 1323.74  4099.5 1321.82  4125.1 1320.85  4142.3 1318.07  4148.3 1315.90
  4214.9 1312.06  4303.7 1307.57  4355.5 1301.56  4445.8 1298.80  4561.3 1295.64
  4654.8 1292.96  4676.7 1290.84  4707.0 1279.61  4728.6 1276.79  4766.1 1268.27
  4839.0 1263.13  4852.5 1264.74  4862.0 1262.35  4942.6 1257.46  4974.2 1253.32
  4974.6 1252.82  4980.1 1253.32  5024.3 1254.89  5067.0 1259.71  5087.5 1260.53
  5270.3 1262.60  5524.4 1263.92  5616.4 1265.63  6210.3 1266.55  6548.4 1269.98
#Mann=11,-1,0
  4026.8    0.07       0  4099.5   0.035       0  4125.1    0.07       0
  4214.9   0.035       0  4445.8    0.07       0  4561.3   0.035       0
  4676.7    0.12       0  4974.2    0.05       0  4980.1    0.12       0
  5087.5    0.07       0  5270.3   0.035       0
Bank Sta=4974.2,4980.1
Exp/Cntr=0.3,0.1

Type RM Length L Ch R = 1,22093,1016,1016,1016
BEGIN DESCRIPTION:
Cypress Tributary 2 39.0
END DESCRIPTION:
XS GIS Cut Line= 3
      2149394.64     13888412.07      2148300.87     13888648.18
      2147385.04     13889831.13
#Sta/Elev= 30
  3878.1 1321.23  3914.6 1315.65  4051.7 1308.49  4082.3 1308.23  4113.0 1305.01
  4177.9 1301.57  4380.9 1294.82  4441.3 1291.52  4471.1 1280.32  4482.4 1277.52
  4501.8 1273.01  4542.7 1268.29  4685.4 1263.26  4864.2 1258.95  4913.5 1253.42
  4951.9 1252.77  4959.8 1251.00  4960.3 1250.50  4965.8 1251.00  4989.8 1252.36
  5115.5 1255.76  5170.1 1257.19  5237.0 1256.69  5305.9 1257.67  5347.5 1260.34
  5525.9 1262.73  5712.4 1263.13  5946.9 1260.69  6210.4 1265.71  6493.1 1268.00
#Mann=10,-1,0
  3878.1   0.035       0  4177.9    0.07       0  4380.9    0.12       0
  4482.4    0.07       0  4685.4    0.12       0  4959.8   0.035       0
  4965.8    0.12       0  4989.8   0.035       0  5115.5    0.07       0
  5237.0    0.12       0
Bank Sta=4959.8,4965.8
Exp/Cntr=0.3,0.1

Type RM Length L Ch R = 1,21077,444,444,444
BEGIN DESCRIPTION:
Cypress Tributary 2 38.0
END DESCRIPTION:
XS GIS Cut Line= 3
      2148453.66     13887693.32      2148054.62     13887755.15
      2147293.91     13888846.13
#Sta/Elev= 30
  4596.2 1261.60  4614.6 1261.60  4834.2 1257.39  4902.3 1252.89  4915.2 1249.67
  4959.1 1247.27  4970.3 1244.13  4979.4 1243.49  5003.0 1247.14  5036.4 1246.34
  5045.8 1243.26  5046.3 1242.76  5051.9 1243.26  5057.6 1245.48  5078.5 1243.74
  5093.4 1247.04  5108.2 1247.76  5207.1 1248.14  5243.6 1250.42  5251.3 1248.71
  5257.4 1250.12  5266.1 1248.80  5301.9 1248.40  5373.4 1250.06  5811.4 1252.18
  5876.9 1251.36  5933.6 1251.86  5991.5 1254.29  6108.9 1257.96  6330.0 1260.71
#Mann=7,-1,0
  4596.2    0.07       0  4614.6    0.12       0  4915.2   0.035       0
  5045.8   0.035       0  5051.9   0.035       0  5991.5    0.07       0
  6108.9    0.12       0
Bank Sta=5045.8,5051.9
Exp/Cntr=0.3,0.1