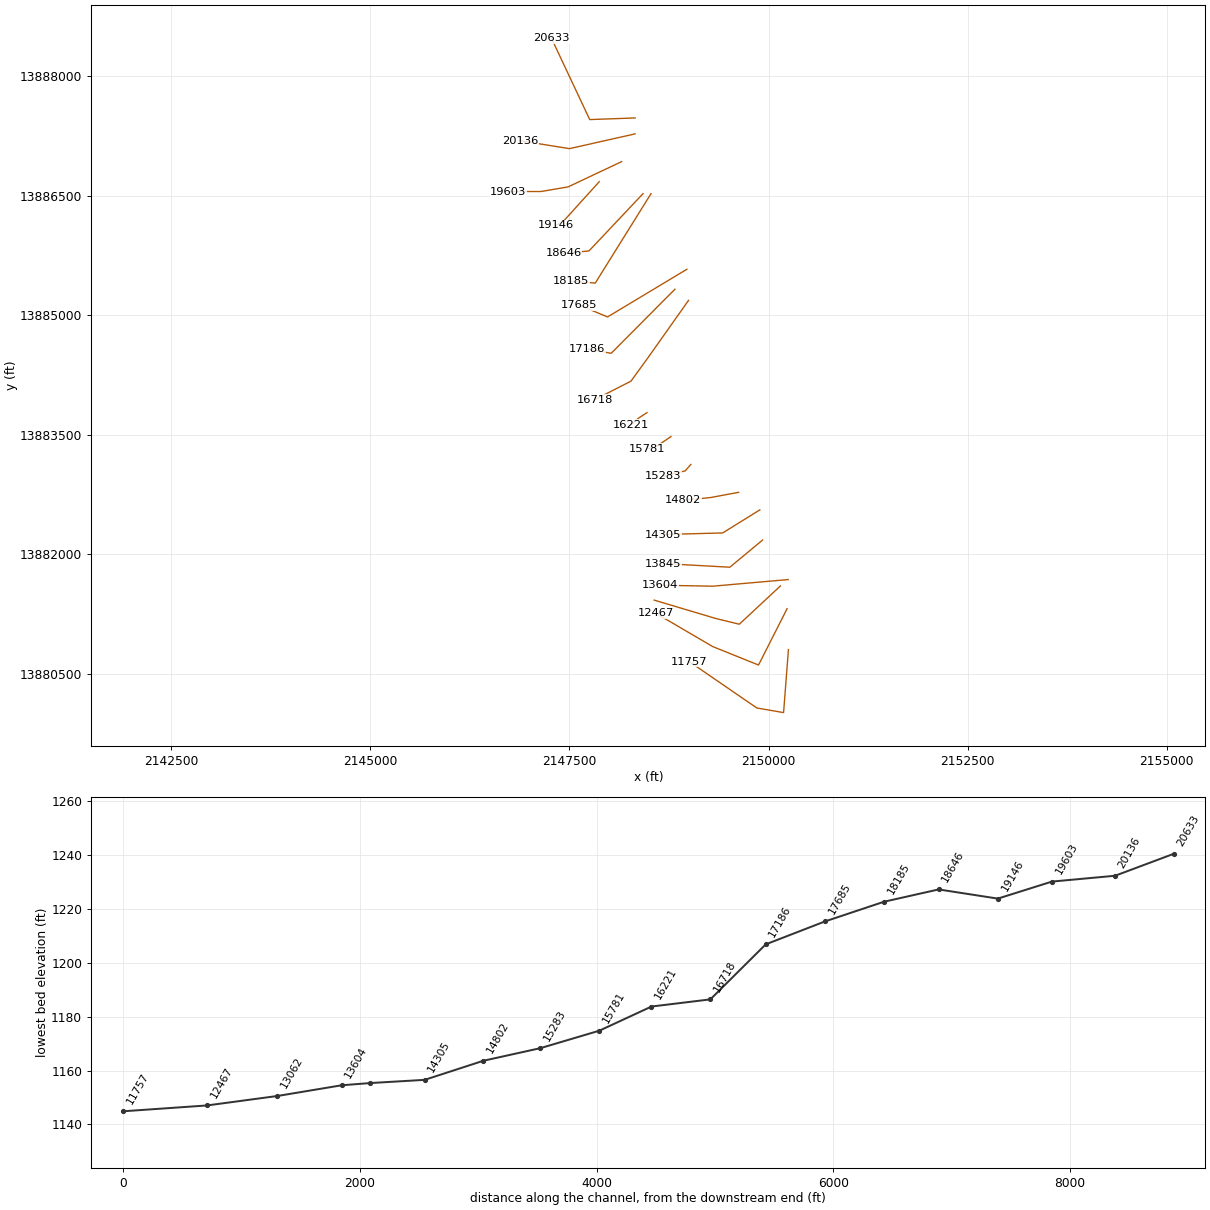
HEC-RAS study Cypress Tributary 2.prj: Cypress Tributary 2 Base Level Engineering

--- Cypress Tributary 2.g01 (geometry) --- (continued)

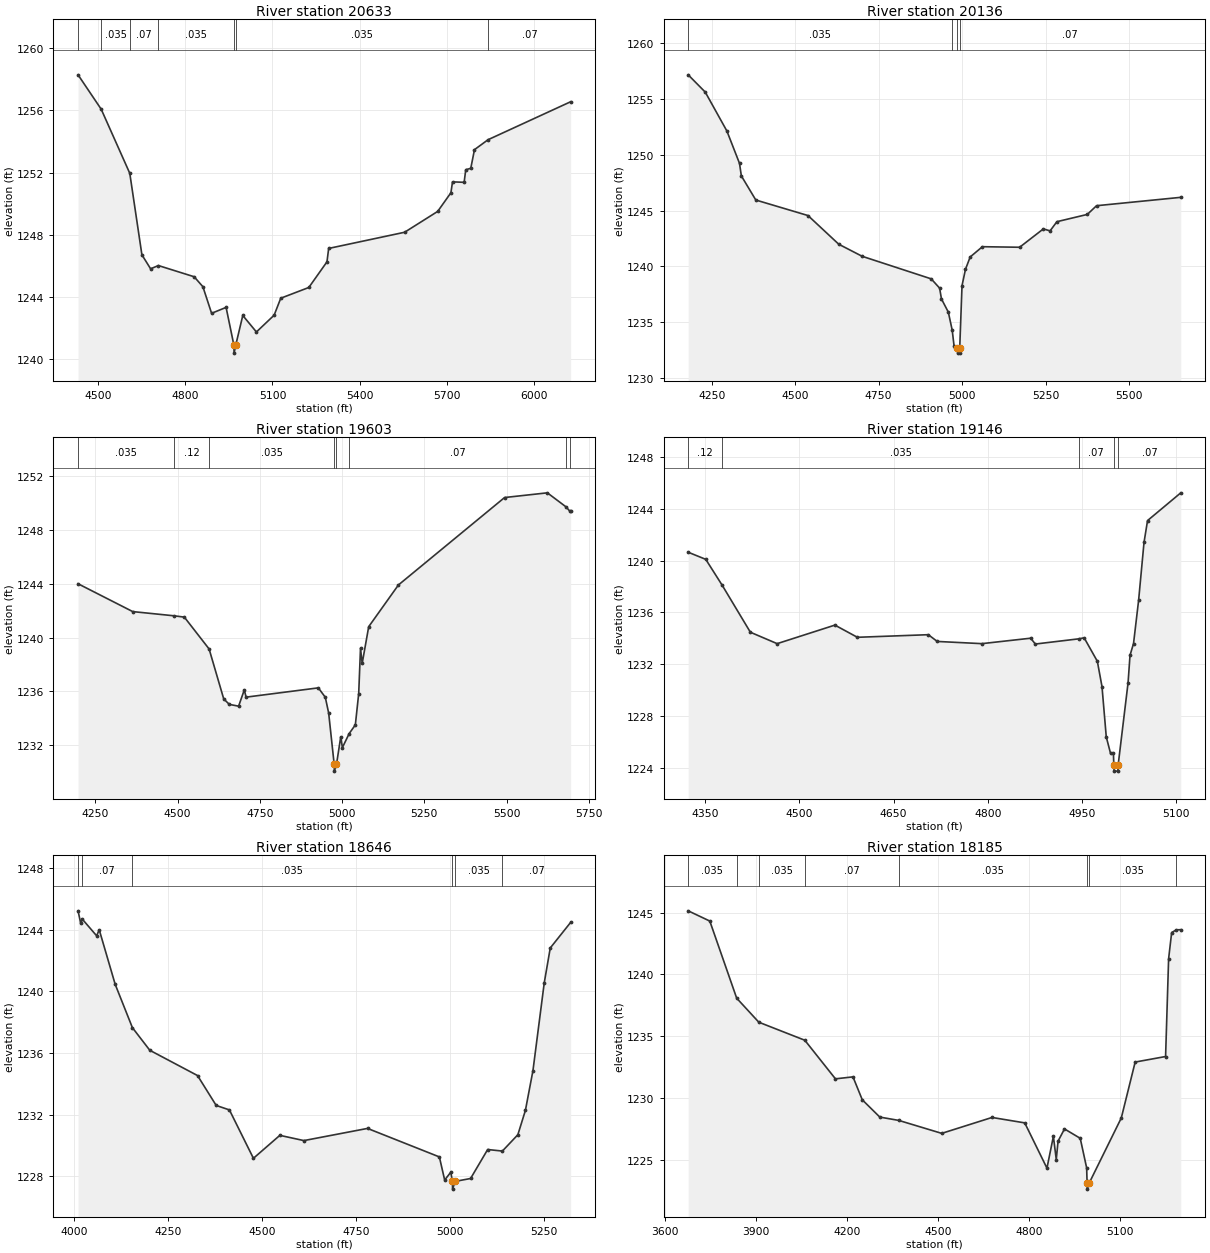
Type RM Length L Ch R = 1,20633,497,497,497
BEGIN DESCRIPTION:
Cypress Tributary 2 37.0
END DESCRIPTION:
XS GIS Cut Line= 3
      2148324.99     13887475.00      2147755.15     13887454.62
      2147275.00     13888474.99
#Sta/Elev= 30
  4429.8 1258.28  4509.6 1256.07  4608.1 1251.95  4649.9 1246.71  4679.9 1245.81
  4706.7 1246.02  4830.0 1245.30  4860.1 1244.66  4890.1 1242.95  4940.1 1243.33
  4967.1 1240.89  4967.6 1240.39  4973.2 1240.89  4997.6 1242.81  5044.6 1241.75
  5105.7 1242.83  5128.5 1243.92  5225.2 1244.61  5287.8 1246.26  5293.6 1247.12
  5555.4 1248.16  5669.4 1249.50  5715.0 1250.70  5720.5 1251.40  5760.6 1251.37
  5766.1 1252.18  5783.4 1252.27  5796.2 1253.47  5843.1 1254.11  6127.7 1256.55
#Mann=7,-1,0
  4429.8    0.07       0  4509.6   0.035       0  4608.1    0.07       0
  4706.7   0.035       0  4967.1   0.035       0  4973.2   0.035       0
  5843.1    0.07       0
Bank Sta=4967.1,4973.2
Exp/Cntr=0.3,0.1

Type RM Length L Ch R = 1,20136,533,533,533
BEGIN DESCRIPTION:
Cypress Tributary 2 36.0
END DESCRIPTION:
XS GIS Cut Line= 3
      2148324.97     13887274.99      2147500.48     13887089.67
      2146878.62     13887189.63
#Sta/Elev= 30
  4179.7 1257.15  4230.9 1255.60  4295.6 1252.12  4333.4 1249.22  4338.9 1248.10
  4382.2 1245.94  4538.4 1244.55  4630.6 1241.98  4700.7 1240.90  4907.4 1238.88
  4932.5 1238.05  4938.1 1237.08  4958.6 1235.90  4970.2 1234.29  4975.8 1232.87
  4985.9 1232.73  4986.4 1232.23  4992.3 1232.23  4992.8 1232.73  4999.6 1238.27
  5009.9 1239.73  5024.0 1240.84  5060.7 1241.76  5172.1 1241.71  5243.0 1243.35
  5263.3 1243.18  5283.7 1244.00  5374.7 1244.65  5402.4 1245.43  5654.6 1246.18
#Mann=4,-1,0
  4179.7   0.035       0  4970.2    0.07       0  4985.9    0.05       0
  4992.8    0.07       0
Bank Sta=4985.9,4992.8
Exp/Cntr=0.3,0.1

Type RM Length L Ch R = 1,19603,457,457,457
BEGIN DESCRIPTION:
Cypress Tributary 2 35.0
END DESCRIPTION:
XS GIS Cut Line= 4
      2148155.31     13886926.39      2147484.39     13886609.68
      2147142.66     13886551.34      2146734.25     13886551.34
#Sta/Elev= 30
  4197.7 1244.00  4363.9 1241.93  4488.5 1241.62  4520.7 1241.52  4596.0 1239.15
  4640.4 1235.44  4657.4 1235.03  4685.7 1234.90  4702.9 1236.11  4708.4 1235.57
  4927.9 1236.26  4949.1 1235.56  4959.3 1234.39  4976.1 1230.57  4976.6 1230.07
  4983.1 1230.57  4996.0 1232.62  5001.0 1231.82  5021.6 1232.86  5040.4 1233.51
  5050.6 1235.84  5056.1 1239.21  5061.2 1238.08  5081.0 1240.81  5171.3 1243.91
  5493.9 1250.41  5623.9 1250.76  5680.4 1249.72  5692.8 1249.38  5694.7 1249.38
#Mann=8,-1,0
  4197.7   0.035       0  4488.5    0.12       0  4596.0   0.035       0
  4976.1   0.035       0  4983.1   0.035       0  5021.6    0.07       0
  5680.4    0.12       0  5692.8    0.07       0
Bank Sta=4976.1,4983.1
Exp/Cntr=0.3,0.1

Type RM Length L Ch R = 1,19146,500,500,500
BEGIN DESCRIPTION:
Cypress Tributary 2 34.0
END DESCRIPTION:
XS GIS Cut Line= 3
      2147875.00     13886674.99      2147420.78     13886173.25
      2147325.04     13886125.02
#Sta/Elev= 30
  4323.2 1240.64  4351.2 1240.09  4377.5 1238.08  4422.2 1234.47  4464.8 1233.59
  4556.7 1235.02  4592.5 1234.08  4705.4 1234.28  4719.6 1233.76  4790.6 1233.59
  4868.3 1234.01  4875.7 1233.56  4944.6 1233.96  4953.4 1234.04  4974.4 1232.23
  4981.8 1230.28  4988.6 1226.40  4995.4 1225.13  5000.0 1225.13  5000.6 1224.26
  5001.1 1223.76  5007.1 1223.76  5007.6 1224.26  5023.3 1230.57  5026.4 1232.69
  5032.0 1233.60  5040.1 1236.94  5048.7 1241.40  5054.3 1243.08  5107.2 1245.22
#Mann=5,-1,0
  4323.2    0.12       0  4377.5   0.035       0  4944.6    0.07       0
  5000.6    0.05       0  5007.6    0.07       0
Bank Sta=5000.6,5007.6
Exp/Cntr=0.3,0.1

Type RM Length L Ch R = 1,18646,461,461,461
BEGIN DESCRIPTION:
Cypress Tributary 2 33.0
END DESCRIPTION:
XS GIS Cut Line= 3
      2148424.98     13886524.98      2147745.60     13885805.16
      2147425.01     13885775.00
#Sta/Elev= 30
  4010.2 1245.22  4017.3 1244.41  4021.2 1244.69  4059.7 1243.60  4066.6 1243.99
  4109.1 1240.45  4154.9 1237.64  4201.3 1236.17  4328.4 1234.53  4378.1 1232.59
  4413.3 1232.30  4477.2 1229.16  4547.6 1230.65  4611.6 1230.31  4781.1 1231.10
  4972.4 1229.25  4986.5 1227.75  5002.8 1228.26  5007.1 1227.66  5007.6 1227.16
  5014.1 1227.66  5055.5 1227.85  5101.0 1229.73  5140.2 1229.63  5181.4 1230.69
  5201.5 1232.27  5221.6 1234.85  5251.7 1240.55  5267.7 1242.81  5322.0 1244.47
#Mann=6,-1,0
  4010.2   0.035       0  4021.2    0.07       0  4154.9   0.035       0
  5007.1   0.035       0  5014.1   0.035       0  5140.2    0.07       0
Bank Sta=5007.1,5014.1
Exp/Cntr=0.3,0.1

Type RM Length L Ch R = 1,18185,500,500,500
BEGIN DESCRIPTION:
Cypress Tributary 2 32.0
END DESCRIPTION:
XS GIS Cut Line= 3
      2148524.98     13886524.97      2147824.84     13885402.07
      2147525.02     13885425.00
#Sta/Elev= 30
  3676.7 1245.16  3748.0 1244.33  3836.6 1238.08  3909.6 1236.13  4061.2 1234.67
  4162.2 1231.54  4220.0 1231.70  4250.7 1229.84  4308.5 1228.44  4371.1 1228.17
  4512.6 1227.12  4678.4 1228.41  4786.3 1227.97  4859.5 1224.30  4880.7 1226.88
  4890.2 1225.00  4896.1 1226.49  4917.3 1227.48  4969.2 1226.72  4990.4 1224.32
  4991.8 1223.10  4992.3 1222.60  4998.9 1223.10  5104.6 1228.37  5150.3 1232.90
  5250.6 1233.35  5260.6 1241.28  5270.6 1243.40  5286.1 1243.62  5300.7 1243.63
#Mann=8,-1,0
  3676.7   0.035       0  3836.6    0.07       0  3909.6   0.035       0
  4061.2    0.07       0  4371.1   0.035       0  4991.8   0.035       0
  4998.9   0.035       0  5286.1    0.07       0
Bank Sta=4991.8,4998.9
Exp/Cntr=0.3,0.1

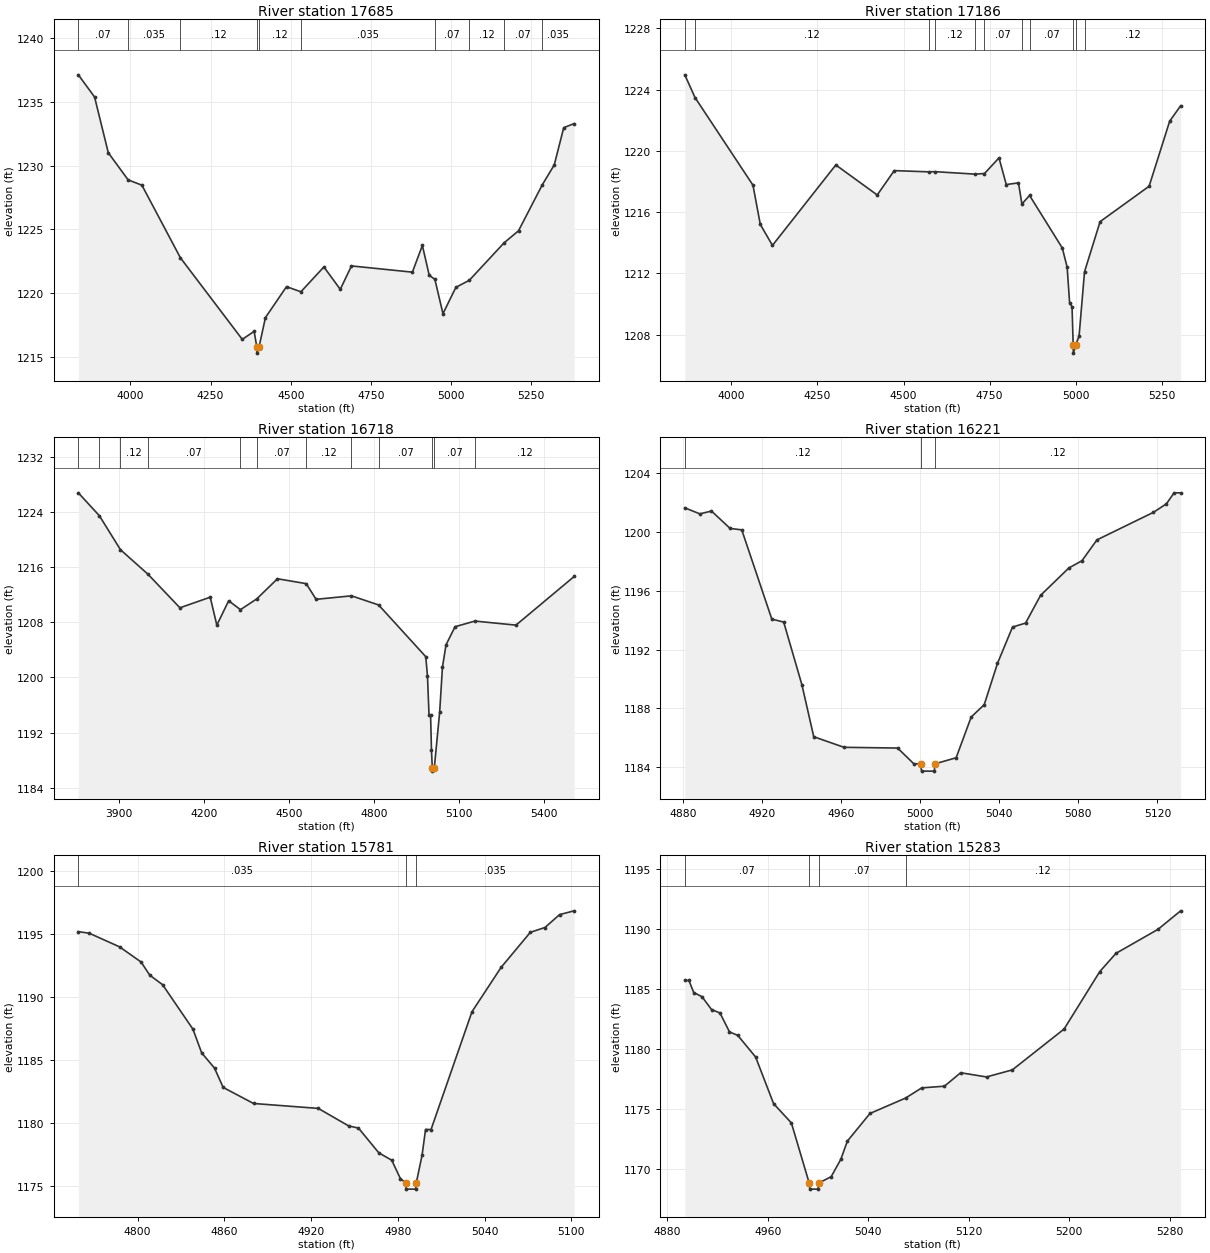
Type RM Length L Ch R = 1,17685,499,499,499
BEGIN DESCRIPTION:
Cypress Tributary 2 31.0
END DESCRIPTION:
XS GIS Cut Line= 3
      2148975.03     13885575.02      2147978.76     13884976.56
      2147625.04     13885124.98
#Sta/Elev= 30
  3837.8 1237.14  3888.4 1235.40  3931.2 1231.02  3993.0 1228.89  4036.0 1228.47
  4156.0 1222.77  4348.9 1216.36  4385.8 1216.99  4394.2 1215.78  4394.7 1215.28
  4401.3 1215.78  4421.1 1218.07  4486.8 1220.50  4531.7 1220.10  4603.4 1222.05
  4654.4 1220.29  4689.4 1222.13  4879.3 1221.64  4910.4 1223.74  4931.8 1221.39
  4949.3 1221.08  4974.6 1218.38  5014.9 1220.45  5056.7 1221.00  5165.0 1223.94
  5210.1 1224.89  5284.2 1228.50  5321.5 1230.06  5351.1 1232.99  5383.6 1233.31
#Mann=10,-1,0
  3837.8    0.07       0  3993.0   0.035       0  4156.0    0.12       0
  4394.2    0.05       0  4401.3    0.12       0  4531.7   0.035       0
  4949.3    0.07       0  5056.7    0.12       0  5165.0    0.07       0
  5284.2   0.035       0
Bank Sta=4394.2,4401.3
Exp/Cntr=0.3,0.1

Type RM Length L Ch R = 1,17186,468,468,468
BEGIN DESCRIPTION:
Cypress Tributary 2 30.0
END DESCRIPTION:
XS GIS Cut Line= 3
      2148824.98     13885324.98      2148024.56     13884520.27
      2147725.02     13884575.00
#Sta/Elev= 30
  3865.0 1224.96  3894.6 1223.48  4062.9 1217.76  4084.2 1215.20  4119.5 1213.83
  4303.4 1219.08  4423.6 1217.12  4473.1 1218.71  4572.6 1218.63  4592.0 1218.64
  4708.1 1218.48  4735.1 1218.52  4777.2 1219.54  4798.3 1217.80  4833.7 1217.91
  4843.7 1216.53  4865.9 1217.09  4961.0 1213.66  4975.1 1212.40  4982.2 1210.08
  4989.3 1209.83  4992.6 1207.30  4993.1 1206.80  4999.7 1207.30  5009.7 1207.92
  5025.5 1212.11  5070.7 1215.38  5213.0 1217.69  5272.8 1221.94  5304.5 1222.94
#Mann=11,-1,0
  3865.0    0.07       0  3894.6    0.12       0  4572.6   0.035       0
  4592.0    0.12       0  4708.1   0.035       0  4735.1    0.07       0
  4843.7   0.035       0  4865.9    0.07       0  4992.6    0.05       0
  4999.7    0.07       0  5025.5    0.12       0
Bank Sta=4992.6,4999.7
Exp/Cntr=0.3,0.1

Type RM Length L Ch R = 1,16718,497,497,497
BEGIN DESCRIPTION:
Cypress Tributary 2 29.0
END DESCRIPTION:
XS GIS Cut Line= 4
      2148996.04     13885184.90      2148500.98     13884484.93
      2148273.57     13884171.11      2147821.89     13883939.94
#Sta/Elev= 30
  3755.1 1226.84  3829.5 1223.51  3904.1 1218.57  4000.7 1215.03  4114.1 1210.13
  4221.2 1211.67  4244.6 1207.61  4286.4 1211.15  4328.1 1209.86  4385.6 1211.42
  4458.8 1214.35  4560.4 1213.64  4595.4 1211.36  4720.5 1211.87  4816.4 1210.54
  4982.9 1203.03  4989.0 1200.23  4994.5 1194.50  5000.0 1194.50  5003.2 1189.39
  5006.0 1186.89  5006.5 1186.39  5013.2 1186.89  5032.1 1194.97  5042.0 1201.52
  5054.6 1204.75  5086.4 1207.38  5156.7 1208.20  5301.7 1207.61  5507.4 1214.68
#Mann=12,-1,0
  3755.1    0.07       0  3829.5   0.035       0  3904.1    0.12       0
  4000.7    0.07       0  4328.1    0.12       0  4385.6    0.07       0
  4560.4    0.12       0  4720.5   0.035       0  4816.4    0.07       0
  5006.0    0.05       0  5013.2    0.07       0  5156.7    0.12       0
Bank Sta=5006,5013.2
Exp/Cntr=0.3,0.1

Type RM Length L Ch R = 1,16221,440,440,440
BEGIN DESCRIPTION:
Cypress Tributary 2 28.0
END DESCRIPTION:
XS GIS Cut Line= 3
      2148475.00     13883775.00      2148374.55     13883711.18
      2148274.98     13883624.98
#Sta/Elev= 30
  4881.0 1201.65  4888.6 1201.24  4894.5 1201.43  4903.9 1200.25  4909.8 1200.15
  4925.0 1194.08  4931.0 1193.88  4940.2 1189.62  4946.2 1186.08  4961.5 1185.36
  4988.6 1185.31  4996.8 1184.24  5000.2 1184.24  5000.7 1183.74  5007.1 1183.74
  5007.6 1184.24  5018.2 1184.65  5025.8 1187.42  5032.4 1188.26  5039.1 1191.07
  5046.7 1193.54  5053.3 1193.81  5060.9 1195.70  5075.2 1197.56  5081.8 1198.05
  5089.4 1199.47  5117.9 1201.34  5124.5 1201.92  5128.4 1202.67  5131.7 1202.67
#Mann=3,-1,0
  4881.0    0.12       0  5000.2    0.05       0  5007.6    0.12       0
Bank Sta=5000.2,5007.6
Exp/Cntr=0.3,0.1

Type RM Length L Ch R = 1,15781,498,498,498
BEGIN DESCRIPTION:
Cypress Tributary 2 27.0
END DESCRIPTION:
XS GIS Cut Line= 3
      2148775.02     13883475.01      2148576.03     13883339.06
      2148475.00     13883325.00
#Sta/Elev= 30
  4759.0 1195.17  4766.5 1195.05  4787.5 1193.97  4802.4 1192.77  4808.4 1191.73
  4817.3 1190.97  4838.3 1187.45  4844.3 1185.58  4853.2 1184.37  4859.2 1182.84
  4880.2 1181.57  4925.0 1181.18  4945.9 1179.80  4952.8 1179.62  4966.9 1177.66
  4975.8 1177.08  4981.8 1175.62  4985.4 1175.29  4985.9 1174.79  4992.3 1174.79
  4992.8 1175.29  4996.8 1177.48  4999.2 1179.51  5003.0 1179.51  5031.3 1188.83
  5051.5 1192.35  5071.7 1195.12  5081.8 1195.50  5091.9 1196.52  5102.0 1196.82
#Mann=3,-1,0
  4759.0   0.035       0  4985.4   0.035       0  4992.8   0.035       0
Bank Sta=4985.4,4992.8
Exp/Cntr=0.3,0.1

Type RM Length L Ch R = 1,15283,481,481,481
BEGIN DESCRIPTION:
Cypress Tributary 2 26.0
END DESCRIPTION:
XS GIS Cut Line= 3
      2149024.98     13883124.97      2148955.07     13883045.02
      2148674.99     13882975.00
#Sta/Elev= 30
  4893.8 1185.68  4897.1 1185.68  4900.9 1184.68  4907.5 1184.33  4915.1 1183.26
  4921.8 1182.98  4929.4 1181.40  4936.0 1181.11  4950.2 1179.31  4964.5 1175.43
  4978.7 1173.82  4992.9 1168.81  4993.4 1168.31  4999.9 1168.31  5000.4 1168.81
  5010.4 1169.35  5018.1 1170.80  5023.3 1172.31  5041.3 1174.61  5069.6 1175.89
  5082.5 1176.74  5100.6 1176.88  5113.5 1178.00  5134.1 1177.65  5154.7 1178.24
  5195.9 1181.64  5224.3 1186.42  5237.2 1187.94  5270.7 1189.94  5288.7 1191.48
#Mann=4,-1,0
  4893.8    0.07       0  4992.9    0.05       0  5000.4    0.07       0
  5069.6    0.12       0
Bank Sta=4992.9,5000.4
Exp/Cntr=0.3,0.1

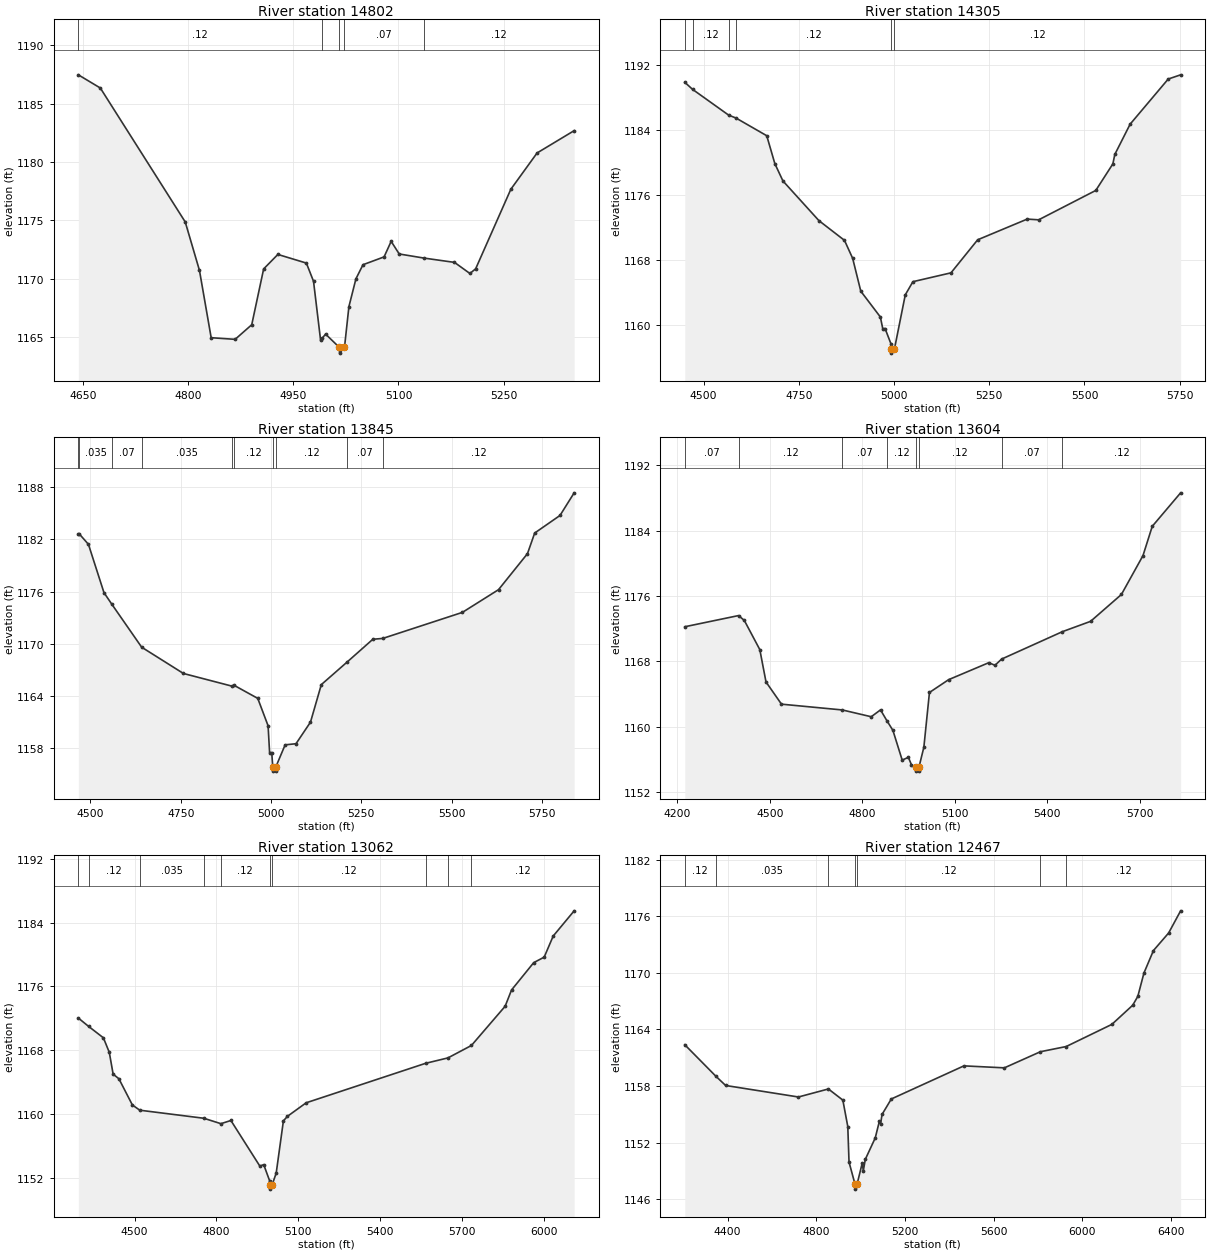
Type RM Length L Ch R = 1,14802,497,497,497
BEGIN DESCRIPTION:
Cypress Tributary 2 25.0
END DESCRIPTION:
XS GIS Cut Line= 3
      2149624.99     13882775.00      2149274.13     13882709.64
      2148925.04     13882675.00
#Sta/Elev= 30
  4643.1 1187.47  4674.5 1186.34  4795.7 1174.87  4816.0 1170.72  4832.7 1164.96
  4866.9 1164.82  4890.6 1166.07  4907.6 1170.85  4927.9 1172.09  4968.6 1171.35
  4978.8 1169.79  4988.9 1164.74  4991.4 1164.93  4996.0 1165.27  5015.5 1164.14
  5016.0 1163.64  5023.0 1164.14  5029.3 1167.62  5039.3 1170.00  5049.4 1171.21
  5079.5 1171.88  5089.6 1173.21  5101.1 1172.13  5136.3 1171.78  5180.0 1171.41
  5202.0 1170.46  5210.2 1170.86  5260.4 1177.67  5297.9 1180.78  5350.8 1182.69
#Mann=5,-1,0
  4643.1    0.12       0  4991.4    0.07       0  5015.5    0.05       0
  5023.0    0.07       0  5136.3    0.12       0
Bank Sta=5015.5,5023
Exp/Cntr=0.3,0.1

Type RM Length L Ch R = 1,14305,460,460,460
BEGIN DESCRIPTION:
Cypress Tributary 2 24.0
END DESCRIPTION:
XS GIS Cut Line= 3
      2149891.17     13882554.45      2149424.55     13882264.81
      2148672.40     13882245.41
#Sta/Elev= 30
  4450.8 1189.91  4471.2 1189.04  4566.1 1185.86  4585.1 1185.51  4665.9 1183.33
  4687.2 1179.89  4708.4 1177.76  4802.9 1172.87  4870.0 1170.44  4891.5 1168.22
  4912.8 1164.18  4964.2 1161.00  4970.6 1159.53  4976.5 1159.58  4991.9 1157.71
  4992.5 1157.05  4993.0 1156.55  5001.1 1157.05  5029.6 1163.73  5049.6 1165.35
  5149.6 1166.44  5219.6 1170.51  5349.7 1173.06  5379.7 1172.97  5529.7 1176.59
  5574.5 1179.86  5579.7 1181.03  5619.8 1184.75  5719.8 1190.31  5752.4 1190.83
#Mann=6,-1,0
  4450.8    0.07       0  4471.2    0.12       0  4566.1    0.07       0
  4585.1    0.12       0  4992.5    0.05       0  5001.1    0.12       0
Bank Sta=4992.5,5001.1
Exp/Cntr=0.3,0.1

Type RM Length L Ch R = 1,13845,241,241,241
BEGIN DESCRIPTION:
Cypress Tributary 2 23.0
END DESCRIPTION:
XS GIS Cut Line= 3
      2149925.00     13882175.00      2149514.19     13881834.63
      2148675.86     13881880.82
#Sta/Elev= 30
  4466.5 1182.61  4469.3 1182.61  4494.5 1181.42  4537.5 1175.87  4558.9 1174.56
  4641.9 1169.60  4757.6 1166.58  4891.6 1165.13  4897.9 1165.22  4963.4 1163.72
  4992.0 1160.57  4996.2 1157.48  5002.1 1157.48  5004.9 1155.86  5005.4 1155.36
  5013.1 1155.36  5013.6 1155.86  5039.2 1158.38  5069.3 1158.51  5109.4 1160.99
  5139.4 1165.30  5210.7 1167.89  5282.0 1170.51  5309.6 1170.61  5530.0 1173.60
  5630.1 1176.21  5710.3 1180.35  5730.3 1182.72  5800.4 1184.74  5839.6 1187.34
#Mann=10,-1,0
  4466.5    0.07       0  4469.3   0.035       0  4558.9    0.07       0
  4641.9   0.035       0  4891.6    0.07       0  4897.9    0.12       0
  5004.9    0.05       0  5013.6    0.12       0  5210.7    0.07       0
  5309.6    0.12       0
Bank Sta=5004.9,5013.6
Exp/Cntr=0.3,0.1

Type RM Length L Ch R = 1,13604,542,542,542
BEGIN DESCRIPTION:
Cypress Tributary 2 22.0
END DESCRIPTION:
XS GIS Cut Line= 3
      2150247.40     13881679.61      2149297.22     13881596.26
      2148642.97     13881608.76
#Sta/Elev= 30
  4223.9 1172.22  4398.3 1173.59  4417.0 1172.99  4467.2 1169.42  4487.3 1165.46
  4537.5 1162.74  4735.0 1162.03  4828.6 1161.20  4858.7 1162.04  4879.3 1160.72
  4898.9 1159.53  4929.0 1155.89  4949.1 1156.23  4959.1 1155.31  4974.8 1155.04
  4975.3 1154.54  4983.0 1154.54  4983.5 1155.04  4999.3 1157.47  5017.4 1164.17
  5079.6 1165.74  5210.0 1167.82  5230.0 1167.50  5251.4 1168.26  5448.8 1171.62
  5540.0 1172.88  5640.0 1176.17  5710.0 1180.93  5740.1 1184.52  5832.1 1188.62
#Mann=8,-1,0
  4223.9    0.07       0  4398.3    0.12       0  4735.0    0.07       0
  4879.3    0.12       0  4974.8    0.05       0  4983.5    0.12       0
  5251.4    0.07       0  5448.8    0.12       0
Bank Sta=4974.8,4983.5
Exp/Cntr=0.3,0.1

Type RM Length L Ch R = 1,13062,595,595,595
BEGIN DESCRIPTION:
Cypress Tributary 2 21.0
END DESCRIPTION:
XS GIS Cut Line= 4
      2150150.00     13881600.00      2149633.43     13881119.06
      2149332.47     13881192.48      2148565.22     13881421.57
#Sta/Elev= 30
  4294.2 1172.03  4331.6 1170.99  4386.0 1169.55  4407.6 1167.73  4421.7 1164.99
  4442.7 1164.42  4492.3 1161.12  4519.4 1160.47  4753.8 1159.46  4816.5 1158.78
  4853.1 1159.18  4959.1 1153.46  4973.3 1153.64  4994.8 1151.63  4994.9 1151.07
  4995.4 1150.57  5003.7 1151.07  5019.0 1152.57  5045.4 1159.13  5060.1 1159.70
  5128.8 1161.40  5566.1 1166.35  5648.1 1167.03  5734.2 1168.59  5857.7 1173.51
  5881.1 1175.55  5962.3 1178.98  6000.7 1179.67  6033.8 1182.32  6110.5 1185.48
#Mann=10,-1,0
  4294.2    0.07       0  4331.6    0.12       0  4519.4   0.035       0
  4753.8    0.07       0  4816.5    0.12       0  4994.9    0.05       0
  5003.7    0.12       0  5566.1   0.035       0  5648.1    0.07       0
  5734.2    0.12       0
Bank Sta=4994.9,5003.7
Exp/Cntr=0.3,0.1

Type RM Length L Ch R = 1,12467,710,710,710
BEGIN DESCRIPTION:
Cypress Tributary 2 20.0
END DESCRIPTION:
XS GIS Cut Line= 4
      2150233.46     13881314.18      2149874.64     13880606.67
      2149299.28     13880838.68      2148588.33     13881254.29
#Sta/Elev= 30
  4206.7 1162.37  4346.5 1159.04  4391.0 1158.05  4719.4 1156.83  4854.6 1157.68
  4919.8 1156.50  4942.1 1153.70  4947.7 1149.93  4975.0 1147.56  4975.5 1147.06
  4983.8 1147.56  5007.0 1149.79  5012.3 1149.02  5021.2 1150.22  5066.0 1152.49
  5084.8 1154.27  5090.2 1153.99  5096.7 1154.98  5138.5 1156.62  5466.1 1160.13
  5648.6 1159.92  5811.3 1161.63  5927.5 1162.18  6133.7 1164.53  6227.7 1166.56
  6250.8 1167.50  6278.3 1169.97  6321.3 1172.36  6389.8 1174.22  6443.9 1176.57
#Mann=7,-1,0
  4206.7    0.12       0  4346.5   0.035       0  4854.6    0.12       0
  4975.0    0.05       0  4983.8    0.12       0  5811.3    0.07       0
  5927.5    0.12       0
Bank Sta=4975,4983.8
Exp/Cntr=0.3,0.1

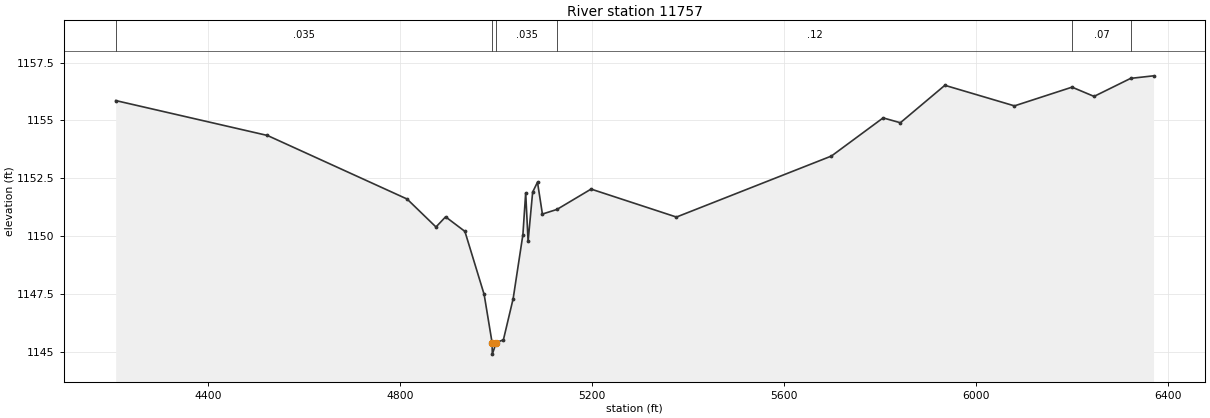
Type RM Length L Ch R = 1,11757,634,634,634
BEGIN DESCRIPTION:
Cypress Tributary 2 19.0
END DESCRIPTION:
XS GIS Cut Line= 4
      2150250.00     13880800.03      2150189.33     13880009.53
      2149853.83     13880067.38      2149006.23     13880648.92
#Sta/Elev= 30
  4208.1 1155.86  4524.1 1154.35  4814.9 1151.60  4875.1 1150.39  4895.1 1150.83
  4935.3 1150.20  4975.4 1147.47  4991.9 1145.39  4992.4 1144.89  5000.7 1145.39
  5015.5 1145.51  5035.8 1147.29  5056.1 1150.06  5061.9 1151.87  5066.9 1149.77
  5076.4 1151.90  5086.5 1152.33  5096.7 1150.95  5127.0 1151.15  5198.1 1152.03
  5375.8 1150.82  5698.6 1153.46  5806.2 1155.11  5842.1 1154.90  5934.8 1156.52
  6079.7 1155.63  6199.6 1156.44  6245.5 1156.04  6321.7 1156.82  6369.3 1156.93
#Mann=6,-1,0
  4208.1   0.035       0  4991.9   0.035       0  5000.7   0.035       0
  5127.0    0.12       0  6199.6    0.07       0  6321.7   0.035       0
Bank Sta=4991.9,5000.7
Exp/Cntr=0.3,0.1