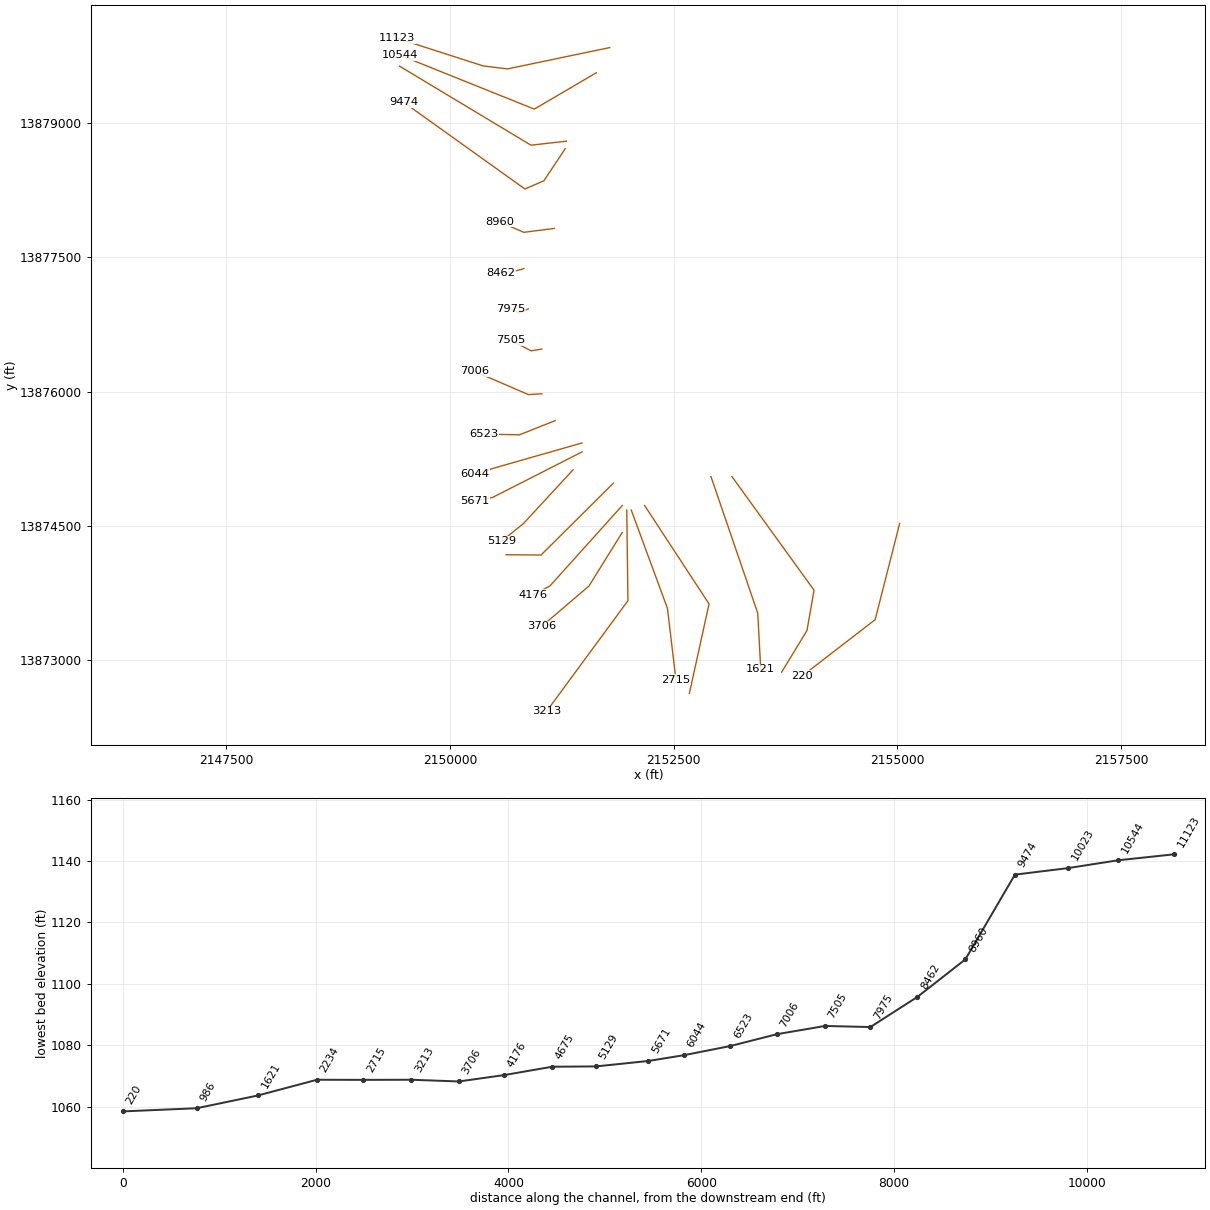
HEC-RAS study Cypress Tributary 2.prj: Cypress Tributary 2 Base Level Engineering

--- Cypress Tributary 2.g01 (geometry) --- (continued)

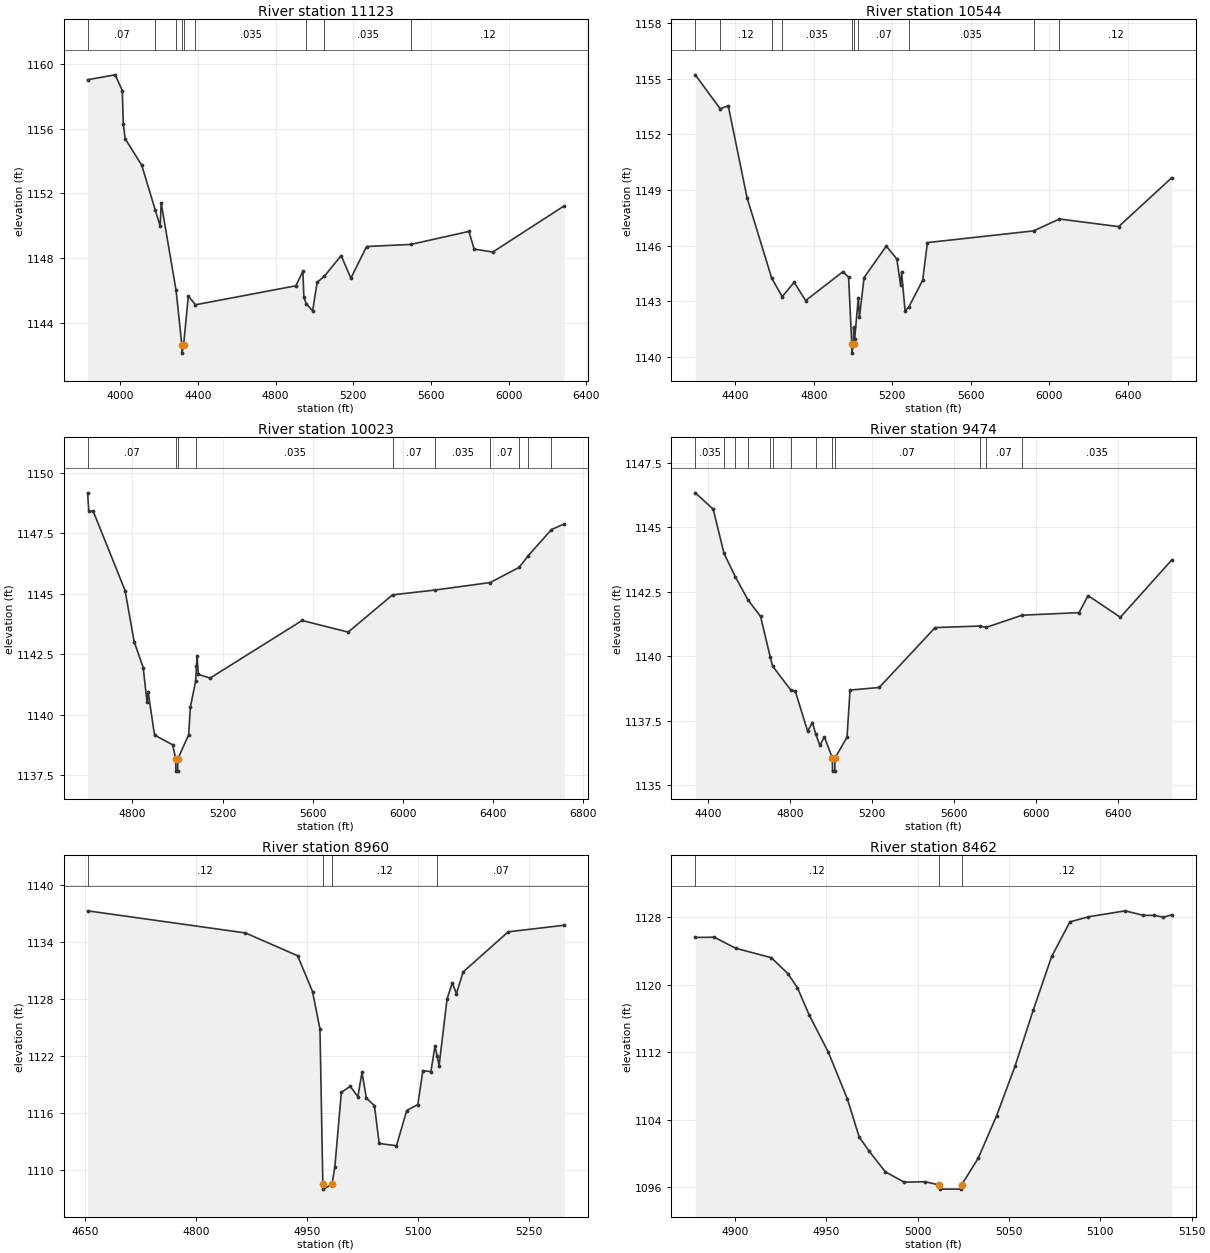
Type RM Length L Ch R = 1,11123,579,579,579
BEGIN DESCRIPTION:
Cypress Tributary 2 18.0
END DESCRIPTION:
XS GIS Cut Line= 4
      2151784.25     13879846.64      2150641.60     13879608.01
      2150369.68     13879641.43      2149407.02     13879951.08
#Sta/Elev= 30
  3832.7 1159.01  3974.9 1159.31  4011.3 1158.33  4016.4 1156.29  4026.0 1155.37
  4111.3 1153.74  4180.9 1150.98  4206.2 1149.98  4211.3 1151.42  4288.0 1146.03
  4317.8 1142.66  4318.3 1142.16  4326.7 1142.66  4351.1 1145.68  4388.0 1145.14
  4904.6 1146.31  4940.8 1147.21  4945.9 1145.59  4958.3 1145.20  4990.8 1144.76
  5014.0 1146.52  5050.6 1146.89  5137.6 1148.17  5188.0 1146.78  5268.6 1148.73
  5497.0 1148.86  5795.3 1149.66  5822.2 1148.57  5918.4 1148.39  6285.2 1151.23
#Mann=9,-1,0
  3832.7    0.07       0  4180.9    0.12       0  4288.0    0.07       0
  4317.8    0.05       0  4326.7    0.07       0  4388.0   0.035       0
  4958.3    0.07       0  5050.6   0.035       0  5497.0    0.12       0
Bank Sta=4317.8,4326.7
Exp/Cntr=0.3,0.1

Type RM Length L Ch R = 1,10544,521,521,521
BEGIN DESCRIPTION:
Cypress Tributary 2 17.2
END DESCRIPTION:
XS GIS Cut Line= 3
      2151634.66     13879565.18      2150941.57     13879158.29
      2149433.87     13879763.94
#Sta/Elev= 30
  4196.3 1155.20  4323.5 1153.37  4364.3 1153.54  4460.1 1148.59  4585.8 1144.26
  4639.3 1143.26  4700.3 1144.03  4759.0 1143.05  4949.6 1144.61  4977.8 1144.30
  4993.9 1140.72  4994.4 1140.22  5002.8 1140.72  5003.1 1141.60  5008.5 1140.96
  5027.3 1143.21  5032.7 1142.14  5056.9 1144.29  5169.8 1145.98  5223.6 1145.29
  5242.4 1143.91  5247.8 1144.58  5265.7 1142.49  5283.5 1142.68  5355.3 1144.14
  5379.5 1146.17  5920.3 1146.80  6052.3 1147.44  6354.2 1147.03  6624.8 1149.66
#Mann=10,-1,0
  4196.3    0.07       0  4323.5    0.12       0  4585.8    0.07       0
  4639.3   0.035       0  4993.9   0.035       0  5002.8   0.035       0
  5027.3    0.07       0  5283.5   0.035       0  5920.3    0.07       0
  6052.3    0.12       0
Bank Sta=4993.9,5002.8
Exp/Cntr=0.3,0.1

Type RM Length L Ch R = 1,10023,549,549,549
BEGIN DESCRIPTION:
Cypress Tributary 2 17.1
END DESCRIPTION:
XS GIS Cut Line= 3
      2151300.03     13878800.00      2150904.18     13878755.00
      2149434.31     13879639.16
#Sta/Elev= 30
  4601.6 1149.18  4606.7 1148.43  4626.8 1148.41  4767.7 1145.14  4808.0 1143.03
  4848.2 1141.95  4865.3 1140.52  4870.3 1140.93  4898.5 1139.16  4979.0 1138.76
  4992.6 1138.17  4993.1 1137.67  5001.0 1137.67  5001.5 1138.17  5050.0 1139.18
  5057.4 1140.32  5080.7 1141.38  5084.5 1142.03  5086.9 1142.44  5092.8 1141.67
  5145.2 1141.52  5553.1 1143.90  5757.6 1143.42  5954.2 1144.96  6143.0 1145.16
  6387.6 1145.47  6516.5 1146.10  6556.2 1146.58  6659.0 1147.66  6715.3 1147.89
#Mann=10,-1,0
  4601.6    0.07       0  4992.6    0.05       0  5001.5    0.07       0
  5084.5   0.035       0  5954.2    0.07       0  6143.0   0.035       0
  6387.6    0.07       0  6516.5    0.12       0  6556.2    0.07       0
  6659.0    0.12       0
Bank Sta=4992.6,5001.5
Exp/Cntr=0.3,0.1

Type RM Length L Ch R = 1,9474,514,514,514
BEGIN DESCRIPTION:
Cypress Tributary 2 17.05
END DESCRIPTION:
XS GIS Cut Line= 4
      2151286.58     13878715.31      2151048.50     13878356.96
      2150836.48     13878265.10      2149482.83     13879233.70
#Sta/Elev= 30
  4338.7 1146.33  4426.0 1145.70  4479.2 1143.98  4534.7 1143.07  4595.6 1142.19
  4657.5 1141.54  4705.0 1139.96  4716.1 1139.62  4804.9 1138.69  4827.2 1138.64
  4887.1 1137.10  4910.6 1137.43  4926.9 1136.98  4947.1 1136.55  4968.9 1136.88
  5008.2 1136.05  5008.7 1135.55  5020.0 1135.55  5020.5 1136.05  5079.5 1136.87
  5094.2 1138.69  5236.7 1138.79  5509.4 1141.11  5726.3 1141.17  5759.2 1141.12
  5934.1 1141.59  6212.2 1141.69  6256.0 1142.35  6413.7 1141.51  6664.5 1143.73
#Mann=13,-1,0
  4338.7   0.035       0  4479.2    0.07       0  4534.7    0.12       0
  4595.6    0.07       0  4705.0    0.12       0  4716.1    0.07       0
  4804.9    0.12       0  4926.9    0.07       0  5008.2    0.05       0
  5020.5    0.07       0  5726.3   0.035       0  5759.2    0.07       0
  5934.1   0.035       0
Bank Sta=5008.2,5020.5
Exp/Cntr=0.3,0.1

Type RM Length L Ch R = 1,8960,498,498,498
BEGIN DESCRIPTION:
Cypress Tributary 2 17.0
END DESCRIPTION:
XS GIS Cut Line= 3
      2151166.91     13877824.05      2150822.65     13877780.52
      2150549.98     13877900.01
#Sta/Elev= 30
  4653.0 1137.29  4866.6 1134.96  4937.2 1132.56  4957.3 1128.79  4967.4 1124.84
  4971.3 1108.48  4971.8 1107.98  4983.6 1108.48  4987.5 1110.30  4996.3 1118.16
  5008.3 1118.81  5018.7 1117.72  5024.2 1120.27  5030.2 1117.57  5041.1 1116.78
  5047.5 1112.79  5070.9 1112.55  5084.8 1116.26  5099.8 1116.89  5106.6 1120.45
  5117.5 1120.36  5123.1 1123.06  5125.9 1122.01  5128.6 1121.00  5139.4 1128.04
  5146.5 1129.71  5152.0 1128.57  5161.2 1130.86  5222.1 1135.08  5297.7 1135.77
#Mann=4,-1,0
  4653.0    0.12       0  4971.3    0.05       0  4983.6    0.12       0
  5125.9    0.07       0
Bank Sta=4971.3,4983.6
Exp/Cntr=0.3,0.1

Type RM Length L Ch R = 1,8462,487,487,487
BEGIN DESCRIPTION:
Cypress Tributary 2 16.0
END DESCRIPTION:
XS GIS Cut Line= 3
      2150825.02     13877375.01      2150708.11     13877341.57
      2150569.56     13877329.21
#Sta/Elev= 30
  4878.4 1125.63  4888.8 1125.66  4900.5 1124.35  4920.0 1123.23  4929.1 1121.33
  4934.3 1119.66  4940.8 1116.40  4951.2 1112.02  4961.6 1106.48  4968.1 1101.94
  4973.3 1100.34  4982.4 1097.81  4992.8 1096.58  5004.1 1096.64  5011.8 1096.26
  5012.3 1095.76  5023.6 1095.76  5024.1 1096.26  5033.2 1099.43  5043.3 1104.49
  5053.3 1110.32  5063.4 1117.06  5073.4 1123.37  5083.4 1127.48  5093.5 1128.08
  5113.6 1128.79  5123.6 1128.25  5129.4 1128.25  5134.5 1128.04  5139.1 1128.31
#Mann=3,-1,0
  4878.4    0.12       0  5011.8    0.05       0  5024.1    0.12       0
Bank Sta=5011.8,5024.1
Exp/Cntr=0.3,0.1

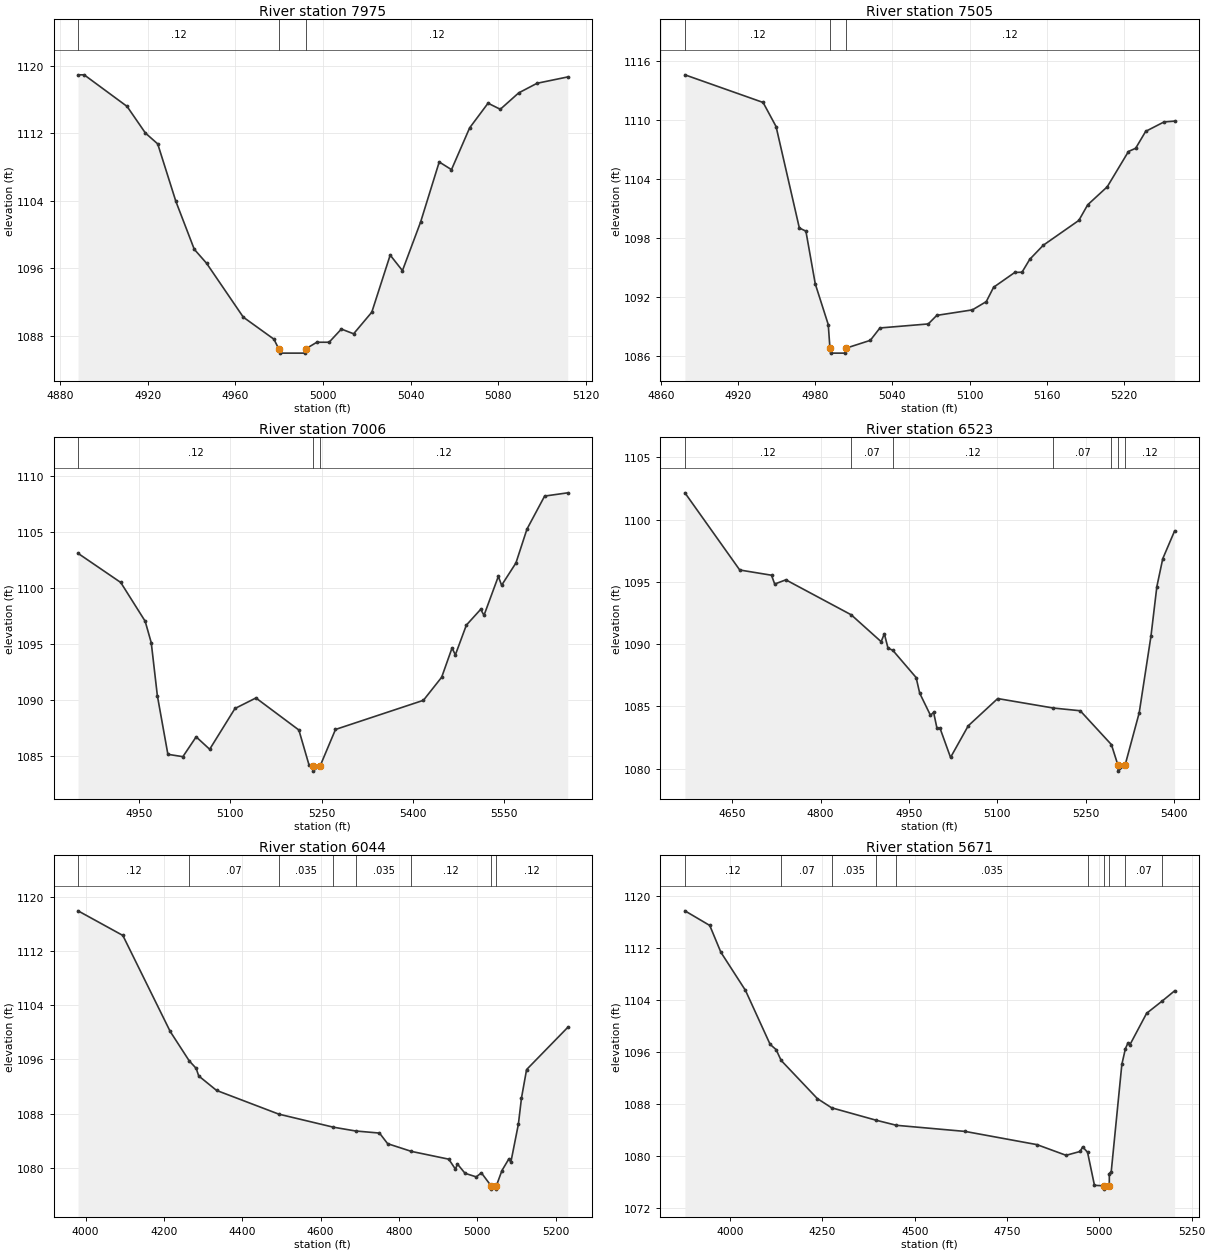
Type RM Length L Ch R = 1,7975,470,470,470
BEGIN DESCRIPTION:
Cypress Tributary 2 15.0
END DESCRIPTION:
XS GIS Cut Line= 3
      2150875.01     13876925.01      2150774.92     13876874.97
      2150674.96     13876925.02
#Sta/Elev= 30
  4888.1 1118.92  4890.9 1118.92  4910.5 1115.18  4918.9 1112.02  4924.5 1110.74
  4932.8 1103.93  4941.2 1098.26  4946.8 1096.61  4963.6 1090.22  4977.6 1087.61
  4979.8 1086.46  4980.3 1085.96  4991.6 1085.96  4992.1 1086.46  4997.2 1087.25
  5002.8 1087.25  5008.4 1088.81  5014.0 1088.25  5022.3 1090.81  5030.7 1097.57
  5036.3 1095.73  5044.6 1101.49  5053.1 1108.60  5058.7 1107.69  5067.0 1112.64
  5075.4 1115.56  5081.0 1114.84  5089.4 1116.78  5097.8 1117.92  5111.8 1118.67
#Mann=3,-1,0
  4888.1    0.12       0  4979.8    0.05       0  4992.1    0.12       0
Bank Sta=4979.8,4992.1
Exp/Cntr=0.3,0.1

Type RM Length L Ch R = 1,7505,499,499,499
BEGIN DESCRIPTION:
Cypress Tributary 2 14.0
END DESCRIPTION:
XS GIS Cut Line= 3
      2151025.00     13876475.00      2150905.23     13876455.17
      2150675.04     13876574.98
#Sta/Elev= 30
  4878.6 1114.62  4939.4 1111.81  4949.5 1109.36  4967.6 1099.04  4972.7 1098.72
  4980.0 1093.35  4990.1 1089.21  4991.4 1086.81  4991.9 1086.31  5003.3 1086.31
  5003.8 1086.81  5022.8 1087.61  5030.3 1088.87  5067.9 1089.28  5074.5 1090.15
  5102.2 1090.71  5113.0 1091.55  5118.7 1093.01  5135.2 1094.52  5140.8 1094.54
  5146.8 1095.85  5157.3 1097.28  5185.0 1099.81  5191.9 1101.40  5207.1 1103.23
  5223.6 1106.82  5229.2 1107.15  5237.0 1108.87  5251.3 1109.83  5259.5 1109.91
#Mann=3,-1,0
  4878.6    0.12       0  4991.4    0.05       0  5003.8    0.12       0
Bank Sta=4991.4,5003.8
Exp/Cntr=0.3,0.1

Type RM Length L Ch R = 1,7006,483,483,483
BEGIN DESCRIPTION:
Cypress Tributary 2 13.0
END DESCRIPTION:
XS GIS Cut Line= 3
      2151024.96     13875975.00      2150875.45     13875965.72
      2150275.03     13876224.98
#Sta/Elev= 30
  4850.2 1103.08  4920.3 1100.48  4960.4 1097.02  4970.4 1095.10  4980.4 1090.38
  4997.7 1085.14  5022.3 1084.93  5044.1 1086.70  5066.3 1085.59  5107.8 1089.23
  5142.2 1090.17  5212.7 1087.31  5229.2 1084.22  5235.5 1084.14  5236.0 1083.64
  5247.9 1084.14  5272.8 1087.36  5417.1 1089.96  5447.1 1092.02  5464.1 1094.63
  5469.6 1094.02  5487.6 1096.67  5511.1 1098.08  5516.6 1097.55  5540.1 1101.02
  5545.5 1100.23  5569.0 1102.22  5587.1 1105.24  5616.1 1108.19  5654.0 1108.48
#Mann=3,-1,0
  4850.2    0.12       0  5235.5    0.05       0  5247.9    0.12       0
Bank Sta=5235.5,5247.9
Exp/Cntr=0.3,0.1

Type RM Length L Ch R = 1,6523,479,479,479
BEGIN DESCRIPTION:
Cypress Tributary 2 12.0
END DESCRIPTION:
XS GIS Cut Line= 3
      2151174.97     13875674.99      2150775.45     13875515.72
      2150374.95     13875525.00
#Sta/Elev= 30
  4569.9 1102.15  4662.9 1095.95  4716.8 1095.53  4722.2 1094.82  4741.1 1095.16
  4852.0 1092.35  4902.8 1090.19  4908.2 1090.83  4914.4 1089.67  4922.5 1089.50
  4962.1 1087.31  4968.2 1086.05  4986.4 1084.28  4991.8 1084.51  4997.5 1083.23
  5002.7 1083.23  5020.5 1080.89  5050.5 1083.43  5100.5 1085.62  5194.8 1084.86
  5240.5 1084.64  5293.4 1081.92  5304.3 1080.29  5304.8 1079.79  5316.7 1080.29
  5340.5 1084.47  5360.5 1090.64  5370.5 1094.62  5380.5 1096.86  5400.6 1099.09
#Mann=7,-1,0
  4569.9    0.12       0  4852.0    0.07       0  4922.5    0.12       0
  5194.8    0.07       0  5293.4    0.12       0  5304.3    0.05       0
  5316.7    0.12       0
Bank Sta=5304.3,5316.7
Exp/Cntr=0.3,0.1

Type RM Length L Ch R = 1,6044,373,373,373
BEGIN DESCRIPTION:
Cypress Tributary 2 11.0
END DESCRIPTION:
XS GIS Cut Line= 3
      2151474.99     13875425.00      2150494.92     13875145.03
      2150274.98     13875074.99
#Sta/Elev= 30
  3980.6 1117.98  4095.0 1114.34  4215.9 1100.14  4264.5 1095.79  4282.2 1094.68
  4288.7 1093.56  4334.2 1091.42  4493.2 1087.91  4632.5 1085.98  4689.1 1085.42
  4750.2 1085.11  4771.0 1083.54  4831.7 1082.40  4927.0 1081.25  4944.0 1079.78
  4949.2 1080.53  4968.6 1079.16  4997.2 1078.63  5010.3 1079.23  5034.9 1077.32
  5035.4 1076.82  5048.1 1076.82  5048.6 1077.32  5062.8 1079.57  5080.4 1081.29
  5085.7 1080.85  5104.7 1086.41  5112.7 1090.31  5125.7 1094.50  5230.7 1100.74
#Mann=8,-1,0
  3980.6    0.12       0  4264.5    0.07       0  4493.2   0.035       0
  4632.5    0.07       0  4689.1   0.035       0  4831.7    0.12       0
  5034.9    0.05       0  5048.6    0.12       0
Bank Sta=5034.9,5048.6
Exp/Cntr=0.3,0.1

Type RM Length L Ch R = 1,5671,542,542,542
BEGIN DESCRIPTION:
Cypress Tributary 2 10.0
END DESCRIPTION:
XS GIS Cut Line= 3
      2151475.00     13875325.00      2150474.55     13874815.72
      2150274.98     13874775.00
#Sta/Elev= 30
  3877.4 1117.70  3944.7 1115.45  3974.7 1111.34  4041.4 1105.47  4108.1 1097.18
  4124.3 1096.37  4138.1 1094.70  4236.0 1088.84  4274.8 1087.42  4394.8 1085.52
  4450.4 1084.73  4636.4 1083.79  4830.9 1081.76  4909.7 1080.12  4947.8 1080.71
  4954.6 1081.42  4967.9 1080.59  4986.6 1075.51  5013.1 1075.42  5013.6 1074.92
  5026.8 1075.42  5026.9 1077.31  5032.0 1077.58  5060.8 1094.10  5070.5 1096.53
  5077.4 1097.39  5082.5 1097.10  5127.9 1101.95  5170.4 1103.85  5203.7 1105.40
#Mann=10,-1,0
  3877.4    0.12       0  4138.1    0.07       0  4274.8   0.035       0
  4394.8    0.07       0  4450.4   0.035       0  4967.9    0.12       0
  5013.1    0.05       0  5026.8    0.12       0  5070.5    0.07       0
  5170.4   0.035       0
Bank Sta=5013.1,5026.8
Exp/Cntr=0.3,0.1

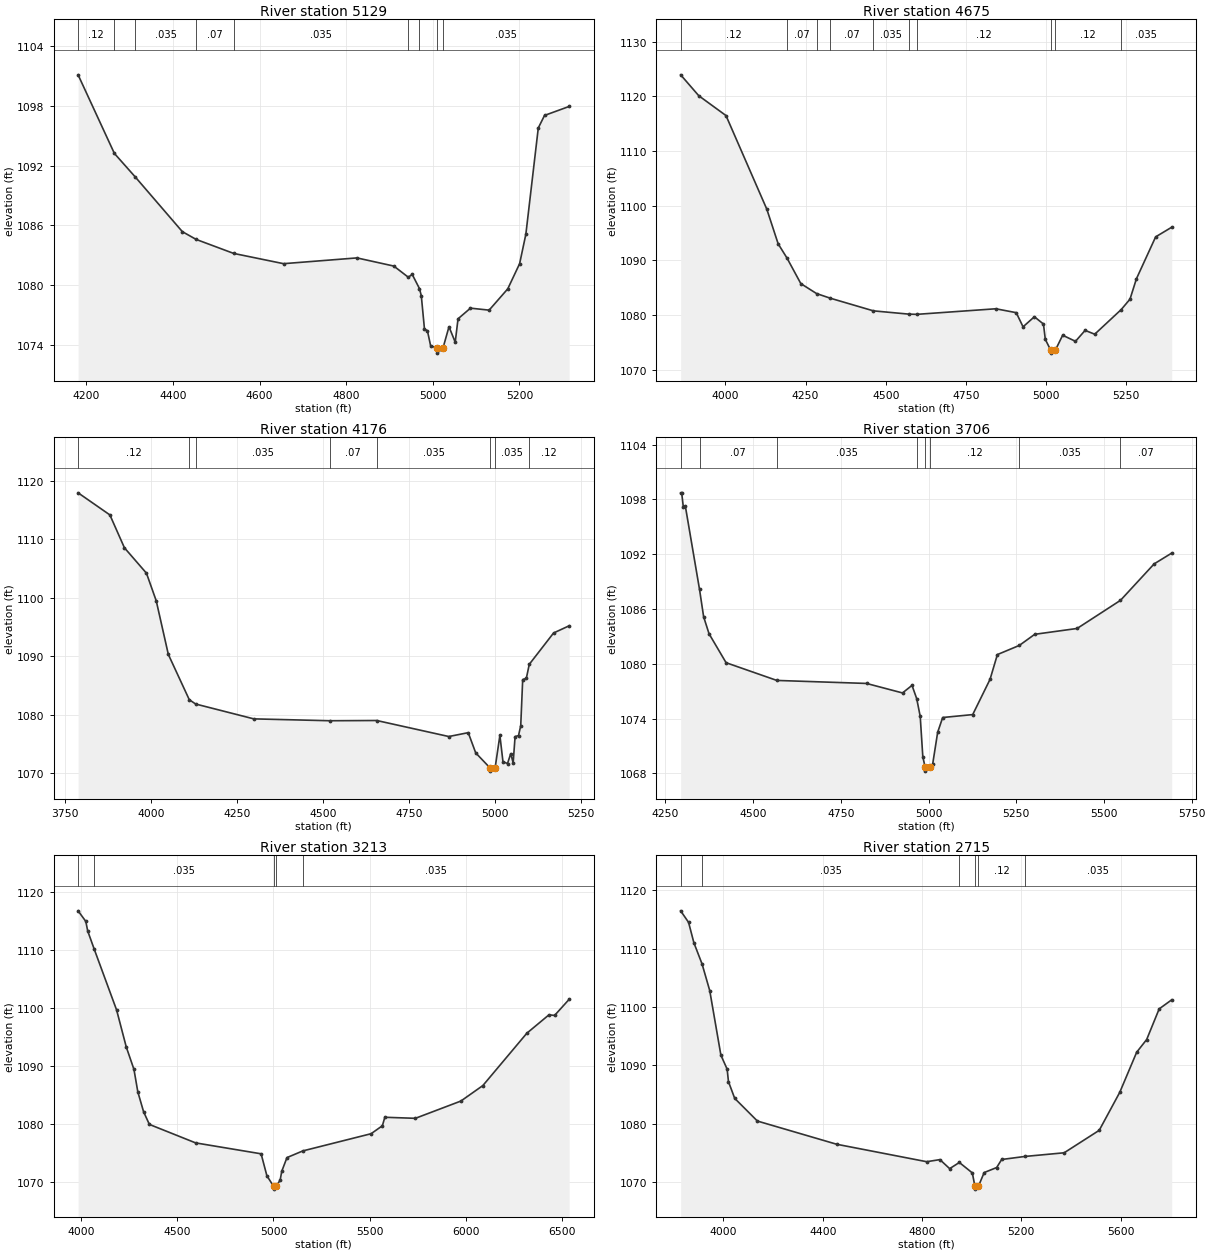
Type RM Length L Ch R = 1,5129,454,454,454
BEGIN DESCRIPTION:
Cypress Tributary 2 9.0
END DESCRIPTION:
XS GIS Cut Line= 3
      2151375.02     13875125.03      2150819.36     13874523.23
      2150574.96     13874324.97
#Sta/Elev= 30
  4180.9 1101.12  4264.7 1093.22  4312.8 1090.86  4421.6 1085.36  4453.4 1084.58
  4540.2 1083.17  4655.3 1082.14  4824.8 1082.72  4909.9 1081.90  4943.3 1080.78
  4952.4 1081.06  4969.2 1079.63  4973.4 1078.91  4980.7 1075.57  4987.5 1075.40
  4994.9 1073.89  5009.7 1073.65  5010.2 1073.15  5023.4 1073.65  5037.3 1075.80
  5051.7 1074.25  5058.2 1076.60  5086.9 1077.67  5130.0 1077.47  5173.0 1079.61
  5200.4 1082.14  5214.8 1085.10  5243.5 1095.78  5257.9 1097.04  5314.7 1097.94
#Mann=9,-1,0
  4180.9    0.12       0  4264.7    0.07       0  4312.8   0.035       0
  4453.4    0.07       0  4540.2   0.035       0  4943.3    0.12       0
  4969.2   0.035       0  5009.7   0.035       0  5023.4   0.035       0
Bank Sta=5009.7,5023.4
Exp/Cntr=0.3,0.1

Type RM Length L Ch R = 1,4675,499,499,499
BEGIN DESCRIPTION:
Cypress Tributary 2 8.0
END DESCRIPTION:
XS GIS Cut Line= 3
      2151825.01     13874975.01      2151016.77     13874171.77
      2150624.98     13874175.00
#Sta/Elev= 30
  3860.5 1123.94  3917.1 1120.11  4001.9 1116.49  4129.2 1099.37  4164.6 1093.03
  4191.9 1090.46  4235.3 1085.76  4284.4 1083.94  4326.8 1083.10  4461.6 1080.78
  4572.3 1080.18  4596.5 1080.14  4843.4 1081.16  4907.0 1080.45  4928.3 1077.86
  4963.6 1079.70  4991.9 1078.37  4997.7 1075.56  5014.9 1073.55  5015.4 1073.05
  5028.7 1073.55  5051.8 1076.32  5091.8 1075.21  5121.8 1077.21  5151.8 1076.51
  5234.3 1081.01  5261.8 1082.92  5281.8 1086.64  5341.8 1094.31  5391.8 1096.07
#Mann=10,-1,0
  3860.5    0.12       0  4191.9    0.07       0  4284.4   0.035       0
  4326.8    0.07       0  4461.6   0.035       0  4572.3    0.07       0
  4596.5    0.12       0  5014.9    0.05       0  5028.7    0.12       0
  5234.3   0.035       0
Bank Sta=5014.9,5028.7
Exp/Cntr=0.3,0.1

Type RM Length L Ch R = 1,4176,470,470,470
BEGIN DESCRIPTION:
Cypress Tributary 2 7.0
END DESCRIPTION:
XS GIS Cut Line= 3
      2151925.01     13874725.01      2151114.95     13873824.88
      2150924.97     13873724.98
#Sta/Elev= 30
  3789.0 1117.94  3881.3 1114.16  3923.5 1108.54  3987.5 1104.19  4015.9 1099.46
  4051.0 1090.29  4111.8 1082.55  4130.3 1081.81  4299.1 1079.27  4520.0 1078.95
  4656.0 1078.99  4865.3 1076.25  4921.7 1076.91  4943.4 1073.45  4985.8 1070.83
  4986.3 1070.33  4999.6 1070.83  5013.6 1076.45  5022.5 1071.95  5035.7 1071.63
  5045.1 1073.32  5052.1 1071.75  5057.7 1076.23  5067.7 1076.42  5074.1 1078.09
  5079.8 1085.99  5090.3 1086.19  5098.9 1088.60  5169.4 1093.96  5214.6 1095.19
#Mann=8,-1,0
  3789.0    0.12       0  4111.8    0.07       0  4130.3   0.035       0
  4520.0    0.07       0  4656.0   0.035       0  4985.8   0.035       0
  4999.6   0.035       0  5098.9    0.12       0
Bank Sta=4985.8,4999.6
Exp/Cntr=0.3,0.1

Type RM Length L Ch R = 1,3706,493,493,493
BEGIN DESCRIPTION:
Cypress Tributary 2 6.0
END DESCRIPTION:
XS GIS Cut Line= 3
      2151924.98     13874424.96      2151552.24     13873824.91
      2151025.00     13873375.00
#Sta/Elev= 30
  4293.6 1098.72  4296.5 1098.72  4301.2 1097.18  4307.1 1097.23  4347.4 1088.14
  4359.1 1085.15  4374.5 1083.29  4423.1 1080.12  4567.7 1078.18  4823.3 1077.85
  4925.9 1076.81  4953.0 1077.64  4966.4 1076.18  4976.4 1074.24  4983.8 1069.81
  4990.1 1068.75  4990.6 1068.25  5003.9 1068.75  5011.8 1069.00  5026.1 1072.50
  5040.4 1074.12  5126.0 1074.44  5175.4 1078.30  5196.3 1081.01  5258.7 1082.01
  5302.8 1083.23  5423.6 1083.87  5547.2 1086.95  5643.1 1090.94  5693.1 1092.12
#Mann=8,-1,0
  4293.6   0.035       0  4347.4    0.07       0  4567.7   0.035       0
  4966.4    0.12       0  4990.1    0.05       0  5003.9    0.12       0
  5258.7   0.035       0  5547.2    0.07       0
Bank Sta=4990.1,5003.9
Exp/Cntr=0.3,0.1

Type RM Length L Ch R = 1,3213,498,498,498
BEGIN DESCRIPTION:
Cypress Tributary 2 5.0
END DESCRIPTION:
XS GIS Cut Line= 3
      2151975.00     13874675.02      2151988.31     13873660.81
      2151079.28     13872424.17
#Sta/Elev= 30
  3985.7 1116.72  4025.7 1114.90  4035.7 1113.24  4069.1 1110.15  4185.7 1099.64
  4235.7 1093.29  4275.7 1089.42  4295.8 1085.55  4325.8 1082.12  4355.8 1079.95
  4595.8 1076.77  4935.8 1074.89  4965.8 1071.11  5000.3 1069.31  5000.8 1068.81
  5014.2 1069.31  5034.6 1070.35  5043.0 1071.89  5070.1 1074.24  5152.5 1075.39
  5506.8 1078.35  5565.3 1079.72  5578.1 1081.18  5736.6 1081.00  5972.7 1083.97
  6087.0 1086.64  6315.3 1095.65  6430.3 1098.82  6459.3 1098.71  6534.8 1101.48
#Mann=5,-1,0
  3985.7    0.12       0  4069.1   0.035       0  5000.3   0.035       0
  5014.2   0.035       0  5152.5   0.035       0
Bank Sta=5000.3,5014.2
Exp/Cntr=0.3,0.1

Type RM Length L Ch R = 1,2715,481,481,481
BEGIN DESCRIPTION:
Cypress Tributary 2 4.0
END DESCRIPTION:
XS GIS Cut Line= 3
      2152025.01     13874674.97      2152429.97     13873574.94
      2152525.00     13872774.96
#Sta/Elev= 30
  3827.8 1116.48  3859.7 1114.50  3881.0 1111.02  3914.1 1107.36  3945.0 1102.79
  3989.9 1091.73  4015.1 1089.33  4020.4 1087.19  4045.5 1084.33  4136.9 1080.44
  4456.5 1076.46  4818.8 1073.47  4872.1 1073.83  4911.3 1072.28  4950.3 1073.34
  5002.6 1071.55  5013.0 1069.27  5013.5 1068.77  5027.2 1069.27  5050.3 1071.61
  5100.6 1072.47  5120.8 1073.85  5214.2 1074.37  5372.5 1075.00  5513.7 1078.85
  5596.4 1085.36  5664.6 1092.24  5704.9 1094.42  5755.2 1099.67  5805.6 1101.22
#Mann=6,-1,0
  3827.8    0.12       0  3914.1   0.035       0  4950.3    0.12       0
  5013.0    0.05       0  5027.2    0.12       0  5214.2   0.035       0
Bank Sta=5013,5027.2
Exp/Cntr=0.3,0.1

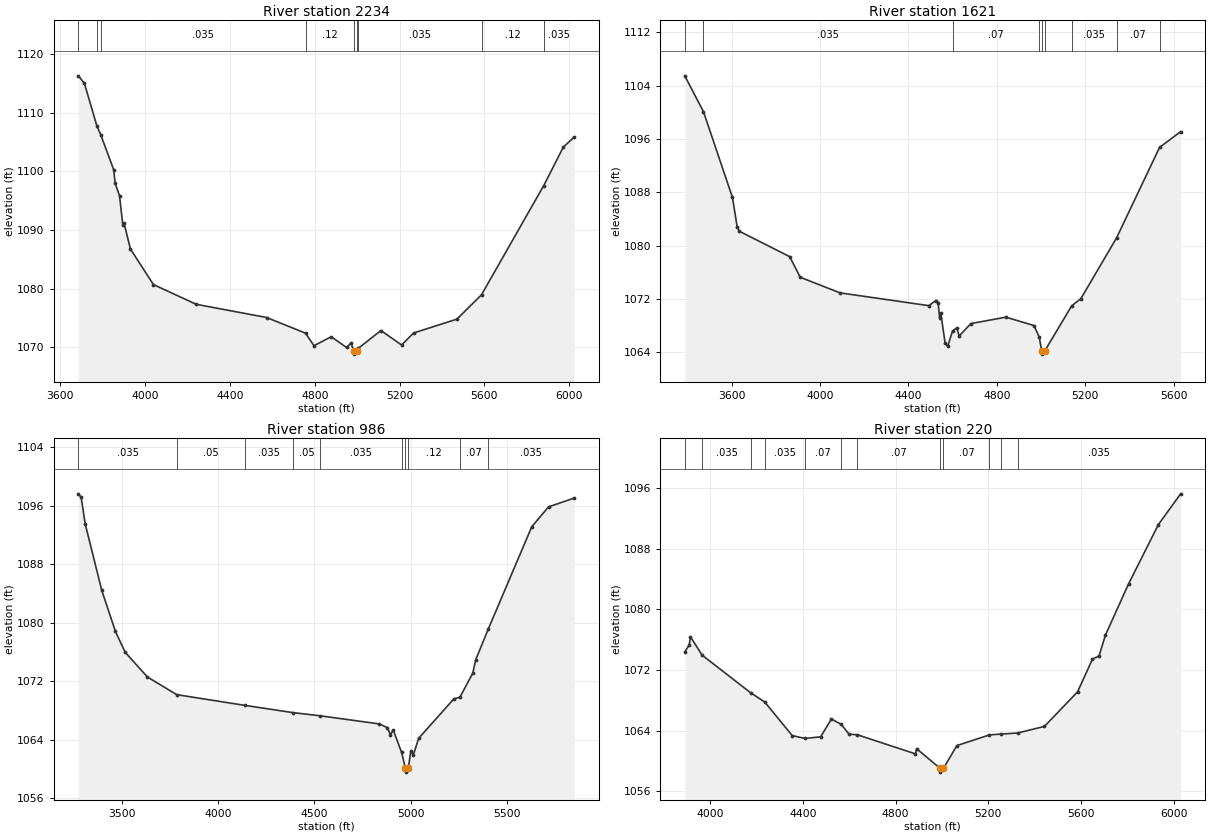
Type RM Length L Ch R = 1,2234,613,613,613
BEGIN DESCRIPTION:
Cypress Tributary 2 3.0
END DESCRIPTION:
XS GIS Cut Line= 3
      2152175.02     13874724.97      2152895.13     13873624.68
      2152675.01     13872625.03
#Sta/Elev= 30
  3685.0 1116.30  3713.6 1115.02  3772.0 1107.82  3790.4 1106.27  3852.3 1100.22
  3858.4 1097.99  3879.4 1095.82  3894.5 1090.93  3900.5 1091.17  3930.7 1086.75
  4039.3 1080.68  4241.3 1077.31  4573.0 1075.06  4756.5 1072.39  4796.4 1070.24
  4877.6 1071.78  4950.0 1069.95  4971.0 1070.68  4985.0 1069.31  4985.5 1068.81
  4999.3 1069.31  5005.7 1069.80  5112.0 1072.84  5209.7 1070.37  5265.9 1072.41
  5470.7 1074.78  5586.6 1078.94  5880.2 1097.58  5972.4 1104.13  6023.6 1105.84
#Mann=9,-1,0
  3685.0   0.035       0  3772.0    0.12       0  3790.4   0.035       0
  4756.5    0.12       0  4985.0    0.05       0  4999.3    0.12       0
  5005.7   0.035       0  5586.6    0.12       0  5880.2   0.035       0
Bank Sta=4985,4999.3
Exp/Cntr=0.3,0.1

Type RM Length L Ch R = 1,1621,635,635,635
BEGIN DESCRIPTION:
Cypress Tributary 2 2.0
END DESCRIPTION:
XS GIS Cut Line= 3
      2152916.51     13875048.95      2153439.28     13873521.47
      2153472.99     13872894.63
#Sta/Elev= 30
  3388.8 1105.48  3473.3 1100.09  3604.4 1087.21  3625.5 1082.83  3636.1 1082.13
  3863.1 1078.33  3910.9 1075.23  4090.6 1072.89  4492.2 1070.97  4523.9 1071.73
  4534.5 1071.40  4541.0 1069.18  4546.3 1069.88  4566.2 1065.32  4577.6 1064.86
  4599.8 1067.18  4619.0 1067.64  4629.6 1066.41  4682.4 1068.28  4841.0 1069.24
  4967.8 1067.98  4991.7 1066.25  5002.6 1064.19  5003.1 1063.69  5016.9 1064.19
  5138.3 1070.94  5180.0 1072.02  5341.4 1081.15  5535.7 1094.73  5631.0 1097.10
#Mann=9,-1,0
  3388.8    0.12       0  3473.3   0.035       0  4599.8    0.07       0
  4991.7    0.12       0  5002.6    0.05       0  5016.9    0.12       0
  5138.3   0.035       0  5341.4    0.07       0  5535.7   0.035       0
Bank Sta=5002.6,5016.9
Exp/Cntr=0.3,0.1

Type RM Length L Ch R = 1,986,766,766,766
BEGIN DESCRIPTION:
Cypress Tributary 2 1.0
END DESCRIPTION:
XS GIS Cut Line= 4
      2153149.99     13875050.01      2154068.93     13873778.15
      2153989.75     13873328.07      2153706.39     13872861.35
#Sta/Elev= 30
  3275.4 1097.65  3290.1 1097.19  3311.0 1093.54  3396.9 1084.43  3468.0 1078.80
  3518.3 1075.96  3633.6 1072.57  3785.7 1070.15  4142.0 1068.67  4388.1 1067.69
  4531.4 1067.25  4836.1 1066.14  4878.2 1065.64  4894.7 1064.64  4908.6 1065.33
  4952.3 1062.24  4972.5 1060.04  4973.0 1059.54  4986.9 1060.04  5000.0 1062.42
  5013.4 1061.90  5040.6 1064.16  5223.4 1069.57  5254.7 1069.79  5321.5 1073.09
  5336.9 1074.93  5401.3 1079.09  5627.7 1093.15  5714.5 1095.86  5847.5 1097.07
#Mann=10,-1,0
  3275.4   0.035       0  3785.7    0.05       0  4142.0   0.035       0
  4388.1    0.05       0  4531.4   0.035       0  4952.3    0.12       0
  4972.5    0.05       0  4986.9    0.12       0  5254.7    0.07       0
  5401.3   0.035       0
Bank Sta=4972.5,4986.9
Exp/Cntr=0.3,0.1

Type RM Length L Ch R = 1,220,0,0,0
BEGIN DESCRIPTION:
Cypress Tributary 2 0.0
END DESCRIPTION:
XS GIS Cut Line= 3
      2155025.84     13874524.08      2154751.80     13873448.65
      2153936.35     13872819.41
#Sta/Elev= 30
  3890.2 1074.37  3909.3 1075.29  3914.5 1076.37  3965.3 1073.93  4174.9 1068.97
  4235.2 1067.76  4353.6 1063.34  4408.5 1062.95  4476.6 1063.17  4522.6 1065.51
  4564.7 1064.83  4599.2 1063.51  4634.8 1063.44  4885.4 1060.92  4890.6 1061.60
  4992.1 1059.01  4992.6 1058.51  5006.6 1059.01  5064.3 1062.01  5205.0 1063.42
  5255.6 1063.53  5326.6 1063.67  5442.1 1064.54  5585.2 1069.10  5649.5 1073.41
  5678.0 1073.84  5705.6 1076.59  5805.3 1083.34  5933.9 1091.16  6030.0 1095.22
#Mann=12,-1,0
  3890.2   0.063       0  3965.3   0.035       0  4174.9    0.05       0
  4235.2   0.035       0  4408.5    0.07       0  4564.7   0.035       0
  4634.8    0.07       0  4992.1    0.05       0  5006.6    0.07       0
  5205.0   0.035       0  5255.6    0.07       0  5326.6   0.035       0
Bank Sta=4992.1,5006.6
Exp/Cntr=0.3,0.1

Chan Stop Cuts=-1