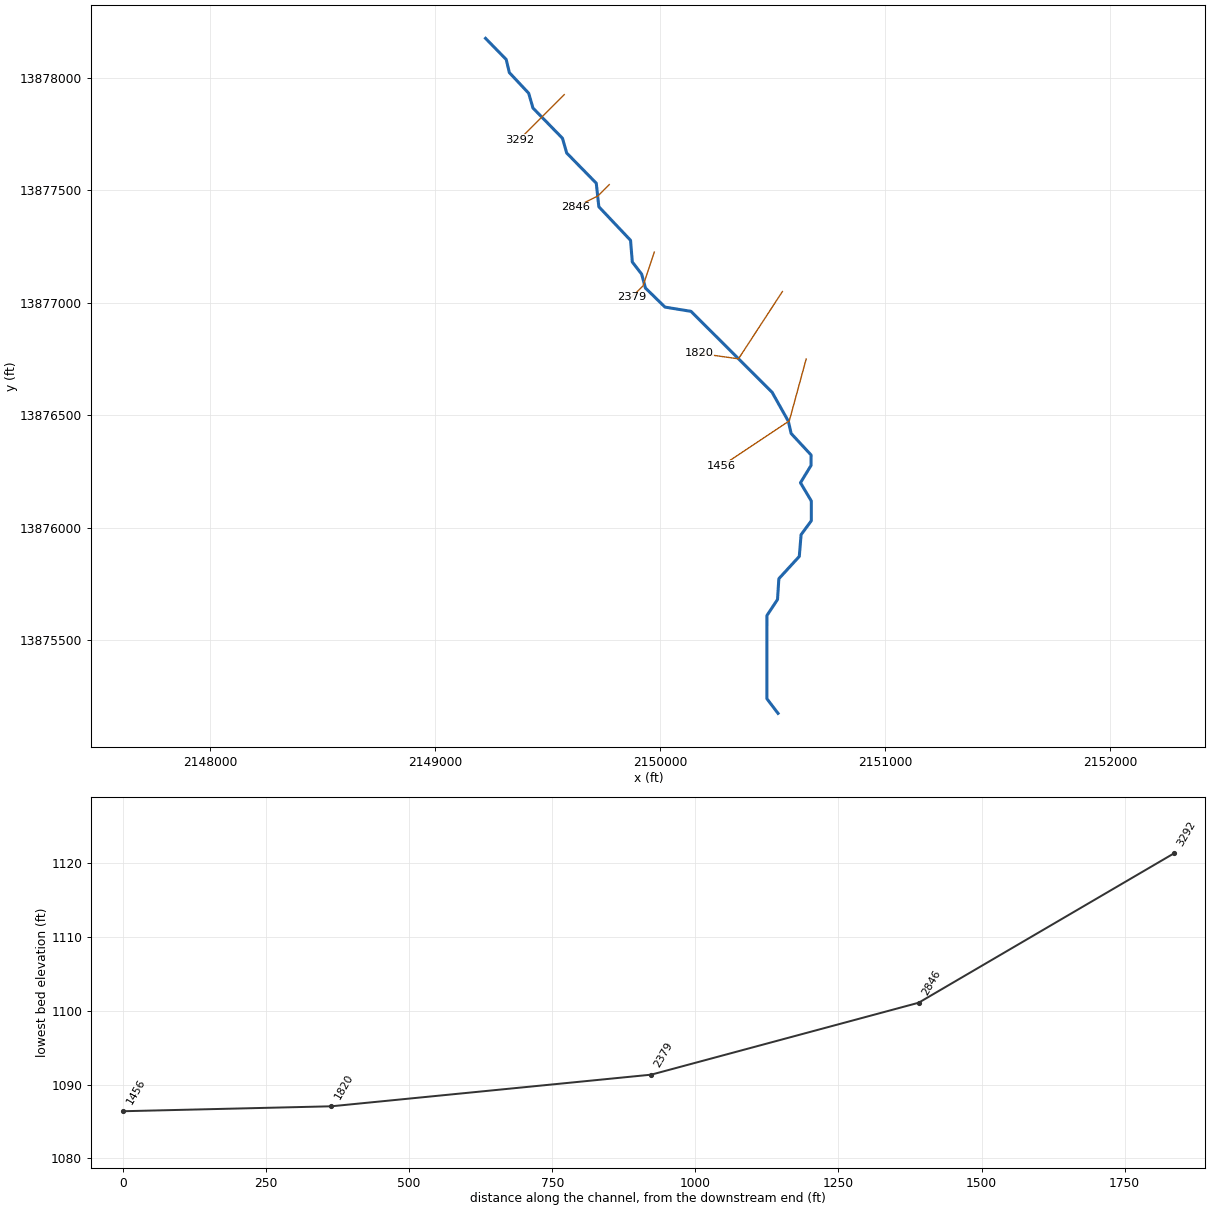
--- Cypress Tributary 2A.prj (project) ---

Proj Title=Cypress Tributary 2A Base Level Engineering
Current Plan=p01
Default Exp/Contr=0.3,0.1
English Units
Geom File=g01
Flow File=f01
Plan File=p01
BEGIN DESCRIPTION:
Cypress Tributary 2A
END DESCRIPTION:

--- Cypress Tributary 2A.p01 (plan) ---

Plan Title=Multiple Run
Short Identifier=Multiple
Geom File=g01
Flow File=f01
Subcritical Flow
K Sum by GR= 0
Std Step Tol= 0.01
Critical Tol= 0.01
Num of Std Step Trials= 20
Max Error Tol= 0.3
Flow Tol Ratio= 0.001
Split Flow NTrial= 30
Split Flow Tol= 0.02
Split Flow Ratio= 0.02
Log Output Level= 0
Friction Slope Method= 1
Unsteady Friction Slope Method= 2
Unsteady Bridges Friction Slope Method= 1
Parabolic Critical Depth
Global Vel Dist=  1 , 1 , 1
Global Log Level= 0
CheckData=True
Encroach Param= -1, 0, 0, 0
BEGIN DESCRIPTION:
Multiple Run
END DESCRIPTION:

--- Cypress Tributary 2A.f01 (steady flow) ---

Flow Title=Multiple
Number of Profiles=7
Profile Names=10-year,25-year,50-year,1pct_min,100-year,1pct_plu,500-year
River Rch & RM= Cypress Tributar,Reach-1,3292
     699    1148    1563    1031    2057    4104    3526
Boundary for River Rch & Prof#=Cypress Tributar,Reach-1,1
Up Type=0
Dn Type=3
Dn Slope=0.005
Boundary for River Rch & Prof#=Cypress Tributar,Reach-1,2
Up Type=0
Dn Type=3
Dn Slope=0.005
Boundary for River Rch & Prof#=Cypress Tributar,Reach-1,3
Up Type=0
Dn Type=3
Dn Slope=0.005
Boundary for River Rch & Prof#=Cypress Tributar,Reach-1,4
Up Type=0
Dn Type=3
Dn Slope=0.005
Boundary for River Rch & Prof#=Cypress Tributar,Reach-1,5
Up Type=0
Dn Type=3
Dn Slope=0.005
Boundary for River Rch & Prof#=Cypress Tributar,Reach-1,6
Up Type=0
Dn Type=3
Dn Slope=0.005
Boundary for River Rch & Prof#=Cypress Tributar,Reach-1,7
Up Type=0
Dn Type=3
Dn Slope=0.005

--- Cypress Tributary 2A.g01 (geometry) ---

Geom Title=Existing Conditions

River Reach=Cypress Tributar,Reach-1
Reach XY= 30
      2149225.00     13878175.00      2149316.89     13878081.07
      2149330.86     13878022.71      2149416.82     13877931.04
      2149435.78     13877865.32      2149566.84     13877731.05
      2149585.78     13877665.32      2149717.14     13877531.17
      2149728.61     13877426.50      2149869.48     13877277.43
      2149877.33     13877180.97      2149918.86     13877127.17
      2149935.75     13877065.29      2150022.56     13876980.52
      2150138.30     13876961.60      2150498.71     13876601.82
      2150570.81     13876473.27      2150583.16     13876418.95
      2150671.86     13876323.36      2150671.63     13876276.74
      2150624.61     13876200.00      2150672.81     13876119.03
      2150672.83     13876030.97      2150627.36     13875969.02
      2150619.46     13875872.58      2150528.62     13875773.50
      2150522.64     13875680.98      2150475.52     13875609.78
      2150475.36     13875240.15      2150525.00     13875175.00

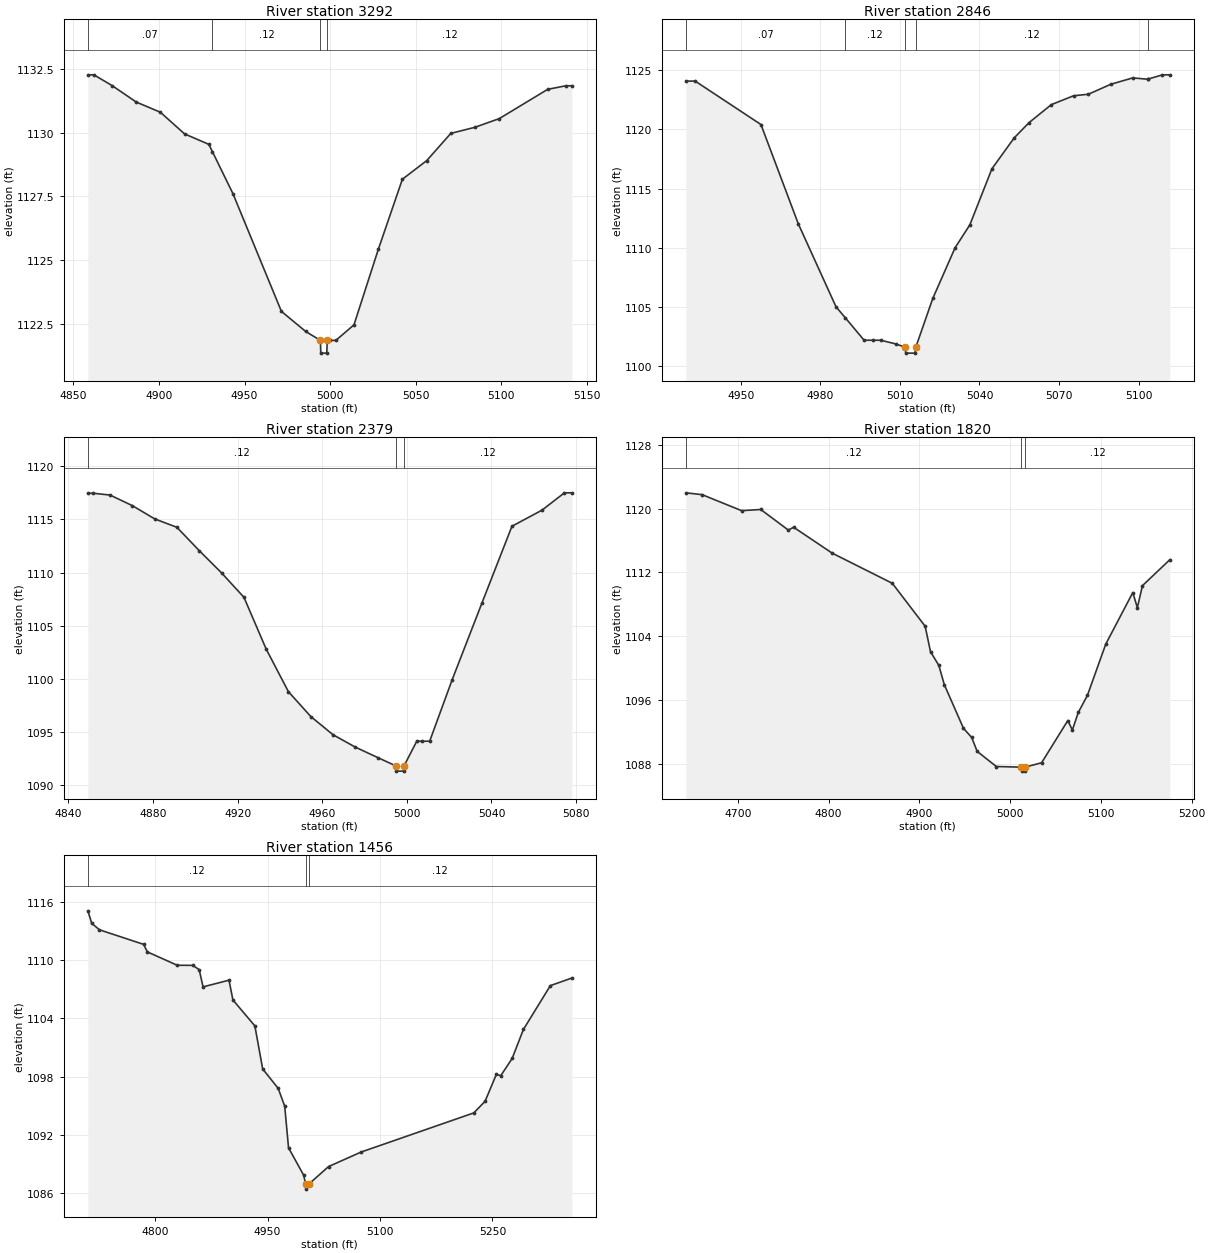
Type RM Length L Ch R = 1,3292,446,446,446
BEGIN DESCRIPTION:
Cypress Tributary 2A 5.0
END DESCRIPTION:
XS GIS Cut Line= 3
      2149574.98     13877924.98      2149475.00     13877825.00
      2149375.01     13877725.01
#Sta/Elev= 27
  4858.4 1132.27  4861.9 1132.27  4872.5 1131.85  4886.7 1131.20  4900.8 1130.80
  4914.9 1129.95  4929.1 1129.54  4931.2 1129.25  4943.2 1127.60  4971.5 1122.98
  4985.7 1122.19  4994.3 1121.84  4994.5 1121.34  4998.0 1121.34  4998.3 1121.84
  4999.8 1121.84  5003.3 1121.84  5013.9 1122.45  5028.1 1125.41  5042.2 1128.17
  5056.4 1128.90  5070.5 1129.97  5084.6 1130.21  5098.8 1130.55  5127.1 1131.70
  5137.7 1131.84  5141.2 1131.84
#Mann=4,-1,0
  4858.4    0.07       0  4931.2    0.12       0  4994.3    0.05       0
  4998.3    0.12       0
Bank Sta=4994.3,4998.3
Exp/Cntr=0.3,0.1

Type RM Length L Ch R = 1,2846,467,467,467
BEGIN DESCRIPTION:
Cypress Tributary 2A 4.0
END DESCRIPTION:
XS GIS Cut Line= 3
      2149775.00     13877525.00      2149725.00     13877475.00
      2149625.02     13877425.01
#Sta/Elev= 29
  4929.3 1124.08  4932.8 1124.08  4957.6 1120.41  4971.7 1112.01  4985.9 1105.01
  4989.4 1104.08  4996.5 1102.18  5000.0 1102.18  5002.8 1102.18  5008.4 1101.87
  5012.0 1101.59  5012.2 1101.09  5015.7 1101.09  5016.0 1101.59  5022.4 1105.71
  5030.8 1109.99  5036.4 1111.94  5044.7 1116.67  5053.1 1119.28  5058.7 1120.57
  5067.1 1122.09  5075.5 1122.84  5081.1 1122.97  5089.5 1123.81  5097.8 1124.35
  5103.4 1124.24  5103.6 1124.25  5109.0 1124.61  5111.8 1124.61
#Mann=5,-1,0
  4929.3    0.07       0  4989.4    0.12       0  5012.0    0.05       0
  5016.0    0.12       0  5103.6    0.07       0
Bank Sta=5012,5016
Exp/Cntr=0.3,0.1

Type RM Length L Ch R = 1,2379,559,559,559
BEGIN DESCRIPTION:
Cypress Tributary 2A 3.0
END DESCRIPTION:
XS GIS Cut Line= 3
      2149974.99     13877224.97      2149925.00     13877075.00
      2149875.00     13877025.00
#Sta/Elev= 28
  4849.2 1117.45  4851.8 1117.45  4859.7 1117.28  4870.3 1116.28  4880.8 1115.04
  4891.3 1114.25  4901.9 1112.05  4912.4 1109.97  4923.0 1107.67  4933.5 1102.81
  4944.0 1098.81  4954.6 1096.47  4965.1 1094.76  4975.7 1093.59  4986.2 1092.62
  4994.7 1091.84  4995.0 1091.34  4998.5 1091.34  4998.7 1091.84  5004.7 1094.15
  5007.3 1094.15  5010.8 1094.15  5021.4 1099.91  5035.6 1107.18  5049.7 1114.35
  5063.9 1115.86  5074.5 1117.49  5078.0 1117.49
#Mann=3,-1,0
  4849.2    0.12       0  4994.7    0.05       0  4998.7    0.12       0
Bank Sta=4994.7,4998.7
Exp/Cntr=0.3,0.1

Type RM Length L Ch R = 1,1820,364,364,364
BEGIN DESCRIPTION:
Cypress Tributary 2A 2.0
END DESCRIPTION:
XS GIS Cut Line= 3
      2150544.53     13877049.98      2150349.27     13876750.75
      2150175.05     13876774.99
#Sta/Elev= 30
  4642.7 1121.97  4660.6 1121.74  4704.1 1119.73  4725.2 1119.88  4755.5 1117.30
  4761.4 1117.65  4803.9 1114.40  4870.1 1110.62  4906.3 1105.23  4912.2 1102.04
  4921.4 1100.31  4927.4 1097.90  4948.5 1092.43  4957.6 1091.27  4963.6 1089.53
  4984.7 1087.63  5012.4 1087.55  5012.7 1087.05  5016.2 1087.05  5016.4 1087.55
  5034.6 1088.10  5063.5 1093.40  5068.5 1092.20  5075.0 1094.41  5085.1 1096.56
  5105.3 1102.99  5135.1 1109.46  5140.1 1107.55  5145.7 1110.32  5175.9 1113.58
#Mann=3,-1,0
  4642.7    0.12       0  5012.4    0.05       0  5016.4    0.12       0
Bank Sta=5012.4,5016.4
Exp/Cntr=0.3,0.1

Type RM Length L Ch R = 1,1456,0,0,0
BEGIN DESCRIPTION:
Cypress Tributary 2A 1.0
END DESCRIPTION:
XS GIS Cut Line= 3
      2150649.99     13876749.98      2150575.00     13876475.00
      2150274.98     13876274.99
#Sta/Elev= 30
  4710.3 1115.11  4715.5 1113.82  4725.8 1113.15  4784.6 1111.65  4789.7 1110.87
  4829.5 1109.49  4850.2 1109.48  4858.8 1109.04  4864.0 1107.26  4898.6 1107.95
  4903.8 1105.91  4933.1 1103.23  4943.5 1098.79  4964.2 1096.78  4972.9 1094.94
  4978.0 1090.65  4998.3 1087.80  5000.8 1086.88  5001.1 1086.38  5004.8 1086.88
  5031.4 1088.71  5074.9 1090.21  5225.2 1094.25  5240.2 1095.45  5255.2 1098.22
  5261.2 1098.10  5276.3 1099.87  5291.3 1102.86  5327.3 1107.39  5355.9 1108.17
#Mann=3,-1,0
  4710.3    0.12       0  5000.8    0.05       0  5004.8    0.12       0
Bank Sta=5000.8,5004.8
Exp/Cntr=0.3,0.1

Chan Stop Cuts=-1