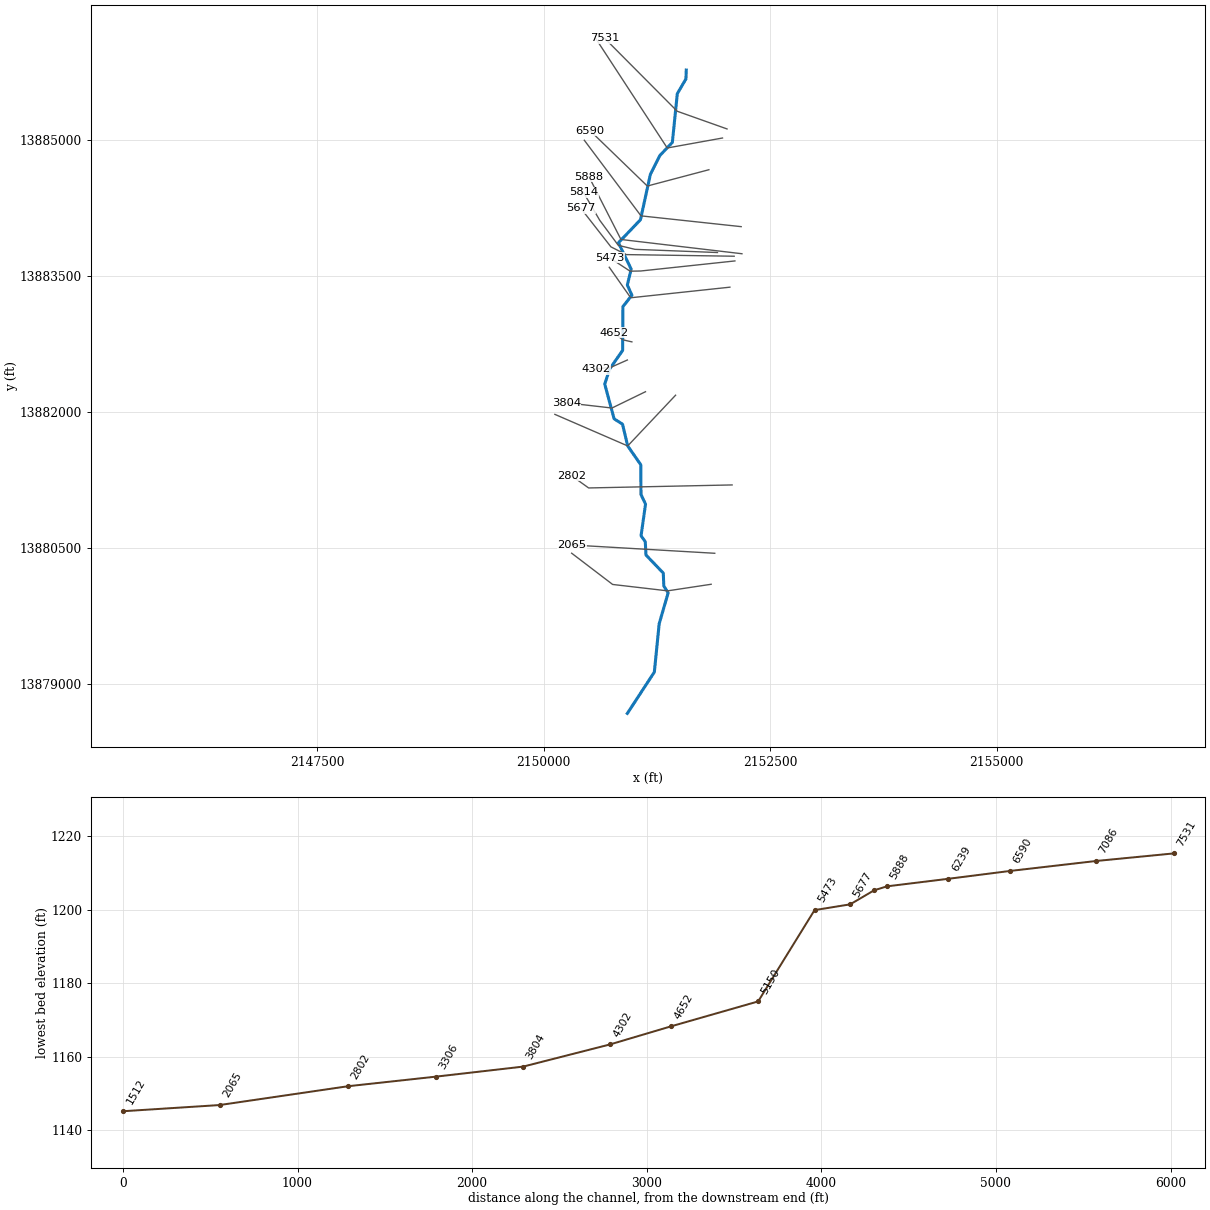
--- Cypress Tributary 4.prj (project) ---

Proj Title=Cypress Tributary 4 Base Level Engineering
Current Plan=p01
Default Exp/Contr=0.3,0.1
English Units
Geom File=g01
Flow File=f01
Plan File=p01
BEGIN DESCRIPTION:
Cypress Tributary 4
END DESCRIPTION:

--- Cypress Tributary 4.p01 (plan) ---

Plan Title=Multiple Run
Short Identifier=Multiple
Geom File=g01
Flow File=f01
Subcritical Flow
K Sum by GR= 0
Std Step Tol= 0.01
Critical Tol= 0.01
Num of Std Step Trials= 20
Max Error Tol= 0.3
Flow Tol Ratio= 0.001
Split Flow NTrial= 30
Split Flow Tol= 0.02
Split Flow Ratio= 0.02
Log Output Level= 0
Friction Slope Method= 1
Unsteady Friction Slope Method= 2
Unsteady Bridges Friction Slope Method= 1
Parabolic Critical Depth
Global Vel Dist=  1 , 1 , 1
Global Log Level= 0
CheckData=True
Encroach Param= -1, 0, 0, 0
BEGIN DESCRIPTION:
Multiple Run
END DESCRIPTION:

--- Cypress Tributary 4.f01 (steady flow) ---

Flow Title=Multiple
Number of Profiles=7
Profile Names=10-year,25-year,50-year,1pct_min,100-year,1pct_plu,500-year
River Rch & RM= Cypress Tributar,Reach-1,7531
    1256    2122    2942    1973    3936    7854    6976
Boundary for River Rch & Prof#=Cypress Tributar,Reach-1,1
Up Type=0
Dn Type=3
Dn Slope=0.005
Boundary for River Rch & Prof#=Cypress Tributar,Reach-1,2
Up Type=0
Dn Type=3
Dn Slope=0.005
Boundary for River Rch & Prof#=Cypress Tributar,Reach-1,3
Up Type=0
Dn Type=3
Dn Slope=0.005
Boundary for River Rch & Prof#=Cypress Tributar,Reach-1,4
Up Type=0
Dn Type=3
Dn Slope=0.005
Boundary for River Rch & Prof#=Cypress Tributar,Reach-1,5
Up Type=0
Dn Type=3
Dn Slope=0.005
Boundary for River Rch & Prof#=Cypress Tributar,Reach-1,6
Up Type=0
Dn Type=3
Dn Slope=0.005
Boundary for River Rch & Prof#=Cypress Tributar,Reach-1,7
Up Type=0
Dn Type=3
Dn Slope=0.005

--- Cypress Tributary 4.g01 (geometry) ---

Geom Title=Existing Conditions

River Reach=Cypress Tributar,Reach-1
Reach XY= 30
      2151575.00     13885775.00      2151571.37     13885676.50
      2151476.20     13885514.50      2151421.46     13884976.46
      2151283.14     13884831.06      2151178.83     13884623.42
      2151069.53     13884122.55      2150826.58     13883868.95
      2150966.92     13883578.30      2150924.70     13883402.16
      2150975.04     13883290.34      2150876.06     13883164.56
      2150872.76     13882680.93      2150730.54     13882477.42
      2150675.09     13882309.61      2150778.55     13881926.29
      2150871.47     13881866.51      2150928.76     13881626.56
      2151072.94     13881419.14      2151075.52     13881090.22
      2151125.50     13880984.26      2151076.22     13880635.51
      2151122.61     13880569.47      2151130.47     13880422.55
      2151321.46     13880223.53      2151327.27     13880080.94
      2151375.09     13880004.90      2151276.22     13879664.50
      2151222.65     13879130.52      2150925.00     13878675.00

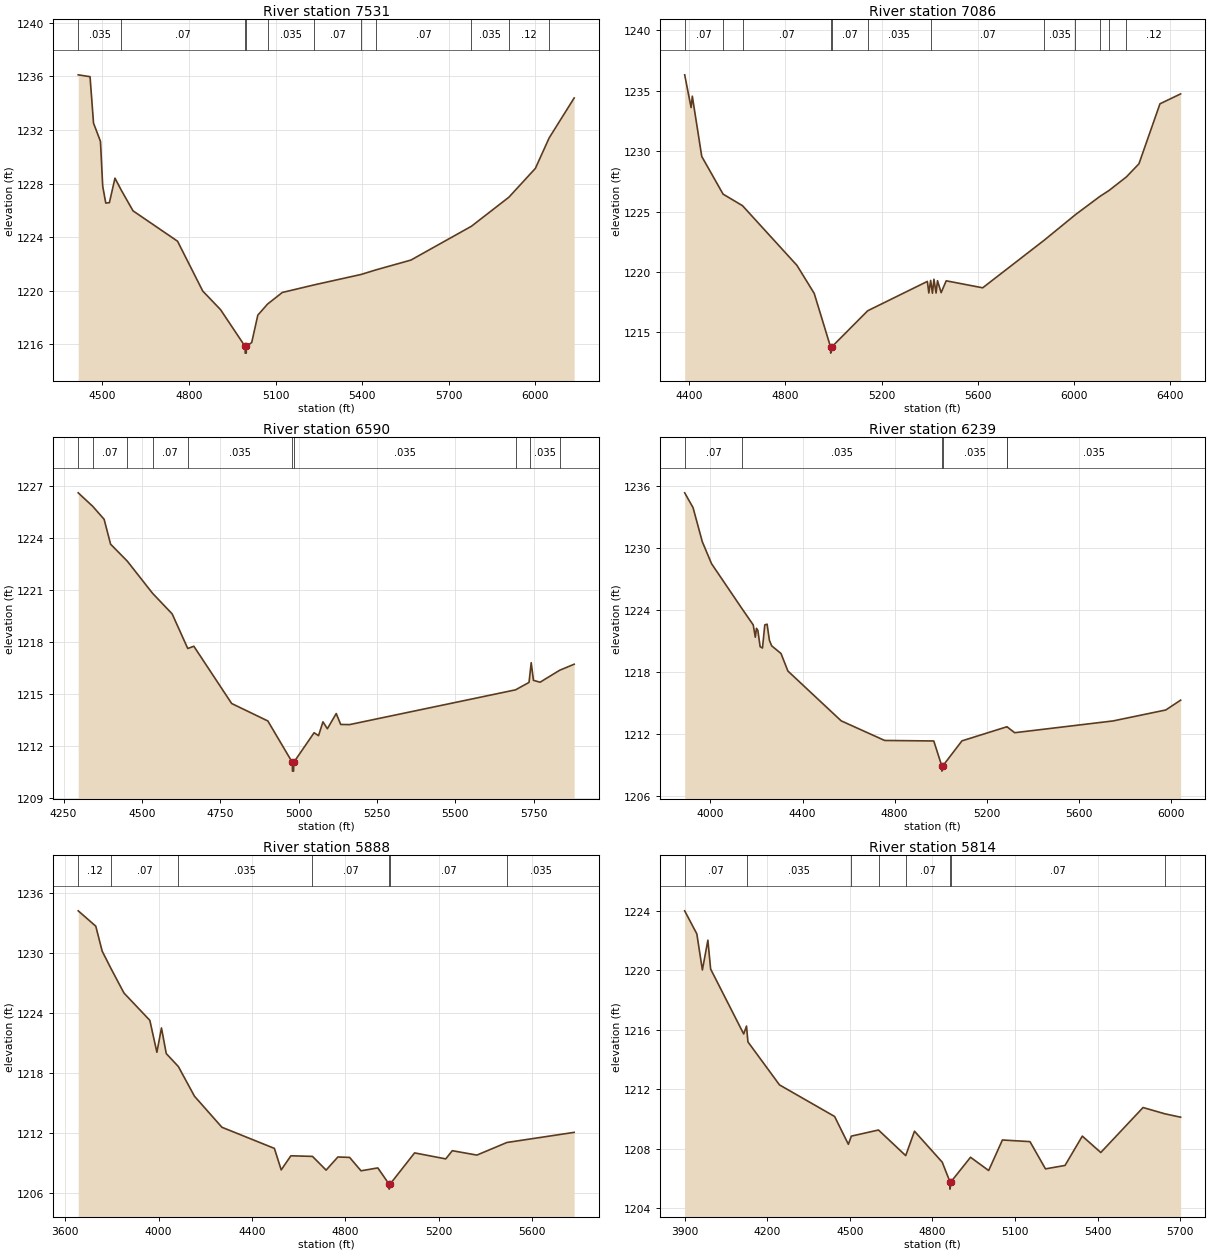
Type RM Length L Ch R = 1,7531,445,445,445
BEGIN DESCRIPTION:
Cypress Tributary 4 10.0
END DESCRIPTION:
XS GIS Cut Line= 3
      2152025.00     13885125.00      2151475.09     13885320.42
      2150674.99     13886125.01
#Sta/Elev= 30
  4416.4 1236.12  4457.4 1235.98  4469.5 1232.51  4493.5 1231.15  4501.3 1227.80
  4511.9 1226.54  4524.4 1226.57  4543.8 1228.40  4565.7 1227.50  4606.3 1225.96
  4760.6 1223.69  4847.8 1219.97  4909.5 1218.58  4994.7 1215.83  4995.0 1215.33
  4998.6 1215.33  4998.8 1215.83  5017.5 1216.12  5038.7 1218.17  5072.7 1219.00
  5123.5 1219.86  5234.2 1220.43  5397.1 1221.21  5448.0 1221.55  5569.0 1222.28
  5778.9 1224.81  5908.7 1226.98  6000.3 1229.13  6048.2 1231.41  6134.7 1234.39
#Mann=11,-1,0
  4416.4   0.035       0  4565.7    0.07       0  4994.7    0.05       0
  4998.8    0.07       0  5072.7   0.035       0  5234.2    0.07       0
  5397.1   0.035       0  5448.0    0.07       0  5778.9   0.035       0
  5908.7    0.12       0  6048.2    0.07       0
Bank Sta=4994.7,4998.8
Exp/Cntr=0.3,0.1

Type RM Length L Ch R = 1,7086,496,496,496
BEGIN DESCRIPTION:
Cypress Tributary 4 9.0
END DESCRIPTION:
XS GIS Cut Line= 3
      2151974.98     13885025.00      2151365.12     13884914.95
      2150574.98     13886125.02
#Sta/Elev= 30
  4380.3 1236.32  4407.1 1233.61  4412.1 1234.55  4451.4 1229.56  4540.2 1226.44
  4621.2 1225.48  4847.7 1220.54  4919.6 1218.22  4987.9 1213.77  4988.2 1213.27
  4992.0 1213.77  5142.4 1216.78  5390.8 1219.21  5396.8 1218.25  5404.4 1219.29
  5411.9 1218.23  5418.1 1219.39  5427.0 1218.25  5433.0 1219.27  5448.1 1218.28
  5469.2 1219.26  5621.1 1218.68  5878.3 1222.64  6007.4 1224.74  6109.1 1226.25
  6147.7 1226.75  6219.2 1227.86  6271.7 1228.95  6359.2 1233.92  6445.2 1234.74
#Mann=12,-1,0
  4380.3    0.07       0  4540.2   0.035       0  4621.2    0.07       0
  4987.9    0.05       0  4992.0    0.07       0  5142.4   0.035       0
  5404.4    0.07       0  5878.3   0.035       0  6007.4    0.07       0
  6109.1    0.12       0  6147.7   0.035       0  6219.2    0.12       0
Bank Sta=4987.9,4992
Exp/Cntr=0.3,0.1

Type RM Length L Ch R = 1,6590,351,351,351
BEGIN DESCRIPTION:
Cypress Tributary 4 8.0
END DESCRIPTION:
XS GIS Cut Line= 3
      2151824.96     13884674.99      2151145.09     13884494.96
      2150512.75     13885106.54
#Sta/Elev= 30
  4296.7 1226.63  4343.0 1225.85  4379.4 1225.10  4400.1 1223.66  4453.4 1222.68
  4534.1 1220.82  4596.6 1219.63  4646.4 1217.63  4665.8 1217.76  4786.5 1214.45
  4902.0 1213.44  4980.3 1211.04  4980.6 1210.54  4984.2 1210.54  4984.5 1211.04
  5049.6 1212.76  5063.8 1212.59  5077.9 1213.39  5092.0 1212.99  5120.3 1213.87
  5134.5 1213.24  5162.8 1213.23  5692.7 1215.24  5735.7 1215.67  5740.0 1216.38
  5742.6 1216.81  5749.8 1215.79  5770.9 1215.68  5833.2 1216.37  5879.7 1216.72
#Mann=10,-1,0
  4296.7   0.035       0  4343.0    0.07       0  4453.4   0.035       0
  4534.1    0.07       0  4646.4   0.035       0  4980.3   0.035       0
  4984.5   0.035       0  5692.7    0.07       0  5740.0   0.035       0
  5833.2    0.12       0
Bank Sta=4980.3,4984.5
Exp/Cntr=0.3,0.1

Type RM Length L Ch R = 1,6239,351,351,351
BEGIN DESCRIPTION:
Cypress Tributary 4 7.0
END DESCRIPTION:
XS GIS Cut Line= 3
      2152181.06     13884046.71      2151075.45     13884165.72
      2150449.99     13885000.01
#Sta/Elev= 30
  3888.0 1235.37  3924.3 1233.94  3964.5 1230.64  4004.7 1228.51  4138.1 1224.12
  4185.8 1222.58  4194.9 1221.39  4199.9 1222.25  4205.9 1222.05  4215.9 1220.47
  4226.0 1220.34  4236.1 1222.58  4246.1 1222.65  4256.2 1221.08  4266.2 1220.55
  4306.5 1219.81  4336.6 1218.11  4567.9 1213.29  4756.8 1211.39  4970.3 1211.34
  5005.1 1208.92  5005.4 1208.42  5009.3 1208.92  5092.6 1211.35  5288.6 1212.72
  5289.7 1212.69  5321.8 1212.14  5749.0 1213.28  5978.1 1214.34  6042.7 1215.29
#Mann=6,-1,0
  3888.0    0.07       0  4138.1   0.035       0  5005.1   0.035       0
  5009.3   0.035       0  5288.6    0.07       0  5289.7   0.035       0
Bank Sta=5005.1,5009.3
Exp/Cntr=0.3,0.1

Type RM Length L Ch R = 1,5888,74,74,74
BEGIN DESCRIPTION:
Cypress Tributary 4 6.0
END DESCRIPTION:
XS GIS Cut Line= 3
      2152189.65     13883747.68      2150854.40     13883905.16
      2150500.00     13884600.00
#Sta/Elev= 30
  3655.5 1234.17  3730.7 1232.64  3758.2 1230.14  3797.9 1228.32  3851.5 1225.96
  3962.3 1223.23  3992.5 1220.04  4012.2 1222.47  4032.7 1219.91  4084.4 1218.62
  4153.6 1215.65  4271.1 1212.55  4495.9 1210.44  4525.1 1208.29  4566.4 1209.70
  4659.1 1209.64  4717.5 1208.27  4767.8 1209.58  4818.1 1209.54  4867.0 1208.20
  4939.0 1208.49  4987.2 1206.87  4987.5 1206.37  4991.4 1206.87  5096.5 1209.99
  5229.9 1209.39  5258.0 1210.21  5363.2 1209.77  5492.1 1211.03  5780.0 1212.04
#Mann=7,-1,0
  3655.5    0.12       0  3797.9    0.07       0  4084.4   0.035       0
  4659.1    0.07       0  4987.2    0.05       0  4991.4    0.07       0
  5492.1   0.035       0
Bank Sta=4987.2,4991.4
Exp/Cntr=0.3,0.1

Type RM Length L Ch R = 1,5814,137,137,137
BEGIN DESCRIPTION:
Cypress Tributary 4 5.3
END DESCRIPTION:
XS GIS Cut Line= 5
      2151919.21     13883761.11      2151008.88     13883796.30
      2150824.90     13883840.36      2150620.05     13884117.12
      2150439.64     13884425.28
#Sta/Elev= 30
  3899.8 1223.98  3944.0 1222.43  3964.1 1220.01  3984.1 1222.01  3994.1 1220.07
  4114.2 1215.71  4124.4 1216.24  4129.6 1215.18  4244.3 1212.29  4444.4 1210.17
  4494.5 1208.30  4505.2 1208.85  4603.9 1209.26  4702.7 1207.54  4734.6 1209.18
  4835.4 1207.10  4863.3 1205.79  4863.5 1205.29  4867.5 1205.79  4938.2 1207.43
  5004.1 1206.54  5054.0 1208.59  5154.2 1208.48  5210.5 1206.65  5281.4 1206.88
  5344.3 1208.85  5411.4 1207.75  5565.0 1210.77  5644.0 1210.35  5701.4 1210.12
#Mann=8,-1,0
  3899.8    0.07       0  4124.4   0.035       0  4505.2    0.07       0
  4603.9   0.035       0  4702.7    0.07       0  4863.3    0.05       0
  4867.5    0.07       0  5644.0   0.035       0
Bank Sta=4863.3,4867.5
Exp/Cntr=0.3,0.1

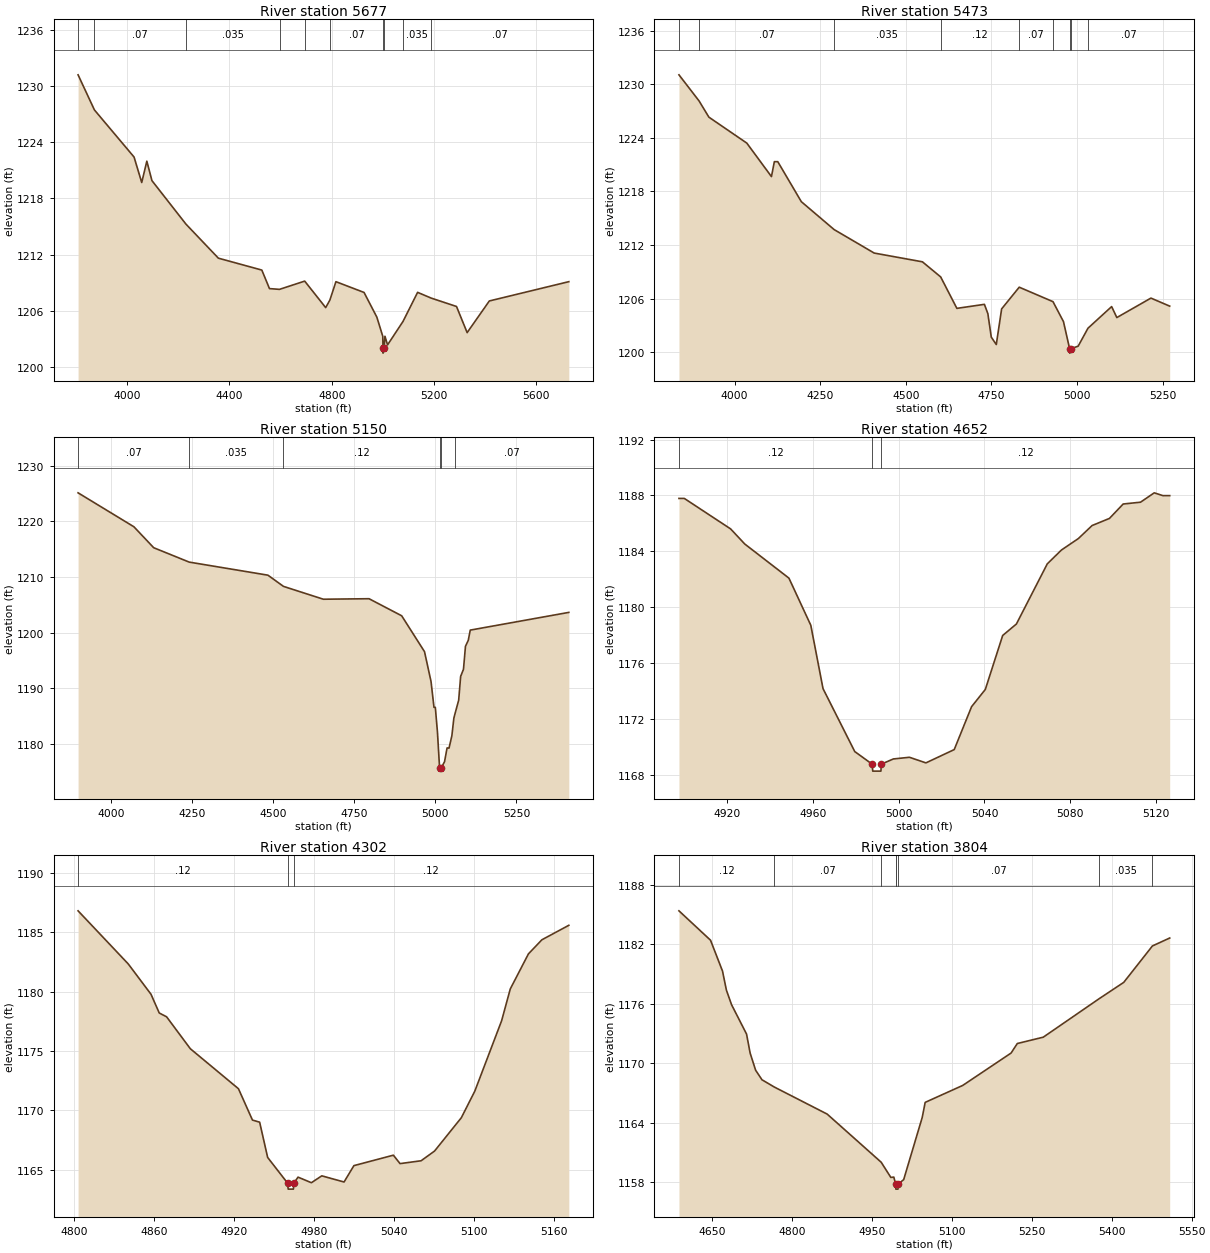
Type RM Length L Ch R = 1,5677,204,204,204
BEGIN DESCRIPTION:
Cypress Tributary 4 5.2
END DESCRIPTION:
XS GIS Cut Line= 4
      2152104.03     13883720.28      2150911.57     13883738.29
      2150743.51     13883823.79      2150411.43     13884248.91
#Sta/Elev= 30
  3807.4 1231.19  3871.4 1227.44  4026.5 1222.41  4056.5 1219.69  4076.5 1221.97
  4096.5 1219.89  4229.5 1215.25  4356.5 1211.61  4526.5 1210.34  4556.5 1208.36
  4595.7 1208.28  4694.3 1209.16  4776.5 1206.33  4792.9 1207.14  4816.5 1209.10
  4926.6 1207.95  4976.6 1205.32  5000.0 1203.26  5000.7 1201.97  5000.9 1201.47
  5004.9 1201.97  5008.4 1203.27  5018.6 1202.35  5079.0 1204.85  5136.2 1207.96
  5189.1 1207.35  5288.5 1206.45  5330.1 1203.66  5416.9 1207.04  5728.0 1209.10
#Mann=10,-1,0
  3807.4    0.12       0  3871.4    0.07       0  4229.5   0.035       0
  4595.7    0.07       0  4694.3   0.035       0  4792.9    0.07       0
  5000.7    0.05       0  5004.9    0.07       0  5079.0   0.035       0
  5189.1    0.07       0
Bank Sta=5000.7,5004.9
Exp/Cntr=0.3,0.1

Type RM Length L Ch R = 1,5473,323,323,323
BEGIN DESCRIPTION:
Cypress Tributary 4 5.1
END DESCRIPTION:
XS GIS Cut Line= 4
      2152111.99     13883668.30      2151072.29     13883557.32
      2150955.22     13883555.17      2150729.19     13883703.59
#Sta/Elev= 30
  3837.3 1231.05  3896.0 1228.13  3924.8 1226.31  4035.4 1223.41  4107.4 1219.66
  4115.9 1221.33  4125.9 1221.33  4194.7 1216.85  4290.4 1213.73  4407.5 1211.10
  4548.3 1210.12  4601.6 1208.43  4648.9 1204.91  4729.3 1205.36  4739.4 1204.32
  4749.4 1201.69  4764.0 1200.86  4779.6 1204.85  4831.0 1207.28  4929.6 1205.66
  4960.2 1203.43  4978.1 1200.40  4978.4 1199.90  4982.3 1200.40  5003.1 1200.68
  5031.8 1202.69  5100.9 1205.11  5116.0 1203.88  5215.6 1206.06  5270.4 1205.16
#Mann=9,-1,0
  3837.3    0.12       0  3896.0    0.07       0  4290.4   0.035       0
  4601.6    0.12       0  4831.0    0.07       0  4929.6   0.035       0
  4978.1   0.035       0  4982.3   0.035       0  5031.8    0.07       0
Bank Sta=4978.1,4982.3
Exp/Cntr=0.3,0.1

Type RM Length L Ch R = 1,5150,498,498,498
BEGIN DESCRIPTION:
Cypress Tributary 4 5.0
END DESCRIPTION:
XS GIS Cut Line= 3
      2152056.82     13883378.73      2150961.85     13883261.80
      2150725.31     13883598.52
#Sta/Elev= 30
  3898.8 1225.15  4070.9 1219.04  4131.9 1215.27  4241.4 1212.68  4483.9 1210.33
  4532.0 1208.31  4654.9 1206.00  4795.7 1206.09  4896.3 1203.02  4966.7 1196.56
  4986.8 1191.18  4995.9 1186.54  5000.0 1186.54  5006.6 1182.07  5013.2 1175.56
  5013.5 1175.06  5017.5 1175.56  5028.4 1176.75  5036.2 1179.23  5042.3 1179.21
  5051.0 1181.42  5057.2 1184.62  5060.6 1185.38  5072.0 1187.83  5078.1 1192.12
  5086.8 1193.39  5092.9 1197.52  5101.6 1198.61  5107.7 1200.44  5411.5 1203.63
#Mann=6,-1,0
  3898.8    0.07       0  4241.4   0.035       0  4532.0    0.12       0
  5013.2    0.05       0  5017.5    0.12       0  5060.6    0.07       0
Bank Sta=5013.2,5017.5
Exp/Cntr=0.3,0.1

Type RM Length L Ch R = 1,4652,350,350,350
BEGIN DESCRIPTION:
Cypress Tributary 4 4.0
END DESCRIPTION:
XS GIS Cut Line= 3
      2150974.98     13882775.00      2150875.03     13882797.72
      2150775.00     13882875.00
#Sta/Elev= 30
  4897.5 1187.79  4900.0 1187.79  4921.6 1185.61  4928.2 1184.53  4948.8 1182.09
  4959.0 1178.72  4964.7 1174.19  4979.5 1169.69  4987.6 1168.79  4987.9 1168.29
  4991.7 1168.29  4991.9 1168.79  4997.5 1169.16  5005.0 1169.28  5012.7 1168.88
  5025.9 1169.83  5034.0 1172.90  5040.4 1174.13  5048.5 1177.99  5054.9 1178.81
  5069.3 1183.11  5075.9 1184.10  5083.8 1184.92  5090.2 1185.85  5098.3 1186.36
  5104.7 1187.39  5112.8 1187.52  5119.2 1188.19  5123.2 1187.99  5126.4 1187.99
#Mann=3,-1,0
  4897.5    0.12       0  4987.6    0.05       0  4991.9    0.12       0
Bank Sta=4987.6,4991.9
Exp/Cntr=0.3,0.1

Type RM Length L Ch R = 1,4302,498,498,498
BEGIN DESCRIPTION:
Cypress Tributary 4 3.0
END DESCRIPTION:
XS GIS Cut Line= 3
      2150924.98     13882574.99      2150744.67     13882495.14
      2150574.96     13882474.99
#Sta/Elev= 30
  4802.8 1186.81  4840.4 1182.34  4857.5 1179.78  4863.7 1178.20  4869.2 1177.88
  4887.0 1175.19  4923.1 1171.82  4933.6 1169.18  4939.0 1169.00  4945.0 1166.03
  4960.0 1163.86  4960.4 1163.36  4964.3 1163.36  4964.6 1163.86  4967.8 1164.37
  4977.8 1163.90  4985.6 1164.48  5002.3 1163.96  5009.7 1165.34  5039.3 1166.22
  5044.3 1165.51  5060.1 1165.75  5070.2 1166.57  5090.3 1169.38  5100.4 1171.62
  5120.5 1177.55  5127.0 1180.23  5140.6 1183.18  5150.7 1184.37  5170.9 1185.59
#Mann=3,-1,0
  4802.8    0.12       0  4960.0    0.05       0  4964.6    0.12       0
Bank Sta=4960,4964.6
Exp/Cntr=0.3,0.1

Type RM Length L Ch R = 1,3804,498,498,498
BEGIN DESCRIPTION:
Cypress Tributary 4 2.0
END DESCRIPTION:
XS GIS Cut Line= 3
      2151125.01     13882225.00      2150754.88     13882044.95
      2150249.40     13882102.97
#Sta/Elev= 30
  4588.4 1185.36  4647.6 1182.40  4670.1 1179.29  4677.4 1177.37  4687.1 1175.90
  4715.2 1172.94  4721.9 1171.03  4732.2 1169.30  4744.1 1168.34  4767.1 1167.61
  4866.4 1164.88  4967.7 1160.03  4985.8 1158.50  4991.4 1158.53  4994.8 1157.84
  4994.9 1157.82  4995.2 1157.32  4999.2 1157.32  4999.5 1157.82  5009.9 1158.28
  5044.7 1164.55  5050.2 1166.06  5120.7 1167.77  5211.3 1171.03  5223.0 1171.99
  5271.7 1172.63  5376.9 1176.52  5422.6 1178.15  5476.4 1181.82  5508.8 1182.62
#Mann=8,-1,0
  4588.4    0.12       0  4767.1    0.07       0  4967.7    0.12       0
  4994.8    0.07       0  4994.9    0.05       0  4999.5    0.07       0
  5376.9   0.035       0  5476.4    0.07       0
Bank Sta=4994.9,4999.5
Exp/Cntr=0.3,0.1

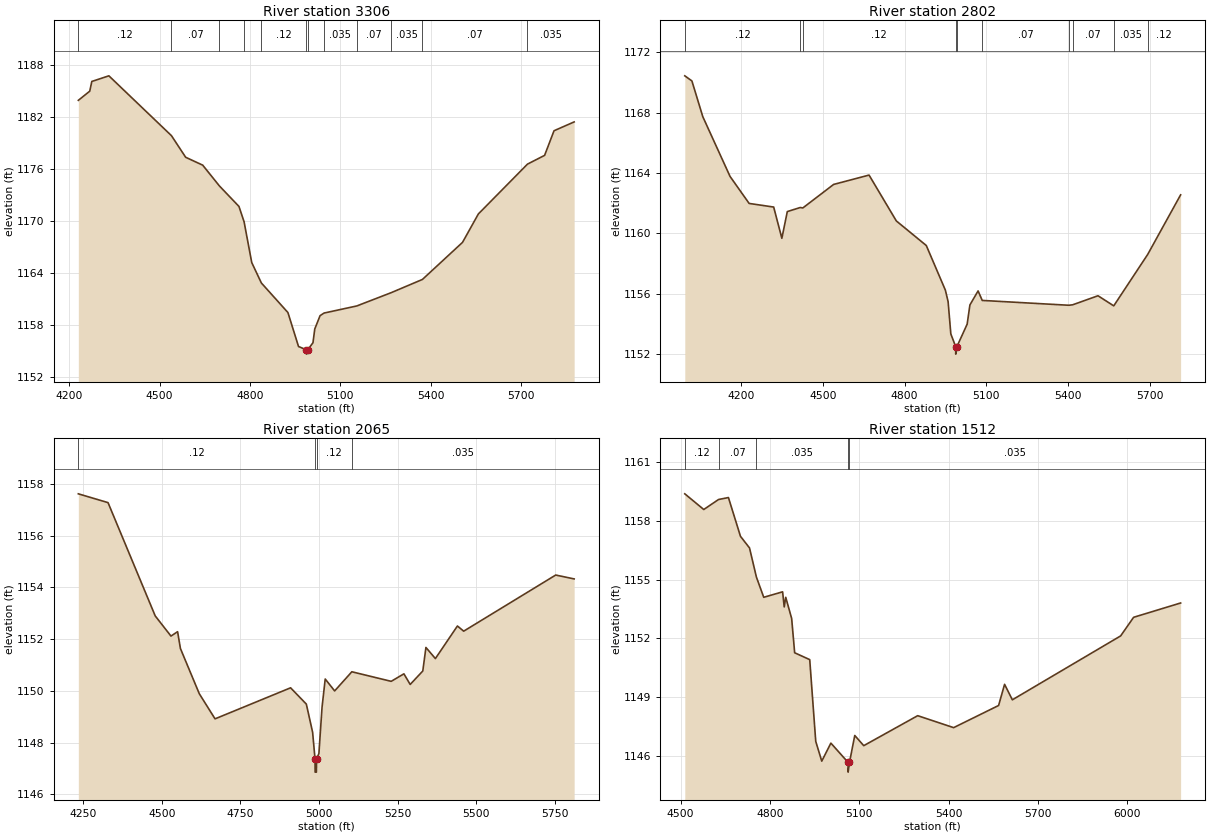
Type RM Length L Ch R = 1,3306,504,504,504
BEGIN DESCRIPTION:
Cypress Tributary 4 1.0
END DESCRIPTION:
XS GIS Cut Line= 3
      2151457.13     13882186.39      2150928.76     13881626.56
      2150125.03     13881974.99
#Sta/Elev= 30
  4230.2 1183.89  4268.1 1184.95  4275.0 1186.07  4331.6 1186.72  4539.4 1179.81
  4586.5 1177.32  4643.1 1176.41  4698.5 1174.01  4763.3 1171.65  4780.3 1169.89
  4805.8 1165.17  4837.8 1162.81  4925.9 1159.40  4961.1 1155.48  4987.1 1155.10
  4987.4 1154.60  4991.8 1155.10  5009.1 1155.92  5015.0 1157.50  5032.6 1159.04
  5045.8 1159.34  5154.6 1160.16  5269.2 1161.70  5372.4 1163.22  5505.5 1167.50
  5558.1 1170.78  5721.1 1176.53  5777.9 1177.54  5809.2 1180.38  5876.0 1181.40
#Mann=12,-1,0
  4230.2    0.12       0  4539.4    0.07       0  4698.5    0.12       0
  4780.3    0.07       0  4837.8    0.12       0  4987.1    0.05       0
  4991.8    0.12       0  5045.8   0.035       0  5154.6    0.07       0
  5269.2   0.035       0  5372.4    0.07       0  5721.1   0.035       0
Bank Sta=4987.1,4991.8
Exp/Cntr=0.3,0.1

Type RM Length L Ch R = 1,2802,737,737,737
BEGIN DESCRIPTION:
Cypress Tributary 4 0.3
END DESCRIPTION:
XS GIS Cut Line= 3
      2152081.09     13881196.19      2150497.44     13881162.85
      2150306.00     13881300.18
#Sta/Elev= 30
  3993.6 1170.44  4019.7 1170.10  4059.7 1167.73  4159.7 1163.77  4229.7 1161.98
  4319.8 1161.74  4349.8 1159.67  4369.8 1161.44  4417.3 1161.71  4426.7 1161.68
  4539.8 1163.24  4669.8 1163.86  4769.9 1160.82  4879.9 1159.19  4949.9 1156.23
  4959.9 1155.47  4969.9 1153.33  4987.6 1152.49  4987.9 1151.99  4992.3 1152.49
  5029.9 1153.98  5039.9 1155.25  5069.9 1156.18  5085.2 1155.55  5402.9 1155.23
  5417.1 1155.26  5510.0 1155.86  5567.8 1155.19  5692.4 1158.60  5813.2 1162.55
#Mann=10,-1,0
  3993.6    0.12       0  4417.3    0.07       0  4426.7    0.12       0
  4987.6    0.05       0  4992.3    0.12       0  5085.2    0.07       0
  5402.9   0.035       0  5417.1    0.07       0  5567.8   0.035       0
  5692.4    0.12       0
Bank Sta=4987.6,4992.3
Exp/Cntr=0.3,0.1

Type RM Length L Ch R = 1,2065,553,553,553
BEGIN DESCRIPTION:
Cypress Tributary 4 0.2
END DESCRIPTION:
XS GIS Cut Line= 2
      2151889.33     13880441.88      2150314.10     13880533.56
#Sta/Elev= 30
  4234.2 1157.62  4328.7 1157.28  4478.9 1152.90  4529.0 1152.12  4550.1 1152.29
  4559.1 1151.64  4619.2 1149.89  4669.3 1148.92  4909.7 1150.12  4959.8 1149.49
  4979.8 1148.40  4987.5 1147.36  4987.8 1146.86  4991.8 1146.86  4992.2 1147.36
  4999.8 1147.58  5009.8 1149.37  5019.9 1150.46  5049.9 1150.00  5104.6 1150.74
  5229.8 1150.37  5270.3 1150.66  5290.3 1150.25  5330.4 1150.77  5340.4 1151.68
  5370.5 1151.25  5440.6 1152.51  5460.6 1152.31  5753.4 1154.48  5812.1 1154.33
#Mann=4,-1,0
  4234.2    0.12       0  4987.5    0.05       0  4992.2    0.12       0
  5104.6   0.035       0
Bank Sta=4987.5,4992.2
Exp/Cntr=0.3,0.1

Type RM Length L Ch R = 1,1512,0,0,0
BEGIN DESCRIPTION:
Cypress Tributary 4 0.15
END DESCRIPTION:
XS GIS Cut Line= 4
      2151849.95     13880099.99      2151369.32     13880027.31
      2150762.47     13880097.80      2150310.27     13880442.63
#Sta/Elev= 30
  4513.9 1159.38  4577.6 1158.58  4627.3 1159.09  4660.5 1159.19  4701.0 1157.21
  4731.3 1156.62  4754.5 1155.13  4779.1 1154.10  4842.5 1154.38  4847.9 1153.61
  4853.0 1154.10  4872.9 1153.02  4883.0 1151.27  4933.6 1150.92  4953.8 1146.75
  4974.0 1145.74  5004.7 1146.66  5062.3 1145.68  5062.6 1145.18  5067.2 1145.68
  5084.9 1147.05  5115.1 1146.53  5296.3 1148.06  5417.1 1147.45  5568.1 1148.58
  5588.2 1149.66  5614.3 1148.87  5978.1 1152.13  6021.7 1153.08  6179.6 1153.81
#Mann=5,-1,0
  4513.9    0.12       0  4627.3    0.07       0  4754.5   0.035       0
  5062.3   0.035       0  5067.2   0.035       0
Bank Sta=5062.3,5067.2
Exp/Cntr=0.3,0.1

Chan Stop Cuts=-1