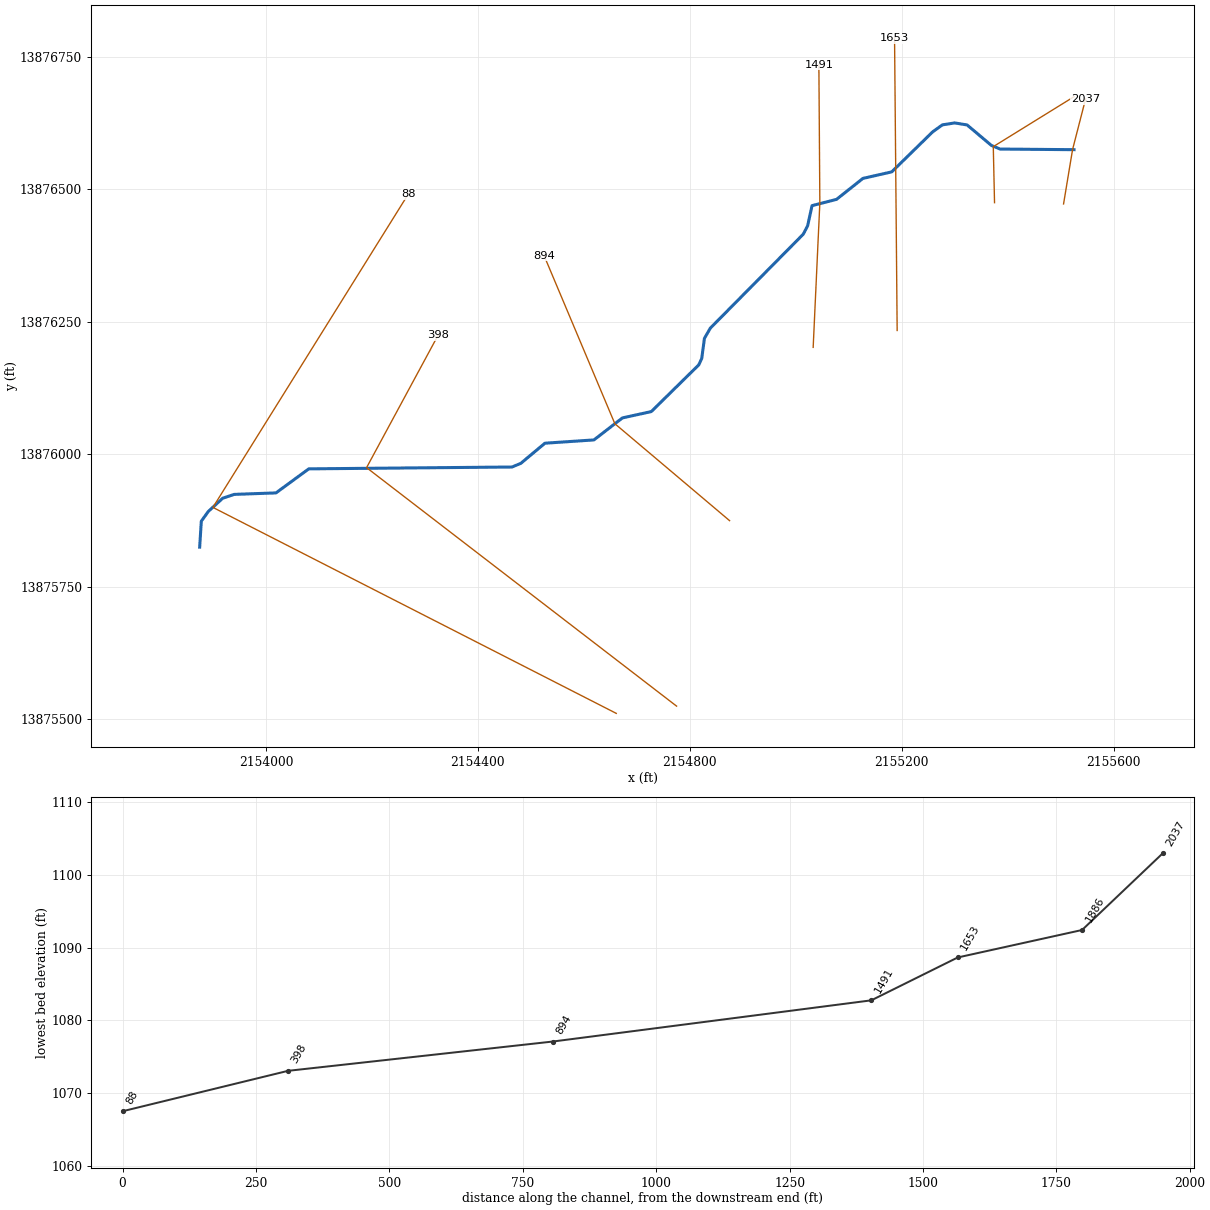
--- Cypress Tributary 5.prj (project) ---

Proj Title=Cypress Tributary 5 Base Level Engineering
Current Plan=p01
Default Exp/Contr=0.3,0.1
English Units
Geom File=g01
Flow File=f01
Plan File=p01
BEGIN DESCRIPTION:
Cypress Tributary 5
END DESCRIPTION:

--- Cypress Tributary 5.p01 (plan) ---

Plan Title=Multiple Run
Short Identifier=Multiple
Geom File=g01
Flow File=f01
Subcritical Flow
K Sum by GR= 0
Std Step Tol= 0.01
Critical Tol= 0.01
Num of Std Step Trials= 20
Max Error Tol= 0.3
Flow Tol Ratio= 0.001
Split Flow NTrial= 30
Split Flow Tol= 0.02
Split Flow Ratio= 0.02
Log Output Level= 0
Friction Slope Method= 1
Unsteady Friction Slope Method= 2
Unsteady Bridges Friction Slope Method= 1
Parabolic Critical Depth
Global Vel Dist=  1 , 1 , 1
Global Log Level= 0
CheckData=True
Encroach Param= -1, 0, 0, 0
BEGIN DESCRIPTION:
Multiple Run
END DESCRIPTION:

--- Cypress Tributary 5.f01 (steady flow) ---

Flow Title=Multiple
Number of Profiles=7
Profile Names=10-year,25-year,50-year,1pct_min,100-year,1pct_plu,500-year
River Rch & RM= Cypress Tributar,Reach-1,2037
     723    1208    1664    1113    2221    4431    3910
River Rch & RM= Cypress Tributar,Reach-1,1653
    1147    1970    2763    1879    3748    7479    6827
Boundary for River Rch & Prof#=Cypress Tributar,Reach-1,1
Up Type=0
Dn Type=3
Dn Slope=0.005
Boundary for River Rch & Prof#=Cypress Tributar,Reach-1,2
Up Type=0
Dn Type=3
Dn Slope=0.005
Boundary for River Rch & Prof#=Cypress Tributar,Reach-1,3
Up Type=0
Dn Type=3
Dn Slope=0.005
Boundary for River Rch & Prof#=Cypress Tributar,Reach-1,4
Up Type=0
Dn Type=3
Dn Slope=0.005
Boundary for River Rch & Prof#=Cypress Tributar,Reach-1,5
Up Type=0
Dn Type=3
Dn Slope=0.005
Boundary for River Rch & Prof#=Cypress Tributar,Reach-1,6
Up Type=0
Dn Type=3
Dn Slope=0.005
Boundary for River Rch & Prof#=Cypress Tributar,Reach-1,7
Up Type=0
Dn Type=3
Dn Slope=0.005

--- Cypress Tributary 5.g01 (geometry) ---

Geom Title=Existing Conditions

River Reach=Cypress Tributar,Reach-1
Reach XY= 30
      2155525.00     13876575.00      2155385.48     13876576.19
      2155368.92     13876583.18      2155323.25     13876621.66
      2155299.96     13876625.50      2155276.64     13876621.86
      2155258.34     13876608.75      2155181.05     13876533.16
      2155126.71     13876520.82      2155076.85     13876481.24
      2155030.61     13876469.41      2155022.31     13876431.44
      2155014.11     13876415.59      2154838.63     13876238.21
      2154827.54     13876218.95      2154822.47     13876181.04
      2154816.85     13876168.93      2154727.31     13876080.82
      2154672.83     13876068.86      2154619.03     13876027.33
      2154526.60     13876021.14      2154481.06     13875983.14
      2154464.50     13875976.22      2154080.94     13875972.74
      2154019.02     13875927.36      2153940.11     13875924.54
      2153918.55     13875917.36      2153891.31     13875892.34
      2153878.12     13875874.01      2153875.00     13875825.00

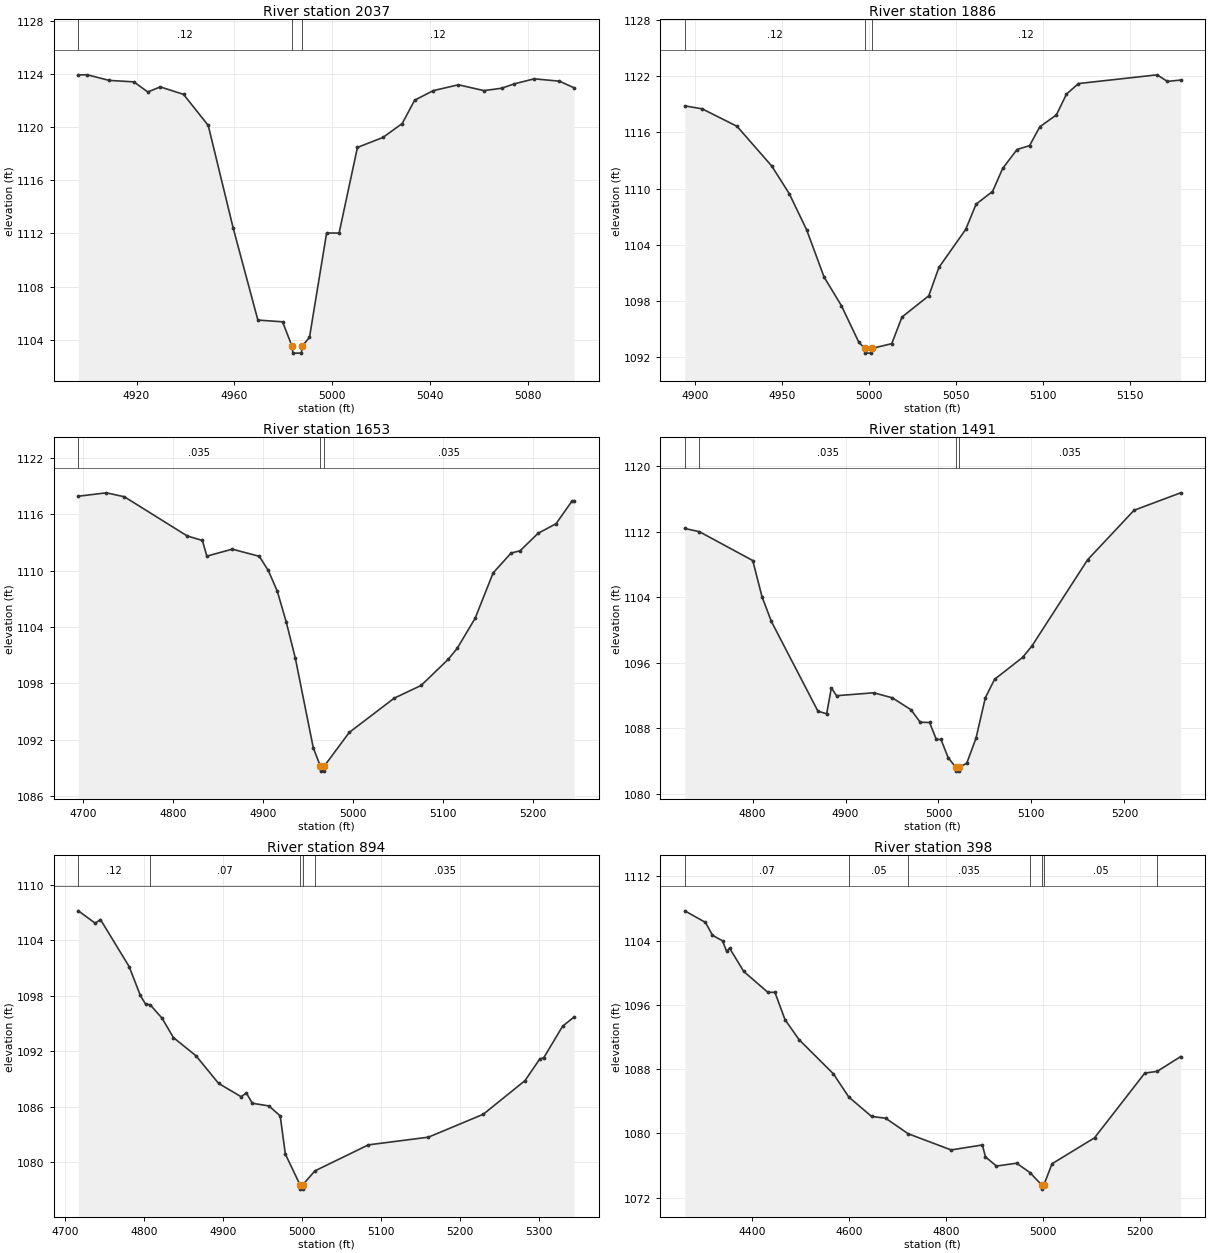
Type RM Length L Ch R = 1,2037,151,151,151
BEGIN DESCRIPTION:
Cypress Tributary 5 5.0
END DESCRIPTION:
XS GIS Cut Line= 3
      2155505.25     13876472.59      2155522.28     13876575.36
      2155546.84     13876670.78
#Sta/Elev= 30
  4896.2 1123.95  4899.9 1123.95  4908.8 1123.53  4918.9 1123.42  4924.6 1122.66
  4929.7 1123.04  4939.2 1122.48  4949.3 1120.14  4959.5 1112.41  4969.6 1105.47
  4979.7 1105.34  4983.6 1103.48  4983.9 1102.98  4987.4 1102.98  4987.6 1103.48
  4990.7 1104.17  4997.7 1112.03  5002.8 1112.03  5010.3 1118.48  5020.7 1119.23
  5028.6 1120.28  5033.7 1122.04  5041.3 1122.76  5051.6 1123.20  5062.0 1122.76
  5069.3 1122.94  5074.4 1123.27  5082.6 1123.65  5092.9 1123.47  5098.9 1122.97
#Mann=3,-1,0
  4896.2    0.12       0  4983.6    0.05       0  4987.6    0.12       0
Bank Sta=4983.6,4987.6
Exp/Cntr=0.3,0.1

Type RM Length L Ch R = 1,1886,233,233,233
BEGIN DESCRIPTION:
Cypress Tributary 5 4.0
END DESCRIPTION:
XS GIS Cut Line= 3
      2155375.00     13876474.99      2155372.64     13876580.77
      2155524.96     13876674.98
#Sta/Elev= 30
  4894.2 1118.82  4904.2 1118.50  4924.2 1116.64  4944.2 1112.39  4954.2 1109.46
  4964.2 1105.60  4974.2 1100.57  4984.2 1097.50  4994.2 1093.60  4997.6 1092.94
  4997.9 1092.44  5001.4 1092.44  5001.6 1092.94  5013.1 1093.45  5019.0 1096.29
  5034.4 1098.56  5040.2 1101.58  5055.6 1105.64  5061.6 1108.34  5071.0 1109.68
  5076.9 1112.16  5085.1 1114.16  5092.3 1114.58  5098.2 1116.59  5107.7 1117.85
  5113.5 1120.07  5120.4 1121.20  5165.6 1122.13  5171.5 1121.43  5179.1 1121.57
#Mann=3,-1,0
  4894.2    0.12       0  4997.6    0.05       0  5001.6    0.12       0
Bank Sta=4997.6,5001.6
Exp/Cntr=0.3,0.1

Type RM Length L Ch R = 1,1653,162,162,162
BEGIN DESCRIPTION:
Cypress Tributary 5 3.5
END DESCRIPTION:
XS GIS Cut Line= 2
      2155191.24     13876233.85      2155186.33     13876785.12
#Sta/Elev= 30
  4694.9 1117.94  4726.1 1118.30  4746.1 1117.88  4816.1 1113.70  4832.8 1113.23
  4837.8 1111.56  4866.1 1112.30  4896.1 1111.54  4906.1 1110.03  4916.1 1107.83
  4926.1 1104.53  4936.1 1100.73  4956.1 1091.16  4964.1 1089.16  4964.3 1088.66
  4967.8 1088.66  4968.1 1089.16  4996.1 1092.78  5046.1 1096.43  5076.1 1097.79
  5106.1 1100.56  5116.1 1101.73  5136.1 1104.94  5156.1 1109.77  5176.1 1111.89
  5186.1 1112.13  5206.1 1113.99  5226.1 1115.01  5243.6 1117.40  5246.2 1117.40
#Mann=3,-1,0
  4694.9   0.035       0  4964.1   0.035       0  4968.1   0.035       0
Bank Sta=4964.1,4968.1
Exp/Cntr=0.3,0.1

Type RM Length L Ch R = 1,1491,597,597,597
BEGIN DESCRIPTION:
Cypress Tributary 5 3.0
END DESCRIPTION:
XS GIS Cut Line= 3
      2155032.75     13876201.98      2155045.34     13876474.59
      2155043.52     13876735.09
#Sta/Elev= 30
  4727.1 1112.40  4742.9 1112.00  4800.2 1108.48  4810.2 1104.05  4820.2 1101.05
  4870.3 1090.09  4879.7 1089.76  4884.8 1092.94  4890.3 1091.97  4930.3 1092.33
  4950.4 1091.71  4970.4 1090.26  4980.4 1088.73  4990.4 1088.70  4997.7 1086.63
  5002.7 1086.63  5010.4 1084.41  5018.4 1083.26  5018.7 1082.76  5022.2 1082.76
  5022.4 1083.26  5030.4 1083.72  5040.4 1086.79  5050.4 1091.72  5060.4 1093.98
  5090.4 1096.64  5100.4 1098.02  5160.4 1108.57  5210.4 1114.62  5260.5 1116.75
#Mann=4,-1,0
  4727.1   0.063       0  4742.9   0.035       0  5018.4   0.035       0
  5022.4   0.035       0
Bank Sta=5018.4,5022.4
Exp/Cntr=0.3,0.1

Type RM Length L Ch R = 1,894,496,496,496
BEGIN DESCRIPTION:
Cypress Tributary 5 2.0
END DESCRIPTION:
XS GIS Cut Line= 3
      2154875.00     13875875.00      2154658.52     13876057.89
      2154524.99     13876375.03
#Sta/Elev= 30
  4716.6 1107.20  4738.0 1105.86  4744.6 1106.26  4780.9 1101.17  4795.1 1098.04
  4801.8 1097.09  4807.4 1097.05  4822.6 1095.58  4836.9 1093.49  4865.5 1091.52
  4894.1 1088.53  4922.6 1087.09  4929.2 1087.49  4936.9 1086.38  4957.8 1086.09
  4972.1 1085.01  4978.6 1080.88  4997.0 1077.59  4997.3 1077.09  5000.8 1077.09
  5001.0 1077.59  5015.9 1079.06  5083.7 1081.88  5159.6 1082.71  5229.1 1085.19
  5282.0 1088.84  5300.3 1091.14  5305.8 1091.33  5329.5 1094.72  5344.1 1095.72
#Mann=5,-1,0
  4716.6    0.12       0  4807.4    0.07       0  4997.0    0.05       0
  5001.0    0.07       0  5015.9   0.035       0
Bank Sta=4997,5001
Exp/Cntr=0.3,0.1

Type RM Length L Ch R = 1,398,310,310,310
BEGIN DESCRIPTION:
Cypress Tributary 5 1.0
END DESCRIPTION:
XS GIS Cut Line= 3
      2154775.01     13875525.00      2154189.98     13875975.04
      2154325.00     13876225.00
#Sta/Elev= 30
  4261.9 1107.71  4304.5 1106.27  4319.0 1104.67  4339.8 1103.97  4348.0 1102.67
  4354.3 1103.06  4383.3 1100.17  4433.2 1097.56  4447.7 1097.57  4468.5 1094.16
  4497.5 1091.67  4568.2 1087.42  4600.1 1084.52  4647.0 1082.11  4676.0 1081.89
  4722.3 1079.96  4811.0 1077.94  4875.4 1078.56  4881.7 1077.08  4904.4 1075.93
  4946.0 1076.29  4973.5 1075.12  4998.0 1073.56  4998.2 1073.06  5002.0 1073.56
  5019.0 1076.22  5106.6 1079.45  5210.3 1087.51  5235.7 1087.72  5284.1 1089.56
#Mann=7,-1,0
  4261.9    0.07       0  4600.1    0.05       0  4722.3   0.035       0
  4973.5    0.05       0  4998.0    0.05       0  5002.0    0.05       0
  5235.7   0.035       0
Bank Sta=4998,5002
Exp/Cntr=0.3,0.1

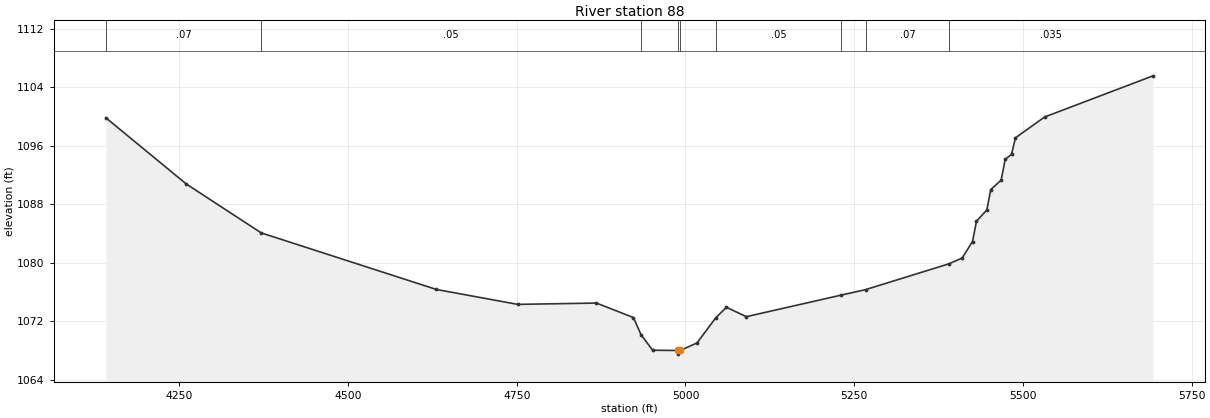
Type RM Length L Ch R = 1,88,0,0,0
BEGIN DESCRIPTION:
Cypress Tributary 5 0.5
END DESCRIPTION:
XS GIS Cut Line= 3
      2154661.17     13875511.33      2153900.00     13875900.00
      2154268.81     13876491.36
#Sta/Elev= 30
  4141.2 1099.80  4260.4 1090.75  4371.4 1084.07  4630.9 1076.34  4751.4 1074.30
  4868.1 1074.48  4922.9 1072.50  4934.2 1070.14  4951.4 1068.03  4988.2 1068.00
  4988.5 1067.50  4992.2 1068.00  5017.1 1069.03  5045.1 1072.49  5060.7 1073.90
  5090.2 1072.62  5230.4 1075.56  5267.0 1076.32  5390.6 1079.85  5410.0 1080.64
  5425.3 1082.89  5431.2 1085.67  5446.5 1087.20  5452.4 1090.00  5467.8 1091.28
  5473.7 1094.12  5483.1 1094.81  5489.0 1097.07  5532.1 1099.91  5692.8 1105.54
#Mann=9,-1,0
  4141.2    0.07       0  4371.4    0.05       0  4934.2   0.035       0
  4988.2   0.035       0  4992.2   0.035       0  5045.1    0.05       0
  5230.4   0.035       0  5267.0    0.07       0  5390.6   0.035       0
Bank Sta=4988.2,4992.2
Exp/Cntr=0.3,0.1

Chan Stop Cuts=-1