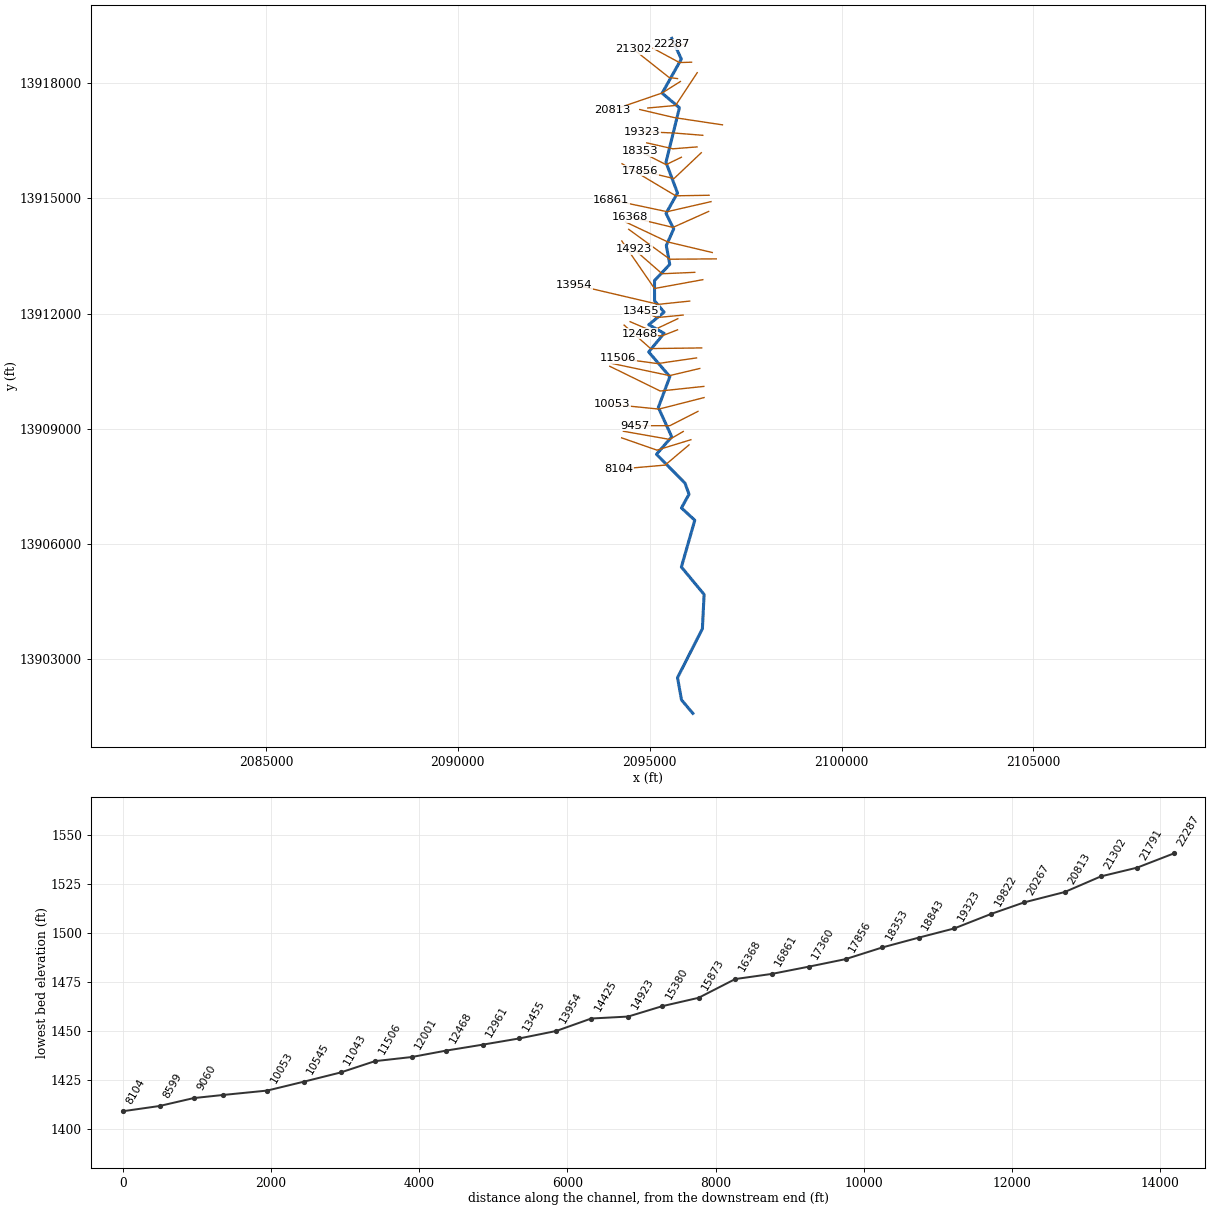
--- DRY CREEK 1.prj (project) ---

Proj Title=DRY CREEK 1 Base Level Engineering
Current Plan=p01
Default Exp/Contr=0.3,0.1
English Units
Geom File=g01
Flow File=f01
Plan File=p01
BEGIN DESCRIPTION:
DRY CREEK 1
END DESCRIPTION:

--- DRY CREEK 1.p01 (plan) ---

Plan Title=Multiple Run
Short Identifier=Multiple
Geom File=g01
Flow File=f01
Subcritical Flow
K Sum by GR= 0
Std Step Tol= 0.01
Critical Tol= 0.01
Num of Std Step Trials= 20
Max Error Tol= 0.3
Flow Tol Ratio= 0.001
Split Flow NTrial= 30
Split Flow Tol= 0.02
Split Flow Ratio= 0.02
Log Output Level= 0
Friction Slope Method= 1
Unsteady Friction Slope Method= 2
Unsteady Bridges Friction Slope Method= 1
Parabolic Critical Depth
Global Vel Dist=  1 , 1 , 1
Global Log Level= 0
CheckData=True
Encroach Param= -1, 0, 0, 0
BEGIN DESCRIPTION:
Multiple Run
END DESCRIPTION:

--- DRY CREEK 1.f01 (steady flow) ---

Flow Title=Multiple
Number of Profiles=7
Profile Names=10-year,25-year,50-year,1pct_min,100-year,1pct_plu,500-year
River Rch & RM= DRY CREEK 1,Reach-1,22287
    1335    2335    3318    2290    4568    9115    8584
River Rch & RM= DRY CREEK 1,Reach-1,20267
    1944    3449    4947    3438    6861   13689   13087
River Rch & RM= DRY CREEK 1,Reach-1,14923
    2740    4895    7050    4906    9789   19532   18695
River Rch & RM= DRY CREEK 1,Reach-1,7115
    3012    5368    7718    5359   10693   21335   20326
Boundary for River Rch & Prof#=DRY CREEK 1,Reach-1,1
Up Type=0
Dn Type=3
Dn Slope=0.005
Boundary for River Rch & Prof#=DRY CREEK 1,Reach-1,2
Up Type=0
Dn Type=3
Dn Slope=0.005
Boundary for River Rch & Prof#=DRY CREEK 1,Reach-1,3
Up Type=0
Dn Type=3
Dn Slope=0.005
Boundary for River Rch & Prof#=DRY CREEK 1,Reach-1,4
Up Type=0
Dn Type=3
Dn Slope=0.005
Boundary for River Rch & Prof#=DRY CREEK 1,Reach-1,5
Up Type=0
Dn Type=3
Dn Slope=0.005
Boundary for River Rch & Prof#=DRY CREEK 1,Reach-1,6
Up Type=0
Dn Type=3
Dn Slope=0.005
Boundary for River Rch & Prof#=DRY CREEK 1,Reach-1,7
Up Type=0
Dn Type=3
Dn Slope=0.005

--- DRY CREEK 1.g01 (geometry) ---

Geom Title=Existing Conditions

River Reach=DRY CREEK 1,Reach-1
Reach XY= 30
      2095575.00     13919175.00      2095823.75     13918634.70
      2095324.62     13917745.27      2095774.52     13917364.51
      2095424.27     13915943.25      2095724.81     13915143.28
      2095425.53     13914611.14      2095625.05     13914205.02
      2095432.56     13913775.00      2095522.83     13913280.44
      2095125.33     13912859.97      2095127.00     13912330.68
      2095374.46     13912035.63      2094975.24     13911709.78
      2095374.32     13911484.84      2094974.51     13910997.77
      2095525.48     13910354.84      2095224.72     13909552.16
      2095573.95     13908785.43      2095177.02     13908330.31
      2095919.27     13907577.55      2096024.65     13907288.78
      2095827.25     13906930.94      2096174.76     13906610.90
      2095825.23     13905391.01      2096417.69     13904675.11
      2096372.93     13903780.86      2095725.14     13902506.75
      2095828.46     13901926.25      2096125.00     13901575.00

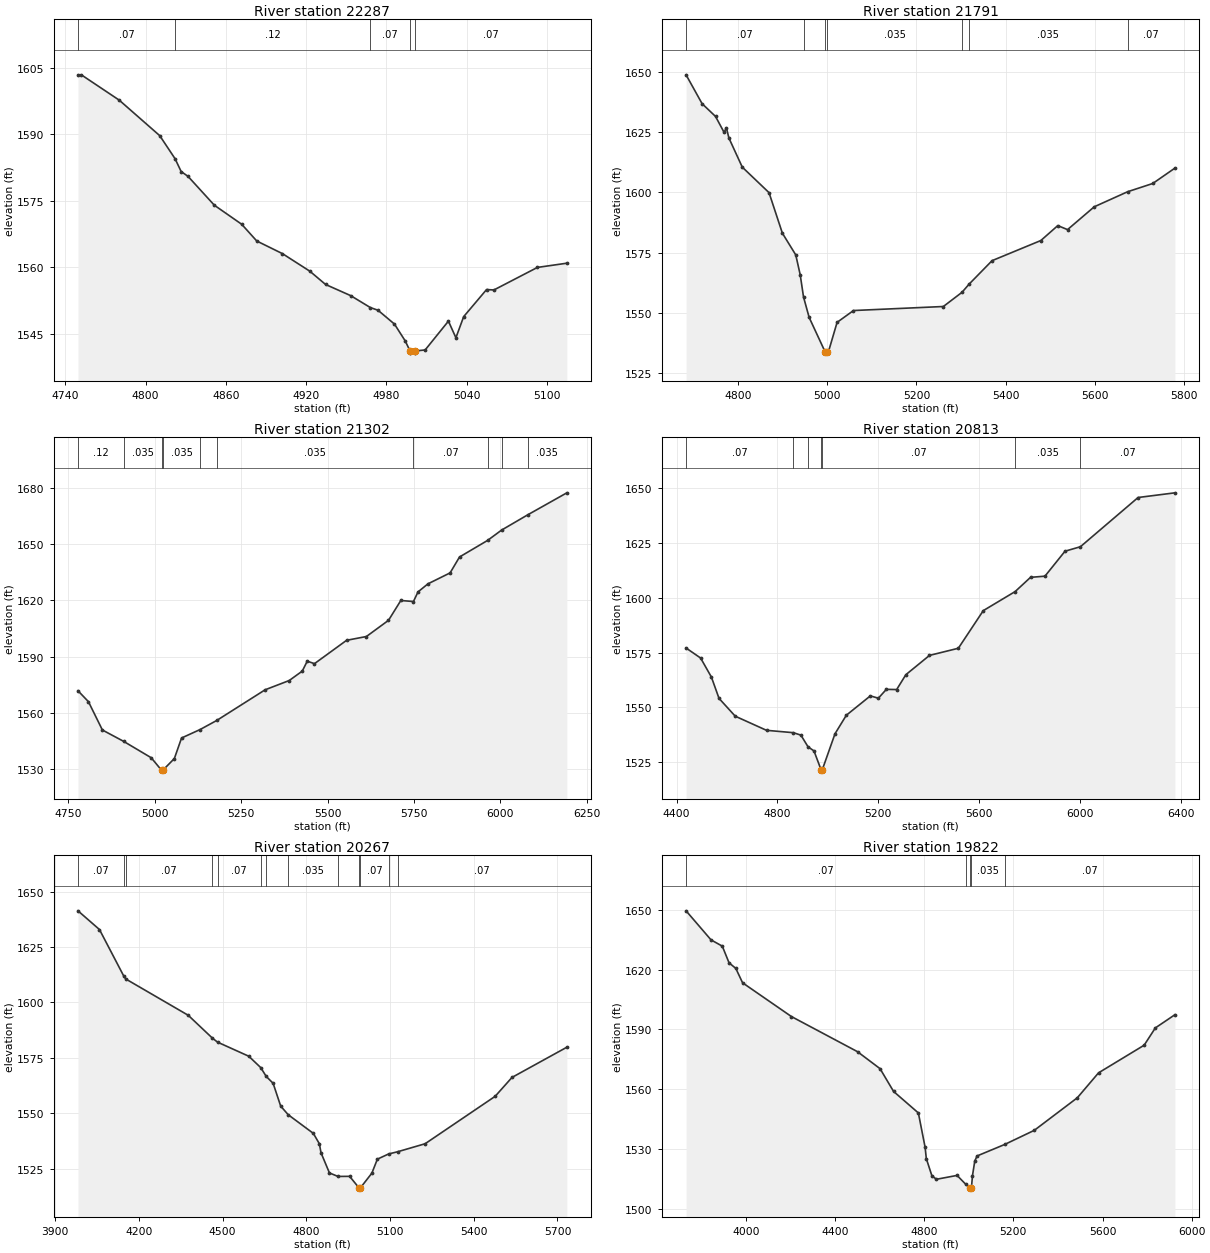
Type RM Length L Ch R = 1,22287,496,496,496
BEGIN DESCRIPTION:
DRY CREEK_1_DS 44.0
END DESCRIPTION:
XS GIS Cut Line= 3
      2095924.97     13919024.99      2095679.16     13918976.72
      2095575.00     13919025.00
#Sta/Elev= 30
  4749.5 1603.38  4752.0 1603.38  4780.3 1597.68  4810.6 1589.67  4822.0 1584.50
  4826.6 1581.59  4831.7 1580.51  4851.4 1574.00  4871.8 1569.72  4883.1 1565.94
  4902.3 1563.09  4922.7 1559.15  4934.5 1556.15  4953.3 1553.63  4968.0 1550.94
  4973.7 1550.34  4986.0 1547.22  4994.0 1543.44  4997.6 1541.18  4997.8 1540.68
  5001.3 1540.68  5001.6 1541.18  5008.9 1541.39  5026.3 1547.89  5031.9 1544.14
  5037.7 1548.90  5054.8 1555.00  5060.3 1554.91  5092.8 1559.99  5114.8 1560.94
#Mann=5,-1,0
  4749.5    0.07       0  4822.0    0.12       0  4968.0    0.07       0
  4997.6    0.05       0  5001.6    0.07       0
Bank Sta=4997.6,5001.6
Exp/Cntr=0.3,0.1

Type RM Length L Ch R = 1,21791,489,489,489
BEGIN DESCRIPTION:
DRY CREEK_1_DS 43.0
END DESCRIPTION:
XS GIS Cut Line= 3
      2096091.03     13918552.60      2095774.41     13918543.43
      2095088.68     13918915.03
#Sta/Elev= 30
  4683.2 1648.73  4719.2 1636.76  4749.3 1631.49  4768.6 1624.85  4773.6 1626.83
  4779.3 1622.55  4809.3 1610.48  4869.3 1599.91  4899.3 1583.10  4929.3 1574.11
  4939.3 1565.85  4946.7 1556.67  4959.3 1548.21  4995.2 1533.91  4995.4 1533.41
  4999.2 1533.91  5002.5 1533.91  5022.0 1546.16  5058.8 1551.06  5260.4 1552.73
  5302.3 1558.62  5317.9 1561.95  5369.7 1571.73  5479.1 1580.07  5517.1 1586.25
  5539.0 1584.59  5598.9 1594.05  5673.8 1600.29  5730.1 1603.70  5779.9 1610.08
#Mann=7,-1,0
  4683.2    0.07       0  4946.7   0.035       0  4995.2   0.035       0
  4999.2   0.035       0  5302.3    0.07       0  5317.9   0.035       0
  5673.8    0.07       0
Bank Sta=4995.2,4999.2
Exp/Cntr=0.3,0.1

Type RM Length L Ch R = 1,21302,489,489,489
BEGIN DESCRIPTION:
DRY CREEK_1_DS 42.0
END DESCRIPTION:
XS GIS Cut Line= 3
      2095724.95     13918125.01      2095504.51     13918155.20
      2094570.68     13918896.19
#Sta/Elev= 30
  4777.5 1571.79  4807.7 1565.99  4848.1 1550.88  4909.4 1544.84  4989.4 1536.09
  5019.2 1529.45  5019.4 1528.95  5023.2 1529.45  5056.4 1535.67  5077.2 1546.61
  5130.9 1551.13  5179.0 1555.96  5319.1 1572.32  5388.7 1577.25  5426.5 1582.28
  5440.9 1587.58  5461.8 1586.24  5554.7 1598.69  5612.1 1600.72  5676.0 1609.34
  5711.7 1619.92  5748.2 1619.37  5761.4 1624.50  5790.2 1628.80  5854.3 1634.64
  5881.5 1643.11  5962.6 1651.93  6003.2 1657.45  6078.7 1665.57  6192.1 1677.32
#Mann=10,-1,0
  4777.5    0.12       0  4909.4   0.035       0  5019.2   0.035       0
  5023.2   0.035       0  5130.9    0.12       0  5179.0   0.035       0
  5748.2    0.07       0  5962.6   0.035       0  6003.2    0.07       0
  6078.7   0.035       0
Bank Sta=5019.2,5023.2
Exp/Cntr=0.3,0.1

Type RM Length L Ch R = 1,20813,546,546,546
BEGIN DESCRIPTION:
DRY CREEK_1_DS 41.0
END DESCRIPTION:
XS GIS Cut Line= 3
      2095800.01     13918050.01      2095324.48     13917750.12
      2094022.81     13917302.12
#Sta/Elev= 30
  4437.8 1577.05  4495.5 1572.48  4538.3 1563.81  4568.5 1554.10  4632.9 1545.98
  4756.8 1539.55  4863.5 1538.47  4893.3 1537.35  4921.6 1532.02  4945.1 1530.17
  4973.6 1521.46  4973.9 1520.96  4977.7 1521.46  5028.5 1537.99  5073.5 1546.43
  5168.7 1555.24  5200.4 1554.18  5232.1 1558.21  5273.0 1558.12  5309.5 1564.89
  5403.2 1573.68  5517.6 1576.93  5616.5 1594.07  5742.9 1602.76  5803.9 1609.24
  5861.1 1609.77  5940.7 1621.15  6001.7 1623.18  6230.5 1645.61  6376.6 1647.74
#Mann=7,-1,0
  4437.8    0.07       0  4863.5   0.035       0  4921.6    0.07       0
  4973.6    0.05       0  4977.7    0.07       0  5742.9   0.035       0
  6001.7    0.07       0
Bank Sta=4973.6,4977.7
Exp/Cntr=0.3,0.1

Type RM Length L Ch R = 1,20267,445,445,445
BEGIN DESCRIPTION:
DRY CREEK_1_DS 40.0
END DESCRIPTION:
XS GIS Cut Line= 3
      2096237.85     13918279.28      2095675.00     13917425.00
      2094949.19     13917358.26
#Sta/Elev= 30
  3981.7 1641.33  4058.7 1632.88  4146.4 1611.72  4153.5 1610.52  4376.8 1594.17
  4463.7 1583.82  4481.9 1582.04  4593.7 1575.69  4636.5 1570.57  4656.2 1566.59
  4681.0 1563.46  4708.1 1553.18  4735.1 1549.27  4825.1 1540.86  4846.7 1536.17
  4852.6 1532.11  4882.8 1523.00  4913.4 1521.42  4955.1 1521.46  4989.2 1516.19
  4989.4 1515.69  4993.3 1516.19  5034.9 1522.91  5054.6 1529.22  5094.9 1531.57
  5126.9 1532.55  5225.7 1536.18  5476.7 1557.59  5537.0 1566.12  5733.6 1579.76
#Mann=13,-1,0
  3981.7    0.07       0  4146.4   0.035       0  4153.5    0.07       0
  4463.7   0.035       0  4481.9    0.07       0  4636.5   0.035       0
  4656.2    0.07       0  4735.1   0.035       0  4913.4    0.07       0
  4989.2    0.05       0  4993.3    0.07       0  5094.9   0.035       0
  5126.9    0.07       0
Bank Sta=4989.2,4993.3
Exp/Cntr=0.3,0.1

Type RM Length L Ch R = 1,19822,499,499,499
BEGIN DESCRIPTION:
DRY CREEK_1_DS 39.0
END DESCRIPTION:
XS GIS Cut Line= 3
      2096895.76     13916919.37      2095641.21     13917108.33
      2094740.55     13917319.14
#Sta/Elev= 30
  3731.3 1649.55  3843.3 1634.96  3893.9 1631.81  3924.2 1623.44  3954.5 1620.65
  3984.9 1613.41  4203.9 1596.48  4500.6 1578.82  4601.8 1570.29  4662.4 1558.87
  4773.7 1548.06  4804.0 1530.81  4809.4 1525.11  4834.4 1516.53  4854.6 1514.75
  4947.4 1516.70  4986.4 1512.23  5007.1 1510.31  5007.4 1509.81  5011.7 1510.31
  5016.6 1516.63  5026.9 1523.94  5037.2 1526.47  5160.7 1532.22  5293.9 1539.33
  5487.0 1555.68  5582.2 1568.20  5786.9 1582.08  5837.1 1590.76  5925.0 1597.39
#Mann=5,-1,0
  3731.3    0.07       0  4986.4   0.035       0  5007.1   0.035       0
  5011.7   0.035       0  5160.7    0.07       0
Bank Sta=5007.1,5011.7
Exp/Cntr=0.3,0.1

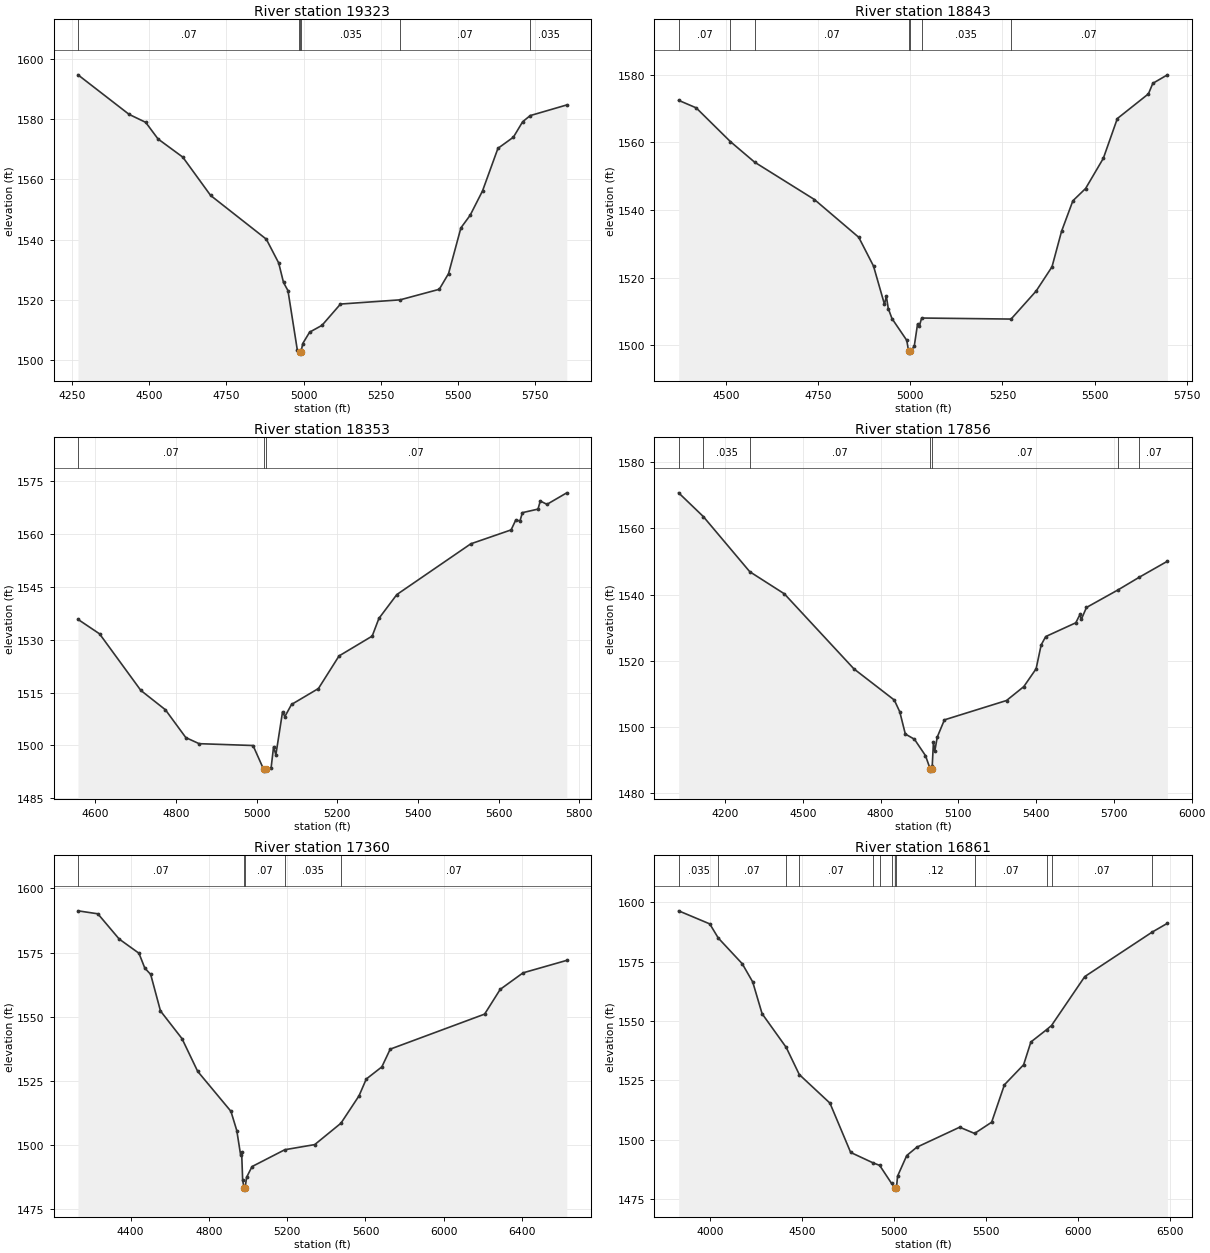
Type RM Length L Ch R = 1,19323,480,480,480
BEGIN DESCRIPTION:
DRY CREEK_1_DS 38.0
END DESCRIPTION:
XS GIS Cut Line= 3
      2096383.75     13916646.65      2095654.59     13916705.17
      2094802.07     13916743.77
#Sta/Elev= 30
  4268.5 1594.72  4434.1 1581.61  4488.0 1578.96  4528.1 1573.44  4608.3 1567.42
  4698.6 1554.70  4879.2 1540.19  4919.3 1532.30  4934.9 1525.83  4949.4 1523.12
  4979.5 1503.55  4985.7 1503.02  4987.2 1502.89  4987.6 1502.39  4991.9 1502.89
  4997.3 1505.57  5019.6 1509.35  5059.7 1511.61  5119.7 1518.67  5313.0 1520.07
  5440.0 1523.57  5470.1 1528.79  5510.1 1543.94  5540.1 1548.13  5580.2 1556.21
  5630.2 1570.33  5680.3 1574.03  5710.3 1579.15  5734.7 1581.19  5853.4 1584.73
#Mann=6,-1,0
  4268.5    0.07       0  4985.7   0.035       0  4987.2   0.035       0
  4991.9   0.035       0  5313.0    0.07       0  5734.7   0.035       0
Bank Sta=4987.2,4991.9
Exp/Cntr=0.3,0.1

Type RM Length L Ch R = 1,18843,490,490,490
BEGIN DESCRIPTION:
DRY CREEK_1_DS 37.0
END DESCRIPTION:
XS GIS Cut Line= 3
      2096232.48     13916344.31      2095605.23     13916294.83
      2094924.70     13916449.55
#Sta/Elev= 30
  4370.8 1572.42  4418.4 1570.20  4511.5 1560.20  4577.1 1554.14  4739.4 1543.10
  4859.8 1531.93  4899.9 1523.42  4929.7 1512.10  4934.7 1514.52  4940.0 1510.85
  4950.1 1507.89  4990.2 1501.46  4995.3 1498.18  4995.6 1497.68  5000.0 1498.18
  5010.5 1499.72  5019.5 1506.28  5024.6 1505.76  5030.6 1508.06  5273.4 1507.75
  5341.4 1516.03  5384.5 1523.19  5410.4 1533.68  5441.2 1542.72  5475.7 1546.35
  5523.9 1555.28  5561.9 1567.03  5646.3 1574.33  5658.2 1577.44  5697.9 1579.96
#Mann=7,-1,0
  4370.8    0.07       0  4511.5   0.035       0  4577.1    0.07       0
  4995.3    0.05       0  5000.0    0.07       0  5030.6   0.035       0
  5273.4    0.07       0
Bank Sta=4995.3,5000
Exp/Cntr=0.3,0.1

Type RM Length L Ch R = 1,18353,497,497,497
BEGIN DESCRIPTION:
DRY CREEK_1_DS 36.0
END DESCRIPTION:
XS GIS Cut Line= 3
      2095824.99     13916074.99      2095426.87     13915880.69
      2094742.10     13916230.17
#Sta/Elev= 30
  4557.0 1535.76  4610.5 1531.65  4712.8 1515.60  4773.8 1510.10  4824.4 1502.20
  4857.4 1500.48  4991.0 1499.96  5017.3 1493.19  5017.7 1492.69  5022.1 1493.19
  5035.8 1493.61  5041.9 1499.59  5047.6 1497.33  5064.2 1509.55  5069.8 1508.15
  5086.4 1511.61  5153.1 1516.13  5204.2 1525.38  5286.4 1531.01  5303.0 1536.02
  5347.5 1542.80  5530.9 1557.20  5630.8 1561.15  5642.0 1563.87  5653.0 1563.74
  5658.7 1566.04  5697.5 1567.05  5703.1 1569.35  5719.7 1568.40  5768.8 1571.67
#Mann=3,-1,0
  4557.0    0.07       0  5017.3    0.05       0  5022.1    0.07       0
Bank Sta=5017.3,5022.1
Exp/Cntr=0.3,0.1

Type RM Length L Ch R = 1,17856,496,496,496
BEGIN DESCRIPTION:
DRY CREEK_1_DS 35.0
END DESCRIPTION:
XS GIS Cut Line= 3
      2096344.04     13916192.19      2095633.14     13915518.94
      2094750.97     13915727.53
#Sta/Elev= 30
  4020.9 1570.70  4116.0 1563.55  4295.4 1546.89  4428.6 1540.23  4697.2 1517.57
  4852.9 1508.17  4874.0 1504.61  4895.4 1497.92  4930.6 1496.34  4973.1 1491.41
  4992.0 1487.22  4992.4 1486.72  4997.0 1487.22  4999.2 1488.25  5003.9 1495.52
  5009.0 1492.73  5018.6 1497.01  5046.2 1502.19  5285.8 1508.03  5352.4 1512.22
  5399.9 1517.60  5419.4 1524.80  5437.0 1527.33  5553.0 1531.48  5569.0 1533.99
  5574.1 1532.48  5594.1 1536.10  5716.4 1541.43  5798.5 1545.26  5906.5 1550.06
#Mann=7,-1,0
  4020.9    0.07       0  4116.0   0.035       0  4295.4    0.07       0
  4992.0    0.05       0  4997.0    0.07       0  5716.4   0.035       0
  5798.5    0.07       0
Bank Sta=4992,4997
Exp/Cntr=0.3,0.1

Type RM Length L Ch R = 1,17360,499,499,499
BEGIN DESCRIPTION:
DRY CREEK_1_DS 34.0
END DESCRIPTION:
XS GIS Cut Line= 3
      2096546.58     13915083.45      2095677.39     13915069.47
      2094279.31     13915905.35
#Sta/Elev= 30
  4130.7 1591.25  4232.3 1590.09  4341.3 1580.26  4442.3 1574.74  4472.3 1568.94
  4502.3 1566.49  4552.3 1552.27  4662.3 1541.49  4742.4 1528.75  4912.4 1513.18
  4942.4 1505.67  4962.1 1496.11  4967.1 1497.37  4972.4 1486.30  4979.8 1483.38
  4980.2 1482.88  4985.0 1483.38  4992.4 1487.49  5020.4 1491.67  5187.9 1498.23
  5340.7 1500.22  5474.6 1508.54  5567.0 1519.20  5604.0 1525.74  5683.7 1530.48
  5726.5 1537.39  6209.0 1551.03  6288.7 1560.67  6405.4 1567.10  6628.9 1571.96
#Mann=5,-1,0
  4130.7    0.07       0  4979.8    0.05       0  4985.0    0.07       0
  5187.9   0.035       0  5474.6    0.07       0
Bank Sta=4979.8,4985
Exp/Cntr=0.3,0.1

Type RM Length L Ch R = 1,16861,493,493,493
BEGIN DESCRIPTION:
DRY CREEK_1_DS 33.0
END DESCRIPTION:
XS GIS Cut Line= 3
      2096597.97     13914917.24      2095454.51     13914655.20
      2093998.53     13914962.75
#Sta/Elev= 30
  3826.9 1596.48  3996.4 1590.97  4042.8 1585.01  4173.2 1574.18  4230.1 1566.52
  4281.3 1553.12  4412.8 1538.89  4483.8 1527.47  4650.7 1515.43  4763.5 1494.65
  4885.5 1490.25  4921.3 1489.20  4985.9 1481.62  5006.8 1479.68  5007.3 1479.18
  5012.6 1479.68  5019.0 1484.67  5068.8 1493.34  5123.6 1496.85  5357.0 1505.28
  5438.2 1502.65  5531.0 1507.38  5600.6 1523.16  5705.2 1531.61  5744.7 1541.20
  5830.0 1546.37  5857.0 1548.14  6038.1 1568.77  6405.5 1587.54  6488.1 1591.23
#Mann=13,-1,0
  3826.9   0.035       0  4042.8    0.07       0  4412.8   0.035       0
  4483.8    0.07       0  4885.5    0.12       0  4921.3    0.07       0
  4985.9    0.12       0  5006.8    0.05       0  5012.6    0.12       0
  5438.2    0.07       0  5830.0   0.035       0  5857.0    0.07       0
  6405.5   0.035       0
Bank Sta=5006.8,5012.6
Exp/Cntr=0.3,0.1

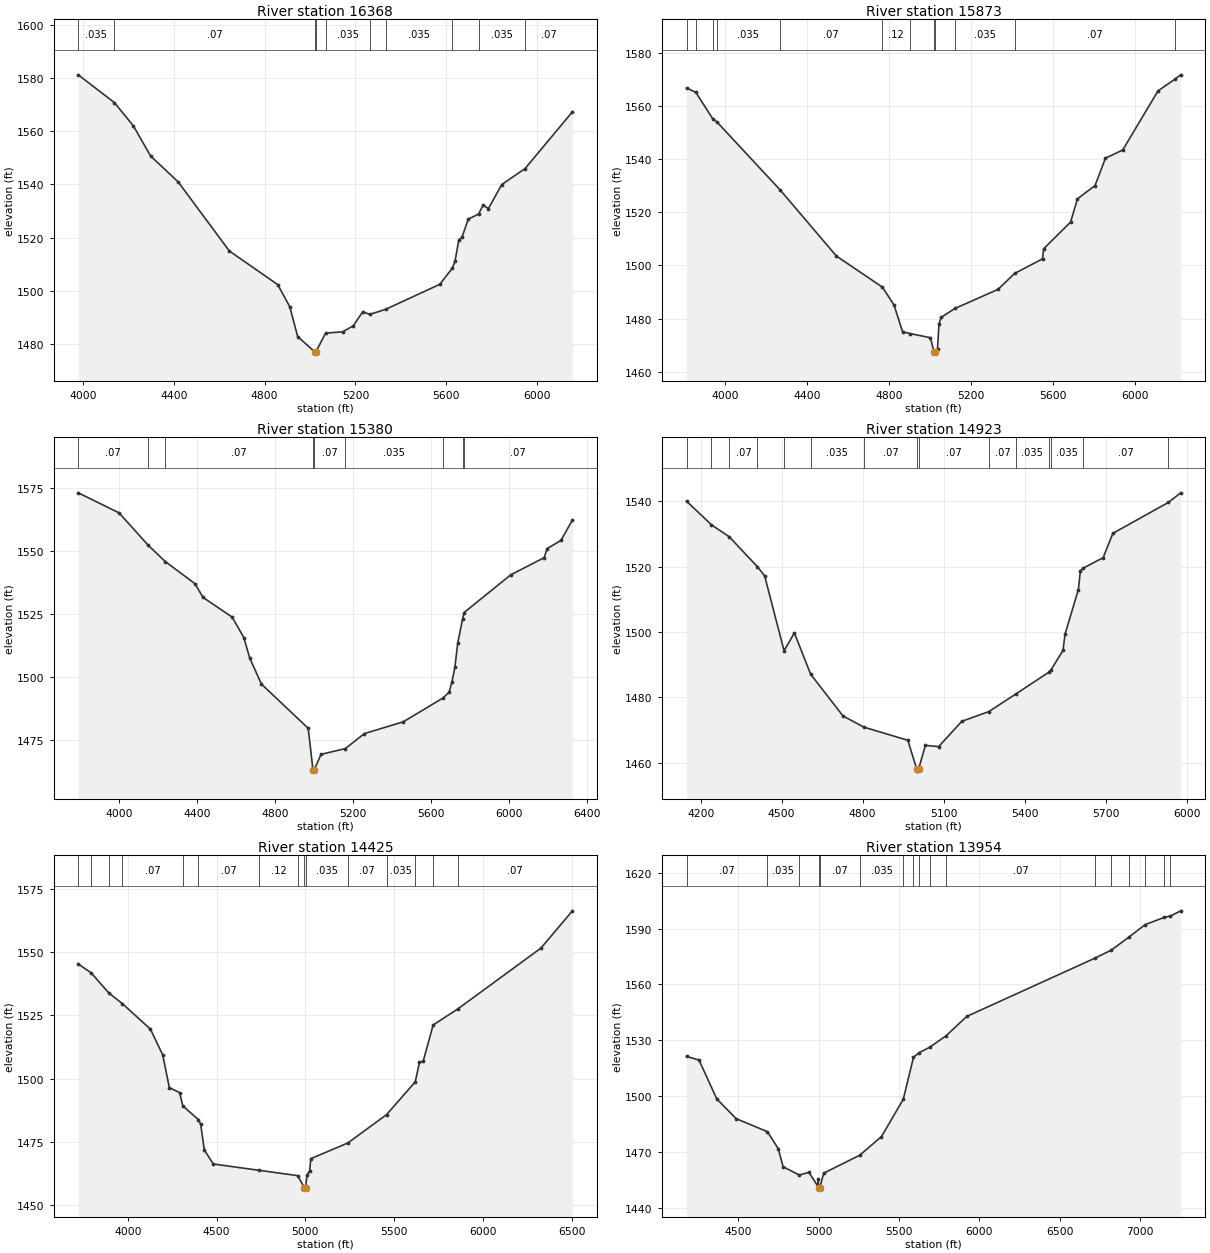
Type RM Length L Ch R = 1,16368,495,495,495
BEGIN DESCRIPTION:
DRY CREEK_1_DS 32.0
END DESCRIPTION:
XS GIS Cut Line= 3
      2096536.62     13914662.09      2095605.40     13914245.16
      2094482.64     13914517.88
#Sta/Elev= 30
  3979.7 1581.12  4138.8 1570.69  4222.5 1561.93  4298.3 1550.62  4419.7 1540.88
  4645.0 1514.93  4858.0 1502.30  4911.0 1493.98  4945.7 1482.78  5020.4 1477.06
  5020.9 1476.56  5026.2 1477.06  5068.7 1484.11  5143.5 1484.54  5190.4 1486.83
  5232.1 1492.09  5263.3 1491.12  5333.4 1493.03  5571.4 1502.41  5627.2 1508.53
  5638.4 1511.14  5654.9 1518.99  5669.3 1520.12  5696.7 1526.91  5742.2 1528.81
  5761.9 1532.18  5785.4 1530.88  5844.3 1539.91  5946.7 1545.89  6155.4 1567.23
#Mann=10,-1,0
  3979.7   0.035       0  4138.8    0.07       0  5020.4    0.05       0
  5026.2    0.07       0  5068.7   0.035       0  5263.3    0.07       0
  5333.4   0.035       0  5627.2    0.07       0  5742.2   0.035       0
  5946.7    0.07       0
Bank Sta=5020.4,5026.2
Exp/Cntr=0.3,0.1

Type RM Length L Ch R = 1,15873,493,493,493
BEGIN DESCRIPTION:
DRY CREEK_1_DS 31.0
END DESCRIPTION:
XS GIS Cut Line= 3
      2096629.71     13913591.00      2095475.35     13913864.82
      2094369.45     13914387.04
#Sta/Elev= 30
  3813.6 1566.92  3859.4 1565.20  3942.5 1555.14  3961.5 1554.11  4269.1 1528.56
  4544.4 1503.56  4768.9 1491.83  4825.6 1485.06  4866.7 1475.09  4903.0 1474.36
  5003.0 1472.79  5019.5 1467.48  5020.0 1466.98  5025.5 1467.48  5037.3 1468.60
  5044.6 1478.01  5054.6 1480.44  5122.0 1483.80  5332.1 1490.99  5413.6 1497.01
  5549.3 1502.50  5554.8 1506.31  5685.9 1516.33  5719.7 1525.12  5805.3 1530.13
  5856.3 1540.44  5940.4 1543.53  6112.3 1565.78  6197.4 1570.35  6223.0 1571.84
#Mann=12,-1,0
  3813.6    0.07       0  3859.4   0.035       0  3942.5    0.07       0
  3961.5   0.035       0  4269.1    0.07       0  4768.9    0.12       0
  4903.0    0.07       0  5019.5    0.05       0  5025.5    0.07       0
  5122.0   0.035       0  5413.6    0.07       0  6197.4   0.035       0
Bank Sta=5019.5,5025.5
Exp/Cntr=0.3,0.1

Type RM Length L Ch R = 1,15380,457,457,457
BEGIN DESCRIPTION:
DRY CREEK_1_DS 30.0
END DESCRIPTION:
XS GIS Cut Line= 3
      2096734.49     13913425.01      2095525.02     13913415.91
      2094452.86     13914195.27
#Sta/Elev= 30
  3790.5 1572.90  4000.0 1564.96  4148.5 1552.20  4236.6 1545.70  4390.0 1536.88
  4430.0 1531.53  4580.0 1523.68  4640.0 1515.55  4670.0 1507.49  4730.0 1497.18
  4970.0 1479.65  4994.5 1463.19  4995.0 1462.69  5000.6 1463.19  5036.0 1469.33
  5160.2 1471.61  5257.8 1477.54  5457.5 1482.21  5661.4 1491.64  5692.9 1493.96
  5707.6 1498.08  5722.3 1503.76  5737.0 1513.30  5761.9 1522.94  5769.7 1525.50
  6009.0 1540.42  6180.6 1547.24  6195.3 1550.79  6266.4 1554.06  6325.5 1562.11
#Mann=9,-1,0
  3790.5    0.07       0  4148.5   0.035       0  4236.6    0.07       0
  4994.5    0.05       0  5000.6    0.07       0  5160.2   0.035       0
  5661.4    0.07       0  5761.9   0.035       0  5769.7    0.07       0
Bank Sta=4994.5,5000.6
Exp/Cntr=0.3,0.1

Type RM Length L Ch R = 1,14923,498,498,498
BEGIN DESCRIPTION:
DRY CREEK_1_DS 29.0
END DESCRIPTION:
XS GIS Cut Line= 3
      2096174.25     13913074.06      2095322.58     13913037.15
      2094585.64     13913680.48
#Sta/Elev= 30
  4147.5 1540.01  4239.8 1532.78  4306.3 1529.07  4410.3 1519.93  4437.0 1517.15
  4508.8 1494.26  4547.1 1499.69  4607.3 1487.07  4727.3 1474.29  4804.4 1470.88
  4967.5 1466.84  5000.7 1457.92  5001.2 1457.42  5006.9 1457.92  5032.3 1465.28
  5081.7 1464.93  5167.1 1472.65  5267.5 1475.63  5368.2 1481.06  5488.7 1487.62
  5497.6 1488.37  5542.1 1494.32  5549.7 1499.31  5599.0 1512.93  5606.6 1518.70
  5617.8 1519.54  5691.1 1522.72  5726.8 1530.15  5932.6 1539.62  5978.2 1542.55
#Mann=15,-1,0
  4147.5    0.07       0  4239.8   0.035       0  4306.3    0.07       0
  4410.3   0.035       0  4508.8    0.07       0  4607.3   0.035       0
  4804.4    0.07       0  5000.7    0.05       0  5006.9    0.07       0
  5267.5    0.07       0  5368.2   0.035       0  5488.7    0.07       0
  5497.6   0.035       0  5617.8    0.07       0  5932.6   0.035       0
Bank Sta=5000.7,5006.9
Exp/Cntr=0.3,0.1

Type RM Length L Ch R = 1,14425,471,471,471
BEGIN DESCRIPTION:
DRY CREEK_1_DS 28.0
END DESCRIPTION:
XS GIS Cut Line= 3
      2096383.20     13912882.53      2095125.00     13912652.27
      2094273.11     13913891.39
#Sta/Elev= 30
  3720.9 1545.33  3793.3 1541.83  3893.0 1533.88  3969.2 1529.67  4127.3 1519.60
  4196.9 1509.36  4233.7 1496.49  4292.0 1494.51  4309.3 1489.34  4397.1 1483.86
  4410.4 1482.03  4430.7 1471.88  4481.5 1466.34  4741.0 1463.83  4956.6 1461.74
  4994.4 1456.92  4994.9 1456.42  5000.6 1456.92  5009.1 1461.98  5024.0 1463.61
  5030.1 1468.42  5239.3 1474.66  5457.0 1485.83  5618.6 1498.78  5642.3 1506.56
  5663.3 1506.92  5719.3 1521.23  5857.8 1527.55  6326.1 1551.58  6503.7 1566.31
#Mann=15,-1,0
  3720.9   0.035       0  3793.3    0.12       0  3893.0   0.035       0
  3969.2    0.07       0  4309.3   0.035       0  4397.1    0.07       0
  4741.0    0.12       0  4956.6   0.035       0  4994.4   0.035       0
  5000.6   0.035       0  5239.3    0.07       0  5457.0   0.035       0
  5618.6    0.07       0  5719.3   0.035       0  5857.8    0.07       0
Bank Sta=4994.4,5000.6
Exp/Cntr=0.3,0.1

Type RM Length L Ch R = 1,13954,499,499,499
BEGIN DESCRIPTION:
DRY CREEK_1_DS 27.0
END DESCRIPTION:
XS GIS Cut Line= 3
      2096042.26     13912324.48      2095226.18     13912239.42
      2093034.03     13912753.43
#Sta/Elev= 30
  4179.5 1521.37  4257.2 1519.41  4367.8 1498.50  4488.4 1487.92  4682.6 1480.92
  4749.8 1471.80  4780.0 1462.11  4880.2 1457.64  4940.9 1459.09  4995.3 1451.67
  4998.1 1455.68  5001.0 1450.57  5001.5 1450.07  5007.8 1450.57  5032.0 1458.63
  5256.0 1468.26  5391.5 1478.29  5527.0 1498.36  5590.2 1520.80  5626.4 1523.42
  5692.2 1526.33  5794.2 1532.54  5921.5 1542.85  6718.9 1574.16  6821.0 1578.49
  6932.4 1585.66  7030.3 1592.13  7148.7 1596.03  7187.2 1596.73  7251.6 1599.57
#Mann=17,-1,0
  4179.5    0.07       0  4682.6   0.035       0  4880.2    0.07       0
  5001.0    0.05       0  5007.8    0.07       0  5256.0   0.035       0
  5527.0    0.07       0  5590.2   0.035       0  5626.4    0.07       0
  5692.2   0.035       0  5794.2    0.07       0  6718.9   0.035       0
  6821.0    0.07       0  6932.4   0.035       0  7030.3    0.07       0
  7148.7   0.035       0  7187.2    0.07       0
Bank Sta=5001,5007.8
Exp/Cntr=0.3,0.1

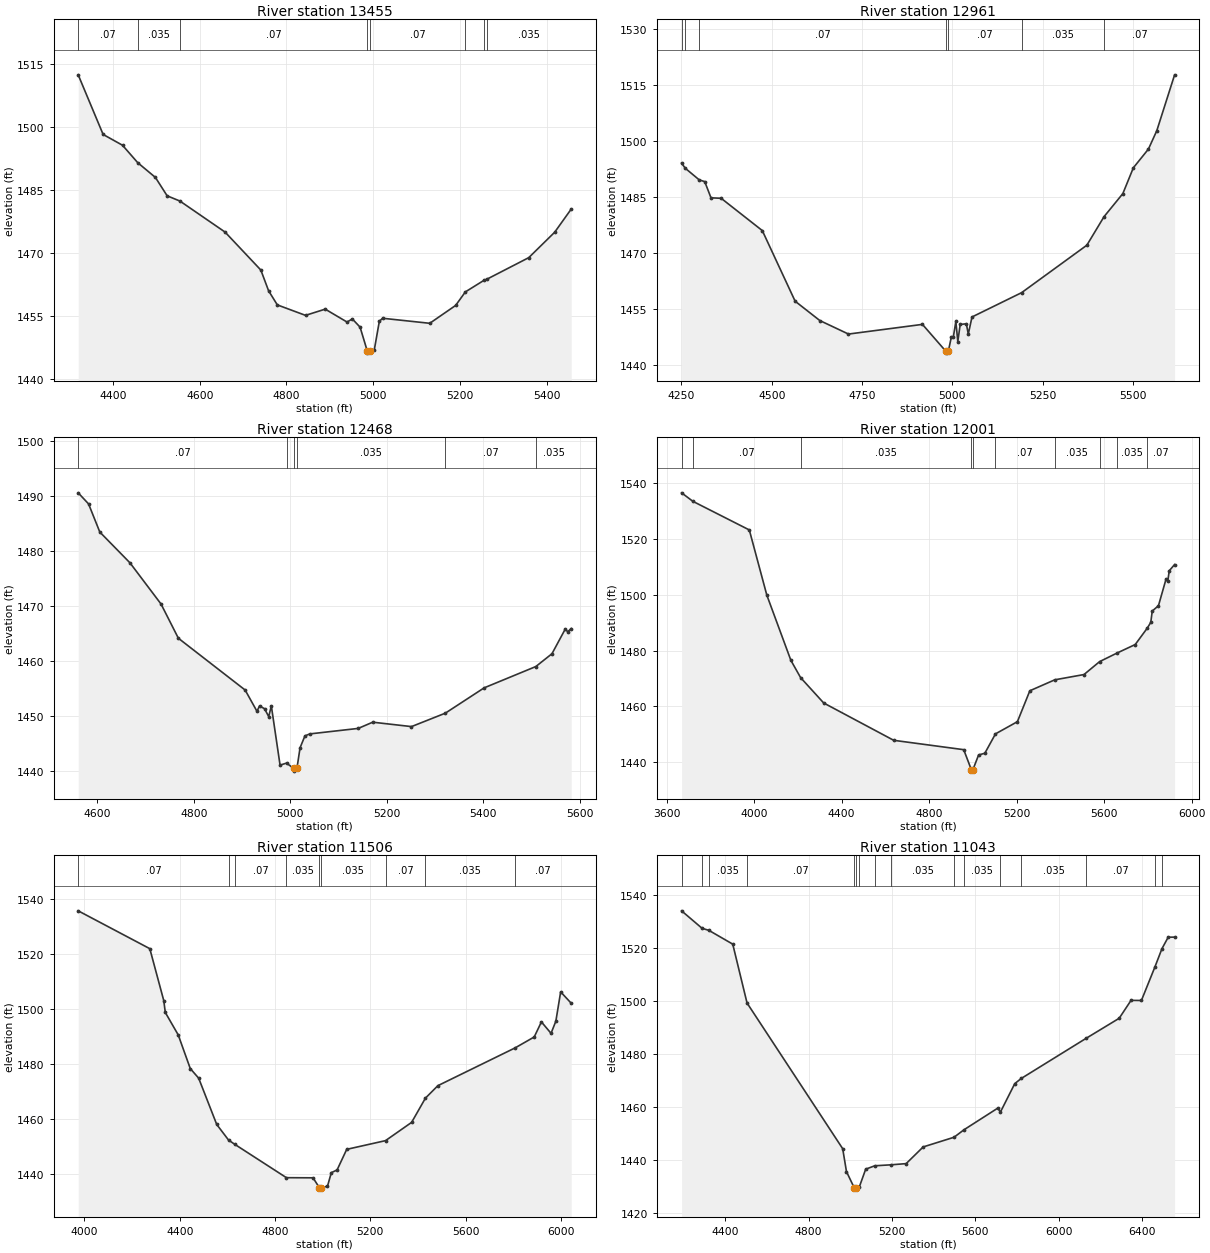
Type RM Length L Ch R = 1,13455,494,494,494
BEGIN DESCRIPTION:
DRY CREEK_1_DS 26.0
END DESCRIPTION:
XS GIS Cut Line= 3
      2095872.27     13911959.64      2095194.93     13911895.18
      2094775.01     13912075.00
#Sta/Elev= 30
  4319.6 1512.50  4377.1 1498.31  4421.8 1495.74  4457.0 1491.58  4497.7 1488.08
  4524.8 1483.70  4554.2 1482.46  4658.4 1475.07  4740.9 1466.03  4758.8 1461.09
  4778.9 1457.74  4843.9 1455.25  4889.4 1456.73  4939.7 1453.66  4951.9 1454.40
  4969.8 1452.44  4986.4 1446.76  4986.9 1446.26  4993.3 1446.76  5002.7 1447.11
  5014.2 1453.83  5021.7 1454.56  5130.5 1453.36  5190.2 1457.61  5212.6 1460.83
  5255.9 1463.61  5262.2 1463.85  5358.9 1468.99  5418.7 1475.04  5456.8 1480.55
#Mann=8,-1,0
  4319.6    0.07       0  4457.0   0.035       0  4554.2    0.07       0
  4986.4    0.05       0  4993.3    0.07       0  5212.6   0.035       0
  5255.9    0.07       0  5262.2   0.035       0
Bank Sta=4986.4,4993.3
Exp/Cntr=0.3,0.1

Type RM Length L Ch R = 1,12961,493,493,493
BEGIN DESCRIPTION:
DRY CREEK_1_DS 25.0
END DESCRIPTION:
XS GIS Cut Line= 3
      2095732.26     13911865.42      2095054.80     13911544.56
      2094489.72     13911787.02
#Sta/Elev= 30
  4250.4 1494.11  4260.6 1492.73  4299.2 1489.61  4314.5 1489.14  4331.8 1484.79
  4360.0 1484.66  4473.8 1475.99  4564.7 1457.02  4633.0 1451.83  4712.3 1448.20
  4917.0 1450.80  4981.8 1443.58  4982.3 1443.08  4988.7 1443.58  4997.1 1447.47
  5002.6 1447.47  5009.5 1451.58  5014.9 1446.20  5021.5 1450.77  5038.5 1450.97
  5043.9 1448.20  5054.2 1452.79  5191.5 1459.32  5372.0 1472.06  5419.7 1479.74
  5471.7 1485.93  5500.7 1492.85  5542.4 1497.87  5565.6 1502.81  5614.9 1517.82
#Mann=7,-1,0
  4250.4    0.07       0  4260.6   0.035       0  4299.2    0.07       0
  4981.8    0.05       0  4988.7    0.07       0  5191.5   0.035       0
  5419.7    0.07       0
Bank Sta=4981.8,4988.7
Exp/Cntr=0.3,0.1

Type RM Length L Ch R = 1,12468,467,467,467
BEGIN DESCRIPTION:
DRY CREEK_1_DS 24.0
END DESCRIPTION:
XS GIS Cut Line= 3
      2095725.00     13911575.00      2095315.14     13911414.96
      2094735.24     13911470.94
#Sta/Elev= 30
  4560.0 1490.61  4581.5 1488.60  4604.8 1483.49  4667.4 1477.89  4731.8 1470.41
  4767.8 1464.19  4906.3 1454.78  4930.8 1450.92  4936.1 1451.89  4946.5 1451.39
  4955.2 1449.95  4960.6 1451.91  4978.7 1441.14  4992.2 1441.51  5006.7 1440.55
  5007.2 1440.05  5013.7 1440.55  5020.2 1444.30  5030.3 1446.45  5040.3 1446.81
  5140.8 1447.81  5170.9 1448.94  5251.3 1448.14  5321.5 1450.58  5402.0 1455.18
  5509.2 1459.05  5542.7 1461.38  5570.3 1465.87  5575.3 1465.37  5582.6 1465.96
#Mann=6,-1,0
  4560.0    0.07       0  4992.2   0.035       0  5006.7   0.035       0
  5013.7   0.035       0  5321.5    0.07       0  5509.2   0.035       0
Bank Sta=5006.7,5013.7
Exp/Cntr=0.3,0.1

Type RM Length L Ch R = 1,12001,495,495,495
BEGIN DESCRIPTION:
DRY CREEK_1_DS 23.0
END DESCRIPTION:
XS GIS Cut Line= 3
      2096354.52     13911103.51      2095023.24     13911085.75
      2094333.77     13911698.04
#Sta/Elev= 30
  3668.6 1536.54  3720.3 1533.49  3978.2 1523.23  4058.2 1499.87  4168.2 1476.48
  4212.6 1470.29  4318.2 1461.19  4638.2 1447.81  4958.2 1444.45  4993.1 1437.26
  4993.6 1436.76  5000.1 1437.26  5026.3 1442.56  5054.7 1443.17  5103.4 1450.12
  5203.6 1454.49  5260.4 1465.57  5374.5 1469.50  5508.0 1471.39  5579.3 1476.02
  5658.5 1479.08  5742.1 1482.15  5796.5 1487.96  5813.2 1490.09  5819.9 1494.15
  5848.3 1496.07  5883.4 1505.74  5891.0 1504.97  5897.7 1508.61  5922.1 1510.83
#Mann=10,-1,0
  3668.6   0.035       0  3720.3    0.07       0  4212.6   0.035       0
  4993.1   0.035       0  5000.1   0.035       0  5103.4    0.07       0
  5374.5   0.035       0  5579.3    0.07       0  5658.5   0.035       0
  5796.5    0.07       0
Bank Sta=4993.1,5000.1
Exp/Cntr=0.3,0.1

Type RM Length L Ch R = 1,11506,463,463,463
BEGIN DESCRIPTION:
DRY CREEK_1_DS 22.0
END DESCRIPTION:
XS GIS Cut Line= 3
      2096220.47     13910842.86      2095205.07     13910695.03
      2094171.06     13910833.90
#Sta/Elev= 30
  3973.9 1535.55  4274.5 1521.83  4333.1 1503.00  4339.5 1498.71  4393.7 1490.58
  4444.3 1478.38  4479.6 1474.88  4555.4 1458.10  4605.1 1452.44  4630.8 1450.92
  4847.9 1438.81  4959.7 1438.76  4986.3 1435.16  4986.8 1434.66  4993.7 1435.16
  5020.3 1435.73  5036.4 1440.62  5060.6 1441.62  5101.0 1449.08  5263.9 1452.24
  5373.4 1458.86  5431.4 1467.65  5483.7 1472.17  5808.2 1485.88  5888.0 1489.82
  5918.2 1495.28  5958.6 1491.14  5978.8 1495.54  5999.0 1506.17  6043.3 1502.05
#Mann=9,-1,0
  3973.9    0.07       0  4605.1   0.035       0  4630.8    0.07       0
  4847.9   0.035       0  4986.3   0.035       0  4993.7   0.035       0
  5263.9    0.07       0  5431.4   0.035       0  5808.2    0.07       0
Bank Sta=4986.3,4993.7
Exp/Cntr=0.3,0.1

Type RM Length L Ch R = 1,11043,498,498,498
BEGIN DESCRIPTION:
DRY CREEK_1_DS 21.0
END DESCRIPTION:
XS GIS Cut Line= 3
      2096304.86     13910567.55      2095517.55     13910381.07
      2093994.82     13910703.09
#Sta/Elev= 30
  4190.9 1534.06  4289.0 1527.47  4322.1 1526.67  4436.4 1521.47  4505.0 1499.22
  4963.9 1444.16  4982.1 1435.49  5019.3 1429.38  5019.8 1428.88  5026.8 1429.38
  5043.9 1429.75  5074.2 1436.42  5117.8 1437.70  5196.3 1438.07  5268.4 1438.52
  5350.1 1444.83  5498.0 1448.48  5546.4 1451.34  5707.9 1459.49  5720.8 1458.02
  5789.6 1468.76  5820.6 1470.70  6132.0 1485.88  6290.5 1493.45  6347.4 1500.22
  6397.1 1500.17  6461.6 1512.78  6495.7 1519.75  6525.6 1524.09  6556.4 1524.12
#Mann=16,-1,0
  4190.9   0.035       0  4289.0    0.07       0  4322.1   0.035       0
  4505.0    0.07       0  5019.3    0.05       0  5026.8    0.07       0
  5043.9   0.035       0  5117.8    0.07       0  5196.3   0.035       0
  5498.0    0.07       0  5546.4   0.035       0  5720.8    0.07       0
  5820.6   0.035       0  6132.0    0.07       0  6461.6   0.035       0
  6495.7    0.07       0
Bank Sta=5019.3,5026.8
Exp/Cntr=0.3,0.1

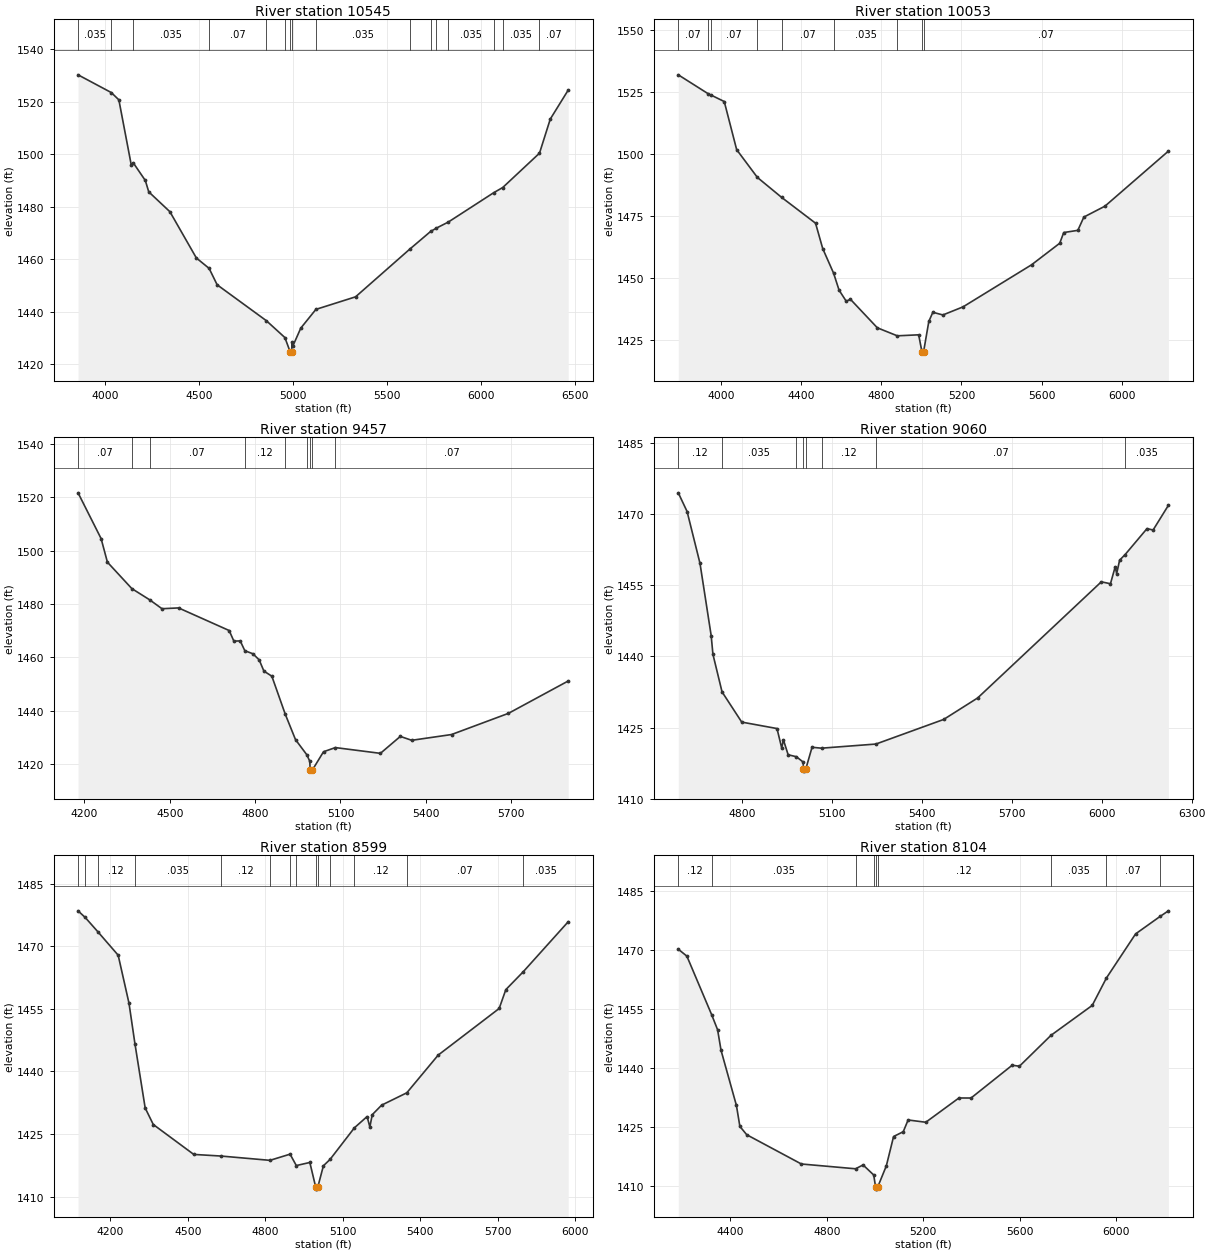
Type RM Length L Ch R = 1,10545,492,492,492
BEGIN DESCRIPTION:
DRY CREEK_1_DS 20.0
END DESCRIPTION:
XS GIS Cut Line= 3
      2096410.90     13910099.88      2095274.53     13909979.74
      2093959.42     13910624.59
#Sta/Elev= 30
  3857.3 1530.20  4034.0 1523.45  4074.4 1520.67  4140.6 1495.78  4150.6 1496.72
  4215.2 1489.94  4233.4 1485.61  4345.9 1478.05  4486.7 1460.42  4554.5 1456.46
  4597.3 1450.20  4858.8 1436.54  4957.6 1430.10  4985.6 1424.67  4986.1 1424.17
  4993.3 1424.67  4996.0 1428.35  4998.8 1426.70  5042.2 1433.70  5122.5 1440.83
  5333.6 1445.62  5621.0 1463.73  5732.5 1470.51  5763.9 1471.81  5827.0 1474.11
  6068.6 1485.30  6116.5 1487.27  6312.0 1500.35  6369.4 1513.35  6464.7 1524.38
#Mann=16,-1,0
  3857.3   0.035       0  4034.0    0.07       0  4150.6   0.035       0
  4554.5    0.07       0  4858.8   0.035       0  4957.6    0.07       0
  4985.6    0.05       0  4993.3    0.07       0  5122.5   0.035       0
  5621.0    0.07       0  5732.5   0.035       0  5763.9    0.07       0
  5827.0   0.035       0  6068.6    0.07       0  6116.5   0.035       0
  6312.0    0.07       0
Bank Sta=4985.6,4993.3
Exp/Cntr=0.3,0.1

Type RM Length L Ch R = 1,10053,596,596,596
BEGIN DESCRIPTION:
DRY CREEK_1_DS 19.0
END DESCRIPTION:
XS GIS Cut Line= 3
      2096417.36     13909808.63      2095241.89     13909508.43
      2094015.17     13909631.68
#Sta/Elev= 30
  3786.8 1531.92  3935.6 1524.31  3950.2 1523.76  4016.3 1521.14  4078.2 1501.73
  4181.6 1490.53  4302.4 1482.49  4471.9 1472.06  4507.6 1461.84  4561.8 1451.92
  4589.3 1445.05  4625.0 1440.59  4645.9 1441.38  4780.1 1429.87  4879.9 1426.63
  4986.5 1427.04  5002.9 1420.15  5003.4 1419.65  5010.9 1420.15  5037.1 1432.41
  5057.2 1436.13  5107.4 1435.05  5207.9 1438.31  5549.6 1455.27  5690.4 1463.98
  5710.5 1468.30  5780.8 1469.18  5810.9 1474.54  5916.2 1478.94  6232.9 1501.15
#Mann=9,-1,0
  3786.8    0.07       0  3935.6   0.035       0  3950.2    0.07       0
  4181.6   0.035       0  4302.4    0.07       0  4561.8   0.035       0
  4879.9    0.07       0  5002.9    0.05       0  5010.9    0.07       0
Bank Sta=5002.9,5010.9
Exp/Cntr=0.3,0.1

Type RM Length L Ch R = 1,9457,397,397,397
BEGIN DESCRIPTION:
DRY CREEK_1_DS 18.0
END DESCRIPTION:
XS GIS Cut Line= 3
      2096257.76     13909449.06      2095525.00     13909075.00
      2094625.01     13909075.00
#Sta/Elev= 30
  4177.8 1521.67  4258.8 1504.53  4281.0 1495.69  4366.9 1485.78  4429.2 1481.61
  4472.8 1478.25  4531.1 1478.55  4708.9 1470.08  4725.5 1466.10  4747.7 1466.20
  4764.0 1462.51  4792.2 1461.38  4814.4 1459.09  4831.0 1454.88  4858.9 1452.97
  4906.0 1438.75  4942.1 1429.20  4981.9 1423.52  4992.2 1421.10  4993.7 1417.90
  4994.2 1417.40  5001.8 1417.90  5040.5 1424.66  5082.2 1426.22  5240.5 1424.06
  5310.5 1430.41  5350.5 1428.95  5490.5 1431.11  5690.5 1439.05  5900.5 1451.17
#Mann=9,-1,0
  4177.8    0.07       0  4366.9   0.035       0  4429.2    0.07       0
  4764.0    0.12       0  4906.0   0.035       0  4981.9    0.12       0
  4993.7    0.05       0  5001.8    0.12       0  5082.2    0.07       0
Bank Sta=4993.7,5001.8
Exp/Cntr=0.3,0.1

Type RM Length L Ch R = 1,9060,461,461,461
BEGIN DESCRIPTION:
DRY CREEK_1_DS 17.0
END DESCRIPTION:
XS GIS Cut Line= 3
      2095875.00     13908925.00      2095518.52     13908718.24
      2094314.64     13908930.82
#Sta/Elev= 30
  4587.9 1474.50  4617.3 1470.56  4660.3 1459.64  4697.6 1444.40  4703.5 1440.44
  4733.9 1432.52  4799.5 1426.15  4917.1 1424.79  4932.8 1420.71  4938.6 1422.39
  4954.3 1419.26  4981.7 1418.85  5004.3 1417.73  5005.3 1416.31  5005.8 1415.81
  5013.4 1416.31  5034.0 1420.84  5065.6 1420.65  5247.0 1421.52  5473.0 1426.71
  5586.3 1431.24  5998.7 1455.73  6029.2 1455.33  6044.9 1458.88  6049.9 1457.47
  6059.7 1460.29  6078.2 1461.49  6151.0 1466.95  6171.4 1466.66  6222.5 1471.87
#Mann=8,-1,0
  4587.9    0.12       0  4733.9   0.035       0  4981.7    0.07       0
  5005.3    0.05       0  5013.4    0.07       0  5065.6    0.12       0
  5247.0    0.07       0  6078.2   0.035       0
Bank Sta=5005.3,5013.4
Exp/Cntr=0.3,0.1

Type RM Length L Ch R = 1,8599,495,495,495
BEGIN DESCRIPTION:
DRY CREEK_1_DS 16.0
END DESCRIPTION:
XS GIS Cut Line= 3
      2096073.68     13908709.64      2095188.68     13908438.16
      2094269.27     13908758.73
#Sta/Elev= 30
  4074.3 1478.48  4102.0 1476.89  4150.4 1473.51  4229.8 1467.84  4271.7 1456.34
  4294.8 1446.60  4334.4 1431.23  4365.8 1427.26  4522.7 1420.09  4628.3 1419.70
  4818.0 1418.67  4895.9 1420.15  4920.1 1417.42  4972.5 1418.16  4995.2 1412.27
  4995.7 1411.77  5003.4 1412.27  5025.1 1417.37  5050.8 1418.89  5145.4 1426.48
  5194.5 1429.17  5205.1 1426.65  5214.3 1429.61  5250.7 1431.90  5348.3 1434.86
  5469.9 1443.90  5706.2 1455.07  5732.0 1459.59  5799.4 1463.87  5973.7 1475.86
#Mann=14,-1,0
  4074.3   0.035       0  4102.0    0.07       0  4150.4    0.12       0
  4294.8   0.035       0  4628.3    0.12       0  4818.0    0.07       0
  4895.9    0.12       0  4920.1   0.035       0  4995.2   0.035       0
  5003.4   0.035       0  5050.8    0.07       0  5145.4    0.12       0
  5348.3    0.07       0  5799.4   0.035       0
Bank Sta=4995.2,5003.4
Exp/Cntr=0.3,0.1

Type RM Length L Ch R = 1,8104,493,493,493
BEGIN DESCRIPTION:
DRY CREEK_1_DS 15.0
END DESCRIPTION:
XS GIS Cut Line= 3
      2096024.98     13908574.99      2095401.30     13908048.18
      2094189.43     13907942.04
#Sta/Elev= 30
  4183.6 1470.20  4219.3 1468.43  4322.3 1453.48  4346.7 1449.68  4361.0 1444.44
  4424.8 1430.40  4439.1 1425.07  4467.6 1422.95  4694.1 1415.50  4918.9 1414.28
  4950.0 1415.26  4994.2 1412.70  5002.1 1409.60  5002.6 1409.10  5010.5 1409.60
  5046.5 1415.02  5076.6 1422.50  5116.7 1423.72  5136.8 1426.71  5210.2 1426.13
  5347.6 1432.31  5397.8 1432.30  5568.5 1440.65  5598.6 1440.40  5729.5 1448.27
  5900.4 1455.88  5959.3 1462.86  6080.4 1474.10  6182.1 1478.55  6216.5 1479.97
#Mann=9,-1,0
  4183.6    0.12       0  4322.3   0.035       0  4918.9    0.07       0
  4994.2    0.12       0  5002.1    0.05       0  5010.5    0.12       0
  5729.5   0.035       0  5959.3    0.07       0  6182.1   0.035       0
Bank Sta=5002.1,5010.5
Exp/Cntr=0.3,0.1