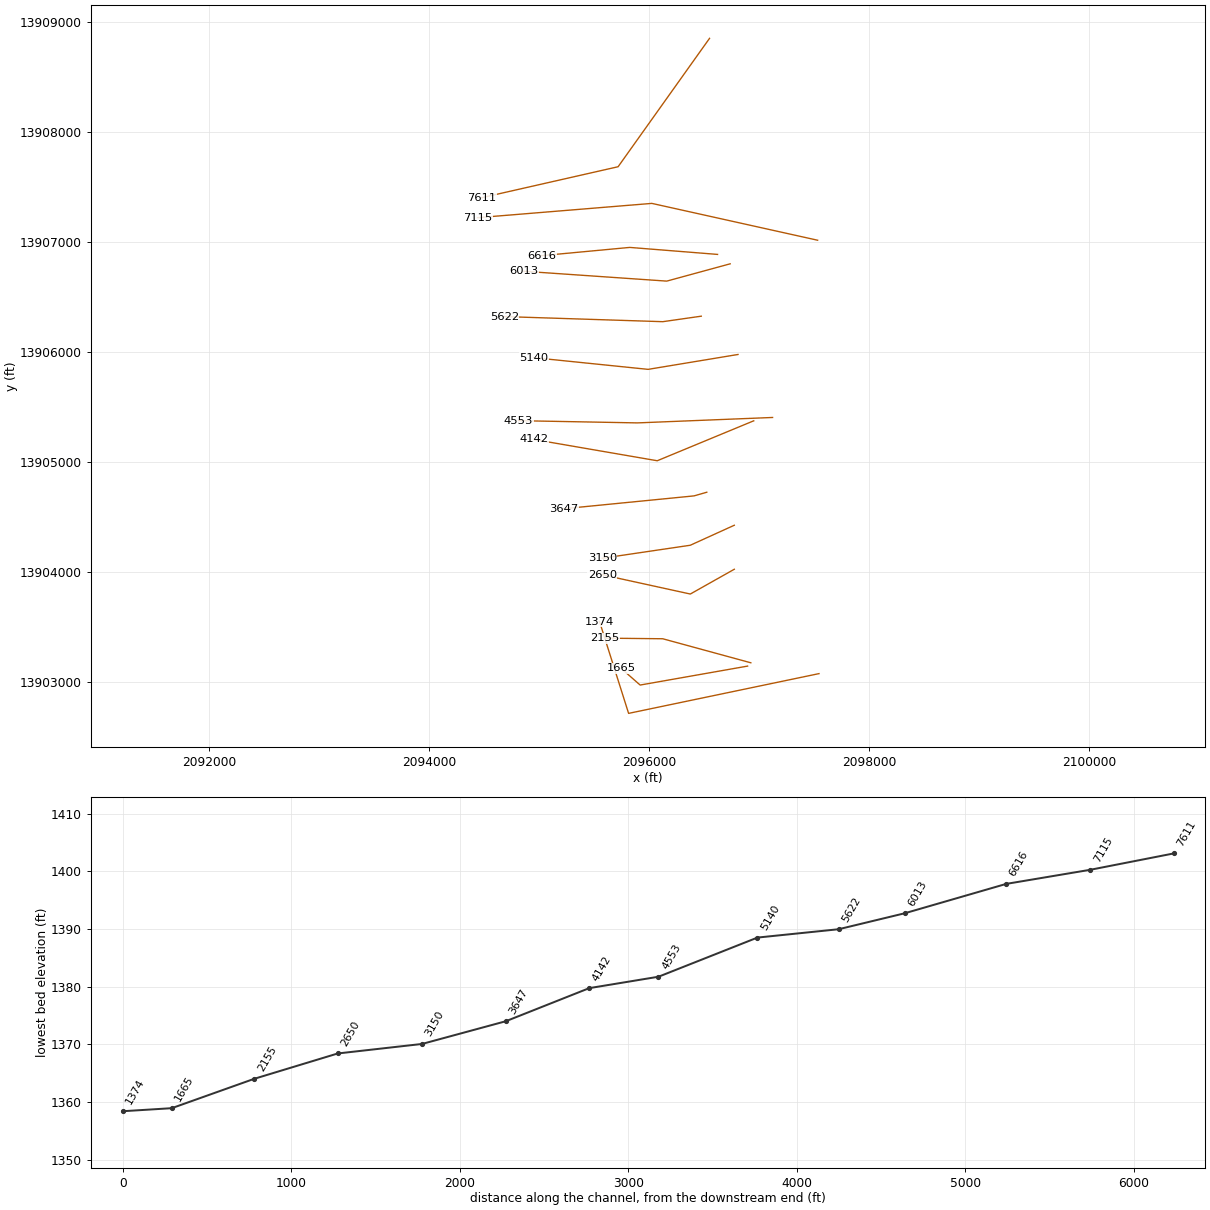
HEC-RAS study DRY CREEK 1.prj: DRY CREEK 1 Base Level Engineering

--- DRY CREEK 1.g01 (geometry) --- (continued)

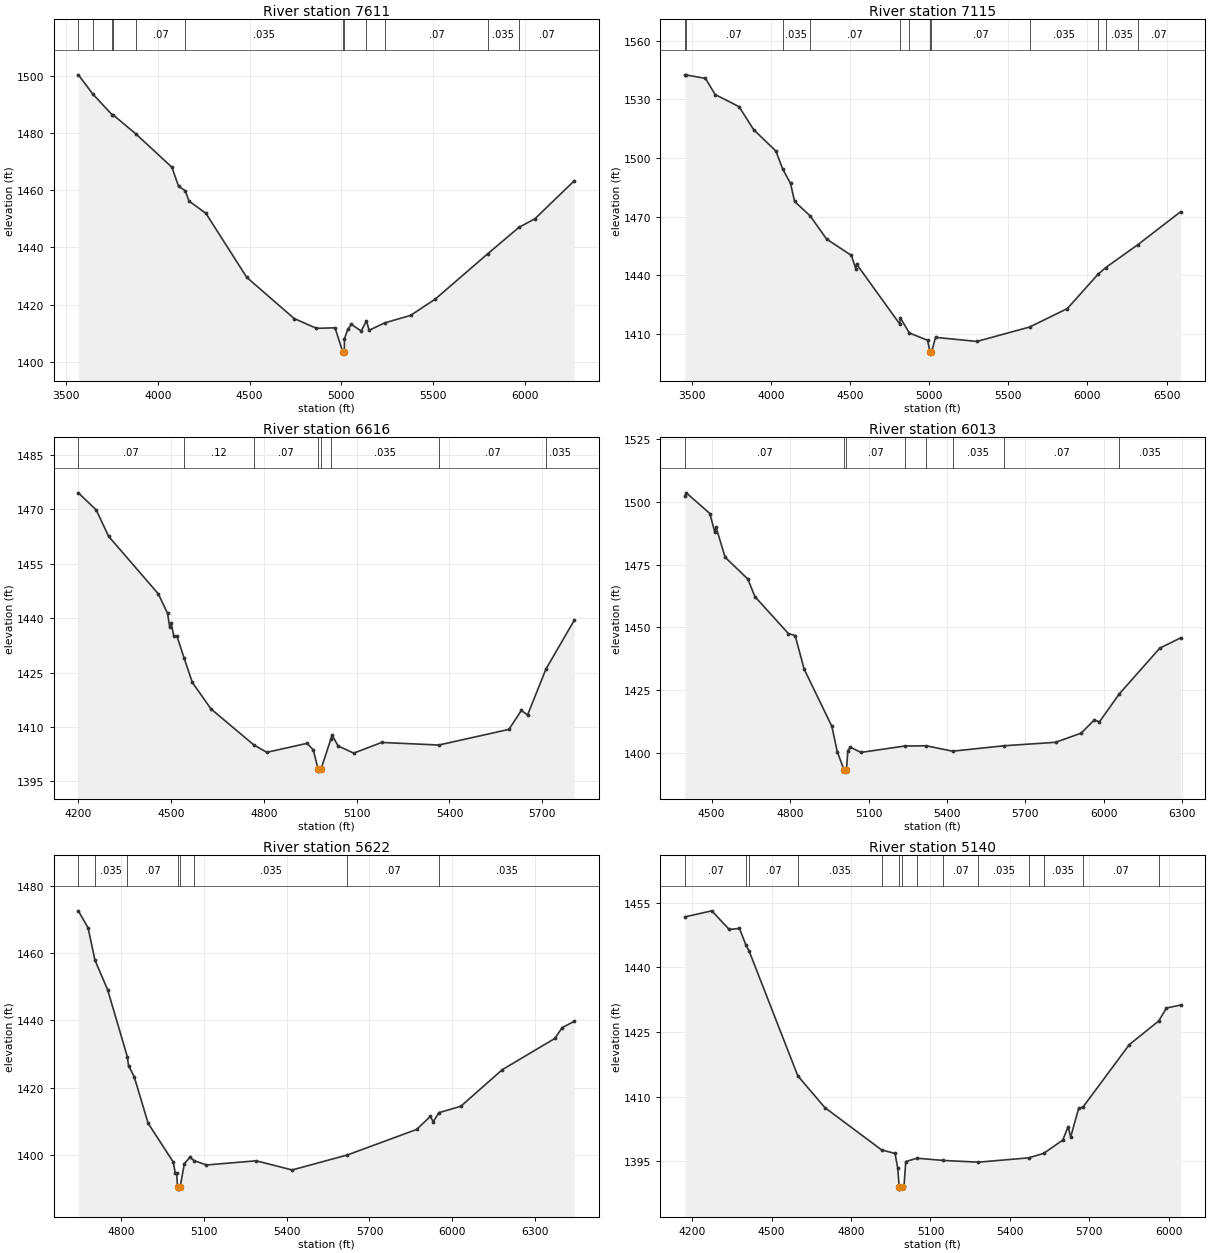
Type RM Length L Ch R = 1,7611,496,496,496
BEGIN DESCRIPTION:
DRY CREEK_1_DS 14.0
END DESCRIPTION:
XS GIS Cut Line= 3
      2096550.03     13908850.04      2095718.94     13907683.14
      2094482.63     13907402.35
#Sta/Elev= 30
  3567.4 1500.25  3646.6 1493.54  3750.5 1486.37  3758.1 1486.21  3881.6 1479.59
  4076.9 1468.01  4113.3 1461.37  4149.9 1459.80  4169.9 1456.22  4262.1 1451.93
  4484.6 1429.58  4742.8 1415.21  4864.5 1411.78  4965.4 1411.97  5007.4 1403.63
  5007.9 1403.13  5016.0 1403.63  5016.8 1408.11  5034.8 1411.45  5054.8 1413.18
  5108.1 1410.82  5136.6 1414.44  5151.2 1411.12  5237.0 1413.71  5376.9 1416.29
  5511.2 1421.98  5797.5 1437.83  5967.4 1447.04  6053.9 1450.01  6267.8 1463.24
#Mann=12,-1,0
  3567.4    0.07       0  3646.6   0.035       0  3750.5    0.07       0
  3758.1   0.035       0  3881.6    0.07       0  4149.9   0.035       0
  5007.4   0.035       0  5016.0   0.035       0  5136.6    0.12       0
  5237.0    0.07       0  5797.5   0.035       0  5967.4    0.07       0
Bank Sta=5007.4,5016
Exp/Cntr=0.3,0.1

Type RM Length L Ch R = 1,7115,499,499,499
BEGIN DESCRIPTION:
DRY CREEK_1_DS 13.0
END DESCRIPTION:
XS GIS Cut Line= 3
      2097532.27     13907015.17      2096025.43     13907349.99
      2094441.74     13907220.12
#Sta/Elev= 30
  3456.4 1542.59  3461.0 1542.58  3586.8 1540.78  3648.2 1532.52  3799.1 1526.33
  3891.3 1514.58  4032.1 1503.61  4074.6 1494.49  4124.3 1487.08  4150.2 1477.82
  4247.9 1470.51  4352.3 1458.64  4508.7 1450.26  4536.7 1443.47  4541.8 1445.81
  4814.4 1415.17  4818.4 1418.29  4875.3 1410.59  4990.2 1406.87  5005.9 1400.79
  5006.4 1400.29  5015.0 1400.79  5040.6 1408.36  5301.4 1406.27  5635.3 1413.64
  5873.3 1423.09  6065.9 1440.50  6116.2 1444.07  6318.6 1455.73  6589.0 1472.60
#Mann=12,-1,0
  3456.4    0.12       0  3461.0    0.07       0  4074.6   0.035       0
  4247.9    0.07       0  4814.4    0.12       0  4875.3    0.07       0
  5005.9    0.05       0  5015.0    0.07       0  5635.3   0.035       0
  6065.9    0.07       0  6116.2   0.035       0  6318.6    0.07       0
Bank Sta=5005.9,5015
Exp/Cntr=0.3,0.1

Type RM Length L Ch R = 1,6616,603,603,603
BEGIN DESCRIPTION:
DRY CREEK_1_DS 12.0
END DESCRIPTION:
XS GIS Cut Line= 3
      2096622.64     13906886.36      2095824.77     13906949.93
      2095024.97     13906875.00
#Sta/Elev= 30
  4199.6 1474.49  4257.4 1469.79  4297.6 1462.51  4458.1 1446.69  4488.2 1441.29
  4495.2 1437.47  4500.2 1438.58  4508.2 1435.08  4518.3 1435.11  4541.8 1428.94
  4568.4 1422.26  4628.6 1414.98  4766.6 1405.10  4809.2 1403.02  4939.6 1405.50
  4959.6 1403.68  4975.2 1398.34  4975.7 1397.84  4984.3 1398.34  5016.3 1406.65
  5019.9 1407.78  5039.9 1404.79  5090.2 1402.79  5180.6 1405.74  5365.6 1405.03
  5592.4 1409.34  5632.5 1414.56  5652.6 1413.30  5712.3 1426.00  5803.3 1439.35
#Mann=8,-1,0
  4199.6    0.07       0  4541.8    0.12       0  4766.6    0.07       0
  4975.2    0.05       0  4984.3    0.07       0  5016.3   0.035       0
  5365.6    0.07       0  5712.3   0.035       0
Bank Sta=4975.2,4984.3
Exp/Cntr=0.3,0.1

Type RM Length L Ch R = 1,6013,391,391,391
BEGIN DESCRIPTION:
DRY CREEK_1_DS 11.0
END DESCRIPTION:
XS GIS Cut Line= 3
      2096737.54     13906800.90      2096161.12     13906643.70
      2094865.27     13906733.04
#Sta/Elev= 30
  4397.3 1502.20  4402.9 1503.65  4493.2 1495.41  4511.8 1488.01  4516.9 1489.95
  4551.5 1477.99  4638.3 1469.30  4665.5 1462.28  4793.8 1447.54  4819.3 1446.78
  4853.8 1433.39  4959.7 1410.61  4980.4 1400.50  5006.3 1393.24  5006.8 1392.74
  5015.5 1393.24  5021.0 1400.94  5031.0 1402.24  5071.1 1400.20  5239.6 1402.76
  5321.5 1402.83  5421.3 1400.69  5617.8 1402.85  5815.6 1404.23  5913.1 1407.88
  5963.5 1413.14  5983.2 1412.39  6058.4 1423.43  6213.8 1441.73  6293.7 1445.85
#Mann=8,-1,0
  4397.3    0.07       0  5006.3    0.05       0  5015.5    0.07       0
  5239.6   0.035       0  5321.5    0.07       0  5421.3   0.035       0
  5617.8    0.07       0  6058.4   0.035       0
Bank Sta=5006.3,5015.5
Exp/Cntr=0.3,0.1

Type RM Length L Ch R = 1,5622,482,482,482
BEGIN DESCRIPTION:
DRY CREEK_1_DS 10.0
END DESCRIPTION:
XS GIS Cut Line= 3
      2096475.02     13906325.00      2096125.08     13906274.97
      2094685.02     13906321.35
#Sta/Elev= 30
  4646.5 1472.50  4681.9 1467.43  4706.6 1457.89  4752.5 1449.11  4823.7 1429.27
  4828.3 1426.56  4848.6 1423.33  4899.1 1409.51  4990.0 1398.02  4997.5 1394.62
  5002.5 1394.62  5005.5 1390.48  5006.0 1389.98  5014.7 1390.48  5030.1 1397.52
  5050.1 1399.42  5066.6 1398.40  5110.1 1397.14  5290.2 1398.38  5420.3 1395.66
  5620.3 1400.12  5870.5 1407.67  5920.6 1411.55  5930.6 1409.96  5951.6 1412.66
  6030.6 1414.55  6180.7 1425.40  6370.8 1434.65  6397.4 1437.88  6440.8 1439.72
#Mann=8,-1,0
  4646.5    0.07       0  4706.6   0.035       0  4823.7    0.07       0
  5005.5    0.05       0  5014.7    0.07       0  5066.6   0.035       0
  5620.3    0.07       0  5951.6   0.035       0
Bank Sta=5005.5,5014.7
Exp/Cntr=0.3,0.1

Type RM Length L Ch R = 1,5140,587,587,587
BEGIN DESCRIPTION:
DRY CREEK_1_DS 9.0
END DESCRIPTION:
XS GIS Cut Line= 3
      2096808.65     13905976.95      2095991.68     13905841.66
      2094951.90     13905948.02
#Sta/Elev= 30
  4171.9 1451.74  4273.8 1453.15  4339.8 1448.82  4378.3 1449.07  4402.5 1445.27
  4414.4 1443.90  4598.9 1414.83  4700.9 1407.47  4915.3 1397.64  4966.2 1396.81
  4976.4 1393.43  4981.9 1389.03  4982.4 1388.53  4991.1 1389.03  5000.0 1389.15
  5006.7 1394.93  5049.0 1395.71  5148.6 1395.19  5281.4 1394.79  5470.5 1395.79
  5527.5 1396.82  5599.8 1399.91  5619.9 1403.01  5629.9 1400.65  5660.1 1407.34
  5676.0 1407.56  5851.1 1422.07  5962.1 1427.56  5991.8 1430.58  6045.2 1431.28
#Mann=14,-1,0
  4171.9    0.07       0  4402.5   0.035       0  4414.4    0.07       0
  4598.9   0.035       0  4915.3    0.07       0  4981.9    0.05       0
  4991.1    0.07       0  5049.0   0.035       0  5148.6    0.07       0
  5281.4   0.035       0  5470.5    0.07       0  5527.5   0.035       0
  5676.0    0.07       0  5962.1   0.035       0
Bank Sta=4981.9,4991.1
Exp/Cntr=0.3,0.1

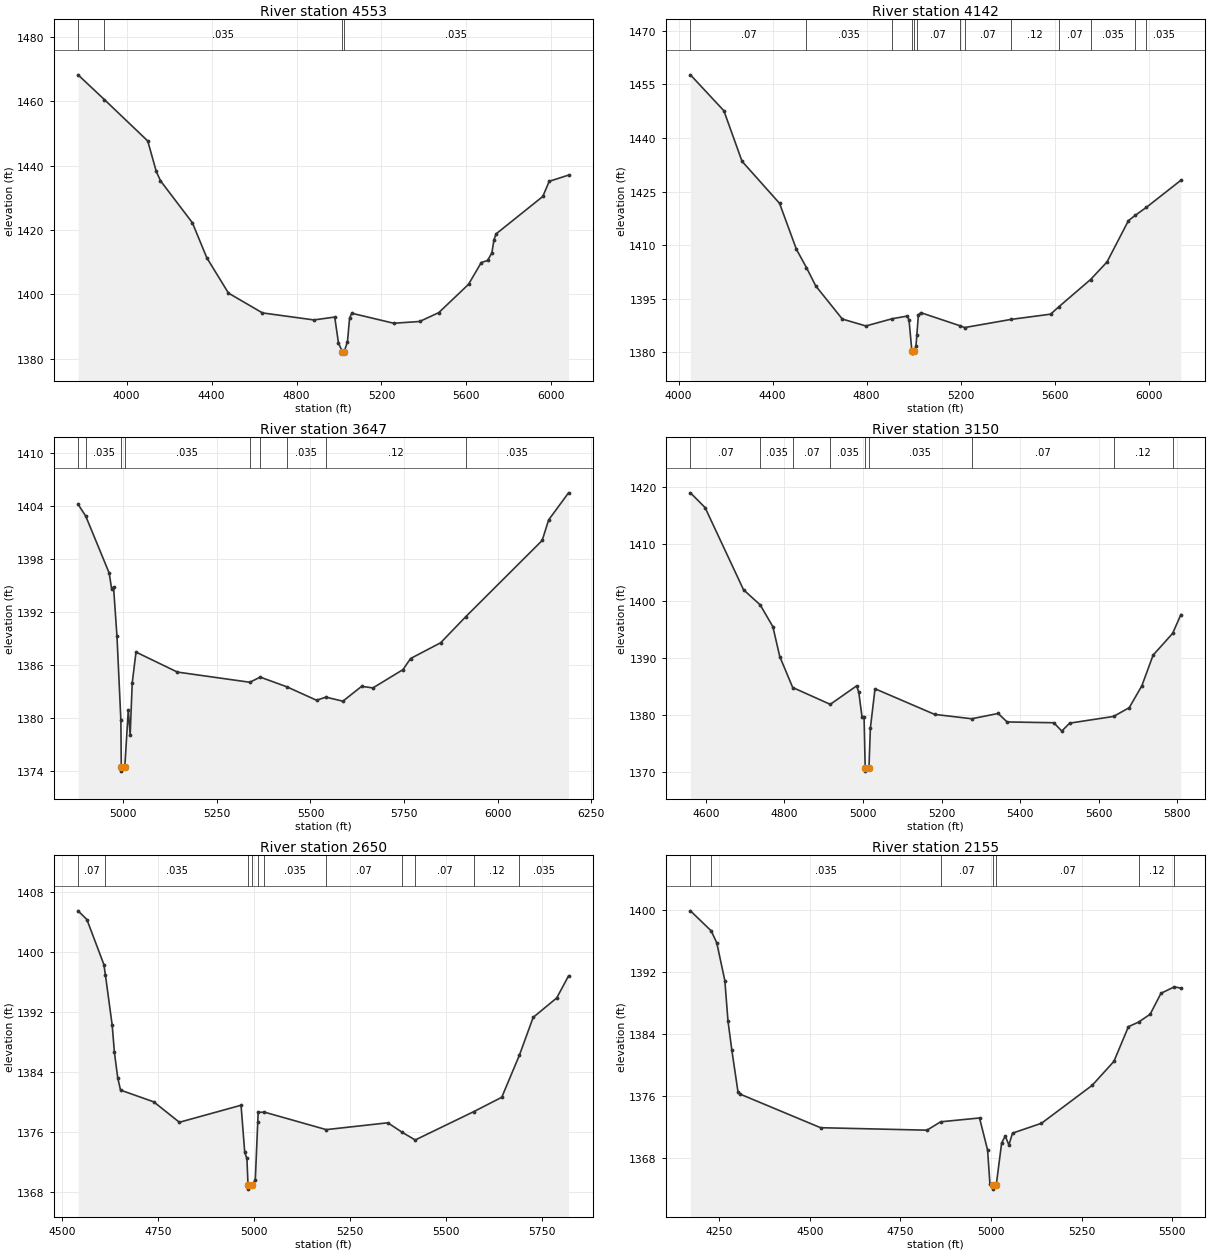
Type RM Length L Ch R = 1,4553,411,411,411
BEGIN DESCRIPTION:
DRY CREEK_1_DS 8.0
END DESCRIPTION:
XS GIS Cut Line= 3
      2097122.89     13905404.48      2095894.88     13905355.14
      2094813.97     13905375.27
#Sta/Elev= 30
  3771.0 1468.18  3895.3 1460.47  4099.2 1447.64  4139.2 1438.21  4159.2 1435.28
  4309.3 1422.25  4377.6 1411.33  4479.5 1400.38  4639.6 1394.23  4881.9 1392.05
  4979.9 1392.94  4997.4 1384.93  5015.2 1382.24  5015.7 1381.74  5024.5 1382.24
  5039.9 1385.26  5049.9 1392.63  5059.9 1394.13  5257.9 1391.02  5379.9 1391.57
  5470.0 1394.32  5610.0 1403.10  5670.0 1409.86  5700.0 1410.53  5720.0 1412.86
  5730.0 1416.95  5740.0 1418.78  5960.0 1430.40  5990.1 1435.10  6081.1 1437.03
#Mann=4,-1,0
  3771.0    0.07       0  3895.3   0.035       0  5015.2   0.035       0
  5024.5   0.035       0
Bank Sta=5015.2,5024.5
Exp/Cntr=0.3,0.1

Type RM Length L Ch R = 1,4142,495,495,495
BEGIN DESCRIPTION:
DRY CREEK_1_DS 7.0
END DESCRIPTION:
XS GIS Cut Line= 3
      2096951.73     13905374.23      2096074.59     13905011.19
      2094955.12     13905204.25
#Sta/Elev= 30
  4050.7 1457.68  4192.9 1447.62  4270.0 1433.48  4429.6 1421.70  4501.3 1408.83
  4543.8 1403.73  4583.8 1398.55  4696.5 1389.30  4796.6 1387.37  4908.7 1389.39
  4972.5 1390.14  4980.1 1389.02  4992.4 1380.26  4992.9 1379.76  5001.7 1380.26
  5009.7 1381.76  5013.4 1384.90  5019.9 1390.42  5030.0 1391.09  5194.8 1387.47
  5216.7 1386.92  5415.6 1389.22  5582.2 1390.67  5616.7 1392.72  5751.8 1400.36
  5821.7 1405.27  5912.9 1416.84  5941.8 1418.34  5989.4 1420.58  6136.0 1428.16
#Mann=13,-1,0
  4050.7    0.07       0  4543.8   0.035       0  4908.7    0.12       0
  4992.4    0.05       0  5001.7    0.12       0  5013.4    0.07       0
  5194.8    0.12       0  5216.7    0.07       0  5415.6    0.12       0
  5616.7    0.07       0  5751.8   0.035       0  5941.8    0.07       0
  5989.4   0.035       0
Bank Sta=4992.4,5001.7
Exp/Cntr=0.3,0.1

Type RM Length L Ch R = 1,3647,497,497,497
BEGIN DESCRIPTION:
DRY CREEK_1_DS 6.0
END DESCRIPTION:
XS GIS Cut Line= 3
      2096524.96     13904724.99      2096408.72     13904691.74
      2095224.97     13904575.00
#Sta/Elev= 30
  4879.1 1404.17  4899.6 1402.83  4962.3 1396.39  4968.7 1394.63  4973.9 1394.82
  4983.1 1389.23  4993.5 1379.77  4994.6 1374.52  4995.1 1374.02  5004.0 1374.52
  5013.3 1380.95  5018.3 1378.08  5023.8 1383.99  5033.9 1387.47  5144.4 1385.21
  5338.0 1384.06  5365.8 1384.64  5436.7 1383.55  5516.2 1382.03  5541.4 1382.38
  5586.6 1381.92  5636.8 1383.60  5666.9 1383.42  5747.3 1385.49  5767.4 1386.74
  5847.8 1388.52  5915.0 1391.47  6119.1 1400.08  6136.4 1402.40  6189.5 1405.46
#Mann=9,-1,0
  4879.1    0.07       0  4899.6   0.035       0  4994.6   0.035       0
  5004.0   0.035       0  5338.0    0.12       0  5365.8    0.07       0
  5436.7   0.035       0  5541.4    0.12       0  5915.0   0.035       0
Bank Sta=4994.6,5004
Exp/Cntr=0.3,0.1

Type RM Length L Ch R = 1,3150,500,500,500
BEGIN DESCRIPTION:
DRY CREEK_1_DS 5.0
END DESCRIPTION:
XS GIS Cut Line= 3
      2096774.98     13904424.99      2096375.15     13904243.23
      2095575.04     13904125.01
#Sta/Elev= 30
  4560.8 1418.97  4598.1 1416.38  4695.9 1401.94  4738.3 1399.29  4770.6 1395.45
  4788.1 1390.21  4821.0 1384.77  4916.6 1381.81  4983.7 1385.06  4989.2 1383.94
  4997.3 1379.65  5002.6 1379.65  5005.5 1370.58  5006.0 1370.08  5015.0 1370.58
  5018.7 1377.67  5030.5 1384.55  5182.1 1380.05  5276.6 1379.28  5343.8 1380.21
  5366.6 1378.72  5485.4 1378.58  5505.8 1377.12  5525.8 1378.51  5637.6 1379.69
  5677.4 1381.23  5709.5 1385.08  5738.1 1390.46  5787.7 1394.27  5808.8 1397.58
#Mann=9,-1,0
  4560.8    0.07       0  4738.3   0.035       0  4821.0    0.07       0
  4916.6   0.035       0  5005.5   0.035       0  5015.0   0.035       0
  5276.6    0.07       0  5637.6    0.12       0  5787.7    0.07       0
Bank Sta=5005.5,5015
Exp/Cntr=0.3,0.1

Type RM Length L Ch R = 1,2650,495,495,495
BEGIN DESCRIPTION:
DRY CREEK_1_DS 4.0
END DESCRIPTION:
XS GIS Cut Line= 3
      2096775.04     13904025.02      2096375.27     13903799.89
      2095575.01     13903975.00
#Sta/Elev= 30
  4541.2 1405.52  4564.2 1404.36  4608.5 1398.36  4612.6 1396.92  4630.1 1390.29
  4635.9 1386.66  4644.5 1383.29  4651.8 1381.63  4738.5 1380.06  4805.2 1377.34
  4965.9 1379.61  4975.5 1373.32  4981.2 1372.52  4984.1 1368.93  4984.6 1368.43
  4993.6 1368.93  5003.0 1369.62  5009.4 1377.33  5010.5 1378.66  5026.9 1378.69
  5187.8 1376.36  5348.3 1377.27  5385.6 1376.01  5419.7 1374.98  5572.3 1378.76
  5645.2 1380.67  5691.2 1386.28  5727.1 1391.32  5788.5 1393.91  5819.2 1396.85
#Mann=11,-1,0
  4541.2    0.07       0  4612.6   0.035       0  4984.1   0.035       0
  4993.6   0.035       0  5009.4    0.07       0  5026.9   0.035       0
  5187.8    0.07       0  5385.6    0.12       0  5419.7    0.07       0
  5572.3    0.12       0  5691.2   0.035       0
Bank Sta=4984.1,4993.6
Exp/Cntr=0.3,0.1

Type RM Length L Ch R = 1,2155,490,490,490
BEGIN DESCRIPTION:
DRY CREEK_1_DS 3.0
END DESCRIPTION:
XS GIS Cut Line= 3
      2096925.04     13903174.99      2096124.40     13903393.43
      2095600.13     13903398.76
#Sta/Elev= 30
  4170.1 1399.83  4227.3 1397.26  4242.7 1395.73  4265.1 1390.86  4273.8 1385.66
  4284.2 1381.98  4301.4 1376.55  4306.6 1376.27  4529.4 1371.94  4823.2 1371.62
  4861.1 1372.70  4968.3 1373.19  4990.6 1369.06  4997.1 1364.65  5004.5 1364.54
  5005.0 1364.04  5014.4 1364.54  5029.4 1369.99  5039.4 1370.87  5049.4 1369.71
  5059.4 1371.24  5139.4 1372.51  5279.4 1377.39  5339.4 1380.47  5379.4 1384.93
  5407.4 1385.52  5439.4 1386.53  5469.4 1389.23  5506.1 1390.05  5524.3 1389.89
#Mann=7,-1,0
  4170.1    0.12       0  4227.3   0.035       0  4861.1    0.07       0
  5004.5    0.05       0  5014.4    0.07       0  5407.4    0.12       0
  5506.1   0.035       0
Bank Sta=5004.5,5014.4
Exp/Cntr=0.3,0.1

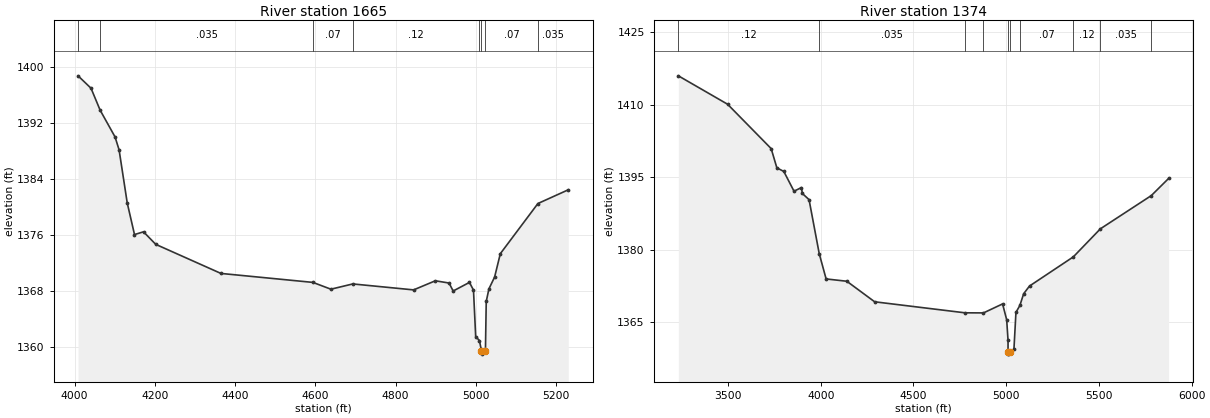
Type RM Length L Ch R = 1,1665,291,291,291
BEGIN DESCRIPTION:
DRY CREEK_1_DS 2.0
END DESCRIPTION:
XS GIS Cut Line= 3
      2096895.75     13903144.92      2095919.23     13902972.68
      2095745.91     13903124.48
#Sta/Elev= 30
  4008.4 1398.67  4040.7 1396.90  4063.5 1393.76  4100.6 1389.95  4110.7 1388.10
  4131.0 1380.52  4149.1 1376.01  4171.6 1376.40  4202.1 1374.61  4364.6 1370.46
  4593.8 1369.18  4638.7 1368.21  4693.3 1368.96  4844.8 1368.11  4899.0 1369.41
  4933.2 1369.09  4943.4 1367.95  4984.0 1369.18  4994.1 1368.08  4999.6 1361.44
  5008.9 1360.88  5013.9 1359.44  5014.4 1358.94  5023.9 1359.44  5025.9 1366.46
  5032.6 1368.26  5046.8 1369.95  5061.0 1373.28  5154.7 1380.44  5230.4 1382.40
#Mann=8,-1,0
  4008.4    0.12       0  4063.5   0.035       0  4593.8    0.07       0
  4693.3    0.12       0  5008.9    0.07       0  5013.9    0.05       0
  5023.9    0.07       0  5154.7   0.035       0
Bank Sta=5013.9,5023.9
Exp/Cntr=0.3,0.1

Type RM Length L Ch R = 1,1374,0,0,0
BEGIN DESCRIPTION:
DRY CREEK_1_DS 1.0
END DESCRIPTION:
XS GIS Cut Line= 3
      2097544.86     13903076.59      2095814.39     13902715.25
      2095550.00     13903549.99
#Sta/Elev= 30
  3232.2 1416.00  3497.7 1410.12  3732.6 1400.94  3763.3 1396.96  3800.8 1396.21
  3855.9 1392.12  3895.7 1392.88  3900.8 1391.65  3936.9 1390.38  3991.9 1379.18
  4028.9 1373.97  4140.6 1373.49  4290.6 1369.24  4777.4 1366.96  4877.4 1366.94
  4980.4 1368.80  5002.5 1365.53  5009.8 1361.30  5010.0 1358.91  5010.5 1358.41
  5020.0 1358.91  5041.7 1359.45  5052.5 1367.05  5073.8 1368.49  5094.1 1370.91
  5125.6 1372.50  5362.0 1378.54  5507.8 1384.34  5782.4 1391.22  5875.6 1394.76
#Mann=10,-1,0
  3232.2    0.12       0  3991.9   0.035       0  4777.4    0.07       0
  4877.4    0.12       0  5010.0    0.05       0  5020.0    0.12       0
  5073.8    0.07       0  5362.0    0.12       0  5507.8   0.035       0
  5782.4    0.07       0
Bank Sta=5010,5020
Exp/Cntr=0.3,0.1

Chan Stop Cuts=-1