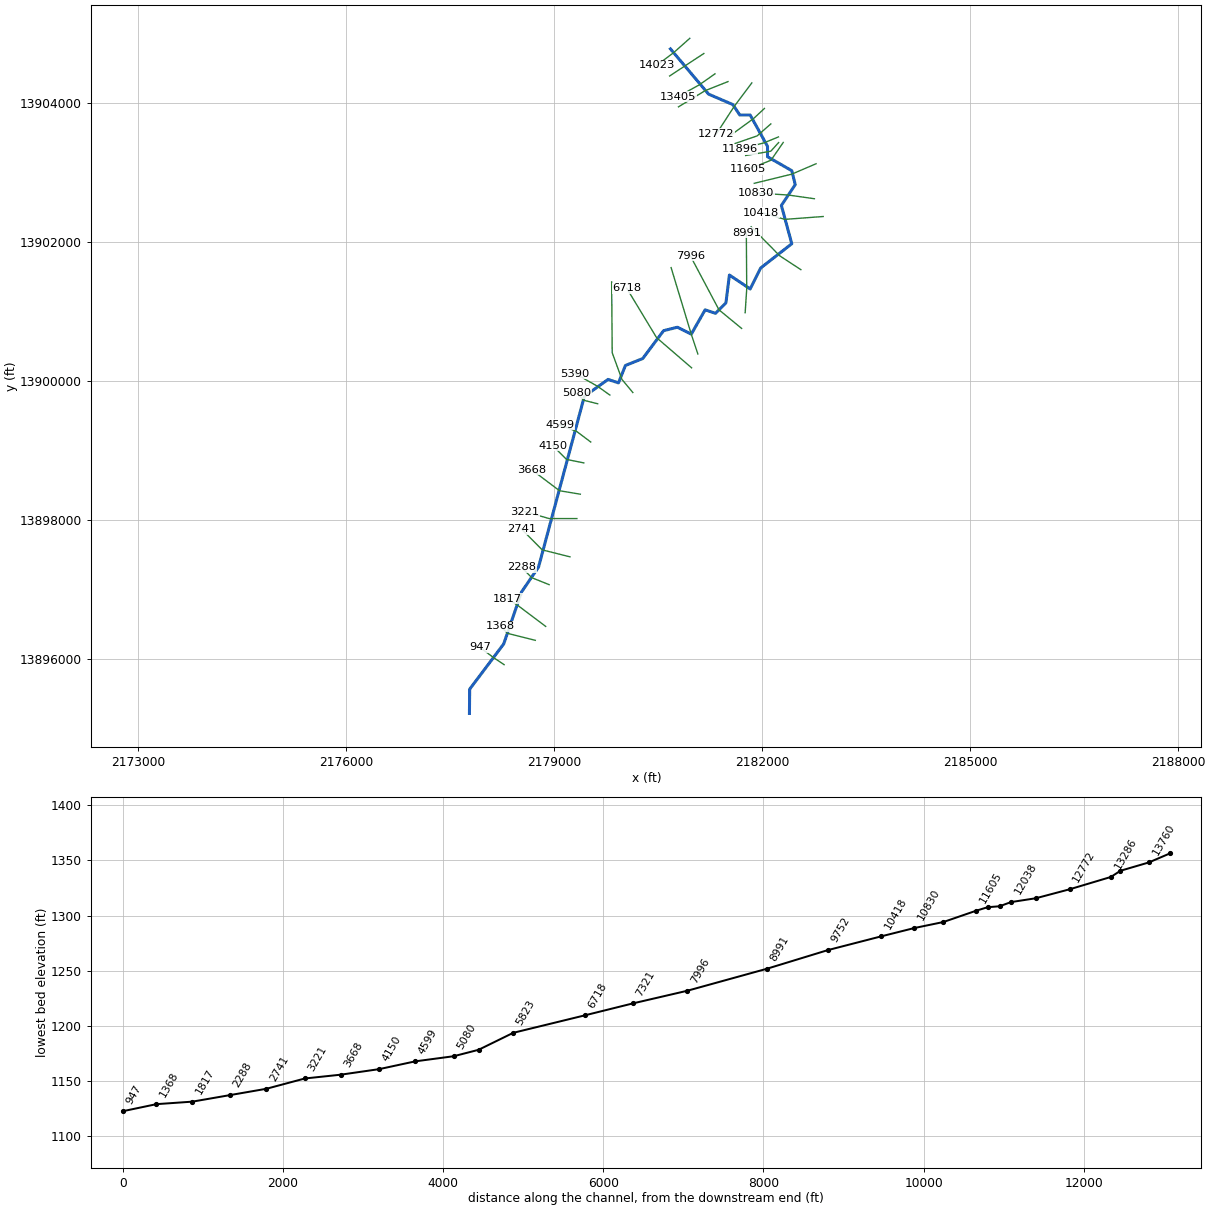
--- Devils Hollow Tributary 5.prj (project) ---

Proj Title=Devils Hollow Tributary 5 Base Level Engineering
Current Plan=p01
Default Exp/Contr=0.3,0.1
English Units
Geom File=g01
Flow File=f01
Plan File=p01
Y Axis Title=Elevation
X Axis Title(PF)=Main Channel Distance
X Axis Title(XS)=Station
BEGIN DESCRIPTION:
Devils Hollow Tributary 5
END DESCRIPTION:
DSS Export Rating Curves= 0
DSS Export Rating Curve Sorted= 0
DSS Export Volume Flow Curves= 0
DXF OffsetX= 0
DXF OffsetY= 0
DXF ScaleX= 1
DXF ScaleY= 10

--- Devils Hollow Tributary 5.p01 (plan) ---

Plan Title=Multiple Run
Short Identifier=Multiple
Geom File=g01
Flow File=f01
Subcritical Flow
K Sum by GR= 0
Std Step Tol= 0.01
Critical Tol= 0.01
Num of Std Step Trials= 20
Max Error Tol= 0.3
Flow Tol Ratio= 0.001
Split Flow NTrial= 30
Split Flow Tol= 0.02
Split Flow Ratio= 0.02
Log Output Level= 0
Friction Slope Method= 1
Unsteady Friction Slope Method= 2
Unsteady Bridges Friction Slope Method= 1
Parabolic Critical Depth
Global Vel Dist=  1 , 1 , 1
Global Log Level= 0
CheckData=True
Encroach Param= -1, 0, 0, 0
BEGIN DESCRIPTION:
Multiple Run
END DESCRIPTION:

--- Devils Hollow Tributary 5.f01 (steady flow) ---

Flow Title=Multiple
Number of Profiles=7
Profile Names=10-year,25-year,50-year,1pct_min,100-year,1pct_plu,500-year
River Rch & RM= Devils Hollow Tr,Reach-1,14023
     264     406     530     338     674    1344    1069
River Rch & RM= Devils Hollow Tr,Reach-1,12772
     629    1029    1397     922    1839    3669    3146
River Rch & RM= Devils Hollow Tr,Reach-1,8991
    1567    2713    3825    2613    5213   10401    9575
River Rch & RM= Devils Hollow Tr,Reach-1,5080
    1847    3227    4577    3141    6268   12506   11636
Boundary for River Rch & Prof#=Devils Hollow Tr,Reach-1,1
Up Type=0
Dn Type=3
Dn Slope=0.005
Boundary for River Rch & Prof#=Devils Hollow Tr,Reach-1,2
Up Type=0
Dn Type=3
Dn Slope=0.005
Boundary for River Rch & Prof#=Devils Hollow Tr,Reach-1,3
Up Type=0
Dn Type=3
Dn Slope=0.005
Boundary for River Rch & Prof#=Devils Hollow Tr,Reach-1,4
Up Type=0
Dn Type=3
Dn Slope=0.005
Boundary for River Rch & Prof#=Devils Hollow Tr,Reach-1,5
Up Type=0
Dn Type=3
Dn Slope=0.005
Boundary for River Rch & Prof#=Devils Hollow Tr,Reach-1,6
Up Type=0
Dn Type=3
Dn Slope=0.005
Boundary for River Rch & Prof#=Devils Hollow Tr,Reach-1,7
Up Type=0
Dn Type=3
Dn Slope=0.005

--- Devils Hollow Tributary 5.g01 (geometry) ---

Geom Title=Existing Conditions
Program Version=4.10

River Reach=Devils Hollow Tr,Reach-1
Reach XY= 30
        2180675.       13904775.        2181225.       13904125.
        2181575.       13903975.        2181675.       13903825.
        2181825.       13903825.        2182075.       13903375.
        2182075.       13903225.        2182425.       13903025.
        2182475.       13902825.        2182275.       13902525.
        2182425.       13901975.        2181975.       13901625.
        2181825.       13901325.        2181525.       13901525.
        2181475.       13901125.        2181325.       13900975.
        2181175.       13901025.        2180975.       13900675.
        2180775.       13900775.        2180575.       13900725.
        2180275.       13900325.        2180025.       13900225.
        2179925.       13899975.        2179775.       13900025.
      2179432.74     13899781.22      2178771.45     13897326.47
      2178528.62      13896973.5      2178269.15     13896222.71
      2177778.55     13895573.53        2177775.       13895225.

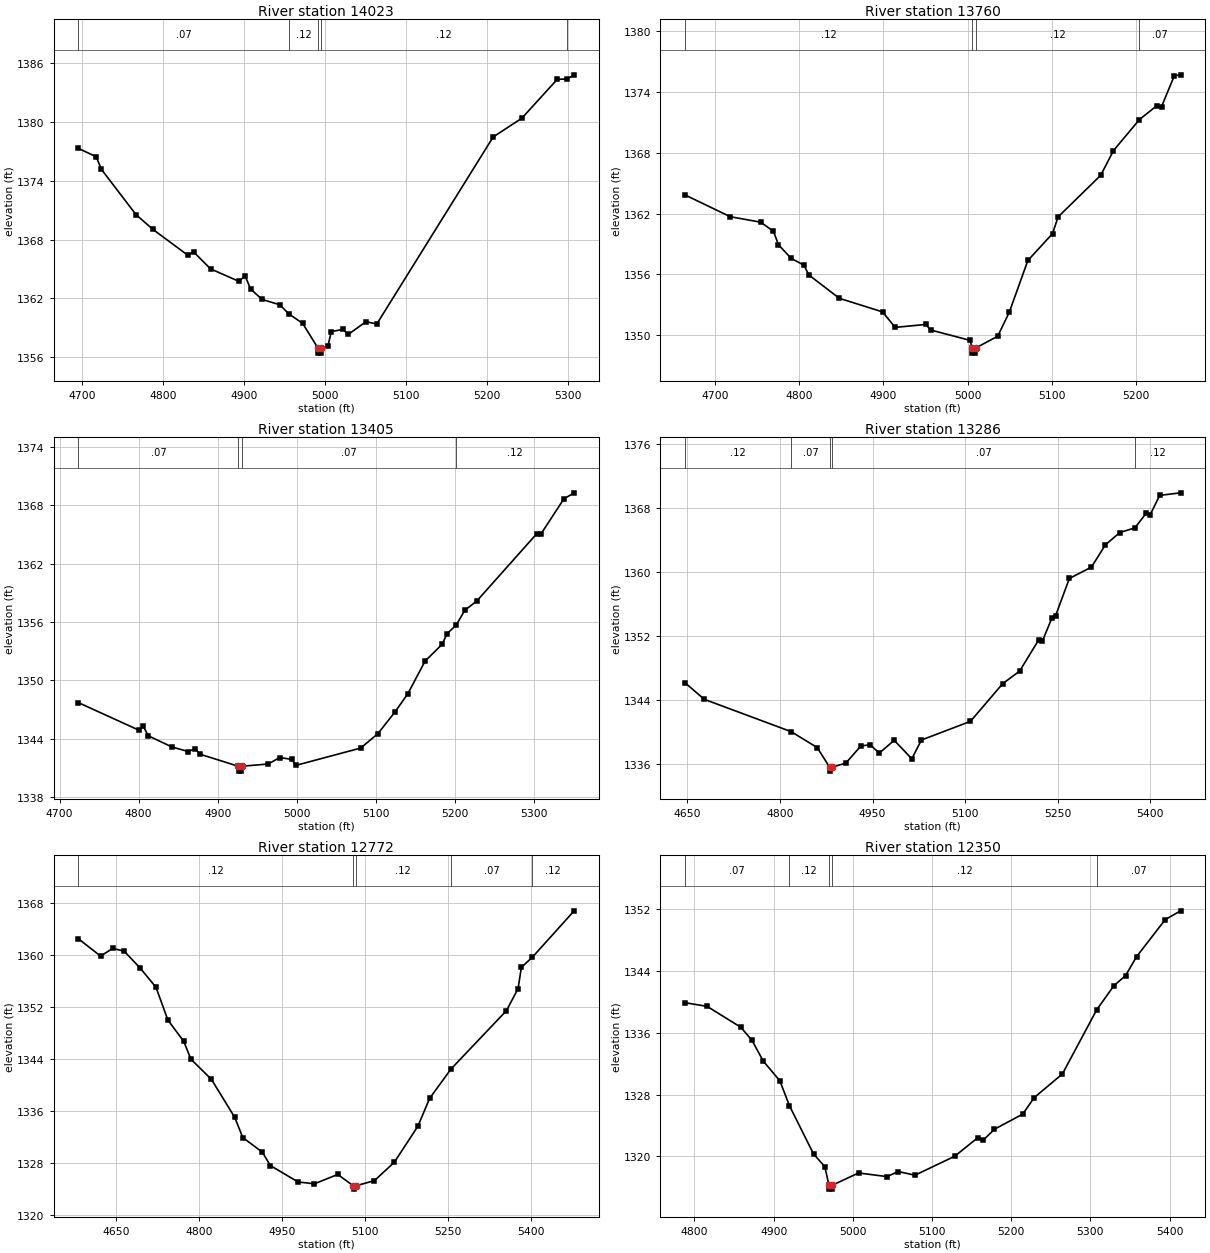
Type RM Length L Ch R = 1 ,14023   ,263,263,263
BEGIN DESCRIPTION:
Devils Hollow Tributary 5 31.0
END DESCRIPTION:
XS GIS Cut Line= 3
      2180953.53     13904927.14        2180725.       13904725.
      2180479.52     13904540.31
#Sta/Elev= 30
  4694.9 1377.29  4716.9 1376.44  4723.5 1375.14  4766.2 1370.53  4787.1 1369.03
  4829.8 1366.42  4837.3 1366.74  4858.2 1365.01  4893.3 1363.74  4900.9  1364.3
  4907.6 1362.96  4921.8  1361.9  4943.5 1361.36  4954.9 1360.43    4972 1359.45
  4990.9 1356.93  4991.1 1356.43  4994.6 1356.43  4994.9 1356.93  5003.1 1357.14
  5007.3 1358.63  5021.9 1358.84  5028.1 1358.33  5050.1 1359.63  5063.5  1359.4
  5207.2 1378.45  5242.6 1380.36  5286.3 1384.32  5298.7 1384.36  5307.2 1384.78
#Mann= 5 ,-1 , 0
  4694.9     .07       0  4954.9     .12       0  4990.9     .05       0
  4994.9     .12       0  5298.7     .07       0
Bank Sta=4990.9,4994.9
XS Rating Curve= 0 ,0
Exp/Cntr=0.3,0.1

Type RM Length L Ch R = 1 ,13760   ,355,355,355
BEGIN DESCRIPTION:
Devils Hollow Tributary 5 30.0
END DESCRIPTION:
XS GIS Cut Line= 3
      2181155.97     13904709.08        2180875.       13904525.
      2180663.16     13904386.31
#Sta/Elev= 30
  4664.1 1363.86  4718.1  1361.7  4754.3 1361.16  4769.4 1360.26  4775.4 1358.93
  4790.5 1357.59  4805.6 1356.92  4811.5 1355.95  4847.7 1353.65    4899 1352.31
  4914.1 1350.78  4950.3 1351.07  4956.3 1350.52    5003  1349.5  5005.6 1348.74
  5005.8 1348.24  5009.3 1348.24  5009.6 1348.74  5035.9 1349.91  5049.7 1352.29
  5071.7 1357.38    5101 1360.03  5107.6 1361.68  5158.3 1365.79  5173.4 1368.22
  5204.3 1371.29  5224.7 1372.64  5230.6 1372.57  5245.7 1375.61  5253.2  1375.7
#Mann= 4 ,-1 , 0
  4664.1     .12       0  5005.6     .05       0  5009.6     .12       0
  5204.3     .07       0
Bank Sta=5005.6,5009.6
XS Rating Curve= 0 ,0
Exp/Cntr=0.3,0.1

Type RM Length L Ch R = 1 ,13405   ,119,119,119
BEGIN DESCRIPTION:
Devils Hollow Tributary 5 29.0
END DESCRIPTION:
XS GIS Cut Line= 3
      2181317.52     13904417.16      2181091.27     13904258.73
      2180783.64     13904089.93
#Sta/Elev= 30
  4723.8 1347.72    4800  1344.9  4806.1 1345.27  4812.3 1344.31  4841.9 1343.17
  4862.8 1342.69  4871.5 1342.99  4877.6 1342.42  4926.2 1341.18  4926.4 1340.68
  4929.9 1340.68  4930.2 1341.18  4963.9 1341.41  4978.7 1342.08  4993.6 1341.88
  4998.9 1341.27  5080.9 1343.05  5102.7 1344.53  5124.5 1346.78  5140.6 1348.64
  5162.4 1351.99  5184.2 1353.73  5189.9 1354.78  5201.9  1355.7  5212.5  1357.2
  5227.8 1358.16  5303.6 1365.07  5309.3 1365.09  5337.9 1368.65  5350.9 1369.27
#Mann= 4 ,-1 , 0
  4723.8     .07       0  4926.2     .05       0  4930.2     .07       0
  5201.9     .12       0
Bank Sta=4926.2,4930.2
XS Rating Curve= 0 ,0
Exp/Cntr=0.3,0.1

Type RM Length L Ch R = 1 ,13286   ,514,514,514
BEGIN DESCRIPTION:
Devils Hollow Tributary 5 28.0
END DESCRIPTION:
XS GIS Cut Line= 3
      2181504.38     13904305.25        2181175.       13904175.
      2180790.72     13903942.57
#Sta/Elev= 30
  4645.8 1346.13  4677.4 1344.04  4818.2    1340  4860.2 1338.02  4880.4 1335.57
  4880.6 1335.07  4884.4 1335.57  4906.7 1336.07  4931.1 1338.22  4946.2 1338.36
  4960.8 1337.32  4985.1 1338.92  5013.6 1336.61  5029.1 1338.95  5108.6 1341.29
    5161 1346.01  5188.2 1347.56  5219.2 1351.47  5225.1 1351.31  5240.6 1354.21
  5246.4 1354.46  5268.8 1359.14  5304.6 1360.56  5327.2 1363.34  5350.6 1364.88
    5375 1365.46  5393.8 1367.34  5399.7 1367.09  5415.2 1369.52  5449.1 1369.84
#Mann= 5 ,-1 , 0
  4645.8     .12       0  4818.2     .07       0  4880.4     .05       0
  4884.4     .07       0    5375     .12       0
Bank Sta=4880.4,4884.4
XS Rating Curve= 0 ,0
Exp/Cntr=0.3,0.1

Type RM Length L Ch R = 1 ,12772   ,422,422,422
BEGIN DESCRIPTION:
Devils Hollow Tributary 5 27.0
END DESCRIPTION:
XS GIS Cut Line= 3
      2181849.05     13904287.17       2181597.2      13903952.8
      2181336.27     13903552.54
#Sta/Elev= 30
  4581.4 1362.45  4621.7 1359.77  4643.4 1360.95  4664.2 1360.54  4693.3 1357.92
  4721.8 1354.97  4743.3 1349.93  4771.9 1346.66    4785  1343.9    4822 1340.81
  4864.1 1334.96  4878.7 1331.85  4914.1 1329.59  4928.6 1327.54  4978.6 1325.01
  5008.3 1324.73  5050.4 1326.17  5078.7 1324.41  5078.9 1323.91  5082.7 1324.41
  5116.8 1325.22  5152.6 1328.04  5195.3 1333.59  5216.4 1337.86  5255.1 1342.39
  5355.3 1351.37  5376.4 1354.77  5382.4 1358.05    5402 1359.58  5477.8 1366.74
#Mann= 5 ,-1 , 0
  4581.4     .12       0  5078.7     .05       0  5082.7     .12       0
  5255.1     .07       0    5402     .12       0
Bank Sta=5078.7,5082.7
XS Rating Curve= 0 ,0
Exp/Cntr=0.3,0.1

Type RM Length L Ch R = 1 ,12350   ,312,312,312
BEGIN DESCRIPTION:
Devils Hollow Tributary 5 26.0
END DESCRIPTION:
XS GIS Cut Line= 3
      2182030.42     13903919.47        2181875.       13903775.
      2181540.05     13903531.69
#Sta/Elev= 30
  4787.8 1339.87    4816 1339.39  4858.6 1336.69  4872.7 1334.99  4886.9 1332.32
  4907.9 1329.76  4919.9 1326.57  4950.4 1320.31  4964.6 1318.68  4969.9 1316.27
  4970.2 1315.77  4973.7 1315.77  4973.9 1316.27  5007.3 1317.86  5042.9 1317.39
  5057.6 1318.04  5078.5 1317.57  5128.7 1320.02  5158.1 1322.44  5164.3 1322.06
  5178.9 1323.51  5214.5 1325.46  5229.2 1327.61  5264.7 1330.66  5308.1 1338.96
  5329.7 1342.06  5344.4 1343.36  5358.4 1345.82  5394.6 1350.61    5414 1351.74
#Mann= 5 ,-1 , 0
  4787.8     .07       0  4919.9     .12       0  4969.9     .05       0
  4973.9     .12       0  5308.1     .07       0
Bank Sta=4969.9,4973.9
XS Rating Curve= 0 ,0
Exp/Cntr=0.3,0.1

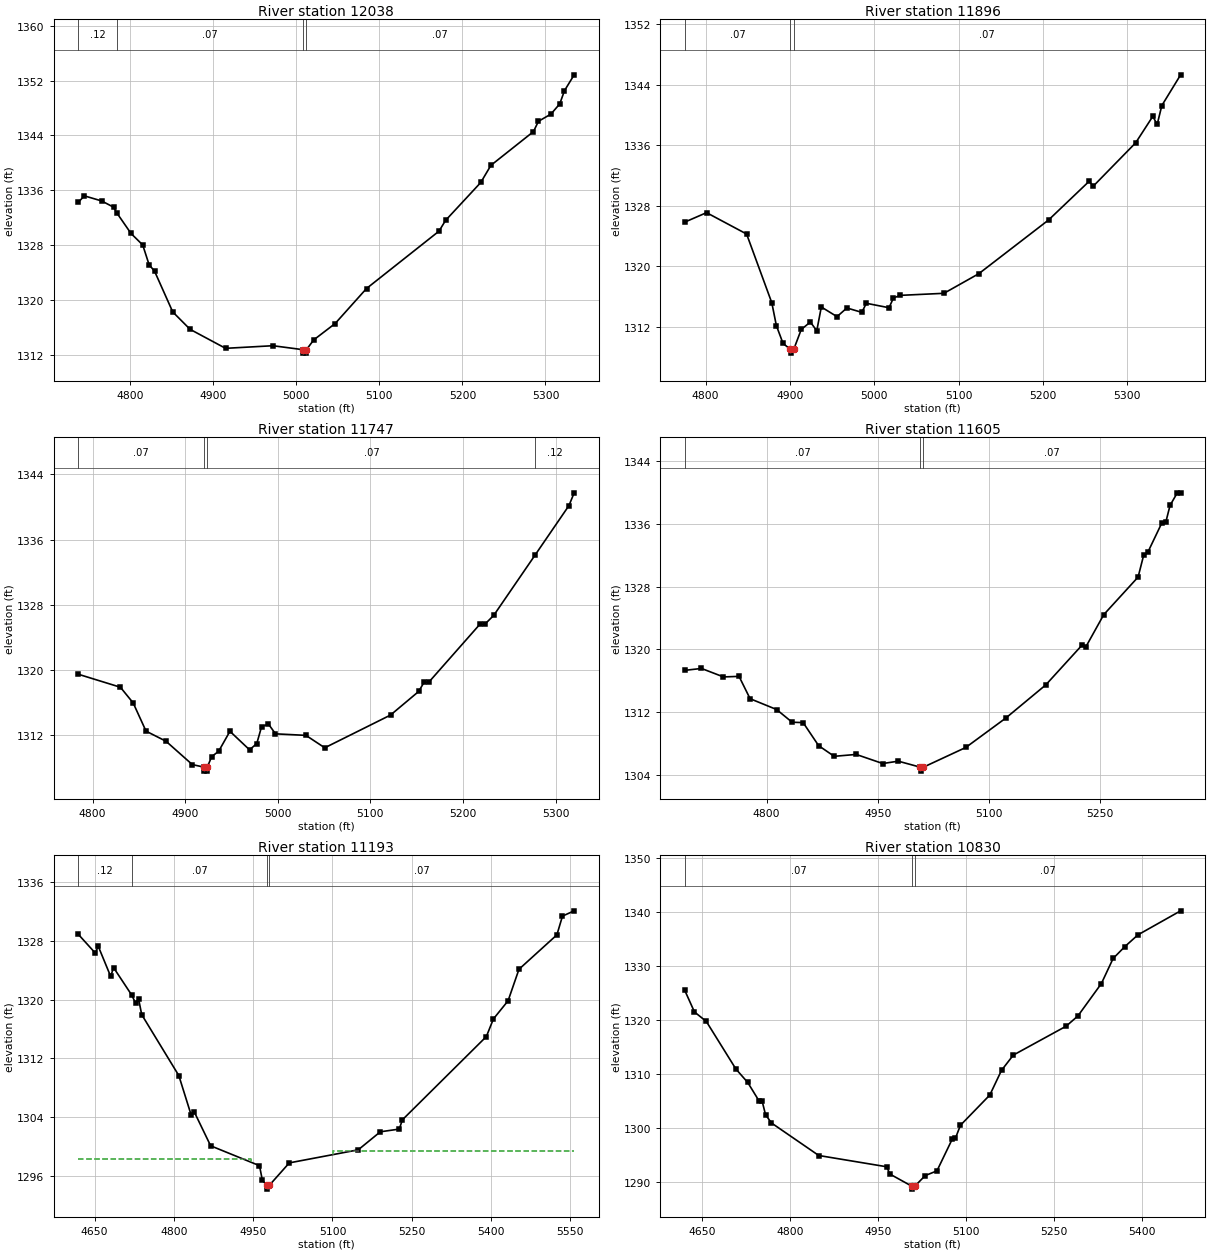
Type RM Length L Ch R = 1 ,12038   ,142,142,142
BEGIN DESCRIPTION:
Devils Hollow Tributary 5 25.0
END DESCRIPTION:
XS GIS Cut Line= 3
      2182122.82     13903697.09        2181925.       13903525.
      2181608.66     13903416.28
#Sta/Elev= 30
  4737.8 1334.27  4745.1 1335.19  4765.9 1334.45  4780.2 1333.54  4783.8 1332.76
  4801.2 1329.71  4815.3 1328.03  4822.9 1325.17  4829.6 1324.19  4851.4 1318.27
  4872.3 1315.73    4915 1312.96    4972 1313.34  5008.3 1312.76  5008.6 1312.26
  5012.1 1312.26  5012.3 1312.76  5021.1 1314.19  5046.9 1316.58  5084.6 1321.68
  5171.8 1330.04  5179.8 1331.62  5222.1 1337.14  5234.3 1339.64  5285.5 1344.56
  5291.5 1346.06  5306.6 1347.12  5317.2 1348.61  5322.8 1350.52  5334.5 1352.84
#Mann= 4 ,-1 , 0
  4737.8     .12       0  4783.8     .07       0  5008.3     .05       0
  5012.3     .07       0
Bank Sta=5008.3,5012.3
XS Rating Curve= 0 ,0
Exp/Cntr=0.3,0.1

Type RM Length L Ch R = 1 ,11896   ,149,149,149
BEGIN DESCRIPTION:
Devils Hollow Tributary 5 24.0
END DESCRIPTION:
XS GIS Cut Line= 3
      2182232.78     13903510.27        2182025.       13903425.
      2181673.48     13903332.86
#Sta/Elev= 30
  4775.4 1325.83  4801.2 1327.08  4848.7 1324.25  4878.6 1315.14    4884 1312.12
  4891.9 1309.77  4900.6 1308.98  4900.8 1308.48  4904.6 1308.98  4913.5 1311.61
  4924.3  1312.6  4931.9 1311.44  4937.3 1314.59  4955.9 1313.31  4967.6 1314.46
  4985.3 1313.88  4990.7 1315.08  5017.6 1314.49  5022.8 1315.78    5031 1316.13
  5082.7  1316.4  5124.1    1319  5206.8 1326.11  5254.8 1331.22    5260 1330.61
  5310.1 1336.33  5330.4 1339.83  5335.6 1338.76  5341.1 1341.26  5363.4 1345.33
#Mann= 3 ,-1 , 0
  4775.4     .07       0  4900.6     .05       0  4904.6     .07       0
Bank Sta=4900.6,4904.6
XS Rating Curve= 0 ,0
Exp/Cntr=0.3,0.1

Type RM Length L Ch R = 1 ,11747   ,142,142,142
BEGIN DESCRIPTION:
Devils Hollow Tributary 5 23.0
END DESCRIPTION:
XS GIS Cut Line= 4
      2182234.87     13903428.81      2182122.67     13903305.24
        2182075.     13903296.36      2181759.45     13903243.16
#Sta/Elev= 30
  4784.6 1319.49    4830  1317.9  4843.8 1315.98  4857.7 1312.52  4879.3 1311.28
  4907.7 1308.42  4919.9 1308.12  4920.1 1307.62  4923.6 1307.62  4923.9 1308.12
  4928.6  1309.4  4936.1 1310.05  4948.3  1312.5  4969.5 1310.23  4977.3    1311
  4982.4 1313.04  4989.8  1313.4  4997.5 1312.19  5030.4    1312  5050.7 1310.48
  5121.7 1314.49  5152.1 1317.38  5157.9  1318.5  5162.9  1318.5  5218.4 1325.64
  5223.4  1325.6  5233.2 1326.71  5278.2 1334.16  5314.4 1340.16    5320 1341.72
#Mann= 4 ,-1 , 0
  4784.6     .07       0  4919.9     .05       0  4923.9     .07       0
  5278.2     .12       0
Bank Sta=4919.9,4923.9
XS Rating Curve= 0 ,0
Exp/Cntr=0.3,0.1

Type RM Length L Ch R = 1 ,11605   ,412,412,412
BEGIN DESCRIPTION:
Devils Hollow Tributary 5 22.0
END DESCRIPTION:
XS GIS Cut Line= 3
      2182301.55      13903430.3        2182125.       13903175.
       2181791.7     13903042.43
#Sta/Elev= 30
  4689.6 1317.34  4712.1 1317.58  4741.8  1316.5  4762.8 1316.57  4777.7 1313.72
  4813.5 1312.34  4834.4 1310.72  4849.3 1310.67  4870.2 1307.73  4891.2 1306.37
  4920.9 1306.61  4956.7 1305.45  4977.7 1305.75  5007.5 1304.98  5007.7 1304.48
  5011.5 1304.98  5068.8  1307.5  5122.8 1311.25  5176.7 1315.48  5225.3 1320.52
  5230.7 1320.32    5255 1324.45  5301.3 1329.24  5308.9 1332.06  5314.3 1332.38
  5333.2 1336.12  5338.6 1336.21  5344.4 1338.38  5354.2 1339.99  5358.7 1339.99
#Mann= 3 ,-1 , 0
  4689.6     .07       0  5007.5     .05       0  5011.5     .07       0
Bank Sta=5007.5,5011.5
XS Rating Curve= 0 ,0
Exp/Cntr=0.3,0.1

Type RM Length L Ch R = 1 ,11193   ,363,363,363
BEGIN DESCRIPTION:
Devils Hollow Tributary 5 21.0
END DESCRIPTION:
XS GIS Cut Line= 3
      2182775.24     13903124.48        2182425.       13902975.
      2181883.56     13902843.43
#Sta/Elev= 30
  4619.2 1328.92  4651.4 1326.36  4656.8 1327.31  4680.4 1323.18  4685.8 1324.39
  4720.1 1320.65  4727.6 1319.53  4733.1 1320.14  4739.1 1317.97  4809.3 1309.66
  4832.9 1304.22  4838.4 1304.72  4869.5 1300.08  4961.9 1297.37  4967.4 1295.36
  4976.3 1294.67  4976.5 1294.17  4980.3 1294.67  5018.3 1297.75  5148.7 1299.53
  5190.5 1301.99  5226.4 1302.36  5232.2 1303.62  5391.1 1314.98  5404.4 1317.38
  5432.2 1319.86  5452.8 1324.16  5524.5 1328.85  5535.1 1331.41  5557.2 1332.13
#Mann= 4 ,-1 , 0
  4619.2     .12       0  4720.1     .07       0  4976.3     .05       0
  4980.3     .07       0
#XS Ineff= 2 , 0
       0  4945.4 1298.24 5101.26       0 1299.32
Permanent Ineff=
       F       F
Bank Sta=4976.3,4980.3
XS Rating Curve= 0 ,0
Exp/Cntr=0.3,0.1

Type RM Length L Ch R = 1 ,10830   ,412,412,412
BEGIN DESCRIPTION:
Devils Hollow Tributary 5 20.0
END DESCRIPTION:
XS GIS Cut Line= 3
      2182751.33     13902621.59        2182375.       13902675.
      2181910.06     13902704.83
#Sta/Elev= 30
  4619.9 1325.52  4636.4 1321.53  4656.6 1319.78  4707.1 1310.96  4727.3 1308.47
  4746.7 1305.03  4751.7 1305.08  4757.6 1302.52  4767.7 1300.97  4848.5 1294.94
  4964.5 1292.85  4969.7 1291.51    5008 1289.21  5008.3 1288.71    5012 1289.21
  5030.1 1291.22  5050.1 1292.09  5076.6 1298.06  5081.6 1298.12  5090.2 1300.54
  5140.3 1306.14  5160.3 1310.72  5180.4 1313.54  5270.6  1318.9  5290.6 1320.79
  5330.7  1326.8  5350.7 1331.44  5370.8 1333.65  5393.1 1335.82  5465.9 1340.27
#Mann= 3 ,-1 , 0
  4619.9     .07       0    5008     .05       0    5012     .07       0
Bank Sta=5008,5012
XS Rating Curve= 0 ,0
Exp/Cntr=0.3,0.1

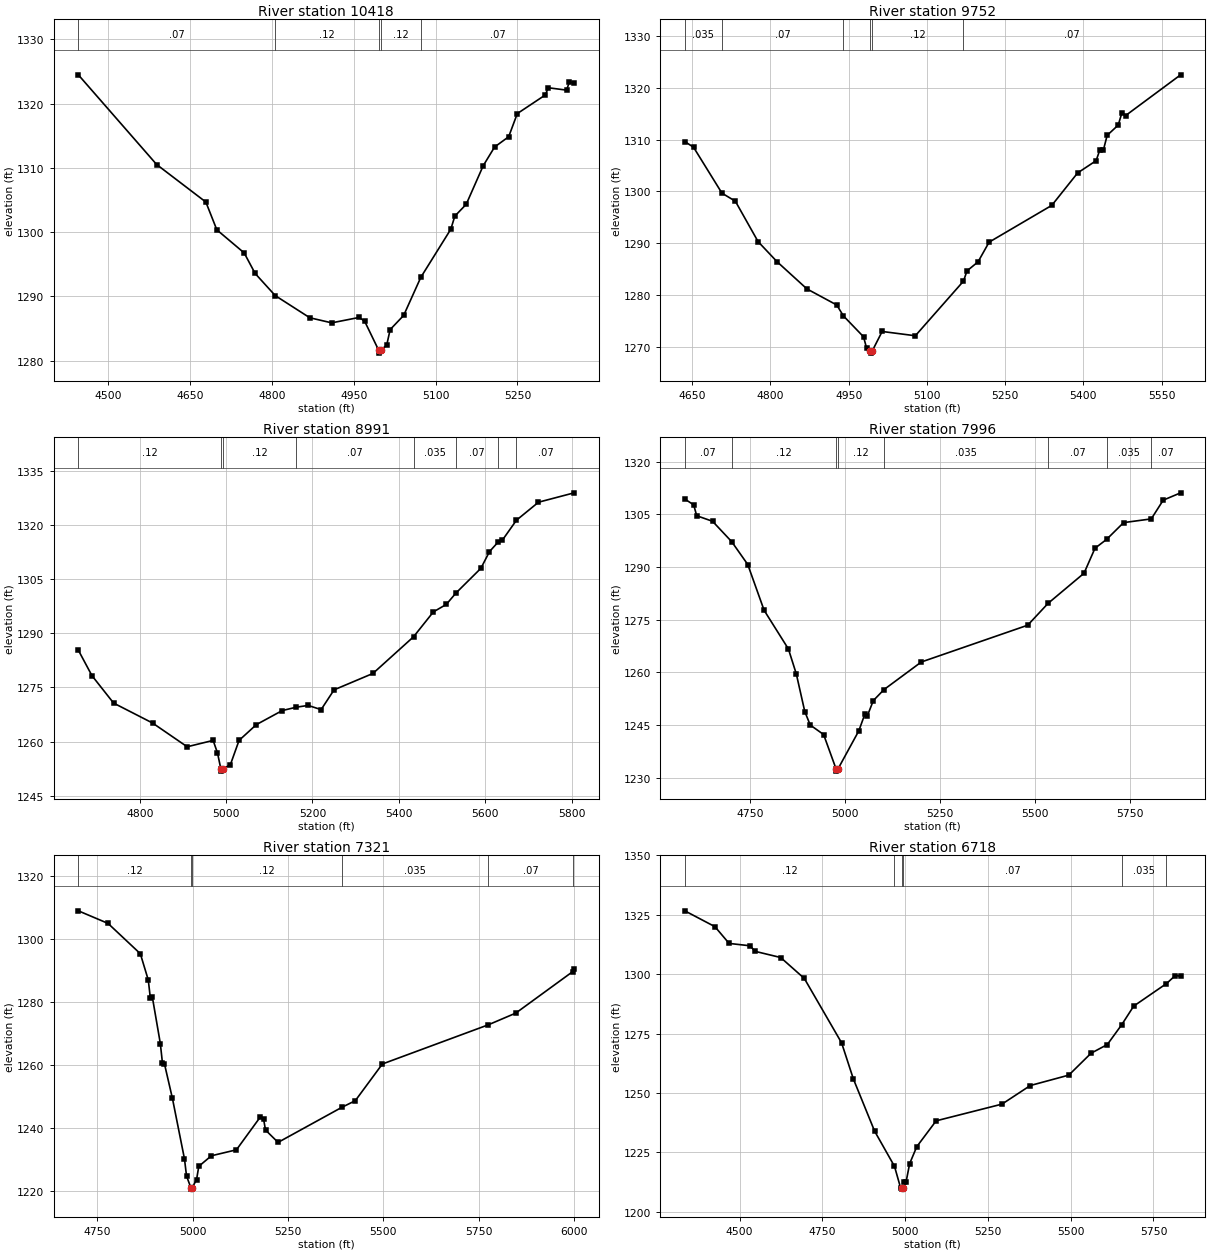
Type RM Length L Ch R = 1 ,10418   ,666,666,666
BEGIN DESCRIPTION:
Devils Hollow Tributary 5 19.0
END DESCRIPTION:
XS GIS Cut Line= 3
      2182878.05     13902366.39        2182325.       13902325.
      2181984.95      13902423.4
#Sta/Elev= 30
  4445.4 1324.48  4588.9 1310.53  4679.1 1304.69  4699.2 1300.37  4749.3 1296.78
  4769.4 1293.58  4806.2 1290.14  4869.6 1286.69  4909.7  1285.9  4959.9 1286.74
  4969.9 1286.18  4995.5 1281.69  4995.7 1281.19  4999.5 1281.69  5010.4  1282.4
  5016.8 1284.85  5041.6 1287.06    5073 1292.98    5128 1300.47  5135.3  1302.5
  5156.2 1304.34  5187.4 1310.35  5208.2 1313.25    5234 1314.85  5249.8 1318.45
  5301.2 1321.35  5306.5 1322.47  5340.1  1322.1  5345.3 1323.38    5354 1323.18
#Mann= 5 ,-1 , 0
  4445.4     .07       0  4806.2     .12       0  4995.5     .05       0
  4999.5     .12       0    5073     .07       0
Bank Sta=4995.5,4999.5
XS Rating Curve= 0 ,0
Exp/Cntr=0.3,0.1

Type RM Length L Ch R = 1 ,9752    ,761,761,761
BEGIN DESCRIPTION:
Devils Hollow Tributary 5 18.0
END DESCRIPTION:
XS GIS Cut Line= 3
      2182556.12     13901602.21      2182251.21     13901801.21
      2181839.17     13902218.31
#Sta/Elev= 30
  4635.9 1309.64  4652.6 1308.56  4707.1 1299.67  4732.8 1298.11  4776.4 1290.29
  4812.6 1286.42  4869.9 1281.15  4927.2 1278.03  4939.8 1275.94  4978.5 1271.88
  4984.5 1269.63  4991.6 1269.22  4991.9 1268.72  4995.6 1269.22  5014.2 1272.91
  5077.8 1272.08  5170.1 1282.65  5176.8 1284.63    5198 1286.38  5219.2 1290.19
  5339.4 1297.31  5388.9 1303.58  5424.3 1305.95  5431.3 1307.99  5438.4 1308.07
  5445.5 1310.85  5466.7 1312.84  5473.8 1315.23  5480.9 1314.68  5586.3 1322.56
#Mann= 6 ,-1 , 0
  4635.9    .035       0  4707.1     .07       0  4939.8     .12       0
  4991.6     .05       0  4995.6     .12       0  5170.1     .07       0
Bank Sta=4991.6,4995.6
XS Rating Curve= 0 ,0
Exp/Cntr=0.3,0.1

Type RM Length L Ch R = 1 ,8991    ,995,995,995
BEGIN DESCRIPTION:
Devils Hollow Tributary 5 17.0
END DESCRIPTION:
XS GIS Cut Line= 3
      2181752.46     13900983.44        2181775.       13901325.
      2181769.42     13902131.08
#Sta/Elev= 30
  4657.7 1285.32  4689.3 1278.25  4739.4 1270.66  4829.6 1265.14  4909.8 1258.56
  4969.9 1260.32    4980 1256.85    4988 1252.31  4988.2 1251.81    4992 1252.31
    5010 1253.64    5030 1260.33    5070 1264.69    5130 1268.59  5162.8 1269.53
    5190 1270.01    5220 1268.85    5250 1274.33    5340 1278.87    5434 1289.02
    5480 1295.92    5510    1298  5532.4 1301.16    5590 1307.99    5610 1312.63
  5630.7 1315.36    5640 1315.83  5672.5 1321.33  5723.5 1326.31  5806.1 1328.91
#Mann= 8 ,-1 , 0
  4657.7     .12       0    4988     .05       0    4992     .12       0
  5162.8     .07       0    5434    .035       0  5532.4     .07       0
  5630.7    .035       0  5672.5     .07       0
Bank Sta=4988,4992
XS Rating Curve= 0 ,0
Exp/Cntr=0.3,0.1

Type RM Length L Ch R = 1 ,7996    ,675,675,675
BEGIN DESCRIPTION:
Devils Hollow Tributary 5 16.0
END DESCRIPTION:
XS GIS Cut Line= 3
      2181701.39     13900757.82        2181375.       13901025.
      2180960.22     13901803.72
#Sta/Elev= 30
  4578.2 1309.39  4601.6 1307.71  4609.5 1304.62  4651.2 1303.04  4701.6 1297.22
  4743.8 1290.72  4786.8 1277.67  4850.7 1266.65  4871.5 1259.53  4893.8  1248.8
  4908.1 1244.97  4943.3 1242.26  4976.5 1232.33  4976.7 1231.83  4980.5 1232.33
  5035.8  1243.3  5052.1 1248.16  5057.7  1247.4    5074 1251.93  5102.1 1255.07
  5200.2 1262.93  5480.1 1273.42  5533.8 1279.66  5628.2 1288.23  5657.1 1295.36
  5687.5 1297.87  5732.3 1302.66  5805.1 1303.72  5836.5 1309.06  5882.3 1311.15
#Mann= 8 ,-1 , 0
  4578.2     .07       0  4701.6     .12       0  4976.5     .05       0
  4980.5     .12       0  5102.1    .035       0  5533.8     .07       0
  5687.5    .035       0  5805.1     .07       0
Bank Sta=4976.5,4980.5
XS Rating Curve= 0 ,0
Exp/Cntr=0.3,0.1

Type RM Length L Ch R = 1 ,7321    ,603,603,603
BEGIN DESCRIPTION:
Devils Hollow Tributary 5 15.0
END DESCRIPTION:
XS GIS Cut Line= 3
      2181070.05     13900391.19        2180975.       13900675.
      2180684.07     13901631.75
#Sta/Elev= 30
  4700.7 1308.98  4778.5 1304.98  4863.2 1295.33    4884 1286.97  4889.5 1281.12
  4894.8 1281.44  4915.6 1266.75  4921.1 1260.58  4926.4 1260.29  4947.3 1249.29
  4978.9 1230.02  4984.2 1224.64  4995.4 1220.94  4995.6 1220.44  4999.4 1220.94
  5010.5 1223.48  5016.4  1227.7  5049.3 1231.05    5115 1232.95  5177.7 1243.41
    5186  1242.8  5191.2 1239.24  5224.1 1235.31  5390.4 1246.41  5426.5 1248.58
  5497.4 1260.25  5775.3 1272.73    5847 1276.44  5995.9 1289.61    6000 1290.48
#Mann= 6 ,-1 , 0
  4700.7     .12       0  4995.4     .05       0  4999.4     .12       0
  5390.4    .035       0  5775.3     .07       0  5995.9    .035       0
Bank Sta=4995.4,4999.4
XS Rating Curve= 0 ,0
Exp/Cntr=0.3,0.1

Type RM Length L Ch R = 1 ,6718    ,895,895,895
BEGIN DESCRIPTION:
Devils Hollow Tributary 5 14.0
END DESCRIPTION:
XS GIS Cut Line= 3
      2180979.86      13900191.4        2180475.       13900625.
      2180043.24      13901336.2
#Sta/Elev= 30
  4334.5 1326.62  4425.5 1319.96  4468.3 1312.91    4532 1311.91  4546.2  1309.6
  4624.1 1306.98  4695.5 1298.17  4808.1 1271.07  4843.6  1255.9  4907.7 1233.96
  4967.8 1219.15  4986.3 1210.06  4990.9 1210.05  4991.1 1209.55  4994.9 1210.05
  4996.7 1212.66  5002.9 1212.66  5013.6 1220.27  5035.1 1227.41  5093.6 1238.28
  5292.5 1245.31    5378 1253.13  5494.3 1257.51  5561.5 1266.72  5610.6 1270.37
  5654.1 1278.71  5690.2 1286.53  5789.3 1296.02    5816 1299.41    5832 1299.12
#Mann= 6 ,-1 , 0
  4334.5     .12       0  4967.8     .07       0  4990.9     .05       0
  4994.9     .07       0  5654.1    .035       0  5789.3     .07       0
Bank Sta=4990.9,4994.9
XS Rating Curve= 0 ,0
Exp/Cntr=0.3,0.1

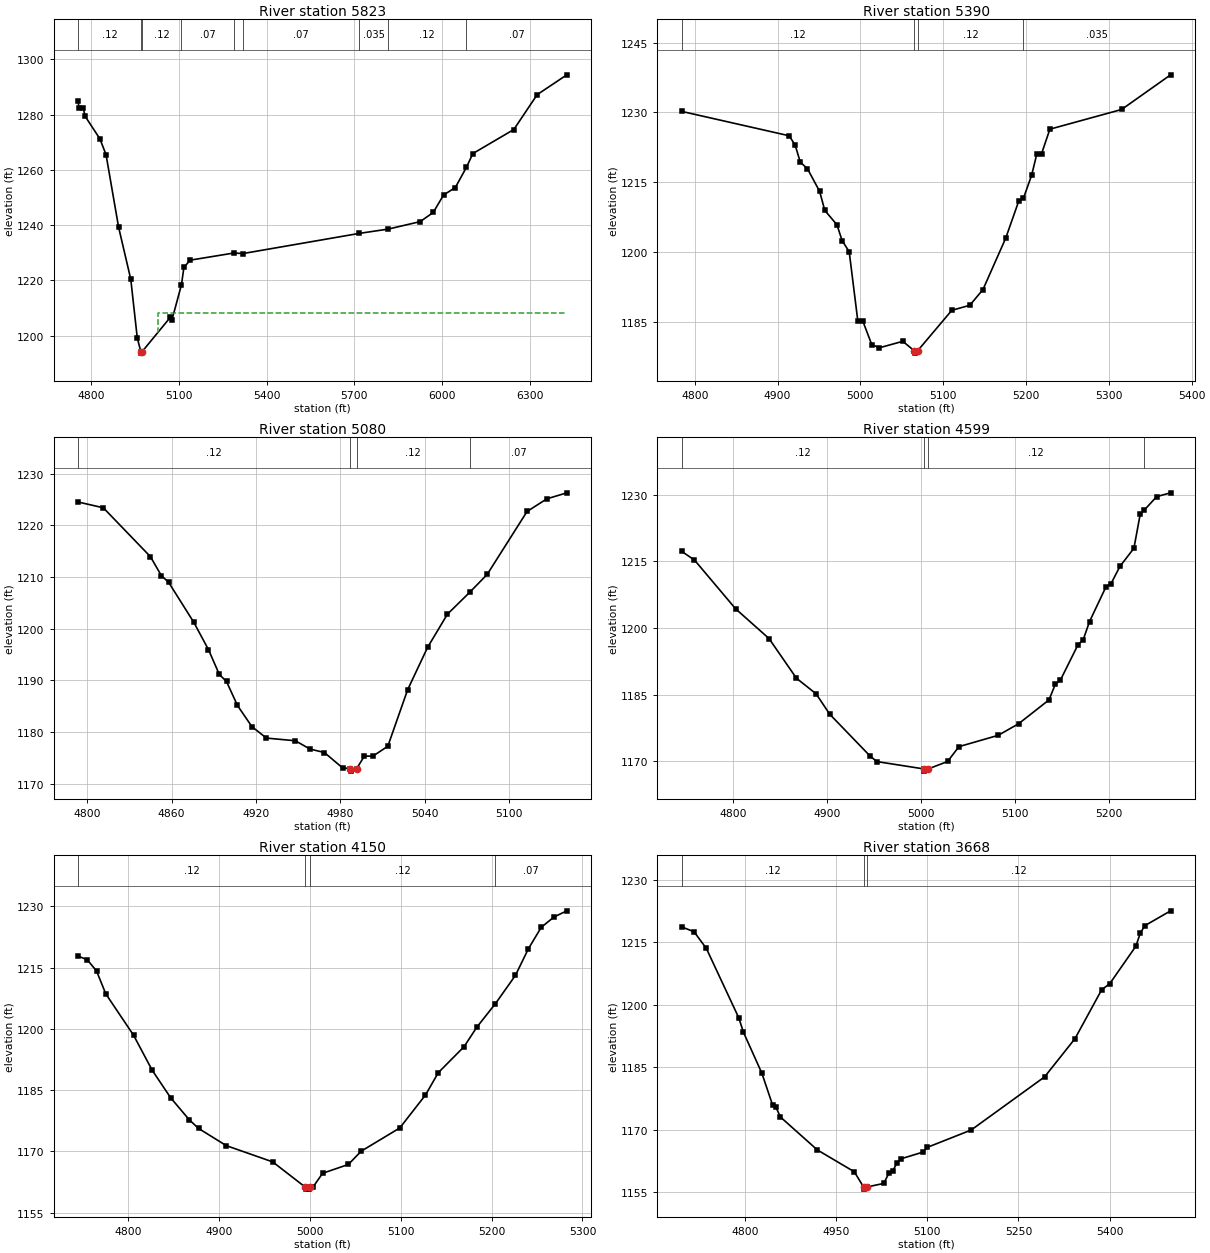
Type RM Length L Ch R = 1 ,5823    ,433,433,433
BEGIN DESCRIPTION:
Devils Hollow Tributary 5 13.0
END DESCRIPTION:
XS GIS Cut Line= 4
      2180131.77     13899836.85        2179975.       13900025.
       2179834.7     13900407.75      2179826.18     13901426.26
#Sta/Elev= 30
  4755.1 1285.07  4758.5 1282.44  4772.8 1282.48  4779.4 1279.42  4830.1 1271.21
    4851  1265.5  4893.9 1239.27  4935.6 1220.37  4957.7 1199.21    4970 1194.18
  4970.3 1193.68    4974 1194.18  5070.9 1206.65  5076.3 1205.71  5108.8 1218.43
  5117.2  1224.7  5138.5 1227.32  5288.7 1229.92  5318.8 1229.71  5716.7 1237.01
  5815.1 1238.56  5924.9 1241.27  5969.5 1244.59  6004.9 1250.92  6044.9 1253.59
    6083 1260.93  6104.9  1265.9  6244.9  1274.6  6324.9 1287.23  6426.2 1294.39
#Mann= 9 ,-1 , 0
  4755.1     .12       0    4970     .05       0    4974     .12       0
  5108.8     .07       0  5288.7     .12       0  5318.8     .07       0
  5716.7    .035       0  5815.1     .12       0    6083     .07       0
#XS Ineff= 2 , 0
       0                 5027.84       0 1208.38
Permanent Ineff=
       F       F
Bank Sta=4970,4974
XS Rating Curve= 0 ,0
Exp/Cntr=0.3,0.1

Type RM Length L Ch R = 1 ,5390    ,310,310,310
BEGIN DESCRIPTION:
Devils Hollow Tributary 5 12.0
END DESCRIPTION:
XS GIS Cut Line= 3
      2179800.75     13899799.95        2179625.       13899925.
      2179298.91     13900109.36
#Sta/Elev= 30
  4784.3 1230.21  4914.1 1224.97  4921.3 1222.92  4927.4 1219.31  4936.1 1217.89
  4950.8 1213.02    4957 1208.94  4971.7 1205.85  4977.9 1202.47  4986.5 1200.05
  4996.9 1185.17  5002.9 1185.17  5013.7 1180.11    5023 1179.42  5051.2 1180.81
  5065.1 1178.77  5065.4 1178.27  5069.1 1178.77  5110.4 1187.47  5132.1 1188.55
    5148 1191.93  5175.4 1202.94  5191.3 1210.99  5196.8 1211.51  5206.8 1216.51
  5212.9 1220.97  5218.7 1221.09  5228.8 1226.39  5315.4 1230.62  5374.6 1238.07
#Mann= 4 ,-1 , 0
  4784.3     .12       0  5065.1     .05       0  5069.1     .12       0
  5196.8    .035       0
Bank Sta=5065.1,5069.1
XS Rating Curve= 0 ,0
Exp/Cntr=0.3,0.1

Type RM Length L Ch R = 1 ,5080    ,481,481,481
BEGIN DESCRIPTION:
Devils Hollow Tributary 5 11.0
END DESCRIPTION:
XS GIS Cut Line= 3
      2179624.98       13899675.        2179425.       13899725.
      2179324.97     13899825.03
#Sta/Elev= 30
  4793.4  1224.5  4811.4 1223.38  4844.9 1213.93  4852.7 1210.25  4857.8 1208.99
  4875.8 1201.21  4886.2 1195.94  4893.9 1191.15    4899 1189.79  4906.8 1185.15
  4917.1 1181.05  4927.4 1178.85    4948 1178.33  4958.3 1176.73  4968.6 1176.06
  4981.5 1173.09  4986.9 1172.96  4987.2 1172.46  4991.6 1172.96    4997 1175.36
  5003.1 1175.36  5013.7 1177.27  5027.8  1188.2    5042  1196.4  5056.1 1202.81
  5072.1 1207.08  5084.4 1210.51  5112.7 1222.66  5126.8 1225.11    5141 1226.27
#Mann= 4 ,-1 , 0
  4793.4     .12       0  4986.9     .05       0  4991.6     .12       0
  5072.1     .07       0
Bank Sta=4986.9,4991.6
XS Rating Curve= 0 ,0
Exp/Cntr=0.3,0.1

Type RM Length L Ch R = 1 ,4599    ,449,449,449
BEGIN DESCRIPTION:
Devils Hollow Tributary 5 10.0
END DESCRIPTION:
XS GIS Cut Line= 3
      2179524.96     13899125.03        2179325.       13899275.
      2179075.01       13899375.
#Sta/Elev= 30
  4745.9 1217.26  4759.4 1215.32  4803.1 1204.34  4838.6 1197.64  4867.7 1188.71
  4888.6  1185.2  4903.1  1180.6  4945.9  1171.2  4953.1 1169.95  5002.9  1168.3
  5003.2  1167.8  5007.7  1168.3  5028.2 1169.97  5040.3 1173.31    5082 1175.86
  5103.6 1178.46  5135.9 1183.83  5142.6 1187.33    5148 1188.27  5166.8 1196.28
  5172.2 1197.35    5179 1201.48  5196.5 1209.32  5201.8    1210  5211.3  1213.9
  5226.1 1217.97  5232.8 1225.63  5237.2 1226.58  5250.3  1229.6  5265.1 1230.45
#Mann= 4 ,-1 , 0
  4745.9     .12       0  5002.9     .05       0  5007.7     .12       0
  5237.2     .07       0
Bank Sta=5002.9,5007.7
XS Rating Curve= 0 ,0
Exp/Cntr=0.3,0.1

Type RM Length L Ch R = 1 ,4150    ,482,482,482
BEGIN DESCRIPTION:
Devils Hollow Tributary 5 9.0
END DESCRIPTION:
XS GIS Cut Line= 3
      2179425.04     13898824.99        2179175.       13898875.
      2178975.03     13899074.97
#Sta/Elev= 30
    4745 1217.84  4755.2 1216.94  4765.4 1214.19  4775.6 1208.58  4806.2 1198.43
  4826.6 1189.89    4847 1183.12  4867.4 1177.75  4877.6 1175.63  4908.2 1171.41
  4959.2 1167.43    4995 1161.26  4995.4 1160.76  4999.5 1160.76  4999.9 1161.26
  5003.5 1161.26  5014.1 1164.64  5042.4  1166.8  5056.6 1170.06    5099 1175.74
  5127.3 1183.82  5141.4 1189.29  5169.7 1195.64  5183.8 1200.43  5204.3 1206.21
  5226.3 1213.13  5240.4 1219.59  5254.6 1224.87  5268.7 1227.42  5282.8 1228.92
#Mann= 4 ,-1 , 0
    4745     .12       0    4995     .05       0  4999.9     .12       0
  5204.3     .07       0
Bank Sta=4995,4999.9
XS Rating Curve= 0 ,0
Exp/Cntr=0.3,0.1

Type RM Length L Ch R = 1 ,3668    ,447,447,447
BEGIN DESCRIPTION:
Devils Hollow Tributary 5 8.0
END DESCRIPTION:
XS GIS Cut Line= 3
      2179374.98       13898375.        2179075.       13898425.
      2178675.01     13898724.99
#Sta/Elev= 30
  4696.2 1218.71  4716.5 1217.53  4736.7 1213.52    4790 1196.86  4797.6 1193.42
    4828 1183.54  4845.7 1175.86  4850.8 1175.49  4858.4 1173.04  4919.2 1165.12
    4980 1159.87  4995.3  1156.2  4995.7  1155.7  5000.3  1156.2  5028.4 1157.07
  5036.8 1159.49    5043 1159.99  5050.3 1162.04  5057.6 1163.02    5093  1164.6
  5100.3 1165.75  5172.2  1169.9    5293 1182.67    5343 1191.86  5386.8 1203.58
  5400.3 1205.09    5443 1214.04  5450.3 1217.13  5457.6 1218.98  5500.3 1222.57
#Mann= 3 ,-1 , 0
  4696.2     .12       0  4995.3     .05       0  5000.3     .12       0
Bank Sta=4995.3,5000.3
XS Rating Curve= 0 ,0
Exp/Cntr=0.3,0.1

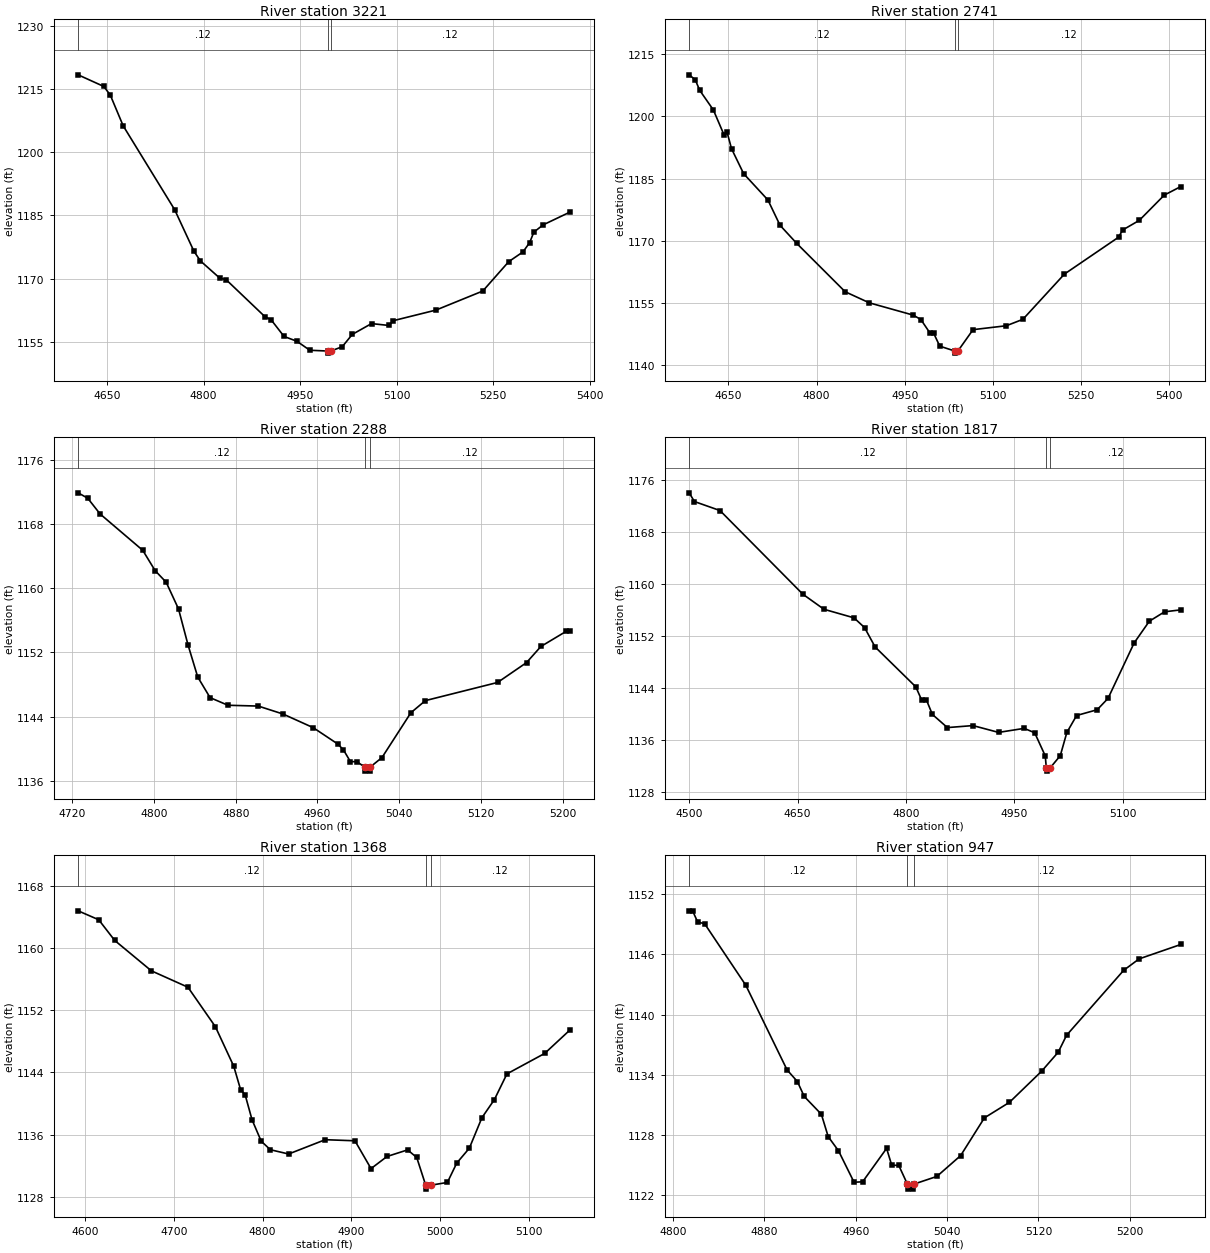
Type RM Length L Ch R = 1 ,3221    ,480,480,480
BEGIN DESCRIPTION:
Devils Hollow Tributary 5 7.0
END DESCRIPTION:
XS GIS Cut Line= 3
        2179325.       13898025.        2178925.       13898025.
      2178575.01       13898125.
#Sta/Elev= 30
    4605 1218.41    4645 1215.64    4655 1213.59    4675 1206.29    4755 1186.36
    4785 1176.47    4795 1174.19    4825 1170.11    4835 1169.72    4895 1160.97
    4905 1160.17    4925 1156.23    4945 1155.09    4965 1152.95  4992.5 1152.77
  4992.9 1152.27  4997.5 1152.77  5015.4 1153.79    5031 1156.72  5060.9 1159.29
  5088.2 1158.84  5094.7 1159.98    5161  1162.5  5233.8 1167.03  5274.1 1174.01
  5296.2 1176.32  5306.6 1178.53  5313.1 1181.02  5327.4 1182.74    5369 1185.77
#Mann= 3 ,-1 , 0
    4605     .12       0  4992.5     .05       0  4997.5     .12       0
Bank Sta=4992.5,4997.5
XS Rating Curve= 0 ,0
Exp/Cntr=0.3,0.1

Type RM Length L Ch R = 1 ,2741    ,453,453,453
BEGIN DESCRIPTION:
Devils Hollow Tributary 5 6.0
END DESCRIPTION:
XS GIS Cut Line= 3
      2179224.96     13897475.01        2178825.       13897575.
      2178525.03     13897874.97
#Sta/Elev= 30
  4583.1 1210.02  4593.4 1208.85  4601.1 1206.28  4624.3 1201.55  4642.3 1195.59
  4647.5 1196.24  4655.2 1192.21  4675.8 1186.19  4717.1 1179.85  4737.7 1173.75
    4766  1169.4  4848.5 1157.73  4889.7 1155.05  4964.4 1152.09  4977.3 1151.03
  4992.8 1147.78  4998.9 1147.78  5009.5 1144.61  5035.2 1143.43  5035.6 1142.93
  5040.3 1143.43  5066.1 1148.59  5122.7 1149.53  5150.9 1151.08  5221.6 1161.99
  5313.6 1170.87  5320.6 1172.61  5348.9 1174.93  5391.4 1181.02  5419.6 1183.09
#Mann= 3 ,-1 , 0
  4583.1     .12       0  5035.2     .05       0  5040.3     .12       0
Bank Sta=5035.2,5040.3
XS Rating Curve= 0 ,0
Exp/Cntr=0.3,0.1

Type RM Length L Ch R = 1 ,2288    ,471,471,471
BEGIN DESCRIPTION:
Devils Hollow Tributary 5 5.0
END DESCRIPTION:
XS GIS Cut Line= 3
      2178924.99       13897075.        2178675.       13897175.
      2178524.99     13897325.01
#Sta/Elev= 30
  4725.7 1171.86  4735.1 1171.19  4747.2 1169.23    4789  1164.7  4801.1 1162.17
  4811.9 1160.73    4824  1157.4  4833.4 1152.88  4842.8 1148.93  4854.9 1146.36
  4872.4 1145.41  4902.1 1145.31  4926.3 1144.32  4955.9 1142.62  4980.1 1140.57
  4985.5 1139.85  4992.3 1138.39  4998.5 1138.39  5006.5 1137.71  5006.9 1137.21
  5011.3 1137.21  5011.6 1137.71  5023.2  1138.9  5051.5 1144.48  5065.7 1145.99
  5136.4 1148.25  5164.7 1150.72  5178.8 1152.73  5203.5 1154.61  5207.1 1154.61
#Mann= 3 ,-1 , 0
  4725.7     .12       0  5006.5     .05       0  5011.6     .12       0
Bank Sta=5006.5,5011.6
XS Rating Curve= 0 ,0
Exp/Cntr=0.3,0.1

Type RM Length L Ch R = 1 ,1817    ,449,449,449
BEGIN DESCRIPTION:
Devils Hollow Tributary 5 4.0
END DESCRIPTION:
XS GIS Cut Line= 3
      2178875.02     13896474.99        2178475.       13896775.
        2178325.       13896875.
#Sta/Elev= 30
    4500 1174.09  4507.3 1172.75  4542.7 1171.36  4657.3 1158.49  4686.5 1156.17
  4728.1 1154.85  4742.7 1153.35  4757.3 1150.37  4813.6 1144.23  4821.9 1142.15
  4828.1 1142.27  4836.5 1139.99  4857.3 1137.96  4892.7 1138.27  4928.1 1137.22
  4963.6 1137.84  4978.1 1137.16  4992.7 1133.61  4994.2 1131.76  4994.6 1131.26
  4999.5 1131.76  5013.5 1133.64  5022.6 1137.21  5036.1 1139.82  5064.6 1140.71
  5079.6 1142.46  5115.7 1150.99  5136.7 1154.33  5157.8 1155.78  5180.3 1156.08
#Mann= 3 ,-1 , 0
    4500     .12       0  4994.2     .05       0  4999.5     .12       0
Bank Sta=4994.2,4999.5
XS Rating Curve= 0 ,0
Exp/Cntr=0.3,0.1

Type RM Length L Ch R = 1 ,1368    ,421,421,421
BEGIN DESCRIPTION:
Devils Hollow Tributary 5 3.0
END DESCRIPTION:
XS GIS Cut Line= 3
      2178725.02       13896275.        2178325.       13896375.
      2178224.96     13896475.04
#Sta/Elev= 30
  4592.3 1164.79  4615.5 1163.64  4633.5 1160.98  4674.8 1157.07    4716 1154.96
  4746.9 1149.88  4767.6 1144.79  4775.3 1141.78  4780.4 1141.12  4788.2  1137.9
  4798.5 1135.15  4808.8 1134.05  4829.4  1133.5  4870.6 1135.34  4904.1  1135.2
  4922.2 1131.62  4940.2 1133.18  4963.4 1134.03  4973.7 1133.05  4983.8 1129.48
  4984.3 1128.98  4989.3 1129.48  5008.2 1129.84  5018.8 1132.34  5032.9 1134.24
  5047.1 1138.17  5061.2 1140.51  5075.3 1143.81  5117.8 1146.44  5146.1 1149.44
#Mann= 3 ,-1 , 0
  4592.3     .12       0  4983.8     .05       0  4989.3     .12       0
Bank Sta=4983.8,4989.3
XS Rating Curve= 0 ,0
Exp/Cntr=0.3,0.1

Type RM Length L Ch R = 1 ,947     ,410,410,410
BEGIN DESCRIPTION:
Devils Hollow Tributary 5 2.0
END DESCRIPTION:
XS GIS Cut Line= 3
      2178275.02     13895924.98        2178125.       13896025.
        2177925.       13896175.
#Sta/Elev= 30
  4814.3 1150.36  4817.3 1150.36  4821.8 1149.23  4827.8 1149.08  4863.9 1142.92
    4900 1134.47    4909 1133.31    4915 1131.82    4930 1130.04    4936  1127.8
    4945 1126.39  4958.6 1123.25  4966.1 1123.29  4987.1 1126.63  4991.6 1124.94
  4997.7 1124.94  5005.3 1123.06  5005.7 1122.56  5010.5 1122.56    5011 1123.06
  5031.1 1123.83  5051.9 1125.91  5072.7 1129.68  5094.6 1131.23  5122.7 1134.33
  5137.3 1136.24  5144.6 1137.93  5194.6 1144.42  5208.1 1145.56  5244.6    1147
#Mann= 3 ,-1 , 0
  4814.3     .12       0  5005.3     .05       0    5011     .12       0
Bank Sta=5005.3,5011
XS Rating Curve= 0 ,0
Exp/Cntr=0.3,0.1