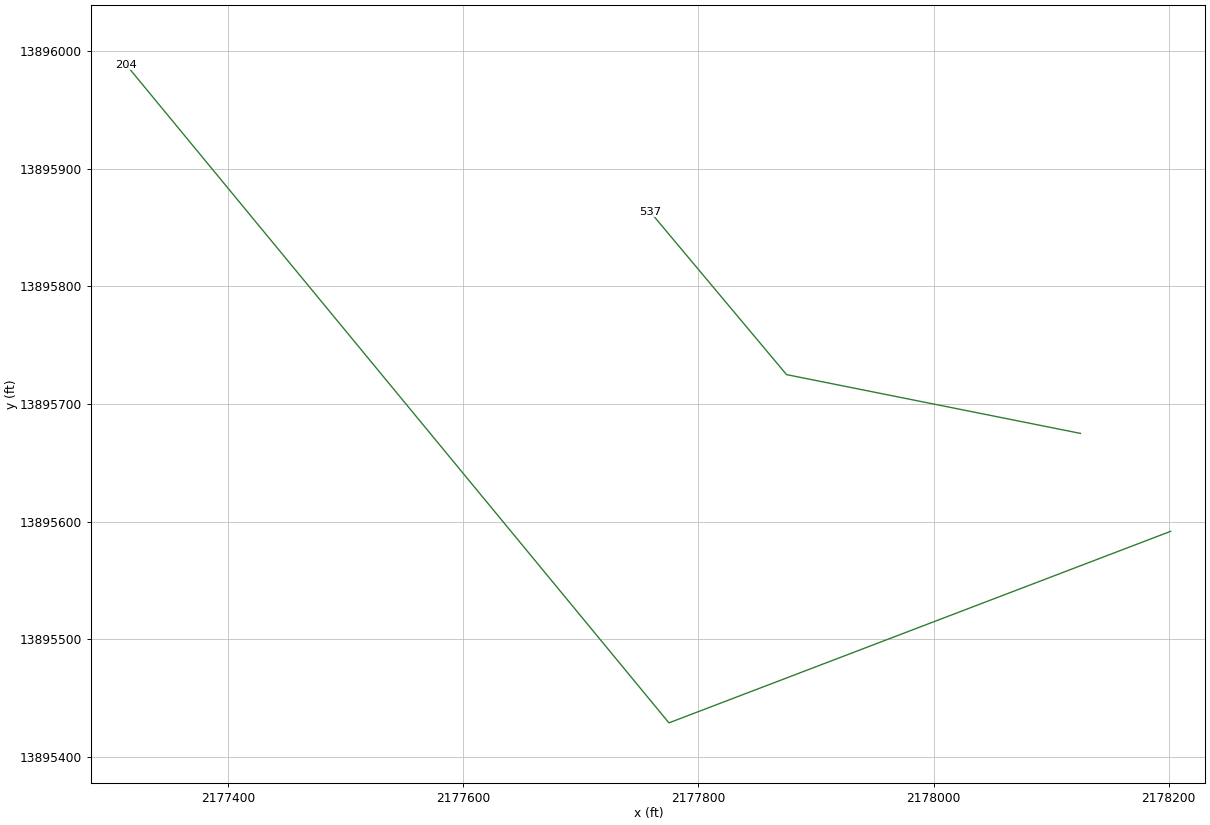
HEC-RAS study Devils Hollow Tributary 5.prj: Devils Hollow Tributary 5 Base Level Engineering

--- Devils Hollow Tributary 5.g01 (geometry) --- (continued)

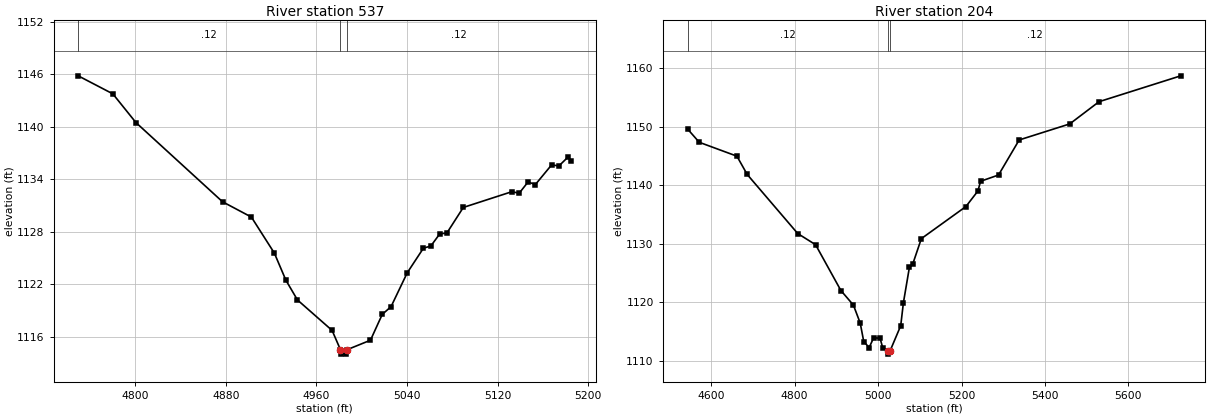
Type RM Length L Ch R = 1 ,537     ,333,333,333
BEGIN DESCRIPTION:
Devils Hollow Tributary 5 1.0
END DESCRIPTION:
XS GIS Cut Line= 3
      2178124.98       13895675.        2177875.       13895725.
       2177758.9     13895863.56
#Sta/Elev= 30
  4749.5  1145.8  4780.1 1143.74  4800.5 1140.46    4877 1131.41  4902.5 1129.66
  4922.8 1125.54    4933 1122.44  4943.2 1120.19  4973.8 1116.71  4981.2  1114.5
  4981.6    1114  4986.4    1114  4986.9  1114.5  5007.7 1115.59  5018.1 1118.54
  5025.9 1119.43  5040.2  1123.3  5054.5 1126.11    5061 1126.35  5068.8 1127.72
  5075.3 1127.86  5089.7 1130.76  5132.6 1132.56  5139.1 1132.39  5146.9 1133.67
  5153.4 1133.38  5167.7 1135.62  5174.2 1135.51    5182 1136.49  5185.2 1136.08
#Mann= 3 ,-1 , 0
  4749.5     .12       0  4981.2     .05       0  4986.9     .12       0
Bank Sta=4981.2,4986.9
XS Rating Curve= 0 ,0
Exp/Cntr=0.3,0.1

Type RM Length L Ch R = 1 ,204     ,0,0,0
BEGIN DESCRIPTION:
Devils Hollow Tributary 5 0.1
END DESCRIPTION:
XS GIS Cut Line= 3
      2178201.73     13895591.73      2177774.97     13895428.81
      2177313.32      13895988.6
#Sta/Elev= 30
  4543.2 1149.63  4571.3 1147.36  4661.5 1144.99  4686.2 1141.86  4807.3 1131.77
  4850.1 1129.86  4910.8 1122.03  4940.8 1119.54  4957.2 1116.45  4965.6  1113.3
  4978.6 1112.29  4989.3 1113.95  5004.7 1113.88  5011.2 1112.21  5022.6 1111.66
  5023.1 1111.16  5028.4 1111.66  5054.2 1116.01  5060.7 1119.96    5075 1125.97
  5082.9 1126.52  5103.7  1130.9  5210.5 1136.38  5239.2 1139.03  5245.7  1140.7
  5288.7 1141.77  5338.2 1147.76  5459.4  1150.5  5529.7  1154.3  5725.6 1158.72
#Mann= 3 ,-1 , 0
  4543.2     .12       0  5022.6     .05       0  5028.4     .12       0
Bank Sta=5022.6,5028.4
XS Rating Curve= 0 ,0
Exp/Cntr=0.3,0.1

Chan Stop Cuts=-1
Use User Specified Reach Order=0
Composite Channel Slope=5