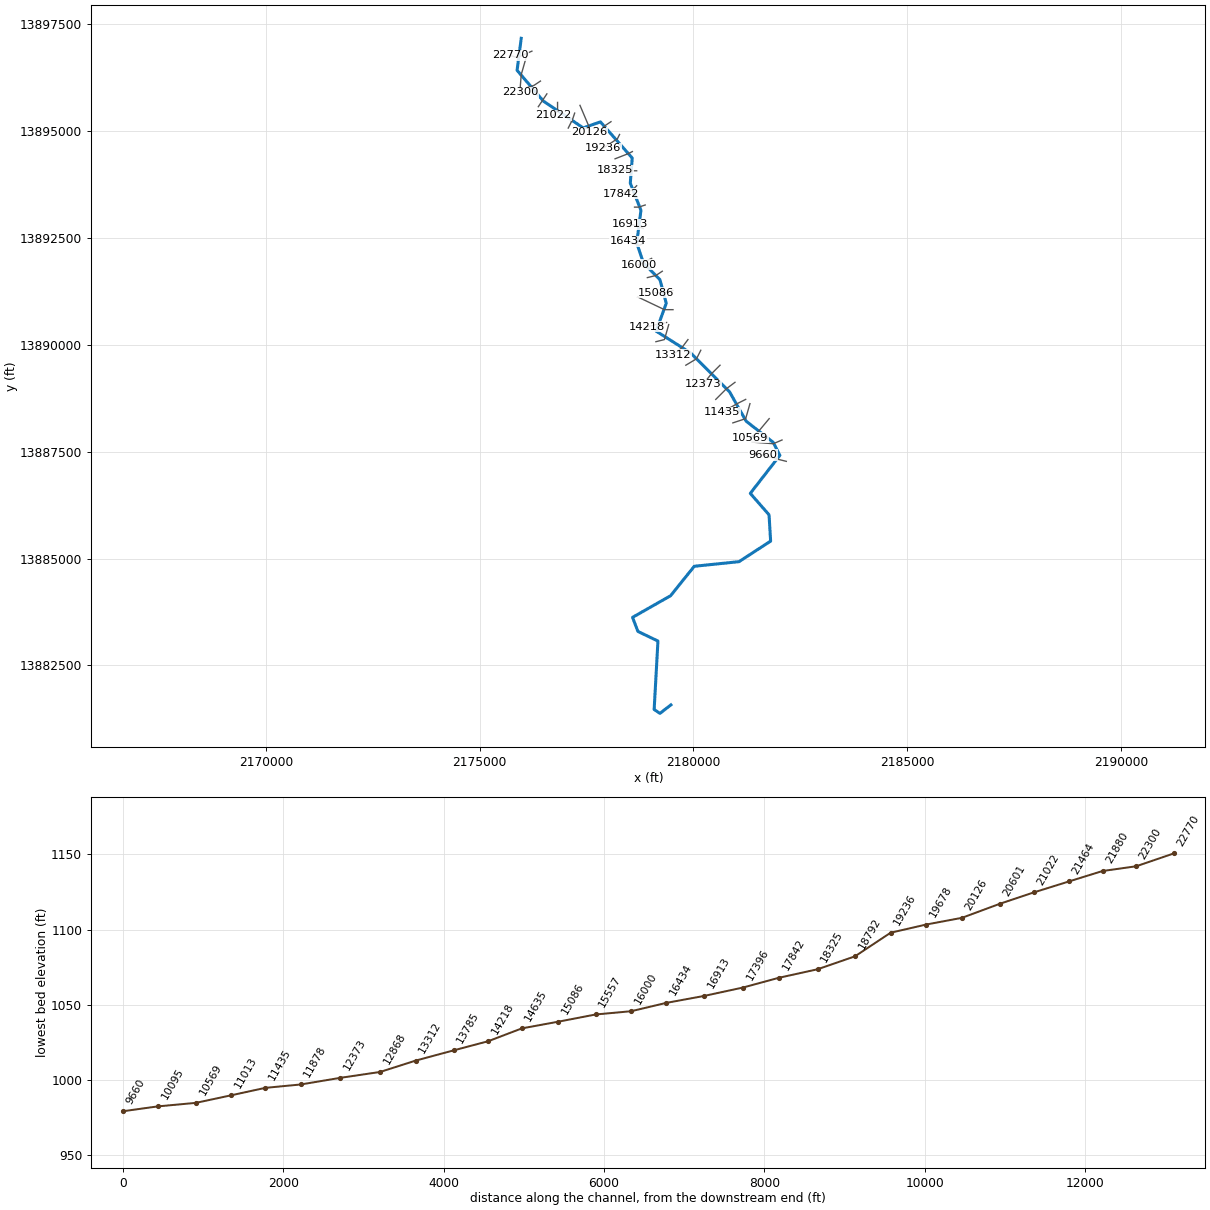
--- Devils Hollow.prj (project) ---

Proj Title=Devils Hollow Base Level Engineering
Current Plan=p01
Default Exp/Contr=0.3,0.1
English Units
Geom File=g01
Flow File=f01
Plan File=p01
BEGIN DESCRIPTION:
Devils Hollow
END DESCRIPTION:

--- Devils Hollow.p01 (plan) ---

Plan Title=Multiple Run
Short Identifier=Multiple
Geom File=g01
Flow File=f01
Subcritical Flow
K Sum by GR= 0
Std Step Tol= 0.01
Critical Tol= 0.01
Num of Std Step Trials= 20
Max Error Tol= 0.3
Flow Tol Ratio= 0.001
Split Flow NTrial= 30
Split Flow Tol= 0.02
Split Flow Ratio= 0.02
Log Output Level= 0
Friction Slope Method= 1
Unsteady Friction Slope Method= 2
Unsteady Bridges Friction Slope Method= 1
Parabolic Critical Depth
Global Vel Dist=  1 , 1 , 1
Global Log Level= 0
CheckData=True
Encroach Param= -1, 0, 0, 0
BEGIN DESCRIPTION:
Multiple Run
END DESCRIPTION:

--- Devils Hollow.f01 (steady flow) ---

Flow Title=Multiple
Number of Profiles=7
Profile Names=10-year,25-year,50-year,1pct_min,100-year,1pct_plu,500-year
River Rch & RM= Devils Hollow,Reach-1,22770
    1918    3371    4803    3311    6605   13180   12371
River Rch & RM= Devils Hollow,Reach-1,19678
    3353    6036    8738    6107   12185   24313   23477
River Rch & RM= Devils Hollow,Reach-1,16000
    3832    6938   10078    7066   14098   28130   27334
River Rch & RM= Devils Hollow,Reach-1,14218
    4065    7350   10668    7469   14903   29735   28816
River Rch & RM= Devils Hollow,Reach-1,5533
    4154    7498   10868    7597   15158   30245   29215
Boundary for River Rch & Prof#=Devils Hollow,Reach-1,1
Up Type=0
Dn Type=3
Dn Slope=0.005
Boundary for River Rch & Prof#=Devils Hollow,Reach-1,2
Up Type=0
Dn Type=3
Dn Slope=0.005
Boundary for River Rch & Prof#=Devils Hollow,Reach-1,3
Up Type=0
Dn Type=3
Dn Slope=0.005
Boundary for River Rch & Prof#=Devils Hollow,Reach-1,4
Up Type=0
Dn Type=3
Dn Slope=0.005
Boundary for River Rch & Prof#=Devils Hollow,Reach-1,5
Up Type=0
Dn Type=3
Dn Slope=0.005
Boundary for River Rch & Prof#=Devils Hollow,Reach-1,6
Up Type=0
Dn Type=3
Dn Slope=0.005
Boundary for River Rch & Prof#=Devils Hollow,Reach-1,7
Up Type=0
Dn Type=3
Dn Slope=0.005

--- Devils Hollow.g01 (geometry) ---

Geom Title=Existing Conditions

River Reach=Devils Hollow,Reach-1
Reach XY= 30
      2175975.00     13897175.00      2175878.61     13896426.48
      2176494.78     13895704.91      2177426.47     13895078.54
      2177827.51     13895219.67      2178571.39     13894373.50
      2178526.22     13893785.51      2178775.23     13893150.07
      2178676.38     13892384.66      2178832.74     13891918.55
      2179219.48     13891527.43      2179367.22     13890974.90
      2179130.45     13890322.55      2179938.21     13889811.38
      2180845.38     13888905.16      2181235.78     13888215.32
      2181869.38     13887719.38      2182024.08     13887415.15
      2181332.53     13886525.01      2181771.54     13886023.75
      2181808.36     13885408.32      2181069.06     13884927.26
      2180022.71     13884819.15      2179469.39     13884130.59
      2178578.46     13883623.50      2178704.46     13883294.46
      2179172.94     13883069.15      2179084.28     13881468.31
      2179219.36     13881376.69      2179475.00     13881575.00

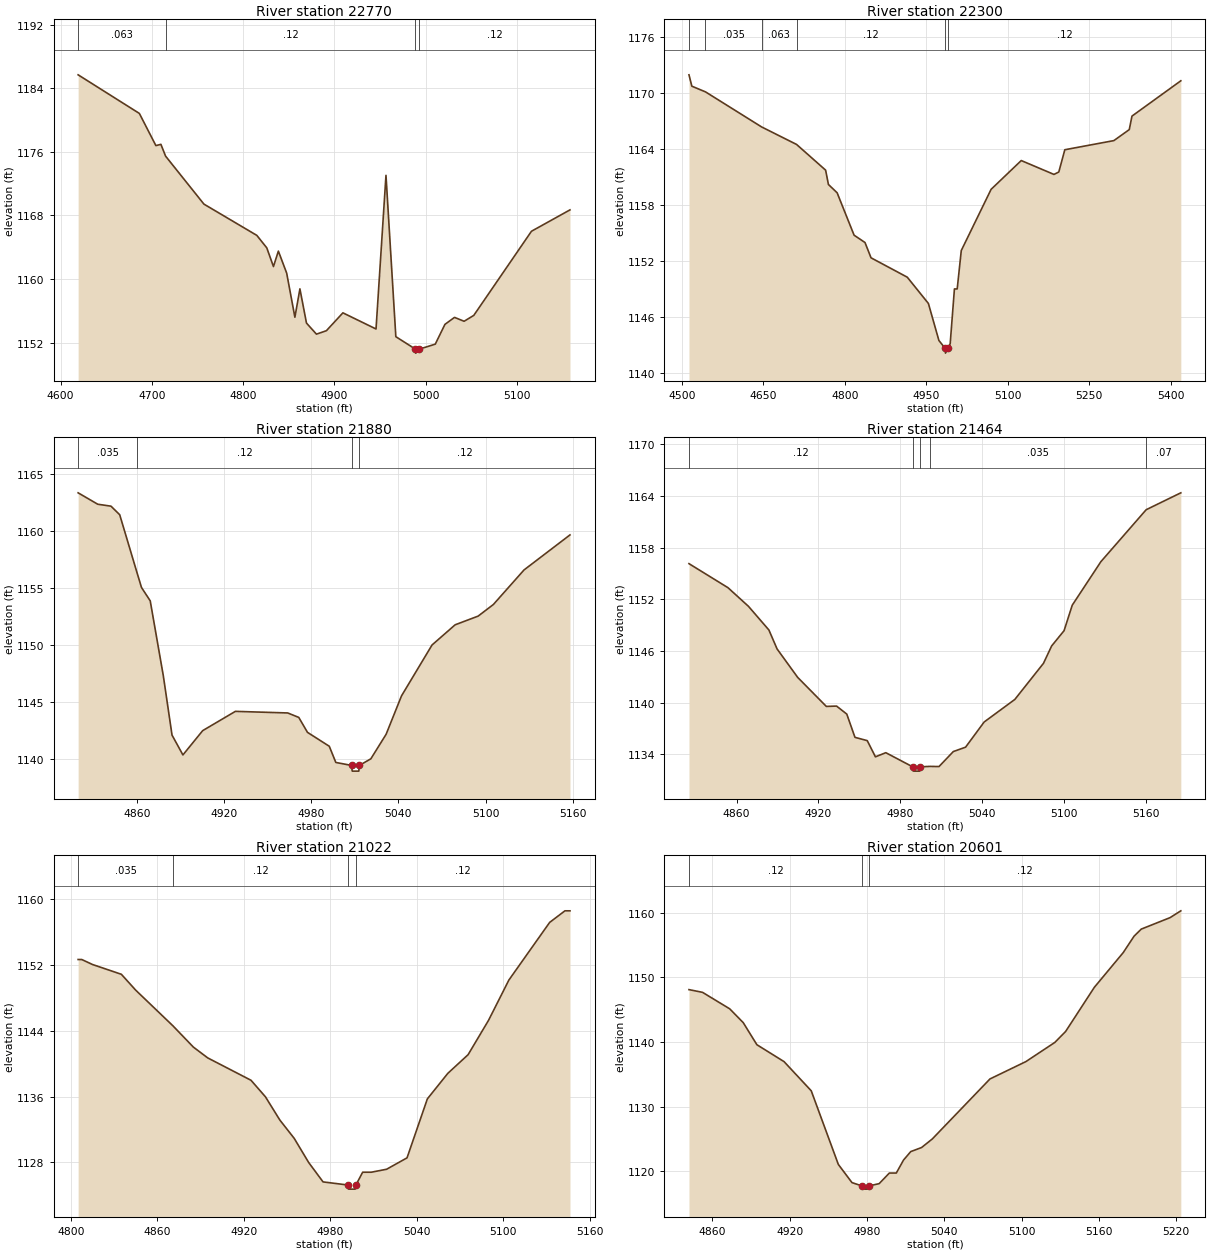
Type RM Length L Ch R = 1,22770,470,470,470
BEGIN DESCRIPTION:
Devils Hollow 49.0
END DESCRIPTION:
XS GIS Cut Line= 3
      2176224.99     13896875.00      2175875.00     13896725.00
      2175724.99     13896775.00
#Sta/Elev= 30
  4619.2 1185.70  4686.3 1180.84  4704.4 1176.79  4709.9 1176.95  4715.0 1175.47
  4757.0 1169.43  4815.0 1165.49  4825.9 1163.92  4833.2 1161.57  4838.6 1163.51
  4847.7 1160.74  4856.7 1155.19  4862.2 1158.76  4869.4 1154.45  4880.3 1153.06
  4891.2 1153.49  4909.3 1155.74  4945.6 1153.71  4956.5 1173.05  4967.3 1152.74
  4988.8 1151.17  4989.1 1150.67  4993.0 1151.17  5010.5 1151.80  5021.1 1154.29
  5031.6 1155.17  5042.1 1154.68  5052.7 1155.42  5115.9 1166.01  5158.1 1168.70
#Mann=4,-1,0
  4619.2   0.063       0  4715.0    0.12       0  4988.8    0.05       0
  4993.0    0.12       0
Bank Sta=4988.8,4993
Exp/Cntr=0.3,0.1

Type RM Length L Ch R = 1,22300,420,420,420
BEGIN DESCRIPTION:
Devils Hollow 48.0
END DESCRIPTION:
XS GIS Cut Line= 3
      2176110.88     13896797.05      2175975.00     13896325.00
      2175942.89     13895912.16
#Sta/Elev= 30
  4513.1 1171.99  4518.4 1170.77  4543.5 1170.16  4646.7 1166.40  4711.1 1164.52
  4764.6 1161.76  4769.8 1160.22  4785.8 1159.33  4817.0 1154.78  4837.1 1153.99
  4848.2 1152.35  4914.9 1150.27  4953.8 1147.45  4973.1 1143.48  4984.8 1142.62
  4985.2 1142.12  4990.2 1142.62  4993.9 1143.14  5001.7 1149.01  5006.8 1149.01
  5014.3 1153.13  5069.2 1159.70  5124.7 1162.79  5184.9 1161.30  5193.8 1161.56
  5204.9 1163.95  5295.2 1164.93  5323.5 1166.11  5328.5 1167.56  5418.4 1171.35
#Mann=6,-1,0
  4513.1    0.12       0  4543.5   0.035       0  4646.7   0.063       0
  4711.1    0.12       0  4984.8    0.05       0  4990.2    0.12       0
Bank Sta=4984.8,4990.2
Exp/Cntr=0.3,0.1

Type RM Length L Ch R = 1,21880,416,416,416
BEGIN DESCRIPTION:
Devils Hollow 47.0
END DESCRIPTION:
XS GIS Cut Line= 3
      2176425.02     13896175.01      2176275.00     13896075.00
      2176125.01     13896025.00
#Sta/Elev= 30
  4819.7 1163.36  4833.2 1162.36  4842.3 1162.19  4848.3 1161.44  4860.5 1156.24
  4863.3 1155.06  4869.3 1153.89  4878.3 1147.33  4884.3 1142.12  4891.8 1140.38
  4905.4 1142.51  4927.9 1144.20  4963.9 1144.06  4971.5 1143.67  4977.5 1142.36
  4992.5 1141.14  4997.0 1139.72  5007.8 1139.46  5008.3 1138.96  5012.8 1138.96
  5013.2 1139.46  5021.1 1140.04  5031.6 1142.19  5042.2 1145.56  5063.2 1150.02
  5079.1 1151.79  5094.9 1152.55  5105.4 1153.57  5126.5 1156.60  5158.1 1159.67
#Mann=4,-1,0
  4819.7   0.035       0  4860.5    0.12       0  5007.8    0.05       0
  5013.2    0.12       0
Bank Sta=5007.8,5013.2
Exp/Cntr=0.3,0.1

Type RM Length L Ch R = 1,21464,442,442,442
BEGIN DESCRIPTION:
Devils Hollow 46.0
END DESCRIPTION:
XS GIS Cut Line= 3
      2176575.02     13895875.03      2176475.00     13895725.00
      2176374.99     13895574.99
#Sta/Elev= 30
  4825.1 1156.15  4853.7 1153.36  4868.7 1151.20  4883.7 1148.45  4889.7 1146.25
  4904.8 1142.95  4925.8 1139.58  4933.3 1139.62  4940.8 1138.69  4946.8 1135.99
  4955.8 1135.61  4961.8 1133.73  4969.4 1134.21  4989.1 1132.57  4989.6 1132.07
  4994.2 1132.07  4994.6 1132.57  5001.8 1132.62  5008.4 1132.60  5018.9 1134.34
  5027.9 1134.85  5041.5 1137.77  5064.0 1140.39  5085.0 1144.58  5091.0 1146.60
  5100.1 1148.37  5106.1 1151.33  5127.1 1156.38  5160.3 1162.41  5185.7 1164.37
#Mann=5,-1,0
  4825.1    0.12       0  4989.1    0.05       0  4994.6    0.12       0
  5001.8   0.035       0  5160.3    0.07       0
Bank Sta=4989.1,4994.6
Exp/Cntr=0.3,0.1

Type RM Length L Ch R = 1,21022,421,421,421
BEGIN DESCRIPTION:
Devils Hollow 45.0
END DESCRIPTION:
XS GIS Cut Line= 3
      2176825.00     13895675.01      2176825.00     13895475.00
      2176725.02     13895375.02
#Sta/Elev= 30
  4805.0 1152.69  4807.5 1152.69  4815.0 1152.08  4835.0 1150.89  4845.0 1148.95
  4870.7 1144.63  4885.0 1142.02  4895.0 1140.70  4925.0 1137.98  4935.0 1135.97
  4945.0 1133.14  4955.0 1130.90  4965.0 1127.97  4975.0 1125.60  4992.3 1125.22
  4992.7 1124.72  4997.3 1124.72  4997.8 1125.22  5002.5 1126.78  5008.5 1126.78
  5019.1 1127.14  5033.3 1128.53  5047.4 1135.71  5061.6 1138.82  5075.7 1141.10
  5089.9 1145.29  5104.0 1150.19  5132.3 1157.21  5142.9 1158.62  5146.4 1158.62
#Mann=4,-1,0
  4805.0   0.035       0  4870.7    0.12       0  4992.3    0.05       0
  4997.8    0.12       0
Bank Sta=4992.3,4997.8
Exp/Cntr=0.3,0.1

Type RM Length L Ch R = 1,20601,475,475,475
BEGIN DESCRIPTION:
Devils Hollow 44.0
END DESCRIPTION:
XS GIS Cut Line= 3
      2177224.99     13895424.98      2177175.00     13895275.00
      2177075.00     13895075.00
#Sta/Elev= 30
  4841.9 1148.10  4852.4 1147.68  4873.5 1145.13  4884.0 1142.99  4894.6 1139.57
  4915.7 1136.95  4936.8 1132.43  4957.8 1121.04  4968.4 1118.22  4976.1 1117.71
  4976.6 1117.21  4981.3 1117.21  4981.7 1117.71  4989.5 1118.06  4997.4 1119.70
  5002.8 1119.70  5008.4 1121.71  5014.0 1123.02  5022.4 1123.65  5030.7 1124.97
  5075.5 1134.27  5103.4 1136.96  5125.8 1139.92  5134.2 1141.62  5156.5 1148.46
  5178.9 1153.83  5187.3 1156.37  5192.9 1157.47  5215.2 1159.24  5223.6 1160.30
#Mann=3,-1,0
  4841.9    0.12       0  4976.1    0.05       0  4981.7    0.12       0
Bank Sta=4976.1,4981.7
Exp/Cntr=0.3,0.1

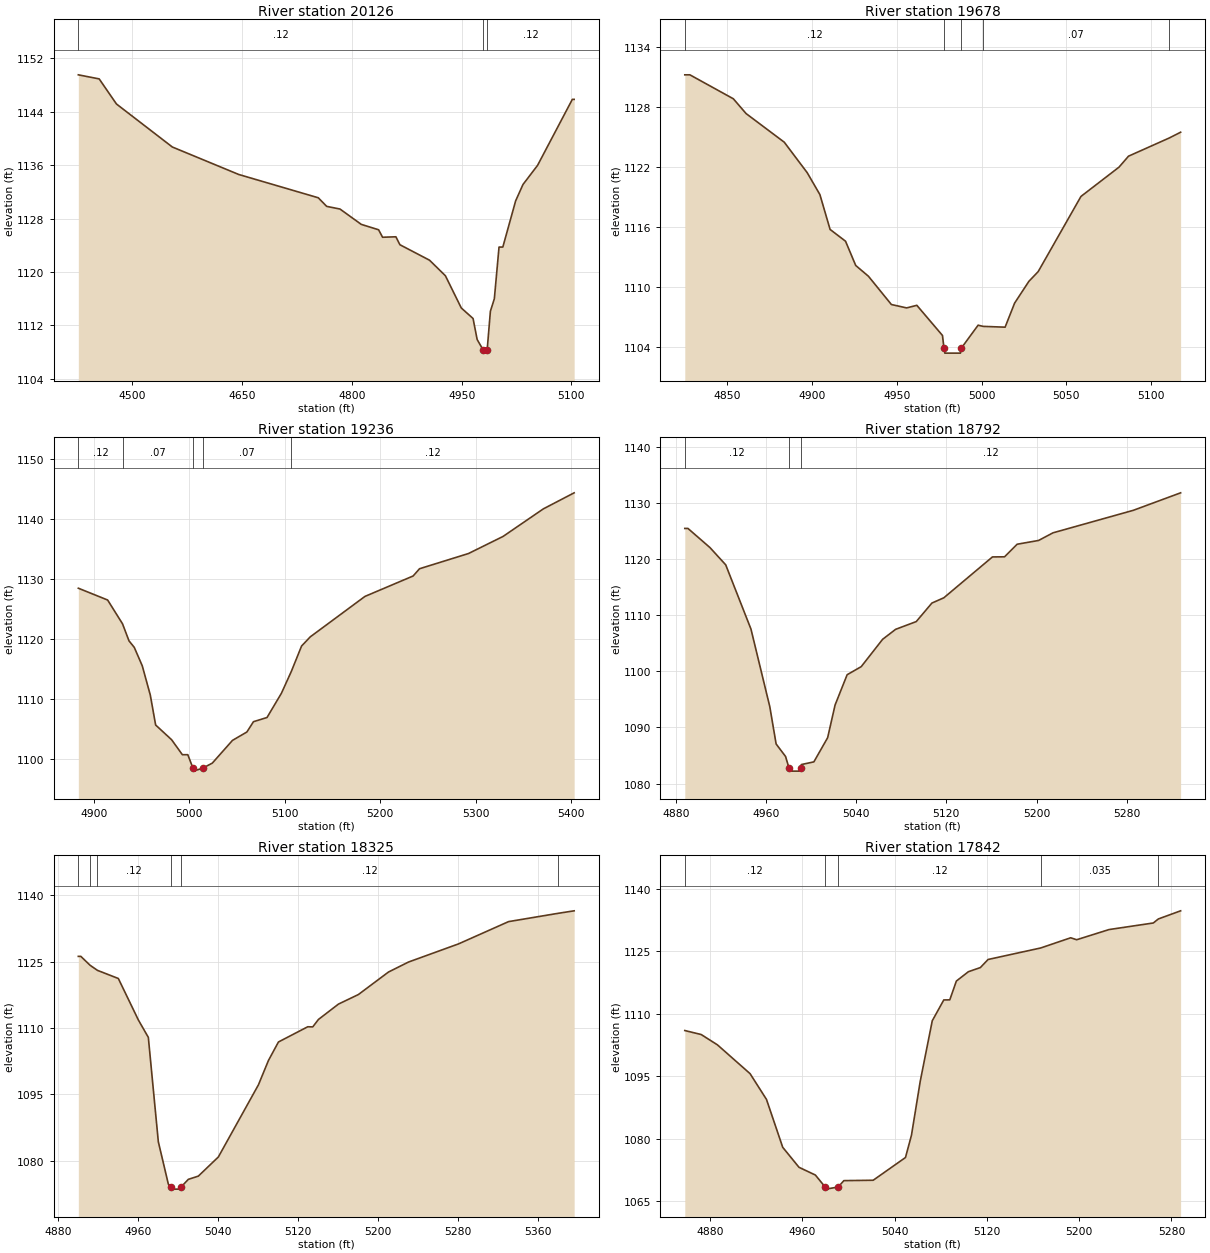
Type RM Length L Ch R = 1,20126,448,448,448
BEGIN DESCRIPTION:
Devils Hollow 43.0
END DESCRIPTION:
XS GIS Cut Line= 3
      2177349.16     13895606.87      2177575.00     13895075.00
      2177575.00     13894975.03
#Sta/Elev= 30
  4426.0 1149.54  4454.5 1148.93  4478.1 1145.17  4554.5 1138.72  4645.3 1134.60
  4754.0 1131.11  4765.5 1129.82  4783.7 1129.42  4812.8 1127.12  4836.5 1126.31
  4841.9 1125.19  4860.1 1125.26  4865.6 1124.07  4906.1 1121.75  4927.8 1119.42
  4949.5 1114.59  4965.6 1113.01  4971.2 1109.86  4979.3 1108.32  4979.8 1107.82
  4984.9 1108.32  4989.3 1114.10  4994.7 1115.97  5001.1 1123.72  5006.3 1123.72
  5023.8 1130.64  5033.8 1133.09  5053.8 1135.97  5101.3 1145.86  5103.8 1145.86
#Mann=3,-1,0
  4426.0    0.12       0  4979.3    0.05       0  4984.9    0.12       0
Bank Sta=4979.3,4984.9
Exp/Cntr=0.3,0.1

Type RM Length L Ch R = 1,19678,442,442,442
BEGIN DESCRIPTION:
Devils Hollow 42.0
END DESCRIPTION:
XS GIS Cut Line= 3
      2178075.01     13895225.01      2177925.00     13895125.00
      2177875.00     13895025.00
#Sta/Elev= 30
  4825.2 1131.22  4828.2 1131.22  4853.8 1128.82  4861.3 1127.34  4883.8 1124.47
  4897.3 1121.42  4904.8 1119.22  4910.8 1115.73  4919.9 1114.55  4925.9 1112.12
  4933.4 1111.04  4946.9 1108.21  4955.9 1107.87  4961.9 1108.13  4977.0 1105.11
  4977.9 1103.84  4978.4 1103.34  4987.6 1103.34  4988.1 1103.84  4998.0 1106.14
  5000.9 1106.02  5013.9 1105.94  5019.5 1108.35  5027.9 1110.53  5033.4 1111.51
  5058.6 1119.04  5081.0 1121.97  5086.6 1123.07  5110.7 1124.90  5117.3 1125.47
#Mann=5,-1,0
  4825.2    0.12       0  4977.9    0.05       0  4988.1    0.12       0
  5000.9    0.07       0  5110.7    0.12       0
Bank Sta=4977.9,4988.1
Exp/Cntr=0.3,0.1

Type RM Length L Ch R = 1,19236,444,444,444
BEGIN DESCRIPTION:
Devils Hollow 41.0
END DESCRIPTION:
XS GIS Cut Line= 3
      2178274.98     13894924.96      2178225.00     13894825.00
      2177883.79     13894601.77
#Sta/Elev= 30
  4883.8 1128.44  4914.5 1126.47  4930.1 1122.50  4936.9 1119.65  4942.4 1118.57
  4950.8 1115.48  4959.2 1110.61  4964.8 1105.61  4981.6 1103.14  4992.8 1100.65
  4998.5 1100.65  5003.9 1098.41  5004.4 1097.91  5014.2 1098.41  5024.2 1099.25
  5045.3 1103.04  5060.4 1104.44  5067.3 1106.16  5081.5 1106.86  5096.6 1110.91
  5107.1 1114.60  5117.7 1118.79  5126.8 1120.32  5184.1 1127.07  5234.6 1130.48
  5241.3 1131.69  5292.6 1134.23  5328.8 1137.08  5371.0 1141.68  5403.3 1144.36
#Mann=5,-1,0
  4883.8    0.12       0  4930.1    0.07       0  5003.9    0.05       0
  5014.2    0.07       0  5107.1    0.12       0
Bank Sta=5003.9,5014.2
Exp/Cntr=0.3,0.1

Type RM Length L Ch R = 1,18792,467,467,467
BEGIN DESCRIPTION:
Devils Hollow 40.0
END DESCRIPTION:
XS GIS Cut Line= 3
      2178574.97     13894524.98      2178475.00     13894475.00
      2178169.62     13894355.22
#Sta/Elev= 30
  4888.0 1125.42  4890.8 1125.42  4910.3 1122.02  4924.3 1118.94  4946.7 1107.50
  4963.4 1093.69  4969.0 1087.06  4977.4 1084.82  4980.5 1082.72  4981.0 1082.22
  4990.5 1082.22  4991.0 1082.72  4991.4 1083.39  5002.5 1083.87  5014.7 1088.17
  5021.3 1093.99  5032.0 1099.38  5044.5 1100.82  5063.5 1105.69  5075.0 1107.46
  5093.3 1108.84  5107.2 1112.14  5117.8 1113.08  5160.9 1120.35  5171.6 1120.37
  5182.8 1122.61  5201.8 1123.28  5214.6 1124.64  5285.9 1128.65  5327.8 1131.76
#Mann=3,-1,0
  4888.0    0.12       0  4980.5    0.05       0  4991.0    0.12       0
Bank Sta=4980.5,4991
Exp/Cntr=0.3,0.1

Type RM Length L Ch R = 1,18325,483,483,483
BEGIN DESCRIPTION:
Devils Hollow 39.0
END DESCRIPTION:
XS GIS Cut Line= 3
      2178675.02     13894075.00      2178575.00     13894075.00
      2178179.50     13894089.80
#Sta/Elev= 30
  4900.3 1126.21  4902.8 1126.21  4912.1 1124.19  4919.4 1123.05  4940.3 1121.21
  4960.3 1111.85  4970.3 1107.90  4980.3 1084.31  4990.3 1074.75  4992.6 1074.11
  4993.1 1073.61  5002.6 1073.61  5003.1 1074.11  5010.3 1075.82  5020.3 1076.55
  5040.3 1080.87  5080.4 1097.18  5090.4 1102.68  5100.4 1106.86  5129.7 1110.30
  5134.7 1110.27  5140.4 1111.95  5160.4 1115.42  5180.4 1117.59  5210.5 1122.68
  5230.5 1124.93  5280.5 1129.03  5330.5 1134.06  5379.6 1135.92  5396.1 1136.50
#Mann=6,-1,0
  4900.3    0.12       0  4912.1   0.094       0  4919.4    0.12       0
  4992.6    0.05       0  5003.1    0.12       0  5379.6    0.07       0
Bank Sta=4992.6,5003.1
Exp/Cntr=0.3,0.1

Type RM Length L Ch R = 1,17842,446,446,446
BEGIN DESCRIPTION:
Devils Hollow 38.0
END DESCRIPTION:
XS GIS Cut Line= 3
      2178675.03     13893725.03      2178575.00     13893625.00
      2178298.62     13893542.84
#Sta/Elev= 30
  4858.2 1106.01  4872.4 1105.05  4886.5 1102.57  4914.8 1095.65  4929.0 1089.48
  4943.1 1077.97  4957.2 1073.18  4971.4 1071.32  4979.9 1068.44  4980.4 1067.94
  4991.1 1068.44  4996.1 1069.98  5021.5 1070.07  5049.5 1075.53  5054.7 1080.90
  5062.3 1093.85  5072.7 1108.34  5082.7 1113.35  5087.9 1113.37  5093.6 1117.88
  5104.0 1120.12  5114.4 1121.12  5121.1 1123.06  5166.8 1125.83  5192.7 1128.27
  5197.9 1127.80  5225.9 1130.24  5264.3 1131.82  5268.7 1132.79  5288.0 1134.74
#Mann=5,-1,0
  4858.2    0.12       0  4979.9    0.05       0  4991.1    0.12       0
  5166.8   0.035       0  5268.7    0.07       0
Bank Sta=4979.9,4991.1
Exp/Cntr=0.3,0.1

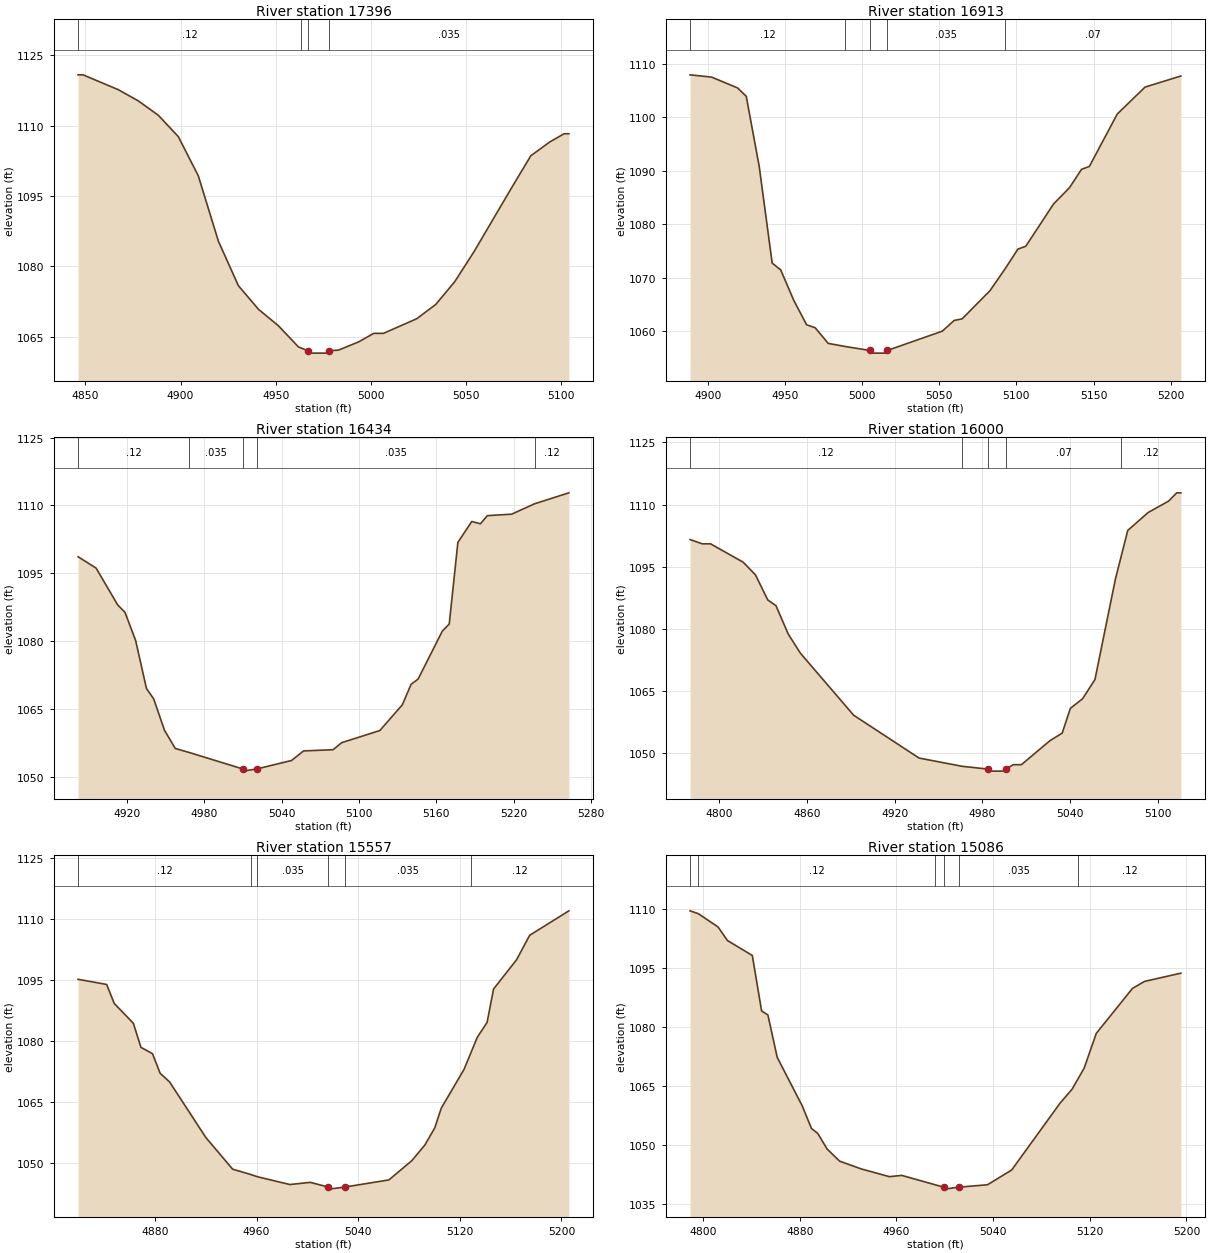
Type RM Length L Ch R = 1,17396,483,483,483
BEGIN DESCRIPTION:
Devils Hollow 37.0
END DESCRIPTION:
XS GIS Cut Line= 3
      2178874.99     13893275.00      2178725.00     13893225.00
      2178625.01     13893225.00
#Sta/Elev= 30
  4846.1 1120.86  4848.7 1120.86  4867.2 1117.70  4877.7 1115.32  4888.3 1112.23
  4898.8 1107.68  4909.3 1099.34  4919.9 1085.35  4930.4 1075.87  4941.0 1070.82
  4951.5 1067.30  4962.0 1062.80  4963.3 1062.59  4967.0 1061.98  4967.5 1061.48
  4977.7 1061.48  4978.2 1061.98  4983.1 1062.13  4993.7 1063.89  5001.6 1065.70
  5006.7 1065.70  5024.2 1068.82  5034.2 1071.87  5044.2 1076.74  5054.2 1083.05
  5074.2 1096.84  5084.2 1103.60  5094.2 1106.55  5101.7 1108.29  5104.2 1108.29
#Mann=4,-1,0
  4846.1    0.12       0  4963.3   0.035       0  4967.0   0.035       0
  4978.2   0.035       0
Bank Sta=4967,4978.2
Exp/Cntr=0.3,0.1

Type RM Length L Ch R = 1,16913,479,479,479
BEGIN DESCRIPTION:
Devils Hollow 36.0
END DESCRIPTION:
XS GIS Cut Line= 3
      2178825.04     13892724.98      2178725.00     13892775.00
      2178525.01     13892825.00
#Sta/Elev= 30
  4888.6 1107.90  4902.6 1107.47  4919.4 1105.45  4925.0 1103.89  4933.4 1090.80
  4941.8 1072.73  4947.3 1071.47  4955.7 1065.83  4964.1 1061.21  4969.7 1060.64
  4978.1 1057.73  4989.3 1057.14  5005.1 1056.41  5005.6 1055.91  5015.9 1055.91
  5016.4 1056.41  5052.0 1060.01  5059.7 1062.01  5064.9 1062.32  5082.9 1067.57
  5092.6 1071.61  5101.0 1075.34  5106.1 1075.87  5124.1 1083.77  5134.5 1086.84
  5142.2 1090.24  5147.3 1090.78  5165.4 1100.58  5183.4 1105.61  5206.6 1107.68
#Mann=5,-1,0
  4888.6    0.12       0  4989.3   0.035       0  5005.1   0.035       0
  5016.4   0.035       0  5092.6    0.07       0
Bank Sta=5005.1,5016.4
Exp/Cntr=0.3,0.1

Type RM Length L Ch R = 1,16434,434,434,434
BEGIN DESCRIPTION:
Devils Hollow 35.0
END DESCRIPTION:
XS GIS Cut Line= 3
      2178825.02     13892375.01      2178725.00     13892325.00
      2178474.99     13892425.00
#Sta/Elev= 30
  4881.9 1098.65  4895.9 1096.13  4912.7 1087.97  4918.3 1086.37  4926.6 1080.10
  4935.0 1069.49  4940.6 1067.20  4949.0 1060.25  4957.4 1056.22  4967.9 1055.36
  5009.6 1051.71  5010.1 1051.21  5020.9 1051.71  5047.6 1053.56  5057.0 1055.68
  5079.9 1055.95  5086.6 1057.51  5116.2 1060.19  5133.7 1065.90  5140.5 1070.43
  5145.9 1071.57  5164.7 1082.18  5170.1 1083.77  5176.8 1101.82  5187.6 1106.45
  5194.3 1105.94  5199.7 1107.74  5218.6 1108.07  5236.4 1110.37  5263.0 1112.79
#Mann=5,-1,0
  4881.9    0.12       0  4967.9   0.035       0  5009.6   0.035       0
  5020.9   0.035       0  5236.4    0.12       0
Bank Sta=5009.6,5020.9
Exp/Cntr=0.3,0.1

Type RM Length L Ch R = 1,16000,443,443,443
BEGIN DESCRIPTION:
Devils Hollow 34.0
END DESCRIPTION:
XS GIS Cut Line= 3
      2179024.98     13892024.99      2178825.00     13891925.00
      2178724.99     13891875.00
#Sta/Elev= 30
  4780.2 1101.55  4788.6 1100.52  4794.2 1100.52  4816.5 1096.09  4824.9 1093.03
  4833.3 1086.99  4838.9 1085.61  4847.3 1078.76  4855.6 1074.15  4892.0 1059.19
  4936.7 1048.86  4966.2 1046.87  4983.5 1046.21  4984.0 1045.71  4995.6 1045.71
  4996.1 1046.21  5001.0 1047.26  5006.6 1047.26  5026.1 1053.04  5034.5 1054.88
  5040.1 1060.85  5048.5 1063.19  5056.9 1067.81  5070.9 1092.08  5074.7 1097.36
  5079.3 1103.75  5093.2 1108.07  5107.2 1110.82  5112.8 1112.82  5115.6 1112.82
#Mann=5,-1,0
  4780.2    0.12       0  4966.2    0.07       0  4983.5   0.035       0
  4996.1    0.07       0  5074.7    0.12       0
Bank Sta=4983.5,4996.1
Exp/Cntr=0.3,0.1

Type RM Length L Ch R = 1,15557,471,471,471
BEGIN DESCRIPTION:
Devils Hollow 33.0
END DESCRIPTION:
XS GIS Cut Line= 3
      2179274.98     13891724.99      2179125.00     13891625.00
      2178925.01     13891575.00
#Sta/Elev= 30
  4819.5 1095.09  4842.0 1093.82  4848.0 1089.14  4863.0 1084.30  4869.0 1078.37
  4878.1 1076.81  4884.1 1072.00  4891.6 1069.85  4920.1 1056.21  4941.2 1048.44
  4955.5 1047.13  4960.5 1046.60  4986.2 1044.67  5002.3 1045.20  5016.6 1044.04
  5017.1 1043.54  5029.3 1044.04  5064.2 1045.80  5082.2 1050.52  5092.5 1054.37
  5100.3 1058.57  5105.4 1063.41  5123.4 1072.99  5128.8 1077.07  5133.8 1080.85
  5141.5 1084.50  5146.6 1092.70  5164.7 1099.88  5175.0 1105.89  5205.9 1111.91
#Mann=6,-1,0
  4819.5    0.12       0  4955.5    0.07       0  4960.5   0.035       0
  5016.6   0.035       0  5029.3   0.035       0  5128.8    0.12       0
Bank Sta=5016.6,5029.3
Exp/Cntr=0.3,0.1

Type RM Length L Ch R = 1,15086,451,451,451
BEGIN DESCRIPTION:
Devils Hollow 32.0
END DESCRIPTION:
XS GIS Cut Line= 3
      2179524.98     13891274.99      2179325.00     13891225.00
      2179125.03     13891225.00
#Sta/Elev= 30
  4789.3 1109.42  4796.1 1108.70  4812.5 1105.31  4820.2 1101.88  4840.8 1098.08
  4848.5 1083.98  4853.7 1082.96  4861.4 1072.19  4882.0 1059.92  4889.8 1054.09
  4894.9 1052.88  4902.7 1048.89  4913.0 1045.82  4931.0 1043.83  4954.2 1041.87
  4964.5 1042.19  4991.9 1039.82  4999.0 1039.20  4999.5 1038.70  5011.8 1039.20
  5035.4 1039.81  5055.4 1043.56  5095.4 1060.53  5105.4 1064.10  5110.5 1066.83
  5115.4 1069.46  5125.4 1078.28  5155.4 1089.72  5165.4 1091.49  5195.4 1093.58
#Mann=6,-1,0
  4789.3    0.07       0  4796.1    0.12       0  4991.9   0.035       0
  4999.0   0.035       0  5011.8   0.035       0  5110.5    0.12       0
Bank Sta=4999,5011.8
Exp/Cntr=0.3,0.1

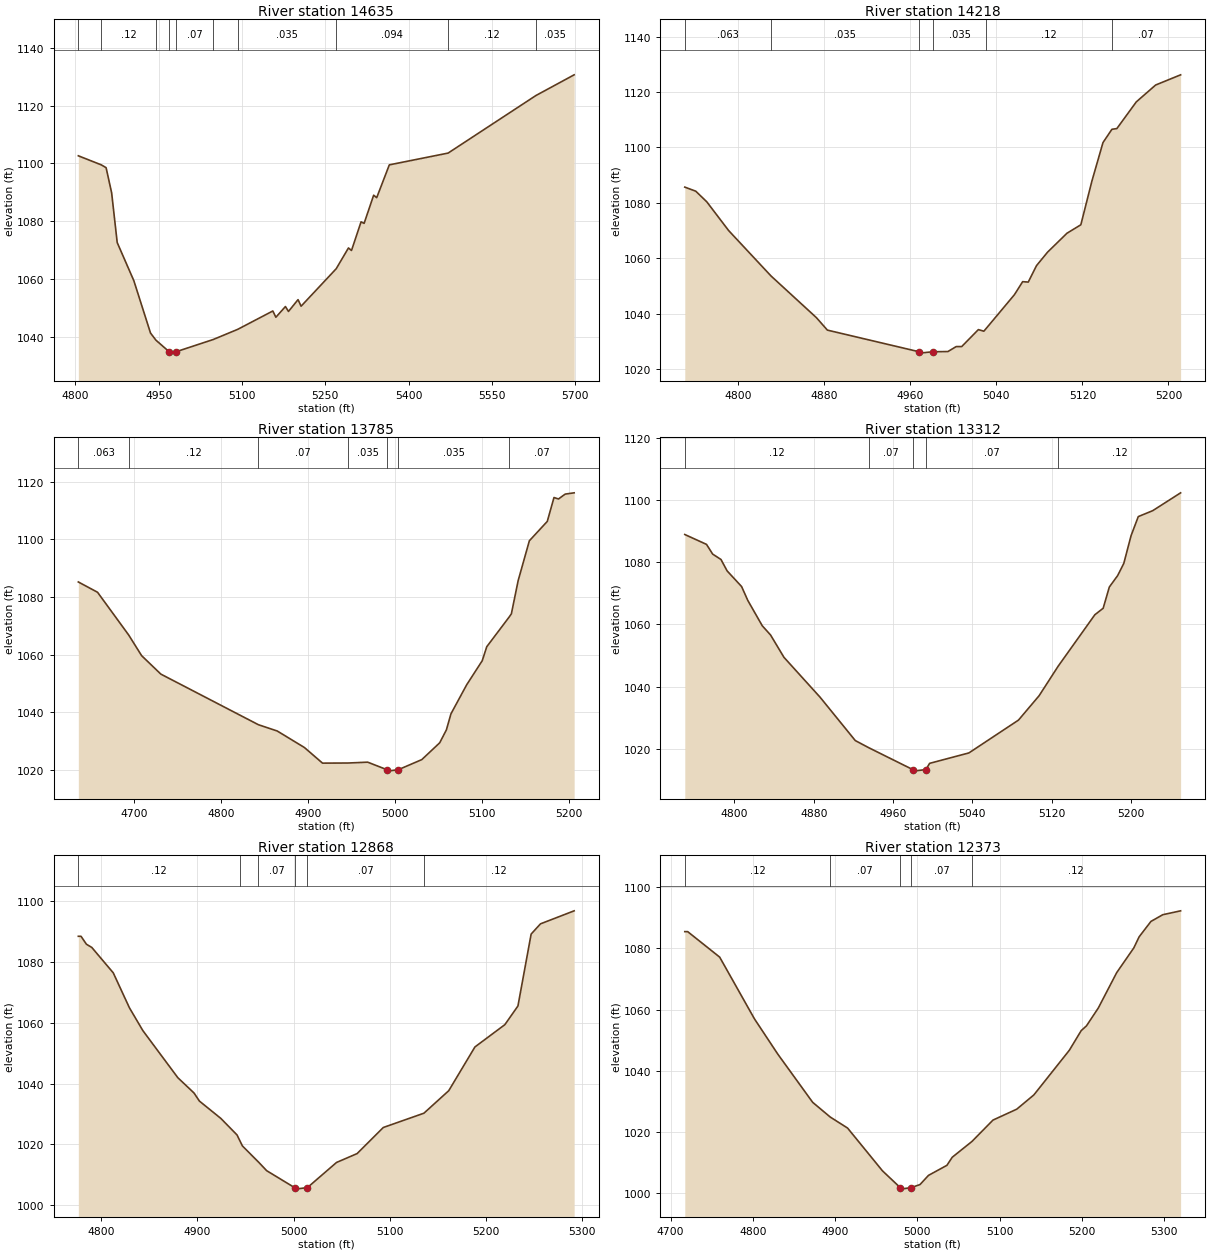
Type RM Length L Ch R = 1,14635,417,417,417
BEGIN DESCRIPTION:
Devils Hollow 31.0
END DESCRIPTION:
XS GIS Cut Line= 3
      2179524.96     13890825.00      2179325.00     13890825.00
      2178699.35     13891123.11
#Sta/Elev= 30
  4805.3 1102.64  4846.4 1099.52  4855.3 1098.53  4865.3 1089.82  4875.3 1072.60
  4905.3 1059.36  4935.3 1041.24  4945.0 1038.78  4968.8 1034.78  4969.3 1034.28
  4981.7 1034.78  5048.3 1039.00  5092.5 1042.53  5155.6 1048.88  5161.1 1046.71
  5178.3 1050.42  5183.8 1048.72  5201.0 1052.81  5206.5 1050.53  5269.8 1063.53
  5291.8 1070.71  5297.3 1069.84  5314.5 1079.75  5320.0 1079.23  5337.2 1088.99
  5342.7 1088.13  5365.4 1099.50  5471.3 1103.58  5629.7 1123.55  5698.3 1130.69
#Mann=10,-1,0
  4805.3    0.07       0  4846.4    0.12       0  4945.0    0.07       0
  4968.8    0.05       0  4981.7    0.07       0  5048.3   0.063       0
  5092.5   0.035       0  5269.8   0.094       0  5471.3    0.12       0
  5629.7   0.035       0
Bank Sta=4968.8,4981.7
Exp/Cntr=0.3,0.1

Type RM Length L Ch R = 1,14218,433,433,433
BEGIN DESCRIPTION:
Devils Hollow 30.0
END DESCRIPTION:
XS GIS Cut Line= 3
      2179374.98     13890525.00      2179125.00     13890475.00
      2178924.98     13890425.00
#Sta/Elev= 30
  4750.2 1085.67  4760.4 1084.20  4770.6 1080.39  4791.0 1069.99  4830.4 1053.61
  4872.6 1038.58  4882.8 1034.08  4968.0 1026.28  4968.5 1025.78  4981.1 1026.28
  4994.9 1026.35  5002.6 1028.14  5007.7 1028.14  5023.2 1034.26  5028.3 1033.69
  5030.5 1034.69  5056.7 1046.84  5064.4 1051.56  5069.6 1051.41  5077.3 1057.35
  5087.6 1062.22  5105.6 1069.03  5118.5 1072.08  5128.8 1087.85  5139.1 1101.74
  5147.4 1106.53  5152.0 1106.79  5170.1 1116.43  5188.1 1122.51  5211.3 1126.18
#Mann=6,-1,0
  4750.2   0.063       0  4830.4   0.035       0  4968.0   0.035       0
  4981.1   0.035       0  5030.5    0.12       0  5147.4    0.07       0
Bank Sta=4968,4981.1
Exp/Cntr=0.3,0.1

Type RM Length L Ch R = 1,13785,473,473,473
BEGIN DESCRIPTION:
Devils Hollow 29.0
END DESCRIPTION:
XS GIS Cut Line= 3
      2179425.01     13890475.04      2179325.00     13890125.00
      2179125.00     13890075.00
#Sta/Elev= 30
  4635.9 1085.20  4658.0 1081.63  4693.8 1066.83  4708.7 1059.67  4730.8 1053.28
  4842.9 1035.76  4864.7 1033.56  4895.9 1027.85  4916.7 1022.44  4946.1 1022.48
  4968.7 1022.77  4990.8 1020.17  4991.3 1019.67  5003.9 1020.17  5030.9 1023.66
  5051.5 1029.49  5059.2 1033.98  5064.4 1039.51  5082.4 1049.53  5100.4 1057.93
  5105.6 1062.77  5131.2 1072.99  5133.9 1074.16  5141.7 1085.67  5154.6 1099.47
  5175.2 1106.18  5182.9 1114.45  5188.1 1113.95  5195.8 1115.64  5206.1 1116.08
#Mann=7,-1,0
  4635.9   0.063       0  4693.8    0.12       0  4842.9    0.07       0
  4946.1   0.035       0  4990.8   0.035       0  5003.9   0.035       0
  5131.2    0.07       0
Bank Sta=4990.8,5003.9
Exp/Cntr=0.3,0.1

Type RM Length L Ch R = 1,13312,444,444,444
BEGIN DESCRIPTION:
Devils Hollow 28.0
END DESCRIPTION:
XS GIS Cut Line= 3
      2179875.00     13890125.00      2179725.00     13889925.00
      2179525.00     13889775.00
#Sta/Elev= 30
  4750.0 1088.92  4771.9 1085.75  4778.1 1082.63  4786.5 1080.89  4792.7 1077.22
  4807.3 1072.19  4813.5 1067.76  4828.1 1059.60  4836.5 1056.62  4850.0 1049.45
  4886.5 1036.60  4921.9 1022.70  4935.6 1020.38  4979.9 1013.37  4980.4 1012.87
  4993.1 1013.37  4996.9 1015.37  5036.5 1018.72  5086.5 1029.27  5107.3 1037.11
  5126.5 1046.59  5163.5 1063.13  5171.9 1065.22  5178.1 1072.04  5186.5 1075.72
  5192.7 1079.64  5200.0 1088.52  5207.3 1094.68  5221.9 1096.59  5250.0 1102.32
#Mann=5,-1,0
  4750.0    0.12       0  4935.6    0.07       0  4979.9    0.05       0
  4993.1    0.07       0  5126.5    0.12       0
Bank Sta=4979.9,4993.1
Exp/Cntr=0.3,0.1

Type RM Length L Ch R = 1,12868,495,495,495
BEGIN DESCRIPTION:
Devils Hollow 27.0
END DESCRIPTION:
XS GIS Cut Line= 3
      2180175.00     13889875.00      2180075.00     13889675.00
      2179824.96     13889524.98
#Sta/Elev= 30
  4776.4 1088.37  4779.2 1088.37  4784.8 1085.76  4790.4 1084.70  4812.7 1076.36
  4829.5 1064.87  4843.5 1057.36  4879.8 1041.91  4896.6 1036.89  4902.2 1034.24
  4924.5 1028.53  4941.3 1023.11  4944.3 1021.18  4946.9 1019.50  4963.5 1014.24
  4972.1 1011.37  5001.1 1005.81  5001.6 1005.31  5014.4 1005.81  5044.7 1014.07
  5066.1 1016.99  5093.3 1025.56  5135.5 1030.25  5161.3 1037.65  5188.5 1052.01
  5219.6 1059.34  5233.2 1065.48  5246.9 1089.09  5256.6 1092.45  5291.6 1096.73
#Mann=6,-1,0
  4776.4    0.12       0  4944.3   0.035       0  4963.5    0.07       0
  5001.1    0.05       0  5014.4    0.07       0  5135.5    0.12       0
Bank Sta=5001.1,5014.4
Exp/Cntr=0.3,0.1

Type RM Length L Ch R = 1,12373,495,495,495
BEGIN DESCRIPTION:
Devils Hollow 26.0
END DESCRIPTION:
XS GIS Cut Line= 3
      2180624.97     13889524.97      2180425.00     13889325.00
      2180224.97     13889074.97
#Sta/Elev= 30
  4717.2 1085.44  4720.7 1085.44  4759.6 1077.13  4802.0 1056.94  4830.3 1045.47
  4872.7 1029.74  4894.1 1024.93  4915.2 1021.33  4957.6 1007.38  4979.2 1001.91
  4979.7 1001.41  4992.5 1001.91  5003.2 1002.89  5013.6 1005.90  5036.0 1009.18
  5042.4 1011.80  5066.4 1016.96  5092.0 1023.94  5120.9 1027.50  5141.7 1032.15
  5184.9 1046.74  5199.3 1053.14  5205.7 1054.69  5220.1 1060.52  5242.5 1072.08
  5263.3 1080.14  5269.7 1083.73  5284.1 1088.77  5298.5 1090.96  5320.2 1092.23
#Mann=5,-1,0
  4717.2    0.12       0  4894.1    0.07       0  4979.2    0.05       0
  4992.5    0.07       0  5066.4    0.12       0
Bank Sta=4979.2,4992.5
Exp/Cntr=0.3,0.1

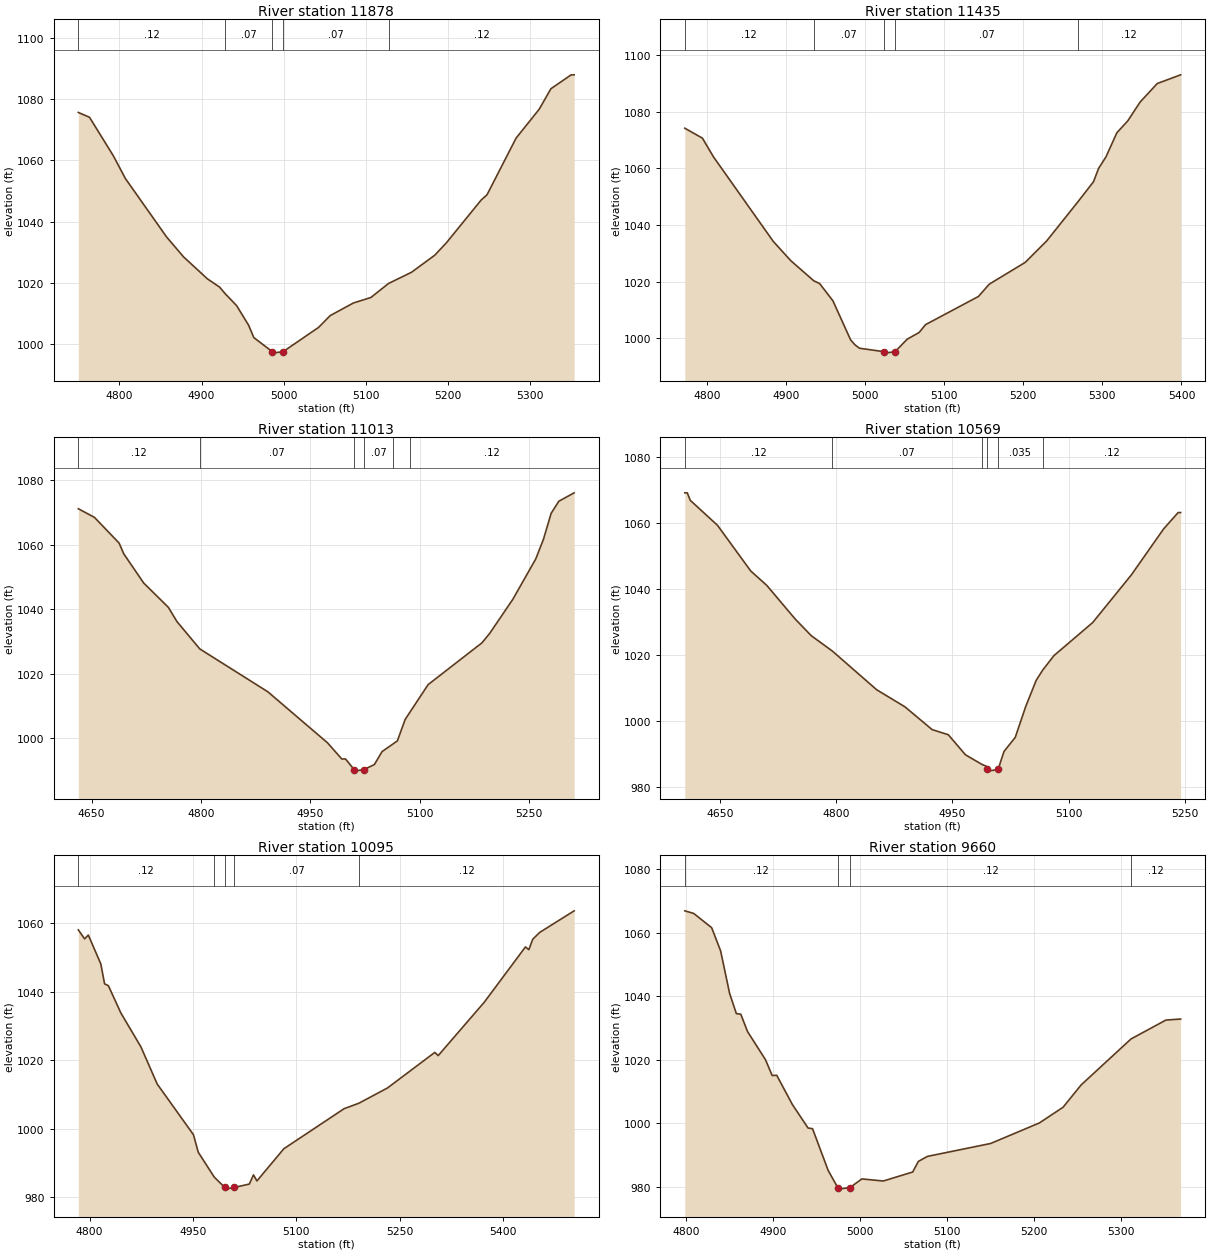
Type RM Length L Ch R = 1,11878,443,443,443
BEGIN DESCRIPTION:
Devils Hollow 25.0
END DESCRIPTION:
XS GIS Cut Line= 3
      2180975.02     13889125.01      2180775.00     13888975.00
      2180524.98     13888724.98
#Sta/Elev= 30
  4750.0 1075.64  4763.6 1074.06  4792.7 1061.44  4807.3 1054.04  4857.3 1035.00
  4878.1 1028.44  4907.3 1021.23  4921.9 1018.58  4928.9 1016.37  4942.7 1012.51
  4957.3 1006.11  4963.6 1002.08  4986.0  997.49  4986.5  996.99  4999.4  997.49
  5042.4 1005.38  5056.6 1009.25  5084.9 1013.38  5106.1 1015.16  5127.7 1019.76
  5155.6 1023.41  5183.9 1028.99  5198.0 1033.02  5240.4 1047.02  5247.5 1048.73
  5282.9 1067.24  5311.1 1076.71  5325.3 1083.39  5350.0 1087.93  5353.6 1087.93
#Mann=5,-1,0
  4750.0    0.12       0  4928.9    0.07       0  4986.0    0.05       0
  4999.4    0.07       0  5127.7    0.12       0
Bank Sta=4986,4999.4
Exp/Cntr=0.3,0.1

Type RM Length L Ch R = 1,11435,422,422,422
BEGIN DESCRIPTION:
Devils Hollow 24.0
END DESCRIPTION:
XS GIS Cut Line= 3
      2181224.98     13888724.99      2181025.00     13888625.00
      2180675.00     13888425.00
#Sta/Elev= 30
  4772.2 1074.21  4794.5 1070.69  4808.5 1064.06  4884.0 1034.22  4906.3 1027.36
  4935.3 1020.28  4942.7 1019.29  4959.5 1013.18  4981.8  999.41  4987.4  997.63
  4993.0  996.46  5024.2  995.23  5024.7  994.73  5037.9  995.23  5053.4  999.68
  5068.5 1002.04  5076.4 1004.78  5143.4 1014.76  5157.0 1019.09  5202.4 1026.78
  5229.7 1034.41  5268.8 1048.10  5288.8 1055.29  5295.2 1059.99  5304.6 1064.11
  5318.3 1072.59  5332.0 1076.76  5347.8 1083.48  5369.4 1090.00  5398.9 1093.07
#Mann=5,-1,0
  4772.2    0.12       0  4935.3    0.07       0  5024.2    0.05       0
  5037.9    0.07       0  5268.8    0.12       0
Bank Sta=5024.2,5037.9
Exp/Cntr=0.3,0.1

Type RM Length L Ch R = 1,11013,444,444,444
BEGIN DESCRIPTION:
Devils Hollow 23.0
END DESCRIPTION:
XS GIS Cut Line= 3
      2181324.99     13888624.95      2181225.00     13888275.00
      2180924.99     13888175.00
#Sta/Elev= 30
  4631.7 1071.12  4653.8 1068.45  4687.6 1060.49  4694.1 1057.12  4721.4 1048.10
  4755.2 1040.57  4766.9 1036.19  4798.3 1027.69  4891.7 1014.40  4973.6  998.58
  4993.1  993.59  4998.3  993.59  5009.9  990.32  5010.4  989.82  5023.6  990.32
  5037.8  991.85  5048.4  995.88  5063.8  998.31  5069.4  999.19  5080.0 1005.81
  5086.5 1008.04  5111.6 1016.63  5185.4 1029.57  5195.9 1032.46  5227.6 1043.00
  5259.2 1055.55  5269.7 1061.60  5280.3 1069.68  5290.8 1073.43  5311.9 1076.05
#Mann=6,-1,0
  4631.7    0.12       0  4798.3    0.07       0  5009.9    0.05       0
  5023.6    0.07       0  5063.8   0.035       0  5086.5    0.12       0
Bank Sta=5009.9,5023.6
Exp/Cntr=0.3,0.1

Type RM Length L Ch R = 1,10569,474,474,474
BEGIN DESCRIPTION:
Devils Hollow 22.0
END DESCRIPTION:
XS GIS Cut Line= 3
      2181774.97     13888274.96      2181525.00     13887975.00
      2181324.97     13887824.98
#Sta/Elev= 30
  4604.3 1069.20  4607.5 1069.20  4611.4 1066.92  4646.6 1059.33  4689.5 1045.48
  4710.3 1041.09  4746.8 1030.93  4767.6 1025.86  4795.0 1021.17  4852.2 1009.44
  4888.7 1004.26  4923.8  997.35  4944.7  995.80  4966.8  989.72  4987.7  986.85
  4994.8  986.12  4995.2  985.25  4995.7  984.75  5009.0  985.25  5016.6  990.70
  5031.2  995.00  5044.8 1004.43  5058.3 1012.33  5066.7 1015.43  5081.2 1019.81
  5131.2 1029.83  5181.2 1044.31  5222.9 1058.27  5241.6 1063.21  5244.8 1063.21
#Mann=6,-1,0
  4604.3    0.12       0  4795.0    0.07       0  4987.7   0.035       0
  4995.2   0.035       0  5009.0   0.035       0  5066.7    0.12       0
Bank Sta=4995.2,5009
Exp/Cntr=0.3,0.1

Type RM Length L Ch R = 1,10095,435,435,435
BEGIN DESCRIPTION:
Devils Hollow 21.0
END DESCRIPTION:
XS GIS Cut Line= 3
      2182075.02     13887775.01      2181870.42     13887687.54
      2181375.04     13887725.00
#Sta/Elev= 30
  4783.7 1058.14  4792.8 1055.51  4798.2 1056.62  4816.3 1048.21  4821.8 1042.38
  4827.3 1041.83  4845.4 1033.87  4874.5 1023.96  4898.1 1013.12  4950.7  998.31
  4957.7  993.18  4980.9  985.92  4996.1  982.91  4996.6  982.41  5010.1  982.91
  5031.7  983.88  5037.8  986.56  5042.8  984.80  5081.8  994.20  5169.3 1005.91
  5190.8 1007.51  5232.3 1011.97  5300.8 1022.34  5305.8 1021.42  5372.7 1037.03
  5432.3 1053.15  5437.3 1052.36  5442.9 1055.39  5452.9 1057.38  5503.0 1063.70
#Mann=5,-1,0
  4783.7    0.12       0  4980.9    0.07       0  4996.1    0.05       0
  5010.1    0.07       0  5190.8    0.12       0
Bank Sta=4996.1,5010.1
Exp/Cntr=0.3,0.1

Type RM Length L Ch R = 1,9660,419,419,419
BEGIN DESCRIPTION:
Devils Hollow 20.0
END DESCRIPTION:
XS GIS Cut Line= 3
      2182175.00     13887275.00      2181975.00     13887325.00
      2181624.96     13887425.01
#Sta/Elev= 30
  4798.5 1066.96  4808.8 1066.13  4829.4 1061.64  4839.7 1054.33  4850.0 1040.95
  4857.8 1034.55  4862.9 1034.35  4870.7 1028.86  4891.3 1020.01  4899.0 1015.02
  4904.2 1015.10  4922.2 1005.89  4940.2  998.47  4945.4  998.25  4963.4  985.07
  4974.4  979.69  4974.9  979.19  4988.5  979.69  5002.1  982.41  5026.8  981.75
  5060.6  984.59  5067.1  987.93  5077.5  989.51  5150.3  993.59  5206.2 1000.05
  5233.5 1005.01  5254.3 1012.05  5311.7 1026.56  5351.8 1032.51  5368.7 1032.83
#Mann=4,-1,0
  4798.5    0.12       0  4974.4    0.05       0  4988.5    0.12       0
  5311.7    0.12       0
Bank Sta=4974.4,4988.5
Exp/Cntr=0.3,0.1