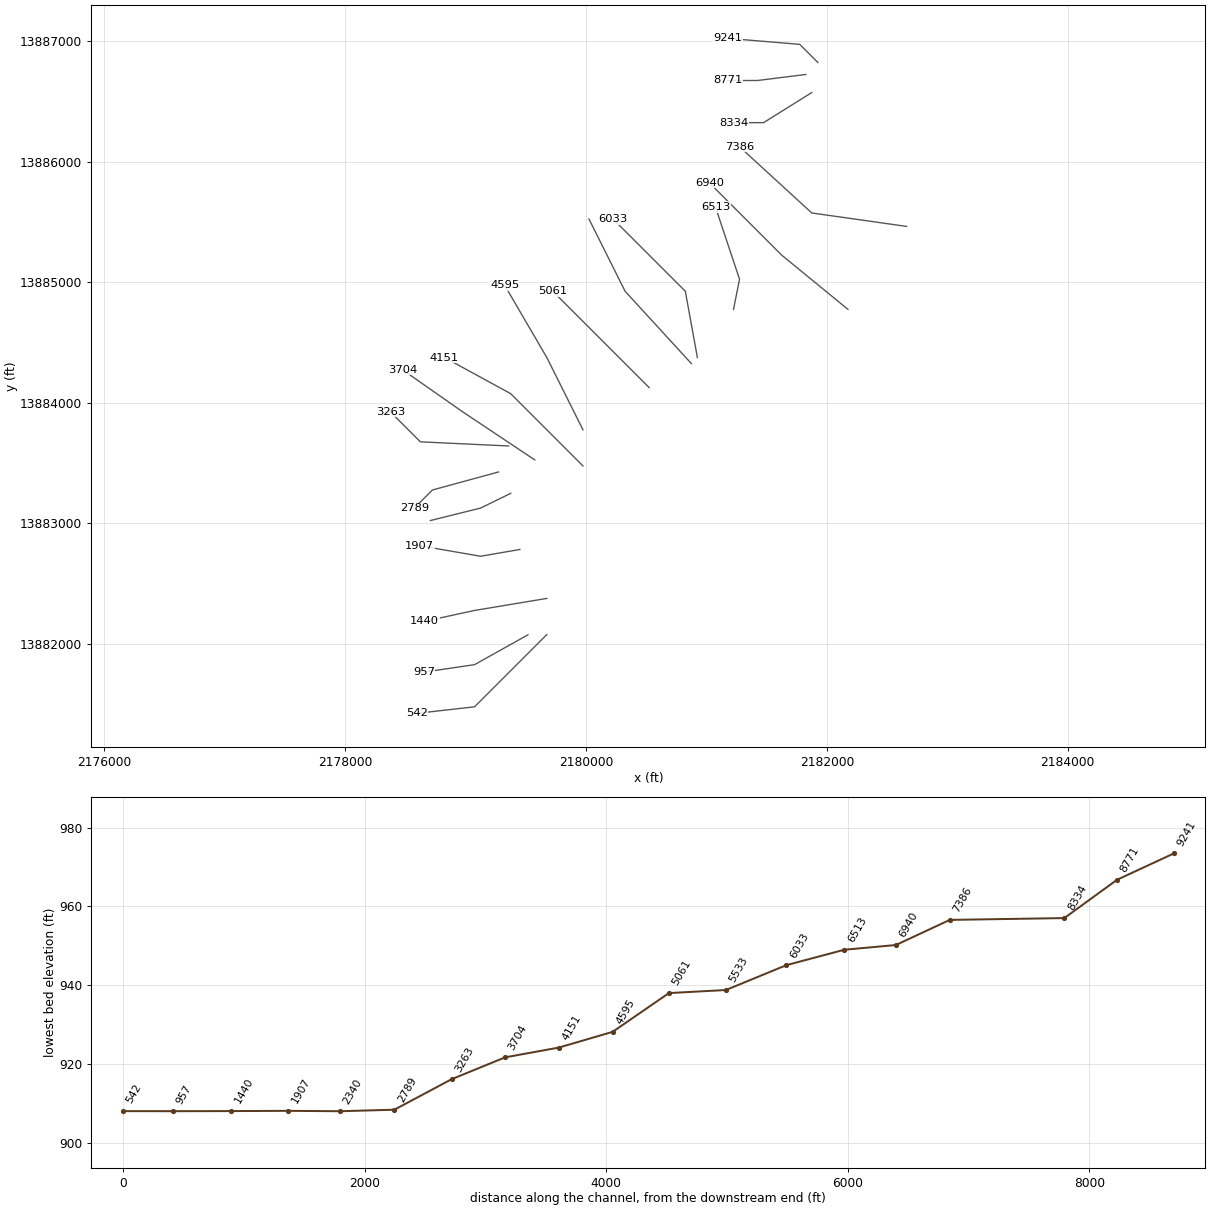
HEC-RAS study Devils Hollow.prj: Devils Hollow Base Level Engineering

--- Devils Hollow.g01 (geometry) --- (continued)

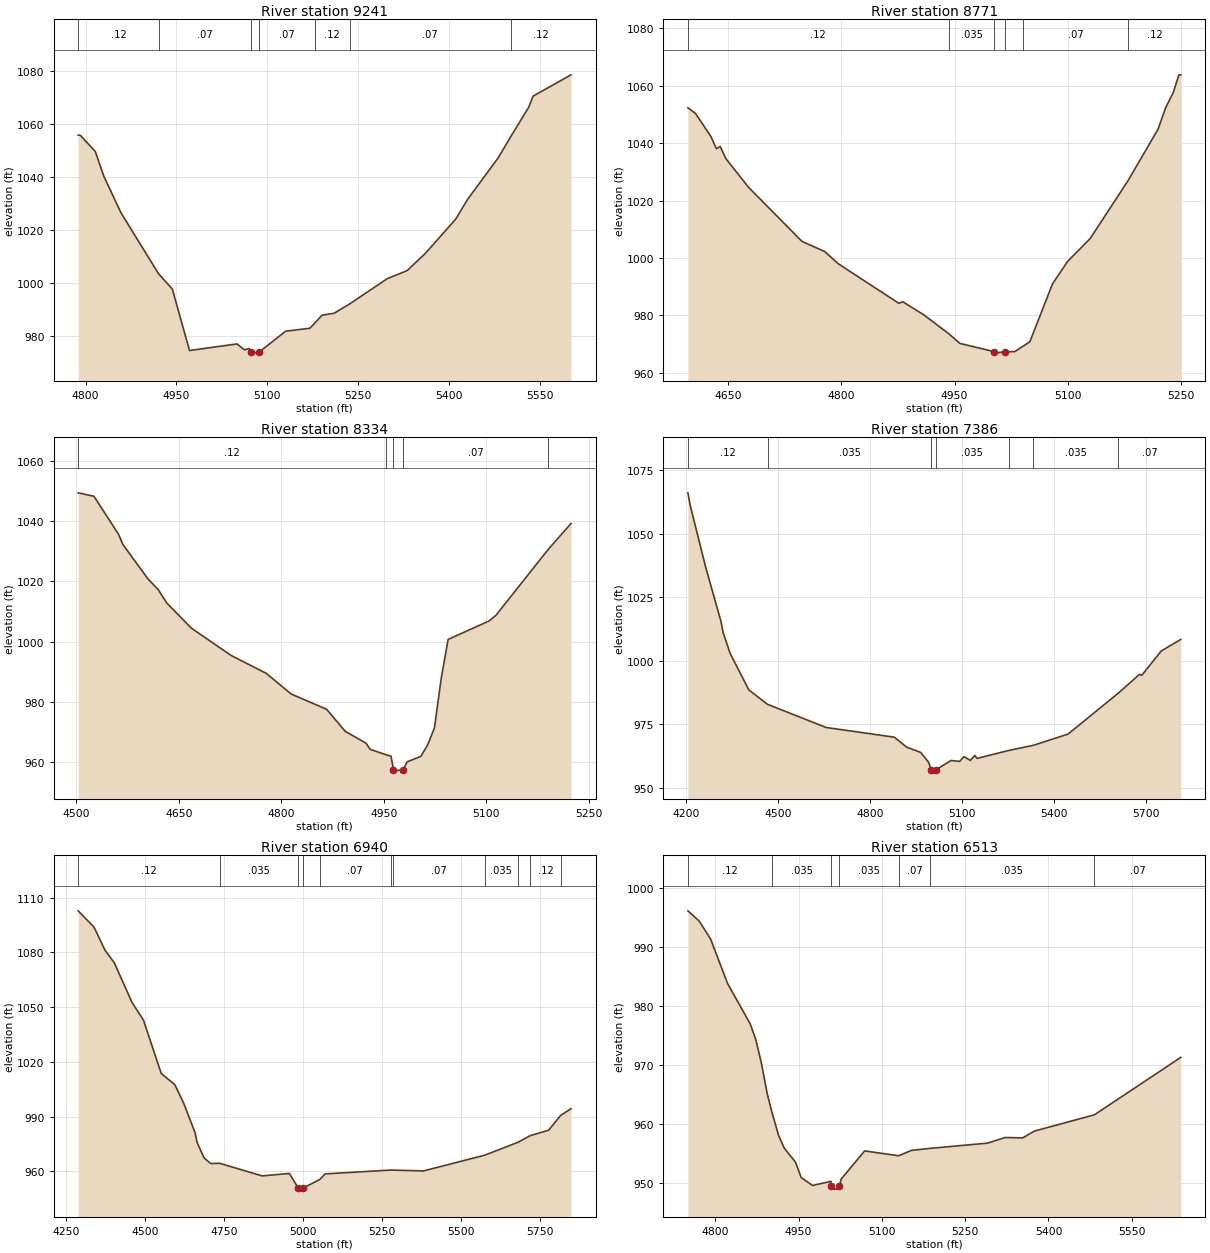
Type RM Length L Ch R = 1,9241,470,470,470
BEGIN DESCRIPTION:
Devils Hollow 19.0
END DESCRIPTION:
XS GIS Cut Line= 3
      2181925.00     13886825.00      2181775.00     13886975.00
      2181175.01     13887025.00
#Sta/Elev= 30
  4787.9 1055.87  4791.4 1055.87  4816.2 1049.71  4830.3 1040.32  4858.6 1026.54
  4920.7 1003.46  4943.5  997.66  4971.8  974.44  5050.2  976.93  5062.8  974.68
  5070.3  975.19  5073.3  973.95  5073.8  973.45  5087.4  973.95  5130.5  981.73
  5170.6  982.86  5178.6  984.76  5190.7  987.78  5210.8  988.54  5236.2  992.04
  5298.6 1001.62  5331.2 1004.64  5361.3 1011.13  5411.5 1024.10  5431.5 1031.71
  5481.7 1047.28  5502.1 1055.19  5531.9 1066.33  5539.4 1070.65  5602.1 1078.71
#Mann=7,-1,0
  4787.9    0.12       0  4920.7    0.07       0  5073.3    0.05       0
  5087.4    0.07       0  5178.6    0.12       0  5236.2    0.07       0
  5502.1    0.12       0
Bank Sta=5073.3,5087.4
Exp/Cntr=0.3,0.1

Type RM Length L Ch R = 1,8771,437,437,437
BEGIN DESCRIPTION:
Devils Hollow 18.0
END DESCRIPTION:
XS GIS Cut Line= 3
      2181824.99     13886725.00      2181425.00     13886675.00
      2181175.00     13886675.00
#Sta/Elev= 30
  4596.6 1052.34  4606.7 1050.36  4626.8 1042.45  4634.4 1038.06  4639.4 1038.85
  4647.0 1034.57  4677.2 1024.54  4747.8 1005.73  4778.0 1002.19  4795.6  997.98
  4876.2  984.13  4881.3  984.69  4909.0  980.16  4942.3  973.54  4956.9  970.17
  5002.6  967.27  5003.1  966.77  5016.8  967.27  5029.7  967.29  5041.1  969.25
  5049.7  970.72  5079.7  990.91  5099.7  998.75  5129.7 1006.74  5179.9 1026.96
  5219.7 1044.93  5229.7 1052.41  5239.7 1057.61  5247.2 1063.84  5249.7 1063.84
#Mann=6,-1,0
  4596.6    0.12       0  4942.3   0.035       0  5002.6   0.035       0
  5016.8   0.035       0  5041.1    0.07       0  5179.9    0.12       0
Bank Sta=5002.6,5016.8
Exp/Cntr=0.3,0.1

Type RM Length L Ch R = 1,8334,948,948,948
BEGIN DESCRIPTION:
Devils Hollow 17.0
END DESCRIPTION:
XS GIS Cut Line= 3
      2181875.00     13886575.00      2181475.00     13886325.00
      2181225.00     13886325.00
#Sta/Elev= 30
  4502.7 1049.43  4525.7 1048.30  4561.7 1035.72  4568.2 1032.28  4604.7 1020.92
  4620.0 1017.26  4632.4 1012.87  4668.4 1004.52  4726.8  995.43  4778.1  989.51
  4814.6  982.65  4866.5  977.58  4893.6  970.29  4924.3  966.31  4930.2  964.29
  4953.9  962.46  4960.8  962.03  4964.4  957.55  4964.9  957.05  4978.6  957.55
  4984.4  960.13  5004.4  961.94  5014.4  965.73  5024.4  971.43  5034.4  987.98
  5044.4 1000.76  5104.4 1006.89  5114.4 1008.76  5190.9 1030.63  5224.4 1039.25
#Mann=5,-1,0
  4502.7    0.12       0  4953.9    0.07       0  4964.4    0.05       0
  4978.6    0.07       0  5190.9    0.12       0
Bank Sta=4964.4,4978.6
Exp/Cntr=0.3,0.1

Type RM Length L Ch R = 1,7386,446,446,446
BEGIN DESCRIPTION:
Devils Hollow 16.0
END DESCRIPTION:
XS GIS Cut Line= 3
      2182662.03     13885463.59      2181875.00     13885575.00
      2181275.02     13886124.99
#Sta/Elev= 30
  4205.6 1066.18  4212.7 1061.43  4263.2 1037.06  4313.7 1015.48  4320.7 1011.07
  4344.0 1002.81  4404.6  988.55  4465.5  982.89  4657.1  973.77  4879.3  969.96
  4919.7  966.03  4965.0  963.98  4990.4  960.22  5000.4  957.09  5000.9  956.59
  5014.7  957.09  5064.3  960.76  5092.7  960.43  5106.8  962.29  5127.8  960.80
  5142.0  962.78  5149.4  961.60  5252.5  964.72  5333.6  966.77  5446.6  971.18
  5610.7  987.32  5679.7  994.69  5687.1  994.34  5750.6 1003.89  5814.4 1008.47
#Mann=7,-1,0
  4205.6    0.12       0  4465.5   0.035       0  5000.4   0.035       0
  5014.7   0.035       0  5252.5    0.07       0  5333.6   0.035       0
  5610.7    0.07       0
Bank Sta=5000.4,5014.7
Exp/Cntr=0.3,0.1

Type RM Length L Ch R = 1,6940,427,427,427
BEGIN DESCRIPTION:
Devils Hollow 15.0
END DESCRIPTION:
XS GIS Cut Line= 3
      2182174.99     13884775.01      2181625.00     13885225.00
      2181024.97     13885825.03
#Sta/Elev= 30
  4289.4 1102.70  4339.6 1093.74  4374.8 1080.96  4403.5 1074.31  4459.5 1052.57
  4496.1 1042.75  4552.1 1013.59  4595.2 1007.46  4623.9  997.01  4659.1  981.20
  4665.5  975.86  4687.8  967.27  4708.6  964.25  4737.2  964.37  4871.5  957.46
  4957.7  958.81  4985.7  950.72  4986.2  950.22  5000.0  950.72  5053.4  955.47
  5070.7  958.56  5278.1  960.67  5285.2  960.64  5381.9  960.20  5575.5  968.81
  5680.6  975.86  5719.2  979.49  5777.8  982.52  5815.7  990.60  5848.6  994.31
#Mann=11,-1,0
  4289.4    0.12       0  4737.2   0.035       0  4985.7   0.035       0
  5000.0   0.035       0  5053.4    0.07       0  5278.1   0.035       0
  5285.2    0.07       0  5575.5   0.035       0  5680.6    0.07       0
  5719.2    0.12       0  5815.7    0.07       0
Bank Sta=4985.7,5000
Exp/Cntr=0.3,0.1

Type RM Length L Ch R = 1,6513,480,480,480
BEGIN DESCRIPTION:
Devils Hollow 14.0
END DESCRIPTION:
XS GIS Cut Line= 3
      2181224.99     13884774.95      2181275.00     13885025.00
      2181074.99     13885625.04
#Sta/Elev= 30
  4750.7  996.21  4771.1  994.46  4791.5  991.44  4822.1  983.89  4862.9  977.04
  4873.1  974.32  4883.3  970.25  4893.5  965.22  4901.3  962.29  4913.9  958.16
  4924.1  955.99  4944.5  953.57  4954.7  950.98  4975.1  949.64  5008.3  950.34
  5009.0  949.52  5009.5  949.02  5023.0  949.02  5023.5  949.52  5026.8  950.74
  5068.9  955.50  5130.2  954.68  5153.3  955.59  5186.6  955.93  5290.3  956.82
  5321.9  957.77  5353.6  957.71  5374.6  958.86  5482.6  961.62  5638.2  971.36
#Mann=7,-1,0
  4750.7    0.12       0  4901.3   0.035       0  5009.0   0.035       0
  5023.5   0.035       0  5130.2    0.07       0  5186.6   0.035       0
  5482.6    0.07       0
Bank Sta=5009,5023.5
Exp/Cntr=0.3,0.1

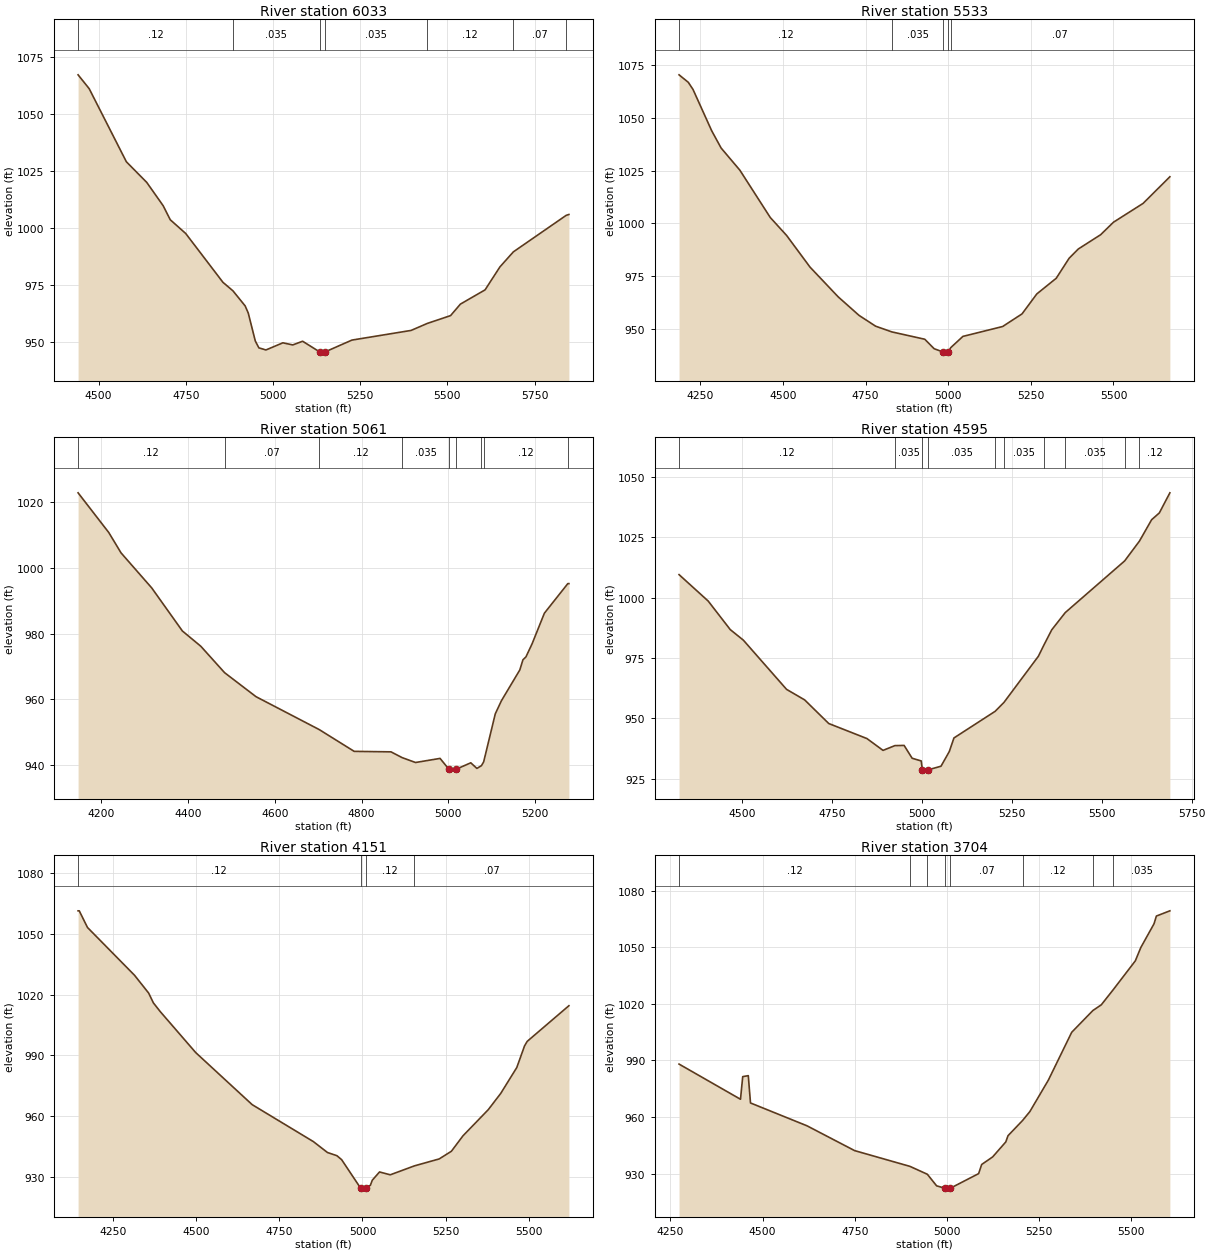
Type RM Length L Ch R = 1,6033,500,500,500
BEGIN DESCRIPTION:
Devils Hollow 13.0
END DESCRIPTION:
XS GIS Cut Line= 3
      2180925.00     13884375.01      2180825.00     13884925.00
      2180225.03     13885524.97
#Sta/Elev= 30
  4441.0 1067.17  4472.8 1061.11  4579.5 1029.03  4637.9 1019.99  4684.9 1009.79
  4705.3 1003.61  4749.7  997.57  4856.4  976.17  4885.1  972.43  4920.0  965.84
  4928.9  962.73  4949.2  950.44  4959.4  947.43  4979.7  946.50  5028.3  949.63
  5056.6  948.71  5084.9  950.32  5134.2  945.61  5134.7  945.11  5148.7  945.61
  5226.3  950.83  5396.0  955.07  5442.5  958.14  5509.1  961.56  5537.4  966.61
  5608.1  972.86  5650.5  982.89  5689.1  989.51  5840.8 1005.55  5848.5 1005.92
#Mann=7,-1,0
  4441.0    0.12       0  4885.1   0.035       0  5134.2   0.035       0
  5148.7   0.035       0  5442.5    0.12       0  5689.1    0.07       0
  5840.8    0.12       0
Bank Sta=5134.2,5148.7
Exp/Cntr=0.3,0.1

Type RM Length L Ch R = 1,5533,472,472,472
BEGIN DESCRIPTION:
Devils Hollow 12.0
END DESCRIPTION:
XS GIS Cut Line= 3
      2180874.97     13884325.04      2180325.00     13884925.00
      2180025.01     13885524.99
#Sta/Elev= 30
  4186.0 1070.16  4214.0 1066.62  4228.2 1063.27  4284.9 1043.71  4313.3 1035.60
  4370.0 1025.15  4461.9 1002.83  4511.5  994.32  4582.1  979.42  4667.2  965.40
  4730.7  956.59  4780.7  951.52  4829.9  948.82  4929.3  945.36  4957.7  940.88
  4985.4  939.31  4985.9  938.81  5000.2  939.31  5007.7  941.37  5044.6  946.70
  5164.8  951.37  5223.5  957.33  5268.2  966.75  5326.9  974.14  5366.0  983.61
  5394.0  987.99  5461.1  994.68  5500.2 1000.61  5589.7 1009.48  5670.7 1022.05
#Mann=5,-1,0
  4186.0    0.12       0  4829.9   0.035       0  4985.4   0.035       0
  5000.2   0.035       0  5007.7    0.07       0
Bank Sta=4985.4,5000.2
Exp/Cntr=0.3,0.1

Type RM Length L Ch R = 1,5061,466,466,466
BEGIN DESCRIPTION:
Devils Hollow 11.0
END DESCRIPTION:
XS GIS Cut Line= 3
      2180524.97     13884125.03      2179925.00     13884725.00
      2179725.02     13884924.98
#Sta/Elev= 30
  4146.7 1022.92  4217.4 1010.82  4245.7 1004.61  4316.4  993.92  4387.1  980.78
  4429.5  976.13  4484.3  968.07  4556.8  960.74  4702.4  950.71  4783.1  944.06
  4867.9  943.91  4893.8  942.14  4924.5  940.66  4981.0  941.91  5001.9  938.53
  5002.4  938.03  5016.8  938.53  5051.8  940.57  5065.9  938.86  5076.3  939.68
  5081.5  940.84  5108.3  955.51  5122.5  959.51  5164.9  968.91  5172.0  971.98
  5179.0  972.88  5193.2  976.89  5221.5  986.21  5275.5  995.23  5278.0  995.23
#Mann=9,-1,0
  4146.7    0.12       0  4484.3    0.07       0  4702.4    0.12       0
  4893.8   0.035       0  5001.9   0.035       0  5016.8   0.035       0
  5076.3    0.07       0  5081.5    0.12       0  5275.5    0.07       0
Bank Sta=5001.9,5016.8
Exp/Cntr=0.3,0.1

Type RM Length L Ch R = 1,4595,444,444,444
BEGIN DESCRIPTION:
Devils Hollow 10.0
END DESCRIPTION:
XS GIS Cut Line= 3
      2179974.99     13883775.02      2179675.00     13884375.00
      2179325.01     13884974.98
#Sta/Elev= 30
  4324.0 1009.49  4405.0  998.57  4466.5  986.74  4502.9  982.38  4623.1  962.02
  4673.4  957.67  4740.4  947.90  4846.7  941.67  4891.4  936.78  4924.4  938.75
  4950.1  938.83  4972.4  933.53  4997.7  932.41  5000.9  928.70  5001.4  928.20
  5015.9  928.70  5052.7  930.23  5075.8  936.31  5088.7  941.92  5203.2  952.93
  5227.8  956.62  5323.5  975.70  5339.7  980.57  5360.7  986.64  5398.4  993.79
  5563.5 1015.15  5604.7 1023.35  5638.6 1032.20  5660.1 1035.02  5689.4 1043.33
#Mann=10,-1,0
  4324.0    0.12       0  4924.4   0.035       0  5000.9   0.035       0
  5015.9   0.035       0  5203.2    0.12       0  5227.8   0.035       0
  5339.7    0.07       0  5398.4   0.035       0  5563.5    0.07       0
  5604.7    0.12       0
Bank Sta=5000.9,5015.9
Exp/Cntr=0.3,0.1

Type RM Length L Ch R = 1,4151,447,447,447
BEGIN DESCRIPTION:
Devils Hollow 9.0
END DESCRIPTION:
XS GIS Cut Line= 3
      2179974.99     13883475.01      2179375.00     13884075.00
      2178825.01     13884375.00
#Sta/Elev= 30
  4145.4 1061.20  4148.9 1061.20  4173.7 1053.00  4315.1 1029.47  4357.5 1020.71
  4371.7 1015.89  4392.9 1011.49  4498.9  991.43  4668.6  965.80  4852.5  947.61
  4894.9  942.24  4923.2  940.68  4937.3  938.74  4994.4  924.72  4994.9  924.22
  5009.6  924.72  5023.8  926.12  5029.5  928.60  5051.3  932.67  5083.6  931.27
  5156.0  935.66  5230.7  939.09  5267.3  942.87  5301.9  950.43  5377.9  963.30
  5415.4  971.30  5463.8  984.08  5487.0  994.69  5495.1  996.95  5620.4 1014.50
#Mann=4,-1,0
  4145.4    0.12       0  4994.4    0.05       0  5009.6    0.12       0
  5156.0    0.07       0
Bank Sta=4994.4,5009.6
Exp/Cntr=0.3,0.1

Type RM Length L Ch R = 1,3704,441,441,441
BEGIN DESCRIPTION:
Devils Hollow 8.0
END DESCRIPTION:
XS GIS Cut Line= 3
      2179574.98     13883525.01      2178975.00     13883925.00
      2178475.01     13884274.99
#Sta/Elev= 30
  4273.3  988.04  4440.0  969.38  4446.0  981.38  4461.1  981.90  4467.1  967.42
  4620.3  955.31  4749.5  942.15  4899.6  933.79  4946.8  929.61  4971.9  923.47
  4994.2  922.22  4994.7  921.72  5009.4  922.22  5085.9  929.94  5094.2  934.79
  5123.9  938.79  5159.6  946.75  5165.7  950.07  5205.2  958.14  5225.0  962.88
  5275.1  979.54  5338.4 1004.90  5395.9 1016.46  5418.6 1019.46  5451.0 1027.48
  5511.0 1042.79  5525.8 1049.83  5561.6 1062.41  5568.1 1066.55  5604.7 1069.32
#Mann=8,-1,0
  4273.3    0.12       0  4899.6   0.035       0  4946.8    0.07       0
  4994.2    0.05       0  5009.4    0.07       0  5205.2    0.12       0
  5395.9    0.07       0  5451.0   0.035       0
Bank Sta=4994.2,5009.4
Exp/Cntr=0.3,0.1

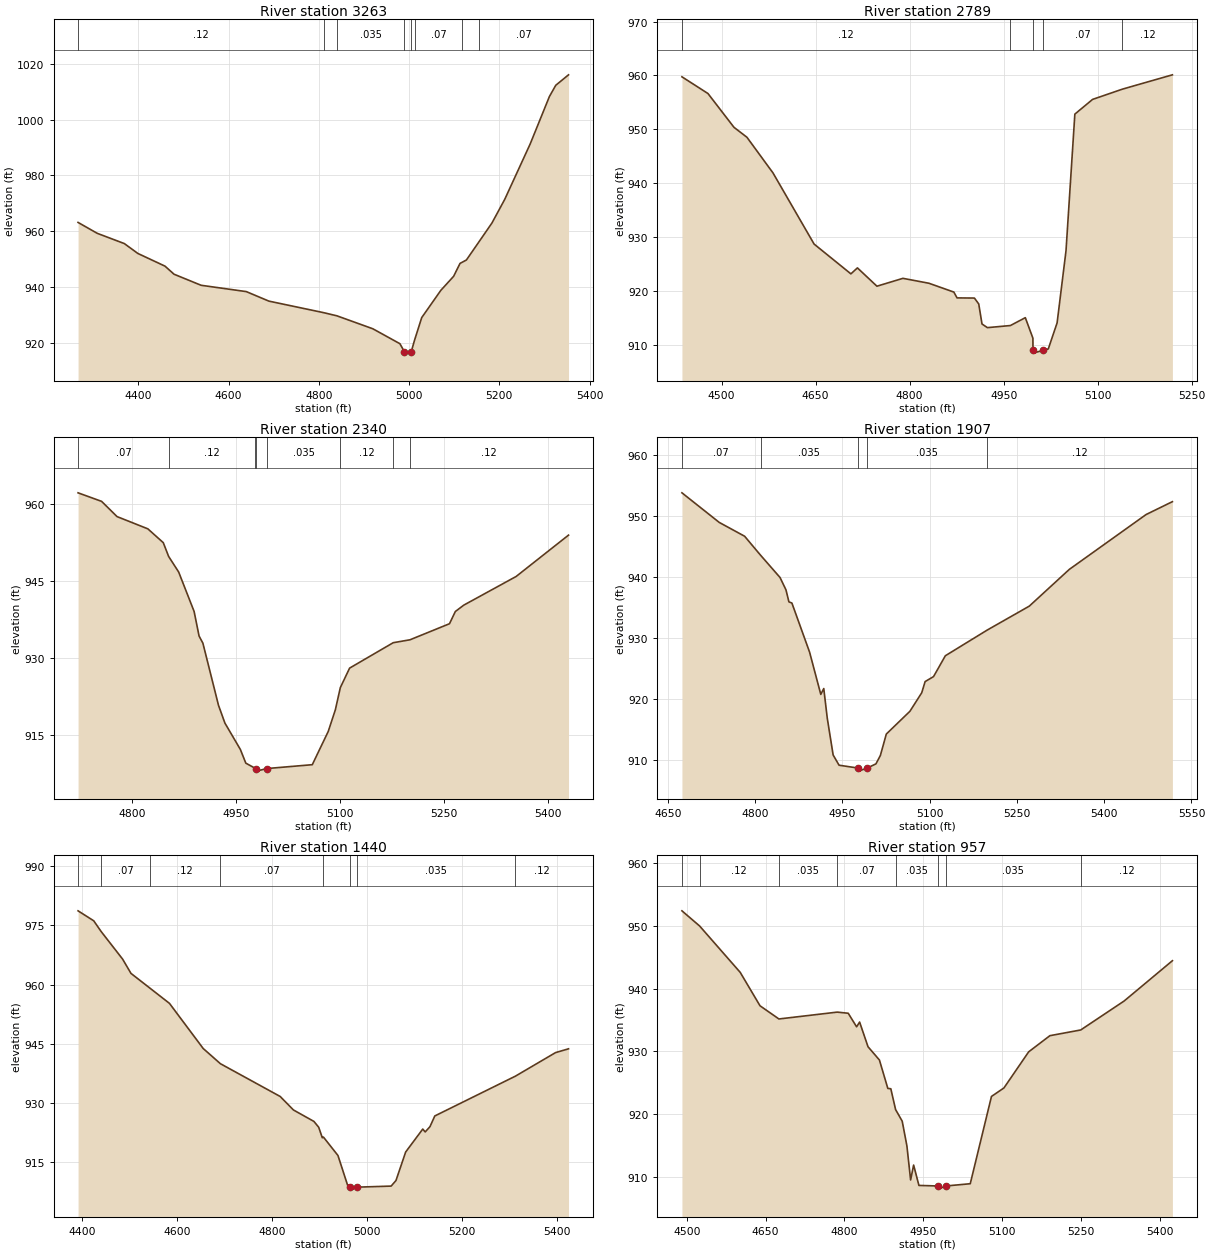
Type RM Length L Ch R = 1,3263,474,474,474
BEGIN DESCRIPTION:
Devils Hollow 7.0
END DESCRIPTION:
XS GIS Cut Line= 3
      2179357.43     13883640.66      2178625.00     13883675.00
      2178374.99     13883925.01
#Sta/Elev= 30
  4266.5  963.13  4309.0  959.22  4369.0  955.54  4399.1  951.98  4459.1  947.44
  4479.2  944.53  4539.2  940.56  4639.3  938.29  4689.4  934.87  4810.7  930.73
  4840.4  929.58  4919.7  924.94  4979.7  919.58  4989.6  916.70  4990.1  916.20
  5004.8  916.70  5012.2  920.90  5028.0  928.96  5070.4  938.75  5098.7  943.79
  5112.9  948.42  5117.9  948.85  5127.0  949.64  5155.9  956.41  5183.6  962.92
  5211.9  971.40  5268.4  991.33  5310.9 1008.32  5325.0 1012.37  5353.3 1016.13
#Mann=8,-1,0
  4266.5    0.12       0  4810.7    0.07       0  4840.4   0.035       0
  4989.6   0.035       0  5004.8   0.035       0  5012.2    0.07       0
  5117.9    0.12       0  5155.9    0.07       0
Bank Sta=4989.6,5004.8
Exp/Cntr=0.3,0.1

Type RM Length L Ch R = 1,2789,449,449,449
BEGIN DESCRIPTION:
Devils Hollow 6.0
END DESCRIPTION:
XS GIS Cut Line= 3
      2179275.04     13883425.01      2178725.00     13883275.00
      2178574.98     13883124.98
#Sta/Elev= 30
  4436.9  959.74  4478.4  956.64  4519.9  950.37  4540.6  948.52  4582.1  941.91
  4647.7  928.70  4706.4  923.17  4716.8  924.28  4747.9  920.88  4789.4  922.34
  4830.8  921.43  4870.6  919.79  4875.7  918.71  4903.4  918.68  4910.3  917.58
  4915.5  913.87  4924.1  913.19  4960.8  913.58  4984.6  915.04  4996.7  911.23
  4996.8  908.96  4997.3  908.46  5012.1  908.96  5021.2  909.23  5035.3  914.08
  5049.5  927.47  5063.6  952.82  5091.9  955.55  5139.4  957.45  5219.2  960.11
#Mann=5,-1,0
  4436.9    0.12       0  4960.8    0.07       0  4996.8    0.05       0
  5012.1    0.07       0  5139.4    0.12       0
Bank Sta=4996.8,5012.1
Exp/Cntr=0.3,0.1

Type RM Length L Ch R = 1,2340,433,433,433
BEGIN DESCRIPTION:
Devils Hollow 5.0
END DESCRIPTION:
XS GIS Cut Line= 3
      2179375.58     13883247.41      2179125.00     13883125.00
      2178708.18     13883021.33
#Sta/Elev= 30
  4721.4  962.16  4755.4  960.50  4777.7  957.54  4822.2  955.16  4844.5  952.47
  4852.2  949.80  4866.7  946.77  4889.0  939.11  4896.2  934.32  4901.7  932.94
  4924.2  920.88  4933.5  917.41  4955.8  912.29  4963.7  909.62  4976.6  908.67
  4978.6  908.57  4979.1  908.07  4993.9  908.57  5059.7  909.32  5082.7  915.77
  5093.0  919.98  5100.2  924.30  5113.6  928.09  5176.6  933.03  5200.9  933.60
  5257.9  936.72  5266.3  939.09  5278.5  940.33  5354.1  945.90  5429.8  953.94
#Mann=8,-1,0
  4721.4    0.07       0  4852.2    0.12       0  4976.6   0.035       0
  4978.6   0.035       0  4993.9   0.035       0  5100.2    0.12       0
  5176.6   0.035       0  5200.9    0.12       0
Bank Sta=4978.6,4993.9
Exp/Cntr=0.3,0.1

Type RM Length L Ch R = 1,1907,467,467,467
BEGIN DESCRIPTION:
Devils Hollow 4.0
END DESCRIPTION:
XS GIS Cut Line= 3
      2179451.16     13882781.29      2179125.00     13882725.00
      2178620.42     13882812.54
#Sta/Elev= 30
  4674.1  953.83  4738.3  948.97  4781.8  946.71  4809.3  943.59  4842.7  939.94
  4852.9  937.92  4858.0  935.94  4863.1  935.75  4893.5  927.70  4912.8  920.76
  4917.9  921.72  4923.9  916.87  4934.0  910.82  4944.2  909.14  4977.1  908.67
  4977.6  908.17  4992.4  908.67  5007.6  909.36  5015.2  910.74  5025.4  914.25
  5066.0  917.99  5086.3  921.03  5092.1  922.86  5106.6  923.68  5126.9  927.10
  5198.8  931.31  5271.2  935.24  5340.0  941.27  5472.0  950.27  5517.2  952.38
#Mann=5,-1,0
  4674.1    0.07       0  4809.3   0.035       0  4977.1   0.035       0
  4992.4   0.035       0  5198.8    0.12       0
Bank Sta=4977.1,4992.4
Exp/Cntr=0.3,0.1

Type RM Length L Ch R = 1,1440,483,483,483
BEGIN DESCRIPTION:
Devils Hollow 3.0
END DESCRIPTION:
XS GIS Cut Line= 3
      2179675.02     13882375.00      2179075.00     13882275.00
      2178659.73     13882184.99
#Sta/Elev= 30
  4391.7  978.70  4424.7  976.17  4440.2  973.47  4485.5  966.46  4503.2  962.83
  4543.1  959.09  4584.3  955.22  4655.3  943.78  4691.6  939.92  4817.5  931.61
  4845.4  928.19  4888.5  925.29  4898.6  923.81  4906.2  921.14  4908.6  921.31
  4939.2  916.64  4959.4  909.14  4964.4  908.61  4964.9  908.11  4979.8  908.61
  5051.2  908.88  5061.4  910.29  5081.8  917.52  5117.8  923.34  5123.0  922.62
  5133.0  923.95  5143.2  926.67  5313.1  936.77  5397.6  942.74  5424.9  943.70
#Mann=8,-1,0
  4391.7    0.12       0  4440.2    0.07       0  4543.1    0.12       0
  4691.6    0.07       0  4908.6   0.035       0  4964.4   0.035       0
  4979.8   0.035       0  5313.1    0.12       0
Bank Sta=4964.4,4979.8
Exp/Cntr=0.3,0.1

Type RM Length L Ch R = 1,957,415,415,415
BEGIN DESCRIPTION:
Devils Hollow 2.0
END DESCRIPTION:
XS GIS Cut Line= 3
      2179518.82     13882072.94      2179075.00     13881825.00
      2178654.31     13881763.07
#Sta/Elev= 30
  4490.8  952.37  4524.4  949.96  4601.7  942.58  4639.4  937.26  4675.4  935.16
  4786.4  936.25  4807.3  936.07  4823.3  933.91  4829.0  934.67  4845.0  930.74
  4866.7  928.63  4882.7  924.11  4888.4  924.05  4897.5  920.74  4910.1  918.89
  4919.0  914.97  4926.1  909.54  4931.8  911.91  4941.9  908.67  4977.7  908.58
  4978.2  908.08  4993.2  908.58  5039.6  908.94  5080.0  922.83  5103.7  924.18
  5150.8  929.93  5191.2  932.50  5249.9  933.41  5332.7  938.03  5424.4  944.43
#Mann=8,-1,0
  4490.8    0.07       0  4524.4    0.12       0  4675.4   0.035       0
  4786.4    0.07       0  4897.5   0.035       0  4977.7   0.035       0
  4993.2   0.035       0  5249.9    0.12       0
Bank Sta=4977.7,4993.2
Exp/Cntr=0.3,0.1

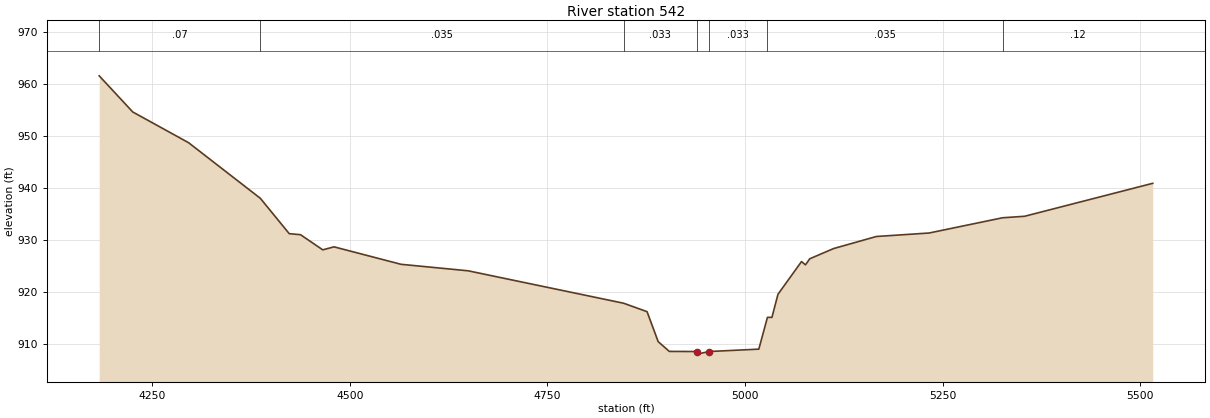
Type RM Length L Ch R = 1,542,0,0,0
BEGIN DESCRIPTION:
Devils Hollow 1.0
END DESCRIPTION:
XS GIS Cut Line= 3
      2179675.00     13882075.00      2179075.00     13881475.00
      2178593.90     13881420.51
#Sta/Elev= 30
  4183.0  961.64  4225.4  954.69  4296.1  948.77  4386.8  938.08  4423.4  931.27
  4437.6  931.08  4465.8  928.16  4480.0  928.74  4564.8  925.38  4649.7  924.13
  4846.4  917.89  4876.0  916.27  4890.1  910.50  4904.2  908.62  4938.9  908.60
  4939.4  908.10  4954.4  908.60  5017.4  909.06  5028.3  915.17  5034.0  915.17
  5041.6  919.61  5071.4  925.91  5076.4  925.28  5081.8  926.44  5112.0  928.41
  5166.1  930.73  5232.8  931.40  5325.7  934.33  5353.6  934.62  5515.7  940.96
#Mann=7,-1,0
  4183.0    0.07       0  4386.8   0.035       0  4846.4   0.033       0
  4938.9   0.033       0  4954.4   0.033       0  5028.3   0.035       0
  5325.7    0.12       0
Bank Sta=4938.9,4954.4
Exp/Cntr=0.3,0.1

Chan Stop Cuts=-1