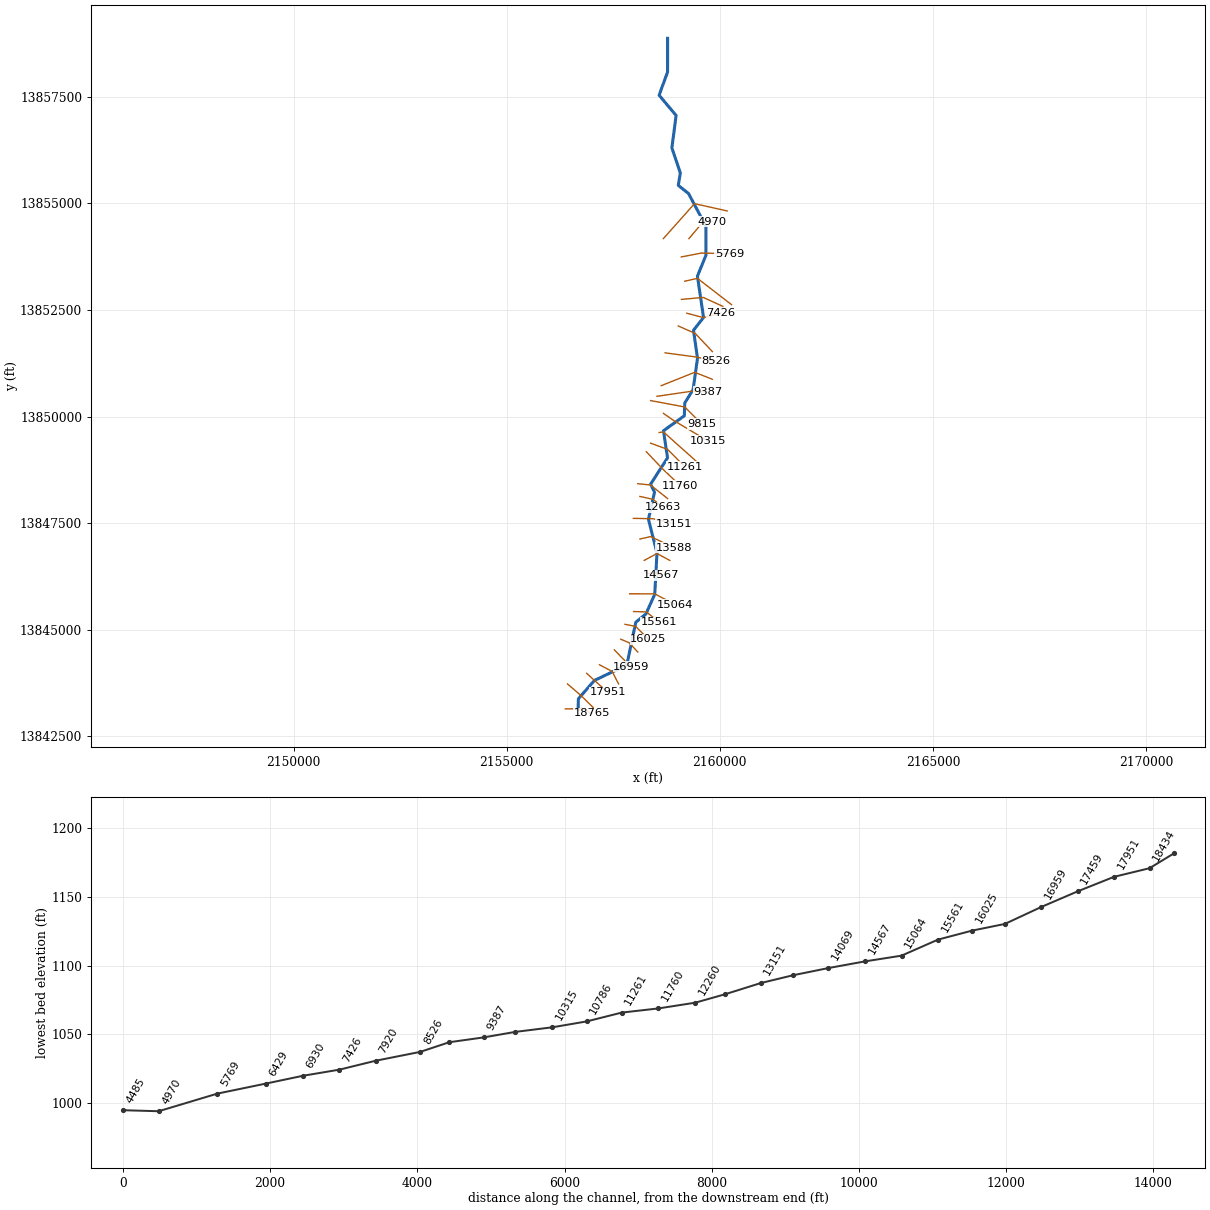
--- Elm Creek.prj (project) ---

Proj Title=Elm Creek Base Level Engineering
Current Plan=p01
Default Exp/Contr=0.3,0.1
English Units
Geom File=g01
Flow File=f01
Plan File=p01
BEGIN DESCRIPTION:
Elm Creek
END DESCRIPTION:

--- Elm Creek.p01 (plan) ---

Plan Title=Multiple Run
Short Identifier=Multiple
Geom File=g01
Flow File=f01
Subcritical Flow
K Sum by GR= 0
Std Step Tol= 0.01
Critical Tol= 0.01
Num of Std Step Trials= 20
Max Error Tol= 0.3
Flow Tol Ratio= 0.001
Split Flow NTrial= 30
Split Flow Tol= 0.02
Split Flow Ratio= 0.02
Log Output Level= 0
Friction Slope Method= 1
Unsteady Friction Slope Method= 2
Unsteady Bridges Friction Slope Method= 1
Parabolic Critical Depth
Global Vel Dist=  1 , 1 , 1
Global Log Level= 0
CheckData=True
Encroach Param= -1, 0, 0, 0
BEGIN DESCRIPTION:
Multiple Run
END DESCRIPTION:

--- Elm Creek.f01 (steady flow) ---

Flow Title=Multiple
Number of Profiles=7
Profile Names=10-year,25-year,50-year,1pct_min,100-year,1pct_plu,500-year
River Rch & RM= Elm Creek,Reach-1,18765
     415     668     899     589    1174    2343    1978
River Rch & RM= Elm Creek,Reach-1,17951
     821    1382    1913    1285    2564    5116    4556
River Rch & RM= Elm Creek,Reach-1,15561
    1314    2270    3196    2180    4349    8677    7972
River Rch & RM= Elm Creek,Reach-1,12260
    1839    3216    4562    3130    6245   12460   11589
River Rch & RM= Elm Creek,Reach-1,3635
    3954    7163   10407    7294   14553   29037   28207
Boundary for River Rch & Prof#=Elm Creek,Reach-1,1
Up Type=0
Dn Type=3
Dn Slope=0.005
Boundary for River Rch & Prof#=Elm Creek,Reach-1,2
Up Type=0
Dn Type=3
Dn Slope=0.005
Boundary for River Rch & Prof#=Elm Creek,Reach-1,3
Up Type=0
Dn Type=3
Dn Slope=0.005
Boundary for River Rch & Prof#=Elm Creek,Reach-1,4
Up Type=0
Dn Type=3
Dn Slope=0.005
Boundary for River Rch & Prof#=Elm Creek,Reach-1,5
Up Type=0
Dn Type=3
Dn Slope=0.005
Boundary for River Rch & Prof#=Elm Creek,Reach-1,6
Up Type=0
Dn Type=3
Dn Slope=0.005
Boundary for River Rch & Prof#=Elm Creek,Reach-1,7
Up Type=0
Dn Type=3
Dn Slope=0.005

--- Elm Creek.g01 (geometry) ---

Geom Title=Existing Conditions

River Reach=Elm Creek,Reach-1
Reach XY= 30
      2156675.00     13843125.00      2156680.46     13843377.45
      2157058.32     13843808.36      2157817.12     13844168.83
      2158028.53     13845173.55      2158266.87     13845368.93
      2158472.83     13845830.44      2158525.31     13846800.11
      2158325.09     13847590.40      2158467.74     13848225.30
      2158376.19     13848415.39      2158772.65     13849030.52
      2158678.03     13849666.99      2159167.31     13850018.52
      2159177.35     13850319.48      2159372.82     13850630.45
      2159475.78     13851365.86      2159382.32     13852025.10
      2159617.74     13852324.70      2159474.64     13853295.15
      2159673.80     13853784.60      2159673.78     13854464.50
      2159266.98     13855231.34      2159025.00     13855425.00
      2159073.64     13855715.35      2158874.72     13856302.15
      2158973.80     13857065.40      2158575.24     13857540.22
      2158773.80     13858085.50      2158775.00     13858875.00

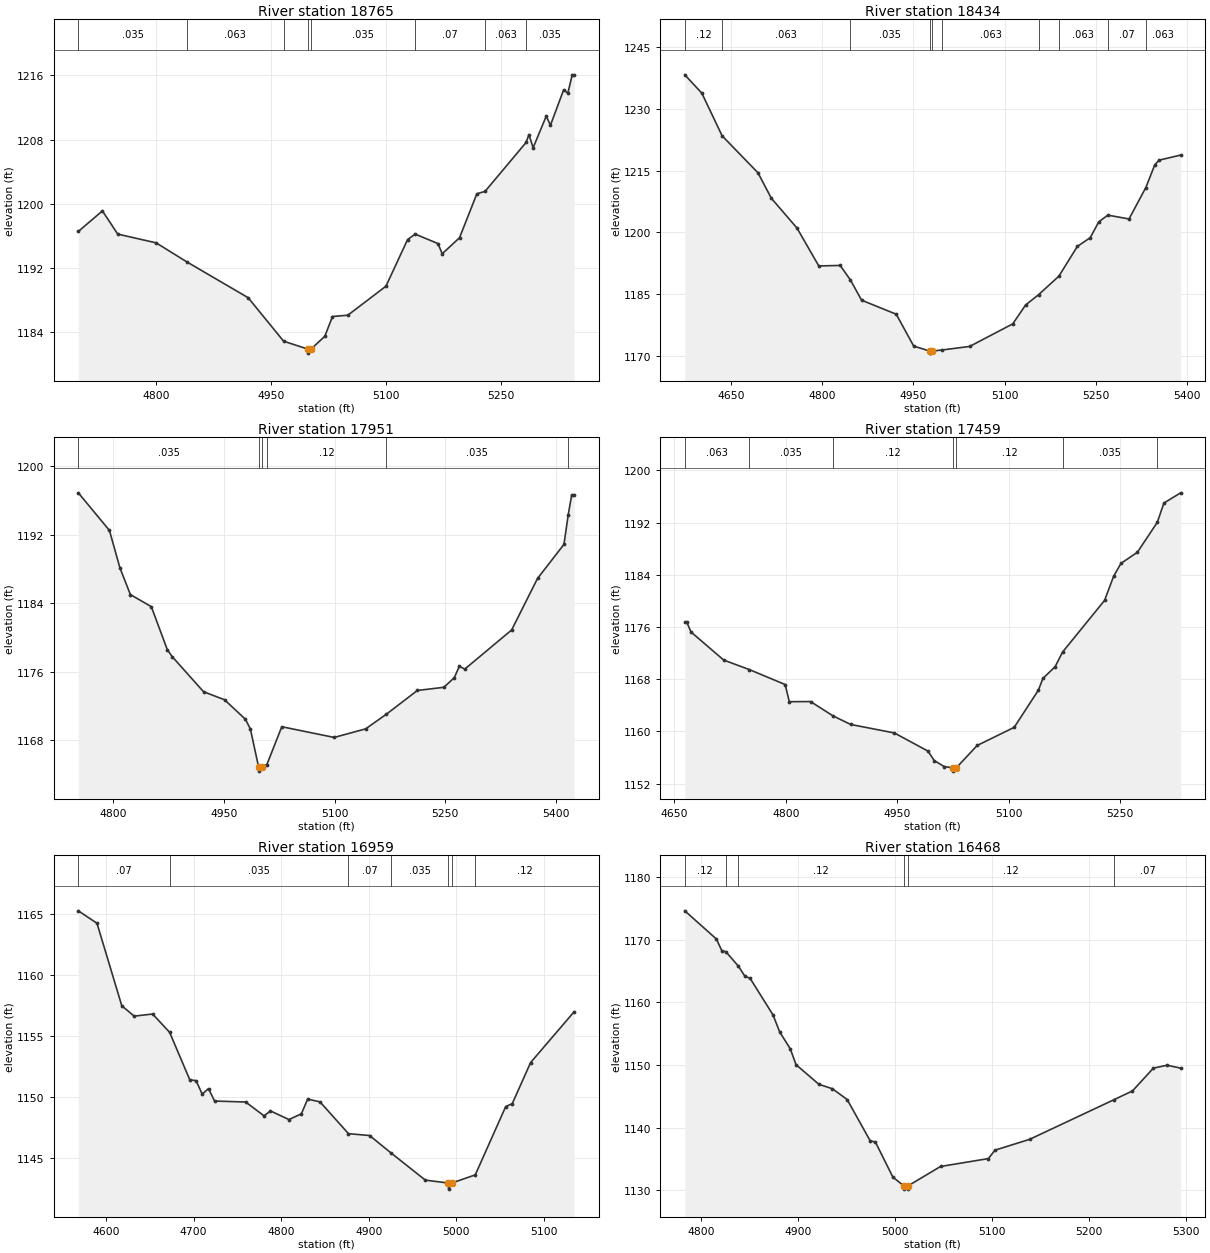
Type RM Length L Ch R = 1,18765,331,331,331
BEGIN DESCRIPTION:
Elm Creek_DS 32.0
END DESCRIPTION:
XS GIS Cut Line= 3
      2156373.56     13843139.18      2156761.10     13843147.51
      2156994.47     13843034.99
#Sta/Elev= 30
  4698.5 1196.57  4729.9 1199.13  4749.9 1196.24  4800.0 1195.15  4840.2 1192.77
  4920.0 1188.32  4966.3 1182.90  4998.0 1181.92  4998.3 1181.42  5002.0 1181.92
  5020.0 1183.52  5030.0 1185.98  5050.0 1186.14  5099.7 1189.75  5127.9 1195.55
  5137.8 1196.24  5167.6 1195.06  5173.1 1193.79  5195.7 1195.79  5218.3 1201.26
  5229.0 1201.56  5282.6 1207.66  5286.2 1208.63  5291.7 1206.99  5308.8 1210.93
  5314.3 1209.80  5331.4 1214.18  5337.0 1213.80  5342.7 1216.07  5345.2 1216.07
#Mann=8,-1,0
  4698.5   0.035       0  4840.2   0.063       0  4966.3   0.035       0
  4998.0   0.035       0  5002.0   0.035       0  5137.8    0.07       0
  5229.0   0.063       0  5282.6   0.035       0
Bank Sta=4998,5002
Exp/Cntr=0.3,0.1

Type RM Length L Ch R = 1,18434,483,483,483
BEGIN DESCRIPTION:
Elm Creek_DS 31.0
END DESCRIPTION:
XS GIS Cut Line= 3
      2156424.98     13843725.02      2156748.27     13843448.36
      2157025.01     13843174.99
#Sta/Elev= 30
  4574.5 1238.31  4602.5 1233.85  4635.8 1223.49  4694.7 1214.50  4716.7 1208.30
  4758.8 1201.07  4794.6 1191.86  4829.7 1191.98  4846.6 1188.45  4864.9 1183.54
  4921.9 1180.12  4950.5 1172.38  4977.0 1171.17  4977.3 1170.67  4981.0 1171.17
  4997.6 1171.44  5042.5 1172.30  5113.2 1177.78  5134.5 1182.40  5155.6 1184.86
  5189.1 1189.39  5219.3 1196.60  5240.5 1198.73  5254.6 1202.58  5269.4 1204.21
  5304.2 1203.28  5331.9 1210.92  5346.6 1216.45  5353.6 1217.57  5389.0 1218.81
#Mann=10,-1,0
  4574.5    0.12       0  4635.8   0.063       0  4846.6   0.035       0
  4977.0    0.05       0  4981.0   0.035       0  4997.6   0.063       0
  5155.6   0.035       0  5189.1   0.063       0  5269.4    0.07       0
  5331.9   0.063       0
Bank Sta=4977,4981
Exp/Cntr=0.3,0.1

Type RM Length L Ch R = 1,17951,492,492,492
BEGIN DESCRIPTION:
Elm Creek_DS 30.0
END DESCRIPTION:
XS GIS Cut Line= 3
      2156875.03     13843974.97      2157058.32     13843808.36
      2157374.97     13843525.03
#Sta/Elev= 30
  4752.3 1196.87  4794.5 1192.48  4808.7 1188.12  4822.9 1185.00  4851.3 1183.59
  4872.9 1178.59  4879.6 1177.76  4922.2 1173.66  4950.6 1172.73  4979.0 1170.45
  4985.7 1169.31  4996.8 1164.90  4997.0 1164.40  5000.8 1164.90  5008.0 1165.15
  5028.3 1169.58  5099.4 1168.33  5142.0 1169.33  5169.7 1171.01  5212.2 1173.81
  5248.1 1174.18  5262.3 1175.30  5269.1 1176.63  5276.6 1176.31  5340.1 1180.87
  5375.2 1186.88  5411.1 1190.86  5416.8 1194.28  5421.6 1196.64  5424.9 1196.64
#Mann=6,-1,0
  4752.3   0.035       0  4996.8   0.035       0  5000.8   0.035       0
  5008.0    0.12       0  5169.7   0.035       0  5416.8   0.063       0
Bank Sta=4996.8,5000.8
Exp/Cntr=0.3,0.1

Type RM Length L Ch R = 1,17459,500,500,500
BEGIN DESCRIPTION:
Elm Creek_DS 29.0
END DESCRIPTION:
XS GIS Cut Line= 3
      2157174.97     13844175.02      2157472.57     13844019.48
      2157625.00     13843724.99
#Sta/Elev= 30
  4664.2 1176.68  4667.1 1176.68  4672.5 1175.23  4716.6 1170.92  4751.1 1169.46
  4799.3 1167.17  4804.9 1164.54  4833.5 1164.56  4864.1 1162.34  4887.6 1161.05
  4946.3 1159.75  4991.5 1156.97  5000.0 1155.51  5013.4 1154.60  5025.6 1154.40
  5025.8 1153.90  5029.6 1154.40  5057.7 1157.83  5107.6 1160.61  5140.2 1166.32
  5146.2 1168.10  5162.7 1169.91  5172.7 1172.15  5229.2 1180.06  5241.5 1183.78
  5251.3 1185.74  5273.4 1187.44  5300.2 1192.03  5309.1 1194.98  5331.6 1196.55
#Mann=7,-1,0
  4664.2   0.063       0  4751.1   0.035       0  4864.1    0.12       0
  5025.6    0.05       0  5029.6    0.12       0  5172.7   0.035       0
  5300.2    0.12       0
Bank Sta=5025.6,5029.6
Exp/Cntr=0.3,0.1

Type RM Length L Ch R = 1,16959,491,491,491
BEGIN DESCRIPTION:
Elm Creek_DS 28.0
END DESCRIPTION:
XS GIS Cut Line= 3
      2157524.98     13844525.02      2157825.18     13844214.93
      2157925.03     13844124.97
#Sta/Elev= 30
  4568.4 1165.27  4589.7 1164.25  4618.0 1157.48  4632.1 1156.63  4653.2 1156.80
  4672.6 1155.30  4695.6 1151.41  4702.8 1151.33  4709.8 1150.23  4717.0 1150.68
  4723.9 1149.66  4759.4 1149.58  4780.5 1148.44  4787.7 1148.85  4808.8 1148.14
  4823.0 1148.61  4830.2 1149.82  4844.3 1149.59  4876.8 1146.98  4900.9 1146.83
  4925.7 1145.38  4964.5 1143.17  4990.7 1142.93  4991.0 1142.43  4994.7 1142.93
  5021.5 1143.60  5056.3 1149.21  5063.7 1149.44  5084.7 1152.82  5134.4 1156.99
#Mann=7,-1,0
  4568.4    0.07       0  4672.6   0.035       0  4876.8    0.07       0
  4925.7   0.035       0  4990.7   0.035       0  4994.7   0.035       0
  5021.5    0.12       0
Bank Sta=4990.7,4994.7
Exp/Cntr=0.3,0.1

Type RM Length L Ch R = 1,16468,443,443,443
BEGIN DESCRIPTION:
Elm Creek_DS 27.0
END DESCRIPTION:
XS GIS Cut Line= 3
      2157674.98     13844775.01      2157874.51     13844690.20
      2158074.98     13844475.02
#Sta/Elev= 30
  4783.2 1174.58  4815.8 1170.08  4821.4 1168.20  4825.5 1168.06  4838.4 1165.76
  4845.1 1164.16  4850.5 1163.81  4874.1 1157.98  4881.0 1155.26  4891.9 1152.57
  4897.8 1150.05  4921.4 1146.91  4935.3 1146.21  4950.5 1144.49  4974.2 1137.91
  4979.6 1137.71  4997.6 1132.12  5009.0 1130.70  5009.3 1130.20  5012.8 1130.20
  5013.0 1130.70  5046.7 1133.81  5096.0 1135.07  5102.8 1136.41  5138.5 1138.14
  5225.7 1144.48  5244.5 1145.86  5266.0 1149.49  5280.2 1149.96  5294.1 1149.49
#Mann=6,-1,0
  4783.2    0.12       0  4825.5   0.063       0  4838.4    0.12       0
  5009.0    0.05       0  5013.0    0.12       0  5225.7    0.07       0
Bank Sta=5009,5013
Exp/Cntr=0.3,0.1

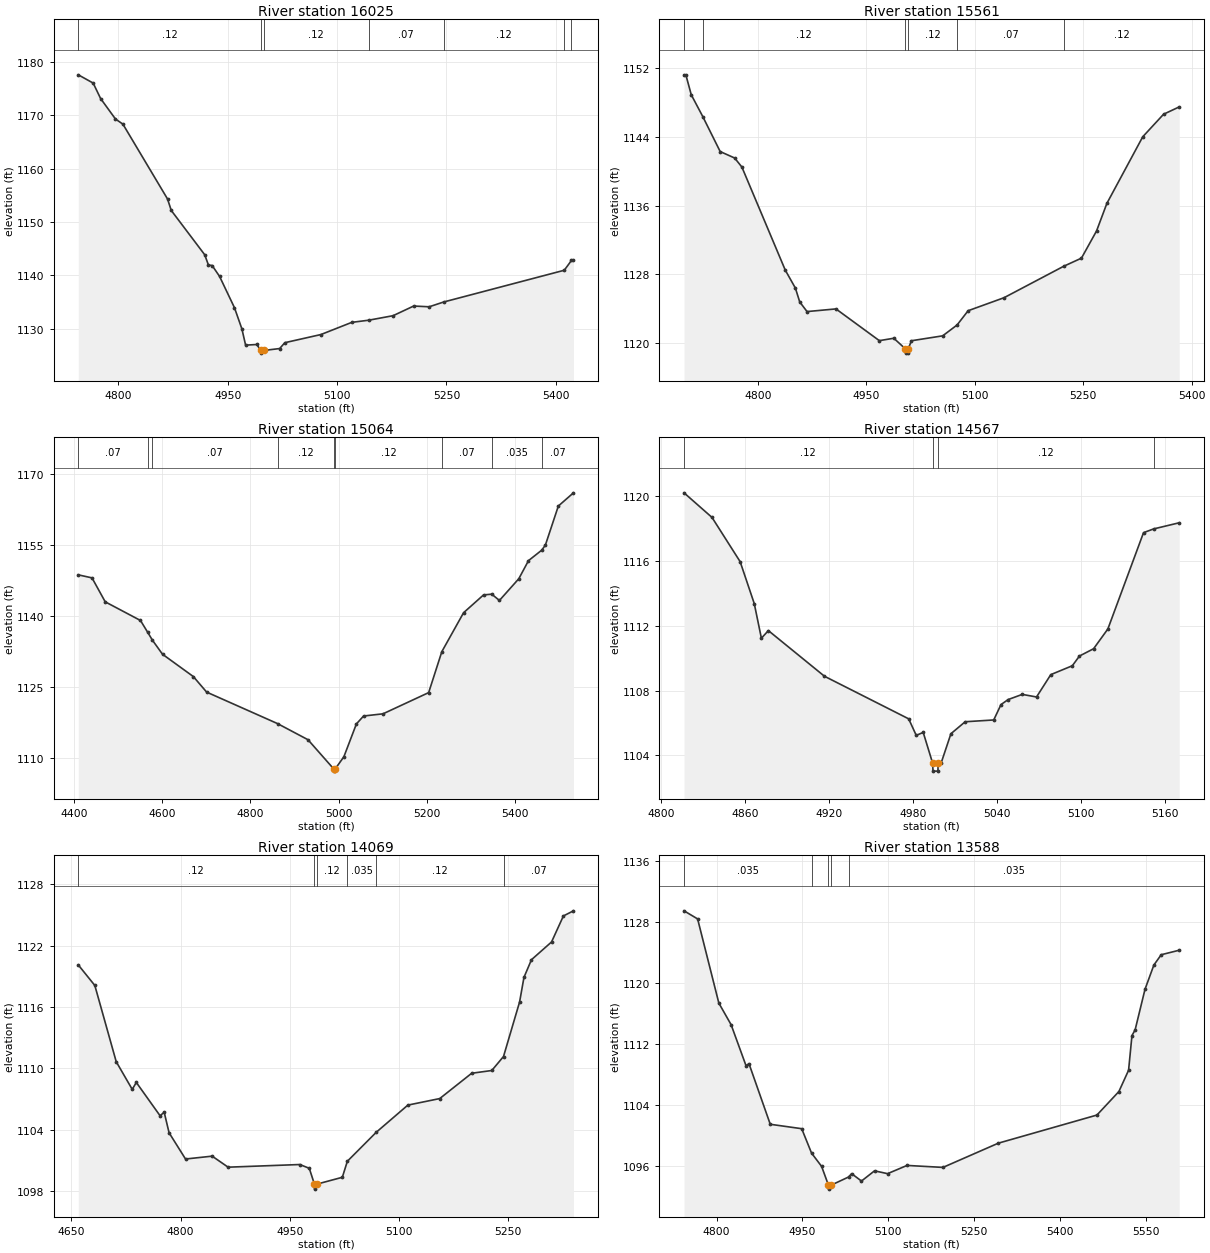
Type RM Length L Ch R = 1,16025,464,464,464
BEGIN DESCRIPTION:
Elm Creek_DS 26.0
END DESCRIPTION:
XS GIS Cut Line= 3
      2157774.97     13845125.01      2158024.92     13845075.03
      2158324.97     13844775.03
#Sta/Elev= 30
  4745.1 1177.63  4765.5 1176.08  4775.7 1173.18  4796.1 1169.33  4806.3 1168.37
  4867.5 1154.32  4872.6 1152.17  4918.5 1143.85  4923.6 1141.92  4928.7 1141.83
  4938.9 1139.78  4959.3 1133.91  4969.5 1129.93  4974.6 1126.88  4989.9 1127.00
  4995.5 1125.88  4995.7 1125.38  4999.5 1125.88  5021.3 1126.24  5028.4 1127.34
  5077.9 1128.87  5120.3 1131.16  5143.4 1131.56  5176.9 1132.41  5205.1 1134.22
  5226.4 1134.08  5246.3 1134.98  5411.7 1140.94  5421.6 1142.79  5424.3 1142.79
#Mann=7,-1,0
  4745.1    0.12       0  4995.5    0.05       0  4999.5    0.12       0
  5143.4    0.07       0  5246.3    0.12       0  5411.7    0.07       0
  5421.6   0.035       0
Bank Sta=4995.5,4999.5
Exp/Cntr=0.3,0.1

Type RM Length L Ch R = 1,15561,497,497,497
BEGIN DESCRIPTION:
Elm Creek_DS 25.0
END DESCRIPTION:
XS GIS Cut Line= 3
      2157975.04     13845425.00      2158276.88     13845415.13
      2158575.00     13845175.00
#Sta/Elev= 30
  4698.0 1151.20  4700.5 1151.20  4708.0 1148.88  4723.9 1146.35  4748.0 1142.28
  4768.0 1141.53  4778.0 1140.48  4838.0 1128.50  4852.0 1126.41  4858.0 1124.80
  4868.1 1123.68  4908.1 1123.99  4968.1 1120.30  4988.1 1120.58  5004.1 1119.35
  5004.3 1118.85  5007.8 1118.85  5008.1 1119.35  5012.5 1120.29  5055.7 1120.86
  5075.6 1122.12  5090.9 1123.78  5140.5 1125.29  5222.9 1128.94  5247.6 1129.89
  5268.5 1133.05  5282.8 1136.26  5332.4 1144.00  5361.2 1146.62  5382.8 1147.47
#Mann=6,-1,0
  4698.0    0.07       0  4723.9    0.12       0  5004.1    0.05       0
  5008.1    0.12       0  5075.6    0.07       0  5222.9    0.12       0
Bank Sta=5004.1,5008.1
Exp/Cntr=0.3,0.1

Type RM Length L Ch R = 1,15064,497,497,497
BEGIN DESCRIPTION:
Elm Creek_DS 24.0
END DESCRIPTION:
XS GIS Cut Line= 3
      2157883.87     13845841.61      2158474.46     13845838.86
      2158945.32     13845589.72
#Sta/Elev= 30
  4409.4 1148.63  4440.5 1147.99  4470.5 1142.93  4550.5 1138.99  4566.4 1136.56
  4577.7 1134.81  4600.5 1131.86  4670.5 1127.14  4700.5 1123.87  4861.3 1117.22
  4930.5 1113.81  4988.5 1107.68  4988.8 1107.18  4992.5 1107.68  5011.9 1110.22
  5040.3 1117.15  5056.6 1118.82  5100.6 1119.28  5204.2 1123.76  5234.1 1132.41
  5283.4 1140.63  5328.7 1144.39  5347.4 1144.55  5364.7 1143.22  5408.7 1147.81
  5430.7 1151.63  5460.7 1153.84  5469.0 1154.91  5498.4 1163.16  5532.7 1165.95
#Mann=9,-1,0
  4409.4    0.07       0  4566.4   0.063       0  4577.7    0.07       0
  4861.3    0.12       0  4988.5    0.05       0  4992.5    0.12       0
  5234.1    0.07       0  5347.4   0.035       0  5460.7    0.07       0
Bank Sta=4988.5,4992.5
Exp/Cntr=0.3,0.1

Type RM Length L Ch R = 1,14567,498,498,498
BEGIN DESCRIPTION:
Elm Creek_DS 23.0
END DESCRIPTION:
XS GIS Cut Line= 3
      2158275.05     13846325.00      2158458.10     13846308.42
      2158624.98     13846275.00
#Sta/Elev= 30
  4816.2 1120.21  4836.2 1118.69  4856.3 1115.96  4866.4 1113.37  4871.5 1111.23
  4876.5 1111.70  4916.6 1108.88  4976.8 1106.25  4982.2 1105.23  4987.2 1105.41
  4993.9 1103.52  4994.2 1103.02  4997.7 1103.02  4997.9 1103.52  5000.0 1103.52
  5007.0 1105.33  5017.2 1106.07  5037.6 1106.18  5042.8 1107.13  5047.9 1107.44
  5058.0 1107.76  5068.2 1107.60  5078.4 1108.98  5093.8 1109.53  5098.9 1110.13
  5109.0 1110.58  5119.2 1111.80  5144.7 1117.75  5151.9 1117.98  5170.2 1118.36
#Mann=4,-1,0
  4816.2    0.12       0  4993.9    0.05       0  4997.9    0.12       0
  5151.9    0.07       0
Bank Sta=4993.9,4997.9
Exp/Cntr=0.3,0.1

Type RM Length L Ch R = 1,14069,481,481,481
BEGIN DESCRIPTION:
Elm Creek_DS 22.0
END DESCRIPTION:
XS GIS Cut Line= 3
      2158224.97     13846624.99      2158525.55     13846785.19
      2158824.99     13846625.00
#Sta/Elev= 30
  4659.4 1120.12  4682.1 1118.11  4711.5 1110.64  4733.5 1107.93  4739.1 1108.61
  4771.7 1105.35  4777.4 1105.69  4784.1 1103.68  4806.7 1101.11  4843.3 1101.39
  4865.2 1100.31  4963.7 1100.57  4976.7 1100.20  4983.7 1098.66  4983.9 1098.16
  4987.7 1098.66  5022.1 1099.32  5029.0 1100.89  5068.7 1103.73  5112.1 1106.39
  5155.9 1107.03  5199.8 1109.51  5227.4 1109.78  5243.5 1111.15  5265.6 1116.49
  5271.6 1118.90  5281.9 1120.63  5309.5 1122.37  5325.8 1124.92  5339.6 1125.42
#Mann=6,-1,0
  4659.4    0.12       0  4983.7    0.05       0  4987.7    0.12       0
  5029.0   0.035       0  5068.7    0.12       0  5243.5    0.07       0
Bank Sta=4983.7,4987.7
Exp/Cntr=0.3,0.1

Type RM Length L Ch R = 1,13588,437,437,437
BEGIN DESCRIPTION:
Elm Creek_DS 21.0
END DESCRIPTION:
XS GIS Cut Line= 3
      2158125.03     13847125.01      2158374.95     13847184.07
      2158924.99     13846925.00
#Sta/Elev= 30
  4743.2 1129.45  4766.9 1128.39  4804.0 1117.34  4825.4 1114.51  4851.5 1109.12
  4856.6 1109.40  4893.8 1101.44  4948.7 1100.86  4965.9 1097.66  4983.5 1095.91
  4995.5 1093.43  4995.7 1092.93  4999.5 1093.43  5030.5 1094.52  5035.9 1094.96
  5053.1 1093.99  5075.9 1095.33  5098.7 1094.96  5132.7 1096.04  5195.4 1095.78
  5292.1 1098.96  5464.3 1102.65  5502.7 1105.74  5519.6 1108.53  5525.5 1113.08
  5531.0 1113.82  5548.3 1119.16  5563.8 1122.34  5576.6 1123.69  5608.0 1124.28
#Mann=5,-1,0
  4743.2   0.035       0  4965.9    0.07       0  4995.5    0.05       0
  4999.5    0.07       0  5030.5   0.035       0
Bank Sta=4995.5,4999.5
Exp/Cntr=0.3,0.1

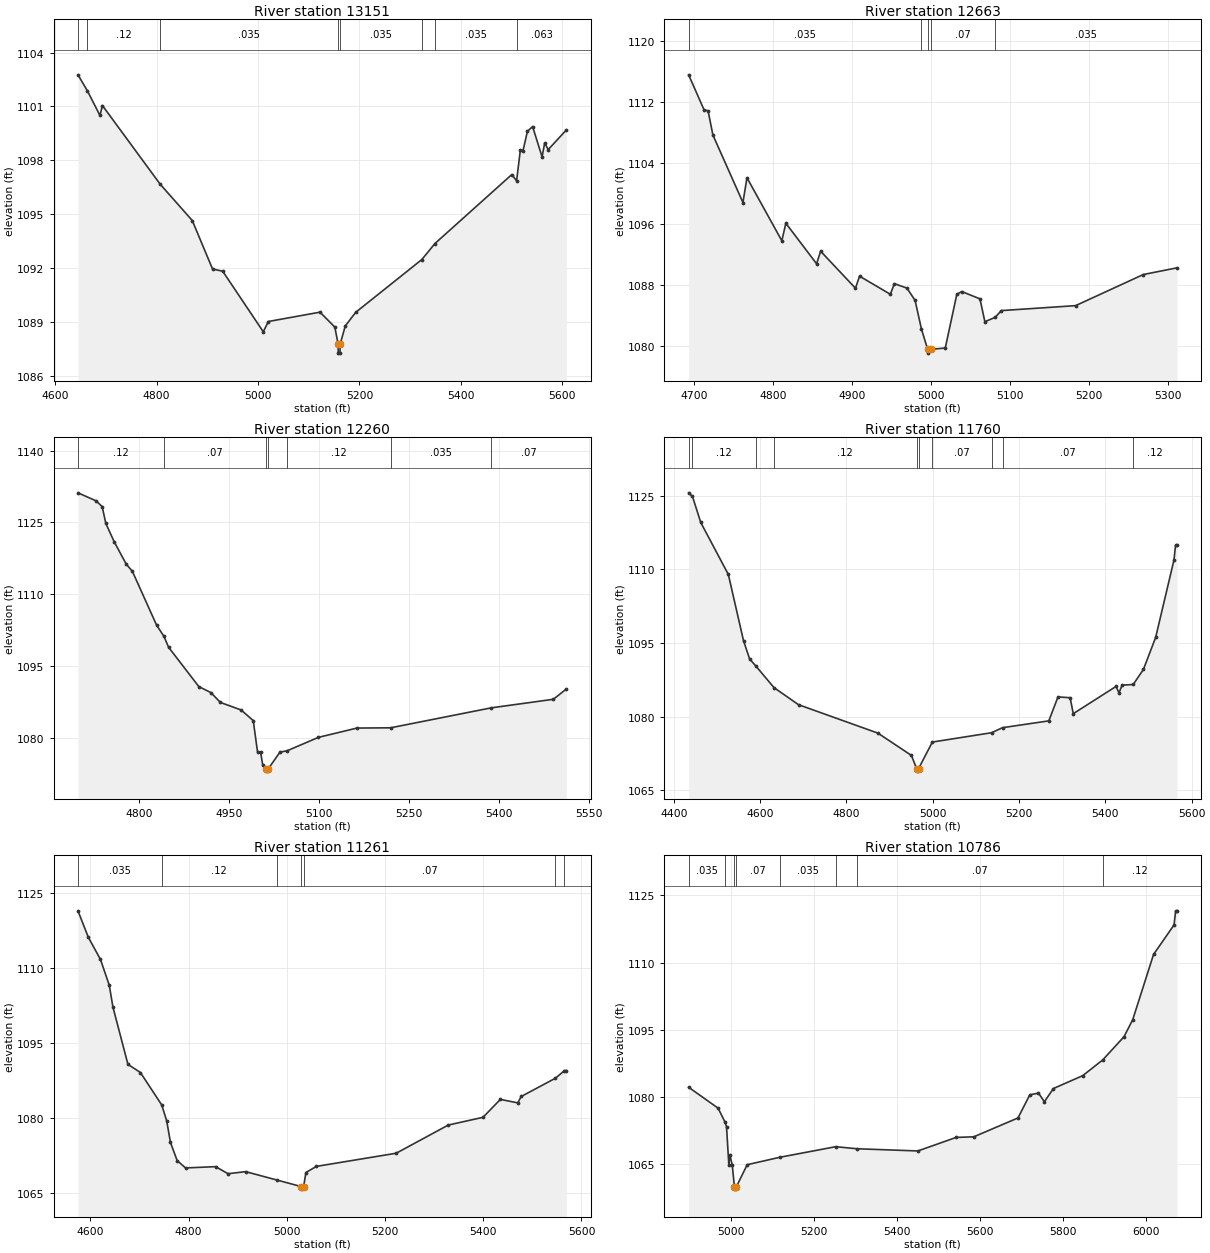
Type RM Length L Ch R = 1,13151,488,488,488
BEGIN DESCRIPTION:
Elm Creek_DS 20.0
END DESCRIPTION:
XS GIS Cut Line= 3
      2157969.65     13847610.83      2158432.24     13847602.50
      2158919.76     13847489.99
#Sta/Elev= 30
  4644.9 1102.76  4663.5 1101.87  4688.2 1100.50  4693.2 1101.05  4806.8 1096.68
  4870.3 1094.65  4910.3 1091.95  4930.3 1091.83  5010.3 1088.46  5020.3 1089.03
  5122.2 1089.55  5151.4 1088.72  5157.9 1087.77  5158.1 1087.27  5161.6 1087.27
  5161.9 1087.77  5172.0 1088.78  5192.5 1089.54  5323.0 1092.48  5348.8 1093.37
  5500.4 1097.21  5509.8 1096.86  5517.3 1098.59  5522.5 1098.54  5531.2 1099.62
  5541.4 1099.88  5560.1 1098.19  5565.2 1098.97  5572.2 1098.60  5607.9 1099.69
#Mann=8,-1,0
  4644.9   0.035       0  4663.5    0.12       0  4806.8   0.035       0
  5157.9   0.035       0  5161.9   0.035       0  5323.0    0.07       0
  5348.8   0.035       0  5509.8   0.063       0
Bank Sta=5157.9,5161.9
Exp/Cntr=0.3,0.1

Type RM Length L Ch R = 1,12663,403,403,403
BEGIN DESCRIPTION:
Elm Creek_DS 19.0
END DESCRIPTION:
XS GIS Cut Line= 3
      2158125.02     13848125.00      2158424.96     13848060.02
      2158674.96     13847875.03
#Sta/Elev= 30
  4693.1 1115.61  4712.6 1111.02  4717.7 1110.89  4723.8 1107.71  4761.8 1098.86
  4766.9 1102.11  4811.0 1093.84  4816.1 1096.14  4855.0 1090.82  4860.1 1092.47
  4904.2 1087.61  4909.3 1089.20  4948.3 1086.82  4953.4 1088.21  4969.3 1087.63
  4979.6 1086.02  4987.7 1082.24  4995.5 1079.60  4995.7 1079.10  4999.5 1079.60
  5017.8 1079.77  5032.4 1086.81  5038.6 1087.18  5061.7 1086.22  5067.9 1083.22
  5081.0 1083.80  5088.7 1084.68  5182.7 1085.33  5268.3 1089.41  5311.0 1090.29
#Mann=5,-1,0
  4693.1   0.035       0  4987.7    0.07       0  4995.5    0.05       0
  4999.5    0.07       0  5081.0   0.035       0
Bank Sta=4995.5,4999.5
Exp/Cntr=0.3,0.1

Type RM Length L Ch R = 1,12260,500,500,500
BEGIN DESCRIPTION:
Elm Creek_DS 18.0
END DESCRIPTION:
XS GIS Cut Line= 3
      2158074.96     13848425.00      2158374.49     13848393.33
      2158775.00     13848075.00
#Sta/Elev= 30
  4698.8 1131.17  4729.0 1129.49  4739.1 1128.29  4745.2 1124.77  4759.2 1120.92
  4779.3 1116.24  4789.3 1114.79  4829.6 1103.54  4841.8 1101.20  4849.7 1098.89
  4900.0 1090.68  4920.1 1089.43  4935.8 1087.37  4970.3 1085.80  4990.5 1083.58
  4997.7 1077.01  5002.7 1077.01  5006.2 1074.38  5011.3 1073.52  5011.6 1073.02
  5015.3 1073.02  5015.6 1073.52  5035.0 1076.99  5046.8 1077.27  5099.1 1080.08
  5163.2 1082.02  5219.0 1082.07  5386.5 1086.24  5490.0 1088.03  5511.6 1090.18
#Mann=7,-1,0
  4698.8    0.12       0  4841.8    0.07       0  5011.3    0.05       0
  5015.6    0.07       0  5046.8    0.12       0  5219.0   0.035       0
  5386.5    0.07       0
Bank Sta=5011.3,5015.6
Exp/Cntr=0.3,0.1

Type RM Length L Ch R = 1,11760,499,499,499
BEGIN DESCRIPTION:
Elm Creek_DS 17.0
END DESCRIPTION:
XS GIS Cut Line= 3
      2158275.01     13849174.99      2158664.56     13848764.92
      2159074.98     13848375.02
#Sta/Elev= 30
  4434.4 1125.62  4443.3 1124.88  4462.5 1119.57  4526.4 1108.97  4561.6 1095.44
  4575.8 1091.72  4591.1 1090.20  4632.2 1085.89  4689.0 1082.41  4873.0 1076.61
  4950.7 1072.06  4962.7 1069.36  4963.0 1068.86  4967.1 1069.36  4999.2 1074.79
  5136.3 1076.69  5161.7 1077.72  5269.0 1079.11  5290.3 1084.00  5318.4 1083.83
  5325.7 1080.58  5424.7 1086.13  5431.6 1084.84  5438.9 1086.39  5464.6 1086.53
  5488.3 1089.61  5516.6 1096.13  5559.0 1111.90  5562.7 1114.91  5566.1 1114.91
#Mann=10,-1,0
  4434.4   0.035       0  4443.3    0.12       0  4591.1   0.035       0
  4632.2    0.12       0  4962.7    0.05       0  4967.1    0.12       0
  4999.2    0.07       0  5136.3   0.035       0  5161.7    0.07       0
  5464.6    0.12       0
Bank Sta=4962.7,4967.1
Exp/Cntr=0.3,0.1

Type RM Length L Ch R = 1,11261,475,475,475
BEGIN DESCRIPTION:
Elm Creek_DS 16.0
END DESCRIPTION:
XS GIS Cut Line= 3
      2158375.05     13849374.98      2158775.10     13849230.04
      2159175.01     13848824.99
#Sta/Elev= 30
  4574.5 1121.41  4595.7 1116.11  4620.4 1111.69  4638.3 1106.54  4645.7 1102.20
  4676.3 1090.75  4701.7 1089.12  4745.2 1082.63  4755.3 1079.44  4762.9 1075.16
  4776.5 1071.54  4793.6 1070.06  4854.8 1070.32  4880.1 1068.91  4916.1 1069.32
  4979.6 1067.65  5029.6 1066.33  5029.9 1065.83  5034.1 1066.33  5038.8 1069.15
  5060.1 1070.37  5222.7 1073.00  5328.8 1078.63  5399.5 1080.17  5434.8 1083.75
  5470.2 1083.06  5477.3 1084.33  5546.8 1087.97  5565.1 1089.47  5569.2 1089.52
#Mann=7,-1,0
  4574.5   0.035       0  4745.2    0.12       0  4979.6    0.07       0
  5029.6    0.05       0  5034.1    0.07       0  5546.8   0.035       0
  5565.1    0.07       0
Bank Sta=5029.6,5034.1
Exp/Cntr=0.3,0.1

Type RM Length L Ch R = 1,10786,471,471,471
BEGIN DESCRIPTION:
Elm Creek_DS 15.0
END DESCRIPTION:
XS GIS Cut Line= 3
      2158574.98     13849625.00      2158674.58     13849640.56
      2159474.97     13848925.02
#Sta/Elev= 30
  4899.2 1082.17  4970.1 1077.50  4986.2 1074.48  4990.3 1073.39  4995.9 1064.80
  4998.2 1067.07  5004.1 1064.80  5009.3 1059.93  5009.6 1059.43  5013.8 1059.93
  5040.0 1064.88  5118.0 1066.53  5252.8 1068.90  5304.3 1068.44  5450.4 1067.95
  5542.4 1070.97  5585.0 1071.11  5691.2 1075.32  5719.6 1080.48  5740.5 1080.86
  5754.7 1078.94  5776.4 1081.89  5846.7 1084.75  5895.1 1088.28  5946.2 1093.46
  5967.1 1097.25  6017.2 1111.82  6066.5 1118.41  6070.3 1121.55  6073.6 1121.55
#Mann=8,-1,0
  4899.2   0.035       0  4986.2    0.07       0  5009.3    0.05       0
  5013.8    0.07       0  5118.0   0.035       0  5252.8    0.12       0
  5304.3    0.07       0  5895.1    0.12       0
Bank Sta=5009.3,5013.8
Exp/Cntr=0.3,0.1

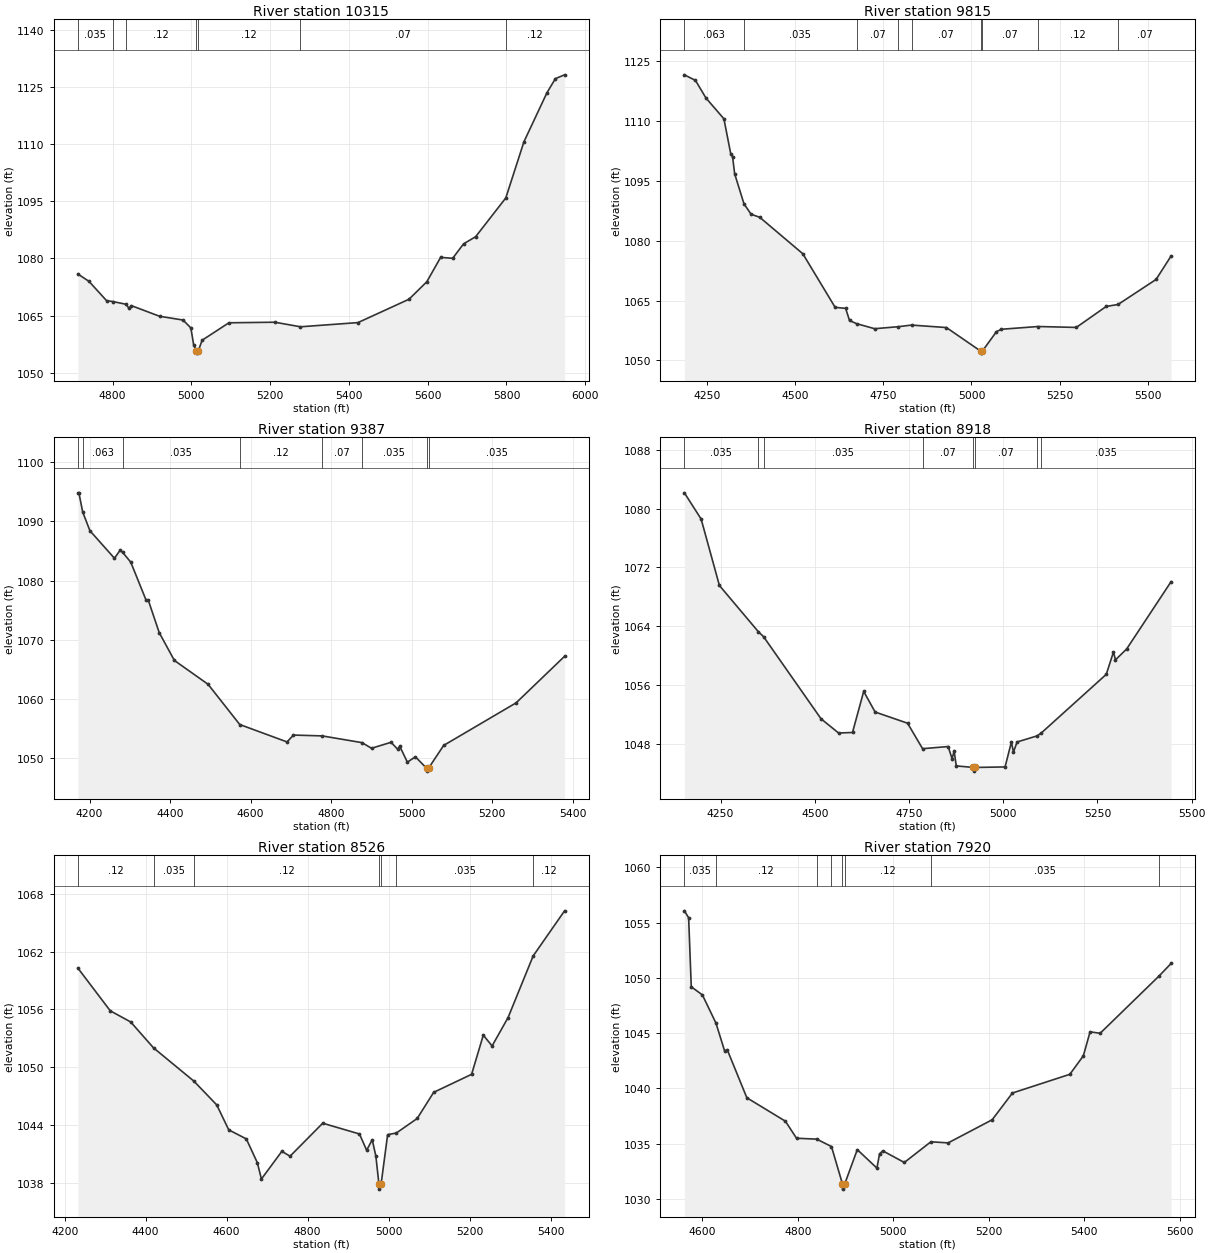
Type RM Length L Ch R = 1,10315,500,500,500
BEGIN DESCRIPTION:
Elm Creek_DS 14.0
END DESCRIPTION:
XS GIS Cut Line= 3
      2158675.03     13850074.98      2158911.84     13849911.25
      2159725.04     13849424.98
#Sta/Elev= 30
  4712.1 1075.90  4740.4 1073.95  4785.0 1068.89  4800.5 1068.67  4834.4 1067.95
  4841.8 1066.88  4847.9 1067.59  4919.5 1064.80  4979.0 1063.81  4998.9 1061.75
  5006.0 1057.31  5013.0 1055.63  5013.4 1055.13  5017.6 1055.63  5027.4 1058.51
  5095.5 1063.09  5212.2 1063.24  5277.1 1062.04  5423.1 1063.14  5552.6 1069.27
  5597.9 1073.86  5632.9 1080.25  5663.5 1080.01  5691.1 1083.80  5721.8 1085.68
  5798.3 1095.84  5844.4 1110.59  5902.7 1123.43  5924.2 1127.15  5947.5 1128.15
#Mann=7,-1,0
  4712.1   0.035       0  4800.5    0.07       0  4834.4    0.12       0
  5013.0    0.05       0  5017.6    0.12       0  5277.1    0.07       0
  5798.3    0.12       0
Bank Sta=5013,5017.6
Exp/Cntr=0.3,0.1

Type RM Length L Ch R = 1,9815,428,428,428
BEGIN DESCRIPTION:
Elm Creek_DS 13.0
END DESCRIPTION:
XS GIS Cut Line= 3
      2158374.96     13850375.01      2159174.92     13850225.03
      2159575.03     13849824.97
#Sta/Elev= 30
  4186.1 1121.57  4217.5 1120.17  4247.2 1115.76  4298.1 1110.55  4317.6 1101.74
  4322.7 1101.04  4328.6 1096.76  4355.0 1089.25  4375.2 1086.63  4399.8 1085.86
  4521.9 1076.72  4613.5 1063.29  4643.2 1063.04  4654.2 1060.00  4674.1 1059.21
  4725.4 1057.94  4792.1 1058.44  4830.0 1058.85  4928.9 1058.23  5026.1 1052.32
  5026.4 1051.82  5030.7 1052.32  5070.8 1057.20  5084.9 1057.80  5188.5 1058.49
  5297.1 1058.26  5381.9 1063.52  5415.4 1064.01  5523.3 1070.29  5565.8 1076.16
#Mann=9,-1,0
  4186.1   0.063       0  4355.0   0.035       0  4674.1    0.07       0
  4792.1    0.12       0  4830.0    0.07       0  5026.1    0.05       0
  5030.7    0.07       0  5188.5    0.12       0  5415.4    0.07       0
Bank Sta=5026.1,5030.7
Exp/Cntr=0.3,0.1

Type RM Length L Ch R = 1,9387,469,469,469
BEGIN DESCRIPTION:
Elm Creek_DS 12.0
END DESCRIPTION:
XS GIS Cut Line= 3
      2158525.02     13850475.00      2159345.42     13850594.83
      2159725.00     13850575.00
#Sta/Elev= 30
  4170.9 1094.83  4173.4 1094.83  4182.9 1091.59  4200.8 1088.43  4261.8 1083.78
  4275.8 1085.13  4282.1 1084.78  4302.3 1083.12  4340.7 1076.65  4345.8 1076.71
  4373.0 1071.22  4410.7 1066.52  4494.3 1062.50  4573.1 1055.70  4690.6 1052.76
  4706.5 1053.92  4777.7 1053.78  4876.9 1052.64  4900.5 1051.69  4949.0 1052.70
  4965.4 1051.53  4970.5 1052.05  4989.5 1049.35  5009.6 1050.24  5037.1 1048.33
  5037.5 1047.83  5042.2 1048.33  5079.7 1052.17  5259.9 1059.37  5380.1 1067.22
#Mann=8,-1,0
  4170.9   0.035       0  4182.9   0.063       0  4282.1   0.035       0
  4573.1    0.12       0  4777.7    0.07       0  4876.9   0.035       0
  5037.1   0.035       0  5042.2   0.035       0
Bank Sta=5037.1,5042.2
Exp/Cntr=0.3,0.1

Type RM Length L Ch R = 1,8918,392,392,392
BEGIN DESCRIPTION:
Elm Creek_DS 11.0
END DESCRIPTION:
XS GIS Cut Line= 3
      2158625.04     13850725.02      2159410.65     13851038.37
      2159825.01     13850875.00
#Sta/Elev= 30
  4154.2 1082.13  4198.6 1078.57  4247.1 1069.54  4350.6 1063.25  4364.2 1062.59
  4516.7 1051.43  4563.3 1049.50  4600.2 1049.57  4629.9 1055.15  4660.2 1052.35
  4746.3 1050.83  4786.1 1047.37  4854.0 1047.66  4864.4 1046.00  4869.8 1047.07
  4875.5 1045.03  4921.1 1044.82  4921.5 1044.32  4926.3 1044.82  5005.0 1044.89
  5021.8 1048.28  5027.2 1046.91  5036.9 1048.28  5090.1 1049.11  5100.6 1049.48
  5273.5 1057.47  5292.5 1060.50  5297.9 1059.44  5327.6 1060.92  5445.4 1070.06
#Mann=8,-1,0
  4154.2   0.035       0  4350.6    0.12       0  4364.2   0.035       0
  4786.1    0.07       0  4921.1    0.05       0  4926.3    0.07       0
  5090.1    0.12       0  5100.6   0.035       0
Bank Sta=4921.1,4926.3
Exp/Cntr=0.3,0.1

Type RM Length L Ch R = 1,8526,606,606,606
BEGIN DESCRIPTION:
Elm Creek_DS 10.0
END DESCRIPTION:
XS GIS Cut Line= 3
      2158715.67     13851494.88      2159432.42     13851399.03
      2159901.66     13851303.52
#Sta/Elev= 30
  4232.7 1060.30  4312.7 1055.86  4363.2 1054.70  4419.5 1052.01  4519.3 1048.55
  4575.7 1046.08  4605.3 1043.49  4648.7 1042.55  4675.9 1040.08  4686.0 1038.38
  4736.5 1041.26  4756.7 1040.75  4837.4 1044.18  4928.2 1043.06  4945.9 1041.37
  4959.7 1042.46  4968.7 1040.75  4976.3 1037.83  4976.7 1037.33  4981.5 1037.83
  4997.7 1042.99  5019.2 1043.16  5070.7 1044.67  5111.5 1047.39  5205.1 1049.26
  5234.0 1053.33  5255.7 1052.21  5295.2 1055.16  5357.1 1061.56  5434.7 1066.25
#Mann=7,-1,0
  4232.7    0.12       0  4419.5   0.035       0  4519.3    0.12       0
  4976.3    0.05       0  4981.5    0.12       0  5019.2   0.035       0
  5357.1    0.12       0
Bank Sta=4976.3,4981.5
Exp/Cntr=0.3,0.1

Type RM Length L Ch R = 1,7920,494,494,494
BEGIN DESCRIPTION:
Elm Creek_DS 9.0
END DESCRIPTION:
XS GIS Cut Line= 3
      2159024.98     13852125.01      2159424.98     13851947.79
      2159824.97     13851525.03
#Sta/Elev= 30
  4562.5 1056.06  4571.4 1055.43  4576.9 1049.19  4600.2 1048.46  4628.7 1045.90
  4646.7 1043.40  4652.2 1043.51  4693.3 1039.16  4774.1 1037.04  4797.4 1035.50
  4839.7 1035.42  4870.6 1034.75  4893.4 1031.40  4893.8 1030.90  4898.6 1031.40
  4924.7 1034.47  4965.8 1032.80  4971.3 1034.09  4978.1 1034.36  5023.2 1033.31
  5078.9 1035.18  5115.0 1035.08  5207.2 1037.17  5249.7 1039.59  5369.9 1041.28
  5398.2 1042.95  5412.3 1045.12  5433.4 1044.99  5557.1 1050.18  5582.0 1051.30
#Mann=8,-1,0
  4562.5   0.035       0  4628.7    0.12       0  4839.7   0.035       0
  4870.6    0.12       0  4893.4    0.05       0  4898.6    0.12       0
  5078.9   0.035       0  5557.1    0.12       0
Bank Sta=4893.4,4898.6
Exp/Cntr=0.3,0.1

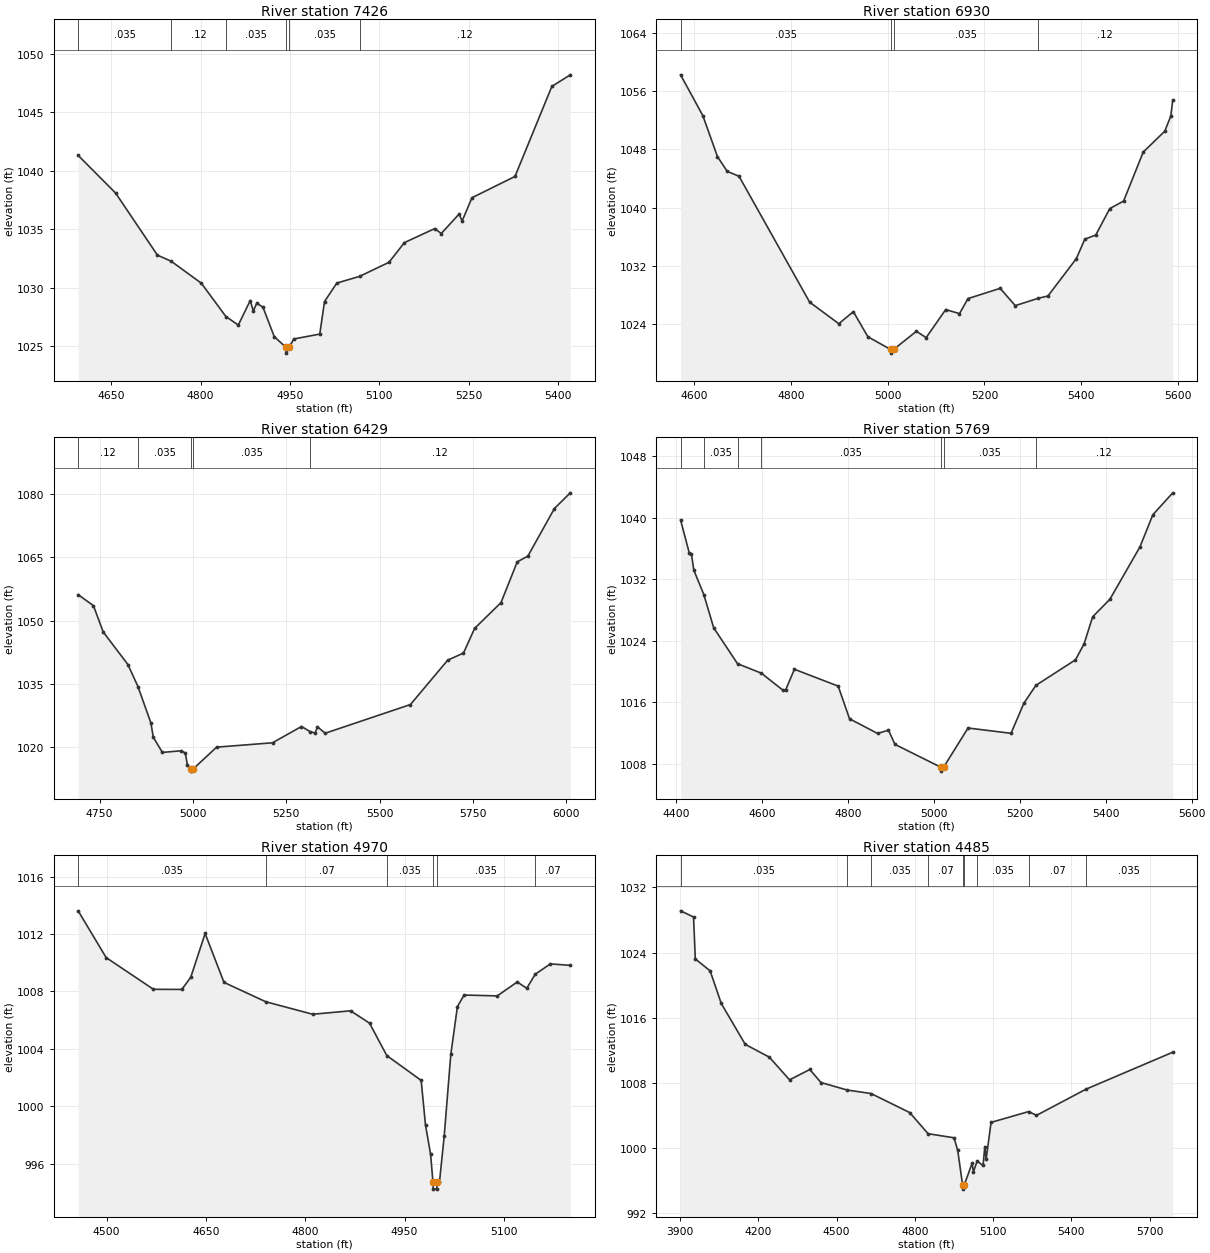
Type RM Length L Ch R = 1,7426,496,496,496
BEGIN DESCRIPTION:
Elm Creek_DS 8.0
END DESCRIPTION:
XS GIS Cut Line= 3
      2159225.03     13852424.99      2159617.27     13852321.35
      2160025.00     13852425.00
#Sta/Elev= 30
  4594.3 1041.32  4657.2 1038.10  4727.4 1032.79  4750.8 1032.26  4801.1 1030.39
  4842.4 1027.54  4863.2 1026.81  4883.3 1028.91  4888.4 1028.01  4894.2 1028.68
  4904.6 1028.34  4923.5 1025.83  4943.0 1024.91  4943.5 1024.41  4948.8 1024.91
  4956.3 1025.62  5000.0 1026.04  5008.0 1028.82  5028.6 1030.40  5067.2 1030.98
  5116.3 1032.18  5142.1 1033.86  5193.0 1035.06  5204.0 1034.64  5233.9 1036.30
  5239.1 1035.72  5255.6 1037.70  5327.8 1039.52  5389.7 1047.22  5420.7 1048.21
#Mann=6,-1,0
  4594.3   0.035       0  4750.8    0.12       0  4842.4   0.035       0
  4943.0   0.035       0  4948.8   0.035       0  5067.2    0.12       0
Bank Sta=4943,4948.8
Exp/Cntr=0.3,0.1

Type RM Length L Ch R = 1,6930,501,501,501
BEGIN DESCRIPTION:
Elm Creek_DS 7.0
END DESCRIPTION:
XS GIS Cut Line= 3
      2159099.04     13852749.28      2159611.62     13852795.12
      2160070.06     13852586.74
#Sta/Elev= 30
  4571.4 1058.28  4617.5 1052.65  4647.7 1047.02  4667.7 1045.00  4692.3 1044.31
  4838.4 1026.98  4898.7 1024.01  4928.8 1025.67  4958.9 1022.21  5006.1 1020.46
  5006.6 1019.96  5012.0 1020.46  5059.3 1022.97  5079.4 1022.09  5119.9 1025.96
  5148.4 1025.40  5166.0 1027.47  5232.5 1028.88  5263.8 1026.50  5310.8 1027.50
  5331.4 1027.83  5390.1 1032.97  5407.7 1035.65  5430.3 1036.22  5459.3 1039.86
  5487.9 1040.90  5528.5 1047.64  5573.1 1050.52  5585.6 1052.61  5589.6 1054.83
#Mann=4,-1,0
  4571.4   0.035       0  5006.1   0.035       0  5012.0   0.035       0
  5310.8    0.12       0
Bank Sta=5006.1,5012
Exp/Cntr=0.3,0.1

Type RM Length L Ch R = 1,6429,660,660,660
BEGIN DESCRIPTION:
Elm Creek_DS 6.0
END DESCRIPTION:
XS GIS Cut Line= 3
      2159174.98     13853174.99      2159474.81     13853243.23
      2160275.00     13852625.00
#Sta/Elev= 30
  4692.5 1056.17  4733.5 1053.55  4759.7 1047.31  4825.8 1039.60  4852.8 1034.36
  4887.4 1025.75  4893.9 1022.34  4918.2 1018.76  4969.4 1019.15  4979.7 1018.58
  4985.1 1015.85  4994.6 1014.82  4995.1 1014.32  5000.5 1014.82  5063.4 1020.00
  5213.3 1021.04  5290.9 1024.90  5314.2 1023.69  5327.4 1023.35  5333.8 1024.81
  5354.6 1023.31  5582.8 1030.11  5682.6 1040.62  5725.0 1042.32  5754.9 1048.18
  5825.5 1054.28  5869.0 1063.94  5897.5 1065.31  5968.6 1076.59  6011.2 1080.31
#Mann=5,-1,0
  4692.5    0.12       0  4852.8   0.035       0  4994.6   0.035       0
  5000.5   0.035       0  5314.2    0.12       0
Bank Sta=4994.6,5000.5
Exp/Cntr=0.3,0.1

Type RM Length L Ch R = 1,5769,799,799,799
BEGIN DESCRIPTION:
Elm Creek_DS 4.0
END DESCRIPTION:
XS GIS Cut Line= 3
      2159094.87     13853745.30      2159569.95     13853836.98
      2160231.29     13853820.34
#Sta/Elev= 30
  4410.6 1039.70  4430.7 1035.44  4435.8 1035.32  4441.3 1033.19  4464.6 1030.01
  4487.7 1025.67  4543.1 1021.01  4598.7 1019.77  4648.3 1017.58  4655.2 1017.60
  4675.5 1020.28  4777.4 1018.09  4803.8 1013.84  4869.0 1011.93  4894.4 1012.36
  4909.5 1010.51  5016.5 1007.53  5017.0 1007.03  5022.6 1007.53  5079.6 1012.64
  5179.6 1011.95  5209.6 1015.87  5237.5 1018.19  5329.6 1021.51  5349.6 1023.58
  5369.6 1027.11  5409.7 1029.39  5479.7 1036.21  5509.7 1040.39  5556.0 1043.24
#Mann=7,-1,0
  4410.6    0.12       0  4464.6   0.035       0  4543.1    0.12       0
  4598.7   0.035       0  5016.5   0.035       0  5022.6   0.035       0
  5237.5    0.12       0
Bank Sta=5016.5,5022.6
Exp/Cntr=0.3,0.1

Type RM Length L Ch R = 1,4970,485,485,485
BEGIN DESCRIPTION:
Elm Creek_DS 3.0
END DESCRIPTION:
XS GIS Cut Line= 3
      2159275.02     13854175.02      2159625.15     13854590.06
      2159824.98     13854575.00
#Sta/Elev= 30
  4457.0 1013.62  4499.3 1010.36  4570.7 1008.15  4613.6 1008.14  4627.1 1008.99
  4648.8 1012.04  4677.3 1008.63  4740.5 1007.28  4811.3 1006.41  4868.5 1006.65
  4897.1 1005.79  4923.2 1003.53  4975.1 1001.80  4981.7  998.67  4989.4  996.64
  4992.9  994.72  4993.4  994.22  4998.6  994.22  4999.1  994.72  5002.8  994.72
  5009.9  997.91  5019.9 1003.62  5029.9 1006.95  5040.0 1007.75  5090.1 1007.69
  5120.2 1008.66  5134.6 1008.22  5147.4 1009.20  5170.3 1009.92  5200.4 1009.82
#Mann=6,-1,0
  4457.0   0.035       0  4740.5    0.07       0  4923.2   0.035       0
  4992.9   0.035       0  4999.1   0.035       0  5147.4    0.07       0
Bank Sta=4992.9,4999.1
Exp/Cntr=0.3,0.1

Type RM Length L Ch R = 1,4485,498,498,498
BEGIN DESCRIPTION:
Elm Creek_DS 2.0
END DESCRIPTION:
XS GIS Cut Line= 3
      2158675.02     13854175.02      2159405.17     13854995.07
      2160175.01     13854825.00
#Sta/Elev= 30
  3902.0 1029.12  3951.7 1028.36  3958.4 1023.22  4015.3 1021.75  4057.9 1017.75
  4149.9 1012.73  4241.9 1011.17  4319.6 1008.38  4397.4 1009.65  4440.0 1008.05
  4540.5 1007.13  4632.2 1006.70  4780.3 1004.36  4850.7 1001.77  4950.1 1001.27
  4964.3  999.71  4982.9  995.47  4983.4  994.97  4989.1  995.47  5019.3  998.13
  5024.5  997.12  5038.7  998.40  5061.3  997.87  5068.1 1000.19  5073.2  998.65
  5092.0 1003.16  5236.4 1004.49  5266.1 1004.02  5456.3 1007.24  5788.4 1011.77
#Mann=9,-1,0
  3902.0   0.035       0  4540.5    0.07       0  4632.2   0.035       0
  4850.7    0.07       0  4982.9    0.05       0  4989.1    0.07       0
  5038.7   0.035       0  5236.4    0.07       0  5456.3   0.035       0
Bank Sta=4982.9,4989.1
Exp/Cntr=0.3,0.1