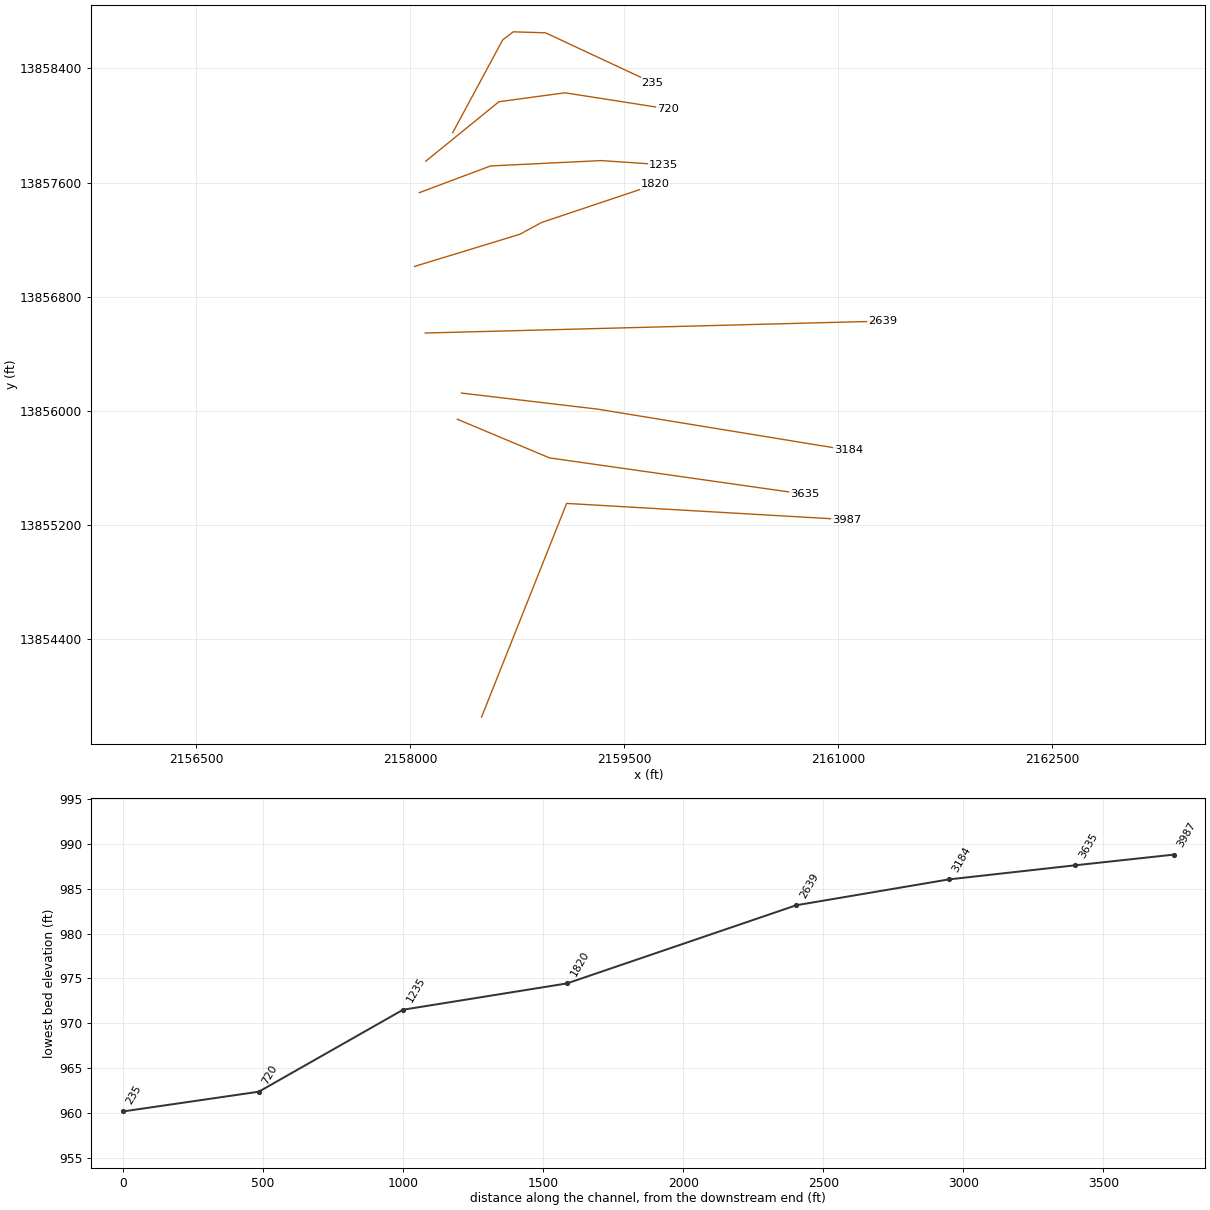
HEC-RAS study Elm Creek.prj: Elm Creek Base Level Engineering

--- Elm Creek.g01 (geometry) --- (continued)

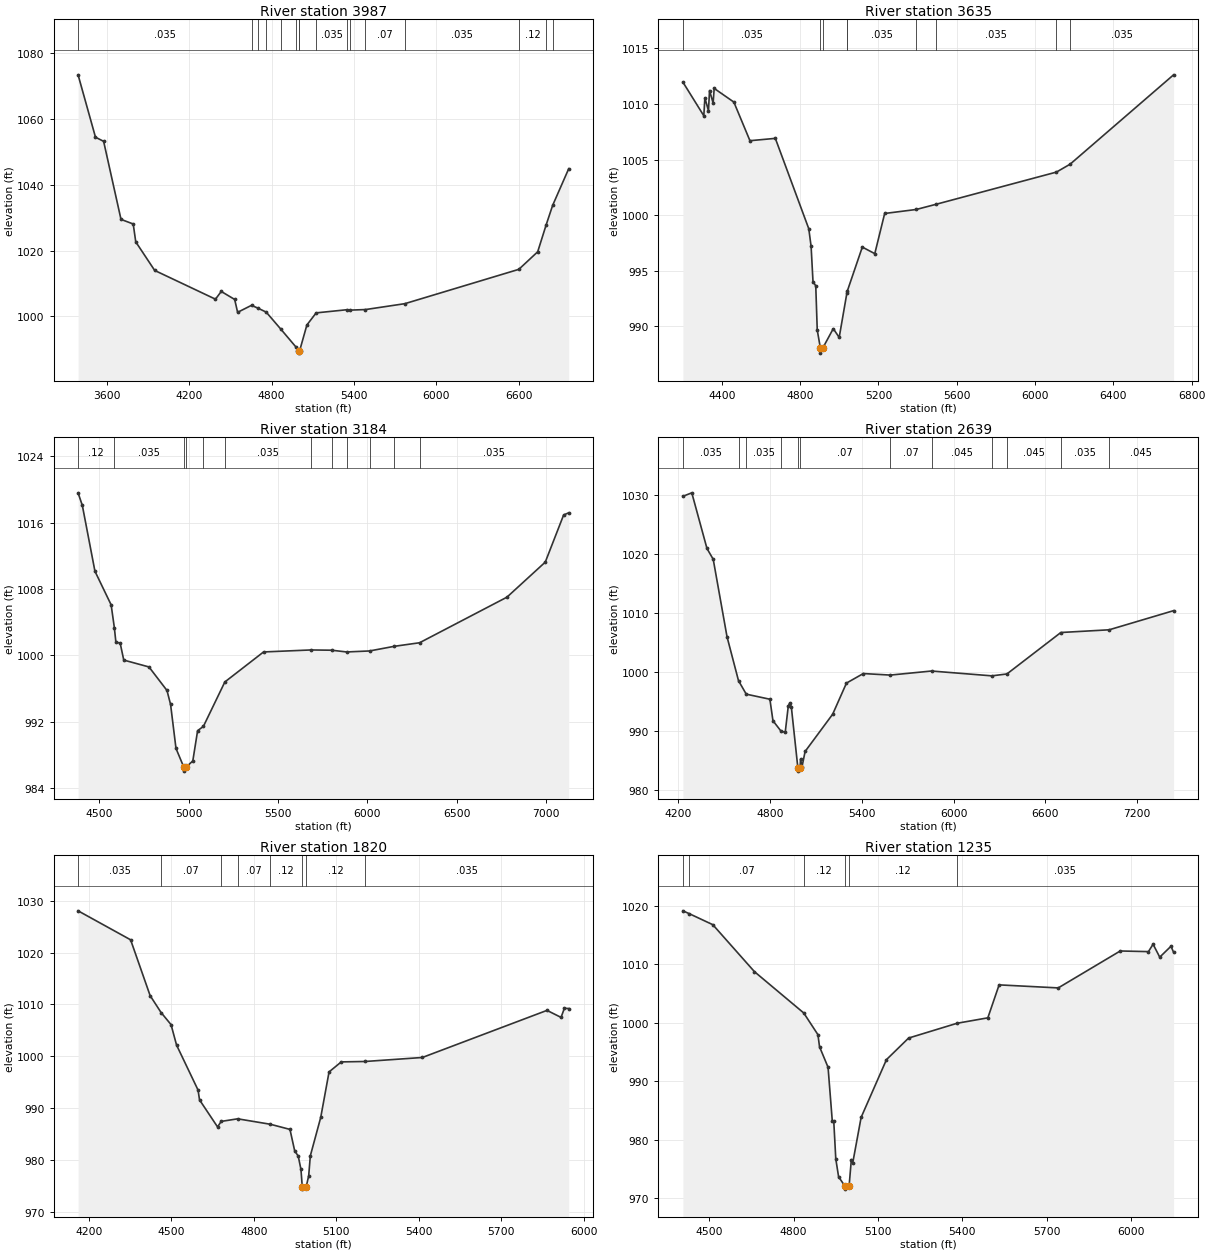
Type RM Length L Ch R = 1,3987,352,352,352
BEGIN DESCRIPTION:
Elm Creek_DS 1.0
END DESCRIPTION:
XS GIS Cut Line= 3
      2158502.11     13853854.24      2159098.31     13855351.61
      2161060.92     13855237.92
#Sta/Elev= 30
  3388.3 1073.49  3515.3 1054.50  3574.6 1053.25  3701.3 1029.50  3790.4 1028.09
  3808.9 1022.65  3946.9 1013.96  4390.1 1005.21  4432.3 1007.56  4530.1 1005.13
  4551.6 1001.21  4652.9 1003.34  4702.3 1002.43  4760.1 1001.27  4867.3  996.06
  4976.2  990.69  4996.0  989.29  4996.5  988.79  5002.3  989.29  5056.8  997.36
  5124.3 1001.04  5349.0 1002.00  5372.7 1001.88  5484.0 1002.05  5770.8 1003.84
  6602.1 1014.29  6739.6 1019.63  6802.2 1027.93  6848.8 1033.77  6965.9 1044.92
#Mann=16,-1,0
  3388.3   0.035       0  4652.9    0.07       0  4702.3   0.035       0
  4760.1    0.07       0  4867.3   0.035       0  4976.2    0.07       0
  4996.0    0.05       0  5002.3    0.07       0  5124.3   0.035       0
  5349.0    0.07       0  5372.7   0.035       0  5484.0    0.07       0
  5770.8   0.035       0  6602.1    0.12       0  6802.2    0.07       0
  6848.8    0.12       0
Bank Sta=4996,5002.3
Exp/Cntr=0.3,0.1

Type RM Length L Ch R = 1,3635,451,451,451
BEGIN DESCRIPTION:
Elm Creek_DS 0.5
END DESCRIPTION:
XS GIS Cut Line= 3
      2158332.25     13855941.52      2158978.17     13855670.65
      2160765.97     13855416.44
#Sta/Elev= 30
  4201.5 1011.95  4308.2 1008.93  4313.6 1010.54  4332.0 1009.39  4337.4 1011.20
  4355.7 1010.08  4361.2 1011.39  4461.7 1010.16  4543.8 1006.69  4673.5 1006.90
  4844.3  998.78  4856.2  997.20  4865.9  994.02  4880.0  993.65  4887.6  989.67
  4903.2  988.10  4903.7  987.60  4917.2  988.10  4969.4  989.80  4999.7  989.01
  5038.7  992.97  5041.6  993.20  5117.8  997.13  5181.5  996.54  5232.0 1000.15
  5393.5 1000.51  5493.4 1000.97  6109.4 1003.87  6179.3 1004.58  6707.7 1012.61
#Mann=9,-1,0
  4201.5   0.035       0  4903.2   0.035       0  4917.2   0.035       0
  5038.7    0.07       0  5041.6   0.035       0  5393.5    0.07       0
  5493.4   0.035       0  6109.4   0.045       0  6179.3   0.035       0
Bank Sta=4903.2,4917.2
Exp/Cntr=0.3,0.1

Type RM Length L Ch R = 1,3184,545,545,545
BEGIN DESCRIPTION:
Elm Creek_DS 0.4
END DESCRIPTION:
XS GIS Cut Line= 3
      2158361.35     13856124.91      2159315.73     13856012.38
      2161074.38     13855724.83
#Sta/Elev= 30
  4382.2 1019.61  4406.0 1018.09  4476.5 1010.15  4567.1 1006.09  4584.9 1003.36
  4593.6 1001.60  4617.5 1001.48  4637.6  999.43  4778.6  998.60  4879.3  995.76
  4899.4  994.07  4929.6  988.77  4972.9  986.53  4973.4  986.03  4987.0  986.53
  5023.6  987.26  5050.5  990.91  5082.9  991.43  5202.8  996.79  5419.2 1000.41
  5683.0 1000.65  5799.2 1000.62  5883.7 1000.41  6011.7 1000.53  6150.1 1001.09
  6291.4 1001.52  6779.8 1007.02  6994.1 1011.25  7096.8 1016.94  7125.2 1017.20
#Mann=12,-1,0
  4382.2    0.12       0  4584.9   0.035       0  4972.9   0.035       0
  4987.0   0.035       0  5082.9    0.07       0  5202.8   0.035       0
  5683.0    0.07       0  5799.2   0.035       0  5883.7   0.045       0
  6011.7   0.035       0  6150.1   0.045       0  6291.4   0.035       0
Bank Sta=4972.9,4987
Exp/Cntr=0.3,0.1

Type RM Length L Ch R = 1,2639,819,819,819
BEGIN DESCRIPTION:
Elm Creek_DS 0.3
END DESCRIPTION:
XS GIS Cut Line= 2
      2158107.15     13856545.81      2161310.96     13856629.14
#Sta/Elev= 30
  4231.9 1029.82  4289.8 1030.41  4388.9 1020.96  4429.8 1019.12  4519.9 1005.97
  4594.9  998.51  4645.5  996.22  4799.9  995.36  4820.0  991.71  4870.8  990.00
  4900.0  989.72  4920.0  994.19  4930.0  994.73  4940.0  994.06  4982.9  983.65
  4983.4  983.15  4997.1  983.65  5000.0  985.18  5010.0  983.92  5030.0  986.49
  5210.1  992.82  5300.1  998.10  5410.2  999.72  5586.6  999.46  5855.7 1000.15
  6249.7  999.33  6348.2  999.65  6700.4 1006.69  7016.0 1007.15  7436.8 1010.40
#Mann=12,-1,0
  4231.9   0.035       0  4594.9    0.12       0  4645.5   0.035       0
  4870.8    0.07       0  4982.9   0.035       0  4997.1    0.07       0
  5586.6    0.07       0  5855.7   0.045       0  6249.7   0.035       0
  6348.2   0.045       0  6700.4   0.035       0  7016.0   0.045       0
Bank Sta=4982.9,4997.1
Exp/Cntr=0.3,0.1

Type RM Length L Ch R = 1,1820,585,585,585
BEGIN DESCRIPTION:
Elm Creek_DS 0.2
END DESCRIPTION:
XS GIS Cut Line= 4
      2158032.12     13857012.55      2158769.80     13857237.61
      2158924.00     13857320.96      2159719.97     13857587.67
#Sta/Elev= 30
  4160.0 1028.03  4351.2 1022.45  4422.3 1011.70  4462.1 1008.45  4498.4 1006.12
  4518.5 1002.18  4596.8  993.51  4602.1  991.63  4667.7  986.42  4681.0  987.48
  4740.9  987.98  4860.1  986.93  4931.3  985.94  4948.5  981.81  4961.4  980.80
  4971.3  978.24  4976.0  974.94  4976.5  974.44  4990.6  974.94  4999.5  977.02
  5005.4  980.85  5043.3  988.25  5073.6  997.01  5118.1  998.94  5205.1  999.02
  5413.2  999.79  5866.9 1008.86  5918.1 1007.51  5930.2 1009.26  5946.0 1009.22
#Mann=8,-1,0
  4160.0   0.035       0  4462.1    0.07       0  4681.0   0.035       0
  4740.9    0.07       0  4860.1    0.12       0  4976.0    0.05       0
  4990.6    0.12       0  5205.1   0.035       0
Bank Sta=4976,4990.6
Exp/Cntr=0.3,0.1

Type RM Length L Ch R = 1,1235,515,515,515
BEGIN DESCRIPTION:
Elm Creek_DS 0.15
END DESCRIPTION:
XS GIS Cut Line= 4
      2158065.52     13857529.33      2158565.60     13857716.86
      2159340.74     13857754.37      2159774.13     13857725.20
#Sta/Elev= 30
  4406.4 1019.13  4428.1 1018.66  4512.6 1016.76  4660.7 1008.72  4836.0 1001.65
  4886.4  997.94  4892.1  995.87  4922.4  992.36  4937.5  983.12  4942.7  983.12
  4949.9  976.68  4959.9  973.62  4982.6  972.01  4983.1  971.51  4997.2  972.01
  5005.2  976.56  5010.2  976.01  5040.0  983.79  5130.1  993.67  5208.8  997.36
  5381.1  999.89  5490.5 1000.82  5530.6 1006.46  5740.8 1005.94  5961.3 1012.26
  6061.6 1012.15  6078.0 1013.42  6101.7 1011.20  6141.7 1013.07  6150.9 1012.04
#Mann=6,-1,0
  4406.4   0.035       0  4428.1    0.07       0  4836.0    0.12       0
  4982.6    0.05       0  4997.2    0.12       0  5381.1   0.035       0
Bank Sta=4982.6,4997.2
Exp/Cntr=0.3,0.1

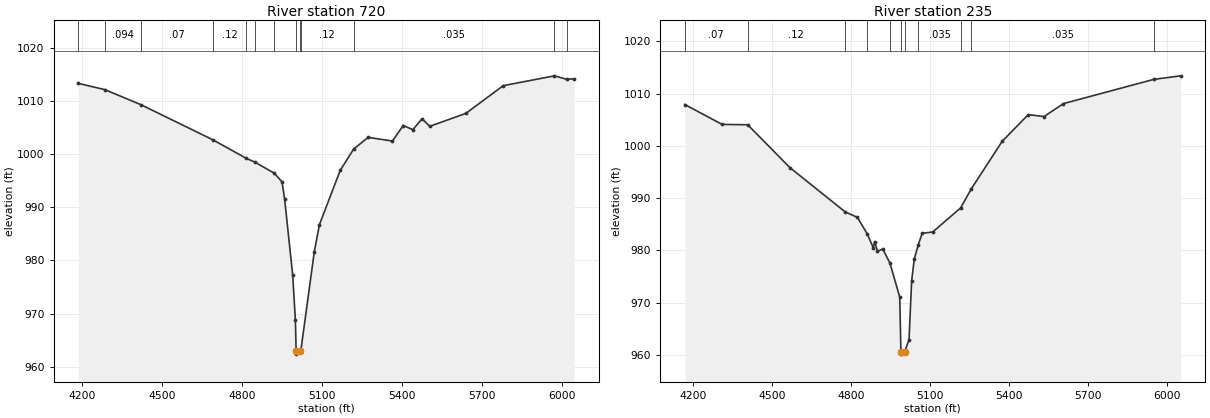
Type RM Length L Ch R = 1,720,485,485,485
BEGIN DESCRIPTION:
Elm Creek_DS 0.1
END DESCRIPTION:
XS GIS Cut Line= 4
      2158111.36     13857750.21      2158623.94     13858166.94
      2159086.53     13858229.46      2159807.50     13858116.93
#Sta/Elev= 30
  4186.9 1013.28  4286.5 1012.10  4420.6 1009.29  4691.6 1002.65  4815.5  999.20
  4848.4  998.47  4920.9  996.39  4949.8  994.77  4959.6  991.53  4989.8  977.23
  4999.9  968.76  5002.7  962.88  5003.2  962.38  5017.4  962.88  5020.0  962.91
  5070.6  981.58  5090.0  986.73  5167.7  996.91  5218.0 1000.93  5272.4 1003.13
  5363.4 1002.44  5403.8 1005.36  5439.9 1004.58  5474.7 1006.64  5502.7 1005.20
  5638.4 1007.64  5778.3 1012.85  5970.3 1014.70  6016.1 1014.04  6044.0 1014.14
#Mann=13,-1,0
  4186.9   0.035       0  4286.5   0.094       0  4420.6    0.07       0
  4691.6    0.12       0  4815.5    0.12       0  4848.4    0.12       0
  4920.9    0.12       0  5002.7    0.05       0  5017.4    0.12       0
  5020.0    0.12       0  5218.0   0.035       0  5970.3   0.045       0
  6016.1   0.035       0
Bank Sta=5002.7,5017.4
Exp/Cntr=0.3,0.1

Type RM Length L Ch R = 1,235,0,0,0
BEGIN DESCRIPTION:
Elm Creek_DS 0.0
END DESCRIPTION:
XS GIS Cut Line= 5
      2158299.99     13857949.99      2158650.00     13858600.00
      2158724.36     13858656.76      2158950.00     13858650.00
      2159700.01     13858300.00
#Sta/Elev= 30
  4168.2 1007.91  4310.2 1004.11  4407.5 1004.04  4567.4  995.86  4777.3  987.41
  4824.5  986.32  4861.8  983.18  4884.6  980.56  4890.2  981.65  4900.8  979.85
  4921.0  980.28  4948.1  977.59  4985.4  971.10  4989.9  960.68  4990.4  960.18
  5004.6  960.68  5020.7  962.92  5030.7  974.18  5040.7  978.38  5056.4  981.14
  5070.7  983.29  5110.7  983.53  5216.9  988.14  5257.0  991.74  5374.7 1000.86
  5474.0 1005.98  5533.9 1005.61  5608.0 1008.09  5952.0 1012.73  6053.4 1013.40
#Mann=11,-1,0
  4168.2    0.07       0  4407.5    0.12       0  4777.3    0.12       0
  4861.8   0.033       0  4948.1    0.12       0  4989.9    0.05       0
  5004.6    0.12       0  5056.4   0.035       0  5216.9    0.12       0
  5257.0   0.035       0  5952.0   0.045       0
Bank Sta=4989.9,5004.6
Exp/Cntr=0.3,0.1

Chan Stop Cuts=-1