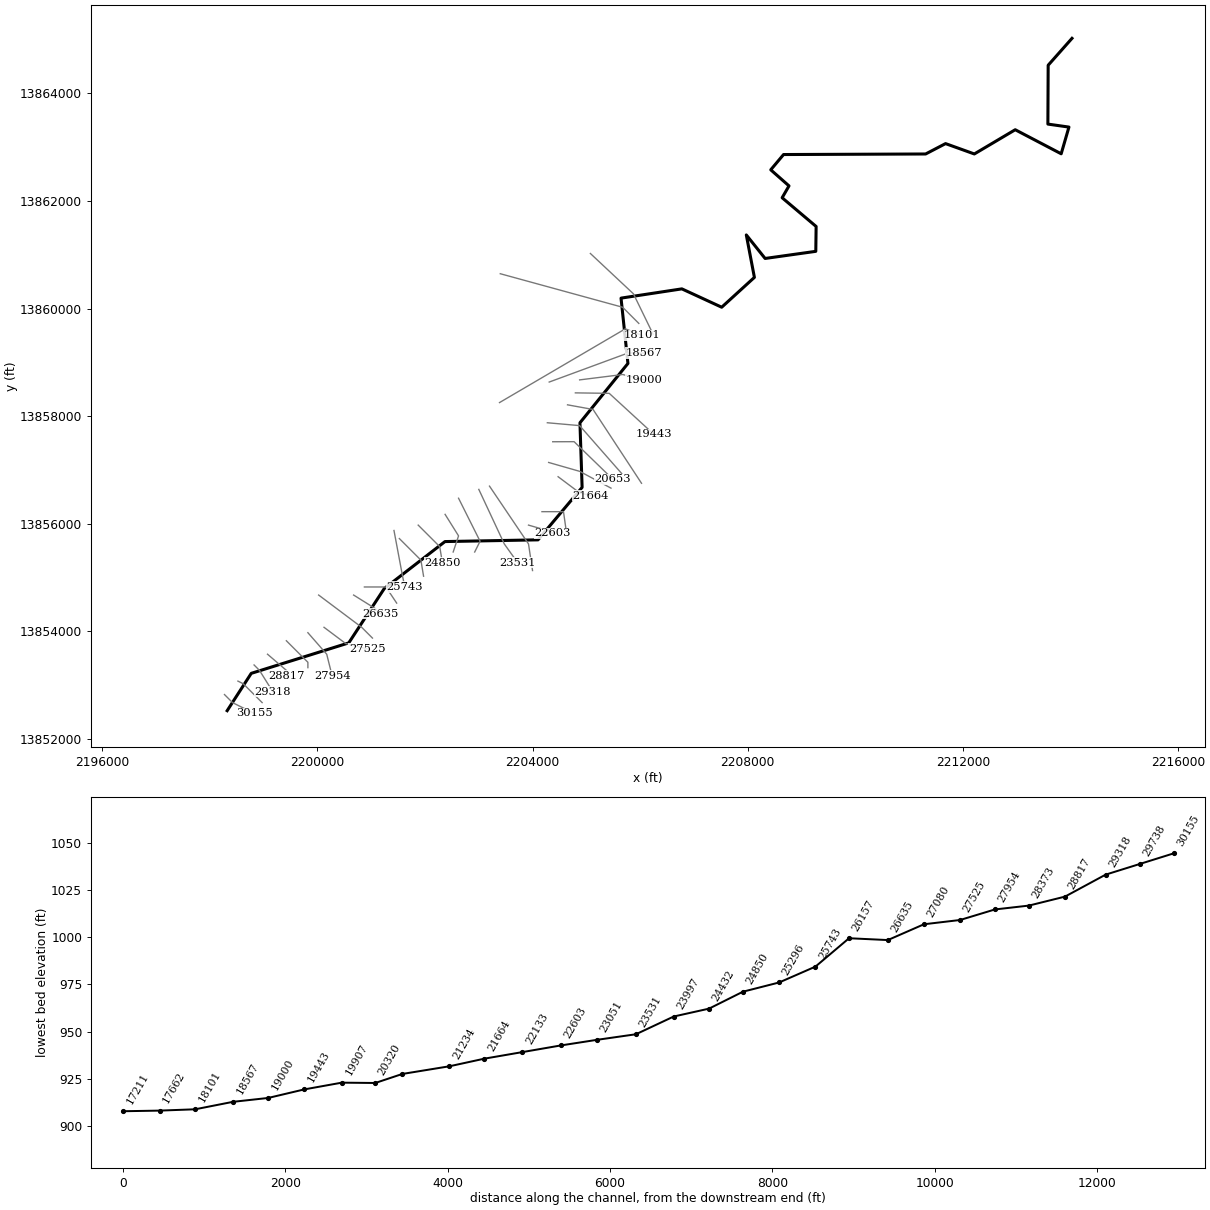
--- Guadalupe Tributary 36.prj (project) ---

Proj Title=Guadalupe Tributary 36 Base Level Engineering
Current Plan=p01
Default Exp/Contr=0.3,0.1
English Units
Geom File=g01
Flow File=f01
Plan File=p01
BEGIN DESCRIPTION:
Guadalupe Tributary 36
END DESCRIPTION:

--- Guadalupe Tributary 36.p01 (plan) ---

Plan Title=Multiple Run
Short Identifier=Multiple
Geom File=g01
Flow File=f01
Subcritical Flow
K Sum by GR= 0
Std Step Tol= 0.01
Critical Tol= 0.01
Num of Std Step Trials= 20
Max Error Tol= 0.3
Flow Tol Ratio= 0.001
Split Flow NTrial= 30
Split Flow Tol= 0.02
Split Flow Ratio= 0.02
Log Output Level= 0
Friction Slope Method= 1
Unsteady Friction Slope Method= 2
Unsteady Bridges Friction Slope Method= 1
Parabolic Critical Depth
Global Vel Dist=  1 , 1 , 1
Global Log Level= 0
CheckData=True
Encroach Param= -1, 0, 0, 0
BEGIN DESCRIPTION:
Multiple Run
END DESCRIPTION:

--- Guadalupe Tributary 36.f01 (steady flow) ---

Flow Title=Multiple
Number of Profiles=7
Profile Names=10-year,25-year,50-year,1pct_min,100-year,1pct_plu,500-year
River Rch & RM= Guadalupe Tribut,Reach-1,30155
    2035    3575    5092    3510    7003   13973   13108
River Rch & RM= Guadalupe Tribut,Reach-1,23531
    2495    4441    6381    4433    8844   17646   16825
River Rch & RM= Guadalupe Tribut,Reach-1,21664
    3046    5441    7835    5451   10876   21700   20746
River Rch & RM= Guadalupe Tribut,Reach-1,17211
    3554    6387    9233    6444   12858   25655   24692
River Rch & RM= Guadalupe Tribut,Reach-1,14936
    3799    6829    9873    6889   13744   27424   26379
River Rch & RM= Guadalupe Tribut,Reach-1,11793
    3970    7109   10250    7128   14222   28376   27113
Boundary for River Rch & Prof#=Guadalupe Tribut,Reach-1,1
Up Type=0
Dn Type=3
Dn Slope=0.005
Boundary for River Rch & Prof#=Guadalupe Tribut,Reach-1,2
Up Type=0
Dn Type=3
Dn Slope=0.005
Boundary for River Rch & Prof#=Guadalupe Tribut,Reach-1,3
Up Type=0
Dn Type=3
Dn Slope=0.005
Boundary for River Rch & Prof#=Guadalupe Tribut,Reach-1,4
Up Type=0
Dn Type=3
Dn Slope=0.005
Boundary for River Rch & Prof#=Guadalupe Tribut,Reach-1,5
Up Type=0
Dn Type=3
Dn Slope=0.005
Boundary for River Rch & Prof#=Guadalupe Tribut,Reach-1,6
Up Type=0
Dn Type=3
Dn Slope=0.005
Boundary for River Rch & Prof#=Guadalupe Tribut,Reach-1,7
Up Type=0
Dn Type=3
Dn Slope=0.005

--- Guadalupe Tributary 36.g01 (geometry) ---

Geom Title=Existing Conditions

River Reach=Guadalupe Tribut,Reach-1
Reach XY= 30
      2198325.00     13852525.00      2198772.69     13853219.18
      2200584.79     13853785.52      2201244.54     13854795.51
      2202372.70     13855669.17      2204101.87     13855701.18
      2204921.26     13856676.56      2204880.83     13857877.30
      2205772.65     13858980.52      2205644.41     13860195.13
      2206774.90     13860367.21      2207515.13     13860025.88
      2208122.84     13860580.45      2207972.42     13861370.05
      2208321.83     13860932.51      2209263.77     13861064.98
      2209269.91     13861527.30      2208638.27     13862061.31
      2208765.89     13862281.73      2208426.67     13862580.67
      2208664.77     13862864.65      2211305.02     13862874.96
      2211675.00     13863067.92      2212209.84     13862875.38
      2212969.92     13863325.86      2213823.98     13862878.45
      2213968.12     13863375.04      2213576.69     13863430.63
      2213582.08     13864525.03      2214025.00     13865025.00

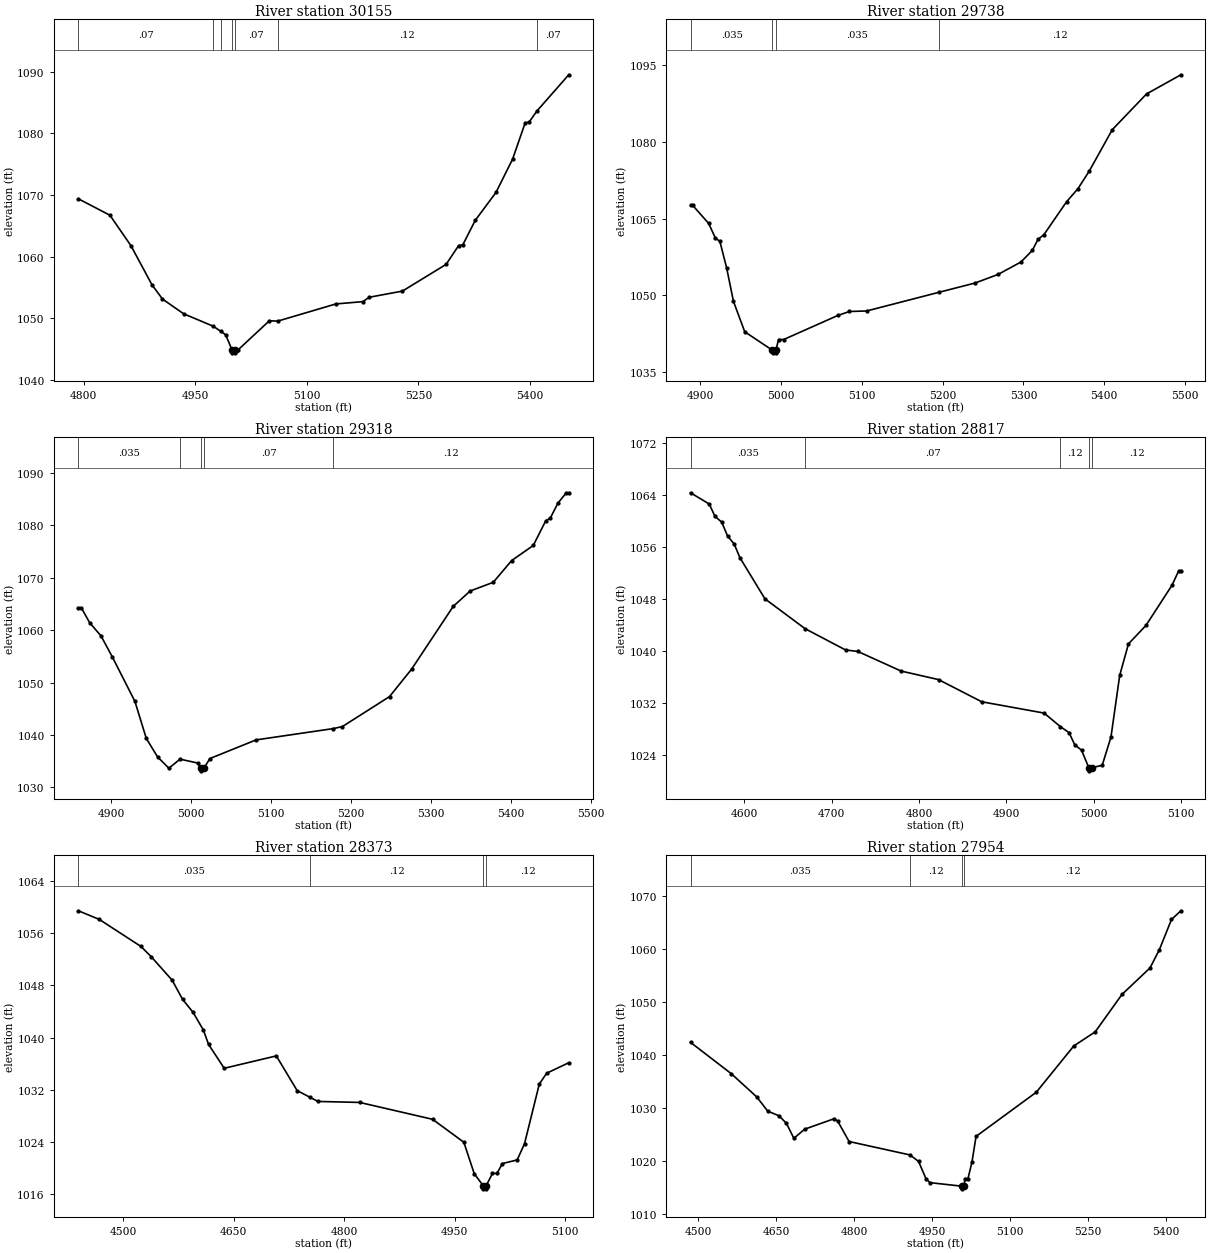
Type RM Length L Ch R = 1,30155,417,417,417
BEGIN DESCRIPTION:
Guadalupe Tributary 36 47.0
END DESCRIPTION:
XS GIS Cut Line= 3
      2198275.03     13852824.97      2198425.00     13852675.00
      2198824.99     13852475.00
#Sta/Elev= 30
  4792.9 1069.38  4835.3 1066.72  4863.6 1061.78  4891.9 1055.43  4906.0 1053.13
  4934.3 1050.75  4974.3 1048.72  4984.6 1047.88  4990.9 1047.34  4999.4 1044.91
  4999.7 1044.41  5003.3 1044.41  5003.5 1044.91  5007.8 1044.91  5049.7 1049.61
  5060.8 1049.55  5139.2 1052.34  5175.5 1052.71  5183.9 1053.42  5228.6 1054.42
  5287.3 1058.75  5304.1 1061.79  5309.7 1061.90  5326.4 1065.87  5354.4 1070.42
  5376.7 1075.81  5393.5 1081.65  5399.1 1081.85  5409.3 1083.60  5452.2 1089.49
#Mann=7,-1,0
  4792.9    0.07       0  4974.3   0.035       0  4984.6    0.07       0
  4999.4    0.05       0  5003.5    0.07       0  5060.8    0.12       0
  5409.3    0.07       0
Bank Sta=4999.4,5003.5
Exp/Cntr=0.3,0.1

Type RM Length L Ch R = 1,29738,420,420,420
BEGIN DESCRIPTION:
Guadalupe Tributary 36 46.0
END DESCRIPTION:
XS GIS Cut Line= 3
      2198525.01     13853075.00      2198625.00     13853025.00
      2198975.02     13852674.98
#Sta/Elev= 30
  4888.0 1067.56  4890.8 1067.56  4910.4 1064.07  4918.7 1061.22  4924.3 1060.55
  4932.7 1055.37  4941.1 1048.85  4955.1 1042.91  4989.4 1039.30  4989.6 1038.80
  4993.2 1038.80  4993.5 1039.30  4997.0 1041.40  5003.3 1041.40  5070.5 1046.11
  5084.6 1046.87  5105.9 1046.97  5195.5 1050.62  5240.2 1052.43  5268.5 1054.10
  5296.8 1056.52  5310.9 1058.78  5318.0 1060.96  5325.1 1061.82  5353.3 1068.28
  5367.5 1070.86  5381.6 1074.33  5409.9 1082.36  5452.3 1089.33  5494.8 1093.07
#Mann=4,-1,0
  4888.0   0.035       0  4989.4   0.035       0  4993.5   0.035       0
  5195.5    0.12       0
Bank Sta=4989.4,4993.5
Exp/Cntr=0.3,0.1

Type RM Length L Ch R = 1,29318,501,501,501
BEGIN DESCRIPTION:
Guadalupe Tributary 36 45.0
END DESCRIPTION:
XS GIS Cut Line= 3
      2198824.98     13853375.02      2198925.00     13853275.00
      2199175.02     13852874.96
#Sta/Elev= 30
  4859.1 1064.28  4862.7 1064.28  4873.3 1061.40  4887.4 1058.90  4901.6 1054.88
  4929.8 1046.41  4944.0 1039.36  4958.1 1035.82  4972.3 1033.66  4986.2 1035.39
  5008.2 1034.65  5012.0 1033.66  5012.3 1033.16  5016.2 1033.66  5023.5 1035.50
  5081.3 1039.06  5177.5 1041.21  5189.2 1041.60  5248.2 1047.32  5275.9 1052.58
  5327.8 1064.52  5349.0 1067.46  5377.9 1069.12  5400.9 1073.27  5428.0 1076.16
  5443.4 1080.82  5449.3 1081.38  5458.7 1084.21  5469.3 1086.20  5472.3 1086.20
#Mann=5,-1,0
  4859.1   0.035       0  4986.2    0.07       0  5012.0    0.05       0
  5016.2    0.07       0  5177.5    0.12       0
Bank Sta=5012,5016.2
Exp/Cntr=0.3,0.1

Type RM Length L Ch R = 1,28817,444,444,444
BEGIN DESCRIPTION:
Guadalupe Tributary 36 44.0
END DESCRIPTION:
XS GIS Cut Line= 3
      2199074.99     13853575.01      2199425.00     13853275.00
      2199425.00     13853174.99
#Sta/Elev= 30
  4538.6 1064.27  4560.0 1062.54  4566.6 1060.63  4574.3 1059.76  4580.9 1057.64
  4588.6 1056.38  4595.1 1054.29  4623.7 1047.97  4669.6 1043.38  4715.9 1040.11
  4730.1 1039.87  4779.5 1036.86  4822.3 1035.55  4871.7 1032.14  4943.1 1030.40
  4961.7 1028.32  4971.6 1027.40  4978.2 1025.52  4985.9 1024.70  4994.2 1022.02
  4994.5 1021.52  4998.4 1022.02  5009.6 1022.38  5019.6 1026.72  5029.6 1036.20
  5039.6 1041.04  5059.6 1043.87  5089.6 1050.09  5097.1 1052.28  5099.6 1052.28
#Mann=5,-1,0
  4538.6   0.035       0  4669.6    0.07       0  4961.7    0.12       0
  4994.2    0.05       0  4998.4    0.12       0
Bank Sta=4994.2,4998.4
Exp/Cntr=0.3,0.1

Type RM Length L Ch R = 1,28373,419,419,419
BEGIN DESCRIPTION:
Guadalupe Tributary 36 43.0
END DESCRIPTION:
XS GIS Cut Line= 3
      2199424.99     13853825.01      2199825.00     13853425.00
      2199825.00     13853325.00
#Sta/Elev= 30
  4438.9 1059.45  4467.2 1058.13  4523.8 1053.98  4537.9 1052.39  4566.2 1048.80
  4580.3 1045.87  4594.5 1043.88  4608.6 1041.15  4615.7 1038.93  4636.9 1035.28
  4707.6 1037.18  4735.9 1031.86  4753.8 1030.80  4764.2 1030.19  4820.8 1030.04
  4919.8 1027.45  4962.2 1023.93  4976.3 1019.11  4988.3 1017.28  4988.6 1016.78
  4992.3 1016.78  4992.6 1017.28  5001.1 1019.15  5007.1 1019.15  5014.6 1020.66
  5034.6 1021.22  5044.6 1023.71  5064.6 1032.85  5074.6 1034.52  5104.6 1036.13
#Mann=4,-1,0
  4438.9   0.035       0  4753.8    0.12       0  4988.3    0.05       0
  4992.6    0.12       0
Bank Sta=4988.3,4992.6
Exp/Cntr=0.3,0.1

Type RM Length L Ch R = 1,27954,429,429,429
BEGIN DESCRIPTION:
Guadalupe Tributary 36 42.0
END DESCRIPTION:
XS GIS Cut Line= 3
      2199824.97     13853975.04      2200175.00     13853575.00
      2200275.01     13853174.97
#Sta/Elev= 30
  4484.7 1042.37  4563.0 1036.47  4612.4 1032.05  4633.3 1029.39  4655.1 1028.51
  4669.4 1027.08  4683.6 1024.26  4704.5 1025.99  4761.4 1027.97  4768.1 1027.49
  4789.9 1023.66  4907.4 1021.12  4923.7 1019.89  4938.0 1016.62  4945.5 1015.90
  5006.9 1015.23  5007.2 1014.73  5011.3 1015.23  5012.9 1016.66  5018.8 1016.66
  5026.6 1019.88  5034.3 1024.63  5150.3 1032.96  5222.4 1041.69  5263.6 1044.35
  5315.2 1051.41  5369.3 1056.43  5387.3 1059.89  5410.5 1065.56  5428.6 1067.20
#Mann=4,-1,0
  4484.7   0.035       0  4907.4    0.12       0  5006.9    0.05       0
  5011.3    0.12       0
Bank Sta=5006.9,5011.3
Exp/Cntr=0.3,0.1

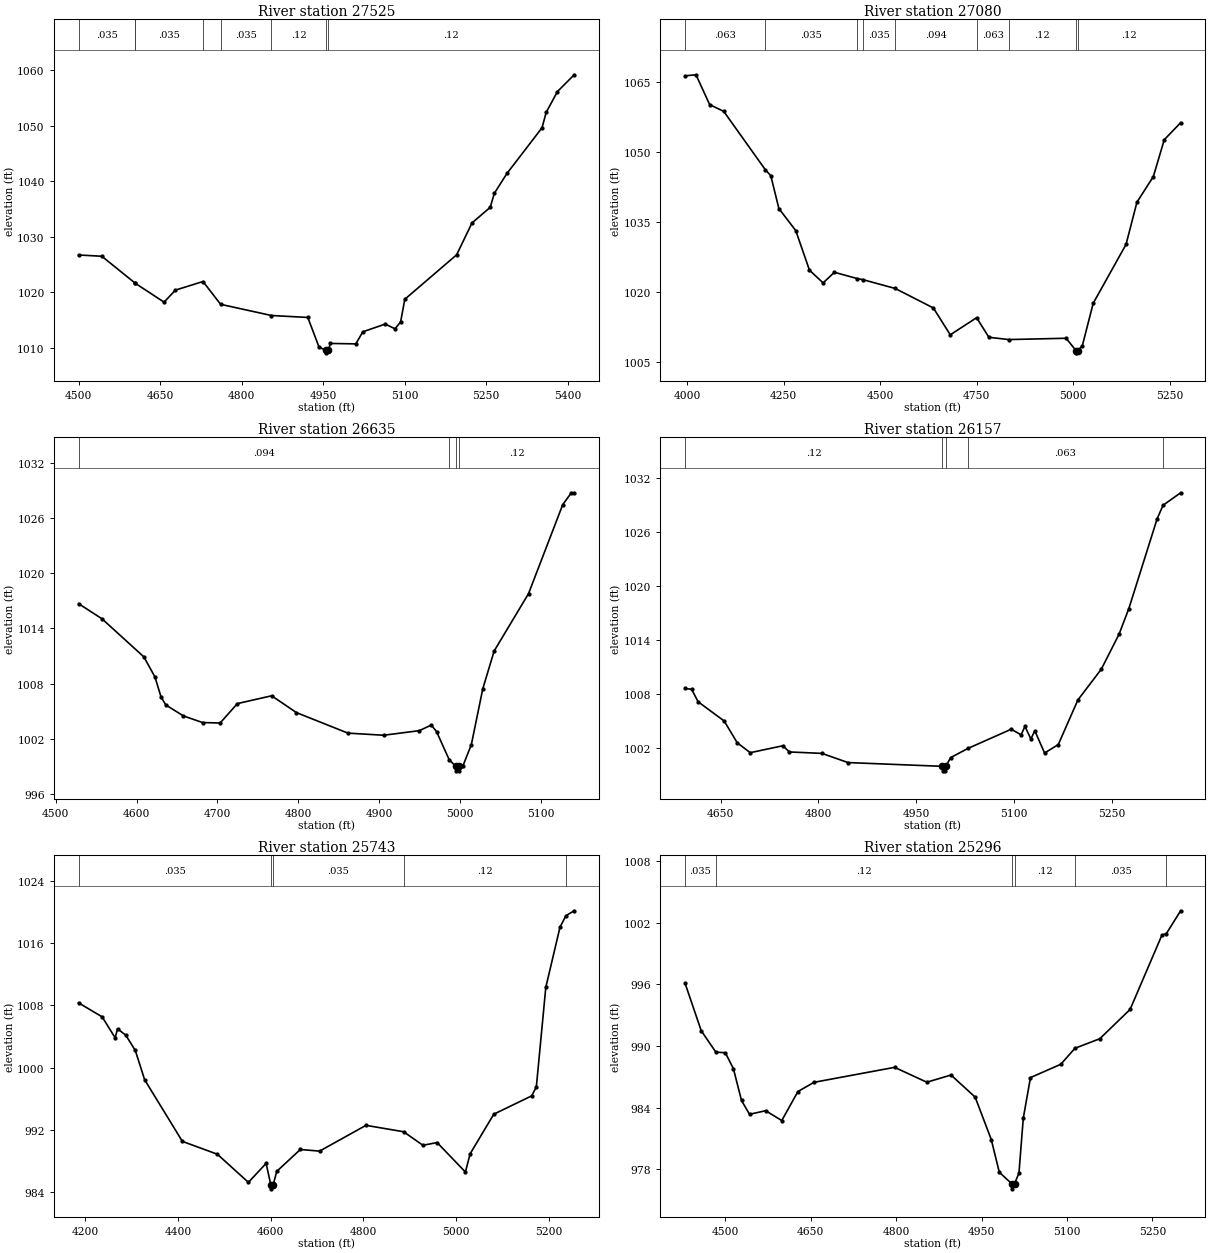
Type RM Length L Ch R = 1,27525,445,445,445
BEGIN DESCRIPTION:
Guadalupe Tributary 36 41.0
END DESCRIPTION:
XS GIS Cut Line= 3
      2200124.98     13854075.01      2200525.00     13853775.00
      2200924.97     13853675.01
#Sta/Elev= 30
  4499.8 1026.74  4542.5 1026.51  4602.8 1021.76  4603.5 1021.69  4657.1 1018.26
  4677.9 1020.42  4728.8 1021.97  4761.2 1017.87  4854.8 1015.86  4921.7 1015.51
  4942.5 1010.15  4954.7 1009.65  4955.1 1009.15  4959.5 1009.65  4963.4 1010.84
  5010.1 1010.76  5023.0 1012.93  5064.2 1014.32  5082.3 1013.47  5092.6 1014.72
  5100.3 1018.78  5195.7 1026.77  5224.0 1032.50  5257.5 1035.30  5265.2 1037.84
  5288.4 1041.40  5352.9 1049.60  5360.6 1052.37  5381.2 1056.10  5412.1 1059.13
#Mann=8,-1,0
  4499.8   0.035       0  4602.8   0.094       0  4603.5   0.035       0
  4728.8   0.063       0  4761.2   0.035       0  4854.8    0.12       0
  4954.7    0.05       0  4959.5    0.12       0
Bank Sta=4954.7,4959.5
Exp/Cntr=0.3,0.1

Type RM Length L Ch R = 1,27080,445,445,445
BEGIN DESCRIPTION:
Guadalupe Tributary 36 40.0
END DESCRIPTION:
XS GIS Cut Line= 3
      2200024.96     13854675.03      2200825.00     13854075.00
      2201025.01     13853874.99
#Sta/Elev= 30
  3994.9 1066.34  4023.1 1066.57  4058.5 1060.16  4094.9 1058.72  4202.7 1046.18
  4216.8 1044.91  4237.7 1037.86  4281.4 1033.13  4316.8 1024.64  4352.2 1021.90
  4381.4 1024.18  4441.0 1022.82  4454.7 1022.61  4538.7 1020.71  4637.7 1016.52
  4681.4 1010.76  4749.6 1014.43  4781.4 1010.23  4832.7 1009.74  4981.4 1010.02
  5006.7 1007.39  5007.0 1006.89  5011.5 1007.39  5023.2 1008.38  5051.5 1017.54
  5136.4 1030.15  5164.7 1039.23  5207.1 1044.71  5235.4 1052.63  5277.8 1056.28
#Mann=9,-1,0
  3994.9   0.063       0  4202.7   0.035       0  4441.0   0.094       0
  4454.7   0.035       0  4538.7   0.094       0  4749.6   0.063       0
  4832.7    0.12       0  5006.7    0.05       0  5011.5    0.12       0
Bank Sta=5006.7,5011.5
Exp/Cntr=0.3,0.1

Type RM Length L Ch R = 1,26635,478,478,478
BEGIN DESCRIPTION:
Guadalupe Tributary 36 39.0
END DESCRIPTION:
XS GIS Cut Line= 3
      2200674.98     13854675.01      2201075.00     13854425.00
      2201174.97     13854325.03
#Sta/Elev= 30
  4528.3 1016.69  4557.2 1015.05  4609.1 1010.90  4622.7 1008.73  4630.3 1006.54
  4636.2 1005.68  4658.0 1004.49  4681.6 1003.77  4703.4 1003.72  4724.7 1005.83
  4767.1 1006.68  4797.8 1004.85  4861.5 1002.62  4905.7 1002.39  4949.9 1002.89
  4964.6 1003.50  4971.1 1002.79  4986.7  999.74  4994.7  999.02  4995.0  998.52
  4999.1  998.52  4999.5  999.02  5003.6  999.02  5014.2 1001.38  5028.3 1007.43
  5042.4 1011.55  5084.9 1017.78  5127.3 1027.47  5137.9 1028.75  5141.4 1028.75
#Mann=4,-1,0
  4528.3   0.094       0  4986.7    0.12       0  4994.7    0.05       0
  4999.5    0.12       0
Bank Sta=4994.7,4999.5
Exp/Cntr=0.3,0.1

Type RM Length L Ch R = 1,26157,414,414,414
BEGIN DESCRIPTION:
Guadalupe Tributary 36 38.0
END DESCRIPTION:
XS GIS Cut Line= 3
      2200875.05     13854825.00      2201275.00     13854825.00
      2201475.00     13854525.01
#Sta/Elev= 30
  4595.5 1008.65  4605.5 1008.56  4615.5 1007.17  4655.5 1005.03  4675.5 1002.61
  4695.5 1001.51  4745.5 1002.28  4755.5 1001.59  4805.5 1001.43  4845.5 1000.41
  4990.5  999.99  4990.9  999.49  4995.1  999.49  4995.5  999.99  5003.0 1000.96
  5029.5 1001.98  5096.1 1004.12  5111.1 1003.49  5117.1 1004.43  5126.2 1003.03
  5132.2 1003.95  5147.2 1001.47  5168.2 1002.41  5198.3 1007.37  5234.3 1010.80
  5261.4 1014.67  5276.4 1017.51  5320.0 1027.53  5329.0 1029.02  5356.0 1030.41
#Mann=5,-1,0
  4595.5    0.12       0  4990.5    0.05       0  4995.5    0.12       0
  5029.5   0.063       0  5329.0    0.12       0
Bank Sta=4990.5,4995.5
Exp/Cntr=0.3,0.1

Type RM Length L Ch R = 1,25743,447,447,447
BEGIN DESCRIPTION:
Guadalupe Tributary 36 37.0
END DESCRIPTION:
XS GIS Cut Line= 3
      2201425.01     13855874.97      2201575.00     13855075.00
      2201625.01     13854824.96
#Sta/Elev= 30
  4185.8 1008.33  4236.6 1006.53  4264.6 1003.84  4269.7 1005.00  4287.5 1004.18
  4307.9 1002.24  4328.2  998.46  4409.6  990.55  4485.1  988.90  4552.0  985.29
  4590.2  987.73  4600.4  984.96  4600.8  984.46  4605.4  984.96  4613.1  986.70
  4664.0  989.51  4705.5  989.30  4805.6  992.61  4886.7  991.79  4928.5  990.05
  4959.0  990.40  5020.1  986.62  5030.3  988.96  5081.3  994.04  5162.9  996.39
  5173.1  997.54  5193.5 1010.32  5224.1 1018.04  5236.9 1019.52  5254.7 1020.15
#Mann=5,-1,0
  4185.8   0.035       0  4600.4    0.05       0  4605.4   0.035       0
  4886.7    0.12       0  5236.9   0.094       0
Bank Sta=4600.4,4605.4
Exp/Cntr=0.3,0.1

Type RM Length L Ch R = 1,25296,446,446,446
BEGIN DESCRIPTION:
Guadalupe Tributary 36 36.0
END DESCRIPTION:
XS GIS Cut Line= 3
      2201525.01     13855724.99      2201925.00     13855325.00
      2201975.00     13855025.01
#Sta/Elev= 30
  4429.6  996.11  4457.9  991.49  4483.5  989.41  4500.3  989.34  4514.4  987.79
  4528.6  984.69  4542.7  983.34  4571.0  983.69  4599.3  982.73  4627.6  985.56
  4655.9  986.46  4797.3  987.92  4853.9  986.47  4896.3  987.17  4938.7  985.02
  4967.0  980.88  4981.1  977.69  5002.9  976.57  5003.3  976.07  5007.9  976.57
  5015.6  977.61  5023.2  982.96  5035.8  986.92  5089.1  988.22  5113.9  989.78
  5157.5  990.71  5210.7  993.57  5266.5 1000.81  5274.4 1000.97  5299.4 1003.19
#Mann=6,-1,0
  4429.6   0.035       0  4483.5    0.12       0  5002.9    0.05       0
  5007.9    0.12       0  5113.9   0.035       0  5274.4    0.12       0
Bank Sta=5002.9,5007.9
Exp/Cntr=0.3,0.1

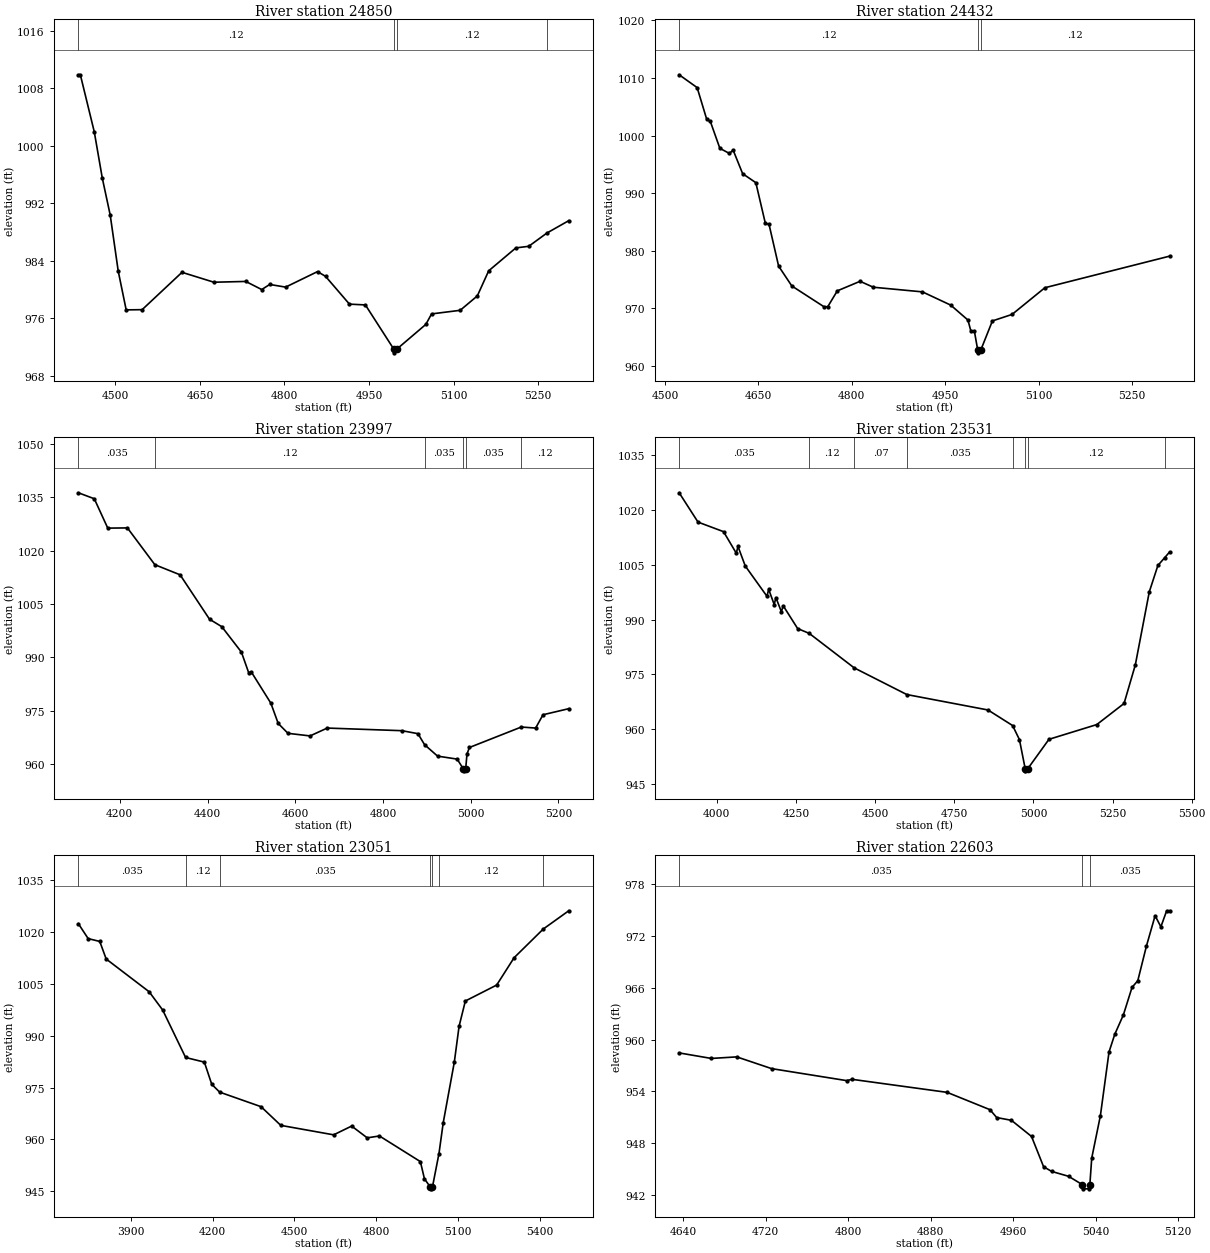
Type RM Length L Ch R = 1,24850,418,418,418
BEGIN DESCRIPTION:
Guadalupe Tributary 36 35.0
END DESCRIPTION:
XS GIS Cut Line= 3
      2201875.03     13855974.97      2202275.00     13855575.00
      2202325.00     13855274.97
#Sta/Elev= 30
  4434.4 1009.89  4437.9 1009.89  4462.6 1001.95  4476.8  995.52  4490.9  990.35
  4505.1  982.55  4519.2  977.16  4547.5  977.19  4618.2  982.39  4674.8  981.01
  4731.3  981.12  4759.6  979.99  4773.8  980.70  4802.0  980.33  4858.6  982.49
  4872.8  981.83  4915.2  977.96  4943.5  977.85  4994.0  971.68  4994.4  971.18
  4999.0  971.68  5050.7  975.14  5060.9  976.60  5111.6  977.10  5142.0  979.10
  5162.2  982.60  5210.4  985.79  5233.2  986.01  5265.5  987.86  5304.2  989.58
#Mann=4,-1,0
  4434.4    0.12       0  4994.0    0.05       0  4999.0    0.12       0
  5265.5   0.035       0
Bank Sta=4994,4999
Exp/Cntr=0.3,0.1

Type RM Length L Ch R = 1,24432,435,435,435
BEGIN DESCRIPTION:
Guadalupe Tributary 36 34.0
END DESCRIPTION:
XS GIS Cut Line= 3
      2202375.01     13856174.98      2202625.00     13855775.00
      2202525.00     13855475.01
#Sta/Elev= 30
  4522.6 1010.56  4551.5 1008.33  4566.8 1002.84  4572.7 1002.45  4588.0  997.77
  4603.4  996.88  4609.3  997.47  4624.6  993.36  4645.8  991.80  4661.1  984.72
  4667.0  984.55  4682.4  977.29  4703.6  973.84  4755.5  970.21  4761.4  970.24
  4776.7  972.99  4813.3  974.65  4834.5  973.62  4913.5  972.81  4958.9  970.51
  4986.6  967.91  4991.3  966.00  4996.9  966.00  5002.3  962.71  5002.7  962.21
  5007.3  962.71  5025.9  967.76  5057.5  968.89  5110.2  973.53  5310.5  979.02
#Mann=3,-1,0
  4522.6    0.12       0  5002.3    0.05       0  5007.3    0.12       0
Bank Sta=5002.3,5007.3
Exp/Cntr=0.3,0.1

Type RM Length L Ch R = 1,23997,466,466,466
BEGIN DESCRIPTION:
Guadalupe Tributary 36 33.0
END DESCRIPTION:
XS GIS Cut Line= 3
      2202625.02     13856474.96      2203025.00     13855675.00
      2202924.99     13855474.99
#Sta/Elev= 30
  4105.6 1036.24  4141.9 1034.56  4172.6 1026.30  4217.4 1026.36  4280.0 1016.01
  4337.5 1013.17  4404.6 1000.68  4432.6  998.58  4477.3  991.43  4494.1  985.56
  4499.7  985.89  4544.4  977.08  4561.2  971.36  4583.5  968.59  4633.8  967.86
  4673.0  970.07  4843.5  969.33  4879.8  968.49  4894.9  965.39  4924.5  962.18
  4969.2  961.34  4983.5  958.54  4983.9  958.04  4988.6  958.54  4991.6  962.78
  4997.2  964.61  5115.4  970.36  5148.1  970.07  5164.9  973.81  5223.6  975.52
#Mann=6,-1,0
  4105.6   0.035       0  4280.0    0.12       0  4894.9   0.035       0
  4983.5   0.035       0  4988.6   0.035       0  5115.4    0.12       0
Bank Sta=4983.5,4988.6
Exp/Cntr=0.3,0.1

Type RM Length L Ch R = 1,23531,480,480,480
BEGIN DESCRIPTION:
Guadalupe Tributary 36 32.0
END DESCRIPTION:
XS GIS Cut Line= 3
      2203001.59     13856638.96      2203475.00     13855625.00
      2203724.97     13855275.04
#Sta/Elev= 30
  3881.0 1024.67  3940.6 1016.65  4021.2 1014.04  4061.4 1008.16  4066.9 1009.99
  4089.8 1004.65  4158.3  996.38  4163.8  998.26  4181.2  994.12  4186.7  995.99
  4204.0  992.13  4209.6  993.79  4255.3  987.54  4292.0  986.22  4434.0  976.79
  4600.1  969.50  4856.6  965.28  4934.4  961.02  4955.9  957.18  4974.3  949.14
  4974.8  948.64  4981.6  949.14  5049.2  957.26  5200.3  961.29  5286.4  967.06
  5322.0  977.60  5366.2  997.60  5393.3 1004.79  5414.9 1006.94  5430.1 1008.46
#Mann=8,-1,0
  3881.0   0.035       0  4292.0    0.12       0  4434.0    0.07       0
  4600.1   0.035       0  4934.4    0.12       0  4974.3    0.05       0
  4981.6    0.12       0  5414.9   0.063       0
Bank Sta=4974.3,4981.6
Exp/Cntr=0.3,0.1

Type RM Length L Ch R = 1,23051,448,448,448
BEGIN DESCRIPTION:
Guadalupe Tributary 36 31.0
END DESCRIPTION:
XS GIS Cut Line= 3
      2203200.03     13856699.96      2203925.00     13855625.00
      2203999.66     13855130.38
#Sta/Elev= 30
  3708.1 1022.48  3744.0 1018.16  3786.5 1017.34  3810.0 1012.25  3967.4 1002.77
  4016.9  997.49  4101.0  983.73  4169.7  982.39  4196.8  975.97  4225.7  973.70
  4377.5  969.48  4449.8  964.07  4643.5  961.33  4709.4  963.87  4766.4  960.46
  4811.3  961.00  4961.2  953.58  4976.2  948.58  4998.0  946.19  4998.5  945.69
  5005.4  946.19  5029.4  955.92  5045.1  964.90  5085.6  982.38  5103.0  992.75
  5126.0 1000.09  5240.8 1004.71  5304.6 1012.62  5411.6 1020.94  5504.9 1026.22
#Mann=7,-1,0
  3708.1   0.035       0  4101.0    0.12       0  4225.7   0.035       0
  4998.0   0.035       0  5005.4   0.035       0  5029.4    0.12       0
  5411.6   0.063       0
Bank Sta=4998,5005.4
Exp/Cntr=0.3,0.1

Type RM Length L Ch R = 1,22603,470,470,470
BEGIN DESCRIPTION:
Guadalupe Tributary 36 30.0
END DESCRIPTION:
XS GIS Cut Line= 3
      2203925.04     13855974.99      2204275.00     13855875.00
      2204375.03     13855824.99
#Sta/Elev= 30
  4636.0  958.45  4667.2  957.81  4691.9  957.99  4725.7  956.63  4798.5  955.24
  4803.7  955.39  4896.0  953.88  4937.6  951.87  4944.1  950.96  4958.4  950.64
  4977.9  948.77  4989.6  945.26  4997.4  944.72  5013.9  944.15  5027.0  943.20
  5027.5  942.70  5034.0  942.70  5034.5  943.20  5036.3  946.26  5044.7  951.17
  5053.1  958.57  5058.7  960.62  5067.0  962.85  5075.4  966.04  5081.0  966.82
  5089.4  970.84  5097.8  974.35  5103.4  973.06  5109.0  974.92  5111.8  974.92
#Mann=3,-1,0
  4636.0   0.035       0  5027.0   0.035       0  5034.5   0.035       0
Bank Sta=5027,5034.5
Exp/Cntr=0.3,0.1

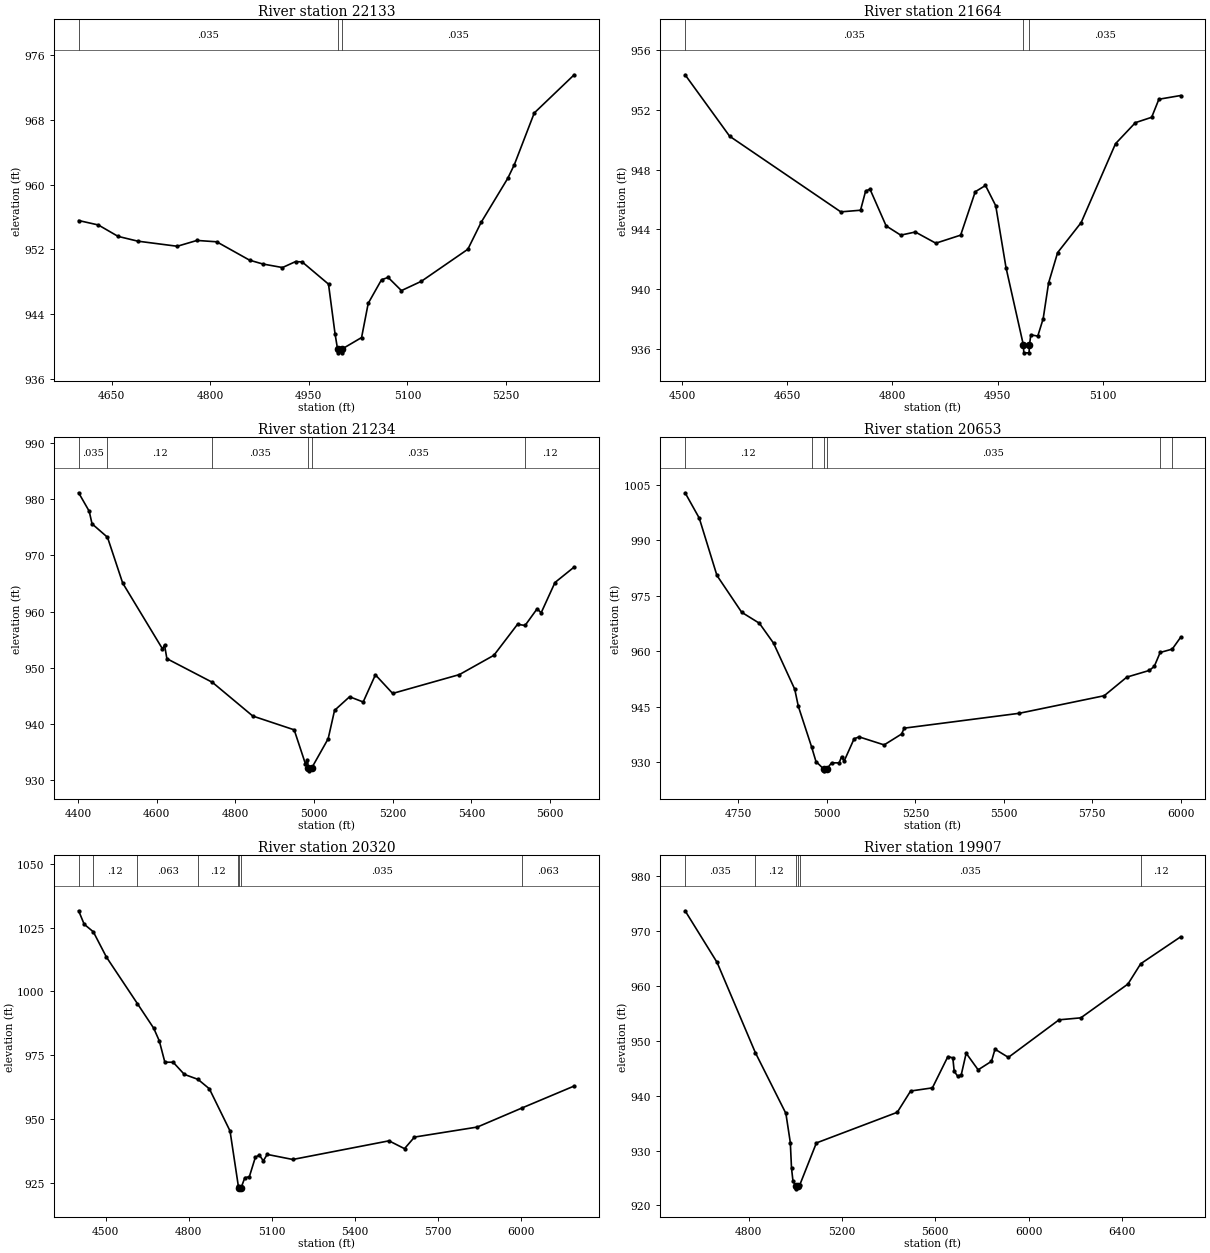
Type RM Length L Ch R = 1,22133,469,469,469
BEGIN DESCRIPTION:
Guadalupe Tributary 36 29.0
END DESCRIPTION:
XS GIS Cut Line= 3
      2204175.00     13856225.00      2204575.00     13856225.00
      2204625.01     13855874.95
#Sta/Elev= 30
  4600.0  955.55  4630.0  955.00  4660.0  953.59  4690.0  953.00  4750.0  952.37
  4780.0  953.09  4810.0  952.92  4860.0  950.65  4880.0  950.18  4910.0  949.74
  4930.0  950.48  4940.0  950.43  4980.0  947.69  4990.0  941.52  4993.7  939.70
  4994.2  939.20  5000.7  939.20  5001.2  939.70  5030.3  941.09  5040.4  945.32
  5060.6  948.23  5070.7  948.52  5090.9  946.89  5121.2  948.04  5191.9  952.00
  5212.1  955.32  5252.5  960.75  5262.6  962.45  5292.9  968.84  5353.6  973.56
#Mann=3,-1,0
  4600.0   0.035       0  4993.7   0.035       0  5001.2   0.035       0
Bank Sta=4993.7,5001.2
Exp/Cntr=0.3,0.1

Type RM Length L Ch R = 1,21664,430,430,430
BEGIN DESCRIPTION:
Guadalupe Tributary 36 28.0
END DESCRIPTION:
XS GIS Cut Line= 3
      2204475.00     13856875.00      2204875.00     13856575.00
      2205075.04     13856524.99
#Sta/Elev= 30
  4504.5  954.36  4568.0  950.24  4726.4  945.17  4754.5  945.28  4761.8  946.57
  4768.0  946.69  4791.0  944.23  4811.8  943.61  4832.6  943.82  4861.8  943.07
  4897.2  943.61  4918.0  946.52  4932.6  946.94  4947.2  945.58  4961.8  941.44
  4986.7  936.22  4987.2  935.72  4994.7  935.72  4995.2  936.22  4997.2  936.93
  5007.1  936.84  5014.8  938.01  5022.5  940.40  5035.4  942.44  5068.9  944.45
  5117.9  949.74  5146.2  951.15  5169.4  951.51  5179.7  952.72  5210.7  952.97
#Mann=3,-1,0
  4504.5   0.035       0  4986.7   0.035       0  4995.2   0.035       0
Bank Sta=4986.7,4995.2
Exp/Cntr=0.3,0.1

Type RM Length L Ch R = 1,21234,581,581,581
BEGIN DESCRIPTION:
Guadalupe Tributary 36 27.0
END DESCRIPTION:
XS GIS Cut Line= 3
      2204299.16     13857139.92      2204875.00     13856975.00
      2205458.03     13856662.48
#Sta/Elev= 30
  4401.1  981.12  4428.0  977.84  4435.2  975.60  4474.5  973.21  4513.1  965.08
  4614.4  953.37  4619.6  954.05  4625.6  951.63  4741.4  947.42  4844.1  941.43
  4949.4  938.98  4978.0  932.93  4983.2  933.68  4985.4  932.19  4985.9  931.69
  4993.9  932.19  5035.8  937.39  5052.1  942.44  5090.3  944.86  5124.9  943.93
  5156.0  948.76  5199.9  945.45  5369.7  948.80  5457.4  952.23  5517.5  957.74
  5536.7  957.53  5567.4  960.50  5577.6  959.78  5612.8  965.17  5661.6  967.92
#Mann=6,-1,0
  4401.1   0.035       0  4474.5    0.12       0  4741.4   0.035       0
  4985.4   0.035       0  4993.9   0.035       0  5536.7    0.12       0
Bank Sta=4985.4,4993.9
Exp/Cntr=0.3,0.1

Type RM Length L Ch R = 1,20653,333,333,333
BEGIN DESCRIPTION:
Guadalupe Tributary 36 26.0
END DESCRIPTION:
XS GIS Cut Line= 3
      2204375.04     13857525.00      2204772.23     13857526.21
      2205492.73     13856827.42
#Sta/Elev= 30
  4599.1 1002.87  4639.1  996.02  4689.1  980.50  4759.1  970.53  4809.1  967.56
  4849.1  962.18  4909.1  949.69  4919.1  945.12  4956.6  934.13  4969.1  930.14
  4990.8  928.12  4991.3  927.62  4999.5  928.12  5013.3  929.79  5034.5  929.77
  5041.6  931.46  5048.6  930.24  5076.9  936.30  5091.0  936.81  5161.8  934.64
  5211.2  937.59  5218.4  939.17  5543.5  943.19  5784.0  947.95  5847.8  952.98
  5911.4  954.79  5925.5  955.89  5942.1  959.65  5976.2  960.56  6000.0  963.76
#Mann=6,-1,0
  4599.1    0.12       0  4956.6   0.035       0  4990.8   0.035       0
  4999.5   0.035       0  5942.1   0.063       0  5976.2    0.12       0
Bank Sta=4990.8,4999.5
Exp/Cntr=0.3,0.1

Type RM Length L Ch R = 1,20320,413,413,413
BEGIN DESCRIPTION:
Guadalupe Tributary 36 25.0
END DESCRIPTION:
XS GIS Cut Line= 3
      2204275.09     13857878.07      2204875.00     13857825.00
      2205657.08     13856933.60
#Sta/Elev= 30
  4402.6 1031.56  4422.6 1026.30  4455.6 1023.34  4502.9 1013.45  4614.4  995.30
  4673.6  985.63  4693.6  980.71  4713.7  972.37  4743.8  972.33  4784.0  967.59
  4833.3  965.64  4874.3  961.96  4948.9  945.47  4978.6  924.11  4980.4  923.34
  4980.9  922.84  4989.1  923.34  5002.3  927.19  5018.6  927.58  5040.4  935.21
  5054.7  936.06  5068.9  933.77  5083.1  936.30  5175.2  934.32  5522.5  941.61
  5578.5  938.55  5614.5  943.08  5841.3  947.00  6002.7  954.47  6190.7  963.04
#Mann=8,-1,0
  4402.6   0.063       0  4455.6    0.12       0  4614.4   0.063       0
  4833.3    0.12       0  4978.6   0.035       0  4980.4   0.035       0
  4989.1   0.035       0  6002.7   0.063       0
Bank Sta=4980.4,4989.1
Exp/Cntr=0.3,0.1

Type RM Length L Ch R = 1,19907,464,464,464
BEGIN DESCRIPTION:
Guadalupe Tributary 36 24.0
END DESCRIPTION:
XS GIS Cut Line= 3
      2204650.10     13858211.40      2205125.00     13858125.00
      2206025.14     13856753.03
#Sta/Elev= 30
  4527.6  973.73  4664.7  964.31  4828.5  947.87  4959.5  936.77  4978.5  931.46
  4983.6  926.79  4990.0  924.39  5003.4  923.51  5003.9  923.01  5012.2  923.51
  5019.4  923.76  5090.2  931.38  5436.8  936.97  5494.0  940.85  5587.4  941.43
  5653.8  947.14  5674.9  946.90  5680.9  944.43  5696.0  943.55  5711.0  943.81
  5732.1  947.75  5783.4  944.72  5840.6  946.27  5855.7  948.48  5913.0  946.99
  6130.0  953.84  6223.4  954.20  6425.3  960.36  6480.1  964.07  6651.2  968.98
#Mann=6,-1,0
  4527.6   0.035       0  4828.5    0.12       0  5003.4    0.05       0
  5012.2    0.12       0  5019.4   0.035       0  6480.1    0.12       0
Bank Sta=5003.4,5012.2
Exp/Cntr=0.3,0.1

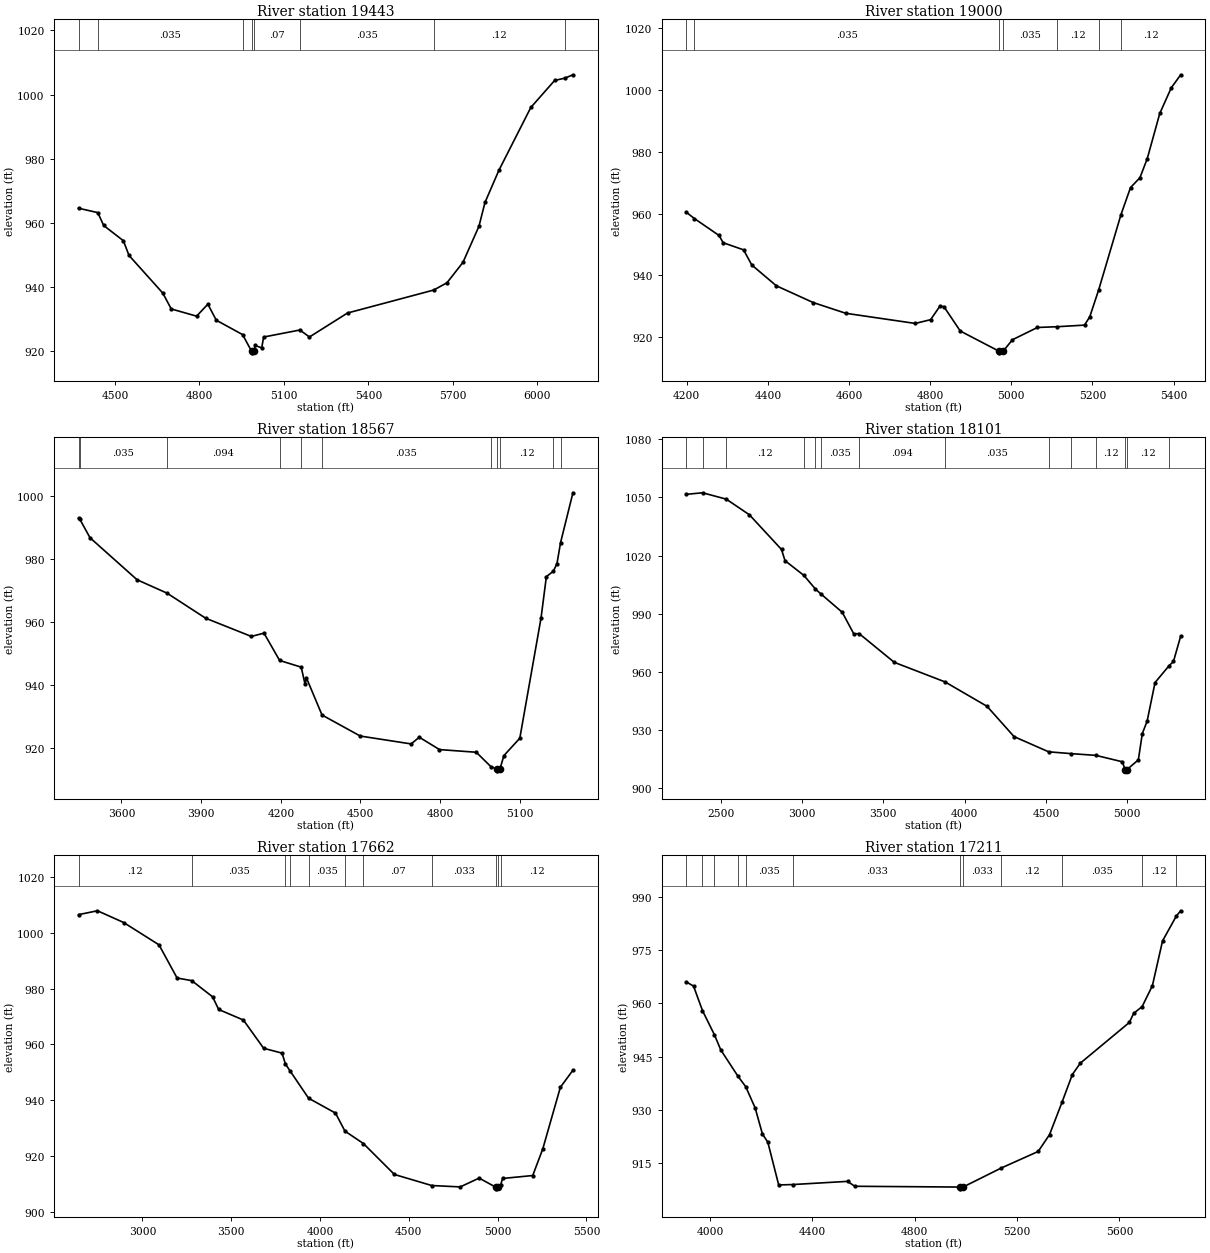
Type RM Length L Ch R = 1,19443,443,443,443
BEGIN DESCRIPTION:
Guadalupe Tributary 36 23.0
END DESCRIPTION:
XS GIS Cut Line= 3
      2204795.94     13858433.62      2205425.00     13858425.00
      2206254.31     13857662.77
#Sta/Elev= 30
  4370.9  964.53  4439.2  963.16  4460.0  959.15  4530.0  954.39  4550.0  949.80
  4670.0  938.06  4700.0  933.11  4790.0  930.86  4830.0  934.60  4860.0  929.59
  4953.3  925.11  4985.3  919.92  4985.8  919.42  4994.8  919.92  4997.5  921.71
  5021.3  920.99  5028.1  924.35  5156.7  926.54  5190.8  924.37  5325.9  931.84
  5632.1  939.01  5679.2  941.28  5735.9  947.64  5792.6  958.88  5814.2  966.35
  5863.5  976.36  5976.9  995.97  6061.4 1004.38  6098.0 1005.12  6126.4 1006.16
#Mann=8,-1,0
  4370.9   0.063       0  4439.2   0.035       0  4953.3    0.07       0
  4985.3    0.05       0  4994.8    0.07       0  5156.7   0.035       0
  5632.1    0.12       0  6098.0   0.063       0
Bank Sta=4985.3,4994.8
Exp/Cntr=0.3,0.1

Type RM Length L Ch R = 1,19000,433,433,433
BEGIN DESCRIPTION:
Guadalupe Tributary 36 22.0
END DESCRIPTION:
XS GIS Cut Line= 3
      2204874.95     13858674.99      2205675.00     13858775.00
      2206075.02     13858675.00
#Sta/Elev= 30
  4199.1  960.43  4219.2  958.39  4279.8  952.92  4289.8  950.58  4340.2  948.27
  4360.4  943.37  4420.9  936.63  4511.6  931.21  4592.2  927.72  4763.5  924.43
  4801.3  925.66  4824.0  930.00  4834.0  929.87  4874.4  921.97  4970.3  915.41
  4970.8  914.91  4979.9  915.41  5002.9  919.15  5064.6  923.13  5113.1  923.37
  5180.6  923.89  5193.5  926.58  5215.5  935.30  5270.4  959.65  5294.0  968.44
  5317.2  971.64  5335.2  977.79  5366.1  992.45  5394.5 1000.77  5417.7 1004.98
#Mann=7,-1,0
  4199.1   0.094       0  4219.2   0.035       0  4970.3   0.035       0
  4979.9   0.035       0  5113.1    0.12       0  5215.5   0.094       0
  5270.4    0.12       0
Bank Sta=4970.3,4979.9
Exp/Cntr=0.3,0.1

Type RM Length L Ch R = 1,18567,466,466,466
BEGIN DESCRIPTION:
Guadalupe Tributary 36 21.0
END DESCRIPTION:
XS GIS Cut Line= 3
      2204309.83     13858635.00      2205775.00     13859175.00
      2206074.99     13859175.00
#Sta/Elev= 30
  3438.4  992.93  3441.9  992.81  3481.5  986.75  3658.8  973.43  3771.6  969.19
  3916.8  961.25  4088.9  955.47  4136.7  956.51  4195.4  947.85  4276.8  945.73
  4291.3  940.26  4296.6  942.29  4355.1  930.56  4499.1  923.89  4690.8  921.39
  4721.3  923.52  4797.4  919.60  4936.0  918.75  4991.2  914.17  5015.1  913.36
  5015.6  912.86  5024.8  913.36  5039.9  917.68  5099.9  923.20  5179.9  961.35
  5199.9  974.44  5226.0  976.12  5239.9  978.56  5253.3  985.20  5299.9 1001.01
#Mann=11,-1,0
  3438.4   0.094       0  3441.9   0.035       0  3771.6   0.094       0
  4195.4   0.035       0  4276.8   0.094       0  4355.1   0.035       0
  4991.2    0.12       0  5015.1    0.05       0  5024.8    0.12       0
  5226.0   0.035       0  5253.3    0.12       0
Bank Sta=5015.1,5024.8
Exp/Cntr=0.3,0.1

Type RM Length L Ch R = 1,18101,439,439,439
BEGIN DESCRIPTION:
Guadalupe Tributary 36 20.0
END DESCRIPTION:
XS GIS Cut Line= 3
      2203386.27     13858253.09      2205725.00     13859625.00
      2206031.04     13859503.47
#Sta/Elev= 30
  2288.2 1051.63  2388.1 1052.43  2533.9 1049.14  2676.2 1041.06  2873.6 1023.16
  2895.1 1017.39  3011.1 1009.79  3082.1 1002.76  3116.1 1000.20  3246.9  990.77
  3318.5  979.55  3350.8  979.77  3567.3  964.91  3878.9  954.83  4137.9  942.21
  4304.0  926.57  4516.7  918.73  4656.8  917.78  4807.2  916.89  4970.3  913.58
  4986.9  909.41  4987.4  908.91  4996.6  909.41  5068.5  914.59  5092.8  928.15
  5122.4  934.56  5171.1  954.49  5257.8  963.21  5284.4  965.36  5328.9  978.46
#Mann=14,-1,0
  2288.2    0.12       0  2388.1   0.063       0  2533.9    0.12       0
  3011.1   0.035       0  3082.1    0.12       0  3116.1   0.035       0
  3350.8   0.094       0  3878.9   0.035       0  4516.7    0.12       0
  4656.8   0.035       0  4807.2    0.12       0  4986.9    0.05       0
  4996.6    0.12       0  5257.8   0.035       0
Bank Sta=4986.9,4996.6
Exp/Cntr=0.3,0.1

Type RM Length L Ch R = 1,17662,451,451,451
BEGIN DESCRIPTION:
Guadalupe Tributary 36 19.0
END DESCRIPTION:
XS GIS Cut Line= 3
      2203400.16     13860648.89      2205675.00     13860025.00
      2205975.00     13859725.00
#Sta/Elev= 30
  2640.6 1006.52  2747.0 1007.90  2894.5 1003.69  3093.4  995.69  3195.2  983.80
  3277.8  982.85  3395.0  977.06  3429.4  972.51  3568.5  968.73  3682.5  958.61
  3786.2  956.86  3805.0  952.98  3832.2  950.40  3935.3  940.71  4086.9  935.37
  4140.3  928.90  4244.3  924.44  4418.8  913.36  4628.6  909.40  4789.2  908.90
  4895.7  912.06  4991.9  908.71  4992.4  908.21  5001.7  908.71  5016.2  909.46
  5027.7  911.93  5197.4  912.98  5254.0  922.53  5353.0  944.62  5423.7  950.74
#Mann=11,-1,0
  2640.6    0.12       0  3277.8   0.035       0  3805.0   0.063       0
  3832.2    0.12       0  3935.3   0.035       0  4140.3    0.12       0
  4244.3    0.07       0  4628.6   0.033       0  4991.9   0.033       0
  5001.7   0.033       0  5016.2    0.12       0
Bank Sta=4991.9,5001.7
Exp/Cntr=0.3,0.1

Type RM Length L Ch R = 1,17211,452,452,452
BEGIN DESCRIPTION:
Guadalupe Tributary 36 18.0
END DESCRIPTION:
XS GIS Cut Line= 3
      2205074.97     13861025.02      2205875.00     13860275.00
      2206240.19     13859524.34
#Sta/Elev= 30
  3908.0  966.01  3936.1  964.85  3971.1  957.95  4017.4  951.21  4042.6  946.91
  4110.1  939.47  4139.8  936.61  4176.9  930.60  4205.3  923.28  4226.3  921.00
  4268.8  908.97  4325.1  909.09  4537.9  909.98  4566.0  908.60  4977.7  908.38
  4978.2  907.88  4989.0  908.38  5137.7  913.71  5282.6  918.38  5327.1  923.13
  5375.6  932.19  5416.1  940.00  5447.1  943.18  5638.6  954.62  5655.6  957.18
  5688.8  959.10  5728.8  964.96  5768.4  977.53  5822.6  984.57  5839.4  986.01
#Mann=12,-1,0
  3908.0   0.063       0  3971.1    0.12       0  4017.4   0.035       0
  4110.1    0.12       0  4139.8   0.035       0  4325.1   0.033       0
  4977.7   0.033       0  4989.0   0.033       0  5137.7    0.12       0
  5375.6   0.035       0  5688.8    0.12       0  5822.6   0.035       0
Bank Sta=4977.7,4989
Exp/Cntr=0.3,0.1