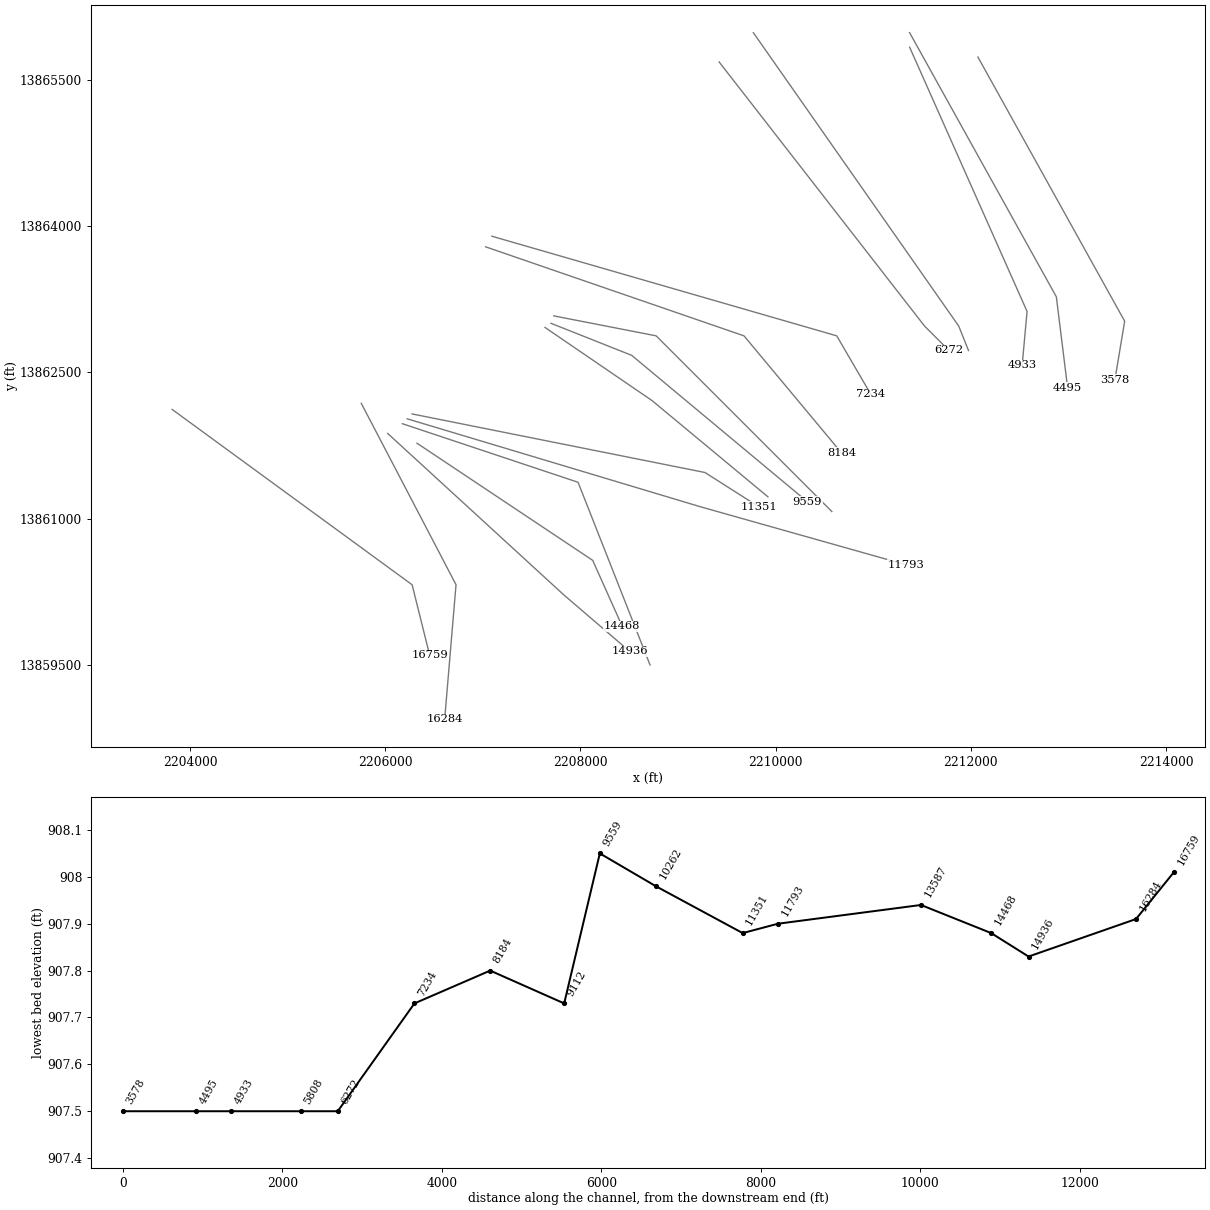
HEC-RAS study Guadalupe Tributary 36.prj: Guadalupe Tributary 36 Base Level Engineering

--- Guadalupe Tributary 36.g01 (geometry) --- (continued)

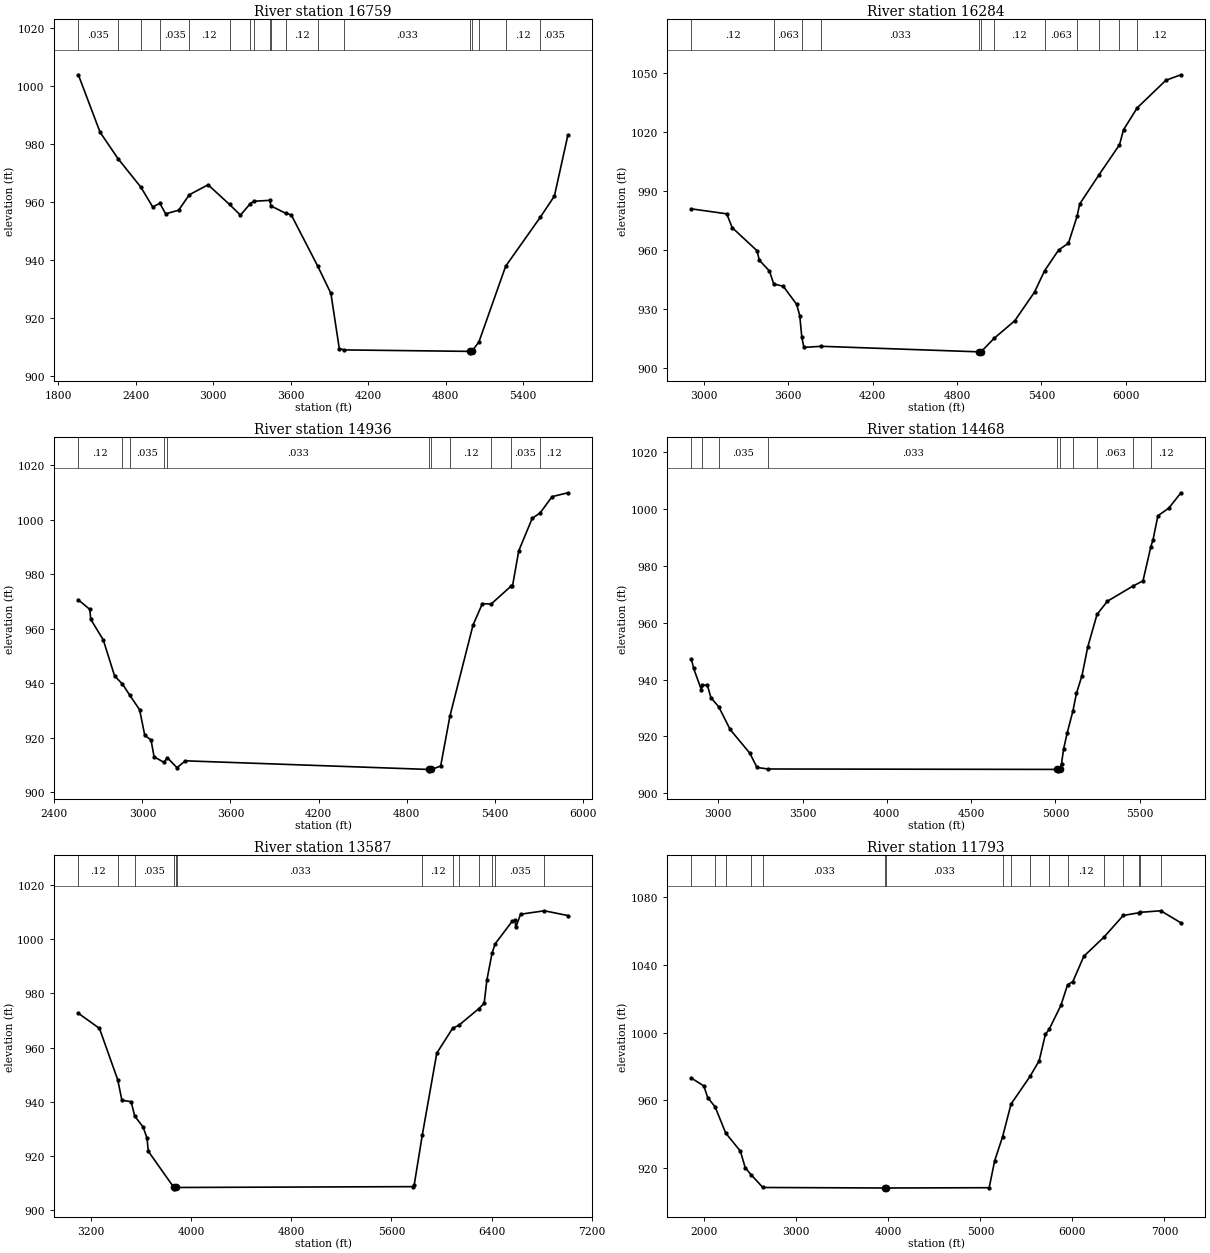
Type RM Length L Ch R = 1,16759,475,475,475
BEGIN DESCRIPTION:
Guadalupe Tributary 36 17.0
END DESCRIPTION:
XS GIS Cut Line= 3
      2203816.79     13862121.12      2206275.00     13860325.00
      2206455.68     13859600.26
#Sta/Elev= 30
  1955.1 1003.73  2123.3  983.97  2262.5  974.86  2440.2  965.00  2531.0  958.23
  2586.2  959.48  2631.4  955.86  2731.8  957.11  2814.6  962.42  2959.7  965.87
  3126.0  959.09  3210.6  955.41  3286.2  959.34  3313.7  960.18  3438.5  960.51
  3446.4  958.59  3563.3  956.00  3603.7  955.53  3810.3  937.75  3911.1  928.48
  3976.0  909.49  4013.4  909.02  4990.6  908.51  4991.1  908.01  5002.3  908.51
  5057.8  911.80  5264.5  937.82  5533.3  954.73  5642.0  961.98  5746.5  982.97
#Mann=18,-1,0
  1955.1   0.035       0  2262.5    0.12       0  2440.2   0.063       0
  2586.2   0.035       0  2814.6    0.12       0  3126.0   0.035       0
  3286.2    0.12       0  3313.7   0.035       0  3438.5    0.12       0
  3446.4   0.035       0  3563.3    0.12       0  3810.3   0.035       0
  4013.4   0.033       0  4990.6   0.033       0  5002.3   0.033       0
  5057.8    0.07       0  5264.5    0.12       0  5533.3   0.035       0
Bank Sta=4990.6,5002.3
Exp/Cntr=0.3,0.1

Type RM Length L Ch R = 1,16284,1348,1348,1348
BEGIN DESCRIPTION:
Guadalupe Tributary 36 16.0
END DESCRIPTION:
XS GIS Cut Line= 3
      2205754.27     13862183.66      2206725.00     13860325.00
      2206608.57     13858948.80
#Sta/Elev= 30
  2913.1  981.13  3164.3  978.60  3202.8  971.60  3379.4  959.84  3395.9  955.00
  3467.8  949.52  3498.2  942.91  3565.9  941.77  3660.9  932.57  3682.9  926.87
  3697.8  915.72  3712.6  910.66  3834.3  911.24  4959.0  908.41  4959.5  907.91
  4970.8  908.41  5062.9  915.23  5210.7  924.22  5351.2  938.84  5422.3  949.63
  5521.8  960.18  5592.1  963.69  5653.2  977.36  5672.3  983.68  5808.1  998.34
  5954.6 1013.72  5983.5 1021.41  6080.8 1032.52  6284.5 1046.52  6391.1 1049.31
#Mann=12,-1,0
  2913.1    0.12       0  3498.2   0.063       0  3697.8    0.07       0
  3834.3   0.033       0  4959.0   0.033       0  4970.8   0.033       0
  5062.9    0.12       0  5422.3   0.063       0  5653.2   0.035       0
  5808.1    0.12       0  5954.6   0.035       0  6080.8    0.12       0
Bank Sta=4959,4970.8
Exp/Cntr=0.3,0.1

Type RM Length L Ch R = 1,14936,468,468,468
BEGIN DESCRIPTION:
Guadalupe Tributary 36 15.0
END DESCRIPTION:
XS GIS Cut Line= 3
      2206025.01     13861874.99      2207825.00     13860225.00
      2208504.28     13859641.96
#Sta/Elev= 30
  2562.9  970.64  2640.9  967.15  2647.7  963.48  2732.8  955.94  2810.5  942.63
  2863.7  939.74  2913.9  935.56  2980.6  930.27  3015.8  920.88  3058.3  919.18
  3079.3  912.99  3145.7  910.97  3170.3  912.62  3235.3  908.98  3292.0  911.51
  4956.0  908.33  4956.5  907.83  4969.0  908.33  5032.7  909.59  5095.9  927.97
  5253.3  961.38  5316.9  969.25  5376.7  969.09  5510.0  975.56  5522.2  975.65
  5565.0  988.65  5657.1 1000.63  5709.2 1002.47  5792.1 1008.55  5899.9 1009.97
#Mann=11,-1,0
  2562.9    0.12       0  2863.7   0.063       0  2913.9   0.035       0
  3145.7    0.07       0  3170.3   0.033       0  4956.0   0.033       0
  4969.0   0.033       0  5095.9    0.12       0  5376.7   0.063       0
  5510.0   0.035       0  5709.2    0.12       0
Bank Sta=4956,4969
Exp/Cntr=0.3,0.1

Type RM Length L Ch R = 1,14468,881,881,881
BEGIN DESCRIPTION:
Guadalupe Tributary 36 14.0
END DESCRIPTION:
XS GIS Cut Line= 3
      2206324.99     13861775.01      2208125.00     13860575.00
      2208427.66     13859899.44
#Sta/Elev= 30
  2840.6  947.31  2854.1  943.94  2899.2  936.51  2905.8  938.02  2935.3  938.11
  2956.3  933.66  3002.6  930.44  3070.5  922.44  3187.6  914.07  3229.7  909.07
  3294.8  908.53  5011.8  908.38  5012.3  907.88  5024.8  908.38  5036.0  910.42
  5047.8  915.42  5070.1  921.36  5103.9  929.05  5124.5  935.18  5157.4  941.42
  5191.5  951.50  5246.4  962.93  5307.5  967.58  5459.1  972.93  5519.0  974.76
  5565.5  986.74  5579.0  989.33  5607.6  997.71  5671.7 1000.35  5744.2 1005.79
#Mann=10,-1,0
  2840.6    0.12       0  2905.8   0.063       0  3002.6   0.035       0
  3294.8   0.033       0  5011.8   0.033       0  5024.8   0.033       0
  5103.9    0.12       0  5246.4   0.063       0  5459.1   0.035       0
  5565.5    0.12       0
Bank Sta=5011.8,5024.8
Exp/Cntr=0.3,0.1

Type RM Length L Ch R = 1,13587,1794,1794,1794
BEGIN DESCRIPTION:
Guadalupe Tributary 36 13.0
END DESCRIPTION:
XS GIS Cut Line= 3
      2206174.98     13861975.01      2207975.00     13861375.00
      2208712.62     13859503.07
#Sta/Elev= 30
  3099.3  972.66  3268.0  967.07  3414.1  948.11  3447.2  940.58  3521.0  940.07
  3549.2  934.77  3615.8  930.79  3647.4  926.71  3658.0  921.80  3862.3  908.44
  3862.8  907.94  3875.3  908.44  3890.4  908.44  5769.6  908.75  5781.3  909.33
  5845.4  927.60  5961.8  957.96  6089.4  967.19  6136.5  968.16  6298.5  974.39
  6340.2  976.31  6361.7  984.87  6403.0  994.76  6427.5  998.21  6562.8 1006.49
  6587.2 1006.95  6592.6 1004.28  6630.4 1009.15  6821.0 1010.42  7008.7 1008.66
#Mann=13,-1,0
  3099.3    0.12       0  3414.1   0.063       0  3549.2   0.035       0
  3862.3   0.033       0  3875.3   0.035       0  3890.4   0.033       0
  5845.4    0.12       0  6089.4   0.063       0  6136.5   0.035       0
  6298.5   0.063       0  6403.0    0.12       0  6427.5   0.035       0
  6821.0    0.12       0
Bank Sta=3862.3,3875.3
Exp/Cntr=0.3,0.1

Type RM Length L Ch R = 1,11793,442,442,442
BEGIN DESCRIPTION:
Guadalupe Tributary 36 12.0
END DESCRIPTION:
XS GIS Cut Line= 3
      2206224.98     13862025.01      2209225.00     13861125.00
      2211330.38     13860530.93
#Sta/Elev= 30
  1859.6  973.16  1995.3  968.50  2037.1  961.62  2116.8  956.28  2232.8  940.76
  2392.1  930.11  2444.3  920.39  2507.3  916.28  2635.9  908.70  3962.5  908.40
  3963.0  907.90  3976.3  908.40  5095.6  908.57  5155.1  924.41  5241.2  938.60
  5333.2  957.86  5539.8  974.17  5638.6  983.38  5706.6  998.90  5746.3 1001.80
  5874.9 1015.96  5947.3 1028.16  6004.6 1029.99  6124.3 1044.94  6345.5 1056.35
  6553.0 1068.99  6725.5 1070.58  6729.5 1070.79  6960.4 1071.73  7179.3 1064.62
#Mann=17,-1,0
  1859.6    0.12       0  2116.8   0.063       0  2232.8   0.035       0
  2507.3    0.07       0  2635.9   0.033       0  3962.5   0.033       0
  3976.3   0.033       0  5241.2   0.035       0  5333.2   0.063       0
  5539.8    0.12       0  5746.3   0.035       0  5947.3    0.12       0
  6345.5   0.063       0  6553.0   0.035       0  6725.5   0.063       0
  6729.5   0.035       0  6960.4   0.063       0
Bank Sta=3962.5,3976.3
Exp/Cntr=0.3,0.1

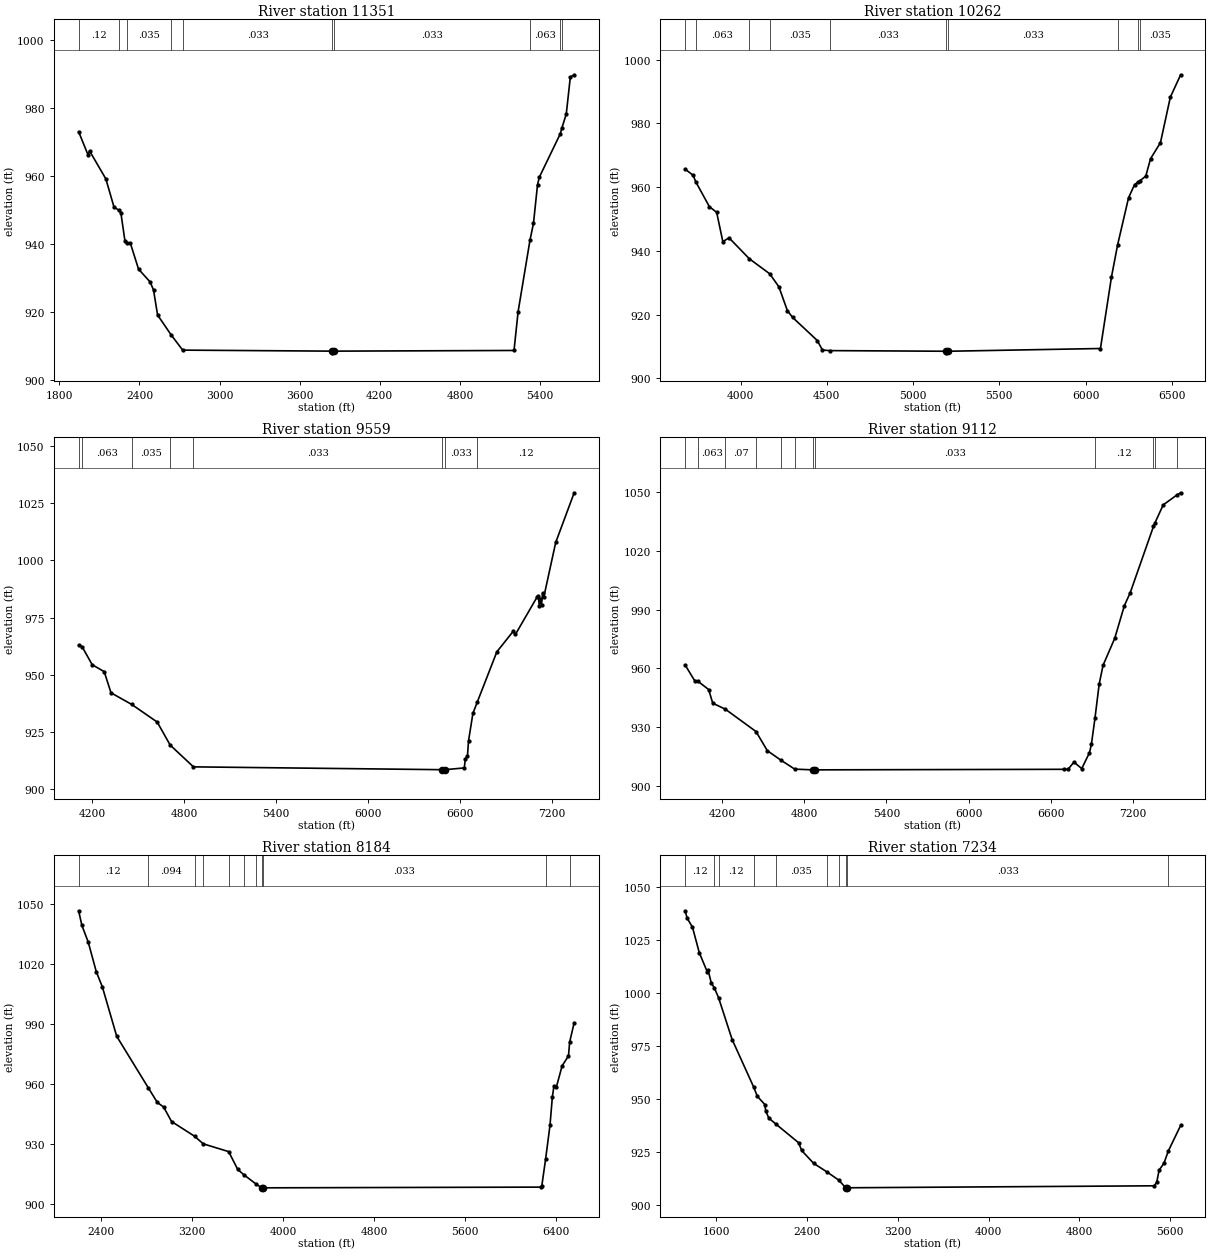
Type RM Length L Ch R = 1,11351,1089,1089,1089
BEGIN DESCRIPTION:
Guadalupe Tributary 36 11.0
END DESCRIPTION:
XS GIS Cut Line= 3
      2206274.97     13862075.01      2209275.00     13861475.00
      2209825.03     13861124.98
#Sta/Elev= 30
  1944.5  973.00  2015.9  966.09  2026.1  967.37  2148.5  959.10  2209.7  950.76
  2243.3  949.96  2260.7  949.15  2291.3  940.85  2309.1  940.24  2332.1  940.15
  2393.2  932.53  2479.9  928.76  2505.4  926.38  2536.0  919.01  2636.5  913.21
  2723.8  908.68  3844.7  908.38  3845.2  907.88  3858.5  908.38  5205.4  908.58
  5235.9  919.99  5324.6  940.99  5351.1  946.02  5381.5  957.42  5395.1  959.62
  5552.7  972.46  5562.8  973.99  5596.6  978.17  5627.1  989.11  5655.9  989.77
#Mann=10,-1,0
  1944.5    0.12       0  2243.3   0.063       0  2309.1   0.035       0
  2636.5    0.07       0  2723.8   0.033       0  3844.7   0.033       0
  3858.5   0.033       0  5324.6   0.063       0  5552.7   0.035       0
  5562.8   0.063       0
Bank Sta=3844.7,3858.5
Exp/Cntr=0.3,0.1

Type RM Length L Ch R = 1,10262,703,703,703
BEGIN DESCRIPTION:
Guadalupe Tributary 36 10.0
END DESCRIPTION:
XS GIS Cut Line= 3
      2207636.27     13862961.37      2208733.46     13862211.40
      2209920.52     13861225.65
#Sta/Elev= 30
  3678.6  965.62  3725.5  963.66  3739.5  961.73  3819.6  953.82  3861.5  952.06
  3897.4  942.86  3933.3  944.06  4051.0  937.49  4169.0  932.78  4222.1  928.70
  4271.2  921.25  4301.1  919.12  4444.6  911.85  4474.5  908.86  4515.7  908.68
  5190.8  908.48  5191.3  907.98  5205.0  908.48  6085.9  909.34  6149.7  931.77
  6185.1  941.81  6248.7  956.62  6283.8  960.78  6304.5  961.55  6316.5  962.04
  6348.5  963.41  6376.3  968.88  6433.6  973.91  6490.9  988.19  6550.6  995.21
#Mann=10,-1,0
  3678.6    0.12       0  3739.5   0.063       0  4051.0    0.12       0
  4169.0   0.035       0  4515.7   0.033       0  5190.8   0.033       0
  5205.0   0.033       0  6185.1   0.035       0  6304.5   0.063       0
  6316.5   0.035       0
Bank Sta=5190.8,5205
Exp/Cntr=0.3,0.1

Type RM Length L Ch R = 1,9559,447,447,447
BEGIN DESCRIPTION:
Guadalupe Tributary 36 9.0
END DESCRIPTION:
XS GIS Cut Line= 3
      2207698.71     13863003.07      2208525.00     13862675.00
      2210324.99     13861175.01
#Sta/Elev= 30
  4111.9  963.01  4135.5  962.17  4200.4  954.43  4278.8  951.39  4323.1  942.14
  4457.7  937.08  4624.4  929.37  4708.9  919.31  4860.8  909.79  6484.9  908.55
  6485.4  908.05  6499.1  908.55  6627.4  909.32  6633.9  913.23  6648.2  914.63
  6654.8  921.08  6683.4  933.12  6712.1  938.12  6839.6  960.05  6946.3  969.03
  6960.7  967.65  7102.5  984.06  7109.7  984.34  7116.9  980.13  7123.4  983.29
  7131.2  980.71  7137.7  985.69  7145.5  983.86  7223.6 1007.85  7344.0 1029.56
#Mann=8,-1,0
  4111.9    0.12       0  4135.5   0.063       0  4457.7   0.035       0
  4708.9    0.07       0  4860.8   0.033       0  6484.9   0.033       0
  6499.1   0.033       0  6712.1    0.12       0
Bank Sta=6484.9,6499.1
Exp/Cntr=0.3,0.1

Type RM Length L Ch R = 1,9112,928,928,928
BEGIN DESCRIPTION:
Guadalupe Tributary 36 8.0
END DESCRIPTION:
XS GIS Cut Line= 3
      2207726.47     13863079.46      2208775.00     13862875.00
      2210575.03     13861074.97
#Sta/Elev= 30
  3931.3  961.80  4001.1  953.77  4024.0  953.52  4103.0  949.25  4133.0  942.28
  4225.9  939.16  4448.4  927.80  4530.9  918.03  4629.9  913.18  4730.9  908.60
  4863.4  908.23  4863.9  907.73  4877.7  908.23  6696.6  908.51  6724.9  908.60
  6767.3  912.19  6823.9  908.87  6880.5  917.01  6894.6  921.36  6920.4  934.59
  6951.2  952.08  6979.5  961.65  7064.3  975.36  7135.0  992.12  7177.5  998.69
  7347.2 1032.56  7357.8 1034.33  7417.9 1043.53  7517.7 1048.59  7545.2 1049.73
#Mann=12,-1,0
  3931.3   0.094       0  4024.0   0.063       0  4225.9    0.07       0
  4448.4   0.035       0  4629.9    0.07       0  4730.9   0.033       0
  4863.4   0.033       0  4877.7   0.033       0  6920.4    0.12       0
  7347.2   0.063       0  7357.8   0.035       0  7517.7   0.063       0
Bank Sta=4863.4,4877.7
Exp/Cntr=0.3,0.1

Type RM Length L Ch R = 1,8184,950,950,950
BEGIN DESCRIPTION:
Guadalupe Tributary 36 7.0
END DESCRIPTION:
XS GIS Cut Line= 3
      2207028.07     13863786.88      2209675.00     13862875.00
      2210674.97     13861675.04
#Sta/Elev= 30
  2200.4 1046.38  2228.9 1039.12  2285.0 1030.75  2355.8 1016.02  2409.9 1008.33
  2535.6  983.82  2813.0  958.20  2893.4  950.83  2948.1  948.60  3018.3  941.36
  3221.2  934.00  3297.4  930.22  3521.0  926.35  3600.8  917.46  3652.6  914.92
  3757.9  910.36  3812.2  908.30  3812.7  907.80  3826.5  908.30  6271.1  908.66
  6277.6  909.44  6310.4  922.56  6349.2  939.45  6370.0  953.65  6384.4  959.18
  6405.8  958.63  6456.0  969.14  6511.9  974.02  6522.2  980.97  6562.0  990.59
#Mann=11,-1,0
  2200.4    0.12       0  2813.0   0.094       0  3221.2   0.035       0
  3297.4    0.07       0  3521.0   0.035       0  3652.6    0.07       0
  3757.9   0.033       0  3812.2   0.033       0  3826.5   0.033       0
  6310.4    0.12       0  6522.2   0.035       0
Bank Sta=3812.2,3826.5
Exp/Cntr=0.3,0.1

Type RM Length L Ch R = 1,7234,962,962,962
BEGIN DESCRIPTION:
Guadalupe Tributary 36 6.0
END DESCRIPTION:
XS GIS Cut Line= 3
      2207092.66     13863895.48      2210625.00     13862875.00
      2210974.99     13862275.02
#Sta/Elev= 30
  1323.2 1038.59  1342.1 1035.01  1388.1 1030.90  1448.2 1018.89  1520.7 1009.59
  1525.9 1010.65  1554.3 1004.61  1581.5 1002.27  1618.7  997.64  1738.0  978.01
  1926.7  955.80  1960.6  951.27  2027.9  947.33  2033.4  944.52  2061.5  941.04
  2122.8  938.27  2324.9  929.41  2351.4  925.78  2457.4  919.72  2575.2  915.67
  2678.7  911.83  2740.1  908.23  2740.6  907.73  2754.4  908.23  5461.8  909.16
  5483.3  910.79  5504.8  916.53  5547.8  919.81  5585.1  925.44  5694.6  937.56
#Mann=10,-1,0
  1323.2    0.12       0  1581.5   0.033       0  1618.7    0.12       0
  1926.7   0.094       0  2122.8   0.035       0  2575.2    0.07       0
  2678.7   0.033       0  2740.1   0.033       0  2754.4   0.033       0
  5585.1    0.07       0
Bank Sta=2740.1,2754.4
Exp/Cntr=0.3,0.1

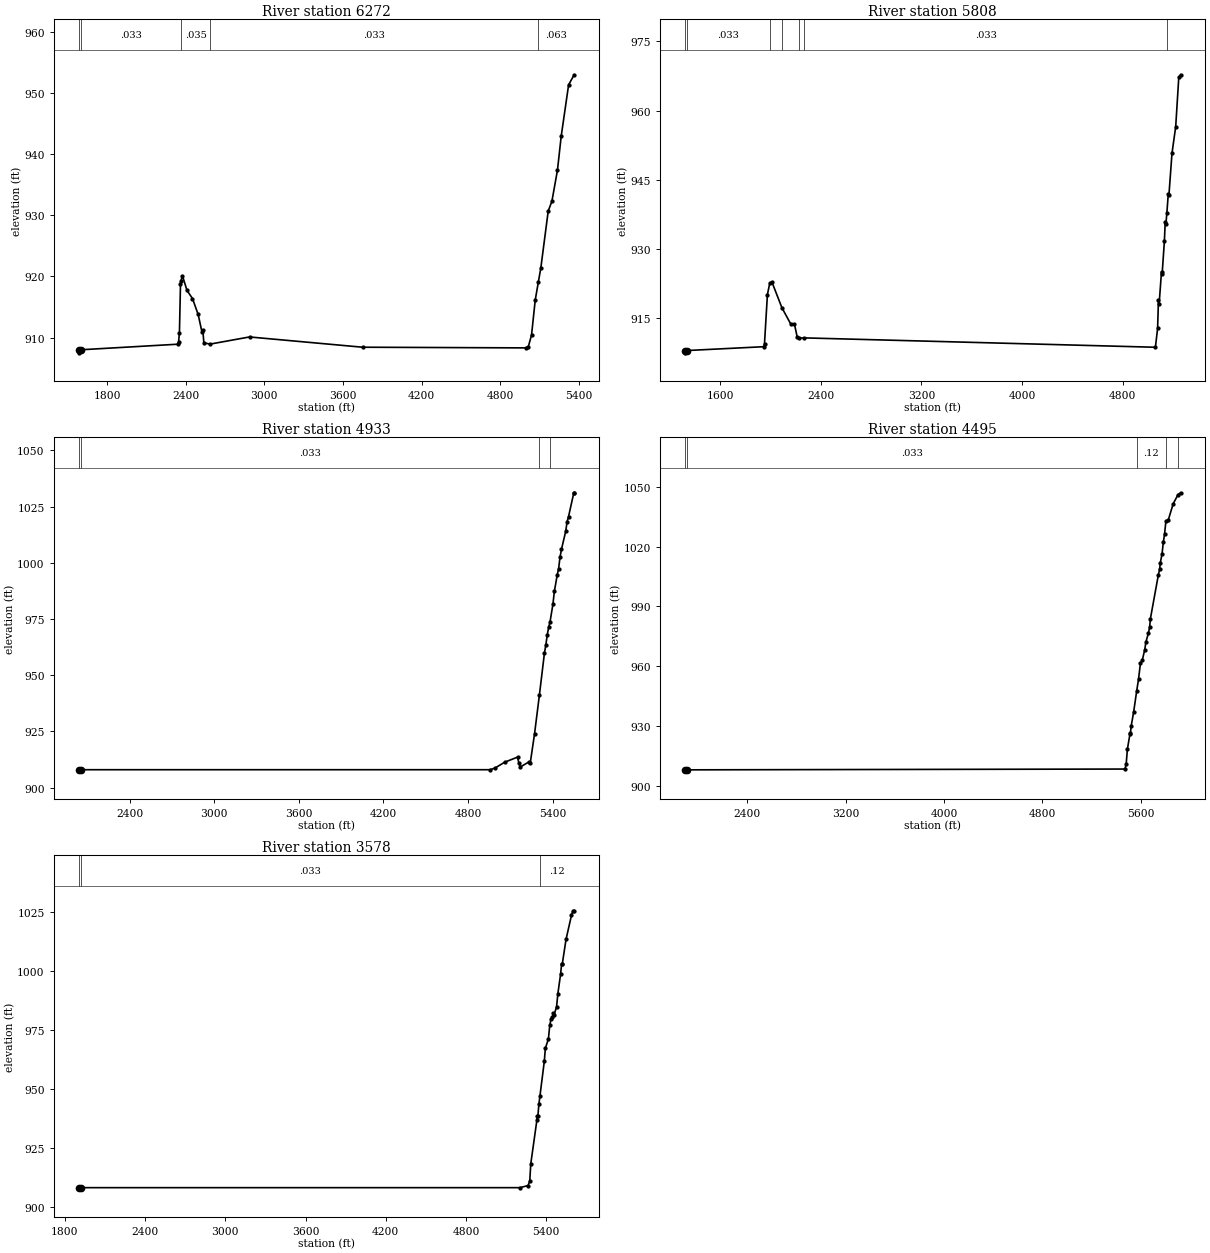
Type RM Length L Ch R = 1,6272,464,464,464
BEGIN DESCRIPTION:
Guadalupe Tributary 36 5.0
END DESCRIPTION:
XS GIS Cut Line= 3
      2209420.56     13865680.71      2211525.00     13862975.00
      2211774.99     13862725.01
#Sta/Elev= 30
  1583.2  908.00  1583.7  907.50  1597.7  908.00  2337.9  908.91  2346.0  909.30
  2352.4  910.82  2360.5  918.77  2364.3  919.27  2375.0  920.14  2410.3  917.71
  2451.9  916.39  2495.3  913.78  2524.3  910.91  2530.6  911.29  2538.8  909.14
  2586.5  908.93  2887.2  910.10  3749.5  908.42  4997.4  908.31  5014.5  908.50
  5039.2  910.42  5067.5  916.16  5090.7  919.03  5110.0  921.39  5166.5  930.72
  5194.8  932.33  5237.2  937.44  5265.5  942.96  5322.1  951.38  5364.5  953.02
#Mann=5,-1,0
  1583.2   0.033       0  1597.7   0.033       0  2364.3   0.035       0
  2586.5   0.033       0  5090.7   0.063       0
Bank Sta=1583.2,1597.7
Exp/Cntr=0.3,0.1

Type RM Length L Ch R = 1,5808,875,875,875
BEGIN DESCRIPTION:
Guadalupe Tributary 36 4.0
END DESCRIPTION:
XS GIS Cut Line= 3
      2209770.84     13865980.95      2211875.00     13862975.00
      2211975.01     13862724.98
#Sta/Elev= 30
  1321.8  908.00  1322.3  907.50  1336.4  908.00  1946.8  908.83  1952.9  909.49
  1976.0  920.14  1995.1  922.65  2012.2  922.83  2091.0  917.29  2161.3  913.76
  2190.9  913.73  2211.9  911.04  2230.3  910.70  2270.6  910.74  5059.7  908.71
  5077.2  912.78  5083.9  918.90  5089.3  918.06  5108.2  925.10  5113.5  924.68
  5131.0  931.66  5137.8  935.85  5143.2  935.45  5151.1  937.88  5162.0  941.93
  5167.4  941.75  5191.6  950.77  5221.2  956.55  5245.5  967.22  5260.3  967.77
#Mann=7,-1,0
  1321.8   0.033       0  1336.4   0.033       0  1995.1    0.07       0
  2091.0   0.035       0  2230.3    0.07       0  2270.6   0.033       0
  5151.1    0.12       0
Bank Sta=1321.8,1336.4
Exp/Cntr=0.3,0.1

Type RM Length L Ch R = 1,4933,438,438,438
BEGIN DESCRIPTION:
Guadalupe Tributary 36 3.0
END DESCRIPTION:
XS GIS Cut Line= 3
      2211372.04     13865831.67      2212575.00     13863125.00
      2212525.00     13862575.02
#Sta/Elev= 30
  2038.6  908.00  2039.1  907.50  2052.7  907.50  2053.2  908.00  4956.8  908.00
  4991.7  908.75  5060.8  911.37  5151.2  913.60  5161.2  910.79  5171.3  909.24
  5231.5  911.43  5241.5  911.02  5271.7  923.94  5306.4  941.28  5342.0  959.90
  5352.0  963.47  5362.0  967.93  5372.1  971.43  5380.9  973.46  5402.2  981.58
  5412.2  987.24  5432.3  994.49  5442.4  997.37  5452.4 1002.49  5462.5 1005.92
  5492.6 1013.95  5502.6 1018.23  5512.7 1020.50  5550.3 1031.12  5552.8 1031.12
#Mann=4,-1,0
  2038.6   0.033       0  2053.2   0.033       0  5306.4    0.07       0
  5380.9    0.12       0
Bank Sta=2038.6,2053.2
Exp/Cntr=0.3,0.1

Type RM Length L Ch R = 1,4495,917,917,917
BEGIN DESCRIPTION:
Guadalupe Tributary 36 2.0
END DESCRIPTION:
XS GIS Cut Line= 3
      2211371.45     13865981.39      2212875.00     13863275.00
      2212990.20     13862345.00
#Sta/Elev= 30
  1892.9  908.00  1893.4  907.50  1907.6  908.00  5472.6  908.40  5482.6  910.76
  5492.7  918.38  5512.8  925.76  5517.8  926.57  5522.9  929.76  5543.1  936.84
  5567.8  947.36  5583.4  953.56  5598.8  961.44  5613.6  962.91  5633.8  968.30
  5643.9  972.29  5664.0  976.57  5674.1  979.79  5679.7  983.76  5744.6 1005.78
  5754.7 1008.53  5760.7 1011.83  5774.9 1016.49  5784.9 1022.14  5795.0 1026.24
  5806.0 1032.65  5825.2 1033.31  5865.5 1041.49  5904.7 1046.07  5926.0 1047.00
#Mann=5,-1,0
  1892.9   0.033       0  1907.6   0.033       0  5567.8    0.12       0
  5806.0   0.063       0  5904.7   0.094       0
Bank Sta=1892.9,1907.6
Exp/Cntr=0.3,0.1

Type RM Length L Ch R = 1,3578,0,0,0
BEGIN DESCRIPTION:
Guadalupe Tributary 36 1.0
END DESCRIPTION:
XS GIS Cut Line= 3
      2212071.45     13865731.39      2213575.00     13863025.00
      2213475.00     13862424.98
#Sta/Elev= 30
  1904.0  908.00  1904.5  907.50  1918.2  907.50  1918.7  908.00  5202.8  908.00
  5263.6  908.89  5276.3  910.87  5283.9  918.12  5329.5  936.60  5332.0  938.21
  5337.1  938.45  5344.7  943.39  5352.6  946.97  5385.2  961.64  5392.8  967.09
  5415.7  971.03  5425.8  976.85  5435.9  979.67  5446.1  980.41  5453.7  982.13
  5458.7  981.38  5476.5  984.66  5486.6  990.30  5506.9  998.62  5514.5 1002.85
  5519.6 1002.91  5547.4 1013.27  5588.0 1023.46  5598.1 1025.29  5608.3 1025.41
#Mann=3,-1,0
  1904.0   0.033       0  1918.7   0.033       0  5352.6    0.12       0
Bank Sta=1904,1918.7
Exp/Cntr=0.3,0.1

Chan Stop Cuts=-1