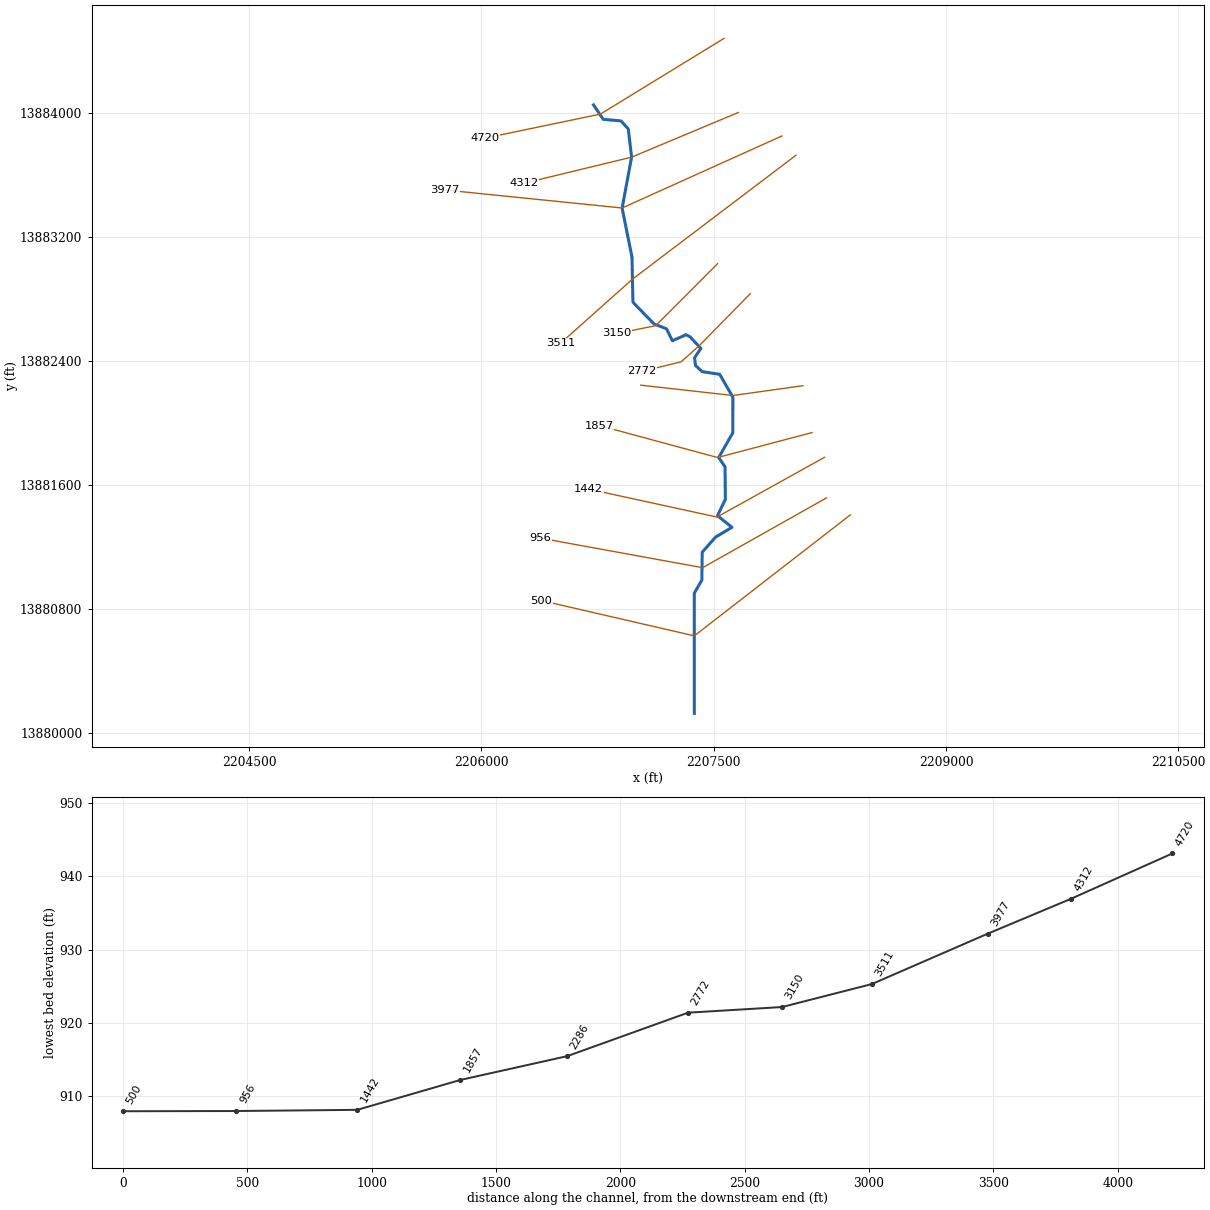
--- Guadalupe Tributary 46.prj (project) ---

Proj Title=Guadalupe Tributary 46 Base Level Engineering
Current Plan=p01
Default Exp/Contr=0.3,0.1
English Units
Geom File=g01
Flow File=f01
Plan File=p01
Y Axis Title=Elevation
X Axis Title(PF)=Main Channel Distance
X Axis Title(XS)=Station
BEGIN DESCRIPTION:
Guadalupe Tributary 46
END DESCRIPTION:
DSS Export Rating Curves= 0
DSS Export Rating Curve Sorted= 0
DSS Export Volume Flow Curves= 0
DXF OffsetX= 0
DXF OffsetY= 0
DXF ScaleX= 1
DXF ScaleY= 10

--- Guadalupe Tributary 46.p01 (plan) ---

Plan Title=Multiple Run
Short Identifier=Multiple
Geom File=g01
Flow File=f01
Subcritical Flow
K Sum by GR= 0
Std Step Tol= 0.01
Critical Tol= 0.01
Num of Std Step Trials= 20
Max Error Tol= 0.3
Flow Tol Ratio= 0.001
Split Flow NTrial= 30
Split Flow Tol= 0.02
Split Flow Ratio= 0.02
Log Output Level= 0
Friction Slope Method= 1
Unsteady Friction Slope Method= 2
Unsteady Bridges Friction Slope Method= 1
Parabolic Critical Depth
Global Vel Dist=  1 , 1 , 1
Global Log Level= 0
CheckData=True
Encroach Param= -1, 0, 0, 0
BEGIN DESCRIPTION:
Multiple Run
END DESCRIPTION:

--- Guadalupe Tributary 46.f01 (steady flow) ---

Flow Title=Multiple
Number of Profiles=7
Profile Names=10-year,25-year,50-year,1pct_min,100-year,1pct_plu,500-year
River Rch & RM= Guadalupe Tribut,Reach-1,4720
    1270    2172    3038    2060    4110    8200    7438
River Rch & RM= Guadalupe Tribut,Reach-1,3150
    1548    2667    3748    2550    5088   10152    9277
Boundary for River Rch & Prof#=Guadalupe Tribut,Reach-1,1
Up Type=0
Dn Type=3
Dn Slope=0.005
Boundary for River Rch & Prof#=Guadalupe Tribut,Reach-1,2
Up Type=0
Dn Type=3
Dn Slope=0.005
Boundary for River Rch & Prof#=Guadalupe Tribut,Reach-1,3
Up Type=0
Dn Type=3
Dn Slope=0.005
Boundary for River Rch & Prof#=Guadalupe Tribut,Reach-1,4
Up Type=0
Dn Type=3
Dn Slope=0.005
Boundary for River Rch & Prof#=Guadalupe Tribut,Reach-1,5
Up Type=0
Dn Type=3
Dn Slope=0.005
Boundary for River Rch & Prof#=Guadalupe Tribut,Reach-1,6
Up Type=0
Dn Type=3
Dn Slope=0.005
Boundary for River Rch & Prof#=Guadalupe Tribut,Reach-1,7
Up Type=0
Dn Type=3
Dn Slope=0.005

--- Guadalupe Tributary 46.g01 (geometry) ---

Geom Title=Existing Conditions
Program Version=4.10

River Reach=Guadalupe Tribut,Reach-1
Reach XY= 30
      2206724.04     13884049.15      2206786.83     13883955.79
      2206901.29     13883945.85      2206948.31     13883894.03
      2206969.84     13883712.08      2206908.75     13883384.18
      2206972.44     13883067.18       2206978.5     13882776.45
      2207115.34     13882635.78      2207195.43     13882605.25
      2207233.22     13882527.86      2207321.75     13882567.07
      2207348.46     13882552.54      2207417.18     13882478.44
      2207376.97     13882418.91      2207382.37     13882368.63
      2207426.22     13882328.53      2207538.66     13882311.74
       2207623.8      13882164.5      2207623.64     13881934.65
      2207532.53     13881775.01      2207573.62     13881714.56
      2207575.35     13881504.84      2207524.49     13881399.88
      2207618.07     13881324.99      2207511.79     13881261.38
      2207426.05     13881164.57      2207423.62     13880984.66
       2207374.8     13880900.08        2207375.       13880125.

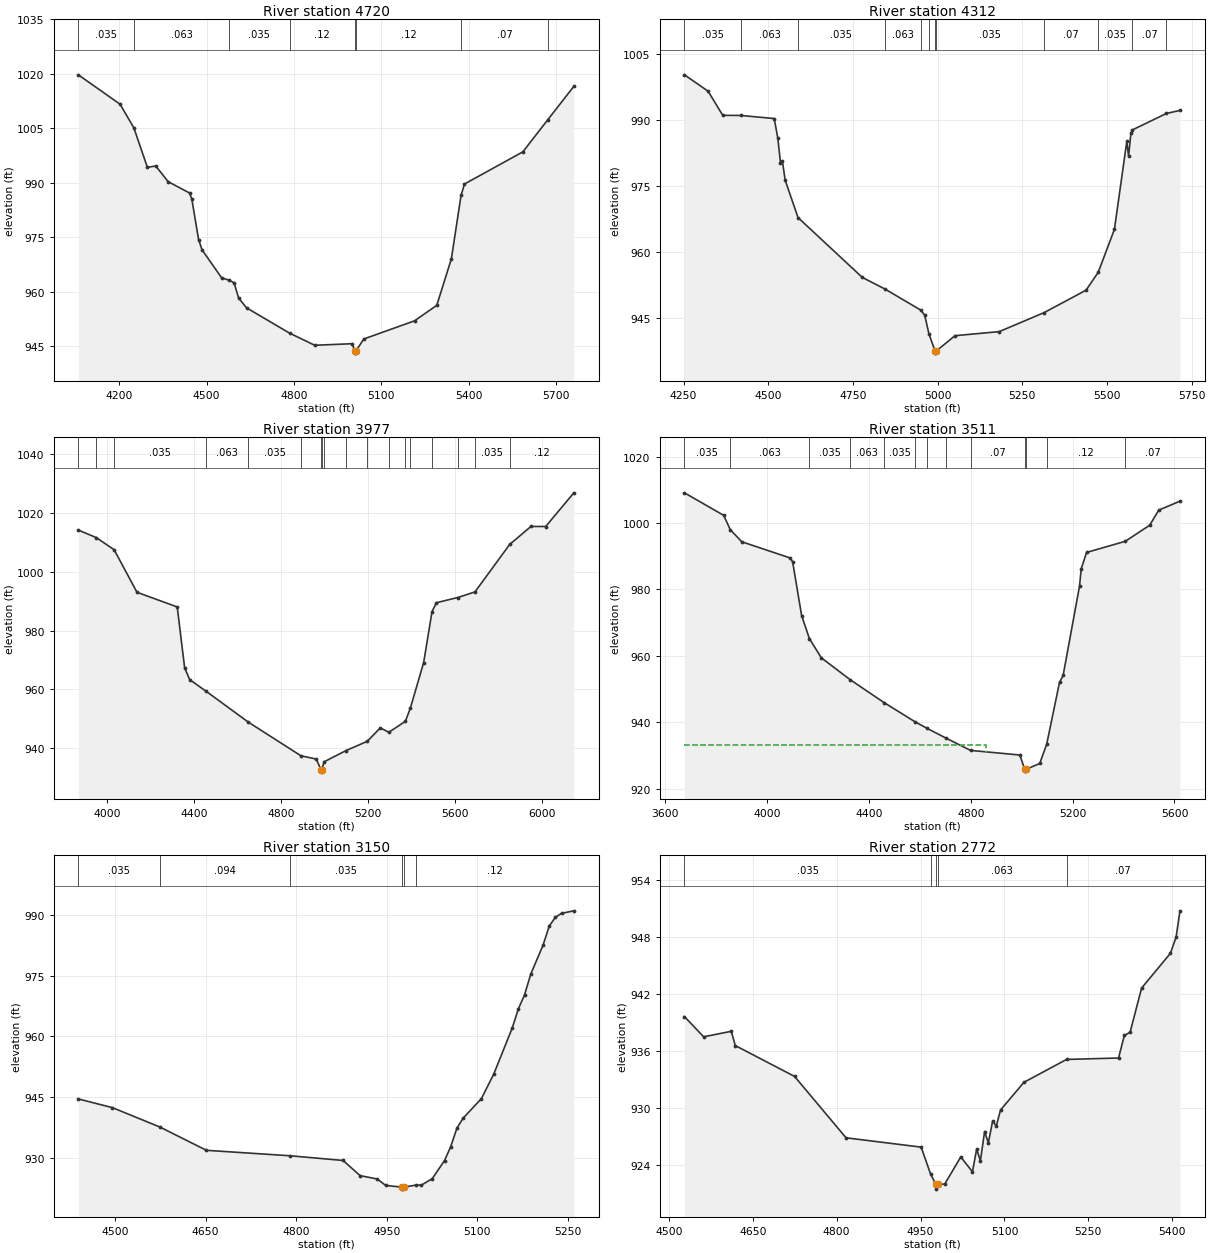
Type RM Length L Ch R = 1 ,4720    ,408,408,408
BEGIN DESCRIPTION:
Guadalupe Tributary 46 11.0
END DESCRIPTION:
XS GIS Cut Line= 3
      2207567.29     13884478.34      2206768.31      13883989.7
      2206019.97     13883834.11
#Sta/Elev= 30
  4059.6 1019.74    4203 1011.65  4250.3 1005.13  4296.7  994.27  4325.4  994.65
    4368  990.33  4441.5  987.21  4449.1   985.6  4472.4  974.41  4484.3  971.57
  4551.7  963.84  4577.3  963.23  4594.4  962.49  4609.8  958.31    4637  955.61
  4784.6  948.65  4871.1   945.3  5000.4  945.74  5007.8  943.64    5008  943.14
  5011.8  943.64  5039.5  947.03    5214  952.04    5290   956.3  5340.1  969.08
  5373.3  986.54  5385.1  989.69  5585.5  998.54  5671.7 1007.44  5760.5 1016.57
#Mann= 8 ,-1 , 0
  4059.6    .035       0  4250.3    .063       0  4577.3    .035       0
  4784.6     .12       0  5007.8     .05       0  5011.8     .12       0
  5373.3     .07       0  5671.7     .12       0
Bank Sta=5007.8,5011.8
XS Rating Curve= 0 ,0
Exp/Cntr=0.3,0.1

Type RM Length L Ch R = 1 ,4312    ,335,335,335
BEGIN DESCRIPTION:
Guadalupe Tributary 46 10.0
END DESCRIPTION:
XS GIS Cut Line= 3
      2207659.36     13884000.22      2206969.84     13883712.08
      2206274.29     13883543.89
#Sta/Elev= 30
  4252.7 1000.36  4322.5  996.63  4365.8  991.13  4419.7   991.1  4517.8   990.4
  4528.4  985.87  4536.2  980.33  4541.6   980.8  4550.1  976.34    4588  967.83
  4777.6  954.21    4844  951.58    4950  946.77  4961.9  945.62  4974.4  941.37
  4992.4  937.45  4992.7  936.95  4996.4  937.45  5051.3  940.92    5182  941.85
  5314.7  946.19  5438.3  951.29  5474.4  955.39    5522  965.14  5558.7  985.22
  5563.8  981.85  5570.8  987.09  5575.1  987.81  5675.7  991.56  5715.6  992.25
#Mann= 12 ,-1 , 0
  4252.7    .035       0  4419.7    .063       0    4588    .035       0
    4844    .063       0    4950     .12       0  4974.4    .035       0
  4992.4    .035       0  4996.4    .035       0  5314.7     .07       0
  5474.4    .035       0  5575.1     .07       0  5675.7    .035       0
Bank Sta=4992.4,4996.4
XS Rating Curve= 0 ,0
Exp/Cntr=0.3,0.1

Type RM Length L Ch R = 1 ,3977    ,466,466,466
BEGIN DESCRIPTION:
Guadalupe Tributary 46 9.0
END DESCRIPTION:
XS GIS Cut Line= 3
       2207940.8     13883848.78      2206908.75     13883384.18
      2205765.92     13883500.11
#Sta/Elev= 30
  3868.2 1014.25  3950.9 1011.69  4033.1 1007.55  4138.2  993.07  4323.4  988.08
  4357.5  967.37  4380.7  963.33  4457.8   959.3    4651  948.85  4892.6  937.42
  4963.6  936.29  4984.7  932.69    4985  932.19  4988.7  932.69  4999.2  935.35
  5098.7  939.13    5198  942.34    5258  946.91  5297.4  945.43  5373.4  949.13
  5396.7  953.73  5457.6  969.16  5496.1  986.53  5516.4  989.52  5614.4  991.29
  5693.6   993.2  5853.5 1009.36  5951.5 1015.49    6019 1015.46  6148.7 1026.93
#Mann= 18 ,-1 , 0
  3868.2    .035       0  3950.9    .063       0  4033.1    .035       0
  4457.8    .063       0    4651    .035       0  4892.6     .07       0
  4984.7     .05       0  4988.7     .07       0  4999.2     .12       0
  5098.7     .07       0    5198    .035       0  5297.4     .07       0
  5373.4    .035       0  5396.7     .07       0  5496.1    .035       0
  5614.4     .07       0  5693.6    .035       0  5853.5     .12       0
Bank Sta=4984.7,4988.7
XS Rating Curve= 0 ,0
Exp/Cntr=0.3,0.1

Type RM Length L Ch R = 1 ,3511    ,361,361,361
BEGIN DESCRIPTION:
Guadalupe Tributary 46 8.0
END DESCRIPTION:
XS GIS Cut Line= 3
      2208031.48     13883724.34        2206975.       13882925.
      2206510.78     13882511.61
#Sta/Elev= 30
  3675.2  1009.1  3829.5 1002.31  3855.1  998.01  3900.3  994.37  4090.9  989.48
  4100.1  988.34  4135.5  972.13    4166  965.21  4212.7  959.44  4325.7  952.87
  4459.3  945.95  4580.1  940.21  4629.1  938.16  4700.9  935.33  4798.9  931.56
  4992.7  930.17  5011.8  925.82  5012.1  925.32  5015.8  925.82  5070.7  927.62
  5097.9  933.37  5148.4  952.03  5162.6  954.12    5227  980.99  5233.7  986.22
  5254.6  991.15  5406.9  994.51  5502.9  999.36  5538.1 1003.89  5621.6 1006.59
#Mann= 13 ,-1 , 0
  3675.2    .035       0  3855.1    .063       0    4166    .035       0
  4325.7    .063       0  4459.3    .035       0  4580.1    .063       0
  4629.1     .07       0  4700.9     .12       0  4798.9     .07       0
  5011.8     .05       0  5015.8     .07       0  5097.9     .12       0
  5406.9     .07       0
#XS Ineff= 2 , 0
       0 4858.85  933.25               0
Permanent Ineff=
       F       F
Bank Sta=5011.8,5015.8
XS Rating Curve= 0 ,0
Exp/Cntr=0.3,0.1

Type RM Length L Ch R = 1 ,3150    ,378,378,378
BEGIN DESCRIPTION:
Guadalupe Tributary 46 7.0
END DESCRIPTION:
XS GIS Cut Line= 3
      2207525.03     13883025.03        2207125.       13882625.
      2206874.98       13882575.
#Sta/Elev= 30
  4439.1   944.5  4495.7  942.34  4574.2  937.55  4651.3  931.79    4789  930.45
  4877.6  929.28  4905.8  925.53  4934.1   924.7  4948.3   923.1  4974.5  922.69
  4974.8  922.19  4978.5  922.69  4998.7   923.2  5007.4  923.19  5025.2  924.77
  5045.6  929.25  5055.8  932.66    5066  937.21  5076.2   939.7  5106.8   944.6
  5127.2  950.66  5157.8  962.05    5168  966.81  5178.2  970.26  5188.4  975.36
  5208.8  982.53    5219  987.24  5229.2  989.42  5239.4  990.41  5259.8  991.03
#Mann= 6 ,-1 , 0
  4439.1    .035       0  4574.2    .094       0    4789    .035       0
  4974.5     .05       0  4978.5    .035       0  4998.7     .12       0
Bank Sta=4974.5,4978.5
XS Rating Curve= 0 ,0
Exp/Cntr=0.3,0.1

Type RM Length L Ch R = 1 ,2772    ,486,486,486
BEGIN DESCRIPTION:
Guadalupe Tributary 46 6.0
END DESCRIPTION:
XS GIS Cut Line= 4
      2207736.65      13882831.8       2207405.7     13882495.12
      2207289.86     13882392.27      2207038.32       13882331.
#Sta/Elev= 30
  4527.9  939.58  4562.2  937.45  4611.6  938.03  4618.8  936.53  4724.8  933.28
  4816.8  926.82  4951.1  925.84  4967.8  923.03  4977.3  921.92  4977.6  921.42
  4981.4  921.92  4993.2  921.95  5021.9  924.81  5042.8  923.24  5050.3  925.63
    5057   924.4  5064.5  927.48  5071.2  926.29  5078.8  928.57  5085.4  928.06
    5093  929.75  5134.8  932.66    5211  935.07    5304  935.22  5314.3  937.59
  5324.6  937.93  5345.2  942.58  5396.6  946.23  5406.9  947.95  5413.8  950.71
#Mann= 5 ,-1 , 0
  4527.9    .035       0  4967.8    .063       0  4977.3     .05       0
  4981.4    .063       0    5211     .07       0
Bank Sta=4977.3,4981.4
XS Rating Curve= 0 ,0
Exp/Cntr=0.3,0.1

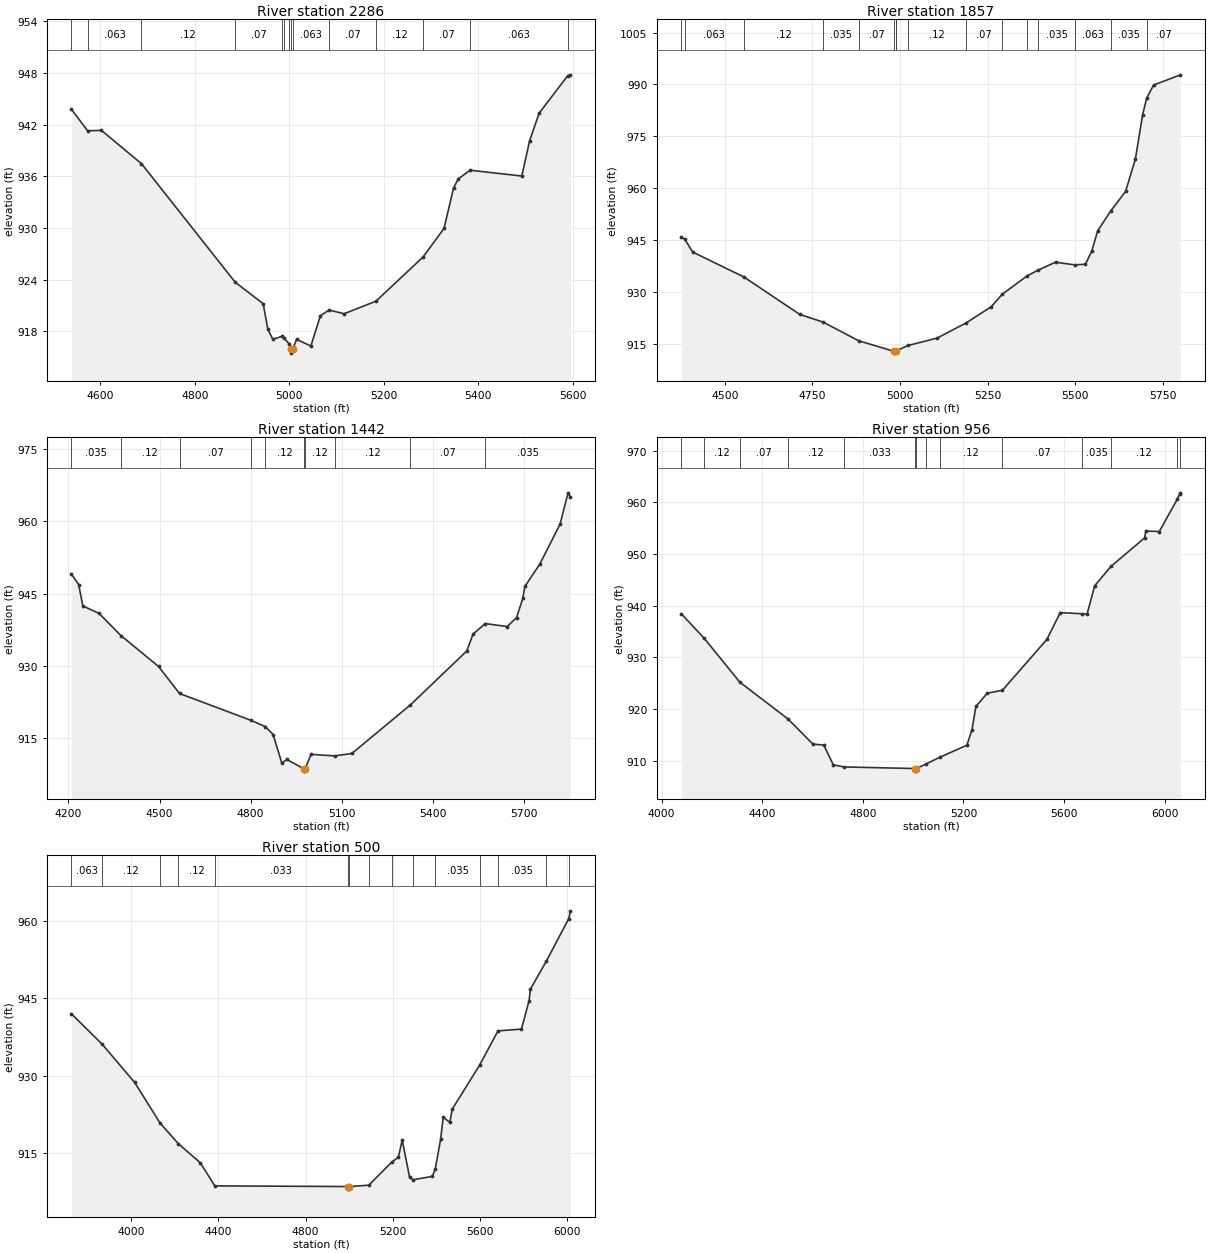
Type RM Length L Ch R = 1 ,2286    ,429,429,429
BEGIN DESCRIPTION:
Guadalupe Tributary 46 5.0
END DESCRIPTION:
XS GIS Cut Line= 3
      2208076.77     13882238.22        2207625.       13882175.
      2207029.08      13882241.6
#Sta/Elev= 30
    4539  943.77  4573.1  941.29  4602.4  941.33  4687.1  937.47  4885.3  923.72
  4944.7  921.22  4954.4  918.26  4964.9   917.1  4984.4  917.43  4988.6  917.24
  5000.2  916.52    5003  915.99  5003.3  915.49  5007.5  915.99  5015.3  917.09
  5045.5  916.31  5065.6  919.82  5083.8  920.49  5115.9  920.06  5183.3  921.52
  5282.8  926.64  5327.2  929.96  5347.4  934.65  5357.4  935.71  5382.3  936.71
  5491.8  936.04  5508.3  940.13  5528.5  943.33  5589.1  947.69  5594.8  947.78
#Mann= 14 ,-1 , 0
    4539    .035       0  4573.1    .063       0  4687.1     .12       0
  4885.3     .07       0  4984.4    .063       0  4988.6    .035       0
  5000.2    .063       0    5003    .035       0  5007.5    .063       0
  5083.8     .07       0  5183.3     .12       0  5282.8     .07       0
  5382.3    .063       0  5589.1     .12       0
Bank Sta=5003,5007.5
XS Rating Curve= 0 ,0
Exp/Cntr=0.3,0.1

Type RM Length L Ch R = 1 ,1857    ,415,415,415
BEGIN DESCRIPTION:
Guadalupe Tributary 46 4.0
END DESCRIPTION:
XS GIS Cut Line= 3
      2208135.82     13881936.14        2207525.       13881775.
      2206760.87     13881981.27
#Sta/Elev= 30
  4376.4  945.74  4386.1  945.17  4408.3   941.5  4554.2   934.3  4713.7  923.46
    4781   921.2  4882.1  915.81  4983.1  912.75  4983.4  912.25  4987.7  912.75
  4989.5  912.92  5022.7  914.46  5105.3  916.59  5188.6  921.01  5259.7  925.66
  5291.5   929.3  5362.3   934.6  5394.5   936.3  5443.2  938.56  5497.4  937.79
  5528.7  937.97  5546.7  941.79  5563.4  947.62  5600.3  953.31  5643.2  959.06
    5671   968.4  5691.7  981.21  5703.2  986.01    5723  989.81  5799.6  992.77
#Mann= 16 ,-1 , 0
  4376.4    .035       0  4386.1    .063       0  4554.2     .12       0
    4781    .035       0  4882.1     .07       0  4983.1     .05       0
  4987.7     .07       0  4989.5     .12       0  5022.7     .12       0
  5188.6     .07       0  5291.5    .035       0  5362.3     .07       0
  5394.5    .035       0  5497.4    .063       0  5600.3    .035       0
  5703.2     .07       0
Bank Sta=4983.1,4987.7
XS Rating Curve= 0 ,0
Exp/Cntr=0.3,0.1

Type RM Length L Ch R = 1 ,1442    ,486,486,486
BEGIN DESCRIPTION:
Guadalupe Tributary 46 3.0
END DESCRIPTION:
XS GIS Cut Line= 3
      2208215.66      13881776.4      2207521.25       13881391.
      2206691.35     13881571.57
#Sta/Elev= 30
  4210.1  949.04  4233.7  946.89  4247.4  942.45  4301.2  940.88  4373.1  936.29
  4496.8  929.89  4565.9  924.28  4801.7   918.7  4848.9  917.39  4874.2  915.77
  4903.1  909.78  4919.1   910.6  4974.8  908.67  4975.2  908.17  4979.4  908.67
  4999.3  911.65  5076.9  911.33  5133.5  911.83  5326.3  921.91    5512   933.1
  5532.6   936.6  5572.7  938.79  5645.2  938.17  5675.9  940.03  5696.4     944
  5703.3   946.5  5752.4  951.12  5819.2  959.41  5845.5  965.92  5853.6  965.02
#Mann= 10 ,-1 , 0
  4210.1    .035       0  4373.1     .12       0  4565.9     .07       0
  4801.7     .12       0  4848.9     .12       0  4974.8     .05       0
  4979.4     .12       0  5076.9     .12       0  5326.3     .07       0
  5572.7    .035       0
Bank Sta=4974.8,4979.4
XS Rating Curve= 0 ,0
Exp/Cntr=0.3,0.1

Type RM Length L Ch R = 1 ,956     ,456,456,456
BEGIN DESCRIPTION:
Guadalupe Tributary 46 2.0
END DESCRIPTION:
XS GIS Cut Line= 3
      2208228.43     13881514.56      2207428.47     13881064.58
      2206379.43     13881255.49
#Sta/Elev= 30
  4078.7  938.42    4169  933.71  4310.8  925.22  4502.6  918.09  4601.3  913.24
  4644.8  913.05  4682.3  909.23  4724.9  908.82  5007.9  908.51  5008.2  908.01
  5012.6  908.51  5052.7  909.42  5107.4  910.73  5213.5  913.01  5233.8  916.01
  5249.6  920.55  5294.8  923.09  5354.8  923.65  5531.6  933.49  5584.9  938.68
  5673.2  938.45  5691.2  938.36  5721.7  943.86  5786.3  947.61  5920.2  953.13
  5925.3  954.46  5978.6  954.36  6050.5  960.65  6059.9  961.63  6062.8  961.85
#Mann= 14 ,-1 , 0
  4078.7    .063       0    4169     .12       0  4310.8     .07       0
  4502.6     .12       0  4724.9    .033       0  5007.9    .033       0
  5012.6    .033       0  5052.7     .12       0  5107.4     .12       0
  5354.8     .07       0  5673.2    .035       0  5786.3     .12       0
  6050.5    .035       0  6059.9     .12       0
Bank Sta=5007.9,5012.6
XS Rating Curve= 0 ,0
Exp/Cntr=0.3,0.1

Type RM Length L Ch R = 1 ,500     ,0,0,0
BEGIN DESCRIPTION:
Guadalupe Tributary 46 1.0
END DESCRIPTION:
XS GIS Cut Line= 3
      2208382.37      13881404.9        2207375.       13880625.
      2206385.79     13880852.82
#Sta/Elev= 30
    3726  941.99    3866  936.14  4015.8  928.68  4132.9  920.77  4216.4  916.79
  4316.4  913.12  4383.5  908.61  4994.4  908.48  4994.7  907.98  4999.3  908.48
  5089.6  908.74  5195.2  913.22  5225.7  914.19  5243.1  917.51  5277.1  910.27
  5293.3   909.8  5381.8  910.46  5395.1  911.98  5419.4  917.66    5431  921.94
  5461.8  920.92  5472.5  923.49  5598.8  932.09  5682.4  938.69  5790.1  939.04
  5825.2  944.56  5831.2  946.79  5904.3  952.23  6006.2  960.41  6015.1  961.99
#Mann= 15 ,-1 , 0
    3726    .063       0    3866     .12       0  4132.9     .07       0
  4216.4     .12       0  4383.5    .033       0  4994.4    .033       0
  4999.3    .033       0  5089.6     .07       0  5195.2     .12       0
  5293.3     .07       0  5395.1    .035       0  5598.8     .07       0
  5682.4    .035       0  5904.3     .07       0  6006.2     .12       0
Bank Sta=4994.4,4999.3
XS Rating Curve= 0 ,0
Exp/Cntr=0.3,0.1

Chan Stop Cuts=-1
Use User Specified Reach Order=0
Composite Channel Slope=5