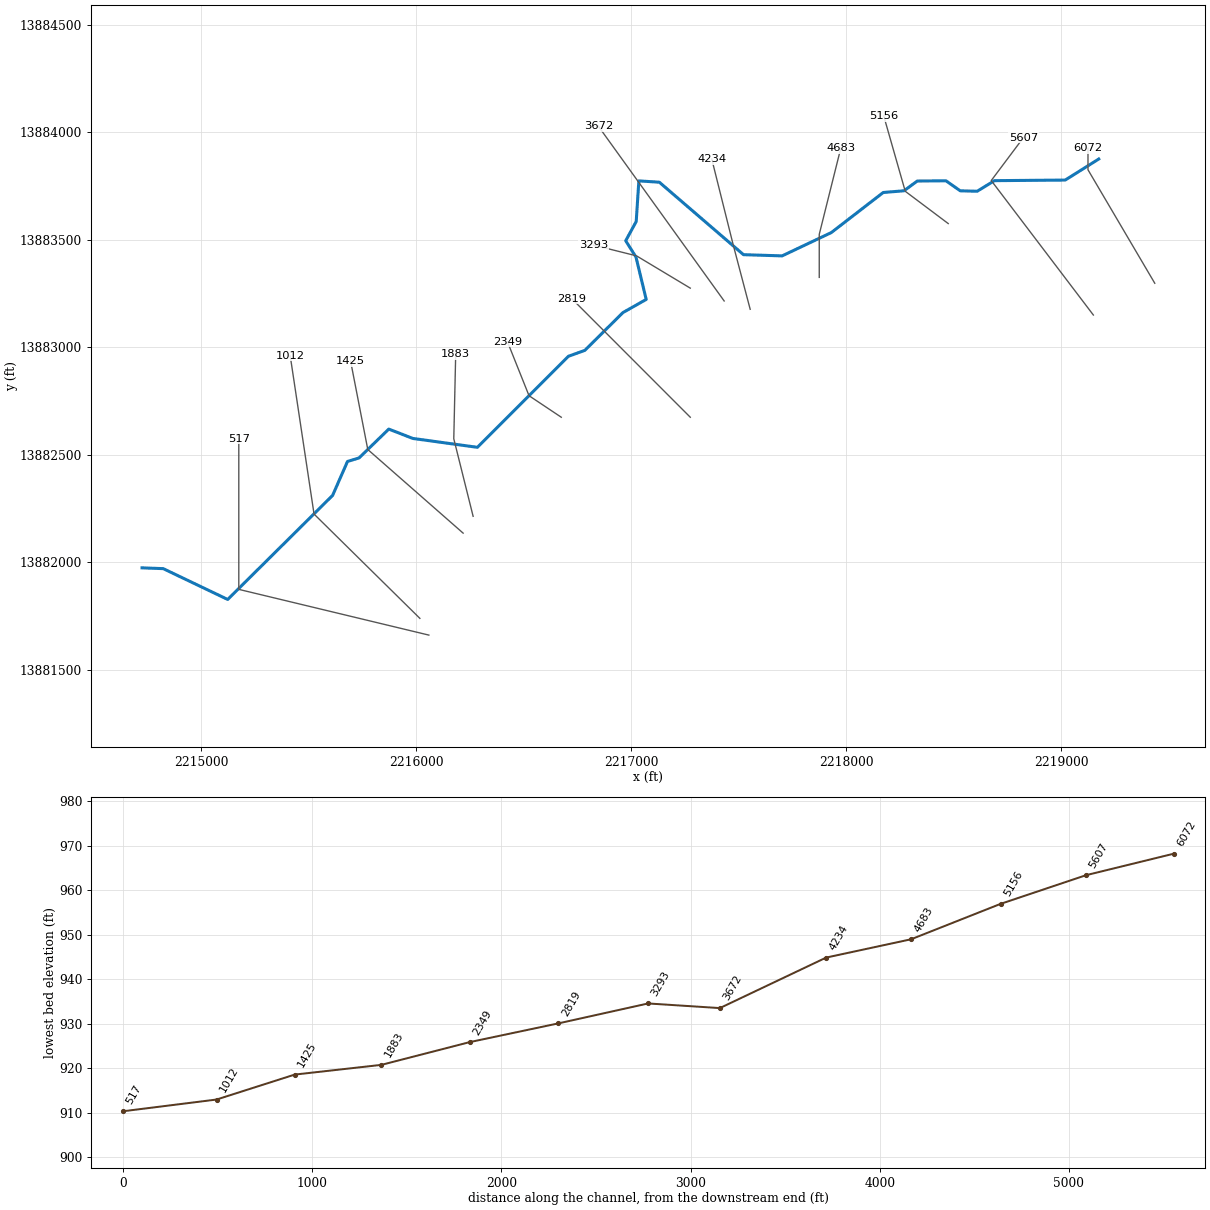
--- Guadalupe Tributary 49.prj (project) ---

Proj Title=Guadalupe Tributary 49 Base Level Engineering
Current Plan=p01
Default Exp/Contr=0.3,0.1
English Units
Geom File=g01
Flow File=f01
Plan File=p01
BEGIN DESCRIPTION:
Guadalupe Tributary 49
END DESCRIPTION:

--- Guadalupe Tributary 49.p01 (plan) ---

Plan Title=Multiple Run
Short Identifier=Multiple
Geom File=g01
Flow File=f01
Subcritical Flow
K Sum by GR= 0
Std Step Tol= 0.01
Critical Tol= 0.01
Num of Std Step Trials= 20
Max Error Tol= 0.3
Flow Tol Ratio= 0.001
Split Flow NTrial= 30
Split Flow Tol= 0.02
Split Flow Ratio= 0.02
Log Output Level= 0
Friction Slope Method= 1
Unsteady Friction Slope Method= 2
Unsteady Bridges Friction Slope Method= 1
Parabolic Critical Depth
Global Vel Dist=  1 , 1 , 1
Global Log Level= 0
CheckData=True
Encroach Param= -1, 0, 0, 0
BEGIN DESCRIPTION:
Multiple Run
END DESCRIPTION:

--- Guadalupe Tributary 49.f01 (steady flow) ---

Flow Title=Multiple
Number of Profiles=7
Profile Names=10-year,25-year,50-year,1pct_min,100-year,1pct_plu,500-year
River Rch & RM= Guadalupe Tribut,Reach-1,6072
    1377    2370    3331    2268    4526    9030    8263
River Rch & RM= Guadalupe Tribut,Reach-1,5156
    1794    3118    4410    3017    6020   12012   11105
Boundary for River Rch & Prof#=Guadalupe Tribut,Reach-1,1
Up Type=0
Dn Type=3
Dn Slope=0.005
Boundary for River Rch & Prof#=Guadalupe Tribut,Reach-1,2
Up Type=0
Dn Type=3
Dn Slope=0.005
Boundary for River Rch & Prof#=Guadalupe Tribut,Reach-1,3
Up Type=0
Dn Type=3
Dn Slope=0.005
Boundary for River Rch & Prof#=Guadalupe Tribut,Reach-1,4
Up Type=0
Dn Type=3
Dn Slope=0.005
Boundary for River Rch & Prof#=Guadalupe Tribut,Reach-1,5
Up Type=0
Dn Type=3
Dn Slope=0.005
Boundary for River Rch & Prof#=Guadalupe Tribut,Reach-1,6
Up Type=0
Dn Type=3
Dn Slope=0.005
Boundary for River Rch & Prof#=Guadalupe Tribut,Reach-1,7
Up Type=0
Dn Type=3
Dn Slope=0.005

--- Guadalupe Tributary 49.g01 (geometry) ---

Geom Title=Existing Conditions

River Reach=Guadalupe Tribut,Reach-1
Reach XY= 30
      2219175.00     13883875.00      2219019.08     13883777.23
      2218690.22     13883774.48      2218609.73     13883725.38
      2218530.98     13883727.17      2218464.49     13883773.79
      2218330.94     13883772.75      2218269.02     13883727.36
      2218172.58     13883719.46      2217931.05     13883533.16
      2217702.32     13883424.89      2217522.55     13883430.46
      2217131.12     13883767.26      2217035.84     13883773.41
      2217023.60     13883584.66      2216974.72     13883495.18
      2217022.51     13883419.44      2217070.01     13883222.45
      2216961.80     13883161.36      2216784.68     13882985.78
      2216708.33     13882958.35      2216284.68     13882535.19
      2215984.65     13882576.40      2215872.70     13882619.91
      2215734.41     13882485.89      2215680.59     13882469.39
      2215611.38     13882311.79      2215123.37     13881828.12
      2214823.50     13881971.37      2214725.00     13881975.00

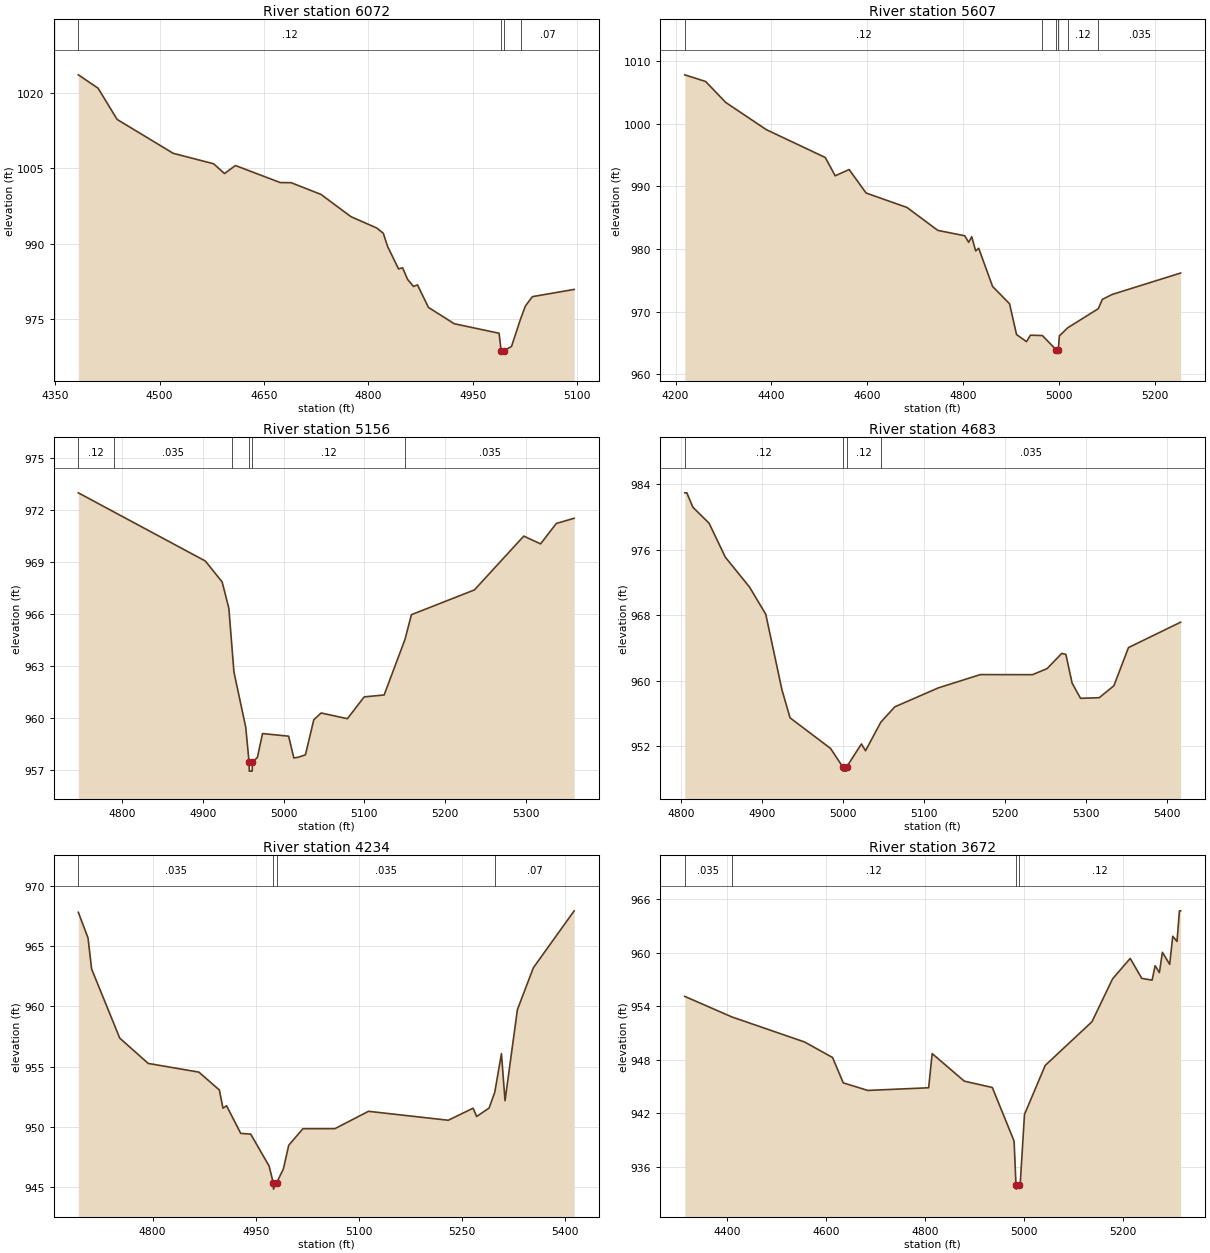
Type RM Length L Ch R = 1,6072,465,465,465
BEGIN DESCRIPTION:
Guadalupe Tributary 49 13.0
END DESCRIPTION:
XS GIS Cut Line= 3
      2219435.67     13883297.59      2219125.00     13883825.00
      2219125.00     13883924.99
#Sta/Elev= 30
  4383.3 1023.67  4411.7 1021.00  4439.0 1014.78  4519.6 1008.02  4577.6 1005.94
  4593.2 1003.99  4608.9 1005.59  4673.3 1002.19  4688.9 1002.17  4731.8  999.83
  4774.9  995.39  4811.9  993.13  4821.3  992.08  4827.5  989.45  4843.2  984.98
  4849.0  985.20  4856.1  982.91  4864.6  981.49  4870.4  981.79  4886.1  977.31
  4923.2  974.05  4987.6  972.15  4990.5  968.69  4990.8  968.19  4994.5  968.69
  5005.4  969.51  5018.4  974.98  5025.4  977.59  5035.4  979.45  5095.4  980.89
#Mann=4,-1,0
  4383.3    0.12       0  4990.5    0.05       0  4994.5    0.12       0
  5018.4    0.07       0
Bank Sta=4990.5,4994.5
Exp/Cntr=0.3,0.1

Type RM Length L Ch R = 1,5607,451,451,451
BEGIN DESCRIPTION:
Guadalupe Tributary 49 12.0
END DESCRIPTION:
XS GIS Cut Line= 3
      2219149.99     13883150.01      2218675.00     13883775.00
      2218825.00     13883975.00
#Sta/Elev= 30
  4219.3 1007.86  4262.9 1006.79  4304.6 1003.45  4389.8  999.08  4512.5  994.64
  4533.3  991.71  4562.4  992.71  4597.7  988.96  4683.0  986.65  4747.5  982.98
  4803.7  982.12  4811.9  981.07  4818.2  981.97  4826.5  979.70  4832.8  980.12
  4861.8  974.01  4897.2  971.25  4911.8  966.32  4932.6  965.19  4940.8  966.22
  4965.7  966.16  4995.0  963.85  4995.3  963.35  4999.0  963.85  5001.2  966.11
  5018.6  967.40  5082.5  970.46  5090.8  971.94  5111.6  972.74  5254.3  976.16
#Mann=6,-1,0
  4219.3    0.12       0  4965.7   0.035       0  4995.0   0.035       0
  4999.0   0.035       0  5018.6    0.12       0  5082.5   0.035       0
Bank Sta=4995,4999
Exp/Cntr=0.3,0.1

Type RM Length L Ch R = 1,5156,473,473,473
BEGIN DESCRIPTION:
Guadalupe Tributary 49 11.0
END DESCRIPTION:
XS GIS Cut Line= 3
      2218474.97     13883575.02      2218275.00     13883725.00
      2218174.99     13884075.03
#Sta/Elev= 30
  4745.8  973.00  4789.7  971.90  4903.1  969.06  4923.9  967.85  4932.2  966.33
  4935.5  964.40  4938.5  962.65  4953.1  959.46  4957.3  957.42  4957.5  956.92
  4961.1  956.92  4961.4  957.42  4967.6  957.72  4973.9  959.09  5006.2  958.94
  5012.7  957.68  5017.9  957.72  5027.0  957.86  5037.4  959.89  5046.5  960.28
  5079.0  959.95  5099.8  961.21  5124.5  961.32  5150.3  964.53  5158.3  965.96
  5236.3  967.39  5297.4  970.50  5318.2  970.05  5337.7  971.23  5359.8  971.53
#Mann=6,-1,0
  4745.8    0.12       0  4789.7   0.035       0  4935.5    0.12       0
  4957.3    0.05       0  4961.4    0.12       0  5150.3   0.035       0
Bank Sta=4957.3,4961.4
Exp/Cntr=0.3,0.1

Type RM Length L Ch R = 1,4683,449,449,449
BEGIN DESCRIPTION:
Guadalupe Tributary 49 10.0
END DESCRIPTION:
XS GIS Cut Line= 3
      2217875.00     13883324.96      2217875.00     13883525.00
      2217974.99     13883924.95
#Sta/Elev= 30
  4805.0  982.96  4807.5  982.96  4815.0  981.20  4835.0  979.25  4855.0  975.11
  4885.0  971.44  4905.0  968.13  4925.0  958.89  4935.0  955.48  4985.0  951.74
  5000.2  949.47  5000.5  948.97  5004.5  948.97  5004.8  949.47  5023.1  952.29
  5028.2  951.46  5047.0  954.94  5064.3  956.82  5118.4  959.15  5170.0  960.76
  5234.4  960.75  5252.4  961.49  5270.5  963.35  5275.6  963.23  5283.3  959.72
  5293.7  957.86  5316.8  957.94  5334.9  959.40  5352.9  964.06  5417.3  967.16
#Mann=4,-1,0
  4805.0    0.12       0  5000.2    0.05       0  5004.8    0.12       0
  5047.0   0.035       0
Bank Sta=5000.2,5004.8
Exp/Cntr=0.3,0.1

Type RM Length L Ch R = 1,4234,562,562,562
BEGIN DESCRIPTION:
Guadalupe Tributary 49 9.0
END DESCRIPTION:
XS GIS Cut Line= 3
      2217553.70     13883176.75      2217475.00     13883475.00
      2217374.99     13883875.03
#Sta/Elev= 30
  4692.1  967.81  4706.2  965.68  4711.4  963.11  4752.3  957.38  4793.7  955.28
  4867.3  954.56  4897.1  953.08  4902.4  951.57  4907.6  951.77  4928.2  949.48
  4942.7  949.42  4969.5  946.77  4975.5  945.36  4975.8  944.86  4980.2  945.36
  4990.2  946.54  4998.0  948.50  5018.6  949.87  5065.0  949.87  5113.9  951.31
  5229.9  950.57  5266.0  951.57  5271.1  950.88  5289.2  951.58  5297.5  952.89
  5307.2  956.09  5312.4  952.19  5330.4  959.74  5353.6  963.21  5412.9  967.93
#Mann=4,-1,0
  4692.1   0.035       0  4975.5   0.035       0  4980.2   0.035       0
  5297.5    0.07       0
Bank Sta=4975.5,4980.2
Exp/Cntr=0.3,0.1

Type RM Length L Ch R = 1,3672,379,379,379
BEGIN DESCRIPTION:
Guadalupe Tributary 49 8.0
END DESCRIPTION:
XS GIS Cut Line= 2
      2217432.67     13883215.33      2216847.16     13884027.96
#Sta/Elev= 30
  4314.5  955.12  4409.5  952.82  4556.5  950.01  4613.0  948.27  4634.6  945.43
  4684.2  944.58  4807.1  944.88  4814.2  948.71  4879.2  945.62  4935.7  944.91
  4979.7  938.90  4983.5  934.02  4983.9  933.52  4988.6  934.02  4992.2  934.21
  5000.7  941.89  5042.5  947.38  5137.0  952.28  5178.7  957.09  5214.3  959.38
  5237.6  957.14  5258.5  956.94  5264.6  958.56  5273.2  957.79  5279.3  960.06
  5294.0  958.71  5300.2  961.86  5308.8  961.28  5313.7  964.71  5316.1  964.71
#Mann=4,-1,0
  4314.5   0.035       0  4409.5    0.12       0  4983.5    0.05       0
  4988.6    0.12       0
Bank Sta=4983.5,4988.6
Exp/Cntr=0.3,0.1

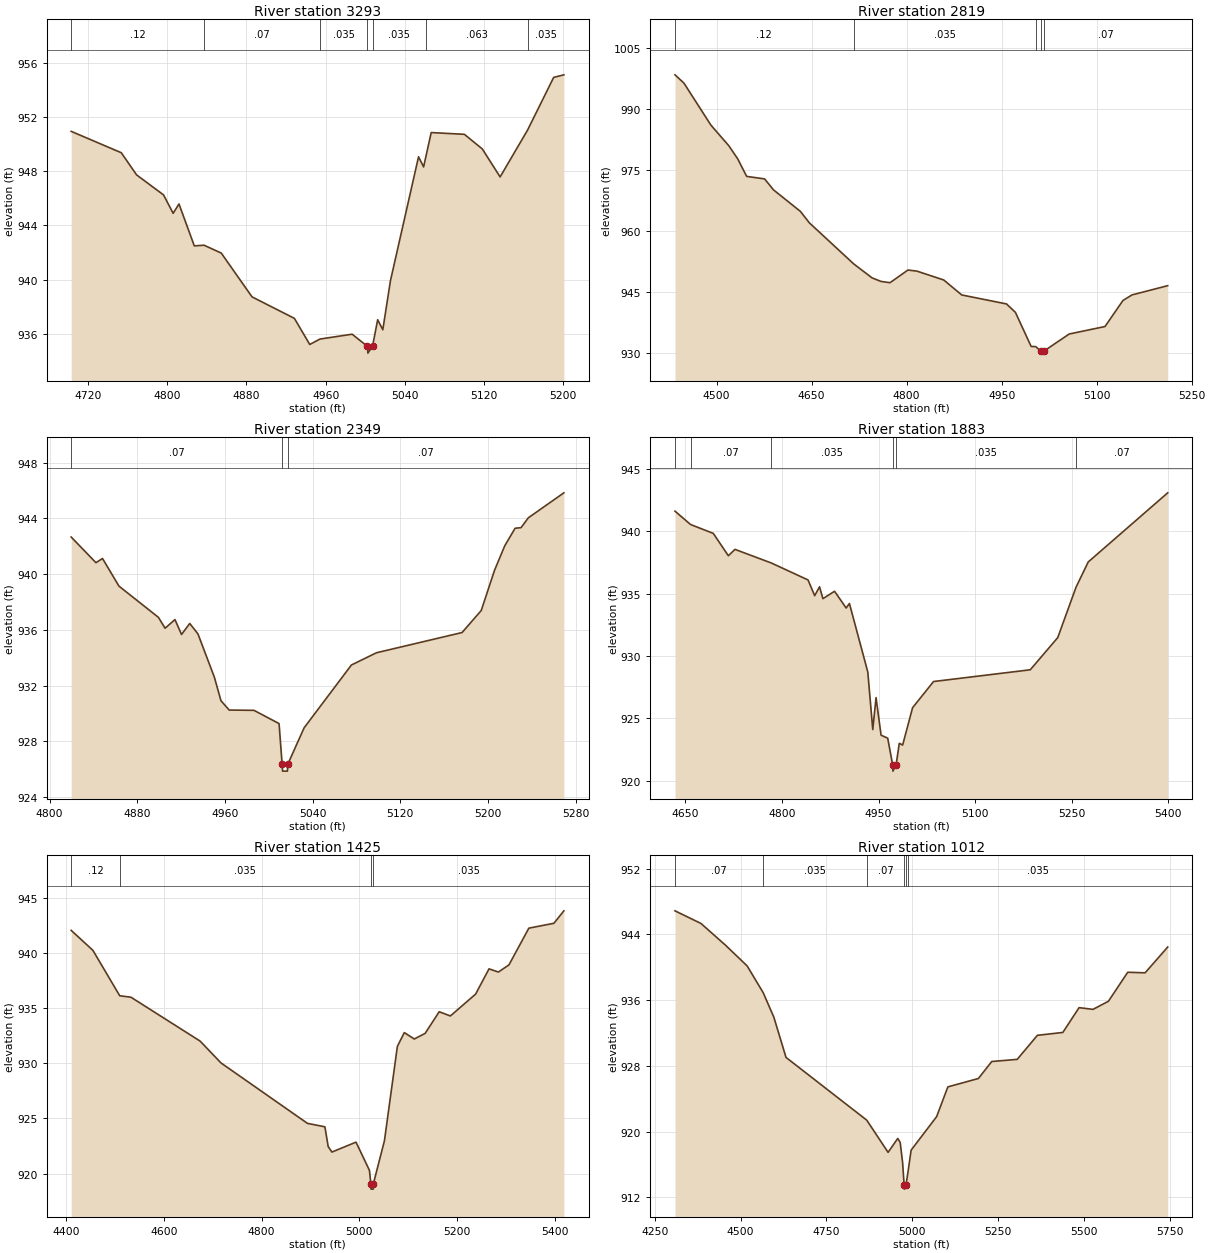
Type RM Length L Ch R = 1,3293,474,474,474
BEGIN DESCRIPTION:
Guadalupe Tributary 49 7.0
END DESCRIPTION:
XS GIS Cut Line= 3
      2217275.03     13883274.98      2217025.00     13883425.00
      2216825.04     13883474.99
#Sta/Elev= 30
  4702.9  950.96  4753.5  949.38  4769.0  947.74  4796.2  946.26  4805.9  944.90
  4811.8  945.59  4827.3  942.49  4837.1  942.54  4854.5  941.96  4885.6  938.72
  4928.4  937.13  4943.9  935.20  4954.2  935.60  4986.7  935.96  5002.2  935.06
  5002.6  934.56  5007.3  935.06  5012.5  937.03  5017.7  936.29  5025.4  939.91
  5053.8  949.08  5058.9  948.33  5061.6  949.22  5066.6  950.87  5100.1  950.74
  5118.2  949.66  5136.2  947.59  5163.9  951.05  5190.3  954.95  5200.6  955.14
#Mann=7,-1,0
  4702.9    0.12       0  4837.1    0.07       0  4954.2   0.035       0
  5002.2   0.035       0  5007.3   0.035       0  5061.6   0.063       0
  5163.9   0.035       0
Bank Sta=5002.2,5007.3
Exp/Cntr=0.3,0.1

Type RM Length L Ch R = 1,2819,470,470,470
BEGIN DESCRIPTION:
Guadalupe Tributary 49 6.0
END DESCRIPTION:
XS GIS Cut Line= 3
      2217275.01     13882674.99      2216875.00     13883075.00
      2216725.02     13883224.98
#Sta/Elev= 30
  4434.3  998.49  4448.5  996.43  4490.9  986.14  4519.2  981.07  4533.3  977.84
  4547.4  973.53  4575.7  972.91  4589.9  970.20  4632.3  964.92  4646.4  962.11
  4716.4  952.02  4745.4  948.58  4759.6  947.71  4773.7  947.40  4802.0  950.51
  4816.1  950.25  4858.6  948.06  4886.9  944.39  4957.6  942.18  4971.7  940.11
  4996.5  931.73  5003.8  931.69  5011.6  930.59  5011.9  930.09  5016.7  930.59
  5056.6  934.79  5113.1  936.63  5141.4  943.02  5155.6  944.39  5212.1  946.67
#Mann=5,-1,0
  4434.3    0.12       0  4716.4   0.035       0  5003.8    0.07       0
  5011.6   0.035       0  5016.7    0.07       0
Bank Sta=5011.6,5016.7
Exp/Cntr=0.3,0.1

Type RM Length L Ch R = 1,2349,466,466,466
BEGIN DESCRIPTION:
Guadalupe Tributary 49 5.0
END DESCRIPTION:
XS GIS Cut Line= 3
      2216675.02     13882674.99      2216525.00     13882775.00
      2216424.98     13883025.04
#Sta/Elev= 30
  4819.7  942.66  4842.3  940.82  4848.3  941.12  4863.3  939.14  4899.3  936.90
  4905.4  936.12  4914.4  936.74  4920.4  935.67  4927.9  936.46  4935.4  935.71
  4950.4  932.60  4956.4  930.92  4963.9  930.25  4986.5  930.23  5009.4  929.28
  5012.2  926.37  5012.6  925.87  5017.0  925.87  5017.4  926.37  5032.3  928.98
  5075.4  933.48  5098.3  934.36  5176.4  935.81  5193.9  937.39  5206.0  940.27
  5215.4  942.04  5224.8  943.29  5230.2  943.33  5236.9  944.04  5269.3  945.83
#Mann=3,-1,0
  4819.7    0.07       0  5012.2    0.05       0  5017.4    0.07       0
Bank Sta=5012.2,5017.4
Exp/Cntr=0.3,0.1

Type RM Length L Ch R = 1,1883,458,458,458
BEGIN DESCRIPTION:
Guadalupe Tributary 49 4.0
END DESCRIPTION:
XS GIS Cut Line= 3
      2216264.94     13882214.63      2216175.00     13882575.00
      2216183.92     13882968.37
#Sta/Elev= 30
  4634.0  941.60  4658.2  940.53  4693.4  939.82  4716.8  938.03  4727.1  938.54
  4783.4  937.45  4840.5  936.09  4850.8  934.83  4858.4  935.54  4863.6  934.59
  4881.7  935.18  4899.7  933.84  4904.8  934.20  4933.3  928.71  4941.0  924.10
  4946.1  926.66  4953.9  923.65  4964.2  923.41  4971.9  921.27  4972.3  920.77
  4977.2  921.27  4982.2  923.00  4987.4  922.86  5002.8  925.85  5035.4  927.95
  5185.5  928.89  5228.2  931.47  5256.5  935.50  5275.5  937.53  5398.9  943.07
#Mann=6,-1,0
  4634.0    0.12       0  4658.2    0.07       0  4783.4   0.035       0
  4971.9   0.035       0  4977.2   0.035       0  5256.5    0.07       0
Bank Sta=4971.9,4977.2
Exp/Cntr=0.3,0.1

Type RM Length L Ch R = 1,1425,413,413,413
BEGIN DESCRIPTION:
Guadalupe Tributary 49 3.0
END DESCRIPTION:
XS GIS Cut Line= 3
      2216218.47     13882136.38      2215775.00     13882525.00
      2215695.16     13882935.26
#Sta/Elev= 30
  4410.5  942.05  4454.9  940.24  4509.8  936.12  4532.7  935.99  4674.2  932.01
  4716.9  930.03  4893.8  924.55  4929.4  924.24  4936.1  922.45  4943.7  921.95
  4993.0  922.85  5020.5  920.29  5023.3  919.09  5023.7  918.59  5028.2  918.59
  5028.6  919.09  5051.1  922.97  5077.6  931.53  5091.8  932.78  5112.2  932.20
  5134.4  932.71  5163.1  934.67  5186.0  934.29  5237.6  936.27  5265.0  938.56
  5284.2  938.27  5305.8  938.92  5346.5  942.25  5397.7  942.69  5418.1  943.82
#Mann=4,-1,0
  4410.5    0.12       0  4509.8   0.035       0  5023.3   0.035       0
  5028.6   0.035       0
Bank Sta=5023.3,5028.6
Exp/Cntr=0.3,0.1

Type RM Length L Ch R = 1,1012,495,495,495
BEGIN DESCRIPTION:
Guadalupe Tributary 49 2.0
END DESCRIPTION:
XS GIS Cut Line= 3
      2216017.23     13881740.29      2215525.00     13882225.00
      2215414.22     13882960.08
#Sta/Elev= 30
  4309.2  946.88  4384.8  945.34  4455.5  942.72  4519.2  940.17  4565.9  936.91
  4596.9  933.93  4632.3  929.03  4867.3  921.39  4929.4  917.47  4957.6  919.16
  4964.7  918.67  4971.8  916.18  4976.1  913.49  4976.6  912.99  4981.5  913.49
  4987.8  915.20  4996.5  917.74  5070.8  921.82  5103.4  925.44  5192.2  926.46
  5231.2  928.53  5305.2  928.79  5364.1  931.72  5438.1  932.07  5485.4  935.09
  5525.9  934.88  5570.9  935.87  5627.0  939.40  5677.6  939.33  5743.4  942.47
#Mann=6,-1,0
  4309.2    0.07       0  4565.9   0.035       0  4867.3    0.07       0
  4976.1   0.035       0  4981.5    0.07       0  4987.8   0.035       0
Bank Sta=4976.1,4981.5
Exp/Cntr=0.3,0.1

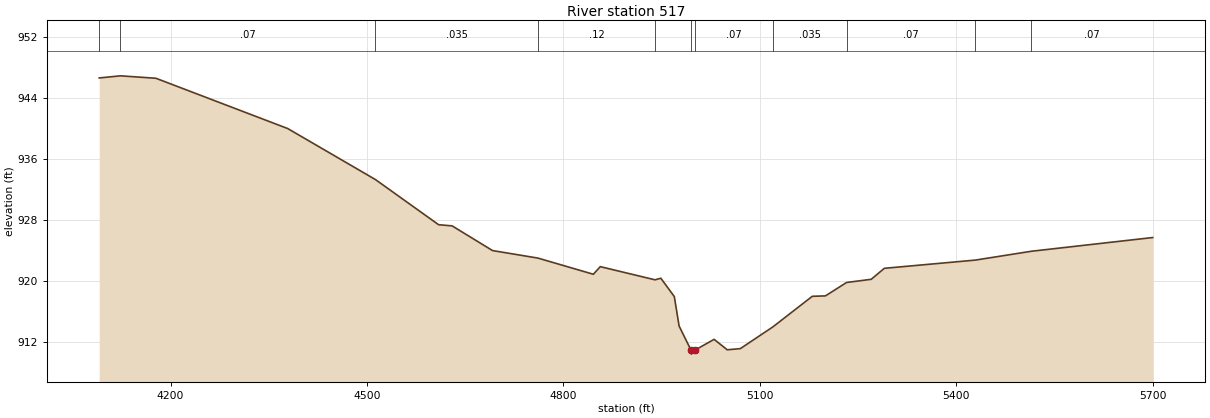
Type RM Length L Ch R = 1,517,0,0,0
BEGIN DESCRIPTION:
Guadalupe Tributary 49 1.0
END DESCRIPTION:
XS GIS Cut Line= 3
      2216059.16     13881662.46      2215175.00     13881875.00
      2215175.00     13882574.95
#Sta/Elev= 30
  4091.0  946.59  4123.4  946.87  4177.6  946.55  4379.0  939.95  4512.9  933.26
  4609.5  927.33  4630.1  927.18  4691.8  923.94  4761.3  922.95  4845.8  920.83
  4856.4  921.83  4940.1  920.10  4948.9  920.31  4969.5  917.90  4976.8  914.04
  4995.1  910.85  4995.5  910.35  5000.5  910.85  5030.3  912.29  5050.3  910.92
  5070.3  911.07  5120.0  913.92  5180.3  917.94  5200.3  917.99  5232.6  919.75
  5270.3  920.17  5290.3  921.61  5429.4  922.69  5515.0  923.85  5700.3  925.65
#Mann=11,-1,0
  4091.0   0.035       0  4123.4    0.07       0  4512.9   0.035       0
  4761.3    0.12       0  4940.1    0.07       0  4995.1    0.05       0
  5000.5    0.07       0  5120.0   0.035       0  5232.6    0.07       0
  5429.4   0.035       0  5515.0    0.07       0
Bank Sta=4995.1,5000.5
Exp/Cntr=0.3,0.1

Chan Stop Cuts=-1