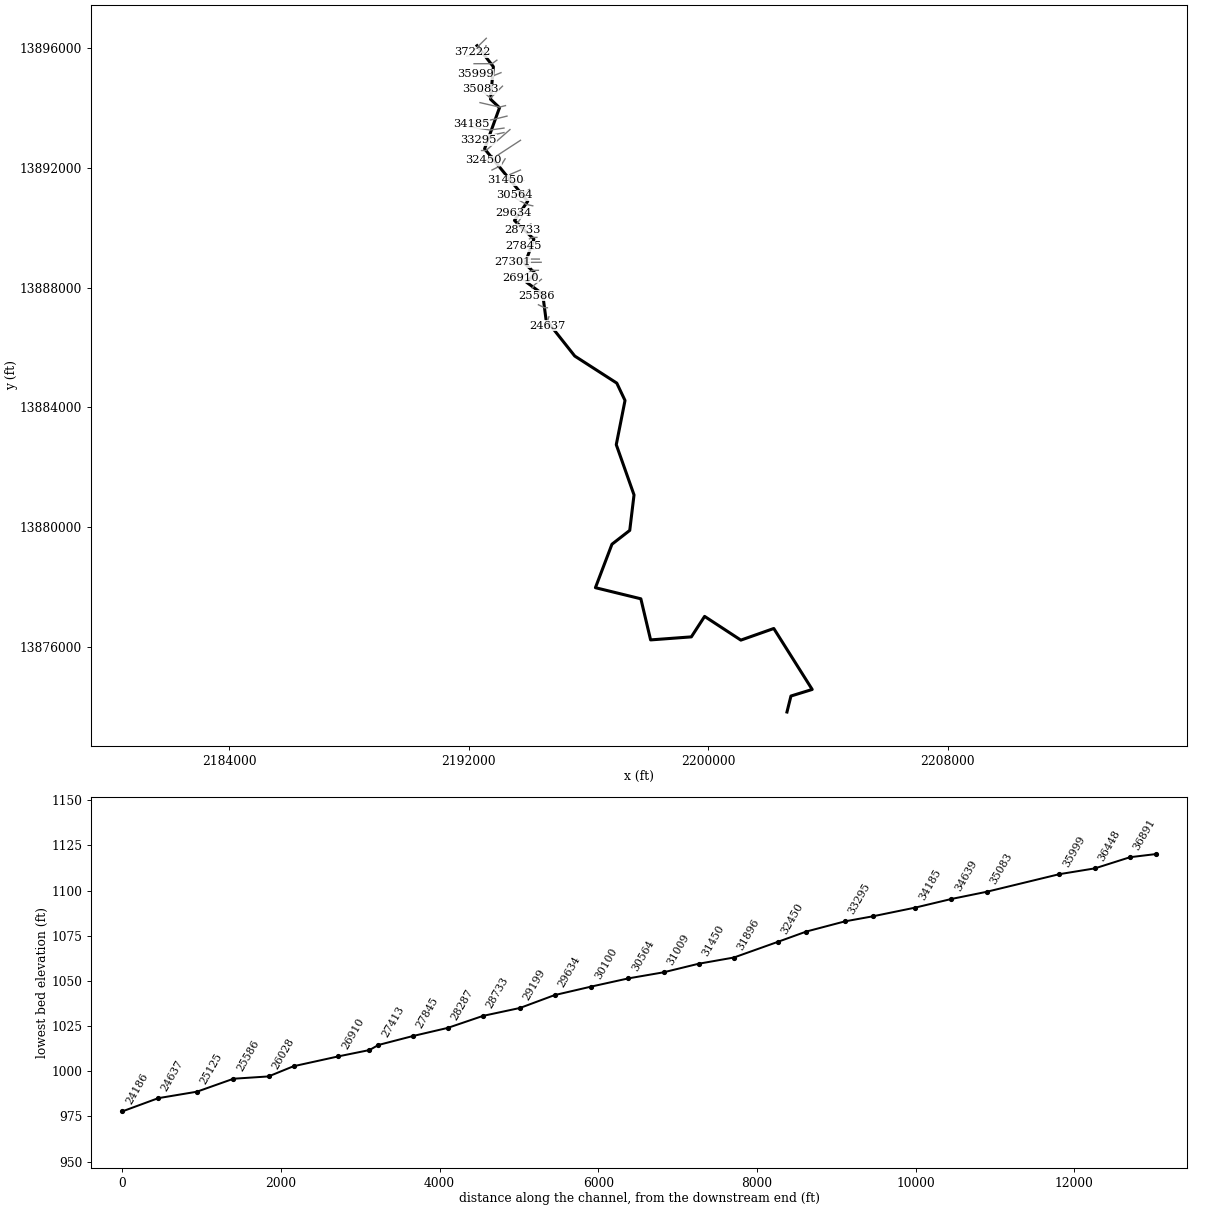
--- Guadalupe Tributary 51.prj (project) ---

Proj Title=Guadalupe Tributary 51 Base Level Engineering
Current Plan=p01
Default Exp/Contr=0.3,0.1
English Units
Geom File=g01
Flow File=f01
Plan File=p01
Y Axis Title=Elevation
X Axis Title(PF)=Main Channel Distance
X Axis Title(XS)=Station
BEGIN DESCRIPTION:
Guadalupe Tributary 51
END DESCRIPTION:
DSS Export Rating Curves= 0
DSS Export Rating Curve Sorted= 0
DSS Export Volume Flow Curves= 0
DXF OffsetX= 0
DXF OffsetY= 0
DXF ScaleX= 1
DXF ScaleY= 10

--- Guadalupe Tributary 51.p01 (plan) ---

Plan Title=Multiple Run
Short Identifier=Multiple
Geom File=g01
Flow File=f01
Subcritical Flow
K Sum by GR= 0
Std Step Tol= 0.01
Critical Tol= 0.01
Num of Std Step Trials= 20
Max Error Tol= 0.3
Flow Tol Ratio= 0.001
Split Flow NTrial= 30
Split Flow Tol= 0.02
Split Flow Ratio= 0.02
Log Output Level= 0
Friction Slope Method= 1
Unsteady Friction Slope Method= 2
Unsteady Bridges Friction Slope Method= 1
Parabolic Critical Depth
Global Vel Dist=  1 , 1 , 1
Global Log Level= 0
CheckData=True
Encroach Param= -1, 0, 0, 0
BEGIN DESCRIPTION:
Multiple Run
END DESCRIPTION:

--- Guadalupe Tributary 51.f01 (steady flow) ---

Flow Title=Multiple
Number of Profiles=7
Profile Names=10-year,25-year,50-year,1pct_min,100-year,1pct_plu,500-year
River Rch & RM= Guadalupe Tribut,Reach-1,37222
    1140    1927    2674    1798    3588    7158    6384
River Rch & RM= Guadalupe Tribut,Reach-1,35083
    1657    2849    3999    2715    5417   10809    9837
River Rch & RM= Guadalupe Tribut,Reach-1,26343
    2059    3596    5097    3491    6966   13899   12888
River Rch & RM= Guadalupe Tribut,Reach-1,23760
    2544    4483    6394    4403    8785   17529   16429
River Rch & RM= Guadalupe Tribut,Reach-1,18070
    2762    4858    6917    4752    9481   18917   17648
River Rch & RM= Guadalupe Tribut,Reach-1,8671
    2925    5116    7258    4966    9909   19770   18287
Boundary for River Rch & Prof#=Guadalupe Tribut,Reach-1,1
Up Type=0
Dn Type=3
Dn Slope=0.005
Boundary for River Rch & Prof#=Guadalupe Tribut,Reach-1,2
Up Type=0
Dn Type=3
Dn Slope=0.005
Boundary for River Rch & Prof#=Guadalupe Tribut,Reach-1,3
Up Type=0
Dn Type=3
Dn Slope=0.005
Boundary for River Rch & Prof#=Guadalupe Tribut,Reach-1,4
Up Type=0
Dn Type=3
Dn Slope=0.005
Boundary for River Rch & Prof#=Guadalupe Tribut,Reach-1,5
Up Type=0
Dn Type=3
Dn Slope=0.005
Boundary for River Rch & Prof#=Guadalupe Tribut,Reach-1,6
Up Type=0
Dn Type=3
Dn Slope=0.005
Boundary for River Rch & Prof#=Guadalupe Tribut,Reach-1,7
Up Type=0
Dn Type=3
Dn Slope=0.005

--- Guadalupe Tributary 51.g01 (geometry) ---

Geom Title=Existing Conditions
Program Version=4.10

River Reach=Guadalupe Tribut,Reach-1
Reach XY= 30
        2192275.       13896075.      2192821.17     13895373.42
      2192725.54     13894288.86      2193025.25     13894005.05
      2192527.17     13892630.44      2193967.24     13890878.42
      2193524.53     13890240.16       2194173.8     13889614.48
       2193874.8     13888797.64      2194217.52     13888471.42
      2193928.34     13888176.35      2194467.17     13887781.19
      2194580.42     13886922.32      2195538.63     13885711.79
      2196941.71     13884808.37      2197216.92      13884228.3
      2196924.71     13882752.16      2197517.73     13881074.94
      2197374.56     13879889.89      2196780.54     13879427.42
      2196228.74     13877976.56      2197745.65      13877605.6
      2198071.33     13876232.69        2199432.     13876334.17
      2199874.91     13877017.71      2201085.47     13876225.48
      2202185.05     13876614.04       2203467.5     13874578.13
       2202758.2     13874358.58        2202625.       13873825.

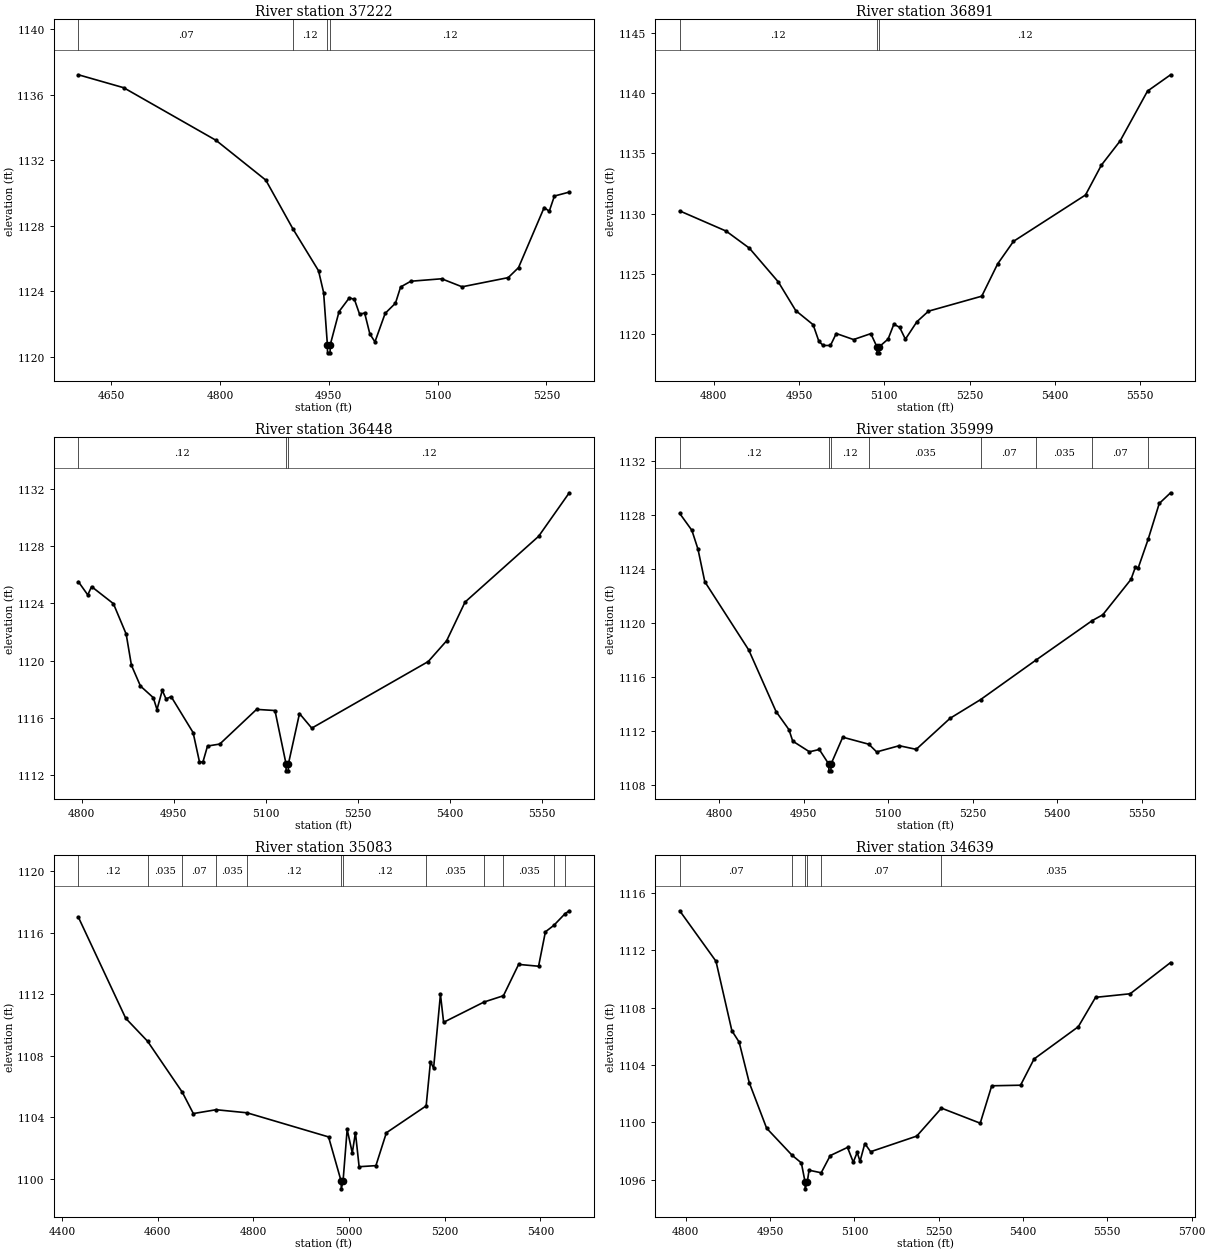
Type RM Length L Ch R = 1 ,37222   ,331,331,331
BEGIN DESCRIPTION:
Guadalupe Tributary 51 58.0
END DESCRIPTION:
XS GIS Cut Line= 2
      2192584.39       13896324.      2192101.53     13895849.47
#Sta/Elev= 30
  4604.6 1137.21  4667.1 1136.42  4794.4 1133.21  4863.1 1130.78  4900.4 1127.81
  4935.8 1125.25  4942.8 1123.92    4948 1120.74  4948.2 1120.24  4951.7 1120.24
    4952 1120.74  4964.1 1122.76  4978.3  1123.6  4985.3  1123.5  4992.4  1122.6
  4999.4 1122.67  5006.6 1121.39  5013.6 1120.91  5027.7 1122.65  5041.9 1123.27
    5049 1124.26  5063.1 1124.61  5105.6 1124.76  5133.8 1124.27  5197.4 1124.83
  5211.6 1125.44    5247 1129.11    5254 1128.88  5261.1 1129.81  5281.6 1130.05
#Mann= 4 ,-1 , 0
  4604.6     .07       0  4900.4     .12       0    4948     .05       0
    4952     .12       0
Bank Sta=4948,4952
XS Rating Curve= 0 ,0
Exp/Cntr=0.3,0.1

Type RM Length L Ch R = 1 ,36891   ,443,443,443
BEGIN DESCRIPTION:
Guadalupe Tributary 51 57.0
END DESCRIPTION:
XS GIS Cut Line= 3
      2192575.01     13896075.03        2192525.       13895825.
      2191924.96     13895724.99
#Sta/Elev= 30
  4740.3 1130.23  4821.9 1128.56  4862.7 1127.15  4913.7 1124.35  4944.3 1121.98
  4974.9 1120.81  4985.1 1119.43  4992.7 1119.09  5005.4 1119.09  5015.6 1120.08
    5046 1119.58  5076.4 1120.07  5087.1 1118.98  5087.3 1118.48  5090.8 1118.48
  5091.1 1118.98  5106.8 1119.62  5116.9 1120.85  5127.1 1120.59  5137.2 1119.61
  5157.5 1121.06  5177.8 1121.93  5271.5 1123.17  5299.4 1125.84  5327.3 1127.71
    5454 1131.55  5481.9 1134.02  5514.8 1136.02    5563 1140.15  5603.6  1141.5
#Mann= 3 ,-1 , 0
  4740.3     .12       0  5087.1     .05       0  5091.1     .12       0
Bank Sta=5087.1,5091.1
XS Rating Curve= 0 ,0
Exp/Cntr=0.3,0.1

Type RM Length L Ch R = 1 ,36448   ,449,449,449
BEGIN DESCRIPTION:
Guadalupe Tributary 51 56.0
END DESCRIPTION:
XS GIS Cut Line= 3
      2192937.66      13895592.4        2192775.       13895475.
        2192175.       13895475.
#Sta/Elev= 30
  4794.4  1125.5  4809.7 1124.58  4815.9 1125.16  4851.5 1123.97  4872.3 1121.85
  4880.9 1119.67  4895.6 1118.22  4916.5 1117.41  4922.6 1116.58  4931.2 1117.92
  4937.3 1117.32  4945.7 1117.48  4981.5 1114.97  4991.9 1112.92  4997.5 1112.92
    5005 1114.03    5025 1114.17    5085 1116.59    5115 1116.51    5133  1112.8
  5133.2  1112.3  5136.7  1112.3    5137  1112.8    5155  1116.3    5175 1115.28
    5365 1119.93    5395 1121.38    5425 1124.08    5545 1128.67    5595 1131.71
#Mann= 3 ,-1 , 0
  4794.4     .12       0    5133     .05       0    5137     .12       0
Bank Sta=5133,5137
XS Rating Curve= 0 ,0
Exp/Cntr=0.3,0.1

Type RM Length L Ch R = 1 ,35999   ,916,916,916
BEGIN DESCRIPTION:
Guadalupe Tributary 51 55.0
END DESCRIPTION:
XS GIS Cut Line= 3
      2193075.04     13895175.02        2192825.       13895075.
      2192224.98       13895125.
#Sta/Elev= 30
  4729.9 1128.13  4751.5 1126.88  4762.3 1125.49  4774.4 1123.08  4852.5 1118.02
  4900.9 1113.47  4923.8 1112.13  4930.5 1111.28  4960.2 1110.49  4977.7 1110.66
  4994.5 1109.58  4994.8 1109.08  4998.3 1109.08  4998.5 1109.58  5019.3 1111.57
  5065.6 1111.05  5079.5 1110.48  5119.6 1110.94  5149.7 1110.67  5209.9 1112.97
  5263.9 1114.35  5363.1  1117.3  5462.2  1120.2  5480.9 1120.63    5531 1123.25
  5538.6 1124.13  5543.6 1124.07  5561.4 1126.21  5581.2 1128.87  5601.3 1129.66
#Mann= 8 ,-1 , 0
  4729.9     .12       0  4994.5     .05       0  4998.5     .12       0
  5065.6    .035       0  5263.9     .07       0  5363.1    .035       0
  5462.2     .07       0  5561.4    .035       0
Bank Sta=4994.5,4998.5
XS Rating Curve= 0 ,0
Exp/Cntr=0.3,0.1

Type RM Length L Ch R = 1 ,35083   ,444,444,444
BEGIN DESCRIPTION:
Guadalupe Tributary 51 54.0
END DESCRIPTION:
XS GIS Cut Line= 3
      2193124.98     13894724.98        2192725.       13894325.
      2192375.03     13894624.97
#Sta/Elev= 30
  4433.8 1117.01  4532.8 1110.43  4578.4 1108.94  4651.1 1105.62  4674.2 1104.23
  4721.9 1104.48  4786.4 1104.28    4957 1102.71  4983.3 1099.83  4983.6 1099.33
  4987.3 1099.83  4995.9  1103.2  5006.6 1101.67  5013.2 1102.99  5020.9 1100.77
    5056 1100.84  5077.9 1102.98  5161.1 1104.73  5170.1  1107.6  5176.7 1107.19
    5191 1111.99  5197.6 1110.17  5282.1 1111.49  5322.7  1111.9  5354.5 1113.94
  5396.2 1113.82  5410.5 1116.06  5428.1 1116.48  5451.6 1117.24  5460.4 1117.43
#Mann= 12 ,-1 , 0
  4433.8     .12       0  4578.4    .035       0  4651.1     .07       0
  4721.9    .035       0  4786.4     .12       0  4983.3     .05       0
  4987.3     .12       0  5161.1    .035       0  5282.1     .07       0
  5322.7    .035       0  5428.1     .12       0  5451.6     .07       0
Bank Sta=4983.3,4987.3
XS Rating Curve= 0 ,0
Exp/Cntr=0.3,0.1

Type RM Length L Ch R = 1 ,34639   ,454,454,454
BEGIN DESCRIPTION:
Guadalupe Tributary 51 53.0
END DESCRIPTION:
XS GIS Cut Line= 3
      2193225.03     13894075.01        2193025.       13894025.
      2192374.97     13894175.01
#Sta/Elev= 30
  4789.2 1114.76  4853.7 1111.24    4882 1106.39  4894.9  1105.6  4912.9 1102.77
  4943.8 1099.59  4989.2  1097.7  5005.6 1097.17  5012.1 1095.86  5012.4 1095.36
  5016.2 1095.86  5019.3 1096.66  5040.9 1096.48    5057 1097.68  5087.7 1098.25
    5098 1097.22  5104.9  1097.9    5110 1097.28  5118.5 1098.52  5128.8 1097.95
  5210.9 1099.04  5254.9 1100.99  5323.8 1099.94  5344.3 1102.55  5395.6 1102.59
  5419.6 1104.42  5498.3 1106.67    5529 1108.72  5590.6 1108.97  5662.5 1111.15
#Mann= 6 ,-1 , 0
  4789.2     .07       0  4989.2    .035       0  5012.1    .035       0
  5016.2    .035       0  5040.9     .07       0  5254.9    .035       0
Bank Sta=5012.1,5016.2
XS Rating Curve= 0 ,0
Exp/Cntr=0.3,0.1

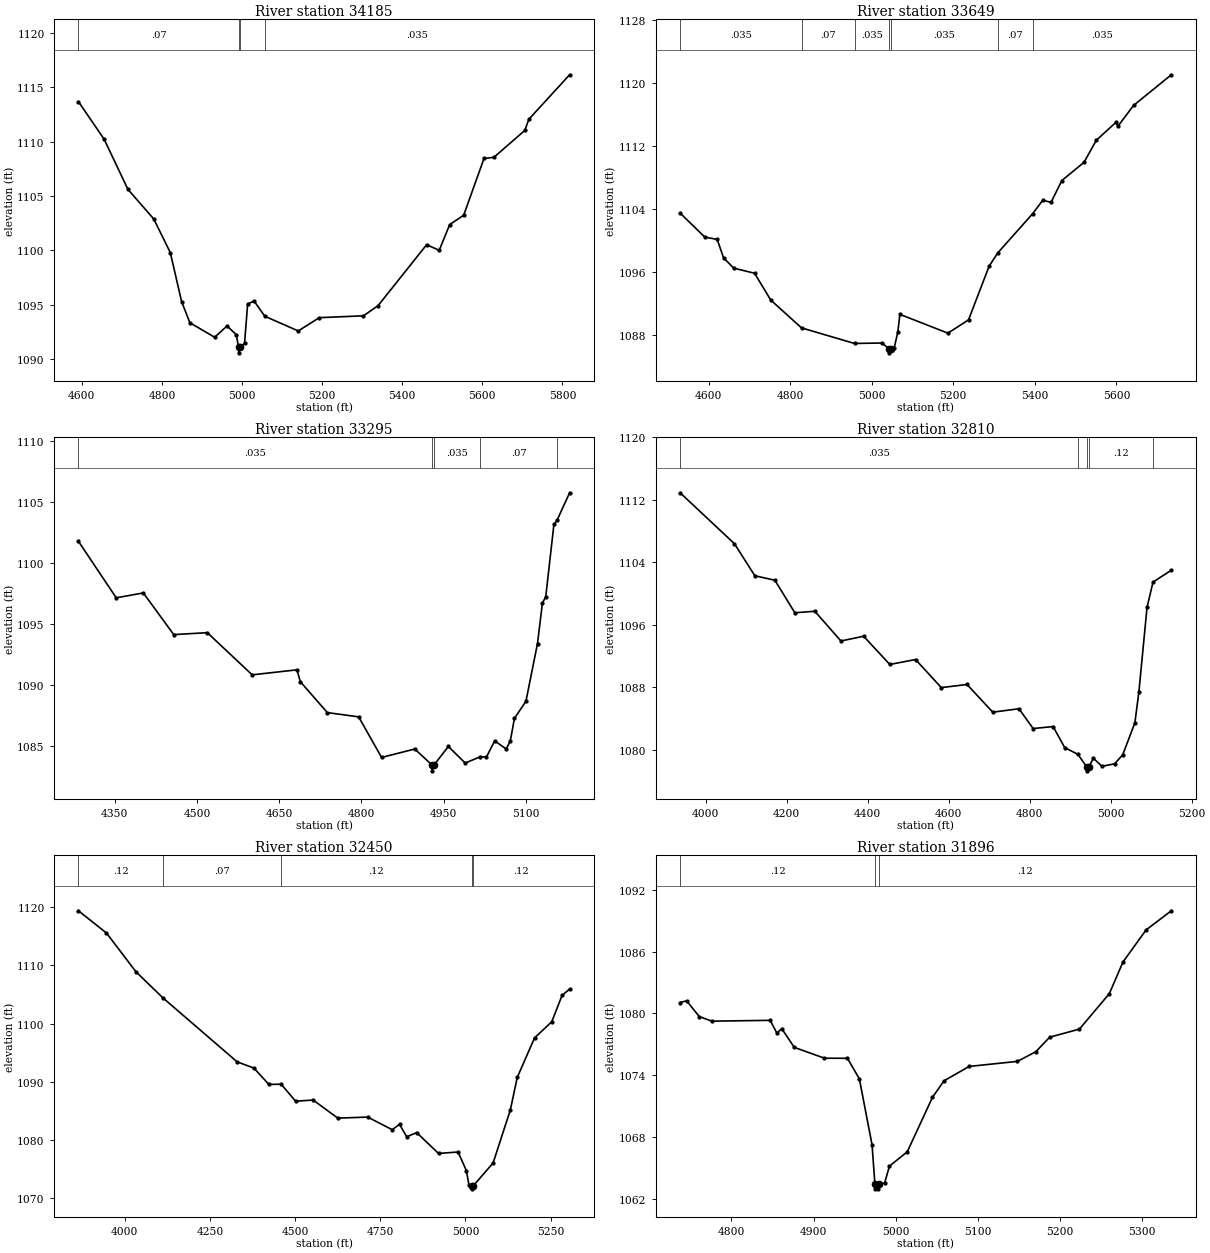
Type RM Length L Ch R = 1 ,34185   ,536,536,536
BEGIN DESCRIPTION:
Guadalupe Tributary 51 52.0
END DESCRIPTION:
XS GIS Cut Line= 3
      2193274.96     13893724.99        2192875.       13893625.
      2192075.01       13893475.
#Sta/Elev= 30
  4591.6 1113.67    4656  1110.2  4715.2 1105.61  4779.7 1102.89  4820.9 1099.81
  4849.2 1095.31  4869.9 1093.36  4931.7 1092.03  4962.6 1093.07  4985.8 1092.26
  4991.5  1091.1  4991.8  1090.6  4995.7  1091.1  5006.4 1091.48    5014 1095.08
  5030.1 1095.36  5056.9 1093.96  5140.4 1092.61  5192.9 1093.83  5303.2    1094
  5339.6 1094.93  5460.9 1100.53  5492.2 1100.01  5518.5 1102.38  5553.3 1103.23
  5604.1 1108.45  5628.7 1108.55  5705.9 1111.02  5716.1 1112.05  5817.8 1116.13
#Mann= 4 ,-1 , 0
  4591.6     .07       0  4991.5     .05       0  4995.7     .07       0
  5056.9    .035       0
Bank Sta=4991.5,4995.7
XS Rating Curve= 0 ,0
Exp/Cntr=0.3,0.1

Type RM Length L Ch R = 1 ,33649   ,354,354,354
BEGIN DESCRIPTION:
Guadalupe Tributary 51 51.0
END DESCRIPTION:
XS GIS Cut Line= 3
      2193174.96     13893324.99      2192711.96     13893259.49
      2191983.32     13893370.09
#Sta/Elev= 30
  4530.1 1103.52  4590.7 1100.47    4621 1100.18  4636.6 1097.85  4661.4 1096.53
  4712.7 1095.88  4752.3 1092.48  4827.8 1088.94  4957.8 1086.96    5025 1087.02
  5043.1 1086.27  5043.4 1085.77  5047.4 1086.27  5055.3 1086.41  5064.1 1088.46
  5069.1 1090.66  5186.8 1088.27  5237.4 1089.96    5288 1096.79  5309.5 1098.49
  5394.9 1103.46  5419.5 1105.16  5439.7 1104.88  5466.3 1107.66  5520.6 1109.97
  5550.9 1112.78  5598.6 1115.03  5603.7 1114.55    5642 1117.19  5734.7 1121.09
#Mann= 7 ,-1 , 0
  4530.1    .035       0  4827.8     .07       0  4957.8    .035       0
  5043.1    .035       0  5047.4    .035       0  5309.5     .07       0
  5394.9    .035       0
Bank Sta=5043.1,5047.4
XS Rating Curve= 0 ,0
Exp/Cntr=0.3,0.1

Type RM Length L Ch R = 1 ,33295   ,485,485,485
BEGIN DESCRIPTION:
Guadalupe Tributary 51 50.0
END DESCRIPTION:
XS GIS Cut Line= 3
      2193174.99       13893175.        2192475.       13893025.
      2192324.97     13892924.98
#Sta/Elev= 30
  4283.6 1101.79  4352.6 1097.15  4402.1 1097.55  4457.5 1094.13  4518.8 1094.29
  4600.6 1090.83  4682.4 1091.24  4688.4 1090.27  4737.8 1087.73  4794.9 1087.38
  4836.7 1084.05  4897.2 1084.74  4928.3 1083.45  4928.6 1082.95  4932.7 1083.45
  4958.6 1084.95  4989.3 1083.59  5017.1 1084.11    5028 1084.08  5043.1 1085.41
  5064.1 1084.74  5071.6 1085.41  5079.1 1087.25  5100.1 1088.66  5121.2  1093.4
  5130.2 1096.73  5136.2 1097.22  5151.2 1103.19  5156.7  1103.5  5179.8 1105.77
#Mann= 5 ,-1 , 0
  4283.6    .035       0  4928.3    .035       0  4932.7    .035       0
  5017.1     .07       0  5156.7    .035       0
Bank Sta=4928.3,4932.7
XS Rating Curve= 0 ,0
Exp/Cntr=0.3,0.1

Type RM Length L Ch R = 1 ,32810   ,360,360,360
BEGIN DESCRIPTION:
Guadalupe Tributary 51 49.0
END DESCRIPTION:
XS GIS Cut Line= 3
      2193375.02     13893275.02        2192575.       13892575.
      2192425.04       13892575.
#Sta/Elev= 30
  3936.6 1112.89  4070.9 1106.37  4121.2 1102.28  4170.6 1101.71  4219.9 1097.55
  4269.3 1097.74  4333.8 1093.94  4389.8 1094.55  4454.4 1090.94    4518 1091.57
  4581.6 1087.98  4645.1 1088.38  4708.7 1084.84  4773.3 1085.28  4808.4 1082.75
  4857.7    1083  4886.2 1080.32  4918.8 1079.45  4940.9 1077.84  4941.3 1077.34
  4945.4 1077.84  4957.4 1078.94  4978.3 1077.92  5009.6 1078.24  5029.6 1079.39
  5059.6 1083.48  5069.6 1087.47  5089.6 1098.23  5104.4 1101.47  5149.6 1102.99
#Mann= 5 ,-1 , 0
  3936.6    .035       0  4918.8     .12       0  4940.9     .05       0
  4945.4     .12       0  5104.4    .035       0
Bank Sta=4940.9,4945.4
XS Rating Curve= 0 ,0
Exp/Cntr=0.3,0.1

Type RM Length L Ch R = 1 ,32450   ,554,554,554
BEGIN DESCRIPTION:
Guadalupe Tributary 51 48.0
END DESCRIPTION:
XS GIS Cut Line= 3
      2193726.33      13892916.8      2192774.89     13892295.95
      2192473.24     13892248.21
#Sta/Elev= 30
  3864.1  1119.4  3946.5 1115.58  4032.9 1108.92  4112.6 1104.41  4329.7 1093.45
  4379.1 1092.37  4423.2 1089.55  4458.8 1089.61  4501.6 1086.68  4552.9 1086.88
  4625.4 1083.77  4712.9 1083.95  4785.1 1081.78  4806.4  1082.7  4827.5 1080.57
  4856.8 1081.28    4921  1077.7  4978.3 1077.95  5002.7 1074.73  5010.2 1072.28
  5018.1 1072.12  5018.4 1071.62  5022.6 1072.12  5081.1 1076.07  5131.7 1085.19
  5151.9 1090.76  5202.6 1097.55  5253.2 1100.33  5283.6 1104.88  5305.6 1105.94
#Mann= 5 ,-1 , 0
  3864.1     .12       0  4112.6     .07       0  4458.8     .12       0
  5018.1     .05       0  5022.6     .12       0
Bank Sta=5018.1,5022.6
XS Rating Curve= 0 ,0
Exp/Cntr=0.3,0.1

Type RM Length L Ch R = 1 ,31896   ,446,446,446
BEGIN DESCRIPTION:
Guadalupe Tributary 51 47.0
END DESCRIPTION:
XS GIS Cut Line= 3
      2193213.27     13892298.14        2193075.       13892075.
      2192775.01     13891925.01
#Sta/Elev= 30
  4737.5 1081.06  4745.4 1081.23  4760.8  1079.7  4776.1 1079.25  4847.1 1079.33
  4855.3 1078.09  4861.2 1078.52  4876.5  1076.7  4913.2 1075.65  4941.2 1075.64
  4955.7 1073.64  4971.1 1067.25  4974.6 1063.45    4975 1062.95  4978.9 1062.95
  4979.2 1063.45  4986.4  1063.5  4992.3 1065.16    5014 1066.55  5044.7 1071.85
  5058.7 1073.45  5089.4 1074.85  5148.1 1075.34  5170.5 1076.28  5187.3 1077.69
  5223.6 1078.48  5259.9 1081.92  5276.7 1085.02  5304.7 1088.12  5335.4 1089.98
#Mann= 3 ,-1 , 0
  4737.5     .12       0  4974.6     .05       0  4979.2     .12       0
Bank Sta=4974.6,4979.2
XS Rating Curve= 0 ,0
Exp/Cntr=0.3,0.1

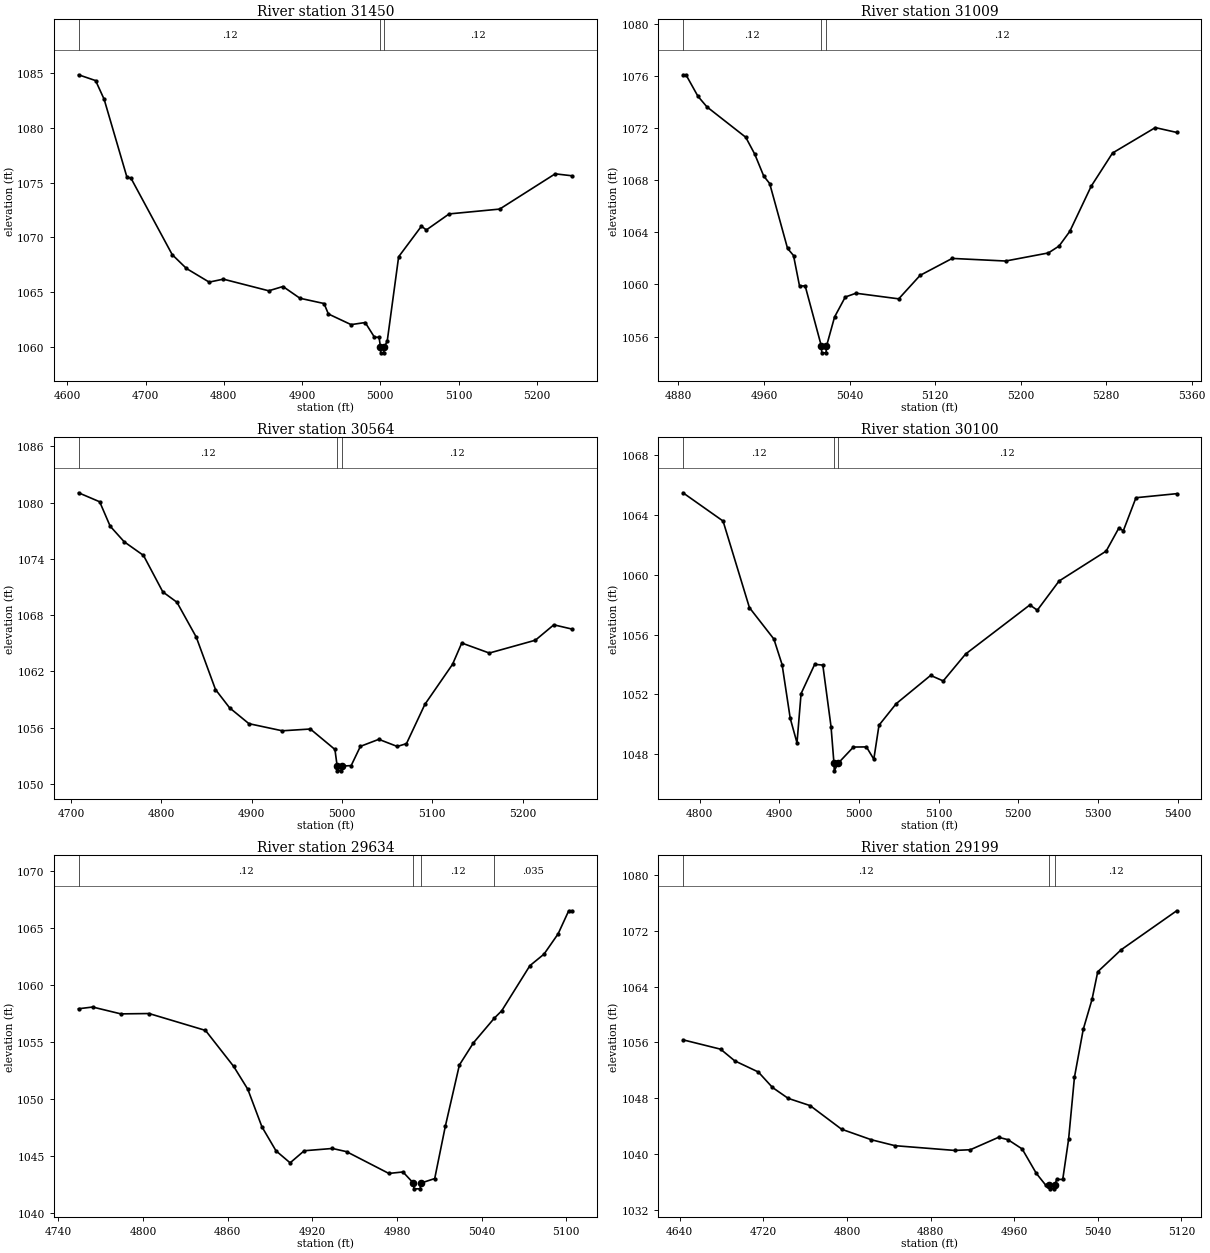
Type RM Length L Ch R = 1 ,31450   ,441,441,441
BEGIN DESCRIPTION:
Guadalupe Tributary 51 46.0
END DESCRIPTION:
XS GIS Cut Line= 3
      2193725.04     13891925.02        2193375.       13891775.
      2193225.02     13891575.03
#Sta/Elev= 30
  4614.4 1084.81  4636.2 1084.28  4647.1 1082.58  4676.1 1075.52  4681.5 1075.38
  4734.1 1068.43  4752.3 1067.17  4781.3 1065.93  4799.4  1066.2  4857.4 1065.14
  4875.6 1065.53  4897.3 1064.46  4928.1 1063.98  4933.6 1063.03  4962.6 1062.06
  4980.7 1062.25  4992.5 1060.91  4998.4 1060.91  5000.2 1059.99  5000.5 1059.49
  5004.5 1059.49  5004.8 1059.99  5008.8 1060.55  5023.4 1068.24  5052.5 1071.02
  5058.8 1070.68  5087.9 1072.14  5152.5 1072.58  5223.4 1075.79  5245.2 1075.61
#Mann= 3 ,-1 , 0
  4614.4     .12       0  5000.2     .05       0  5004.8     .12       0
Bank Sta=5000.2,5004.8
XS Rating Curve= 0 ,0
Exp/Cntr=0.3,0.1

Type RM Length L Ch R = 1 ,31009   ,445,445,445
BEGIN DESCRIPTION:
Guadalupe Tributary 51 45.0
END DESCRIPTION:
XS GIS Cut Line= 3
      2193825.02     13891575.01        2193725.       13891525.
      2193375.02       13891525.
#Sta/Elev= 30
  4884.2 1076.08    4887 1076.08  4898.2 1074.43  4906.6 1073.62  4942.9 1071.29
  4951.3    1070  4959.7 1068.32  4965.3 1067.74    4982 1062.77  4987.6 1062.22
  4993.2 1059.89  4998.5 1059.89  5013.7 1055.26    5014 1054.76    5018 1054.76
  5018.4 1055.26    5026 1057.51    5036 1059.04    5046 1059.33    5086  1058.9
    5106  1060.7    5136    1062    5186  1061.8    5226 1062.42    5236 1062.95
    5246 1064.07    5266 1067.53    5286 1070.08    5326 1072.03    5346 1071.66
#Mann= 3 ,-1 , 0
  4884.2     .12       0  5013.7     .05       0  5018.4     .12       0
Bank Sta=5013.7,5018.4
XS Rating Curve= 0 ,0
Exp/Cntr=0.3,0.1

Type RM Length L Ch R = 1 ,30564   ,464,464,464
BEGIN DESCRIPTION:
Guadalupe Tributary 51 44.0
END DESCRIPTION:
XS GIS Cut Line= 3
      2194025.03     13891275.02        2193775.       13891125.
      2193525.03     13891075.01
#Sta/Elev= 30
  4708.4 1081.04  4731.8 1080.08  4743.4 1077.48    4759 1075.81  4780.3 1074.36
  4801.7 1070.47  4817.3 1069.37  4838.7 1065.65    4860 1060.06  4875.6 1058.11
    4897 1056.42  4933.9 1055.66    4965 1055.85  4992.2 1053.67  4994.7 1051.89
    4995 1051.39  4999.1 1051.39  4999.5 1051.89  5010.2 1051.95  5020.4    1054
  5040.8 1054.75  5061.2 1053.99  5071.4 1054.29  5091.8 1058.48  5122.4 1062.75
  5132.6 1065.02  5163.1 1063.95  5214.1 1065.32  5234.5 1066.96  5254.9  1066.5
#Mann= 3 ,-1 , 0
  4708.4     .12       0  4994.7     .05       0  4999.5     .12       0
Bank Sta=4994.7,4999.5
XS Rating Curve= 0 ,0
Exp/Cntr=0.3,0.1

Type RM Length L Ch R = 1 ,30100   ,466,466,466
BEGIN DESCRIPTION:
Guadalupe Tributary 51 43.0
END DESCRIPTION:
XS GIS Cut Line= 3
      2194136.47     13890728.67        2193925.       13890775.
        2193575.       13890975.
#Sta/Elev= 30
  4779.2 1065.48  4829.5 1063.59  4862.6  1057.8  4893.3  1055.7  4903.6 1053.99
  4913.8  1050.4  4922.3 1048.76  4927.4 1052.05  4944.5 1054.01  4954.7 1053.96
    4965 1049.85  4968.7 1047.39  4969.1 1046.89  4973.8 1047.39  4993.1 1048.48
  5009.4 1048.49  5018.7 1047.67  5025.2 1049.94  5046.8 1051.38    5090 1053.27
  5105.8  1052.9  5133.9  1054.7  5214.5 1057.98  5223.9 1057.63  5251.2 1059.58
  5310.3 1061.58  5326.1 1063.11  5331.9 1062.95  5347.7 1065.15  5398.8 1065.42
#Mann= 3 ,-1 , 0
  4779.2     .12       0  4968.7     .05       0  4973.8     .12       0
Bank Sta=4968.7,4973.8
XS Rating Curve= 0 ,0
Exp/Cntr=0.3,0.1

Type RM Length L Ch R = 1 ,29634   ,435,435,435
BEGIN DESCRIPTION:
Guadalupe Tributary 51 42.0
END DESCRIPTION:
XS GIS Cut Line= 3
      2193824.96       13890475.        2193575.       13890475.
      2193474.96       13890475.
#Sta/Elev= 30
  4754.3 1057.92  4764.3 1058.07  4784.3 1057.47  4804.3  1057.5  4844.3 1056.02
  4864.3 1052.86  4874.3 1050.86  4884.3 1047.57  4894.3 1045.46  4904.3 1044.41
  4914.3 1045.47  4934.3 1045.67  4944.3 1045.39  4974.3 1043.48  4984.3 1043.61
  4991.7 1042.63  4992.1 1042.13  4996.5 1042.13  4996.9 1042.63  5006.8 1043.03
  5014.3  1047.6  5024.3 1052.99  5034.3 1054.94  5049.1  1057.1  5054.3 1057.74
  5074.3  1061.7  5084.3 1062.71  5094.3 1064.49  5101.8 1066.51  5104.3 1066.51
#Mann= 4 ,-1 , 0
  4754.3     .12       0  4991.7     .05       0  4996.9     .12       0
  5049.1    .035       0
Bank Sta=4991.7,4996.9
XS Rating Curve= 0 ,0
Exp/Cntr=0.3,0.1

Type RM Length L Ch R = 1 ,29199   ,466,466,466
BEGIN DESCRIPTION:
Guadalupe Tributary 51 41.0
END DESCRIPTION:
XS GIS Cut Line= 3
      2193774.98     13890374.96        2193575.       13890075.
      2193475.01     13890025.01
#Sta/Elev= 30
  4643.2 1056.37  4679.2 1055.03  4692.7 1053.36  4715.3 1051.76  4728.8 1049.55
  4743.8 1047.99  4764.8 1046.95  4794.9 1043.57  4823.4 1042.06    4846 1041.21
  4903.1 1040.53  4918.1 1040.63  4945.1 1042.41  4954.1 1042.07  4967.7 1040.74
  4981.2 1037.25  4990.2 1035.56  4993.6 1035.53    4994 1035.03  4998.4 1035.03
  4998.8 1035.53  5000.7 1036.38  5006.5 1036.38  5012.1 1042.12  5017.7 1051.01
  5026.1 1057.86  5034.5 1062.15    5040 1066.12  5062.4 1069.27  5115.5 1074.85
#Mann= 3 ,-1 , 0
  4643.2     .12       0  4993.6     .05       0  4998.8     .12       0
Bank Sta=4993.6,4998.8
XS Rating Curve= 0 ,0
Exp/Cntr=0.3,0.1

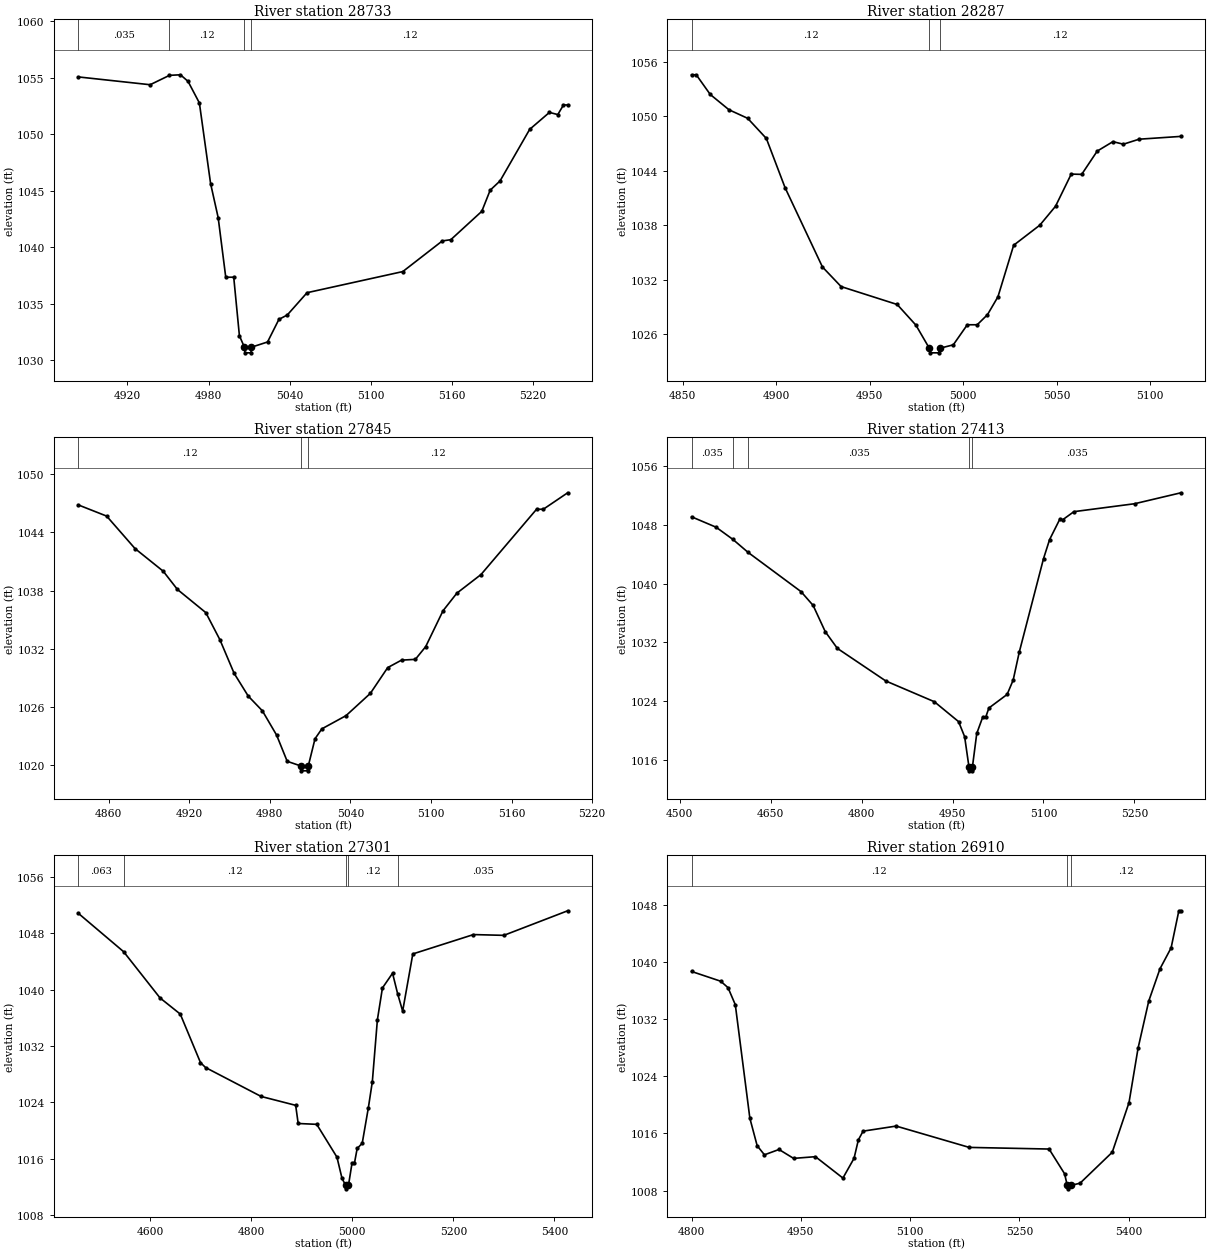
Type RM Length L Ch R = 1 ,28733   ,446,446,446
BEGIN DESCRIPTION:
Guadalupe Tributary 51 40.0
END DESCRIPTION:
XS GIS Cut Line= 3
      2194075.01     13890125.01        2193975.       13890075.
      2193775.01     13889925.01
#Sta/Elev= 30
  4883.7 1055.06  4936.8 1054.37  4951.1  1055.2  4959.2 1055.25  4964.8 1054.67
  4973.2 1052.76  4981.5 1045.62  4987.1 1042.61  4992.7 1037.34  4998.6 1037.34
  5002.8 1032.16  5006.5 1031.15  5006.9 1030.65  5011.3 1030.65  5011.7 1031.15
  5023.6 1031.61    5032 1033.61  5038.2    1034  5052.8 1035.97  5123.6 1037.84
  5152.8 1040.55  5159.1 1040.66    5182 1043.17  5188.2 1045.04  5195.5 1045.86
  5217.4 1050.42    5232 1051.92  5238.2 1051.73  5242.4 1052.58  5245.5 1052.58
#Mann= 4 ,-1 , 0
  4883.7    .035       0  4951.1     .12       0  5006.5     .05       0
  5011.7     .12       0
Bank Sta=5006.5,5011.7
XS Rating Curve= 0 ,0
Exp/Cntr=0.3,0.1

Type RM Length L Ch R = 1 ,28287   ,442,442,442
BEGIN DESCRIPTION:
Guadalupe Tributary 51 39.0
END DESCRIPTION:
XS GIS Cut Line= 3
      2194274.96       13889675.        2194125.       13889675.
      2194024.96     13889624.98
#Sta/Elev= 30
  4854.7 1054.58  4857.2 1054.58  4864.7 1052.41  4874.7 1050.73  4884.7 1049.79
  4894.7 1047.57  4904.7 1042.16  4924.7 1033.43  4934.7 1031.27  4964.7  1029.3
  4974.7 1027.03  4981.9 1024.48  4982.4 1023.98    4987 1023.98  4987.4 1024.48
  4994.7 1024.86  5002.2 1027.07  5007.5 1027.07    5013 1028.18  5018.6 1030.15
    5027 1035.82    5041 1038.03  5049.4 1040.11  5057.8 1043.65  5063.4 1043.62
  5071.7 1046.18  5080.1 1047.22  5085.7 1046.94  5094.1 1047.49  5116.5  1047.8
#Mann= 3 ,-1 , 0
  4854.7     .12       0  4981.9     .05       0  4987.4     .12       0
Bank Sta=4981.9,4987.4
XS Rating Curve= 0 ,0
Exp/Cntr=0.3,0.1

Type RM Length L Ch R = 1 ,27845   ,432,432,432
BEGIN DESCRIPTION:
Guadalupe Tributary 51 38.0
END DESCRIPTION:
XS GIS Cut Line= 3
        2194175.       13889275.        2194025.       13889325.
      2193824.97     13889375.01
#Sta/Elev= 30
  4837.5 1046.81  4858.6 1045.66  4879.7 1042.32  4900.7 1039.99  4911.3 1038.11
  4932.4 1035.73  4942.9 1032.94  4953.5 1029.48    4964 1027.14  4974.5 1025.63
  4985.1 1023.13    4993 1020.43  5003.2 1019.95  5003.6 1019.45  5008.3 1019.45
  5008.7 1019.95  5013.7 1022.75  5018.8 1023.77  5036.8 1025.13  5054.9 1027.42
  5067.8 1030.07  5078.1 1030.84  5088.4 1030.92  5096.1 1032.23    5109 1035.92
  5119.3 1037.73  5137.3 1039.65  5178.6 1046.36  5183.7 1046.37  5201.8 1048.06
#Mann= 3 ,-1 , 0
  4837.5     .12       0  5003.2     .05       0  5008.7     .12       0
Bank Sta=5003.2,5008.7
XS Rating Curve= 0 ,0
Exp/Cntr=0.3,0.1

Type RM Length L Ch R = 1 ,27413   ,112,112,112
BEGIN DESCRIPTION:
Guadalupe Tributary 51 37.0
END DESCRIPTION:
XS GIS Cut Line= 3
      2194355.47     13888950.38      2193870.08     13888951.87
      2193548.77     13888973.01
#Sta/Elev= 30
  4519.5 1049.11    4560 1047.69  4587.7 1046.03  4612.8 1044.26    4700 1038.93
    4720 1037.05    4740 1033.48    4760  1031.2    4840 1026.76    4920 1023.94
    4960 1021.23    4970 1019.18  4977.2 1015.03  4977.6 1014.53  4982.3 1014.53
  4982.8 1015.03    4990 1019.62  4999.9 1021.86  5004.9 1021.86    5010 1023.08
  5040.1 1024.93  5050.1 1026.89  5060.1 1030.68  5100.2 1043.43  5110.2 1046.01
    5127 1048.78    5132 1048.72  5150.3 1049.81  5250.5 1050.89  5326.9 1052.38
#Mann= 5 ,-1 , 0
  4519.5    .035       0  4587.7    .063       0  4612.8    .035       0
  4977.2    .035       0  4982.8    .035       0
Bank Sta=4977.2,4982.8
XS Rating Curve= 0 ,0
Exp/Cntr=0.3,0.1

Type RM Length L Ch R = 1 ,27301   ,391,391,391
BEGIN DESCRIPTION:
Guadalupe Tributary 51 36.5
END DESCRIPTION:
XS GIS Cut Line= 3
      2194416.68     13888843.14      2193870.54     13888839.18
      2193448.72     13888853.02
#Sta/Elev= 30
    4458 1050.86  4547.6 1045.41  4619.7 1038.84  4659.7 1036.55  4699.7 1029.66
  4709.7 1028.96  4819.7 1024.85    4888 1023.59    4893 1021.01  4929.7 1020.89
  4969.7 1016.23  4979.7 1013.22  4986.9 1012.23  4987.3 1011.73  4992.5 1012.23
  4999.4 1015.33  5004.2 1015.33  5009.7 1017.46  5019.7  1018.2  5031.9 1023.27
  5039.7 1026.94  5049.7 1035.73  5059.7 1040.26  5079.7 1042.35  5089.9  1039.4
  5099.7 1036.97  5119.8 1045.09  5239.8 1047.84  5299.9 1047.73  5426.2 1051.22
#Mann= 5 ,-1 , 0
    4458    .063       0  4547.6     .12       0  4986.9     .05       0
  4992.5     .12       0  5089.9    .035       0
Bank Sta=4986.9,4992.5
XS Rating Curve= 0 ,0
Exp/Cntr=0.3,0.1

Type RM Length L Ch R = 1 ,26910   ,567,567,567
BEGIN DESCRIPTION:
Guadalupe Tributary 51 36.0
END DESCRIPTION:
XS GIS Cut Line= 3
      2194325.05       13888575.        2194125.       13888575.
      2193725.04     13888325.03
#Sta/Elev= 30
    4800 1038.72    4840 1037.35    4850 1036.45    4860 1034.06    4880 1018.13
    4890 1014.29    4900 1013.01    4920 1013.76    4940 1012.51    4970 1012.75
  5007.7 1009.75    5023 1012.52  5028.9  1015.1  5035.4 1016.33  5080.8 1017.04
  5181.1 1014.05  5290.7 1013.82    5312 1010.35  5315.6 1008.74  5316.1 1008.24
  5321.2 1008.74  5333.2 1009.03  5377.4 1013.37  5400.4 1020.33  5412.8 1027.94
  5427.5 1034.57  5442.9 1039.09  5458.2 1042.03  5468.8 1047.23  5471.7 1047.23
#Mann= 3 ,-1 , 0
    4800     .12       0  5315.6     .05       0  5321.2     .12       0
Bank Sta=5315.6,5321.2
XS Rating Curve= 0 ,0
Exp/Cntr=0.3,0.1

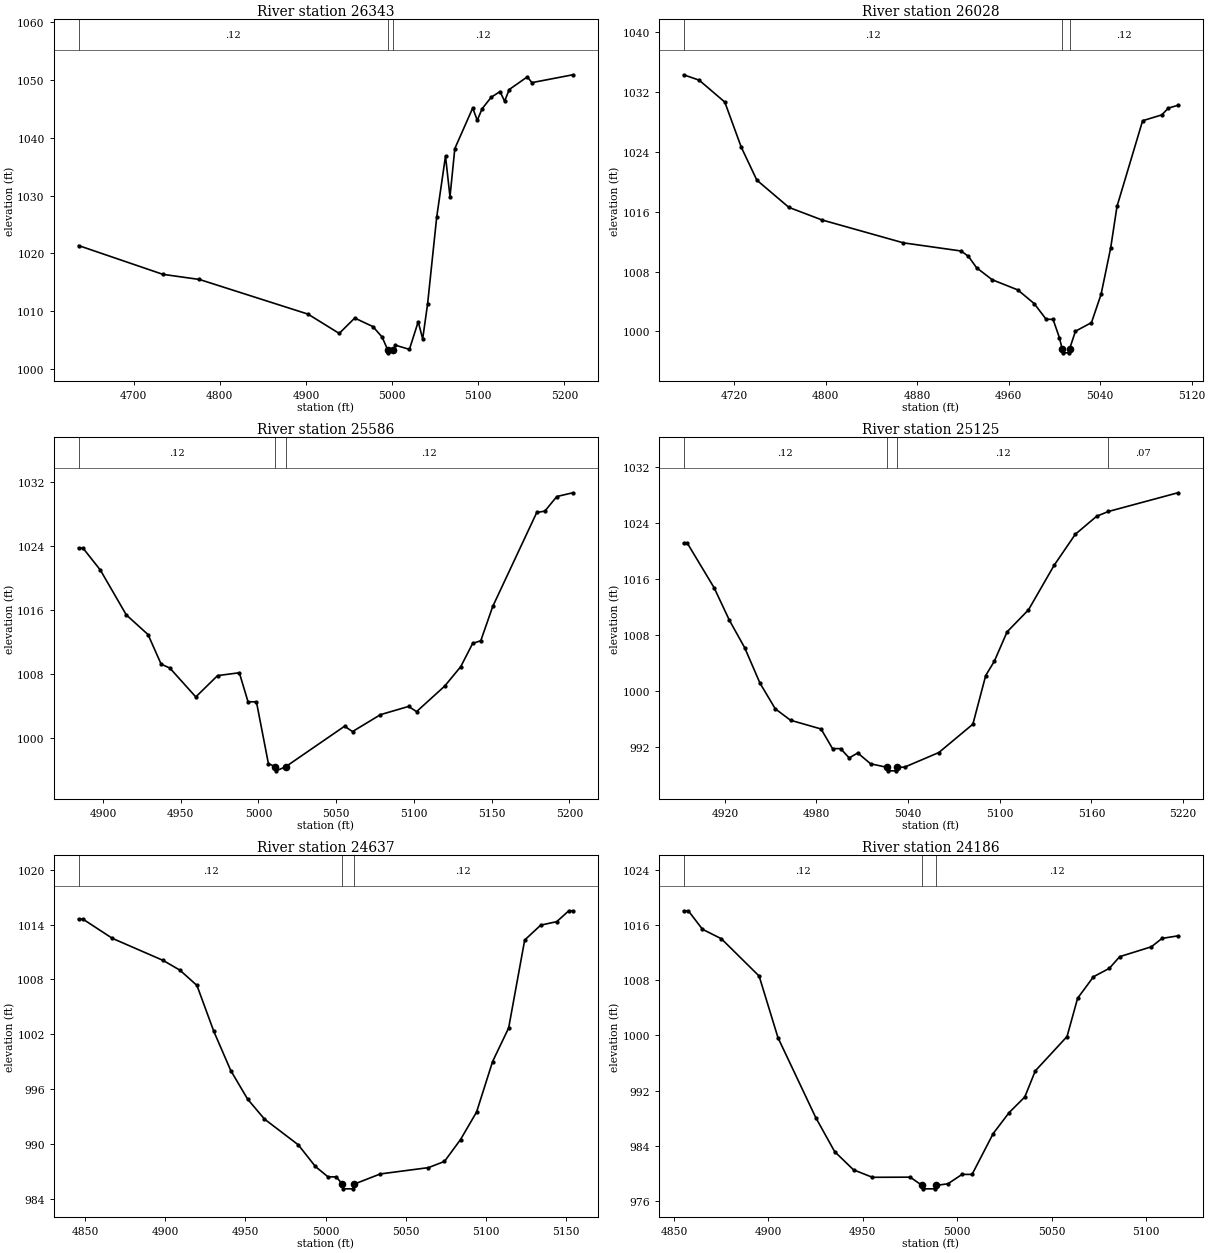
Type RM Length L Ch R = 1 ,26343   ,315,315,315
BEGIN DESCRIPTION:
Guadalupe Tributary 51 35.0
END DESCRIPTION:
XS GIS Cut Line= 3
      2194267.21     13888330.38      2193924.34     13888208.86
      2193724.99       13888275.
#Sta/Elev= 30
    4636 1021.34  4733.8 1016.36  4776.3 1015.47  4902.4 1009.47  4938.6 1006.13
  4956.6 1008.79  4977.8 1007.31  4988.5 1005.48  4994.9 1003.27  4995.4 1002.77
  5001.3 1003.27  5003.9 1004.09  5020.1 1003.37  5030.3 1008.15  5035.5 1005.19
  5041.2 1011.23  5051.8 1026.29    5062 1036.83  5067.2 1029.78  5072.8 1038.12
  5093.6 1045.15  5098.9 1043.01  5104.4    1045    5115    1047  5125.3    1048
  5130.6 1046.33    5136 1048.35    5157 1050.54  5162.3 1049.54  5209.8  1050.9
#Mann= 3 ,-1 , 0
    4636     .12       0  4994.9     .05       0  5001.3     .12       0
Bank Sta=4994.9,5001.3
XS Rating Curve= 0 ,0
Exp/Cntr=0.3,0.1

Type RM Length L Ch R = 1 ,26028   ,442,442,442
BEGIN DESCRIPTION:
Guadalupe Tributary 51 34.0
END DESCRIPTION:
XS GIS Cut Line= 3
      2194424.99       13888275.        2194175.       13888075.
      2194124.98     13887974.96
#Sta/Elev= 30
  4675.9 1034.29  4689.5 1033.57  4711.9 1030.64  4726.3 1024.61  4739.9 1020.21
  4767.9 1016.57  4796.8 1014.89    4868 1011.83  4918.4 1010.74  4924.8 1010.03
    4932  1008.5  4945.6  1006.9    4968 1005.54  4982.4  1003.7  4992.8 1001.61
  4998.8 1001.61  5004.4  999.14  5006.8  997.63  5007.3  997.13  5012.7  997.13
  5013.2  997.63  5018.4 1000.02  5032.4 1001.17  5040.8 1004.96  5049.2 1011.17
  5054.7  1016.7  5077.1 1028.15  5093.9 1028.93  5099.5 1029.83  5107.9 1030.21
#Mann= 3 ,-1 , 0
  4675.9     .12       0  5006.8     .05       0  5013.2     .12       0
Bank Sta=5006.8,5013.2
XS Rating Curve= 0 ,0
Exp/Cntr=0.3,0.1

Type RM Length L Ch R = 1 ,25586   ,461,461,461
BEGIN DESCRIPTION:
Guadalupe Tributary 51 33.0
END DESCRIPTION:
XS GIS Cut Line= 3
      2194574.98     13887725.01        2194475.       13887775.
      2194275.04     13887725.01
#Sta/Elev= 30
  4884.3 1023.77  4887.1 1023.77  4898.3 1021.01    4915 1015.39    4929 1012.92
  4937.4 1009.22    4943 1008.73  4959.7 1005.11  4973.7 1007.78  4987.7 1008.14
  4993.3  1004.5  4998.7  1004.5  5006.4  996.76  5010.9  996.35  5011.4  995.85
  5017.4  996.35  5055.4 1001.44  5060.5 1000.77  5078.5 1002.89  5096.6 1003.92
  5101.7 1003.27  5119.8 1006.47  5130.1  1008.9  5137.8 1011.82    5143 1012.15
  5150.7 1016.45    5179 1028.22  5184.2 1028.39  5191.9 1030.22  5202.2 1030.69
#Mann= 3 ,-1 , 0
  4884.3     .12       0  5010.9     .05       0  5017.4     .12       0
Bank Sta=5010.9,5017.4
XS Rating Curve= 0 ,0
Exp/Cntr=0.3,0.1

Type RM Length L Ch R = 1 ,25125   ,488,488,488
BEGIN DESCRIPTION:
Guadalupe Tributary 51 32.0
END DESCRIPTION:
XS GIS Cut Line= 3
        2194625.       13887325.        2194525.       13887325.
      2194325.01       13887425.
#Sta/Elev= 30
    4893 1021.12  4895.5 1021.12    4913 1014.78    4923 1010.14    4933 1006.23
    4943 1001.18    4953  997.52    4963  995.89    4983  994.64  4990.5  991.84
  4995.8  991.84  5001.4  990.51    5007  991.22  5015.4  989.68  5026.1  989.17
  5026.6  988.67  5032.1  988.67  5032.6  989.17  5037.7   989.2  5060.1  991.28
  5082.4  995.33  5090.8 1002.27  5096.4 1004.29  5104.8  1008.5  5118.8 1011.64
  5135.6    1018  5149.5 1022.43  5163.5    1025  5171.1 1025.67  5216.6 1028.34
#Mann= 4 ,-1 , 0
    4893     .12       0  5026.1     .05       0  5032.6     .12       0
  5171.1     .07       0
Bank Sta=5026.1,5032.6
XS Rating Curve= 0 ,0
Exp/Cntr=0.3,0.1

Type RM Length L Ch R = 1 ,24637   ,451,451,451
BEGIN DESCRIPTION:
Guadalupe Tributary 51 31.0
END DESCRIPTION:
XS GIS Cut Line= 3
        2194675.     13887024.99        2194625.       13886875.
        2194625.       13886725.
#Sta/Elev= 30
    4846 1014.61  4848.6 1014.61  4867.1 1012.49  4898.7 1010.08  4909.2 1009.01
  4919.8 1007.34  4930.3 1002.32  4940.9  998.02  4951.4   994.9  4961.9  992.72
    4983   989.9  4993.6  987.54  5001.5   986.4  5006.6   986.4  5010.5  985.59
    5011  985.09  5017.1  985.09  5017.6  985.59  5034.1  986.72  5064.1  987.41
  5074.1  988.09  5084.1  990.48  5094.1  993.49  5104.1  999.02  5114.1 1002.69
  5124.1 1012.31  5134.1 1013.94  5144.1 1014.32  5151.6 1015.51  5154.1 1015.51
#Mann= 3 ,-1 , 0
    4846     .12       0  5010.5     .05       0  5017.6     .12       0
Bank Sta=5010.5,5017.6
XS Rating Curve= 0 ,0
Exp/Cntr=0.3,0.1

Type RM Length L Ch R = 1 ,24186   ,426,426,426
BEGIN DESCRIPTION:
Guadalupe Tributary 51 30.0
END DESCRIPTION:
XS GIS Cut Line= 3
        2195025.     13886874.99        2195025.       13886725.
      2194924.99       13886675.
#Sta/Elev= 30
  4855.1 1018.05  4857.6 1018.05  4865.1 1015.37  4875.1    1014  4895.1  1008.6
  4905.1  999.67  4925.1  988.11  4935.1  983.19  4945.1  980.55  4955.1  979.47
  4975.1  979.49  4981.4   978.3  4981.9   977.8  4988.3   977.8  4988.8   978.3
  4995.1  978.53  5002.6  979.89  5007.9  979.89  5019.1  985.81  5027.5  988.83
  5035.8  991.09  5041.4  994.88  5058.2  999.85  5063.8 1005.39  5072.2  1008.5
  5080.6 1009.72  5086.1 1011.41  5102.9 1012.84  5108.5 1014.05  5116.9 1014.42
#Mann= 3 ,-1 , 0
  4855.1     .12       0  4981.4     .05       0  4988.8     .12       0
Bank Sta=4981.4,4988.8
XS Rating Curve= 0 ,0
Exp/Cntr=0.3,0.1