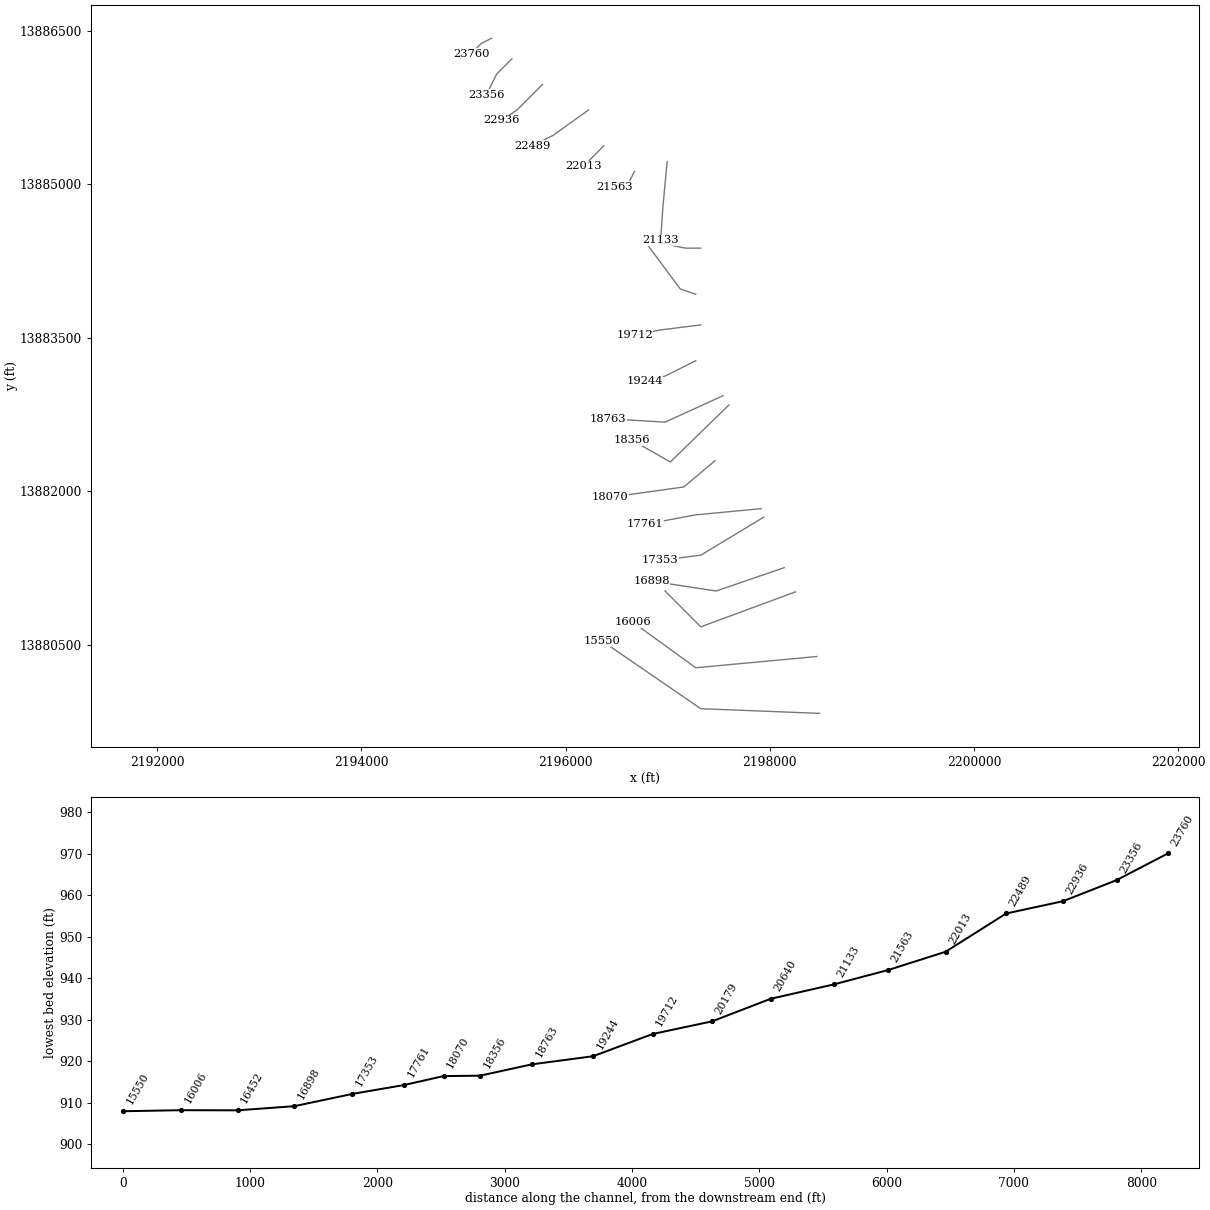
HEC-RAS study Guadalupe Tributary 51.prj: Guadalupe Tributary 51 Base Level Engineering

--- Guadalupe Tributary 51.g01 (geometry) --- (continued)

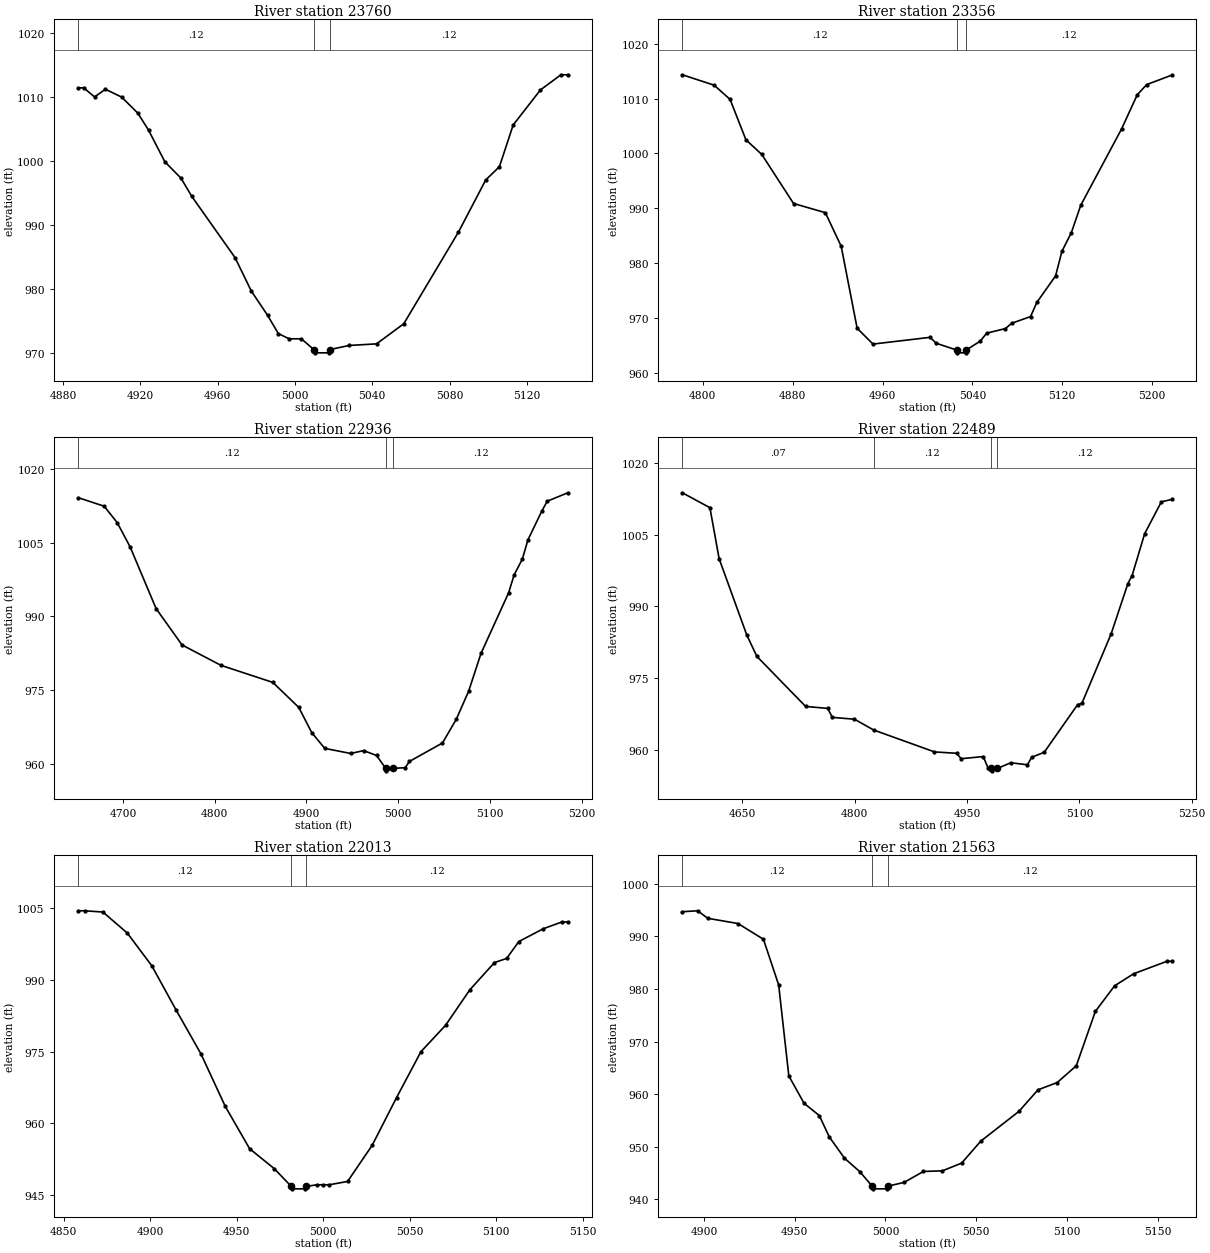
Type RM Length L Ch R = 1 ,23760   ,404,404,404
BEGIN DESCRIPTION:
Guadalupe Tributary 51 29.0
END DESCRIPTION:
XS GIS Cut Line= 3
      2195275.04     13886425.02        2195175.       13886375.
      2195074.98     13886274.98
#Sta/Elev= 30
  4887.9  1011.4  4890.7  1011.4  4896.3 1009.98  4901.9 1011.18  4910.3 1009.96
  4918.7 1007.45  4924.3 1004.76  4932.7  999.85    4941  997.31  4946.6  994.46
    4969   984.9  4977.4  979.69  4985.8  975.91  4991.4  973.04    4997  972.23
  5003.3  972.23  5009.8  970.54  5010.3  970.04  5017.4  970.04  5017.9  970.54
    5028  971.19  5042.2  971.44  5056.3  974.58  5084.6  988.89  5098.7  997.02
  5105.8   999.1  5112.9  1005.6    5127 1011.07  5137.6 1013.44  5141.2 1013.44
#Mann= 3 ,-1 , 0
  4887.9     .12       0  5009.8     .05       0  5017.9     .12       0
Bank Sta=5009.8,5017.9
XS Rating Curve= 0 ,0
Exp/Cntr=0.3,0.1

Type RM Length L Ch R = 1 ,23356   ,420,420,420
BEGIN DESCRIPTION:
Guadalupe Tributary 51 28.0
END DESCRIPTION:
XS GIS Cut Line= 3
      2195475.02     13886225.02        2195325.       13886075.
      2195224.98     13885874.97
#Sta/Elev= 30
  4781.8 1014.36  4810.1 1012.46  4824.3 1009.86  4838.4 1002.49  4852.5  999.82
  4880.8  990.86  4909.1  989.19  4923.2  983.06  4937.4  968.09  4951.5   965.2
  5002.3  966.43  5007.9  965.34  5026.2   964.1  5026.7   963.6  5033.9   963.6
  5034.4   964.1  5047.1  965.75  5052.7  967.19  5069.4  968.03    5075     969
  5091.8  970.22  5097.4  972.81  5114.1  977.66  5119.7  982.13  5128.1  985.53
  5136.5  990.55  5172.8 1004.46  5186.8 1010.72  5195.2 1012.57  5217.6  1014.3
#Mann= 3 ,-1 , 0
  4781.8     .12       0  5026.2     .05       0  5034.4     .12       0
Bank Sta=5026.2,5034.4
XS Rating Curve= 0 ,0
Exp/Cntr=0.3,0.1

Type RM Length L Ch R = 1 ,22936   ,447,447,447
BEGIN DESCRIPTION:
Guadalupe Tributary 51 27.0
END DESCRIPTION:
XS GIS Cut Line= 3
      2195774.97     13885974.97        2195525.       13885725.
      2195374.99     13885624.99
#Sta/Elev= 30
  4651.3 1014.19  4679.5 1012.45  4693.7 1009.11  4707.8 1004.16  4736.1  991.59
  4764.4  984.18  4806.8  980.03  4863.4  976.55  4891.7  971.45  4905.8  966.33
    4920  963.11  4948.2  962.07  4962.4  962.65  4976.5  961.66  4986.5  959.03
    4987  958.53  4994.8  959.03  5007.8  959.18  5012.3  960.44  5048.4  964.21
  5063.4  969.02  5076.9  974.75  5090.4  982.46  5120.5   994.8  5126.5  998.45
  5135.5 1001.69  5141.5 1005.56  5156.5 1011.38  5162.6 1013.47  5185.1 1015.19
#Mann= 3 ,-1 , 0
  4651.3     .12       0  4986.5     .05       0  4994.8     .12       0
Bank Sta=4986.5,4994.8
XS Rating Curve= 0 ,0
Exp/Cntr=0.3,0.1

Type RM Length L Ch R = 1 ,22489   ,476,476,476
BEGIN DESCRIPTION:
Guadalupe Tributary 51 26.0
END DESCRIPTION:
XS GIS Cut Line= 3
      2196224.97     13885724.98        2195875.       13885475.
      2195674.99     13885374.99
#Sta/Elev= 30
  4569.8 1013.73  4606.6 1010.61  4618.9  999.94  4655.8  983.99  4669.3  979.51
  4734.4  969.04  4763.9  968.63  4770.1  966.75  4799.6  966.37  4825.3  964.11
  4906.5  959.53    4936  959.24  4942.1  958.11  4971.6  958.55  4977.8  956.26
  4982.2  956.07  4982.7  955.57  4990.6  956.07  5008.3  957.26  5030.6  956.84
  5036.2   958.4    5053  959.45  5097.7  969.43  5103.3  969.67  5142.4  984.22
  5164.8  994.75  5170.4  996.42  5187.2 1005.19  5209.5 1011.84  5223.5 1012.34
#Mann= 4 ,-1 , 0
  4569.8     .07       0  4825.3     .12       0  4982.2     .05       0
  4990.6     .12       0
Bank Sta=4982.2,4990.6
XS Rating Curve= 0 ,0
Exp/Cntr=0.3,0.1

Type RM Length L Ch R = 1 ,22013   ,450,450,450
BEGIN DESCRIPTION:
Guadalupe Tributary 51 25.0
END DESCRIPTION:
XS GIS Cut Line= 3
      2196375.03     13885375.03        2196275.       13885275.
      2196174.99     13885174.99
#Sta/Elev= 29
  4858.5 1004.36  4862.1 1004.36  4872.7  1004.1  4886.8  999.71    4901  992.86
  4915.1  983.59  4929.3  974.55  4943.4  963.56  4957.5  954.72  4971.7  950.57
  4981.6  946.85  4982.1  946.35  4989.6  946.35  4990.1  946.85  4996.4   947.2
    5000   947.2  5003.5   947.2  5014.1  947.89  5028.3  955.42  5042.4  965.38
  5056.5  974.96  5070.7  980.46  5084.8  987.89    5099  993.56    5106  994.41
  5113.1  997.95  5127.2 1000.61  5137.9 1002.02  5141.4 1002.02
#Mann= 3 ,-1 , 0
  4858.5     .12       0  4981.6     .05       0  4990.1     .12       0
Bank Sta=4981.6,4990.1
XS Rating Curve= 0 ,0
Exp/Cntr=0.3,0.1

Type RM Length L Ch R = 1 ,21563   ,430,430,430
BEGIN DESCRIPTION:
Guadalupe Tributary 51 24.0
END DESCRIPTION:
XS GIS Cut Line= 3
      2196674.99     13885124.99        2196625.       13885025.
        2196475.       13884975.
#Sta/Elev= 30
    4888  994.71  4896.4  994.89    4902  993.46  4918.7  992.46  4932.7  989.47
  4941.1  980.78  4946.7  963.46  4955.1  958.25  4963.5  955.91    4969  951.85
  4977.4  947.79  4985.8  945.24  4992.7  942.46  4993.2  941.96  5000.7  941.96
  5001.2  942.46  5010.3  943.19  5020.9  945.27  5031.4  945.39    5042  946.86
  5052.5  951.03  5073.6  956.71  5084.1  960.81  5094.7   962.2  5105.2  965.39
  5115.7  975.72  5126.3   980.6  5136.8   982.9  5155.3  985.29  5157.9  985.29
#Mann= 3 ,-1 , 0
    4888     .12       0  4992.7     .05       0  5001.2     .12       0
Bank Sta=4992.7,5001.2
XS Rating Curve= 0 ,0
Exp/Cntr=0.3,0.1

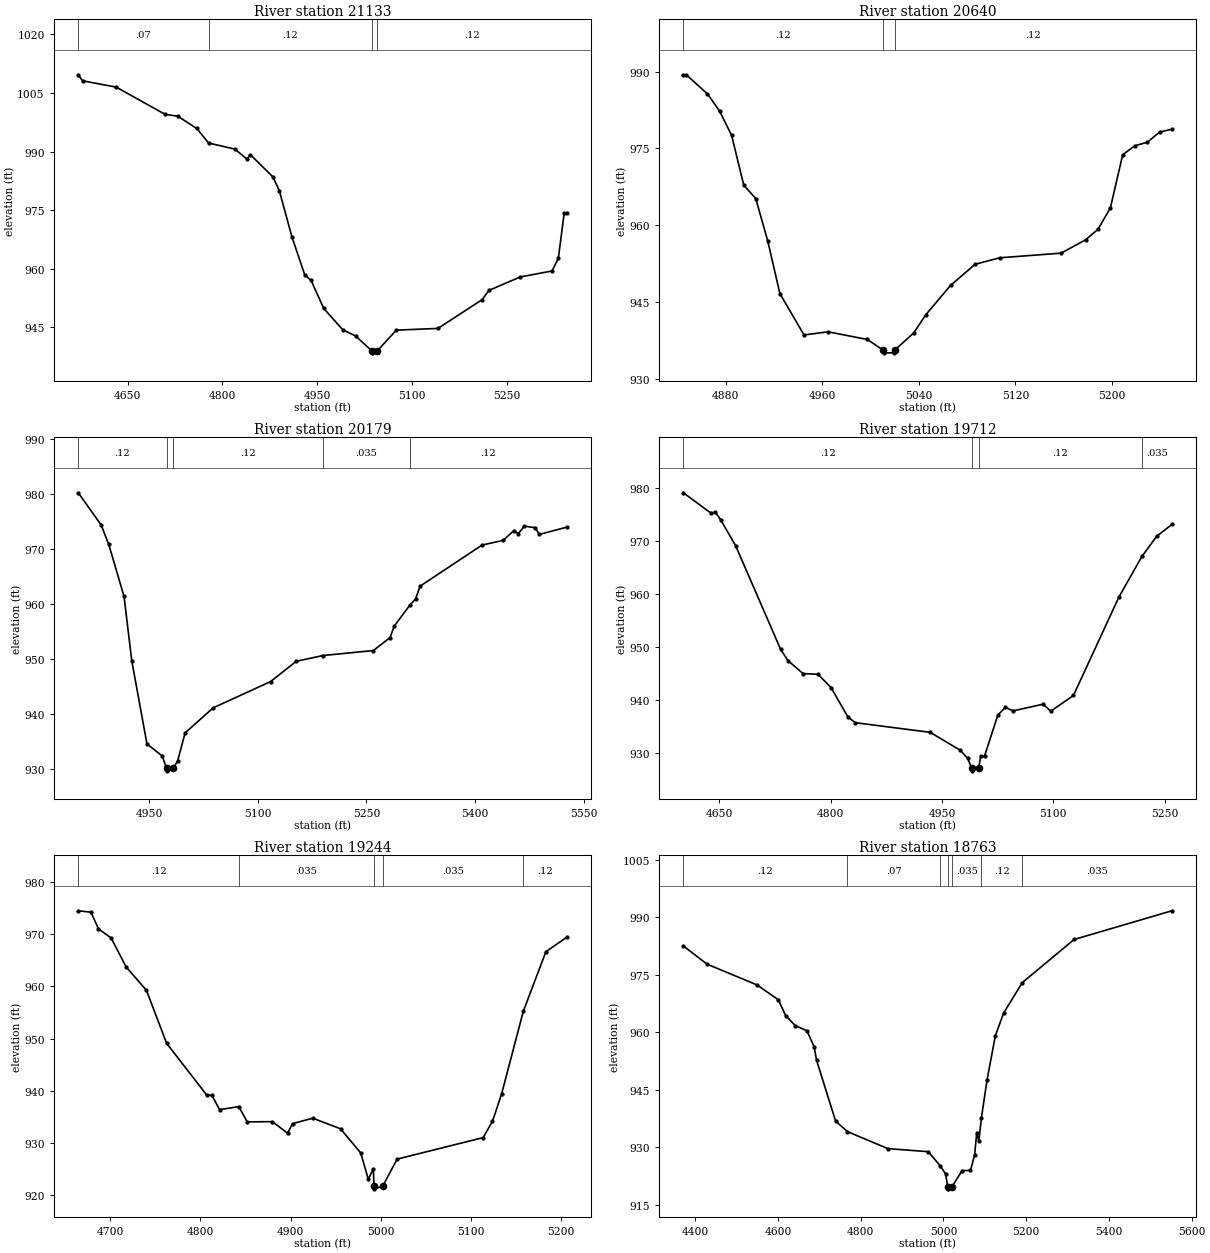
Type RM Length L Ch R = 1 ,21133   ,493,493,493
BEGIN DESCRIPTION:
Guadalupe Tributary 51 23.0
END DESCRIPTION:
XS GIS Cut Line= 3
      2196995.46     13885221.63      2196955.24     13884795.42
      2196930.97     13884451.57
#Sta/Elev= 30
  4571.9 1009.65  4578.6 1008.11  4631.9 1006.49  4709.1  999.53  4729.2  999.04
  4759.4   995.9    4778  992.18  4819.6  990.62  4838.8  988.05  4843.8  989.23
  4879.9  983.49  4889.9  979.98    4910  968.07  4930.1  958.46  4940.2  956.99
  4960.2  949.83  4990.4  944.35  5010.4  942.81  5036.2  938.97  5036.7  938.47
  5044.8  938.97    5075  944.28  5140.8  944.72  5210.9  952.11  5221.2  954.44
  5271.1   957.9  5321.2  959.42  5331.2  962.62  5340.5  974.21  5344.7  974.21
#Mann= 4 ,-1 , 0
  4571.9     .07       0    4778     .12       0  5036.2     .05       0
  5044.8     .12       0
Bank Sta=5036.2,5044.8
XS Rating Curve= 0 ,0
Exp/Cntr=0.3,0.1

Type RM Length L Ch R = 1 ,20640   ,461,461,461
BEGIN DESCRIPTION:
Guadalupe Tributary 51 22.0
END DESCRIPTION:
XS GIS Cut Line= 3
      2197324.98       13884375.        2197175.       13884375.
      2196925.03     13884424.99
#Sta/Elev= 30
  4844.8  989.39  4847.3  989.39  4864.8  985.64  4874.8  982.31  4884.8  977.54
  4894.8  967.84  4904.8   965.2  4914.8  956.84  4924.8  946.61  4944.8  938.53
  4964.8  939.14  4997.3  937.64  5010.5  935.53    5011  935.03  5019.3  935.03
  5019.8  935.53  5035.6  938.88  5045.8   942.5  5066.2   948.2  5086.6  952.35
    5107  953.61  5157.9  954.52  5178.3  957.15  5188.5  959.21  5198.7  963.36
  5208.9  973.76  5219.1  975.53  5229.3  976.19  5239.5  978.19  5249.7  978.75
#Mann= 3 ,-1 , 0
  4844.8     .12       0  5010.5     .05       0  5019.8     .12       0
Bank Sta=5010.5,5019.8
XS Rating Curve= 0 ,0
Exp/Cntr=0.3,0.1

Type RM Length L Ch R = 1 ,20179   ,467,467,467
BEGIN DESCRIPTION:
Guadalupe Tributary 51 21.0
END DESCRIPTION:
XS GIS Cut Line= 3
      2197274.97     13883925.01        2197125.       13883975.
      2196816.64     13884389.25
#Sta/Elev= 30
  4852.1  980.18  4883.7  974.32  4894.2  970.77  4915.3  961.31  4925.9  949.66
  4946.9  934.49    4968  932.29  4973.9  930.09  4974.4  929.59  4983.2  930.09
  4989.1  931.33  4999.6  936.49  5038.3  941.05  5117.6  945.83    5153  949.52
    5190  950.57  5259.5  951.48  5282.4  953.82  5288.6  955.98  5309.9  959.74
  5317.8  960.88    5324  963.19  5409.5  970.66  5438.8  971.53  5453.4   973.3
  5459.6  972.75    5468  974.11  5482.6  973.83  5488.8  972.61  5526.6  973.93
#Mann= 5 ,-1 , 0
  4852.1     .12       0  4973.9     .05       0  4983.2     .12       0
    5190    .035       0  5309.9     .12       0
Bank Sta=4973.9,4983.2
XS Rating Curve= 0 ,0
Exp/Cntr=0.3,0.1

Type RM Length L Ch R = 1 ,19712   ,468,468,468
BEGIN DESCRIPTION:
Guadalupe Tributary 51 20.0
END DESCRIPTION:
XS GIS Cut Line= 3
      2197324.95     13883624.99        2196925.       13883575.
      2196675.01       13883525.
#Sta/Elev= 30
  4601.8  979.05  4639.5  975.15  4644.6  975.45  4652.1  973.95  4672.3  969.02
  4732.8  949.48  4742.8  947.34    4763  944.91  4783.2  944.77  4800.8  942.25
  4823.5  936.69  4833.5  935.63  4934.3  933.81  4974.6  930.44  4984.7  928.92
  4990.1  927.04  4990.6  926.54  4999.5  927.04  5002.3  929.31  5007.4  929.31
  5025.3  937.05  5035.5  938.54  5045.7  937.86  5086.4  939.13  5096.6   937.8
  5127.2  940.78  5188.4  959.36  5219.4  967.03  5239.4  970.85  5259.8  973.07
#Mann= 4 ,-1 , 0
  4601.8     .12       0  4990.1     .05       0  4999.5     .12       0
  5219.4    .035       0
Bank Sta=4990.1,4999.5
XS Rating Curve= 0 ,0
Exp/Cntr=0.3,0.1

Type RM Length L Ch R = 1 ,19244   ,481,481,481
BEGIN DESCRIPTION:
Guadalupe Tributary 51 19.0
END DESCRIPTION:
XS GIS Cut Line= 3
      2197275.02     13883275.01        2196975.       13883125.
      2196774.99       13883075.
#Sta/Elev= 30
  4664.6   974.5  4678.6  974.23    4687  971.03    4701  969.29  4717.7  963.72
  4740.1  959.27  4762.5  949.11  4807.2  939.12  4812.8  939.12  4821.2  936.37
  4842.5  936.95  4851.9  934.03  4879.8  934.07  4896.6  931.85  4902.2   933.7
  4924.6  934.73  4955.3   932.7  4977.7  928.08  4986.1  923.02  4991.7  925.07
  4992.4  921.69  4992.9  921.19    5002  921.69  5018.1  926.89  5113.4  931.01
  5123.7  934.11    5134  939.46  5157.9  955.21    5183  966.66  5206.2  969.44
#Mann= 5 ,-1 , 0
  4664.6     .12       0  4842.5    .035       0  4992.4    .035       0
    5002    .035       0  5157.9     .12       0
Bank Sta=4992.4,5002
XS Rating Curve= 0 ,0
Exp/Cntr=0.3,0.1

Type RM Length L Ch R = 1 ,18763   ,407,407,407
BEGIN DESCRIPTION:
Guadalupe Tributary 51 18.0
END DESCRIPTION:
XS GIS Cut Line= 3
      2197542.88     13882933.34        2196975.       13882675.
      2196418.94     13882707.66
#Sta/Elev= 30
  4371.4  982.49  4428.6  977.75  4549.4  972.34    4601  968.47  4618.6  964.34
  4641.7  961.76  4670.2  960.38  4687.7  956.17  4693.3  952.75  4739.4  936.87
  4767.9  934.14  4865.7   929.7  4963.4  928.91  4992.9  925.14  5005.3   923.1
  5010.5  919.73    5011  919.23  5020.2  919.73  5045.4  923.98  5065.4  924.01
  5075.4  928.06  5080.5  933.79  5085.5  931.66  5091.9  937.75  5105.5  947.63
  5125.5   959.1  5145.5     965  5190.8  972.96  5315.8  984.17  5552.3  991.65
#Mann= 7 ,-1 , 0
  4371.4     .12       0  4767.9     .07       0  4992.9    .035       0
  5010.5    .035       0  5020.2    .035       0  5091.9     .12       0
  5190.8    .035       0
Bank Sta=5010.5,5020.2
XS Rating Curve= 0 ,0
Exp/Cntr=0.3,0.1

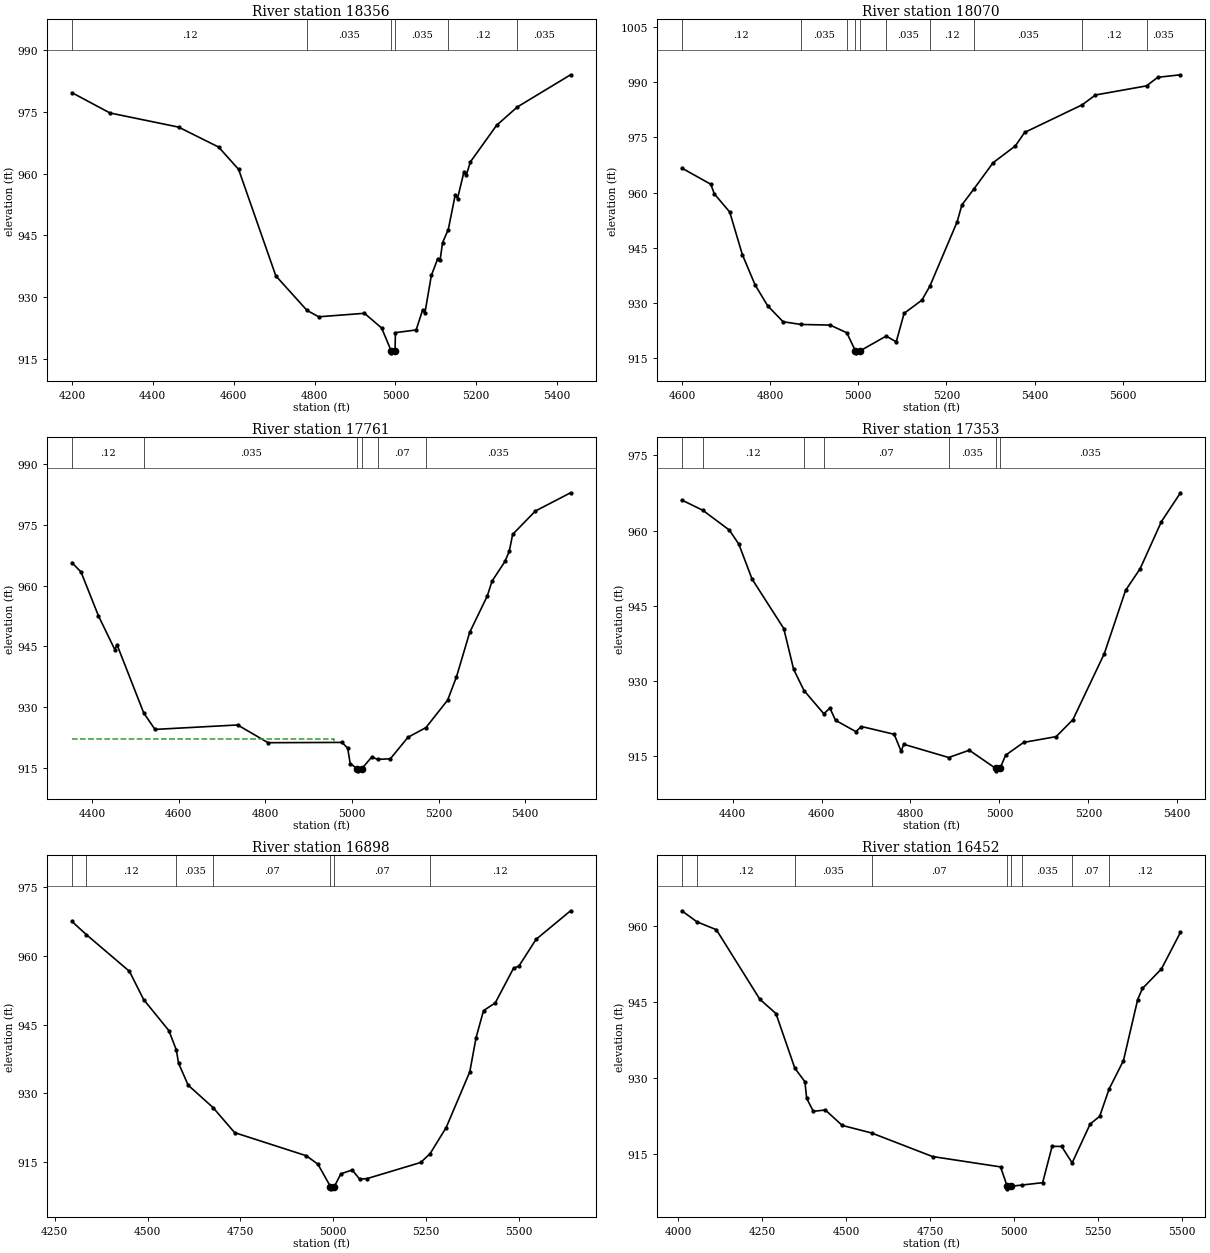
Type RM Length L Ch R = 1 ,18356   ,286,286,286
BEGIN DESCRIPTION:
Guadalupe Tributary 51 17.0
END DESCRIPTION:
XS GIS Cut Line= 3
      2197600.42     13882842.53      2197026.31     13882285.54
      2196650.03     13882499.98
#Sta/Elev= 30
  4200.1  979.66  4294.1  974.73  4463.8   971.3  4562.9  966.45  4612.3  961.03
  4704.3  935.19  4781.3  926.81  4810.3  925.25  4923.5   926.1  4965.9  922.53
  4989.4     917  4989.9   916.5  4999.1     917    5000   921.4  5051.3  922.06
  5067.2   926.9    5073  926.21  5088.8  935.28  5104.7  939.37  5110.4  938.96
  5116.6  943.27  5130.7  946.43  5147.9  954.85  5153.6  953.96  5169.5  960.45
  5175.2  959.62  5185.3  962.84  5250.2  971.73  5301.4  976.18  5433.1     984
#Mann= 6 ,-1 , 0
  4200.1     .12       0  4781.3    .035       0  4989.4    .035       0
  4999.1    .035       0  5130.7     .12       0  5301.4    .035       0
Bank Sta=4989.4,4999.1
XS Rating Curve= 0 ,0
Exp/Cntr=0.3,0.1

Type RM Length L Ch R = 1 ,18070   ,309,309,309
BEGIN DESCRIPTION:
Guadalupe Tributary 51 16.5
END DESCRIPTION:
XS GIS Cut Line= 3
      2197464.87     13882298.54      2197157.98     13882041.52
      2196433.87     13881940.65
#Sta/Elev= 30
  4599.7  966.67  4665.5  962.26  4673.3  959.68  4708.4   954.7    4737  943.14
  4765.7  934.95  4794.3  929.24  4829.4  924.87  4870.2  924.13  4936.1  923.96
    4974  921.87  4993.7  916.91  4994.2  916.41  5003.6  916.91  5063.4  920.97
  5086.2  919.39    5104  927.15  5144.4  930.74  5162.5  934.56  5224.3  952.02
  5235.2  956.66  5261.6  960.85    5306  968.13  5356.4  972.68  5377.5  976.36
  5508.3  983.88  5538.1  986.54    5654  989.02  5679.5  991.35  5731.1  992.04
#Mann= 10 ,-1 , 0
  4599.7     .12       0  4870.2    .035       0    4974     .07       0
  4993.7     .05       0  5003.6     .07       0  5063.4    .035       0
  5162.5     .12       0  5261.6    .035       0  5508.3     .12       0
    5654    .035       0
Bank Sta=4993.7,5003.6
XS Rating Curve= 0 ,0
Exp/Cntr=0.3,0.1

Type RM Length L Ch R = 1 ,17761   ,408,408,408
BEGIN DESCRIPTION:
Guadalupe Tributary 51 16.0
END DESCRIPTION:
XS GIS Cut Line= 3
      2197916.05     13881829.54       2197272.3     13881768.88
      2196775.95     13881675.83
#Sta/Elev= 30
  4353.4  965.69  4374.5  963.35  4414.7  952.53  4452.5  944.19  4457.5  945.42
  4519.4  928.52  4545.3  924.49  4736.1  925.59  4806.4  921.21  4977.2  921.28
  4990.2  919.86  4996.1  916.06  5012.7  914.76  5013.2  914.26  5022.6  914.76
  5045.6  917.65  5059.7  917.09  5088.8  917.24  5129.5  922.54  5171.1  924.95
  5221.1  931.73  5241.4  937.43    5272  948.45  5312.7  957.46  5323.7  961.13
  5353.4  965.96  5363.5  968.51  5371.2  972.65  5423.8  978.43    5505  982.93
#Mann= 6 ,-1 , 0
  4353.4     .12       0  4519.4    .035       0  5012.7    .035       0
  5022.6    .035       0  5059.7     .07       0  5171.1    .035       0
#XS Ineff= 2 , 0
       0 4958.28  922.05               0
Permanent Ineff=
       F       F
Bank Sta=5012.7,5022.6
XS Rating Curve= 0 ,0
Exp/Cntr=0.3,0.1

Type RM Length L Ch R = 1 ,17353   ,455,455,455
BEGIN DESCRIPTION:
Guadalupe Tributary 51 15.0
END DESCRIPTION:
XS GIS Cut Line= 3
      2197940.25     13881746.03        2197325.       13881375.
      2196924.98       13881325.
#Sta/Elev= 30
  4285.7  966.11  4332.9  964.07  4392.6  960.12    4414  957.31  4443.6  950.37
    4515  940.49  4537.1  932.38  4560.5  928.13  4605.1  923.49  4618.8  924.62
  4631.4  922.19  4677.2  919.93  4689.7  920.95  4763.4   919.4    4779  915.99
  4784.8  917.41  4885.9  914.77  4932.3  916.22  4991.4  912.61  4991.9  912.11
  5001.4  912.61  5014.2  915.25  5054.6  917.78  5127.6  918.93  5165.4  922.32
    5236  935.49  5283.8   948.1  5316.6  952.43  5364.5  961.83  5407.3  967.56
#Mann= 7 ,-1 , 0
  4285.7    .094       0  4332.9     .12       0  4560.5    .035       0
  4605.1     .07       0  4885.9    .035       0  4991.4    .035       0
  5001.4    .035       0
Bank Sta=4991.4,5001.4
XS Rating Curve= 0 ,0
Exp/Cntr=0.3,0.1

Type RM Length L Ch R = 1 ,16898   ,446,446,446
BEGIN DESCRIPTION:
Guadalupe Tributary 51 14.0
END DESCRIPTION:
XS GIS Cut Line= 3
      2198141.68       13881253.        2197475.       13881025.
      2196843.05     13881121.04
#Sta/Elev= 30
  4296.2   967.5  4335.4   964.6  4451.2  956.61  4489.5  950.45  4557.4  943.69
  4577.7  939.43  4583.5  936.58  4609.5  931.77  4676.7  926.88  4734.7  921.42
  4927.8  916.38  4959.1  914.54  4992.9  909.66  4993.4  909.16  5003.4  909.66
    5021  912.43  5051.4  913.28  5071.6  911.28  5091.8   911.4  5236.1  914.91
  5261.6  916.86  5304.8  922.54  5368.4  934.69  5385.2  942.11  5405.4  948.03
  5437.1  949.73  5486.3  957.29  5500.7  957.74    5547  963.59    5640  969.82
#Mann= 7 ,-1 , 0
  4296.2     .07       0  4335.4     .12       0  4577.7    .035       0
  4676.7     .07       0  4992.9     .05       0  5003.4     .07       0
  5261.6     .12       0
Bank Sta=4992.9,5003.4
XS Rating Curve= 0 ,0
Exp/Cntr=0.3,0.1

Type RM Length L Ch R = 1 ,16452   ,446,446,446
BEGIN DESCRIPTION:
Guadalupe Tributary 51 13.0
END DESCRIPTION:
XS GIS Cut Line= 3
       2198252.8     13881016.89        2197325.       13880675.
      2196974.97     13881025.03
#Sta/Elev= 30
    4011  962.91  4056.2  960.73  4113.8  959.18  4243.1  945.49  4291.1  942.68
  4347.3  931.91  4377.2  929.26  4382.5  925.98  4402.3  923.42    4438  923.69
  4488.2  920.65  4575.6  919.16    4757  914.52  4959.4  912.48  4979.2  908.66
  4979.7  908.16  4989.9  908.66  5024.5  908.92  5084.6  909.37  5112.9  916.54
  5141.2   916.5  5172.4  913.27  5226.1  920.93  5254.3  922.43  5282.4  927.81
  5325.1  933.41  5367.5  945.44  5381.6  947.61  5438.2  951.46  5494.8  958.68
#Mann= 9 ,-1 , 0
    4011     .07       0  4056.2     .12       0  4347.3    .035       0
  4575.6     .07       0  4979.2     .05       0  4989.9     .07       0
  5024.5    .035       0  5172.4     .07       0  5282.4     .12       0
Bank Sta=4979.2,4989.9
XS Rating Curve= 0 ,0
Exp/Cntr=0.3,0.1

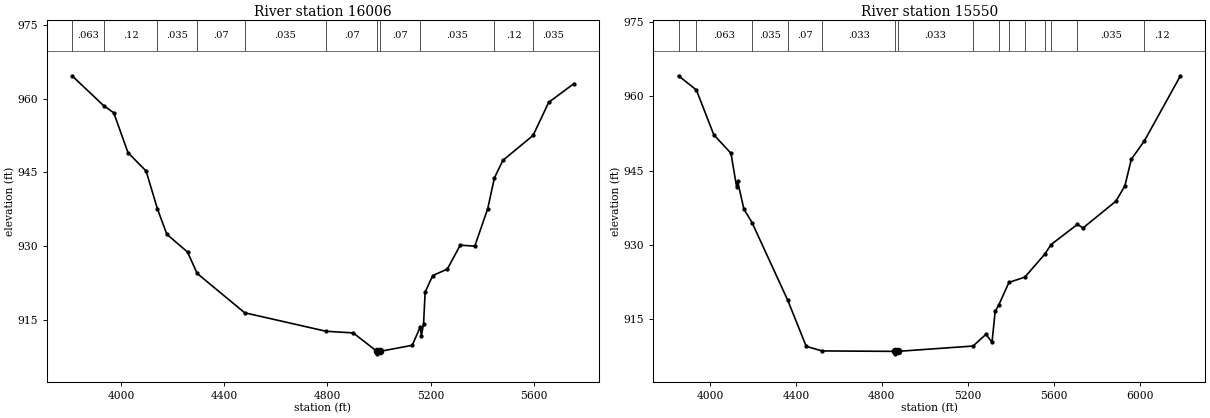
Type RM Length L Ch R = 1 ,16006   ,456,456,456
BEGIN DESCRIPTION:
Guadalupe Tributary 51 12.0
END DESCRIPTION:
XS GIS Cut Line= 3
      2198461.11     13880384.93        2197275.       13880275.
      2196662.46     13880718.28
#Sta/Elev= 30
  3808.8  964.63  3930.9  958.59  3970.6  957.11  4025.8  949.03  4096.1   945.3
    4140  937.63  4176.5  932.46  4256.8  928.86  4294.4   924.5  4478.5  916.53
  4794.6  912.77  4899.6  912.44  4992.1  908.69  4992.6  908.19  5002.9  908.69
  5128.8  909.92  5159.9  913.63  5164.3  911.86  5172.8  914.25    5179  920.72
  5208.4  924.08  5264.9  925.39  5315.2  930.25  5371.6  930.05  5421.9  937.66
  5447.7   943.9  5480.7  947.46  5597.8  952.52  5658.5  959.24  5756.1  963.03
#Mann= 11 ,-1 , 0
  3808.8    .063       0  3930.9     .12       0    4140    .035       0
  4294.4     .07       0  4478.5    .035       0  4794.6     .07       0
  4992.1     .05       0  5002.9     .07       0  5159.9    .035       0
  5447.7     .12       0  5597.8    .035       0
Bank Sta=4992.1,5002.9
XS Rating Curve= 0 ,0
Exp/Cntr=0.3,0.1

Type RM Length L Ch R = 1 ,15550   ,2302,2302,2302
BEGIN DESCRIPTION:
Guadalupe Tributary 51 11.0
END DESCRIPTION:
XS GIS Cut Line= 3
      2198488.92     13879829.37        2197325.       13879875.
      2196358.48     13880536.64
#Sta/Elev= 30
  3853.9  964.17  3936.9   961.3  4017.9  952.26    4098  948.49  4124.1  941.75
  4129.1  942.81  4158.1  937.23  4196.3  934.46  4362.3  918.78  4448.3  909.46
  4521.6  908.53    4863  908.44  4863.5  907.94  4874.1  908.44  5225.3  909.52
  5285.3   911.9  5313.2  910.26  5328.1  916.53  5344.4  917.79  5392.1  922.38
  5466.4  923.46  5558.9  928.09  5588.3  930.04  5710.3   934.1  5737.7  933.42
  5890.1  938.81    5932  941.92  5961.9  947.29  6023.2  951.05    6190  964.12
#Mann= 15 ,-1 , 0
  3853.9     .12       0  3936.9    .063       0  4196.3    .035       0
  4362.3     .07       0  4521.6    .033       0    4863    .033       0
  4874.1    .033       0  5225.3    .035       0  5344.4     .07       0
  5392.1    .035       0  5466.4     .07       0  5558.9    .035       0
  5588.3     .07       0  5710.3    .035       0  6023.2     .12       0
Bank Sta=4863,4874.1
XS Rating Curve= 0 ,0
Exp/Cntr=0.3,0.1