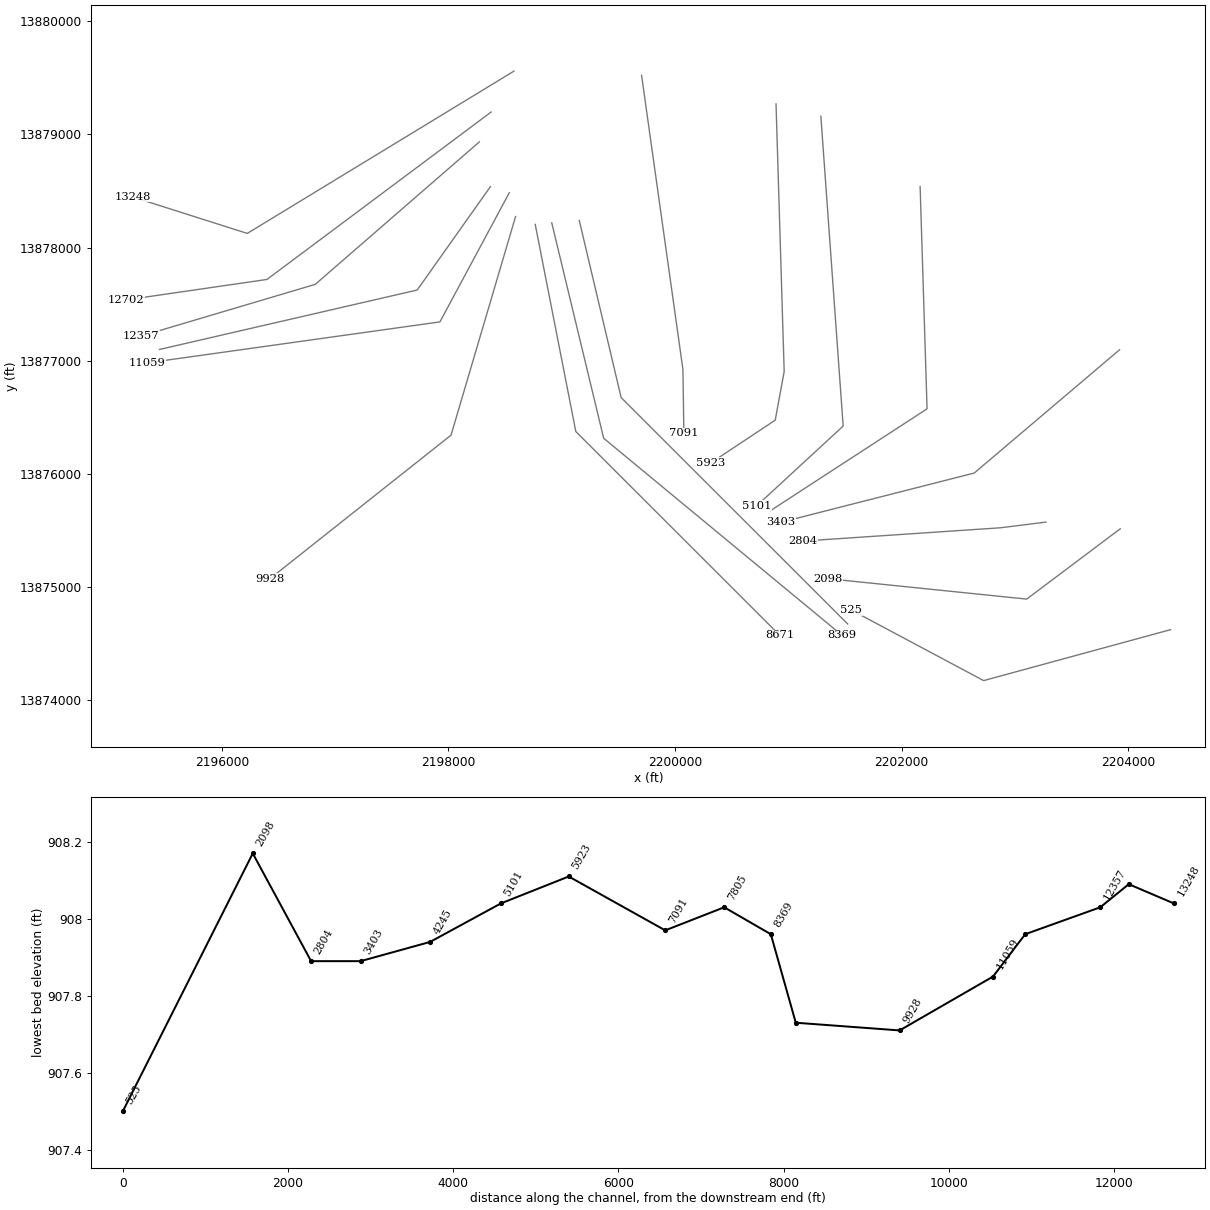
HEC-RAS study Guadalupe Tributary 51.prj: Guadalupe Tributary 51 Base Level Engineering

--- Guadalupe Tributary 51.g01 (geometry) --- (continued)

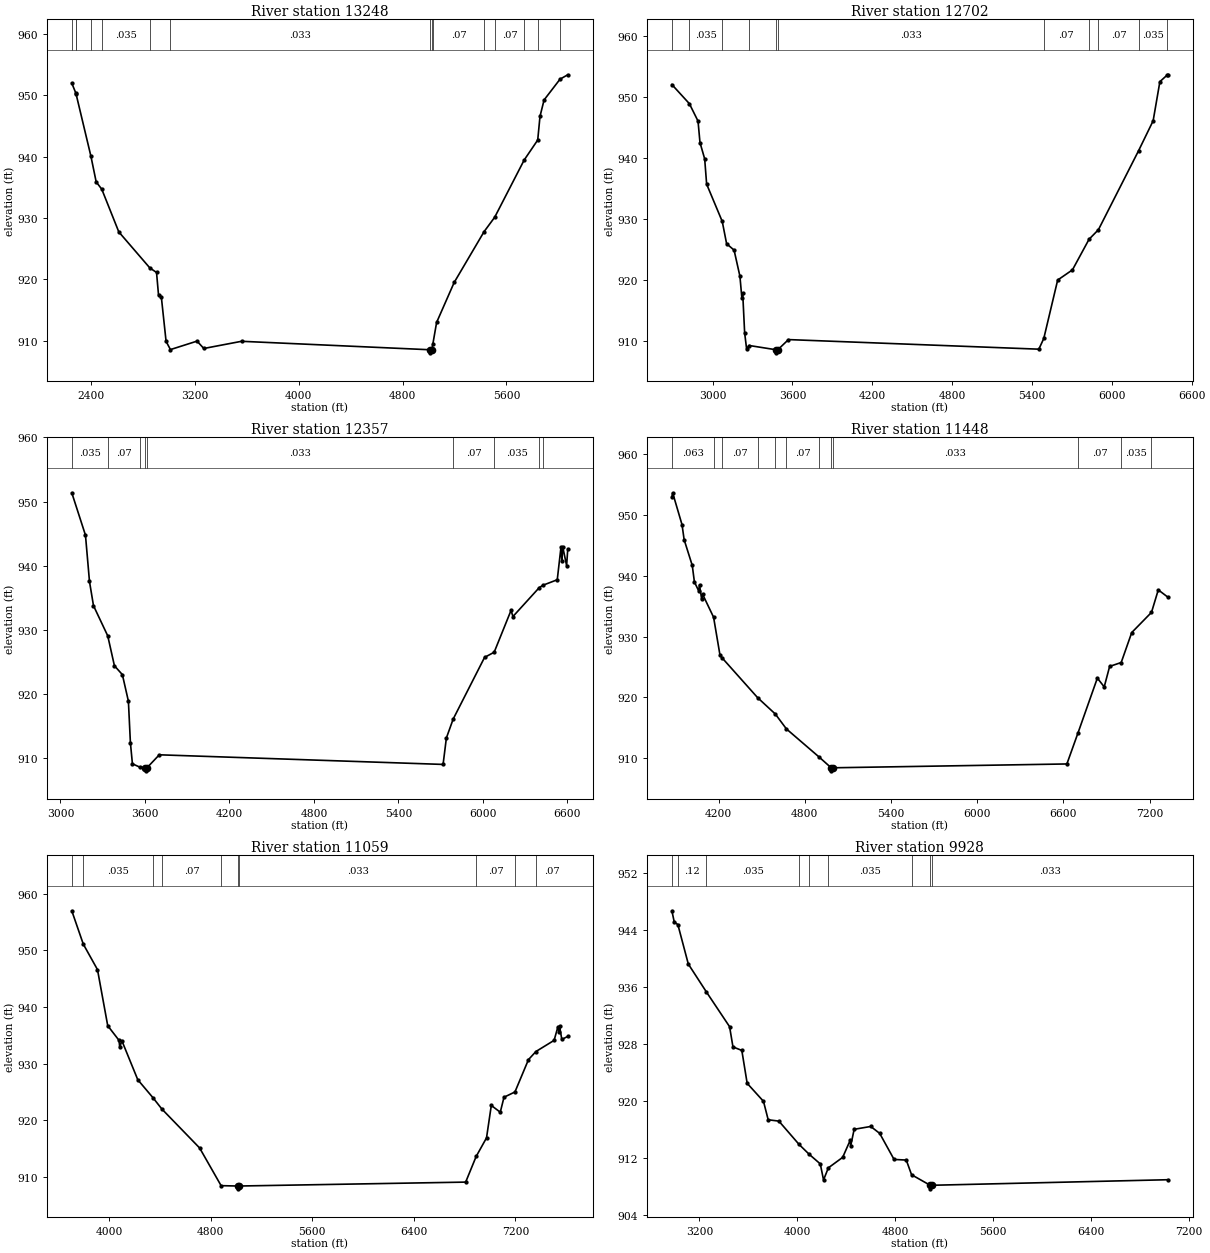
Type RM Length L Ch R = 1 ,13248   ,546,546,546
BEGIN DESCRIPTION:
Guadalupe Tributary 51 10.0
END DESCRIPTION:
XS GIS Cut Line= 3
      2198579.13     13879558.53        2196225.       13878125.
      2195211.09     13878447.43
#Sta/Elev= 30
  2251.9  951.98  2283.9  950.31  2285.9  950.13  2399.2  940.08  2439.8  935.89
  2482.9   934.7  2614.1  927.74  2852.4  921.89  2904.7  921.13  2920.1  917.44
  2941.5  917.18  2978.2  909.91  3011.8  908.57  3216.8  909.95  3268.8  908.75
  3559.4  909.92  5012.9  908.54  5013.4  908.04  5024.4  908.54  5033.2  909.51
  5061.8  912.99    5197   919.5  5427.7  927.79  5509.5  930.14  5736.2  939.45
  5840.6  942.71  5858.1  946.56  5889.6  949.24  6012.7  952.63  6072.1  953.34
#Mann= 15 ,-1 , 0
  2251.9    .035       0  2283.9    .063       0  2285.9    .035       0
  2399.2     .07       0  2482.9    .035       0  2852.4     .07       0
  3011.8    .033       0  5012.9    .033       0  5024.4    .033       0
  5033.2     .07       0  5427.7    .035       0  5509.5     .07       0
  5736.2    .035       0  5840.6     .07       0  6012.7    .035       0
Bank Sta=5012.9,5024.4
XS Rating Curve= 0 ,0
Exp/Cntr=0.3,0.1

Type RM Length L Ch R = 1 ,12702   ,345,345,345
BEGIN DESCRIPTION:
Guadalupe Tributary 51 9.0
END DESCRIPTION:
XS GIS Cut Line= 3
      2198377.78     13879197.44      2196398.59     13877718.26
       2195155.5      13877537.7
#Sta/Elev= 30
  2694.2  952.03  2825.6   948.9  2890.8  946.04  2905.4  942.53  2940.8  939.85
  2955.4  935.72  3072.7  929.61  3105.5  925.96  3161.7  924.91  3205.5  920.64
  3220.1  917.08  3226.4  917.89    3241  911.37  3255.5  908.78  3275.5  909.29
  3478.4  908.59  3478.9  908.09  3489.9  908.59  3570.3  910.26  5451.6  908.69
  5488.9  910.45  5593.1  920.01  5704.3  921.68  5828.9  926.69  5899.2  928.25
    6201  941.19  6310.6   946.1  6361.1   952.5  6415.2  953.57  6421.2  953.63
#Mann= 11 ,-1 , 0
  2694.2     .12       0  2825.6    .035       0  3072.7     .07       0
  3275.5    .033       0  3478.4    .033       0  3489.9    .033       0
  5488.9     .07       0  5828.9    .035       0  5899.2     .07       0
    6201    .035       0  6415.2    .063       0
Bank Sta=3478.4,3489.9
XS Rating Curve= 0 ,0
Exp/Cntr=0.3,0.1

Type RM Length L Ch R = 1 ,12357   ,909,909,909
BEGIN DESCRIPTION:
Guadalupe Tributary 51 8.0
END DESCRIPTION:
XS GIS Cut Line= 3
      2198273.58     13878933.52        2196825.       13877675.
      2195288.77     13877218.64
#Sta/Elev= 30
  3080.8  951.38    3178  944.77  3206.5  937.55  3234.9  933.78  3336.2  929.07
  3383.6  924.41    3440  923.03  3482.8  918.89    3497  912.42  3511.3  909.13
  3562.2  908.62  3604.2  908.53  3604.7  908.03  3615.8  908.53  3702.1  910.53
    5717  909.03  5740.4  913.15  5788.6   916.1  6011.6  925.72  6079.7  926.52
  6199.4  933.04  6213.1  932.09    6400   936.6  6426.5  936.97  6527.6  937.82
  6554.1   942.9  6560.9  940.69  6566.1  942.99  6594.1  940.03  6602.3  942.65
#Mann= 9 ,-1 , 0
  3080.8    .035       0  3336.2     .07       0  3562.2    .033       0
  3604.2    .033       0  3615.8    .033       0  5788.6     .07       0
  6079.7    .035       0    6400     .07       0  6426.5    .035       0
Bank Sta=3604.2,3615.8
XS Rating Curve= 0 ,0
Exp/Cntr=0.3,0.1

Type RM Length L Ch R = 1 ,11448   ,389,389,389
BEGIN DESCRIPTION:
Guadalupe Tributary 51 7.0
END DESCRIPTION:
XS GIS Cut Line= 3
       2198370.8     13878537.69        2197725.       13877625.
      2195449.96     13877099.99
#Sta/Elev= 30
  3874.6  952.85    3880   953.6  3945.3  948.36    3960   945.9  4016.6  941.67
  4031.4  938.97    4061  937.51  4067.1  938.49  4081.9  936.12    4088  936.97
    4165  933.17  4209.9   926.9  4225.2  926.48  4471.5  919.97  4594.6  917.29
    4672  914.84  4898.4  910.25  4983.8  908.46  4984.3  907.96  4995.5  908.46
  6624.5  909.09  6701.5  914.16  6836.6  923.18  6884.4  921.74  6922.1   925.1
  7002.6  925.74    7076  930.66  7213.5  933.97  7260.7  937.66  7327.5  936.47
#Mann= 12 ,-1 , 0
  3874.6    .063       0    4165    .035       0  4225.2     .07       0
  4471.5    .063       0  4594.6    .094       0    4672     .07       0
  4898.4    .033       0  4983.8    .033       0  4995.5    .033       0
  6701.5     .07       0  7002.6    .035       0  7213.5     .07       0
Bank Sta=4983.8,4995.5
XS Rating Curve= 0 ,0
Exp/Cntr=0.3,0.1

Type RM Length L Ch R = 1 ,11059   ,1131,1131,1131
BEGIN DESCRIPTION:
Guadalupe Tributary 51 6.5
END DESCRIPTION:
XS GIS Cut Line= 3
      2198537.82     13878484.52      2197925.49     13877343.44
      2195338.37     13876980.84
#Sta/Elev= 30
    3705  956.99  3795.6   951.1  3907.5  946.59  3988.2  936.68  4077.2  934.09
  4082.9  932.83  4099.1  934.05    4225  927.13  4345.4  923.93  4414.9  921.95
  4712.2  915.07  4881.4  908.41  5014.3  908.35  5014.8  907.85    5026  908.35
    6808  909.04  6890.6  913.57  6972.3  916.86  7009.9  922.59  7080.6  921.39
    7110  924.04  7196.2  924.97  7302.8  930.69  7361.6  932.12  7504.7  934.09
    7535  936.51  7543.2  935.55  7548.3  936.55  7565.3  934.25  7612.4  934.79
#Mann= 10 ,-1 , 0
    3705     .12       0  3795.6    .035       0  4345.4    .094       0
  4414.9     .07       0  4881.4    .033       0  5014.3    .033       0
    5026    .033       0  6890.6     .07       0  7196.2    .035       0
  7361.6     .07       0
Bank Sta=5014.3,5026
XS Rating Curve= 0 ,0
Exp/Cntr=0.3,0.1

Type RM Length L Ch R = 1 ,9928    ,1257,1257,1257
BEGIN DESCRIPTION:
Guadalupe Tributary 51 6.0
END DESCRIPTION:
XS GIS Cut Line= 3
      2198593.02     13878273.78      2198023.59     13876343.26
      2196425.02     13875075.02
#Sta/Elev= 30
  2974.8  946.76  2994.4  945.17  3023.8  944.82  3109.1  939.28    3257  935.36
  3446.5  930.48    3474  927.64  3546.4  927.15  3590.1  922.53  3723.4     920
  3761.9  917.41  3849.3  917.22  4014.6  913.94    4097  912.56  4187.7  911.21
  4214.2  908.96  4253.7  910.66  4370.6  912.13  4431.3   914.5  4436.5  913.77
  4464.4  916.07    4600  916.47    4673   915.5  4790.5  911.84  4890.4  911.75
  4933.6  909.69  5085.9  908.21  5086.4  907.71  5097.7  908.21  7028.1  908.99
#Mann= 9 ,-1 , 0
  2974.8    .035       0  3023.8     .12       0    3257    .035       0
  4014.6     .07       0    4097     .12       0  4253.7    .035       0
  4933.6    .033       0  5085.9    .033       0  5097.7    .033       0
Bank Sta=5085.9,5097.7
XS Rating Curve= 0 ,0
Exp/Cntr=0.3,0.1

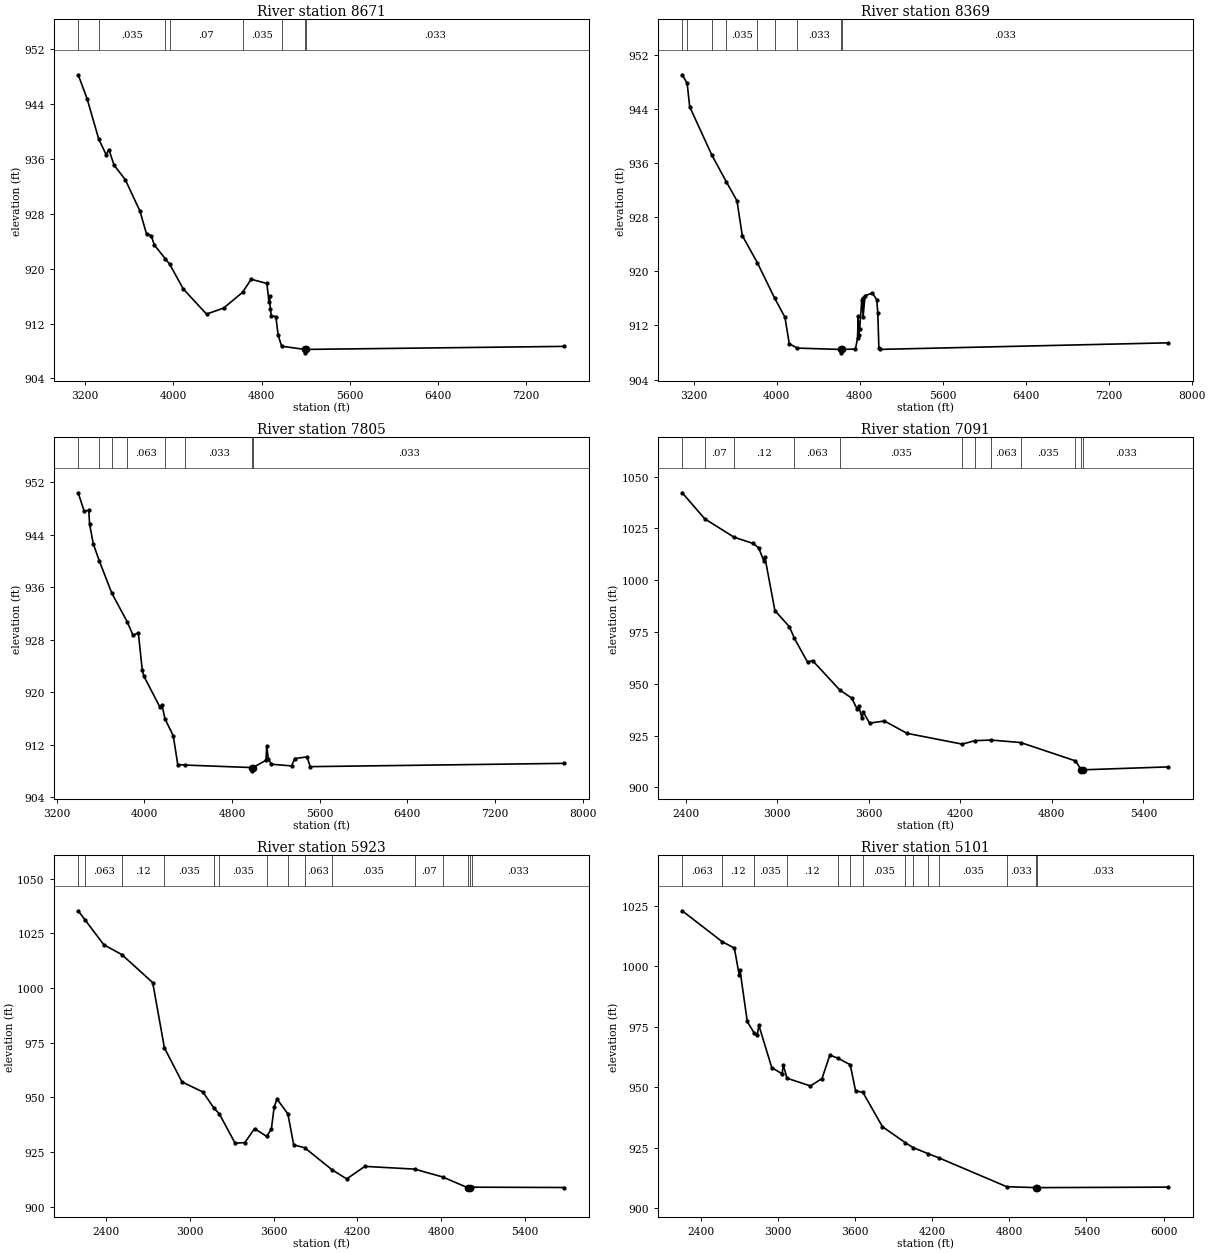
Type RM Length L Ch R = 1 ,8671    ,302,302,302
BEGIN DESCRIPTION:
Guadalupe Tributary 51 5.0
END DESCRIPTION:
XS GIS Cut Line= 3
      2198766.64     13878204.39        2199125.       13876375.
      2200924.97     13874575.03
#Sta/Elev= 30
  3136.2   948.2  3217.1  944.72  3323.1  938.82  3390.3  936.56  3414.8  937.32
  3461.2  935.06  3563.6  932.93    3696  928.38  3757.2  924.97  3797.9   924.8
  3826.7  923.43  3926.8  921.42  3967.2   920.6  4089.2  917.03  4300.2  913.37
  4454.7  914.24  4626.8  916.53  4704.8  918.44  4847.5  917.83  4866.5  915.16
  4871.6  915.96  4878.1  914.13  4888.3  913.15    4929  912.99  4949.4  910.34
  4981.3  908.69  5192.4  908.23  5192.9  907.73  5204.3  908.23  7545.9  908.67
#Mann= 8 ,-1 , 0
  3136.2     .12       0  3323.1    .035       0  3926.8    .063       0
  3967.2     .07       0  4626.8    .035       0  4981.3    .033       0
  5192.4    .033       0  5204.3    .033       0
Bank Sta=5192.4,5204.3
XS Rating Curve= 0 ,0
Exp/Cntr=0.3,0.1

Type RM Length L Ch R = 1 ,8369    ,564,564,564
BEGIN DESCRIPTION:
Guadalupe Tributary 51 4.0
END DESCRIPTION:
XS GIS Cut Line= 3
      2198912.49     13878218.24      2199370.81     13876315.48
        2201475.       13874575.
#Sta/Elev= 30
  3088.6  949.04  3136.1  947.78  3161.1   944.3  3373.5   937.2  3513.1  933.25
  3616.5  930.43  3667.9  925.28    3812   921.3  3979.8  916.04  4079.4   913.2
  4120.5   909.3  4198.5  908.66  4618.5  908.46    4619  907.96  4630.5  908.46
  4758.3  908.52  4778.8   910.1    4785  913.37  4790.2  910.64  4799.4  911.55
    4820  915.75    4827     916  4832.1  913.22  4850.8   916.4  4922.8   916.8
    4964  915.79  4974.3  913.83  4984.6  908.65  4994.6  908.47  7776.5  909.44
#Mann= 9 ,-1 , 0
  3088.6     .12       0  3136.1    .035       0  3373.5     .12       0
  3513.1    .035       0    3812    .063       0  3979.8    .035       0
  4198.5    .033       0  4618.5    .033       0  4630.5    .033       0
Bank Sta=4618.5,4630.5
XS Rating Curve= 0 ,0
Exp/Cntr=0.3,0.1

Type RM Length L Ch R = 1 ,7805    ,714,714,714
BEGIN DESCRIPTION:
Guadalupe Tributary 51 3.0
END DESCRIPTION:
XS GIS Cut Line= 3
      2199155.55     13878239.05        2199525.       13876675.
      2201524.98     13874675.02
#Sta/Elev= 30
  3397.3  950.39  3452.8  947.54  3493.9  947.74  3501.4  945.64    3535  942.63
    3591  939.97  3704.5  935.09  3844.9  930.72  3897.5  928.69  3946.1  929.06
  3982.1  923.36  3997.4  922.44  4141.3  917.79  4161.8  918.06  4189.3  915.93
  4264.6  913.38  4305.7  908.99  4375.7  908.91  4979.7  908.53  4980.2  908.03
  4991.9  908.53  5110.5  909.64  5117.5  911.79  5131.7  909.83    5160  909.04
  5343.8  908.78  5372.1   909.9  5485.2  910.15  5513.5  908.67  7832.8  909.17
#Mann= 8 ,-1 , 0
  3397.3    .035       0    3591     .12       0  3704.5    .035       0
  3844.9    .063       0  4189.3    .035       0  4375.7    .033       0
  4979.7    .033       0  4991.9    .033       0
Bank Sta=4979.7,4991.9
XS Rating Curve= 0 ,0
Exp/Cntr=0.3,0.1

Type RM Length L Ch R = 1 ,7091    ,1168,1168,1168
BEGIN DESCRIPTION:
Guadalupe Tributary 51 2.5
END DESCRIPTION:
XS GIS Cut Line= 3
      2199705.39     13879520.75      2200070.27     13876924.57
      2200078.79     13876360.13
#Sta/Elev= 30
  2378.3 1042.19  2525.8 1029.64  2717.8 1020.75    2843 1017.72  2878.9 1015.63
  2914.3 1009.09  2919.4 1011.35  2985.6  985.32  3080.9   977.5  3113.5  971.91
  3199.4  960.46  3232.4  961.19  3410.3  947.02  3489.5  943.05  3525.2  937.67
  3535.3   939.4  3555.5  933.44  3565.8  936.22    3606     931  3703.3  932.03
  3850.9  926.08  4213.1  920.86  4296.2  922.54  4402.4  922.83  4596.2  921.62
  4954.8  912.78  4992.9  908.47  4993.4  907.97  5005.1  908.47  5564.5  909.88
#Mann= 12 ,-1 , 0
  2378.3     .12       0  2525.8     .07       0  2717.8     .12       0
  3113.5    .063       0  3410.3    .035       0  4213.1    .063       0
  4296.2    .035       0  4402.4    .063       0  4596.2    .035       0
  4954.8    .033       0  4992.9    .033       0  5005.1    .033       0
Bank Sta=4992.9,5005.1
XS Rating Curve= 0 ,0
Exp/Cntr=0.3,0.1

Type RM Length L Ch R = 1 ,5923    ,822,822,822
BEGIN DESCRIPTION:
Guadalupe Tributary 51 2.4
END DESCRIPTION:
XS GIS Cut Line= 4
      2200892.21     13879269.04       2200964.2     13876904.63
      2200885.19     13876475.45      2200315.62      13876097.6
#Sta/Elev= 30
  2198.1 1035.39  2248.3 1031.15  2382.2 1019.83  2511.1 1015.34  2732.4 1002.51
  2816.3  972.62  2942.5  957.05  3092.6  952.42  3170.3  945.15  3209.7  942.46
  3322.7  929.01  3392.7  929.28  3462.7  935.69  3548.7  932.13  3582.8   935.4
  3602.8  945.47  3622.8  949.24  3701.2  942.44  3742.9  928.24  3821.6  926.94
  4018.2  916.81    4123  912.66  4253.1  918.39  4609.2  917.14  4810.4  913.55
  4991.4  908.61  4991.9  908.11    5004  908.61  5021.5  908.87  5683.5  908.72
#Mann= 15 ,-1 , 0
  2198.1     .12       0  2248.3    .063       0  2511.1     .12       0
  2816.3    .035       0  3170.3     .12       0  3209.7    .035       0
  3548.7    .063       0  3701.2    .035       0  3821.6    .063       0
  4018.2    .035       0  4609.2     .07       0  4810.4    .035       0
  4991.4    .035       0    5004    .035       0  5021.5    .033       0
Bank Sta=4991.4,5004
XS Rating Curve= 0 ,0
Exp/Cntr=0.3,0.1

Type RM Length L Ch R = 1 ,5101    ,856,856,856
BEGIN DESCRIPTION:
Guadalupe Tributary 51 2.3
END DESCRIPTION:
XS GIS Cut Line= 3
      2201287.92     13879159.69      2201484.85     13876423.17
      2200721.62     13875718.92
#Sta/Elev= 30
  2256.4 1022.99    2568 1010.18  2662.1 1007.57  2700.3  996.24  2705.3  998.66
  2762.4  977.22  2814.2   972.6  2840.1  971.47  2852.6  975.64  2952.9  958.17
  3033.1  955.59  3043.1   959.2  3071.1  953.77  3253.7  950.58  3343.9  953.65
  3404.5  963.31  3464.7  962.11  3563.1  959.37  3604.6  948.58  3661.6  947.93
    3814  933.71  3991.6  927.13  4051.8   925.1  4166.7  922.62    4257  920.75
  4780.5  908.92  5006.7  908.54  5007.2  908.04  5019.4  908.54  6038.5  908.75
#Mann= 14 ,-1 , 0
  2256.4    .063       0    2568     .12       0  2814.2    .035       0
  3071.1     .12       0  3464.7    .035       0  3563.1    .063       0
  3661.6    .035       0  3991.6    .063       0  4051.8    .035       0
  4166.7    .063       0    4257    .035       0  4780.5    .033       0
  5006.7    .033       0  5019.4    .033       0
Bank Sta=5006.7,5019.4
XS Rating Curve= 0 ,0
Exp/Cntr=0.3,0.1

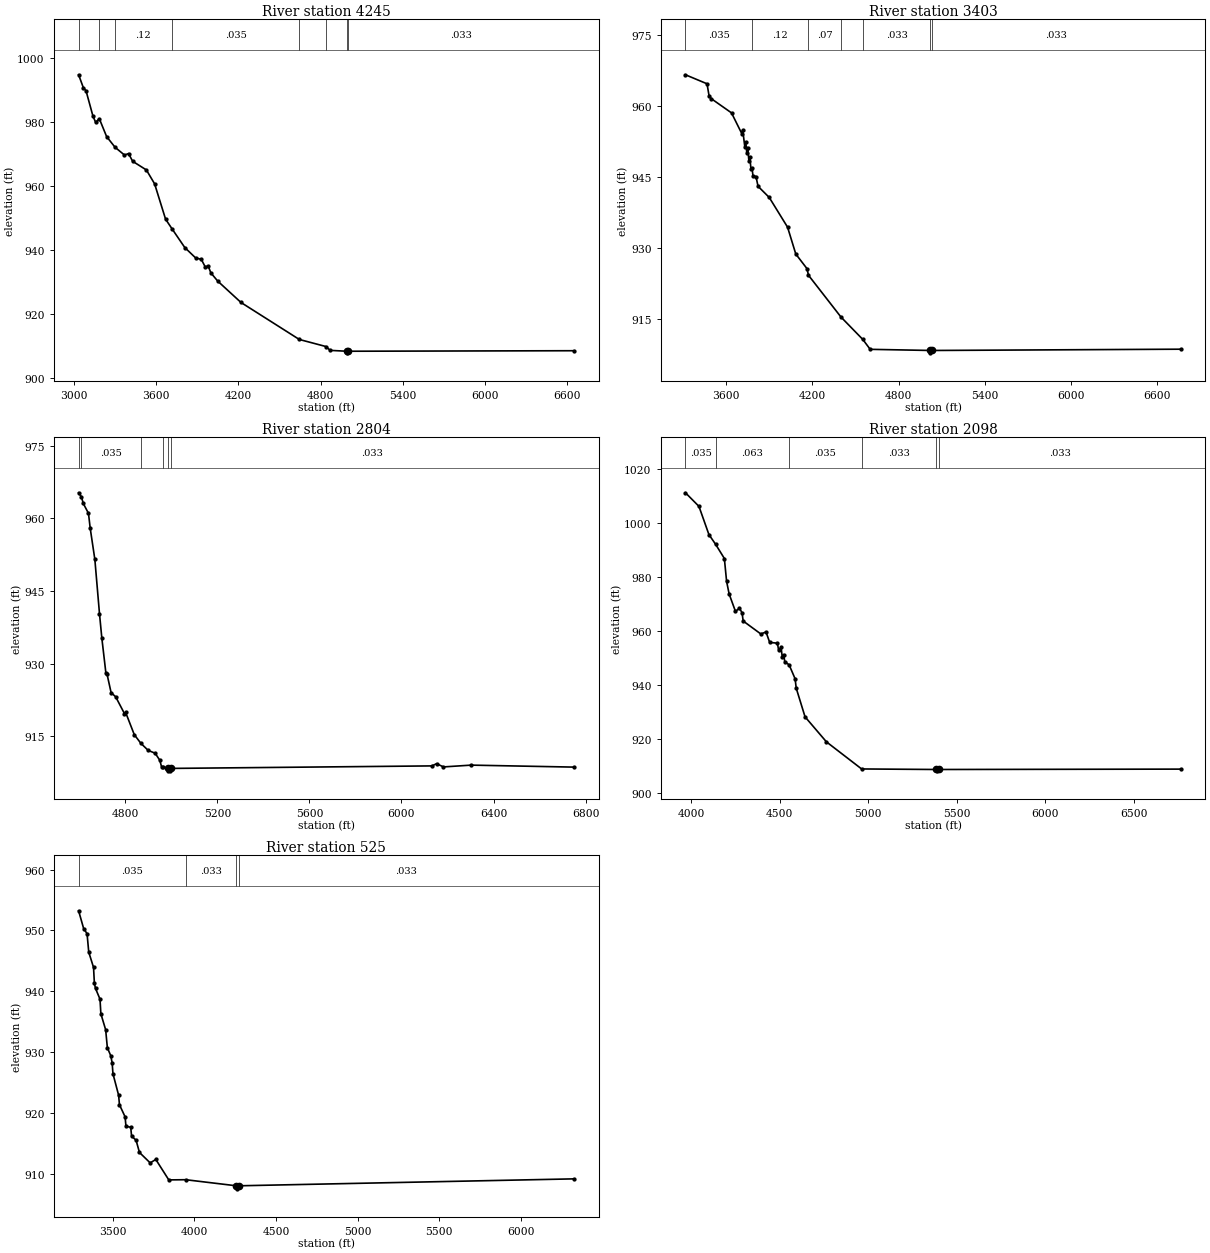
Type RM Length L Ch R = 1 ,4245    ,842,842,842
BEGIN DESCRIPTION:
Guadalupe Tributary 51 2.2
END DESCRIPTION:
XS GIS Cut Line= 3
      2202164.18     13878539.14      2202225.48     13876575.49
      2200844.35     13875676.75
#Sta/Elev= 30
  3035.4  994.65  3069.6  990.66  3089.6  989.65  3139.6  981.82  3159.6  979.81
  3186.5  980.95  3239.6  975.38  3301.1  972.05  3369.7  969.63  3399.7  970.08
  3429.7  967.67  3529.8  964.97  3589.8  960.64  3669.8  949.62  3715.4  946.71
  3809.9  940.78    3890   937.5    3930  937.12    3960  934.66    3980  935.08
    4000  932.89    4050  930.32  4220.1  923.64  4645.4  912.11  4839.4  909.91
  4870.4  908.71  4991.3  908.44  4991.8  907.94  5004.1  908.44  6647.8   908.6
#Mann= 8 ,-1 , 0
  3035.4    .035       0  3186.5    .063       0  3301.1     .12       0
  3715.4    .035       0  4645.4     .07       0  4839.4    .033       0
  4991.3    .033       0  5004.1    .033       0
Bank Sta=4991.3,5004.1
XS Rating Curve= 0 ,0
Exp/Cntr=0.3,0.1

Type RM Length L Ch R = 1 ,3403    ,599,599,599
BEGIN DESCRIPTION:
Guadalupe Tributary 51 2.1
END DESCRIPTION:
XS GIS Cut Line= 3
      2203924.43     13877096.89      2202642.04     13876008.49
      2200934.89     13875573.09
#Sta/Elev= 30
    3318  966.56  3467.9  964.66  3482.2  962.11  3496.5  961.54  3638.2  958.52
  3709.6  954.15  3716.1  954.94  3730.4  951.41    3737  952.44  3744.7  949.98
  3751.3  951.07    3759  948.42  3765.6  949.17  3773.3  946.74  3780.8  946.95
  3787.6   945.2  3808.4  945.09  3822.7  943.03  3900.7  940.67  4028.1   934.4
  4085.2  928.74  4163.2  925.65  4173.4  924.26  4399.3  915.45  4551.5  910.71
  4602.6  908.63  5021.5  908.39    5022  907.89  5034.3  908.39  6761.8  908.66
#Mann= 7 ,-1 , 0
    3318    .035       0  3780.8     .12       0  4173.4     .07       0
  4399.3    .035       0  4551.5    .033       0  5021.5    .033       0
  5034.3    .033       0
Bank Sta=5021.5,5034.3
XS Rating Curve= 0 ,0
Exp/Cntr=0.3,0.1

Type RM Length L Ch R = 1 ,2804    ,706,706,706
BEGIN DESCRIPTION:
Guadalupe Tributary 51 2.0
END DESCRIPTION:
XS GIS Cut Line= 3
      2203275.03       13875575.        2202875.       13875525.
       2201129.9     13875407.47
#Sta/Elev= 30
  4596.7  965.31  4609.1  964.45  4616.9  963.11  4639.6  961.06  4647.1  957.99
  4667.3  951.54  4687.4  940.36  4697.5  935.36  4715.1  928.15  4720.2  927.86
  4737.8  924.06    4758  923.16  4795.8  919.72  4800.8  919.99  4838.6  915.37
    4867  913.59  4899.1  912.11  4929.3  911.53  4949.5  910.08    4957  908.76
  4964.4  908.61  4983.2  908.39  4983.7  907.89  4995.9  907.89  4996.4  908.39
  6132.4  908.91  6152.4  909.37  6182.5   908.7  6302.8  909.07  6748.9  908.66
#Mann= 6 ,-1 , 0
  4596.7    .063       0  4609.1    .035       0    4867     .07       0
  4964.4    .033       0  4983.2    .033       0  4996.4    .033       0
Bank Sta=4983.2,4996.4
XS Rating Curve= 0 ,0
Exp/Cntr=0.3,0.1

Type RM Length L Ch R = 1 ,2098    ,1573,1573,1573
BEGIN DESCRIPTION:
Guadalupe Tributary 51 1.5
END DESCRIPTION:
XS GIS Cut Line= 3
      2203930.84     13875515.88      2203104.73     13874894.87
      2201348.07     13875075.27
#Sta/Elev= 30
  3966.5 1011.36  4042.7 1006.32    4099  995.86  4137.2  992.21  4186.4  986.97
    4199  978.47  4213.5  973.78    4249  967.36  4271.8   968.5  4286.4  966.85
  4292.7  963.77  4392.6  958.96  4421.8  959.71  4442.6  955.84  4486.3  955.54
  4492.6  953.12  4507.2     954  4513.4  950.49  4521.7  951.32    4528  948.64
  4552.3  947.53  4586.3  942.33  4592.6  938.85  4642.5  928.21  4763.3  918.93
  4962.3  908.87  5385.2  908.67  5385.7  908.17  5398.4  908.67  6765.9  908.81
#Mann= 6 ,-1 , 0
  3966.5    .035       0  4137.2    .063       0  4552.3    .035       0
  4962.3    .033       0  5385.2    .033       0  5398.4    .033       0
Bank Sta=5385.2,5398.4
XS Rating Curve= 0 ,0
Exp/Cntr=0.3,0.1

Type RM Length L Ch R = 1 ,525     ,0,0,0
BEGIN DESCRIPTION:
Guadalupe Tributary 51 1.0
END DESCRIPTION:
XS GIS Cut Line= 3
      2204374.95     13874624.99        2202725.       13874175.
      2201555.22     13874798.95
#Sta/Elev= 30
  3289.9  953.22  3320.9  950.28  3341.7  949.46    3352  946.42  3381.4  943.91
  3386.6  941.29  3393.5  940.45  3421.1  938.68  3426.3  936.29  3455.7  933.66
  3466.1  930.71  3486.8   929.4  3495.4  928.25  3500.6  926.41  3535.2  922.89
  3540.3  921.33  3574.9  919.34  3580.1   917.8  3609.4  917.62  3614.6  916.18
  3642.3  915.48    3663  913.48  3728.6  911.77  3763.2  912.33  3842.7  908.97
  3946.7     909  4257.5     908    4258   907.5  4270.8     908  6325.9  909.14
#Mann= 4 ,-1 , 0
  3289.9    .035       0  3946.7    .033       0  4257.5    .033       0
  4270.8    .033       0
Bank Sta=4257.5,4270.8
XS Rating Curve= 0 ,0
Exp/Cntr=0.3,0.1

Chan Stop Cuts=-1
Use User Specified Reach Order=0
Composite Channel Slope=5