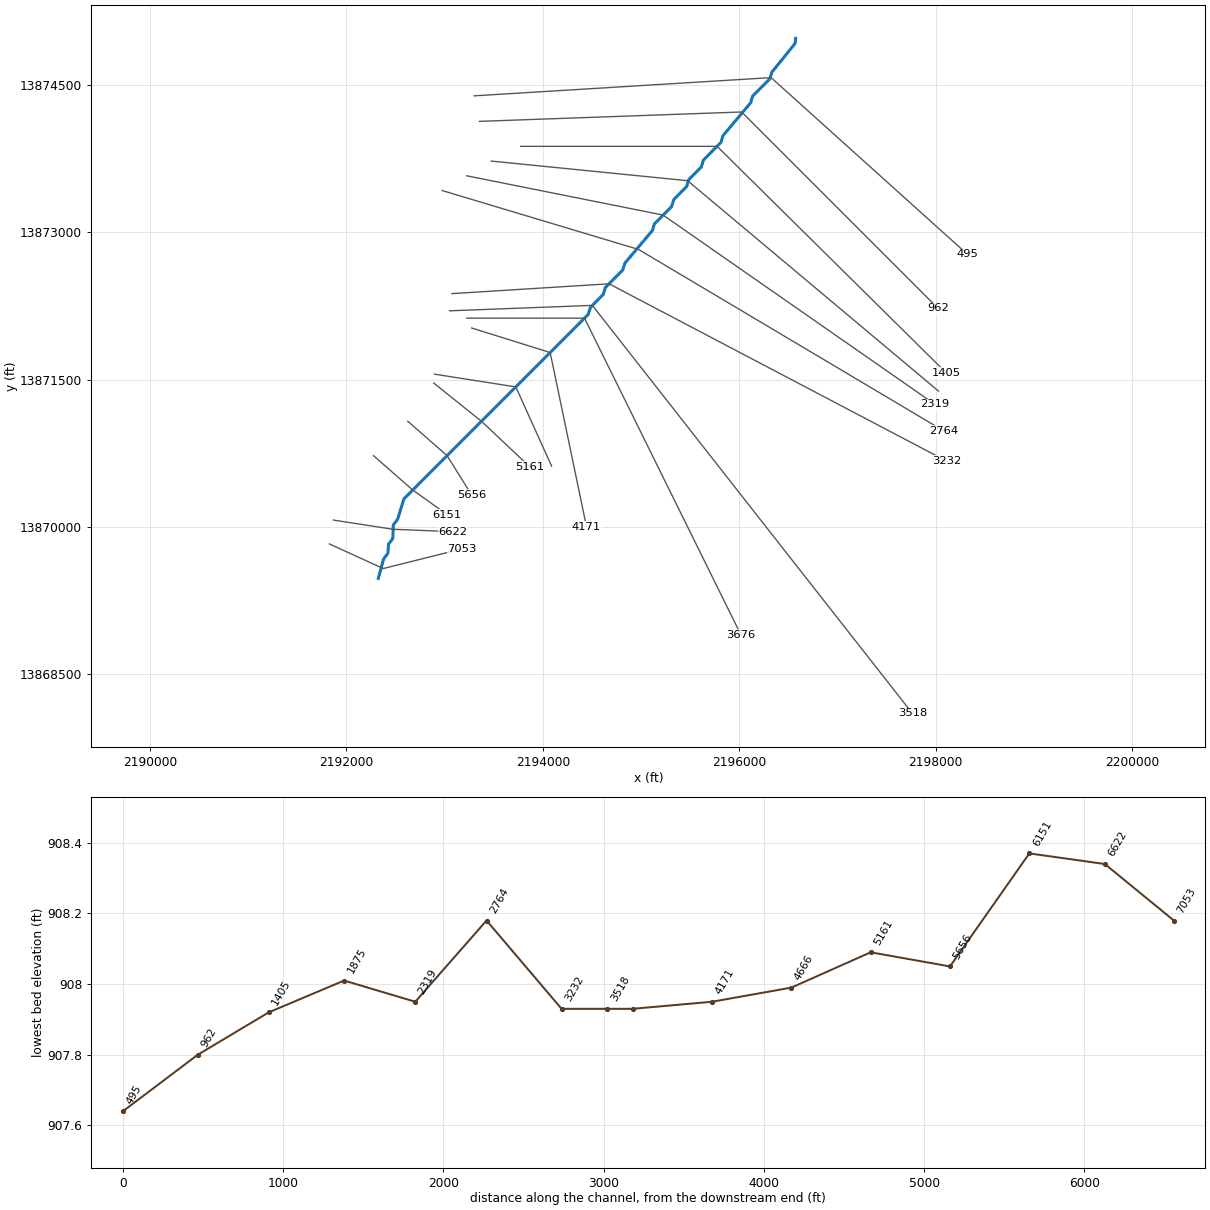
--- Guadalupe Tributary 53.prj (project) ---

Proj Title=Guadalupe Tributary 53 Base Level Engineering
Current Plan=p01
Default Exp/Contr=0.3,0.1
English Units
Geom File=g01
Flow File=f01
Plan File=p01
BEGIN DESCRIPTION:
Guadalupe Tributary 53
END DESCRIPTION:

--- Guadalupe Tributary 53.p01 (plan) ---

Plan Title=Multiple Run
Short Identifier=Multiple
Geom File=g01
Flow File=f01
Subcritical Flow
K Sum by GR= 0
Std Step Tol= 0.01
Critical Tol= 0.01
Num of Std Step Trials= 20
Max Error Tol= 0.3
Flow Tol Ratio= 0.001
Split Flow NTrial= 30
Split Flow Tol= 0.02
Split Flow Ratio= 0.02
Log Output Level= 0
Friction Slope Method= 1
Unsteady Friction Slope Method= 2
Unsteady Bridges Friction Slope Method= 1
Parabolic Critical Depth
Global Vel Dist=  1 , 1 , 1
Global Log Level= 0
CheckData=True
Encroach Param= -1, 0, 0, 0
BEGIN DESCRIPTION:
Multiple Run
END DESCRIPTION:

--- Guadalupe Tributary 53.f01 (steady flow) ---

Flow Title=Multiple
Number of Profiles=7
Profile Names=10-year,25-year,50-year,1pct_min,100-year,1pct_plu,500-year
River Rch & RM= Guadalupe Tribut,Reach-1,7053
    1851    3219    4551    3110    6206   12382   11427
River Rch & RM= Guadalupe Tribut,Reach-1,2319
    1882    3264    4605    3140    6265   12500   11481
Boundary for River Rch & Prof#=Guadalupe Tribut,Reach-1,1
Up Type=0
Dn Type=3
Dn Slope=0.005
Boundary for River Rch & Prof#=Guadalupe Tribut,Reach-1,2
Up Type=0
Dn Type=3
Dn Slope=0.005
Boundary for River Rch & Prof#=Guadalupe Tribut,Reach-1,3
Up Type=0
Dn Type=3
Dn Slope=0.005
Boundary for River Rch & Prof#=Guadalupe Tribut,Reach-1,4
Up Type=0
Dn Type=3
Dn Slope=0.005
Boundary for River Rch & Prof#=Guadalupe Tribut,Reach-1,5
Up Type=0
Dn Type=3
Dn Slope=0.005
Boundary for River Rch & Prof#=Guadalupe Tribut,Reach-1,6
Up Type=0
Dn Type=3
Dn Slope=0.005
Boundary for River Rch & Prof#=Guadalupe Tribut,Reach-1,7
Up Type=0
Dn Type=3
Dn Slope=0.005

--- Guadalupe Tributary 53.g01 (geometry) ---

Geom Title=Existing Conditions

River Reach=Guadalupe Tribut,Reach-1
Reach XY= 30
      2192325.00     13869475.00      2192378.85     13869673.40
      2192422.65     13869730.97      2192428.86     13869823.40
      2192472.73     13869880.94      2192477.27     13870019.06
      2192521.14     13870076.60      2192585.76     13870284.68
      2194461.37     13872161.79      2194485.78     13872234.68
      2194616.84     13872368.95      2194635.78     13872434.68
      2194814.22     13872615.32      2194835.78     13872684.68
      2195116.84     13873018.95      2195135.78     13873084.68
      2195311.37     13873261.79      2195335.78     13873334.68
      2195466.84     13873468.95      2195485.78     13873534.68
      2195614.22     13873665.32      2195635.78     13873734.68
      2195814.22     13873915.32      2195835.78     13873984.68
      2196116.84     13874318.95      2196135.78     13874384.68
      2196314.22     13874565.32      2196333.16     13874631.05
      2196569.67     13874922.49      2196575.00     13874975.00

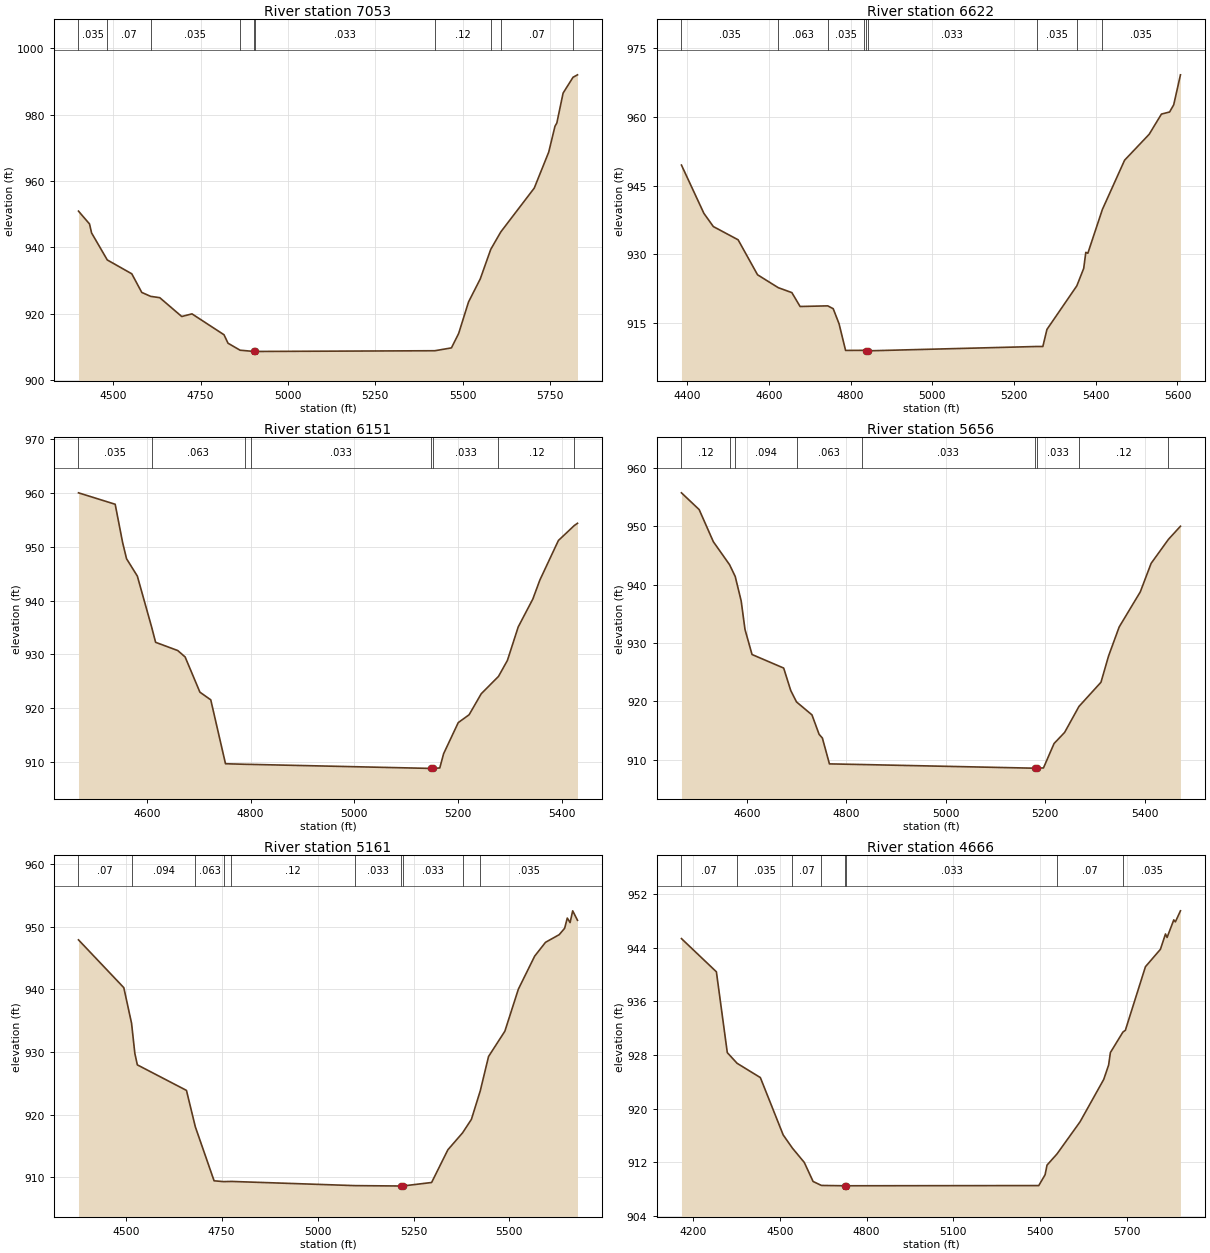
Type RM Length L Ch R = 1,7053,431,431,431
BEGIN DESCRIPTION:
Guadalupe Tributary 53 15.0
END DESCRIPTION:
XS GIS Cut Line= 3
      2191826.25     13869825.69      2192375.00     13869575.00
      2193174.98     13869774.99
#Sta/Elev= 30
  4400.7  950.93  4432.3  947.06  4438.1  944.38  4483.1  936.23  4553.2  932.06
  4581.8  926.45  4607.2  925.27  4633.3  924.87  4696.2  919.20  4725.4  920.00
  4817.1  913.71  4828.6  911.16  4863.1  909.06  4903.0  908.68  4903.2  908.18
  4907.2  908.68  5420.5  908.90  5467.9  909.76  5488.5  914.09  5516.8  923.58
  5550.3  930.51  5580.4  939.42  5609.0  944.65  5704.9  957.87  5746.2  968.68
  5764.2  976.49  5769.4  977.43  5787.4  986.46  5815.8  991.22  5828.6  991.96
#Mann=10,-1,0
  4400.7   0.035       0  4483.1    0.07       0  4607.2   0.035       0
  4863.1   0.033       0  4903.0   0.033       0  4907.2   0.033       0
  5420.5    0.12       0  5580.4   0.035       0  5609.0    0.07       0
  5815.8   0.035       0
Bank Sta=4903,4907.2
Exp/Cntr=0.3,0.1

Type RM Length L Ch R = 1,6622,471,471,471
BEGIN DESCRIPTION:
Guadalupe Tributary 53 14.0
END DESCRIPTION:
XS GIS Cut Line= 3
      2191867.96     13870068.73      2192475.00     13869975.00
      2193081.58     13869950.75
#Sta/Elev= 30
  4386.1  949.48  4441.0  938.92  4464.1  936.03  4524.8  933.13  4572.3  925.48
  4623.0  922.66  4656.3  921.58  4676.5  918.54  4744.1  918.68  4757.5  918.06
  4771.8  914.77  4787.8  908.93  4832.3  908.95  4837.9  908.84  4838.2  908.34
  4842.2  908.84  5255.1  909.79  5270.6  909.79  5280.6  913.52  5353.8  923.07
  5370.6  926.88  5375.7  930.38  5380.7  930.19  5416.3  939.77  5470.7  950.55
  5530.8  956.21  5560.8  960.63  5580.8  961.09  5590.8  962.65  5607.4  969.22
#Mann=9,-1,0
  4386.1   0.035       0  4623.0   0.063       0  4744.1   0.035       0
  4832.3   0.033       0  4837.9   0.033       0  4842.2   0.033       0
  5255.1   0.035       0  5353.8    0.12       0  5416.3   0.035       0
Bank Sta=4837.9,4842.2
Exp/Cntr=0.3,0.1

Type RM Length L Ch R = 1,6151,495,495,495
BEGIN DESCRIPTION:
Guadalupe Tributary 53 13.0
END DESCRIPTION:
XS GIS Cut Line= 3
      2192274.99     13870725.01      2192675.00     13870375.00
      2193024.97     13870125.02
#Sta/Elev= 30
  4468.5  959.98  4539.2  957.86  4553.5  950.78  4561.1  947.76  4581.9  944.54
  4609.5  935.07  4617.1  932.26  4659.8  930.73  4674.0  929.54  4702.5  923.01
  4723.4  921.59  4751.8  909.74  4788.5  909.64  4800.4  909.62  5147.8  908.87
  5148.1  908.37  5152.2  908.87  5164.7  908.96  5172.1  911.60  5200.3  917.37
  5221.2  918.82  5244.6  922.72  5277.8  925.93  5295.0  928.89  5315.9  935.12
  5344.1  940.30  5357.6  943.81  5393.3  951.14  5424.2  953.94  5430.1  954.33
#Mann=8,-1,0
  4468.5   0.035       0  4609.5   0.063       0  4788.5   0.035       0
  4800.4   0.033       0  5147.8   0.033       0  5152.2   0.033       0
  5277.8    0.12       0  5424.2    0.07       0
Bank Sta=5147.8,5152.2
Exp/Cntr=0.3,0.1

Type RM Length L Ch R = 1,5656,495,495,495
BEGIN DESCRIPTION:
Guadalupe Tributary 53 12.0
END DESCRIPTION:
XS GIS Cut Line= 3
      2192625.00     13871075.00      2193025.00     13870725.00
      2193275.00     13870325.00
#Sta/Elev= 30
  4468.5  955.71  4504.1  952.84  4532.6  947.34  4565.3  943.39  4576.6  941.38
  4588.6  937.18  4596.2  932.33  4610.4  928.02  4674.0  925.70  4688.2  921.86
  4699.8  919.90  4730.9  917.68  4745.2  914.36  4751.8  913.72  4766.0  909.29
  4831.6  909.18  5178.8  908.55  5179.1  908.05  5183.2  908.55  5196.3  908.60
  5217.6  912.78  5238.8  914.68  5267.6  919.12  5311.9  923.27  5327.2  927.78
  5348.5  932.74  5390.9  938.74  5412.7  943.63  5447.5  947.74  5471.7  949.99
#Mann=9,-1,0
  4468.5    0.12       0  4565.3   0.063       0  4576.6   0.094       0
  4699.8   0.063       0  4831.6   0.033       0  5178.8   0.033       0
  5183.2   0.033       0  5267.6    0.12       0  5447.5    0.07       0
Bank Sta=5178.8,5183.2
Exp/Cntr=0.3,0.1

Type RM Length L Ch R = 1,5161,495,495,495
BEGIN DESCRIPTION:
Guadalupe Tributary 53 11.0
END DESCRIPTION:
XS GIS Cut Line= 3
      2192888.72     13871464.60      2193375.00     13871075.00
      2193867.95     13870610.38
#Sta/Elev= 30
  4376.9  947.93  4495.0  940.29  4515.2  934.61  4523.8  929.77  4530.3  927.95
  4658.3  923.87  4681.4  918.05  4730.3  909.42  4755.3  909.29  4775.4  909.32
  5097.3  908.65  5217.3  908.59  5217.6  908.09  5221.7  908.59  5297.2  909.15
  5339.6  914.38  5377.8  917.08  5400.9  919.24  5424.0  923.80  5445.6  929.29
  5488.1  933.33  5523.3  940.05  5565.8  945.33  5594.1  947.54  5629.7  948.76
  5643.9  949.78  5650.8  951.41  5658.1  950.69  5664.9  952.57  5677.4  951.06
#Mann=10,-1,0
  4376.9    0.07       0  4515.2   0.094       0  4681.4   0.063       0
  4755.3   0.035       0  4775.4    0.12       0  5097.3   0.033       0
  5217.3    0.05       0  5221.7   0.033       0  5377.8    0.12       0
  5424.0   0.035       0
Bank Sta=5217.3,5221.7
Exp/Cntr=0.3,0.1

Type RM Length L Ch R = 1,4666,495,495,495
BEGIN DESCRIPTION:
Guadalupe Tributary 53 10.0
END DESCRIPTION:
XS GIS Cut Line= 3
      2192895.70     13871554.85      2193725.00     13871425.00
      2194089.46     13870618.86
#Sta/Elev= 30
  4160.6  945.34  4281.3  940.39  4319.0  928.34  4352.8  926.75  4433.2  924.62
  4512.1  916.07  4544.0  914.10  4585.0  911.97  4615.4  909.13  4644.2  908.54
  4724.5  908.49  4724.8  907.99  4729.0  908.49  5395.1  908.52  5417.0  910.14
  5423.7  911.57  5458.2  913.24  5537.8  918.03  5619.5  924.34  5636.5  926.49
  5642.6  928.35  5685.8  931.40  5694.3  931.67  5763.7  941.15  5815.4  943.74
  5833.0  946.03  5838.5  945.51  5861.6  948.13  5867.1  947.83  5884.7  949.48
#Mann=8,-1,0
  4160.6    0.07       0  4352.8   0.035       0  4544.0    0.07       0
  4644.2   0.033       0  4724.5   0.033       0  4729.0   0.033       0
  5458.2    0.07       0  5685.8   0.035       0
Bank Sta=4724.5,4729
Exp/Cntr=0.3,0.1

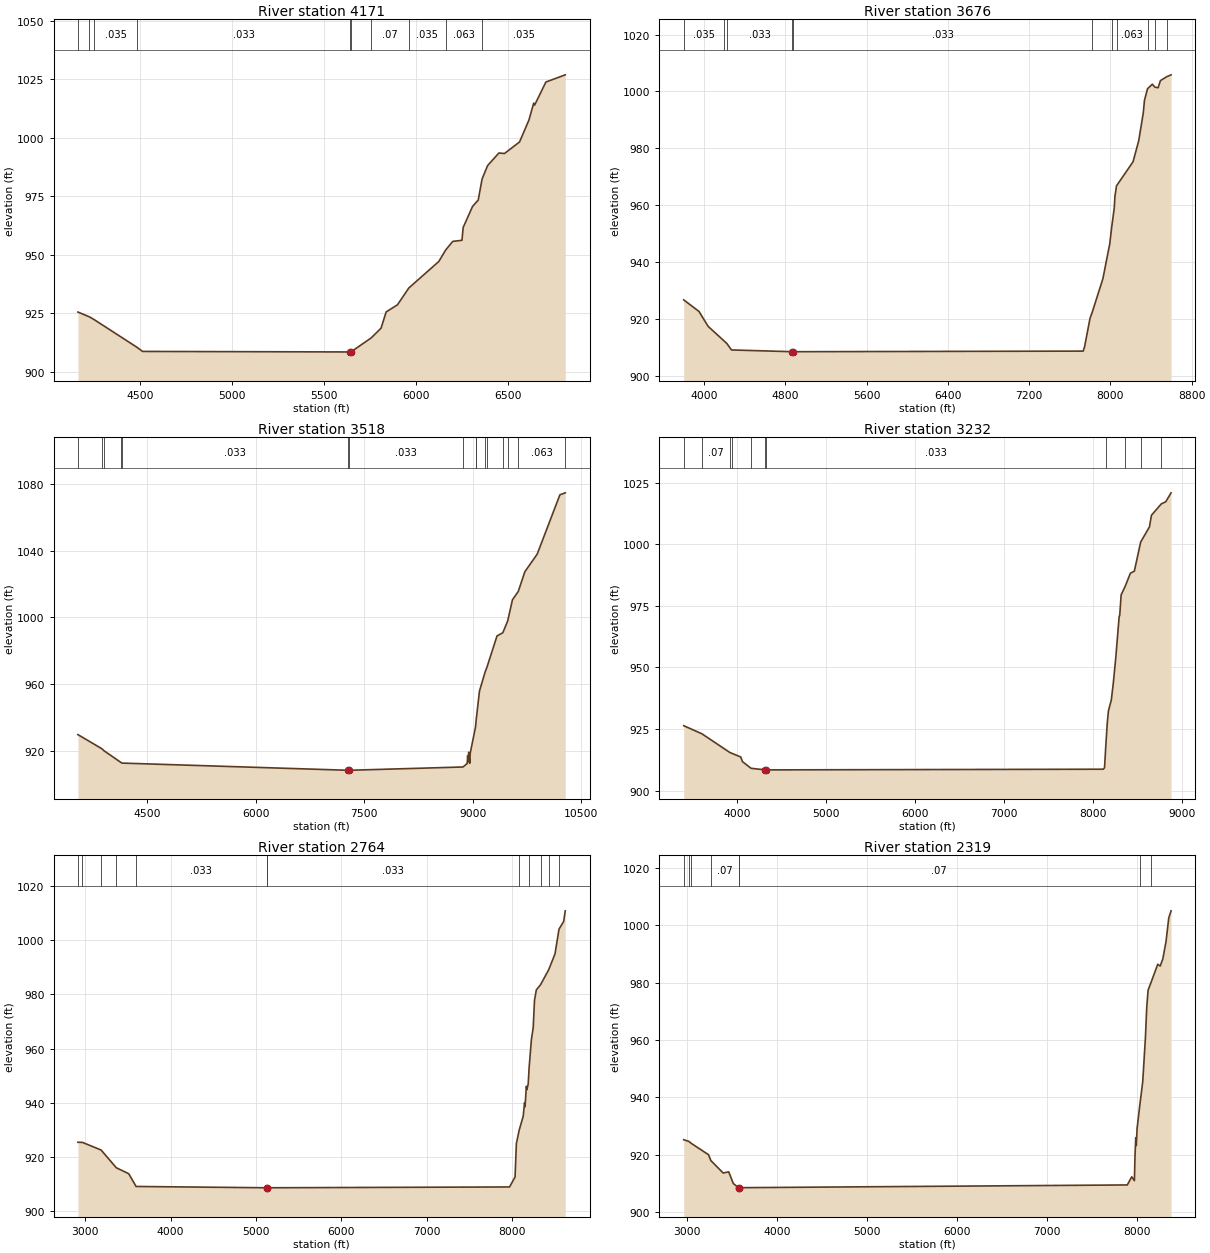
Type RM Length L Ch R = 1,4171,495,495,495
BEGIN DESCRIPTION:
Guadalupe Tributary 53 9.0
END DESCRIPTION:
XS GIS Cut Line= 3
      2193274.96     13872025.01      2194075.00     13871775.00
      2194445.00     13870001.89
#Sta/Elev= 30
  4161.8  925.52  4223.7  923.49  4248.6  922.37  4483.1  910.44  4513.3  908.68
  5641.3  908.45  5641.6  907.95  5645.8  908.45  5755.8  914.43  5809.9  918.62
  5837.7  925.58  5899.0  928.61  5961.2  935.84  6123.7  947.13  6161.4  952.08
  6199.8  955.75  6249.8  956.21  6256.5  961.73  6307.6  970.73  6338.2  973.42
  6359.2  982.44  6389.3  988.18  6450.6  993.55  6481.2  993.34  6563.0  998.28
  6614.0 1007.67  6639.8 1014.88  6644.9 1014.05  6706.0 1023.90  6811.3 1026.99
#Mann=10,-1,0
  4161.8   0.035       0  4223.7    0.07       0  4248.6   0.035       0
  4483.1   0.033       0  5641.3   0.033       0  5645.8   0.033       0
  5755.8    0.07       0  5961.2   0.035       0  6161.4   0.063       0
  6359.2   0.035       0
Bank Sta=5641.3,5645.8
Exp/Cntr=0.3,0.1

Type RM Length L Ch R = 1,3676,158,158,158
BEGIN DESCRIPTION:
Guadalupe Tributary 53 8.0
END DESCRIPTION:
XS GIS Cut Line= 3
      2193225.04     13872125.00      2194425.00     13872125.00
      2196018.07     13868899.41
#Sta/Elev= 30
  3799.8  926.67  3949.8  922.60  4039.8  917.36  4195.0  912.28  4224.4  911.32
  4269.8  909.05  4866.6  908.43  4867.1  907.93  4872.9  908.43  7732.3  908.64
  7746.3  910.22  7799.2  920.12  7823.3  922.55  7925.8  934.06  7993.2  946.25
  8012.9  952.25  8038.0  958.95  8044.6  963.02  8060.4  966.78  8223.2  975.25
  8278.8  982.62  8323.4  992.31  8335.4  996.81  8365.5 1000.92  8412.6 1002.52
  8438.6 1001.48  8470.1 1001.29  8492.5 1003.79  8553.5 1005.14  8597.3 1005.82
#Mann=11,-1,0
  3799.8   0.035       0  4195.0    0.07       0  4224.4   0.033       0
  4866.6   0.033       0  4872.9   0.033       0  7823.3    0.07       0
  8012.9    0.12       0  8060.4   0.063       0  8365.5   0.035       0
  8438.6   0.063       0  8553.5   0.035       0
Bank Sta=4866.6,4872.9
Exp/Cntr=0.3,0.1

Type RM Length L Ch R = 1,3518,286,286,286
BEGIN DESCRIPTION:
Guadalupe Tributary 53 7.5
END DESCRIPTION:
XS GIS Cut Line= 3
      2193049.96     13872200.00      2194504.62     13872255.16
      2197763.67     13868099.99
#Sta/Elev= 30
  3544.3  929.82  3876.9  921.32  3902.2  920.23  4140.0  913.11  4154.5  912.75
  7284.3  908.43  7284.8  907.93  7290.6  908.43  8866.8  910.41  8925.4  912.49
  8931.8  917.21  8939.9  913.59  8946.3  919.27  8960.7  912.64  8967.1  918.65
  9040.4  934.30  9051.3  939.26  9095.4  955.92  9173.5  967.38  9198.9  970.23
  9337.7  988.95  9417.8  990.85  9485.1  997.91  9551.0 1010.60  9631.2 1015.57
  9722.8 1027.43  9893.2 1037.97 10207.3 1073.54 10280.2 1074.66 10280.8 1074.70
#Mann=16,-1,0
  3544.3   0.035       0  3876.9    0.07       0  3902.2   0.035       0
  4140.0    0.07       0  4154.5   0.033       0  7284.3   0.033       0
  7290.6   0.033       0  8866.8    0.12       0  9040.4   0.063       0
  9051.3    0.12       0  9173.5    0.07       0  9198.9   0.035       0
  9417.8   0.063       0  9485.1   0.035       0  9631.2   0.063       0
 10280.2   0.094       0
Bank Sta=7284.3,7290.6
Exp/Cntr=0.3,0.1

Type RM Length L Ch R = 1,3232,468,468,468
BEGIN DESCRIPTION:
Guadalupe Tributary 53 7.0
END DESCRIPTION:
XS GIS Cut Line= 3
      2193075.00     13872375.00      2194675.00     13872475.00
      2198110.26     13870670.46
#Sta/Elev= 30
  3397.2  926.36  3601.4  923.09  3915.7  915.51  3935.6  915.21  4038.4  913.67
  4058.5  911.78  4154.4  909.08  4315.8  908.43  4316.3  907.93  4322.1  908.43
  8117.9  908.71  8132.0  909.29  8145.5  917.68  8163.1  927.58  8176.1  932.42
  8208.3  936.76  8230.9  943.68  8258.6  953.94  8297.1  970.83  8302.7  971.00
  8319.1  979.48  8364.1  982.89  8422.9  988.24  8467.8  989.09  8538.4 1000.86
  8637.6 1007.06  8660.1 1011.78  8771.4 1016.40  8820.6 1017.23  8880.7 1020.87
#Mann=11,-1,0
  3397.2   0.035       0  3601.4    0.07       0  3915.7   0.035       0
  3935.6    0.07       0  4154.4   0.033       0  4315.8   0.033       0
  4322.1   0.033       0  8145.5    0.12       0  8364.1   0.063       0
  8538.4   0.035       0  8771.4   0.063       0
Bank Sta=4315.8,4322.1
Exp/Cntr=0.3,0.1

Type RM Length L Ch R = 1,2764,445,445,445
BEGIN DESCRIPTION:
Guadalupe Tributary 53 6.0
END DESCRIPTION:
XS GIS Cut Line= 3
      2192975.01     13873425.00      2194975.00     13872825.00
      2198081.68     13870978.01
#Sta/Elev= 30
  2916.3  925.46  2968.9  925.41  3187.5  922.60  3366.0  916.05  3511.4  913.86
  3597.1  909.16  5125.8  908.68  5126.3  908.18  5132.2  908.68  7967.1  908.98
  8031.3  912.64  8046.9  924.97  8079.6  929.90  8126.8  935.05  8142.4  940.03
  8148.2  938.56  8163.8  946.07  8169.6  944.85  8185.2  946.94  8195.6  952.76
  8222.2  963.17  8243.6  967.66  8259.2  977.87  8280.7  981.63  8330.2  983.54
  8425.8  989.10  8498.8  994.89  8545.8 1004.01  8600.1 1006.83  8618.6 1010.76
#Mann=12,-1,0
  2916.3   0.035       0  2968.9    0.07       0  3187.5   0.035       0
  3366.0    0.07       0  3597.1   0.033       0  5125.8   0.033       0
  5132.2   0.033       0  8079.6    0.12       0  8195.6   0.094       0
  8330.2   0.063       0  8425.8   0.094       0  8545.8   0.063       0
Bank Sta=5125.8,5132.2
Exp/Cntr=0.3,0.1

Type RM Length L Ch R = 1,2319,444,444,444
BEGIN DESCRIPTION:
Guadalupe Tributary 53 5.0
END DESCRIPTION:
XS GIS Cut Line= 3
      2193225.01     13873575.00      2195225.00     13873175.00
      2197993.83     13871247.09
#Sta/Elev= 30
  2960.4  925.18  3016.8  924.61  3044.6  923.91  3235.7  919.96  3261.4  917.93
  3398.9  913.56  3460.1  913.99  3511.1  909.91  3568.9  908.45  3569.4  907.95
  3575.6  908.45  7887.9  909.41  7937.0  912.25  7966.7  910.90  7973.2  919.41
  7981.6  925.89  7987.6  923.17  7996.4  929.08  8023.3  936.35  8059.2  945.43
  8088.9  960.72  8103.7  971.34  8118.6  977.34  8151.3  980.04  8225.9  986.39
  8253.5  985.76  8282.6  988.29  8318.4  994.42  8348.1 1002.52  8373.9 1005.03
#Mann=8,-1,0
  2960.4   0.035       0  3016.8    0.07       0  3044.6   0.035       0
  3261.4    0.07       0  3568.9   0.033       0  3575.6    0.07       0
  8023.3    0.12       0  8151.3   0.063       0
Bank Sta=3568.9,3575.6
Exp/Cntr=0.3,0.1

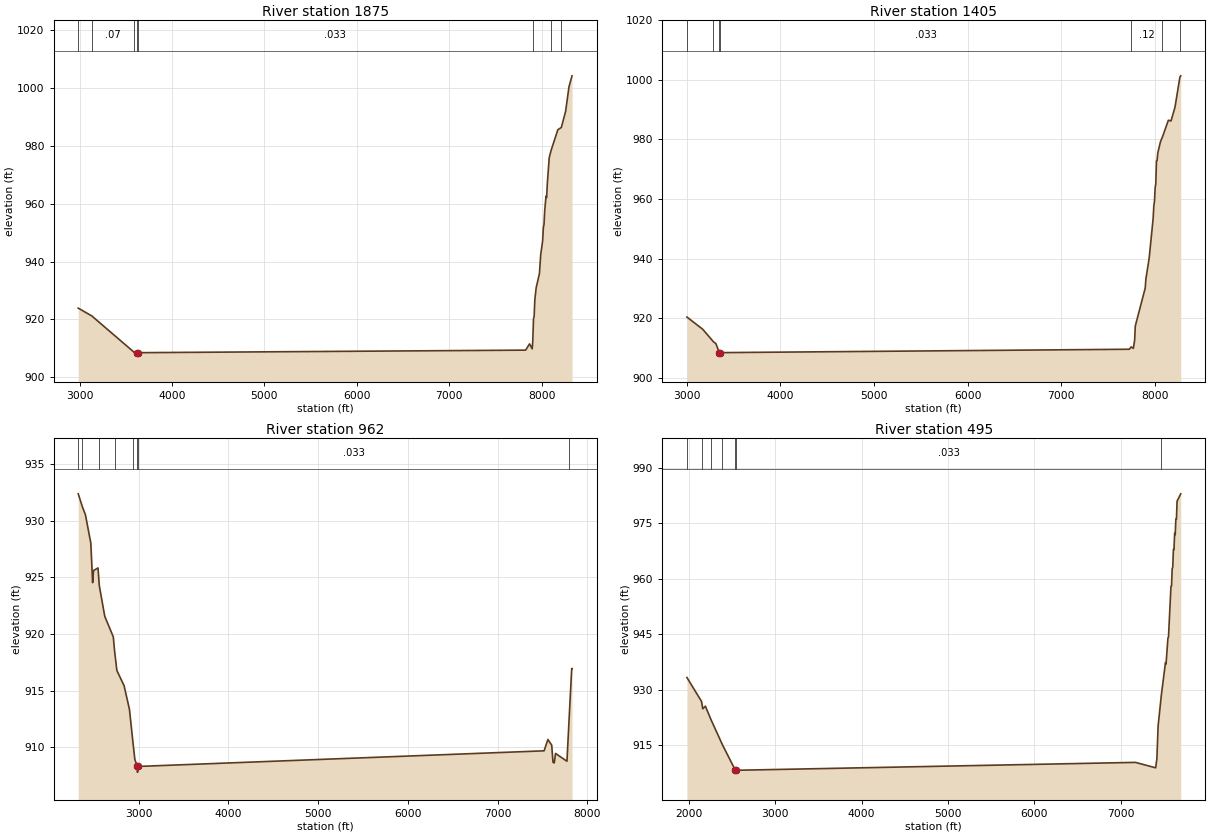
Type RM Length L Ch R = 1,1875,470,470,470
BEGIN DESCRIPTION:
Guadalupe Tributary 53 4.0
END DESCRIPTION:
XS GIS Cut Line= 3
      2193474.99     13873725.00      2195475.00     13873525.00
      2198029.69     13871382.45
#Sta/Elev= 30
  2985.4  923.91  3132.4  921.21  3590.9  908.64  3625.3  908.51  3625.8  908.01
  3632.0  908.51  7827.5  909.39  7869.9  911.55  7898.5  909.85  7904.7  912.53
  7912.8  920.28  7919.3  920.94  7927.1  926.81  7941.4  930.95  7976.5  935.79
  7990.9  942.48  8011.7  947.21  8019.5  951.92  8026.0  952.70  8033.8  957.53
  8048.1  962.65  8054.6  962.15  8062.4  967.12  8083.2  976.03  8102.9  978.43
  8175.6  985.56  8214.1  986.40  8260.2  991.97  8296.6 1000.43  8329.6 1004.23
#Mann=8,-1,0
  2985.4   0.035       0  3132.4    0.07       0  3590.9   0.033       0
  3625.3   0.033       0  3632.0   0.033       0  7904.7    0.12       0
  8102.9   0.094       0  8214.1   0.063       0
Bank Sta=3625.3,3632
Exp/Cntr=0.3,0.1

Type RM Length L Ch R = 1,1405,443,443,443
BEGIN DESCRIPTION:
Guadalupe Tributary 53 3.0
END DESCRIPTION:
XS GIS Cut Line= 3
      2193775.02     13873875.00      2195775.00     13873875.00
      2198106.90     13871570.03
#Sta/Elev= 30
  2999.8  920.37  3169.8  916.24  3282.9  912.08  3309.8  911.44  3346.4  908.42
  3346.9  907.92  3353.2  908.42  7729.2  909.56  7749.2  910.34  7771.7  909.85
  7785.8  912.49  7792.9  917.35  7898.9  930.08  7906.1  933.12  7941.4  940.16
  7983.8  953.47  7990.9  957.66  7997.9  959.14  8005.1  963.65  8012.1  965.16
  8019.2  972.71  8026.2  972.91  8033.3  975.39  8061.6  979.15  8083.3  980.82
  8146.5  986.41  8174.8  986.18  8217.2  990.77  8269.9 1000.91  8278.6 1001.32
#Mann=7,-1,0
  2999.8    0.07       0  3282.9   0.033       0  3346.4   0.033       0
  3353.2   0.033       0  7749.2    0.12       0  8083.3   0.094       0
  8269.9    0.12       0
Bank Sta=3346.4,3353.2
Exp/Cntr=0.3,0.1

Type RM Length L Ch R = 1,962,467,467,467
BEGIN DESCRIPTION:
Guadalupe Tributary 53 2.0
END DESCRIPTION:
XS GIS Cut Line= 3
      2193354.70     13874129.43      2196025.00     13874225.00
      2198024.98     13872225.02
#Sta/Elev= 30
  2328.3  932.36  2374.8  931.21  2408.6  930.51  2468.7  928.01  2488.7  924.52
  2498.7  925.59  2548.7  925.82  2562.6  924.28  2623.9  921.55  2718.8  919.74
  2734.4  918.40  2758.9  916.77  2838.9  915.43  2898.7  913.35  2937.3  910.46
  2959.0  908.92  2985.6  908.30  2986.1  907.80  2992.0  907.80  2992.5  908.30
  7517.6  909.68  7560.0  910.68  7602.5  910.18  7616.6  908.67  7630.7  908.61
  7644.9  909.45  7772.2  908.76  7799.6  913.02  7825.2  916.94  7828.7  916.94
#Mann=8,-1,0
  2328.3   0.035       0  2374.8    0.07       0  2562.6   0.035       0
  2734.4    0.07       0  2937.3   0.033       0  2985.6   0.033       0
  2992.5   0.033       0  7799.6    0.07       0
Bank Sta=2985.6,2992.5
Exp/Cntr=0.3,0.1

Type RM Length L Ch R = 1,495,0,0,0
BEGIN DESCRIPTION:
Guadalupe Tributary 53 1.0
END DESCRIPTION:
XS GIS Cut Line= 3
      2193301.59     13874389.25      2196325.00     13874575.00
      2198324.97     13872775.03
#Sta/Elev= 30
  1975.8  933.27  2145.2  926.79  2159.6  924.80  2189.6  925.51  2255.5  921.81
  2387.0  915.07  2536.8  908.14  2537.3  907.64  2543.7  908.14  7171.3  910.28
  7405.3  908.81  7419.5  911.26  7433.7  920.14  7471.7  928.63  7518.9  937.30
  7525.6  936.91  7547.3  943.90  7554.0  944.28  7582.4  957.91  7589.1  958.07
  7596.6  962.77  7603.3  963.15  7610.8  967.98  7617.5  967.92  7625.0  972.33
  7631.7  971.96  7639.2  976.16  7645.9  976.15  7653.4  981.06  7695.6  983.03
#Mann=7,-1,0
  1975.8   0.035       0  2145.2    0.07       0  2255.5   0.035       0
  2387.0   0.033       0  2536.8   0.033       0  2543.7   0.033       0
  7471.7    0.12       0
Bank Sta=2536.8,2543.7
Exp/Cntr=0.3,0.1

Chan Stop Cuts=-1