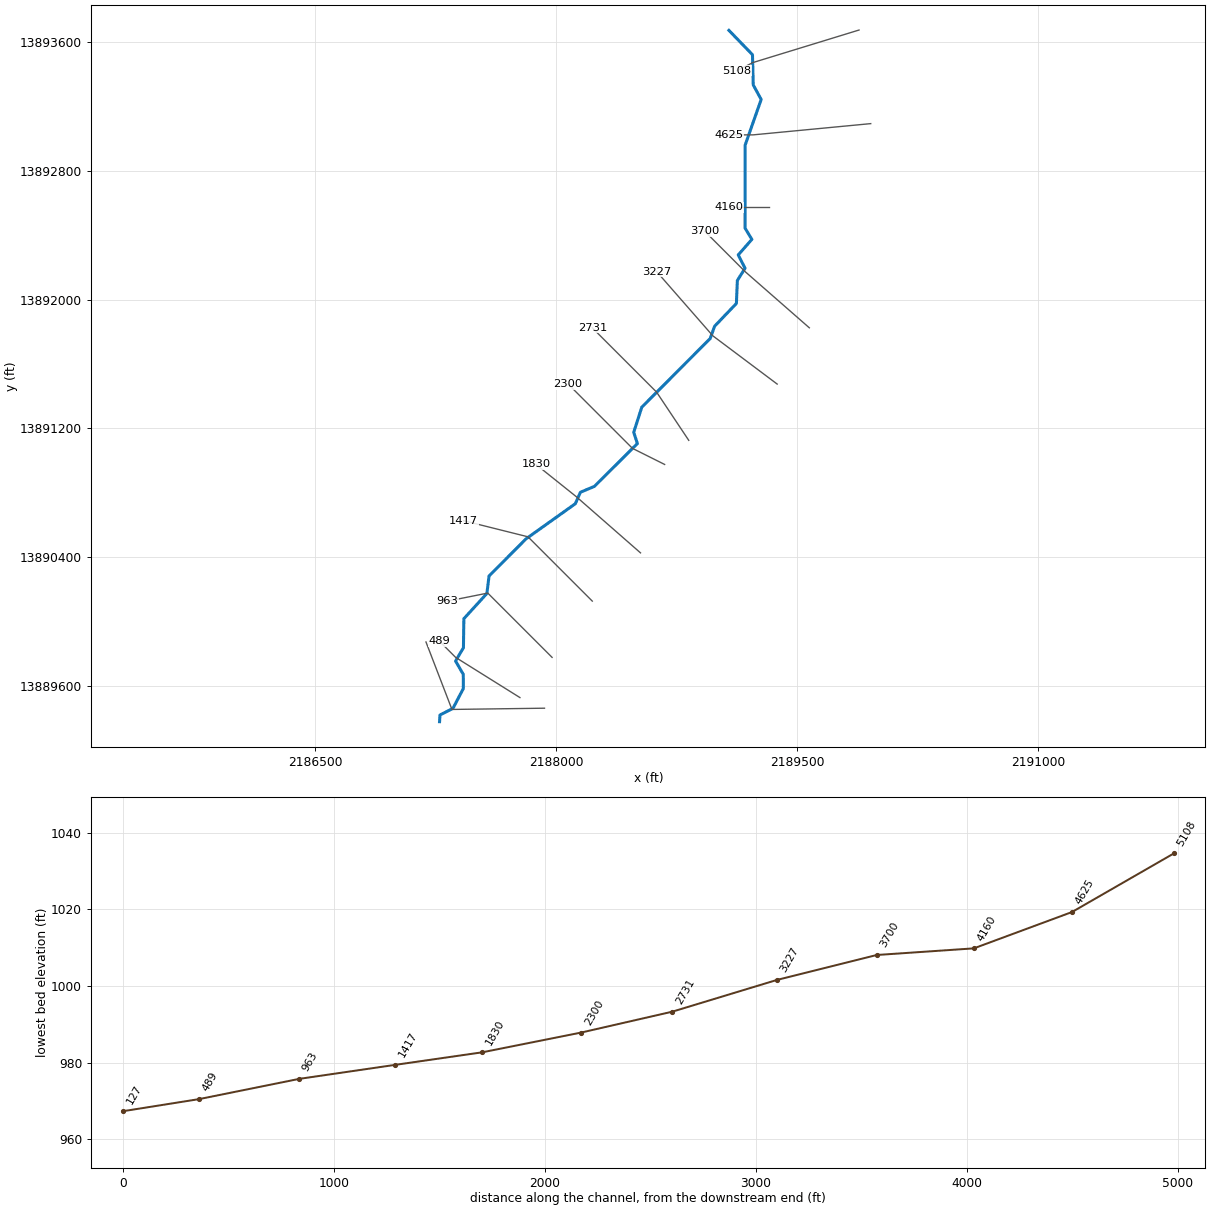
--- Guadalupe Tributary 55.prj (project) ---

Proj Title=Guadalupe Tributary 55 Base Level Engineering
Current Plan=p01
Default Exp/Contr=0.3,0.1
English Units
Geom File=g01
Flow File=f01
Plan File=p01
BEGIN DESCRIPTION:
Guadalupe Tributary 55
END DESCRIPTION:

--- Guadalupe Tributary 55.p01 (plan) ---

Plan Title=Multiple Run
Short Identifier=Multiple
Geom File=g01
Flow File=f01
Subcritical Flow
K Sum by GR= 0
Std Step Tol= 0.01
Critical Tol= 0.01
Num of Std Step Trials= 20
Max Error Tol= 0.3
Flow Tol Ratio= 0.001
Split Flow NTrial= 30
Split Flow Tol= 0.02
Split Flow Ratio= 0.02
Log Output Level= 0
Friction Slope Method= 1
Unsteady Friction Slope Method= 2
Unsteady Bridges Friction Slope Method= 1
Parabolic Critical Depth
Global Vel Dist=  1 , 1 , 1
Global Log Level= 0
CheckData=True
Encroach Param= -1, 0, 0, 0
BEGIN DESCRIPTION:
Multiple Run
END DESCRIPTION:

--- Guadalupe Tributary 55.f01 (steady flow) ---

Flow Title=Multiple
Number of Profiles=7
Profile Names=10-year,25-year,50-year,1pct_min,100-year,1pct_plu,500-year
River Rch & RM= Guadalupe Tribut,Reach-1,5108
    1741    3037    4305    2953    5891   11755   10924
Boundary for River Rch & Prof#=Guadalupe Tribut,Reach-1,1
Up Type=0
Dn Type=3
Dn Slope=0.005
Boundary for River Rch & Prof#=Guadalupe Tribut,Reach-1,2
Up Type=0
Dn Type=3
Dn Slope=0.005
Boundary for River Rch & Prof#=Guadalupe Tribut,Reach-1,3
Up Type=0
Dn Type=3
Dn Slope=0.005
Boundary for River Rch & Prof#=Guadalupe Tribut,Reach-1,4
Up Type=0
Dn Type=3
Dn Slope=0.005
Boundary for River Rch & Prof#=Guadalupe Tribut,Reach-1,5
Up Type=0
Dn Type=3
Dn Slope=0.005
Boundary for River Rch & Prof#=Guadalupe Tribut,Reach-1,6
Up Type=0
Dn Type=3
Dn Slope=0.005
Boundary for River Rch & Prof#=Guadalupe Tribut,Reach-1,7
Up Type=0
Dn Type=3
Dn Slope=0.005

--- Guadalupe Tributary 55.g01 (geometry) ---

Geom Title=Existing Conditions

River Reach=Guadalupe Tribut,Reach-1
Reach XY= 30
      2189075.00     13893675.00      2189221.47     13893523.54
      2189226.22     13893335.50      2189275.59     13893245.05
      2189175.68     13892961.08      2189175.19     13892444.98
      2189217.66     13892374.90      2189132.85     13892278.41
      2189175.21     13892195.21      2189127.41     13892119.48
      2189121.46     13891976.47      2188985.78     13891834.68
      2188958.35     13891758.33      2188532.86     13891331.17
      2188482.80     13891174.90      2188505.63     13891105.00
      2188238.20     13890838.64      2188151.21     13890802.02
      2188119.37     13890730.65      2187811.79     13890511.37
      2187582.86     13890281.17      2187569.48     13890172.57
      2187426.20     13890015.41      2187423.60     13889834.65
      2187374.62     13889752.19      2187422.69     13889669.44
      2187422.86     13889580.96      2187358.49     13889457.95
      2187277.66     13889416.55      2187275.00     13889375.00

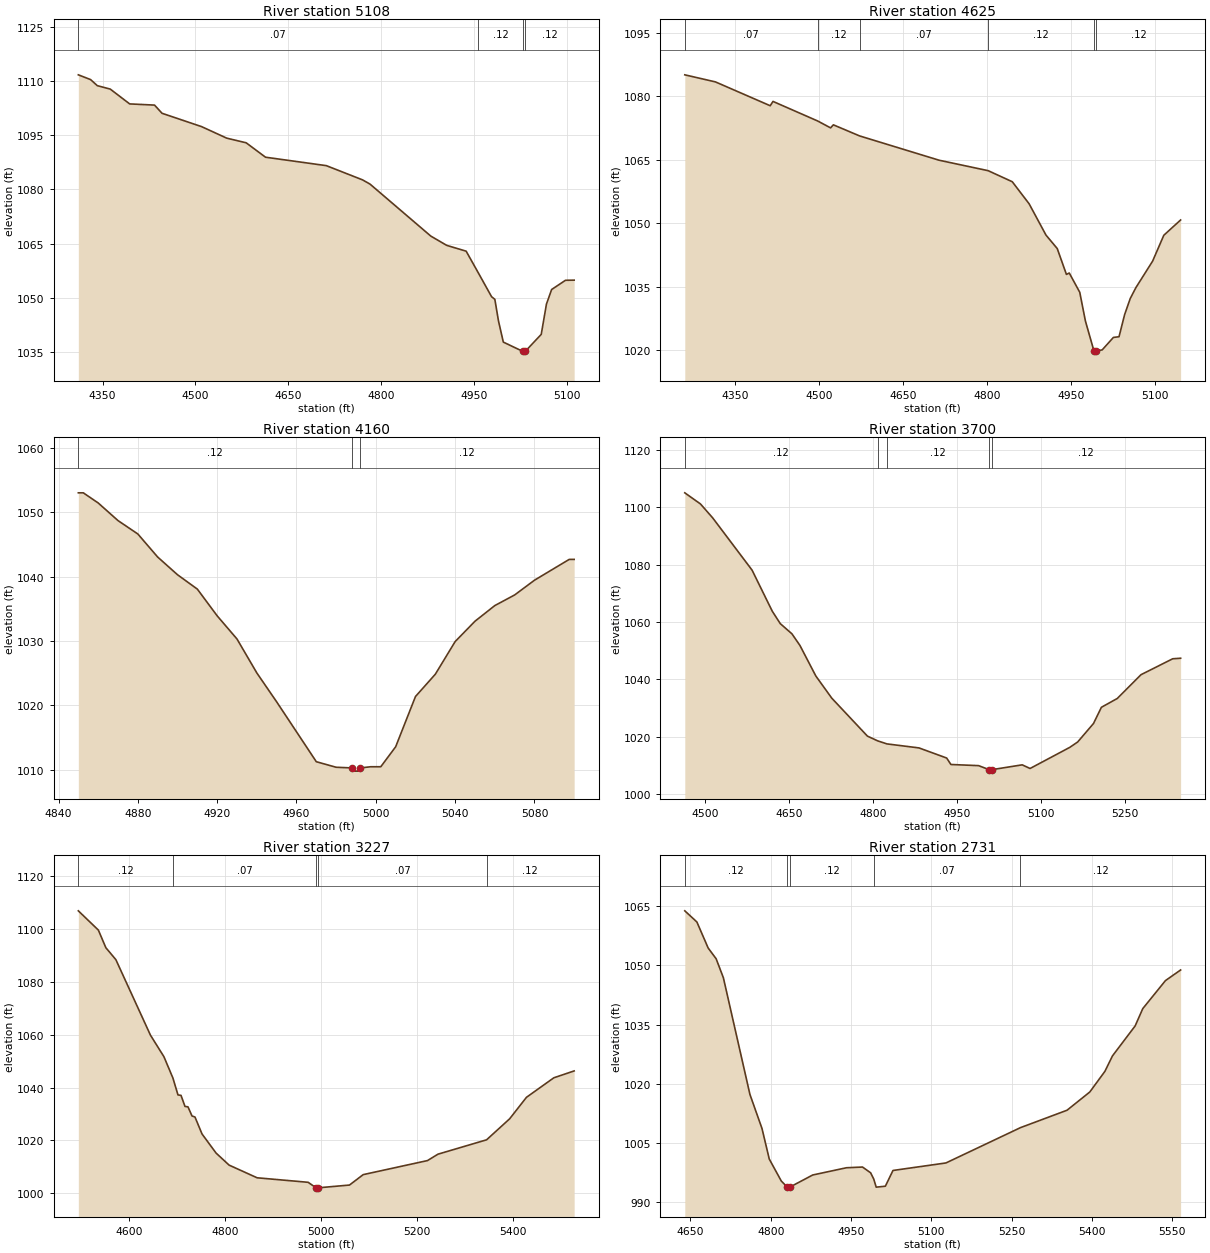
Type RM Length L Ch R = 1,5108,483,483,483
BEGIN DESCRIPTION:
Guadalupe Tributary 55 11.0
END DESCRIPTION:
XS GIS Cut Line= 3
      2189884.35     13893677.18      2189225.00     13893475.00
      2189124.96     13893424.98
#Sta/Elev= 30
  4310.8 1111.81  4330.6 1110.49  4341.5 1108.80  4362.4 1107.85  4393.8 1103.74
  4434.0 1103.41  4446.1 1101.14  4510.0 1097.44  4550.7 1094.24  4582.1 1092.95
  4613.4 1088.95  4711.7 1086.61  4770.3 1082.66  4782.4 1081.48  4880.6 1067.06
  4906.3 1064.49  4937.7 1062.88  4957.0 1056.98  4978.8 1050.25  4984.1 1049.51
  4990.0 1043.50  4997.8 1037.65  5029.1 1035.09  5029.3 1034.59  5033.3 1035.09
  5059.1 1039.80  5067.5 1048.19  5075.9 1052.24  5098.3 1054.80  5112.3 1054.84
#Mann=4,-1,0
  4310.8    0.07       0  4957.0    0.12       0  5029.1    0.05       0
  5033.3    0.12       0
Bank Sta=5029.1,5033.3
Exp/Cntr=0.3,0.1

Type RM Length L Ch R = 1,4625,465,465,465
BEGIN DESCRIPTION:
Guadalupe Tributary 55 10.0
END DESCRIPTION:
XS GIS Cut Line= 3
      2189957.01     13893094.97      2189225.00     13893025.00
      2189075.04     13893025.00
#Sta/Elev= 30
  4260.0 1085.01  4314.7 1083.34  4412.5 1077.71  4417.5 1078.73  4497.2 1074.11
  4520.3 1072.48  4525.3 1073.20  4572.1 1070.58  4714.1 1064.84  4801.7 1062.37
  4844.7 1059.76  4874.8 1054.55  4904.9 1047.16  4925.0 1043.98  4941.4 1037.87
  4946.5 1038.20  4965.2 1033.65  4975.3 1026.87  4990.6 1019.78  4990.9 1019.28
  4995.0 1019.78  5005.3 1020.05  5025.3 1022.99  5035.3 1023.15  5045.3 1028.37
  5055.3 1032.16  5065.3 1034.72  5095.3 1041.01  5115.3 1047.12  5145.3 1050.73
#Mann=6,-1,0
  4260.0    0.07       0  4497.2    0.12       0  4572.1    0.07       0
  4801.7    0.12       0  4990.6    0.05       0  4995.0    0.12       0
Bank Sta=4990.6,4995
Exp/Cntr=0.3,0.1

Type RM Length L Ch R = 1,4160,460,460,460
BEGIN DESCRIPTION:
Guadalupe Tributary 55 9.0
END DESCRIPTION:
XS GIS Cut Line= 3
      2189324.98     13892575.00      2189175.00     13892575.00
      2189074.98     13892575.00
#Sta/Elev= 30
  4850.0 1053.02  4852.5 1053.02  4860.0 1051.45  4870.0 1048.71  4880.0 1046.63
  4890.0 1043.05  4900.0 1040.30  4910.0 1038.07  4920.0 1033.92  4930.0 1030.32
  4940.0 1025.05  4950.0 1020.56  4970.0 1011.26  4980.0 1010.40  4987.8 1010.30
  4988.1 1009.80  4991.9 1009.80  4992.2 1010.30  4997.5 1010.48  5002.5 1010.48
  5010.0 1013.58  5020.0 1021.39  5030.0 1024.85  5040.0 1029.92  5050.0 1033.08
  5060.0 1035.51  5070.0 1037.16  5080.0 1039.45  5097.5 1042.68  5100.0 1042.68
#Mann=3,-1,0
  4850.0    0.12       0  4987.8    0.05       0  4992.2    0.12       0
Bank Sta=4987.8,4992.2
Exp/Cntr=0.3,0.1

Type RM Length L Ch R = 1,3700,473,473,473
BEGIN DESCRIPTION:
Guadalupe Tributary 55 8.0
END DESCRIPTION:
XS GIS Cut Line= 3
      2189574.99     13891825.01      2189175.00     13892175.00
      2188925.03     13892424.97
#Sta/Elev= 30
  4464.3 1105.00  4492.3 1101.12  4514.1 1096.27  4584.4 1078.07  4620.4 1063.78
  4634.7 1059.45  4655.5 1055.90  4669.8 1051.85  4698.2 1041.20  4726.7 1033.47
  4790.3 1020.26  4808.7 1018.60  4825.2 1017.55  4882.4 1016.15  4931.7 1012.63
  4939.3 1010.38  4988.7 1009.98  5007.7 1008.57  5008.0 1008.07  5012.2 1008.57
  5066.5 1010.26  5080.6 1008.99  5151.4 1016.34  5165.5 1018.21  5193.8 1024.66
  5207.9 1030.30  5236.2 1033.37  5278.6 1041.66  5335.2 1047.20  5349.3 1047.39
#Mann=5,-1,0
  4464.3    0.12       0  4808.7    0.07       0  4825.2    0.12       0
  5007.7    0.05       0  5012.2    0.12       0
Bank Sta=5007.7,5012.2
Exp/Cntr=0.3,0.1

Type RM Length L Ch R = 1,3227,496,496,496
BEGIN DESCRIPTION:
Guadalupe Tributary 55 7.0
END DESCRIPTION:
XS GIS Cut Line= 3
      2189375.02     13891474.99      2188975.00     13891775.00
      2188625.02     13892174.98
#Sta/Elev= 30
  4495.0 1106.83  4536.7 1099.54  4552.3 1092.87  4573.1 1088.36  4645.0 1059.82
  4673.1 1051.64  4691.7 1043.62  4702.3 1037.20  4708.6 1037.02  4716.9 1032.84
  4723.1 1032.69  4731.5 1029.23  4737.7 1028.83  4752.3 1022.44  4781.5 1015.21
  4808.6 1010.65  4866.9 1005.85  4973.1 1004.14  4989.6 1002.06  4989.9 1001.56
  4994.2 1002.06  5059.1 1003.10  5087.6 1007.04  5221.4 1012.36  5243.2 1014.78
  5344.3 1020.21  5392.2 1028.14  5427.3 1036.29  5484.3 1043.68  5526.5 1046.27
#Mann=5,-1,0
  4495.0    0.12       0  4691.7    0.07       0  4989.6    0.05       0
  4994.2    0.07       0  5344.3    0.12       0
Bank Sta=4989.6,4994.2
Exp/Cntr=0.3,0.1

Type RM Length L Ch R = 1,2731,431,431,431
BEGIN DESCRIPTION:
Guadalupe Tributary 55 6.0
END DESCRIPTION:
XS GIS Cut Line= 3
      2188825.01     13891124.98      2188625.00     13891425.00
      2188224.98     13891825.02
#Sta/Elev= 30
  4639.4 1063.85  4662.0 1061.02  4683.0 1054.43  4698.0 1051.68  4711.5 1046.87
  4761.1 1017.28  4783.6 1008.66  4797.2 1000.90  4819.7  995.32  4830.9  993.77
  4831.2  993.27  4835.5  993.77  4878.3  996.85  4941.4  998.69  4971.4  998.87
  4986.5  997.42  4992.3  995.86  4997.0  993.77  5014.1  994.01  5028.3  998.00
  5127.3  999.91  5266.3 1008.85  5353.5 1013.28  5396.0 1017.90  5424.2 1023.13
  5438.4 1027.06  5480.8 1034.67  5495.0 1039.05  5537.4 1046.16  5565.7 1048.85
#Mann=5,-1,0
  4639.4    0.12       0  4830.9    0.05       0  4835.5    0.12       0
  4992.3    0.07       0  5266.3    0.12       0
Bank Sta=4830.9,4835.5
Exp/Cntr=0.3,0.1

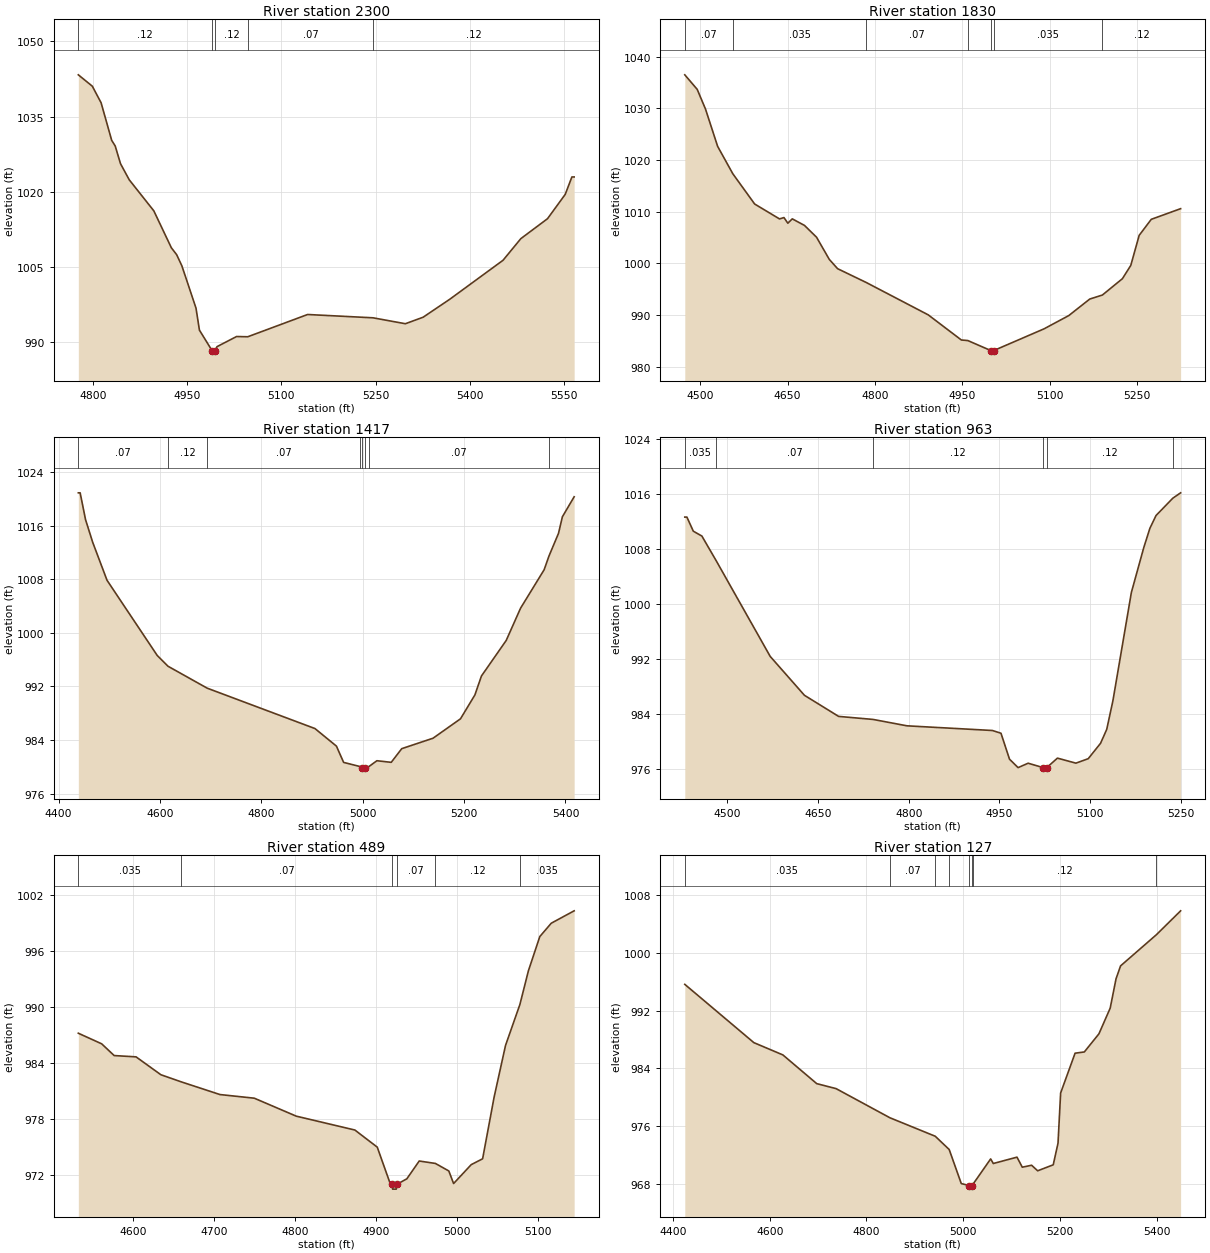
Type RM Length L Ch R = 1,2300,470,470,470
BEGIN DESCRIPTION:
Guadalupe Tributary 55 5.0
END DESCRIPTION:
XS GIS Cut Line= 3
      2188674.99     13890975.01      2188475.00     13891075.00
      2188074.98     13891475.02
#Sta/Elev= 30
  4776.8 1043.31  4799.1 1041.04  4813.1 1037.72  4829.9 1030.25  4835.5 1029.13
  4843.9 1025.61  4857.8 1022.39  4897.0 1016.19  4924.9 1008.83  4933.3 1007.46
  4941.7 1005.21  4964.1  996.81  4969.6  992.41  4989.7  988.33  4990.0  987.83
  4994.4  988.33  4997.6  989.12  5028.7  991.14  5046.5  991.09  5141.8  995.53
  5245.9  994.87  5297.4  993.69  5325.7  994.99  5368.1  998.57  5452.9 1006.34
  5481.2 1010.65  5523.7 1014.63  5551.9 1019.48  5562.5 1022.95  5566.1 1022.95
#Mann=5,-1,0
  4776.8    0.12       0  4989.7    0.05       0  4994.4    0.12       0
  5046.5    0.07       0  5245.9    0.12       0
Bank Sta=4989.7,4994.4
Exp/Cntr=0.3,0.1

Type RM Length L Ch R = 1,1830,413,413,413
BEGIN DESCRIPTION:
Guadalupe Tributary 55 4.0
END DESCRIPTION:
XS GIS Cut Line= 3
      2188524.98     13890425.02      2188125.00     13890775.00
      2187875.03     13890974.98
#Sta/Elev= 30
  4473.3 1036.47  4494.6 1033.66  4508.9 1029.84  4529.7 1022.64  4555.8 1017.34
  4593.3 1011.49  4636.0 1008.61  4643.6 1008.87  4650.3 1007.78  4657.9 1008.62
  4678.8 1007.36  4699.6 1005.07  4721.5 1000.78  4735.7  998.99  4784.9  996.32
  4891.4  990.06  4948.3  985.20  4959.4  985.09  4998.9  983.16  4999.3  982.66
  5004.0  983.16  5090.4  987.36  5132.8  989.92  5168.9  993.12  5190.5  993.89
  5224.9  997.05  5239.3  999.62  5253.7 1005.43  5274.5 1008.53  5324.9 1010.59
#Mann=7,-1,0
  4473.3    0.07       0  4555.8   0.035       0  4784.9    0.07       0
  4959.4   0.035       0  4998.9   0.035       0  5004.0   0.035       0
  5190.5    0.12       0
Bank Sta=4998.9,5004
Exp/Cntr=0.3,0.1

Type RM Length L Ch R = 1,1417,454,454,454
BEGIN DESCRIPTION:
Guadalupe Tributary 55 3.0
END DESCRIPTION:
XS GIS Cut Line= 3
      2188225.02     13890124.98      2187825.00     13890525.00
      2187425.02     13890624.99
#Sta/Elev= 30
  4439.1 1020.88  4442.7 1020.88  4453.3 1016.89  4467.4 1013.51  4495.7 1007.84
  4594.7  996.63  4616.0  995.02  4693.3  991.75  4905.8  985.73  4948.2  983.11
  4962.4  980.68  4995.0  980.06  4998.7  979.88  4999.1  979.38  5003.9  979.88
  5012.6  980.08  5028.0  980.93  5056.3  980.69  5077.0  982.73  5138.8  984.29
  5192.9  987.18  5221.3  990.74  5234.2  993.56  5283.1  998.87  5311.5 1003.69
  5357.9 1009.41  5367.4 1011.45  5386.2 1014.83  5393.9 1017.31  5417.1 1020.29
#Mann=8,-1,0
  4439.1    0.07       0  4616.0    0.12       0  4693.3    0.07       0
  4995.0   0.035       0  4998.7   0.035       0  5003.9   0.035       0
  5012.6    0.07       0  5367.4    0.12       0
Bank Sta=4998.7,5003.9
Exp/Cntr=0.3,0.1

Type RM Length L Ch R = 1,963,474,474,474
BEGIN DESCRIPTION:
Guadalupe Tributary 55 2.0
END DESCRIPTION:
XS GIS Cut Line= 3
      2187975.00     13889775.00      2187575.00     13890175.00
      2187325.04     13890125.01
#Sta/Elev= 30
  4429.4 1012.68  4432.9 1012.68  4443.5 1010.63  4457.7 1009.92  4481.0 1006.39
  4570.8  992.41  4627.4  986.76  4684.0  983.69  4740.9  983.25  4797.1  982.32
  4938.5  981.64  4952.7  981.24  4966.8  977.47  4981.0  976.24  4997.6  976.88
  5023.0  976.23  5023.4  975.73  5028.3  976.23  5046.1  977.62  5076.7  976.89
  5097.1  977.54  5117.5  979.78  5127.7  981.80  5137.9  985.95  5168.5 1001.72
  5188.9 1008.21  5199.1 1011.04  5209.3 1012.91  5237.1 1015.43  5250.0 1016.21
#Mann=6,-1,0
  4429.4   0.035       0  4481.0    0.07       0  4740.9    0.12       0
  5023.0    0.05       0  5028.3    0.12       0  5237.1   0.035       0
Bank Sta=5023,5028.3
Exp/Cntr=0.3,0.1

Type RM Length L Ch R = 1,489,362,362,362
BEGIN DESCRIPTION:
Guadalupe Tributary 55 1.0
END DESCRIPTION:
XS GIS Cut Line= 3
      2187775.04     13889524.97      2187375.00     13889775.00
      2187274.98     13889875.02
#Sta/Elev= 30
  4532.1  987.20  4561.0  986.06  4576.4  984.80  4603.5  984.66  4634.2  982.74
  4659.2  981.98  4707.3  980.61  4749.7  980.22  4801.6  978.29  4874.1  976.80
  4901.8  974.96  4917.2  971.19  4920.4  970.95  4920.8  970.45  4925.3  970.45
  4925.7  970.95  4938.4  971.56  4953.7  973.47  4973.7  973.21  4990.3  972.40
  4996.2  971.05  5018.0  973.08  5032.1  973.71  5046.3  980.33  5060.4  985.88
  5078.2  990.29  5088.7  993.90  5102.8  997.58  5117.0  999.02  5145.3 1000.35
#Mann=6,-1,0
  4532.1   0.035       0  4659.2    0.07       0  4920.4    0.05       0
  4925.7    0.07       0  4973.7    0.12       0  5078.2   0.035       0
Bank Sta=4920.4,4925.7
Exp/Cntr=0.3,0.1

Type RM Length L Ch R = 1,127,0,0,0
BEGIN DESCRIPTION:
Guadalupe Tributary 55 0.1
END DESCRIPTION:
XS GIS Cut Line= 3
      2187927.85     13889458.92      2187352.10     13889451.16
      2187190.56     13889870.95
#Sta/Elev= 30
  4424.2  995.66  4567.1  987.58  4627.1  985.88  4697.1  981.90  4737.1  981.21
  4848.5  977.17  4942.2  974.61  4971.1  972.77  4996.1  968.05  5012.2  967.78
  5012.6  967.28  5017.5  967.78  5019.9  967.92  5056.9  971.47  5062.3  970.83
  5111.3  971.71  5122.3  970.32  5141.6  970.59  5154.1  969.82  5186.3  970.65
  5196.2  973.65  5201.6  980.60  5231.5  986.12  5250.6  986.29  5280.8  988.80
  5304.1  992.36  5316.2  996.43  5325.6  998.22  5399.7 1002.54  5449.8 1005.85
#Mann=8,-1,0
  4424.2   0.035       0  4848.5    0.07       0  4942.2    0.12       0
  4971.1    0.07       0  5012.2    0.05       0  5017.5    0.07       0
  5019.9    0.12       0  5399.7   0.035       0
Bank Sta=5012.2,5017.5
Exp/Cntr=0.3,0.1

Chan Stop Cuts=-1