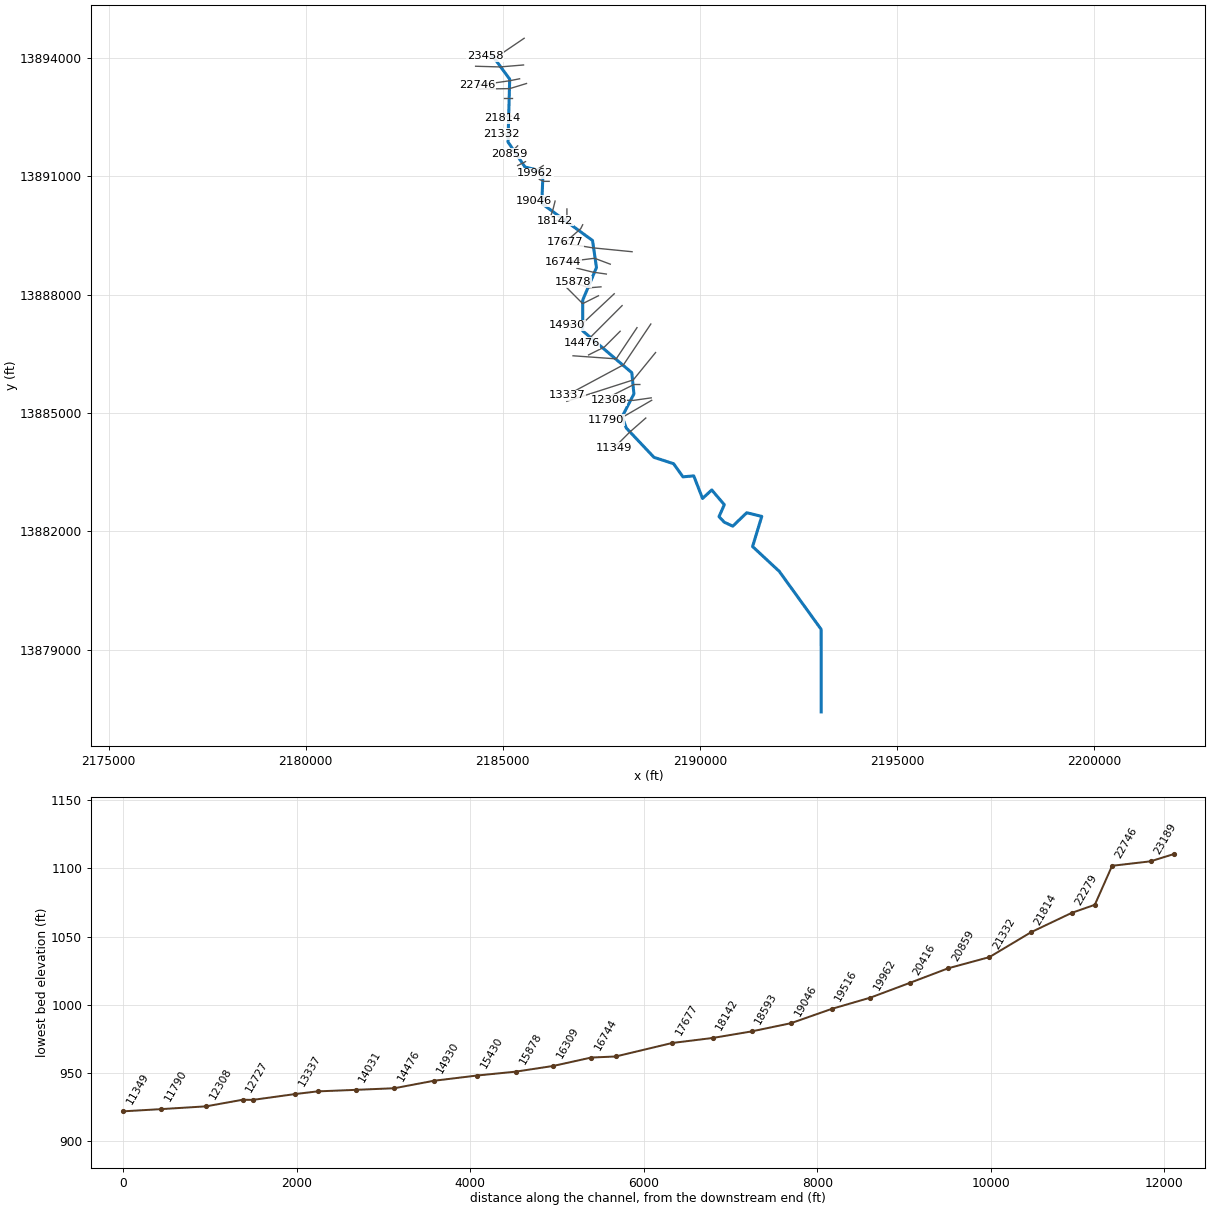
--- Guadalupe Tributary 58.prj (project) ---

Proj Title=Guadalupe Tributary 58 Base Level Engineering
Current Plan=p01
Default Exp/Contr=0.3,0.1
English Units
Geom File=g01
Flow File=f01
Plan File=p01
Y Axis Title=Elevation
X Axis Title(PF)=Main Channel Distance
X Axis Title(XS)=Station
BEGIN DESCRIPTION:
Guadalupe Tributary 58
END DESCRIPTION:
DSS Export Rating Curves= 0
DSS Export Rating Curve Sorted= 0
DSS Export Volume Flow Curves= 0
DXF OffsetX= 0
DXF OffsetY= 0
DXF ScaleX= 1
DXF ScaleY= 10

--- Guadalupe Tributary 58.p01 (plan) ---

Plan Title=Multiple Run
Short Identifier=Multiple
Geom File=g01
Flow File=f01
Subcritical Flow
K Sum by GR= 0
Std Step Tol= 0.01
Critical Tol= 0.01
Num of Std Step Trials= 20
Max Error Tol= 0.3
Flow Tol Ratio= 0.001
Split Flow NTrial= 30
Split Flow Tol= 0.02
Split Flow Ratio= 0.02
Log Output Level= 0
Friction Slope Method= 1
Unsteady Friction Slope Method= 2
Unsteady Bridges Friction Slope Method= 1
Parabolic Critical Depth
Global Vel Dist=  1 , 1 , 1
Global Log Level= 0
CheckData=True
Encroach Param= -1, 0, 0, 0
BEGIN DESCRIPTION:
Multiple Run
END DESCRIPTION:

--- Guadalupe Tributary 58.f01 (steady flow) ---

Flow Title=Multiple
Number of Profiles=7
Profile Names=10-year,25-year,50-year,1pct_min,100-year,1pct_plu,500-year
River Rch & RM= Guadalupe Tribut,Reach-1,23458
    1234    2102    2933    1983    3957    7896    7122
River Rch & RM= Guadalupe Tribut,Reach-1,21814
    1779    3105    4402    3019    6025   12021   11174
River Rch & RM= Guadalupe Tribut,Reach-1,17027
    3052    5462    7875    5482   10938   21824   20906
River Rch & RM= Guadalupe Tribut,Reach-1,12727
    3563    6417    9290    6491   12951   25841   24938
River Rch & RM= Guadalupe Tribut,Reach-1,10439
    3737    6708    9687    6748   13464   26863   25767
River Rch & RM= Guadalupe Tribut,Reach-1,4656
    3827    6853    9877    6865   13697   27328   26097
Boundary for River Rch & Prof#=Guadalupe Tribut,Reach-1,1
Up Type=0
Dn Type=3
Dn Slope=0.005
Boundary for River Rch & Prof#=Guadalupe Tribut,Reach-1,2
Up Type=0
Dn Type=3
Dn Slope=0.005
Boundary for River Rch & Prof#=Guadalupe Tribut,Reach-1,3
Up Type=0
Dn Type=3
Dn Slope=0.005
Boundary for River Rch & Prof#=Guadalupe Tribut,Reach-1,4
Up Type=0
Dn Type=3
Dn Slope=0.005
Boundary for River Rch & Prof#=Guadalupe Tribut,Reach-1,5
Up Type=0
Dn Type=3
Dn Slope=0.005
Boundary for River Rch & Prof#=Guadalupe Tribut,Reach-1,6
Up Type=0
Dn Type=3
Dn Slope=0.005
Boundary for River Rch & Prof#=Guadalupe Tribut,Reach-1,7
Up Type=0
Dn Type=3
Dn Slope=0.005

--- Guadalupe Tributary 58.g01 (geometry) ---

Geom Title=Existing Conditions
Program Version=4.10

River Reach=Guadalupe Tribut,Reach-1
Reach XY= 30
        2184725.       13894075.       2185173.8     13893465.41
      2185130.54     13891872.58      2185561.65     13891238.36
      2186019.72     13891127.71      2185988.36     13890311.66
        2187275.       13889375.       2187374.6     13888688.92
       2187026.2      13887864.5       2187026.2     13887084.59
      2188271.46     13886023.53      2188323.78      13885485.5
      2188025.08     13884909.61      2188130.84     13884622.71
      2188833.19     13883878.67      2189331.06     13883716.86
      2189568.01     13883384.15      2189842.21     13883408.79
      2190064.98     13882835.94      2190298.51     13883052.32
      2190617.21     13882678.42      2190482.29     13882374.91
      2190618.94     13882233.14      2190831.73     13882134.11
      2191185.62      13882474.4      2191567.24      13882381.8
      2191334.11     13881618.27      2192011.38     13880988.21
      2193072.83     13879519.56        2193075.       13877425.

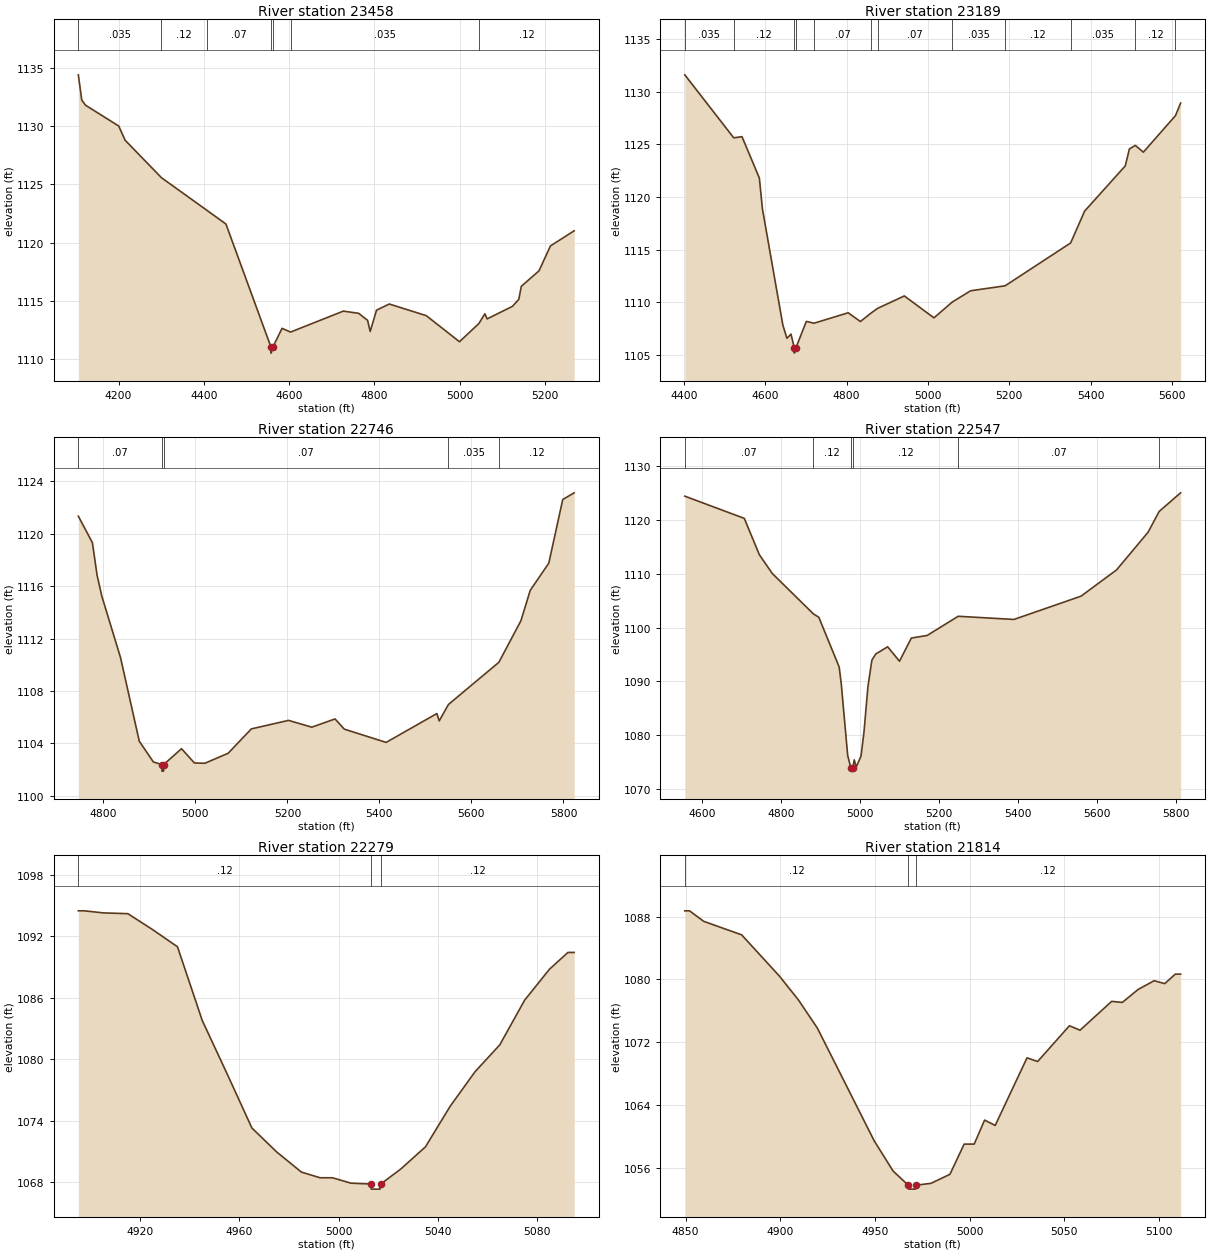
Type RM Length L Ch R = 1 ,23458   ,269,269,269
BEGIN DESCRIPTION:
Guadalupe Tributary 58 51.0
END DESCRIPTION:
XS GIS Cut Line= 3
      2185540.64     13894501.78      2184774.59     13893981.87
      2184545.38     13894044.39
#Sta/Elev= 30
  4105.6 1134.42  4113.6 1132.26  4122.5 1131.81  4200.4 1130.02  4215.4  1128.8
  4300.7 1125.58  4407.3 1122.78    4452  1121.6  4557.8 1111.01    4558 1110.51
  4561.8 1111.01  4583.6 1112.64  4603.6 1112.32  4727.4 1114.12  4763.3 1113.93
  4784.3 1113.33  4790.4 1112.37  4805.3  1114.2  4835.2 1114.73    4922 1113.73
  4999.9 1111.49  5045.4 1113.05  5059.6 1113.89  5064.8 1113.45  5124.3 1114.53
  5139.1 1115.13    5145 1116.25  5186.5 1117.58  5213.4 1119.72    5269 1121.02
#Mann= 7 ,-1 , 0
  4105.6    .035       0  4300.7     .12       0  4407.3     .07       0
  4557.8    .035       0  4561.8     .07       0  4603.6    .035       0
  5045.4     .12       0
Bank Sta=4557.8,4561.8
XS Rating Curve= 0 ,0
Exp/Cntr=0.3,0.1

Type RM Length L Ch R = 1 ,23189   ,443,443,443
BEGIN DESCRIPTION:
Guadalupe Tributary 58 50.0
END DESCRIPTION:
XS GIS Cut Line= 3
      2185525.04       13893825.        2184925.       13893775.
      2184309.18     13893792.64
#Sta/Elev= 30
  4402.7  1131.6  4522.9 1125.62  4543.2 1125.73  4585.9  1121.8  4593.4 1118.88
  4643.6 1107.85  4653.6 1106.59  4663.6 1106.98  4671.7 1105.68  4671.9 1105.18
  4675.7 1105.68  4701.3 1108.19  4720.2 1108.02  4804.1 1109.01  4834.2 1108.18
  4859.6 1108.96  4876.5 1109.43  4942.1 1110.61  5014.8 1108.53  5060.2 1110.04
  5104.9  1111.1  5189.7 1111.57  5350.7 1115.64    5385 1118.66    5485 1122.96
    5495 1124.56  5509.6  1124.9  5529.4 1124.26  5608.3 1127.73  5620.9 1128.92
#Mann= 12 ,-1 , 0
  4402.7    .035       0  4522.9     .12       0  4671.7     .05       0
  4675.7     .12       0  4720.2     .07       0  4859.6     .12       0
  4876.5     .07       0  5060.2    .035       0  5189.7     .12       0
  5350.7    .035       0  5509.6     .12       0  5608.3    .035       0
Bank Sta=4671.7,4675.7
XS Rating Curve= 0 ,0
Exp/Cntr=0.3,0.1

Type RM Length L Ch R = 1 ,22746   ,199,199,199
BEGIN DESCRIPTION:
Guadalupe Tributary 58 49.0
END DESCRIPTION:
XS GIS Cut Line= 3
      2185424.96     13893474.99        2185175.       13893425.
      2184360.43     13893308.29
#Sta/Elev= 30
  4745.5 1121.33  4776.1 1119.31  4786.3 1116.82  4796.5 1115.24  4837.2 1110.55
    4878 1104.17  4908.6 1102.59    4927 1102.39  4927.3 1101.89  4930.8 1101.89
    4931 1102.39  4969.8  1103.6  4997.9 1102.51  5020.6 1102.49  5071.1 1103.25
  5121.6 1105.11  5202.5 1105.76    5253 1105.24  5303.5 1105.87  5323.7 1105.09
  5414.6 1104.08  5524.9 1106.28    5530 1105.72    5550 1106.97  5659.7 1110.19
  5707.6 1113.36  5727.8 1115.67  5768.2 1117.75  5798.5  1122.6  5823.3 1123.11
#Mann= 5 ,-1 , 0
  4745.5     .07       0    4927     .05       0    4931     .07       0
    5550    .035       0  5659.7     .12       0
Bank Sta=4927,4931
XS Rating Curve= 0 ,0
Exp/Cntr=0.3,0.1

Type RM Length L Ch R = 1 ,22547   ,268,268,268
BEGIN DESCRIPTION:
Guadalupe Tributary 58 48.5
END DESCRIPTION:
XS GIS Cut Line= 3
      2185599.93     13893355.18      2185175.03     13893226.01
      2184362.65     13893212.29
#Sta/Elev= 30
  4555.9 1124.45  4706.7 1120.32  4744.8 1113.57  4777.7 1110.06  4881.9 1102.55
  4895.5 1101.93  4947.2 1092.67  4952.5 1089.52  4968.7 1076.24  4977.1 1073.81
  4977.4 1073.31  4981.1 1073.81  4985.3  1075.4  4990.5 1074.09  5002.5 1076.11
    5010 1080.56    5020 1088.99    5030 1093.95    5040  1095.1    5070 1096.44
    5100 1093.75  5130.1 1098.06  5170.1 1098.54  5248.8 1102.11  5390.1 1101.52
  5560.1 1105.85  5650.1 1110.73  5730.1 1117.75  5758.1 1121.61  5812.5 1125.07
#Mann= 6 ,-1 , 0
  4555.9     .07       0  4881.9     .12       0  4977.1     .05       0
  4981.1     .12       0  5248.8     .07       0  5758.1     .12       0
Bank Sta=4977.1,4981.1
XS Rating Curve= 0 ,0
Exp/Cntr=0.3,0.1

Type RM Length L Ch R = 1 ,22279   ,465,465,465
BEGIN DESCRIPTION:
Guadalupe Tributary 58 48.0
END DESCRIPTION:
XS GIS Cut Line= 3
      2185224.96       13892975.        2185125.       13892975.
      2185024.96       13892975.
#Sta/Elev= 27
    4895 1094.49  4897.5 1094.49    4905 1094.29    4915 1094.21    4925 1092.65
    4935 1090.98    4945 1083.78    4955 1078.59    4965  1073.3    4975 1070.96
    4985 1068.99  4992.5 1068.44  4997.5 1068.44    5005 1067.91    5013 1067.83
  5013.2 1067.33  5016.7 1067.33    5017 1067.83    5025 1069.28    5035 1071.45
    5045 1075.42    5055 1078.78    5065 1081.41    5075 1085.76    5085 1088.78
  5092.5 1090.43    5095 1090.43
#Mann= 3 ,-1 , 0
    4895     .12       0    5013     .05       0    5017     .12       0
Bank Sta=5013,5017
XS Rating Curve= 0 ,0
Exp/Cntr=0.3,0.1

Type RM Length L Ch R = 1 ,21814   ,482,482,482
BEGIN DESCRIPTION:
Guadalupe Tributary 58 47.0
END DESCRIPTION:
XS GIS Cut Line= 3
      2185224.96       13892525.        2185075.       13892525.
      2184974.97     13892474.99
#Sta/Elev= 30
  4849.6 1088.73  4852.1 1088.73  4859.6 1087.39  4879.6 1085.67  4899.6  1080.4
  4909.6 1077.37  4919.6 1073.78  4949.6 1059.41  4959.6 1055.55  4967.6 1053.75
  4967.8 1053.25  4971.3 1053.25  4971.6 1053.75  4979.6 1053.99  4989.6 1055.14
  4997.1 1058.99  5002.4 1058.99  5007.9 1062.05  5013.5 1061.37  5030.3 1069.99
  5035.9 1069.52  5052.7 1074.08  5058.3 1073.51    5075 1077.19  5080.6 1077.05
    5089 1078.71  5097.4 1079.82    5103 1079.45  5108.6 1080.66  5111.4 1080.66
#Mann= 3 ,-1 , 0
  4849.6     .12       0  4967.6     .05       0  4971.6     .12       0
Bank Sta=4967.6,4971.6
XS Rating Curve= 0 ,0
Exp/Cntr=0.3,0.1

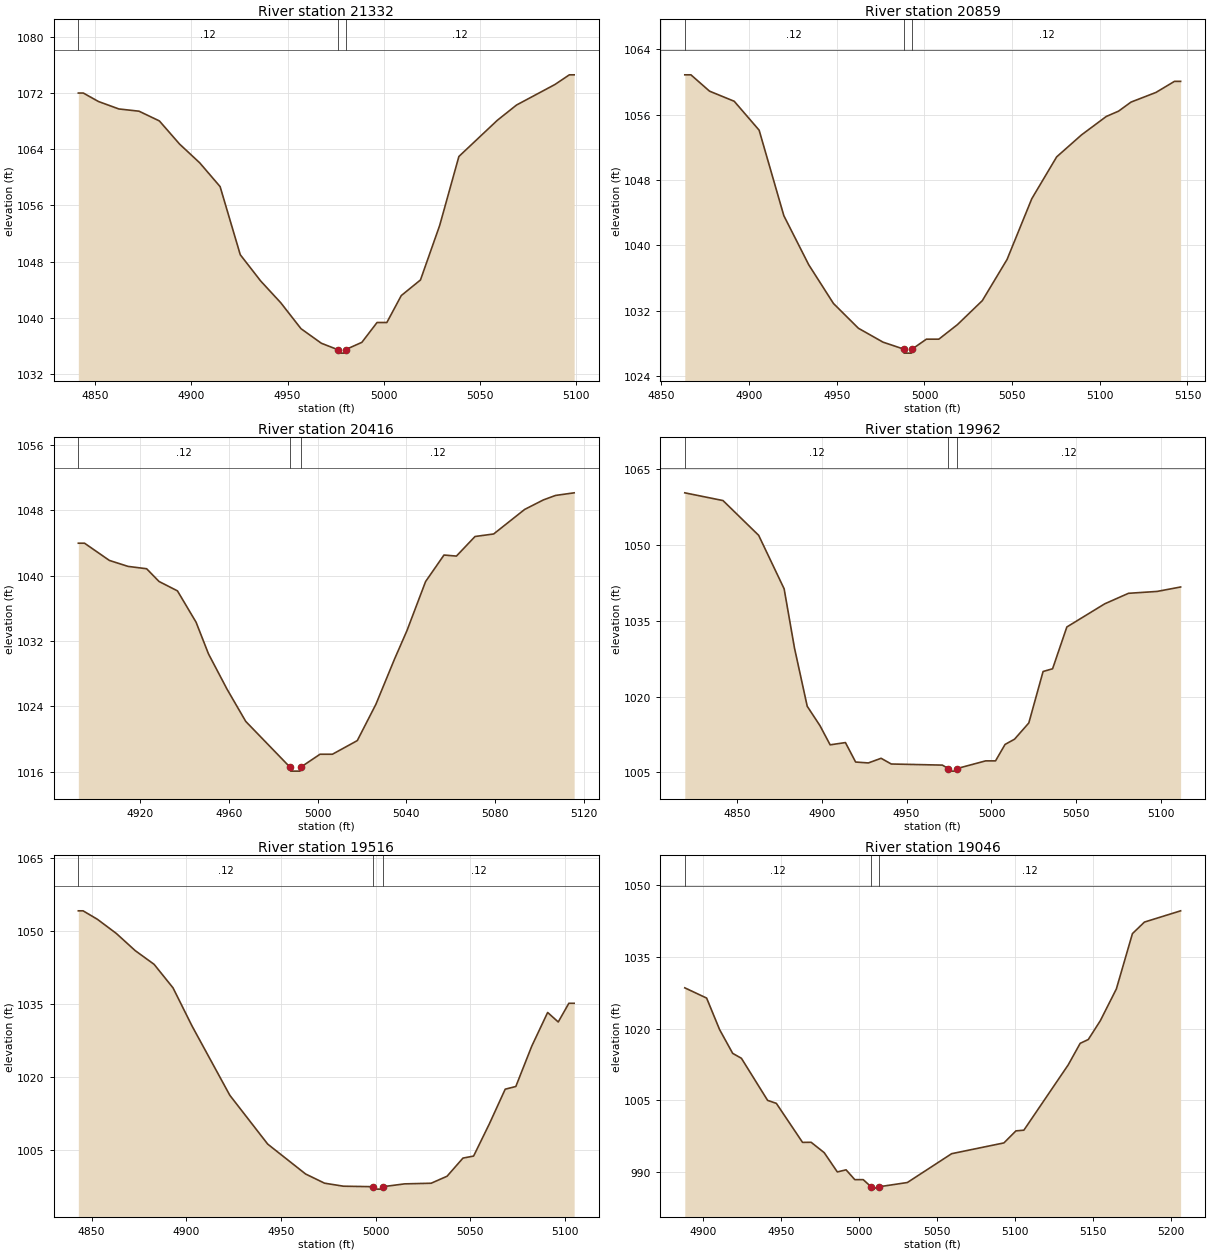
Type RM Length L Ch R = 1 ,21332   ,473,473,473
BEGIN DESCRIPTION:
Guadalupe Tributary 58 46.0
END DESCRIPTION:
XS GIS Cut Line= 3
      2185224.99       13892125.        2185075.       13892075.
        2184975.       13892075.
#Sta/Elev= 30
  4841.1 1072.04  4843.7 1072.04  4851.6 1070.83  4862.2 1069.77  4872.7 1069.45
  4883.3 1068.06  4893.8 1064.76  4904.3 1062.08  4914.9 1058.69  4925.4 1048.97
    4936 1045.23  4946.5 1042.11    4957 1038.42  4967.6 1036.34  4976.1 1035.43
  4976.3 1034.93  4979.9 1034.93  4980.2 1035.43  4988.7 1036.47  4996.6  1039.3
  5001.7  1039.3  5009.2 1043.14  5019.2 1045.37  5029.2 1053.15  5039.2 1062.99
  5059.2 1068.15  5069.2 1070.33  5089.2 1073.26  5096.7 1074.64  5099.2 1074.64
#Mann= 3 ,-1 , 0
  4841.1     .12       0  4976.1     .05       0  4980.2     .12       0
Bank Sta=4976.1,4980.2
XS Rating Curve= 0 ,0
Exp/Cntr=0.3,0.1

Type RM Length L Ch R = 1 ,20859   ,443,443,443
BEGIN DESCRIPTION:
Guadalupe Tributary 58 45.0
END DESCRIPTION:
XS GIS Cut Line= 3
      2185374.97     13891774.97        2185275.       13891675.
        2185175.       13891575.
#Sta/Elev= 28
  4863.3 1060.87  4866.8 1060.87  4877.4 1058.87  4891.5 1057.63  4905.7 1054.09
  4919.8 1043.61    4934  1037.6  4948.1 1032.86  4962.3 1029.83  4976.4 1028.12
  4988.1 1027.28  4988.4 1026.78  4992.6 1026.78    4993 1027.28  5001.1 1028.49
  5008.2 1028.49  5018.8 1030.27    5033 1033.21  5047.1 1038.25  5061.2 1045.69
  5075.4 1050.82  5089.5  1053.5  5103.7 1055.77  5110.7 1056.42  5117.8 1057.53
    5132 1058.71  5142.6 1060.07  5146.1 1060.07
#Mann= 3 ,-1 , 0
  4863.3     .12       0  4988.1     .05       0    4993     .12       0
Bank Sta=4988.1,4993
XS Rating Curve= 0 ,0
Exp/Cntr=0.3,0.1

Type RM Length L Ch R = 1 ,20416   ,454,454,454
BEGIN DESCRIPTION:
Guadalupe Tributary 58 44.0
END DESCRIPTION:
XS GIS Cut Line= 3
      2185575.02     13891375.01        2185475.       13891325.
      2185375.03     13891275.02
#Sta/Elev= 30
  4892.1 1043.99  4894.9 1043.99  4906.1 1041.88  4914.5 1041.15  4922.9 1040.86
  4928.5  1039.3  4936.8 1038.15  4945.2 1034.31  4950.8 1030.43  4959.2 1026.09
  4967.6 1022.16  4987.5 1016.57  4987.9 1016.07  4992.1 1016.07  4992.5 1016.57
  5001.1 1018.14  5006.7 1018.14  5017.9 1019.81  5026.3 1024.26  5034.7  1029.8
  5040.3 1033.28  5048.7 1039.29    5057 1042.54  5062.6 1042.41    5071 1044.81
  5079.4 1045.12  5093.4 1048.13  5101.8 1049.29  5107.3 1049.84  5115.7 1050.16
#Mann= 3 ,-1 , 0
  4892.1     .12       0  4987.5     .05       0  4992.5     .12       0
Bank Sta=4987.5,4992.5
XS Rating Curve= 0 ,0
Exp/Cntr=0.3,0.1

Type RM Length L Ch R = 1 ,19962   ,446,446,446
BEGIN DESCRIPTION:
Guadalupe Tributary 58 43.0
END DESCRIPTION:
XS GIS Cut Line= 3
      2186024.96     13891274.98        2185875.       13891175.
      2185825.02     13891075.03
#Sta/Elev= 30
  4819.4 1060.31  4841.9 1058.78  4862.9  1051.9  4877.9 1041.32    4884  1029.6
  4891.5 1018.08    4899 1014.25    4905 1010.45    4914  1010.9    4920 1007.05
  4927.5 1006.87    4935 1007.79    4941 1006.66  4971.1 1006.44  4974.6 1005.75
  4974.9 1005.25  4979.2 1005.25  4979.6 1005.75  4996.6 1007.28  5002.4 1007.28
    5008 1010.53  5013.6 1011.57    5022 1014.78  5030.4 1024.96    5036  1025.5
  5044.4 1033.77  5066.7 1038.35  5080.7 1040.43  5097.5  1040.8  5111.4 1041.68
#Mann= 3 ,-1 , 0
  4819.4     .12       0  4974.6     .05       0  4979.6     .12       0
Bank Sta=4974.6,4979.6
XS Rating Curve= 0 ,0
Exp/Cntr=0.3,0.1

Type RM Length L Ch R = 1 ,19516   ,470,470,470
BEGIN DESCRIPTION:
Guadalupe Tributary 58 42.0
END DESCRIPTION:
XS GIS Cut Line= 3
      2186174.95       13890875.        2186025.       13890875.
      2185924.96     13890925.02
#Sta/Elev= 30
    4843 1054.18  4845.5 1054.18    4853 1052.46    4863 1049.55    4873 1046.01
    4883 1043.19    4893 1038.35    4903 1030.54    4923 1016.27    4943 1006.24
    4963  1000.1    4973  998.21    4983  997.59  4998.8  997.49  4999.2  996.99
  5003.5  996.99  5003.8  997.49  5015.3  998.07  5029.3   998.2  5037.7  999.64
  5046.1 1003.37  5051.7 1003.78    5060 1010.38  5068.4 1017.53    5074 1018.08
  5082.4 1026.36  5090.8 1033.29  5096.4 1031.34    5102 1035.18  5104.8 1035.18
#Mann= 3 ,-1 , 0
    4843     .12       0  4998.8     .05       0  5003.8     .12       0
Bank Sta=4998.8,5003.8
XS Rating Curve= 0 ,0
Exp/Cntr=0.3,0.1

Type RM Length L Ch R = 1 ,19046   ,453,453,453
BEGIN DESCRIPTION:
Guadalupe Tributary 58 41.0
END DESCRIPTION:
XS GIS Cut Line= 3
      2186074.99     13890474.99        2185975.       13890425.
      2185775.04     13890375.01
#Sta/Elev= 30
  4888.1 1028.52  4902.1 1026.38  4910.4 1019.81  4918.8 1014.84  4924.4 1013.81
  4941.2 1005.02  4946.8  1004.4  4963.6  996.25  4969.1  996.27  4977.5   994.1
  4985.9  990.08  4991.5  990.52  4997.1  988.47  5002.5  988.47  5007.5  986.99
  5007.9  986.49  5012.8  986.99  5030.8  987.87  5059.2  993.89  5092.7  996.14
  5100.4  998.65  5105.5   998.8  5133.9 1012.42  5141.6 1016.93  5146.8 1017.73
  5154.5 1021.65  5164.8 1028.29  5175.1 1039.84  5182.8 1042.25    5206  1044.6
#Mann= 3 ,-1 , 0
  4888.1     .12       0  5007.5     .05       0  5012.8     .12       0
Bank Sta=5007.5,5012.8
XS Rating Curve= 0 ,0
Exp/Cntr=0.3,0.1

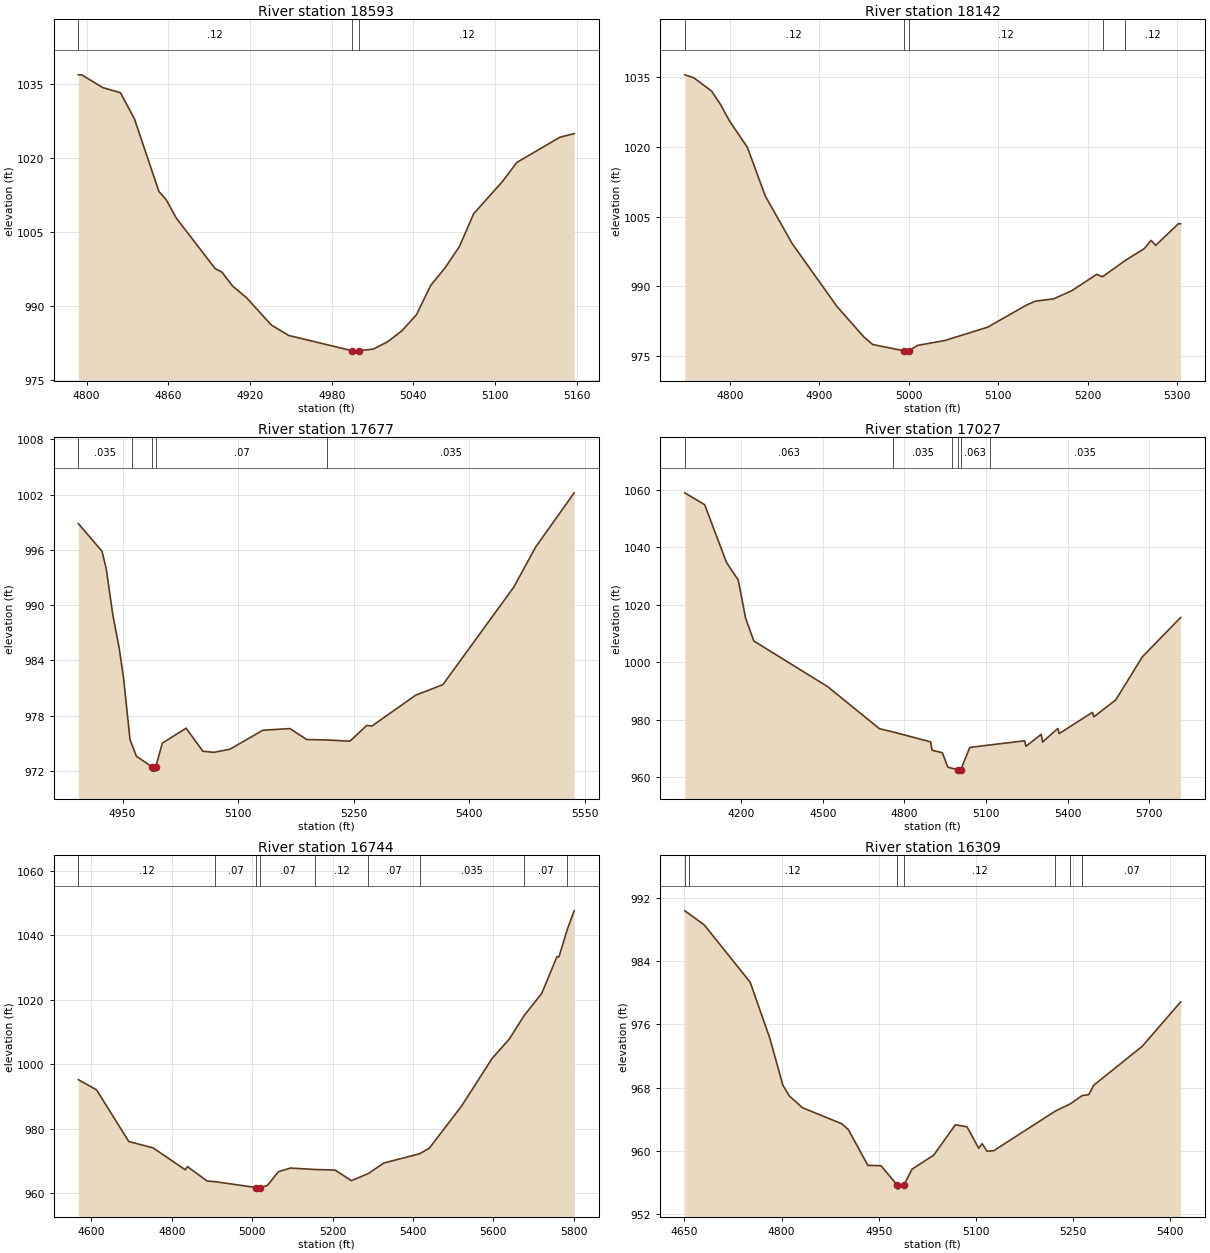
Type RM Length L Ch R = 1 ,18593   ,451,451,451
BEGIN DESCRIPTION:
Guadalupe Tributary 58 40.0
END DESCRIPTION:
XS GIS Cut Line= 3
      2186324.99     13890374.95        2186275.       13890175.
      2186225.01     13890025.02
#Sta/Elev= 30
  4793.9 1036.84  4796.4 1036.84  4811.9 1034.25  4824.8 1033.22  4835.1 1027.93
  4853.1 1013.21  4858.3  1011.6    4866 1007.77  4894.4  997.61  4899.5  996.85
  4907.2  994.07  4917.5  991.69  4935.6  986.19  4948.5  984.05  4994.8  980.98
  4995.2  980.48  4999.7  980.48  5000.1  980.98  5010.5  981.29  5021.1  982.78
  5031.6  985.02  5042.2  988.23  5052.7  994.18  5063.3  997.77  5073.8 1002.06
  5084.3 1008.72  5105.4 1015.22    5116  1019.1  5147.6  1024.2  5158.1 1024.94
#Mann= 3 ,-1 , 0
  4793.9     .12       0  4994.8     .05       0  5000.1     .12       0
Bank Sta=4994.8,5000.1
XS Rating Curve= 0 ,0
Exp/Cntr=0.3,0.1

Type RM Length L Ch R = 1 ,18142   ,465,465,465
BEGIN DESCRIPTION:
Guadalupe Tributary 58 39.0
END DESCRIPTION:
XS GIS Cut Line= 3
        2186625.     13890175.04        2186625.       13889925.
      2186324.98       13889875.
#Sta/Elev= 30
  4749.7 1035.55  4759.7 1034.92  4779.7 1032.05  4789.7 1029.14  4799.7 1025.62
  4819.7 1019.92  4839.7 1009.45  4869.7  999.23  4919.7  985.71  4949.7  979.16
  4959.7   977.5  4994.5  976.14  4994.9  975.64  4999.5  975.64    5000  976.14
  5009.9  977.31  5040.3  978.35  5088.4  981.24  5131.5  985.98  5141.7  986.83
  5161.9  987.32  5182.2  989.08  5210.1   992.6  5216.6  992.08  5242.1   995.6
  5263.3  998.14  5270.9  999.92    5276  998.82  5301.3 1003.49  5303.9 1003.49
#Mann= 5 ,-1 , 0
  4749.7     .12       0  4994.5     .05       0    5000     .12       0
  5216.6     .07       0  5242.1     .12       0
Bank Sta=4994.5,5000
XS Rating Curve= 0 ,0
Exp/Cntr=0.3,0.1

Type RM Length L Ch R = 1 ,17677   ,650,650,650
BEGIN DESCRIPTION:
Guadalupe Tributary 58 38.0
END DESCRIPTION:
XS GIS Cut Line= 3
      2187024.99     13889774.97        2186975.       13889675.
      2186574.98     13889324.99
#Sta/Elev= 30
  4892.6  998.86  4923.3  995.85  4928.9  993.91  4937.3  988.95  4945.7   985.3
  4951.3  982.07  4959.7  975.39  4962.7  974.74    4968  973.59  4987.6  972.48
  4988.1  971.98  4992.7  971.98  4993.1  972.48  5001.6  975.02  5032.4  976.64
  5054.2  974.14  5068.4  974.02  5089.3  974.36    5132  976.42  5167.1   976.6
    5189  975.41  5215.7  975.36    5245  975.23  5266.8  976.94  5273.4  976.87
  5330.4  980.23  5365.5  981.36  5457.6  991.96    5486  996.31  5535.9 1002.19
#Mann= 5 ,-1 , 0
  4892.6    .035       0  4962.7     .07       0  4987.6     .05       0
  4993.1     .07       0  5215.7    .035       0
Bank Sta=4987.6,4993.1
XS Rating Curve= 0 ,0
Exp/Cntr=0.3,0.1

Type RM Length L Ch R = 1 ,17027   ,283,283,283
BEGIN DESCRIPTION:
Guadalupe Tributary 58 37.0
END DESCRIPTION:
XS GIS Cut Line= 3
      2188277.77     13889090.86      2187274.96     13889189.98
      2186469.72     13889322.67
#Sta/Elev= 30
  3992.3 1059.03  4065.4  1054.9  4145.8 1034.77    4189 1028.65  4216.2 1015.27
  4246.3 1007.42  4517.6  991.53  4708.5  976.86  4756.7  975.78  4896.5  972.28
  4901.5  969.38  4939.7   968.5  4959.8  963.45  4976.7  963.06  4997.7  962.59
  4998.2  962.09  5007.5  962.59  5040.5  970.32  5114.2  971.21  5242.1  972.65
  5247.2  970.75  5303.3  974.91  5308.4  972.23  5364.4  976.96  5369.5  975.18
  5491.8  982.58  5496.9  980.99  5577.6  986.91  5675.3 1001.89  5816.1 1015.61
#Mann= 6 ,-1 , 0
  3992.3    .063       0  4756.7    .035       0  4976.7    .063       0
  4997.7     .05       0  5007.5    .063       0  5114.2    .035       0
Bank Sta=4997.7,5007.5
XS Rating Curve= 0 ,0
Exp/Cntr=0.3,0.1

Type RM Length L Ch R = 1 ,16744   ,435,435,435
BEGIN DESCRIPTION:
Guadalupe Tributary 58 36.0
END DESCRIPTION:
XS GIS Cut Line= 3
      2187725.01     13888774.99        2187325.       13888925.
      2186525.04     13888825.01
#Sta/Elev= 30
  4567.7  995.23  4613.1  992.07  4693.2  976.06  4753.7  974.08  4833.8   967.3
  4839.2  968.27  4888.1  963.81  4908.6   963.6  5010.2   961.8  5010.7   961.3
    5020   961.8  5037.7  962.41  5065.5  966.72  5095.7  967.83  5156.3  967.39
  5206.5  967.21  5246.9  963.92  5289.5  966.16  5327.5  969.39    5417  972.27
  5440.9  974.01  5521.5  987.14  5597.1 1001.83  5639.9 1007.83  5676.9 1015.13
  5720.5 1021.98  5758.3 1033.36  5763.3 1033.29  5784.2 1041.85  5801.1 1047.56
#Mann= 9 ,-1 , 0
  4567.7     .12       0  4908.6     .07       0  5010.2     .05       0
    5020     .07       0  5156.3     .12       0  5289.5     .07       0
    5417    .035       0  5676.9     .07       0  5784.2    .035       0
Bank Sta=5010.2,5020
XS Rating Curve= 0 ,0
Exp/Cntr=0.3,0.1

Type RM Length L Ch R = 1 ,16309   ,431,431,431
BEGIN DESCRIPTION:
Guadalupe Tributary 58 35.0
END DESCRIPTION:
XS GIS Cut Line= 3
      2187624.99       13888525.        2187275.       13888575.
      2186874.95     13888675.01
#Sta/Elev= 30
  4650.5  990.32  4656.7  989.97  4680.8  988.52  4751.5   981.3  4781.8  974.24
    4802  968.29  4812.1  966.93  4832.3  965.45  4892.9  963.43    4903   962.7
  4933.3  958.17  4953.5  958.13  4978.9  955.67  4979.4  955.17  4988.8  955.67
  5001.5  957.69    5035  959.46  5068.5   963.3  5086.5  963.04  5104.5  960.33
  5109.7  960.91  5117.4  959.96  5127.7  960.02  5222.5  965.01  5245.9  965.94
  5264.3  966.98  5274.6  967.11  5282.3   968.3  5357.1  973.21  5416.4  978.81
#Mann= 7 ,-1 , 0
  4650.5     .07       0  4656.7     .12       0  4978.9     .05       0
  4988.8     .12       0  5222.5     .07       0  5245.9    .035       0
  5264.3     .07       0
Bank Sta=4978.9,4988.8
XS Rating Curve= 0 ,0
Exp/Cntr=0.3,0.1

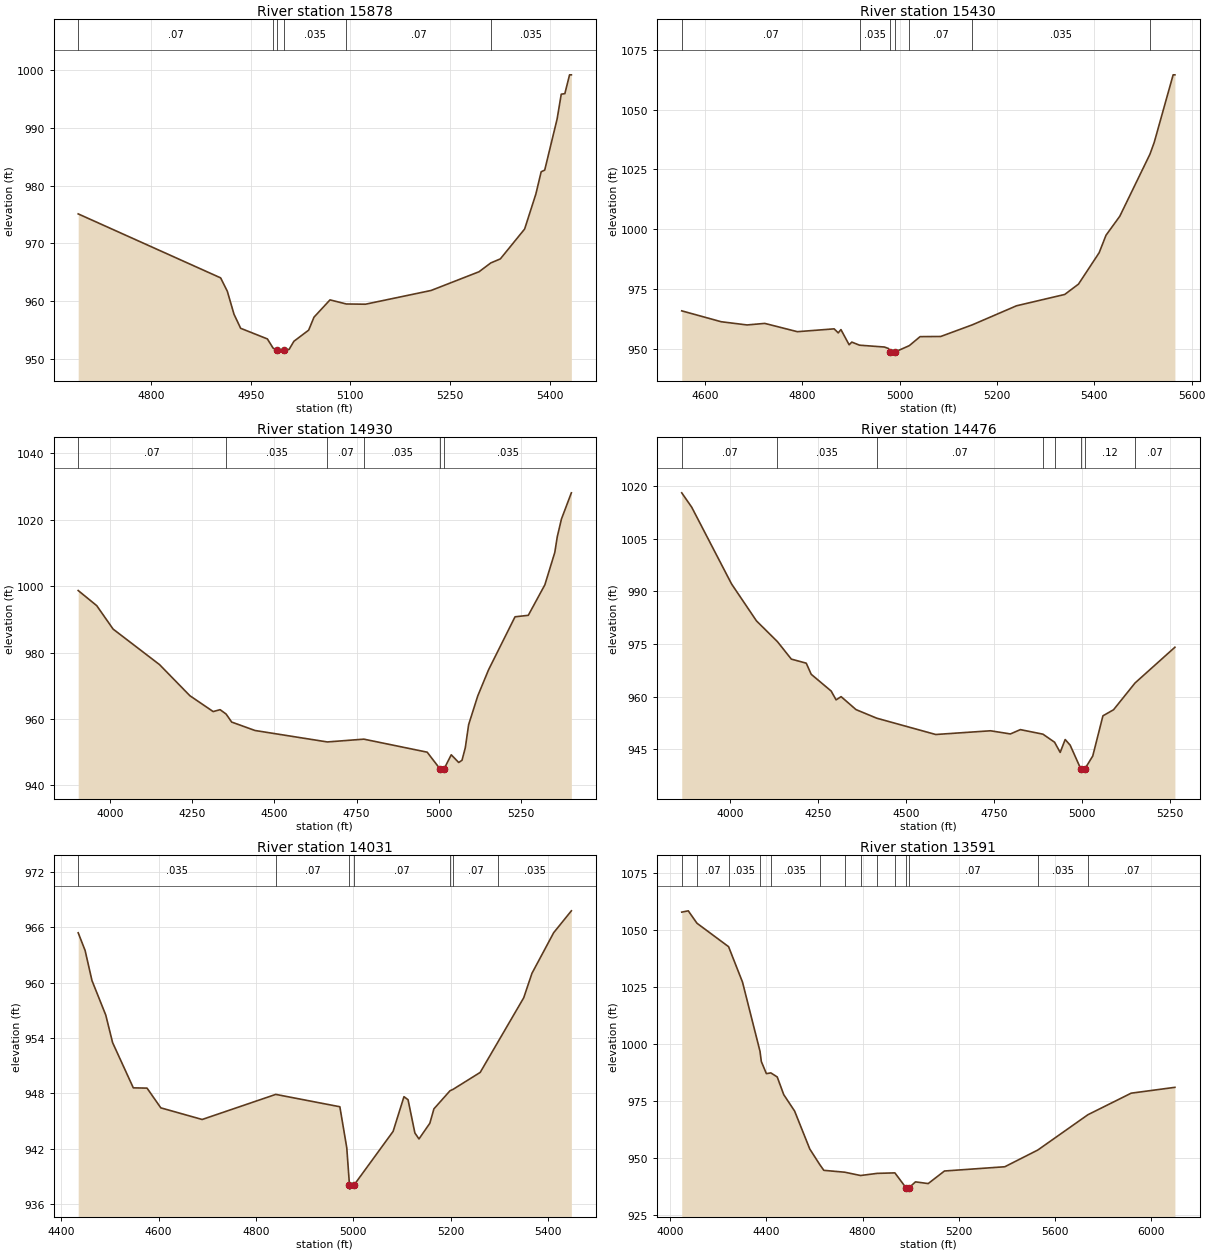
Type RM Length L Ch R = 1 ,15878   ,448,448,448
BEGIN DESCRIPTION:
Guadalupe Tributary 58 34.0
END DESCRIPTION:
XS GIS Cut Line= 3
      2187488.63     13888200.69        2187175.       13888175.
      2186774.98     13888325.01
#Sta/Elev= 30
  4690.6  975.11  4904.9  964.03    4915  961.69    4925  957.73    4935   955.3
  4975.2  953.46  4983.8  951.87  4990.2   951.5  4990.7     951  5000.2   951.5
  5007.9  951.65  5015.1  953.05  5037.3  954.98  5045.3  957.22  5069.4  960.22
    5094  959.51  5122.8  959.47  5221.5  961.85  5293.6  965.09  5311.3  966.62
  5325.7  967.32  5362.2  972.49  5379.1  978.55  5387.1  982.41  5392.4  982.69
  5411.1  991.56  5417.3  995.84  5422.7  995.93  5429.8  999.19  5432.5  999.19
#Mann= 6 ,-1 , 0
  4690.6     .07       0  4983.8    .035       0  4990.2    .035       0
  5000.2    .035       0    5094     .07       0  5311.3    .035       0
Bank Sta=4990.2,5000.2
XS Rating Curve= 0 ,0
Exp/Cntr=0.3,0.1

Type RM Length L Ch R = 1 ,15430   ,500,500,500
BEGIN DESCRIPTION:
Guadalupe Tributary 58 33.0
END DESCRIPTION:
XS GIS Cut Line= 3
      2187424.96     13887974.98        2187025.       13887775.
      2186624.97     13888175.03
#Sta/Elev= 30
  4552.7  965.82  4633.7  961.27  4686.8  959.92  4723.2  960.57  4790.2   957.1
  4865.7  958.29  4874.1  956.61  4879.7  957.98  4896.5  951.62    4902  952.75
    4918  951.45  4969.1  950.68  4977.5  950.05  4980.8  948.63  4981.3  948.13
  4990.9  948.63    5020  951.25  5042.3  955.03  5084.7   955.1  5149.5  959.97
  5240.3  967.94  5339.3  972.68  5367.6  977.01    5410  990.14  5424.1  997.46
  5452.4 1005.41  5514.4  1031.4  5523.1  1036.3    5562 1064.59  5565.6 1064.59
#Mann= 7 ,-1 , 0
  4552.7     .07       0    4918    .035       0  4980.8    .035       0
  4990.9    .035       0    5020     .07       0  5149.5    .035       0
  5514.4     .07       0
Bank Sta=4980.8,4990.9
XS Rating Curve= 0 ,0
Exp/Cntr=0.3,0.1

Type RM Length L Ch R = 1 ,14930   ,454,454,454
BEGIN DESCRIPTION:
Guadalupe Tributary 58 32.0
END DESCRIPTION:
XS GIS Cut Line= 3
      2187825.01     13888025.01        2187025.       13887275.
      2186625.01       13887225.
#Sta/Elev= 30
  3903.4  998.67  3959.8  994.11  4009.6  987.05  4150.8  976.35  4243.1  966.98
  4313.9  962.21    4335  962.78  4353.3  961.45  4370.1  959.05    4441  956.51
  4661.1  953.06  4772.1   953.9  4964.6  949.98    5005  944.77  5005.5  944.27
  5015.2  944.77  5037.8  949.19  5060.5  946.88  5070.5  947.53  5080.6  951.32
  5090.7  958.27  5118.4  966.91  5151.2  974.77  5231.8  990.76  5272.1   991.2
  5322.5 1000.39  5352.7 1010.14  5360.3 1014.89  5372.9 1020.19  5403.1  1028.1
#Mann= 6 ,-1 , 0
  3903.4     .07       0  4353.3    .035       0  4661.1     .07       0
  4772.1    .035       0    5005    .035       0  5015.2    .035       0
Bank Sta=5005,5015.2
XS Rating Curve= 0 ,0
Exp/Cntr=0.3,0.1

Type RM Length L Ch R = 1 ,14476   ,445,445,445
BEGIN DESCRIPTION:
Guadalupe Tributary 58 31.0
END DESCRIPTION:
XS GIS Cut Line= 3
      2188025.03     13887725.03        2187225.       13886925.
      2187000.03     13886777.18
#Sta/Elev= 30
  3863.1 1018.06  3891.4 1013.97  4004.6  992.11  4075.3   981.6    4135  975.67
  4174.3  970.71  4216.7  969.55  4230.8  966.39  4287.4  961.62  4301.5   959.1
  4315.7  960.02  4358.1  956.33  4416.7  953.89  4584.4  949.24    4740   950.3
  4796.5   949.4  4824.8  950.63    4889  949.33    4922  947.04  4937.9  944.14
  4952.1  947.81  4966.2  946.21    4997  939.31  4997.5  938.81  5007.2  939.31
  5030.4  943.12  5059.3  954.56  5089.5  956.29  5150.4   963.9  5263.7  974.09
#Mann= 8 ,-1 , 0
  3863.1     .07       0    4135    .035       0  4416.7     .07       0
    4889    .035       0    4922     .12       0    4997     .05       0
  5007.2     .12       0  5150.4     .07       0
Bank Sta=4997,5007.2
XS Rating Curve= 0 ,0
Exp/Cntr=0.3,0.1

Type RM Length L Ch R = 1 ,14031   ,440,440,440
BEGIN DESCRIPTION:
Guadalupe Tributary 58 30.0
END DESCRIPTION:
XS GIS Cut Line= 3
      2187975.01     13887075.01        2187575.       13886675.
      2187175.02     13886475.01
#Sta/Elev= 30
  4434.7  965.41  4448.9  963.49    4463  960.23  4491.3  956.49  4505.4   953.5
  4547.9   948.6  4576.1  948.57  4604.4  946.43  4689.3  945.17  4840.5  947.89
  4972.1  946.55  4986.3  942.11  4991.8  938.12  4992.3  937.62    5002  938.12
  5081.5  943.88  5103.8  947.64  5112.2  947.31  5126.2  943.71  5134.6  943.06
  5156.9  944.76  5165.3  946.32  5198.3  948.28    5205  948.45  5260.3  950.27
    5296   953.5  5349.8  958.37  5366.6  961.01  5411.3  965.42  5447.6  967.79
#Mann= 7 ,-1 , 0
  4434.7    .035       0  4840.5     .07       0  4991.8     .05       0
    5002     .07       0  5198.3    .035       0    5205     .07       0
    5296    .035       0
Bank Sta=4991.8,5002
XS Rating Curve= 0 ,0
Exp/Cntr=0.3,0.1

Type RM Length L Ch R = 1 ,13591   ,254,254,254
BEGIN DESCRIPTION:
Guadalupe Tributary 58 29.0
END DESCRIPTION:
XS GIS Cut Line= 3
      2188402.67     13887166.12        2187875.       13886375.
      2186780.23     13886453.02
#Sta/Elev= 30
    4049 1057.84  4076.1 1058.41  4112.2 1052.98  4243.6  1042.7  4301.4 1027.19
  4374.1  996.87  4379.6  992.39  4400.6  987.09    4419  987.42  4445.6  985.64
  4472.7  977.89  4517.8  970.71  4580.8  954.09  4621.9  947.32  4639.3  944.73
  4726.3  943.91  4791.8  942.46  4860.7   943.4  4934.3  943.62  4981.3     937
  4981.8   936.5  4991.6     937    5020  939.68  5072.7  938.93  5140.3  944.44
  5390.9   946.3  5527.9  953.62  5736.3   969.1  5915.8  978.53  6097.5  981.09
#Mann= 14 ,-1 , 0
    4049    .035       0  4112.2     .07       0  4243.6    .035       0
  4374.1     .07       0    4419    .035       0  4621.9     .07       0
  4726.3    .035       0  4791.8     .07       0  4860.7    .035       0
  4934.3     .07       0  4981.3     .05       0  4991.6     .07       0
  5527.9    .035       0  5736.3     .07       0
Bank Sta=4981.3,4991.6
XS Rating Curve= 0 ,0
Exp/Cntr=0.3,0.1

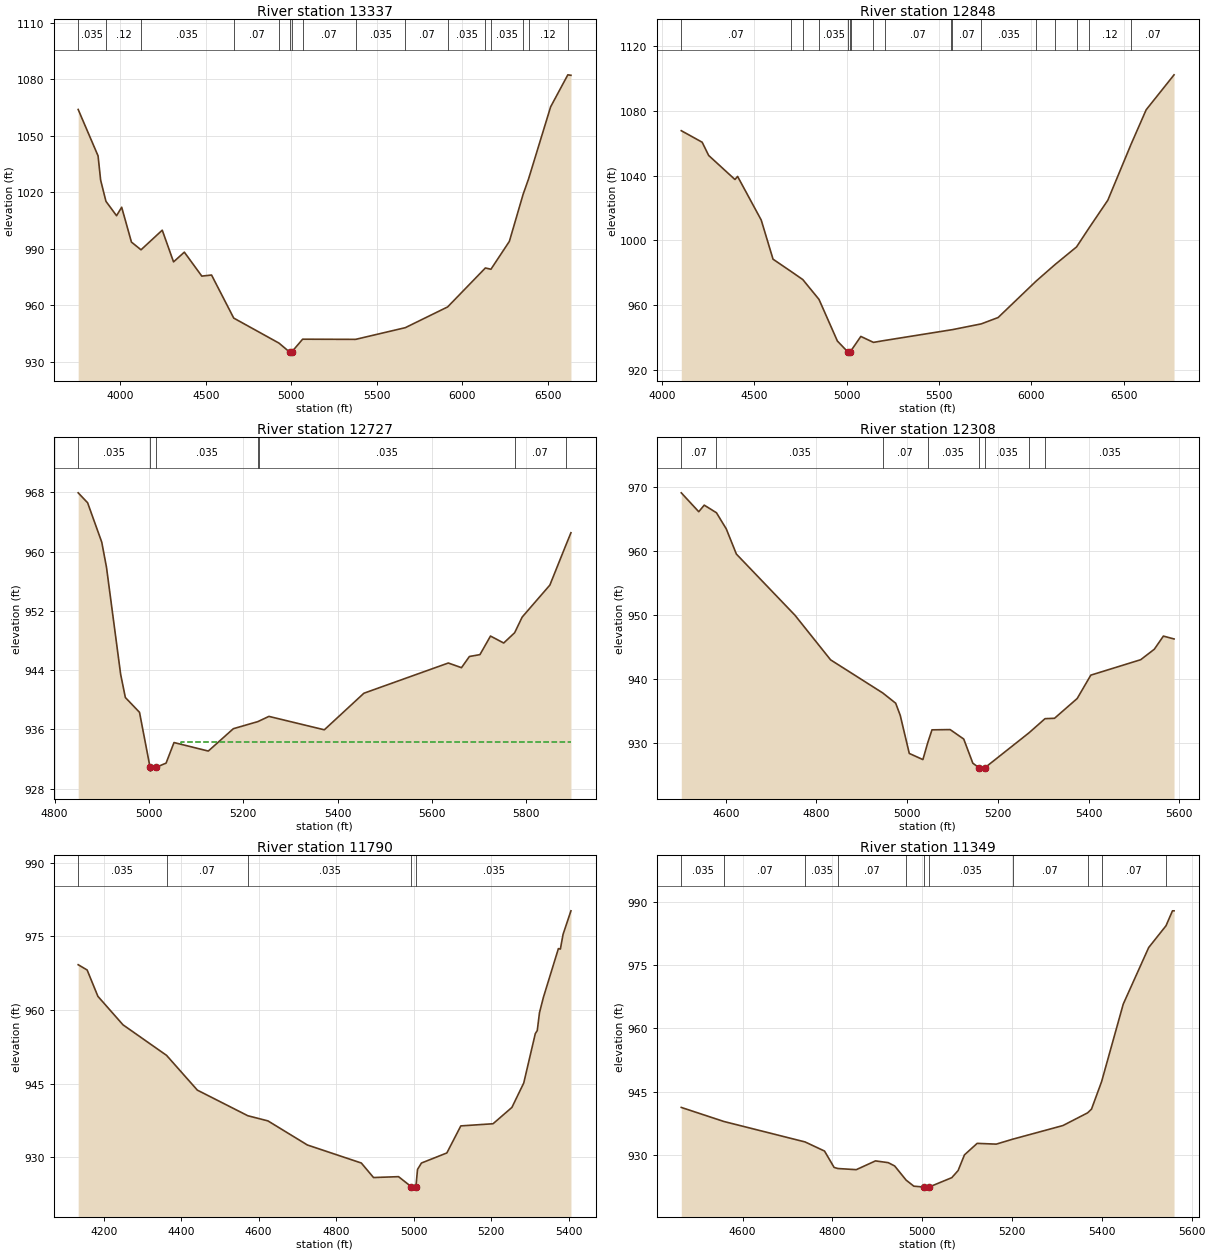
Type RM Length L Ch R = 1 ,13337   ,489,489,489
BEGIN DESCRIPTION:
Guadalupe Tributary 58 28.5
END DESCRIPTION:
XS GIS Cut Line= 3
      2188753.36     13887258.57      2188059.35     13886224.11
       2186619.5     13885451.79
#Sta/Elev= 30
  3754.3 1064.02  3870.5 1039.38  3885.5  1026.5  3916.6 1015.22  3978.6 1007.57
  4008.5 1012.08  4065.6  993.57  4121.5  989.46  4245.6  999.89  4311.6  983.04
  4374.7  988.21  4476.7  975.49  4533.7  976.06  4663.3  953.19  4928.1  939.87
  4990.7  935.07  4991.2  934.57  5001.1  935.07  5065.9  941.97  5375.6  941.88
  5665.9  948.09  5913.4  959.12  6133.9  979.81  6166.4  979.13  6274.1  993.95
  6354.4 1018.94  6386.5 1027.21  6515.3 1065.45  6615.7 1082.42  6633.9 1082.17
#Mann= 16 ,-1 , 0
  3754.3    .035       0  3916.6     .12       0  4121.5    .035       0
  4663.3     .07       0  4928.1    .035       0  4990.7    .035       0
  5001.1    .035       0  5065.9     .07       0  5375.6    .035       0
  5665.9     .07       0  5913.4    .035       0  6133.9     .07       0
  6166.4    .035       0  6354.4     .07       0  6386.5     .12       0
  6615.7     .07       0
Bank Sta=4990.7,5001.1
XS Rating Curve= 0 ,0
Exp/Cntr=0.3,0.1

Type RM Length L Ch R = 1 ,12848   ,121,121,121
BEGIN DESCRIPTION:
Guadalupe Tributary 58 28.0
END DESCRIPTION:
XS GIS Cut Line= 3
      2188873.34     13886535.25      2188308.11     13885841.57
      2186621.36     13885299.54
#Sta/Elev= 30
  4105.2 1067.82  4218.2 1060.69  4253.4  1052.5  4395.6 1037.65    4410 1039.54
  4537.8 1012.57  4601.7  988.37    4700  980.72  4762.8  975.76  4850.5  963.49
    4950  937.75  5008.5  930.78    5009  930.28  5019.1  930.78  5021.3  931.37
  5076.8  940.61  5145.1  936.93  5205.6   938.1    5567  944.71  5570.7  944.76
  5728.1  948.35  5819.8   952.3  6025.8  974.86  6128.3   985.1    6244  995.94
  6312.5  1007.8  6413.3 1024.82  6538.4 1059.24  6620.8 1080.74  6771.7 1102.36
#Mann= 17 ,-1 , 0
  4105.2     .07       0    4700    .035       0  4762.8     .07       0
  4850.5    .035       0  5008.5    .035       0  5019.1    .035       0
  5021.3     .07       0  5145.1    .035       0  5205.6     .07       0
    5567    .035       0  5570.7     .07       0  5728.1    .035       0
  6025.8     .07       0  6128.3     .12       0    6244    .035       0
  6312.5     .12       0  6538.4     .07       0
Bank Sta=5008.5,5019.1
XS Rating Curve= 0 ,0
Exp/Cntr=0.3,0.1

Type RM Length L Ch R = 1 ,12727   ,419,419,419
BEGIN DESCRIPTION:
Guadalupe Tributary 58 27.0
END DESCRIPTION:
XS GIS Cut Line= 3
      2188474.98       13885725.        2188325.       13885725.
        2187525.       13885325.
#Sta/Elev= 30
  4850.1  967.93  4870.1  966.59  4900.1  961.26  4910.1  957.88  4940.1  943.43
  4950.1  940.29  4980.1  938.29  5002.5  930.85    5003  930.35  5014.5  930.85
  5036.4  931.43  5053.2  934.21  5125.9  933.06    5179  936.08  5231.1  937.04
    5233   937.1  5254.4  937.74  5371.8  935.93  5455.7  940.87  5634.6  944.95
  5662.5  944.32  5679.3  945.83  5701.6  946.08    5724  948.59    5752  947.65
  5775.2  949.04  5791.1  951.15  5849.8  955.47  5883.8  960.87  5894.5  962.54
#Mann= 7 ,-1 , 0
  4850.1    .035       0  5002.5    .035       0  5014.5    .035       0
  5231.1     .07       0    5233    .035       0  5775.2     .07       0
  5883.8    .035       0
#XS Ineff= 2 , 0
       0                  5067.2       0  934.23
Permanent Ineff=
       F       F
Bank Sta=5002.5,5014.5
XS Rating Curve= 0 ,0
Exp/Cntr=0.3,0.1

Type RM Length L Ch R = 1 ,12308   ,518,518,518
BEGIN DESCRIPTION:
Guadalupe Tributary 58 26.0
END DESCRIPTION:
XS GIS Cut Line= 3
      2188763.08      13885386.7      2188310.88     13885322.44
      2187681.51     13885332.87
#Sta/Elev= 30
  4502.1  969.15  4540.6  966.19  4552.7  967.22  4579.6  966.03  4601.2  963.51
  4623.6  959.55  4752.7  949.97  4831.2  942.98  4946.4  937.78  4974.7  936.18
  4984.7  934.29  5004.7  928.31  5034.7  927.35  5045.1  929.93  5054.7  932.01
  5094.7  932.05  5124.7  930.57  5144.7  926.79  5158.8  926.04  5159.3  925.54
  5170.8  926.04  5268.7  931.55  5303.9  933.76  5324.8  933.82  5374.8  936.92
  5404.8  940.58  5514.8     943  5544.8  944.64  5564.8   946.7  5588.3  946.25
#Mann= 8 ,-1 , 0
  4502.1     .07       0  4579.6    .035       0  4946.4     .07       0
  5045.1    .035       0  5158.8     .05       0  5170.8    .035       0
  5268.7     .07       0  5303.9    .035       0
Bank Sta=5158.8,5170.8
XS Rating Curve= 0 ,0
Exp/Cntr=0.3,0.1

Type RM Length L Ch R = 1 ,11790   ,441,441,441
BEGIN DESCRIPTION:
Guadalupe Tributary 58 25.0
END DESCRIPTION:
XS GIS Cut Line= 3
      2188774.98     13885324.99      2188037.52     13884896.83
      2187624.97     13884824.99
#Sta/Elev= 30
  4134.3  969.22  4157.4  968.15  4185.2  962.78  4249.9  956.98  4362.4  950.75
  4441.8  943.67  4572.1  938.45    4624   937.4  4725.8  932.49  4864.9  928.82
  4896.4  925.86  4960.9  926.04  4993.7     924  4994.2   923.5  5005.8     924
  5009.9  927.51  5020.1  928.82  5085.6  930.87  5121.6  936.38  5204.8  936.82
  5253.5  940.15    5284  945.12  5313.8  955.17  5318.9  955.81  5324.6  959.44
  5334.7  962.57  5373.4   972.5  5378.5  972.41  5385.5  975.42  5405.8   980.2
#Mann= 5 ,-1 , 0
  4134.3    .035       0  4362.4     .07       0  4572.1    .035       0
  4993.7    .035       0  5005.8    .035       0
Bank Sta=4993.7,5005.8
XS Rating Curve= 0 ,0
Exp/Cntr=0.3,0.1

Type RM Length L Ch R = 1 ,11349   ,463,463,463
BEGIN DESCRIPTION:
Guadalupe Tributary 58 24.0
END DESCRIPTION:
XS GIS Cut Line= 3
      2188625.03     13884875.03        2188225.       13884525.
      2187825.03     13884125.03
#Sta/Elev= 30
  4463.6  941.25  4558.6  937.91  4739.2  933.06  4782.5   930.9  4803.9  927.01
  4812.4  926.75  4853.3  926.48    4896  928.56  4924.4  928.14  4938.7  927.36
  4964.3  923.99  4981.4  922.56  5003.1  922.36  5003.6  921.86  5015.4  922.36
  5065.9  924.58    5080  926.27  5094.1  929.99  5122.4  932.72  5164.9  932.54
  5201.2   933.7  5313.4  936.95  5368.3  939.96    5377  940.85  5399.5  947.38
  5447.7  965.78  5504.3  979.19  5542.9  984.37  5557.3  987.91  5560.8  987.91
#Mann= 11 ,-1 , 0
  4463.6    .035       0  4558.6     .07       0  4739.2    .035       0
  4812.4     .07       0  4964.3    .035       0  5003.1    .035       0
  5015.4    .035       0  5201.2     .07       0  5368.3     .12       0
  5399.5     .07       0  5542.9     .12       0
Bank Sta=5003.1,5015.4
XS Rating Curve= 0 ,0
Exp/Cntr=0.3,0.1