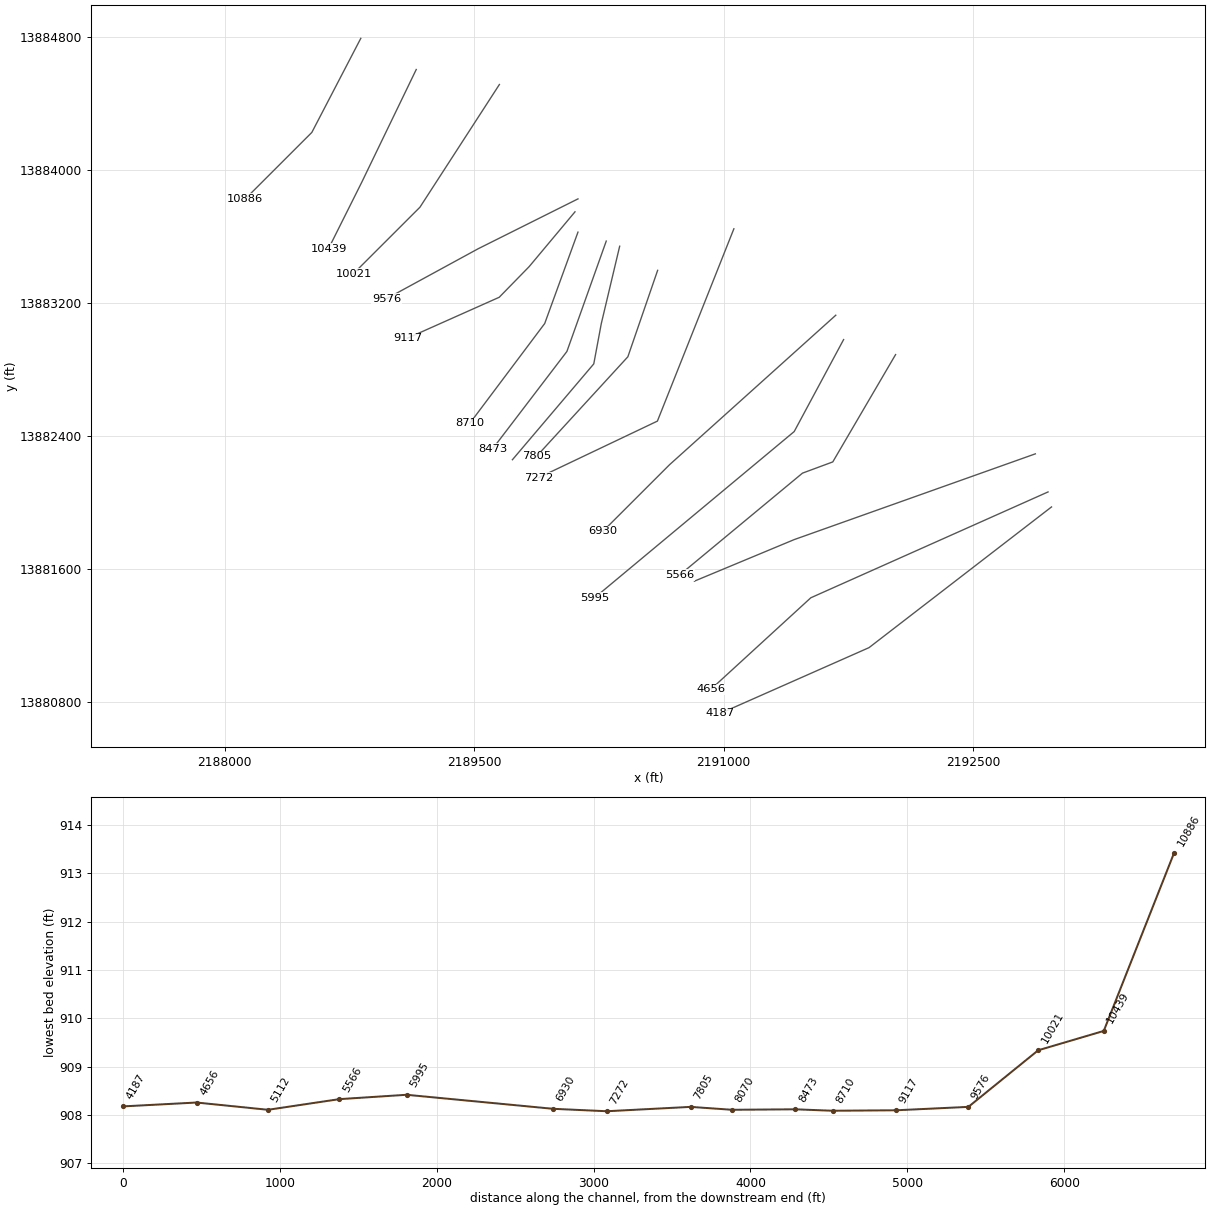
HEC-RAS study Guadalupe Tributary 58.prj: Guadalupe Tributary 58 Base Level Engineering

--- Guadalupe Tributary 58.g01 (geometry) --- (continued)

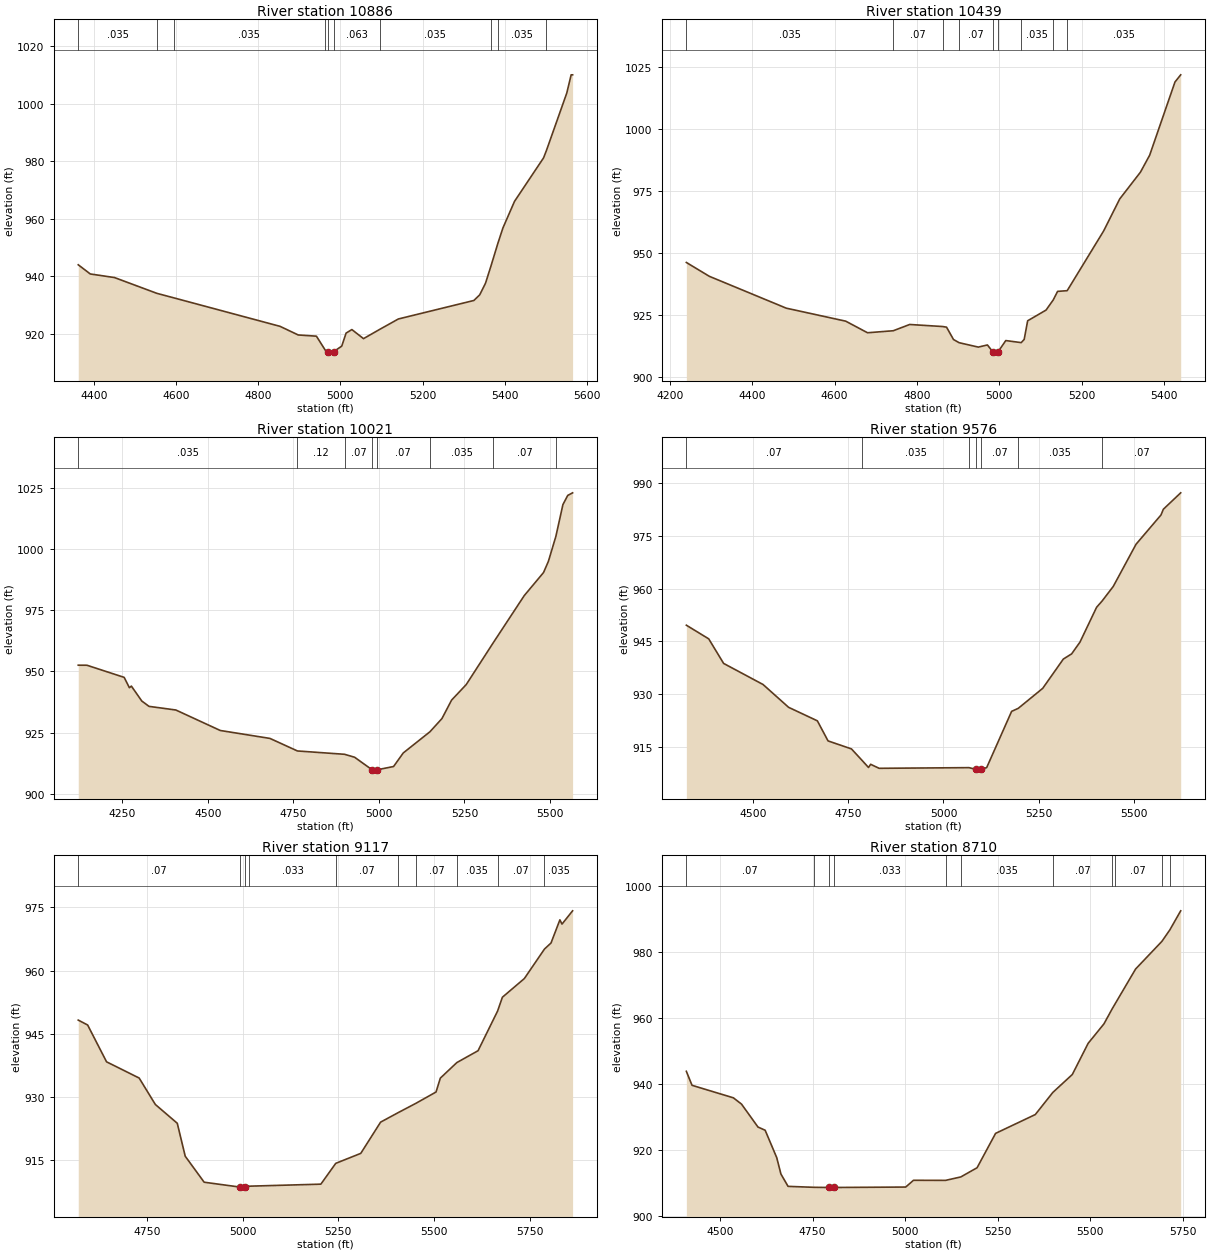
Type RM Length L Ch R = 1 ,10886   ,447,447,447
BEGIN DESCRIPTION:
Guadalupe Tributary 58 23.0
END DESCRIPTION:
XS GIS Cut Line= 3
      2188819.32     13884790.99        2188525.       13884225.
      2188125.02     13883825.02
#Sta/Elev= 30
  4361.8  944.06  4391.1  940.88  4450.1  939.63  4553.3  934.15  4593.7  932.62
  4853.2   922.7  4897.4  919.71  4941.7  919.29  4963.4  914.39    4971  913.91
  4971.5  913.41  4983.4  913.91  5003.3  915.83  5013.9  920.36    5028  921.58
  5056.3  918.44  5095.9  921.66  5141.2  925.26    5325  931.68  5339.2  933.63
  5353.3  937.65  5366.4  943.53  5383.8  951.65  5395.7  956.82    5424  966.08
  5494.7  981.16  5501.7  983.72  5551.3 1003.69  5561.9 1009.98  5565.4 1009.98
#Mann= 10 ,-1 , 0
  4361.8    .035       0  4553.3     .07       0  4593.7    .035       0
  4963.4    .063       0    4971     .05       0  4983.4    .063       0
  5095.9    .035       0  5366.4     .12       0  5383.8    .035       0
  5501.7     .12       0
Bank Sta=4971,4983.4
XS Rating Curve= 0 ,0
Exp/Cntr=0.3,0.1

Type RM Length L Ch R = 1 ,10439   ,418,418,418
BEGIN DESCRIPTION:
Guadalupe Tributary 58 22.0
END DESCRIPTION:
XS GIS Cut Line= 3
      2189152.64     13884603.46        2188825.       13883925.
      2188625.02     13883525.04
#Sta/Elev= 30
  4240.1  946.27  4295.8   940.7  4482.7  927.86  4627.1  922.62  4680.1  917.95
  4742.7  918.76  4782.5  921.28  4862.5  920.46    4872  920.21    4889  915.21
  4902.6  913.94  4949.1  912.17  4971.3  913.03  4984.5  910.24    4985  909.74
    4997  910.24  5015.9   914.8  5053.3  913.97  5060.6  915.26    5069  922.77
  5113.7  927.09  5131.2  931.19  5141.7  934.62    5165   934.9  5253.5  958.95
  5292.6  971.86  5342.9  982.65  5365.3  989.48  5426.8 1018.99  5440.7 1021.88
#Mann= 9 ,-1 , 0
  4240.1    .035       0  4742.7     .07       0  4862.5    .035       0
  4902.6     .07       0  4984.5     .05       0    4997     .07       0
  5053.3    .035       0  5131.2     .07       0    5165    .035       0
Bank Sta=4984.5,4997
XS Rating Curve= 0 ,0
Exp/Cntr=0.3,0.1

Type RM Length L Ch R = 1 ,10021   ,445,445,445
BEGIN DESCRIPTION:
Guadalupe Tributary 58 21.0
END DESCRIPTION:
XS GIS Cut Line= 3
      2189652.62     13884513.15        2189175.       13883775.
      2188774.99     13883374.99
#Sta/Elev= 30
  4121.2  952.57  4146.6  952.55  4255.4   947.6  4270.6  943.39  4276.5  944.03
  4306.9  937.95    4328  935.77  4406.5  934.28  4536.4  925.92  4681.5  922.69
  4761.8  917.57  4899.5  916.21  4928.9  915.01  4980.6  909.84  4981.1  909.34
  4993.1  909.84  5042.8  911.22  5071.1  916.75  5149.2  925.41  5184.2  930.78
  5212.5  938.34    5255  944.62  5333.6   961.6  5424.7  980.95  5481.2  990.39
  5495.4  994.97  5517.2 1005.13  5537.8 1018.11  5551.9 1021.85  5566.1 1022.91
#Mann= 8 ,-1 , 0
  4121.2    .035       0  4761.8     .12       0  4899.5     .07       0
  4980.6     .05       0  4993.1     .07       0  5149.2    .035       0
  5333.6     .07       0  5517.2    .035       0
Bank Sta=4980.6,4993.1
XS Rating Curve= 0 ,0
Exp/Cntr=0.3,0.1

Type RM Length L Ch R = 1 ,9576    ,459,459,459
BEGIN DESCRIPTION:
Guadalupe Tributary 58 20.0
END DESCRIPTION:
XS GIS Cut Line= 3
      2190125.01     13883825.01        2189525.       13883525.
      2188975.03     13883225.02
#Sta/Elev= 30
  4325.2  949.63  4383.9  945.75    4423  938.77  4526.5  932.78  4593.5   926.3
    4669  922.46    4697  916.76  4758.5  914.48  4786.2  911.23  4803.2  909.21
  4808.8  910.11  4831.1  908.97    5067  909.16  5084.9  908.67  5085.4  908.17
  5097.9  908.67  5113.3  909.16  5178.8  925.15  5196.1     926  5260.4  931.69
  5314.5  940.01  5336.3  941.49  5358.2  944.83  5401.8  954.72  5416.3  956.51
  5445.5  960.64  5505.3  972.63  5570.8  980.95    5577  982.58  5622.5  987.24
#Mann= 7 ,-1 , 0
  4325.2     .07       0  4786.2    .035       0    5067     .07       0
  5084.9    .035       0  5097.9     .07       0  5196.1    .035       0
  5416.3     .07       0
Bank Sta=5084.9,5097.9
XS Rating Curve= 0 ,0
Exp/Cntr=0.3,0.1

Type RM Length L Ch R = 1 ,9117    ,407,407,407
BEGIN DESCRIPTION:
Guadalupe Tributary 58 19.0
END DESCRIPTION:
XS GIS Cut Line= 4
      2190107.11     13883747.17       2189831.5     13883417.37
      2189651.52     13883233.01      2189099.34     13882986.63
#Sta/Elev= 30
  4570.2  948.24  4594.7  947.08  4644.2  938.33  4729.4  934.48  4771.7   928.2
    4829  923.74  4849.8  915.91  4899.3  909.74  4991.8   908.6  4992.3   908.1
  5004.8   908.6  5017.1   908.8  5204.3  909.28  5243.2  914.22  5308.6  916.59
  5360.5  924.01  5406.7  926.28  5453.2   928.5  5505.3  931.16  5516.6  934.46
  5559.7  938.15  5615.2  940.97  5666.2  950.38  5678.8  953.67  5736.2  958.11
  5788.8  965.11  5805.9  966.55  5829.1  972.05  5834.6  971.04  5862.3  974.19
#Mann= 10 ,-1 , 0
  4570.2     .07       0  4991.8     .05       0  5004.8     .07       0
  5017.1    .033       0  5243.2     .07       0  5406.7    .035       0
  5453.2     .07       0  5559.7    .035       0  5666.2     .07       0
  5788.8    .035       0
Bank Sta=4991.8,5004.8
XS Rating Curve= 0 ,0
Exp/Cntr=0.3,0.1

Type RM Length L Ch R = 1 ,8710    ,237,237,237
BEGIN DESCRIPTION:
Guadalupe Tributary 58 18.0
END DESCRIPTION:
XS GIS Cut Line= 3
        2190125.     13883624.99        2189925.       13883075.
      2189475.02     13882475.02
#Sta/Elev= 30
  4409.1  943.87  4424.4  939.62  4536.1  935.82  4558.1  933.91  4602.6  926.94
  4621.9  925.98  4653.2  917.66  4664.5  912.68  4683.8  908.93  4753.5  908.64
  4794.2  908.59  4794.7  908.09  4807.4  908.59  5001.6  908.72  5022.5  910.77
  5109.3  910.75  5150.3  911.79  5194.3  914.58  5244.3  925.02  5351.6  930.74
    5399  937.46  5451.6  942.91  5494.3  952.36    5537  958.28  5559.7  962.94
  5565.7  964.08  5622.5  974.94  5693.5  983.33  5714.8  986.79  5744.3  992.61
#Mann= 11 ,-1 , 0
  4409.1     .07       0  4753.5    .033       0  4794.2    .033       0
  4807.4    .033       0  5109.3     .07       0  5150.3    .035       0
    5399     .07       0  5559.7    .035       0  5565.7     .07       0
  5693.5    .035       0  5714.8     .07       0
Bank Sta=4794.2,4807.4
XS Rating Curve= 0 ,0
Exp/Cntr=0.3,0.1

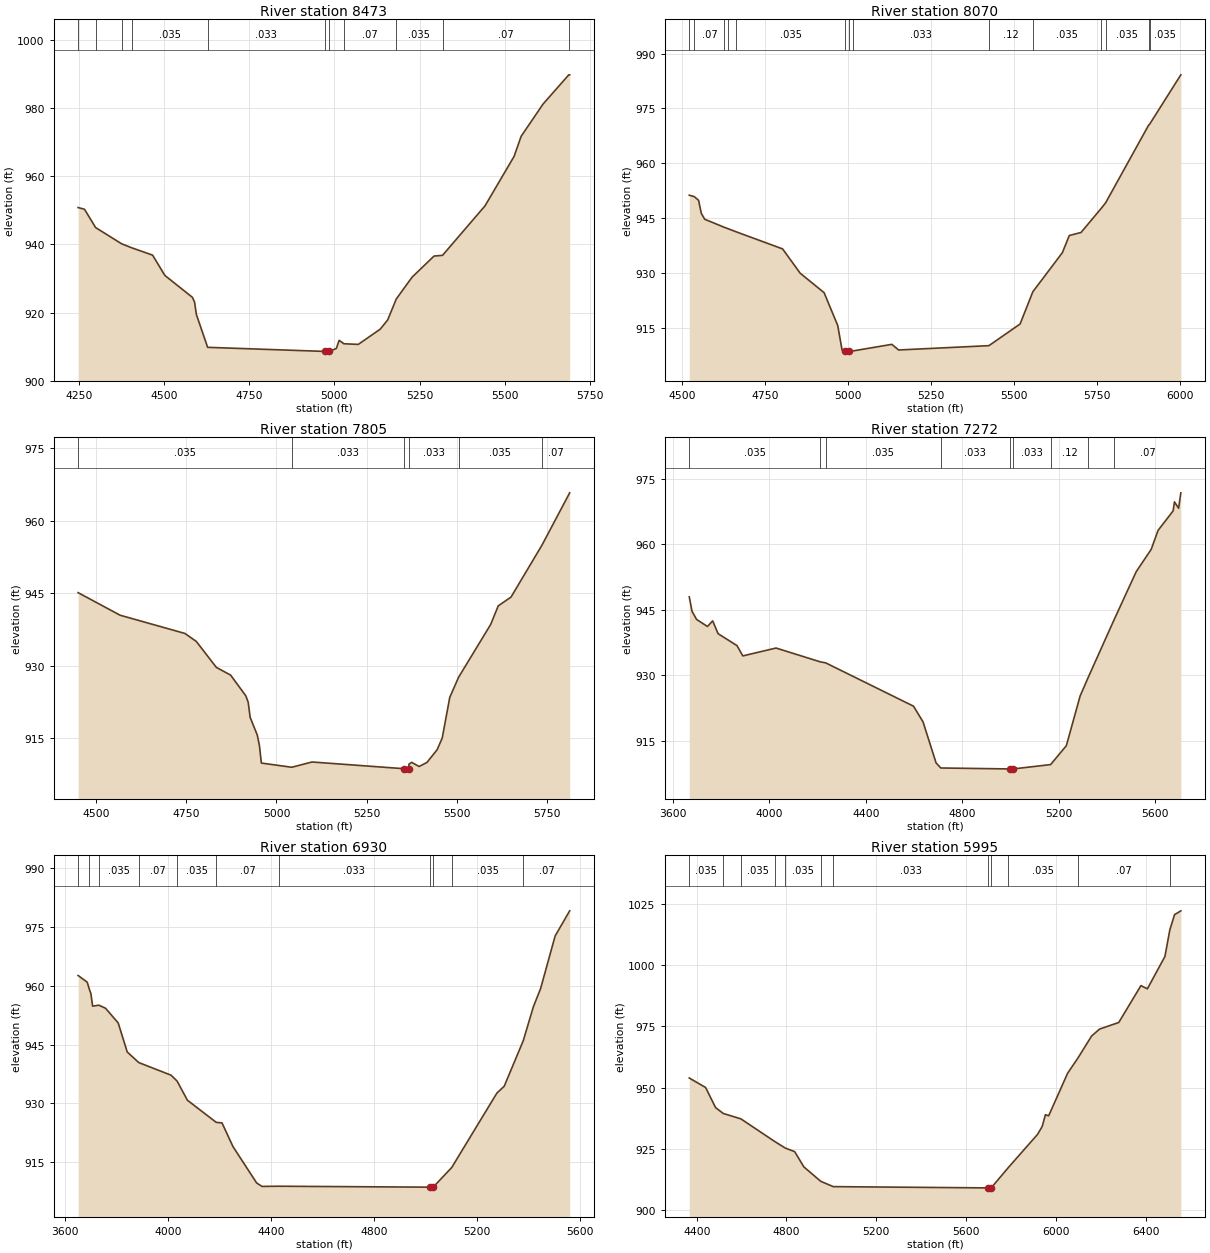
Type RM Length L Ch R = 1 ,8473    ,403,403,403
BEGIN DESCRIPTION:
Guadalupe Tributary 58 17.0
END DESCRIPTION:
XS GIS Cut Line= 3
      2190295.05     13883571.08      2190058.52     13882907.01
      2189611.03     13882320.07
#Sta/Elev= 30
  4247.7  950.81  4266.4  950.31  4299.1  944.94  4375.1   940.2  4404.7  939.02
  4466.3  936.86  4502.4   930.9  4583.2  924.48  4589.6  923.05  4594.9  919.45
  4627.9  909.82    4972  908.62  4972.5  908.12  4985.2  908.62  5005.7  909.49
    5014  911.87  5027.9  910.87  5070.1  910.68  5134.6  915.15  5156.4  917.85
  5181.7     924  5228.1   930.4  5292.5  936.58  5317.5   936.8  5442.1   951.3
  5527.4  965.79  5548.2   971.7  5612.6  981.17  5688.1  989.73  5690.7  989.73
#Mann= 11 ,-1 , 0
  4247.7     .07       0  4299.1    .035       0  4375.1     .07       0
  4404.7    .035       0  4627.9    .033       0    4972    .033       0
  4985.2    .033       0  5027.9     .07       0  5181.7    .035       0
  5317.5     .07       0  5688.1    .035       0
Bank Sta=4972,4985.2
XS Rating Curve= 0 ,0
Exp/Cntr=0.3,0.1

Type RM Length L Ch R = 1 ,8070    ,265,265,265
BEGIN DESCRIPTION:
Guadalupe Tributary 58 16.5
END DESCRIPTION:
XS GIS Cut Line= 4
      2190375.81     13883540.26      2190265.16     13883074.32
      2190220.06     13882832.26      2189730.94     13882255.58
#Sta/Elev= 30
  4521.1  951.29  4536.3  950.89  4549.2  949.88  4557.3  946.35  4567.6  944.71
  4627.2  942.49  4638.1  942.12  4662.3  941.28  4802.4   936.6  4855.4  929.95
  4927.4  924.64  4968.5  915.66  4981.5  908.98  4990.5  908.61    4991  908.11
  5003.7  908.61  5015.1  908.72  5131.5  910.51  5151.9  908.97    5424  910.15
    5518  916.07  5556.4  924.88  5645.4  935.57  5666.3  940.26  5701.6  941.09
  5761.7   947.6  5775.7  949.19  5905.7  970.49    5908  970.64  6002.4  984.19
#Mann= 14 ,-1 , 0
  4521.1    .035       0  4536.3     .07       0  4627.2    .035       0
  4638.1     .07       0  4662.3    .035       0  4990.5    .035       0
  5003.7    .035       0  5015.1    .033       0    5424     .12       0
  5556.4    .035       0  5761.7     .07       0  5775.7    .035       0
  5905.7     .07       0    5908    .035       0
Bank Sta=4990.5,5003.7
XS Rating Curve= 0 ,0
Exp/Cntr=0.3,0.1

Type RM Length L Ch R = 1 ,7805    ,533,533,533
BEGIN DESCRIPTION:
Guadalupe Tributary 58 16.0
END DESCRIPTION:
XS GIS Cut Line= 3
      2190604.03     13883395.11        2190425.       13882875.
        2189875.       13882275.
#Sta/Elev= 30
  4449.7  945.11  4566.2  940.44  4745.9  936.67  4777.7  935.01  4833.3  929.64
  4872.8  928.05  4915.2  923.74  4921.7  922.41    4927  919.32  4946.9  915.63
  4952.9  913.41  4958.2  909.84  5042.6  908.97  5098.7  910.06  5354.2  908.67
  5354.7  908.17  5367.4  908.67  5367.6  909.59    5375  909.99  5395.9  909.13
  5417.5  909.96  5445.9   912.6  5460.1  915.04    5481  923.45  5505.4  927.59
  5594.5  938.53  5615.5  942.38  5650.9  944.19  5736.9  954.95  5813.7  965.77
#Mann= 6 ,-1 , 0
  4449.7    .035       0  5042.6    .033       0  5354.2    .035       0
  5367.4    .033       0  5505.4    .035       0  5736.9     .07       0
Bank Sta=5354.2,5367.4
XS Rating Curve= 0 ,0
Exp/Cntr=0.3,0.1

Type RM Length L Ch R = 1 ,7272    ,342,342,342
BEGIN DESCRIPTION:
Guadalupe Tributary 58 15.0
END DESCRIPTION:
XS GIS Cut Line= 3
      2191062.36     13883645.11      2190602.62     13882487.97
      2189888.25     13882147.67
#Sta/Elev= 30
  3668.9  947.95  3680.2  944.69  3699.1   942.8  3744.3  941.18  3765.9  942.47
  3788.2  939.54  3866.5  936.81  3890.8  934.45  4028.4  936.25  4211.6  933.09
  4234.2  932.85    4598  922.94  4637.5  919.33  4691.3  909.97    4711   908.8
  4997.3  908.58  4997.8  908.08  5010.6  908.58  5165.8  909.58    5231   913.9
    5288  925.26  5321.9  929.57  5430.2  942.89  5520.6  953.74  5582.6  958.84
  5610.8  963.16  5673.4  967.64  5678.9   969.7  5696.1  968.24  5705.3  971.77
#Mann= 9 ,-1 , 0
  3668.9    .035       0  4211.6     .07       0  4234.2    .035       0
    4711    .033       0  4997.3    .033       0  5010.6    .033       0
  5165.8     .12       0  5321.9    .035       0  5430.2     .07       0
Bank Sta=4997.3,5010.6
XS Rating Curve= 0 ,0
Exp/Cntr=0.3,0.1

Type RM Length L Ch R = 1 ,6930    ,935,935,935
BEGIN DESCRIPTION:
Guadalupe Tributary 58 14.0
END DESCRIPTION:
XS GIS Cut Line= 3
      2191674.99     13883124.99        2190675.       13882225.
      2190275.02     13881825.02
#Sta/Elev= 30
  3649.6  962.68  3685.1  960.96  3692.9  959.24  3699.3  958.05    3706  954.85
  3730.1   955.1  3756.1  954.32  3805.4  950.57  3840.6  943.14  3885.3  940.45
    4011  937.22  4034.4  935.72  4074.5  930.83  4186.5  925.18    4209  925.04
  4251.6     919  4343.6  909.71  4364.5  908.82  4428.8  908.87  5016.6  908.63
  5017.1  908.13  5029.9  908.63  5102.2  913.67  5277.8  932.67  5306.1   934.4
  5380.4  946.07  5419.2  954.65  5447.5  959.33  5504.1  972.78  5560.6  979.19
#Mann= 11 ,-1 , 0
  3649.6    .035       0  3692.9     .07       0  3730.1    .035       0
  3885.3     .07       0  4034.4    .035       0  4186.5     .07       0
  4428.8    .033       0  5016.6    .033       0  5029.9    .033       0
  5102.2    .035       0  5380.4     .07       0
Bank Sta=5016.6,5029.9
XS Rating Curve= 0 ,0
Exp/Cntr=0.3,0.1

Type RM Length L Ch R = 1 ,5995    ,429,429,429
BEGIN DESCRIPTION:
Guadalupe Tributary 58 13.0
END DESCRIPTION:
XS GIS Cut Line= 3
      2191722.08     13882978.44        2191425.       13882425.
      2190224.99     13881424.99
#Sta/Elev= 30
  4366.9  953.91  4439.7  950.02  4484.3  941.77  4518.5  939.39  4596.7  937.19
  4748.1  927.89  4794.5  925.24  4836.5  923.77  4877.3  917.54  4952.6  911.62
  5008.6  909.44  5698.3  908.92  5698.8  908.42    5712  908.92  5788.2  917.22
  5918.6  930.82  5939.4  934.07  5953.7  938.87  5968.1  938.42  6052.7  955.87
    6098  961.99  6159.4  971.08  6194.6  973.91  6280.5  976.64  6379.4  991.73
    6408  990.41  6486.1 1003.64  6508.1 1014.56  6529.1 1020.77  6557.1 1022.34
#Mann= 12 ,-1 , 0
  4366.9    .035       0  4518.5     .07       0  4596.7    .035       0
  4748.1     .07       0  4794.5    .035       0  4952.6     .07       0
  5008.6    .033       0  5698.3     .05       0    5712    .033       0
  5788.2    .035       0    6098     .07       0  6508.1     .12       0
Bank Sta=5698.3,5712
XS Rating Curve= 0 ,0
Exp/Cntr=0.3,0.1

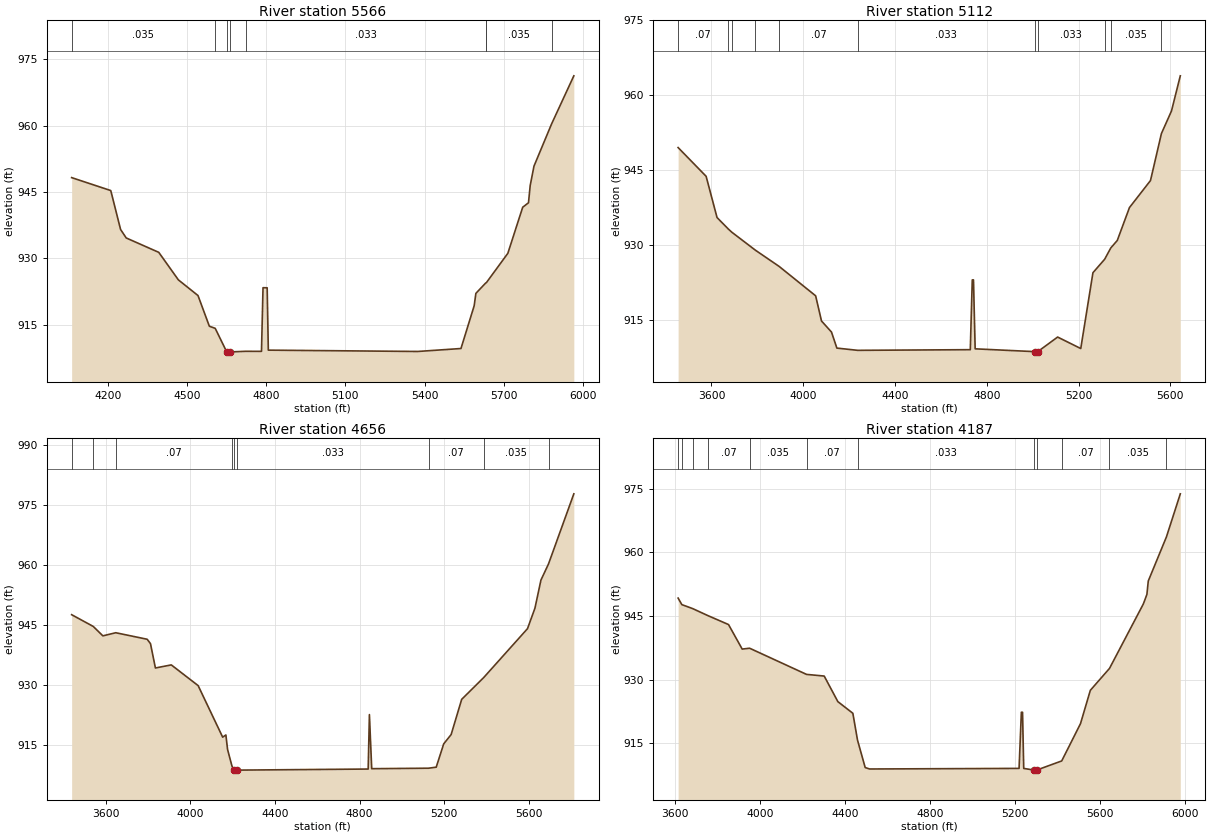
Type RM Length L Ch R = 1 ,5566    ,454,454,454
BEGIN DESCRIPTION:
Guadalupe Tributary 58 12.0
END DESCRIPTION:
XS GIS Cut Line= 4
      2192034.61     13882888.22      2191656.99     13882242.41
        2191475.       13882175.      2190735.96     13881561.78
#Sta/Elev= 30
    4063  948.25  4211.2  945.32  4248.4  936.52  4269.8   934.6    4393  931.35
  4467.4  925.12  4541.7  921.58  4584.7  914.64  4606.9  914.16  4650.5  908.83
    4651  908.33  4664.6  908.83  4722.1  908.97  4782.2  908.96    4788  923.35
  4803.7  923.33  4808.1  909.23  5374.4  908.93  5537.9   909.6  5587.9  919.26
  5594.4  922.07  5631.7  924.42    5634  924.48  5715.5  931.13  5771.8  941.55
  5793.7  942.56  5800.2  946.47  5814.5  950.84  5881.5  960.43  5965.5  971.27
#Mann= 8 ,-1 , 0
    4063    .035       0  4606.9     .07       0  4650.5    .033       0
  4664.6     .07       0  4722.1    .033       0  5631.7     .07       0
    5634    .035       0  5881.5     .07       0
Bank Sta=4650.5,4664.6
XS Rating Curve= 0 ,0
Exp/Cntr=0.3,0.1

Type RM Length L Ch R = 1 ,5112    ,456,456,456
BEGIN DESCRIPTION:
Guadalupe Tributary 58 11.0
END DESCRIPTION:
XS GIS Cut Line= 3
       2192874.9     13882290.97        2191425.       13881775.
      2190824.97     13881524.99
#Sta/Elev= 30
  3454.7  949.49  3576.8  943.73  3624.4  935.47  3673.8  933.16  3688.1  932.56
  3791.6  928.93  3895.1  925.68  4054.2  919.79  4079.7  914.75  4123.3  912.53
  4146.7  909.32  4237.2  908.87  4728.3     909  4736.9  922.98  4742.2  922.98
  4749.5  909.17  5008.3  908.61  5008.8  908.11  5022.4  908.61    5109  911.53
  5209.8  909.23  5262.9  924.42  5313.9  927.11  5340.7  929.38    5369  930.88
  5422.1  937.47  5513.7  942.88  5561.4   952.3  5605.2  956.81  5643.7  963.86
#Mann= 11 ,-1 , 0
  3454.7     .07       0  3673.8     .12       0  3688.1     .07       0
  3791.6    .035       0  3895.1     .07       0  4237.2    .033       0
  5008.3    .033       0  5022.4    .033       0  5313.9     .07       0
  5340.7    .035       0  5561.4     .07       0
Bank Sta=5008.3,5022.4
XS Rating Curve= 0 ,0
Exp/Cntr=0.3,0.1

Type RM Length L Ch R = 1 ,4656    ,469,469,469
BEGIN DESCRIPTION:
Guadalupe Tributary 58 10.0
END DESCRIPTION:
XS GIS Cut Line= 3
      2192951.27      13882061.8        2191525.       13881425.
      2190925.01     13880875.01
#Sta/Elev= 30
    3438  947.61  3540.3  944.67  3585.7  942.32  3646.7   943.1  3795.3  941.47
    3811  940.37  3834.3  934.29  3909.4  935.06  4036.4  929.89  4152.5     917
  4167.7  917.55  4175.7  913.91  4196.3  909.81  4204.4  908.76  4204.9  908.26
  4218.6  908.76  4840.9  909.03  4846.7  922.64  4857.6  909.12  5126.7  909.24
  5162.8   909.5  5198.2  915.32  5233.4  917.65  5283.3  926.45  5387.7  931.91
  5594.7  944.12  5629.9  949.24  5658.2  956.25  5694.1   960.3  5813.9  977.82
#Mann= 9 ,-1 , 0
    3438     .07       0  3540.3     .12       0  3646.7     .07       0
  4196.3    .033       0  4204.4    .033       0  4218.6    .033       0
  5126.7     .07       0  5387.7    .035       0  5694.1     .07       0
Bank Sta=4204.4,4218.6
XS Rating Curve= 0 ,0
Exp/Cntr=0.3,0.1

Type RM Length L Ch R = 1 ,4187    ,441,441,441
BEGIN DESCRIPTION:
Guadalupe Tributary 58 9.0
END DESCRIPTION:
XS GIS Cut Line= 3
      2192972.11     13881971.53        2191875.       13881125.
      2190981.25     13880729.44
#Sta/Elev= 30
  3614.3  949.21  3631.8  947.67  3682.4  946.74  3753.5   945.1  3851.5  942.97
  3915.8  937.19  3950.8  937.39  4218.6  931.22  4301.7  930.83    4366   924.8
  4436.6  922.05  4458.5  915.73  4494.6  909.26  4515.4  908.92  5218.7  909.06
  5229.5   922.3    5235  922.29  5240.6  909.05  5288.2  908.68  5288.7  908.18
  5302.4  908.68  5419.4  910.82  5507.6  919.59  5554.1  927.47  5644.2  932.63
  5803.4  947.82  5820.2  950.07  5826.7  953.24  5912.1  963.63  5977.4  973.79
#Mann= 12 ,-1 , 0
  3614.3    .035       0  3631.8     .07       0  3682.4    .035       0
  3753.5     .07       0  3950.8    .035       0  4218.6     .07       0
  4458.5    .033       0  5288.2    .033       0  5302.4    .033       0
  5419.4     .07       0  5644.2    .035       0  5912.1     .07       0
Bank Sta=5288.2,5302.4
XS Rating Curve= 0 ,0
Exp/Cntr=0.3,0.1