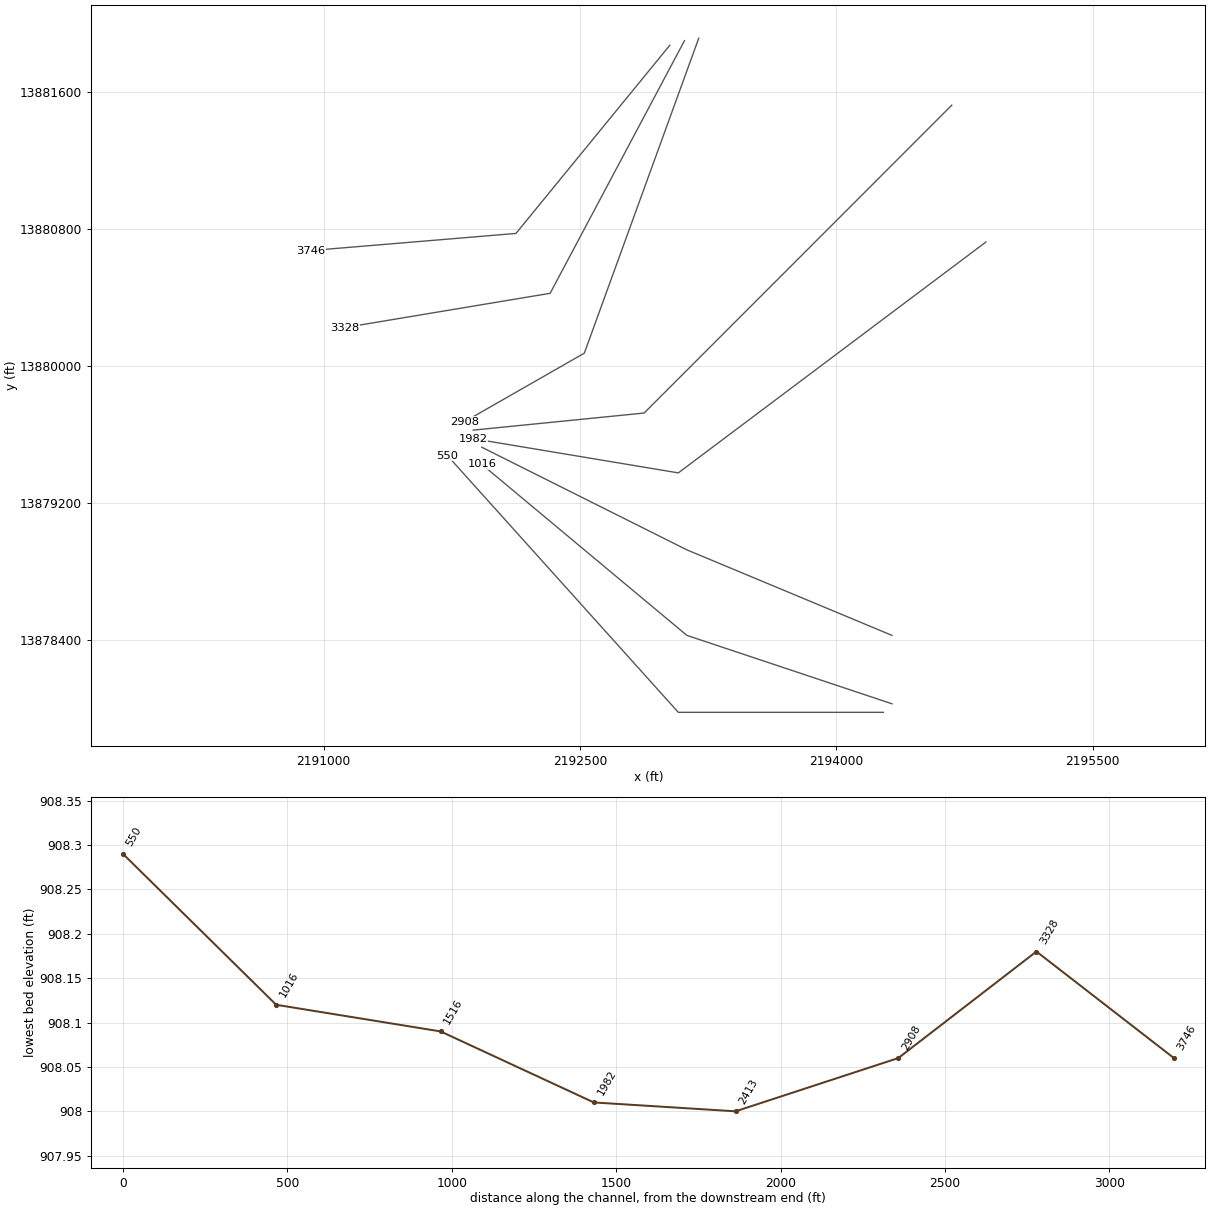
HEC-RAS study Guadalupe Tributary 58.prj: Guadalupe Tributary 58 Base Level Engineering

--- Guadalupe Tributary 58.g01 (geometry) --- (continued)

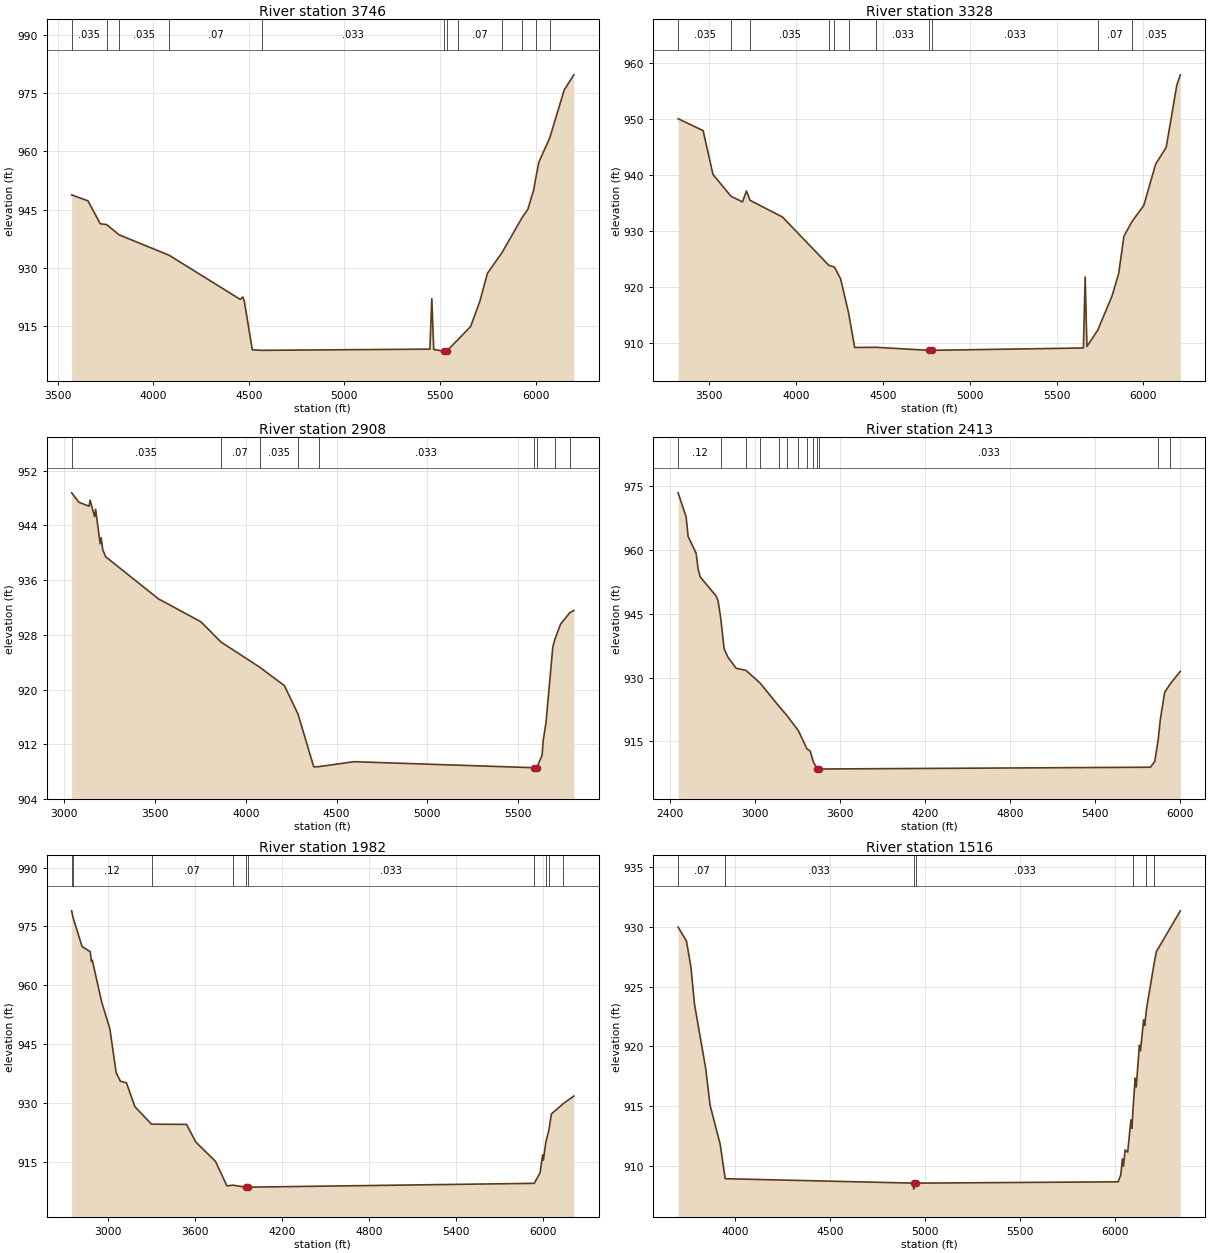
Type RM Length L Ch R = 1 ,3746    ,418,418,418
BEGIN DESCRIPTION:
Guadalupe Tributary 58 8.0
END DESCRIPTION:
XS GIS Cut Line= 3
        2193025.     13881875.01        2192125.       13880775.
      2190925.03       13880675.
#Sta/Elev= 30
  3573.9   948.8  3659.3  947.26  3723.2  941.37  3757.5  941.14  3821.7  938.52
  4083.4  933.26  4454.7  921.91    4469  922.52  4476.9  921.34  4518.5  908.91
  4568.2  908.78  5446.7  909.09  5456.8  922.08  5466.8  909.01  5519.9  908.56
  5520.4  908.06  5534.1  908.56  5594.8   911.6    5660  914.93  5707.6  921.36
  5747.8  928.62  5823.7  933.93  5928.5  942.91  5958.5  945.04  5988.6  949.95
  6001.3  953.35  6016.2   957.2  6073.2  963.45  6149.2  975.83  6199.3   979.7
#Mann= 12 ,-1 , 0
  3573.9    .035       0  3757.5     .07       0  3821.7    .035       0
  4083.4     .07       0  4568.2    .033       0  5519.9    .033       0
  5534.1    .033       0  5594.8     .07       0  5823.7    .035       0
  5928.5     .07       0  6001.3    .035       0  6073.2     .07       0
Bank Sta=5519.9,5534.1
XS Rating Curve= 0 ,0
Exp/Cntr=0.3,0.1

Type RM Length L Ch R = 1 ,3328    ,420,420,420
BEGIN DESCRIPTION:
Guadalupe Tributary 58 7.0
END DESCRIPTION:
XS GIS Cut Line= 3
      2193110.96     13881902.05        2192325.       13880425.
        2191125.       13880225.
#Sta/Elev= 30
  3322.4  950.06  3466.3  947.93    3523  940.11  3626.5  936.21  3692.9   935.2
  3715.5  937.14  3736.6  935.48  3922.8   932.5  4189.6  923.87    4222  923.55
  4257.4  921.46  4302.9  915.42  4338.5  909.19  4460.5  909.22  4766.2  908.68
  4766.7  908.18  4780.5  908.68  5654.5   909.1  5664.6  921.77  5674.8  909.37
  5737.3  912.31  5819.3  918.39  5857.3  922.37  5887.7  929.06    5935  931.74
  6001.7  934.54  6070.2  941.94    6131  944.96  6191.8  956.02  6212.1   957.9
#Mann= 11 ,-1 , 0
  3322.4    .035       0  3626.5     .07       0  3736.6    .035       0
  4189.6     .07       0    4222    .035       0  4302.9     .07       0
  4460.5    .033       0  4766.2    .033       0  4780.5    .033       0
  5737.3     .07       0    5935    .035       0
Bank Sta=4766.2,4780.5
XS Rating Curve= 0 ,0
Exp/Cntr=0.3,0.1

Type RM Length L Ch R = 1 ,2908    ,495,495,495
BEGIN DESCRIPTION:
Guadalupe Tributary 58 6.0
END DESCRIPTION:
XS GIS Cut Line= 3
      2193194.32     13881915.99        2192525.       13880075.
      2191825.01     13879675.01
#Sta/Elev= 30
  3041.1  948.78  3081.2   947.4  3137.1  946.82  3142.4  947.71  3167.7  945.29
    3173  946.37  3198.3  941.32  3203.6  942.21  3212.4  940.45  3228.9  939.42
  3518.8  933.27  3752.9  929.91  3863.8  926.94  4075.5  923.29  4212.6  920.57
  4287.2  916.43  4374.1  908.69  4400.8  908.71  4595.7  909.44  5586.7  908.56
  5587.2  908.06    5601  908.56  5631.3  910.36  5637.1  912.47  5652.9  915.16
  5690.3  926.19  5701.4  927.32  5733.5  929.59  5783.9  931.24  5806.2  931.58
#Mann= 9 ,-1 , 0
  3041.1    .035       0  3863.8     .07       0  4075.5    .035       0
  4287.2     .07       0  4400.8    .033       0  5586.7    .033       0
    5601    .033       0  5701.4     .07       0  5783.9    .035       0
Bank Sta=5586.7,5601
XS Rating Curve= 0 ,0
Exp/Cntr=0.3,0.1

Type RM Length L Ch R = 1 ,2413    ,431,431,431
BEGIN DESCRIPTION:
Guadalupe Tributary 58 5.0
END DESCRIPTION:
XS GIS Cut Line= 3
      2194675.02     13881525.02        2192875.       13879725.
        2191875.       13879625.
#Sta/Elev= 30
  2454.4  973.49    2511  967.83  2525.1  963.25  2581.7  959.29  2595.9  955.56
    2610  953.74  2723.1  949.21  2737.3  948.02  2756.1  943.89  2779.7   936.8
    2808  934.74  2864.6  932.22  2934.4   931.7  3034.3  928.72  3169.6  923.17
  3221.2   921.2  3304.9  917.52  3364.7  913.27  3387.8  912.74  3411.2  910.15
  3437.2   908.5  3437.7     908  3451.5   908.5    5794  908.92  5824.1  910.26
  5848.4  915.36  5864.3  920.28  5894.5  926.54  5935.1  928.59    6005  931.48
#Mann= 13 ,-1 , 0
  2454.4     .12       0  2756.1     .07       0  2934.4    .035       0
  3034.3     .07       0  3169.6    .035       0  3221.2     .07       0
  3304.9    .035       0  3364.7     .07       0  3411.2    .033       0
  3437.2    .033       0  3451.5    .033       0  5848.4     .07       0
  5935.1    .035       0
Bank Sta=3437.2,3451.5
XS Rating Curve= 0 ,0
Exp/Cntr=0.3,0.1

Type RM Length L Ch R = 1 ,1982    ,466,466,466
BEGIN DESCRIPTION:
Guadalupe Tributary 58 4.0
END DESCRIPTION:
XS GIS Cut Line= 3
        2194875.       13880725.        2193075.       13879375.
      2191875.05     13879574.99
#Sta/Elev= 30
  2749.6  978.99  2758.1  977.44  2821.5  969.89  2877.7  968.57  2886.1  966.07
  2892.3  966.39  2956.9  955.73  3013.1  948.94  3056.9  937.73  3086.1  935.53
  3127.7  935.13  3186.1  929.05  3300.8  924.58  3542.3  924.52  3606.9  920.02
  3742.3   915.1  3821.5  908.83  3863.1  909.02  3949.7  908.51  3950.2  908.01
  3964.1  908.51  5942.7  909.49    5983  912.18  6000.7  916.73  6005.8   915.4
    6023  920.07  6043.1  922.93  6061.5  927.19  6143.5  929.83  6216.1  931.76
#Mann= 10 ,-1 , 0
  2749.6    .035       0  2758.1     .12       0  3300.8     .07       0
  3863.1    .033       0  3949.7    .033       0  3964.1    .033       0
  5942.7     .07       0    6023    .033       0  6043.1     .07       0
  6143.5    .035       0
Bank Sta=3949.7,3964.1
XS Rating Curve= 0 ,0
Exp/Cntr=0.3,0.1

Type RM Length L Ch R = 1 ,1516    ,500,500,500
BEGIN DESCRIPTION:
Guadalupe Tributary 58 3.0
END DESCRIPTION:
XS GIS Cut Line= 3
        2194325.       13878425.        2193125.       13878925.
      2191925.04     13879524.98
#Sta/Elev= 30
    3700  929.96  3743.9   928.8  3767.7  926.59  3786.1  923.53  3844.6  918.21
  3868.5  915.07  3921.5  911.82  3947.6  908.96  4938.2  908.59  4938.7  908.09
  4953.4  908.59  6014.6   908.7  6028.6  909.29    6037  910.61  6042.6     910
    6051  911.36  6064.9  911.18  6081.7  913.87  6087.3  913.17    6092  914.54
  6104.1  917.35  6109.7  916.61  6126.4   920.1    6132  919.64  6148.8  922.22
  6154.4  921.75  6163.7  923.12  6203.9  926.94  6215.9  927.92  6341.6  931.32
#Mann= 7 ,-1 , 0
    3700     .07       0  3947.6    .033       0  4938.2    .033       0
  4953.4    .033       0    6092    .035       0  6163.7     .07       0
  6203.9    .035       0
Bank Sta=4938.2,4953.4
XS Rating Curve= 0 ,0
Exp/Cntr=0.3,0.1

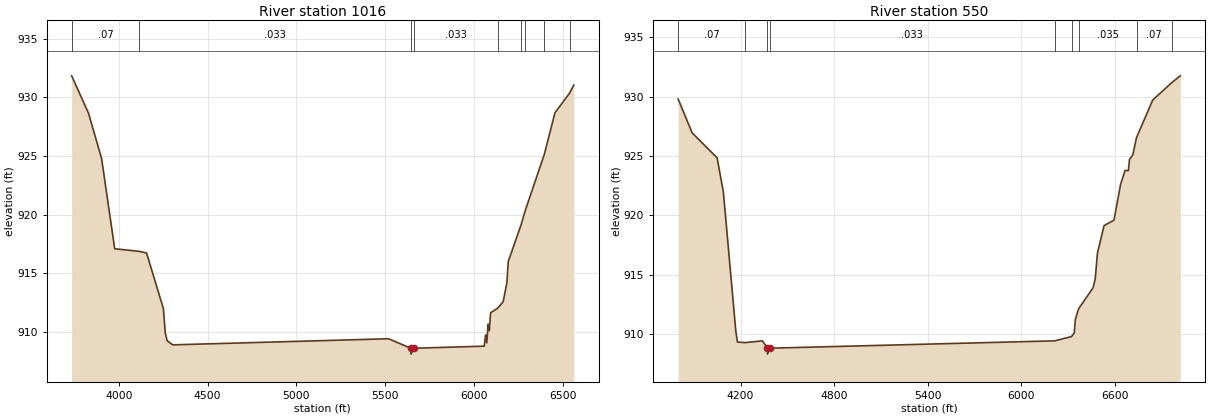
Type RM Length L Ch R = 1 ,1016    ,466,466,466
BEGIN DESCRIPTION:
Guadalupe Tributary 58 2.0
END DESCRIPTION:
XS GIS Cut Line= 3
        2194325.       13878025.        2193125.       13878425.
      2191924.97     13879425.03
#Sta/Elev= 30
  3735.1  931.84    3830  928.66  3903.8  924.78  3977.5   917.1  4115.4  916.88
  4156.7  916.74  4251.6     912  4262.1  909.94  4272.7  909.26  4304.3  908.91
  5518.7  909.43  5645.2  908.62  5645.7  908.12  5660.5  908.62  6057.6   908.8
  6065.5  909.76    6072  909.09  6079.8  910.68  6086.3  910.11  6093.4  911.64
  6132.8  912.03  6164.4  912.59  6185.2  914.22    6193  916.02  6264.4  919.11
    6289  920.38    6396  925.15    6456   928.7  6537.9  930.36  6562.1  931.05
#Mann= 9 ,-1 , 0
  3735.1     .07       0  4115.4    .033       0  5645.2    .033       0
  5660.5    .033       0  6132.8     .07       0  6264.4    .035       0
    6289     .07       0    6396    .035       0  6537.9     .07       0
Bank Sta=5645.2,5660.5
XS Rating Curve= 0 ,0
Exp/Cntr=0.3,0.1

Type RM Length L Ch R = 1 ,550     ,0,0,0
BEGIN DESCRIPTION:
Guadalupe Tributary 58 1.0
END DESCRIPTION:
XS GIS Cut Line= 3
      2194274.98       13877975.        2193075.       13877975.
      2191725.02     13879474.98
#Sta/Elev= 30
    3800  929.81    3890  926.95    4050  924.84    4090  921.96    4170  910.19
    4180  909.31  4228.7  909.26    4340  909.41  4372.3  908.79  4372.8  908.29
  4387.6  908.79  6213.7  909.41  6320.9  909.77  6338.2  910.07  6345.3  911.21
  6366.2  912.11  6458.6  913.88  6472.8  914.63    6487  916.81  6529.6  919.13
  6593.1  919.59  6635.7  922.63  6664.1  923.78  6685.1  923.77  6692.5  924.72
  6713.5  925.08  6737.3  926.55  6841.3  929.72  6965.1  931.21    7018  931.76
#Mann= 9 ,-1 , 0
    3800     .07       0  4228.7    .033       0  4372.3    .033       0
  4387.6    .033       0  6213.7    .035       0  6320.9     .07       0
  6366.2    .035       0  6737.3     .07       0  6965.1    .035       0
Bank Sta=4372.3,4387.6
XS Rating Curve= 0 ,0
Exp/Cntr=0.3,0.1

Chan Stop Cuts=-1
Use User Specified Reach Order=0
Composite Channel Slope=5