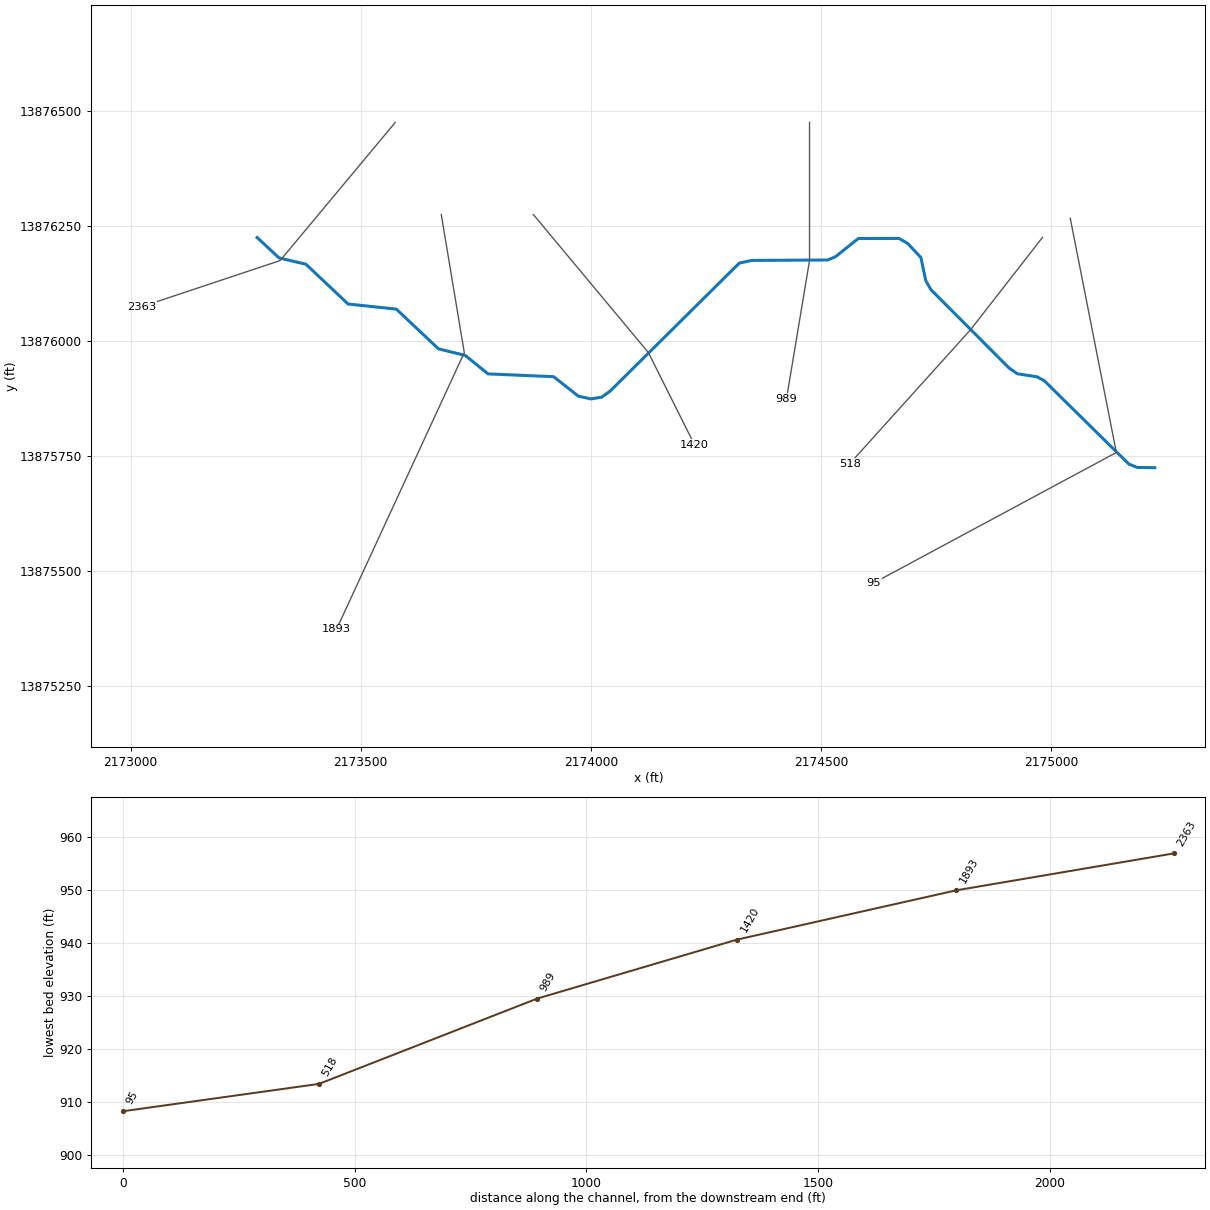
--- Guadalupe Tributary 61.prj (project) ---

Proj Title=Guadalupe Tributary 61 Base Level Engineering
Current Plan=p01
Default Exp/Contr=0.3,0.1
English Units
Geom File=g01
Flow File=f01
Plan File=p01
BEGIN DESCRIPTION:
Guadalupe Tributary 61
END DESCRIPTION:

--- Guadalupe Tributary 61.p01 (plan) ---

Plan Title=Multiple Run
Short Identifier=Multiple
Geom File=g01
Flow File=f01
Subcritical Flow
K Sum by GR= 0
Std Step Tol= 0.01
Critical Tol= 0.01
Num of Std Step Trials= 20
Max Error Tol= 0.3
Flow Tol Ratio= 0.001
Split Flow NTrial= 30
Split Flow Tol= 0.02
Split Flow Ratio= 0.02
Log Output Level= 0
Friction Slope Method= 1
Unsteady Friction Slope Method= 2
Unsteady Bridges Friction Slope Method= 1
Parabolic Critical Depth
Global Vel Dist=  1 , 1 , 1
Global Log Level= 0
CheckData=True
Encroach Param= -1, 0, 0, 0
BEGIN DESCRIPTION:
Multiple Run
END DESCRIPTION:

--- Guadalupe Tributary 61.f01 (steady flow) ---

Flow Title=Multiple
Number of Profiles=7
Profile Names=10-year,25-year,50-year,1pct_min,100-year,1pct_plu,500-year
River Rch & RM= Guadalupe Tribut,Reach-1,2363
     712    1184    1624    1082    2158    4306    3768
Boundary for River Rch & Prof#=Guadalupe Tribut,Reach-1,1
Up Type=0
Dn Type=3
Dn Slope=0.005
Boundary for River Rch & Prof#=Guadalupe Tribut,Reach-1,2
Up Type=0
Dn Type=3
Dn Slope=0.005
Boundary for River Rch & Prof#=Guadalupe Tribut,Reach-1,3
Up Type=0
Dn Type=3
Dn Slope=0.005
Boundary for River Rch & Prof#=Guadalupe Tribut,Reach-1,4
Up Type=0
Dn Type=3
Dn Slope=0.005
Boundary for River Rch & Prof#=Guadalupe Tribut,Reach-1,5
Up Type=0
Dn Type=3
Dn Slope=0.005
Boundary for River Rch & Prof#=Guadalupe Tribut,Reach-1,6
Up Type=0
Dn Type=3
Dn Slope=0.005
Boundary for River Rch & Prof#=Guadalupe Tribut,Reach-1,7
Up Type=0
Dn Type=3
Dn Slope=0.005

--- Guadalupe Tributary 61.g01 (geometry) ---

Geom Title=Existing Conditions

River Reach=Guadalupe Tribut,Reach-1
Reach XY= 30
      2173275.00     13876225.00      2173322.65     13876180.70
      2173381.08     13876166.93      2173472.58     13876080.54
      2173577.42     13876069.46      2173668.95     13875983.16
      2173727.17     13875968.86      2173776.56     13875928.76
      2173919.07     13875922.70      2173972.83     13875880.35
      2174000.04     13875874.50      2174023.37     13875878.13
      2174041.68     13875891.22      2174322.55     13876169.54
      2174349.88     13876175.29      2174514.50     13876176.22
      2174531.06     13876183.15      2174580.98     13876222.84
      2174669.29     13876223.11      2174688.65     13876211.81
      2174716.98     13876181.38      2174727.55     13876131.09
      2174738.64     13876111.80      2174908.33     13875941.65
      2174926.65     13875928.98      2174968.95     13875922.47
      2174984.68     13875914.22      2175168.79     13875732.76
      2175186.84     13875725.59      2175225.00     13875725.00

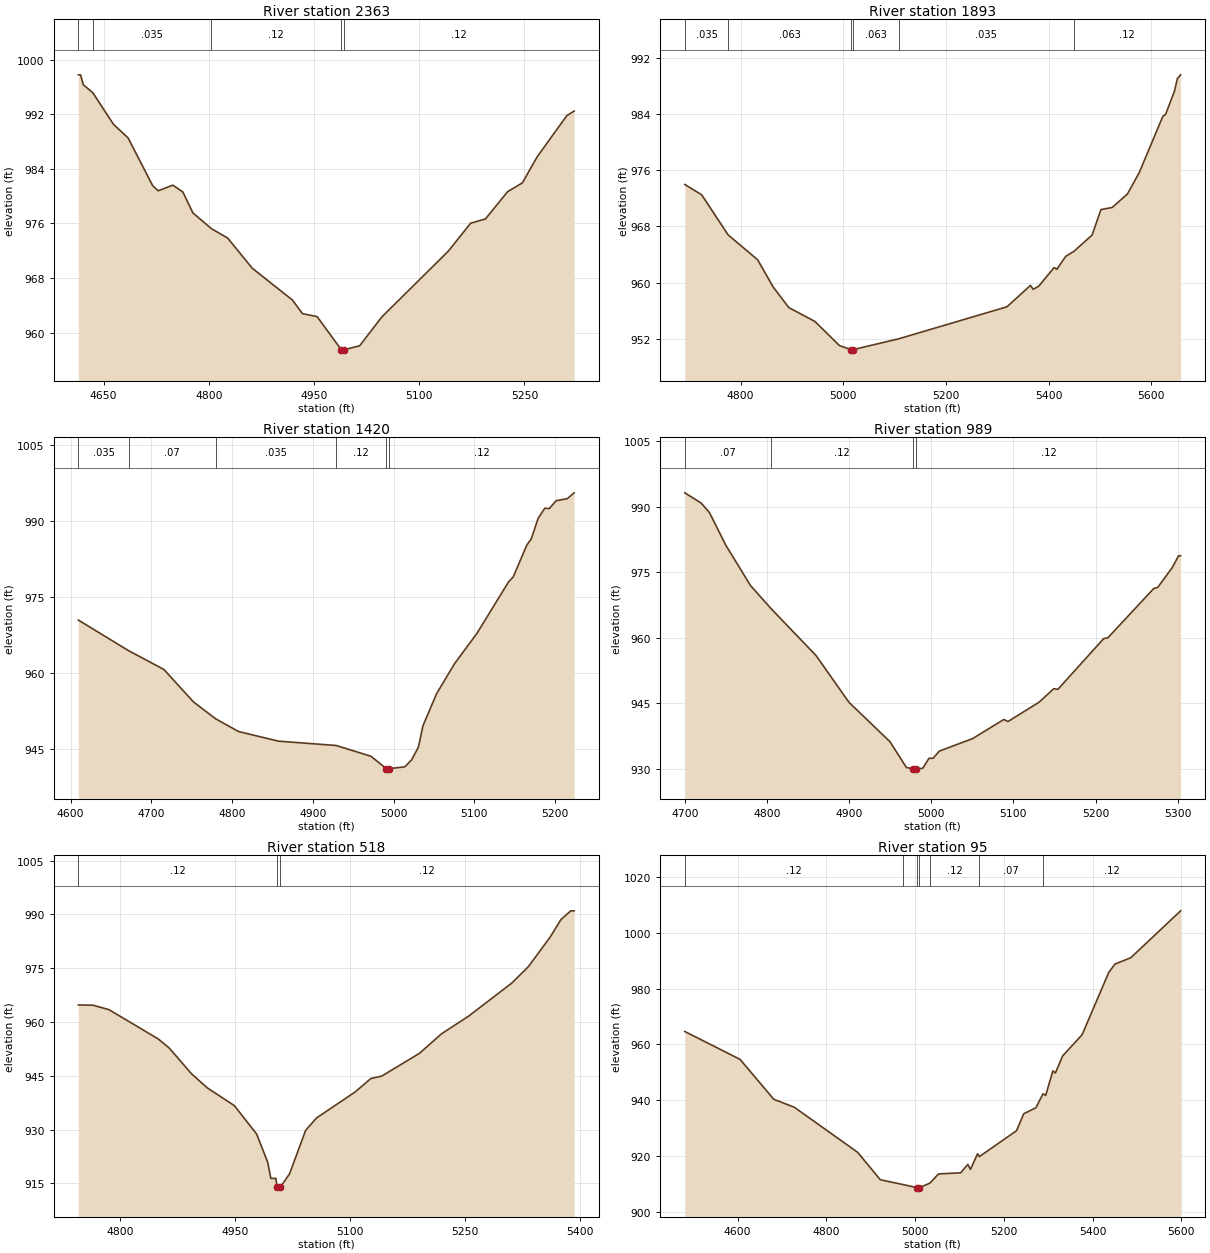
Type RM Length L Ch R = 1,2363,470,470,470
BEGIN DESCRIPTION:
Guadalupe Tributary 61 5.0
END DESCRIPTION:
XS GIS Cut Line= 3
      2173574.97     13876474.97      2173325.00     13876175.00
      2173025.00     13876075.00
#Sta/Elev= 30
  4614.1  997.79  4617.3  997.79  4621.2  996.34  4634.8  995.16  4664.2  990.53
  4685.0  988.54  4720.1  981.53  4728.0  980.79  4748.8  981.61  4763.1  980.61
  4777.4  977.54  4803.7  975.24  4826.9  973.86  4862.0  969.43  4919.3  964.76
  4933.6  962.77  4954.5  962.33  4988.9  957.48  4989.2  956.98  4992.9  957.48
  5015.1  958.06  5046.7  962.29  5141.6  971.95  5173.2  976.03  5194.3  976.65
  5225.9  980.65  5247.0  981.95  5268.1  985.77  5310.3  991.80  5320.8  992.48
#Mann=5,-1,0
  4614.1    0.12       0  4634.8   0.035       0  4803.7    0.12       0
  4988.9    0.05       0  4992.9    0.12       0
Bank Sta=4988.9,4992.9
Exp/Cntr=0.3,0.1

Type RM Length L Ch R = 1,1893,473,473,473
BEGIN DESCRIPTION:
Guadalupe Tributary 61 4.0
END DESCRIPTION:
XS GIS Cut Line= 3
      2173675.00     13876274.98      2173725.00     13875975.00
      2173447.48     13875374.00
#Sta/Elev= 30
  4691.3  973.96  4724.2  972.49  4775.8  966.79  4833.2  963.26  4863.6  959.38
  4894.0  956.46  4944.7  954.50  4992.9  951.05  5015.4  950.49  5015.7  949.99
  5019.4  950.49  5108.3  952.03  5318.9  956.57  5364.8  959.61  5370.3  959.06
  5380.9  959.50  5410.7  962.14  5416.2  961.91  5433.6  963.75  5449.4  964.45
  5485.0  966.78  5502.1  970.39  5524.1  970.69  5553.8  972.61  5576.8  975.65
  5622.6  983.62  5628.1  983.92  5645.3  987.19  5651.1  989.01  5657.4  989.54
#Mann=6,-1,0
  4691.3   0.035       0  4775.8   0.063       0  5015.4    0.05       0
  5019.4   0.063       0  5108.3   0.035       0  5449.4    0.12       0
Bank Sta=5015.4,5019.4
Exp/Cntr=0.3,0.1

Type RM Length L Ch R = 1,1420,431,431,431
BEGIN DESCRIPTION:
Guadalupe Tributary 61 3.0
END DESCRIPTION:
XS GIS Cut Line= 3
      2173875.03     13876274.96      2174125.00     13875975.00
      2174225.01     13875774.98
#Sta/Elev= 30
  4609.5  970.50  4671.8  964.45  4715.5  960.74  4752.0  954.35  4779.5  951.01
  4808.0  948.48  4857.4  946.59  4928.9  945.73  4972.0  943.60  4990.8  941.17
  4991.1  940.67  4994.6  940.67  4994.8  941.17  5013.9  941.52  5022.3  942.90
  5030.7  945.41  5036.3  949.61  5053.1  955.93  5075.4  961.87  5103.4  967.92
  5142.5  978.07  5148.1  979.00  5164.9  985.28  5170.5  986.54  5178.9  990.55
  5187.2  992.58  5192.8  992.51  5201.2  994.06  5215.2  994.48  5223.6  995.62
#Mann=6,-1,0
  4609.5   0.035       0  4671.8    0.07       0  4779.5   0.035       0
  4928.9    0.12       0  4990.8    0.05       0  4994.8    0.12       0
Bank Sta=4990.8,4994.8
Exp/Cntr=0.3,0.1

Type RM Length L Ch R = 1,989,471,471,471
BEGIN DESCRIPTION:
Guadalupe Tributary 61 2.0
END DESCRIPTION:
XS GIS Cut Line= 3
      2174475.00     13876475.00      2174475.00     13876175.00
      2174425.01     13875875.03
#Sta/Elev= 30
  4699.6  993.22  4719.6  990.87  4729.6  988.71  4749.6  981.22  4779.6  972.02
  4805.1  966.64  4859.6  955.96  4899.6  945.28  4949.6  936.25  4969.6  930.36
  4977.6  930.02  4977.8  929.52  4981.6  930.02  4989.6  930.18  4997.1  932.46
  5002.1  932.46  5009.7  934.10  5050.3  936.97  5088.3  941.34  5093.4  940.88
  5131.4  945.31  5149.1  948.39  5154.2  948.24  5210.0  959.86  5215.0  960.03
  5270.8  971.29  5275.9  971.59  5293.6  976.14  5301.2  978.82  5303.7  978.82
#Mann=4,-1,0
  4699.6    0.07       0  4805.1    0.12       0  4977.6    0.05       0
  4981.6    0.12       0
Bank Sta=4977.6,4981.6
Exp/Cntr=0.3,0.1

Type RM Length L Ch R = 1,518,423,423,423
BEGIN DESCRIPTION:
Guadalupe Tributary 61 1.0
END DESCRIPTION:
XS GIS Cut Line= 3
      2174981.38     13876225.63      2174825.00     13876025.00
      2174562.08     13875733.41
#Sta/Elev= 30
  4745.6  964.77  4764.8  964.69  4785.6  963.45  4849.8  955.29  4864.3  952.73
  4893.2  945.58  4914.0  941.61  4949.3  936.66  4978.3  928.74  4992.7  920.89
  4996.8  916.38  5003.3  916.38  5005.1  913.88  5005.3  913.38  5009.1  913.88
  5021.3  917.69  5042.2  929.77  5056.4  933.23  5106.5  940.44  5127.4  944.24
  5141.6  944.92  5190.9  951.29  5219.3  956.67  5255.2  961.69  5311.3  970.88
  5332.9  975.45  5361.3  983.70  5375.5  988.62  5388.2  991.02  5392.6  991.02
#Mann=3,-1,0
  4745.6    0.12       0  5005.1    0.05       0  5009.1    0.12       0
Bank Sta=5005.1,5009.1
Exp/Cntr=0.3,0.1

Type RM Length L Ch R = 1,95,0,0,0
BEGIN DESCRIPTION:
Guadalupe Tributary 61 0.1
END DESCRIPTION:
XS GIS Cut Line= 3
      2175041.32     13876267.06      2175141.54     13875758.03
      2174614.66     13875474.77
#Sta/Elev= 30
  4481.2  964.63  4605.6  954.67  4681.7  940.36  4727.9  937.52  4870.6  921.39
  4921.6  911.58  4971.8  909.88  5005.4  908.71  5005.7  908.21  5009.4  908.71
  5033.4  910.35  5052.8  913.65  5102.7  914.06  5118.9  917.07  5124.6  915.25
  5140.8  920.86  5144.8  919.84  5228.5  929.11  5244.7  935.18  5272.3  937.36
  5288.2  942.34  5294.2  941.75  5310.5  950.54  5316.1  949.77  5332.4  955.89
  5376.2  963.45  5436.3  985.77  5450.2  988.75  5485.8  991.01  5598.2 1007.82
#Mann=7,-1,0
  4481.2    0.12       0  4971.8   0.033       0  5005.4   0.033       0
  5009.4   0.033       0  5033.4    0.12       0  5144.8    0.07       0
  5288.2    0.12       0
Bank Sta=5005.4,5009.4
Exp/Cntr=0.3,0.1

Chan Stop Cuts=-1