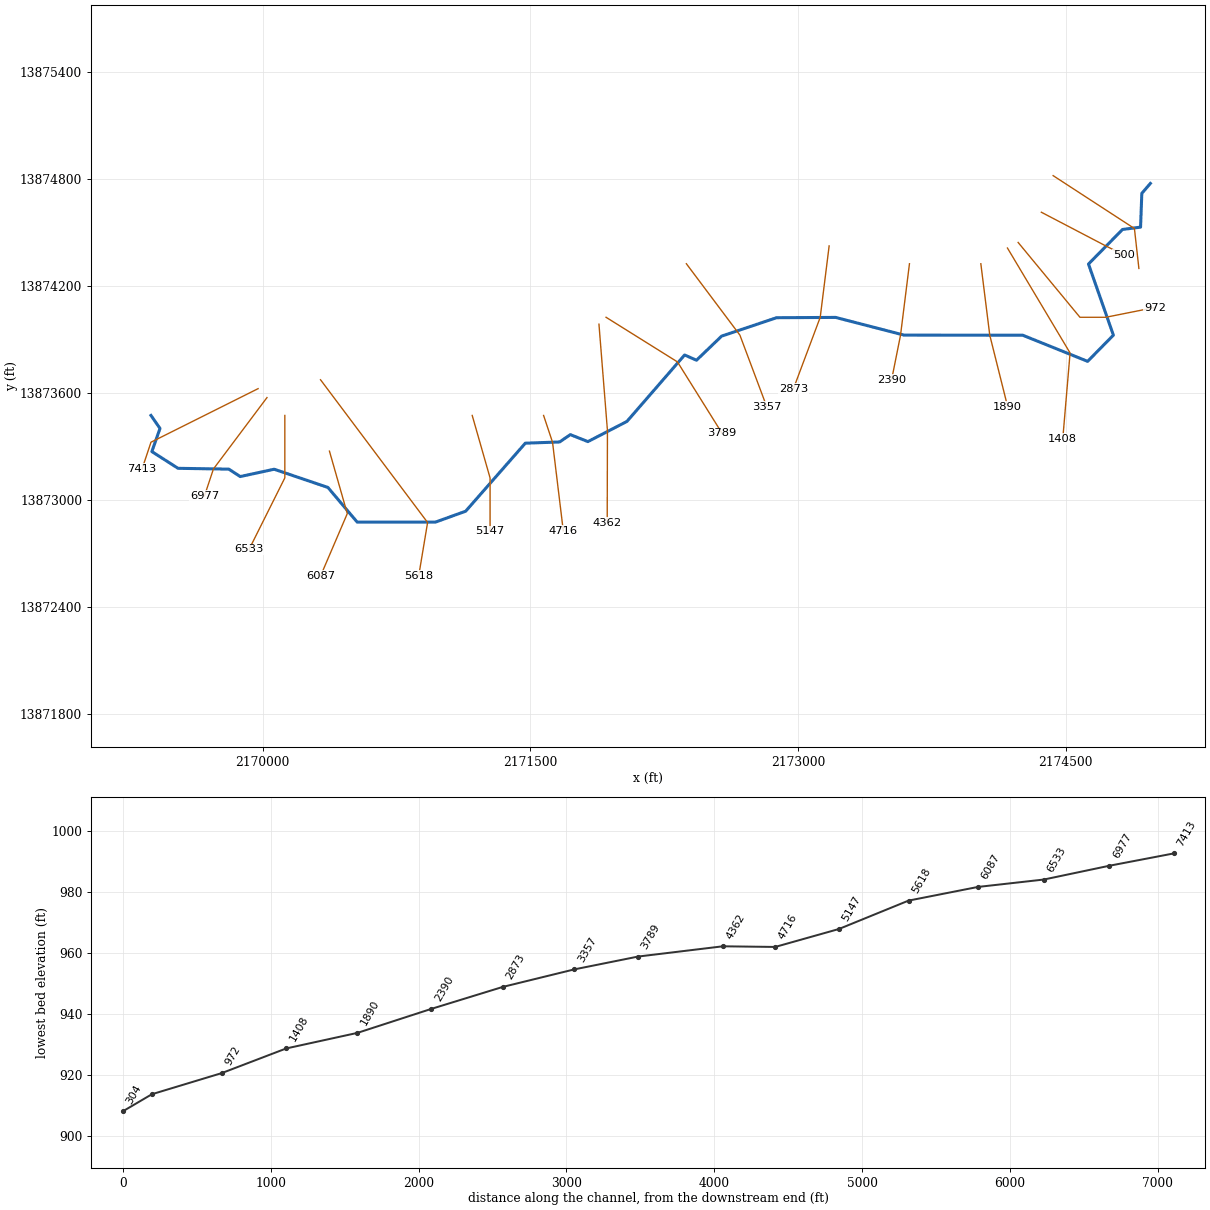
--- Guadalupe Tributary 62.prj (project) ---

Proj Title=Guadalupe Tributary 62 Base Level Engineering
Current Plan=p01
Default Exp/Contr=0.3,0.1
English Units
Geom File=g01
Flow File=f01
Plan File=p01
BEGIN DESCRIPTION:
Guadalupe Tributary 62
END DESCRIPTION:

--- Guadalupe Tributary 62.p01 (plan) ---

Plan Title=Multiple Run
Short Identifier=Multiple
Geom File=g01
Flow File=f01
Subcritical Flow
K Sum by GR= 0
Std Step Tol= 0.01
Critical Tol= 0.01
Num of Std Step Trials= 20
Max Error Tol= 0.3
Flow Tol Ratio= 0.001
Split Flow NTrial= 30
Split Flow Tol= 0.02
Split Flow Ratio= 0.02
Log Output Level= 0
Friction Slope Method= 1
Unsteady Friction Slope Method= 2
Unsteady Bridges Friction Slope Method= 1
Parabolic Critical Depth
Global Vel Dist=  1 , 1 , 1
Global Log Level= 0
CheckData=True
Encroach Param= -1, 0, 0, 0
BEGIN DESCRIPTION:
Multiple Run
END DESCRIPTION:

--- Guadalupe Tributary 62.f01 (steady flow) ---

Flow Title=Multiple
Number of Profiles=7
Profile Names=10-year,25-year,50-year,1pct_min,100-year,1pct_plu,500-year
River Rch & RM= Guadalupe Tribut,Reach-1,7413
    1302    2229    3118    2111    4211    8403    7607
Boundary for River Rch & Prof#=Guadalupe Tribut,Reach-1,1
Up Type=0
Dn Type=3
Dn Slope=0.005
Boundary for River Rch & Prof#=Guadalupe Tribut,Reach-1,2
Up Type=0
Dn Type=3
Dn Slope=0.005
Boundary for River Rch & Prof#=Guadalupe Tribut,Reach-1,3
Up Type=0
Dn Type=3
Dn Slope=0.005
Boundary for River Rch & Prof#=Guadalupe Tribut,Reach-1,4
Up Type=0
Dn Type=3
Dn Slope=0.005
Boundary for River Rch & Prof#=Guadalupe Tribut,Reach-1,5
Up Type=0
Dn Type=3
Dn Slope=0.005
Boundary for River Rch & Prof#=Guadalupe Tribut,Reach-1,6
Up Type=0
Dn Type=3
Dn Slope=0.005
Boundary for River Rch & Prof#=Guadalupe Tribut,Reach-1,7
Up Type=0
Dn Type=3
Dn Slope=0.005

--- Guadalupe Tributary 62.g01 (geometry) ---

Geom Title=Existing Conditions

River Reach=Guadalupe Tribut,Reach-1
Reach XY= 30
      2169375.00     13873475.00      2169425.60     13873402.14
      2169379.99     13873272.45      2169526.55     13873178.75
      2169811.14     13873174.17      2169875.00     13873132.56
      2170065.33     13873173.63      2170366.52     13873071.49
      2170530.44     13872877.17      2170969.06     13872877.26
      2171138.33     13872938.39      2171472.55     13873319.54
      2171664.56     13873326.38      2171725.01     13873367.41
      2171823.26     13873328.37      2172042.05     13873441.49
      2172365.00     13873813.76      2172431.67     13873784.30
      2172572.57     13873919.48      2172880.53     13874022.62
      2173211.08     13874024.32      2173595.03     13873925.07
      2174259.79     13873924.49      2174623.37     13873778.13
      2174767.69     13873924.90      2174628.13     13874323.37
      2174818.88     13874517.12      2174919.97     13874530.08
      2174927.00     13874719.63      2174975.00     13874775.00

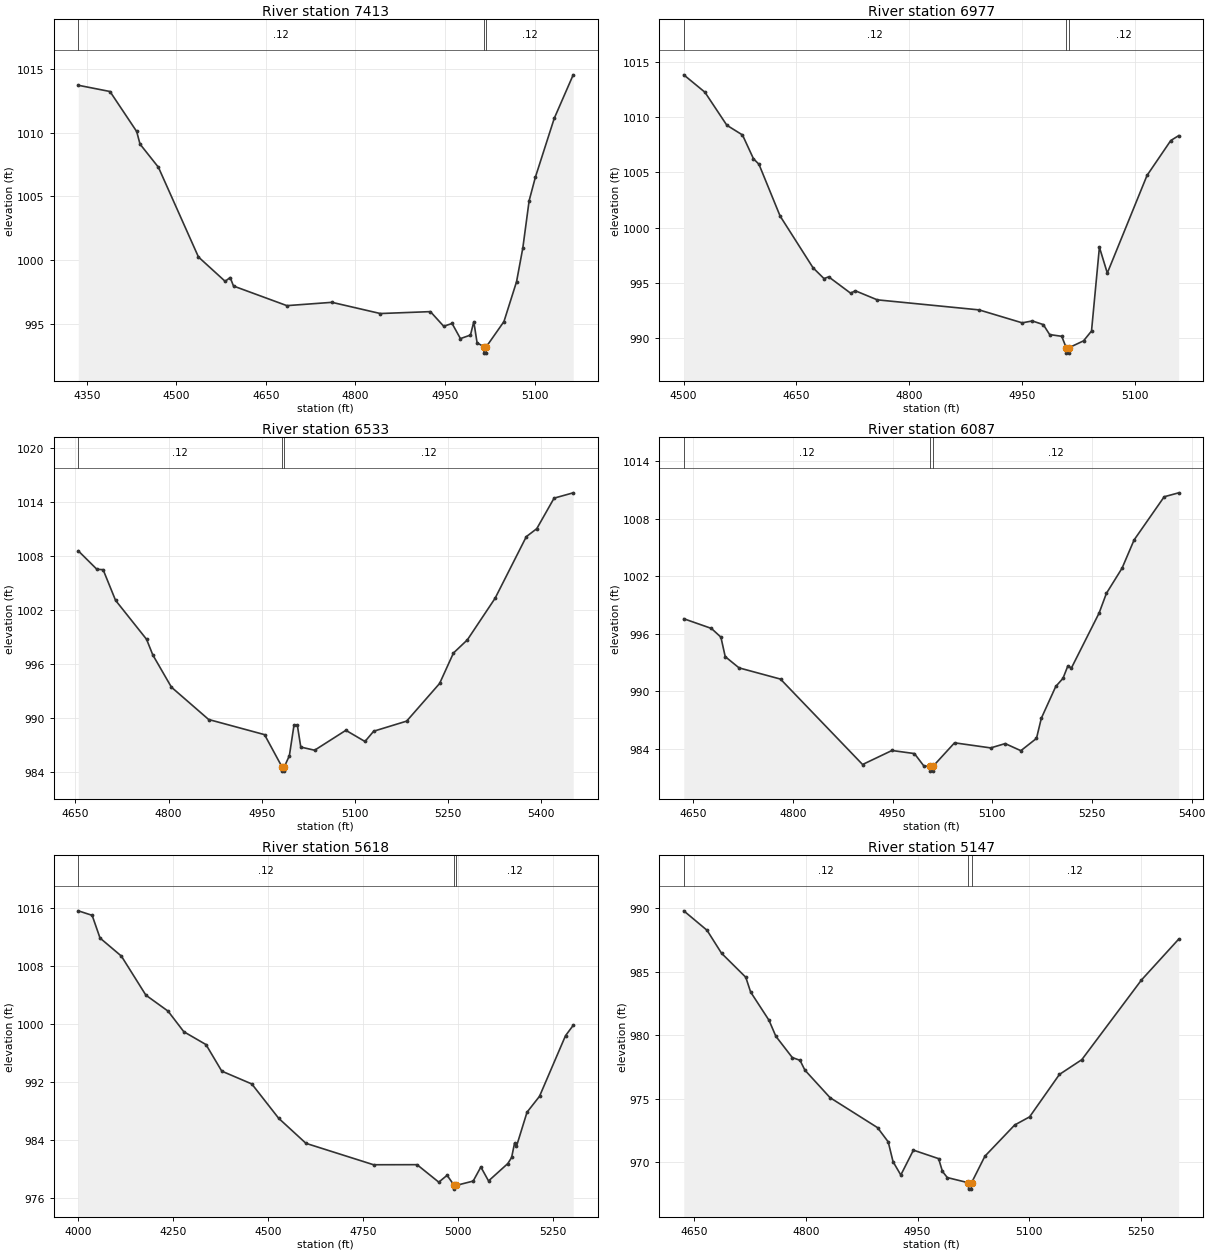
Type RM Length L Ch R = 1,7413,436,436,436
BEGIN DESCRIPTION:
Guadalupe Tributary 62 16.0
END DESCRIPTION:
XS GIS Cut Line= 3
      2169975.02     13873625.01      2169375.00     13873325.00
      2169324.99     13873174.96
#Sta/Elev= 30
  4335.7 1013.73  4388.8 1013.24  4433.5 1010.10  4439.1 1009.11  4469.9 1007.29
  4537.0 1000.24  4581.7  998.33  4590.1  998.63  4595.7  997.96  4685.1  996.42
  4760.6  996.68  4841.6  995.80  4925.5  995.95  4947.8  994.80  4961.8  995.02
  4975.8  993.83  4992.6  994.11  4998.2  995.16  5003.7  993.50  5015.1  993.19
  5015.3  992.69  5018.8  992.69  5019.1  993.19  5048.7  995.17  5069.8  998.30
  5080.3 1000.95  5090.9 1004.67  5101.4 1006.52  5133.0 1011.14  5164.7 1014.55
#Mann=3,-1,0
  4335.7    0.12       0  5015.1    0.05       0  5019.1    0.12       0
Bank Sta=5015.1,5019.1
Exp/Cntr=0.3,0.1

Type RM Length L Ch R = 1,6977,444,444,444
BEGIN DESCRIPTION:
Guadalupe Tributary 62 15.0
END DESCRIPTION:
XS GIS Cut Line= 3
      2170025.00     13873575.00      2169725.00     13873175.00
      2169675.00     13873025.01
#Sta/Elev= 30
  4500.1 1013.82  4528.2 1012.25  4557.4 1009.26  4578.2 1008.38  4592.8 1006.23
  4600.1 1005.73  4628.2 1001.05  4672.0  996.37  4686.6  995.39  4692.8  995.55
  4722.0  994.07  4728.2  994.29  4757.4  993.47  4892.8  992.56  4950.1  991.39
  4963.6  991.56  4978.2  991.23  4986.6  990.33  5002.7  990.17  5008.6  989.15
  5008.9  988.65  5012.4  988.65  5012.6  989.15  5031.7  989.76  5042.3  990.65
  5052.8  998.23  5063.3  995.89  5116.1 1004.72  5147.7 1007.88  5158.2 1008.32
#Mann=3,-1,0
  4500.1    0.12       0  5008.6    0.05       0  5012.6    0.12       0
Bank Sta=5008.6,5012.6
Exp/Cntr=0.3,0.1

Type RM Length L Ch R = 1,6533,446,446,446
BEGIN DESCRIPTION:
Guadalupe Tributary 62 14.0
END DESCRIPTION:
XS GIS Cut Line= 3
      2170125.00     13873474.98      2170125.00     13873125.00
      2169925.00     13872724.99
#Sta/Elev= 30
  4654.6 1008.57  4684.6 1006.52  4694.6 1006.48  4714.6 1003.08  4764.6  998.75
  4774.6  997.02  4804.6  993.44  4864.6  989.85  4954.6  988.17  4982.5  984.62
  4982.8  984.12  4986.4  984.12  4986.6  984.62  4994.6  985.83  5002.1  989.24
  5007.4  989.24  5013.0  986.79  5035.3  986.44  5085.6  988.65  5116.4  987.41
  5130.4  988.55  5183.5  989.67  5236.6  993.85  5258.9  997.23  5281.3  998.69
  5326.0 1003.31  5376.3 1010.15  5393.1 1011.03  5421.0 1014.42  5451.8 1015.01
#Mann=3,-1,0
  4654.6    0.12       0  4982.5    0.05       0  4986.6    0.12       0
Bank Sta=4982.5,4986.6
Exp/Cntr=0.3,0.1

Type RM Length L Ch R = 1,6087,469,469,469
BEGIN DESCRIPTION:
Guadalupe Tributary 62 13.0
END DESCRIPTION:
XS GIS Cut Line= 3
      2170375.00     13873275.01      2170475.00     13872925.00
      2170325.00     13872575.00
#Sta/Elev= 30
  4635.7  997.57  4677.3  996.56  4691.6  995.65  4698.1  993.62  4718.9  992.45
  4781.3  991.28  4904.8  982.38  4949.0  983.84  4982.8  983.52  4997.1  982.22
  5006.7  982.19  5007.0  981.69  5010.6  981.69  5010.8  982.19  5043.2  984.64
  5097.6  984.11  5119.4  984.56  5143.0  983.82  5166.5  985.10  5173.8  987.20
  5195.5  990.51  5206.4  991.36  5213.7  992.65  5219.1  992.44  5260.8  998.17
  5271.7 1000.21  5295.3 1002.84  5313.4 1005.78  5358.7 1010.28  5380.5 1010.69
#Mann=3,-1,0
  4635.7    0.12       0  5006.7    0.05       0  5010.8    0.12       0
Bank Sta=5006.7,5010.8
Exp/Cntr=0.3,0.1

Type RM Length L Ch R = 1,5618,471,471,471
BEGIN DESCRIPTION:
Guadalupe Tributary 62 12.0
END DESCRIPTION:
XS GIS Cut Line= 3
      2170324.99     13873675.01      2170925.00     13872875.00
      2170874.99     13872574.95
#Sta/Elev= 30
  3999.6 1015.56  4036.1 1014.94  4056.9 1011.81  4113.2 1009.32  4177.7 1003.94
  4236.1 1001.74  4277.7  998.90  4336.1  997.13  4377.7  993.47  4456.9  991.70
  4527.7  986.97  4599.6  983.52  4777.7  980.57  4892.3  980.58  4949.6  978.17
  4971.5  979.12  4990.3  977.71  4990.5  977.21  4994.4  977.71  5040.2  978.32
  5060.4  980.26  5080.7  978.34  5131.4  980.73  5141.5  981.57  5149.2  983.54
  5154.2  983.09  5182.1  987.81  5215.0  990.00  5283.5  998.35  5303.8  999.78
#Mann=3,-1,0
  3999.6    0.12       0  4990.3    0.05       0  4994.4    0.12       0
Bank Sta=4990.3,4994.4
Exp/Cntr=0.3,0.1

Type RM Length L Ch R = 1,5147,431,431,431
BEGIN DESCRIPTION:
Guadalupe Tributary 62 11.0
END DESCRIPTION:
XS GIS Cut Line= 3
      2171175.01     13873474.96      2171275.00     13873125.00
      2171275.00     13872824.97
#Sta/Elev= 30
  4636.3  989.81  4667.5  988.28  4687.0  986.47  4719.5  984.58  4726.0  983.42
  4750.7  981.19  4759.8  979.94  4781.9  978.26  4792.3  978.04  4798.8  977.27
  4832.6  975.10  4896.3  972.74  4910.6  971.62  4917.1  970.06  4927.5  969.01
  4944.4  970.97  4978.2  970.30  4983.4  969.29  4989.9  968.81  5018.2  968.40
  5018.5  967.90  5022.1  967.90  5022.4  968.40  5040.3  970.49  5080.3  972.95
  5100.3  973.59  5140.3  976.93  5170.3  978.09  5250.3  984.36  5300.3  987.58
#Mann=3,-1,0
  4636.3    0.12       0  5018.2    0.05       0  5022.4    0.12       0
Bank Sta=5018.2,5022.4
Exp/Cntr=0.3,0.1

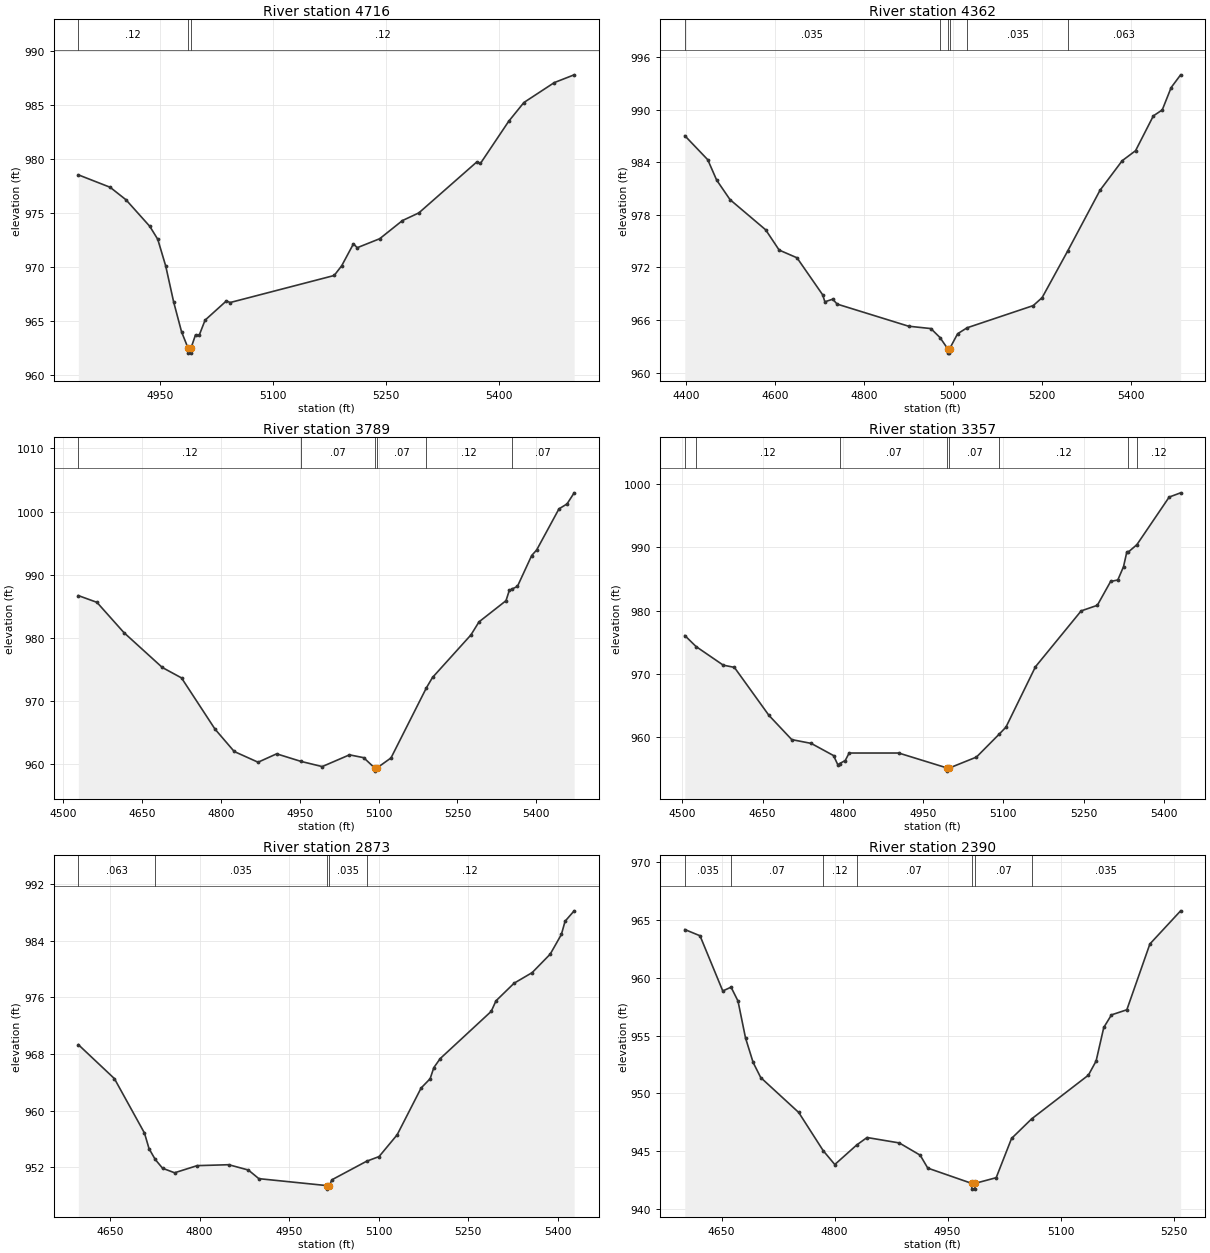
Type RM Length L Ch R = 1,4716,354,354,354
BEGIN DESCRIPTION:
Guadalupe Tributary 62 10.0
END DESCRIPTION:
XS GIS Cut Line= 3
      2171575.00     13873475.01      2171625.00     13873325.00
      2171685.26     13872828.77
#Sta/Elev= 30
  4841.5  978.51  4883.7  977.36  4904.8  976.20  4936.4  973.74  4946.9  972.55
  4957.5  970.07  4968.0  966.75  4978.5  963.99  4986.9  962.52  4987.2  962.02
  4990.9  962.02  4991.2  962.52  4997.0  963.71  5002.1  963.71  5009.7  965.07
  5038.0  966.85  5043.0  966.70  5181.0  969.20  5191.0  970.10  5206.6  972.13
  5211.6  971.77  5241.4  972.60  5271.6  974.28  5293.4  974.99  5370.1  979.69
  5375.2  979.57  5412.6  983.46  5432.8  985.20  5473.1  987.04  5499.5  987.76
#Mann=3,-1,0
  4841.5    0.12       0  4986.9    0.05       0  4991.2    0.12       0
Bank Sta=4986.9,4991.2
Exp/Cntr=0.3,0.1

Type RM Length L Ch R = 1,4362,573,573,573
BEGIN DESCRIPTION:
Guadalupe Tributary 62 9.0
END DESCRIPTION:
XS GIS Cut Line= 3
      2171885.17     13873986.42      2171932.71     13873390.29
      2171931.38     13872873.71
#Sta/Elev= 30
  4396.4  987.02  4448.0  984.28  4468.0  981.96  4498.1  979.73  4578.2  976.29
  4608.5  973.98  4648.6  973.10  4706.3  968.88  4711.3  968.08  4728.9  968.38
  4738.9  967.82  4899.4  965.30  4949.6  965.03  4970.0  964.01  4987.4  962.73
  4987.7  962.23  4991.4  962.23  4991.7  962.73  5009.7  964.44  5031.0  965.12
  5179.7  967.65  5199.7  968.56  5257.5  973.91  5329.7  980.79  5379.7  984.17
  5409.7  985.31  5449.7  989.28  5469.7  989.96  5489.7  992.51  5511.0  993.96
#Mann=6,-1,0
  4396.4   0.035       0  4970.0    0.07       0  4987.4    0.05       0
  4991.7    0.07       0  5031.0   0.035       0  5257.5   0.063       0
Bank Sta=4987.4,4991.7
Exp/Cntr=0.3,0.1

Type RM Length L Ch R = 1,3789,432,432,432
BEGIN DESCRIPTION:
Guadalupe Tributary 62 8.0
END DESCRIPTION:
XS GIS Cut Line= 3
      2171925.02     13874024.99      2172325.00     13873775.00
      2172575.01     13873374.98
#Sta/Elev= 30
  4528.7  986.68  4564.1  985.61  4615.4  980.82  4688.5  975.29  4725.0  973.64
  4788.7  965.53  4825.3  961.98  4870.7  960.28  4906.0  961.61  4952.4  960.41
  4992.7  959.59  5044.6  961.45  5071.7  961.00  5092.5  959.37  5092.8  958.87
  5096.9  959.37  5123.6  960.96  5191.1  972.09  5202.6  973.71  5275.7  980.45
  5291.1  982.52  5342.4  985.87  5348.8  987.52  5353.1  987.69  5364.2  988.14
  5391.3  993.03  5400.7  993.90  5443.2 1000.42  5458.5 1001.20  5472.1 1002.96
#Mann=6,-1,0
  4528.7    0.12       0  4952.4    0.07       0  5092.5    0.05       0
  5096.9    0.07       0  5191.1    0.12       0  5353.1    0.07       0
Bank Sta=5092.5,5096.9
Exp/Cntr=0.3,0.1

Type RM Length L Ch R = 1,3357,484,484,484
BEGIN DESCRIPTION:
Guadalupe Tributary 62 7.0
END DESCRIPTION:
XS GIS Cut Line= 3
      2172375.01     13874324.98      2172675.00     13873925.00
      2172825.01     13873524.98
#Sta/Elev= 30
  4504.4  976.08  4525.6  974.33  4576.3  971.40  4597.1  971.05  4661.7  963.47
  4704.4  959.64  4740.8  959.04  4782.5  957.12  4790.8  955.63  4794.0  955.86
  4804.4  956.33  4811.7  957.52  4904.4  957.52  4994.8  955.16  4995.2  954.66
  4999.3  955.16  5049.8  956.88  5092.3  960.50  5104.9  961.60  5160.1  971.14
  5245.6  979.97  5275.8  980.85  5300.7  984.62  5314.1  984.85  5324.8  986.95
  5331.0  989.28  5333.4  989.24  5349.8  990.43  5410.2  997.95  5431.6  998.62
#Mann=8,-1,0
  4504.4    0.07       0  4525.6    0.12       0  4794.0    0.07       0
  4994.8    0.05       0  4999.3    0.07       0  5092.3    0.12       0
  5333.4    0.07       0  5349.8    0.12       0
Bank Sta=4994.8,4999.3
Exp/Cntr=0.3,0.1

Type RM Length L Ch R = 1,2873,483,483,483
BEGIN DESCRIPTION:
Guadalupe Tributary 62 6.0
END DESCRIPTION:
XS GIS Cut Line= 3
      2173175.00     13874424.96      2173125.00     13874025.00
      2172974.99     13873624.98
#Sta/Elev= 30
  4597.0  969.33  4657.4  964.53  4707.8  956.83  4715.4  954.63  4725.8  953.10
  4738.1  951.86  4758.2  951.22  4796.0  952.23  4848.9  952.36  4881.7  951.61
  4899.3  950.39  5013.0  949.41  5013.3  948.91  5017.5  949.41  5021.4  950.22
  5079.7  952.85  5100.6  953.51  5130.9  956.59  5171.0  963.20  5186.1  964.51
  5192.3  966.08  5203.0  967.36  5288.4  974.03  5296.4  975.52  5326.7  978.01
  5357.0  979.51  5387.2  982.12  5405.9  984.90  5412.1  986.77  5427.3  988.24
#Mann=5,-1,0
  4597.0   0.063       0  4725.8   0.035       0  5013.0   0.035       0
  5017.5   0.035       0  5079.7    0.12       0
Bank Sta=5013,5017.5
Exp/Cntr=0.3,0.1

Type RM Length L Ch R = 1,2390,500,500,500
BEGIN DESCRIPTION:
Guadalupe Tributary 62 5.0
END DESCRIPTION:
XS GIS Cut Line= 3
      2173625.00     13874325.02      2173575.00     13873925.00
      2173525.00     13873674.98
#Sta/Elev= 30
  4601.2  964.19  4621.4  963.65  4651.6  958.87  4662.6  959.20  4671.8  958.00
  4681.8  954.80  4691.9  952.68  4702.0  951.37  4752.4  948.35  4784.9  945.04
  4800.3  943.84  4829.5  945.54  4843.1  946.18  4885.9  945.71  4913.6  944.65
  4923.7  943.53  4981.9  942.21  4982.2  941.71  4986.2  941.71  4986.5  942.21
  5014.5  942.70  5034.9  946.10  5061.5  947.79  5136.9  951.58  5147.1  952.80
  5157.3  955.71  5167.5  956.80  5187.9  957.24  5218.5  962.94  5259.3  965.81
#Mann=7,-1,0
  4601.2   0.035       0  4662.6    0.07       0  4784.9    0.12       0
  4829.5    0.07       0  4981.9    0.05       0  4986.5    0.07       0
  5061.5   0.035       0
Bank Sta=4981.9,4986.5
Exp/Cntr=0.3,0.1

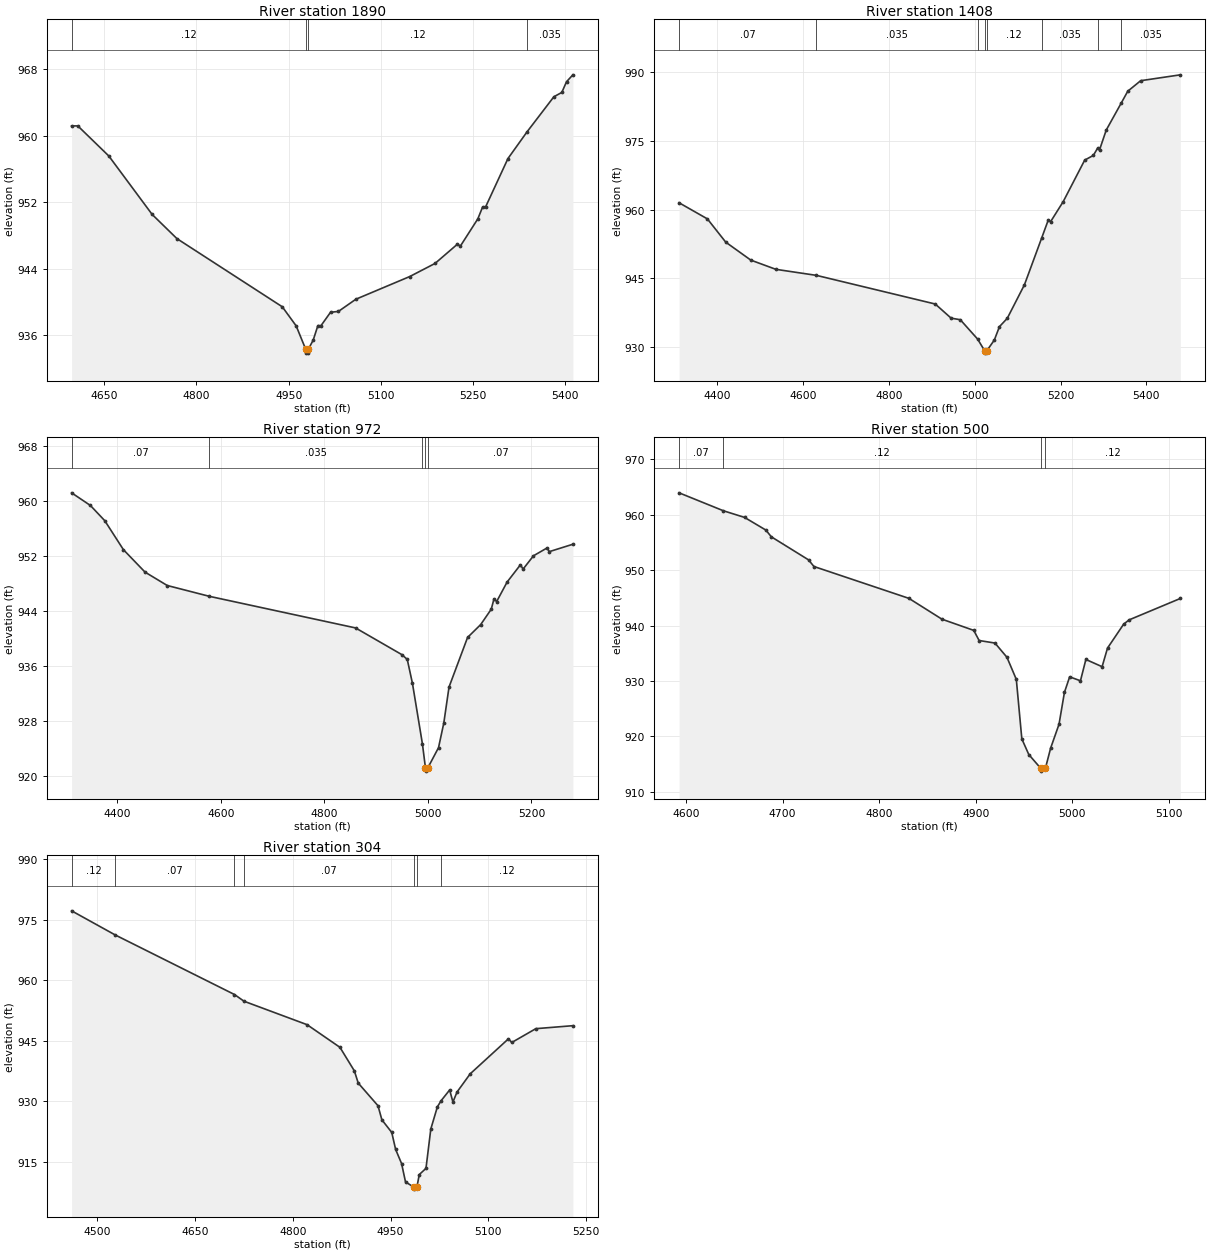
Type RM Length L Ch R = 1,1890,482,482,482
BEGIN DESCRIPTION:
Guadalupe Tributary 62 4.0
END DESCRIPTION:
XS GIS Cut Line= 3
      2174025.00     13874325.01      2174075.00     13873925.00
      2174174.99     13873525.03
#Sta/Elev= 30
  4596.9  961.20  4607.0  961.20  4657.4  957.58  4727.9  950.54  4768.2  947.63
  4939.6  939.42  4962.2  937.12  4977.5  934.34  4977.9  933.84  4981.9  933.84
  4982.2  934.34  4989.9  935.41  4997.5  937.15  5002.6  937.15  5018.1  938.76
  5030.9  938.86  5059.3  940.33  5146.9  943.06  5188.1  944.64  5224.2  946.94
  5229.4  946.74  5257.7  950.01  5265.4  951.42  5270.6  951.49  5306.7  957.27
  5337.8  960.49  5381.4  964.71  5394.3  965.23  5402.0  966.52  5412.3  967.35
#Mann=4,-1,0
  4596.9    0.12       0  4977.5    0.05       0  4982.2    0.12       0
  5337.8   0.035       0
Bank Sta=4977.5,4982.2
Exp/Cntr=0.3,0.1

Type RM Length L Ch R = 1,1408,436,436,436
BEGIN DESCRIPTION:
Guadalupe Tributary 62 3.0
END DESCRIPTION:
XS GIS Cut Line= 3
      2174174.04     13874413.14      2174525.00     13873825.00
      2174483.96     13873342.84
#Sta/Elev= 30
  4310.6  961.49  4376.6  957.98  4419.4  952.91  4477.8  949.00  4536.2  946.99
  4631.0  945.67  4907.9  939.43  4944.9  936.35  4966.3  936.01  5006.7  931.79
  5023.2  929.23  5023.6  928.73  5028.0  929.23  5045.7  931.59  5057.6  934.50
  5075.8  936.31  5115.9  943.63  5156.2  953.85  5171.7  957.80  5176.8  957.36
  5206.3  961.75  5256.4  970.79  5276.5  971.81  5286.6  973.41  5290.9  973.00
  5306.6  977.34  5341.4  983.19  5356.8  985.80  5386.9  988.09  5479.4  989.37
#Mann=8,-1,0
  4310.6    0.07       0  4631.0   0.035       0  5006.7    0.12       0
  5023.2   0.035       0  5028.0    0.12       0  5156.2   0.035       0
  5286.6    0.12       0  5341.4   0.035       0
Bank Sta=5023.2,5028
Exp/Cntr=0.3,0.1

Type RM Length L Ch R = 1,972,472,472,472
BEGIN DESCRIPTION:
Guadalupe Tributary 62 2.0
END DESCRIPTION:
XS GIS Cut Line= 4
      2174233.93     13874444.38      2174580.31     13874025.08
      2174725.00     13874025.00      2174999.63     13874079.78
#Sta/Elev= 30
  4311.4  961.19  4347.7  959.35  4375.5  957.13  4411.5  952.91  4453.3  949.64
  4496.2  947.69  4577.8  946.11  4860.1  941.51  4950.0  937.60  4960.0  936.92
  4970.0  933.44  4989.3  924.61  4995.1  921.15  4995.4  920.65  4999.9  921.15
  5020.4  924.07  5030.6  927.66  5040.7  932.90  5076.5  940.12  5101.9  942.00
  5122.3  944.24  5127.6  945.75  5132.7  945.35  5152.9  948.19  5178.7  950.71
  5183.8  950.08  5203.9  952.02  5229.7  953.14  5234.8  952.63  5280.0  953.70
#Mann=5,-1,0
  4311.4    0.07       0  4577.8   0.035       0  4989.3    0.07       0
  4995.1    0.05       0  4999.9    0.07       0
Bank Sta=4995.1,4999.9
Exp/Cntr=0.3,0.1

Type RM Length L Ch R = 1,500,196,196,196
BEGIN DESCRIPTION:
Guadalupe Tributary 62 1.0
END DESCRIPTION:
XS GIS Cut Line= 3
      2174364.18     13874613.61      2174725.00     13874425.00
      2174824.96     13874375.02
#Sta/Elev= 30
  4592.9  963.97  4638.8  960.73  4660.7  959.53  4682.7  957.25  4688.4  956.03
  4726.9  951.87  4732.5  950.67  4830.8  944.92  4865.0  941.16  4897.9  939.14
  4903.5  937.31  4919.9  936.85  4932.3  934.28  4942.0  930.29  4947.7  919.55
  4954.9  916.73  4967.3  914.23  4967.7  913.73  4972.1  914.23  4977.5  917.87
  4986.2  922.19  4991.8  927.94  4997.2  930.75  5008.4  930.04  5014.0  933.89
  5030.8  932.58  5036.4  935.94  5053.1  940.26  5058.7  941.03  5111.8  944.90
#Mann=4,-1,0
  4592.9    0.07       0  4638.8    0.12       0  4967.3    0.05       0
  4972.1    0.12       0
Bank Sta=4967.3,4972.1
Exp/Cntr=0.3,0.1

Type RM Length L Ch R = 1,304,0,0,0
BEGIN DESCRIPTION:
Guadalupe Tributary 62 0.1
END DESCRIPTION:
XS GIS Cut Line= 3
      2174430.17     13874818.68      2174885.56     13874522.40
      2174910.60     13874298.59
#Sta/Elev= 30
  4461.0  977.18  4527.8  971.20  4710.7  956.42  4725.4  954.75  4822.0  948.94
  4872.4  943.32  4894.5  937.48  4900.4  934.46  4930.7  928.84  4936.7  925.34
  4951.8  922.22  4957.8  917.98  4966.9  914.49  4972.9  909.94  4985.6  908.65
  4986.0  908.15  4990.4  908.65  4994.0  911.76  5004.3  913.30  5011.7  923.06
  5021.8  928.57  5027.5  930.08  5040.6  932.75  5045.6  929.76  5052.0  932.26
  5072.1  936.75  5130.8  945.44  5135.8  944.52  5172.7  947.95  5229.5  948.69
#Mann=7,-1,0
  4461.0    0.12       0  4527.8    0.07       0  4710.7    0.12       0
  4725.4    0.07       0  4985.6    0.05       0  4990.4    0.07       0
  5027.5    0.12       0
Bank Sta=4985.6,4990.4
Exp/Cntr=0.3,0.1

Chan Stop Cuts=-1