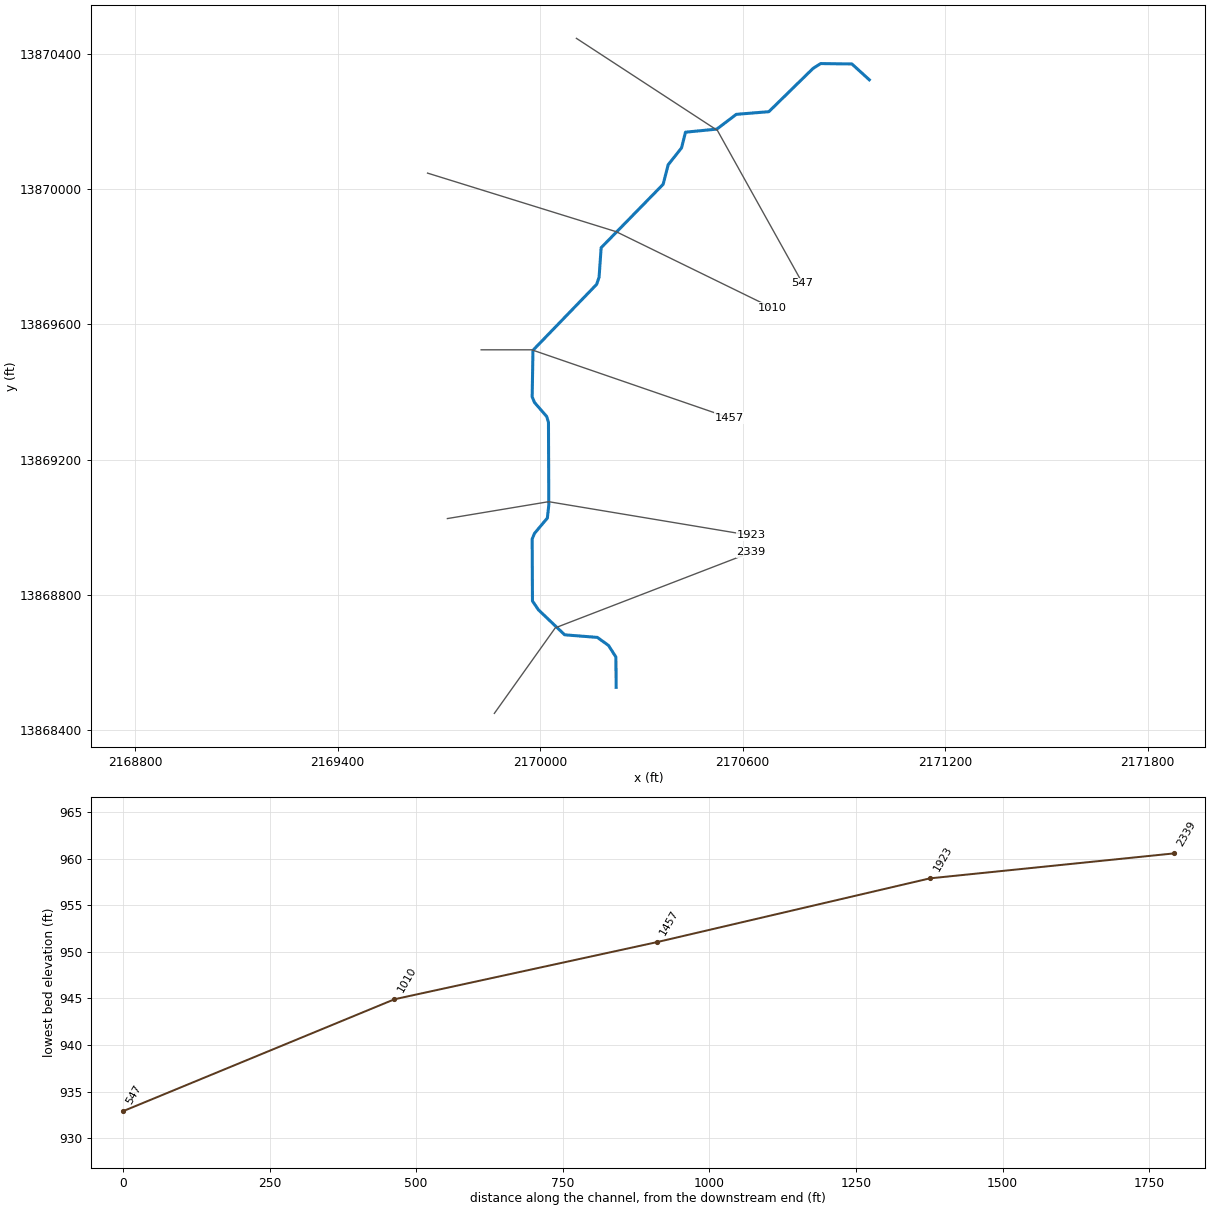
--- Guadalupe Tributary 65.prj (project) ---

Proj Title=Guadalupe Tributary 65 Base Level Engineering
Current Plan=p01
Default Exp/Contr=0.3,0.1
English Units
Geom File=g01
Flow File=f01
Plan File=p01
BEGIN DESCRIPTION:
Guadalupe Tributary 65
END DESCRIPTION:

--- Guadalupe Tributary 65.p01 (plan) ---

Plan Title=Multiple Run
Short Identifier=Multiple
Geom File=g01
Flow File=f01
Subcritical Flow
K Sum by GR= 0
Std Step Tol= 0.01
Critical Tol= 0.01
Num of Std Step Trials= 20
Max Error Tol= 0.3
Flow Tol Ratio= 0.001
Split Flow NTrial= 30
Split Flow Tol= 0.02
Split Flow Ratio= 0.02
Log Output Level= 0
Friction Slope Method= 1
Unsteady Friction Slope Method= 2
Unsteady Bridges Friction Slope Method= 1
Parabolic Critical Depth
Global Vel Dist=  1 , 1 , 1
Global Log Level= 0
CheckData=True
Encroach Param= -1, 0, 0, 0
BEGIN DESCRIPTION:
Multiple Run
END DESCRIPTION:

--- Guadalupe Tributary 65.f01 (steady flow) ---

Flow Title=Multiple
Number of Profiles=7
Profile Names=10-year,25-year,50-year,1pct_min,100-year,1pct_plu,500-year
River Rch & RM= Guadalupe Tribut,Reach-1,2339
    1014    1717    2386    1606    3205    6395    5724
Boundary for River Rch & Prof#=Guadalupe Tribut,Reach-1,1
Up Type=0
Dn Type=3
Dn Slope=0.005
Boundary for River Rch & Prof#=Guadalupe Tribut,Reach-1,2
Up Type=0
Dn Type=3
Dn Slope=0.005
Boundary for River Rch & Prof#=Guadalupe Tribut,Reach-1,3
Up Type=0
Dn Type=3
Dn Slope=0.005
Boundary for River Rch & Prof#=Guadalupe Tribut,Reach-1,4
Up Type=0
Dn Type=3
Dn Slope=0.005
Boundary for River Rch & Prof#=Guadalupe Tribut,Reach-1,5
Up Type=0
Dn Type=3
Dn Slope=0.005
Boundary for River Rch & Prof#=Guadalupe Tribut,Reach-1,6
Up Type=0
Dn Type=3
Dn Slope=0.005
Boundary for River Rch & Prof#=Guadalupe Tribut,Reach-1,7
Up Type=0
Dn Type=3
Dn Slope=0.005

--- Guadalupe Tributary 65.g01 (geometry) ---

Geom Title=Existing Conditions

River Reach=Guadalupe Tribut,Reach-1
Reach XY= 30
      2170225.00     13868525.00      2170224.27     13868614.87
      2170202.34     13868649.05      2170169.31     13868672.94
      2170072.56     13868680.52      2169994.59     13868754.79
      2169977.05     13868780.84      2169976.22     13868964.49
      2169983.14     13868981.06      2170021.22     13869026.57
      2170025.45     13869064.81      2170024.48     13869309.78
      2170019.25     13869327.33      2169983.14     13869368.95
      2169976.21     13869385.51      2169978.53     13869523.53
      2170167.14     13869718.83      2170174.47     13869740.22
      2170180.52     13869827.43      2170364.23     13870015.32
      2170379.18     13870073.30      2170418.74     13870123.20
      2170430.44     13870169.75      2170523.33     13870178.89
      2170580.97     13870222.64      2170677.43     13870230.52
      2170808.24     13870358.60      2170830.88     13870373.05
      2170923.59     13870371.82      2170975.00     13870325.00

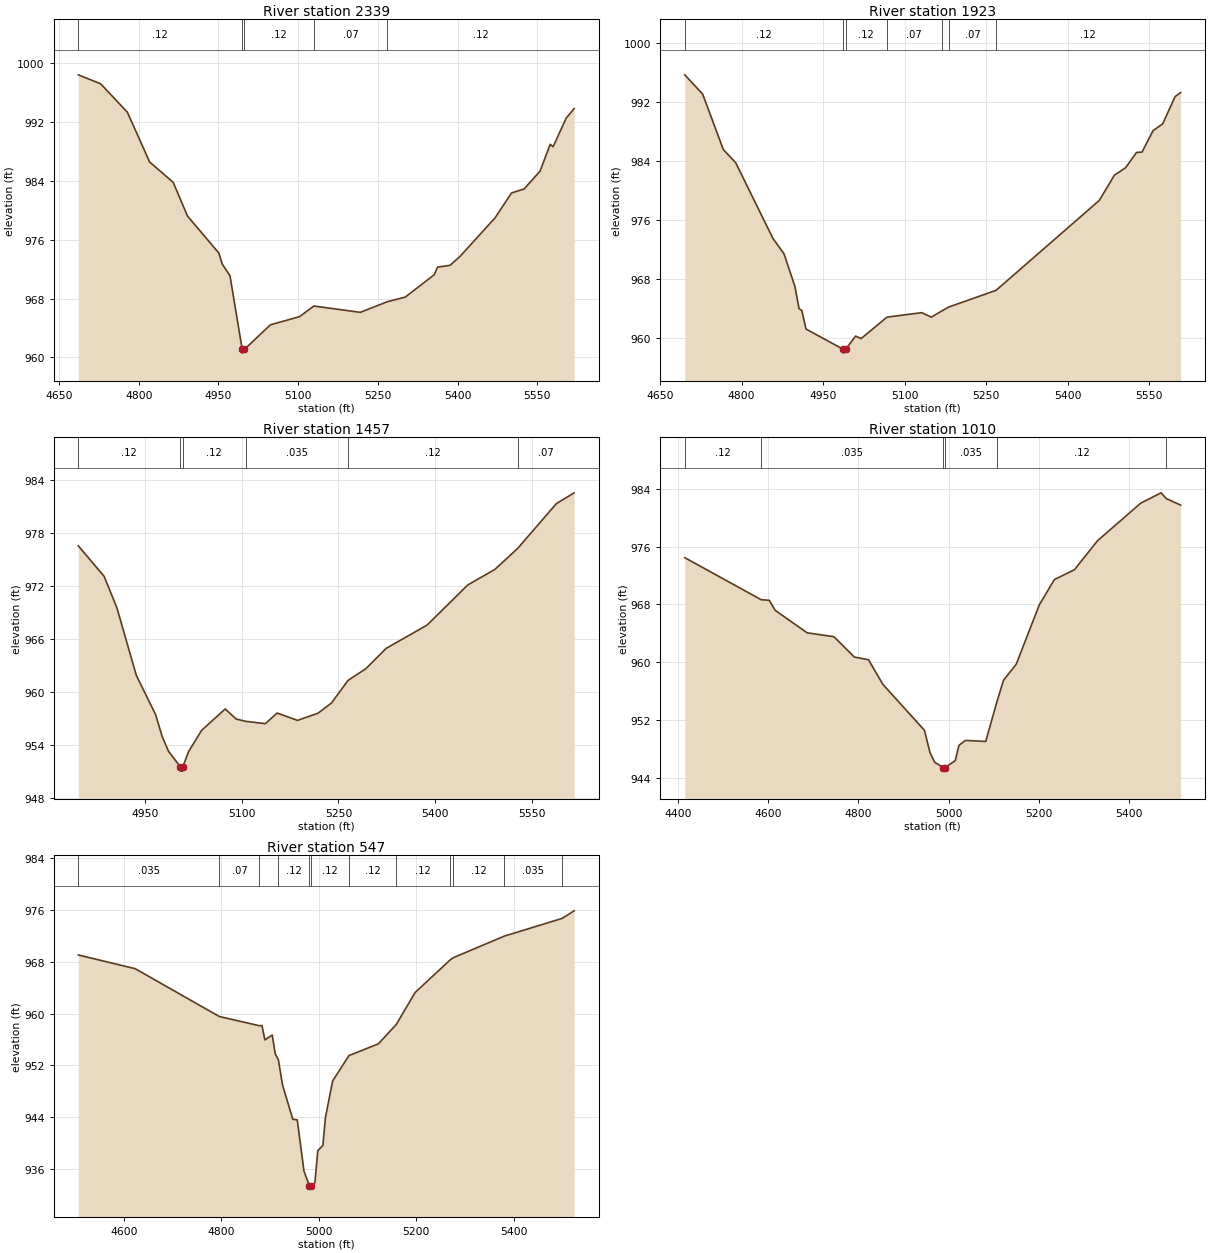
Type RM Length L Ch R = 1,2339,416,416,416
BEGIN DESCRIPTION:
Guadalupe Tributary 65 5.0
END DESCRIPTION:
XS GIS Cut Line= 3
      2169864.17     13868447.83      2170044.72     13868701.29
      2170625.00     13868925.00
#Sta/Elev= 30
  4686.3  998.45  4728.3  997.23  4778.7  993.35  4820.5  986.59  4864.8  983.82
  4891.8  979.23  4950.8  974.19  4957.0  972.71  4971.7  971.12  4994.7  961.08
  4995.0  960.58  4998.7  961.08  5047.8  964.43  5102.4  965.54  5129.7  966.99
  5216.9  966.13  5268.0  967.58  5301.5  968.20  5356.1  971.25  5362.2  972.28
  5386.0  972.53  5405.1  973.78  5470.6  978.99  5501.5  982.37  5525.2  982.92
  5555.2  985.34  5574.4  989.00  5579.8  988.66  5604.4  992.56  5619.4  993.86
#Mann=5,-1,0
  4686.3    0.12       0  4994.7    0.05       0  4998.7    0.12       0
  5129.7    0.07       0  5268.0    0.12       0
Bank Sta=4994.7,4998.7
Exp/Cntr=0.3,0.1

Type RM Length L Ch R = 1,1923,466,466,466
BEGIN DESCRIPTION:
Guadalupe Tributary 65 4.0
END DESCRIPTION:
XS GIS Cut Line= 3
      2169725.03     13869025.00      2170025.00     13869075.00
      2170625.01     13868975.00
#Sta/Elev= 30
  4695.5  995.66  4728.4  993.04  4766.4  985.52  4789.2  983.73  4857.7  973.46
  4878.0  971.39  4898.2  966.93  4905.8  963.93  4910.9  963.68  4918.5  961.17
  4987.5  958.40  4987.7  957.90  4991.5  958.40  5009.7  960.21  5019.9  959.87
  5067.5  962.78  5131.4  963.39  5149.1  962.78  5167.9  963.60  5181.5  964.16
  5268.3  966.42  5458.4  978.63  5486.2  982.06  5506.5  983.05  5526.8  985.13
  5536.9  985.18  5557.2  988.09  5574.9  989.01  5597.7  992.70  5607.9  993.25
#Mann=7,-1,0
  4695.5    0.12       0  4987.5    0.05       0  4991.5    0.12       0
  5067.5    0.07       0  5167.9    0.12       0  5181.5    0.07       0
  5268.3    0.12       0
Bank Sta=4987.5,4991.5
Exp/Cntr=0.3,0.1

Type RM Length L Ch R = 1,1457,447,447,447
BEGIN DESCRIPTION:
Guadalupe Tributary 65 3.0
END DESCRIPTION:
XS GIS Cut Line= 3
      2169825.04     13869525.00      2169975.00     13869525.00
      2170561.06     13869323.17
#Sta/Elev= 30
  4846.2  976.52  4886.2  973.08  4906.2  969.49  4936.2  961.88  4966.2  957.43
  4976.2  954.99  4986.2  953.29  5004.5  951.54  5004.7  951.04  5008.2  951.04
  5008.5  951.54  5017.3  953.24  5037.7  955.66  5074.2  958.07  5091.3  956.93
  5106.2  956.67  5136.6  956.41  5154.8  957.61  5186.5  956.78  5218.3  957.59
  5239.4  958.76  5264.9  961.30  5292.7  962.63  5324.0  964.92  5387.5  967.55
  5450.9  972.10  5493.2  973.87  5528.4  976.24  5588.4  981.30  5616.0  982.52
#Mann=6,-1,0
  4846.2    0.12       0  5004.5    0.05       0  5008.5    0.12       0
  5106.2   0.035       0  5264.9    0.12       0  5528.4    0.07       0
Bank Sta=5004.5,5008.5
Exp/Cntr=0.3,0.1

Type RM Length L Ch R = 1,1010,463,463,463
BEGIN DESCRIPTION:
Guadalupe Tributary 65 2.0
END DESCRIPTION:
XS GIS Cut Line= 3
      2169666.21     13870048.53      2170225.00     13869875.00
      2170686.27     13869649.61
#Sta/Elev= 30
  4415.2  974.46  4584.6  968.64  4602.4  968.56  4615.3  967.18  4686.2  964.06
  4745.6  963.52  4790.9  960.70  4822.3  960.33  4853.8  956.94  4946.2  950.56
  4958.4  947.48  4968.9  946.13  4987.8  945.41  4988.1  944.91  4991.8  945.41
  5014.4  946.36  5022.6  948.48  5036.9  949.16  5081.9  949.02  5107.8  954.75
  5121.4  957.50  5149.5  959.71  5200.7  967.94  5234.0  971.43  5278.6  972.80
  5329.6  976.81  5425.3  982.01  5470.3  983.44  5481.9  982.65  5513.7  981.74
#Mann=6,-1,0
  4415.2    0.12       0  4584.6   0.035       0  4987.8   0.035       0
  4991.8   0.035       0  5107.8    0.12       0  5481.9   0.035       0
Bank Sta=4987.8,4991.8
Exp/Cntr=0.3,0.1

Type RM Length L Ch R = 1,547,0,0,0
BEGIN DESCRIPTION:
Guadalupe Tributary 65 1.0
END DESCRIPTION:
XS GIS Cut Line= 3
      2170107.23     13870447.82      2170525.00     13870175.00
      2170777.36     13869722.12
#Sta/Elev= 30
  4506.4  969.05  4623.2  966.93  4795.8  959.54  4878.1  958.12  4883.2  958.16
  4889.2  955.93  4904.3  956.69  4910.3  953.81  4916.9  952.86  4925.4  948.96
  4946.5  943.67  4955.6  943.58  4969.5  935.63  4980.7  933.38  4980.9  932.88
  4984.7  933.38  4991.8  933.88  4997.8  938.83  5008.2  939.63  5013.4  943.92
  5028.3  949.60  5061.7  953.51  5122.0  955.32  5158.9  958.32  5197.4  963.25
  5269.7  968.31  5275.8  968.63  5380.4  971.96  5498.8  974.69  5523.8  975.87
#Mann=12,-1,0
  4506.4   0.035       0  4795.8    0.07       0  4878.1   0.035       0
  4916.9    0.12       0  4980.7    0.05       0  4984.7    0.12       0
  5061.7    0.12       0  5158.9    0.12       0  5269.7   0.035       0
  5275.8    0.12       0  5380.4   0.035       0  5498.8    0.12       0
Bank Sta=4980.7,4984.7
Exp/Cntr=0.3,0.1

Chan Stop Cuts=-1