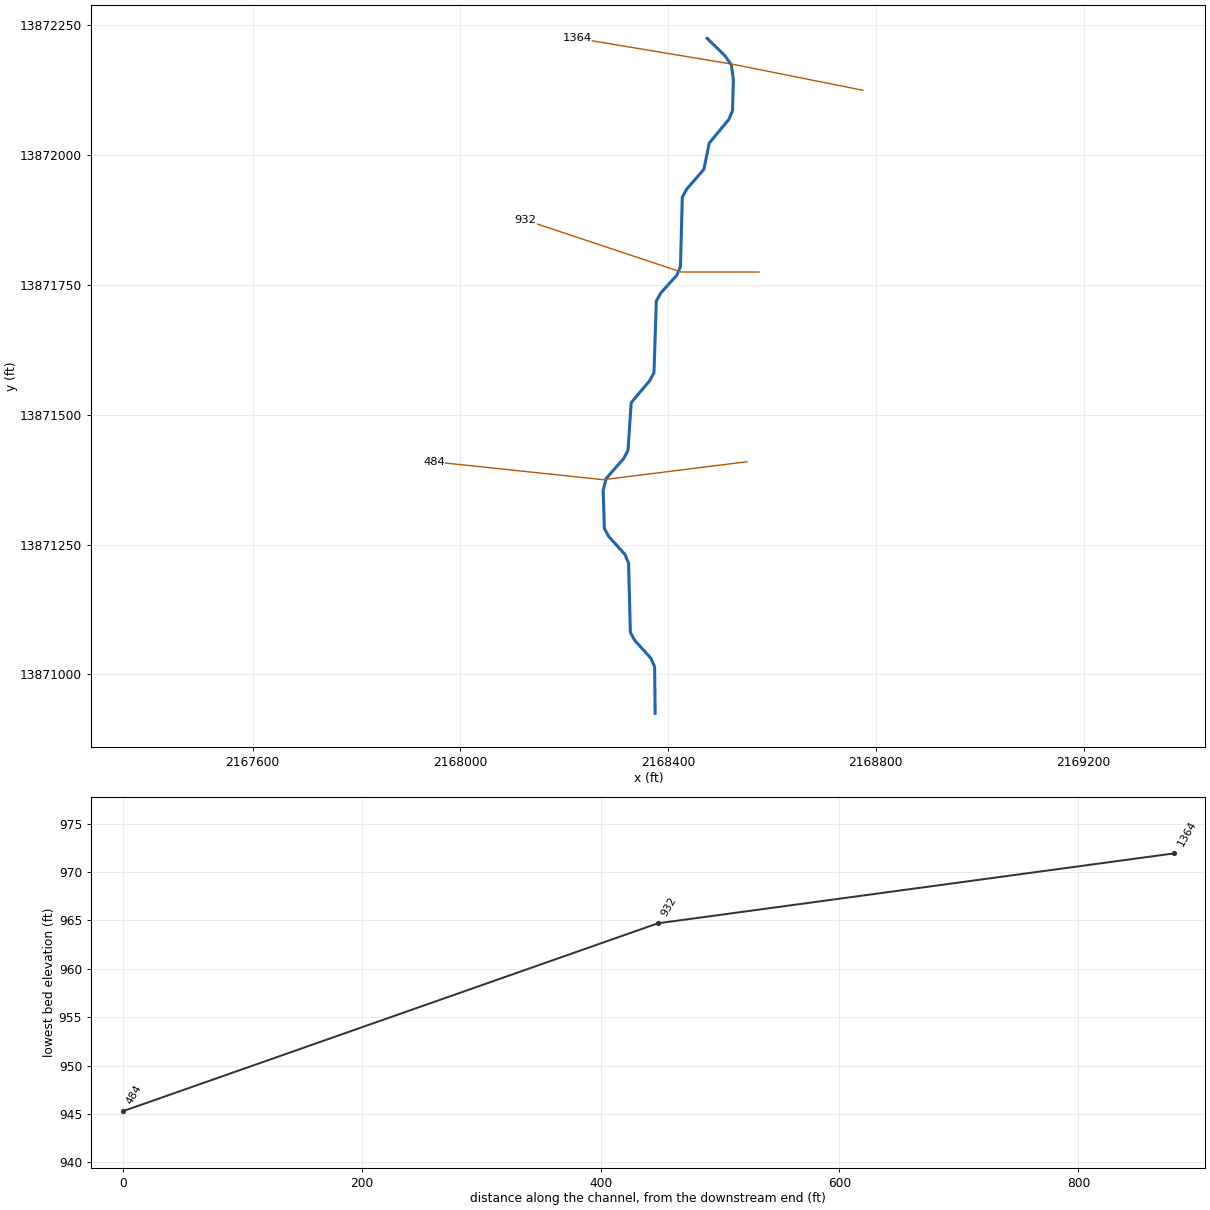
--- Guadalupe Tributary 65b.prj (project) ---

Proj Title=Guadalupe Tributary 65b Base Level Engineering
Current Plan=p01
Default Exp/Contr=0.3,0.1
English Units
Geom File=g01
Flow File=f01
Plan File=p01
BEGIN DESCRIPTION:
Guadalupe Tributary 65b
END DESCRIPTION:

--- Guadalupe Tributary 65b.p01 (plan) ---

Plan Title=Multiple Run
Short Identifier=Multiple
Geom File=g01
Flow File=f01
Subcritical Flow
K Sum by GR= 0
Std Step Tol= 0.01
Critical Tol= 0.01
Num of Std Step Trials= 20
Max Error Tol= 0.3
Flow Tol Ratio= 0.001
Split Flow NTrial= 30
Split Flow Tol= 0.02
Split Flow Ratio= 0.02
Log Output Level= 0
Friction Slope Method= 1
Unsteady Friction Slope Method= 2
Unsteady Bridges Friction Slope Method= 1
Parabolic Critical Depth
Global Vel Dist=  1 , 1 , 1
Global Log Level= 0
CheckData=True
Encroach Param= -1, 0, 0, 0
BEGIN DESCRIPTION:
Multiple Run
END DESCRIPTION:

--- Guadalupe Tributary 65b.f01 (steady flow) ---

Flow Title=Multiple
Number of Profiles=7
Profile Names=10-year,25-year,50-year,1pct_min,100-year,1pct_plu,500-year
River Rch & RM= Guadalupe Tribut,Reach-1,1364
     371     590     787     512    1021    2037    1692
Boundary for River Rch & Prof#=Guadalupe Tribut,Reach-1,1
Up Type=0
Dn Type=3
Dn Slope=0.005
Boundary for River Rch & Prof#=Guadalupe Tribut,Reach-1,2
Up Type=0
Dn Type=3
Dn Slope=0.005
Boundary for River Rch & Prof#=Guadalupe Tribut,Reach-1,3
Up Type=0
Dn Type=3
Dn Slope=0.005
Boundary for River Rch & Prof#=Guadalupe Tribut,Reach-1,4
Up Type=0
Dn Type=3
Dn Slope=0.005
Boundary for River Rch & Prof#=Guadalupe Tribut,Reach-1,5
Up Type=0
Dn Type=3
Dn Slope=0.005
Boundary for River Rch & Prof#=Guadalupe Tribut,Reach-1,6
Up Type=0
Dn Type=3
Dn Slope=0.005
Boundary for River Rch & Prof#=Guadalupe Tribut,Reach-1,7
Up Type=0
Dn Type=3
Dn Slope=0.005

--- Guadalupe Tributary 65b.g01 (geometry) ---

Geom Title=Existing Conditions

River Reach=Guadalupe Tribut,Reach-1
Reach XY= 30
      2168475.00     13872225.00      2168508.96     13872192.05
      2168521.81     13872173.60      2168525.64     13872145.03
      2168523.93     13872085.53      2168516.96     13872068.94
      2168479.19     13872023.27      2168468.88     13871972.82
      2168435.80     13871934.67      2168427.25     13871919.07
      2168423.77     13871785.51      2168416.85     13871768.95
      2168385.86     13871734.65      2168377.27     13871719.06
      2168372.73     13871580.94      2168364.15     13871565.35
      2168328.86     13871523.40      2168322.64     13871430.97
      2168314.10     13871415.37      2168280.68     13871377.31
      2168274.90     13871354.90      2168277.17     13871280.98
      2168285.81     13871265.37      2168316.85     13871231.06
      2168323.77     13871214.49      2168327.25     13871080.93
      2168335.80     13871065.33      2168366.89     13871031.07
      2168373.98     13871014.58      2168375.00     13870925.00

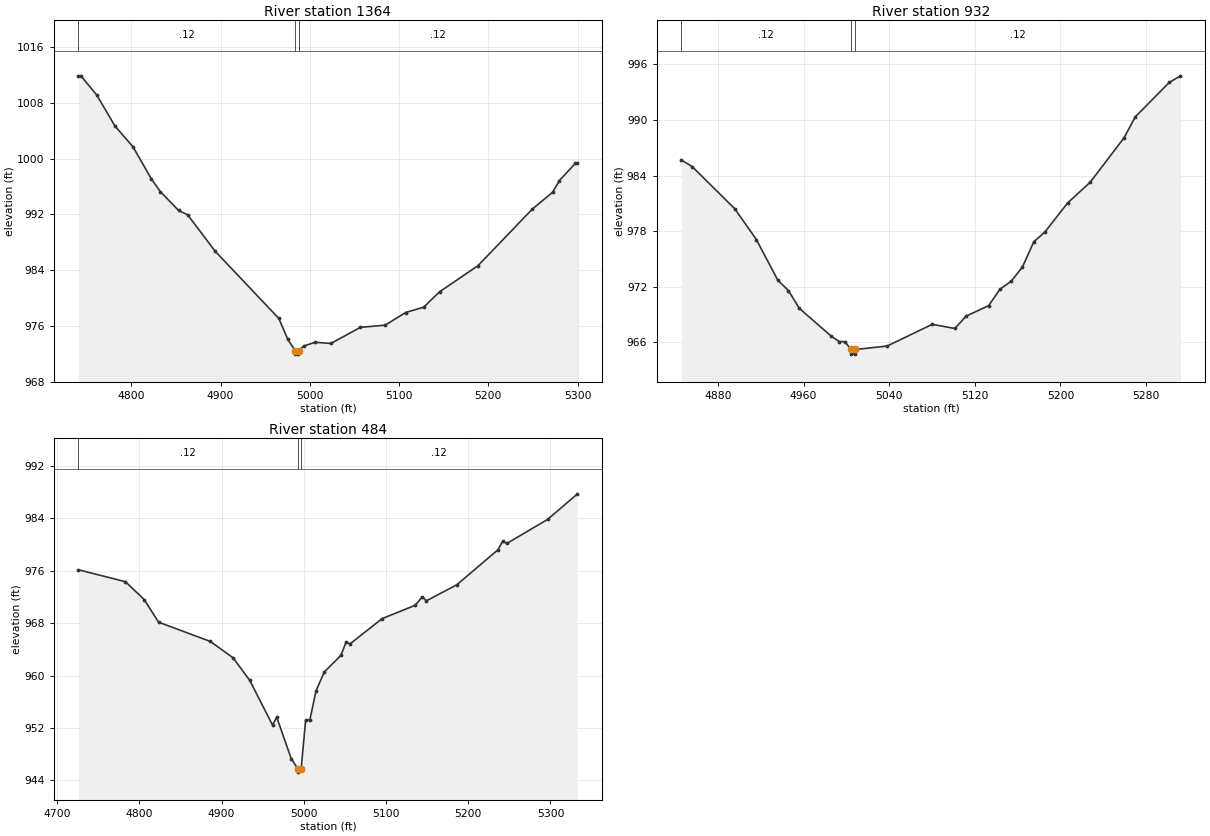
Type RM Length L Ch R = 1,1364,432,432,432
BEGIN DESCRIPTION:
Guadalupe Tributary 65b 3.0
END DESCRIPTION:
XS GIS Cut Line= 3
      2168775.01     13872125.00      2168525.00     13872175.00
      2168225.00     13872225.00
#Sta/Elev= 30
  4740.8 1011.87  4743.4 1011.87  4761.2 1009.13  4781.6 1004.68  4802.0 1001.66
  4822.4  997.09  4832.6  995.24  4853.0  992.55  4863.2  991.92  4893.8  986.72
  4965.2  977.07  4975.4  974.04  4983.6  972.44  4983.8  971.94  4987.3  971.94
  4987.6  972.44  4993.2  973.10  5005.9  973.64  5023.6  973.47  5056.6  975.78
  5084.5  976.10  5107.3  977.91  5127.6  978.68  5145.3  980.88  5188.4  984.63
  5249.2  992.74  5272.0  995.16  5279.6  996.84  5297.4  999.30  5299.9  999.30
#Mann=3,-1,0
  4740.8    0.12       0  4983.6    0.05       0  4987.6    0.12       0
Bank Sta=4983.6,4987.6
Exp/Cntr=0.3,0.1

Type RM Length L Ch R = 1,932,448,448,448
BEGIN DESCRIPTION:
Guadalupe Tributary 65b 2.0
END DESCRIPTION:
XS GIS Cut Line= 3
      2168574.97     13871775.00      2168425.00     13871775.00
      2168125.00     13871875.00
#Sta/Elev= 30
  4845.9  985.67  4855.9  984.97  4895.9  980.39  4915.9  977.08  4935.9  972.70
  4945.9  971.57  4955.9  969.67  4985.9  966.64  4993.4  966.06  4998.5  966.06
  5004.4  965.21  5004.7  964.71  5008.2  964.71  5008.4  965.21  5038.0  965.58
  5080.2  967.93  5101.3  967.48  5111.8  968.81  5132.9  969.95  5143.4  971.71
  5154.0  972.59  5164.5  974.13  5175.1  976.85  5185.6  977.92  5206.7  981.04
  5227.8  983.28  5259.4  988.08  5269.9  990.34  5301.6  994.05  5312.1  994.77
#Mann=3,-1,0
  4845.9    0.12       0  5004.4    0.05       0  5008.4    0.12       0
Bank Sta=5004.4,5008.4
Exp/Cntr=0.3,0.1

Type RM Length L Ch R = 1,484,0,0,0
BEGIN DESCRIPTION:
Guadalupe Tributary 65b 1.0
END DESCRIPTION:
XS GIS Cut Line= 3
      2168551.69     13871409.63      2168275.00     13871375.00
      2167948.77     13871409.49
#Sta/Elev= 30
  4726.0  976.15  4783.1  974.34  4805.9  971.61  4823.4  968.16  4886.5  965.21
  4914.2  962.70  4934.3  959.27  4962.0  952.45  4967.1  953.65  4984.7  947.34
  4992.8  945.77  4993.0  945.27  4996.8  945.77  5002.3  953.25  5007.4  953.25
  5014.9  957.68  5025.0  960.57  5045.1  963.08  5051.3  965.07  5056.3  964.85
  5095.4  968.71  5135.6  970.74  5144.1  972.03  5149.1  971.42  5185.9  973.85
  5236.1  979.20  5241.9  980.51  5246.9  980.17  5296.5  983.84  5332.9  987.75
#Mann=3,-1,0
  4726.0    0.12       0  4992.8    0.05       0  4996.8    0.12       0
Bank Sta=4992.8,4996.8
Exp/Cntr=0.3,0.1

Chan Stop Cuts=-1