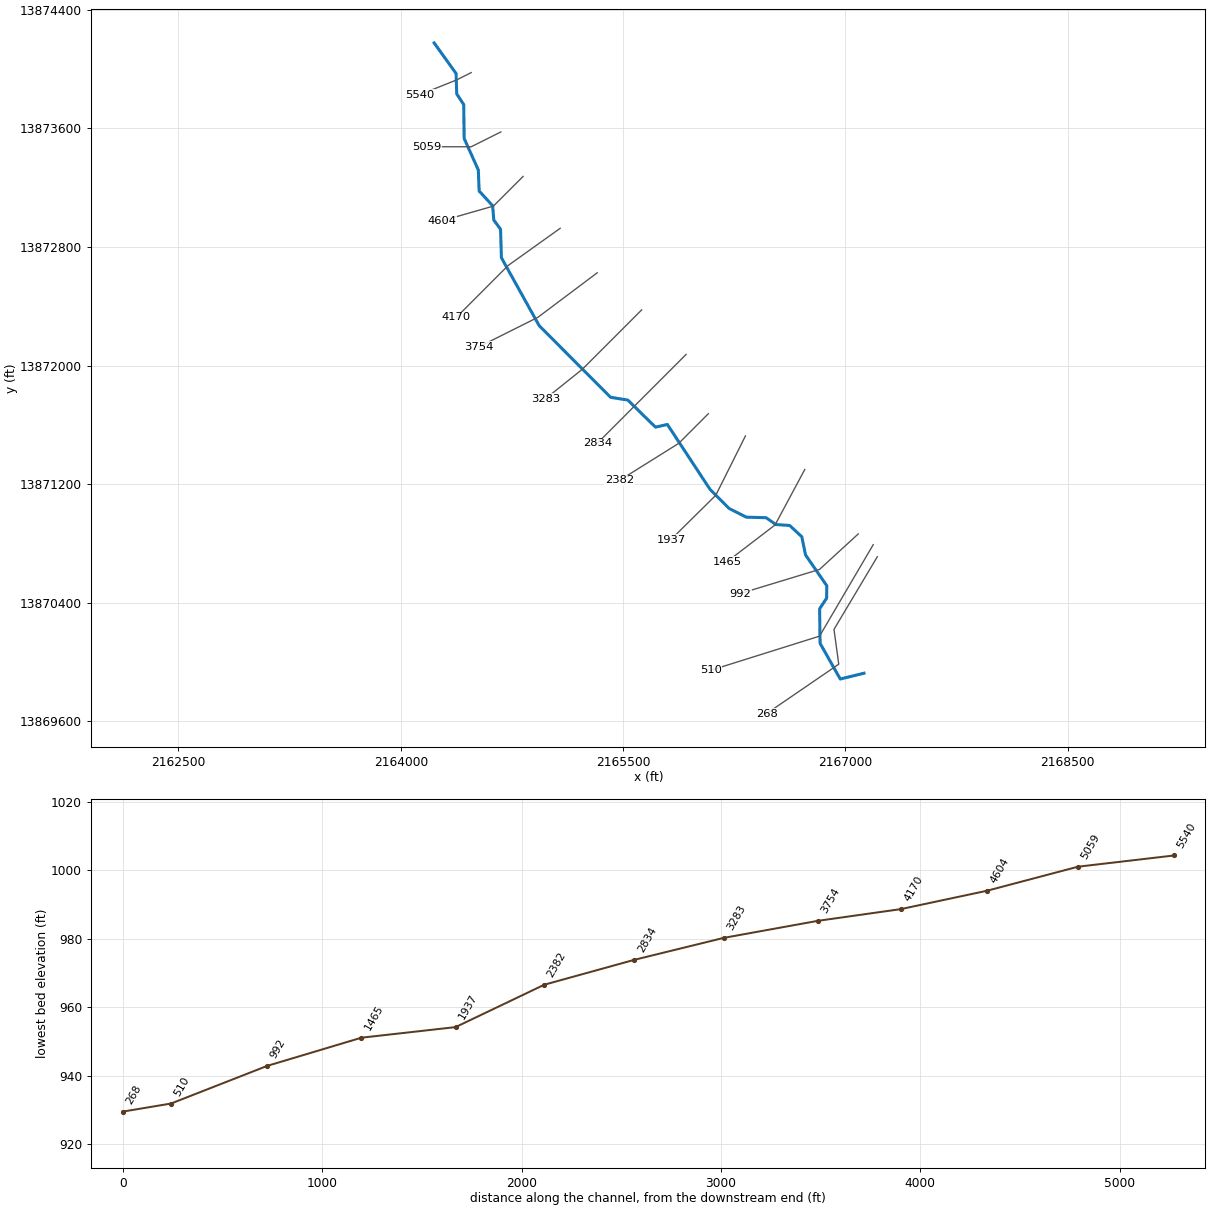
--- Guadalupe Tributary 66.prj (project) ---

Proj Title=Guadalupe Tributary 66 Base Level Engineering
Current Plan=p01
Default Exp/Contr=0.3,0.1
English Units
Geom File=g01
Flow File=f01
Plan File=p01
BEGIN DESCRIPTION:
Guadalupe Tributary 66
END DESCRIPTION:

--- Guadalupe Tributary 66.p01 (plan) ---

Plan Title=Multiple Run
Short Identifier=Multiple
Geom File=g01
Flow File=f01
Subcritical Flow
K Sum by GR= 0
Std Step Tol= 0.01
Critical Tol= 0.01
Num of Std Step Trials= 20
Max Error Tol= 0.3
Flow Tol Ratio= 0.001
Split Flow NTrial= 30
Split Flow Tol= 0.02
Split Flow Ratio= 0.02
Log Output Level= 0
Friction Slope Method= 1
Unsteady Friction Slope Method= 2
Unsteady Bridges Friction Slope Method= 1
Parabolic Critical Depth
Global Vel Dist=  1 , 1 , 1
Global Log Level= 0
CheckData=True
Encroach Param= -1, 0, 0, 0
BEGIN DESCRIPTION:
Multiple Run
END DESCRIPTION:

--- Guadalupe Tributary 66.f01 (steady flow) ---

Flow Title=Multiple
Number of Profiles=7
Profile Names=10-year,25-year,50-year,1pct_min,100-year,1pct_plu,500-year
River Rch & RM= Guadalupe Tribut,Reach-1,5540
    1777    3125    4453    3071    6127   12226   11493
Boundary for River Rch & Prof#=Guadalupe Tribut,Reach-1,1
Up Type=0
Dn Type=3
Dn Slope=0.005
Boundary for River Rch & Prof#=Guadalupe Tribut,Reach-1,2
Up Type=0
Dn Type=3
Dn Slope=0.005
Boundary for River Rch & Prof#=Guadalupe Tribut,Reach-1,3
Up Type=0
Dn Type=3
Dn Slope=0.005
Boundary for River Rch & Prof#=Guadalupe Tribut,Reach-1,4
Up Type=0
Dn Type=3
Dn Slope=0.005
Boundary for River Rch & Prof#=Guadalupe Tribut,Reach-1,5
Up Type=0
Dn Type=3
Dn Slope=0.005
Boundary for River Rch & Prof#=Guadalupe Tribut,Reach-1,6
Up Type=0
Dn Type=3
Dn Slope=0.005
Boundary for River Rch & Prof#=Guadalupe Tribut,Reach-1,7
Up Type=0
Dn Type=3
Dn Slope=0.005

--- Guadalupe Tributary 66.g01 (geometry) ---

Geom Title=Existing Conditions

River Reach=Guadalupe Tribut,Reach-1
Reach XY= 30
      2164225.00     13874175.00      2164372.75     13873969.07
      2164377.27     13873830.94      2164424.48     13873759.78
      2164427.26     13873530.94      2164522.73     13873319.06
      2164528.56     13873176.47      2164619.46     13873077.42
      2164627.47     13872980.57      2164672.74     13872919.06
      2164678.75     13872726.55      2164933.16     13872268.95
      2165415.21     13871785.52      2165531.17     13871767.14
      2165718.33     13871584.30      2165798.38     13871602.50
      2166085.78     13871165.32      2166215.32     13871035.76
      2166330.93     13870977.25      2166464.49     13870973.77
      2166530.57     13870927.47      2166623.52     13870921.39
      2166705.39     13870845.20      2166730.54     13870722.58
      2166873.75     13870515.30      2166872.83     13870430.98
      2166825.52     13870359.78      2166828.75     13870126.55
      2166964.62     13869885.94      2167125.00     13869925.00

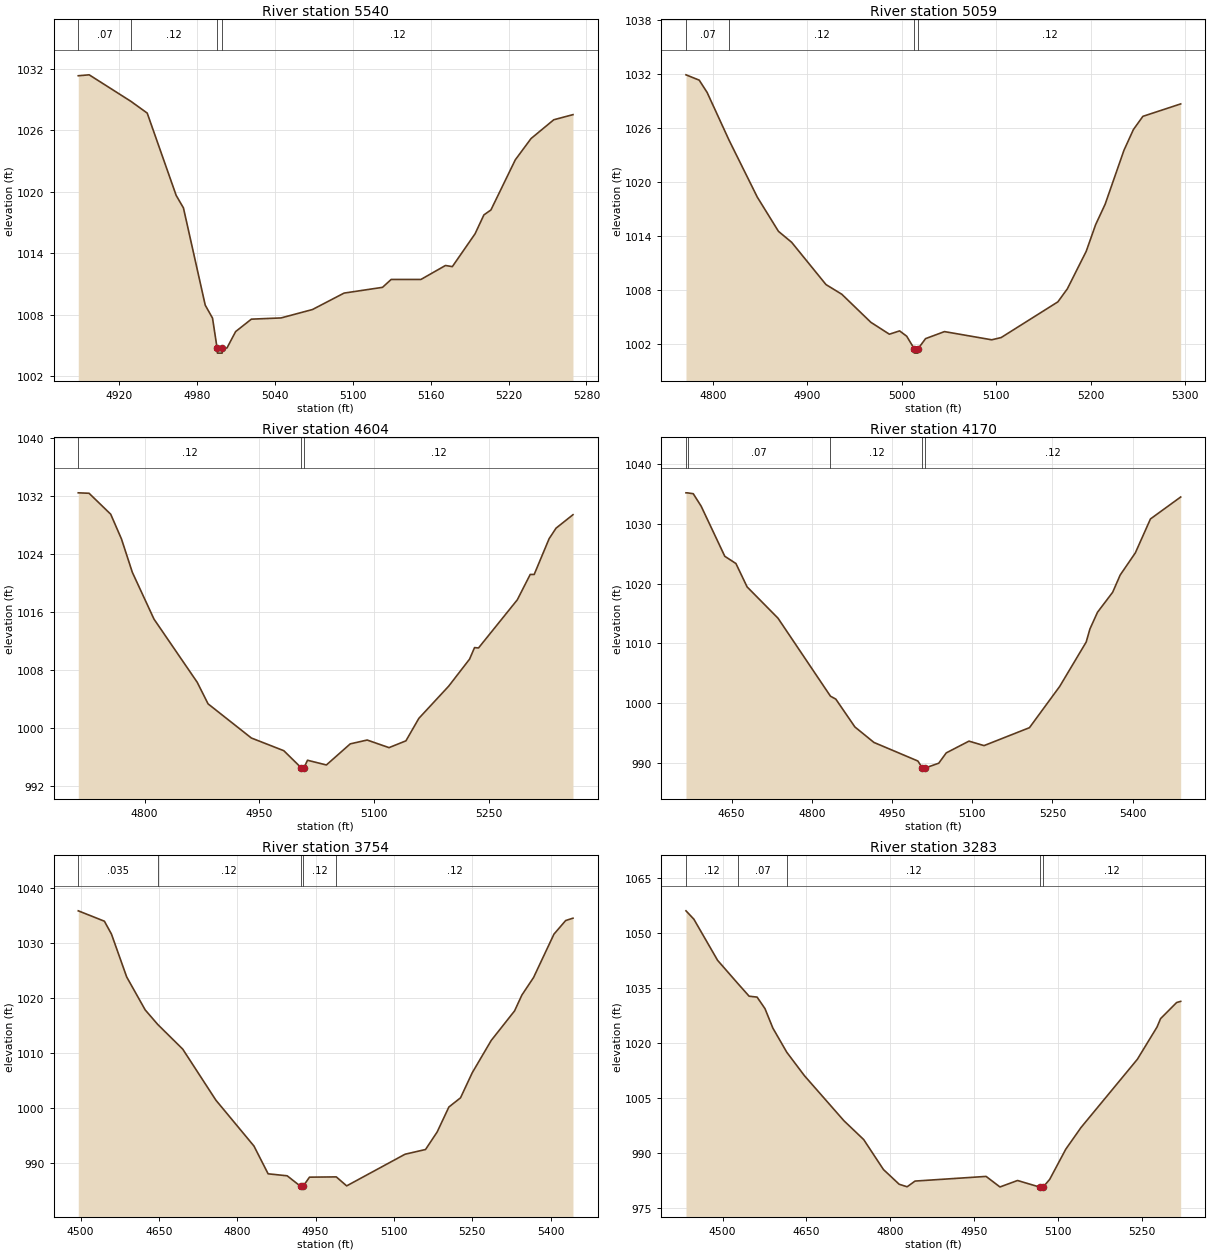
Type RM Length L Ch R = 1,5540,481,481,481
BEGIN DESCRIPTION:
Guadalupe Tributary 66 12.0
END DESCRIPTION:
XS GIS Cut Line= 3
      2164474.97     13873974.99      2164375.00     13873925.00
      2164125.03     13873825.01
#Sta/Elev= 30
  4888.6 1031.30  4897.0 1031.39  4929.1 1028.81  4941.7 1027.66  4964.0 1019.64
  4969.6 1018.42  4986.4 1008.94  4992.0 1007.68  4995.5 1004.77  4995.8 1004.27
  4999.4 1004.27  4999.6 1004.77  5003.1 1004.77  5009.8 1006.37  5021.9 1007.58
  5044.8 1007.70  5069.0 1008.52  5093.3 1010.12  5122.9 1010.68  5129.6 1011.45
  5152.5 1011.45  5171.4 1012.81  5176.7 1012.70  5194.2 1015.90  5201.0 1017.74
  5206.4 1018.22  5225.2 1023.11  5237.3 1025.18  5254.8 1027.01  5269.6 1027.51
#Mann=4,-1,0
  4888.6    0.07       0  4929.1    0.12       0  4995.5    0.05       0
  4999.6    0.12       0
Bank Sta=4995.5,4999.6
Exp/Cntr=0.3,0.1

Type RM Length L Ch R = 1,5059,455,455,455
BEGIN DESCRIPTION:
Guadalupe Tributary 66 11.0
END DESCRIPTION:
XS GIS Cut Line= 3
      2164675.03     13873575.02      2164475.00     13873475.00
      2164175.04     13873475.00
#Sta/Elev= 30
  4771.7 1031.90  4785.7 1031.31  4794.1 1029.94  4817.4 1024.62  4847.2 1018.32
  4869.6 1014.52  4883.5 1013.31  4919.9 1008.61  4936.6 1007.54  4967.4 1004.42
  4987.0 1003.10  4997.8 1003.47  5005.3 1002.88  5013.2 1001.50  5013.5 1001.00
  5017.1 1001.00  5017.4 1001.50  5025.3 1002.61  5045.3 1003.39  5095.3 1002.48
  5105.3 1002.73  5165.3 1006.69  5175.3 1008.13  5195.3 1012.30  5205.3 1015.27
  5215.3 1017.52  5235.3 1023.53  5245.3 1025.83  5255.3 1027.29  5295.3 1028.67
#Mann=4,-1,0
  4771.7    0.07       0  4817.4    0.12       0  5013.2    0.05       0
  5017.4    0.12       0
Bank Sta=5013.2,5017.4
Exp/Cntr=0.3,0.1

Type RM Length L Ch R = 1,4604,434,434,434
BEGIN DESCRIPTION:
Guadalupe Tributary 66 10.0
END DESCRIPTION:
XS GIS Cut Line= 3
      2164824.99     13873274.99      2164625.00     13873075.00
      2164275.03     13872975.01
#Sta/Elev= 30
  4713.2 1032.39  4727.3 1032.33  4755.6 1029.44  4769.7 1026.02  4783.9 1021.42
  4812.2 1014.97  4868.7 1006.26  4882.9 1003.28  4939.5  998.57  4981.9  996.82
  5004.3  994.50  5004.6  994.00  5008.5  994.50  5012.9  995.50  5037.6  994.85
  5068.8  997.76  5090.9  998.29  5119.5  997.24  5141.6  998.18  5158.5 1001.28
  5197.5 1005.72  5224.8 1009.45  5231.3 1011.04  5236.5 1010.99  5287.2 1017.63
  5304.1 1021.13  5309.3 1021.13  5328.8 1026.06  5337.9 1027.52  5360.0 1029.37
#Mann=3,-1,0
  4713.2    0.12       0  5004.3    0.05       0  5008.5    0.12       0
Bank Sta=5004.3,5008.5
Exp/Cntr=0.3,0.1

Type RM Length L Ch R = 1,4170,416,416,416
BEGIN DESCRIPTION:
Guadalupe Tributary 66 9.0
END DESCRIPTION:
XS GIS Cut Line= 3
      2165075.04     13872925.03      2164725.00     13872675.00
      2164375.03     13872325.03
#Sta/Elev= 30
  4564.8 1035.19  4568.0 1035.18  4578.4 1035.04  4593.1 1032.97  4637.4 1024.57
  4658.2 1023.36  4679.1 1019.45  4736.9 1014.21  4835.0 1001.16  4845.0 1000.67
  4880.7  996.01  4916.3  993.42  4998.5  990.31  5006.9  989.12  5007.2  988.62
  5011.3  989.12  5037.4  989.94  5051.5  991.67  5094.0  993.64  5122.2  992.89
  5207.1  995.89  5263.7 1002.80  5313.2 1010.22  5320.2 1012.41  5334.4 1015.21
  5362.7 1018.55  5376.8 1021.44  5405.1 1025.14  5433.4 1030.82  5489.9 1034.49
#Mann=5,-1,0
  4564.8    0.12       0  4568.0    0.07       0  4835.0    0.12       0
  5006.9    0.05       0  5011.3    0.12       0
Bank Sta=5006.9,5011.3
Exp/Cntr=0.3,0.1

Type RM Length L Ch R = 1,3754,471,471,471
BEGIN DESCRIPTION:
Guadalupe Tributary 66 8.0
END DESCRIPTION:
XS GIS Cut Line= 3
      2165324.96     13872624.97      2164925.00     13872325.00
      2164524.97     13872124.98
#Sta/Elev= 30
  4495.7 1035.91  4545.7 1034.02  4559.2 1031.68  4588.4 1023.86  4623.8 1017.86
  4648.0 1015.19  4695.7 1010.71  4759.2 1001.41  4832.1  993.05  4859.2  987.99
  4895.7  987.63  4921.5  985.70  4921.8  985.20  4926.1  985.70  4938.4  987.38
  4989.7  987.43  5009.6  985.79  5121.4  991.56  5160.6  992.42  5182.9  995.62
  5205.3 1000.16  5227.6 1001.84  5250.0 1006.40  5286.3 1012.28  5331.1 1017.68
  5345.0 1020.55  5367.4 1023.75  5406.5 1031.66  5428.9 1034.14  5442.9 1034.57
#Mann=5,-1,0
  4495.7   0.035       0  4648.0    0.12       0  4921.5    0.05       0
  4926.1    0.12       0  4989.7    0.12       0
Bank Sta=4921.5,4926.1
Exp/Cntr=0.3,0.1

Type RM Length L Ch R = 1,3283,449,449,449
BEGIN DESCRIPTION:
Guadalupe Tributary 66 7.0
END DESCRIPTION:
XS GIS Cut Line= 3
      2165625.01     13872375.01      2165225.00     13871975.00
      2164975.04     13871775.03
#Sta/Elev= 30
  4434.3 1055.98  4448.4 1053.71  4490.9 1042.51  4527.8 1036.09  4547.4 1032.74
  4561.6 1032.50  4575.7 1029.38  4589.9 1024.06  4614.8 1017.49  4646.4 1011.11
  4717.2  998.84  4752.5  993.73  4787.9  985.57  4816.1  981.56  4830.3  980.88
  4844.4  982.43  4971.7  983.70  4996.5  980.83  5028.0  982.59  5068.9  980.74
  5069.2  980.24  5073.5  980.74  5085.6  982.91  5114.4  991.12  5141.7  997.02
  5242.5 1015.57  5277.7 1024.34  5284.1 1026.64  5312.9 1031.03  5320.1 1031.34
#Mann=5,-1,0
  4434.3    0.12       0  4527.8    0.07       0  4614.8    0.12       0
  5068.9    0.05       0  5073.5    0.12       0
Bank Sta=5068.9,5073.5
Exp/Cntr=0.3,0.1

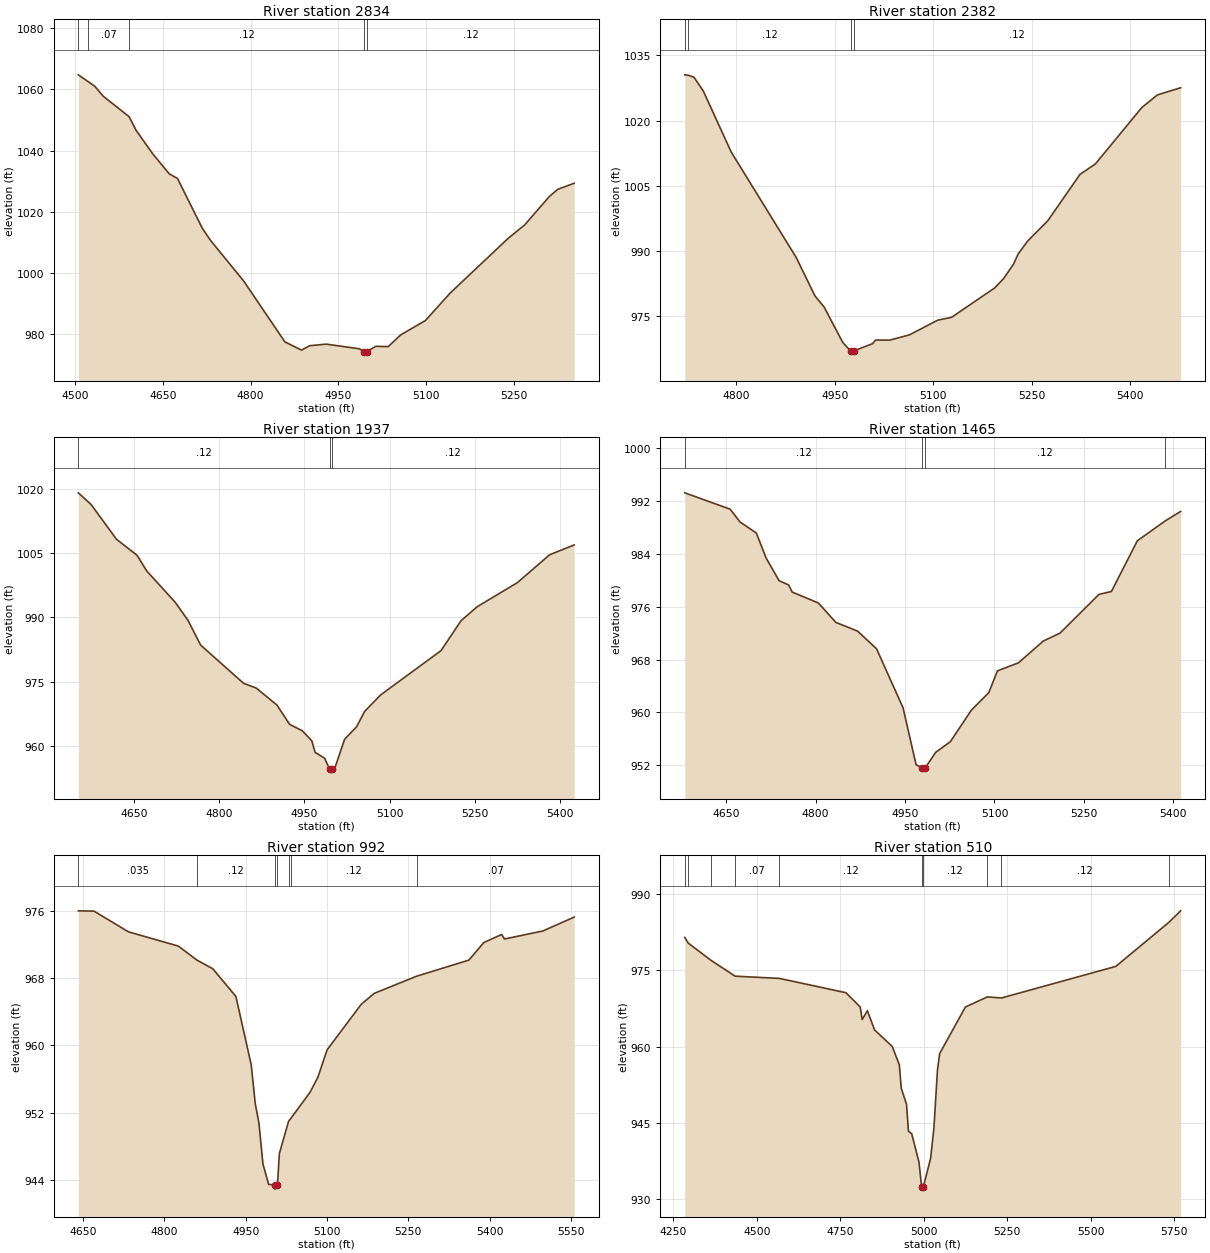
Type RM Length L Ch R = 1,2834,452,452,452
BEGIN DESCRIPTION:
Guadalupe Tributary 66 6.0
END DESCRIPTION:
XS GIS Cut Line= 3
      2165924.99     13872074.99      2165575.00     13871725.00
      2165325.01     13871475.01
#Sta/Elev= 30
  4505.3 1064.77  4521.9 1062.58  4533.6 1061.01  4547.7 1057.82  4592.2 1051.09
  4604.3 1046.60  4632.6 1038.97  4660.8 1032.43  4675.0 1030.90  4717.4 1014.65
  4731.6 1010.65  4788.1  997.44  4858.8  977.51  4887.1  974.82  4901.3  976.25
  4929.5  976.77  4986.1  975.25  4994.4  974.33  4994.7  973.83  4999.1  974.33
  5014.4  976.06  5035.6  975.95  5056.8  979.77  5099.3  984.48  5141.7  993.48
  5240.7 1011.31  5269.0 1015.70  5311.4 1025.02  5325.5 1027.34  5353.8 1029.34
#Mann=5,-1,0
  4505.3   0.035       0  4521.9    0.07       0  4592.2    0.12       0
  4994.4    0.05       0  4999.1    0.12       0
Bank Sta=4994.4,4999.1
Exp/Cntr=0.3,0.1

Type RM Length L Ch R = 1,2382,445,445,445
BEGIN DESCRIPTION:
Guadalupe Tributary 66 5.0
END DESCRIPTION:
XS GIS Cut Line= 3
      2166074.98     13871674.98      2165875.00     13871475.00
      2165475.01     13871225.01
#Sta/Elev= 30
  4722.0 1030.50  4727.6 1030.39  4736.1 1029.93  4750.3 1026.73  4792.7 1012.74
  4891.7  988.49  4920.0  979.72  4934.1  977.13  4962.4  969.00  4974.2  967.06
  4974.5  966.56  4978.6  966.56  4978.9  967.06  5007.8  968.74  5012.5  969.57
  5033.7  969.54  5063.8  970.75  5106.8  974.13  5128.0  974.79  5193.5  981.53
  5207.1  983.68  5222.4  987.05  5228.9  989.25  5243.6  992.29  5274.3  996.96
  5323.2 1007.60  5346.8 1010.03  5417.5 1022.99  5441.1 1025.88  5476.5 1027.53
#Mann=4,-1,0
  4722.0    0.07       0  4727.6    0.12       0  4974.2    0.05       0
  4978.9    0.12       0
Bank Sta=4974.2,4978.9
Exp/Cntr=0.3,0.1

Type RM Length L Ch R = 1,1937,472,472,472
BEGIN DESCRIPTION:
Guadalupe Tributary 66 4.0
END DESCRIPTION:
XS GIS Cut Line= 3
      2166325.01     13871525.02      2166125.00     13871125.00
      2165822.48     13870826.27
#Sta/Elev= 30
  4552.5 1019.01  4574.9 1016.30  4619.6 1008.20  4655.9 1004.45  4672.7 1000.84
  4723.0  993.51  4745.4  989.32  4767.7  983.55  4843.2  974.65  4865.6  973.53
  4901.9  969.59  4924.3  965.09  4946.6  963.59  4963.4  961.24  4969.0  958.57
  4985.8  957.21  4994.5  954.69  4994.9  954.19  4999.3  954.69  5003.3  954.69
  5021.0  961.61  5042.1  964.53  5056.3  968.11  5084.6  971.96  5190.7  982.26
  5226.0  989.24  5254.3  992.48  5325.0  998.09  5381.6 1004.57  5424.9 1006.88
#Mann=3,-1,0
  4552.5    0.12       0  4994.5    0.05       0  4999.3    0.12       0
Bank Sta=4994.5,4999.3
Exp/Cntr=0.3,0.1

Type RM Length L Ch R = 1,1465,473,473,473
BEGIN DESCRIPTION:
Guadalupe Tributary 66 3.0
END DESCRIPTION:
XS GIS Cut Line= 3
      2166725.28     13871298.52      2166525.00     13870925.00
      2166200.95     13870676.97
#Sta/Elev= 30
  4580.4  993.25  4656.6  990.77  4672.9  988.85  4700.5  987.16  4716.7  983.40
  4738.6  979.94  4754.6  979.30  4760.6  978.22  4804.4  976.57  4834.0  973.62
  4870.2  972.31  4902.1  969.63  4946.6  960.69  4968.5  952.05  4979.1  951.60
  4979.5  951.10  4983.9  951.60  5001.4  953.95  5026.0  955.56  5061.3  960.35
  5090.4  962.98  5104.9  966.28  5140.3  967.51  5181.9  970.80  5209.9  972.00
  5275.3  977.87  5296.2  978.31  5339.7  985.99  5386.7  989.01  5412.3  990.43
#Mann=4,-1,0
  4580.4    0.12       0  4979.1    0.05       0  4983.9    0.12       0
  5386.7    0.07       0
Bank Sta=4979.1,4983.9
Exp/Cntr=0.3,0.1

Type RM Length L Ch R = 1,992,482,482,482
BEGIN DESCRIPTION:
Guadalupe Tributary 66 2.0
END DESCRIPTION:
XS GIS Cut Line= 3
      2167086.36     13870864.46      2166825.00     13870625.00
      2166288.89     13870462.05
#Sta/Elev= 30
  4641.2  976.06  4670.2  976.02  4733.9  973.55  4825.8  971.85  4860.1  970.18
  4889.3  969.15  4931.9  965.85  4960.2  957.69  4967.6  953.07  4974.4  950.76
  4981.8  945.88  4992.3  943.44  5003.7  943.37  5004.0  942.87  5008.6  943.37
  5012.1  947.11  5029.2  950.98  5033.2  951.29  5068.8  954.43  5083.1  956.20
  5100.2  959.48  5162.9  964.89  5186.9  966.21  5265.2  968.26  5361.7  970.18
  5389.4  972.28  5422.2  973.24  5427.5  972.70  5498.4  973.66  5556.0  975.31
#Mann=7,-1,0
  4641.2   0.035       0  4860.1    0.12       0  5003.7    0.05       0
  5008.6    0.12       0  5029.2    0.07       0  5033.2    0.12       0
  5265.2    0.07       0
Bank Sta=5003.7,5008.6
Exp/Cntr=0.3,0.1

Type RM Length L Ch R = 1,510,242,242,242
BEGIN DESCRIPTION:
Guadalupe Tributary 66 1.0
END DESCRIPTION:
XS GIS Cut Line= 3
      2167187.11     13870791.61      2166825.00     13870175.00
      2166089.91     13869944.36
#Sta/Elev= 30
  4284.5  981.51  4294.6  980.40  4363.7  976.96  4435.2  973.87  4568.0  973.43
  4767.2  970.61  4810.1  967.79  4815.9  965.32  4831.6  967.06  4853.0  963.27
  4905.9  960.03  4927.3  956.38  4933.1  951.76  4948.8  948.62  4954.6  943.32
  4964.5  942.78  4985.9  937.26  4994.1  932.39  4994.5  931.89  4999.3  932.39
  5021.0  937.95  5031.0  944.05  5041.5  955.42  5048.2  958.63  5125.3  967.79
  5190.8  969.78  5233.1  969.57  5576.0  975.80  5735.1  984.50  5770.0  986.75
#Mann=10,-1,0
  4284.5    0.12       0  4294.6    0.07       0  4363.7   0.035       0
  4435.2    0.07       0  4568.0    0.12       0  4994.1    0.05       0
  4999.3    0.12       0  5190.8    0.07       0  5233.1    0.12       0
  5735.1   0.035       0
Bank Sta=4994.1,4999.3
Exp/Cntr=0.3,0.1

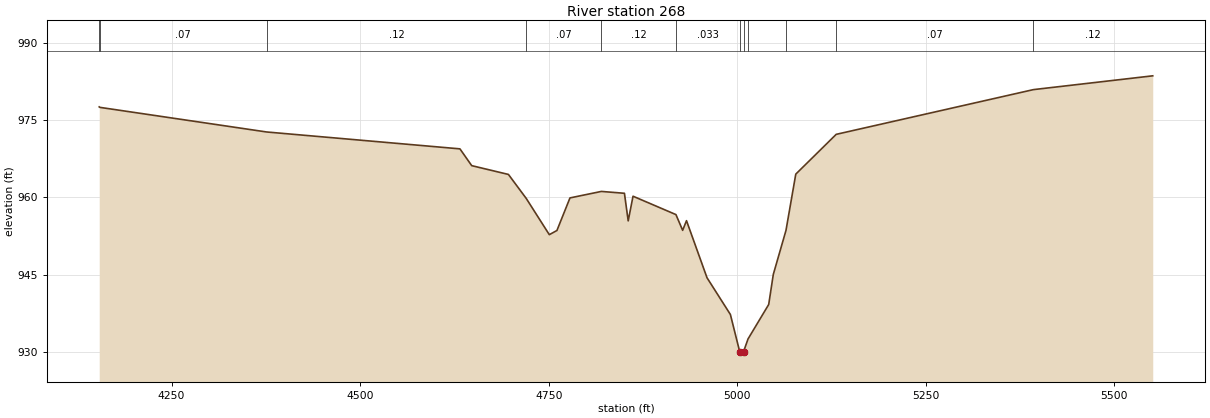
Type RM Length L Ch R = 1,268,0,0,0
BEGIN DESCRIPTION:
Guadalupe Tributary 66 0.0
END DESCRIPTION:
XS GIS Cut Line= 4
      2167215.16     13870710.84      2166922.48     13870220.74
      2166954.64     13869985.79      2166468.50     13869653.38
#Sta/Elev= 30
  4154.0  977.57  4155.0  977.47  4376.0  972.69  4632.3  969.41  4647.9  966.15
  4696.6  964.44  4720.2  959.78  4750.8  952.74  4760.9  953.55  4778.2  959.88
  4819.8  961.14  4850.4  960.78  4855.4  955.42  4861.8  960.21  4918.7  956.64
  4927.6  953.58  4932.7  955.46  4959.9  944.37  4990.9  937.23  5003.2  930.03
  5003.6  929.53  5008.4  930.03  5014.3  932.48  5041.7  939.17  5047.8  945.02
  5064.6  953.56  5077.6  964.50  5131.2  972.23  5392.7  980.92  5550.9  983.60
#Mann=12,-1,0
  4154.0    0.12       0  4155.0    0.07       0  4376.0    0.12       0
  4720.2    0.07       0  4819.8    0.12       0  4918.7   0.033       0
  5003.2   0.033       0  5008.4   0.033       0  5014.3    0.07       0
  5064.6    0.12       0  5131.2    0.07       0  5392.7    0.12       0
Bank Sta=5003.2,5008.4
Exp/Cntr=0.3,0.1

Chan Stop Cuts=-1