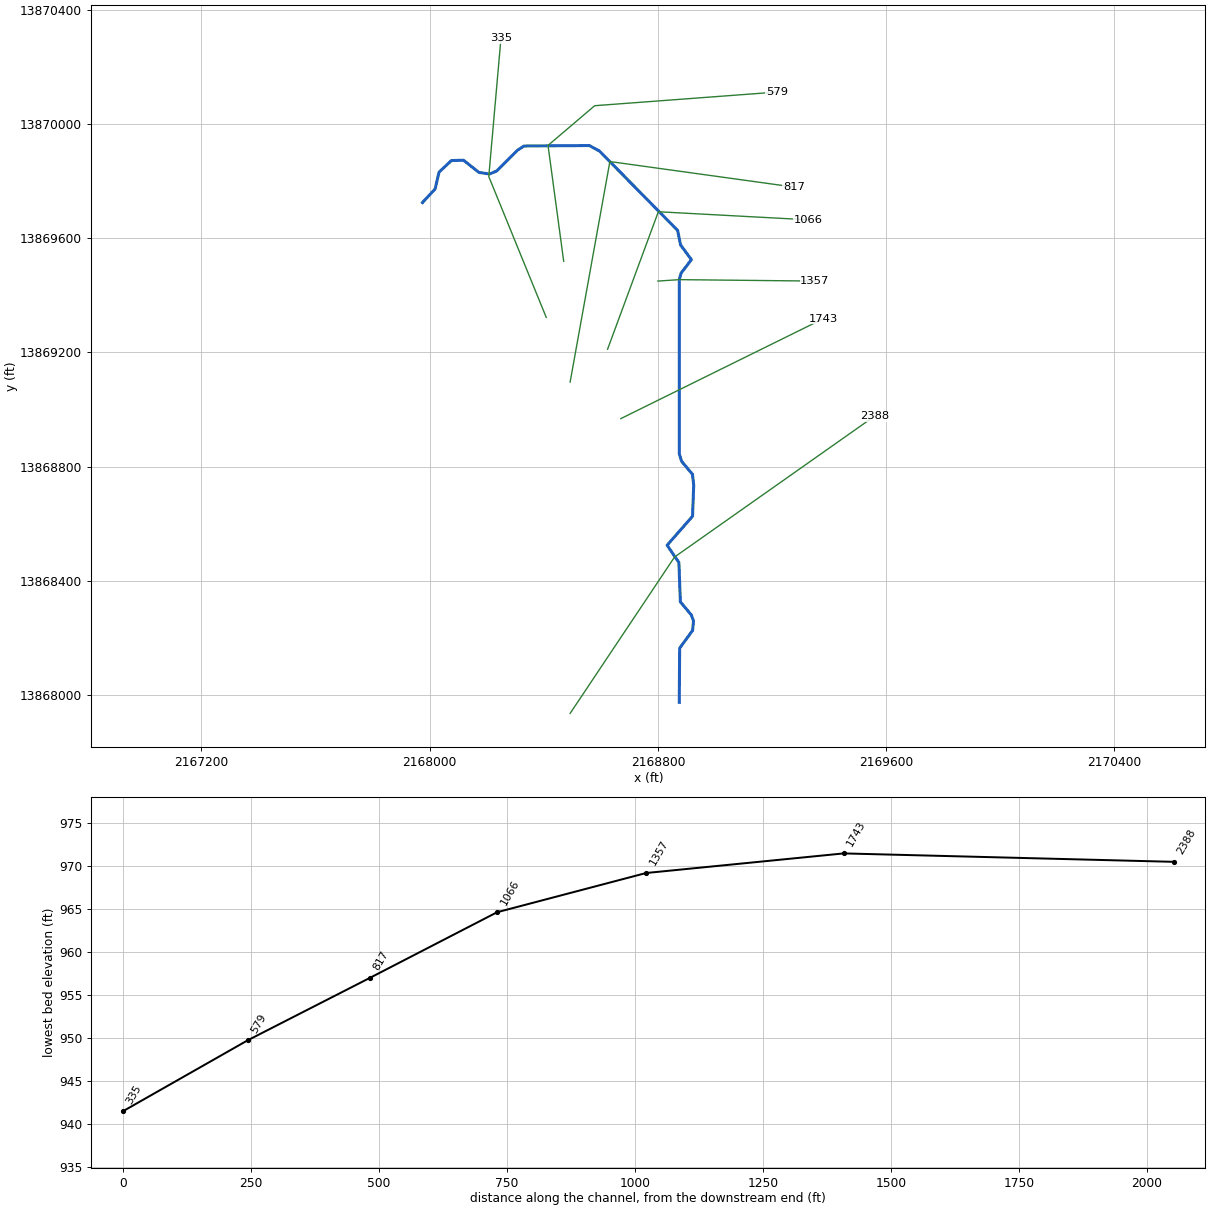
--- Guadalupe Tributary 67.prj (project) ---

Proj Title=Guadalupe Tributary 67 Base Level Engineering
Current Plan=p01
Default Exp/Contr=0.3,0.1
English Units
Geom File=g01
Flow File=f01
Plan File=p01
BEGIN DESCRIPTION:
Guadalupe Tributary 67
END DESCRIPTION:

--- Guadalupe Tributary 67.p01 (plan) ---

Plan Title=Multiple Run
Short Identifier=Multiple
Geom File=g01
Flow File=f01
Subcritical Flow
K Sum by GR= 0
Std Step Tol= 0.01
Critical Tol= 0.01
Num of Std Step Trials= 20
Max Error Tol= 0.3
Flow Tol Ratio= 0.001
Split Flow NTrial= 30
Split Flow Tol= 0.02
Split Flow Ratio= 0.02
Log Output Level= 0
Friction Slope Method= 1
Unsteady Friction Slope Method= 2
Unsteady Bridges Friction Slope Method= 1
Parabolic Critical Depth
Global Vel Dist=  1 , 1 , 1
Global Log Level= 0
CheckData=True
Encroach Param= -1, 0, 0, 0
BEGIN DESCRIPTION:
Multiple Run
END DESCRIPTION:

--- Guadalupe Tributary 67.f01 (steady flow) ---

Flow Title=Multiple
Number of Profiles=7
Profile Names=10-year,25-year,50-year,1pct_min,100-year,1pct_plu,500-year
River Rch & RM= Guadalupe Tribut,Reach-1,2388
     241     369     479     303     605    1208     950
Boundary for River Rch & Prof#=Guadalupe Tribut,Reach-1,1
Up Type=0
Dn Type=3
Dn Slope=0.005
Boundary for River Rch & Prof#=Guadalupe Tribut,Reach-1,2
Up Type=0
Dn Type=3
Dn Slope=0.005
Boundary for River Rch & Prof#=Guadalupe Tribut,Reach-1,3
Up Type=0
Dn Type=3
Dn Slope=0.005
Boundary for River Rch & Prof#=Guadalupe Tribut,Reach-1,4
Up Type=0
Dn Type=3
Dn Slope=0.005
Boundary for River Rch & Prof#=Guadalupe Tribut,Reach-1,5
Up Type=0
Dn Type=3
Dn Slope=0.005
Boundary for River Rch & Prof#=Guadalupe Tribut,Reach-1,6
Up Type=0
Dn Type=3
Dn Slope=0.005
Boundary for River Rch & Prof#=Guadalupe Tribut,Reach-1,7
Up Type=0
Dn Type=3
Dn Slope=0.005

--- Guadalupe Tributary 67.g01 (geometry) ---

Geom Title=Existing Conditions

River Reach=Guadalupe Tribut,Reach-1
Reach XY= 30
      2168875.00     13867975.00      2168876.23     13868164.51
      2168921.63     13868226.74      2168924.91     13868259.61
      2168917.19     13868280.92      2168878.82     13868326.56
      2168873.60     13868464.56      2168832.33     13868525.10
      2168921.45     13868626.47      2168925.50     13868735.17
      2168921.23     13868773.43      2168883.14     13868818.94
      2168875.07     13868845.03      2168875.18     13869455.02
      2168881.02     13869477.45      2168917.47     13869525.01
      2168879.45     13869576.65      2168869.19     13869627.29
      2168595.16     13869905.40      2168559.84     13869924.62
      2168330.86     13869922.93      2168308.25     13869908.53
      2168234.67     13869835.21      2168209.66     13869824.96
      2168172.81     13869830.39      2168118.84     13869873.21
      2168076.42     13869871.97      2168032.93     13869831.50
      2168019.28     13869772.69      2167975.00     13869725.00

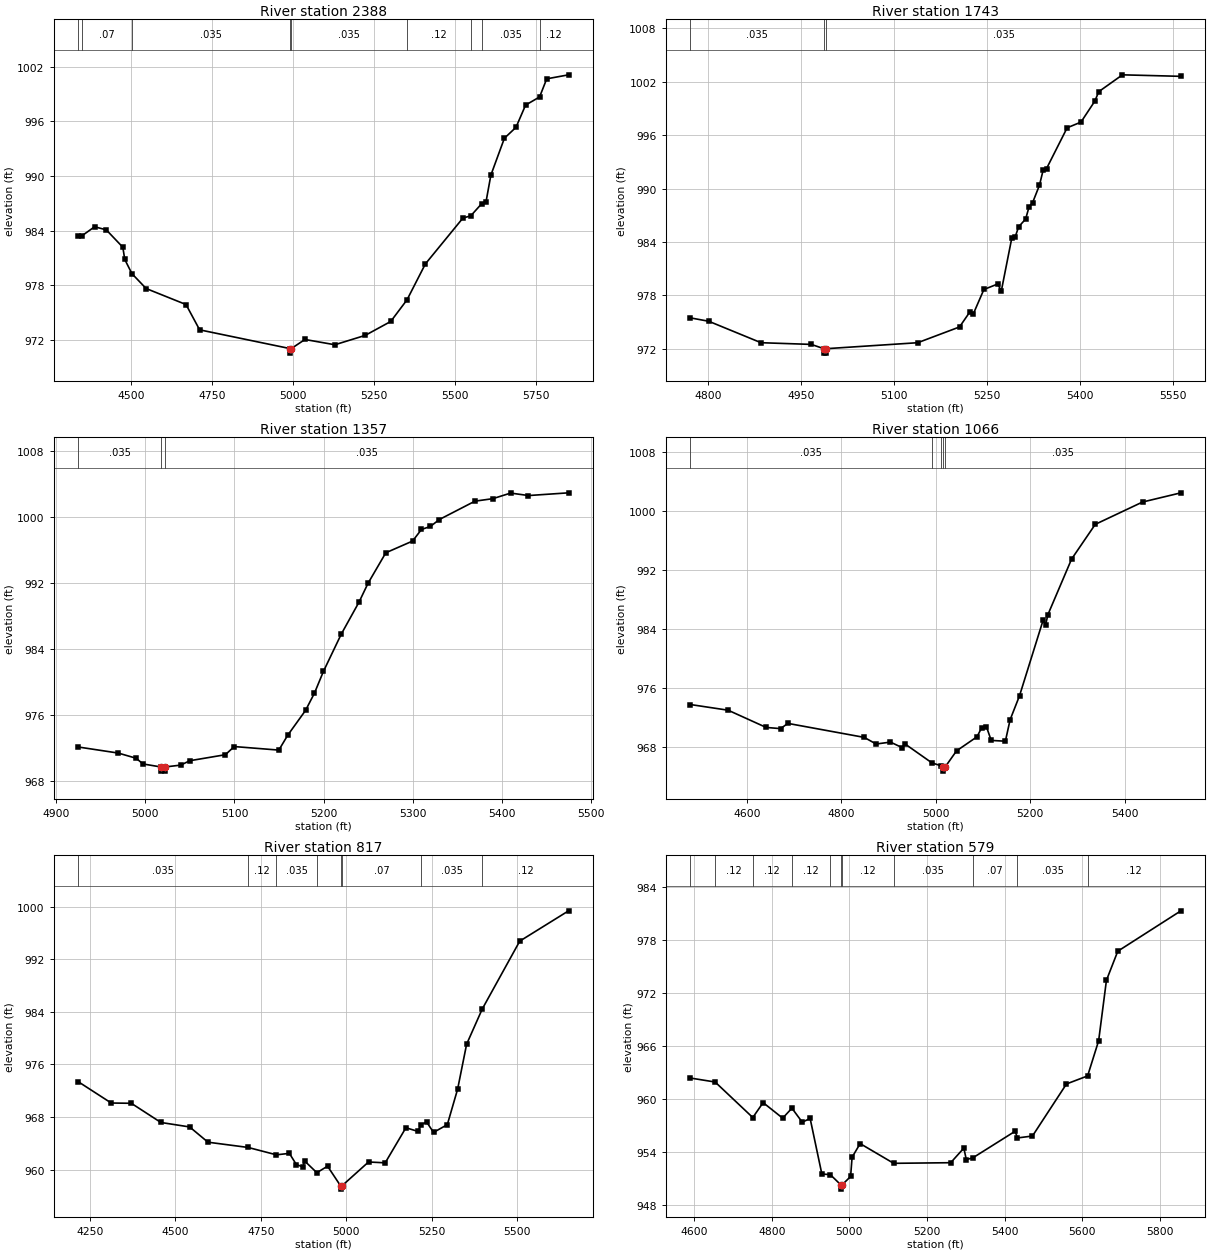
Type RM Length L Ch R = 1,2388,645,645,645
BEGIN DESCRIPTION:
Guadalupe Tributary 67 5.0
END DESCRIPTION:
XS GIS Cut Line= 3
      2168492.46     13867936.26      2168858.57     13868483.85
      2169558.61     13868976.47
#Sta/Elev= 30
  4336.7  983.36  4348.3  983.42  4387.8  984.42  4423.8  984.08  4474.9  982.17
  4480.9  980.83  4502.9  979.27  4546.9  977.63  4670.1  975.87  4712.1  973.09
  4991.1  971.03  4991.3  970.53  4995.1  971.03  5037.3  972.03  5129.7  971.45
  5223.4  972.48  5302.2  974.01  5352.5  976.39  5409.3  980.34  5525.2  985.38
  5549.3  985.62  5583.2  986.96  5596.6  987.19  5611.4  990.09  5653.2  994.15
  5689.0  995.35  5718.6  997.79  5761.9  998.69  5783.9 1000.68  5851.4 1001.12
#Mann=9,-1,0
  4336.7   0.035       0  4348.3    0.07       0  4502.9   0.035       0
  4991.1   0.035       0  4995.1   0.035       0  5352.5    0.12       0
  5549.3    0.07       0  5583.2   0.035       0  5761.9    0.12       0
Bank Sta=4991.1,4995.1
Exp/Cntr=0.3,0.1

Type RM Length L Ch R = 1,1743,386,386,386
BEGIN DESCRIPTION:
Guadalupe Tributary 67 4.0
END DESCRIPTION:
XS GIS Cut Line= 2
      2168670.22     13868968.48      2169379.53     13869318.13
#Sta/Elev= 30
  4771.7  975.47  4801.3  975.09  4885.6  972.68  4966.6  972.49  4986.9  972.01
  4987.1  971.51  4990.6  971.51  4990.9  972.01  5138.2  972.68  5205.6  974.45
  5222.4  976.15  5228.0  975.94  5244.9  978.66  5267.4  979.28  5272.9  978.46
  5289.8  984.41  5295.4  984.58  5301.0  985.71  5312.2  986.57  5317.8  987.96
  5323.4  988.41  5334.5  990.37  5340.3  992.03  5345.9  992.24  5379.1  996.82
  5401.4  997.46  5423.7  999.81  5430.1 1000.88  5468.3 1002.77  5562.5 1002.60
#Mann=3,-1,0
  4771.7   0.035       0  4986.9   0.035       0  4990.9   0.035       0
Bank Sta=4986.9,4990.9
Exp/Cntr=0.3,0.1

Type RM Length L Ch R = 1,1357,291,291,291
BEGIN DESCRIPTION:
Guadalupe Tributary 67 3.5
END DESCRIPTION:
XS GIS Cut Line= 3
      2168799.95     13869450.00      2168875.18     13869455.02
      2169349.96     13869450.00
#Sta/Elev= 30
  4924.6  972.16  4969.7  971.42  4989.8  970.79  4997.4  970.10  5017.8  969.73
  5018.1  969.23  5021.6  969.23  5021.8  969.73  5039.8  969.96  5049.8  970.49
  5089.8  971.22  5099.8  972.21  5149.8  971.78  5159.8  973.59  5179.8  976.60
  5189.8  978.70  5199.8  981.32  5219.8  985.84  5239.8  989.74  5249.8  992.00
  5269.8  995.71  5299.8  997.13  5309.8  998.54  5319.8  998.90  5329.8  999.74
  5369.8 1001.97  5389.8 1002.27  5409.8 1002.95  5429.8 1002.65  5474.8 1002.98
#Mann=3,-1,0
  4924.6   0.035       0  5017.8   0.035       0  5021.8   0.035       0
Bank Sta=5017.8,5021.8
Exp/Cntr=0.3,0.1

Type RM Length L Ch R = 1,1066,249,249,249
BEGIN DESCRIPTION:
Guadalupe Tributary 67 3.0
END DESCRIPTION:
XS GIS Cut Line= 3
      2168623.68     13869211.37      2168801.55     13869692.79
      2169326.07     13869664.62
#Sta/Elev= 30
  4480.6  973.71  4560.5  972.94  4641.1  970.60  4671.5  970.44  4687.0  971.15
  4848.7  969.25  4873.8  968.35  4904.2  968.61  4929.3  967.85  4934.6  968.38
  4992.2  965.78  5011.9  965.39  5015.3  965.17  5015.6  964.67  5019.3  965.17
  5044.1  967.42  5087.4  969.33  5097.4  970.57  5107.4  970.70  5117.5  968.84
  5147.5  968.73  5157.5  971.64  5177.5  974.91  5227.5  985.18  5232.5  984.49
  5237.6  985.92  5287.7  993.46  5337.8  998.17  5437.9 1001.20  5519.1 1002.45
#Mann=5,-1,0
  4480.6   0.035       0  4992.2    0.07       0  5011.9   0.035       0
  5015.3    0.05       0  5019.3   0.035       0
Bank Sta=5015.3,5019.3
Exp/Cntr=0.3,0.1

Type RM Length L Ch R = 1,817,238,238,238
BEGIN DESCRIPTION:
Guadalupe Tributary 67 2.0
END DESCRIPTION:
XS GIS Cut Line= 3
      2168492.40     13869096.38      2168631.74     13869868.51
      2169276.59     13869779.23
#Sta/Elev= 30
  4215.4  973.38  4312.5  970.12  4371.2  970.08  4457.9  967.16  4542.0  966.48
  4595.6  964.16  4713.1  963.36  4795.9  962.24  4833.9  962.46  4854.2  960.76
  4873.5  960.40  4878.6  961.30  4914.2  959.52  4945.6  960.51  4983.7  957.52
  4984.0  957.02  4987.7  957.52  5065.5  961.15  5114.3  961.02  5174.9  966.36
  5209.1  965.82  5220.5  966.85  5235.5  967.24  5255.7  965.65  5296.1  966.83
  5326.3  972.24  5352.6  979.07  5398.3  984.42  5508.1  994.75  5651.0  999.36
#Mann=8,-1,0
  4215.4   0.035       0  4713.1    0.12       0  4795.9   0.035       0
  4914.2    0.07       0  4983.7    0.05       0  4987.7    0.07       0
  5220.5   0.035       0  5398.3    0.12       0
Bank Sta=4983.7,4987.7
Exp/Cntr=0.3,0.1

Type RM Length L Ch R = 1,579,244,244,244
BEGIN DESCRIPTION:
Guadalupe Tributary 67 1.5
END DESCRIPTION:
XS GIS Cut Line= 4
      2168469.85     13869519.32      2168414.95     13869925.12
      2168578.54     13870064.11      2169216.30     13870111.82
#Sta/Elev= 30
  4590.5  962.35  4654.3  961.90  4751.3  957.88  4777.9  959.57  4828.3  957.81
  4852.1  958.94  4878.8  957.35  4899.0  957.78  4929.2  951.49  4951.0  951.42
  4977.7  950.28  4977.9  949.78  4981.7  950.28  5003.3  951.21  5007.1  953.39
  5027.9  954.93  5114.3  952.70  5261.2  952.77  5295.0  954.42  5301.4  953.12
  5318.2  953.32  5427.2  956.33  5433.0  955.57  5471.8  955.79  5559.4  961.68
  5613.9  962.59  5642.3  966.57  5662.4  973.41  5691.6  976.70  5854.2  981.27
#Mann=11,-1,0
  4590.5   0.035       0  4654.3    0.12       0  4751.3    0.12       0
  4852.1    0.12       0  4951.0    0.12       0  4977.7    0.05       0
  4981.7    0.12       0  5114.3   0.035       0  5318.2    0.07       0
  5433.0   0.035       0  5613.9    0.12       0
Bank Sta=4977.7,4981.7
Exp/Cntr=0.3,0.1

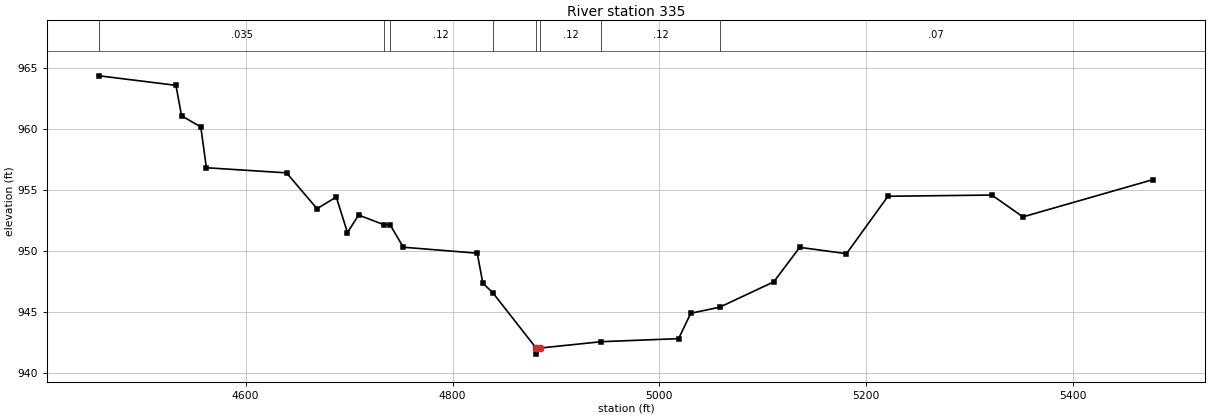
Type RM Length L Ch R = 1,335,0,0,0
BEGIN DESCRIPTION:
Guadalupe Tributary 67 1.0
END DESCRIPTION:
XS GIS Cut Line= 3
      2168408.68     13869322.82      2168207.29     13869816.01
      2168250.00     13870300.00
#Sta/Elev= 30
  4458.4  964.35  4532.6  963.57  4538.0  961.07  4556.6  960.16  4562.0  956.81
  4639.5  956.39  4669.0  953.45  4687.6  954.41  4698.4  951.49  4709.2  952.93
  4733.9  952.13  4739.5  952.15  4752.4  950.29  4823.9  949.80  4829.3  947.34
  4838.8  946.57  4880.8  942.02  4881.0  941.52  4884.8  942.02  4943.8  942.54
  5018.6  942.79  5030.3  944.87  5058.3  945.37  5110.6  947.45  5135.7  950.28
  5180.9  949.76  5221.0  954.47  5321.4  954.57  5351.5  952.78  5477.0  955.83
#Mann=8,-1,0
  4458.4   0.035       0  4733.9    0.12       0  4739.5    0.12       0
  4838.8    0.12       0  4880.8    0.05       0  4884.8    0.12       0
  4943.8    0.12       0  5058.3    0.07       0
Bank Sta=4880.8,4884.8
Exp/Cntr=0.3,0.1

Chan Stop Cuts=-1