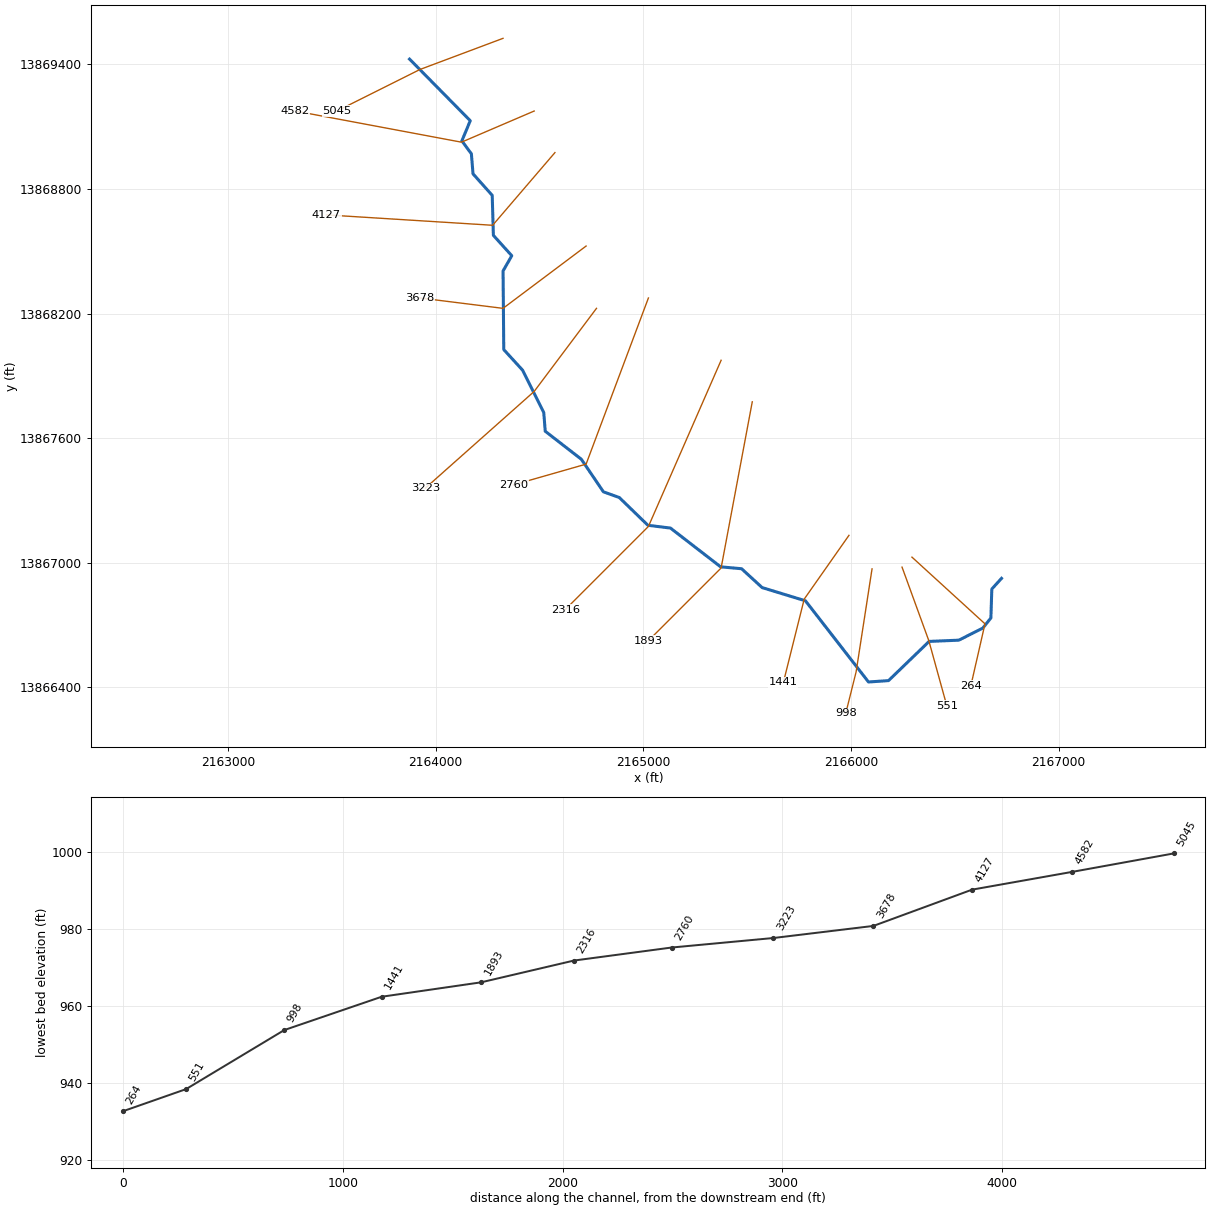
--- Guadalupe Tributary 68.prj (project) ---

Proj Title=Guadalupe Tributary 68 Base Level Engineering
Current Plan=p01
Default Exp/Contr=0.3,0.1
English Units
Geom File=g01
Flow File=f01
Plan File=p01
BEGIN DESCRIPTION:
Guadalupe Tributary 68
END DESCRIPTION:

--- Guadalupe Tributary 68.p01 (plan) ---

Plan Title=Multiple Run
Short Identifier=Multiple
Geom File=g01
Flow File=f01
Subcritical Flow
K Sum by GR= 0
Std Step Tol= 0.01
Critical Tol= 0.01
Num of Std Step Trials= 20
Max Error Tol= 0.3
Flow Tol Ratio= 0.001
Split Flow NTrial= 30
Split Flow Tol= 0.02
Split Flow Ratio= 0.02
Log Output Level= 0
Friction Slope Method= 1
Unsteady Friction Slope Method= 2
Unsteady Bridges Friction Slope Method= 1
Parabolic Critical Depth
Global Vel Dist=  1 , 1 , 1
Global Log Level= 0
CheckData=True
Encroach Param= -1, 0, 0, 0
BEGIN DESCRIPTION:
Multiple Run
END DESCRIPTION:

--- Guadalupe Tributary 68.f01 (steady flow) ---

Flow Title=Multiple
Number of Profiles=7
Profile Names=10-year,25-year,50-year,1pct_min,100-year,1pct_plu,500-year
River Rch & RM= Guadalupe Tribut,Reach-1,5045
    1638    2844    4016    2743    5474   10922   10072
Boundary for River Rch & Prof#=Guadalupe Tribut,Reach-1,1
Up Type=0
Dn Type=3
Dn Slope=0.005
Boundary for River Rch & Prof#=Guadalupe Tribut,Reach-1,2
Up Type=0
Dn Type=3
Dn Slope=0.005
Boundary for River Rch & Prof#=Guadalupe Tribut,Reach-1,3
Up Type=0
Dn Type=3
Dn Slope=0.005
Boundary for River Rch & Prof#=Guadalupe Tribut,Reach-1,4
Up Type=0
Dn Type=3
Dn Slope=0.005
Boundary for River Rch & Prof#=Guadalupe Tribut,Reach-1,5
Up Type=0
Dn Type=3
Dn Slope=0.005
Boundary for River Rch & Prof#=Guadalupe Tribut,Reach-1,6
Up Type=0
Dn Type=3
Dn Slope=0.005
Boundary for River Rch & Prof#=Guadalupe Tribut,Reach-1,7
Up Type=0
Dn Type=3
Dn Slope=0.005

--- Guadalupe Tributary 68.g01 (geometry) ---

Geom Title=Existing Conditions

River Reach=Guadalupe Tribut,Reach-1
Reach XY= 30
      2163875.00     13869425.00      2164167.18     13869128.41
      2164126.86     13869031.13      2164172.62     13868969.03
      2164180.54     13868872.58      2164272.93     13868769.14
      2164278.56     13868576.46      2164367.19     13868478.41
      2164325.19     13868405.02      2164328.55     13868026.47
      2164419.15     13867927.29      2164521.14     13867723.34
      2164528.16     13867633.34      2164701.99     13867498.47
      2164808.29     13867341.64      2164884.68     13867314.22
      2165022.57     13867180.52      2165131.16     13867167.12
      2165372.58     13866980.54      2165473.50     13866971.37
      2165572.58     13866880.54      2165781.07     13866816.87
      2166084.63     13866426.08      2166181.17     13866432.76
      2166376.47     13866621.46      2166519.48     13866627.36
      2166635.06     13866685.61      2166673.86     13866734.43
      2166678.30     13866873.63      2166725.00     13866925.00

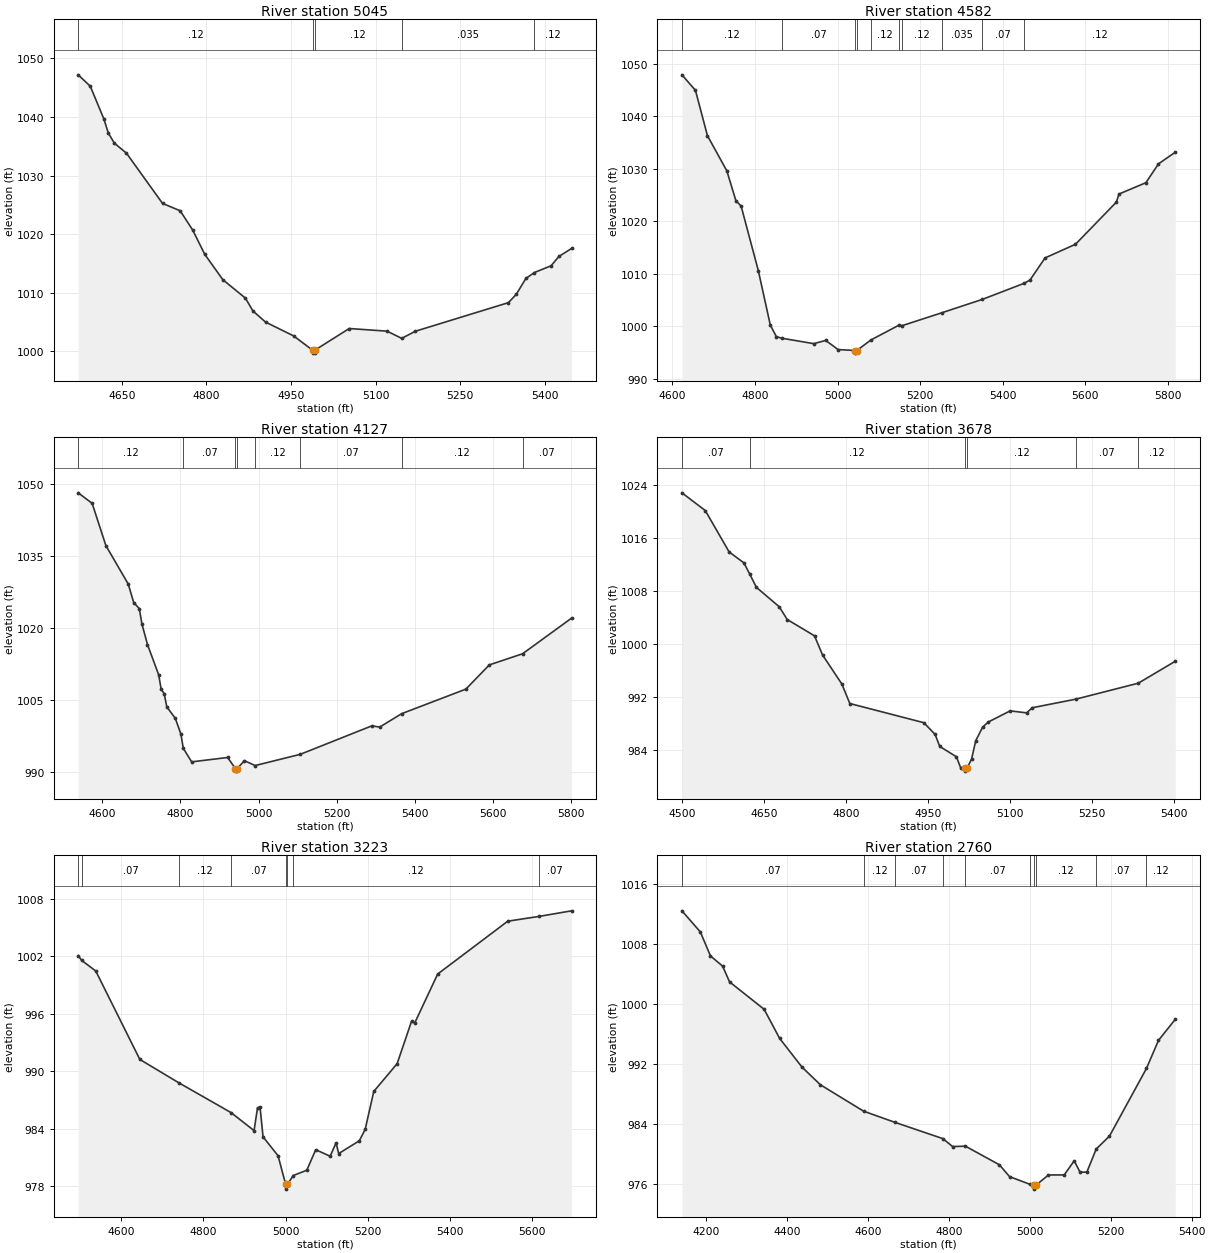
Type RM Length L Ch R = 1,5045,463,463,463
BEGIN DESCRIPTION:
Guadalupe Tributary 68 11.0
END DESCRIPTION:
XS GIS Cut Line= 3
      2164325.01     13869525.00      2163925.00     13869375.00
      2163525.02     13869175.01
#Sta/Elev= 30
  4572.8 1047.19  4594.2 1045.24  4618.2 1039.68  4626.2 1037.25  4636.9 1035.52
  4658.3 1033.82  4722.3 1025.24  4753.5 1023.99  4775.7 1020.70  4797.1 1016.55
  4829.1 1012.23  4869.2 1009.07  4882.5 1006.89  4904.8 1004.99  4954.6 1002.63
  4988.2 1000.19  4988.5  999.69  4992.0  999.69  4992.2 1000.19  5053.1 1003.89
  5120.2 1003.44  5146.2 1002.21  5170.5 1003.43  5335.4 1008.31  5349.4 1009.75
  5366.2 1012.43  5381.4 1013.45  5410.9 1014.60  5424.9 1016.20  5447.2 1017.55
#Mann=5,-1,0
  4572.8    0.12       0  4988.2    0.05       0  4992.2    0.12       0
  5146.2   0.035       0  5381.4    0.12       0
Bank Sta=4988.2,4992.2
Exp/Cntr=0.3,0.1

Type RM Length L Ch R = 1,4582,455,455,455
BEGIN DESCRIPTION:
Guadalupe Tributary 68 10.0
END DESCRIPTION:
XS GIS Cut Line= 3
      2164475.04     13869175.02      2164125.00     13869025.00
      2163324.97     13869175.00
#Sta/Elev= 30
  4623.0 1047.94  4655.7 1044.98  4684.7 1036.35  4731.8 1029.62  4753.6 1023.96
  4766.3 1022.92  4808.0 1010.60  4837.0 1000.24  4851.5  998.05  4864.1  997.74
  4942.2  996.70  4971.2  997.31  5001.1  995.57  5042.5  995.39  5042.8  994.89
  5046.6  995.39  5080.9  997.41  5148.6 1000.22  5156.4 1000.13  5253.8 1002.62
  5350.3 1005.13  5451.1 1008.18  5465.9 1008.82  5502.4 1013.04  5576.1 1015.64
  5675.3 1023.69  5681.3 1025.21  5746.6 1027.38  5777.1 1030.97  5817.8 1033.19
#Mann=10,-1,0
  4623.0    0.12       0  4864.1    0.07       0  5042.5    0.05       0
  5046.6    0.07       0  5080.9    0.12       0  5148.6   0.035       0
  5156.4    0.12       0  5253.8   0.035       0  5350.3    0.07       0
  5451.1    0.12       0
Bank Sta=5042.5,5046.6
Exp/Cntr=0.3,0.1

Type RM Length L Ch R = 1,4127,449,449,449
BEGIN DESCRIPTION:
Guadalupe Tributary 68 9.0
END DESCRIPTION:
XS GIS Cut Line= 3
      2164575.00     13868975.00      2164275.00     13868625.00
      2163475.03     13868675.00
#Sta/Elev= 30
  4538.6 1048.22  4574.3 1046.03  4609.4 1037.24  4666.5 1029.25  4680.7 1025.37
  4695.0 1024.11  4701.6 1020.93  4715.9 1016.63  4744.4 1010.36  4751.0 1007.31
  4758.7 1006.41  4765.2 1003.68  4787.2 1001.25  4801.5  997.96  4807.5  995.03
  4828.9  992.21  4921.1  993.12  4941.0  990.78  4941.2  990.28  4945.1  990.78
  4963.9  992.46  4991.3  991.44  5106.6  993.77  5290.1  999.71  5310.2  999.45
  5366.3 1002.24  5530.6 1007.35  5590.7 1012.40  5675.7 1014.71  5801.1 1022.13
#Mann=8,-1,0
  4538.6    0.12       0  4807.5    0.07       0  4941.0    0.05       0
  4945.1    0.07       0  4991.3    0.12       0  5106.6    0.07       0
  5366.3    0.12       0  5675.7    0.07       0
Bank Sta=4941,4945.1
Exp/Cntr=0.3,0.1

Type RM Length L Ch R = 1,3678,455,455,455
BEGIN DESCRIPTION:
Guadalupe Tributary 68 8.0
END DESCRIPTION:
XS GIS Cut Line= 3
      2164724.99     13868524.99      2164325.00     13868225.00
      2163925.00     13868275.00
#Sta/Elev= 30
  4500.0 1022.80  4542.7 1020.13  4586.4 1013.89  4613.5 1012.24  4623.9 1010.58
  4636.4 1008.55  4678.1 1005.63  4692.7 1003.71  4742.7 1001.25  4757.3  998.38
  4792.7  993.99  4807.3  991.05  4942.7  988.16  4963.5  986.39  4971.9  984.58
  5002.5  983.02  5010.1  981.38  5018.0  981.36  5018.3  980.86  5022.2  981.36
  5030.2  982.68  5037.8  985.45  5050.4  987.48  5060.5  988.25  5100.8  989.94
  5131.0  989.64  5141.1  990.41  5221.2  991.71  5335.3  994.11  5403.1  997.42
#Mann=6,-1,0
  4500.0    0.07       0  4623.9    0.12       0  5018.0    0.05       0
  5022.2    0.12       0  5221.2    0.07       0  5335.3    0.12       0
Bank Sta=5018,5022.2
Exp/Cntr=0.3,0.1

Type RM Length L Ch R = 1,3223,463,463,463
BEGIN DESCRIPTION:
Guadalupe Tributary 68 7.0
END DESCRIPTION:
XS GIS Cut Line= 3
      2164775.01     13868225.02      2164475.00     13867825.00
      2163950.99     13867359.40
#Sta/Elev= 30
  4495.1 1002.05  4503.7 1001.56  4537.8 1000.46  4645.1  991.24  4740.2  988.80
  4867.1  985.70  4923.2  983.82  4931.6  986.20  4937.8  986.26  4945.1  983.17
  4981.6  981.20  5000.1  978.22  5000.4  977.72  5004.4  978.22  5018.7  979.14
  5051.6  979.69  5073.3  981.83  5108.4  981.15  5122.7  982.53  5129.3  981.43
  5179.5  982.76  5193.7  983.95  5214.6  987.90  5271.5  990.80  5306.6  995.22
  5314.2  995.03  5370.2 1000.14  5540.8 1005.65  5615.8 1006.14  5696.1 1006.73
#Mann=8,-1,0
  4495.1   0.035       0  4503.7    0.07       0  4740.2    0.12       0
  4867.1    0.07       0  5000.1    0.05       0  5004.4    0.07       0
  5018.7    0.12       0  5615.8    0.07       0
Bank Sta=5000.1,5004.4
Exp/Cntr=0.3,0.1

Type RM Length L Ch R = 1,2760,444,444,444
BEGIN DESCRIPTION:
Guadalupe Tributary 68 6.0
END DESCRIPTION:
XS GIS Cut Line= 3
      2165025.01     13868275.04      2164725.00     13867475.00
      2164375.05     13867375.01
#Sta/Elev= 30
  4141.2 1012.44  4186.6 1009.62  4211.6 1006.42  4241.8 1005.04  4258.7 1002.95
  4344.2  999.28  4382.4  995.40  4437.6  991.56  4483.0  989.20  4589.7  985.67
  4667.9  984.16  4785.5  982.00  4809.6  980.94  4841.3  980.99  4925.3  978.50
  4950.3  976.92  5000.4  975.90  5010.1  975.75  5010.4  975.25  5015.0  975.75
  5046.3  977.14  5085.3  977.15  5110.0  979.04  5124.3  977.52  5141.2  977.52
  5164.3  980.61  5197.1  982.34  5288.4  991.38  5318.0  995.12  5359.6  997.95
#Mann=10,-1,0
  4141.2    0.07       0  4589.7    0.12       0  4667.9    0.07       0
  4785.5    0.12       0  4841.3    0.07       0  5000.4    0.12       0
  5010.1    0.05       0  5015.0    0.12       0  5164.3    0.07       0
  5288.4    0.12       0
Bank Sta=5010.1,5015
Exp/Cntr=0.3,0.1

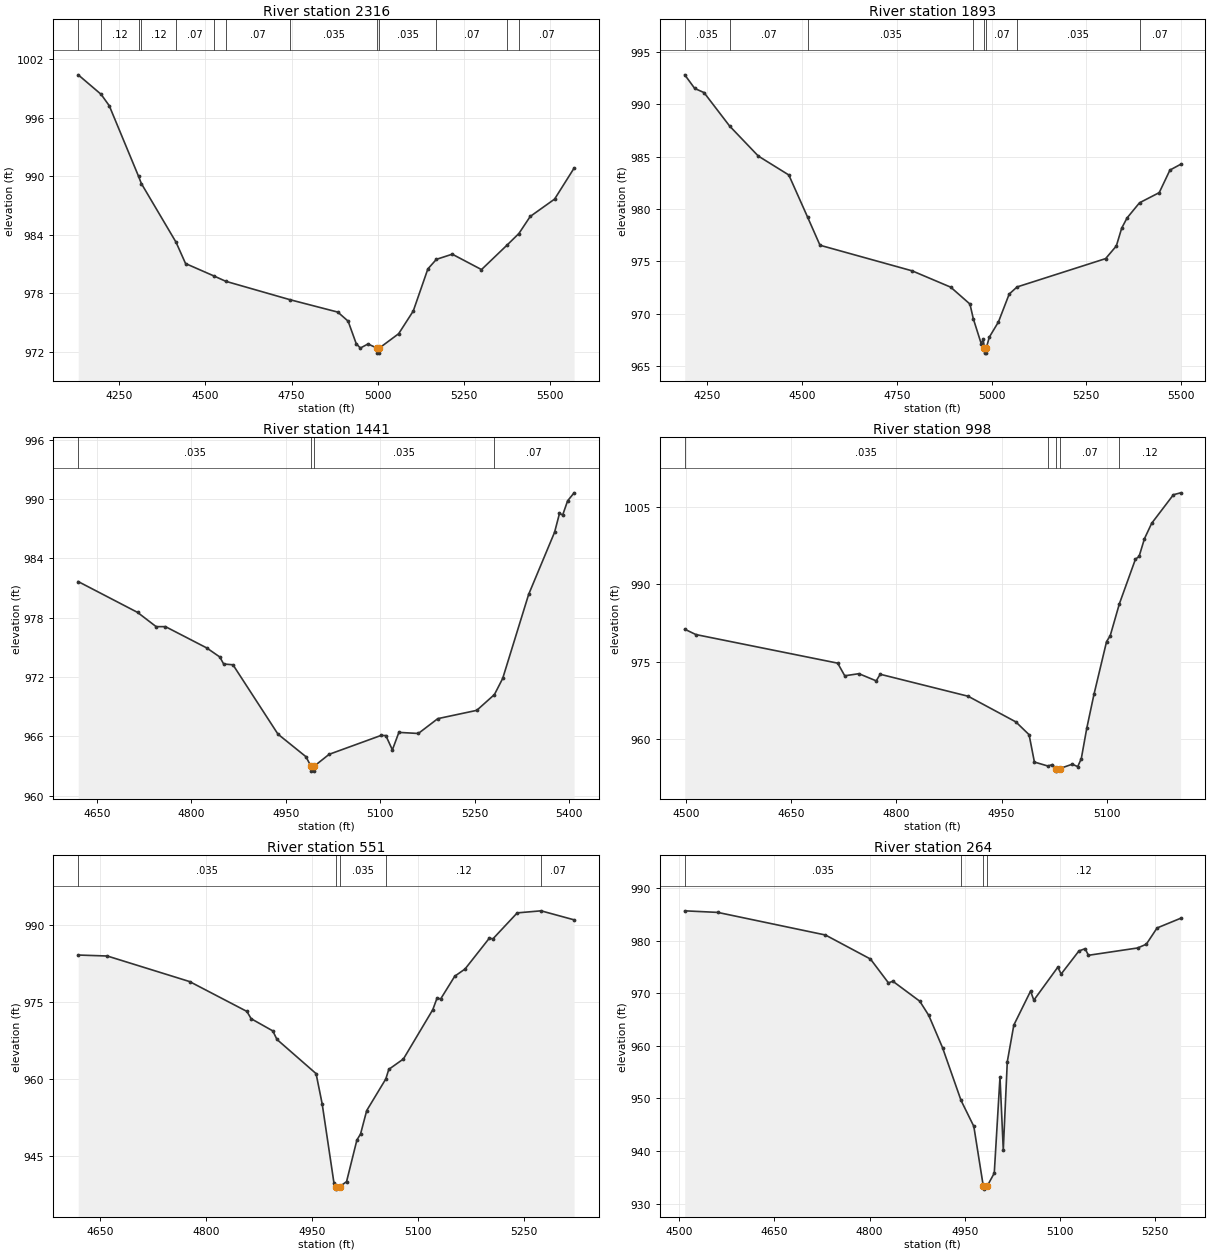
Type RM Length L Ch R = 1,2316,423,423,423
BEGIN DESCRIPTION:
Guadalupe Tributary 68 5.0
END DESCRIPTION:
XS GIS Cut Line= 3
      2165375.00     13867975.01      2165025.00     13867175.00
      2164625.00     13866775.00
#Sta/Elev= 30
  4130.7 1000.42  4197.1  998.42  4220.8  997.25  4305.9  990.00  4313.9  989.27
  4414.7  983.24  4442.2  981.06  4523.6  979.80  4558.8  979.24  4746.3  977.34
  4883.9  976.08  4913.9  975.15  4937.3  972.85  4949.3  972.39  4971.6  972.81
  4998.7  972.37  4999.1  971.87  5003.3  971.87  5003.7  972.37  5060.5  973.86
  5102.9  976.19  5145.3  980.51  5170.0  981.49  5216.1  982.02  5300.9  980.44
  5375.0  982.95  5409.4  984.14  5442.3  985.89  5513.0  987.67  5569.6  990.85
#Mann=13,-1,0
  4130.7    0.07       0  4197.1    0.12       0  4305.9   0.035       0
  4313.9    0.12       0  4414.7    0.07       0  4523.6   0.035       0
  4558.8    0.07       0  4746.3   0.035       0  4998.7   0.035       0
  5003.7   0.035       0  5170.0    0.07       0  5375.0    0.12       0
  5409.4    0.07       0
Bank Sta=4998.7,5003.7
Exp/Cntr=0.3,0.1

Type RM Length L Ch R = 1,1893,452,452,452
BEGIN DESCRIPTION:
Guadalupe Tributary 68 4.0
END DESCRIPTION:
XS GIS Cut Line= 3
      2165525.00     13867775.02      2165375.00     13866975.00
      2165025.03     13866625.03
#Sta/Elev= 30
  4190.1  992.83  4216.4  991.53  4241.0  991.13  4308.6  987.93  4384.3  985.06
  4464.8  983.25  4514.5  979.21  4547.1  976.53  4790.4  974.08  4892.1  972.52
  4943.0  970.90  4951.7  969.51  4972.7  967.11  4977.8  967.52  4981.2  966.71
  4981.6  966.21  4985.9  966.21  4986.2  966.71  4993.9  967.73  5018.2  969.20
  5046.5  971.86  5067.3  972.54  5301.0  975.25  5329.3  976.46  5343.5  978.17
  5357.6  979.14  5390.5  980.59  5442.5  981.56  5470.8  983.72  5499.0  984.27
#Mann=8,-1,0
  4190.1   0.035       0  4308.6    0.07       0  4514.5   0.035       0
  4951.7    0.07       0  4981.2    0.05       0  4986.2    0.07       0
  5067.3   0.035       0  5390.5    0.07       0
Bank Sta=4981.2,4986.2
Exp/Cntr=0.3,0.1

Type RM Length L Ch R = 1,1441,443,443,443
BEGIN DESCRIPTION:
Guadalupe Tributary 68 3.0
END DESCRIPTION:
XS GIS Cut Line= 3
      2165990.54     13867132.18      2165775.00     13866825.00
      2165674.99     13866424.97
#Sta/Elev= 30
  4620.4  981.65  4714.7  978.53  4744.2  977.09  4759.0  977.09  4824.4  974.94
  4845.3  974.02  4851.4  973.31  4866.2  973.23  4937.7  966.21  4982.1  963.93
  4990.0  962.97  4990.4  962.47  4994.8  962.47  4995.2  962.97  5018.9  964.17
  5101.3  966.08  5109.0  966.07  5119.4  964.62  5129.7  966.39  5160.6  966.28
  5191.5  967.78  5253.4  968.62  5281.5  970.22  5294.6  971.85  5335.8  980.35
  5377.0  986.64  5384.8  988.54  5389.9  988.39  5397.7  989.82  5408.0  990.63
#Mann=4,-1,0
  4620.4   0.035       0  4990.0   0.035       0  4995.2   0.035       0
  5281.5    0.07       0
Bank Sta=4990,4995.2
Exp/Cntr=0.3,0.1

Type RM Length L Ch R = 1,998,447,447,447
BEGIN DESCRIPTION:
Guadalupe Tributary 68 2.0
END DESCRIPTION:
XS GIS Cut Line= 3
      2166101.66     13866970.72      2166025.00     13866475.00
      2165974.99     13866274.97
#Sta/Elev= 30
  4497.8  981.32  4513.7  980.28  4716.1  974.74  4726.2  972.29  4746.4  972.70
  4771.1  971.31  4776.8  972.59  4902.3  968.33  4970.4  963.36  4989.3  960.88
  4996.9  955.58  5016.1  954.81  5022.6  955.09  5027.5  954.32  5028.0  953.82
  5033.1  954.32  5051.0  955.16  5058.7  954.69  5063.8  956.22  5071.6  962.10
  5081.9  968.68  5099.9  978.92  5105.1  980.05  5118.2  986.25  5141.1  994.88
  5146.3  995.41  5154.0  998.86  5164.3 1001.84  5195.3 1007.37  5205.6 1007.74
#Mann=5,-1,0
  4497.8   0.035       0  5016.1    0.07       0  5027.5   0.035       0
  5033.1    0.07       0  5118.2    0.12       0
Bank Sta=5027.5,5033.1
Exp/Cntr=0.3,0.1

Type RM Length L Ch R = 1,551,287,287,287
BEGIN DESCRIPTION:
Guadalupe Tributary 68 1.0
END DESCRIPTION:
XS GIS Cut Line= 3
      2166246.11     13866979.08      2166375.00     13866625.00
      2166461.38     13866312.42
#Sta/Elev= 30
  4619.3  984.18  4660.4  983.99  4776.8  979.00  4857.8  973.17  4863.8  971.75
  4894.4  969.37  4900.3  967.70  4955.6  961.03  4964.2  955.15  4980.8  939.76
  4983.3  938.98  4983.8  938.48  4989.0  938.98  4998.7  939.94  5013.3  948.06
  5018.5  949.25  5027.2  953.82  5054.2  959.99  5058.4  961.86  5079.1  963.89
  5120.6  973.51  5126.6  975.76  5131.8  975.62  5151.7  980.05  5166.2  981.45
  5200.5  987.46  5205.7  987.35  5240.0  992.41  5273.7  992.81  5320.4  991.05
#Mann=5,-1,0
  4619.3   0.035       0  4983.3   0.035       0  4989.0   0.035       0
  5054.2    0.12       0  5273.7    0.07       0
Bank Sta=4983.3,4989
Exp/Cntr=0.3,0.1

Type RM Length L Ch R = 1,264,0,0,0
BEGIN DESCRIPTION:
Guadalupe Tributary 68 0.1
END DESCRIPTION:
XS GIS Cut Line= 3
      2166293.89     13867027.15      2166645.43     13866706.15
      2166577.59     13866408.84
#Sta/Elev= 30
  4508.8  985.69  4560.8  985.39  4730.4  981.09  4801.3  976.52  4829.7  971.97
  4836.5  972.30  4879.0  968.49  4893.2  965.78  4914.8  959.66  4944.0  949.61
  4964.1  944.68  4979.1  933.24  4979.6  932.74  4984.8  933.24  4996.3  935.79
  5005.3  954.05  5010.5  940.20  5016.8  956.97  5027.1  963.95  5053.5  970.42
  5058.6  968.69  5096.4  974.97  5101.6  973.66  5129.6  978.05  5139.4  978.49
  5144.6  977.23  5221.9  978.62  5235.7  979.33  5252.7  982.43  5289.8  984.27
#Mann=4,-1,0
  4508.8   0.035       0  4944.0    0.12       0  4979.1    0.05       0
  4984.8    0.12       0
Bank Sta=4979.1,4984.8
Exp/Cntr=0.3,0.1

Chan Stop Cuts=-1