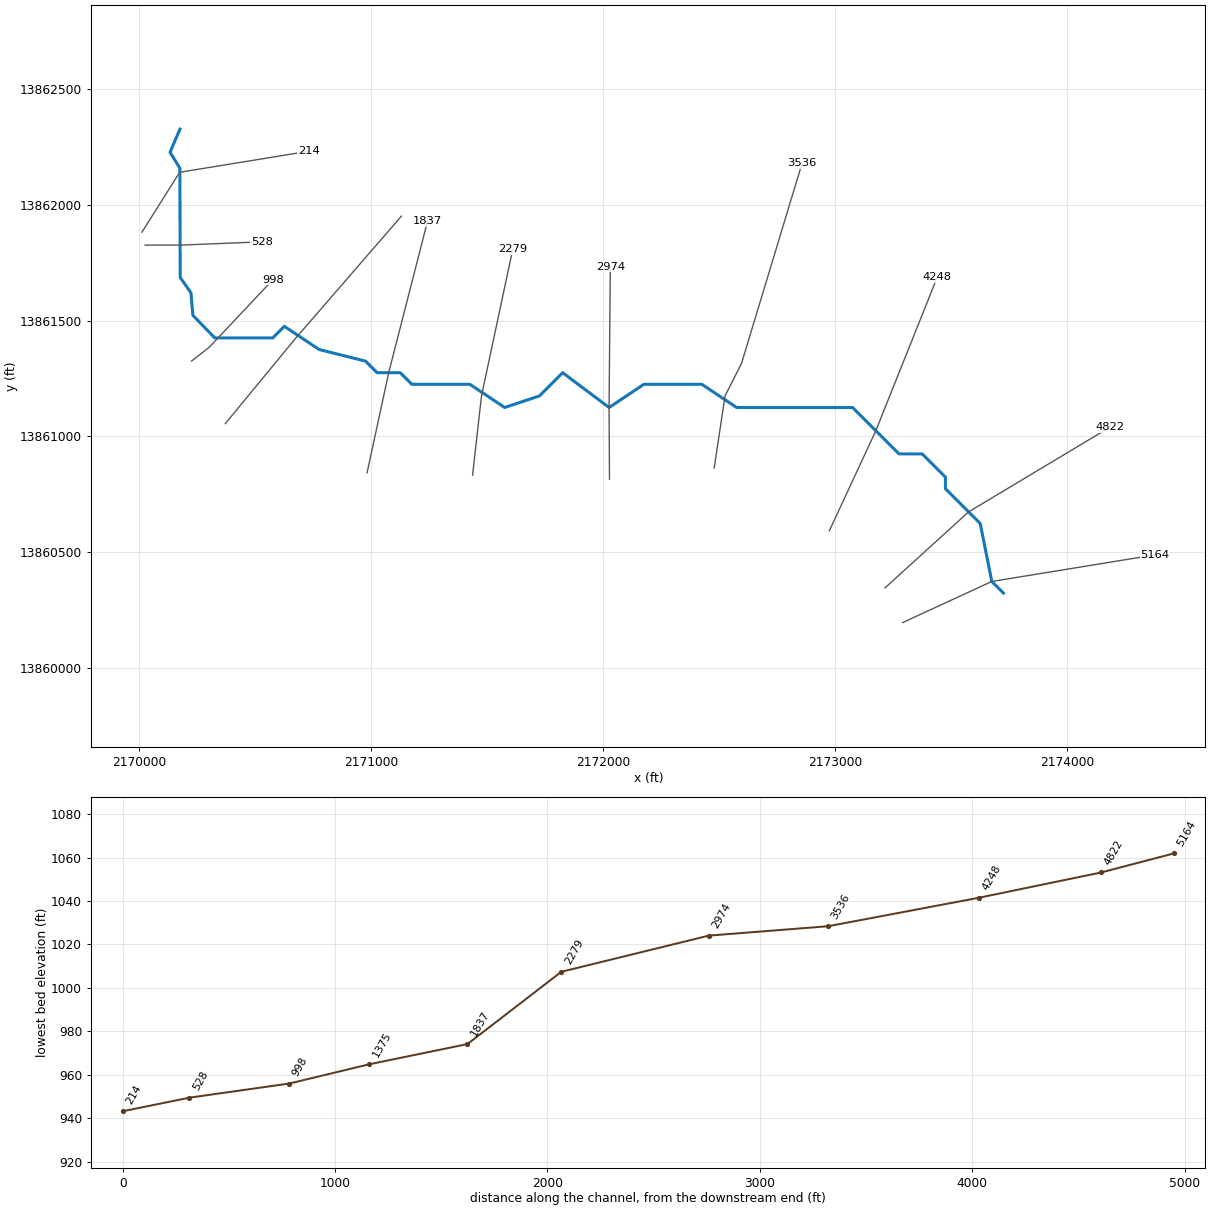
--- Guadalupe Tributary 70.prj (project) ---

Proj Title=Guadalupe Tributary 70 Base Level Engineering
Current Plan=p01
Default Exp/Contr=0.3,0.1
English Units
Geom File=g01
Flow File=f01
Plan File=p01
BEGIN DESCRIPTION:
Guadalupe Tributary 70
END DESCRIPTION:

--- Guadalupe Tributary 70.p01 (plan) ---

Plan Title=Multiple Run
Short Identifier=Multiple
Geom File=g01
Flow File=f01
Subcritical Flow
K Sum by GR= 0
Std Step Tol= 0.01
Critical Tol= 0.01
Num of Std Step Trials= 20
Max Error Tol= 0.3
Flow Tol Ratio= 0.001
Split Flow NTrial= 30
Split Flow Tol= 0.02
Split Flow Ratio= 0.02
Log Output Level= 0
Friction Slope Method= 1
Unsteady Friction Slope Method= 2
Unsteady Bridges Friction Slope Method= 1
Parabolic Critical Depth
Global Vel Dist=  1 , 1 , 1
Global Log Level= 0
CheckData=True
Encroach Param= -1, 0, 0, 0
BEGIN DESCRIPTION:
Multiple Run
END DESCRIPTION:

--- Guadalupe Tributary 70.f01 (steady flow) ---

Flow Title=Multiple
Number of Profiles=7
Profile Names=10-year,25-year,50-year,1pct_min,100-year,1pct_plu,500-year
River Rch & RM= Guadalupe Tribut,Reach-1,5164
     428     691     931     611    1220    2433    2063
River Rch & RM= Guadalupe Tribut,Reach-1,4248
    1467    2566    3644    2508    5005    9986    9345
Boundary for River Rch & Prof#=Guadalupe Tribut,Reach-1,1
Up Type=0
Dn Type=3
Dn Slope=0.005
Boundary for River Rch & Prof#=Guadalupe Tribut,Reach-1,2
Up Type=0
Dn Type=3
Dn Slope=0.005
Boundary for River Rch & Prof#=Guadalupe Tribut,Reach-1,3
Up Type=0
Dn Type=3
Dn Slope=0.005
Boundary for River Rch & Prof#=Guadalupe Tribut,Reach-1,4
Up Type=0
Dn Type=3
Dn Slope=0.005
Boundary for River Rch & Prof#=Guadalupe Tribut,Reach-1,5
Up Type=0
Dn Type=3
Dn Slope=0.005
Boundary for River Rch & Prof#=Guadalupe Tribut,Reach-1,6
Up Type=0
Dn Type=3
Dn Slope=0.005
Boundary for River Rch & Prof#=Guadalupe Tribut,Reach-1,7
Up Type=0
Dn Type=3
Dn Slope=0.005

--- Guadalupe Tributary 70.g01 (geometry) ---

Geom Title=Existing Conditions

River Reach=Guadalupe Tribut,Reach-1
Reach XY= 30
      2173725.00     13860325.00      2173675.00     13860375.00
      2173625.00     13860625.00      2173475.00     13860775.00
      2173475.00     13860825.00      2173375.00     13860925.00
      2173275.00     13860925.00      2173075.00     13861125.00
      2172575.00     13861125.00      2172425.00     13861225.00
      2172175.00     13861225.00      2172025.00     13861125.00
      2171825.00     13861275.00      2171725.00     13861175.00
      2171575.00     13861125.00      2171425.00     13861225.00
      2171175.00     13861225.00      2171125.00     13861275.00
      2171025.00     13861275.00      2170975.00     13861325.00
      2170775.00     13861375.00      2170625.00     13861475.00
      2170575.00     13861425.00      2170325.00     13861425.00
      2170230.69     13861522.67      2170222.53     13861619.43
      2170176.22     13861685.50      2170174.67     13862156.78
      2170132.31     13862225.04      2170175.00     13862325.00

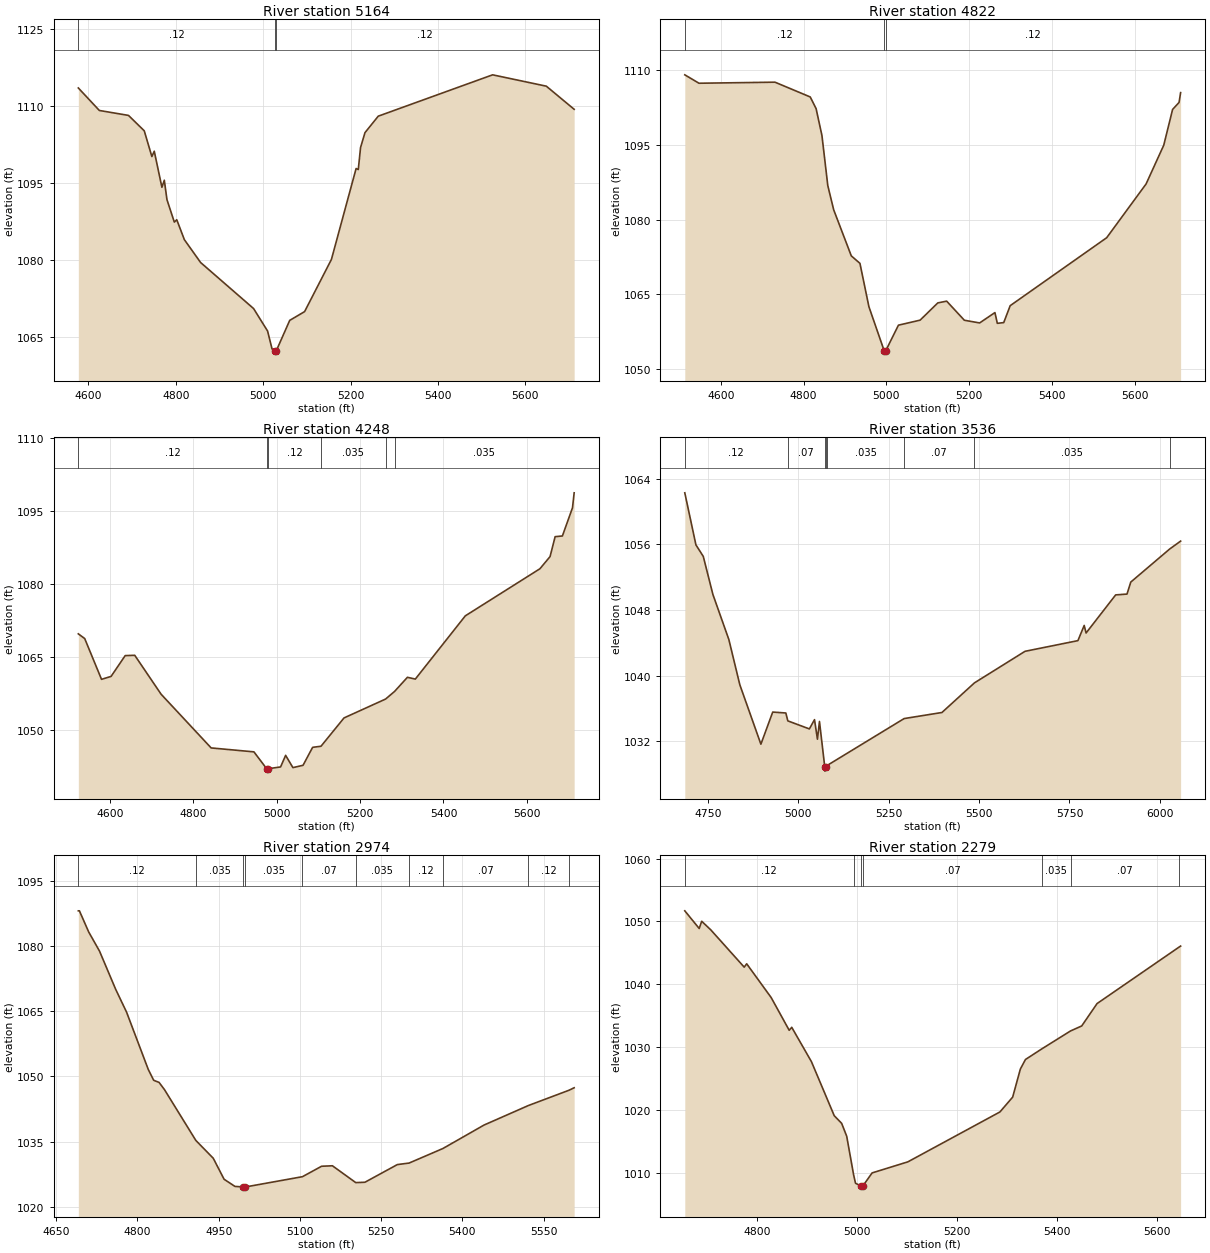
Type RM Length L Ch R = 1,5164,342,342,342
BEGIN DESCRIPTION:
Guadalupe Tributary 70 10.0
END DESCRIPTION:
XS GIS Cut Line= 3
      2173290.78     13860197.83      2173675.00     13860375.00
      2174377.53     13860489.47
#Sta/Elev= 30
  4576.9 1113.52  4625.0 1109.14  4691.7 1108.18  4727.8 1105.18  4745.2 1100.17
  4750.7 1101.21  4768.2 1094.19  4773.7 1095.56  4779.8 1091.77  4796.6 1087.41
  4802.2 1087.87  4819.6 1083.99  4856.8 1079.54  4978.0 1070.58  5010.1 1066.20
  5020.3 1062.72  5026.2 1062.40  5026.5 1061.90  5030.2 1062.40  5060.8 1068.28
  5094.8 1069.98  5156.2 1080.14  5212.7 1097.84  5217.7 1097.64  5222.9 1101.93
  5233.0 1104.82  5263.4 1108.03  5525.2 1116.08  5648.1 1113.87  5711.8 1109.37
#Mann=3,-1,0
  4576.9    0.12       0  5026.2    0.05       0  5030.2    0.12       0
Bank Sta=5026.2,5030.2
Exp/Cntr=0.3,0.1

Type RM Length L Ch R = 1,4822,574,574,574
BEGIN DESCRIPTION:
Guadalupe Tributary 70 9.0
END DESCRIPTION:
XS GIS Cut Line= 3
      2173214.36     13860347.13      2173575.00     13860675.00
      2174185.28     13861040.78
#Sta/Elev= 30
  4512.6 1109.09  4546.9 1107.40  4730.7 1107.61  4815.9 1104.64  4830.1 1102.29
  4844.2 1096.90  4858.4 1086.81  4872.6 1081.96  4915.2 1072.69  4936.1 1071.19
  4957.8 1062.47  4994.6 1053.64  4994.9 1053.14  4998.6 1053.64  5029.2 1058.76
  5081.6 1059.77  5124.4 1063.24  5145.8 1063.59  5188.6 1059.75  5225.5 1059.21
  5262.5 1061.29  5268.3 1059.13  5283.8 1059.28  5299.4 1062.68  5532.7 1076.34
  5628.0 1087.15  5670.7 1094.94  5692.1 1102.13  5707.7 1103.54  5711.5 1105.51
#Mann=3,-1,0
  4512.6    0.12       0  4994.6    0.05       0  4998.6    0.12       0
Bank Sta=4994.6,4998.6
Exp/Cntr=0.3,0.1

Type RM Length L Ch R = 1,4248,712,712,712
BEGIN DESCRIPTION:
Guadalupe Tributary 70 8.0
END DESCRIPTION:
XS GIS Cut Line= 3
      2172974.75     13860593.61      2173175.00     13861025.00
      2173440.03     13861687.35
#Sta/Elev= 30
  4524.4 1069.74  4539.7 1068.77  4580.0 1060.39  4602.9 1060.99  4636.8 1065.27
  4659.7 1065.33  4722.9 1057.33  4842.9 1046.29  4945.5 1045.48  4976.0 1042.02
  4976.2 1041.52  4980.0 1042.02  5009.4 1042.38  5021.5 1044.76  5039.0 1042.24
  5063.3 1042.72  5086.2 1046.41  5106.4 1046.64  5161.6 1052.46  5261.1 1056.33
  5282.6 1057.89  5313.6 1060.81  5332.5 1060.44  5452.4 1073.44  5631.3 1083.12
  5655.6 1085.62  5667.8 1089.72  5685.2 1089.86  5709.4 1095.65  5713.4 1098.73
#Mann=6,-1,0
  4524.4    0.12       0  4976.0    0.05       0  4980.0    0.12       0
  5106.4   0.035       0  5261.1    0.07       0  5282.6   0.035       0
Bank Sta=4976,4980
Exp/Cntr=0.3,0.1

Type RM Length L Ch R = 1,3536,562,562,562
BEGIN DESCRIPTION:
Guadalupe Tributary 70 7.0
END DESCRIPTION:
XS GIS Cut Line= 4
      2172478.24     13860864.50      2172525.00     13861175.00
      2172596.29     13861315.86      2172856.71     13862176.97
#Sta/Elev= 30
  4686.0 1062.27  4716.8 1055.93  4737.1 1054.53  4763.7 1049.90  4807.9 1044.40
  4838.2 1038.90  4896.5 1031.66  4929.2 1035.57  4965.5 1035.46  4971.0 1034.50
  5030.6 1033.52  5044.8 1034.65  5052.9 1032.27  5058.5 1034.43  5073.2 1028.88
  5073.4 1028.38  5077.2 1028.88  5079.4 1029.06  5292.7 1034.78  5397.3 1035.52
  5487.3 1039.13  5627.1 1042.97  5773.4 1044.27  5790.8 1046.12  5796.0 1045.20
  5877.8 1049.84  5909.2 1049.94  5919.6 1051.40  6027.3 1055.43  6057.5 1056.39
#Mann=8,-1,0
  4686.0    0.12       0  4971.0    0.07       0  5073.2    0.05       0
  5077.2    0.07       0  5079.4   0.035       0  5292.7    0.07       0
  5487.3   0.035       0  6027.3    0.12       0
Bank Sta=5073.2,5077.2
Exp/Cntr=0.3,0.1

Type RM Length L Ch R = 1,2974,695,695,695
BEGIN DESCRIPTION:
Guadalupe Tributary 70 6.0
END DESCRIPTION:
XS GIS Cut Line= 3
      2172026.85     13860815.91      2172025.00     13861125.00
      2172030.31     13861731.28
#Sta/Elev= 30
  4690.9 1088.05  4692.9 1088.05  4710.0 1083.20  4730.0 1078.79  4760.0 1069.96
  4780.0 1064.74  4820.0 1051.58  4830.0 1049.08  4840.0 1048.59  4850.0 1046.92
  4907.9 1035.24  4940.0 1031.15  4960.0 1026.32  4980.0 1024.68  4995.5 1024.55
  4995.7 1024.05  4999.2 1024.05  4999.5 1024.55  5104.7 1026.91  5140.0 1029.31
  5160.0 1029.42  5203.1 1025.55  5220.0 1025.63  5280.0 1029.70  5301.5 1030.04
  5364.0 1033.39  5440.0 1038.79  5521.9 1043.28  5596.8 1046.79  5606.3 1047.36
#Mann=10,-1,0
  4690.9    0.12       0  4907.9   0.035       0  4995.5   0.035       0
  4999.5   0.035       0  5104.7    0.07       0  5203.1   0.035       0
  5301.5    0.12       0  5364.0    0.07       0  5521.9    0.12       0
  5596.8    0.07       0
Bank Sta=4995.5,4999.5
Exp/Cntr=0.3,0.1

Type RM Length L Ch R = 1,2279,442,442,442
BEGIN DESCRIPTION:
Guadalupe Tributary 70 5.0
END DESCRIPTION:
XS GIS Cut Line= 3
      2171436.58     13860833.25      2171475.00     13861175.00
      2171610.08     13861808.46
#Sta/Elev= 30
  4656.1 1051.68  4684.9 1048.87  4689.9 1050.02  4708.2 1048.64  4774.9 1042.72
  4779.9 1043.25  4828.9 1037.87  4864.9 1032.67  4870.0 1033.14  4909.4 1027.67
  4955.0 1019.07  4969.8 1017.86  4979.9 1015.81  4993.7 1009.68  4997.5 1008.33
  5008.2 1007.89  5008.5 1007.39  5012.2 1007.89  5030.7 1009.97  5102.2 1011.73
  5286.3 1019.67  5311.8 1022.03  5327.2 1026.50  5337.4 1028.02  5370.7 1029.74
  5427.5 1032.56  5449.9 1033.36  5480.6 1036.92  5645.0 1045.93  5647.7 1046.07
#Mann=7,-1,0
  4656.1    0.12       0  4993.7    0.07       0  5008.2    0.05       0
  5012.2    0.07       0  5370.7   0.035       0  5427.5    0.07       0
  5645.0   0.035       0
Bank Sta=5008.2,5012.2
Exp/Cntr=0.3,0.1

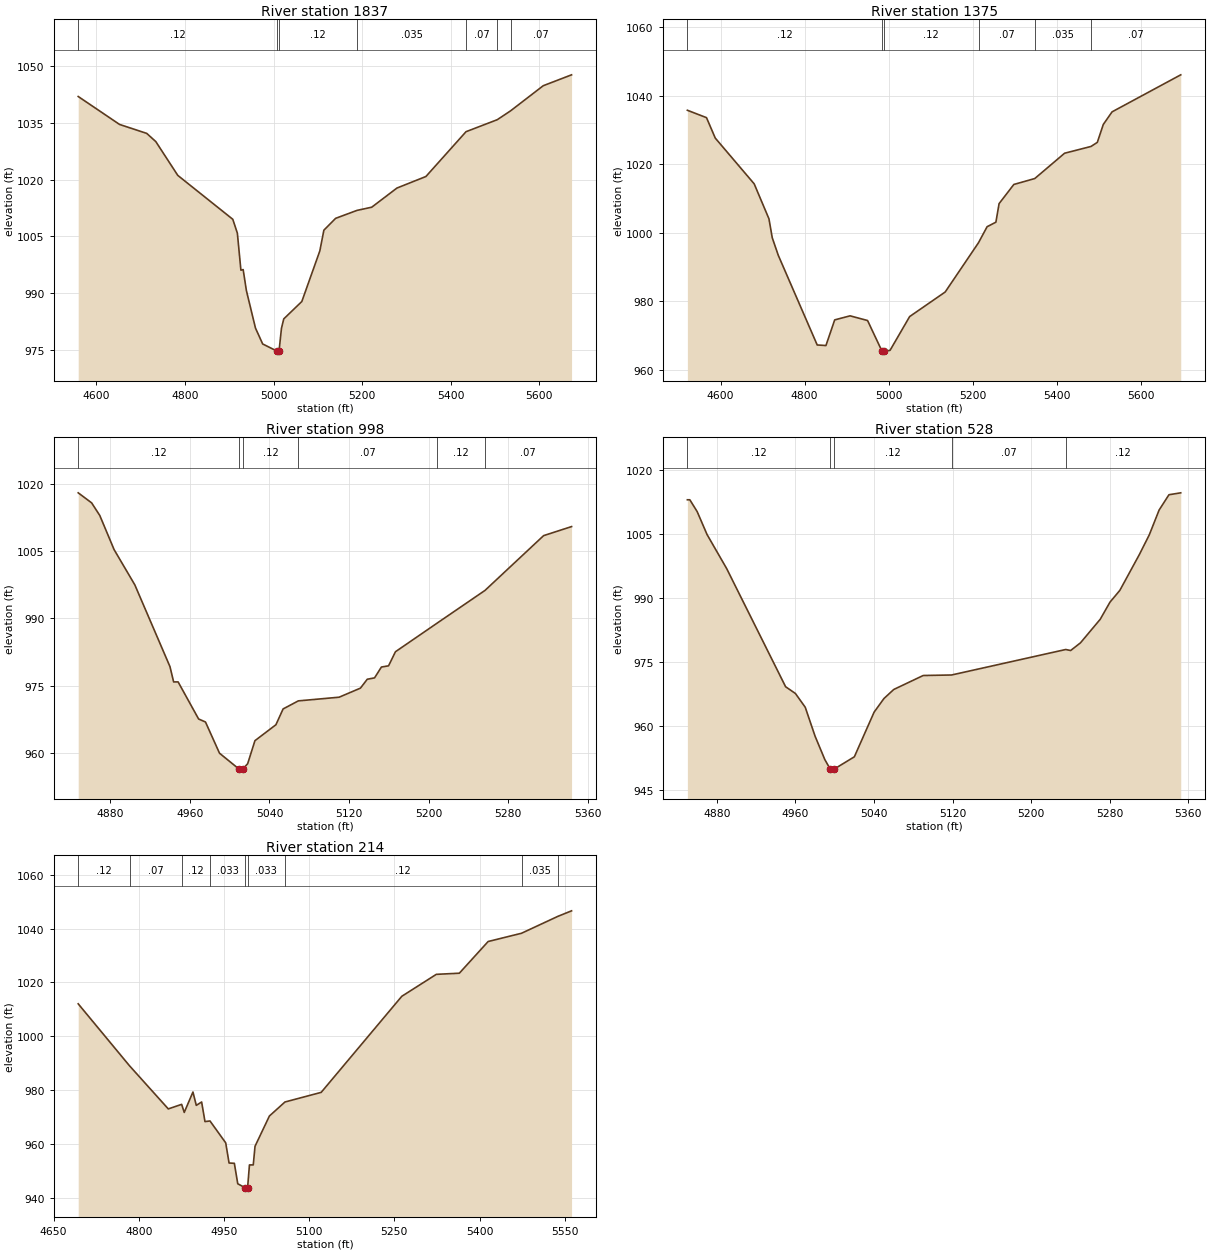
Type RM Length L Ch R = 1,1837,462,462,462
BEGIN DESCRIPTION:
Guadalupe Tributary 70 4.0
END DESCRIPTION:
XS GIS Cut Line= 3
      2170981.72     13860843.67      2171075.00     13861275.00
      2171242.14     13861927.02
#Sta/Elev= 30
  4558.7 1041.98  4652.1 1034.59  4713.5 1032.22  4734.0 1030.05  4783.6 1021.12
  4907.9 1009.50  4918.2 1005.83  4926.2  996.05  4931.3  996.20  4938.6  990.65
  4959.1  980.74  4975.4  976.53  5008.3  974.61  5008.6  974.11  5012.3  974.61
  5017.8  980.66  5023.0  983.16  5063.8  987.76  5104.5 1001.15  5113.6 1006.62
  5140.2 1009.76  5188.5 1011.86  5221.7 1012.70  5278.7 1017.77  5344.1 1020.82
  5434.7 1032.67  5505.2 1035.84  5535.3 1038.18  5609.1 1044.83  5673.1 1047.71
#Mann=7,-1,0
  4558.7    0.12       0  5008.3    0.05       0  5012.3    0.12       0
  5188.5   0.035       0  5434.7    0.07       0  5505.2   0.035       0
  5535.3    0.07       0
Bank Sta=5008.3,5012.3
Exp/Cntr=0.3,0.1

Type RM Length L Ch R = 1,1375,377,377,377
BEGIN DESCRIPTION:
Guadalupe Tributary 70 3.0
END DESCRIPTION:
XS GIS Cut Line= 3
      2170370.59     13861055.43      2170675.00     13861425.00
      2171129.93     13861950.02
#Sta/Elev= 30
  4521.2 1035.75  4566.7 1033.59  4587.5 1027.63  4680.1 1014.26  4715.2 1004.06
  4723.1  998.50  4737.4  993.39  4830.0  967.20  4850.8  967.04  4871.6  974.53
  4908.2  975.71  4949.8  974.34  4984.4  965.32  4984.6  964.82  4988.4  965.32
  5003.3  965.64  5049.9  975.50  5134.4  982.67  5213.8  997.09  5234.1 1001.74
  5255.0 1003.06  5262.6 1008.48  5297.7 1014.08  5347.5 1015.81  5418.4 1023.20
  5481.2 1025.18  5496.2 1026.36  5510.5 1031.61  5531.4 1035.29  5694.7 1046.10
#Mann=6,-1,0
  4521.2    0.12       0  4984.4    0.05       0  4988.4    0.12       0
  5213.8    0.07       0  5347.5   0.035       0  5481.2    0.07       0
Bank Sta=4984.4,4988.4
Exp/Cntr=0.3,0.1

Type RM Length L Ch R = 1,998,470,470,470
BEGIN DESCRIPTION:
Guadalupe Tributary 70 2.0
END DESCRIPTION:
XS GIS Cut Line= 3
      2170225.03     13861325.02      2170301.16     13861384.60
      2170574.99     13861674.99
#Sta/Elev= 30
  4847.8 1018.02  4861.3 1015.78  4869.5 1012.96  4883.9 1005.34  4904.7  997.49
  4940.0  979.26  4943.7  975.84  4948.2  975.84  4968.8  967.57  4975.7  966.90
  4989.8  959.94  5009.2  956.44  5009.5  955.94  5013.4  956.44  5018.1  957.60
  5025.4  962.73  5046.5  966.29  5053.7  969.81  5069.0  971.61  5110.0  972.43
  5131.4  974.45  5138.3  976.44  5145.6  976.74  5152.5  979.16  5159.7  979.43
  5166.6  982.57  5208.2  988.91  5256.6  996.25  5315.5 1008.47  5343.6 1010.49
#Mann=6,-1,0
  4847.8    0.12       0  5009.2    0.05       0  5013.4    0.12       0
  5069.0    0.07       0  5208.2    0.12       0  5256.6    0.07       0
Bank Sta=5009.2,5013.4
Exp/Cntr=0.3,0.1

Type RM Length L Ch R = 1,528,314,314,314
BEGIN DESCRIPTION:
Guadalupe Tributary 70 1.0
END DESCRIPTION:
XS GIS Cut Line= 3
      2170024.97     13861825.00      2170175.00     13861825.00
      2170526.98     13861839.21
#Sta/Elev= 30
  4850.0 1013.09  4852.5 1013.09  4860.0 1010.30  4870.0 1004.95  4890.0  996.95
  4950.0  969.24  4960.0  967.65  4970.0  964.42  4980.0  957.64  4990.0  952.12
  4995.4  949.94  4995.7  949.44  4999.6  949.94  5020.0  952.80  5040.1  963.27
  5050.1  966.46  5060.1  968.59  5090.1  971.87  5119.0  971.99  5235.2  977.97
  5240.2  977.73  5250.2  979.53  5270.3  985.05  5280.3  989.09  5290.3  991.84
  5310.3 1000.30  5320.3 1004.88  5330.3 1010.69  5340.3 1014.27  5352.3 1014.72
#Mann=5,-1,0
  4850.0    0.12       0  4995.4    0.05       0  4999.6    0.12       0
  5119.0    0.07       0  5235.2    0.12       0
Bank Sta=4995.4,4999.6
Exp/Cntr=0.3,0.1

Type RM Length L Ch R = 1,214,0,0,0
BEGIN DESCRIPTION:
Guadalupe Tributary 70 0.1
END DESCRIPTION:
XS GIS Cut Line= 3
      2170011.18     13861880.87      2170173.96     13862139.01
      2170730.03     13862229.72
#Sta/Elev= 30
  4693.4 1012.07  4783.7  989.05  4852.0  973.01  4875.5  974.70  4880.1  971.71
  4895.4  979.29  4901.3  974.32  4910.7  975.59  4916.6  968.29  4925.4  968.53
  4953.1  960.39  4959.0  952.90  4968.3  952.78  4974.3  945.18  4987.4  943.69
  4987.7  943.19  4991.6  943.69  4994.9  952.19  5001.6  952.19  5004.7  959.12
  5030.0  970.36  5057.4  975.58  5121.2  979.16  5263.1 1014.87  5323.9 1023.03
  5364.4 1023.45  5415.1 1035.23  5473.9 1038.30  5537.7 1044.57  5562.0 1046.64
#Mann=9,-1,0
  4693.4    0.12       0  4783.7    0.07       0  4875.5    0.12       0
  4925.4   0.033       0  4987.4   0.033       0  4991.6   0.033       0
  5057.4    0.12       0  5473.9   0.035       0  5537.7    0.07       0
Bank Sta=4987.4,4991.6
Exp/Cntr=0.3,0.1

Chan Stop Cuts=-1