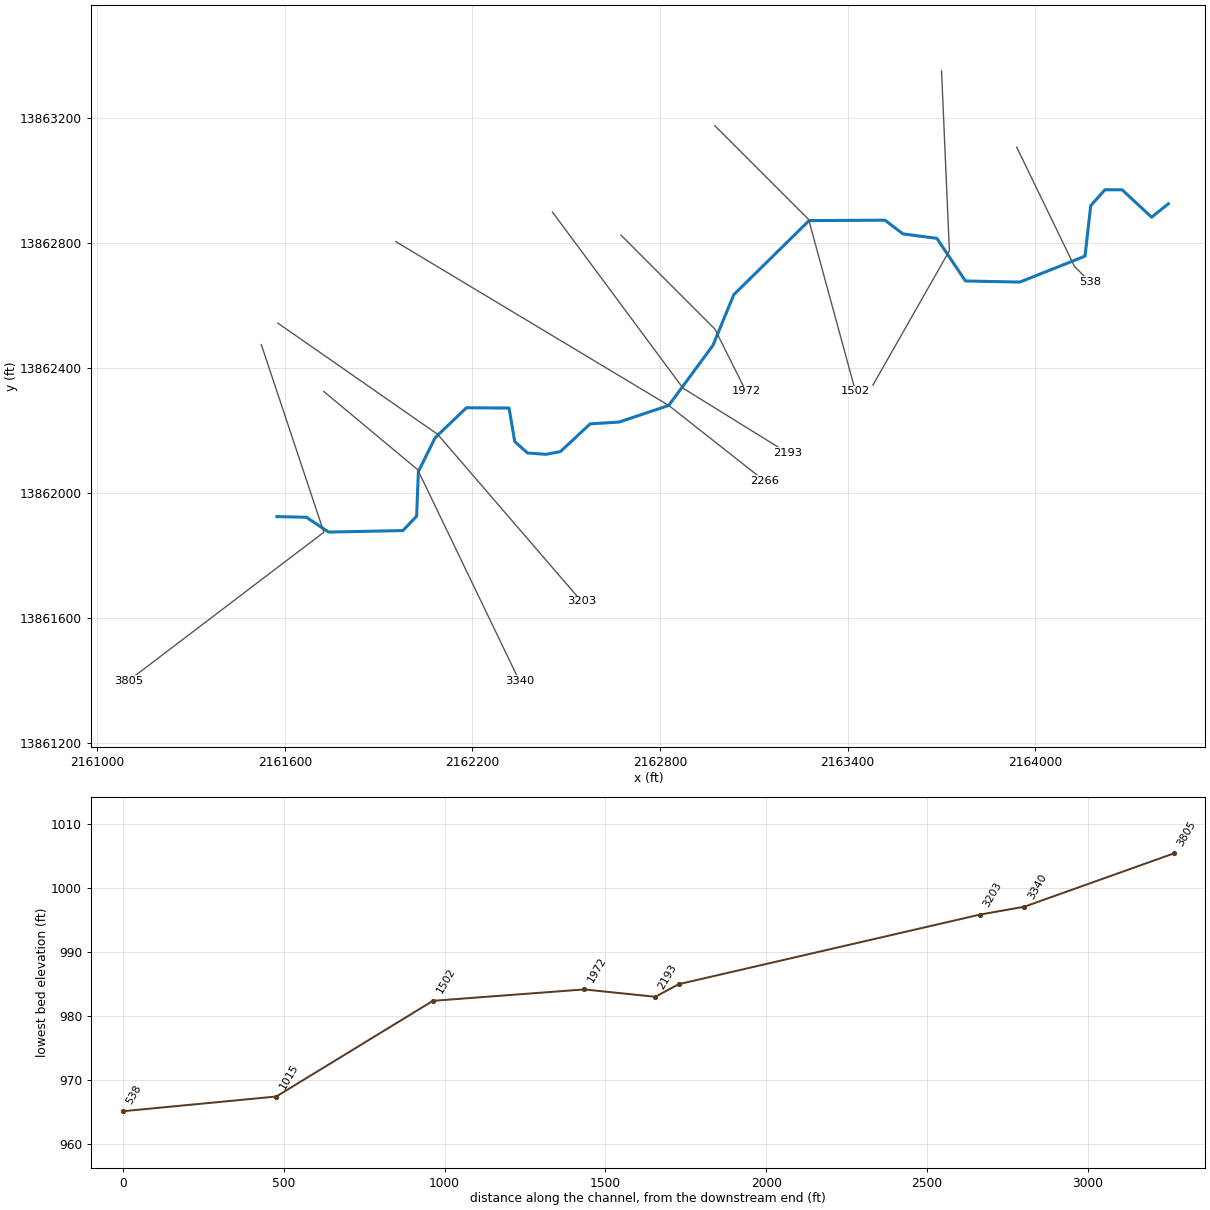
--- Guadalupe Tributary 73.prj (project) ---

Proj Title=Guadalupe Tributary 73 Base Level Engineering
Current Plan=p01
Default Exp/Contr=0.3,0.1
English Units
Geom File=g01
Flow File=f01
Plan File=p01
BEGIN DESCRIPTION:
Guadalupe Tributary 73
END DESCRIPTION:

--- Guadalupe Tributary 73.p01 (plan) ---

Plan Title=Multiple Run
Short Identifier=Multiple
Geom File=g01
Flow File=f01
Subcritical Flow
K Sum by GR= 0
Std Step Tol= 0.01
Critical Tol= 0.01
Num of Std Step Trials= 20
Max Error Tol= 0.3
Flow Tol Ratio= 0.001
Split Flow NTrial= 30
Split Flow Tol= 0.02
Split Flow Ratio= 0.02
Log Output Level= 0
Friction Slope Method= 1
Unsteady Friction Slope Method= 2
Unsteady Bridges Friction Slope Method= 1
Parabolic Critical Depth
Global Vel Dist=  1 , 1 , 1
Global Log Level= 0
CheckData=True
Encroach Param= -1, 0, 0, 0
BEGIN DESCRIPTION:
Multiple Run
END DESCRIPTION:

--- Guadalupe Tributary 73.f01 (steady flow) ---

Flow Title=Multiple
Number of Profiles=7
Profile Names=10-year,25-year,50-year,1pct_min,100-year,1pct_plu,500-year
River Rch & RM= Guadalupe Tribut,Reach-1,3805
     788    1316    1810    1208    2410    4809    4227
Boundary for River Rch & Prof#=Guadalupe Tribut,Reach-1,1
Up Type=0
Dn Type=3
Dn Slope=0.005
Boundary for River Rch & Prof#=Guadalupe Tribut,Reach-1,2
Up Type=0
Dn Type=3
Dn Slope=0.005
Boundary for River Rch & Prof#=Guadalupe Tribut,Reach-1,3
Up Type=0
Dn Type=3
Dn Slope=0.005
Boundary for River Rch & Prof#=Guadalupe Tribut,Reach-1,4
Up Type=0
Dn Type=3
Dn Slope=0.005
Boundary for River Rch & Prof#=Guadalupe Tribut,Reach-1,5
Up Type=0
Dn Type=3
Dn Slope=0.005
Boundary for River Rch & Prof#=Guadalupe Tribut,Reach-1,6
Up Type=0
Dn Type=3
Dn Slope=0.005
Boundary for River Rch & Prof#=Guadalupe Tribut,Reach-1,7
Up Type=0
Dn Type=3
Dn Slope=0.005

--- Guadalupe Tributary 73.g01 (geometry) ---

Geom Title=Existing Conditions

River Reach=Guadalupe Tribut,Reach-1
Reach XY= 30
      2161575.00     13861925.00      2161669.13     13861922.90
      2161740.21     13861875.51      2161977.74     13861880.34
      2162021.56     13861926.22      2162027.25     13862069.07
      2162080.82     13862177.31      2162180.86     13862272.96
      2162317.02     13862272.07      2162335.38     13862164.87
      2162376.26     13862128.36      2162435.04     13862124.15
      2162481.16     13862132.78      2162576.50     13862221.38
      2162669.02     13862227.36      2162827.67     13862280.42
      2162969.15     13862472.71      2163035.76     13862634.68
      2163276.46     13862871.46      2163519.06     13862872.74
      2163576.60     13862828.86      2163685.10     13862814.61
      2163776.25     13862678.45      2163950.08     13862674.80
      2164158.76     13862757.78      2164176.99     13862919.37
      2164222.42     13862970.05      2164277.26     13862969.93
      2164371.67     13862882.27      2164425.00     13862925.00

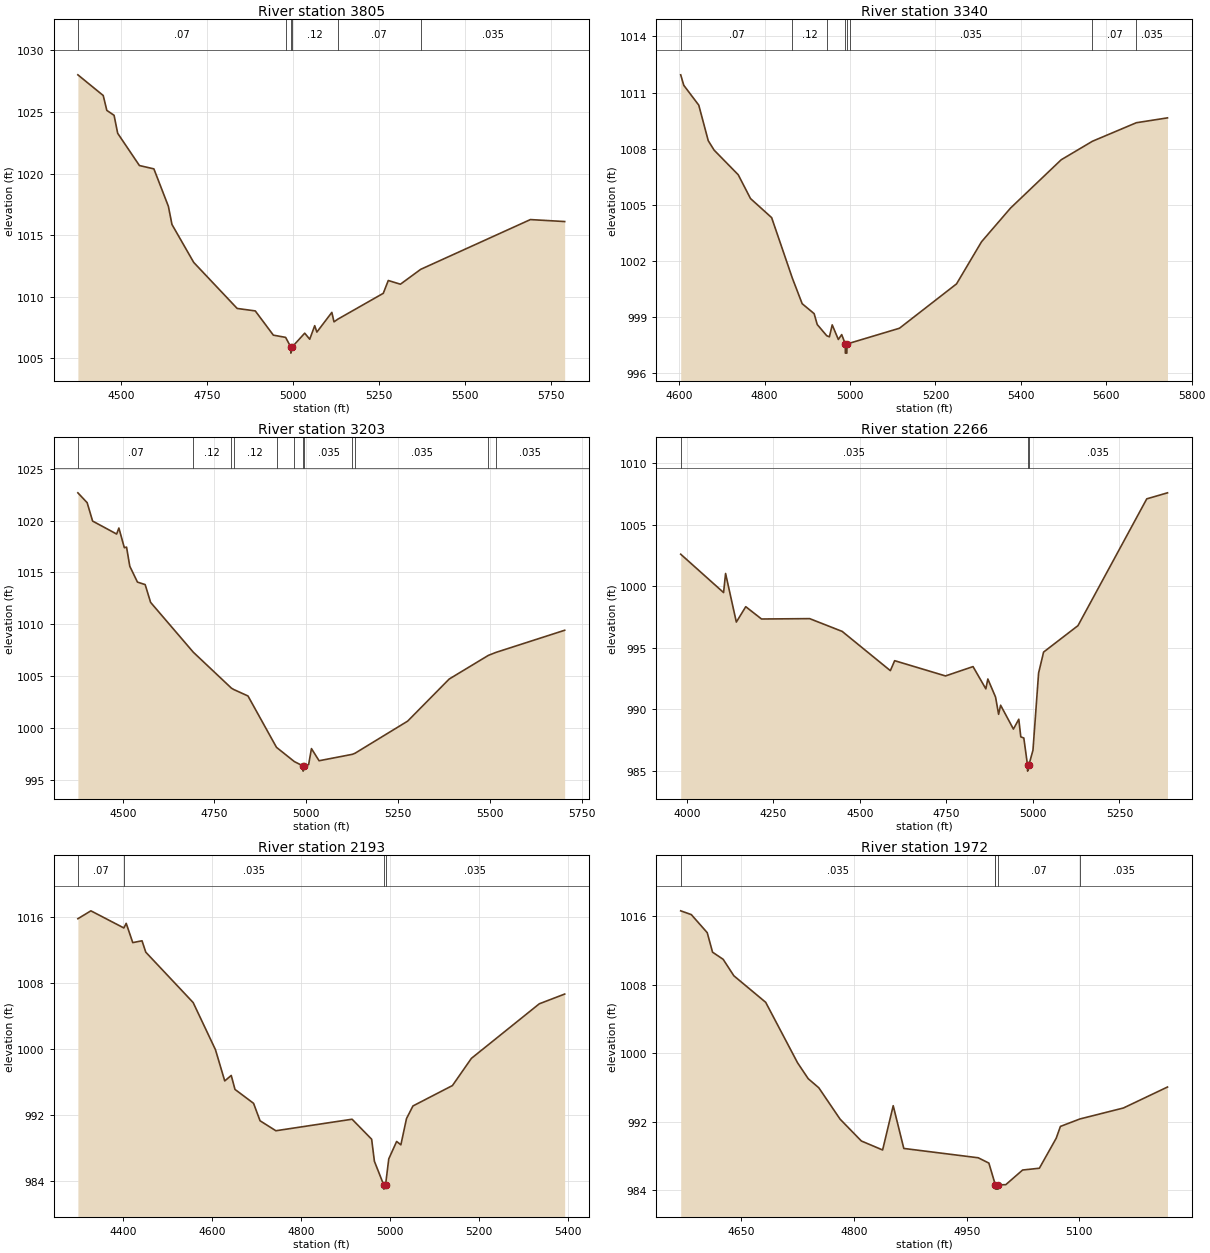
Type RM Length L Ch R = 1,3805,465,465,465
BEGIN DESCRIPTION:
Guadalupe Tributary 73 8.0
END DESCRIPTION:
XS GIS Cut Line= 3
      2161525.01     13862474.98      2161725.00     13861875.00
      2161100.04     13861400.03
#Sta/Elev= 30
  4373.3 1028.02  4447.1 1026.34  4457.6 1025.13  4478.7 1024.73  4489.2 1023.27
  4552.5 1020.65  4594.6 1020.38  4636.8 1017.34  4647.3 1015.86  4710.6 1012.78
  4837.1 1009.04  4889.8 1008.84  4942.5 1006.87  4978.2 1006.69  4993.2 1005.91
  4993.4 1005.41  4997.2 1005.91  5033.8 1007.03  5048.4 1006.54  5062.9 1007.64
  5069.2 1007.12  5112.8 1008.72  5119.1 1007.95  5129.7 1008.16  5262.6 1010.27
  5277.1 1011.31  5312.5 1011.01  5371.7 1012.22  5690.9 1016.26  5790.7 1016.10
#Mann=6,-1,0
  4373.3    0.07       0  4978.2    0.12       0  4993.2    0.05       0
  4997.2    0.12       0  5129.7    0.07       0  5371.7   0.035       0
Bank Sta=4993.2,4997.2
Exp/Cntr=0.3,0.1

Type RM Length L Ch R = 1,3340,137,137,137
BEGIN DESCRIPTION:
Guadalupe Tributary 73 7.0
END DESCRIPTION:
XS GIS Cut Line= 3
      2161724.98     13862325.01      2162025.00     13862075.00
      2162350.00     13861400.00
#Sta/Elev= 30
  4603.7 1011.95  4610.9 1011.39  4646.0 1010.33  4668.2 1008.43  4681.8 1007.93
  4738.4 1006.61  4767.1 1005.34  4816.6 1004.32  4865.2 1001.08  4888.1  999.72
  4916.1  999.19  4923.3  998.61  4945.6  998.01  4951.9  997.95  4958.4  998.59
  4972.8  997.81  4980.6  998.07  4989.0  997.58  4989.2  997.08  4992.7  997.08
  4993.0  997.58  4999.0  997.61  5115.9  998.41  5249.5 1000.78  5308.0 1003.03
  5375.9 1004.83  5494.5 1007.41  5567.6 1008.40  5670.4 1009.39  5743.4 1009.65
#Mann=8,-1,0
  4603.7    0.07       0  4865.2    0.12       0  4945.6    0.07       0
  4989.0   0.035       0  4993.0    0.07       0  4999.0   0.035       0
  5567.6    0.07       0  5670.4   0.035       0
Bank Sta=4989,4993
Exp/Cntr=0.3,0.1

Type RM Length L Ch R = 1,3203,937,937,937
BEGIN DESCRIPTION:
Guadalupe Tributary 73 6.5
END DESCRIPTION:
XS GIS Cut Line= 3
      2161577.97     13862543.57      2162088.61     13862188.24
      2162548.09     13861654.87
#Sta/Elev= 30
  4377.9 1022.67  4403.2 1021.72  4418.0 1019.95  4483.5 1018.70  4489.6 1019.28
  4504.5 1017.38  4510.5 1017.44  4519.3 1015.60  4540.2 1014.07  4561.2 1013.83
  4576.0 1012.12  4692.2 1007.32  4796.3 1003.85  4802.6 1003.72  4841.3 1003.10
  4919.0  998.15  4967.6  996.78  4991.2  996.36  4991.5  995.86  4995.2  996.36
  5006.5  996.49  5014.2  998.03  5035.0  996.86  5125.8  997.48  5133.3  997.59
  5276.4 1000.68  5389.4 1004.73  5496.1 1007.01  5517.0 1007.30  5704.0 1009.43
#Mann=12,-1,0
  4377.9    0.07       0  4692.2    0.12       0  4796.3    0.07       0
  4802.6    0.12       0  4919.0    0.07       0  4967.6   0.035       0
  4991.2   0.035       0  4995.2   0.035       0  5125.8    0.07       0
  5133.3   0.035       0  5496.1    0.07       0  5517.0   0.035       0
Bank Sta=4991.2,4995.2
Exp/Cntr=0.3,0.1

Type RM Length L Ch R = 1,2266,73,73,73
BEGIN DESCRIPTION:
Guadalupe Tributary 73 6.0
END DESCRIPTION:
XS GIS Cut Line= 3
      2161954.73     13862804.35      2162827.67     13862280.42
      2163133.03     13862039.75
#Sta/Elev= 30
  3981.9 1002.62  4105.8  999.50  4111.6 1001.05  4142.7  997.10  4169.9  998.35
  4215.5  997.35  4354.6  997.38  4448.7  996.34  4587.8  993.15  4600.3  993.96
  4747.2  992.72  4826.8  993.48  4863.8  991.67  4869.6  992.47  4891.9  991.00
  4900.7  989.60  4906.5  990.34  4943.5  988.40  4959.0  989.20  4964.8  987.77
  4973.6  987.67  4984.2  985.48  4984.5  984.98  4988.2  985.48  5000.0  986.68
  5016.3  992.96  5030.7  994.66  5130.1  996.81  5328.9 1007.12  5388.8 1007.61
#Mann=3,-1,0
  3981.9   0.035       0  4984.2   0.035       0  4988.2   0.035       0
Bank Sta=4984.2,4988.2
Exp/Cntr=0.3,0.1

Type RM Length L Ch R = 1,2193,221,221,221
BEGIN DESCRIPTION:
Guadalupe Tributary 73 5.0
END DESCRIPTION:
XS GIS Cut Line= 3
      2162456.20     13862898.34      2162873.52     13862335.47
      2163206.94     13862129.13
#Sta/Elev= 30
  4299.3 1015.85  4328.5 1016.81  4402.5 1014.73  4407.8 1015.29  4422.5 1012.95
  4443.3 1013.17  4451.7 1011.79  4558.1 1005.67  4608.2  999.94  4629.0  996.15
  4643.6  996.82  4652.0  995.12  4693.7  993.43  4708.3  991.31  4743.8  990.10
  4914.9  991.50  4958.8  989.07  4965.0  986.39  4986.0  983.51  4986.2  983.01
  4990.0  983.51  4997.2  986.68  5014.9  988.80  5024.4  988.39  5037.0  991.57
  5051.5  993.11  5140.2  995.59  5182.7  998.89  5335.2 1005.52  5392.1 1006.70
#Mann=4,-1,0
  4299.3    0.07       0  4402.5   0.035       0  4986.0   0.035       0
  4990.0   0.035       0
Bank Sta=4986,4990
Exp/Cntr=0.3,0.1

Type RM Length L Ch R = 1,1972,470,470,470
BEGIN DESCRIPTION:
Guadalupe Tributary 73 4.0
END DESCRIPTION:
XS GIS Cut Line= 3
      2162675.03     13862824.97      2162975.00     13862525.00
      2163074.99     13862325.02
#Sta/Elev= 30
  4569.4 1016.65  4583.5 1016.21  4604.7 1014.10  4611.8 1011.82  4625.9 1010.99
  4640.1 1009.07  4682.5 1005.97  4724.9  998.91  4739.1  997.05  4753.2  995.99
  4781.5  992.33  4809.8  989.78  4838.1  988.73  4852.2  993.90  4866.3  988.91
  4965.3  987.82  4979.5  987.20  4987.3  984.90  4988.1  984.66  4988.3  984.16
  4991.8  984.16  4992.1  984.66  5002.0  984.68  5024.4  986.39  5046.7  986.60
  5069.1  990.10  5074.7  991.48  5100.6  992.35  5158.5  993.63  5217.2  996.08
#Mann=5,-1,0
  4569.4   0.035       0  4987.3    0.07       0  4988.1    0.05       0
  4992.1    0.07       0  5100.6   0.035       0
Bank Sta=4988.1,4992.1
Exp/Cntr=0.3,0.1

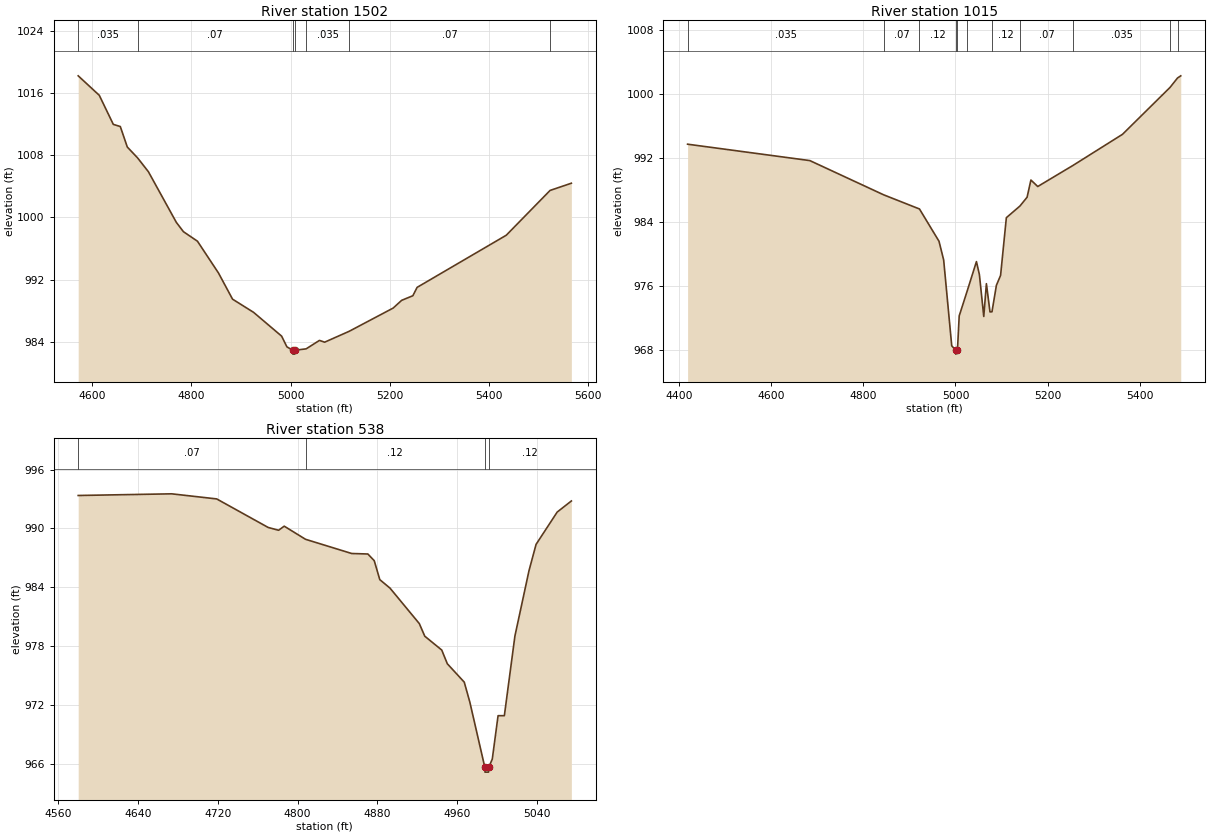
Type RM Length L Ch R = 1,1502,487,487,487
BEGIN DESCRIPTION:
Guadalupe Tributary 73 3.0
END DESCRIPTION:
XS GIS Cut Line= 3
      2162974.97     13863175.03      2163275.00     13862875.00
      2163425.00     13862325.00
#Sta/Elev= 30
  4571.8 1018.27  4614.3 1015.76  4642.6 1012.01  4656.7 1011.73  4670.8 1009.09
  4691.5 1007.69  4713.3 1005.91  4769.8  999.36  4784.0  998.17  4812.3  996.94
  4854.7  992.84  4883.0  989.47  4925.4  987.77  4982.0  984.70  4992.6  983.32
  5004.5  982.88  5004.7  982.38  5008.2  982.38  5008.5  982.88  5031.4  983.06
  5058.3  984.15  5068.7  983.92  5118.1  985.32  5206.9  988.32  5224.1  989.32
  5246.6  989.91  5255.2  990.99  5434.9  997.71  5523.3 1003.49  5566.2 1004.42
#Mann=7,-1,0
  4571.8   0.035       0  4691.5    0.07       0  5004.5    0.05       0
  5008.5    0.07       0  5031.4   0.035       0  5118.1    0.07       0
  5523.3   0.035       0
Bank Sta=5004.5,5008.5
Exp/Cntr=0.3,0.1

Type RM Length L Ch R = 1,1015,477,477,477
BEGIN DESCRIPTION:
Guadalupe Tributary 73 2.0
END DESCRIPTION:
XS GIS Cut Line= 3
      2163700.00     13863350.03      2163725.00     13862775.00
      2163480.48     13862345.27
#Sta/Elev= 30
  4418.8  993.68  4684.1  991.63  4844.2  987.35  4921.9  985.58  4964.3  981.54
  4974.4  979.20  4991.9  968.47  5000.3  967.93  5000.6  967.43  5004.3  967.93
  5008.1  972.21  5024.7  975.19  5045.5  979.00  5051.9  977.38  5061.4  972.14
  5067.1  976.24  5074.9  972.71  5079.2  972.72  5088.8  976.03  5097.9  977.28
  5110.4  984.49  5139.9  985.95  5155.4  987.05  5163.7  989.20  5178.5  988.39
  5255.1  991.03  5362.5  994.92  5465.5 1000.78  5481.8 1001.96  5488.8 1002.23
#Mann=11,-1,0
  4418.8   0.035       0  4844.2    0.07       0  4921.9    0.12       0
  5000.3    0.05       0  5004.3    0.12       0  5024.7    0.12       0
  5079.2    0.12       0  5139.9    0.07       0  5255.1   0.035       0
  5465.5    0.07       0  5481.8   0.035       0
Bank Sta=5000.3,5004.3
Exp/Cntr=0.3,0.1

Type RM Length L Ch R = 1,538,0,0,0
BEGIN DESCRIPTION:
Guadalupe Tributary 73 1.0
END DESCRIPTION:
XS GIS Cut Line= 3
      2163940.15     13863106.43      2164125.00     13862725.00
      2164175.02     13862674.98
#Sta/Elev= 30
  4579.9  993.36  4673.6  993.53  4718.8  993.01  4770.4  990.10  4780.9  989.81
  4786.5  990.23  4807.9  988.89  4854.2  987.44  4870.4  987.39  4876.8  986.71
  4882.4  984.77  4892.6  983.91  4922.0  980.29  4927.5  979.00  4944.5  977.59
  4950.1  976.19  4967.1  974.31  4972.7  972.27  4987.7  965.63  4987.9  965.13
  4991.4  965.13  4991.7  965.63  4995.2  966.46  5001.0  970.89  5007.3  970.89
  5017.9  979.02  5032.0  985.68  5039.1  988.37  5060.3  991.67  5074.5  992.80
#Mann=4,-1,0
  4579.9    0.07       0  4807.9    0.12       0  4987.7    0.05       0
  4991.7    0.12       0
Bank Sta=4987.7,4991.7
Exp/Cntr=0.3,0.1

Chan Stop Cuts=-1