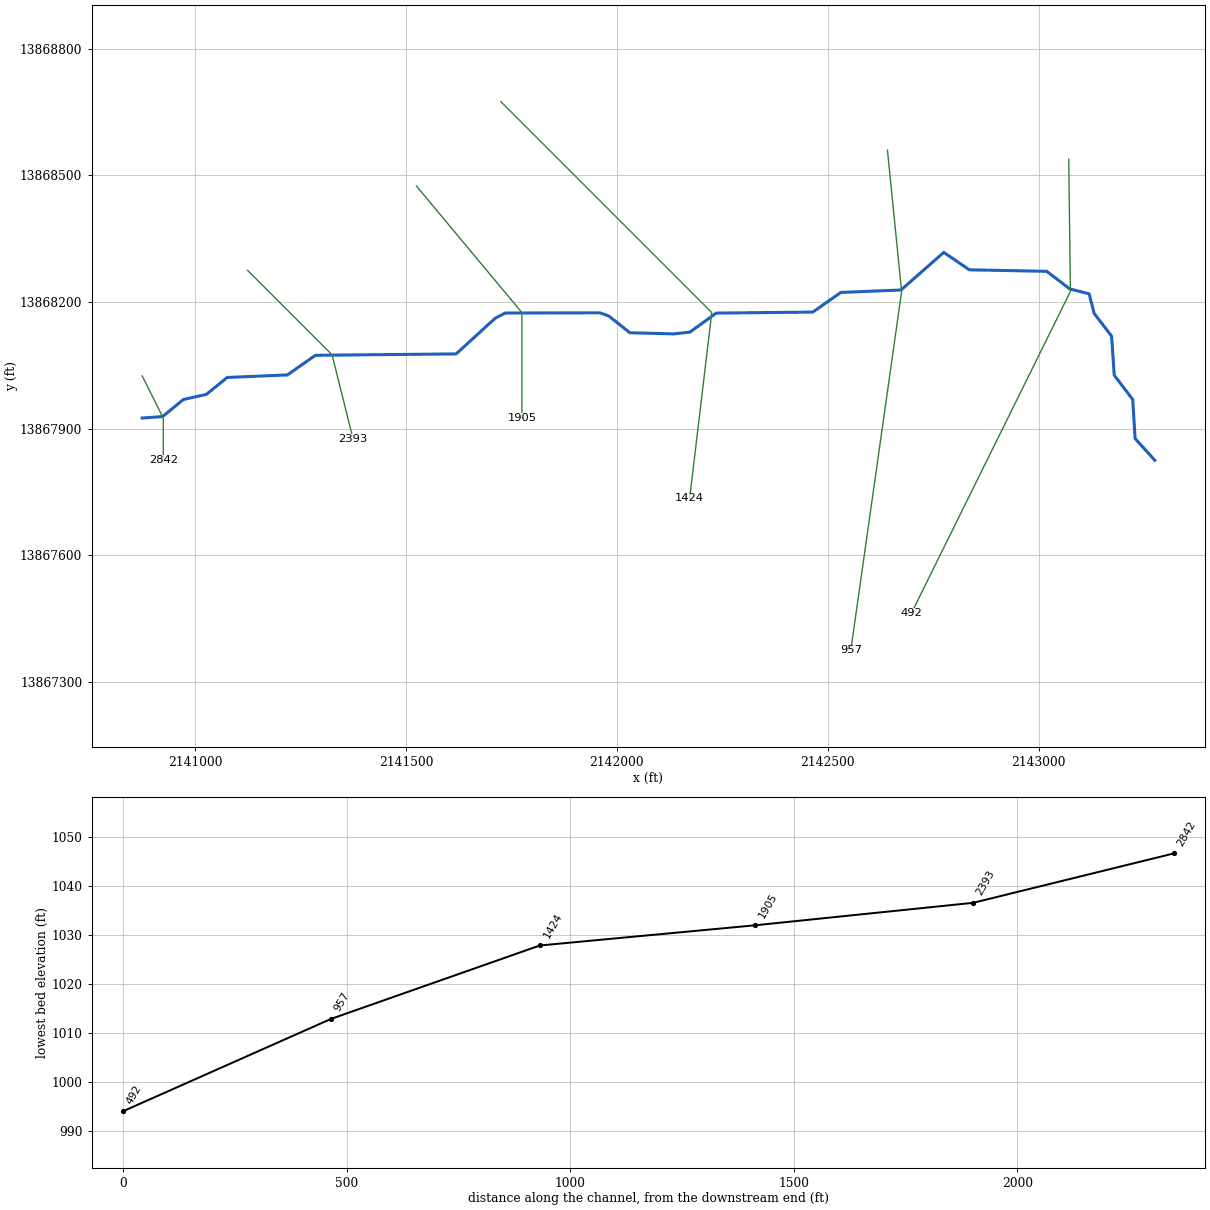
--- Guadalupe Tributary 76.prj (project) ---

Proj Title=Guadalupe Tributary 76 Base Level Engineering
Current Plan=p01
Default Exp/Contr=0.3,0.1
English Units
Geom File=g01
Flow File=f01
Plan File=p01
BEGIN DESCRIPTION:
Guadalupe Tributary 76
END DESCRIPTION:

--- Guadalupe Tributary 76.p01 (plan) ---

Plan Title=Multiple Run
Short Identifier=Multiple
Geom File=g01
Flow File=f01
Subcritical Flow
K Sum by GR= 0
Std Step Tol= 0.01
Critical Tol= 0.01
Num of Std Step Trials= 20
Max Error Tol= 0.3
Flow Tol Ratio= 0.001
Split Flow NTrial= 30
Split Flow Tol= 0.02
Split Flow Ratio= 0.02
Log Output Level= 0
Friction Slope Method= 1
Unsteady Friction Slope Method= 2
Unsteady Bridges Friction Slope Method= 1
Parabolic Critical Depth
Global Vel Dist=  1 , 1 , 1
Global Log Level= 0
CheckData=True
Encroach Param= -1, 0, 0, 0
BEGIN DESCRIPTION:
Multiple Run
END DESCRIPTION:

--- Guadalupe Tributary 76.f01 (steady flow) ---

Flow Title=Multiple
Number of Profiles=7
Profile Names=10-year,25-year,50-year,1pct_min,100-year,1pct_plu,500-year
River Rch & RM= Guadalupe Tribut,Reach-1,2842
     563     921    1250     825    1646    3285    2819
Boundary for River Rch & Prof#=Guadalupe Tribut,Reach-1,1
Up Type=0
Dn Type=3
Dn Slope=0.005
Boundary for River Rch & Prof#=Guadalupe Tribut,Reach-1,2
Up Type=0
Dn Type=3
Dn Slope=0.005
Boundary for River Rch & Prof#=Guadalupe Tribut,Reach-1,3
Up Type=0
Dn Type=3
Dn Slope=0.005
Boundary for River Rch & Prof#=Guadalupe Tribut,Reach-1,4
Up Type=0
Dn Type=3
Dn Slope=0.005
Boundary for River Rch & Prof#=Guadalupe Tribut,Reach-1,5
Up Type=0
Dn Type=3
Dn Slope=0.005
Boundary for River Rch & Prof#=Guadalupe Tribut,Reach-1,6
Up Type=0
Dn Type=3
Dn Slope=0.005
Boundary for River Rch & Prof#=Guadalupe Tribut,Reach-1,7
Up Type=0
Dn Type=3
Dn Slope=0.005

--- Guadalupe Tributary 76.g01 (geometry) ---

Geom Title=Existing Conditions

River Reach=Guadalupe Tribut,Reach-1
Reach XY= 30
      2140875.00     13867925.00      2140923.51     13867928.60
      2140972.75     13867969.05      2141027.19     13867981.11
      2141076.56     13868021.24      2141219.06     13868027.27
      2141285.50     13868073.78      2141619.14     13868077.07
      2141711.69     13868161.60      2141735.44     13868173.94
      2141959.78     13868174.48      2141981.06     13868166.86
      2142030.94     13868127.25      2142135.17     13868124.50
      2142173.43     13868128.77      2142235.50     13868173.78
      2142464.50     13868176.22      2142530.94     13868222.73
      2142673.53     13868228.57      2142774.90     13868317.67
      2142835.43     13868276.39      2143019.10     13868272.77
      2143073.16     13868231.28      2143119.42     13868219.42
      2143131.28     13868173.16      2143172.68     13868119.06
      2143178.85     13868026.60      2143222.68     13867969.04
      2143228.39     13867876.40      2143275.00     13867825.00

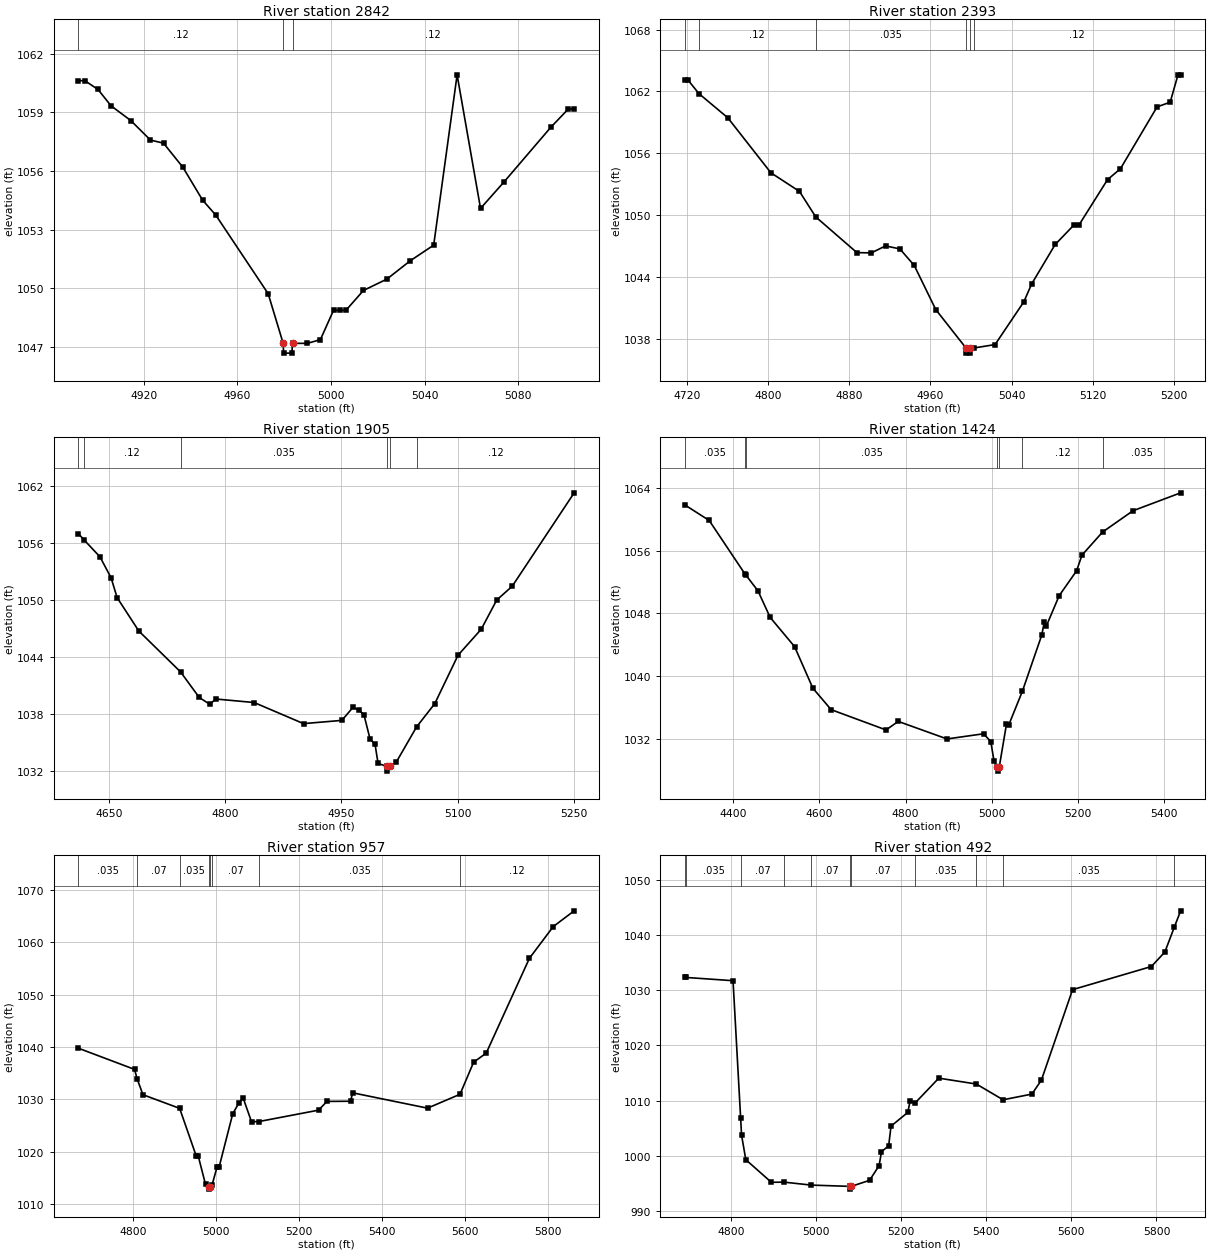
Type RM Length L Ch R = 1,2842,449,449,449
BEGIN DESCRIPTION:
Guadalupe Tributary 76 6.0
END DESCRIPTION:
XS GIS Cut Line= 3
      2140874.99     13868025.02      2140925.00     13867925.00
      2140925.00     13867825.02
#Sta/Elev= 30
  4892.1 1060.62  4894.9 1060.62  4900.5 1060.17  4906.1 1059.33  4914.5 1058.58
  4922.9 1057.58  4928.5 1057.42  4936.8 1056.18  4945.2 1054.50  4950.8 1053.74
  4973.2 1049.71  4979.6 1047.17  4979.8 1046.67  4983.3 1046.67  4983.6 1047.17
  4989.9 1047.17  4995.5 1047.36  5001.1 1048.86  5003.9 1048.86  5006.4 1048.86
  5013.9 1049.88  5023.9 1050.46  5033.9 1051.40  5043.9 1052.20  5053.9 1060.92
  5063.9 1054.08  5073.9 1055.43  5093.9 1058.23  5101.4 1059.17  5103.9 1059.17
#Mann=3,-1,0
  4892.1    0.12       0  4979.6    0.05       0  4983.6    0.12       0
Bank Sta=4979.6,4983.6
Exp/Cntr=0.3,0.1

Type RM Length L Ch R = 1,2393,488,488,488
BEGIN DESCRIPTION:
Guadalupe Tributary 76 5.0
END DESCRIPTION:
XS GIS Cut Line= 3
      2141124.99     13868275.01      2141325.00     13868075.00
      2141375.00     13867875.01
#Sta/Elev= 30
  4717.7 1063.05  4721.2 1063.05  4731.7 1061.77  4760.1 1059.43  4802.6 1054.09
  4830.8 1052.28  4846.8 1049.81  4887.4 1046.34  4901.6 1046.31  4915.7 1046.99
  4929.8 1046.70  4944.0 1045.09  4965.2 1040.81  4995.0 1037.08  4995.3 1036.58
  4998.8 1036.58  4999.0 1037.08  5002.9 1037.08  5023.7 1037.41  5052.1 1041.57
  5059.8 1043.30  5083.0 1047.13  5101.1 1048.98  5106.2 1048.98  5134.6 1053.42
  5147.4 1054.49  5183.5 1060.49  5196.4 1060.94  5204.1 1063.60  5206.7 1063.60
#Mann=6,-1,0
  4717.7   0.035       0  4731.7    0.12       0  4846.8   0.035       0
  4995.0   0.035       0  4999.0   0.035       0  5002.9    0.12       0
Bank Sta=4995,4999
Exp/Cntr=0.3,0.1

Type RM Length L Ch R = 1,1905,481,481,481
BEGIN DESCRIPTION:
Guadalupe Tributary 76 4.0
END DESCRIPTION:
XS GIS Cut Line= 3
      2141525.03     13868474.97      2141775.00     13868175.00
      2141775.00     13867924.97
#Sta/Elev= 30
  4610.1 1056.99  4617.3 1056.34  4638.0 1054.55  4652.4 1052.34  4660.2 1050.25
  4688.2 1046.74  4742.2 1042.43  4766.3 1039.74  4779.9 1039.03  4787.7 1039.58
  4837.2 1039.21  4901.0 1036.99  4950.5 1037.33  4964.8 1038.69  4972.6 1038.41
  4979.1 1037.91  4986.9 1035.38  4993.4 1034.80  4997.3 1032.80  5008.6 1032.49
  5008.8 1031.99  5012.6 1032.49  5020.6 1032.91  5047.1 1036.65  5070.6 1039.10
  5100.6 1044.19  5130.6 1046.93  5150.6 1050.00  5170.6 1051.45  5250.6 1061.28
#Mann=6,-1,0
  4610.1    0.07       0  4617.3    0.12       0  4742.2   0.035       0
  5008.6   0.035       0  5012.6   0.035       0  5047.1    0.12       0
Bank Sta=5008.6,5012.6
Exp/Cntr=0.3,0.1

Type RM Length L Ch R = 1,1424,467,467,467
BEGIN DESCRIPTION:
Guadalupe Tributary 76 3.0
END DESCRIPTION:
XS GIS Cut Line= 3
      2141725.00     13868675.00      2142225.00     13868175.00
      2142172.64     13867735.31
#Sta/Elev= 30
  4288.0 1061.87  4344.6 1059.88  4427.0 1053.09  4429.5 1052.92  4457.7 1050.89
  4486.0 1047.50  4542.6 1043.77  4585.0 1038.46  4627.4 1035.72  4754.7 1033.13
  4783.0 1034.22  4896.1 1031.98  4981.0 1032.64  4997.6 1031.64  5005.2 1029.15
  5013.2 1028.37  5013.5 1027.87  5017.2 1028.37  5033.9 1033.83  5038.9 1033.71
  5070.9 1038.07  5116.0 1045.27  5121.5 1046.88  5126.5 1046.40  5156.2 1050.27
  5196.5 1053.44  5209.1 1055.45  5256.8 1058.40  5327.4 1061.12  5437.9 1063.41
#Mann=7,-1,0
  4288.0   0.035       0  4427.0    0.12       0  4429.5   0.035       0
  5013.2   0.035       0  5017.2   0.035       0  5070.9    0.12       0
  5256.8   0.035       0
Bank Sta=5013.2,5017.2
Exp/Cntr=0.3,0.1

Type RM Length L Ch R = 1,957,465,465,465
BEGIN DESCRIPTION:
Guadalupe Tributary 76 2.0
END DESCRIPTION:
XS GIS Cut Line= 3
      2142641.40     13868559.93      2142675.00     13868225.00
      2142554.59     13867375.10
#Sta/Elev= 30
  4667.5 1039.79  4803.1 1035.74  4809.1 1033.96  4823.2 1030.91  4911.7 1028.30
  4951.4 1019.26  4956.5 1019.19  4974.0 1013.79  4982.0 1013.38  4982.3 1012.88
  4986.0 1013.38  4990.0 1013.73  5001.6 1017.04  5006.6 1017.04  5039.6 1027.26
  5054.6 1029.35  5064.7 1030.29  5084.9 1025.74  5103.1 1025.79  5246.5 1027.96
  5266.7 1029.63  5323.6 1029.66  5328.6 1031.27  5509.1 1028.34  5587.4 1030.99
  5620.2 1037.12  5650.5 1038.84  5754.6 1056.95  5812.1 1063.01  5862.5 1066.02
#Mann=8,-1,0
  4667.5   0.035       0  4809.1    0.07       0  4911.7   0.035       0
  4982.0    0.05       0  4986.0   0.035       0  4990.0    0.07       0
  5103.1   0.035       0  5587.4    0.12       0
Bank Sta=4982,4986
Exp/Cntr=0.3,0.1

Type RM Length L Ch R = 1,492,0,0,0
BEGIN DESCRIPTION:
Guadalupe Tributary 76 1.0
END DESCRIPTION:
XS GIS Cut Line= 3
      2143071.08     13868538.30      2143075.00     13868225.00
      2142697.81     13867461.85
#Sta/Elev= 30
  4692.1 1032.29  4696.0 1032.29  4805.4 1031.71  4823.2 1006.94  4825.4 1003.80
  4835.4  999.35  4895.4  995.27  4925.7  995.29  4988.8  994.76  5079.2  994.53
  5079.4  994.03  5083.2  994.53  5126.1  995.62  5148.5  998.28  5154.1 1000.81
  5170.9 1001.84  5176.5 1005.42  5215.8 1007.89  5221.4 1010.00  5232.4 1009.55
  5288.7 1014.09  5376.9 1013.03  5439.7 1010.18  5507.4 1011.21  5529.7 1013.74
  5602.9 1030.09  5787.9 1034.27  5819.7 1036.89  5841.6 1041.33  5856.7 1044.34
#Mann=11,-1,0
  4692.1    0.07       0  4696.0   0.035       0  4823.2    0.07       0
  4925.7   0.035       0  4988.8    0.07       0  5079.2    0.05       0
  5083.2    0.07       0  5232.4   0.035       0  5376.9    0.07       0
  5439.7   0.035       0  5841.6    0.12       0
Bank Sta=5079.2,5083.2
Exp/Cntr=0.3,0.1

Chan Stop Cuts=-1