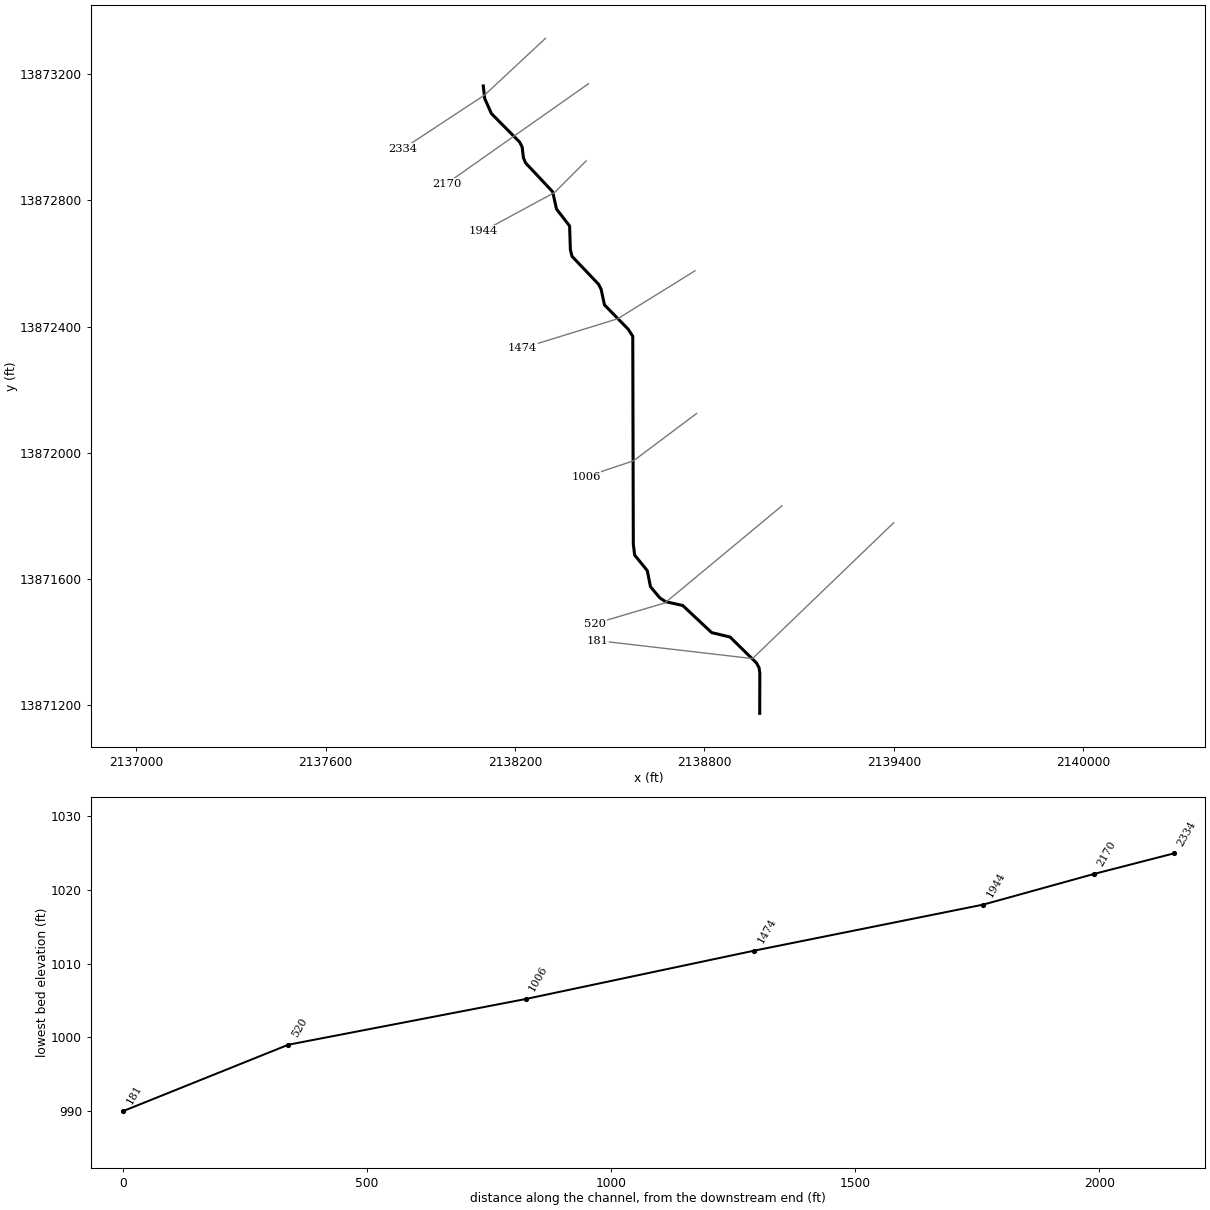
--- Guadalupe Tributary 78.prj (project) ---

Proj Title=Guadalupe Tributary 78 Base Level Engineering
Current Plan=p01
Default Exp/Contr=0.3,0.1
English Units
Geom File=g01
Flow File=f01
Plan File=p01
BEGIN DESCRIPTION:
Guadalupe Tributary 78
END DESCRIPTION:

--- Guadalupe Tributary 78.p01 (plan) ---

Plan Title=Multiple Run
Short Identifier=Multiple
Geom File=g01
Flow File=f01
Subcritical Flow
K Sum by GR= 0
Std Step Tol= 0.01
Critical Tol= 0.01
Num of Std Step Trials= 20
Max Error Tol= 0.3
Flow Tol Ratio= 0.001
Split Flow NTrial= 30
Split Flow Tol= 0.02
Split Flow Ratio= 0.02
Log Output Level= 0
Friction Slope Method= 1
Unsteady Friction Slope Method= 2
Unsteady Bridges Friction Slope Method= 1
Parabolic Critical Depth
Global Vel Dist=  1 , 1 , 1
Global Log Level= 0
CheckData=True
Encroach Param= -1, 0, 0, 0
BEGIN DESCRIPTION:
Multiple Run
END DESCRIPTION:

--- Guadalupe Tributary 78.f01 (steady flow) ---

Flow Title=Multiple
Number of Profiles=7
Profile Names=10-year,25-year,50-year,1pct_min,100-year,1pct_plu,500-year
River Rch & RM= Guadalupe Tribut,Reach-1,2334
    1180    2012    2807    1898    3787    7556    6819
River Rch & RM= Guadalupe Tribut,Reach-1,1944
    1290    2208    3090    2095    4179    8339    7565
Boundary for River Rch & Prof#=Guadalupe Tribut,Reach-1,1
Up Type=0
Dn Type=3
Dn Slope=0.005
Boundary for River Rch & Prof#=Guadalupe Tribut,Reach-1,2
Up Type=0
Dn Type=3
Dn Slope=0.005
Boundary for River Rch & Prof#=Guadalupe Tribut,Reach-1,3
Up Type=0
Dn Type=3
Dn Slope=0.005
Boundary for River Rch & Prof#=Guadalupe Tribut,Reach-1,4
Up Type=0
Dn Type=3
Dn Slope=0.005
Boundary for River Rch & Prof#=Guadalupe Tribut,Reach-1,5
Up Type=0
Dn Type=3
Dn Slope=0.005
Boundary for River Rch & Prof#=Guadalupe Tribut,Reach-1,6
Up Type=0
Dn Type=3
Dn Slope=0.005
Boundary for River Rch & Prof#=Guadalupe Tribut,Reach-1,7
Up Type=0
Dn Type=3
Dn Slope=0.005

--- Guadalupe Tributary 78.g01 (geometry) ---

Geom Title=Existing Conditions

River Reach=Guadalupe Tribut,Reach-1
Reach XY= 30
      2138099.30     13873162.58      2138103.81     13873122.72
      2138125.00     13873075.00      2138214.50     13872984.79
      2138222.44     13872968.94      2138226.33     13872935.55
      2138233.07     13872918.92      2138319.16     13872827.29
      2138331.14     13872772.83      2138372.67     13872719.03
      2138375.25     13872643.29      2138380.54     13872622.58
      2138464.20     13872534.67      2138472.46     13872518.95
      2138483.18     13872468.96      2138558.54     13872391.75
      2138572.82     13872369.55      2138574.55     13871711.18
      2138578.75     13871676.55      2138618.85     13871627.15
      2138628.86     13871576.42      2138657.95     13871541.49
      2138676.43     13871528.89      2138731.02     13871516.82
      2138822.72     13871430.87      2138881.07     13871416.85
      2138964.55     13871334.83      2138972.88     13871319.59
      2138975.28     13871302.39      2138975.00     13871175.00

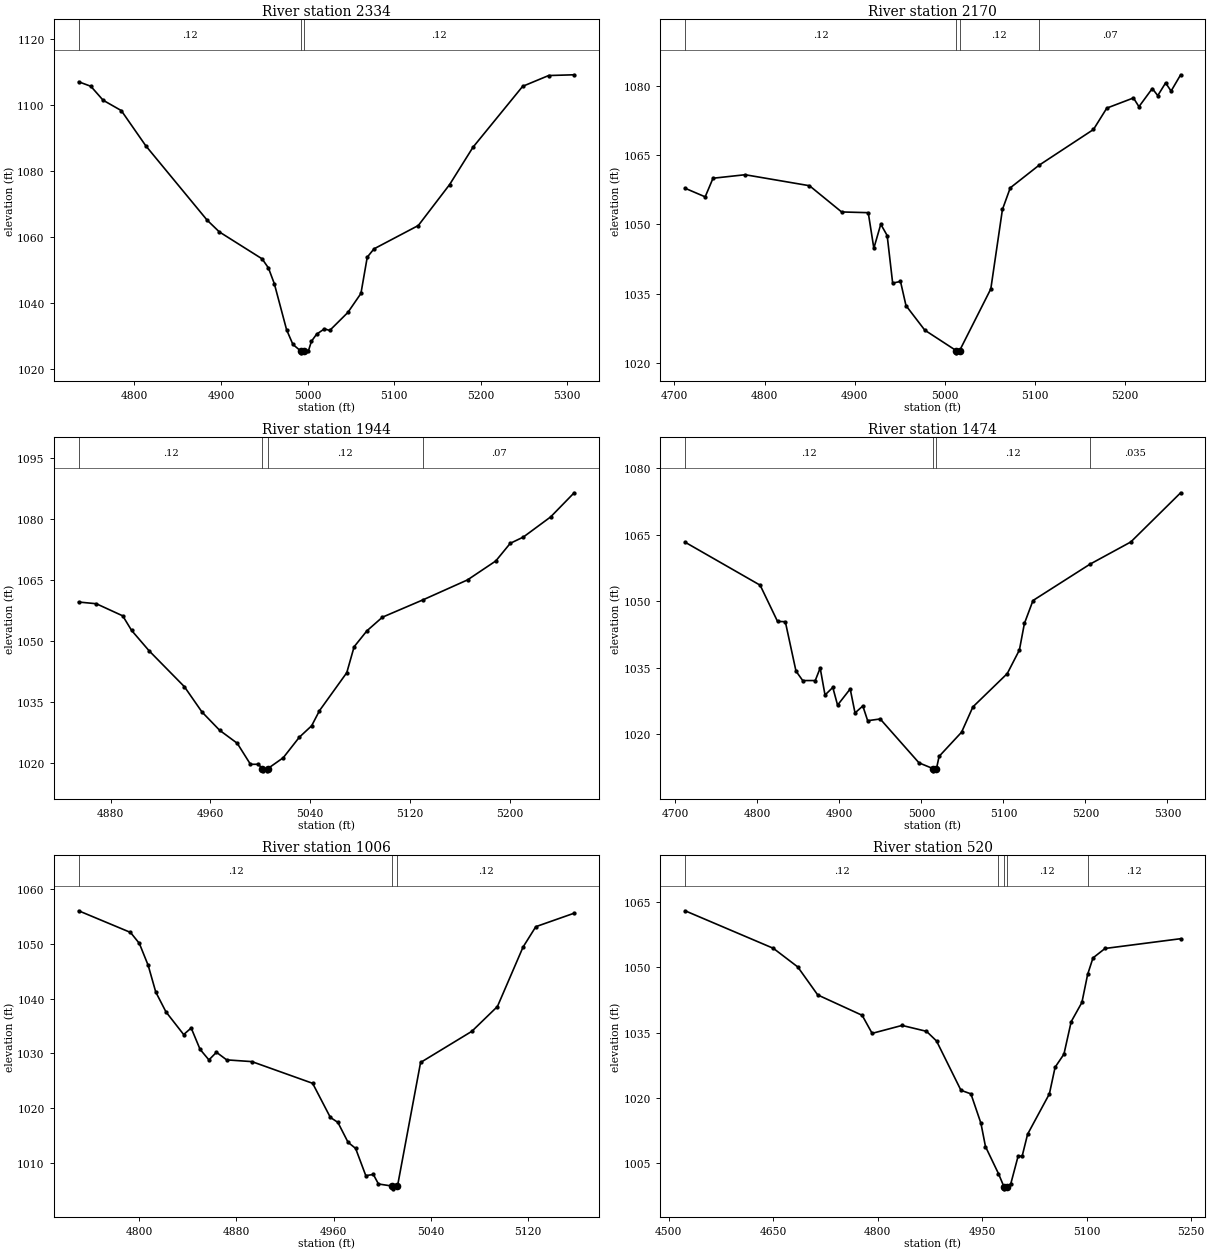
Type RM Length L Ch R = 1,2334,164,164,164
BEGIN DESCRIPTION:
Guadalupe Tributary 78 6.0
END DESCRIPTION:
XS GIS Cut Line= 3
      2138296.29     13873313.36      2138103.76     13873133.99
      2137845.27     13872963.84
#Sta/Elev= 30
  4735.5 1107.16  4749.6 1105.79  4763.8 1101.56  4784.8 1098.42  4813.1 1087.74
  4883.9 1065.21  4898.1 1061.62  4947.5 1053.45  4954.8 1050.70  4961.6 1045.93
  4975.8 1031.94  4983.1 1027.49  4992.4 1025.44  4992.6 1024.94  4996.4 1025.44
  5000.9 1025.44  5004.5 1028.44  5010.5 1030.60  5019.6 1032.23  5025.6 1031.72
  5046.6 1037.19  5061.7 1042.95  5069.0 1053.96  5076.8 1056.48  5128.0 1063.56
  5164.2 1075.99  5191.2 1087.31  5248.6 1105.78  5278.6 1109.05  5308.1 1109.28
#Mann=3,-1,0
  4735.5    0.12       0  4992.4    0.05       0  4996.4    0.12       0
Bank Sta=4992.4,4996.4
Exp/Cntr=0.3,0.1

Type RM Length L Ch R = 1,2170,226,226,226
BEGIN DESCRIPTION:
Guadalupe Tributary 78 5.0
END DESCRIPTION:
XS GIS Cut Line= 2
      2138432.69     13873169.68      2137982.65     13872852.99
#Sta/Elev= 30
  4711.8 1057.80  4734.1 1055.94  4742.8 1059.97  4778.5 1060.73  4849.9 1058.35
  4885.6 1052.67  4915.2 1052.51  4921.4 1044.81  4929.1 1050.01  4936.2 1047.56
  4942.3 1037.25  4951.0 1037.62  4957.1 1032.38  4978.0 1027.06  5012.7 1022.65
  5012.9 1022.15  5016.7 1022.65  5051.3 1036.00  5064.2 1053.20  5072.9 1057.89
  5104.6 1062.75  5165.3 1070.53  5180.1 1075.16  5209.7 1077.36  5215.8 1075.47
  5230.6 1079.40  5236.7 1077.87  5245.4 1080.62  5251.5 1078.85  5262.1 1082.38
#Mann=4,-1,0
  4711.8    0.12       0  5012.7    0.05       0  5016.7    0.12       0
  5104.6    0.07       0
Bank Sta=5012.7,5016.7
Exp/Cntr=0.3,0.1

Type RM Length L Ch R = 1,1944,470,470,470
BEGIN DESCRIPTION:
Guadalupe Tributary 78 4.0
END DESCRIPTION:
XS GIS Cut Line= 3
      2138425.03     13872925.03      2138325.00     13872825.00
      2138099.69     13872702.98
#Sta/Elev= 30
  4854.2 1059.53  4868.4 1059.11  4889.6 1056.13  4896.7 1052.55  4910.8 1047.52
  4939.1 1038.70  4953.2 1032.48  4967.4 1027.98  4981.5 1024.79  4992.1 1019.62
  4998.5 1019.62  5001.7 1018.51  5002.0 1018.01  5005.5 1018.01  5005.8 1018.51
  5018.4 1021.23  5031.3 1026.27  5041.2 1029.09  5047.5 1032.81  5069.4 1042.15
  5075.3 1048.53  5085.6 1052.46  5098.0 1055.80  5130.6 1060.07  5166.3 1064.97
  5189.0 1069.63  5200.6 1073.97  5211.1 1075.51  5233.0 1080.46  5251.9 1086.40
#Mann=4,-1,0
  4854.2    0.12       0  5001.7    0.05       0  5005.8    0.12       0
  5130.6    0.07       0
Bank Sta=5001.7,5005.8
Exp/Cntr=0.3,0.1

Type RM Length L Ch R = 1,1474,468,468,468
BEGIN DESCRIPTION:
Guadalupe Tributary 78 3.0
END DESCRIPTION:
XS GIS Cut Line= 3
      2138769.85     13872576.88      2138525.00     13872425.00
      2138223.02     13872331.68
#Sta/Elev= 30
  4711.9 1063.29  4803.4 1053.60  4824.6 1045.44  4834.1 1045.37  4847.1 1034.24
  4855.3 1032.11  4870.6 1032.11  4876.6 1034.94  4882.5 1028.85  4892.0 1030.56
  4897.8 1026.57  4913.2 1030.22  4919.1 1024.81  4928.6 1026.38  4934.5 1023.06
  4949.8 1023.45  4997.1 1013.56  5014.2 1012.26  5014.5 1011.76  5018.4 1012.26
  5021.6 1015.02  5049.0 1020.47  5062.8 1026.17  5104.7 1033.68  5119.5 1038.99
  5125.6 1044.97  5136.1 1050.15  5205.6 1058.34  5255.3 1063.34  5316.1 1074.43
#Mann=4,-1,0
  4711.9    0.12       0  5014.2    0.05       0  5018.4    0.12       0
  5205.6   0.035       0
Bank Sta=5014.2,5018.4
Exp/Cntr=0.3,0.1

Type RM Length L Ch R = 1,1006,486,486,486
BEGIN DESCRIPTION:
Guadalupe Tributary 78 2.0
END DESCRIPTION:
XS GIS Cut Line= 3
      2138775.00     13872125.00      2138575.00     13871975.00
      2138425.01     13871925.00
#Sta/Elev= 30
  4750.0 1056.09  4792.7 1052.13  4800.0 1050.12  4807.3 1046.09  4813.5 1041.23
  4821.9 1037.60  4836.5 1033.44  4842.7 1034.64  4850.0 1030.74  4857.3 1028.80
  4863.5 1030.20  4871.9 1028.81  4892.7 1028.49  4942.7 1024.52  4957.3 1018.28
  4963.5 1017.37  4971.9 1013.72  4978.1 1012.61  4986.5 1007.62  4992.7 1007.85
  4996.9 1006.10  5008.4 1005.71  5008.7 1005.21  5012.6 1005.71  5031.6 1028.33
  5073.8 1034.03  5094.9 1038.57  5116.0 1049.45  5126.5 1053.18  5158.1 1055.65
#Mann=3,-1,0
  4750.0    0.12       0  5008.4    0.05       0  5012.6    0.12       0
Bank Sta=5008.4,5012.6
Exp/Cntr=0.3,0.1

Type RM Length L Ch R = 1,520,339,339,339
BEGIN DESCRIPTION:
Guadalupe Tributary 78 1.0
END DESCRIPTION:
XS GIS Cut Line= 3
      2139045.49     13871832.55      2138675.00     13871525.00
      2138454.28     13871459.64
#Sta/Elev= 30
  4523.4 1063.05  4650.1 1054.41  4685.2 1050.12  4713.9 1043.67  4777.7 1038.98
  4792.0 1034.82  4835.0 1036.65  4870.1 1035.29  4884.5 1033.07  4919.6 1021.71
  4933.9 1020.89  4948.3 1014.11  4954.8 1008.76  4973.5 1002.51  4981.3  999.52
  4981.5  999.02  4985.6  999.52  4991.2 1000.21  5001.7 1006.56  5007.5 1006.56
  5015.3 1011.60  5046.6 1020.89  5054.8 1027.02  5067.5 1030.04  5077.9 1037.51
  5093.3 1041.94  5101.5 1048.38  5109.2 1052.19  5126.5 1054.37  5235.1 1056.62
#Mann=5,-1,0
  4523.4    0.12       0  4973.5    0.12       0  4981.3    0.05       0
  4985.6    0.12       0  5101.5    0.12       0
Bank Sta=4981.3,4985.6
Exp/Cntr=0.3,0.1

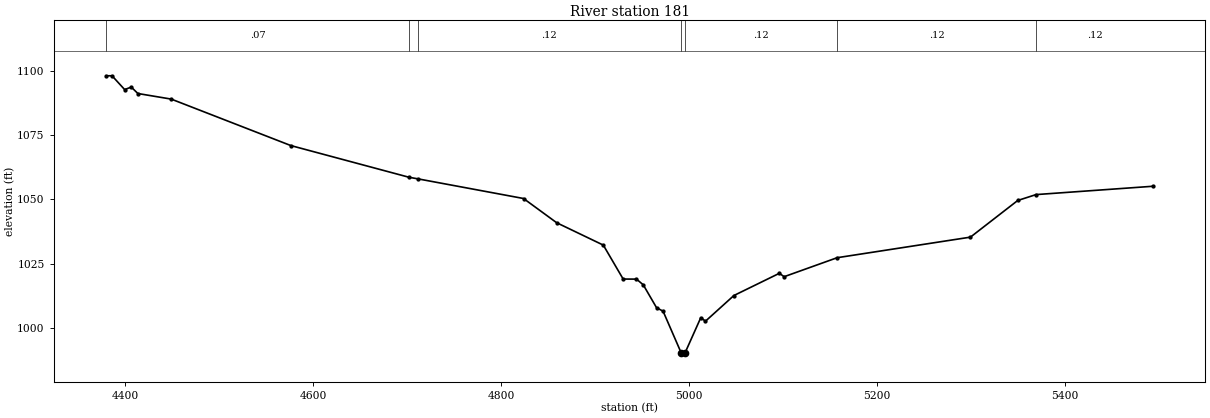
Type RM Length L Ch R = 1,181,0,0,0
BEGIN DESCRIPTION:
Guadalupe Tributary 78 0.0
END DESCRIPTION:
XS GIS Cut Line= 3
      2139399.14     13871778.67      2138952.16     13871348.58
      2138461.95     13871405.46
#Sta/Elev= 30
  4379.7 1098.04  4385.9 1098.04  4399.3 1092.69  4406.4 1093.64  4413.4 1091.15
  4448.9 1088.98  4576.2 1070.92  4701.9 1058.61  4711.1 1058.01  4823.7 1050.36
  4859.0 1040.94  4908.6 1032.25  4929.7 1019.07  4943.9 1019.04  4951.1 1016.82
  4965.2 1007.96  4972.2 1006.56  4991.3  990.51  4991.6  990.01  4995.7  990.51
  5012.3 1004.06  5017.3 1002.70  5047.5 1012.66  5095.9 1021.30  5101.0 1019.98
  5157.4 1027.36  5299.2 1035.35  5349.5 1049.59  5369.0 1051.88  5493.5 1055.12
#Mann=7,-1,0
  4379.7    0.07       0  4701.9   0.035       0  4711.1    0.12       0
  4991.3    0.05       0  4995.7    0.12       0  5157.4    0.12       0
  5369.0    0.12       0
Bank Sta=4991.3,4995.7
Exp/Cntr=0.3,0.1

Chan Stop Cuts=-1