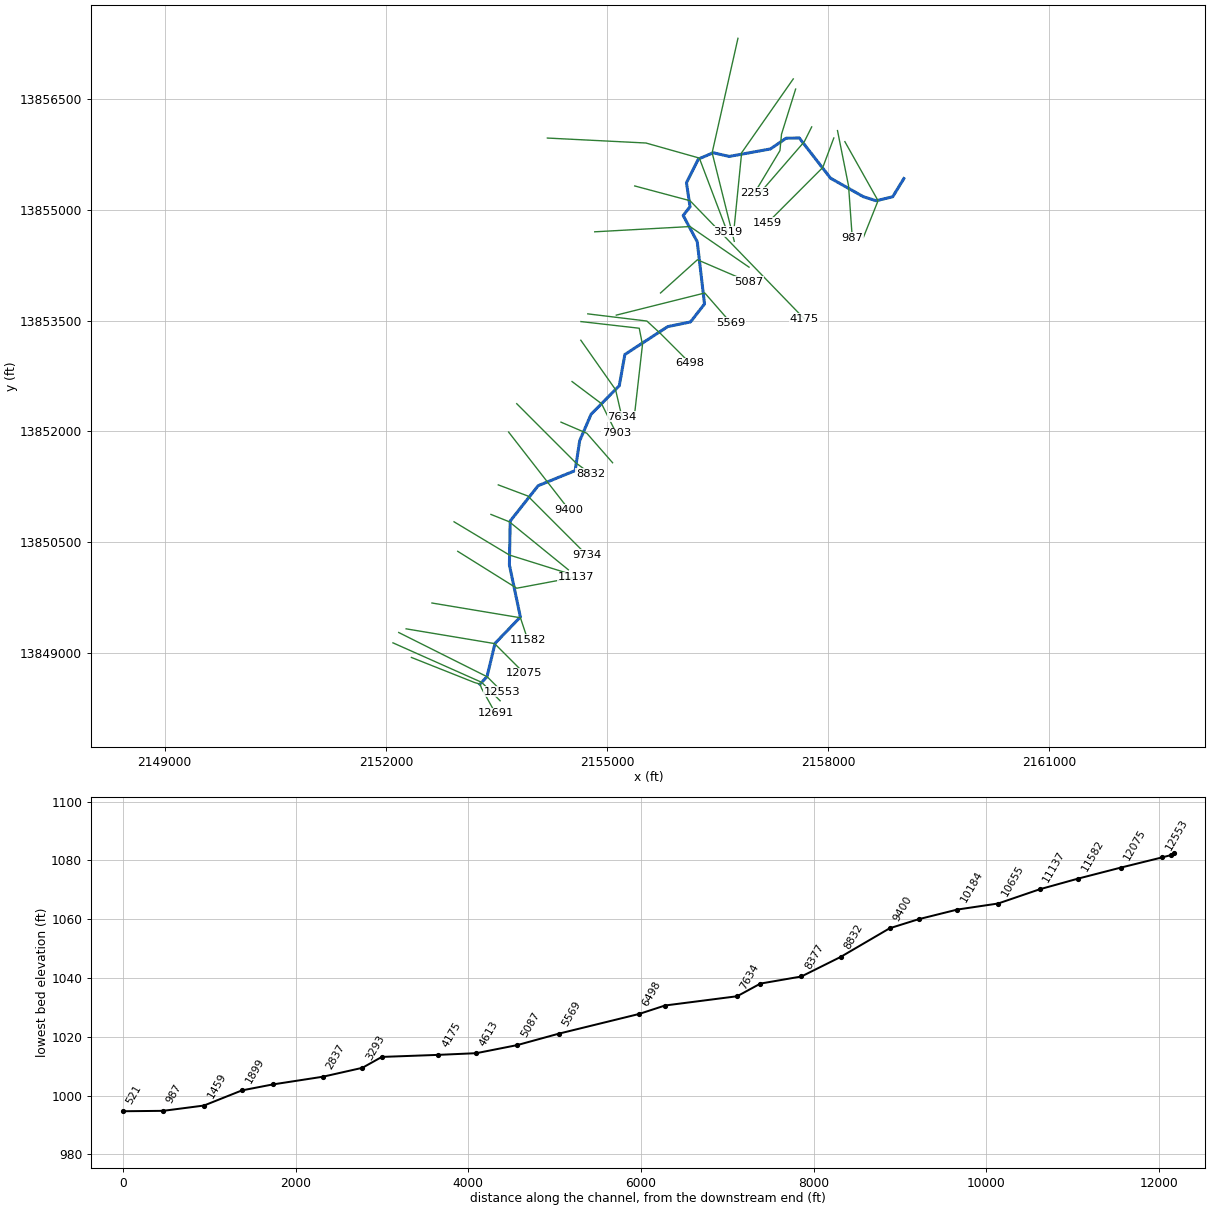
--- Hanz Creek.prj (project) ---

Proj Title=Hanz Creek Base Level Engineering
Current Plan=p01
Default Exp/Contr=0.3,0.1
English Units
Geom File=g01
Flow File=f01
Plan File=p01
BEGIN DESCRIPTION:
Hanz Creek
END DESCRIPTION:

--- Hanz Creek.p01 (plan) ---

Plan Title=Multiple Run
Short Identifier=Multiple
Geom File=g01
Flow File=f01
Subcritical Flow
K Sum by GR= 0
Std Step Tol= 0.01
Critical Tol= 0.01
Num of Std Step Trials= 20
Max Error Tol= 0.3
Flow Tol Ratio= 0.001
Split Flow NTrial= 30
Split Flow Tol= 0.02
Split Flow Ratio= 0.02
Log Output Level= 0
Friction Slope Method= 1
Unsteady Friction Slope Method= 2
Unsteady Bridges Friction Slope Method= 1
Parabolic Critical Depth
Global Vel Dist=  1 , 1 , 1
Global Log Level= 0
CheckData=True
Encroach Param= -1, 0, 0, 0
BEGIN DESCRIPTION:
Multiple Run
END DESCRIPTION:

--- Hanz Creek.f01 (steady flow) ---

Flow Title=Multiple
Number of Profiles=7
Profile Names=10-year,25-year,50-year,1pct_min,100-year,1pct_plu,500-year
River Rch & RM= Hanz Creek,Reach-1,12691
    1762    3105    4431    3061    6108   12187   11496
River Rch & RM= Hanz Creek,Reach-1,12659
    2245    3980    5699    3945    7872   15707   14881
River Rch & RM= Hanz Creek,Reach-1,5087
    2728    4865    6994    4856    9689   19332   18426
Boundary for River Rch & Prof#=Hanz Creek,Reach-1,1
Up Type=0
Dn Type=3
Dn Slope=0.005
Boundary for River Rch & Prof#=Hanz Creek,Reach-1,2
Up Type=0
Dn Type=3
Dn Slope=0.005
Boundary for River Rch & Prof#=Hanz Creek,Reach-1,3
Up Type=0
Dn Type=3
Dn Slope=0.005
Boundary for River Rch & Prof#=Hanz Creek,Reach-1,4
Up Type=0
Dn Type=3
Dn Slope=0.005
Boundary for River Rch & Prof#=Hanz Creek,Reach-1,5
Up Type=0
Dn Type=3
Dn Slope=0.005
Boundary for River Rch & Prof#=Hanz Creek,Reach-1,6
Up Type=0
Dn Type=3
Dn Slope=0.005
Boundary for River Rch & Prof#=Hanz Creek,Reach-1,7
Up Type=0
Dn Type=3
Dn Slope=0.005

--- Hanz Creek.g01 (geometry) ---

Geom Title=Existing Conditions

River Reach=Hanz Creek,Reach-1
Reach XY= 30
      2153275.00     13848575.00      2153371.44     13848676.48
      2153480.52     13849127.43      2153824.40     13849485.62
      2153675.52     13850190.22      2153686.13     13850785.04
      2154065.32     13851264.22      2154567.31     13851468.52
      2154628.62     13851873.50      2154782.86     13852231.17
      2155165.71     13852618.33      2155241.43     13853041.77
      2155822.57     13853419.48      2156131.47     13853482.70
      2156321.47     13853726.47      2156222.74     13854569.06
      2156032.29     13854925.06      2156124.90     13855043.22
      2156076.74     13855369.37      2156238.40     13855689.09
      2156439.06     13855774.84      2156656.54     13855724.89
      2157215.41     13855826.21      2157426.55     13855971.25
      2157606.79     13855974.92      2158030.47     13855430.26
      2158476.58     13855178.82      2158650.00     13855124.60
      2158873.54     13855178.54      2159025.00     13855425.00

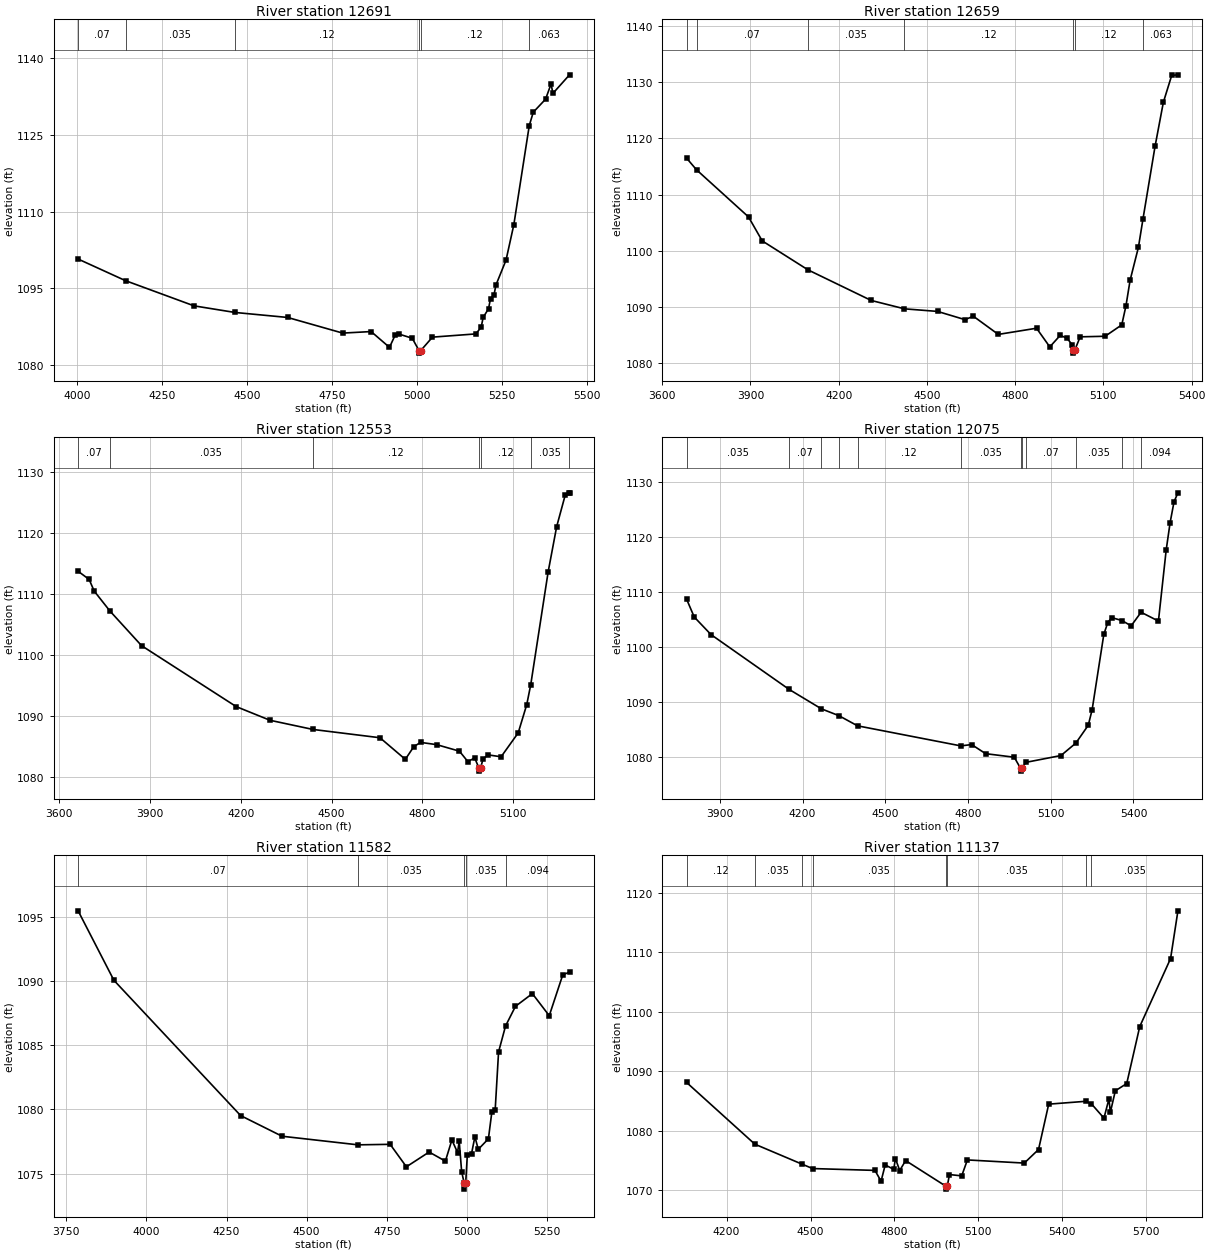
Type RM Length L Ch R = 1,12691,32,32,32
BEGIN DESCRIPTION:
Hanz Creek 27.0
END DESCRIPTION:
XS GIS Cut Line= 5
      2152346.80     13848937.43      2153204.56     13848596.94
      2153277.92     13848576.54      2153296.38     13848521.37
      2153486.31     13848181.99
#Sta/Elev= 30
  4002.1 1100.74  4141.6 1096.51  4343.3 1091.58  4463.5 1090.29  4618.7 1089.31
  4780.7 1086.25  4864.4 1086.55  4918.4 1083.46  4935.8 1085.95  4945.9 1086.07
  4985.4 1085.24  5005.3 1082.83  5005.7 1082.33  5010.4 1082.83  5044.9 1085.46
  5172.3 1086.09  5188.2 1087.39  5194.0 1089.31  5209.9 1091.02  5215.7 1093.00
  5225.9 1093.70  5231.6 1095.64  5261.4 1100.54  5284.3 1107.45  5329.8 1126.87
  5341.6 1129.48  5377.8 1132.03  5393.8 1134.98  5399.5 1133.17  5448.2 1136.79
#Mann=6,-1,0
  4002.1    0.07       0  4141.6   0.035       0  4463.5    0.12       0
  5005.3    0.05       0  5010.4    0.12       0  5329.8   0.063       0
Bank Sta=5005.3,5010.4
Exp/Cntr=0.3,0.1

Type RM Length L Ch R = 1,12659,106,106,106
BEGIN DESCRIPTION:
Hanz Creek 26.0
END DESCRIPTION:
XS GIS Cut Line= 3
      2152096.46     13849135.21      2153300.00     13848600.00
      2153549.98     13848350.02
#Sta/Elev= 30
  3682.7 1116.49  3716.8 1114.40  3893.5 1106.02  3940.0 1101.76  4095.8 1096.60
  4310.6 1091.16  4423.8 1089.67  4536.2 1089.21  4629.2 1087.75  4658.0 1088.35
  4742.7 1085.12  4872.7 1086.22  4917.8 1082.90  4953.4 1084.96  4976.6 1084.42
  4994.4 1083.25  4997.3 1082.29  4997.7 1081.79  5002.4 1082.29  5021.1 1084.69
  5105.9 1084.79  5162.5 1086.82  5176.7 1090.20  5190.8 1094.75  5219.1 1100.62
  5234.8 1105.72  5275.6 1118.56  5303.9 1126.42  5332.2 1131.19  5353.4 1131.30
#Mann=7,-1,0
  3682.7   0.035       0  3716.8    0.07       0  4095.8   0.035       0
  4423.8    0.12       0  4997.3    0.05       0  5002.4    0.12       0
  5234.8   0.063       0
Bank Sta=4997.3,5002.4
Exp/Cntr=0.3,0.1

Type RM Length L Ch R = 1,12553,478,478,478
BEGIN DESCRIPTION:
Hanz Creek 25.0
END DESCRIPTION:
XS GIS Cut Line= 3
      2152174.96     13849275.02      2153375.00     13848675.00
      2153574.98     13848475.02
#Sta/Elev= 30
  3662.2 1113.74  3698.6 1112.40  3715.4 1110.49  3767.3 1107.23  3871.9 1101.55
  4184.9 1091.56  4296.7 1089.32  4438.5 1087.82  4660.1 1086.46  4743.9 1082.92
  4771.9 1085.00  4794.3 1085.70  4847.4 1085.33  4922.8 1084.26  4950.8 1082.54
  4973.1 1083.16  4987.4 1081.49  4987.8 1080.99  4992.5 1081.49  5001.1 1083.02
  5018.0 1083.65  5060.5 1083.34  5117.0 1087.25  5145.3 1091.89  5158.5 1095.15
  5216.0 1113.62  5244.3 1121.07  5272.6 1126.24  5283.5 1126.59  5286.7 1126.59
#Mann=7,-1,0
  3662.2    0.07       0  3767.3   0.035       0  4438.5    0.12       0
  4987.4    0.05       0  4992.5    0.12       0  5158.5   0.035       0
  5283.5   0.094       0
Bank Sta=4987.4,4992.5
Exp/Cntr=0.3,0.1

Type RM Length L Ch R = 1,12075,493,493,493
BEGIN DESCRIPTION:
Hanz Creek 24.0
END DESCRIPTION:
XS GIS Cut Line= 3
      2152275.01     13849325.00      2153475.00     13849125.00
      2153874.98     13848725.02
#Sta/Elev= 30
  3779.1 1108.76  3807.0 1105.49  3867.8 1102.30  4150.9 1092.36  4268.4 1088.82
  4331.5 1087.59  4399.4 1085.74  4773.9 1082.10  4813.2 1082.34  4863.8 1080.69
  4967.8 1080.04  4990.6 1078.02  4991.0 1077.52  4995.7 1078.02  5009.7 1079.11
  5137.1 1080.35  5191.0 1082.60  5236.1 1085.84  5250.2 1088.67  5292.6 1102.35
  5306.8 1104.46  5320.9 1105.38  5358.6 1104.84  5391.6 1103.88  5427.7 1106.35
  5490.6 1104.75  5518.9 1117.72  5533.0 1122.62  5547.2 1126.40  5561.3 1128.02
#Mann=12,-1,0
  3779.1   0.035       0  4150.9    0.07       0  4268.4   0.035       0
  4331.5    0.07       0  4399.4    0.12       0  4773.9   0.035       0
  4990.6   0.035       0  4995.7   0.035       0  5009.7    0.07       0
  5191.0   0.035       0  5358.6   0.063       0  5427.7   0.094       0
Bank Sta=4990.6,4995.7
Exp/Cntr=0.3,0.1

Type RM Length L Ch R = 1,11582,445,445,445
BEGIN DESCRIPTION:
Hanz Creek 23.0
END DESCRIPTION:
XS GIS Cut Line= 3
      2152624.96     13849675.01      2153825.00     13849475.00
      2153924.99     13849175.02
#Sta/Elev= 30
  3787.1 1095.47  3898.7 1090.06  4294.0 1079.52  4423.3 1077.91  4660.3 1077.24
  4760.4 1077.28  4811.1 1075.53  4882.0 1076.68  4932.7 1075.97  4953.0 1077.62
  4970.7 1076.64  4975.8 1077.53  4983.4 1075.16  4991.0 1074.29  4991.4 1073.79
  4996.1 1074.29  5001.2 1076.47  5014.2 1076.55  5024.8 1077.87  5035.3 1076.89
  5066.9 1077.71  5077.5 1079.77  5088.0 1079.94  5098.6 1084.48  5120.4 1086.50
  5151.3 1088.03  5204.0 1089.02  5256.7 1087.30  5298.8 1090.48  5319.9 1090.70
#Mann=5,-1,0
  3787.1    0.07       0  4660.3   0.035       0  4991.0   0.035       0
  4996.1   0.035       0  5120.4   0.094       0
Bank Sta=4991,4996.1
Exp/Cntr=0.3,0.1

Type RM Length L Ch R = 1,11137,482,482,482
BEGIN DESCRIPTION:
Hanz Creek 22.0
END DESCRIPTION:
XS GIS Cut Line= 3
      2152975.01     13850374.99      2153775.00     13849875.00
      2154574.98     13850025.00
#Sta/Elev= 30
  4056.6 1088.11  4300.9 1077.72  4468.7 1074.38  4507.5 1073.62  4730.5 1073.31
  4752.3 1071.49  4767.1 1074.23  4797.7 1073.48  4803.6 1075.31  4819.0 1073.29
  4840.2 1074.96  4983.8 1070.66  4984.2 1070.16  4989.0 1070.66  4997.0 1072.61
  5040.7 1072.39  5061.0 1075.07  5264.5 1074.54  5315.4 1076.82  5351.8 1084.45
  5484.8 1084.93  5504.6 1084.50  5549.4 1082.10  5567.2 1085.32  5572.3 1083.08
  5590.1 1086.70  5630.8 1087.91  5677.4 1097.50  5787.6 1108.93  5813.9 1116.96
#Mann=8,-1,0
  4056.6    0.12       0  4300.9   0.035       0  4468.7    0.07       0
  4507.5   0.035       0  4983.8   0.035       0  4989.0   0.035       0
  5484.8   0.063       0  5504.6   0.035       0
Bank Sta=4983.8,4989
Exp/Cntr=0.3,0.1

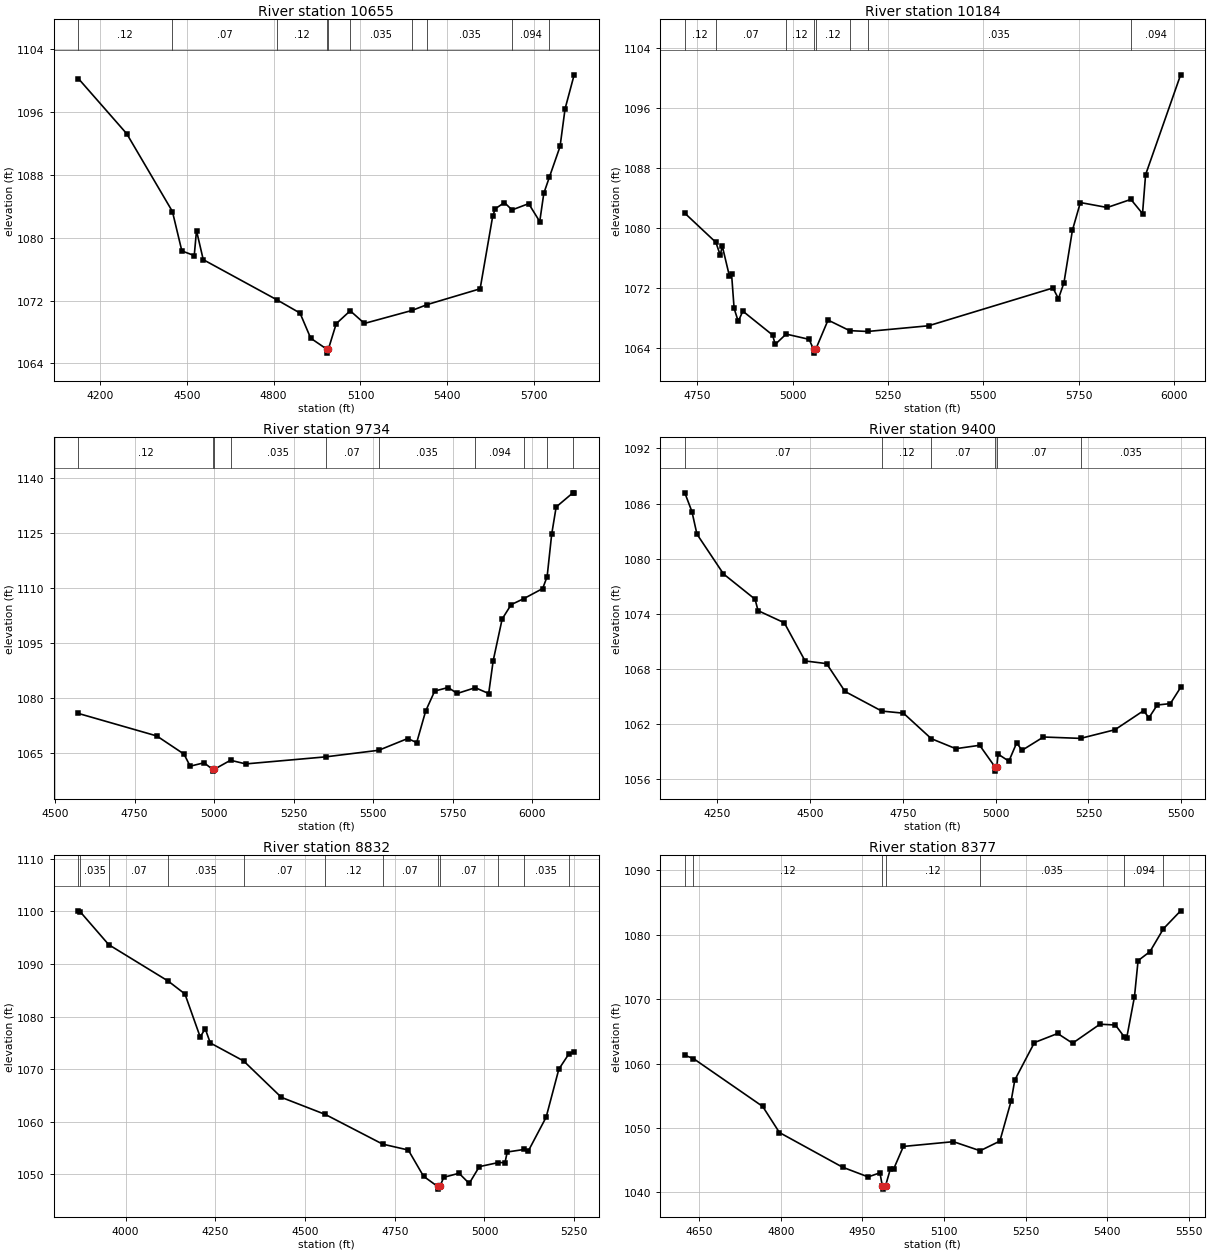
Type RM Length L Ch R = 1,10655,471,471,471
BEGIN DESCRIPTION:
Hanz Creek 21.0
END DESCRIPTION:
XS GIS Cut Line= 3
      2152925.00     13850775.00      2153675.00     13850325.00
      2154475.01     13850075.00
#Sta/Elev= 30
  4125.4 1100.28  4292.6 1093.25  4450.4 1083.35  4483.0 1078.33  4525.8 1077.74
  4533.6 1080.91  4556.9 1077.22  4811.7 1072.10  4891.2 1070.42  4928.1 1067.22
  4983.8 1065.82  4984.2 1065.32  4989.1 1065.82  5016.3 1069.07  5064.6 1070.71
  5113.7 1069.10  5277.6 1070.75  5331.3 1071.51  5513.4 1073.51  5556.9 1082.77
  5565.8 1083.70  5597.2 1084.49  5623.6 1083.55  5681.0 1084.35  5719.3 1082.07
  5733.4 1085.67  5752.4 1087.70  5789.5 1091.63  5806.8 1096.42  5838.2 1100.75
#Mann=10,-1,0
  4125.4    0.12       0  4450.4    0.07       0  4811.7    0.12       0
  4983.8    0.05       0  4989.1    0.12       0  5064.6   0.035       0
  5277.6    0.07       0  5331.3   0.035       0  5623.6   0.094       0
  5752.4   0.035       0
Bank Sta=4983.8,4989.1
Exp/Cntr=0.3,0.1

Type RM Length L Ch R = 1,10184,450,450,450
BEGIN DESCRIPTION:
Hanz Creek 20.0
END DESCRIPTION:
XS GIS Cut Line= 3
      2153424.96     13850875.02      2153675.00     13850775.00
      2154475.01     13850124.99
#Sta/Elev= 30
  4717.0 1081.94  4798.5 1078.05  4809.9 1076.35  4815.3 1077.55  4834.2 1073.51
  4839.6 1073.85  4846.3 1069.24  4857.1 1067.51  4869.2 1068.87  4947.3 1065.68
  4954.0 1064.43  4982.7 1065.81  5043.0 1065.11  5054.6 1063.77  5055.1 1063.27
  5060.2 1063.77  5092.6 1067.68  5149.2 1066.27  5196.3 1066.16  5356.2 1066.92
  5682.3 1071.96  5696.7 1070.54  5711.1 1072.64  5733.4 1079.67  5754.2 1083.36
  5824.6 1082.70  5886.7 1083.78  5917.2 1081.88  5925.2 1087.07  6017.1 1100.40
#Mann=8,-1,0
  4717.0    0.12       0  4798.5    0.07       0  4982.7    0.12       0
  5054.6    0.05       0  5060.2    0.12       0  5149.2    0.07       0
  5196.3   0.035       0  5886.7   0.094       0
Bank Sta=5054.6,5060.2
Exp/Cntr=0.3,0.1

Type RM Length L Ch R = 1,9734,334,334,334
BEGIN DESCRIPTION:
Hanz Creek 19.0
END DESCRIPTION:
XS GIS Cut Line= 3
      2153524.96     13851275.02      2153925.00     13851125.00
      2154724.99     13850325.01
#Sta/Elev= 30
  4573.0 1075.74  4819.6 1069.59  4905.0 1064.64  4924.6 1061.33  4968.2 1062.26
  4994.8 1060.48  4995.2 1059.98  5000.4 1060.48  5051.4 1062.95  5099.2 1061.95
  5350.8 1063.88  5517.4 1065.68  5608.4 1068.89  5636.6 1067.77  5664.9 1076.41
  5693.2 1081.85  5735.6 1082.82  5763.9 1081.19  5820.7 1082.77  5862.9 1081.18
  5877.1 1090.15  5905.3 1101.54  5933.6 1105.46  5973.0 1107.08  6032.6 1109.85
  6046.7 1113.14  6060.9 1124.65  6075.0 1132.13  6127.0 1135.95  6131.6 1136.00
#Mann=10,-1,0
  4573.0    0.12       0  4994.8    0.05       0  5000.4    0.12       0
  5051.4   0.035       0  5350.8    0.07       0  5517.4   0.035       0
  5820.7   0.094       0  5973.0   0.063       0  6046.7   0.094       0
  6127.0   0.035       0
Bank Sta=4994.8,5000.4
Exp/Cntr=0.3,0.1

Type RM Length L Ch R = 1,9400,568,568,568
BEGIN DESCRIPTION:
Hanz Creek 18.0
END DESCRIPTION:
XS GIS Cut Line= 2
      2153664.72     13851990.78      2154485.70     13850936.41
#Sta/Elev= 30
  4162.2 1087.17  4181.5 1085.12  4194.9 1082.68  4266.5 1078.35  4351.6 1075.60
  4359.6 1074.36  4430.3 1073.04  4486.4 1068.89  4544.3 1068.60  4594.0 1065.57
  4693.0 1063.44  4751.5 1063.21  4826.5 1060.44  4892.6 1059.35  4956.9 1059.72
  4997.4 1057.41  4997.9 1056.91  5003.2 1057.41  5006.6 1058.76  5035.6 1057.99
  5056.7 1059.99  5070.9 1059.17  5128.8 1060.62  5228.8 1060.47  5321.5 1061.41
  5398.9 1063.49  5412.9 1062.70  5435.5 1064.10  5470.8 1064.25  5498.5 1066.01
#Mann=6,-1,0
  4162.2    0.07       0  4693.0    0.12       0  4826.5    0.07       0
  4997.4    0.05       0  5003.2    0.07       0  5228.8   0.035       0
Bank Sta=4997.4,5003.2
Exp/Cntr=0.3,0.1

Type RM Length L Ch R = 1,8832,455,455,455
BEGIN DESCRIPTION:
Hanz Creek 17.0
END DESCRIPTION:
XS GIS Cut Line= 3
      2153774.99     13852375.01      2154575.00     13851575.00
      2154775.01     13851424.99
#Sta/Elev= 30
  3868.5 1100.11  3873.6 1099.94  3953.2 1093.67  4118.9 1086.74  4165.5 1084.29
  4207.9 1076.13  4222.1 1077.65  4236.2 1074.97  4329.1 1071.54  4434.2 1064.62
  4556.9 1061.36  4716.4 1055.72  4787.8 1054.60  4830.2 1049.61  4869.7 1047.66
  4870.2 1047.16  4875.6 1047.66  4886.7 1049.41  4929.2 1050.18  4957.5 1048.24
  4985.7 1051.44  5039.1 1052.22  5057.2 1052.20  5063.4 1054.22  5109.6 1054.70
  5121.8 1054.37  5171.8 1060.84  5207.2 1069.98  5235.6 1072.93  5249.9 1073.29
#Mann=12,-1,0
  3868.5    0.07       0  3873.6   0.035       0  3953.2    0.07       0
  4118.9   0.035       0  4329.1    0.07       0  4556.9    0.12       0
  4716.4    0.07       0  4869.7    0.05       0  4875.6    0.07       0
  5039.1    0.12       0  5109.6   0.035       0  5235.6   0.094       0
Bank Sta=4869.7,4875.6
Exp/Cntr=0.3,0.1

Type RM Length L Ch R = 1,8377,474,474,474
BEGIN DESCRIPTION:
Hanz Creek 16.0
END DESCRIPTION:
XS GIS Cut Line= 3
      2154374.97     13852125.01      2154725.00     13851975.00
      2155074.98     13851575.02
#Sta/Elev= 30
  4623.1 1061.29  4638.9 1060.79  4766.4 1053.35  4797.2 1049.30  4913.3 1043.92
  4960.4 1042.41  4982.2 1043.04  4986.5 1041.01  4987.0 1040.51  4992.4 1041.01
  5001.2 1043.60  5007.2 1043.60  5025.3 1047.14  5117.3 1047.88  5166.5 1046.47
  5202.8 1047.97  5223.6 1054.22  5230.3 1057.46  5266.4 1063.27  5309.1 1064.68
  5336.6 1063.17  5386.9 1066.12  5415.4 1066.00  5432.0 1064.12  5436.3 1064.05
  5450.5 1070.41  5457.1 1075.99  5479.0 1077.40  5503.8 1080.95  5535.4 1083.73
#Mann=7,-1,0
  4623.1    0.07       0  4638.9    0.12       0  4986.5    0.05       0
  4992.4    0.12       0  5166.5   0.035       0  5432.0   0.094       0
  5503.8   0.035       0
Bank Sta=4986.5,4992.4
Exp/Cntr=0.3,0.1

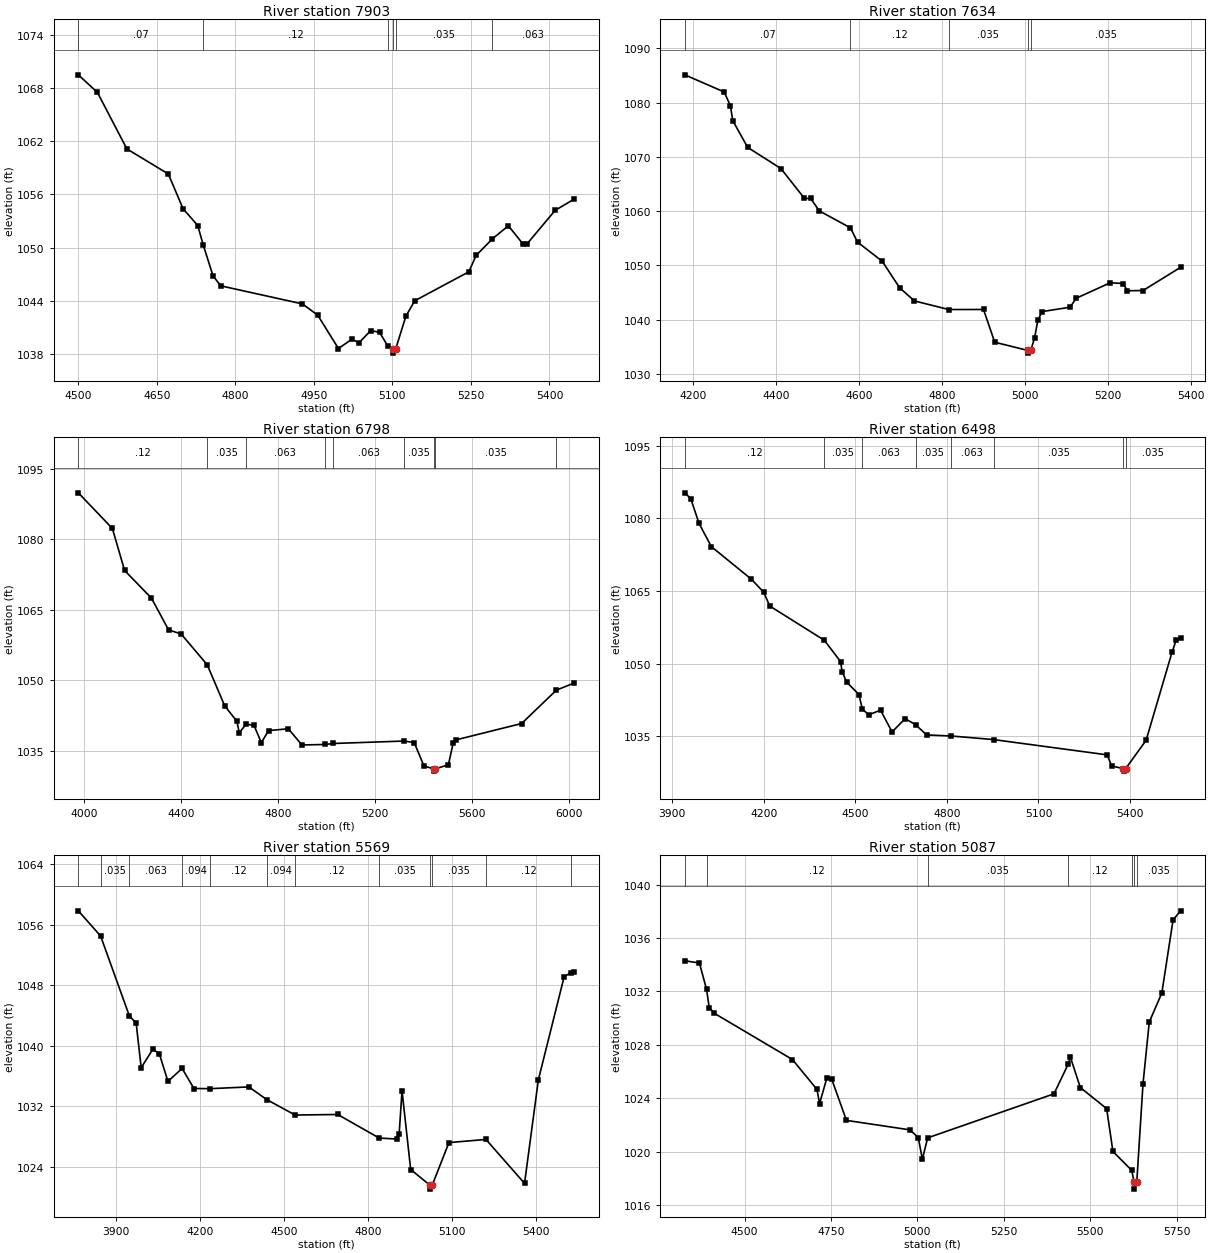
Type RM Length L Ch R = 1,7903,269,269,269
BEGIN DESCRIPTION:
Hanz Creek 15.0
END DESCRIPTION:
XS GIS Cut Line= 3
      2154524.99     13852675.01      2154925.00     13852375.00
      2155124.99     13851975.03
#Sta/Elev= 30
  4500.0 1069.48  4536.5 1067.49  4592.7 1061.13  4671.9 1058.30  4700.0 1054.39
  4728.1 1052.49  4738.6 1050.30  4757.3 1046.82  4771.9 1045.69  4928.1 1043.65
  4957.3 1042.38  4996.9 1038.62  5022.4 1039.66  5036.4 1039.28  5058.7 1040.65
  5075.5 1040.44  5091.2 1038.90  5100.4 1038.60  5100.9 1038.10  5106.4 1038.60
  5125.8 1042.27  5142.6 1044.00  5246.0 1047.27  5260.0 1049.12  5290.7 1050.97
  5321.5 1052.46  5349.4 1050.41  5357.8 1050.46  5410.9 1054.20  5447.2 1055.46
#Mann=6,-1,0
  4500.0    0.07       0  4738.6    0.12       0  5091.2   0.035       0
  5100.4    0.05       0  5106.4   0.035       0  5290.7   0.063       0
Bank Sta=5100.4,5106.4
Exp/Cntr=0.3,0.1

Type RM Length L Ch R = 1,7634,836,836,836
BEGIN DESCRIPTION:
Hanz Creek 14.0
END DESCRIPTION:
XS GIS Cut Line= 3
      2154643.80     13853235.15      2155115.30     13852565.00
      2155200.00     13852200.00
#Sta/Elev= 30
  4180.6 1085.13  4275.4 1081.97  4290.2 1079.46  4296.3 1076.66  4332.0 1071.75
  4412.1 1067.85  4468.8 1062.33  4483.6 1062.34  4504.5 1060.04  4579.4 1056.91
  4596.9 1054.26  4656.1 1050.74  4697.9 1045.86  4733.6 1043.43  4816.3 1041.84
  4900.0 1041.85  4927.0 1035.81  5006.7 1034.30  5007.2 1033.80  5013.9 1034.30
  5023.2 1036.67  5030.8 1039.88  5041.1 1041.46  5108.5 1042.27  5123.2 1043.92
  5205.3 1046.78  5236.1 1046.64  5246.7 1045.30  5284.3 1045.35  5374.7 1049.63
#Mann=5,-1,0
  4180.6    0.07       0  4579.4    0.12       0  4816.3   0.035       0
  5006.7   0.035       0  5013.9   0.035       0
Bank Sta=5006.7,5013.9
Exp/Cntr=0.3,0.1

Type RM Length L Ch R = 1,6798,300,300,300
BEGIN DESCRIPTION:
Hanz Creek 13.0
END DESCRIPTION:
XS GIS Cut Line= 4
      2154645.46     13853487.67      2155436.28     13853397.38
      2155480.16     13853174.62      2155364.68     13852159.77
#Sta/Elev= 30
  3977.0 1089.85  4117.4 1082.27  4167.8 1073.33  4278.5 1067.45  4348.9 1060.71
  4400.8 1059.82  4508.4 1053.28  4580.4 1044.55  4630.8 1041.24  4640.8 1038.77
  4668.0 1040.63  4701.2 1040.41  4731.4 1036.72  4761.6 1039.27  4842.8 1039.66
  4899.2 1036.21  4992.2 1036.32  5028.5 1036.53  5320.7 1037.05  5361.9 1036.72
  5402.2 1031.73  5441.9 1031.15  5442.4 1030.65  5449.2 1031.15  5502.8 1031.99
  5523.0 1036.70  5535.1 1037.31  5804.8 1040.78  5948.2 1047.88  6021.4 1049.39
#Mann=9,-1,0
  3977.0    0.12       0  4508.4   0.035       0  4668.0   0.063       0
  4992.2   0.035       0  5028.5   0.063       0  5320.7   0.035       0
  5441.9   0.035       0  5449.2   0.035       0  5948.2    0.12       0
Bank Sta=5441.9,5449.2
Exp/Cntr=0.3,0.1

Type RM Length L Ch R = 1,6498,929,929,929
BEGIN DESCRIPTION:
Hanz Creek 12.0
END DESCRIPTION:
XS GIS Cut Line= 4
      2154738.61     13853592.08      2155539.88     13853494.89
      2155725.00     13853325.00      2156125.00     13852925.00
#Sta/Elev= 30
  3941.6 1085.28  3961.0 1084.09  3988.3 1078.95  4028.6 1074.16  4159.6 1067.43
  4199.9 1064.75  4220.0 1061.88  4398.5 1054.82  4451.7 1050.42  4457.0 1048.31
  4471.9 1046.16  4512.1 1043.59  4522.9 1040.63  4543.8 1039.40  4582.7 1040.37
  4620.6 1035.86  4663.2 1038.62  4697.4 1037.37  4733.8 1035.25  4814.2 1035.03
  4953.0 1034.29  5325.3 1031.13  5339.4 1028.86  5378.2 1028.27  5378.7 1027.77
  5385.5 1028.27  5452.6 1034.14  5537.4 1052.30  5551.6 1054.93  5565.7 1055.20
#Mann=8,-1,0
  3941.6    0.12       0  4398.5   0.035       0  4522.9   0.063       0
  4697.4   0.035       0  4814.2   0.063       0  4953.0   0.035       0
  5378.2   0.035       0  5385.5   0.035       0
Bank Sta=5378.2,5385.5
Exp/Cntr=0.3,0.1

Type RM Length L Ch R = 1,5569,482,482,482
BEGIN DESCRIPTION:
Hanz Creek 11.0
END DESCRIPTION:
XS GIS Cut Line= 3
      2155124.96     13853574.99      2156325.00     13853875.00
      2156675.01     13853474.99
#Sta/Elev= 30
  3767.2 1057.81  3846.6 1054.49  3949.3 1043.93  3973.4 1043.01  3991.4 1037.11
  4032.7 1039.52  4055.9 1038.97  4086.8 1035.30  4137.2 1037.01  4179.6 1034.36
  4238.0 1034.34  4375.4 1034.57  4439.6 1032.89  4540.4 1030.86  4692.4 1030.93
  4840.4 1027.82  4903.7 1027.69  4911.4 1028.29  4921.7 1034.07  4952.6 1023.67
  5021.9 1021.58  5022.4 1021.08  5029.2 1021.58  5089.1 1027.22  5221.0 1027.64
  5358.7 1021.84  5408.0 1035.50  5500.1 1049.13  5525.3 1049.66  5535.7 1049.79
#Mann=12,-1,0
  3767.2    0.12       0  3846.6   0.035       0  3949.3   0.063       0
  4137.2   0.094       0  4238.0    0.12       0  4439.6   0.094       0
  4540.4    0.12       0  4840.4   0.035       0  5021.9   0.035       0
  5029.2   0.035       0  5221.0    0.12       0  5525.3   0.035       0
Bank Sta=5021.9,5029.2
Exp/Cntr=0.3,0.1

Type RM Length L Ch R = 1,5087,474,474,474
BEGIN DESCRIPTION:
Hanz Creek 10.0
END DESCRIPTION:
XS GIS Cut Line= 3
      2155724.97     13853874.97      2156225.00     13854325.00
      2156925.00     13854025.00
#Sta/Elev= 30
  4327.3 1034.30  4369.6 1034.13  4390.3 1032.15  4398.0 1030.78  4412.2 1030.37
  4638.6 1026.90  4709.6 1024.66  4717.1 1023.60  4738.0 1025.49  4752.3 1025.43
  4794.9 1022.34  4978.7 1021.63  5002.7 1021.05  5014.5 1019.43  5029.8 1021.03
  5395.3 1024.33  5436.5 1026.56  5442.5 1027.09  5471.5 1024.80  5547.6 1023.22
  5565.8 1020.01  5620.0 1018.60  5627.3 1017.69  5627.8 1017.19  5634.7 1017.69
  5652.8 1025.09  5670.9 1029.71  5707.2 1031.88  5739.8 1037.36  5761.6 1038.04
#Mann=7,-1,0
  4327.3    0.12       0  4390.3    0.12       0  5029.8   0.035       0
  5436.5    0.12       0  5620.0   0.035       0  5627.3    0.05       0
  5634.7   0.035       0
Bank Sta=5627.3,5634.7
Exp/Cntr=0.3,0.1

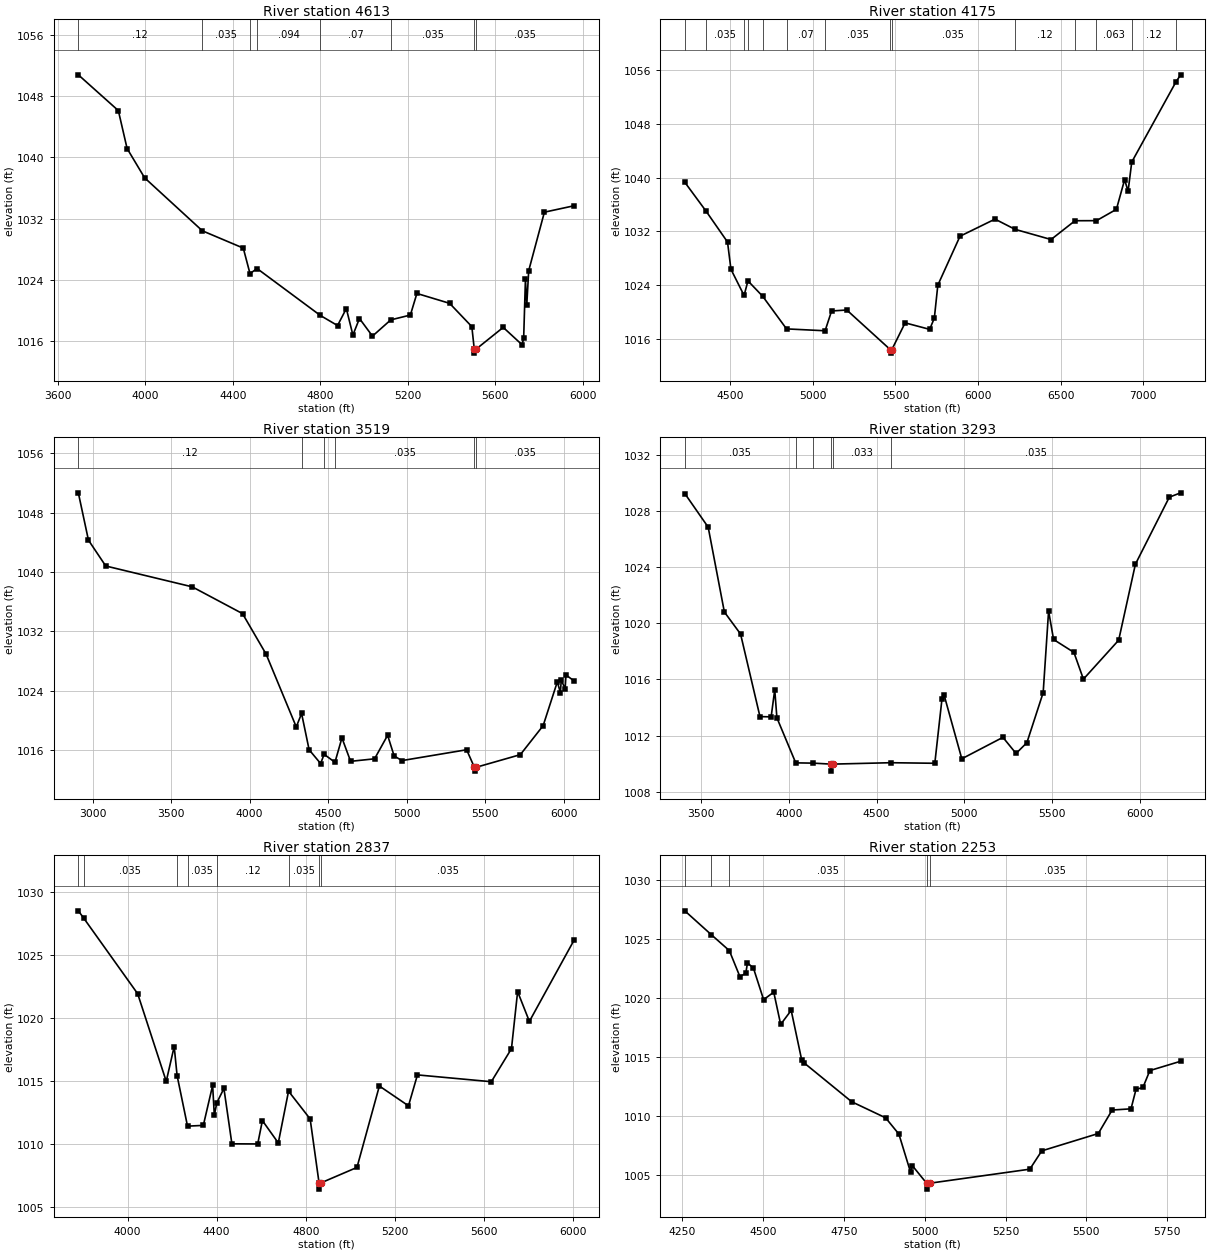
Type RM Length L Ch R = 1,4613,438,438,438
BEGIN DESCRIPTION:
Hanz Creek 9.0
END DESCRIPTION:
XS GIS Cut Line= 3
      2154832.50     13854703.79      2156125.00     13854775.00
      2156925.01     13854224.99
#Sta/Elev= 30
  3694.7 1050.77  3877.5 1046.10  3917.5 1041.15  3997.7 1037.32  4261.2 1030.41
  4448.3 1028.15  4478.9 1024.83  4511.4 1025.48  4800.3 1019.36  4879.0 1018.04
  4919.1 1020.26  4949.1 1016.80  4979.1 1018.96  5038.5 1016.66  5122.1 1018.78
  5211.7 1019.41  5241.5 1022.23  5391.0 1020.94  5492.5 1017.90  5503.7 1014.94
  5504.2 1014.44  5511.1 1014.94  5635.9 1017.80  5722.5 1015.52  5729.4 1016.47
  5737.4 1024.08  5743.5 1020.74  5752.3 1025.20  5824.0 1032.84  5960.0 1033.68
#Mann=8,-1,0
  3694.7    0.12       0  4261.2   0.035       0  4478.9   0.063       0
  4511.4   0.094       0  4800.3    0.07       0  5122.1   0.035       0
  5503.7    0.05       0  5511.1   0.035       0
Bank Sta=5503.7,5511.1
Exp/Cntr=0.3,0.1

Type RM Length L Ch R = 1,4175,656,656,656
BEGIN DESCRIPTION:
Hanz Creek 8.0
END DESCRIPTION:
XS GIS Cut Line= 3
      2155374.97     13855325.01      2156125.00     13855125.00
      2157674.99     13853525.01
#Sta/Elev= 30
  4223.6 1039.32  4352.6 1035.01  4482.4 1030.42  4503.1 1026.36  4582.7 1022.46
  4606.3 1024.63  4695.7 1022.33  4839.9 1017.48  5073.6 1017.20  5112.9 1020.15
  5205.0 1020.29  5469.7 1014.37  5470.2 1013.87  5477.5 1014.37  5558.4 1018.38
  5707.1 1017.41  5735.4 1019.09  5756.5 1023.99  5890.9 1031.28  6103.0 1033.83
  6224.1 1032.31  6442.5 1030.79  6587.7 1033.59  6717.8 1033.60  6838.5 1035.29
  6888.1 1039.70  6909.2 1037.98  6931.4 1042.33  7199.1 1054.26  7227.5 1055.32
#Mann=14,-1,0
  4223.6    0.12       0  4352.6   0.035       0  4582.7   0.063       0
  4606.3    0.07       0  4695.7   0.035       0  4839.9    0.07       0
  5073.6   0.035       0  5469.7    0.05       0  5477.5   0.035       0
  6224.1    0.12       0  6587.7    0.07       0  6717.8   0.063       0
  6931.4    0.12       0  7199.1   0.035       0
Bank Sta=5469.7,5477.5
Exp/Cntr=0.3,0.1

Type RM Length L Ch R = 1,3519,226,226,226
BEGIN DESCRIPTION:
Hanz Creek 7.5
END DESCRIPTION:
XS GIS Cut Line= 4
      2154190.69     13855973.95      2155527.51     13855906.75
      2156251.18     13855702.68      2156629.85     13854704.82
#Sta/Elev= 30
  2909.6 1050.68  2974.0 1044.30  3084.1 1040.82  3634.8 1038.01  3955.2 1034.40
  4105.4 1028.94  4297.5 1019.13  4331.4 1020.94  4379.4 1016.05  4452.7 1014.19
  4474.8 1015.44  4543.9 1014.36  4588.4 1017.65  4643.5 1014.49  4796.2 1014.83
  4879.3 1018.00  4920.8 1015.22  4970.3 1014.59  5382.6 1016.05  5432.2 1013.67
  5432.7 1013.17  5440.0 1013.67  5724.5 1015.39  5869.8 1019.30  5960.2 1025.21
  5979.7 1023.73  5985.0 1025.47  6009.8 1024.25  6015.2 1026.13  6067.3 1025.32
#Mann=6,-1,0
  2909.6    0.12       0  4331.4   0.035       0  4474.8   0.063       0
  4543.9   0.035       0  5432.2   0.035       0  5440.0   0.035       0
Bank Sta=5432.2,5440
Exp/Cntr=0.3,0.1

Type RM Length L Ch R = 1,3293,456,456,456
BEGIN DESCRIPTION:
Hanz Creek 7.0
END DESCRIPTION:
XS GIS Cut Line= 3
      2156775.00     13857325.01      2156425.00     13855775.00
      2156725.01     13854574.97
#Sta/Elev= 30
  3407.3 1029.26  3540.6 1026.86  3632.8 1020.81  3725.1 1019.24  3835.7 1013.35
  3899.4 1013.33  3919.9 1015.26  3932.3 1013.26  4039.5 1010.05  4138.9 1010.03
  4240.9 1009.96  4241.4 1009.46  4249.2 1009.96  4581.3 1010.06  4832.3 1010.02
  4873.3 1014.63  4885.8 1014.86  4986.1 1010.34  5220.5 1011.87  5295.3 1010.72
  5357.1 1011.49  5449.9 1015.06  5480.8 1020.88  5509.1 1018.85  5625.1 1017.93
  5679.2 1016.02  5880.2 1018.80  5975.6 1024.22  6168.8 1029.00  6233.3 1029.31
#Mann=6,-1,0
  3407.3   0.035       0  4039.5   0.094       0  4138.9   0.033       0
  4240.9   0.035       0  4249.2   0.033       0  4581.3   0.035       0
Bank Sta=4240.9,4249.2
Exp/Cntr=0.3,0.1

Type RM Length L Ch R = 1,2837,584,584,584
BEGIN DESCRIPTION:
Hanz Creek 6.0
END DESCRIPTION:
XS GIS Cut Line= 3
      2157525.02     13856775.03      2156825.00     13855775.00
      2156725.00     13854774.97
#Sta/Elev= 30
  3779.0 1028.49  3802.4 1027.93  4045.4 1021.92  4173.6 1014.98  4209.3 1017.74
  4222.3 1015.44  4269.1 1011.43  4340.1 1011.49  4381.9 1014.66  4389.4 1012.29
  4400.7 1013.28  4432.5 1014.42  4468.3 1010.03  4584.2 1010.02  4605.2 1011.87
  4676.6 1010.10  4722.6 1014.20  4819.6 1012.00  4859.5 1006.94  4860.0 1006.44
  4868.7 1006.94  5029.8 1008.16  5130.3 1014.61  5261.0 1013.04  5301.2 1015.49
  5632.8 1014.95  5723.3 1017.57  5750.9 1022.09  5803.7 1019.73  6004.7 1026.18
#Mann=8,-1,0
  3779.0    0.12       0  3802.4   0.035       0  4222.3    0.12       0
  4269.1   0.035       0  4400.7    0.12       0  4722.6   0.035       0
  4859.5   0.035       0  4868.7   0.035       0
Bank Sta=4859.5,4868.7
Exp/Cntr=0.3,0.1

Type RM Length L Ch R = 1,2253,354,354,354
BEGIN DESCRIPTION:
Hanz Creek 5.0
END DESCRIPTION:
XS GIS Cut Line= 4
      2157557.08     13856637.49      2157365.38     13856024.88
      2157344.54     13855804.01      2156999.66     13855230.59
#Sta/Elev= 30
  4258.4 1027.37  4339.9 1025.36  4396.1 1024.00  4428.7 1021.80  4446.9 1022.08
  4452.2 1022.96  4470.6 1022.52  4502.0 1019.85  4533.4 1020.48  4554.8 1017.75
  4587.3 1018.94  4619.7 1014.75  4627.7 1014.48  4774.4 1011.20  4879.2 1009.84
  4920.3 1008.46  4956.5 1005.22  4961.5 1005.80  5006.0 1004.30  5006.5 1003.80
  5015.4 1004.30  5325.1 1005.49  5362.0 1007.04  5536.8 1008.51  5579.6 1010.50
  5637.9 1010.60  5653.4 1012.25  5674.8 1012.41  5696.1 1013.84  5791.3 1014.63
#Mann=5,-1,0
  4258.4   0.035       0  4339.9    0.12       0  4396.1   0.035       0
  5006.0   0.035       0  5015.4   0.035       0
Bank Sta=5006,5015.4
Exp/Cntr=0.3,0.1

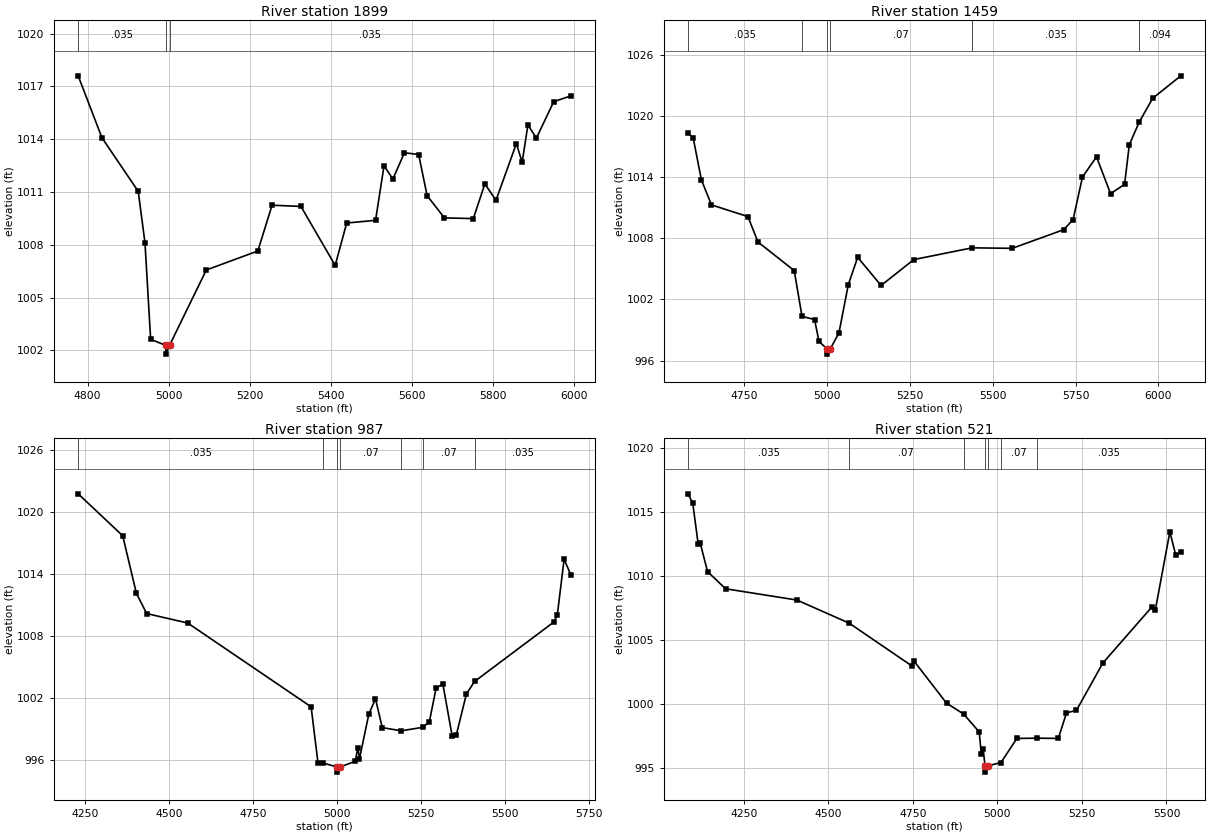
Type RM Length L Ch R = 1,1899,440,440,440
BEGIN DESCRIPTION:
Hanz Creek 4.0
END DESCRIPTION:
XS GIS Cut Line= 3
      2157775.01     13856125.03      2157675.00     13855925.00
      2157025.00     13855175.00
#Sta/Elev= 30
  4776.9 1017.60  4835.6 1014.08  4925.1 1011.04  4941.8 1008.12  4955.8 1002.63
  4993.0 1002.29  4993.5 1001.79  5002.5 1002.29  5093.2 1006.57  5220.4 1007.65
  5255.5 1010.25  5326.8 1010.18  5411.3 1006.83  5439.8 1009.24  5511.0 1009.39
  5531.9 1012.49  5553.8 1011.74  5582.3 1013.23  5617.4 1013.13  5638.3 1010.79
  5681.0 1009.53  5752.3 1009.49  5780.8 1011.46  5808.3 1010.53  5858.6 1013.75
  5872.9 1012.69  5887.1 1014.81  5908.0 1014.06  5950.8 1016.13  5993.0 1016.46
#Mann=3,-1,0
  4776.9   0.035       0  4993.0   0.035       0  5002.5   0.035       0
Bank Sta=4993,5002.5
Exp/Cntr=0.3,0.1

Type RM Length L Ch R = 1,1459,472,472,472
BEGIN DESCRIPTION:
Hanz Creek 3.0
END DESCRIPTION:
XS GIS Cut Line= 3
      2158074.99     13855974.98      2157925.00     13855575.00
      2157175.03     13854825.03
#Sta/Elev= 30
  4579.8 1018.27  4594.9 1017.86  4619.8 1013.73  4650.1 1011.27  4760.4 1010.12
  4790.7 1007.63  4900.2 1004.83  4923.7 1000.34  4961.6 1000.03  4974.9  997.89
  4999.6  997.14  5000.1  996.64  5009.1  997.14  5035.3  998.73  5063.5 1003.45
  5091.8 1006.13  5162.5 1003.37  5261.5 1005.91  5437.8 1007.06  5558.5 1007.01
  5714.1 1008.84  5742.4 1009.83  5770.7 1014.00  5813.1 1015.98  5855.5 1012.37
  5897.9 1013.28  5912.1 1017.16  5941.6 1019.36  5982.8 1021.72  6067.6 1023.92
#Mann=6,-1,0
  4579.8   0.035       0  4923.7    0.07       0  4999.6    0.05       0
  5009.1    0.07       0  5437.8   0.035       0  5941.6   0.094       0
Bank Sta=4999.6,5009.1
Exp/Cntr=0.3,0.1

Type RM Length L Ch R = 1,987,466,466,466
BEGIN DESCRIPTION:
Hanz Creek 2.0
END DESCRIPTION:
XS GIS Cut Line= 3
      2158125.00     13856074.99      2158275.00     13855325.00
      2158325.00     13854625.03
#Sta/Elev= 30
  4230.2 1021.78  4362.8 1017.72  4403.6 1012.14  4434.2 1010.19  4556.5 1009.27
  4923.7 1001.16  4944.1  995.73  4959.7  995.72  5000.3  995.34  5000.8  994.84
  5009.8  995.34  5055.2  995.89  5062.7  997.22  5067.7  996.14  5095.3 1000.44
  5115.3 1001.94  5135.4  999.15  5192.0  998.84  5256.8  999.18  5275.8  999.74
  5295.8 1002.98  5315.9 1003.36  5343.4  998.36  5356.0  998.44  5386.0 1002.42
  5410.5 1003.62  5646.7 1009.38  5656.7 1010.09  5676.8 1015.44  5696.8 1013.94
#Mann=7,-1,0
  4230.2   0.035       0  4959.7    0.07       0  5000.3    0.05       0
  5009.8    0.07       0  5192.0   0.035       0  5256.8    0.07       0
  5410.5   0.035       0
Bank Sta=5000.3,5009.8
Exp/Cntr=0.3,0.1

Type RM Length L Ch R = 1,521,0,0,0
BEGIN DESCRIPTION:
Hanz Creek 1.0
END DESCRIPTION:
XS GIS Cut Line= 3
      2158224.98     13855925.03      2158675.00     13855125.00
      2158475.01     13854625.03
#Sta/Elev= 30
  4085.9 1016.42  4099.6 1015.68  4115.6 1012.49  4121.3 1012.61  4143.3 1010.35
  4196.5 1009.01  4407.5 1008.13  4561.7 1006.33  4747.3 1002.99  4753.0 1003.39
  4849.9 1000.08  4900.0  999.24  4946.4  997.84  4952.5  996.09  4958.2  996.51
  4963.4  995.20  4963.9  994.70  4973.4  995.20  5010.8  995.45  5057.7  997.33
  5118.1  997.35  5180.2  997.33  5204.4  999.32  5234.0  999.53  5312.1 1003.22
  5456.2 1007.57  5466.9 1007.33  5510.0 1013.45  5527.5 1011.63  5542.3 1011.90
#Mann=7,-1,0
  4085.9   0.035       0  4561.7    0.07       0  4900.0   0.035       0
  4963.4   0.035       0  4973.4   0.035       0  5010.8    0.07       0
  5118.1   0.035       0
Bank Sta=4963.4,4973.4
Exp/Cntr=0.3,0.1

Chan Stop Cuts=-1