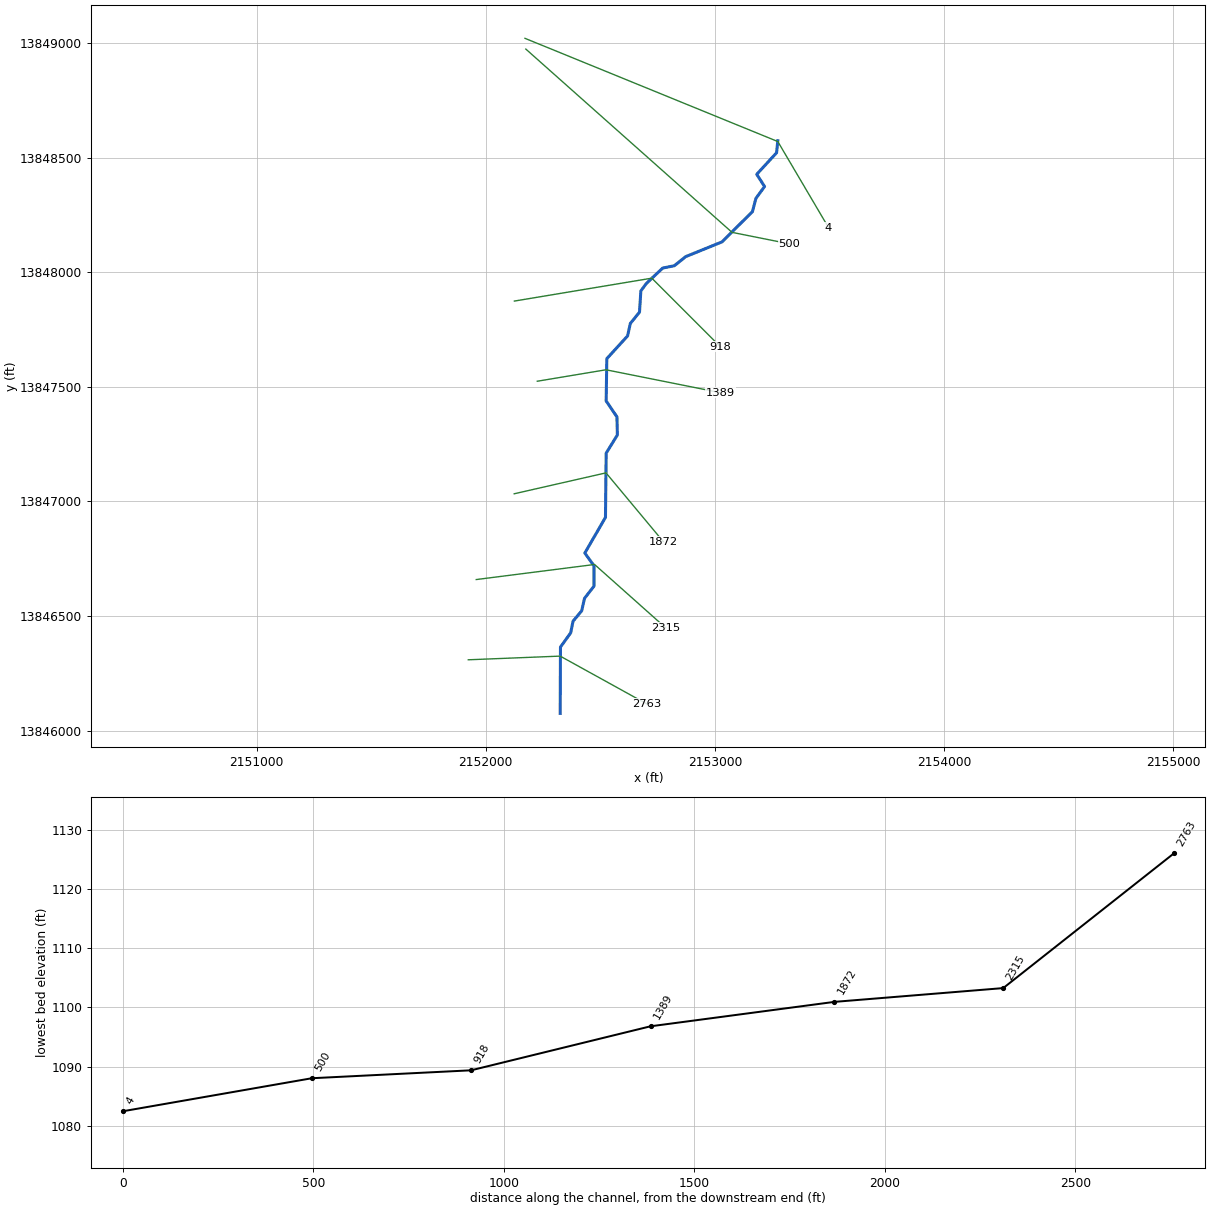
--- Hanz Tributary 3.prj (project) ---

Proj Title=Hanz Tributary 3 Base Level Engineering
Current Plan=p01
Default Exp/Contr=0.3,0.1
English Units
Geom File=g01
Flow File=f01
Plan File=p01
BEGIN DESCRIPTION:
Hanz Tributary 3
END DESCRIPTION:

--- Hanz Tributary 3.p01 (plan) ---

Plan Title=Multiple Run
Short Identifier=Multiple
Geom File=g01
Flow File=f01
Subcritical Flow
K Sum by GR= 0
Std Step Tol= 0.01
Critical Tol= 0.01
Num of Std Step Trials= 20
Max Error Tol= 0.3
Flow Tol Ratio= 0.001
Split Flow NTrial= 30
Split Flow Tol= 0.02
Split Flow Ratio= 0.02
Log Output Level= 0
Friction Slope Method= 1
Unsteady Friction Slope Method= 2
Unsteady Bridges Friction Slope Method= 1
Parabolic Critical Depth
Global Vel Dist=  1 , 1 , 1
Global Log Level= 0
CheckData=True
Encroach Param= -1, 0, 0, 0
BEGIN DESCRIPTION:
Multiple Run
END DESCRIPTION:

--- Hanz Tributary 3.f01 (steady flow) ---

Flow Title=Multiple
Number of Profiles=7
Profile Names=10-year,25-year,50-year,1pct_min,100-year,1pct_plu,500-year
River Rch & RM= Hanz Tributary 3,Reach-1,2763
    1762    3105    4431    3061    6108   12187   11496
Boundary for River Rch & Prof#=Hanz Tributary 3,Reach-1,1
Up Type=0
Dn Type=3
Dn Slope=0.005
Boundary for River Rch & Prof#=Hanz Tributary 3,Reach-1,2
Up Type=0
Dn Type=3
Dn Slope=0.005
Boundary for River Rch & Prof#=Hanz Tributary 3,Reach-1,3
Up Type=0
Dn Type=3
Dn Slope=0.005
Boundary for River Rch & Prof#=Hanz Tributary 3,Reach-1,4
Up Type=0
Dn Type=3
Dn Slope=0.005
Boundary for River Rch & Prof#=Hanz Tributary 3,Reach-1,5
Up Type=0
Dn Type=3
Dn Slope=0.005
Boundary for River Rch & Prof#=Hanz Tributary 3,Reach-1,6
Up Type=0
Dn Type=3
Dn Slope=0.005
Boundary for River Rch & Prof#=Hanz Tributary 3,Reach-1,7
Up Type=0
Dn Type=3
Dn Slope=0.005

--- Hanz Tributary 3.g01 (geometry) ---

Geom Title=Existing Conditions

River Reach=Hanz Tributary 3,Reach-1
Reach XY= 30
      2152325.00     13846075.00      2152326.20     13846364.50
      2152370.81     13846426.74      2152381.08     13846477.20
      2152418.92     13846522.80      2152431.12     13846577.18
      2152472.74     13846630.56      2152472.63     13846719.11
      2152432.53     13846775.01      2152522.65     13846930.52
      2152525.69     13847211.08      2152574.62     13847290.27
      2152572.71     13847369.43      2152525.68     13847438.92
      2152528.55     13847623.53      2152619.15     13847722.71
      2152631.14     13847777.17      2152671.17     13847826.59
      2152677.15     13847919.12      2152701.15     13847951.93
      2152772.69     13848019.17      2152823.26     13848029.19
      2152872.80     13848068.92      2153031.06     13848133.14
      2153164.25     13848265.32      2153179.44     13848323.35
      2153217.23     13848375.09      2153182.98     13848428.33
      2153269.65     13848522.48      2153275.00     13848575.00

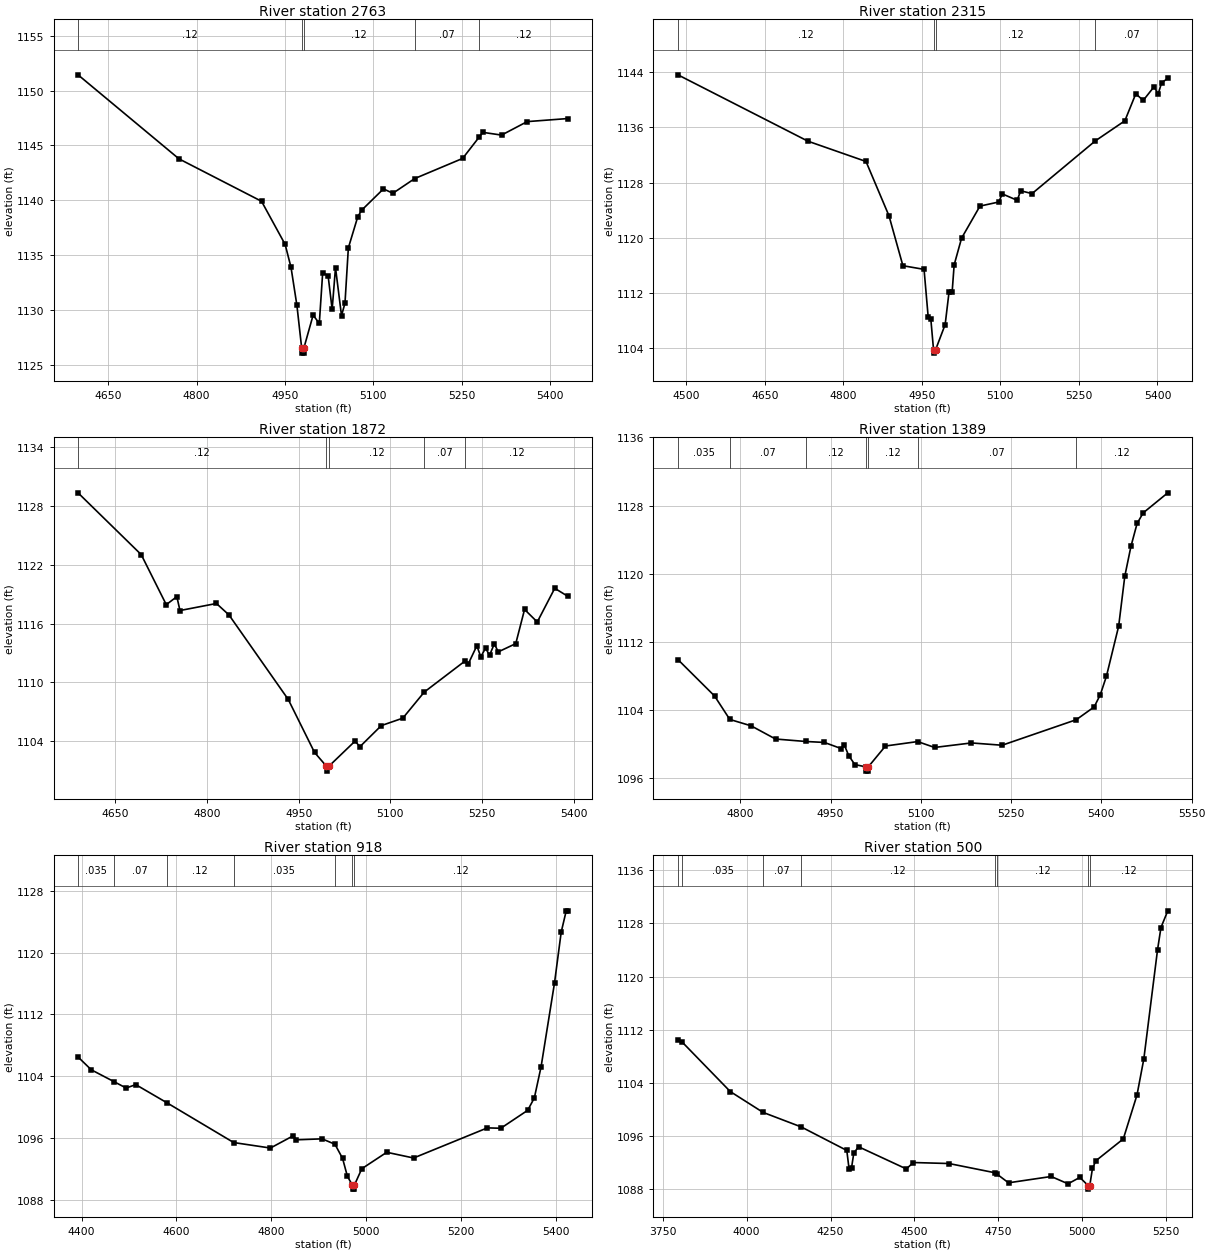
Type RM Length L Ch R = 1,2763,448,448,448
BEGIN DESCRIPTION:
Hanz Tributary 3 6.0
END DESCRIPTION:
XS GIS Cut Line= 3
      2151923.72     13846308.94      2152325.00     13846325.00
      2152701.41     13846117.12
#Sta/Elev= 30
  4598.8 1151.44  4770.2 1143.77  4910.3 1139.90  4950.4 1135.96  4960.4 1133.86
  4970.4 1130.39  4978.4 1126.54  4978.6 1126.04  4982.1 1126.04  4982.4 1126.54
  4997.9 1129.51  5008.4 1128.75  5014.1 1133.36  5023.3 1133.12  5030.2 1130.04
  5035.9 1133.84  5046.1 1129.46  5052.0 1130.61  5057.7 1135.64  5073.7 1138.49
  5080.4 1139.09  5117.3 1141.03  5133.3 1140.63  5170.3 1141.97  5251.7 1143.81
  5279.7 1145.75  5286.0 1146.19  5317.8 1145.94  5361.3 1147.17  5430.4 1147.45
#Mann=5,-1,0
  4598.8    0.12       0  4978.4    0.05       0  4982.4    0.12       0
  5170.3    0.07       0  5279.7    0.12       0
Bank Sta=4978.4,4982.4
Exp/Cntr=0.3,0.1

Type RM Length L Ch R = 1,2315,443,443,443
BEGIN DESCRIPTION:
Hanz Tributary 3 5.0
END DESCRIPTION:
XS GIS Cut Line= 3
      2151958.61     13846659.24      2152475.00     13846725.00
      2152785.14     13846448.88
#Sta/Elev= 30
  4483.9 1143.64  4732.4 1134.01  4843.2 1131.07  4887.1 1123.19  4913.7 1115.95
  4954.1 1115.42  4962.0 1108.51  4967.0 1108.24  4972.2 1103.77  4972.5 1103.27
  4976.2 1103.77  4994.4 1107.41  5001.9 1112.18  5007.8 1112.18  5011.6 1116.07
  5025.8 1119.95  5060.9 1124.60  5096.8 1125.19  5103.5 1126.37  5132.0 1125.44
  5138.7 1126.82  5160.4 1126.41  5281.3 1134.06  5337.7 1136.97  5358.6 1140.89
  5372.8 1139.93  5393.7 1141.93  5401.2 1140.82  5407.9 1142.49  5419.7 1143.12
#Mann=4,-1,0
  4483.9    0.12       0  4972.2    0.05       0  4976.2    0.12       0
  5281.3    0.07       0
Bank Sta=4972.2,4976.2
Exp/Cntr=0.3,0.1

Type RM Length L Ch R = 1,1872,483,483,483
BEGIN DESCRIPTION:
Hanz Tributary 3 4.0
END DESCRIPTION:
XS GIS Cut Line= 3
      2152124.19     13847033.66      2152525.00     13847125.00
      2152775.00     13846825.00
#Sta/Elev= 30
  4589.0 1129.36  4692.4 1123.05  4733.4 1117.94  4750.7 1118.76  4755.8 1117.34
  4815.5 1118.06  4836.0 1116.89  4933.0 1108.26  4976.0 1102.85  4995.5 1101.44
  4995.8 1100.94  4999.5 1101.44  5042.4 1104.01  5050.2 1103.43  5085.3 1105.59
  5120.5 1106.35  5155.5 1109.01  5222.8 1112.21  5227.2 1111.84  5241.6 1113.74
  5248.1 1112.62  5255.9 1113.50  5262.4 1112.77  5270.2 1113.94  5276.7 1113.12
  5305.3 1113.96  5319.7 1117.45  5340.5 1116.17  5369.1 1119.61  5390.6 1118.79
#Mann=5,-1,0
  4589.0    0.12       0  4995.5    0.05       0  4999.5    0.12       0
  5155.5    0.07       0  5222.8    0.12       0
Bank Sta=4995.5,4999.5
Exp/Cntr=0.3,0.1

Type RM Length L Ch R = 1,1389,471,471,471
BEGIN DESCRIPTION:
Hanz Tributary 3 3.0
END DESCRIPTION:
XS GIS Cut Line= 3
      2152225.01     13847525.00      2152525.00     13847575.00
      2153024.97     13847475.01
#Sta/Elev= 30
  4696.3 1109.91  4757.1 1105.64  4782.5 1102.88  4817.9 1102.13  4858.5 1100.58
  4908.9 1100.29  4939.6 1100.18  4967.5 1099.46  4972.6 1099.91  4980.2 1098.62
  4990.3 1097.58  5008.6 1097.31  5008.9 1096.81  5012.4 1096.81  5012.6 1097.31
  5041.2 1099.76  5094.6 1100.28  5122.8 1099.59  5184.0 1100.12  5235.0 1099.85
  5358.3 1102.85  5388.0 1104.35  5398.2 1105.79  5408.4 1107.96  5428.7 1113.84
  5438.9 1119.71  5449.1 1123.20  5459.3 1125.89  5469.5 1127.14  5510.3 1129.49
#Mann=7,-1,0
  4696.3   0.035       0  4782.5    0.07       0  4908.9    0.12       0
  5008.6    0.05       0  5012.6    0.12       0  5094.6    0.07       0
  5358.3    0.12       0
Bank Sta=5008.6,5012.6
Exp/Cntr=0.3,0.1

Type RM Length L Ch R = 1,918,418,418,418
BEGIN DESCRIPTION:
Hanz Tributary 3 2.0
END DESCRIPTION:
XS GIS Cut Line= 3
      2152125.00     13847875.00      2152725.00     13847975.00
      2153024.97     13847675.03
#Sta/Elev= 30
  4392.6 1106.48  4420.5 1104.82  4467.9 1103.30  4494.0 1102.46  4514.3 1102.90
  4579.4 1100.57  4720.7 1095.40  4798.1 1094.69  4846.3 1096.28  4851.3 1095.75
  4907.1 1095.88  4934.1 1095.18  4950.2 1093.35  4960.3 1091.04  4971.0 1089.87
  4971.2 1089.37  4974.7 1089.37  4975.0 1089.87  4990.7 1092.01  5043.3 1094.14
  5099.9 1093.40  5255.4 1097.30  5283.7 1097.25  5340.3 1099.57  5354.4 1101.18
  5368.6 1105.21  5396.9 1116.06  5411.0 1122.64  5421.6 1125.40  5425.1 1125.40
#Mann=7,-1,0
  4392.6   0.035       0  4467.9    0.07       0  4579.4    0.12       0
  4720.7   0.035       0  4934.1    0.12       0  4971.0    0.05       0
  4975.0    0.12       0
Bank Sta=4971,4975
Exp/Cntr=0.3,0.1

Type RM Length L Ch R = 1,500,496,496,496
BEGIN DESCRIPTION:
Hanz Tributary 3 1.0
END DESCRIPTION:
XS GIS Cut Line= 3
      2152174.97     13848975.02      2153075.00     13848175.00
      2153324.95     13848125.01
#Sta/Elev= 30
  3795.5 1110.49  3808.8 1110.11  3951.5 1102.70  4049.1 1099.57  4162.9 1097.38
  4298.5 1093.85  4305.2 1091.09  4312.7 1091.25  4319.4 1093.47  4333.6 1094.40
  4475.8 1091.07  4496.7 1092.03  4602.9 1091.88  4740.0 1090.49  4746.3 1090.27
  4780.2 1088.98  4907.3 1089.93  4957.5 1088.83  4992.6 1089.79  5018.1 1088.53
  5018.3 1088.03  5022.1 1088.53  5030.3 1091.15  5040.5 1092.30  5122.1 1095.58
  5162.9 1102.18  5183.3 1107.62  5224.1 1124.02  5234.3 1127.37  5254.6 1129.88
#Mann=8,-1,0
  3795.5    0.07       0  3808.8   0.035       0  4049.1    0.07       0
  4162.9    0.12       0  4740.0    0.07       0  4746.3    0.12       0
  5018.1    0.05       0  5022.1    0.12       0
Bank Sta=5018.1,5022.1
Exp/Cntr=0.3,0.1

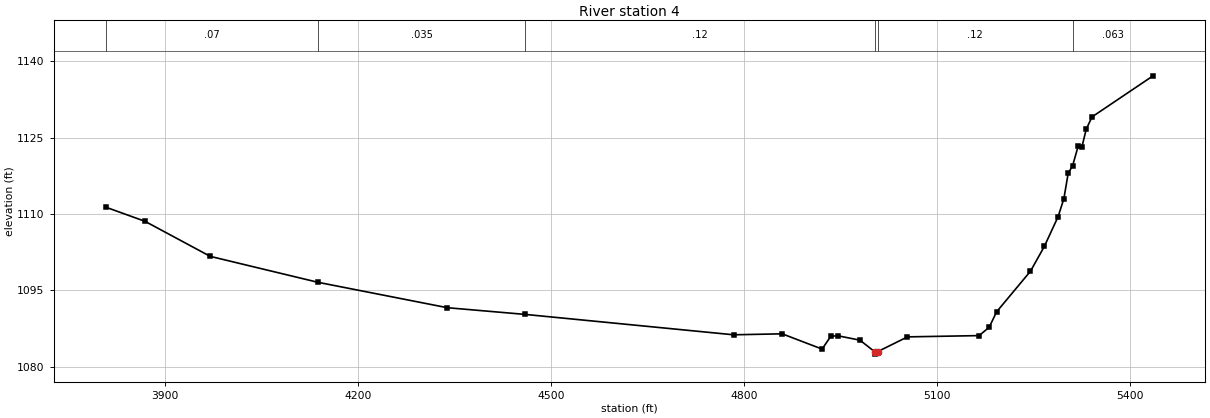
Type RM Length L Ch R = 1,4,0,0,0
BEGIN DESCRIPTION:
Hanz Tributary 3 0.1
END DESCRIPTION:
XS GIS Cut Line= 3
      2152171.32     13849021.97      2153275.01     13848571.45
      2153496.55     13848195.46
#Sta/Elev= 30
  3807.8 1111.32  3868.6 1108.55  3970.1 1101.66  4137.0 1096.58  4338.9 1091.57
  4460.3 1090.25  4783.9 1086.25  4859.5 1086.44  4921.6 1083.44  4935.1 1085.95
  4945.7 1086.07  4980.5 1085.19  5003.1 1082.95  5003.5 1082.45  5008.2 1082.95
  5054.4 1085.84  5165.7 1086.09  5181.4 1087.72  5193.1 1090.78  5245.7 1098.75
  5267.2 1103.61  5288.6 1109.46  5297.6 1112.99  5304.3 1117.99  5311.2 1119.47
  5319.9 1123.36  5325.7 1123.19  5332.4 1126.66  5341.4 1129.07  5436.3 1137.14
#Mann=6,-1,0
  3807.8    0.07       0  4137.0   0.035       0  4460.3    0.12       0
  5003.1    0.05       0  5008.2    0.12       0  5311.2   0.063       0
Bank Sta=5003.1,5008.2
Exp/Cntr=0.3,0.1

Chan Stop Cuts=-1