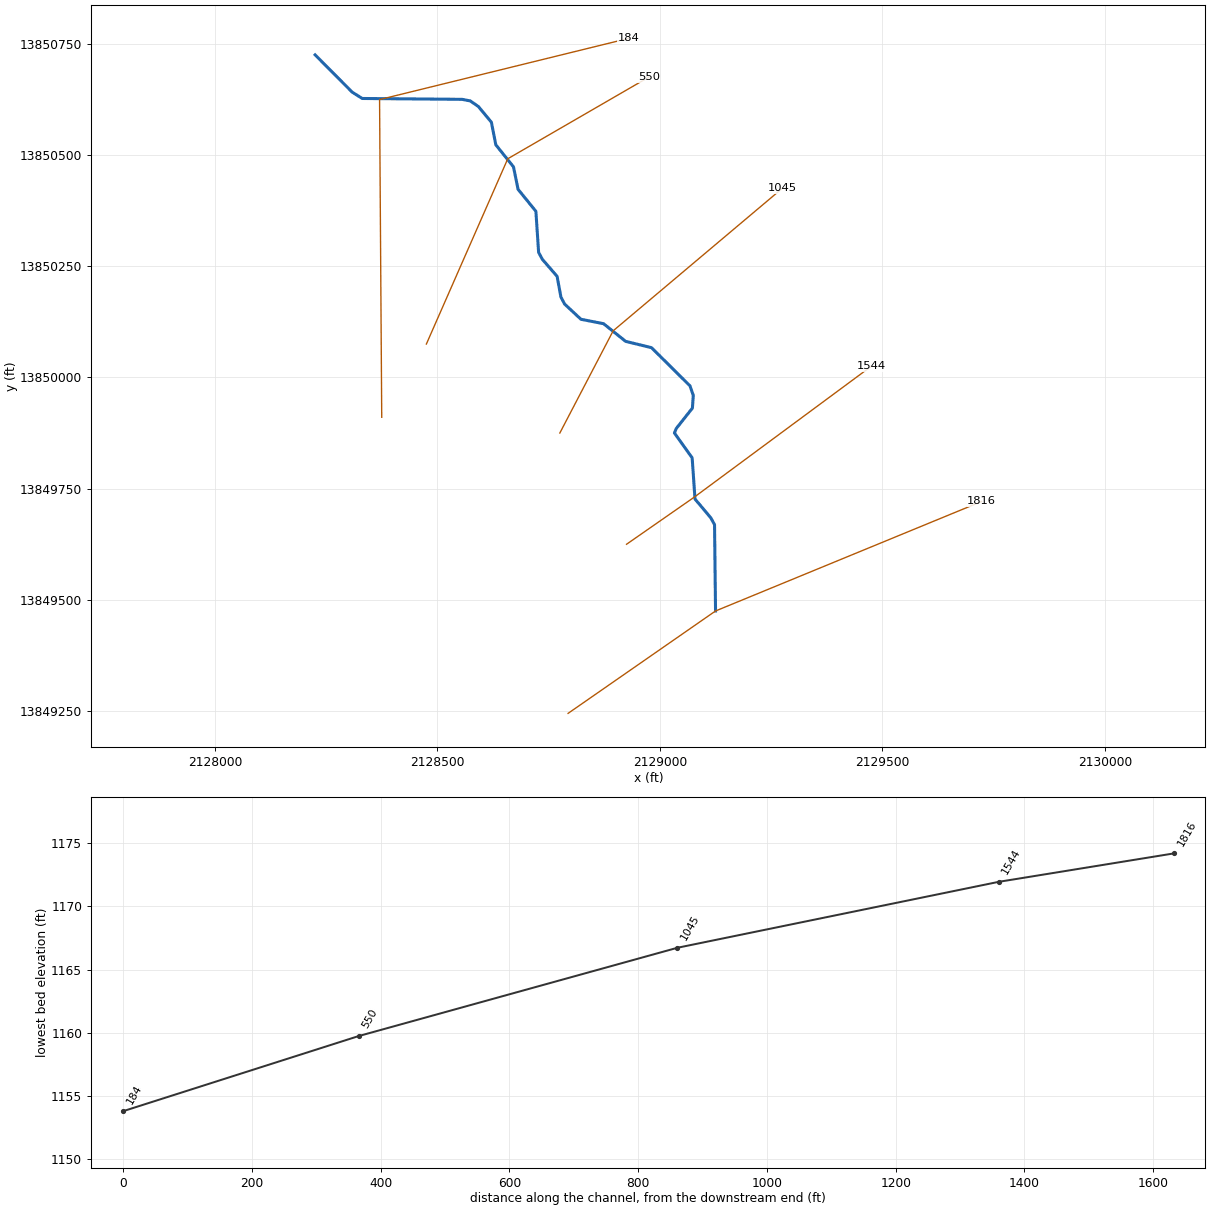
--- Honey Tributary 10.prj (project) ---

Proj Title=Honey Tributary 10 Base Level Engineering
Current Plan=p01
Default Exp/Contr=0.3,0.1
English Units
Geom File=g01
Flow File=f01
Plan File=p01
BEGIN DESCRIPTION:
Honey Tributary 10
END DESCRIPTION:

--- Honey Tributary 10.p01 (plan) ---

Plan Title=Multiple Run
Short Identifier=Multiple
Geom File=g01
Flow File=f01
Subcritical Flow
K Sum by GR= 0
Std Step Tol= 0.01
Critical Tol= 0.01
Num of Std Step Trials= 20
Max Error Tol= 0.3
Flow Tol Ratio= 0.001
Split Flow NTrial= 30
Split Flow Tol= 0.02
Split Flow Ratio= 0.02
Log Output Level= 0
Friction Slope Method= 1
Unsteady Friction Slope Method= 2
Unsteady Bridges Friction Slope Method= 1
Parabolic Critical Depth
Global Vel Dist=  1 , 1 , 1
Global Log Level= 0
CheckData=True
Encroach Param= -1, 0, 0, 0
BEGIN DESCRIPTION:
Multiple Run
END DESCRIPTION:

--- Honey Tributary 10.f01 (steady flow) ---

Flow Title=Multiple
Number of Profiles=7
Profile Names=10-year,25-year,50-year,1pct_min,100-year,1pct_plu,500-year
River Rch & RM= Honey Tributary ,Reach-1,1816
    1062    1792    2483    1667    3325    6635    5901
River Rch & RM= Honey Tributary ,Reach-1,1544
    1166    1976    2747    1849    3689    7360    6584
Boundary for River Rch & Prof#=Honey Tributary ,Reach-1,1
Up Type=0
Dn Type=3
Dn Slope=0.005
Boundary for River Rch & Prof#=Honey Tributary ,Reach-1,2
Up Type=0
Dn Type=3
Dn Slope=0.005
Boundary for River Rch & Prof#=Honey Tributary ,Reach-1,3
Up Type=0
Dn Type=3
Dn Slope=0.005
Boundary for River Rch & Prof#=Honey Tributary ,Reach-1,4
Up Type=0
Dn Type=3
Dn Slope=0.005
Boundary for River Rch & Prof#=Honey Tributary ,Reach-1,5
Up Type=0
Dn Type=3
Dn Slope=0.005
Boundary for River Rch & Prof#=Honey Tributary ,Reach-1,6
Up Type=0
Dn Type=3
Dn Slope=0.005
Boundary for River Rch & Prof#=Honey Tributary ,Reach-1,7
Up Type=0
Dn Type=3
Dn Slope=0.005

--- Honey Tributary 10.g01 (geometry) ---

Geom Title=Existing Conditions

River Reach=Honey Tributary ,Reach-1
Reach XY= 30
      2129125.00     13849475.00      2129122.75     13849669.07
      2129114.15     13849684.65      2129078.85     13849726.60
      2129072.45     13849819.11      2129032.59     13849875.01
      2129036.53     13849884.93      2129073.02     13849931.06
      2129074.99     13849959.65      2129067.51     13849981.07
      2128981.08     13850066.87      2128922.81     13850081.10
      2128873.24     13850120.80      2128822.45     13850130.73
      2128785.63     13850165.00      2128777.42     13850180.85
      2128768.85     13850227.15      2128735.83     13850265.34
      2128727.33     13850280.96      2128721.17     13850373.42
      2128681.12     13850422.82      2128670.84     13850473.28
      2128631.12     13850522.84      2128621.15     13850573.61
      2128592.14     13850608.73      2128573.75     13850621.55
      2128555.12     13850625.09      2128330.84     13850627.02
      2128308.19     13850641.33      2128225.00     13850725.00

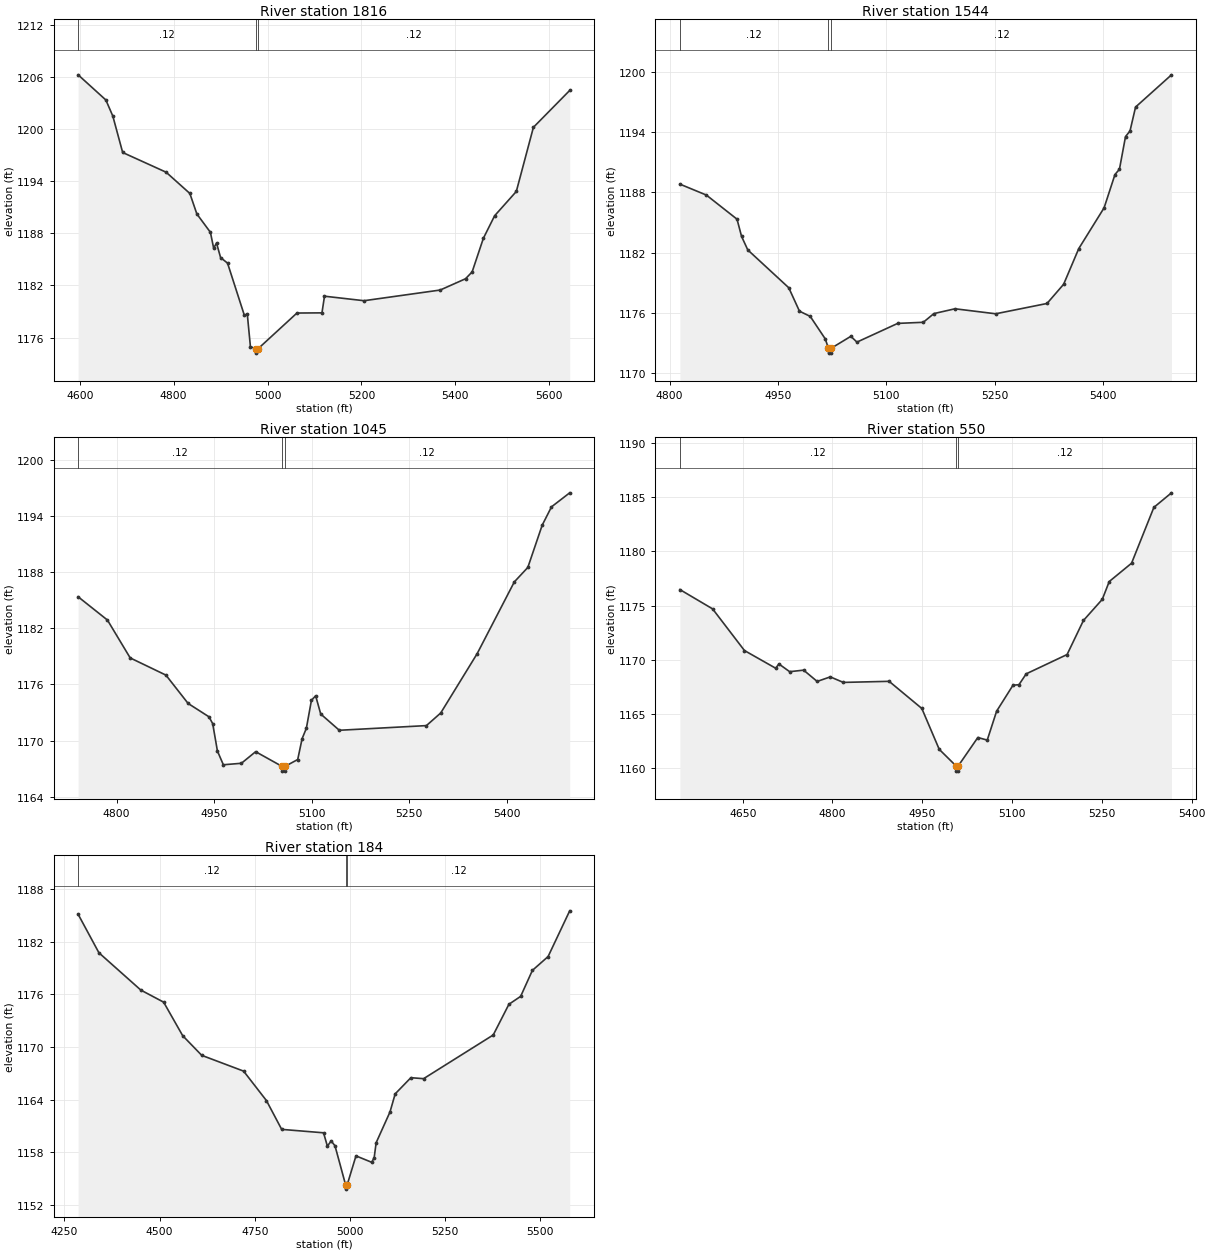
Type RM Length L Ch R = 1,1816,272,272,272
BEGIN DESCRIPTION:
Honey Tributary 10 4.0
END DESCRIPTION:
XS GIS Cut Line= 3
      2128793.53     13849244.84      2129125.00     13849475.00
      2129723.24     13849721.18
#Sta/Elev= 30
  4596.5 1206.27  4655.6 1203.37  4670.4 1201.52  4691.4 1197.32  4783.9 1195.05
  4834.5 1192.60  4849.4 1190.24  4878.3 1188.12  4885.2 1186.30  4891.3 1186.88
  4900.0 1185.21  4914.8 1184.57  4950.7 1178.54  4956.8 1178.73  4963.5 1174.95
  4975.7 1174.70  4976.0 1174.20  4979.7 1174.70  5062.6 1178.82  5115.9 1178.84
  5121.3 1180.76  5205.5 1180.24  5367.7 1181.47  5421.7 1182.77  5435.8 1183.56
  5459.7 1187.43  5483.7 1190.03  5529.9 1192.83  5566.3 1200.22  5643.6 1204.47
#Mann=3,-1,0
  4596.5    0.12       0  4975.7    0.05       0  4979.7    0.12       0
Bank Sta=4975.7,4979.7
Exp/Cntr=0.3,0.1

Type RM Length L Ch R = 1,1544,499,499,499
BEGIN DESCRIPTION:
Honey Tributary 10 3.0
END DESCRIPTION:
XS GIS Cut Line= 3
      2128924.99     13849624.99      2129077.35     13849730.98
      2129474.96     13850024.97
#Sta/Elev= 30
  4814.4 1188.83  4851.0 1187.74  4893.4 1185.33  4899.7 1183.61  4908.3 1182.26
  4965.0 1178.48  4979.8 1176.14  4994.7 1175.62  5015.5 1173.37  5019.8 1172.45
  5020.1 1171.95  5023.7 1171.95  5024.0 1172.45  5050.9 1173.63  5059.3 1173.05
  5115.7 1174.92  5151.1 1175.03  5165.8 1175.90  5195.0 1176.38  5251.3 1175.88
  5322.3 1176.91  5345.3 1178.83  5366.2 1182.39  5401.3 1186.47  5416.3 1189.79
  5422.5 1190.32  5430.9 1193.58  5437.1 1194.14  5444.8 1196.53  5494.5 1199.75
#Mann=3,-1,0
  4814.4    0.12       0  5019.8    0.05       0  5024.0    0.12       0
Bank Sta=5019.8,5024
Exp/Cntr=0.3,0.1

Type RM Length L Ch R = 1,1045,495,495,495
BEGIN DESCRIPTION:
Honey Tributary 10 2.0
END DESCRIPTION:
XS GIS Cut Line= 3
      2128775.01     13849875.02      2128894.92     13850104.82
      2129275.03     13850425.02
#Sta/Elev= 30
  4740.8 1185.38  4785.9 1182.89  4820.9 1178.84  4875.9 1177.00  4910.0 1173.97
  4942.1 1172.54  4947.8 1171.81  4955.1 1168.88  4964.2 1167.41  4992.0 1167.57
  5013.9 1168.81  5054.7 1167.23  5054.9 1166.73  5058.6 1166.73  5058.9 1167.23
  5078.6 1167.97  5085.4 1170.21  5091.9 1171.31  5099.7 1174.30  5106.2 1174.79
  5114.0 1172.84  5142.6 1171.10  5276.6 1171.60  5298.6 1172.95  5354.6 1179.29
  5411.8 1186.97  5432.6 1188.52  5454.7 1193.04  5469.0 1195.00  5497.0 1196.50
#Mann=3,-1,0
  4740.8    0.12       0  5054.7    0.05       0  5058.9    0.12       0
Bank Sta=5054.7,5058.9
Exp/Cntr=0.3,0.1

Type RM Length L Ch R = 1,550,366,366,366
BEGIN DESCRIPTION:
Honey Tributary 10 1.0
END DESCRIPTION:
XS GIS Cut Line= 3
      2128475.02     13850075.04      2128657.99     13850491.53
      2128975.02     13850675.01
#Sta/Elev= 30
  4545.1 1176.48  4599.7 1174.70  4652.9 1170.86  4705.0 1169.23  4710.5 1169.62
  4728.4 1168.91  4751.8 1169.05  4774.4 1168.01  4796.3 1168.43  4818.1 1167.92
  4894.6 1168.02  4949.2 1165.52  4978.3 1161.75  5006.0 1160.24  5006.3 1159.74
  5010.0 1159.74  5010.3 1160.24  5042.8 1162.84  5058.5 1162.60  5074.2 1165.27
  5101.5 1167.66  5111.5 1167.71  5123.6 1168.71  5191.9 1170.49  5219.2 1173.63
  5250.7 1175.58  5262.3 1177.22  5299.6 1178.91  5336.9 1184.06  5366.3 1185.40
#Mann=3,-1,0
  4545.1    0.12       0  5006.0    0.05       0  5010.3    0.12       0
Bank Sta=5006,5010.3
Exp/Cntr=0.3,0.1

Type RM Length L Ch R = 1,184,0,0,0
BEGIN DESCRIPTION:
Honey Tributary 10 0.0
END DESCRIPTION:
XS GIS Cut Line= 3
      2128374.66     13849910.44      2128369.80     13850624.53
      2128930.03     13850762.21
#Sta/Elev= 30
  4285.9 1185.12  4340.5 1180.73  4450.5 1176.48  4510.5 1175.10  4560.5 1171.28
  4610.5 1169.04  4720.5 1167.24  4780.5 1163.88  4820.5 1160.60  4930.5 1160.21
  4940.5 1158.69  4950.5 1159.28  4960.5 1158.73  4988.3 1154.29  4988.6 1153.79
  4992.6 1154.29  5015.6 1157.58  5056.8 1156.85  5063.4 1157.37  5068.6 1159.08
  5105.0 1162.59  5118.6 1164.65  5159.8 1166.49  5193.2 1166.38  5376.1 1171.36
  5417.3 1174.86  5448.1 1175.76  5478.9 1178.72  5520.2 1180.30  5576.9 1185.51
#Mann=3,-1,0
  4285.9    0.12       0  4988.3    0.05       0  4992.6    0.12       0
Bank Sta=4988.3,4992.6
Exp/Cntr=0.3,0.1

Chan Stop Cuts=-1