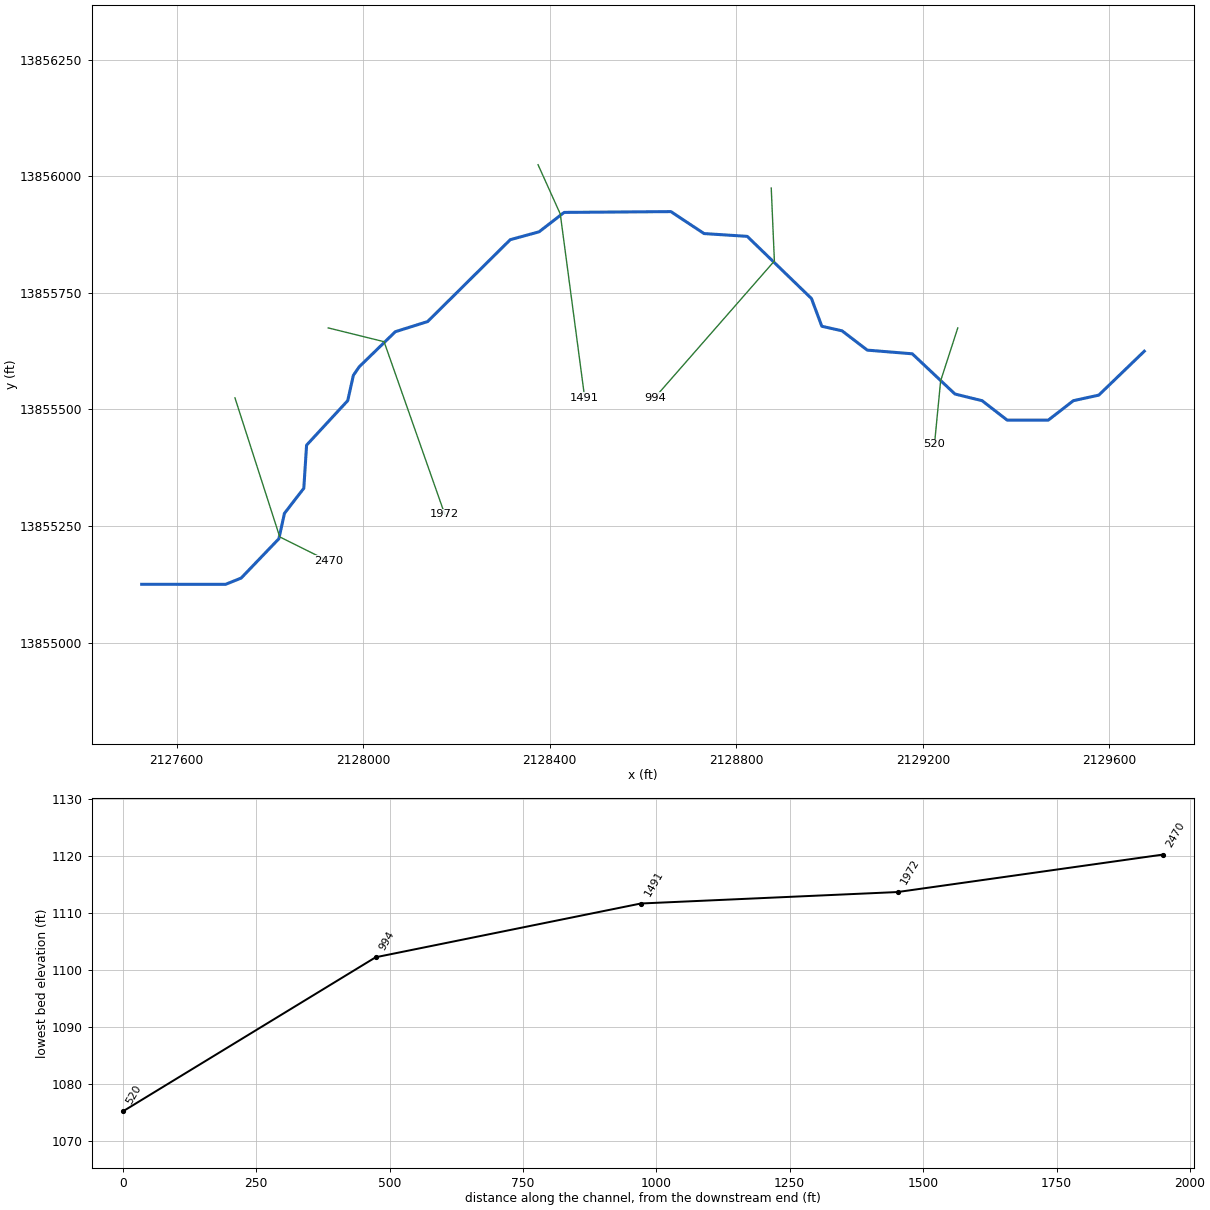
--- Honey Tributary 5.prj (project) ---

Proj Title=Honey Tributary 5 Base Level Engineering
Current Plan=p01
Default Exp/Contr=0.3,0.1
English Units
Geom File=g01
Flow File=f01
Plan File=p01
BEGIN DESCRIPTION:
Honey Tributary 5
END DESCRIPTION:

--- Honey Tributary 5.p01 (plan) ---

Plan Title=Multiple Run
Short Identifier=Multiple
Geom File=g01
Flow File=f01
Subcritical Flow
K Sum by GR= 0
Std Step Tol= 0.01
Critical Tol= 0.01
Num of Std Step Trials= 20
Max Error Tol= 0.3
Flow Tol Ratio= 0.001
Split Flow NTrial= 30
Split Flow Tol= 0.02
Split Flow Ratio= 0.02
Log Output Level= 0
Friction Slope Method= 1
Unsteady Friction Slope Method= 2
Unsteady Bridges Friction Slope Method= 1
Parabolic Critical Depth
Global Vel Dist=  1 , 1 , 1
Global Log Level= 0
CheckData=True
Encroach Param= -1, 0, 0, 0
BEGIN DESCRIPTION:
Multiple Run
END DESCRIPTION:

--- Honey Tributary 5.f01 (steady flow) ---

Flow Title=Multiple
Number of Profiles=7
Profile Names=10-year,25-year,50-year,1pct_min,100-year,1pct_plu,500-year
River Rch & RM= Honey Tributary ,Reach-1,2470
    1540    2665    3756    2563    5114   10203    9380
Boundary for River Rch & Prof#=Honey Tributary ,Reach-1,1
Up Type=0
Dn Type=3
Dn Slope=0.005
Boundary for River Rch & Prof#=Honey Tributary ,Reach-1,2
Up Type=0
Dn Type=3
Dn Slope=0.005
Boundary for River Rch & Prof#=Honey Tributary ,Reach-1,3
Up Type=0
Dn Type=3
Dn Slope=0.005
Boundary for River Rch & Prof#=Honey Tributary ,Reach-1,4
Up Type=0
Dn Type=3
Dn Slope=0.005
Boundary for River Rch & Prof#=Honey Tributary ,Reach-1,5
Up Type=0
Dn Type=3
Dn Slope=0.005
Boundary for River Rch & Prof#=Honey Tributary ,Reach-1,6
Up Type=0
Dn Type=3
Dn Slope=0.005
Boundary for River Rch & Prof#=Honey Tributary ,Reach-1,7
Up Type=0
Dn Type=3
Dn Slope=0.005

--- Honey Tributary 5.g01 (geometry) ---

Geom Title=Existing Conditions

River Reach=Honey Tributary ,Reach-1
Reach XY= 30
      2127525.00     13855125.00      2127705.03     13855124.94
      2127738.35     13855138.36      2127819.18     13855222.69
      2127831.14     13855277.17      2127872.67     13855330.97
      2127878.62     13855423.50      2127966.82     13855518.96
      2127978.97     13855573.36      2127991.64     13855591.71
      2128068.93     13855666.85      2128138.21     13855688.63
      2128315.32     13855864.24      2128377.17     13855881.14
      2128430.93     13855922.76      2128659.78     13855924.48
      2128730.98     13855877.36      2128823.50     13855871.39
      2128961.27     13855737.98      2128983.48     13855678.51
      2129026.84     13855668.72      2129080.94     13855627.32
      2129177.42     13855619.46      2129268.95     13855533.16
      2129327.17     13855518.85      2129380.97     13855477.14
      2129469.03     13855477.14      2129522.83     13855518.86
      2129577.32     13855530.79      2129675.00     13855625.00

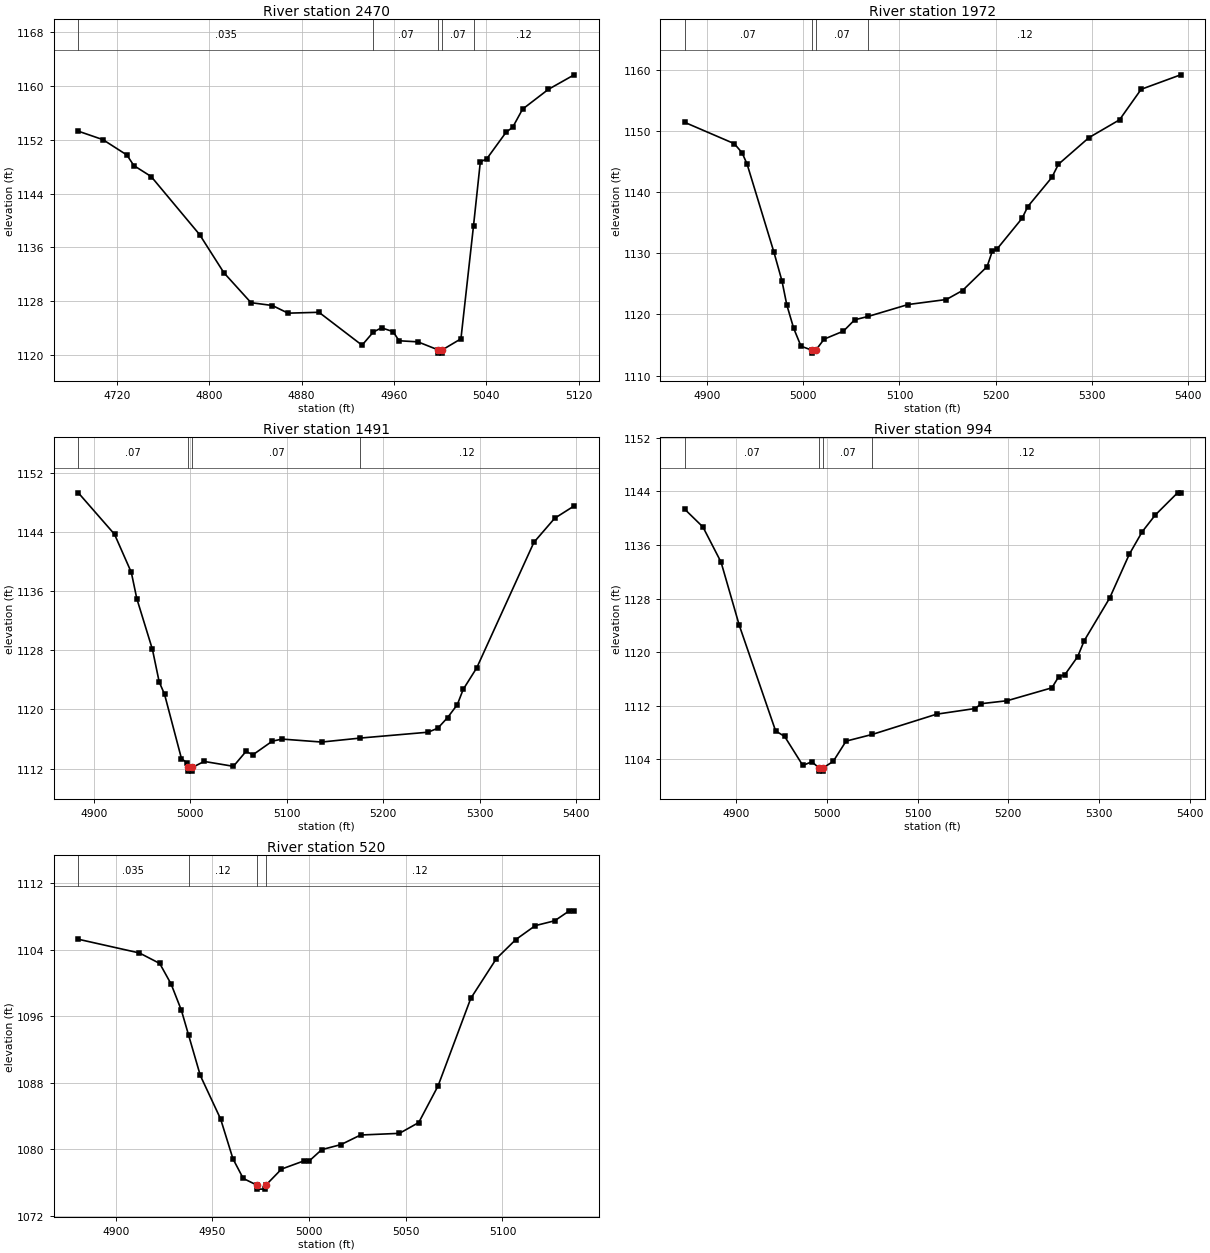
Type RM Length L Ch R = 1,2470,498,498,498
BEGIN DESCRIPTION:
Honey Tributary 5 5.0
END DESCRIPTION:
XS GIS Cut Line= 3
      2127724.99     13855525.04      2127821.06     13855226.62
      2127925.04     13855174.98
#Sta/Elev= 30
  4686.5 1153.30  4707.8 1152.04  4728.6 1149.75  4734.6 1148.18  4749.6 1146.55
  4791.6 1137.90  4812.6 1132.23  4836.1 1127.77  4854.6 1127.35  4868.2 1126.21
  4895.0 1126.34  4932.3 1121.44  4942.1 1123.40  4949.2 1124.03  4959.2 1123.46
  4964.4 1122.10  4980.7 1121.94  4998.0 1120.76  4998.3 1120.26  5001.8 1120.26
  5002.0 1120.76  5018.0 1122.39  5028.9 1139.22  5034.8 1148.73  5040.4 1149.19
  5057.2 1153.16  5062.8 1153.87  5071.4 1156.58  5093.7 1159.52  5116.1 1161.69
#Mann=5,-1,0
  4686.5   0.035       0  4942.1    0.07       0  4998.0    0.05       0
  5002.0    0.07       0  5028.9    0.12       0
Bank Sta=4998,5002
Exp/Cntr=0.3,0.1

Type RM Length L Ch R = 1,1972,481,481,481
BEGIN DESCRIPTION:
Honey Tributary 5 4.0
END DESCRIPTION:
XS GIS Cut Line= 3
      2127924.97     13855675.01      2128044.77     13855645.42
      2128174.99     13855275.04
#Sta/Elev= 30
  4876.6 1151.42  4928.1 1147.94  4936.2 1146.45  4941.4 1144.61  4969.3 1130.22
  4977.7 1125.50  4982.8 1121.54  4989.9 1117.75  4997.5 1114.82  5008.5 1114.18
  5008.8 1113.68  5013.0 1114.18  5021.6 1115.97  5041.7 1117.28  5053.4 1119.13
  5067.6 1119.69  5109.0 1121.63  5148.8 1122.45  5165.6 1123.92  5191.2 1127.83
  5196.6 1130.35  5201.9 1130.78  5227.6 1135.73  5233.6 1137.66  5258.6 1142.42
  5265.4 1144.57  5297.2 1148.93  5329.0 1151.84  5351.5 1156.83  5392.6 1159.20
#Mann=4,-1,0
  4876.6    0.07       0  5008.5    0.05       0  5013.0    0.07       0
  5067.6    0.12       0
Bank Sta=5008.5,5013
Exp/Cntr=0.3,0.1

Type RM Length L Ch R = 1,1491,497,497,497
BEGIN DESCRIPTION:
Honey Tributary 5 3.0
END DESCRIPTION:
XS GIS Cut Line= 3
      2128374.98     13856025.05      2128422.65     13855919.29
      2128475.01     13855524.95
#Sta/Elev= 30
  4884.0 1149.28  4921.5 1143.68  4938.9 1138.53  4944.6 1134.98  4960.8 1128.11
  4967.8 1123.72  4973.3 1122.07  4990.9 1113.35  4996.4 1112.81  4997.2 1112.17
  4997.6 1111.67  5001.7 1111.67  5002.1 1112.17  5014.4 1112.98  5044.7 1112.32
  5057.8 1114.34  5064.9 1113.88  5085.0 1115.72  5095.1 1116.00  5136.2 1115.60
  5176.3 1116.14  5246.4 1116.93  5256.5 1117.47  5266.6 1118.90  5276.7 1120.65
  5282.8 1122.71  5296.9 1125.64  5356.1 1142.59  5377.6 1145.84  5397.8 1147.51
#Mann=4,-1,0
  4884.0    0.07       0  4997.2    0.05       0  5002.1    0.07       0
  5176.3    0.12       0
Bank Sta=4997.2,5002.1
Exp/Cntr=0.3,0.1

Type RM Length L Ch R = 1,994,474,474,474
BEGIN DESCRIPTION:
Honey Tributary 5 2.0
END DESCRIPTION:
XS GIS Cut Line= 3
      2128875.00     13855974.97      2128881.75     13855818.51
      2128624.98     13855524.97
#Sta/Elev= 30
  4843.4 1141.33  4863.4 1138.69  4883.4 1133.43  4903.4 1124.03  4943.5 1108.25
  4953.5 1107.41  4973.5 1103.09  4983.5 1103.64  4991.1 1102.74  4991.4 1102.24
  4995.6 1102.24  4996.0 1102.74  5007.0 1103.69  5021.2 1106.72  5050.1 1107.72
  5120.9 1110.74  5163.6 1111.59  5170.2 1112.31  5198.7 1112.75  5248.1 1114.68
  5255.7 1116.36  5262.3 1116.62  5276.5 1119.33  5283.7 1121.71  5311.7 1128.06
  5333.5 1134.64  5347.7 1137.99  5362.0 1140.47  5386.6 1143.79  5390.0 1143.79
#Mann=4,-1,0
  4843.4    0.07       0  4991.1    0.05       0  4996.0    0.07       0
  5050.1    0.12       0
Bank Sta=4991.1,4996
Exp/Cntr=0.3,0.1

Type RM Length L Ch R = 1,520,0,0,0
BEGIN DESCRIPTION:
Honey Tributary 5 1.0
END DESCRIPTION:
XS GIS Cut Line= 3
      2129275.01     13855675.03      2129238.24     13855561.43
      2129225.00     13855424.97
#Sta/Elev= 30
  4880.6 1105.25  4912.2 1103.60  4922.7 1102.34  4928.6 1099.86  4933.9 1096.71
  4937.6 1093.75  4943.7 1088.86  4954.2 1083.63  4960.6 1078.83  4965.9 1076.48
  4972.8 1075.69  4973.1 1075.19  4977.3 1075.19  4977.7 1075.69  4985.7 1077.60
  4997.1 1078.57  5000.0 1078.57  5006.5 1079.94  5016.5 1080.55  5026.6 1081.70
  5046.7 1081.90  5056.7 1083.20  5066.7 1087.61  5083.6 1098.13  5096.9 1102.93
  5106.9 1105.21  5117.0 1106.89  5127.0 1107.47  5134.6 1108.67  5137.1 1108.67
#Mann=4,-1,0
  4880.6   0.035       0  4937.6    0.12       0  4972.8    0.05       0
  4977.7    0.12       0
Bank Sta=4972.8,4977.7
Exp/Cntr=0.3,0.1

Chan Stop Cuts=-1