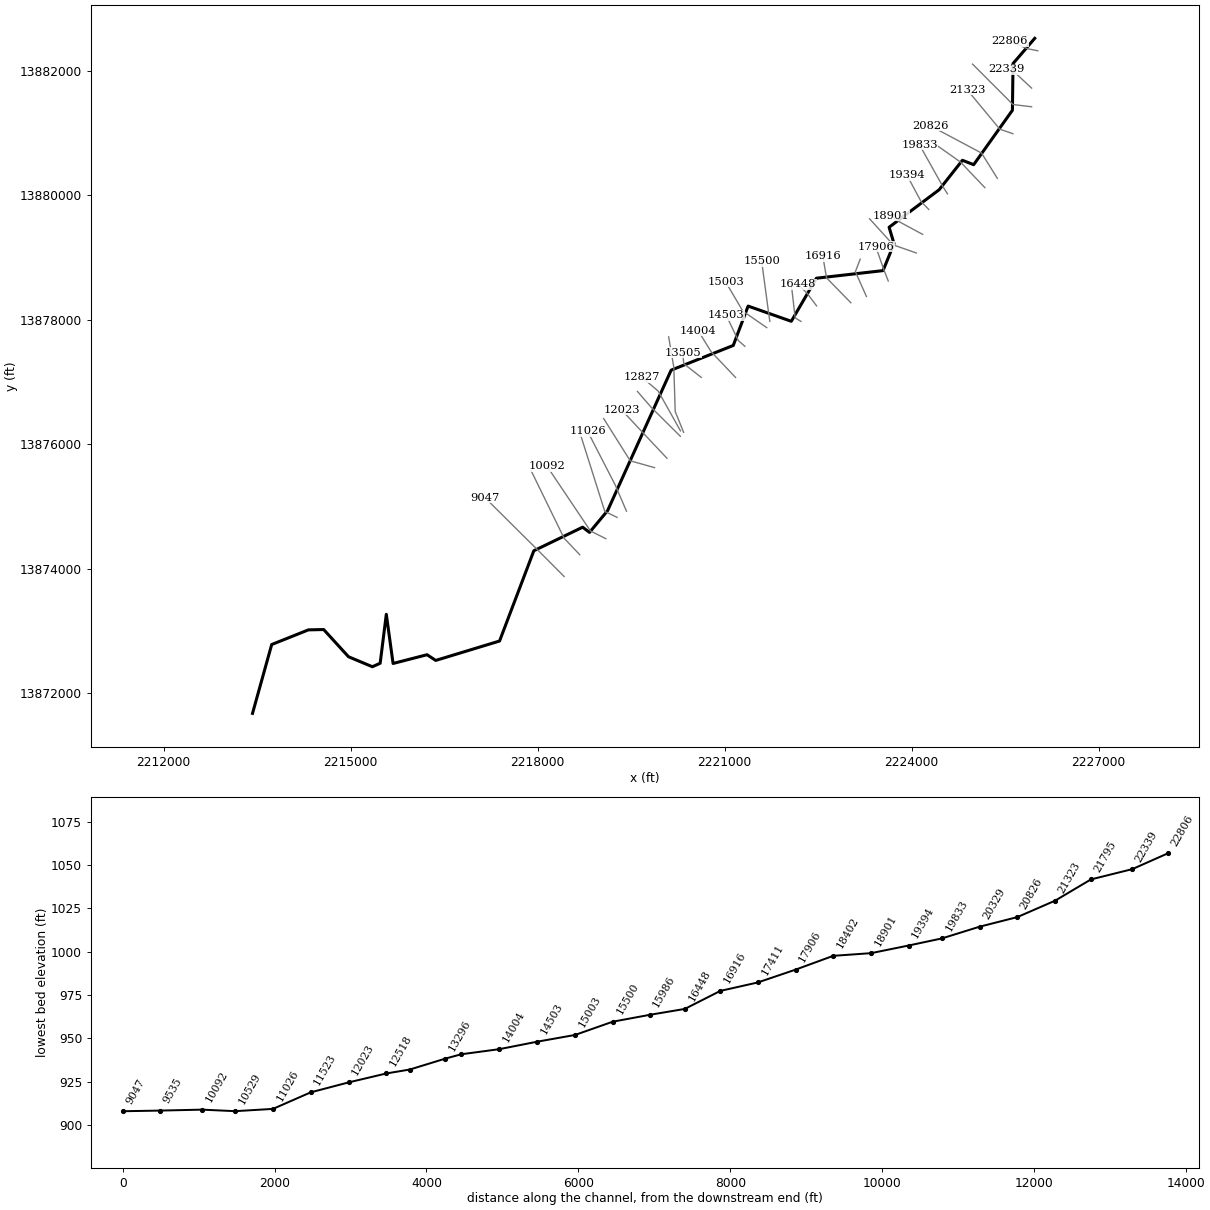
--- Jacobs Creek 2.prj (project) ---

Proj Title=Jacobs Creek 2 Base Level Engineering
Current Plan=p01
Default Exp/Contr=0.3,0.1
English Units
Geom File=g01
Flow File=f01
Plan File=p01
BEGIN DESCRIPTION:
Jacobs Creek 2
END DESCRIPTION:

--- Jacobs Creek 2.p01 (plan) ---

Plan Title=Multiple Run
Short Identifier=Multiple
Geom File=g01
Flow File=f01
Subcritical Flow
K Sum by GR= 0
Std Step Tol= 0.01
Critical Tol= 0.01
Num of Std Step Trials= 20
Max Error Tol= 0.3
Flow Tol Ratio= 0.001
Split Flow NTrial= 30
Split Flow Tol= 0.02
Split Flow Ratio= 0.02
Log Output Level= 0
Friction Slope Method= 1
Unsteady Friction Slope Method= 2
Unsteady Bridges Friction Slope Method= 1
Parabolic Critical Depth
Global Vel Dist=  1 , 1 , 1
Global Log Level= 0
CheckData=True
Encroach Param= -1, 0, 0, 0
BEGIN DESCRIPTION:
Multiple Run
END DESCRIPTION:

--- Jacobs Creek 2.f01 (steady flow) ---

Flow Title=Multiple
Number of Profiles=7
Profile Names=10-year,25-year,50-year,1pct_min,100-year,1pct_plu,500-year
River Rch & RM= Jacobs Creek 2,Reach-1,22806
    1374    2360    3310    2250    4489    8956    8164
River Rch & RM= Jacobs Creek 2,Reach-1,20826
    1963    3418    4836    3310    6604   13176   12186
River Rch & RM= Jacobs Creek 2,Reach-1,12023
    2371    4147    5886    4035    8050   16063   14911
River Rch & RM= Jacobs Creek 2,Reach-1,5573
    2431    4239    6003    4105    8190   16340   15091
Boundary for River Rch & Prof#=Jacobs Creek 2,Reach-1,1
Up Type=0
Dn Type=3
Dn Slope=0.005
Boundary for River Rch & Prof#=Jacobs Creek 2,Reach-1,2
Up Type=0
Dn Type=3
Dn Slope=0.005
Boundary for River Rch & Prof#=Jacobs Creek 2,Reach-1,3
Up Type=0
Dn Type=3
Dn Slope=0.005
Boundary for River Rch & Prof#=Jacobs Creek 2,Reach-1,4
Up Type=0
Dn Type=3
Dn Slope=0.005
Boundary for River Rch & Prof#=Jacobs Creek 2,Reach-1,5
Up Type=0
Dn Type=3
Dn Slope=0.005
Boundary for River Rch & Prof#=Jacobs Creek 2,Reach-1,6
Up Type=0
Dn Type=3
Dn Slope=0.005
Boundary for River Rch & Prof#=Jacobs Creek 2,Reach-1,7
Up Type=0
Dn Type=3
Dn Slope=0.005

--- Jacobs Creek 2.g01 (geometry) ---

Geom Title=Existing Conditions

River Reach=Jacobs Creek 2,Reach-1
Reach XY= 30
      2225975.00     13882525.00      2225626.98     13882119.33
      2225617.19     13881368.81      2224995.39     13880494.05
      2224815.00     13880564.96      2224441.67     13880091.65
      2223638.52     13879488.41      2223717.67     13879224.90
      2223541.67     13878791.63      2222472.55     13878669.54
      2222069.15     13877977.06      2221376.46     13878221.48
      2221138.22     13877588.62      2220141.65     13877191.68
      2219121.76     13874933.01      2218831.70     13874583.97
      2218721.67     13874667.38      2217938.63     13874289.00
      2217388.65     13872837.95      2216364.34     13872526.05
      2216225.29     13872617.77      2215680.23     13872477.08
      2215571.63     13873267.60      2215473.03     13872480.64
      2215347.78     13872424.71      2214965.32     13872585.20
      2214566.85     13873022.50      2214321.58     13873017.20
      2213732.74     13872781.55      2213425.00     13871675.00

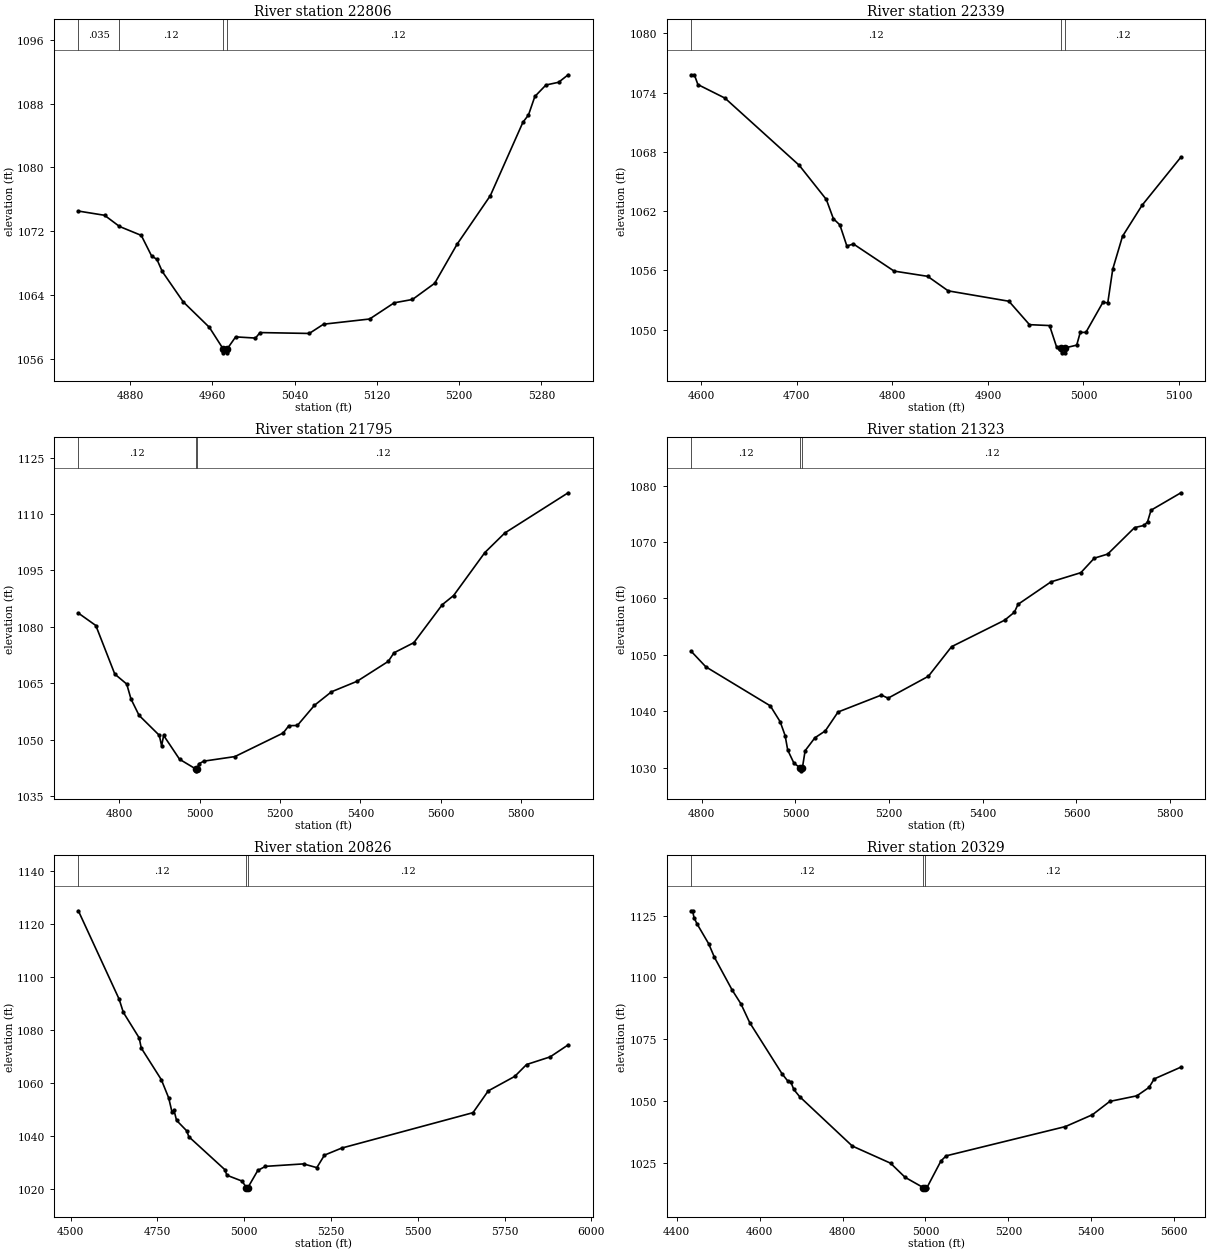
Type RM Length L Ch R = 1,22806,467,467,467
BEGIN DESCRIPTION:
JACOBS CREEK_2 35.0
END DESCRIPTION:
XS GIS Cut Line= 3
      2226025.03     13882324.99      2225858.05     13882358.45
      2225575.00     13882475.00
#Sta/Elev= 30
  4829.7 1074.52  4855.2 1073.99  4869.7 1072.59  4890.9 1071.47  4901.0 1068.88
  4906.1 1068.47  4911.3 1066.95  4931.7 1063.14  4957.1 1059.95  4970.5 1057.25
  4970.8 1056.75  4974.3 1056.75  4974.5 1057.25  4982.7 1058.75  5002.0 1058.60
  5006.4 1059.29  5054.3 1059.18  5068.2 1060.34  5113.0 1060.99  5136.9 1063.02
  5154.7 1063.44  5176.3 1065.47  5198.0 1070.35  5230.4 1076.45  5262.1 1085.65
  5267.5 1086.56  5273.7 1088.88  5284.5 1090.32  5296.8 1090.66  5306.1 1091.60
#Mann=4,-1,0
  4829.7   0.035       0  4869.7    0.12       0  4970.5    0.05       0
  4974.5    0.12       0
Bank Sta=4970.5,4974.5
Exp/Cntr=0.3,0.1

Type RM Length L Ch R = 1,22339,544,544,544
BEGIN DESCRIPTION:
JACOBS CREEK_2 34.0
END DESCRIPTION:
XS GIS Cut Line= 3
      2225925.00     13881725.00      2225624.97     13882005.01
      2225525.04     13882024.99
#Sta/Elev= 30
  4589.6 1075.80  4593.0 1075.80  4596.7 1074.81  4625.0 1073.44  4702.7 1066.64
  4731.0 1063.19  4738.4 1061.24  4745.2 1060.61  4752.5 1058.48  4759.4 1058.68
  4801.9 1055.94  4837.0 1055.41  4858.5 1053.94  4922.0 1052.89  4943.5 1050.52
  4964.5 1050.43  4971.9 1048.25  4976.7 1048.17  4977.0 1047.67  4980.5 1047.67
  4980.7 1048.17  4992.9 1048.45  4996.6 1049.74  5002.5 1049.74  5020.3 1052.78
  5025.4 1052.73  5030.6 1056.14  5040.8 1059.46  5061.2 1062.59  5101.9 1067.47
#Mann=3,-1,0
  4589.6    0.12       0  4976.7    0.05       0  4980.7    0.12       0
Bank Sta=4976.7,4980.7
Exp/Cntr=0.3,0.1

Type RM Length L Ch R = 1,21795,472,472,472
BEGIN DESCRIPTION:
JACOBS CREEK_2 33.0
END DESCRIPTION:
XS GIS Cut Line= 3
      2225925.05     13881424.99      2225625.14     13881461.31
      2224977.48     13882110.63
#Sta/Elev= 30
  4697.9 1083.67  4741.4 1080.37  4788.6 1067.46  4818.3 1064.81  4828.9 1060.85
  4849.0 1056.49  4899.4 1051.18  4905.2 1048.38  4910.2 1051.15  4949.8 1044.82
  4990.1 1042.24  4990.4 1041.74  4994.1 1042.24  4997.6 1043.57  5009.8 1044.31
  5087.6 1045.53  5207.8 1051.80  5221.9 1053.74  5243.1 1053.80  5285.6 1059.16
  5328.0 1062.75  5391.6 1065.54  5469.4 1070.84  5483.5 1073.11  5533.0 1075.81
  5603.7 1085.90  5632.0 1088.34  5709.8 1099.77  5759.3 1104.95  5917.1 1115.65
#Mann=3,-1,0
  4697.9    0.12       0  4990.1    0.05       0  4994.1    0.12       0
Bank Sta=4990.1,4994.1
Exp/Cntr=0.3,0.1

Type RM Length L Ch R = 1,21323,497,497,497
BEGIN DESCRIPTION:
JACOBS CREEK_2 32.0
END DESCRIPTION:
XS GIS Cut Line= 3
      2225624.77     13880992.41      2225414.24     13881065.32
      2224889.86     13881699.90
#Sta/Elev= 30
  4777.2 1050.66  4808.7 1047.89  4946.3 1040.98  4967.4 1038.17  4978.0 1035.70
  4983.5 1033.15  4996.9 1030.81  5010.8 1029.97  5011.1 1029.47  5014.8 1029.97
  5020.7 1033.04  5041.5 1035.32  5063.7 1036.54  5091.0 1039.89  5183.5 1042.89
  5197.8 1042.34  5283.9 1046.22  5333.4 1051.46  5446.7 1056.15  5467.5 1057.56
  5475.3 1058.96  5545.7 1062.94  5609.5 1064.57  5638.2 1067.14  5666.8 1067.86
  5724.2 1072.55  5745.0 1072.95  5752.0 1073.60  5759.3 1075.63  5823.2 1078.72
#Mann=3,-1,0
  4777.2    0.12       0  5010.8    0.05       0  5014.8    0.12       0
Bank Sta=5010.8,5014.8
Exp/Cntr=0.3,0.1

Type RM Length L Ch R = 1,20826,497,497,497
BEGIN DESCRIPTION:
JACOBS CREEK_2 31.0
END DESCRIPTION:
XS GIS Cut Line= 3
      2225375.00     13880274.99      2225122.35     13880680.64
      2224299.28     13881119.59
#Sta/Elev= 30
  4522.1 1124.89  4639.5 1091.57  4651.7 1086.56  4697.4 1076.91  4703.3 1073.11
  4761.1 1061.18  4782.3 1054.30  4791.8 1048.99  4797.7 1049.60  4804.9 1045.83
  4834.3 1041.87  4840.2 1039.67  4944.0 1027.24  4949.9 1025.13  4993.4 1022.93
  5006.2 1020.50  5006.5 1020.00  5010.5 1020.50  5038.9 1026.93  5060.9 1028.48
  5170.6 1029.41  5208.9 1027.99  5230.9 1032.71  5280.4 1035.37  5658.7 1048.73
  5702.6 1056.95  5779.0 1062.42  5813.0 1066.89  5881.0 1069.78  5932.8 1074.31
#Mann=3,-1,0
  4522.1    0.12       0  5006.2    0.05       0  5010.5    0.12       0
Bank Sta=5006.2,5010.5
Exp/Cntr=0.3,0.1

Type RM Length L Ch R = 1,20329,496,496,496
BEGIN DESCRIPTION:
JACOBS CREEK_2 30.0
END DESCRIPTION:
XS GIS Cut Line= 3
      2225175.00     13880125.00      2224785.65     13880535.11
      2224282.33     13880890.78
#Sta/Elev= 30
  4434.5 1126.91  4437.9 1126.91  4441.6 1124.14  4448.5 1121.70  4476.8 1113.60
  4490.9 1108.05  4533.4 1094.90  4554.8 1089.25  4575.9 1081.67  4653.9 1060.99
  4668.1 1057.99  4675.0 1057.72  4682.2 1054.66  4696.4 1051.74  4823.4 1031.77
  4915.6 1024.84  4950.8 1019.12  4994.7 1014.96  4995.0 1014.46  4999.0 1014.96
  5003.5 1014.96  5037.3 1025.73  5049.8 1027.80  5337.6 1039.64  5402.9 1044.44
  5444.7 1049.82  5510.0 1052.08  5539.5 1055.49  5551.8 1058.91  5616.3 1063.68
#Mann=3,-1,0
  4434.5    0.12       0  4994.7    0.05       0  4999.0    0.12       0
Bank Sta=4994.7,4999
Exp/Cntr=0.3,0.1

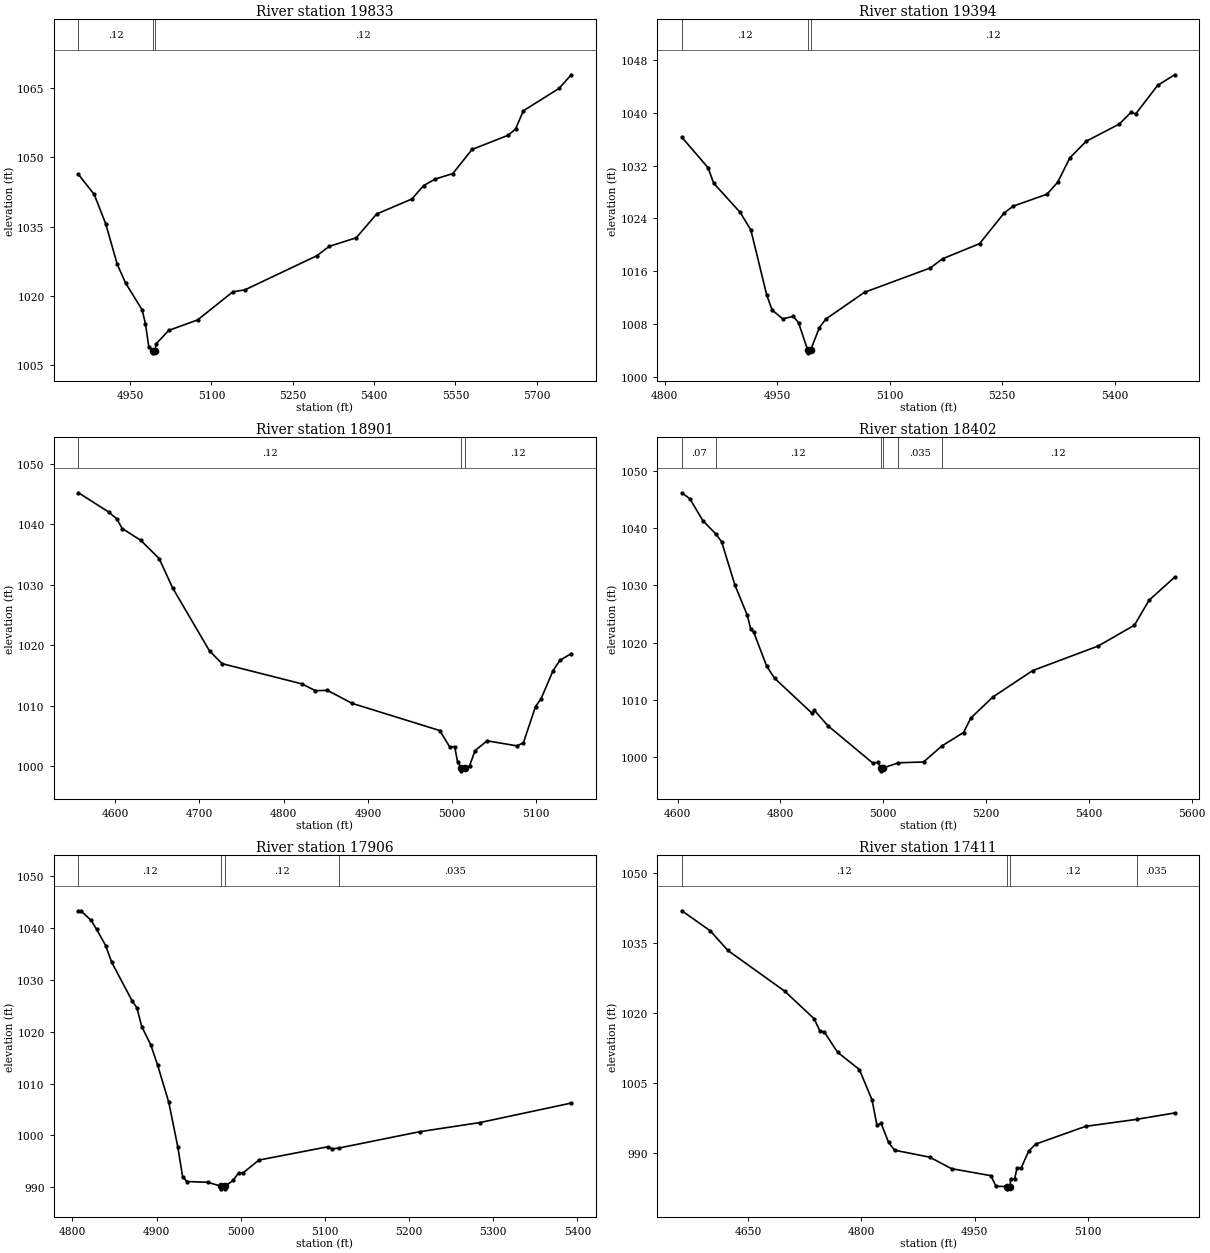
Type RM Length L Ch R = 1,19833,439,439,439
BEGIN DESCRIPTION:
JACOBS CREEK_2 29.0
END DESCRIPTION:
XS GIS Cut Line= 3
      2224575.02     13880024.96      2224498.36     13880148.27
      2224125.52     13880814.66
#Sta/Elev= 30
  4854.8 1046.30  4883.8 1041.98  4905.0 1035.63  4926.3 1026.86  4941.6 1022.82
  4972.3 1016.98  4978.2 1014.02  4984.4 1009.06  4991.4 1008.20  4991.7 1007.70
  4995.8 1008.20  4998.4 1009.69  5021.0 1012.54  5074.6 1014.83  5139.7 1020.93
  5161.4 1021.31  5294.2 1028.70  5317.1 1030.74  5367.0 1032.60  5404.6 1037.74
  5469.7 1041.00  5491.4 1043.91  5513.1 1045.33  5545.1 1046.49  5580.6 1051.71
  5647.8 1054.82  5660.9 1056.16  5675.3 1060.08  5741.1 1064.93  5763.6 1067.88
#Mann=3,-1,0
  4854.8    0.12       0  4991.4    0.05       0  4995.8    0.12       0
Bank Sta=4991.4,4995.8
Exp/Cntr=0.3,0.1

Type RM Length L Ch R = 1,19394,493,493,493
BEGIN DESCRIPTION:
JACOBS CREEK_2 28.0
END DESCRIPTION:
XS GIS Cut Line= 3
      2224275.03     13879774.97      2224151.56     13879901.94
      2223925.00     13880324.99
#Sta/Elev= 30
  4822.9 1036.28  4857.8 1031.67  4865.3 1029.32  4900.7 1024.88  4914.9 1022.22
  4936.0 1012.36  4943.2 1010.10  4957.3 1008.76  4971.5 1009.12  4978.4 1008.18
  4990.4 1004.10  4990.7 1003.60  4994.8 1004.10  5006.2 1007.41  5014.8 1008.72
  5066.4 1012.78  5154.1 1016.47  5170.4 1017.86  5219.9 1020.16  5252.4 1024.78
  5264.4 1025.83  5309.8 1027.66  5323.9 1029.46  5340.2 1033.17  5362.1 1035.69
  5406.0 1038.28  5422.2 1040.12  5427.9 1039.81  5457.2 1044.15  5479.9 1045.76
#Mann=3,-1,0
  4822.9    0.12       0  4990.4    0.05       0  4994.8    0.12       0
Bank Sta=4990.4,4994.8
Exp/Cntr=0.3,0.1

Type RM Length L Ch R = 1,18901,499,499,499
BEGIN DESCRIPTION:
JACOBS CREEK_2 27.0
END DESCRIPTION:
XS GIS Cut Line= 3
      2224175.00     13879375.00      2223784.68     13879585.78
      2223674.99     13879675.01
#Sta/Elev= 30
  4556.4 1045.19  4592.1 1042.02  4601.9 1040.86  4608.3 1039.28  4630.2 1037.34
  4652.1 1034.32  4668.3 1029.42  4712.0 1019.02  4726.9 1016.93  4821.5 1013.59
  4837.7 1012.46  4851.9 1012.51  4881.5 1010.35  4985.2 1005.87  4997.0 1003.19
  5003.0 1003.19  5006.4 1000.71  5010.5  999.70  5010.9  999.20  5015.1  999.70
  5020.7 1000.02  5027.2 1002.55  5041.5 1004.17  5076.9 1003.33  5084.6 1003.84
  5099.0 1009.84  5105.5 1011.11  5119.8 1015.77  5127.8 1017.46  5141.4 1018.60
#Mann=3,-1,0
  4556.4    0.12       0  5010.5    0.05       0  5015.1    0.12       0
Bank Sta=5010.5,5015.1
Exp/Cntr=0.3,0.1

Type RM Length L Ch R = 1,18402,496,496,496
BEGIN DESCRIPTION:
JACOBS CREEK_2 26.0
END DESCRIPTION:
XS GIS Cut Line= 3
      2224074.96     13879075.01      2223705.66     13879204.98
      2223324.97     13879625.04
#Sta/Elev= 30
  4608.5 1046.18  4623.9 1045.15  4649.6 1041.28  4674.2 1039.03  4685.9 1037.62
  4711.5 1030.11  4735.7 1024.81  4742.5 1022.36  4747.8 1021.93  4773.5 1015.91
  4788.7 1013.82  4861.0 1007.75  4866.3 1008.21  4892.0 1005.56  4979.5  999.03
  4990.2  999.12  4995.4  998.15  4995.7  997.65  5000.0  998.15  5029.4  999.05
  5078.6  999.20  5113.7 1001.96  5156.3 1004.34  5170.5 1006.86  5213.1 1010.52
  5290.8 1015.15  5418.4 1019.44  5488.8 1023.08  5517.2 1027.43  5566.9 1031.45
#Mann=6,-1,0
  4608.5    0.07       0  4674.2    0.12       0  4995.4    0.05       0
  5000.0    0.12       0  5029.4   0.035       0  5113.7    0.12       0
Bank Sta=4995.4,5000
Exp/Cntr=0.3,0.1

Type RM Length L Ch R = 1,17906,495,495,495
BEGIN DESCRIPTION:
JACOBS CREEK_2 25.0
END DESCRIPTION:
XS GIS Cut Line= 3
      2223625.00     13878625.01      2223555.16     13878804.61
      2223425.00     13879175.00
#Sta/Elev= 30
  4807.3 1043.33  4810.0 1043.33  4822.2 1041.50  4828.8 1039.76  4839.5 1036.63
  4846.8 1033.38  4871.3 1025.86  4876.7 1024.60  4882.4 1021.00  4893.1 1017.48
  4901.2 1013.59  4914.6 1006.35  4925.3  997.73  4931.1  991.90  4936.4  991.09
  4961.0  990.94  4976.6  990.18  4977.0  989.68  4981.0  989.68  4981.3  990.18
  4990.9  991.29  4997.5  992.77  5002.9  992.77  5021.6  995.23  5103.6  997.80
  5108.9  997.40  5116.2  997.54  5212.4 1000.70  5284.2 1002.47  5392.6 1006.23
#Mann=4,-1,0
  4807.3    0.12       0  4976.6    0.05       0  4981.3    0.12       0
  5116.2   0.035       0
Bank Sta=4976.6,4981.3
Exp/Cntr=0.3,0.1

Type RM Length L Ch R = 1,17411,495,495,495
BEGIN DESCRIPTION:
JACOBS CREEK_2 24.0
END DESCRIPTION:
XS GIS Cut Line= 3
      2223274.99     13878375.02      2223097.69     13878775.09
      2223174.99     13878974.97
#Sta/Elev= 30
  4562.4 1041.82  4600.0 1037.52  4623.3 1033.32  4698.6 1024.59  4737.4 1018.71
  4745.2 1016.01  4750.6 1015.94  4768.4 1011.54  4797.2 1007.84  4814.0 1001.32
  4820.5  995.88  4825.9  996.34  4835.8  992.26  4843.8  990.58  4890.3  989.09
  4919.1  986.63  4971.1  985.13  4978.0  982.86  4992.0  982.81  4992.3  982.31
  4996.8  982.81  4997.2  984.45  5002.6  984.45  5005.8  986.76  5011.2  986.75
  5021.3  990.40  5030.4  991.88  5096.4  995.68  5164.0  997.18  5214.3  998.55
#Mann=4,-1,0
  4562.4    0.12       0  4992.0    0.05       0  4996.8    0.12       0
  5164.0   0.035       0
Bank Sta=4992,4996.8
Exp/Cntr=0.3,0.1

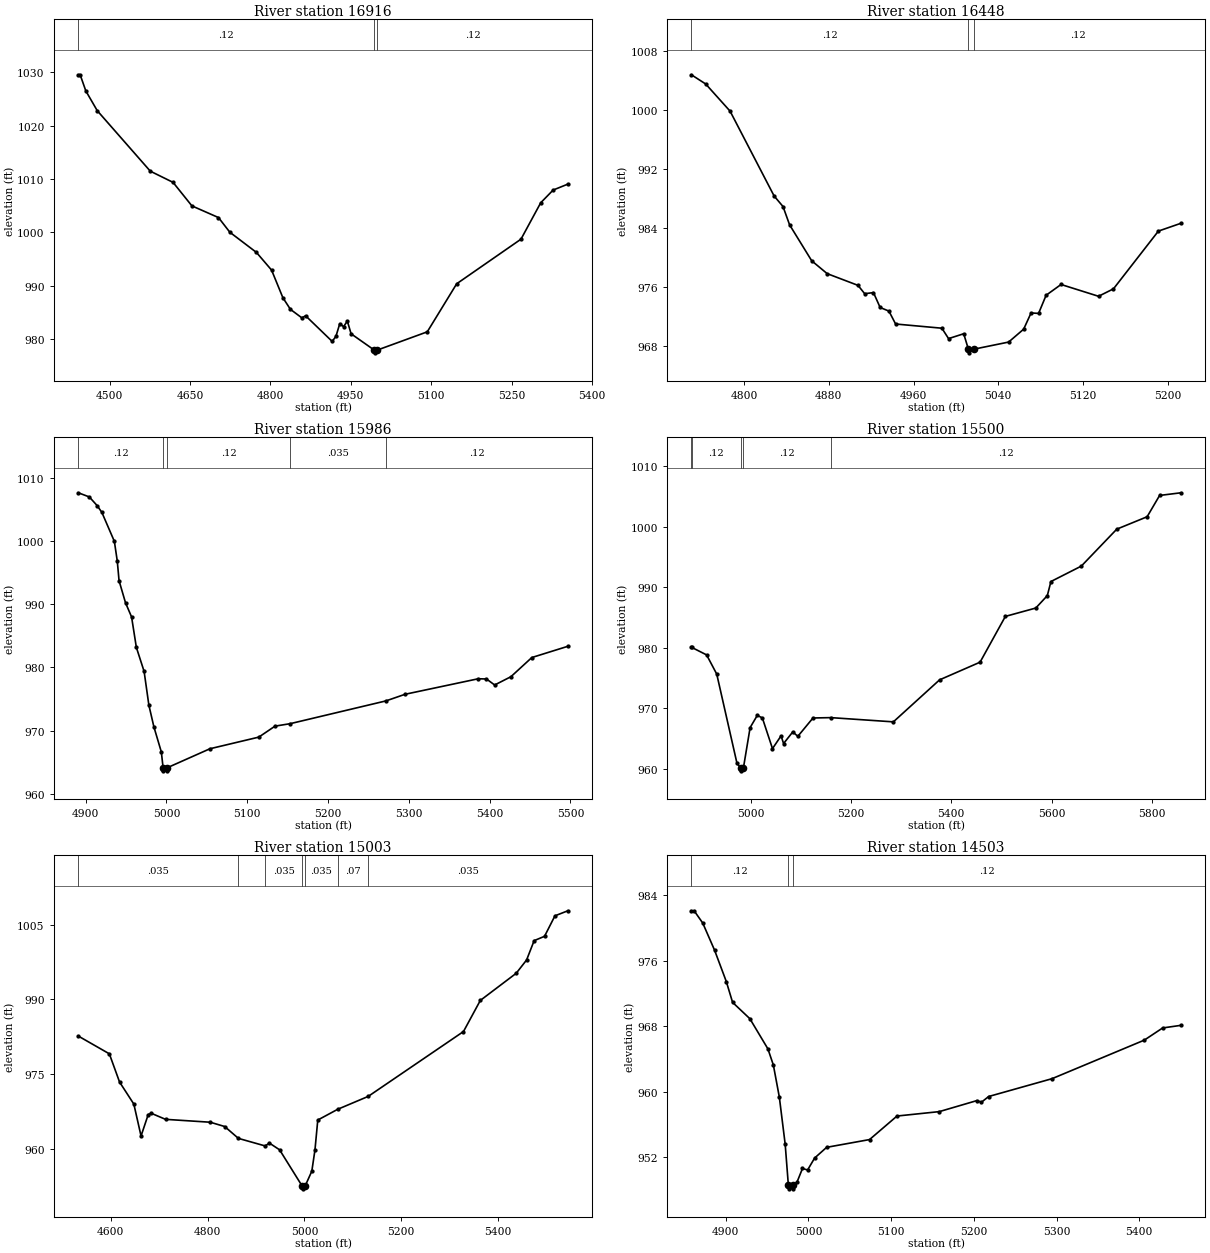
Type RM Length L Ch R = 1,16916,468,468,468
BEGIN DESCRIPTION:
JACOBS CREEK_2 23.0
END DESCRIPTION:
XS GIS Cut Line= 3
      2223024.97     13878275.04      2222635.05     13878674.89
      2222575.00     13879024.98
#Sta/Elev= 30
  4441.5 1029.55  4444.9 1029.55  4455.5 1026.52  4476.8 1022.82  4575.8 1011.48
  4618.3 1009.38  4653.5 1004.97  4703.1 1002.78  4724.3 1000.03  4773.9  996.25
  4802.2  992.93  4823.3  987.75  4837.4  985.57  4858.7  983.98  4865.7  984.37
  4915.3  979.56  4922.3  980.51  4929.5  982.90  4936.5  982.32  4943.6  983.38
  4950.6  980.99  4994.1  977.92  4994.5  977.42  4999.0  977.92  5092.8  981.36
  5147.7  990.37  5267.7  998.73  5304.5 1005.55  5327.7 1007.94  5355.2 1009.05
#Mann=3,-1,0
  4441.5    0.12       0  4994.1    0.05       0  4999.0    0.12       0
Bank Sta=4994.1,4999
Exp/Cntr=0.3,0.1

Type RM Length L Ch R = 1,16448,462,462,462
BEGIN DESCRIPTION:
JACOBS CREEK_2 22.0
END DESCRIPTION:
XS GIS Cut Line= 3
      2222475.00     13878224.99      2222325.33     13878424.86
      2222174.97     13878575.03
#Sta/Elev= 30
  4750.3 1004.73  4763.8 1003.48  4786.8  999.80  4828.4  988.29  4836.8  986.86
  4843.0  984.38  4863.9  979.50  4878.5  977.76  4907.6  976.17  4913.9  975.04
  4922.2  975.19  4928.5  973.17  4936.8  972.68  4943.1  970.93  4986.8  970.36
  4993.1  968.95  5007.4  969.61  5011.8  967.52  5012.2  967.02  5017.1  967.52
  5049.8  968.48  5064.0  970.23  5071.0  972.43  5078.1  972.37  5085.2  974.83
  5099.3  976.29  5134.7  974.69  5148.8  975.70  5191.2  983.53  5212.5  984.59
#Mann=3,-1,0
  4750.3    0.12       0  5011.8    0.05       0  5017.1    0.12       0
Bank Sta=5011.8,5017.1
Exp/Cntr=0.3,0.1

Type RM Length L Ch R = 1,15986,486,486,486
BEGIN DESCRIPTION:
JACOBS CREEK_2 21.0
END DESCRIPTION:
XS GIS Cut Line= 3
      2222224.98     13877975.01      2222131.76     13878031.48
      2222075.00     13878525.03
#Sta/Elev= 30
  4891.0 1007.66  4904.6 1007.00  4914.2 1005.64  4920.1 1004.56  4935.6  999.96
  4939.2  996.84  4941.4  993.73  4949.4  990.23  4956.9  987.99  4962.8  983.17
  4972.4  979.36  4978.3  974.01  4984.5  970.58  4993.7  966.61  4995.9  964.11
  4996.3  963.61  5000.8  963.61  5001.2  964.11  5053.9  967.11  5114.3  968.95
  5134.4  970.69  5153.1  971.08  5271.7  974.69  5295.4  975.74  5386.0  978.20
  5396.1  978.16  5406.2  977.21  5426.3  978.52  5452.2  981.56  5496.8  983.34
#Mann=5,-1,0
  4891.0    0.12       0  4995.9    0.05       0  5001.2    0.12       0
  5153.1   0.035       0  5271.7    0.12       0
Bank Sta=4995.9,5001.2
Exp/Cntr=0.3,0.1

Type RM Length L Ch R = 1,15500,497,497,497
BEGIN DESCRIPTION:
JACOBS CREEK_2 20.0
END DESCRIPTION:
XS GIS Cut Line= 3
      2221725.00     13877974.97      2221708.34     13878091.68
      2221594.31     13878941.77
#Sta/Elev= 30
  4882.1  980.07  4882.3  980.07  4912.4  978.81  4932.6  975.64  4973.0  960.88
  4980.4  960.16  4980.9  959.66  4985.8  960.16  4999.1  966.80  5013.4  968.82
  5023.5  968.40  5043.7  963.33  5060.8  965.44  5065.8  964.17  5084.1  966.09
  5094.2  965.36  5124.4  968.39  5160.0  968.45  5284.6  967.75  5376.7  974.69
  5457.4  977.61  5507.8  985.17  5568.4  986.55  5591.4  988.60  5598.6  990.93
  5659.2  993.48  5729.8  999.58  5790.3 1001.63  5815.2 1005.15  5857.7 1005.59
#Mann=5,-1,0
  4882.1   0.035       0  4882.3    0.12       0  4980.4   0.035       0
  4985.8    0.12       0  5160.0    0.12       0
Bank Sta=4980.4,4985.8
Exp/Cntr=0.3,0.1

Type RM Length L Ch R = 1,15003,500,500,500
BEGIN DESCRIPTION:
JACOBS CREEK_2 19.0
END DESCRIPTION:
XS GIS Cut Line= 3
      2221674.96     13877875.03      2221291.41     13878141.80
      2221015.16     13878610.90
#Sta/Elev= 30
  4532.8  982.64  4596.9  979.08  4618.0  973.42  4647.5  969.00  4662.4  962.60
  4677.2  966.89  4683.3  967.16  4713.0  965.94  4805.5  965.36  4835.2  964.50
  4863.6  962.12  4918.7  960.61  4927.7  961.17  4948.7  959.83  4995.7  952.50
  4996.1  952.00  5001.2  952.50  5015.3  955.55  5021.8  959.81  5027.6  965.80
  5068.9  967.96  5131.8  970.54  5328.7  983.55  5363.5  989.79  5437.6  995.23
  5459.1  997.90  5474.7 1001.78  5496.2 1002.65  5517.7 1006.76  5544.4 1007.77
#Mann=7,-1,0
  4532.8   0.035       0  4863.6    0.12       0  4918.7   0.035       0
  4995.7   0.035       0  5001.2   0.035       0  5068.9    0.07       0
  5131.8   0.035       0
Bank Sta=4995.7,5001.2
Exp/Cntr=0.3,0.1

Type RM Length L Ch R = 1,14503,499,499,499
BEGIN DESCRIPTION:
JACOBS CREEK_2 18.0
END DESCRIPTION:
XS GIS Cut Line= 3
      2221324.97     13877575.03      2221218.52     13877668.24
      2221025.02     13878074.96
#Sta/Elev= 30
  4858.5  982.13  4861.8  982.13  4872.2  980.63  4886.5  977.31  4900.7  973.47
  4908.3  970.92  4929.2  968.92  4951.0  965.23  4957.6  963.25  4964.8  959.34
  4971.9  953.55  4975.7  948.60  4976.2  948.10  4980.9  948.10  4981.3  948.60
  4986.1  948.90  4992.8  950.59  4999.0  950.41  5007.5  951.87  5022.0  953.18
  5073.9  954.13  5107.1  957.01  5158.2  957.55  5203.7  958.90  5209.2  958.70
  5217.9  959.40  5294.5  961.58  5406.1  966.30  5428.3  967.79  5450.4  968.11
#Mann=3,-1,0
  4858.5    0.12       0  4975.7    0.05       0  4981.3    0.12       0
Bank Sta=4975.7,4981.3
Exp/Cntr=0.3,0.1

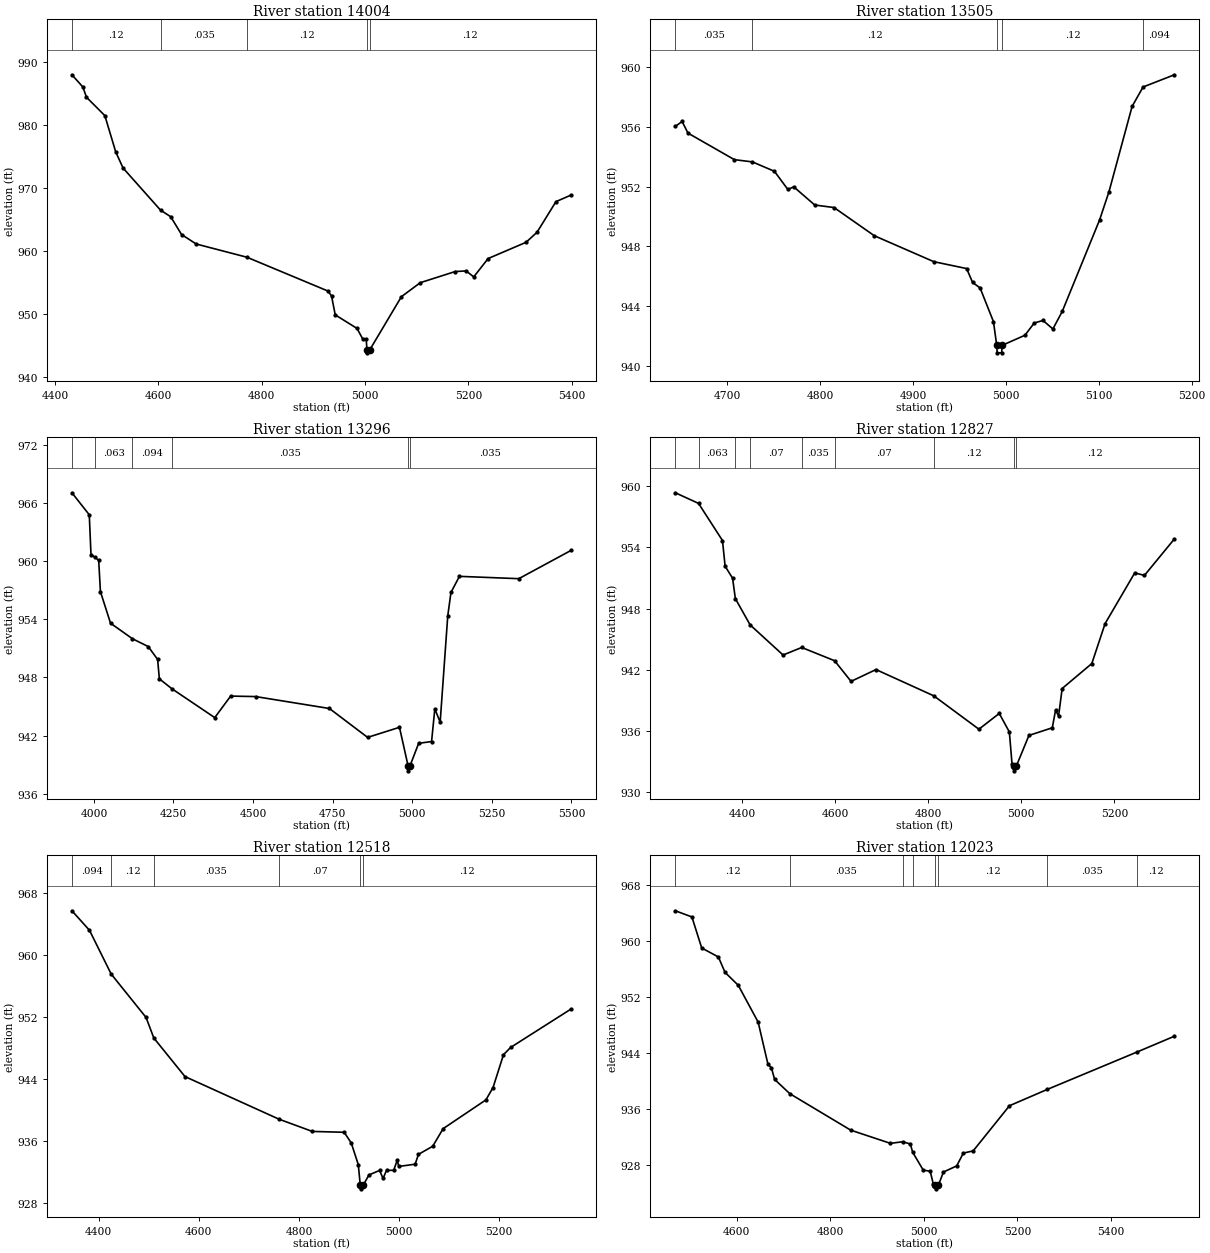
Type RM Length L Ch R = 1,14004,499,499,499
BEGIN DESCRIPTION:
JACOBS CREEK_2 17.0
END DESCRIPTION:
XS GIS Cut Line= 3
      2221174.99     13877075.01      2220784.53     13877486.14
      2220575.00     13877825.00
#Sta/Elev= 30
  4433.0  988.02  4454.2  986.07  4461.1  984.45  4496.7  981.52  4517.7  975.76
  4531.9  973.19  4604.4  966.49  4624.1  965.44  4645.1  962.61  4673.5  961.10
  4771.5  959.00  4928.3  953.62  4935.2  952.85  4942.4  949.83  4984.6  947.67
  4996.0  945.93  5002.3  945.93  5003.8  944.29  5004.2  943.79  5009.4  944.29
  5070.4  952.72  5107.0  954.95  5174.4  956.72  5195.7  956.82  5210.3  955.87
  5238.2  958.79  5311.5  961.37  5332.8  962.97  5369.4  967.84  5398.4  968.88
#Mann=5,-1,0
  4433.0    0.12       0  4604.4   0.035       0  4771.5    0.12       0
  5003.8    0.05       0  5009.4    0.12       0
Bank Sta=5003.8,5009.4
Exp/Cntr=0.3,0.1

Type RM Length L Ch R = 1,13505,209,209,209
BEGIN DESCRIPTION:
JACOBS CREEK_2 16.0
END DESCRIPTION:
XS GIS Cut Line= 3
      2220625.02     13877074.98      2220344.84     13877294.76
      2220325.00     13877474.97
#Sta/Elev= 30
  4643.9  956.04  4651.2  956.37  4657.5  955.59  4707.5  953.81  4726.9  953.66
  4750.6  953.03  4765.1  951.81  4771.4  951.99  4794.0  950.77  4814.8  950.60
  4858.2  948.71  4922.3  946.97  4957.6  946.51  4964.0  945.58  4972.1  945.21
  4986.5  942.95  4990.0  941.36  4990.5  940.86  4995.3  940.86  4995.8  941.36
  5020.4  942.04  5030.4  942.86  5039.8  943.03  5050.5  942.46  5060.6  943.64
  5100.8  949.77  5110.9  951.66  5135.8  957.38  5147.6  958.68  5181.3  959.50
#Mann=5,-1,0
  4643.9   0.035       0  4726.9    0.12       0  4990.0    0.05       0
  4995.8    0.12       0  5147.6   0.094       0
Bank Sta=4990,4995.8
Exp/Cntr=0.3,0.1

Type RM Length L Ch R = 1,13296,469,469,469
BEGIN DESCRIPTION:
JACOBS CREEK_2 15.5
END DESCRIPTION:
XS GIS Cut Line= 4
      2220341.70     13876192.63      2220206.83     13876526.73
      2220184.87     13877235.10      2220101.94     13877726.65
#Sta/Elev= 30
  3931.0  967.04  3985.5  964.77  3990.9  960.64  4004.3  960.37  4015.1  960.06
  4020.5  956.85  4052.2  953.59  4120.8  951.99  4170.7  951.18  4200.2  949.85
  4205.6  947.85  4245.3  946.82  4379.6  943.85  4429.6  946.07  4508.2  946.02
  4739.8  944.79  4859.8  941.81  4959.9  942.85  4987.0  938.86  4987.5  938.36
  4992.8  938.86  5020.2  941.20  5060.7  941.38  5070.9  944.75  5087.7  943.38
  5111.5  954.33  5121.6  956.76  5148.2  958.42  5334.7  958.18  5498.5  961.09
#Mann=6,-1,0
  3931.0   0.094       0  4004.3   0.063       0  4120.8   0.094       0
  4245.3   0.035       0  4987.0   0.035       0  4992.8   0.035       0
Bank Sta=4987,4992.8
Exp/Cntr=0.3,0.1

Type RM Length L Ch R = 1,12827,309,309,309
BEGIN DESCRIPTION:
JACOBS CREEK_2 15.0
END DESCRIPTION:
XS GIS Cut Line= 3
      2220291.73     13876215.67      2219933.73     13876855.34
      2219675.02     13877074.98
#Sta/Elev= 30
  4256.6  959.37  4306.4  958.33  4357.9  954.68  4363.6  952.15  4379.6  950.98
  4385.6  948.97  4417.3  946.39  4488.1  943.43  4528.2  944.17  4598.8  942.87
  4634.2  940.84  4687.8  942.00  4812.0  939.42  4909.0  936.14  4952.7  937.69
  4974.4  935.87  4980.2  932.71  4983.5  932.55  4984.0  932.05  4989.7  932.55
  5016.5  935.53  5066.7  936.28  5073.7  938.01  5080.2  937.44  5087.9  940.14
  5151.6  942.59  5180.2  946.52  5243.9  951.50  5264.7  951.25  5329.0  954.83
#Mann=9,-1,0
  4256.6   0.094       0  4306.4   0.063       0  4385.6   0.035       0
  4417.3    0.07       0  4528.2   0.035       0  4598.8    0.07       0
  4812.0    0.12       0  4983.5    0.05       0  4989.7    0.12       0
Bank Sta=4983.5,4989.7
Exp/Cntr=0.3,0.1

Type RM Length L Ch R = 1,12518,495,495,495
BEGIN DESCRIPTION:
JACOBS CREEK_2 14.0
END DESCRIPTION:
XS GIS Cut Line= 3
      2220288.59     13876128.99      2219825.39     13876590.27
      2219600.12     13876850.11
#Sta/Elev= 30
  4346.3  965.67  4381.4  963.15  4424.7  957.51  4494.5  951.90  4510.0  949.25
  4572.3  944.27  4760.3  938.77  4826.9  937.19  4890.5  937.08  4904.6  935.72
  4918.8  932.90  4922.7  930.28  4923.2  929.78  4929.0  930.28  4940.0  931.57
  4961.2  932.15  4968.3  931.13  4975.3  932.17  4989.5  932.17  4996.6  933.46
  4999.8  932.67  5032.4  932.96  5039.1  934.23  5067.6  935.28  5088.4  937.55
  5173.9  941.26  5188.2  942.86  5209.0  947.09  5223.3  948.03  5343.9  952.98
#Mann=6,-1,0
  4346.3   0.094       0  4424.7    0.12       0  4510.0   0.035       0
  4760.3    0.07       0  4922.7    0.05       0  4929.0    0.12       0
Bank Sta=4922.7,4929
Exp/Cntr=0.3,0.1

Type RM Length L Ch R = 1,12023,500,500,500
BEGIN DESCRIPTION:
JACOBS CREEK_2 13.0
END DESCRIPTION:
XS GIS Cut Line= 3
      2220074.99     13875775.01      2219711.03     13876161.93
      2219345.87     13876553.62
#Sta/Elev= 30
  4468.8  964.38  4504.2  963.50  4525.2  959.06  4560.8  957.78  4575.0  955.58
  4603.3  953.73  4645.8  948.47  4666.8  942.44  4674.1  941.95  4681.0  940.28
  4713.5  938.24  4843.6  933.03  4928.6  931.14  4954.8  931.37  4971.1  931.05
  4976.2  929.86  4998.7  927.32  5013.6  927.15  5020.4  925.28  5024.6  925.14
  5025.1  924.64  5031.0  925.14  5041.9  927.04  5070.3  927.92  5084.4  929.75
  5105.4  930.06  5183.1  936.52  5264.3  938.86  5456.3  944.21  5535.5  946.45
#Mann=8,-1,0
  4468.8    0.12       0  4713.5   0.035       0  4954.8    0.07       0
  4976.2    0.12       0  5024.6    0.05       0  5031.0    0.12       0
  5264.3   0.035       0  5456.3    0.12       0
Bank Sta=5024.6,5031
Exp/Cntr=0.3,0.1

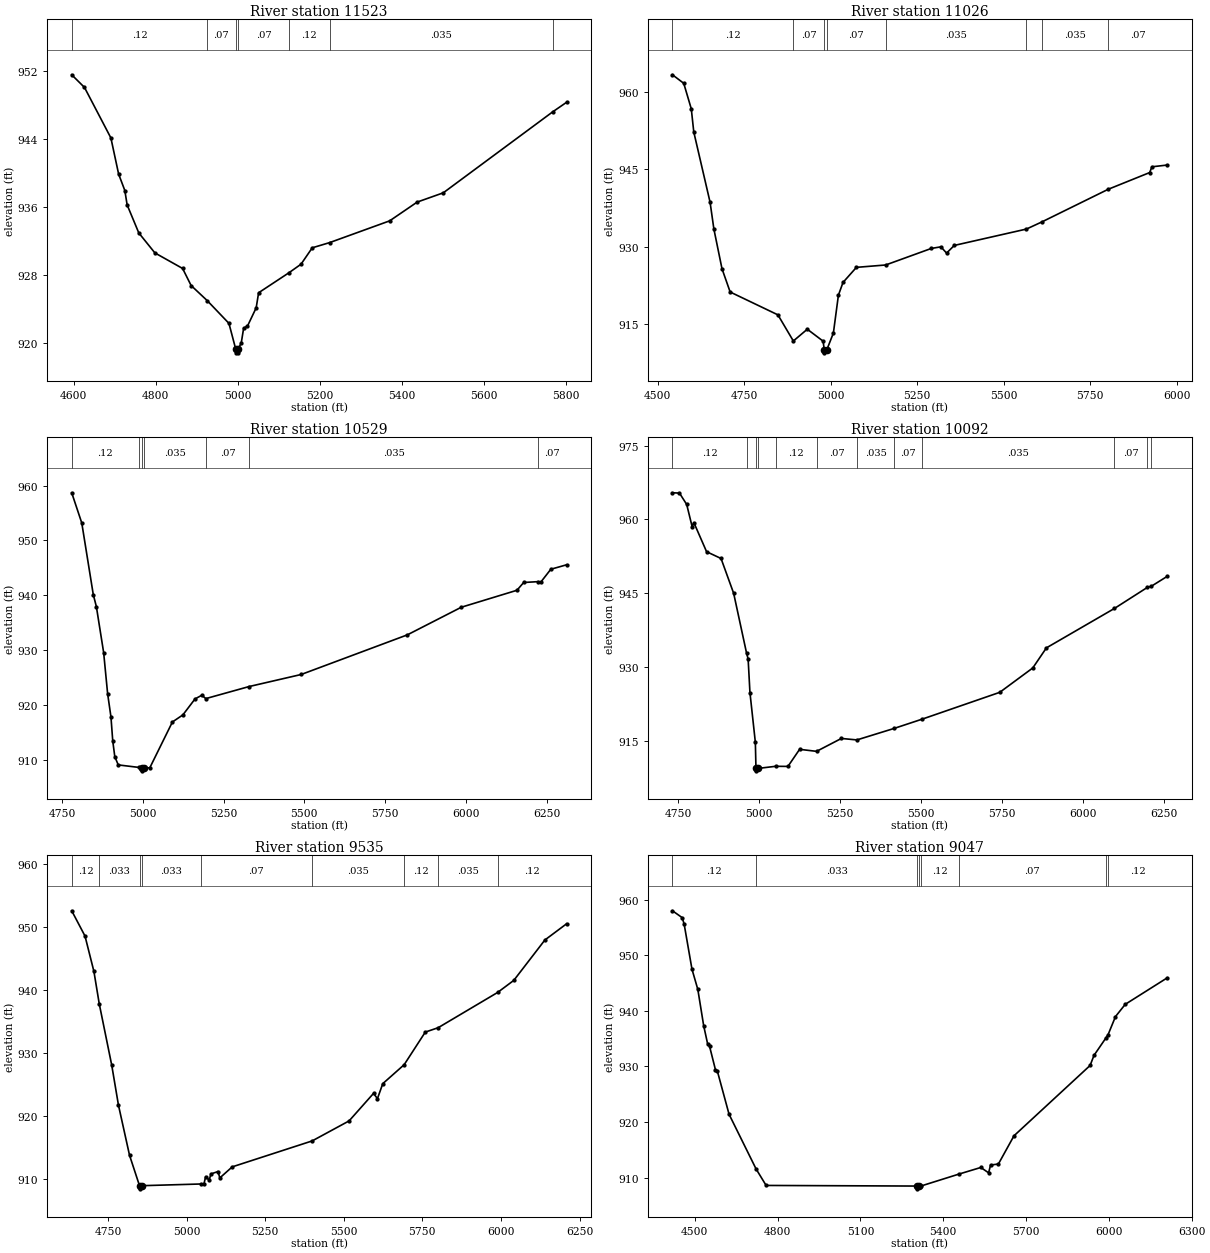
Type RM Length L Ch R = 1,11523,497,497,497
BEGIN DESCRIPTION:
JACOBS CREEK_2 12.0
END DESCRIPTION:
XS GIS Cut Line= 3
      2219874.97     13875625.01      2219485.18     13875734.93
      2219059.30     13876412.74
#Sta/Elev= 30
  4595.0  951.61  4626.1  950.12  4690.4  944.18  4709.3  939.92  4724.4  937.99
  4730.0  936.30  4758.4  933.00  4797.6  930.65  4865.1  928.82  4885.9  926.81
  4925.0  925.04  4978.0  922.36  4994.2  919.39  4994.7  918.89  5000.2  918.89
  5000.7  919.39  5007.9  920.02  5013.8  921.79  5023.2  922.04  5044.4  924.19
  5050.3  925.96  5124.4  928.32  5153.6  929.32  5181.0  931.25  5223.2  931.86
  5369.5  934.42  5436.6  936.63  5500.2  937.72  5766.8  947.25  5800.5  948.37
#Mann=7,-1,0
  4595.0    0.12       0  4925.0    0.07       0  4994.2    0.05       0
  5000.7    0.07       0  5124.4    0.12       0  5223.2   0.035       0
  5766.8    0.07       0
Bank Sta=4994.2,5000.7
Exp/Cntr=0.3,0.1

Type RM Length L Ch R = 1,11026,497,497,497
BEGIN DESCRIPTION:
JACOBS CREEK_2 11.0
END DESCRIPTION:
XS GIS Cut Line= 3
      2219424.99     13874925.03      2219244.63     13875345.15
      2218800.14     13876210.24
#Sta/Elev= 30
  4542.8  963.37  4575.4  961.71  4597.2  956.75  4604.4  952.25  4651.5  938.60
  4662.5  933.39  4685.9  925.69  4709.5  921.16  4847.5  916.72  4892.1  911.64
  4932.4  913.93  4978.1  911.61  4981.6  909.84  4982.1  909.34  4988.3  909.84
  5007.8  913.19  5022.3  920.54  5035.6  923.02  5074.3  925.95  5158.8  926.41
  5290.5  929.62  5318.4  929.94  5334.9  928.72  5357.1  930.21  5565.5  933.39
  5609.3  934.75  5802.2  941.13  5921.7  944.37  5928.2  945.49  5972.6  945.83
#Mann=8,-1,0
  4542.8    0.12       0  4892.1    0.07       0  4981.6    0.05       0
  4988.3    0.07       0  5158.8   0.035       0  5565.5    0.07       0
  5609.3   0.035       0  5802.2    0.07       0
Bank Sta=4981.6,4988.3
Exp/Cntr=0.3,0.1

Type RM Length L Ch R = 1,10529,437,437,437
BEGIN DESCRIPTION:
JACOBS CREEK_2 10.0
END DESCRIPTION:
XS GIS Cut Line= 3
      2219275.00     13874825.00      2219077.09     13874920.84
      2218682.18     13876171.47
#Sta/Elev= 30
  4780.1  958.68  4811.2  953.18  4846.8  940.14  4856.4  937.94  4878.9  929.58
  4891.2  922.09  4901.5  917.86  4907.1  913.46  4913.4  910.62  4924.1  909.11
  4987.1  908.66  4996.3  908.53  4996.8  908.03  5003.7  908.53  5021.8  908.59
  5091.7  916.93  5124.1  918.22  5161.7  921.13  5182.6  921.80  5195.2  921.19
  5329.4  923.39  5490.2  925.58  5818.8  932.80  5985.8  937.83  6157.9  940.92
  6178.9  942.34  6222.8  942.49  6231.3  942.37  6262.8  944.75  6311.5  945.56
#Mann=7,-1,0
  4780.1    0.12       0  4987.1   0.035       0  4996.3   0.035       0
  5003.7   0.035       0  5195.2    0.07       0  5329.4   0.035       0
  6222.8    0.07       0
Bank Sta=4996.3,5003.7
Exp/Cntr=0.3,0.1

Type RM Length L Ch R = 1,10092,557,557,557
BEGIN DESCRIPTION:
JACOBS CREEK_2 9.0
END DESCRIPTION:
XS GIS Cut Line= 3
      2219094.09     13874482.67      2218847.44     13874606.50
      2218149.94     13875647.19
#Sta/Elev= 30
  4731.6  965.40  4753.2  965.34  4775.6  963.03  4792.3  958.54  4797.9  959.32
  4837.0  953.43  4881.7  952.05  4920.7  944.97  4960.4  932.87  4965.4  931.62
  4971.0  924.82  4987.7  914.69  4989.6  909.41  4990.1  908.91  4997.1  909.41
  5050.2  909.83  5088.4  909.81  5124.4  913.28  5176.8  912.87  5253.5  915.49
  5301.4  915.19  5416.5  917.53  5503.4  919.42  5742.8  924.86  5844.8  929.81
  5886.9  933.89  6097.1  941.90  6198.9  946.18  6211.1  946.41  6260.4  948.43
#Mann=12,-1,0
  4731.6    0.12       0  4960.4   0.033       0  4989.6   0.033       0
  4997.1   0.033       0  5050.2    0.12       0  5176.8    0.07       0
  5301.4   0.035       0  5416.5    0.07       0  5503.4   0.035       0
  6097.1    0.07       0  6198.9   0.035       0  6211.1    0.07       0
Bank Sta=4989.6,4997.1
Exp/Cntr=0.3,0.1

Type RM Length L Ch R = 1,9535,488,488,488
BEGIN DESCRIPTION:
JACOBS CREEK_2 8.0
END DESCRIPTION:
XS GIS Cut Line= 3
      2218675.00     13874225.00      2218424.16     13874490.28
      2217894.71     13875576.97
#Sta/Elev= 30
  4634.9  952.53  4677.2  948.51  4705.5  942.89  4722.6  937.71  4762.1  928.02
  4783.6  921.64  4818.8  913.69  4850.5  908.86  4851.0  908.36  4858.2  908.86
  5045.2  909.13  5055.2  909.08  5060.9  910.30  5072.0  909.74  5077.8  910.73
  5100.3  911.11  5105.9  910.09  5145.4  911.85  5399.6  915.97  5517.1  919.15
  5594.8  923.52  5607.3  922.69  5624.3  925.07  5692.3  928.08  5759.5  933.26
  5800.2  933.95  5989.7  939.56  6041.1  941.48  6139.9  947.89  6208.8  950.46
#Mann=9,-1,0
  4634.9    0.12       0  4722.6   0.033       0  4850.5   0.033       0
  4858.2   0.033       0  5045.2    0.07       0  5399.6   0.035       0
  5692.3    0.12       0  5800.2   0.035       0  5989.7    0.12       0
Bank Sta=4850.5,4858.2
Exp/Cntr=0.3,0.1

Type RM Length L Ch R = 1,9047,2479,2479,2479
BEGIN DESCRIPTION:
JACOBS CREEK_2 7.0
END DESCRIPTION:
XS GIS Cut Line= 3
      2218425.01     13873874.99      2218014.92     13874286.85
      2217155.65     13875141.17
#Sta/Elev= 30
  4418.8  957.98  4454.2  956.74  4461.2  955.57  4489.5  947.48  4510.7  943.84
  4531.9  937.32  4546.1  934.08  4553.2  933.62  4574.4  929.43  4581.4  929.17
  4623.9  921.39  4721.7  911.57  4758.2  908.60  5305.9  908.49  5306.4  907.99
  5313.7  908.49  5320.0  908.51  5455.4  910.62  5536.0  911.83  5564.3  910.87
  5571.4  912.27  5599.7  912.45  5656.3  917.53  5932.0  930.17  5946.2  931.99
  5990.2  935.18  5997.2  935.71  6024.0  938.96  6059.3  941.16  6211.7  945.93
#Mann=8,-1,0
  4418.8    0.12       0  4721.7   0.033       0  5305.9   0.033       0
  5313.7   0.033       0  5320.0    0.12       0  5455.4    0.07       0
  5990.2   0.035       0  5997.2    0.12       0
Bank Sta=5305.9,5313.7
Exp/Cntr=0.3,0.1