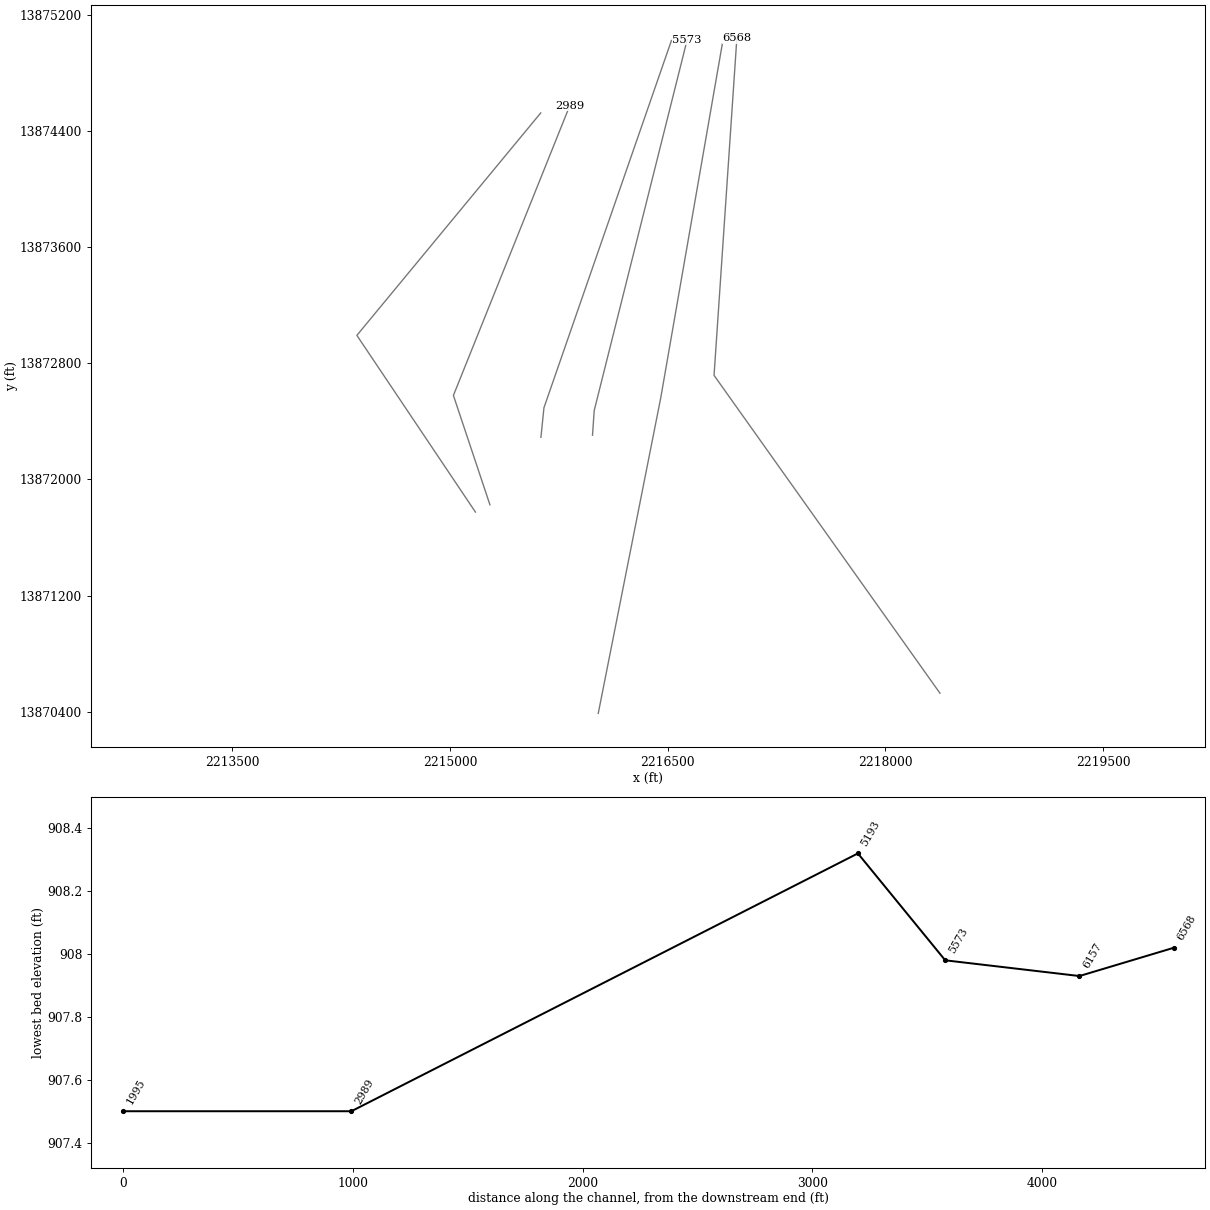
HEC-RAS study Jacobs Creek 2.prj: Jacobs Creek 2 Base Level Engineering

--- Jacobs Creek 2.g01 (geometry) --- (continued)

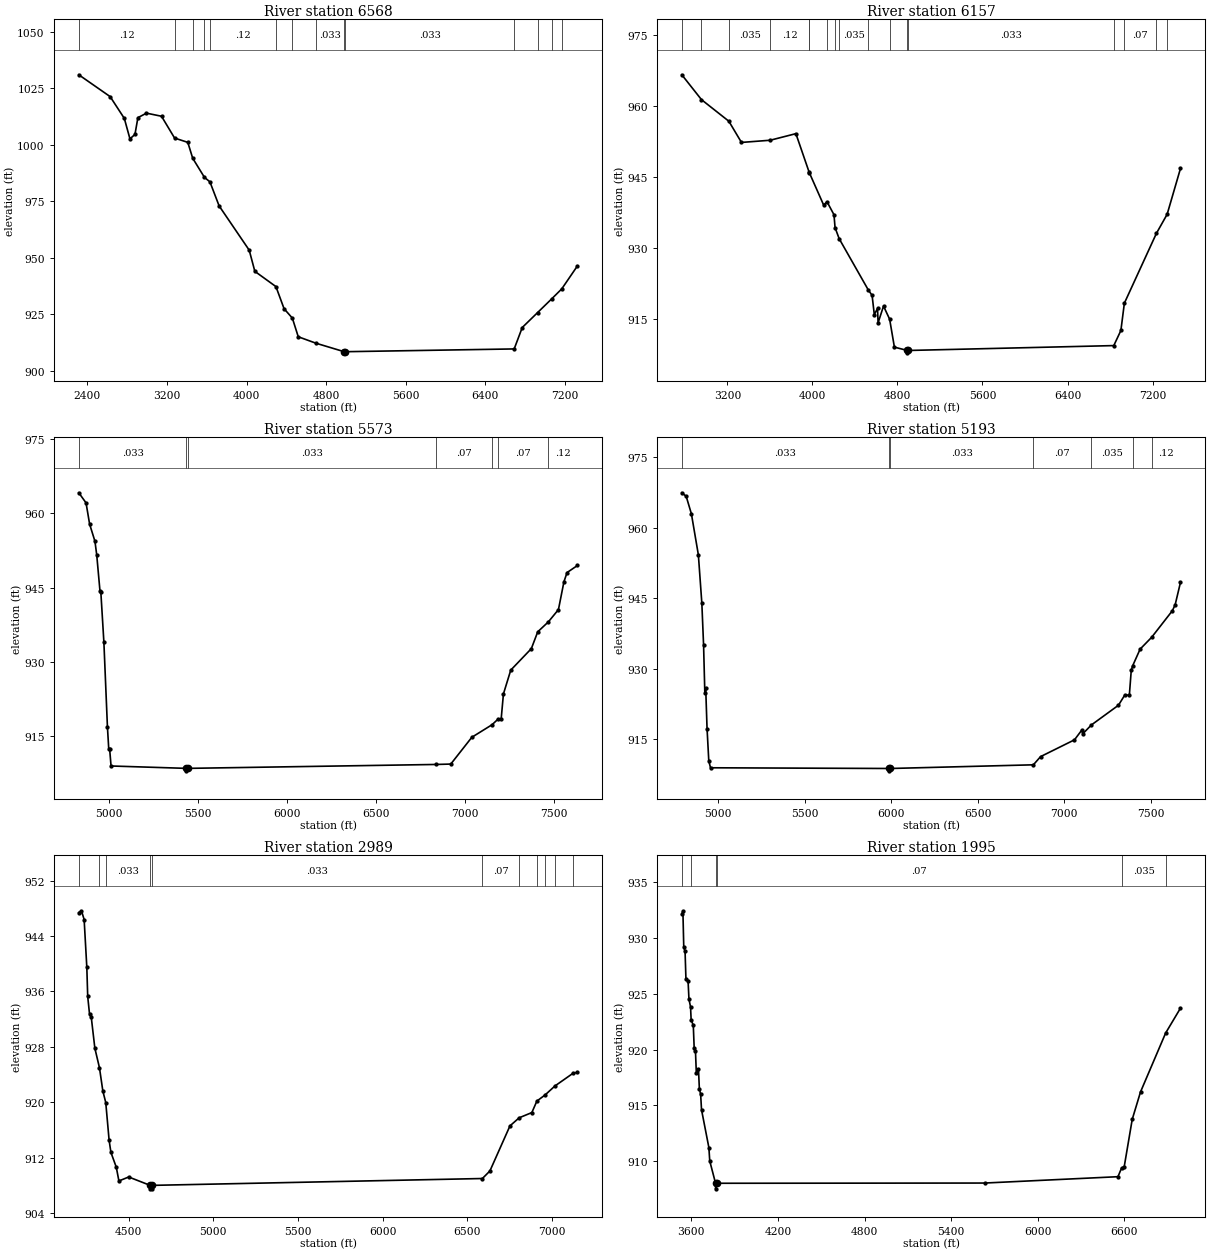
Type RM Length L Ch R = 1,6568,411,411,411
BEGIN DESCRIPTION:
JACOBS CREEK_2 6.0
END DESCRIPTION:
XS GIS Cut Line= 3
      2218375.34     13870527.00      2216818.95     13872716.85
      2216976.09     13875038.74
#Sta/Elev= 30
  2313.4 1031.06  2628.6 1021.40  2771.2 1011.76  2827.8 1002.70  2878.2 1004.68
  2907.7 1012.08  2993.8 1014.08  3145.1 1012.71  3276.6 1003.06  3409.5 1001.15
  3458.6  994.14  3576.8  985.67  3631.8  983.69  3724.4  973.03  4027.0  953.45
  4083.5  944.08  4295.6  937.33  4377.5  927.53  4460.6  923.39  4520.1  915.13
  4698.0  912.28  4982.0  908.52  4982.5  908.02  4990.5  908.52  6691.1  909.75
  6772.2  919.23  6926.6  925.84  7070.6  932.01  7169.4  936.32  7327.2  946.50
#Mann=14,-1,0
  2313.4    0.12       0  3276.6   0.063       0  3458.6   0.035       0
  3576.8   0.063       0  3631.8    0.12       0  4295.6    0.07       0
  4460.6   0.035       0  4698.0   0.033       0  4982.0   0.033       0
  4990.5   0.033       0  6691.1    0.07       0  6926.6   0.035       0
  7070.6    0.07       0  7169.4    0.12       0
Bank Sta=4982,4990.5
Exp/Cntr=0.3,0.1

Type RM Length L Ch R = 1,6157,584,584,584
BEGIN DESCRIPTION:
JACOBS CREEK_2 5.0
END DESCRIPTION:
XS GIS Cut Line= 3
      2216021.18     13870388.11      2216451.73     13872561.72
      2216876.24     13875001.83
#Sta/Elev= 30
  2770.6  966.63  2955.6  961.38  3213.0  956.83  3331.9  952.35  3602.1  952.81
  3844.1  954.20  3966.8  946.19  3972.1  945.88  4105.3  939.13  4137.0  939.83
  4202.6  937.08  4212.7  934.36  4251.5  932.02  4524.5  921.24  4561.2  920.06
  4582.0  916.01  4612.4  917.31  4617.5  914.26  4668.7  917.80  4726.3  915.03
  4771.1  909.13  4893.7  908.43  4894.2  907.93  4902.4  908.43  6835.6  909.46
  6902.4  912.65  6935.1  918.41  7237.1  933.17  7337.5  937.17  7463.2  946.85
#Mann=17,-1,0
  2770.6   0.063       0  2955.6    0.12       0  3213.0   0.035       0
  3602.1    0.12       0  3966.8   0.063       0  3972.1    0.12       0
  4137.0   0.035       0  4212.7    0.12       0  4251.5   0.035       0
  4524.5    0.07       0  4726.3   0.033       0  4893.7   0.033       0
  4902.4   0.033       0  6835.6   0.035       0  6935.1    0.07       0
  7237.1   0.035       0  7337.5    0.12       0
Bank Sta=4893.7,4902.4
Exp/Cntr=0.3,0.1

Type RM Length L Ch R = 1,5573,380,380,380
BEGIN DESCRIPTION:
JACOBS CREEK_2 4.0
END DESCRIPTION:
XS GIS Cut Line= 3
      2215981.54     13872304.29      2215993.41     13872474.87
      2216633.76     13875028.72
#Sta/Elev= 30
  4829.0  964.16  4869.8  962.12  4889.9  957.83  4919.9  954.35  4930.0  951.57
  4947.9  944.41  4952.9  944.16  4970.1  933.98  4990.1  916.83  4997.6  912.34
  5002.6  912.34  5010.4  908.96  5433.7  908.48  5434.2  907.98  5442.9  908.48
  6839.7  909.27  6920.7  909.35  7039.0  914.76  7152.4  917.29  7185.8  918.41
  7203.8  918.38  7216.7  923.52  7257.9  928.33  7373.6  932.67  7409.6  936.07
  7469.4  938.08  7526.0  940.56  7556.9  946.18  7574.4  948.04  7632.9  949.47
#Mann=7,-1,0
  4829.0   0.033       0  5433.7   0.033       0  5442.9   0.033       0
  6839.7    0.07       0  7152.4   0.035       0  7185.8    0.07       0
  7469.4    0.12       0
Bank Sta=5433.7,5442.9
Exp/Cntr=0.3,0.1

Type RM Length L Ch R = 1,5193,2204,2204,2204
BEGIN DESCRIPTION:
JACOBS CREEK_2 3.0
END DESCRIPTION:
XS GIS Cut Line= 3
      2215626.21     13872289.84      2215647.07     13872493.66
      2216525.40     13875023.87
#Sta/Elev= 30
  4788.9  967.38  4814.2  966.63  4844.3  962.91  4884.6  954.20  4904.7  943.91
  4914.7  935.06  4922.0  924.82  4927.1  925.81  4934.8  917.31  4944.9  910.41
  4954.9  908.97  5985.6  908.82  5986.1  908.32  5994.8  908.82  6821.5  909.60
  6863.2  911.34  7059.3  914.91  7101.6  916.98  7106.9  916.17  7156.8  918.06
  7313.4  922.25  7350.6  924.45  7376.4  924.37  7387.5  929.68  7395.6  930.63
  7438.7  934.17  7505.5  936.69  7625.4  942.34  7641.5  943.62  7672.1  948.36
#Mann=7,-1,0
  4788.9   0.033       0  5985.6   0.033       0  5994.8   0.033       0
  6821.5    0.07       0  7156.8   0.035       0  7395.6    0.07       0
  7505.5    0.12       0
Bank Sta=5985.6,5994.8
Exp/Cntr=0.3,0.1

Type RM Length L Ch R = 1,2989,994,994,994
BEGIN DESCRIPTION:
JACOBS CREEK_2 2.0
END DESCRIPTION:
XS GIS Cut Line= 3
      2215275.00     13871824.99      2215023.35     13872578.59
      2215824.98     13874574.95
#Sta/Elev= 30
  4205.5  947.39  4221.3  947.64  4237.1  946.38  4252.9  939.50  4258.2  935.27
  4268.8  932.76  4279.2  932.28  4300.4  927.80  4327.6  924.98  4347.7  921.61
  4364.8  919.96  4384.7  914.50  4395.3  912.76  4426.9  910.63  4442.5  908.64
  4500.4  909.21  4627.4  908.00  4627.9  907.50  4636.3  907.50  4636.8  908.00
  6589.7  908.99  6634.1  910.08  6752.6  916.59  6807.3  917.76  6881.9  918.51
  6911.6  920.17  6960.0  921.05  7018.9  922.36  7126.2  924.20  7151.3  924.31
#Mann=11,-1,0
  4205.5    0.12       0  4327.6    0.07       0  4364.8   0.033       0
  4627.4   0.033       0  4636.8   0.033       0  6589.7    0.07       0
  6807.3   0.035       0  6911.6    0.07       0  6960.0   0.035       0
  7018.9    0.07       0  7126.2   0.035       0
Bank Sta=4627.4,4636.8
Exp/Cntr=0.3,0.1

Type RM Length L Ch R = 1,1995,0,0,0
BEGIN DESCRIPTION:
JACOBS CREEK_2 1.0
END DESCRIPTION:
XS GIS Cut Line= 3
      2215174.98     13871775.03      2214358.25     13872992.33
      2215625.00     13874525.00
#Sta/Elev= 30
  3534.1  932.14  3541.6  932.46  3547.6  929.18  3556.6  928.83  3562.6  926.36
  3577.6  926.12  3583.6  924.52  3594.6  923.83  3598.6  922.68  3613.6  922.17
  3619.6  920.18  3628.6  919.89  3634.6  917.90  3649.6  918.24  3655.6  916.50
  3664.6  915.97  3670.6  914.60  3721.6  911.20  3727.6  910.00  3767.8  908.00
  3768.3  907.50  3777.4  908.00  5631.7  908.02  6555.3  908.59  6580.5  909.37
  6598.3  909.46  6654.2  913.74  6711.6  916.20  6885.4  921.48  6988.4  923.72
#Mann=6,-1,0
  3534.1    0.12       0  3594.6    0.07       0  3767.8   0.033       0
  3777.4    0.07       0  6580.5   0.035       0  6885.4    0.07       0
Bank Sta=3767.8,3777.4
Exp/Cntr=0.3,0.1

Chan Stop Cuts=-1