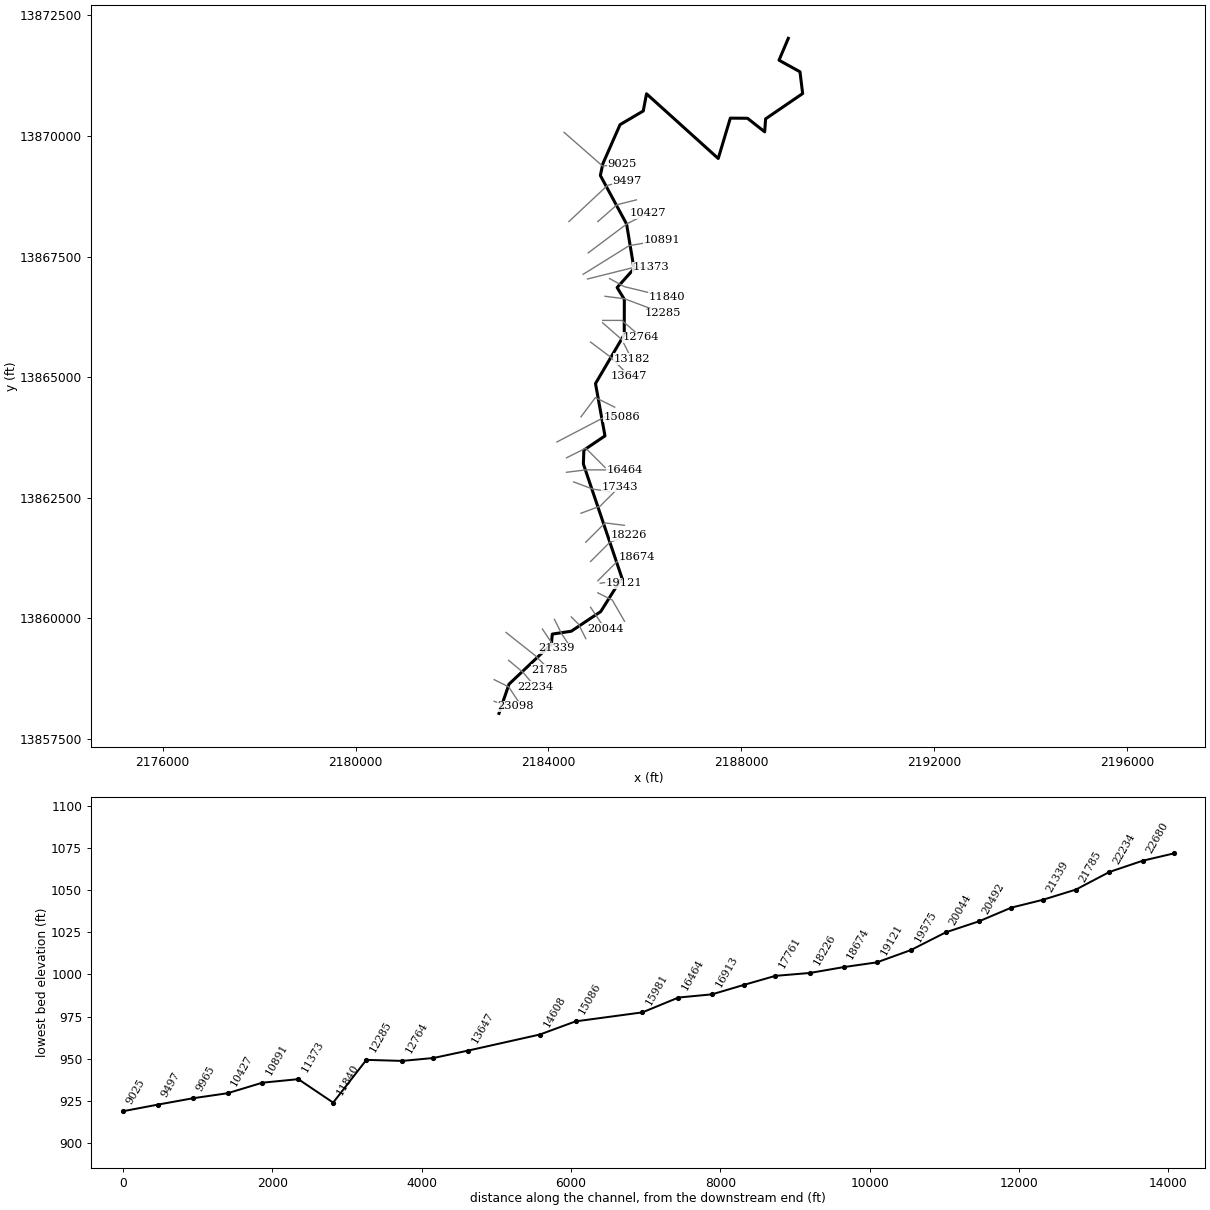
--- Jentsch Creek.prj (project) ---

Proj Title=Jentsch Creek Base Level Engineering
Current Plan=p01
Default Exp/Contr=0.3,0.1
English Units
Geom File=g01
Flow File=f01
Plan File=p01
Y Axis Title=Elevation
X Axis Title(PF)=Main Channel Distance
X Axis Title(XS)=Station
BEGIN DESCRIPTION:
Jentsch Creek
END DESCRIPTION:
DSS Export Rating Curves= 0
DSS Export Rating Curve Sorted= 0
DSS Export Volume Flow Curves= 0
DXF OffsetX= 0
DXF OffsetY= 0
DXF ScaleX= 1
DXF ScaleY= 10

--- Jentsch Creek.p01 (plan) ---

Plan Title=Multiple Run
Short Identifier=Multiple
Geom File=g01
Flow File=f01
Subcritical Flow
K Sum by GR= 0
Std Step Tol= 0.01
Critical Tol= 0.01
Num of Std Step Trials= 20
Max Error Tol= 0.3
Flow Tol Ratio= 0.001
Split Flow NTrial= 30
Split Flow Tol= 0.02
Split Flow Ratio= 0.02
Log Output Level= 0
Friction Slope Method= 1
Unsteady Friction Slope Method= 2
Unsteady Bridges Friction Slope Method= 1
Parabolic Critical Depth
Global Vel Dist=  1 , 1 , 1
Global Log Level= 0
CheckData=True
Encroach Param= -1, 0, 0, 0
BEGIN DESCRIPTION:
Multiple Run
END DESCRIPTION:

--- Jentsch Creek.f01 (steady flow) ---

Flow Title=Multiple
Program Version=4.10
Number of Profiles= 7
Profile Names=10-year,25-year,50-year,1pct_min,100-year,1pct_plu,500-year
River Rch & RM=Jentsch Creek,Reach-1         ,23098
    1473    2548    3590    2450    4889    9754    8971
River Rch & RM=Jentsch Creek,Reach-1         ,19121
    1682    2919    4121    2815    5617   11207   10330
River Rch & RM=Jentsch Creek,Reach-1         ,13647
    2974    5333    7695    5362   10699   21347   20497
River Rch & RM=Jentsch Creek,Reach-1         ,12764
    3293    5909    8528    5939   11850   23644   22681
River Rch & RM=Jentsch Creek,Reach-1         ,9025
    4086    7327   10572    7353   14671   29273   27997
Boundary for River Rch & Prof#=Jentsch Creek,Reach-1         , 1
Up Type= 0
Dn Type= 3
Dn Slope=0.005
Boundary for River Rch & Prof#=Jentsch Creek,Reach-1         , 2
Up Type= 0
Dn Type= 3
Dn Slope=0.005
Boundary for River Rch & Prof#=Jentsch Creek,Reach-1         , 3
Up Type= 0
Dn Type= 3
Dn Slope=0.005
Boundary for River Rch & Prof#=Jentsch Creek,Reach-1         , 4
Up Type= 0
Dn Type= 3
Dn Slope=0.005
Boundary for River Rch & Prof#=Jentsch Creek,Reach-1         , 5
Up Type= 0
Dn Type= 3
Dn Slope=0.005
Boundary for River Rch & Prof#=Jentsch Creek,Reach-1         , 6
Up Type= 0
Dn Type= 3
Dn Slope=0.005
Boundary for River Rch & Prof#=Jentsch Creek,Reach-1         , 7
Up Type= 0
Dn Type= 3
Dn Slope=0.005
DSS Import GetInterval= 0
DSS Import GetPeak= 0
DSS Import FillOption= 0

--- Jentsch Creek.g01 (geometry) ---

Geom Title=Existing Conditions
Program Version=4.10

River Reach=Jentsch Creek   ,Reach-1
Reach XY= 30
        2182975.       13858025.      2183182.81     13858631.19
      2184061.78     13859461.33      2184080.17     13859669.59
       2184473.5     13859728.61      2185084.68     13860135.76
      2185524.23     13860835.69       2184724.9     13863197.69
      2184735.47     13863484.82      2185172.92     13863780.24
      2184976.35     13864865.35      2185572.81     13865880.45
      2185574.46     13866611.14      2185424.96     13866856.62
      2185775.13     13867247.69      2185621.24     13868173.44
      2185077.14     13869180.97      2185128.62      13869423.5
      2185485.75     13870234.68      2185966.86     13870518.32
      2186034.84     13870874.59      2187521.95     13869532.76
      2187772.71     13870369.93      2188128.43     13870367.21
       2188485.5     13870085.96      2188504.49      13870355.2
      2189272.93     13870880.24      2189217.19     13871331.19
      2188782.65      13871571.3        2188975.       13872025.

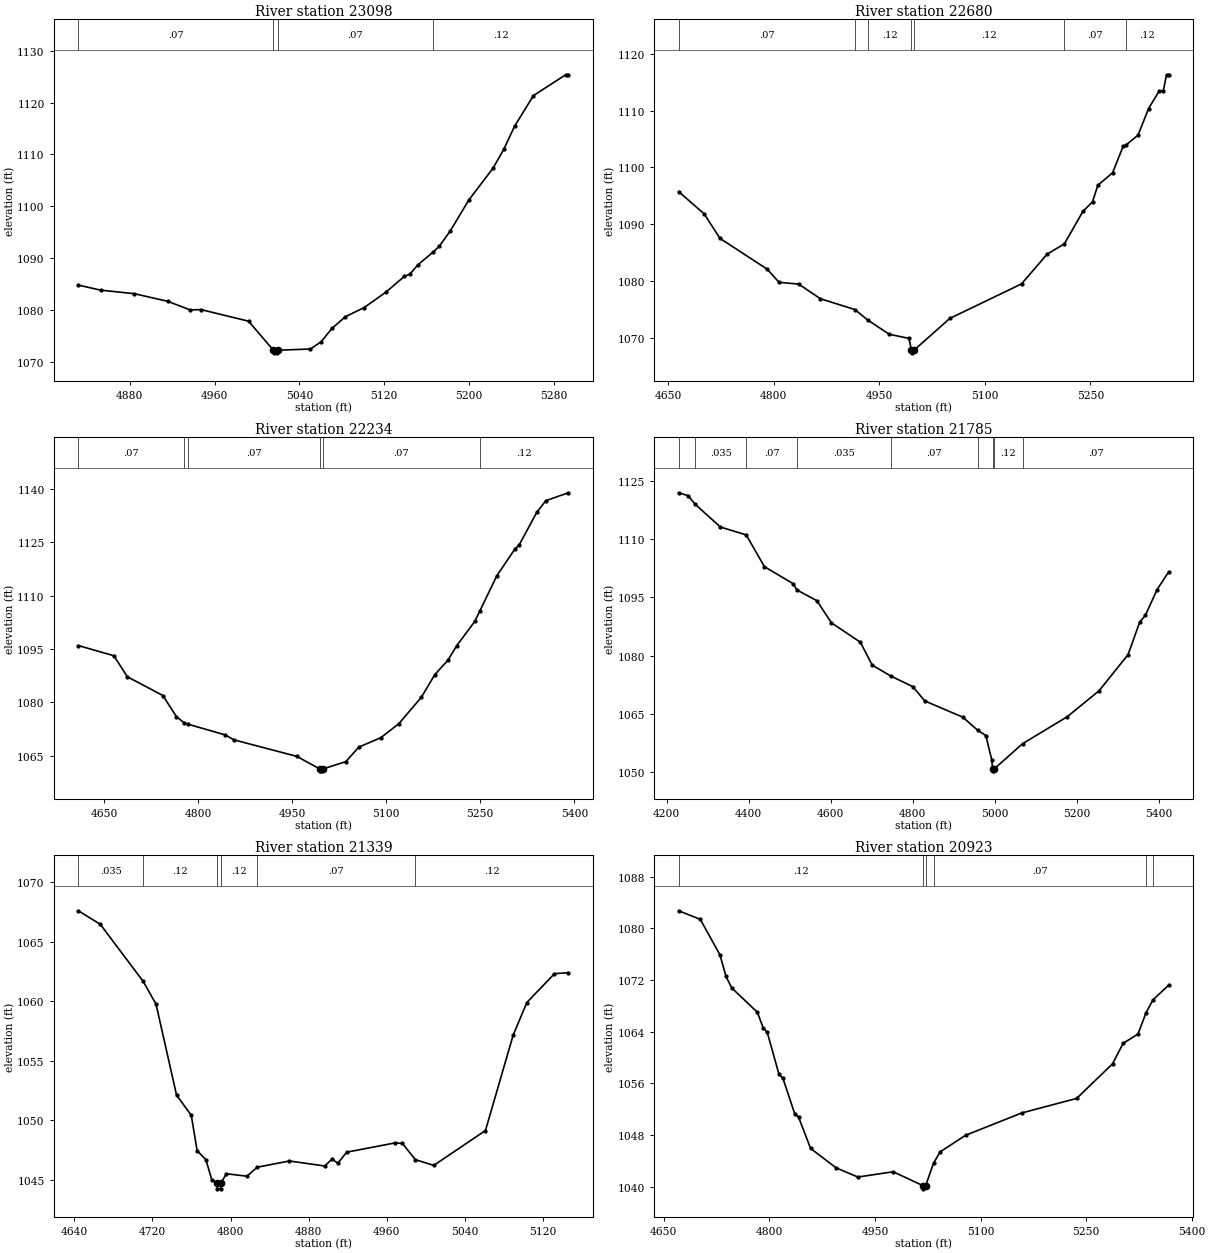
Type RM Length L Ch R = 1 ,23098   ,418,418,418
BEGIN DESCRIPTION:
Jentsch Creek 44.0
END DESCRIPTION:
XS GIS Cut Line= 3
      2182875.03     13858274.99        2183025.       13858225.
      2183324.98       13858175.
#Sta/Elev= 30
  4831.4 1084.85  4852.5 1083.88  4884.1  1083.2  4915.7 1081.73  4936.8 1080.08
  4947.3 1080.13    4992  1077.9  5015.4 1072.31  5015.6 1071.81  5019.1 1071.81
  5019.4 1072.31  5050.3 1072.55  5060.4 1073.93  5070.6 1076.51  5083.3 1078.77
    5101 1080.52  5121.3 1083.46    5139 1086.54  5144.1 1086.97  5151.7 1088.76
  5165.8 1091.16    5172 1092.36  5182.1 1095.24  5199.8 1101.25  5222.7  1107.4
  5232.8 1111.03  5242.9 1115.44  5260.7 1121.34  5291.1 1125.35  5293.6 1125.35
#Mann= 4 ,-1 , 0
  4831.4     .07       0  5015.4     .05       0  5019.4     .07       0
  5165.8     .12       0
Bank Sta=5015.4,5019.4
XS Rating Curve= 0 ,0
Exp/Cntr=0.3,0.1

Type RM Length L Ch R = 1 ,22680   ,446,446,446
BEGIN DESCRIPTION:
Jentsch Creek 43.0
END DESCRIPTION:
XS GIS Cut Line= 3
      2182875.03     13858724.98        2183175.       13858575.
      2183374.98     13858275.03
#Sta/Elev= 30
  4665.1 1095.76  4701.4 1091.85  4723.8 1087.55  4790.8 1082.16  4807.6 1079.85
  4835.6 1079.53  4866.3 1076.97  4915.5 1075.06  4933.4 1073.25  4964.1 1070.73
  4992.1 1070.01  4995.7 1067.97  4995.9 1067.47  4999.7 1067.97  5050.1  1073.5
  5152.2 1079.58  5188.3 1084.78  5212.9  1086.6  5239.3  1092.3  5252.9 1093.98
  5260.4 1096.87  5281.4 1099.07  5296.4 1103.73  5300.7 1103.97  5317.5 1105.67
  5332.5 1110.34  5347.5 1113.41  5353.5  1113.5    5358 1116.27    5361 1116.27
#Mann= 7 ,-1 , 0
  4665.1     .07       0  4915.5    .035       0  4933.4     .12       0
  4995.7     .05       0  4999.7     .12       0  5212.9     .07       0
  5300.7     .12       0
Bank Sta=4995.7,4999.7
XS Rating Curve= 0 ,0
Exp/Cntr=0.3,0.1

Type RM Length L Ch R = 1 ,22234   ,449,449,449
BEGIN DESCRIPTION:
Jentsch Creek 42.0
END DESCRIPTION:
XS GIS Cut Line= 3
      2183175.02     13859124.98        2183475.       13858875.
        2183725.     13858574.99
#Sta/Elev= 30
  4609.3    1096  4665.9 1093.14  4687.4 1087.23    4744 1081.96  4765.5 1076.05
  4778.2 1074.25  4784.4 1073.88  4843.6 1070.88  4857.2  1069.5  4957.5 1064.86
  4994.5 1061.29  4994.8 1060.79  4998.3 1060.79  4998.5 1061.29  5035.6 1063.37
  5056.4 1067.46  5091.6 1070.13  5120.2 1074.04    5156 1081.46  5177.5 1087.83
  5198.3 1091.85  5212.6 1096.01  5241.2 1102.78  5249.3 1105.74  5276.4 1115.63
    5305 1123.09  5312.2 1124.35  5340.2 1133.51  5354.5 1136.72  5390.3 1138.94
#Mann= 6 ,-1 , 0
  4609.3     .07       0  4778.2    .035       0  4784.4     .07       0
  4994.5     .05       0  4998.5     .07       0  5249.3     .12       0
Bank Sta=4994.5,4998.5
XS Rating Curve= 0 ,0
Exp/Cntr=0.3,0.1

Type RM Length L Ch R = 1 ,21785   ,446,446,446
BEGIN DESCRIPTION:
Jentsch Creek 41.0
END DESCRIPTION:
XS GIS Cut Line= 3
      2183120.69     13859703.55        2183725.       13859225.
      2184024.99     13858925.01
#Sta/Elev= 30
  4229.4 1121.95  4252.6  1121.2  4268.8 1119.07  4331.2 1113.13  4394.1  1111.1
  4438.6 1102.92  4509.1 1098.51  4517.4 1096.95  4566.6 1094.15    4602 1088.46
  4672.5 1083.47  4701.4 1077.57  4746.1  1074.8  4800.7 1072.01  4829.6 1068.34
  4922.5 1064.16  4958.6  1060.8  4978.6 1059.43    4993  1053.2  4995.1 1050.84
  4995.3 1050.34  4999.1 1050.84  5068.3 1057.34    5177 1064.26  5254.8 1070.96
  5325.5 1080.27  5353.8 1088.62  5367.9 1090.41  5396.2 1096.99  5424.5 1101.58
#Mann= 9 ,-1 , 0
  4229.4     .07       0  4268.8    .035       0  4394.1     .07       0
  4517.4    .035       0  4746.1     .07       0  4958.6     .12       0
  4995.1     .05       0  4999.1     .12       0  5068.3     .07       0
Bank Sta=4995.1,4999.1
XS Rating Curve= 0 ,0
Exp/Cntr=0.3,0.1

Type RM Length L Ch R = 1 ,21339   ,416,416,416
BEGIN DESCRIPTION:
Jentsch Creek 40.0
END DESCRIPTION:
XS GIS Cut Line= 3
      2183875.01     13859774.98        2184075.       13859475.
      2184175.03     13859374.97
#Sta/Elev= 30
  4644.1 1067.61  4666.6 1066.47  4710.5 1061.68  4723.7 1059.76  4744.7 1052.12
  4759.8 1050.42  4765.8 1047.45  4774.8 1046.68  4780.8 1045.01  4786.3 1044.74
  4786.5 1044.24    4790 1044.24  4790.3 1044.74  4795.8 1045.51  4816.8  1045.3
  4827.4 1046.06  4860.4 1046.58  4896.5 1046.16    4904 1046.74    4910 1046.39
    4919 1047.32  4968.6  1048.1  4976.1 1048.06  4989.4 1046.69  5008.2 1046.21
  5061.2 1049.14  5089.5 1057.13  5103.6  1059.9  5131.9 1062.32  5146.1 1062.41
#Mann= 6 ,-1 , 0
  4644.1    .035       0  4710.5     .12       0  4786.3     .05       0
  4790.3     .12       0  4827.4     .07       0  4989.4     .12       0
Bank Sta=4786.3,4790.3
XS Rating Curve= 0 ,0
Exp/Cntr=0.3,0.1

Type RM Length L Ch R = 1 ,20923   ,431,431,431
BEGIN DESCRIPTION:
Jentsch Creek 39.0
END DESCRIPTION:
XS GIS Cut Line= 3
        2184125.       13859975.        2184275.       13859675.
      2184475.02     13859374.97
#Sta/Elev= 30
  4671.2 1082.73  4701.9  1081.4  4729.9  1075.9  4738.3 1072.59  4746.7 1070.77
    4783 1067.02  4791.4 1064.56    4797 1063.91  4813.7 1057.41  4819.3 1056.79
  4836.1 1051.29  4841.7 1050.74  4858.5 1045.95  4894.8 1042.93  4925.6 1041.51
  4975.9 1042.32  5018.1 1040.18  5018.4 1039.68  5022.1 1040.18  5033.2 1043.65
  5042.7 1045.41  5078.7 1047.97  5158.3 1051.42  5236.5 1053.68  5287.5 1059.03
  5302.6 1062.21  5323.6 1063.64  5335.2 1066.97  5345.1 1068.96  5367.2 1071.21
#Mann= 6 ,-1 , 0
  4671.2     .12       0  5018.1     .05       0  5022.1     .12       0
  5033.2     .07       0  5335.2     .12       0  5345.1     .07       0
Bank Sta=5018.1,5022.1
XS Rating Curve= 0 ,0
Exp/Cntr=0.3,0.1

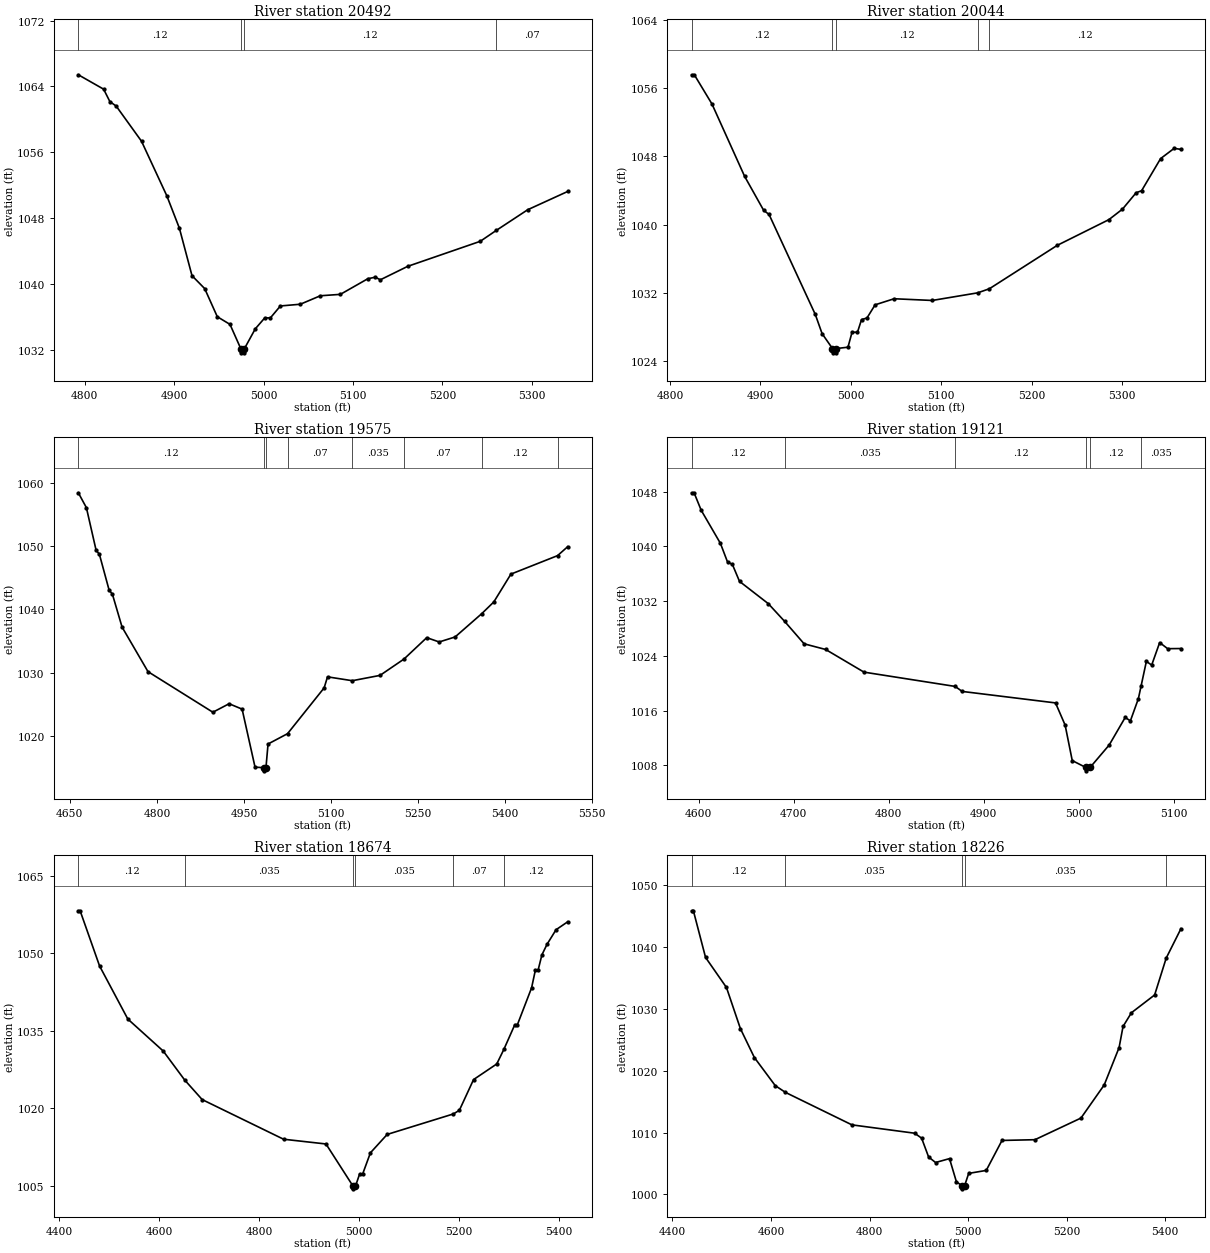
Type RM Length L Ch R = 1 ,20492   ,448,448,448
BEGIN DESCRIPTION:
Jentsch Creek 38.0
END DESCRIPTION:
XS GIS Cut Line= 3
      2184475.02     13860024.98        2184625.       13859875.
        2184775.     13859575.01
#Sta/Elev= 30
  4792.7 1065.41    4821 1063.66    4828 1062.15  4835.1  1061.6  4863.4 1057.33
  4891.7  1050.7  4905.8 1046.75  4919.9 1040.98  4934.1 1039.41  4948.2 1035.99
  4962.4 1035.06  4974.5  1032.1  4974.8  1031.6  4978.3  1031.6  4978.5  1032.1
  4990.7 1034.52  5001.3 1035.85  5007.6 1035.85  5018.8  1037.3  5041.1 1037.51
  5063.5 1038.54  5085.9 1038.71  5116.6 1040.61    5125  1040.8  5130.6 1040.48
  5161.3 1042.12  5242.4 1045.16  5260.4 1046.49  5295.5    1049  5340.2 1051.22
#Mann= 4 ,-1 , 0
  4792.7     .12       0  4974.5     .05       0  4978.5     .12       0
  5260.4     .07       0
Bank Sta=4974.5,4978.5
XS Rating Curve= 0 ,0
Exp/Cntr=0.3,0.1

Type RM Length L Ch R = 1 ,20044   ,469,469,469
BEGIN DESCRIPTION:
Jentsch Creek 37.0
END DESCRIPTION:
XS GIS Cut Line= 3
        2184875.       13860225.        2184975.       13860075.
      2185174.98     13859775.02
#Sta/Elev= 30
    4824 1057.54    4827 1057.54  4846.5 1054.12  4882.6 1045.65  4903.6 1041.68
  4909.6 1041.19  4960.7 1029.49  4968.2 1027.25  4979.7  1025.5    4980    1025
  4983.5    1025  4983.7  1025.5  4996.8 1025.66  5001.3 1027.41  5007.3 1027.41
  5011.8 1028.89  5017.8 1029.08  5026.8 1030.62  5047.8 1031.33  5089.9 1031.13
  5140.1 1032.02  5153.1  1032.5  5228.1 1037.58  5285.2 1040.59  5300.2 1041.82
  5315.3 1043.74  5321.3 1043.97  5342.3 1047.73  5357.3 1048.93  5364.8 1048.81
#Mann= 5 ,-1 , 0
    4824     .12       0  4979.7     .05       0  4983.7     .12       0
  5140.1    .035       0  5153.1     .12       0
Bank Sta=4979.7,4983.7
XS Rating Curve= 0 ,0
Exp/Cntr=0.3,0.1

Type RM Length L Ch R = 1 ,19575   ,454,454,454
BEGIN DESCRIPTION:
Jentsch Creek 36.0
END DESCRIPTION:
XS GIS Cut Line= 3
      2185025.04     13860524.98        2185325.       13860375.
      2185578.44      13859934.7
#Sta/Elev= 30
  4664.6  1058.4  4678.5 1056.05  4695.3  1049.3  4700.9 1048.69  4717.7 1043.01
  4723.3 1042.39    4740 1037.18  4784.7 1030.14  4896.5 1023.73  4924.5 1025.07
  4946.9 1024.22  4969.2 1015.05    4984 1014.97  4984.2 1014.47    4988 1014.97
  4991.6 1018.71  5025.2 1020.34  5088.3 1027.58  5094.1 1029.32  5136.8 1028.71
  5184.6 1029.55  5225.9 1032.13  5265.1 1035.51  5286.6 1034.83    5314 1035.62
  5359.9  1039.3  5380.7 1041.15  5410.2 1045.55  5490.6 1048.47    5508 1049.88
#Mann= 8 ,-1 , 0
  4664.6     .12       0    4984     .05       0    4988     .12       0
  5025.2     .07       0  5136.8    .035       0  5225.9     .07       0
  5359.9     .12       0  5490.6     .07       0
Bank Sta=4984,4988
XS Rating Curve= 0 ,0
Exp/Cntr=0.3,0.1

Type RM Length L Ch R = 1 ,19121   ,447,447,447
BEGIN DESCRIPTION:
Jentsch Creek 35.0
END DESCRIPTION:
XS GIS Cut Line= 3
      2185074.97       13860725.        2185475.       13860775.
      2185575.04     13860724.98
#Sta/Elev= 30
  4592.7 1047.84  4595.3 1047.84  4602.8 1045.28    4623 1040.45  4630.5 1037.72
  4635.6 1037.37  4643.1 1034.89  4673.4 1031.63  4690.6 1029.04  4711.1 1025.76
  4733.8 1024.93  4774.1 1021.62  4870.1 1019.53  4877.4  1018.8  4975.7 1017.12
  4985.8 1013.88  4993.3 1008.69  5007.5 1007.69  5007.8 1007.19  5012.1 1007.69
  5032.2 1010.97    5049 1014.99  5054.5  1014.5  5062.9 1017.74  5065.7 1019.56
  5071.3 1023.19  5076.9 1022.65  5085.3 1025.94  5093.7 1025.05  5107.7 1025.07
#Mann= 6 ,-1 , 0
  4592.7     .12       0  4690.6    .035       0  4870.1     .12       0
  5007.5     .05       0  5012.1     .12       0  5065.7    .035       0
Bank Sta=5007.5,5012.1
XS Rating Curve= 0 ,0
Exp/Cntr=0.3,0.1

Type RM Length L Ch R = 1 ,18674   ,448,448,448
BEGIN DESCRIPTION:
Jentsch Creek 34.0
END DESCRIPTION:
XS GIS Cut Line= 3
      2185024.97     13860774.97        2185425.       13861175.
      2185824.97     13861274.99
#Sta/Elev= 30
  4438.9 1058.22  4442.5 1058.22  4481.4 1047.52  4537.9 1037.24  4608.6 1031.05
  4651.4 1025.45  4686.4 1021.65  4849.1 1013.97  4933.9 1013.05  4988.1 1004.86
  4988.5 1004.36  4992.8 1004.86  5001.1 1007.24  5007.2 1007.24  5022.7 1011.34
  5056.2  1014.9  5188.6 1018.87  5200.5 1019.58  5228.8 1025.52  5275.2 1028.55
  5289.4 1031.37  5311.3 1036.16  5316.4 1036.14  5344.8 1043.29  5352.5 1046.78
  5357.7 1046.67  5365.4 1049.67  5375.7 1051.73  5393.7 1054.55  5416.9 1056.08
#Mann= 6 ,-1 , 0
  4438.9     .12       0  4651.4    .035       0  4988.1    .035       0
  4992.8    .035       0  5188.6     .07       0  5289.4     .12       0
Bank Sta=4988.1,4992.8
XS Rating Curve= 0 ,0
Exp/Cntr=0.3,0.1

Type RM Length L Ch R = 1 ,18226   ,465,465,465
BEGIN DESCRIPTION:
Jentsch Creek 33.0
END DESCRIPTION:
XS GIS Cut Line= 3
      2184874.97     13861174.97        2185275.       13861575.
      2185674.98     13861724.99
#Sta/Elev= 30
  4438.9  1045.9  4442.5  1045.9  4467.2 1038.35  4509.6 1033.49  4537.9 1026.83
  4566.2 1022.16  4608.6 1017.61  4629.2 1016.52  4764.2 1011.26  4891.5 1009.91
  4905.6 1009.11  4919.8 1006.06  4933.9 1005.17  4962.2  1005.8  4976.3 1002.02
  4988.1 1001.41  4988.5 1000.91  4992.8 1001.41  5001.1 1003.41  5036.7 1003.89
  5068.7 1008.74  5135.5 1008.86  5228.9 1012.36  5276.1 1017.72  5306.3 1023.77
  5314.3 1027.18  5331.3  1029.4  5378.4 1032.28  5401.9 1038.25  5431.8    1043
#Mann= 5 ,-1 , 0
  4438.9     .12       0  4629.2    .035       0  4988.1    .035       0
  4992.8    .035       0  5401.9     .12       0
Bank Sta=4988.1,4992.8
XS Rating Curve= 0 ,0
Exp/Cntr=0.3,0.1

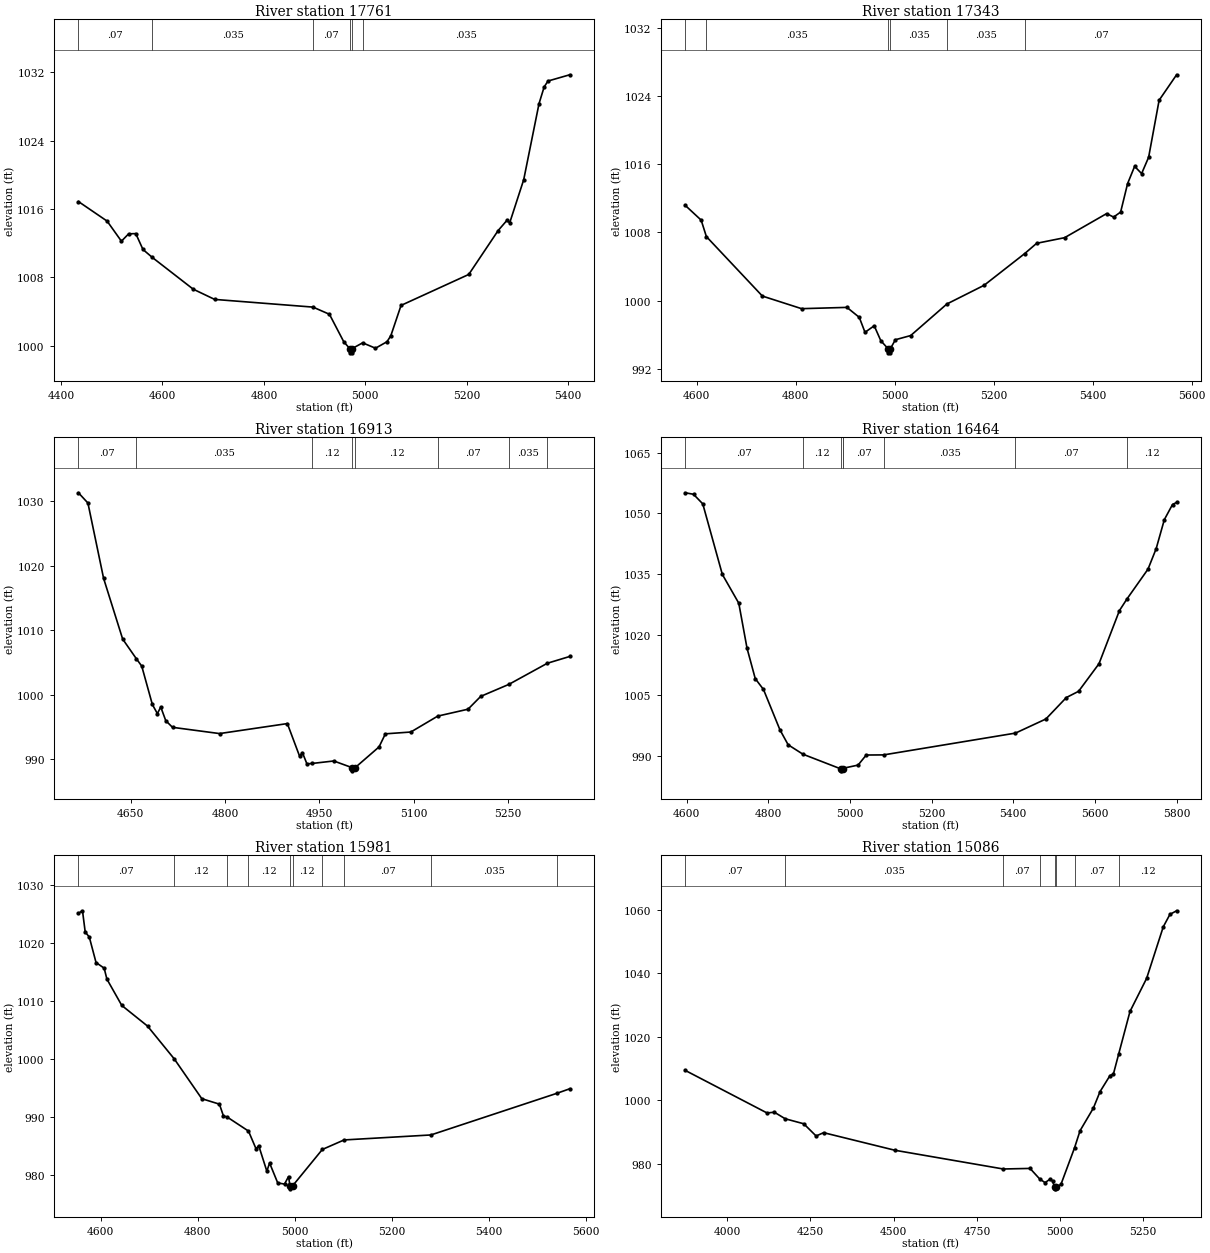
Type RM Length L Ch R = 1 ,17761   ,418,418,418
BEGIN DESCRIPTION:
Jentsch Creek 32.0
END DESCRIPTION:
XS GIS Cut Line= 3
      2184775.01     13861575.01        2185175.       13861975.
      2185575.02       13861925.
#Sta/Elev= 30
  4434.2 1016.88  4490.8 1014.59    4519 1012.24  4533.2  1013.1  4547.3 1013.13
  4561.5 1011.27  4579.7 1010.35  4660.5 1006.63  4702.9 1005.43  4896.8 1004.53
  4929.2 1003.69  4957.4 1000.48  4969.2  999.68  4969.5  999.18  4973.6  999.18
    4974  999.68  4994.7 1000.35    5020  999.72  5042.7 1000.48  5050.3 1001.19
  5070.4 1004.73  5203.9 1008.35  5261.9 1013.49  5279.5  1014.7  5284.6 1014.38
  5312.3 1019.44  5342.5 1028.34  5352.6 1030.29  5360.2 1030.98    5403 1031.71
#Mann= 6 ,-1 , 0
  4434.2     .07       0  4579.7    .035       0  4896.8     .07       0
  4969.2    .035       0    4974     .07       0  4994.7    .035       0
Bank Sta=4969.2,4974
XS Rating Curve= 0 ,0
Exp/Cntr=0.3,0.1

Type RM Length L Ch R = 1 ,17343   ,430,430,430
BEGIN DESCRIPTION:
Jentsch Creek 31.0
END DESCRIPTION:
XS GIS Cut Line= 3
      2184674.97     13862174.99        2185075.       13862325.
      2185474.99     13862724.99
#Sta/Elev= 30
  4576.7 1011.18  4608.8 1009.45  4619.3 1007.52  4732.5 1000.53  4811.7  999.05
  4903.4   999.2  4928.3  998.03  4939.9  996.27  4958.5  997.04  4971.9  995.28
  4986.3  994.36  4986.7  993.86    4991  993.86  4991.3  994.36  5001.3   995.4
  5032.2  995.89  5105.4   999.6  5180.7  1001.8  5262.8 1005.53  5286.8 1006.73
  5343.3 1007.39  5428.2 1010.22  5442.3 1009.81  5456.5  1010.4  5470.6 1013.75
  5484.8 1015.77  5498.9 1014.92  5513.1 1016.84  5534.3 1023.54  5569.6 1026.53
#Mann= 6 ,-1 , 0
  4576.7     .07       0  4619.3    .035       0  4986.3     .05       0
  4991.3    .035       0  5105.4    .035       0  5262.8     .07       0
Bank Sta=4986.3,4991.3
XS Rating Curve= 0 ,0
Exp/Cntr=0.3,0.1

Type RM Length L Ch R = 1 ,16913   ,449,449,449
BEGIN DESCRIPTION:
Jentsch Creek 30.0
END DESCRIPTION:
XS GIS Cut Line= 3
        2184525.       13862825.        2184925.       13862675.
      2185274.95     13862625.01
#Sta/Elev= 30
  4567.1 1031.35  4582.2 1029.76  4607.1 1018.08  4637.4 1008.66    4659 1005.63
  4667.7 1004.47  4684.6  998.51  4692.6  997.09  4697.9  998.13  4705.9     996
  4716.6  994.97  4791.4     994  4899.1  995.55  4918.6  990.48  4923.1  991.04
  4930.2   989.3  4938.9  989.37  4972.9  989.75  5001.8  988.72  5002.2  988.22
  5006.9  988.72  5044.8  991.93  5054.9  993.96  5095.3  994.24  5138.1  996.71
  5186.2  997.78  5206.4  999.77  5251.1 1001.63  5312.3 1004.91  5347.8 1005.96
#Mann= 8 ,-1 , 0
  4567.1     .07       0    4659    .035       0  4938.9     .12       0
  5001.8     .05       0  5006.9     .12       0  5138.1     .07       0
  5251.1    .035       0  5312.3     .07       0
Bank Sta=5001.8,5006.9
XS Rating Curve= 0 ,0
Exp/Cntr=0.3,0.1

Type RM Length L Ch R = 1 ,16464   ,483,483,483
BEGIN DESCRIPTION:
Jentsch Creek 29.0
END DESCRIPTION:
XS GIS Cut Line= 3
      2184375.01       13863025.        2184775.       13863075.
        2185575.       13863075.
#Sta/Elev= 30
  4596.9 1055.07    4617  1054.7  4639.7 1052.33  4687.6 1034.89  4727.9 1027.77
  4748.1 1016.63  4768.2 1009.13  4788.4 1006.44  4828.7  996.46  4848.8  992.77
    4885  990.44  4977.3  986.83  4977.6  986.33  4982.4  986.83    4984  986.98
    5020  987.75    5040  990.24  5082.6  990.27  5405.5  995.66    5480  999.15
    5530 1004.45    5560 1005.99    5610 1012.81    5660 1025.94  5678.4 1028.81
    5730 1036.19    5750 1041.26    5770 1048.43    5790 1052.17    5800 1052.69
#Mann= 8 ,-1 , 0
  4596.9     .07       0    4885     .12       0  4977.3     .05       0
  4982.4     .12       0    4984     .07       0  5082.6    .035       0
  5405.5     .07       0  5678.4     .12       0
Bank Sta=4977.3,4982.4
XS Rating Curve= 0 ,0
Exp/Cntr=0.3,0.1

Type RM Length L Ch R = 1 ,15981   ,895,895,895
BEGIN DESCRIPTION:
Jentsch Creek 28.0
END DESCRIPTION:
XS GIS Cut Line= 3
        2184375.       13863325.        2184775.       13863525.
        2185175.       13863125.
#Sta/Elev= 30
  4554.4 1025.04  4562.8 1025.47  4568.4 1021.81  4576.8 1020.95  4590.7 1016.55
  4607.5 1015.57  4613.1 1013.69  4643.8 1009.15  4696.9 1005.59    4752  999.93
  4808.8  993.07  4845.1  992.13  4853.5  990.07  4860.5  989.94    4905  987.49
  4920.6  984.43  4926.1  984.98  4942.9  980.57  4948.5  981.99  4965.3  978.55
  4979.3  978.35  4987.6  979.65  4990.6  978.03    4991  977.53  4995.8  978.03
  5057.3  984.32  5102.1  985.96  5281.1  986.82  5541.9  994.03  5567.3  994.78
#Mann= 10 ,-1 , 0
  4554.4     .07       0    4752     .12       0  4860.5     .12       0
    4905     .12       0  4990.6     .05       0  4995.8     .12       0
  5057.3     .12       0  5102.1     .07       0  5281.1    .035       0
  5541.9     .07       0
Bank Sta=4990.6,4995.8
XS Rating Curve= 0 ,0
Exp/Cntr=0.3,0.1

Type RM Length L Ch R = 1 ,15086   ,478,478,478
BEGIN DESCRIPTION:
Jentsch Creek 27.0
END DESCRIPTION:
XS GIS Cut Line= 3
      2184176.54     13863654.31        2185175.       13864175.
      2185525.03       13864175.
#Sta/Elev= 30
  3873.9 1009.42  4119.4  996.05  4141.5  996.28  4174.1  994.22  4229.8  992.65
  4266.9  988.81  4289.5  989.85  4503.7  984.32  4829.4  978.43  4909.7  978.61
  4938.8  975.28  4954.9  974.14  4969.7  975.23  4977.4  974.65  4983.5  972.69
  4983.9  972.19  4988.8  972.69  5002.5  973.57  5043.4  985.09    5060  990.48
    5100  997.58    5120 1002.75    5150 1007.82    5160 1008.22  5176.2 1014.66
    5210 1027.97    5260 1038.37    5310 1054.58    5330 1058.49    5350 1059.62
#Mann= 8 ,-1 , 0
  3873.9     .07       0  4174.1    .035       0  4829.4     .07       0
  4938.8     .12       0  4983.5     .05       0  4988.8     .12       0
  5043.4     .07       0  5176.2     .12       0
Bank Sta=4983.5,4988.8
XS Rating Curve= 0 ,0
Exp/Cntr=0.3,0.1

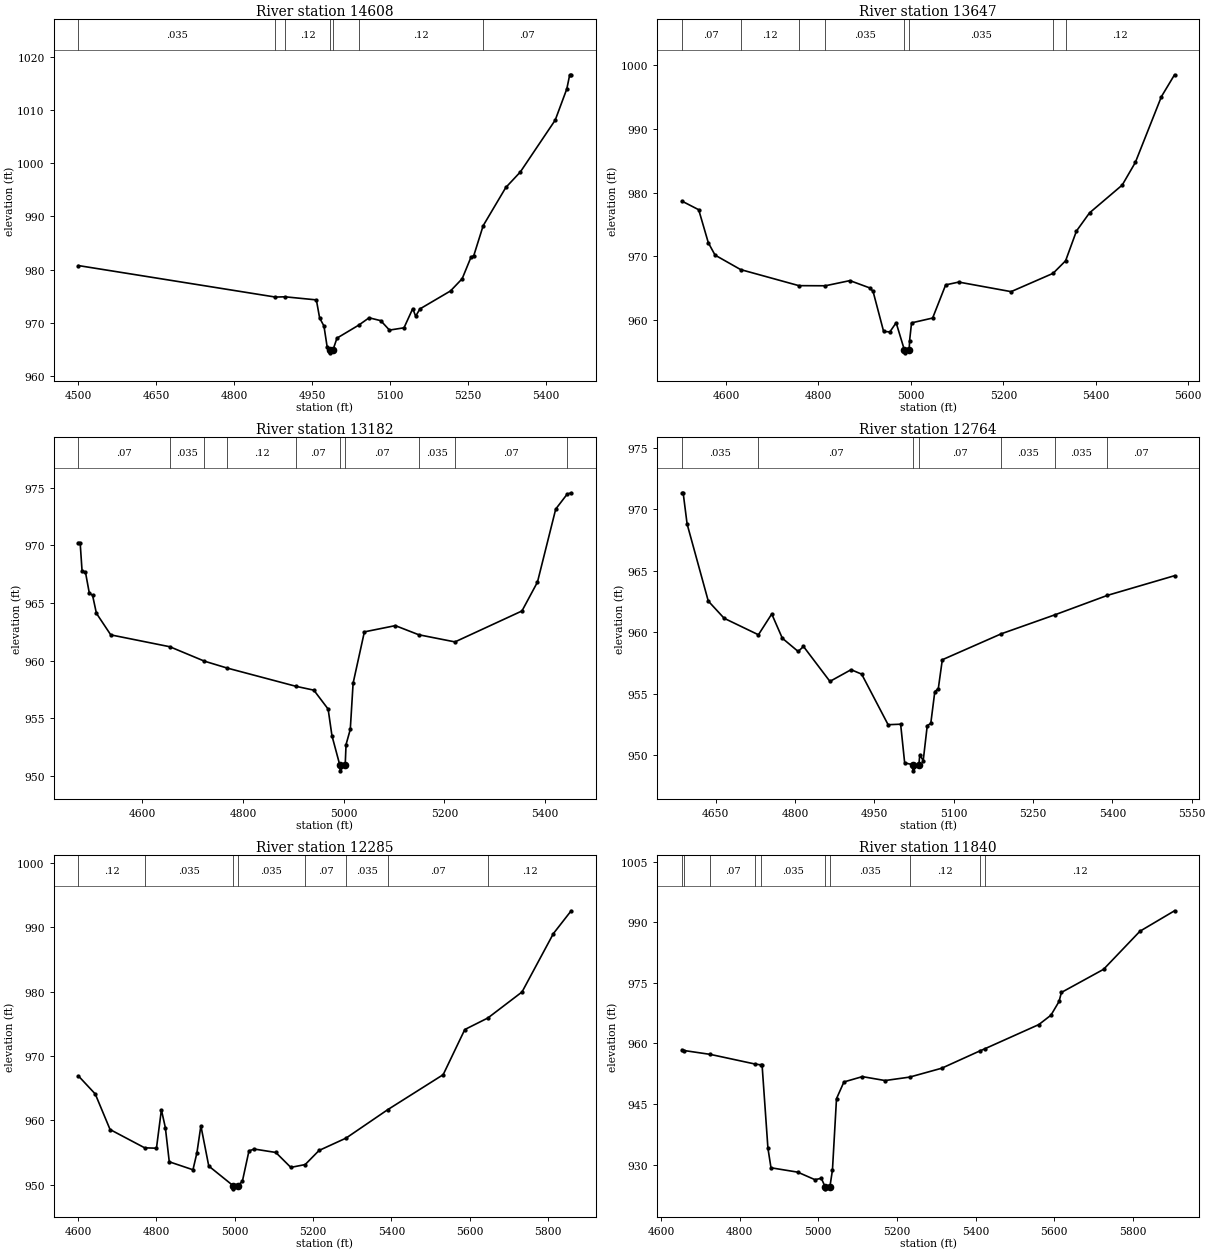
Type RM Length L Ch R = 1 ,14608   ,961,961,961
BEGIN DESCRIPTION:
Jentsch Creek 26.0
END DESCRIPTION:
XS GIS Cut Line= 3
      2184674.99     13864174.99        2184975.       13864575.
      2185374.97     13864375.01
#Sta/Elev= 30
  4500.7  980.77  4879.3  974.86  4897.7  974.91    4958  974.33  4964.3  970.93
  4972.6  969.43  4978.8  965.47  4984.5  964.89  4984.9  964.39  4989.8  964.89
  4997.6  967.15  5039.6   969.6  5059.4  970.97  5081.8  970.43  5098.5  968.66
  5126.5  969.09  5143.3  972.69  5148.9  971.27  5157.2  972.64  5215.9  976.01
  5238.3   978.3  5255.1   982.3  5260.7  982.66  5278.7  988.26  5322.2  995.43
  5350.1  998.34  5417.2 1008.08  5439.5 1013.94  5445.1 1016.59  5447.9 1016.59
#Mann= 7 ,-1 , 0
  4500.7    .035       0  4879.3     .12       0  4897.7     .12       0
  4984.5     .05       0  4989.8     .12       0  5039.6     .12       0
  5278.7     .07       0
Bank Sta=4984.5,4989.8
XS Rating Curve= 0 ,0
Exp/Cntr=0.3,0.1

Type RM Length L Ch R = 1 ,13647   ,465,465,465
BEGIN DESCRIPTION:
Jentsch Creek 25.0
END DESCRIPTION:
XS GIS Cut Line= 3
      2184874.98     13865725.02        2185275.       13865425.
      2185674.99     13865025.01
#Sta/Elev= 30
  4504.5  978.67    4541  977.31  4561.8  972.13  4576.4  970.19  4631.7  967.92
  4757.7   965.4  4814.9  965.38  4868.1  966.19  4910.8  965.05  4918.1  964.51
    4941  958.21  4954.5  958.15  4968.1  959.58  4985.7  955.36  4986.2  954.86
  4996.3  955.36  4997.2  956.79  5001.4  959.56    5047  960.32  5075.2  965.52
  5103.5  965.96  5216.7  964.46  5307.5  967.33  5334.6   969.3  5358.1  973.97
  5386.4  976.82  5457.1  981.18  5485.4  984.72  5541.9  995.06  5570.2  998.48
#Mann= 8 ,-1 , 0
  4504.5     .07       0  4631.7     .12       0  4757.7     .07       0
  4814.9    .035       0  4985.7    .035       0  4996.3    .035       0
  5307.5     .07       0  5334.6     .12       0
Bank Sta=4985.7,4996.3
XS Rating Curve= 0 ,0
Exp/Cntr=0.3,0.1

Type RM Length L Ch R = 1 ,13182   ,418,418,418
BEGIN DESCRIPTION:
Jentsch Creek 24.0
END DESCRIPTION:
XS GIS Cut Line= 3
      2185124.98     13866125.02        2185525.       13865775.
      2185724.98     13865375.04
#Sta/Elev= 30
  4473.1  970.23  4476.4  970.23  4480.2  967.77  4486.9  967.68  4494.5  965.88
  4501.1  965.66  4508.7  964.11  4537.2  962.24  4654.6  961.21  4723.4  959.96
    4768  959.37  4905.4  957.78  4940.6  957.45    4969  955.81  4976.6   953.5
  4992.2  950.96  4992.7  950.46  5002.9  950.96  5004.6  952.74    5013  954.05
  5018.6  958.05    5041   962.5  5102.5  963.04    5149  962.25  5220.9  961.63
    5354  964.31  5384.8  966.81  5421.1  973.14  5443.8  974.43  5451.8  974.55
#Mann= 10 ,-1 , 0
  4473.1     .07       0  4654.6    .035       0  4723.4     .07       0
    4768     .12       0  4905.4     .07       0  4992.2     .05       0
  5002.9     .07       0    5149    .035       0  5220.9     .07       0
  5443.8     .12       0
Bank Sta=4992.2,5002.9
XS Rating Curve= 0 ,0
Exp/Cntr=0.3,0.1

Type RM Length L Ch R = 1 ,12764   ,479,479,479
BEGIN DESCRIPTION:
Jentsch Creek 23.0
END DESCRIPTION:
XS GIS Cut Line= 3
      2185125.03       13866175.        2185525.       13866175.
      2185925.02     13865824.98
#Sta/Elev= 30
  4586.1  971.34  4588.6  971.34  4596.1   968.8  4636.1  962.54  4666.1  961.14
  4730.9   959.8  4756.1  961.49  4776.1  959.52  4806.1  958.44  4816.1  958.85
  4866.1  956.01  4906.1  956.96  4926.1   956.6  4976.1  952.49  4999.8  952.53
  5007.4  949.39  5022.3  949.24  5022.8  948.74  5034.3  949.24  5035.9  950.02
  5042.5  949.58  5050.1  952.41  5056.8   952.6  5064.4  955.18    5071  955.42
  5078.6  957.77  5190.2  959.88    5292  961.43  5390.6     963  5517.6   964.6
#Mann= 7 ,-1 , 0
  4586.1    .035       0  4730.9     .07       0  5022.3     .05       0
  5034.3     .07       0  5190.2    .035       0    5292    .035       0
  5390.6     .07       0
Bank Sta=5022.3,5034.3
XS Rating Curve= 0 ,0
Exp/Cntr=0.3,0.1

Type RM Length L Ch R = 1 ,12285   ,445,445,445
BEGIN DESCRIPTION:
Jentsch Creek 22.0
END DESCRIPTION:
XS GIS Cut Line= 3
      2185175.04     13866674.99        2185575.       13866625.
      2186375.03     13866324.99
#Sta/Elev= 30
  4601.5  966.88  4644.3  964.09  4682.1  958.57  4770.4  955.73  4800.5  955.67
  4813.1  961.63  4823.2  958.87  4833.2  953.56  4893.7  952.32  4903.8  954.97
  4913.9  959.15    4934   952.9    4996  949.86  4996.5  949.36    5008  949.86
  5019.7  950.51  5036.6  955.25    5050  955.54  5105.1  955.01  5143.4  952.69
  5180.1  953.13  5215.5  955.32  5284.4  957.24  5390.9  961.66  5532.3  967.09
  5587.5   974.1  5646.3  975.89  5733.5  979.93  5813.6     989    5859  992.54
#Mann= 8 ,-1 , 0
  4601.5     .12       0  4770.4    .035       0    4996    .035       0
    5008    .035       0  5180.1     .07       0  5284.4    .035       0
  5390.9     .07       0  5646.3     .12       0
Bank Sta=4996,5008
XS Rating Curve= 0 ,0
Exp/Cntr=0.3,0.1

Type RM Length L Ch R = 1 ,11840   ,467,467,467
BEGIN DESCRIPTION:
Jentsch Creek 21.0
END DESCRIPTION:
XS GIS Cut Line= 3
      2185265.98     13867044.05        2185575.       13866875.
      2186450.38     13866662.23
#Sta/Elev= 30
  4652.8  958.41  4658.9  958.22  4725.4  957.27  4839.7  954.87  4853.1  954.69
  4856.9  954.68  4871.8  934.05  4879.6  929.21  4947.6  928.13  4991.3  926.27
  5007.6  926.61  5017.3   924.5  5017.8     924  5029.4   924.5  5035.9  928.64
  5046.2  946.32  5065.1  950.45    5112  951.77  5169.7   950.8  5232.2  951.65
  5313.8  953.85  5411.7  958.17  5423.2  958.65  5560.8  964.65  5591.6  966.97
  5612.2  970.36  5618.2   972.6  5725.4  978.32    5818  987.75  5905.9  992.81
#Mann= 10 ,-1 , 0
  4652.8     .07       0  4658.9     .12       0  4725.4     .07       0
  4839.7     .12       0  4853.1    .035       0  5017.3    .035       0
  5029.4    .035       0  5232.2     .12       0  5411.7     .07       0
  5423.2     .12       0
Bank Sta=5017.3,5029.4
XS Rating Curve= 0 ,0
Exp/Cntr=0.3,0.1

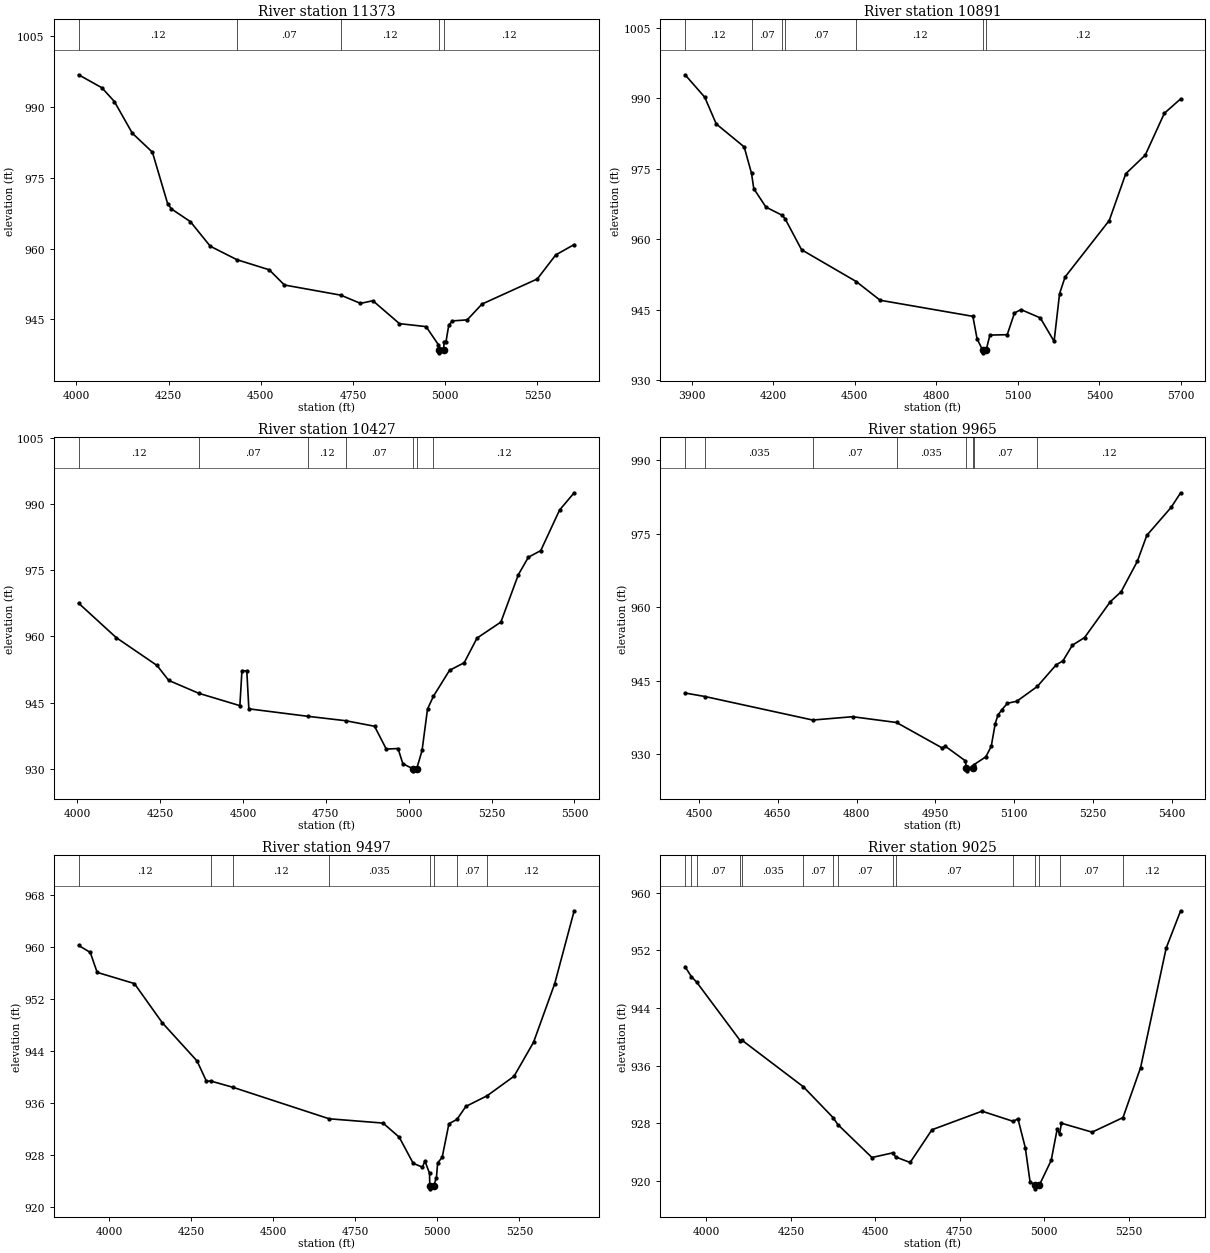
Type RM Length L Ch R = 1 ,11373   ,482,482,482
BEGIN DESCRIPTION:
Jentsch Creek 20.0
END DESCRIPTION:
XS GIS Cut Line= 3
        2184811.     13867034.17        2185775.       13867275.
      2186124.98       13867275.
#Sta/Elev= 30
  4005.9  996.78    4069  994.03  4102.8  991.12  4151.4  984.42  4205.9   980.4
  4247.1  969.53  4257.4  968.39  4308.9  965.69  4362.8  960.49    4435  957.64
  4522.6   955.5  4563.9  952.28  4716.7  950.13  4770.1  948.39  4803.7  948.95
  4875.8   944.1    4948  943.47  4981.5  939.62  4983.1  938.42  4983.6  937.92
  4995.3  938.42  4996.9   940.3    5002   940.3  5009.5  943.79  5019.5  944.68
  5059.5   944.9  5099.5  948.24  5249.5  953.56  5299.5  958.65  5349.5  960.84
#Mann= 5 ,-1 , 0
  4005.9     .12       0    4435     .07       0  4716.7     .12       0
  4983.1     .05       0  4995.3     .12       0
Bank Sta=4983.1,4995.3
XS Rating Curve= 0 ,0
Exp/Cntr=0.3,0.1

Type RM Length L Ch R = 1 ,10891   ,464,464,464
BEGIN DESCRIPTION:
Jentsch Creek 19.0
END DESCRIPTION:
XS GIS Cut Line= 3
      2184720.46     13867130.89        2185675.       13867725.
        2186364.     13867842.67
#Sta/Elev= 30
  3875.7  994.98  3947.8  990.22  3990.3  984.52  4093.1  979.63  4120.1     974
  4128.4  970.75  4173.2  966.82    4234  965.05  4244.3  964.28  4304.2  957.75
  4505.1  950.99  4593.4     947  4934.5  943.58  4949.9  938.83  4970.9  936.31
  4971.4  935.81  4983.1  936.31  4997.1  939.59  5060.9  939.67  5087.7   944.3
  5111.6  945.01  5182.6  943.25  5233.4  938.25  5253.6  948.42  5273.9  951.96
  5436.3  963.97  5497.1  973.92  5568.8  977.89  5639.1  986.79    5699  989.85
#Mann= 7 ,-1 , 0
  3875.7     .12       0  4120.1     .07       0    4234     .12       0
  4244.3     .07       0  4505.1     .12       0  4970.9     .05       0
  4983.1     .12       0
Bank Sta=4970.9,4983.1
XS Rating Curve= 0 ,0
Exp/Cntr=0.3,0.1

Type RM Length L Ch R = 1 ,10427   ,462,462,462
BEGIN DESCRIPTION:
Jentsch Creek 18.0
END DESCRIPTION:
XS GIS Cut Line= 3
      2184825.03     13867575.02        2185625.       13868175.
      2186064.53     13868402.56
#Sta/Elev= 30
  4004.3  967.51  4117.8  959.72  4240.7  953.43  4276.1  950.04    4367  947.12
  4490.7  944.33    4497  952.26  4511.6  952.18  4517.8  943.61  4695.7  941.92
    4810  940.92    4897  939.67  4932.4   934.5  4967.8  934.63  4982.4  931.19
    5012  930.08  5012.5  929.58  5024.3  930.08  5040.3  934.19  5056.8  943.56
  5074.8  946.49  5123.2  952.32  5167.5  954.05  5206.1  959.62  5278.1  963.24
  5330.8  973.97  5361.1  977.92  5398.4  979.42  5455.2   988.6  5499.2   992.5
#Mann= 7 ,-1 , 0
  4004.3     .12       0    4367     .07       0  4695.7     .12       0
    4810     .07       0    5012     .05       0  5024.3     .07       0
  5074.8     .12       0
Bank Sta=5012,5024.3
XS Rating Curve= 0 ,0
Exp/Cntr=0.3,0.1

Type RM Length L Ch R = 1 ,9965    ,468,468,468
BEGIN DESCRIPTION:
Jentsch Creek 17.0
END DESCRIPTION:
XS GIS Cut Line= 3
      2185025.03     13868225.03        2185425.       13868575.
      2185825.02     13868675.01
#Sta/Elev= 30
  4473.4   942.5  4511.4  941.78  4716.5  936.98  4792.3  937.66  4876.1  936.48
  4962.6  931.31  4969.3  931.61  5007.4  928.64    5009  927.11  5009.5  926.61
  5021.3  927.11  5022.9  927.82  5046.1  929.47  5056.4  931.58  5064.1  936.27
  5069.3     938    5077  939.12  5087.3   940.4  5105.4  940.83  5144.1  943.83
  5180.1  948.25    5193  949.06    5211  952.26  5234.2  953.82  5283.2  961.13
  5303.8  963.17  5334.7  969.38  5352.8  974.69  5399.1   980.4  5417.2  983.38
#Mann= 8 ,-1 , 0
  4473.4     .07       0  4511.4    .035       0  4716.5     .07       0
  4876.1    .035       0    5009    .035       0  5021.3    .035       0
  5022.9     .07       0  5144.1     .12       0
Bank Sta=5009,5021.3
XS Rating Curve= 0 ,0
Exp/Cntr=0.3,0.1

Type RM Length L Ch R = 1 ,9497    ,472,472,472
BEGIN DESCRIPTION:
Jentsch Creek 16.0
END DESCRIPTION:
XS GIS Cut Line= 3
      2184424.99     13868224.99        2185225.       13868975.
      2185624.99       13869075.
#Sta/Elev= 30
  3907.7  960.31  3943.1  959.23  3964.1  956.16  4077.5  954.44  4162.4  948.41
  4268.4  942.52  4296.8  939.41    4310  939.44  4377.9  938.47  4670.5  933.63
  4834.6  932.97  4883.9   930.8  4926.4  926.78  4954.7  926.18    4962  927.15
  4976.2  925.23  4976.9  923.35  4977.4  922.85  4989.2  923.35  4997.2  924.57
  5000.9  926.86  5014.6  927.68  5035.2  932.86  5059.7  933.54  5086.8  935.53
  5151.4  937.17  5233.6  940.18  5292.9  945.41  5357.3  954.42  5416.6  965.64
#Mann= 8 ,-1 , 0
  3907.7     .12       0    4310     .07       0  4377.9     .12       0
  4670.5    .035       0  4976.9    .035       0  4989.2    .035       0
  5059.7     .07       0  5151.4     .12       0
Bank Sta=4976.9,4989.2
XS Rating Curve= 0 ,0
Exp/Cntr=0.3,0.1

Type RM Length L Ch R = 1 ,9025    ,452,452,452
BEGIN DESCRIPTION:
Jentsch Creek 15.0
END DESCRIPTION:
XS GIS Cut Line= 3
      2184325.03     13870074.97        2185125.       13869375.
      2185525.02       13869425.
#Sta/Elev= 30
  3937.1  949.72  3955.6  948.35  3971.2  947.59  4100.1  939.47  4105.7  939.51
  4286.7  933.07  4374.7  928.79  4388.9  927.82  4489.9  923.24  4551.8  923.89
  4559.9  923.32  4602.9  922.55  4667.4  927.09  4815.5  929.67  4907.7  928.26
  4921.8  928.62  4943.6   924.6  4957.8  919.84  4972.4  919.39  4972.9  918.89
    4985  919.39  5020.2  922.84  5037.9  927.17  5045.1  926.49  5050.5     928
  5141.2  926.76  5232.6  928.78  5284.8  935.73  5360.4  952.31  5403.2  957.49
#Mann= 15 ,-1 , 0
  3937.1     .07       0  3955.6     .12       0  3971.2     .07       0
  4100.1     .12       0  4105.7    .035       0  4286.7     .07       0
  4374.7    .035       0  4388.9     .07       0  4551.8    .035       0
  4559.9     .07       0  4907.7    .035       0  4972.4    .035       0
    4985    .035       0  5045.1     .07       0  5232.6     .12       0
Bank Sta=4972.4,4985
XS Rating Curve= 0 ,0
Exp/Cntr=0.3,0.1