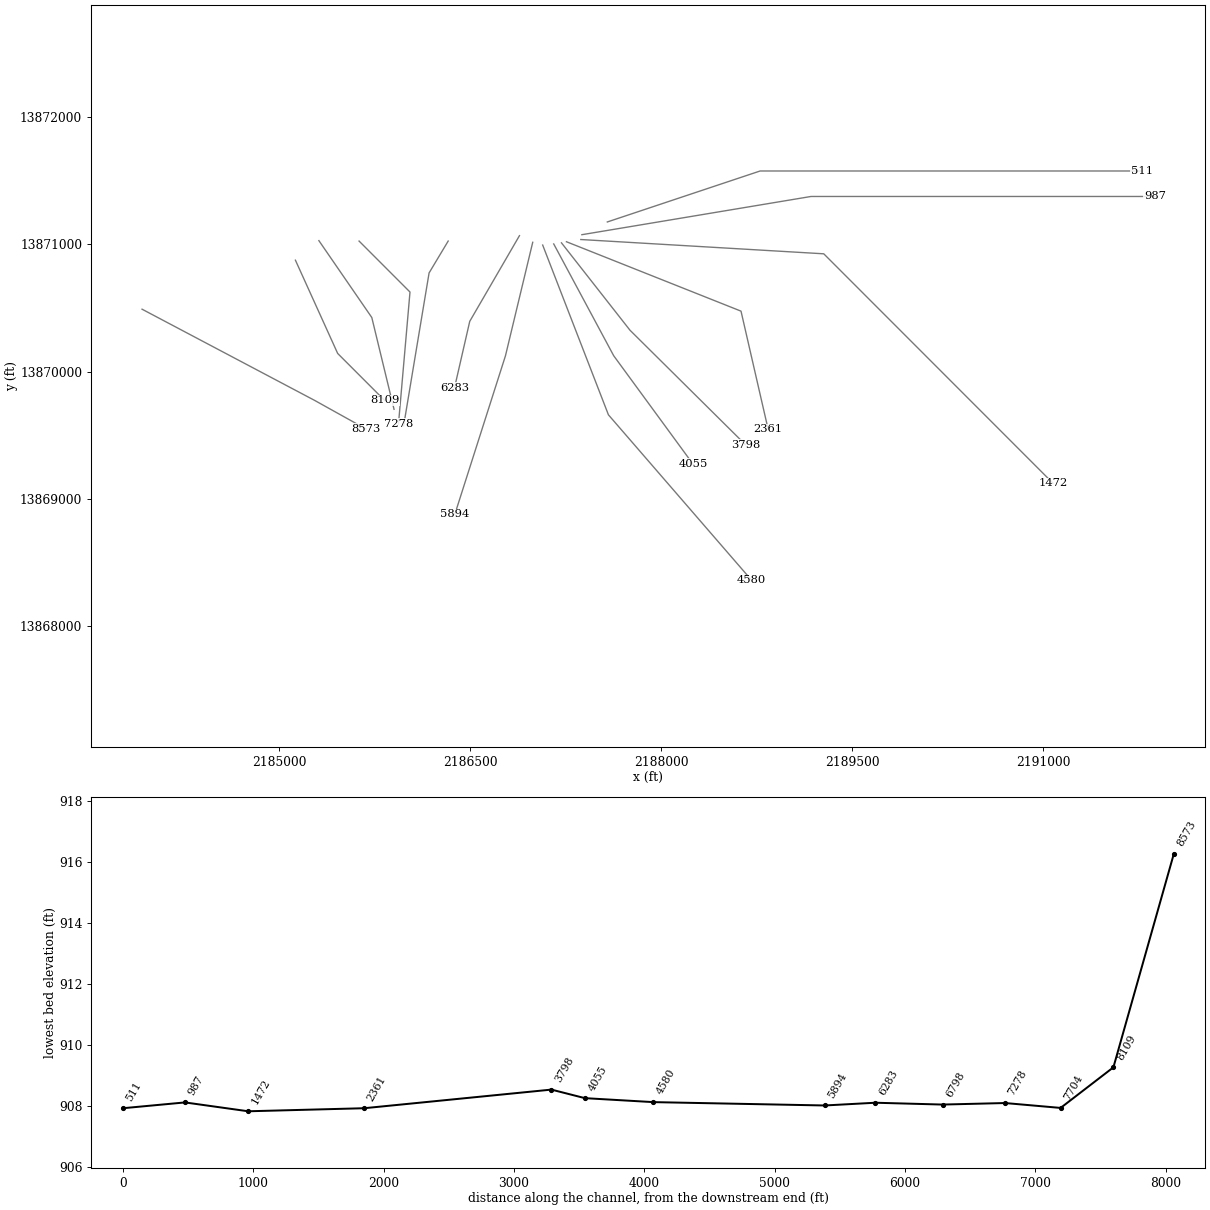
HEC-RAS study Jentsch Creek.prj: Jentsch Creek Base Level Engineering

--- Jentsch Creek.g01 (geometry) --- (continued)

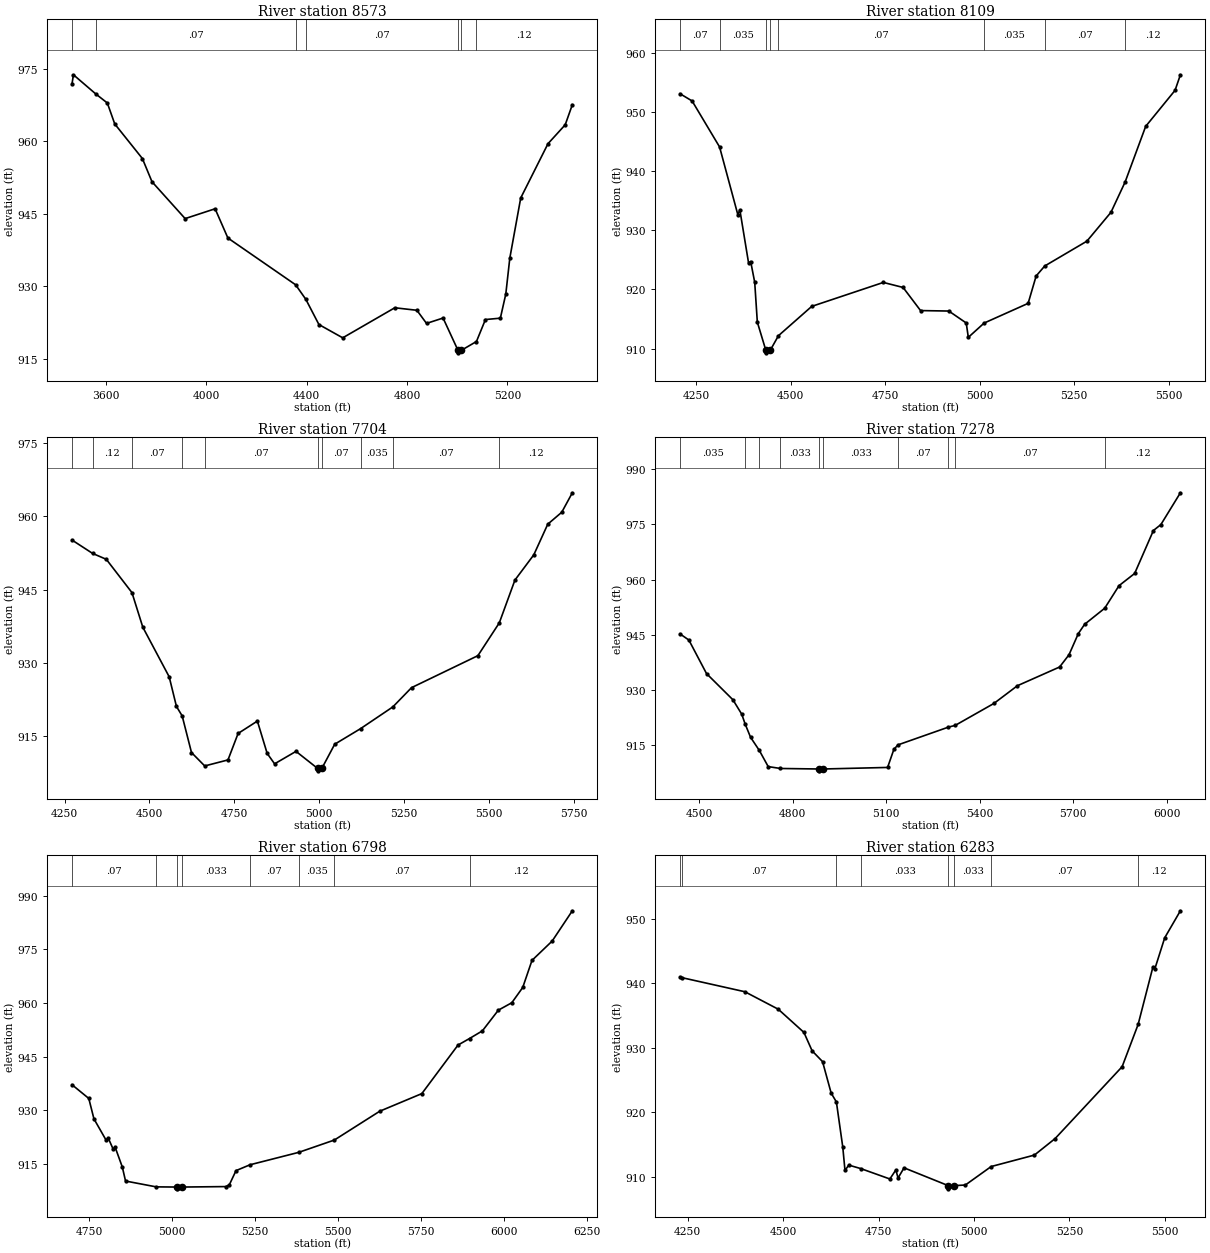
Type RM Length L Ch R = 1 ,8573    ,464,464,464
BEGIN DESCRIPTION:
Jentsch Creek 14.0
END DESCRIPTION:
XS GIS Cut Line= 3
      2183920.43     13870490.26        2185275.       13869775.
      2185679.83     13869549.95
#Sta/Elev= 30
  3464.2  971.82  3469.9  973.72  3558.6  969.78  3605.1  967.89  3634.7  963.56
  3744.8  956.42  3783.2  951.62  3915.3  944.01  4034.8  946.04  4085.8     940
  4355.8  930.34  4396.5  927.34  4448.7  922.13  4543.7  919.38  4751.3  925.59
  4839.4  925.07  4877.8  922.36  4943.8  923.47  5003.4  916.78  5003.9  916.28
    5016  916.78  5076.9  918.62  5112.7  923.16  5172.2  923.44  5193.9  928.43
  5209.9  935.85  5253.4  948.27  5362.1  959.48  5430.8  963.39  5459.2  967.54
#Mann= 7 ,-1 , 0
  3464.2     .12       0  3558.6     .07       0  4355.8    .035       0
  4396.5     .07       0  5003.4     .05       0    5016     .07       0
  5076.9     .12       0
Bank Sta=5003.4,5016
XS Rating Curve= 0 ,0
Exp/Cntr=0.3,0.1

Type RM Length L Ch R = 1 ,8109    ,405,405,405
BEGIN DESCRIPTION:
Jentsch Creek 13.0
END DESCRIPTION:
XS GIS Cut Line= 3
      2185125.01     13870874.99      2185456.92     13870143.02
      2185824.99     13869775.01
#Sta/Elev= 30
  4207.2  953.11  4239.1  951.89  4311.8  944.11    4360  932.68  4365.5  933.45
  4388.6  924.45  4394.1  924.73  4404.8  921.21  4411.7  914.48  4433.9  909.78
  4434.4  909.28  4446.5  909.78  4467.6  912.18  4555.7  917.14  4745.2  921.19
  4797.5  920.34  4843.7  916.43  4918.5  916.35  4964.6  914.33  4970.1   911.9
    5012  914.32  5128.4  917.65  5149.6  922.28  5172.3  923.97  5283.9  928.17
  5347.6  933.05  5385.1  938.18  5439.5  947.59  5517.3  953.69  5531.4  956.32
#Mann= 8 ,-1 , 0
  4207.2     .07       0  4311.8    .035       0  4433.9     .05       0
  4446.5    .035       0  4467.6     .07       0    5012    .035       0
  5172.3     .07       0  5385.1     .12       0
Bank Sta=4433.9,4446.5
XS Rating Curve= 0 ,0
Exp/Cntr=0.3,0.1

Type RM Length L Ch R = 1 ,7704    ,426,426,426
BEGIN DESCRIPTION:
Jentsch Creek 12.0
END DESCRIPTION:
XS GIS Cut Line= 3
      2185309.37     13871028.41        2185725.       13870425.
      2185899.62     13869704.67
#Sta/Elev= 30
    4272  955.12  4332.6  952.39  4373.1  951.18  4448.6  944.38  4480.6  937.31
  4558.3  927.17  4579.7  921.11  4596.5  919.19    4624  911.69    4663  908.95
  4731.5  910.18  4761.3  915.59  4818.1  918.12  4846.9  911.52  4868.8  909.38
  4931.9  911.93  4995.4  908.45  4995.9  907.95    5008  908.45  5045.9  913.39
    5122  916.57  5217.2  921.02  5272.2  924.95  5467.7  931.49  5530.8   938.2
  5576.8  946.94  5632.4   952.1  5673.5  958.36  5714.7   960.8  5745.9  964.78
#Mann= 10 ,-1 , 0
    4272     .07       0  4332.6     .12       0  4448.6     .07       0
  4596.5    .035       0    4663     .07       0  4995.4     .05       0
    5008     .07       0    5122    .035       0  5217.2     .07       0
  5530.8     .12       0
Bank Sta=4995.4,5008
XS Rating Curve= 0 ,0
Exp/Cntr=0.3,0.1

Type RM Length L Ch R = 1 ,7278    ,480,480,480
BEGIN DESCRIPTION:
Jentsch Creek 11.0
END DESCRIPTION:
XS GIS Cut Line= 3
      2185624.97     13871025.03        2186025.       13870625.
      2185934.46     13869588.77
#Sta/Elev= 30
  4438.4  945.24  4466.7  943.58  4523.3  934.49  4608.1  927.38  4636.4  923.47
  4647.1  920.85  4664.7  917.21  4692.8  913.64  4721.3  909.26  4760.7  908.75
  4884.7  908.61  4885.2  908.11  4897.3  908.61  5104.5  909.03  5124.6  913.92
  5137.8  915.15  5299.9  919.97  5321.6  920.44  5445.8  926.39  5521.1  931.19
  5656.6  936.27  5686.7  939.58  5716.8  945.35  5736.9  947.85  5801.4  952.21
  5847.3  958.33  5897.5  961.64  5957.7  973.29  5981.7   974.9  6044.3  983.52
#Mann= 10 ,-1 , 0
  4438.4    .035       0  4647.1     .07       0  4692.8    .035       0
  4760.7    .033       0  4884.7    .033       0  4897.3    .033       0
  5137.8     .07       0  5299.9    .035       0  5321.6     .07       0
  5801.4     .12       0
Bank Sta=4884.7,4897.3
XS Rating Curve= 0 ,0
Exp/Cntr=0.3,0.1

Type RM Length L Ch R = 1 ,6798    ,515,515,515
BEGIN DESCRIPTION:
Jentsch Creek 10.0
END DESCRIPTION:
XS GIS Cut Line= 3
      2186325.02     13871025.04        2186175.       13870775.
      2185975.01     13869575.04
#Sta/Elev= 30
  4698.2  937.15  4748.8  933.32  4764.3  927.62  4801.3  921.61  4807.1  922.31
  4822.6  919.08  4828.5  919.63  4849.8  914.17  4859.6  910.24    4952  908.61
  5015.1  908.56  5015.6  908.06  5030.3  908.56  5162.1  908.69  5172.3  909.16
  5192.6  913.15  5234.7  914.78  5381.9  918.26  5489.1   921.7  5625.9  929.75
  5752.7  934.67  5861.7  948.23  5896.4  950.06  5935.2   952.2  5983.3  957.98
  6023.9  960.06  6056.8  964.32  6084.7  971.89  6145.5  977.29  6206.3  985.75
#Mann= 8 ,-1 , 0
  4698.2     .07       0    4952    .033       0  5015.1    .033       0
  5030.3    .033       0  5234.7     .07       0  5381.9    .035       0
  5489.1     .07       0  5896.4     .12       0
Bank Sta=5015.1,5030.3
XS Rating Curve= 0 ,0
Exp/Cntr=0.3,0.1

Type RM Length L Ch R = 1 ,6283    ,389,389,389
BEGIN DESCRIPTION:
Jentsch Creek 9.0
END DESCRIPTION:
XS GIS Cut Line= 3
      2186884.86     13871067.49      2186494.24     13870394.76
        2186375.     13869874.98
#Sta/Elev= 30
  4229.8  940.98    4235  940.88  4399.6   938.7  4487.1  935.99  4554.4  932.39
  4575.9  929.53  4603.2  927.86  4625.8  922.97  4639.5   921.6  4656.2  914.61
    4662  910.98    4672   911.8  4703.5  911.26  4779.6  909.65  4795.3  911.05
  4801.1   909.8  4816.8  911.38  4932.5  908.62    4933  908.12  4947.8  908.62
  4977.4  908.71  5045.1  911.58  5158.5  913.36  5212.7  915.92  5388.3  927.07
  5430.2  933.62    5469  942.54  5474.1  942.26  5499.9  947.07    5541  951.26
#Mann= 8 ,-1 , 0
  4229.8     .12       0    4235     .07       0  4639.5     .12       0
  4703.5    .033       0  4932.5    .033       0  4947.8    .033       0
  5045.1     .07       0  5430.2     .12       0
Bank Sta=4932.5,4947.8
XS Rating Curve= 0 ,0
Exp/Cntr=0.3,0.1

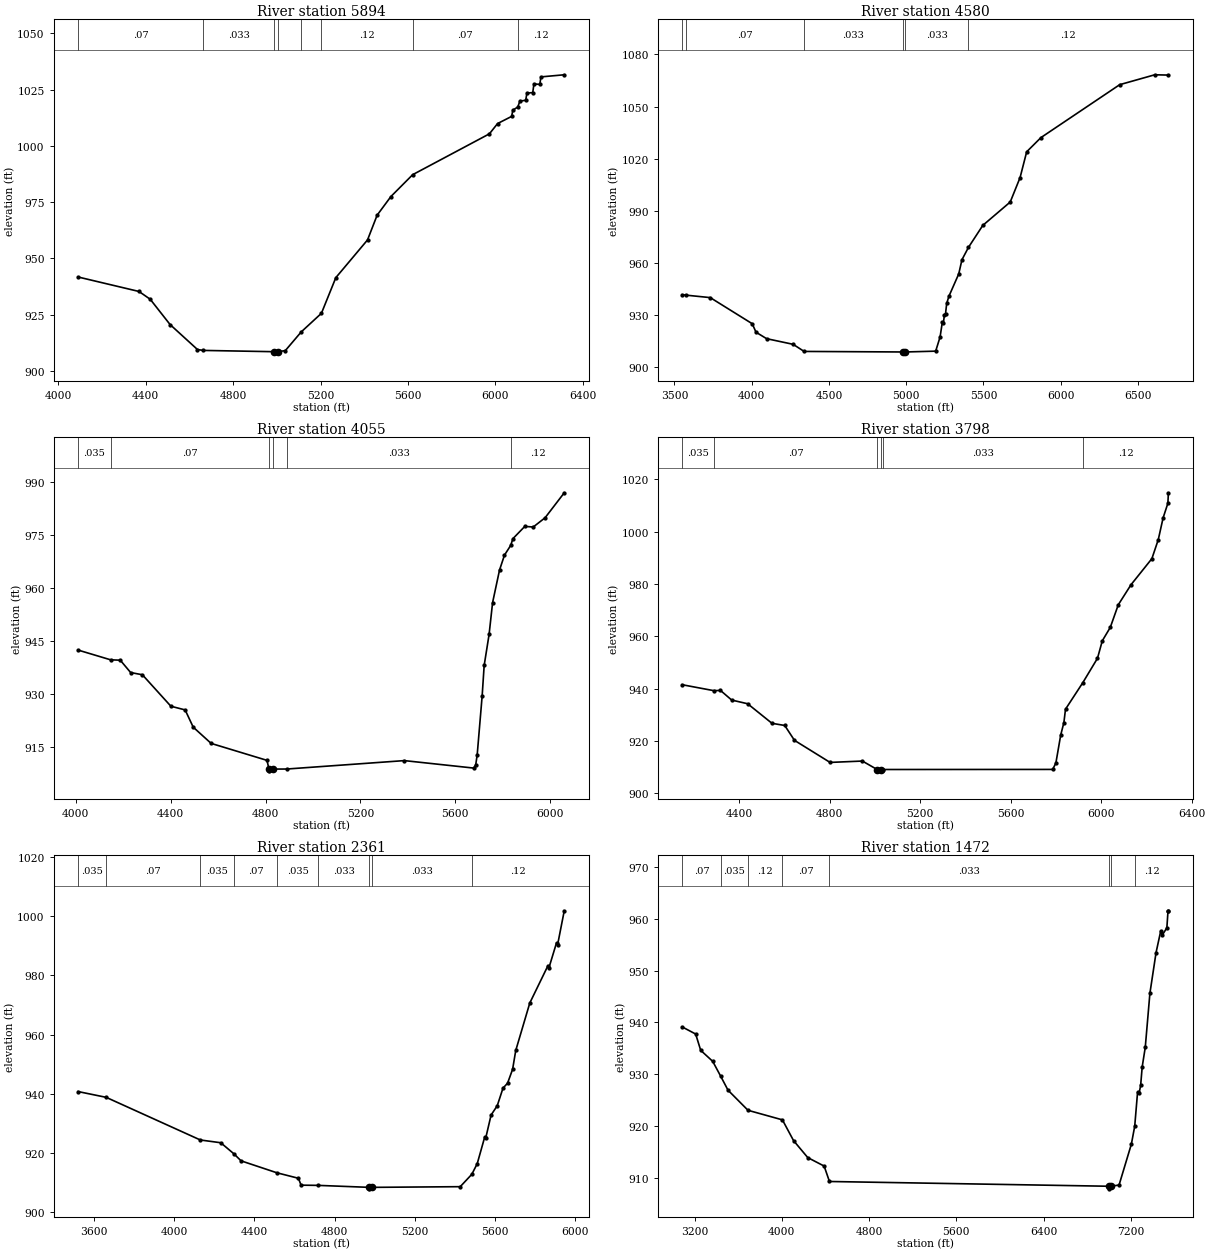
Type RM Length L Ch R = 1 ,5894    ,1314,1314,1314
BEGIN DESCRIPTION:
Jentsch Creek 8.0
END DESCRIPTION:
XS GIS Cut Line= 3
      2186989.03     13871015.42        2186775.       13870125.
      2186377.06     13868880.03
#Sta/Elev= 30
  4091.8  941.72  4369.9   935.3  4421.3  931.84  4512.2  920.59  4637.3  909.51
  4662.8  909.11  4989.6  908.53  4990.1  908.03  5004.9  908.53  5039.1  909.02
  5111.9  917.33  5204.2   925.6    5270  941.43    5415   958.2    5459  969.21
    5522  977.49  5621.3  987.18  5972.3 1005.34  6009.8 1009.91  6074.1 1013.09
  6079.4 1015.86  6102.2 1017.27  6111.5 1019.87  6138.4 1020.26  6143.7 1023.38
  6170.6  1023.7  6175.9 1027.51  6202.8 1027.31    6208 1030.64  6314.6 1031.58
#Mann= 8 ,-1 , 0
  4091.8     .07       0  4662.8    .033       0  4989.6    .033       0
  5004.9    .033       0  5111.9     .07       0  5204.2     .12       0
  5621.3     .07       0  6102.2     .12       0
Bank Sta=4989.6,5004.9
XS Rating Curve= 0 ,0
Exp/Cntr=0.3,0.1

Type RM Length L Ch R = 1 ,4580    ,525,525,525
BEGIN DESCRIPTION:
Jentsch Creek 7.0
END DESCRIPTION:
XS GIS Cut Line= 3
      2187067.17     13870993.69      2187583.65     13869661.25
      2188707.75     13868363.55
#Sta/Elev= 30
  3551.1  941.59    3577  941.35    3732  939.95  4003.6  924.91  4028.1  920.02
  4096.7   916.3  4268.3  913.05  4339.5  908.95  4977.9  908.64  4978.4  908.14
  4993.7  908.64  5190.9  909.11  5219.4  917.29  5233.7  925.66  5240.3  925.12
  5247.9  930.22  5254.5   930.6  5262.2  936.56  5276.4   940.7  5340.1  953.58
  5360.9  961.76  5403.1  968.89  5495.8  981.54  5673.4  995.01  5737.1 1009.09
  5779.8 1023.93  5871.9  1032.1  6381.9 1062.59  6608.9 1068.29    6697 1068.11
#Mann= 6 ,-1 , 0
  3551.1    .035       0    3577     .07       0  4339.5    .033       0
  4977.9    .033       0  4993.7    .033       0  5403.1     .12       0
Bank Sta=4977.9,4993.7
XS Rating Curve= 0 ,0
Exp/Cntr=0.3,0.1

Type RM Length L Ch R = 1 ,4055    ,257,257,257
BEGIN DESCRIPTION:
Jentsch Creek 6.0
END DESCRIPTION:
XS GIS Cut Line= 3
      2187153.94     13871002.44        2187625.       13870125.
      2188247.71     13869274.98
#Sta/Elev= 30
  4009.8  942.38  4146.8  939.63  4187.3  939.53  4231.1  936.04  4280.6  935.41
  4400.8  926.52  4460.9  925.48  4494.9  920.61  4570.5  916.02    4806  911.23
  4814.3  908.77  4814.8  908.27  4830.1  908.77  4888.9  908.78  5385.1  911.16
  5677.7  909.05  5686.1  909.97  5692.3  912.79  5713.2  929.42  5721.7  938.03
  5742.5  946.81  5757.2  955.79  5786.5     965  5807.3   969.2  5833.7  971.97
  5842.9  973.86    5893  977.32  5928.6  977.15  5978.7  979.77  6059.4  986.82
#Mann= 6 ,-1 , 0
  4009.8    .035       0  4146.8     .07       0  4814.3    .033       0
  4830.1     .07       0  4888.9    .033       0  5833.7     .12       0
Bank Sta=4814.3,4830.1
XS Rating Curve= 0 ,0
Exp/Cntr=0.3,0.1

Type RM Length L Ch R = 1 ,3798    ,1437,1437,1437
BEGIN DESCRIPTION:
Jentsch Creek 5.0
END DESCRIPTION:
XS GIS Cut Line= 3
      2187214.72     13871011.09      2187752.92     13870325.32
      2188660.05     13869426.87
#Sta/Elev= 30
  4148.4  941.45  4287.9  939.19    4317  939.29  4366.7   935.6  4437.2  934.19
  4544.8  926.71  4601.1  925.89  4644.2   920.2  4801.5  911.77  4944.3  912.29
  5009.8  909.05  5010.3  908.55  5025.7  909.05    5037  909.06  5785.5  909.09
  5799.6  911.55  5820.9  922.21    5835  927.02  5842.1  932.11  5918.5  942.23
  5983.5  951.58  6004.7  958.24  6040.1  963.39  6075.5  972.04    6132  979.72
  6223.9  989.64  6252.2  996.93  6273.5 1005.22  6294.6 1010.81  6296.9 1014.82
#Mann= 6 ,-1 , 0
  4148.4    .035       0  4287.9     .07       0  5009.8     .05       0
  5025.7     .07       0    5037    .033       0  5918.5     .12       0
Bank Sta=5009.8,5025.7
XS Rating Curve= 0 ,0
Exp/Cntr=0.3,0.1

Type RM Length L Ch R = 1 ,2361    ,889,889,889
BEGIN DESCRIPTION:
Jentsch Creek 4.0
END DESCRIPTION:
XS GIS Cut Line= 3
      2187253.81     13871019.75        2188625.       13870475.
      2188837.81     13869549.18
#Sta/Elev= 30
  3520.9  940.77  3660.5  938.83  4130.6  924.43  4232.4   923.5  4298.2  919.75
  4333.7  917.39  4512.9  913.35  4619.7  911.51  4633.3  909.18  4717.8  909.11
  4973.5  908.44    4974  907.94  4989.5  908.44  5427.3  908.67  5485.1  912.85
  5512.1  916.44  5549.8  925.52  5554.9  925.21  5581.2  932.85    5612     936
  5640.6  941.93  5663.3  943.59  5688.6  948.29  5704.3  954.65  5774.3  970.66
  5865.1  983.29  5870.2  982.63  5907.9  991.03    5913   990.3  5946.3  1001.8
#Mann= 9 ,-1 , 0
  3520.9    .035       0  3660.5     .07       0  4130.6    .035       0
  4298.2     .07       0  4512.9    .035       0  4717.8    .033       0
  4973.5    .033       0  4989.5    .033       0  5485.1     .12       0
Bank Sta=4973.5,4989.5
XS Rating Curve= 0 ,0
Exp/Cntr=0.3,0.1

Type RM Length L Ch R = 1 ,1472    ,485,485,485
BEGIN DESCRIPTION:
Jentsch Creek 3.0
END DESCRIPTION:
XS GIS Cut Line= 3
      2187366.64     13871037.12        2189275.       13870925.
      2191074.97     13869125.03
#Sta/Elev= 30
  3087.6  939.12  3210.1  937.76  3256.3  934.61  3366.4  932.48  3439.5  929.61
  3506.7  926.91  3690.1  923.02  4005.6  921.17  4107.7  917.16  4237.9  913.88
  4388.2  912.24  4436.8  909.26  6999.2  908.34  6999.7  907.84  7015.7  908.34
  7092.3  908.57  7205.4  916.49    7236  919.95    7262   926.5  7276.1  926.32
  7290.3  927.82  7304.4  931.39  7332.7  935.19  7375.1  945.62  7431.7  953.51
  7474.1  957.64  7488.3  956.87  7530.7  958.28  7541.3  961.58  7544.8  961.58
#Mann= 8 ,-1 , 0
  3087.6     .07       0  3439.5    .035       0  3690.1     .12       0
  4005.6     .07       0  4436.8    .033       0  6999.2    .033       0
  7015.7    .033       0    7236     .12       0
Bank Sta=6999.2,7015.7
XS Rating Curve= 0 ,0
Exp/Cntr=0.3,0.1

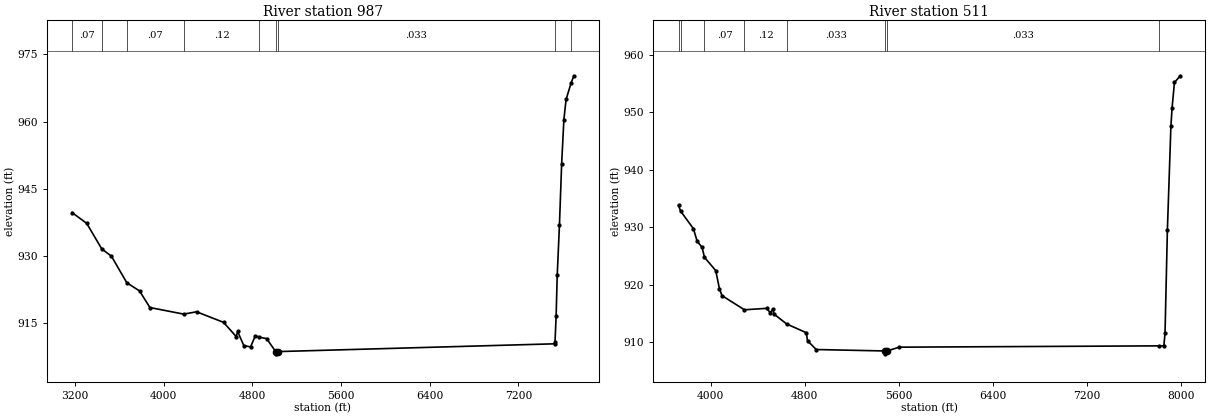
Type RM Length L Ch R = 1 ,987     ,476,476,476
BEGIN DESCRIPTION:
Jentsch Creek 2.0
END DESCRIPTION:
XS GIS Cut Line= 3
      2187375.03       13871075.        2189175.       13871375.
        2191875.       13871375.
#Sta/Elev= 30
  3174.8  939.67  3306.6  937.28  3442.6  931.56  3529.6  929.94  3668.6     924
  3783.1  922.18  3876.8  918.47  4181.7     917  4297.6  917.52  4540.9  915.16
  4654.9  911.98  4667.6  913.12  4723.3  909.99  4784.2  909.67  4827.3  912.16
  4863.9  911.85  4928.6  911.53  5011.3  908.63  5011.8  908.13  5027.9  908.63
  7526.1  910.37  7529.6  910.81  7539.6  916.48  7549.6   925.7  7569.6  936.88
  7589.6   950.6  7609.6  960.46  7629.6  964.96  7675.3  968.66  7699.6  970.23
#Mann= 9 ,-1 , 0
  3174.8     .07       0  3442.6    .035       0  3668.6     .07       0
  4181.7     .12       0  4863.9    .033       0  5011.3    .033       0
  5027.9    .033       0  7526.1     .12       0  7675.3    .063       0
Bank Sta=5011.3,5027.9
XS Rating Curve= 0 ,0
Exp/Cntr=0.3,0.1

Type RM Length L Ch R = 1 ,511     ,0,0,0
BEGIN DESCRIPTION:
Jentsch Creek 1.0
END DESCRIPTION:
XS GIS Cut Line= 3
      2187574.95     13871174.98        2188775.       13871575.
      2191775.04       13871575.
#Sta/Elev= 30
  3727.8  933.78  3745.7  932.78  3854.3  929.73    3886  927.55  3928.1  926.48
    3948  924.75  4044.1  922.43  4075.7  919.26  4096.8  918.08    4288  915.61
  4476.3  915.86  4507.9   915.1    4529  915.71  4539.5  914.86  4646.9  913.14
  4813.6  911.62  4824.1  910.23  4897.9  908.69  5484.4  908.44  5484.9  907.94
  5501.1  908.44  5602.8   909.1  7814.6  909.33  7852.8  909.33  7862.8  911.55
  7882.8  929.46  7912.8  947.58  7922.8   950.8  7942.8  955.18  7992.8  956.35
#Mann= 8 ,-1 , 0
  3727.8     .07       0  3745.7    .035       0    3948     .07       0
    4288     .12       0  4646.9    .033       0  5484.4    .033       0
  5501.1    .033       0  7814.6     .07       0
Bank Sta=5484.4,5501.1
XS Rating Curve= 0 ,0
Exp/Cntr=0.3,0.1

Chan Stop Cuts=-1
Use User Specified Reach Order=0
Composite Channel Slope=5