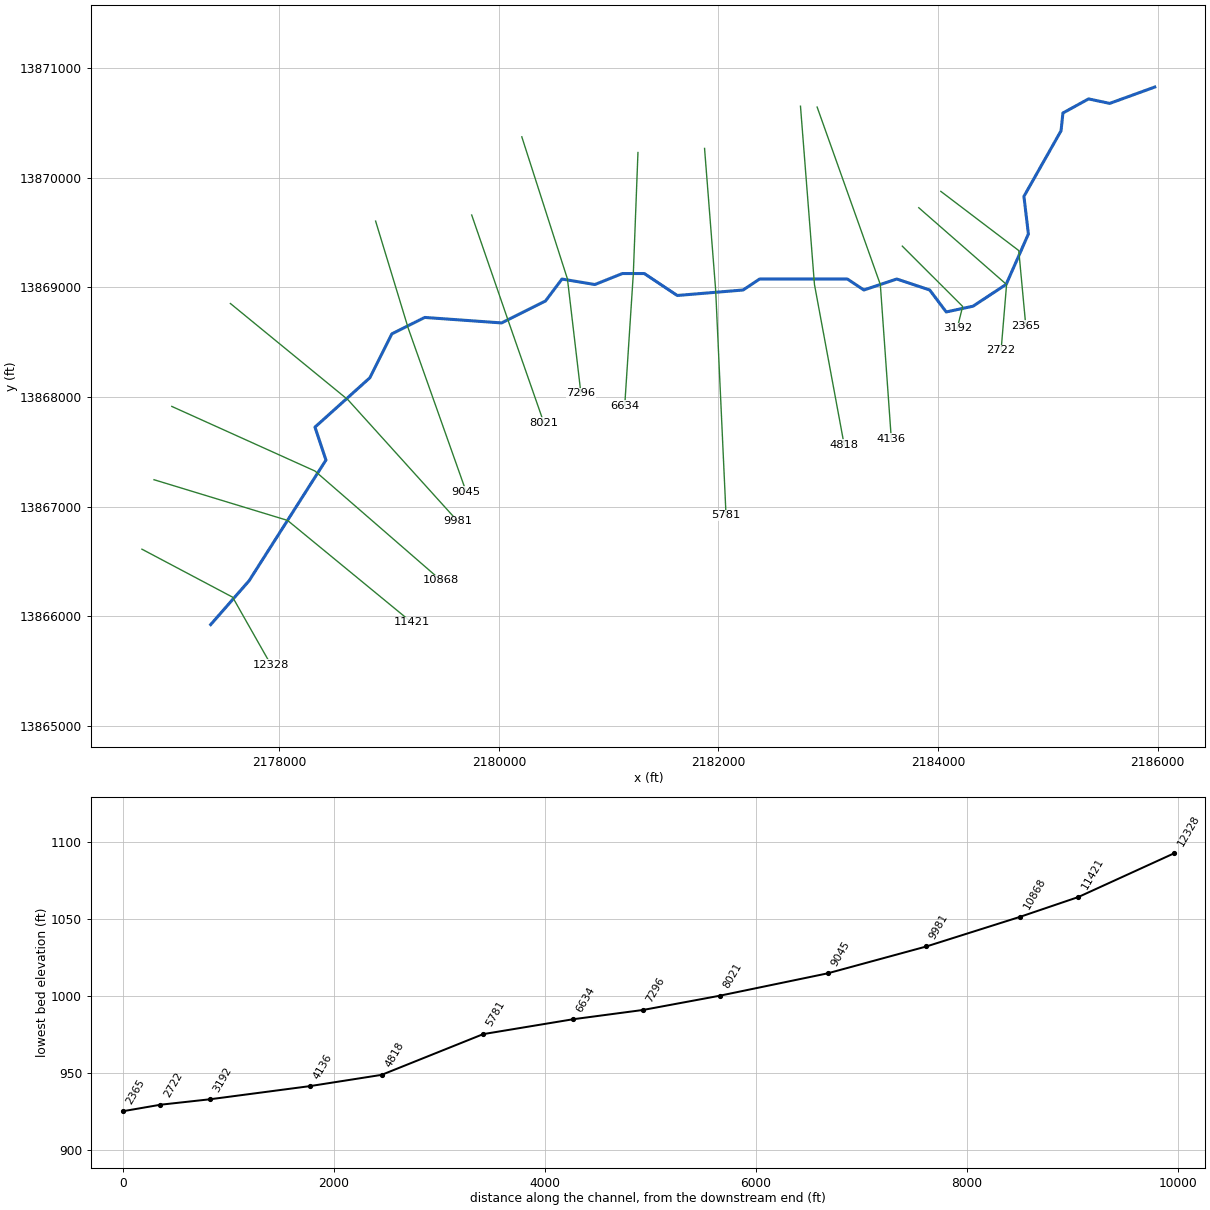
--- Jentsch Tributary 2.prj (project) ---

Proj Title=Jentsch Tributary 2 Base Level Engineering
Current Plan=p01
Default Exp/Contr=0.3,0.1
English Units
Geom File=g01
Flow File=f01
Plan File=p01
BEGIN DESCRIPTION:
Jentsch Tributary 2
END DESCRIPTION:

--- Jentsch Tributary 2.p01 (plan) ---

Plan Title=Multiple Run
Short Identifier=Multiple
Geom File=g01
Flow File=f01
Subcritical Flow
K Sum by GR= 0
Std Step Tol= 0.01
Critical Tol= 0.01
Num of Std Step Trials= 20
Max Error Tol= 0.3
Flow Tol Ratio= 0.001
Split Flow NTrial= 30
Split Flow Tol= 0.02
Split Flow Ratio= 0.02
Log Output Level= 0
Friction Slope Method= 1
Unsteady Friction Slope Method= 2
Unsteady Bridges Friction Slope Method= 1
Parabolic Critical Depth
Global Vel Dist=  1 , 1 , 1
Global Log Level= 0
CheckData=True
Encroach Param= -1, 0, 0, 0
BEGIN DESCRIPTION:
Multiple Run
END DESCRIPTION:

--- Jentsch Tributary 2.f01 (steady flow) ---

Flow Title=Multiple
Number of Profiles=7
Profile Names=10-year,25-year,50-year,1pct_min,100-year,1pct_plu,500-year
River Rch & RM= Jentsch Tributar,Reach-1,12328
     205     311     402     254     506    1010     790
River Rch & RM= Jentsch Tributar,Reach-1,11421
     477     771    1039     681    1358    2710    2291
River Rch & RM= Jentsch Tributar,Reach-1,8021
    1281    2201    3085    2095    4180    8340    7595
River Rch & RM= Jentsch Tributar,Reach-1,3192
    1355    2327    3262    2213    4415    8809    8010
Boundary for River Rch & Prof#=Jentsch Tributar,Reach-1,1
Up Type=0
Dn Type=3
Dn Slope=0.005
Boundary for River Rch & Prof#=Jentsch Tributar,Reach-1,2
Up Type=0
Dn Type=3
Dn Slope=0.005
Boundary for River Rch & Prof#=Jentsch Tributar,Reach-1,3
Up Type=0
Dn Type=3
Dn Slope=0.005
Boundary for River Rch & Prof#=Jentsch Tributar,Reach-1,4
Up Type=0
Dn Type=3
Dn Slope=0.005
Boundary for River Rch & Prof#=Jentsch Tributar,Reach-1,5
Up Type=0
Dn Type=3
Dn Slope=0.005
Boundary for River Rch & Prof#=Jentsch Tributar,Reach-1,6
Up Type=0
Dn Type=3
Dn Slope=0.005
Boundary for River Rch & Prof#=Jentsch Tributar,Reach-1,7
Up Type=0
Dn Type=3
Dn Slope=0.005

--- Jentsch Tributary 2.g01 (geometry) ---

Geom Title=Existing Conditions

River Reach=Jentsch Tributar,Reach-1
Reach XY= 30
      2177375.00     13865925.00      2177725.00     13866325.00
      2178425.00     13867425.00      2178325.00     13867725.00
      2178825.00     13868175.00      2179025.00     13868575.00
      2179325.00     13868725.00      2180025.00     13868675.00
      2180425.00     13868875.00      2180575.00     13869075.00
      2180875.00     13869025.00      2181125.00     13869125.00
      2181325.00     13869125.00      2181625.00     13868925.00
      2182225.00     13868975.00      2182375.00     13869075.00
      2183175.00     13869075.00      2183325.00     13868975.00
      2183625.00     13869075.00      2183925.00     13868975.00
      2184075.00     13868775.00      2184319.07     13868827.24
      2184621.46     13869026.46      2184823.80     13869485.50
      2184783.04     13869828.32      2185121.24     13870426.56
      2185138.36     13870588.35      2185371.70     13870716.92
      2185564.56     13870676.04      2185975.00     13870825.00

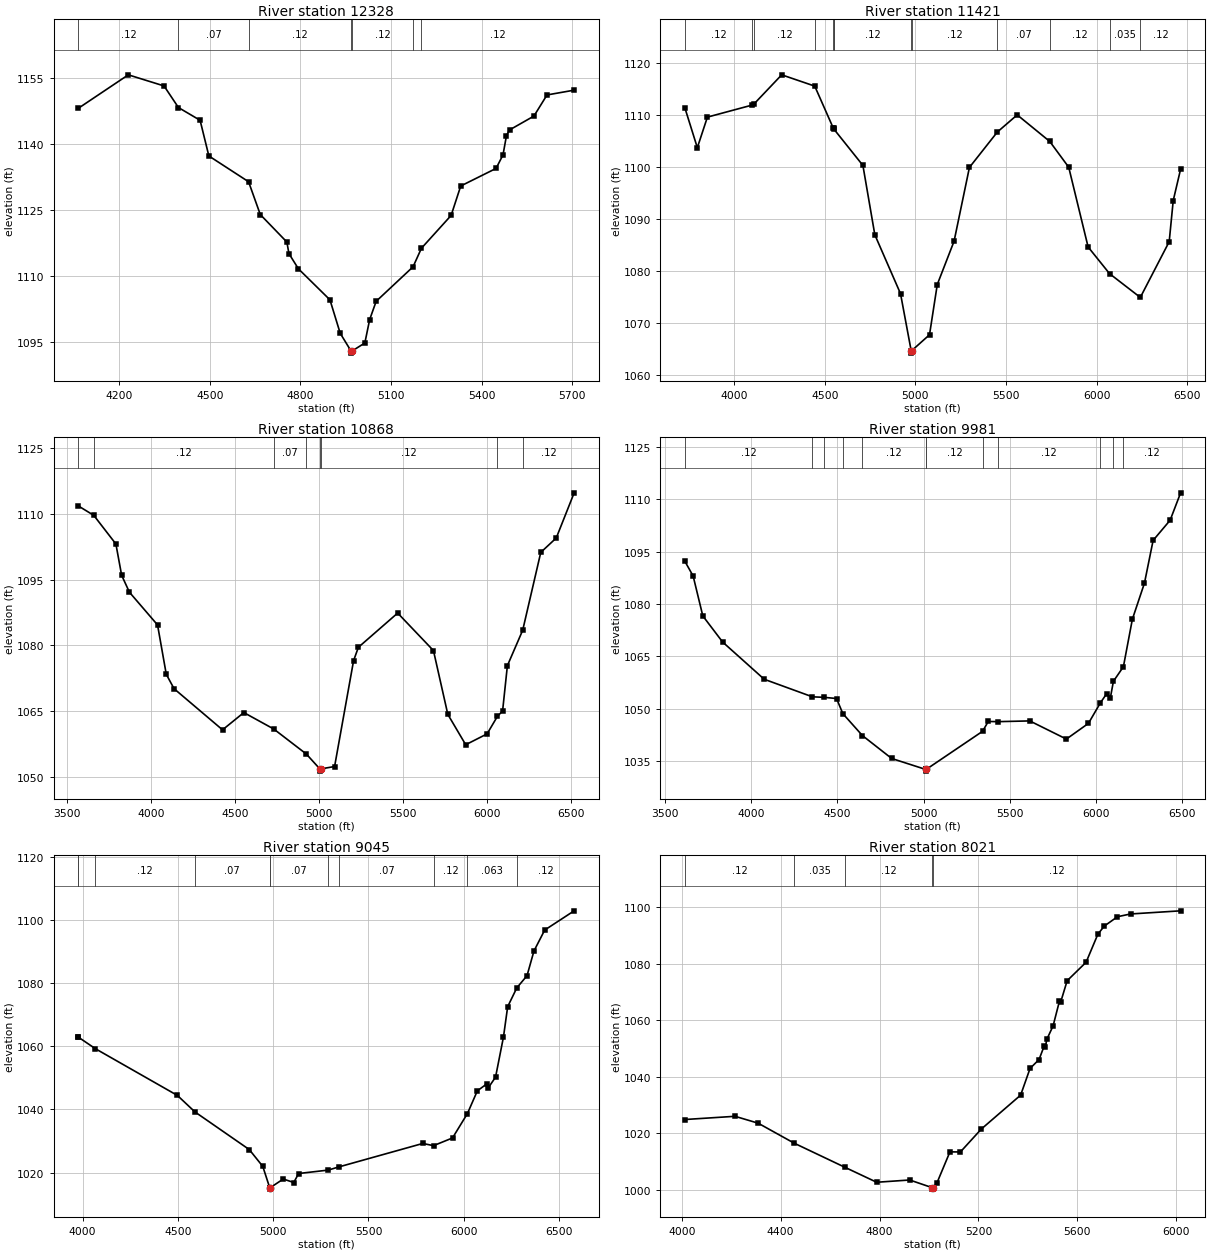
Type RM Length L Ch R = 1,12328,907,907,907
BEGIN DESCRIPTION:
Jentsch Tributary 2 13.0
END DESCRIPTION:
XS GIS Cut Line= 3
      2176748.72     13866612.59      2177575.00     13866175.00
      2177923.24     13865559.94
#Sta/Elev= 30
  4065.0 1148.20  4230.5 1155.82  4348.8 1153.29  4396.5 1148.37  4468.2 1145.47
  4497.2 1137.35  4628.7 1131.48  4667.5 1124.01  4755.5 1117.75  4762.4 1115.11
  4793.8 1111.65  4898.2 1104.59  4932.1 1096.98  4967.8 1092.96  4968.1 1092.46
  4971.8 1092.96  5013.7 1094.77  5029.6 1100.08  5051.2 1104.26  5173.4 1112.12
  5201.1 1116.34  5299.4 1123.81  5331.2 1130.51  5448.2 1134.51  5471.2 1137.60
  5482.7 1141.99  5492.8 1143.27  5573.6 1146.43  5616.9 1151.24  5706.8 1152.33
#Mann=7,-1,0
  4065.0    0.12       0  4396.5    0.07       0  4628.7    0.12       0
  4967.8    0.05       0  4971.8    0.12       0  5173.4    0.07       0
  5201.1    0.12       0
Bank Sta=4967.8,4971.8
Exp/Cntr=0.3,0.1

Type RM Length L Ch R = 1,11421,553,553,553
BEGIN DESCRIPTION:
Jentsch Tributary 2 12.0
END DESCRIPTION:
XS GIS Cut Line= 3
      2176858.86     13867245.76      2178075.00     13866875.00
      2179204.50     13865946.58
#Sta/Elev= 30
  3728.6 1111.37  3797.7 1103.66  3853.2 1109.54  4101.6 1111.87  4111.1 1112.10
  4262.8 1117.67  4445.0 1115.50  4546.1 1107.51  4549.0 1107.37  4551.6 1107.19
  4710.5 1100.25  4776.2 1086.92  4917.9 1075.59  4976.4 1064.66  4976.6 1064.16
  4980.4 1064.66  5077.7 1067.69  5120.5 1077.35  5213.1 1085.68  5297.8 1099.87
  5451.6 1106.67  5561.1 1109.97  5740.7 1104.86  5845.2 1099.90  5952.1 1084.57
  6070.3 1079.44  6239.9 1074.87  6399.1 1085.59  6421.3 1093.49  6462.1 1099.55
#Mann=13,-1,0
  3728.6    0.12       0  4101.6    0.07       0  4111.1    0.12       0
  4445.0    0.07       0  4546.1    0.12       0  4549.0    0.07       0
  4551.6    0.12       0  4976.4    0.05       0  4980.4    0.12       0
  5451.6    0.07       0  5740.7    0.12       0  6070.3   0.035       0
  6239.9    0.12       0
Bank Sta=4976.4,4980.4
Exp/Cntr=0.3,0.1

Type RM Length L Ch R = 1,10868,887,887,887
BEGIN DESCRIPTION:
Jentsch Tributary 2 11.0
END DESCRIPTION:
XS GIS Cut Line= 3
      2177020.77     13867913.86      2178325.00     13867325.00
      2179470.30     13866330.22
#Sta/Elev= 30
  3569.0 1111.82  3660.9 1109.67  3792.3 1103.14  3826.4 1096.01  3872.7 1092.14
  4040.0 1084.67  4091.8 1073.42  4138.0 1070.13  4426.4 1060.74  4553.0 1064.68
  4731.2 1060.92  4924.9 1055.21  5005.1 1051.82  5005.4 1051.32  5009.1 1051.82
  5092.6 1052.37  5205.6 1076.54  5234.1 1079.57  5467.7 1087.38  5680.4 1078.82
  5765.9 1064.26  5872.2 1057.34  5999.4 1059.82  6060.5 1063.80  6091.5 1065.05
  6120.0 1075.38  6211.1 1083.47  6318.5 1101.22  6410.6 1104.51  6517.0 1114.81
#Mann=8,-1,0
  3569.0    0.07       0  3660.9    0.12       0  4731.2    0.07       0
  4924.9    0.12       0  5005.1    0.05       0  5009.1    0.12       0
  6060.5   0.035       0  6211.1    0.12       0
Bank Sta=5005.1,5009.1
Exp/Cntr=0.3,0.1

Type RM Length L Ch R = 1,9981,936,936,936
BEGIN DESCRIPTION:
Jentsch Tributary 2 10.0
END DESCRIPTION:
XS GIS Cut Line= 3
      2177554.34     13868852.16      2178625.00     13867975.00
      2179624.13     13866868.55
#Sta/Elev= 30
  3615.9 1092.28  3664.3 1088.02  3720.3 1076.60  3835.1 1069.13  4076.3 1058.46
  4355.8 1053.43  4424.7 1053.28  4495.8 1052.94  4532.2 1048.62  4645.6 1042.34
  4815.5 1035.77  5011.8 1032.65  5012.1 1032.15  5015.8 1032.65  5342.3 1043.55
  5375.5 1046.37  5432.5 1046.32  5616.1 1046.53  5828.4 1041.33  5956.2 1045.82
  6025.8 1051.72  6062.3 1054.36  6083.2 1053.08  6101.1 1057.88  6159.0 1062.05
  6211.0 1075.65  6281.2 1086.01  6331.3 1098.23  6430.0 1104.01  6490.8 1111.85
#Mann=12,-1,0
  3615.9    0.12       0  4355.8    0.07       0  4424.7    0.12       0
  4532.2    0.07       0  4645.6    0.12       0  5011.8    0.05       0
  5015.8    0.12       0  5342.3    0.07       0  5432.5    0.12       0
  6025.8   0.063       0  6101.1   0.035       0  6159.0    0.12       0
Bank Sta=5011.8,5015.8
Exp/Cntr=0.3,0.1

Type RM Length L Ch R = 1,9045,1024,1024,1024
BEGIN DESCRIPTION:
Jentsch Tributary 2 9.0
END DESCRIPTION:
XS GIS Cut Line= 3
      2178877.38     13869603.12      2179175.00     13868625.00
      2179702.33     13867136.13
#Sta/Elev= 30
  3977.6 1062.94  3978.1 1062.89  4067.2 1059.24  4497.5 1044.43  4589.5 1039.21
  4874.6 1027.28  4945.5 1021.95  4981.6 1015.24  4981.8 1014.74  4985.6 1015.24
  5053.0 1017.94  5108.1 1016.84  5133.7 1019.69  5288.6 1020.77  5345.9 1021.80
  5785.0 1029.21  5841.7 1028.52  5941.2 1030.96  6019.4 1038.69  6071.5 1045.89
  6121.2 1048.10  6126.5 1046.65  6167.0 1050.23  6208.6 1062.98  6230.6 1072.56
  6278.6 1078.53  6332.1 1082.38  6368.5 1090.20  6424.8 1096.84  6579.5 1102.94
#Mann=11,-1,0
  3977.6   0.035       0  3978.1    0.07       0  4067.2    0.12       0
  4589.5    0.07       0  4981.6    0.05       0  4985.6    0.07       0
  5288.6   0.035       0  5345.9    0.07       0  5841.7    0.12       0
  6019.4   0.063       0  6278.6    0.12       0
Bank Sta=4981.6,4985.6
Exp/Cntr=0.3,0.1

Type RM Length L Ch R = 1,8021,725,725,725
BEGIN DESCRIPTION:
Jentsch Tributary 2 8.0
END DESCRIPTION:
XS GIS Cut Line= 3
      2179752.62     13869658.71      2180075.00     13868725.00
      2180410.25     13867763.89
#Sta/Elev= 30
  4012.2 1024.85  4215.3 1025.99  4308.8 1023.56  4455.2 1016.46  4661.2 1007.90
  4788.4 1002.66  4922.0 1003.46  5013.5 1000.73  5013.8 1000.23  5017.5 1000.73
  5031.8 1002.34  5084.7 1013.41  5127.1 1013.38  5211.8 1021.49  5370.7 1033.48
  5408.8 1042.92  5445.2 1046.07  5465.7 1050.81  5471.0 1050.60  5476.6 1053.21
  5502.0 1057.96  5527.8 1066.77  5533.1 1066.50  5558.9 1073.95  5635.5 1080.48
  5683.1 1090.39  5708.9 1093.26  5762.5 1096.59  5815.5 1097.56  6017.9 1098.67
#Mann=5,-1,0
  4012.2    0.12       0  4455.2   0.035       0  4661.2    0.12       0
  5013.5    0.05       0  5017.5    0.12       0
Bank Sta=5013.5,5017.5
Exp/Cntr=0.3,0.1

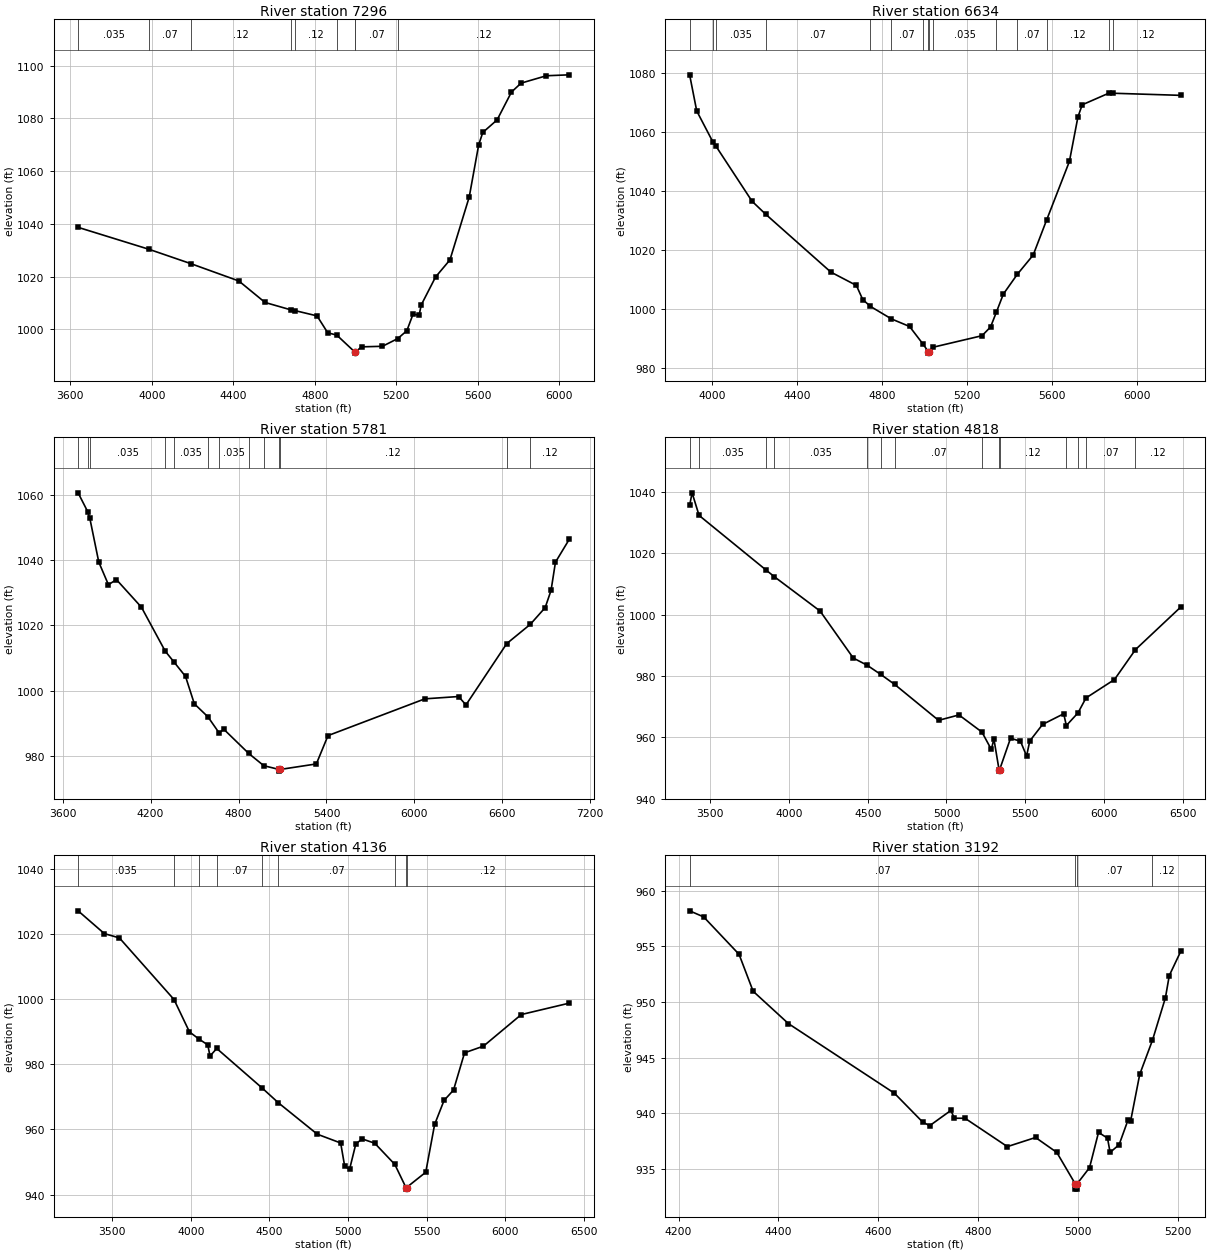
Type RM Length L Ch R = 1,7296,662,662,662
BEGIN DESCRIPTION:
Jentsch Tributary 2 7.0
END DESCRIPTION:
XS GIS Cut Line= 3
      2180209.10     13870371.32      2180625.00     13869075.00
      2180747.46     13868033.17
#Sta/Elev= 30
  3638.6 1038.69  3987.0 1030.36  4191.6 1024.94  4427.4 1018.37  4555.9 1010.23
  4682.4 1007.43  4703.2 1007.14  4811.0 1005.14  4863.5  998.74  4907.9  997.86
  4995.4  991.53  4995.6  991.03  4999.4  991.53  5030.2  993.41  5132.2  993.62
  5207.3  996.55  5251.7  999.52  5281.9 1005.74  5312.1 1005.43  5322.2 1009.26
  5392.7 1019.88  5463.2 1026.36  5557.8 1050.18  5604.1 1069.91  5624.3 1074.64
  5694.7 1079.41  5765.2 1089.96  5812.2 1093.33  5936.4 1096.13  6049.0 1096.48
#Mann=9,-1,0
  3638.6   0.035       0  3987.0    0.07       0  4191.6    0.12       0
  4682.4    0.07       0  4703.2    0.12       0  4907.9    0.07       0
  4995.4    0.05       0  4999.4    0.07       0  5207.3    0.12       0
Bank Sta=4995.4,4999.4
Exp/Cntr=0.3,0.1

Type RM Length L Ch R = 1,6634,853,853,853
BEGIN DESCRIPTION:
Jentsch Tributary 2 6.0
END DESCRIPTION:
XS GIS Cut Line= 3
      2181267.17     13870228.29      2181225.00     13869125.00
      2181146.63     13867922.15
#Sta/Elev= 30
  3895.9 1079.24  3929.2 1067.01  4006.2 1056.38  4019.5 1055.10  4189.4 1036.44
  4253.3 1032.05  4559.7 1012.47  4679.8 1007.95  4709.8 1003.16  4746.1 1000.84
  4844.7  996.61  4929.9  994.05  4993.7  988.04  5018.0  985.53  5018.3  985.03
  5022.0  985.53  5041.9  987.05  5270.6  990.93  5310.7  993.88  5338.2  998.92
  5370.8 1005.01  5437.0 1011.76  5511.1 1018.23  5574.6 1030.15  5681.4 1049.92
  5721.5 1064.99  5741.6 1069.09  5868.7 1073.09  5885.5 1073.01  6205.4 1072.29
#Mann=15,-1,0
  3895.9   0.035       0  4006.2    0.07       0  4019.5   0.035       0
  4253.3    0.07       0  4746.1    0.12       0  4844.7    0.07       0
  4993.7    0.12       0  5018.0    0.05       0  5022.0    0.12       0
  5041.9   0.035       0  5338.2    0.12       0  5437.0    0.07       0
  5574.6    0.12       0  5868.7   0.035       0  5885.5    0.12       0
Bank Sta=5018,5022
Exp/Cntr=0.3,0.1

Type RM Length L Ch R = 1,5781,963,963,963
BEGIN DESCRIPTION:
Jentsch Tributary 2 5.0
END DESCRIPTION:
XS GIS Cut Line= 3
      2181873.77     13870265.54      2181975.00     13868975.00
      2182069.54     13866920.47
#Sta/Elev= 30
  3705.5 1060.54  3770.6 1054.81  3785.8 1052.69  3846.5 1039.36  3912.4 1032.42
  3966.8 1033.99  4137.4 1025.55  4299.8 1012.09  4357.9 1008.87  4438.3 1004.36
  4498.5  995.98  4591.3  991.99  4668.1  987.04  4699.1  988.21  4869.0  980.81
  4972.4  977.04  5078.1  975.88  5078.3  975.38  5082.1  975.88  5330.8  977.58
  5410.4  986.25  6071.1  997.50  6301.4  998.21  6351.4  995.63  6629.7 1014.40
  6790.8 1020.31  6892.0 1025.42  6932.0 1030.68  6962.1 1039.31  7056.7 1046.35
#Mann=13,-1,0
  3705.5   0.035       0  3770.6    0.07       0  3785.8   0.035       0
  4299.8    0.07       0  4357.9   0.035       0  4591.3    0.07       0
  4668.1   0.035       0  4869.0    0.07       0  4972.4    0.12       0
  5078.1    0.05       0  5082.1    0.12       0  6629.7    0.07       0
  6790.8    0.12       0
Bank Sta=5078.1,5082.1
Exp/Cntr=0.3,0.1

Type RM Length L Ch R = 1,4818,682,682,682
BEGIN DESCRIPTION:
Jentsch Tributary 2 4.0
END DESCRIPTION:
XS GIS Cut Line= 3
      2182747.65     13870650.52      2182875.00     13869025.00
      2183146.05     13867562.00
#Sta/Elev= 30
  3369.5 1035.56  3385.1 1039.67  3429.4 1032.31  3856.1 1014.45  3907.3 1012.33
  4197.5 1001.15  4408.2  985.84  4495.5  983.51  4582.8  980.49  4671.3  977.23
  4949.8  965.53  5079.3  967.29  5225.2  961.70  5284.8  956.03  5301.0  959.47
  5333.6  949.48  5333.9  948.98  5337.6  949.48  5406.7  959.71  5469.8  958.71
  5508.5  953.91  5528.8  958.80  5610.2  964.20  5744.3  967.67  5760.9  963.83
  5834.9  967.96  5885.6  972.82  6066.6  978.83  6199.8  988.58  6487.9 1002.48
#Mann=14,-1,0
  3369.5    0.07       0  3429.4   0.035       0  3856.1    0.07       0
  3907.3   0.035       0  4495.5    0.07       0  4582.8   0.035       0
  4671.3    0.07       0  5225.2    0.12       0  5333.6    0.05       0
  5337.6    0.12       0  5760.9    0.07       0  5834.9    0.12       0
  5885.6    0.07       0  6199.8    0.12       0
Bank Sta=5333.6,5337.6
Exp/Cntr=0.3,0.1

Type RM Length L Ch R = 1,4136,944,944,944
BEGIN DESCRIPTION:
Jentsch Tributary 2 3.0
END DESCRIPTION:
XS GIS Cut Line= 3
      2182899.37     13870642.42      2183475.00     13869025.00
      2183574.87     13867620.15
#Sta/Elev= 30
  3283.2 1027.21  3450.3 1020.20  3545.8 1018.89  3893.5  999.94  3991.6  990.00
  4050.9  987.84  4108.4  986.00  4122.2  982.57  4165.3  984.90  4454.2  972.74
  4557.5  968.20  4804.9  958.55  4953.7  955.85  4978.8  948.83  5010.0  947.71
  5050.1  955.55  5090.2  957.11  5170.4  955.78  5298.1  949.27  5368.9  942.17
  5369.2  941.67  5372.9  942.17  5494.9  946.86  5551.4  961.54  5611.5  968.94
  5671.7  972.12  5741.9  983.57  5862.2  985.62  6102.8  995.33  6408.4  998.84
#Mann=9,-1,0
  3283.2   0.035       0  3893.5    0.07       0  4050.9   0.035       0
  4165.3    0.07       0  4454.2    0.12       0  4557.5    0.07       0
  5298.1    0.12       0  5368.9    0.05       0  5372.9    0.12       0
Bank Sta=5368.9,5372.9
Exp/Cntr=0.3,0.1

Type RM Length L Ch R = 1,3192,470,470,470
BEGIN DESCRIPTION:
Jentsch Tributary 2 2.0
END DESCRIPTION:
XS GIS Cut Line= 3
      2183675.03     13869374.97      2184225.00     13868825.00
      2184175.01     13868625.03
#Sta/Elev= 30
  4222.2  958.19  4250.4  957.64  4321.2  954.28  4349.4  950.96  4420.2  948.05
  4632.3  941.80  4688.9  939.21  4703.0  938.88  4745.4  940.25  4752.5  939.55
  4773.7  939.55  4858.6  937.00  4915.1  937.82  4957.6  936.48  4994.2  933.68
  4994.5  933.18  4998.4  933.18  4998.7  933.68  5023.2  935.11  5041.2  938.28
  5059.2  937.76  5064.4  936.48  5082.4  937.17  5100.5  939.42  5105.6  939.32
  5123.7  943.49  5149.3  946.57  5175.2  950.38  5182.9  952.37  5206.1  954.57
#Mann=4,-1,0
  4222.2    0.07       0  4994.2    0.05       0  4998.7    0.07       0
  5149.3    0.12       0
Bank Sta=4994.2,4998.7
Exp/Cntr=0.3,0.1

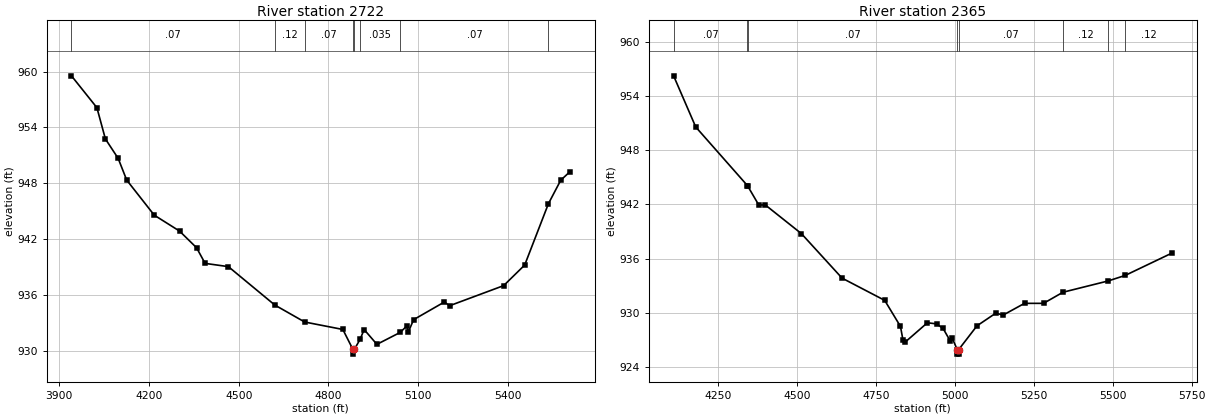
Type RM Length L Ch R = 1,2722,357,357,357
BEGIN DESCRIPTION:
Jentsch Tributary 2 1.0
END DESCRIPTION:
XS GIS Cut Line= 3
      2183824.99     13869725.01      2184625.00     13869025.00
      2184575.00     13868425.01
#Sta/Elev= 30
  3941.1  959.54  4026.1  956.12  4054.5  952.76  4097.2  950.67  4125.7  948.34
  4217.8  944.57  4302.3  942.86  4359.2  941.07  4387.7  939.39  4465.5  939.04
  4620.4  934.92  4720.5  933.09  4848.0  932.29  4881.8  930.14  4882.1  929.64
  4886.3  930.14  4905.7  931.23  4919.2  932.28  4961.9  930.69  5040.1  931.98
  5061.8  932.67  5066.8  932.01  5084.4  933.34  5187.3  935.24  5204.8  934.84
  5385.4  937.00  5455.7  939.21  5535.0  945.80  5576.1  948.32  5606.2  949.22
#Mann=8,-1,0
  3941.1    0.07       0  4620.4    0.12       0  4720.5    0.07       0
  4881.8   0.035       0  4886.3    0.07       0  4905.7   0.035       0
  5040.1    0.07       0  5535.0    0.12       0
Bank Sta=4881.8,4886.3
Exp/Cntr=0.3,0.1

Type RM Length L Ch R = 1,2365,0,0,0
BEGIN DESCRIPTION:
Jentsch Tributary 2 0.1
END DESCRIPTION:
XS GIS Cut Line= 3
      2184026.21     13869873.98      2184736.17     13869334.30
      2184800.00     13868649.97
#Sta/Elev= 30
  4108.2  956.22  4178.3  950.56  4342.2  944.07  4342.4  944.06  4378.0  941.93
  4398.8  941.93  4513.1  938.76  4642.1  933.83  4777.2  931.37  4827.1  928.49
  4835.2  926.96  4841.7  926.74  4912.4  928.89  4941.5  928.77  4962.3  928.26
  4985.1  926.86  4991.4  927.16  5007.1  925.92  5007.4  925.42  5011.3  925.42
  5011.6  925.92  5069.6  928.55  5129.9  929.97  5151.9  929.73  5220.3  931.04
  5280.5  931.04  5342.2  932.27  5485.5  933.52  5539.3  934.13  5687.3  936.60
#Mann=8,-1,0
  4108.2    0.07       0  4342.2    0.12       0  4342.4    0.07       0
  5007.1    0.05       0  5011.6    0.07       0  5342.2    0.12       0
  5485.5    0.07       0  5539.3    0.12       0
Bank Sta=5007.1,5011.6
Exp/Cntr=0.3,0.1

Chan Stop Cuts=-1