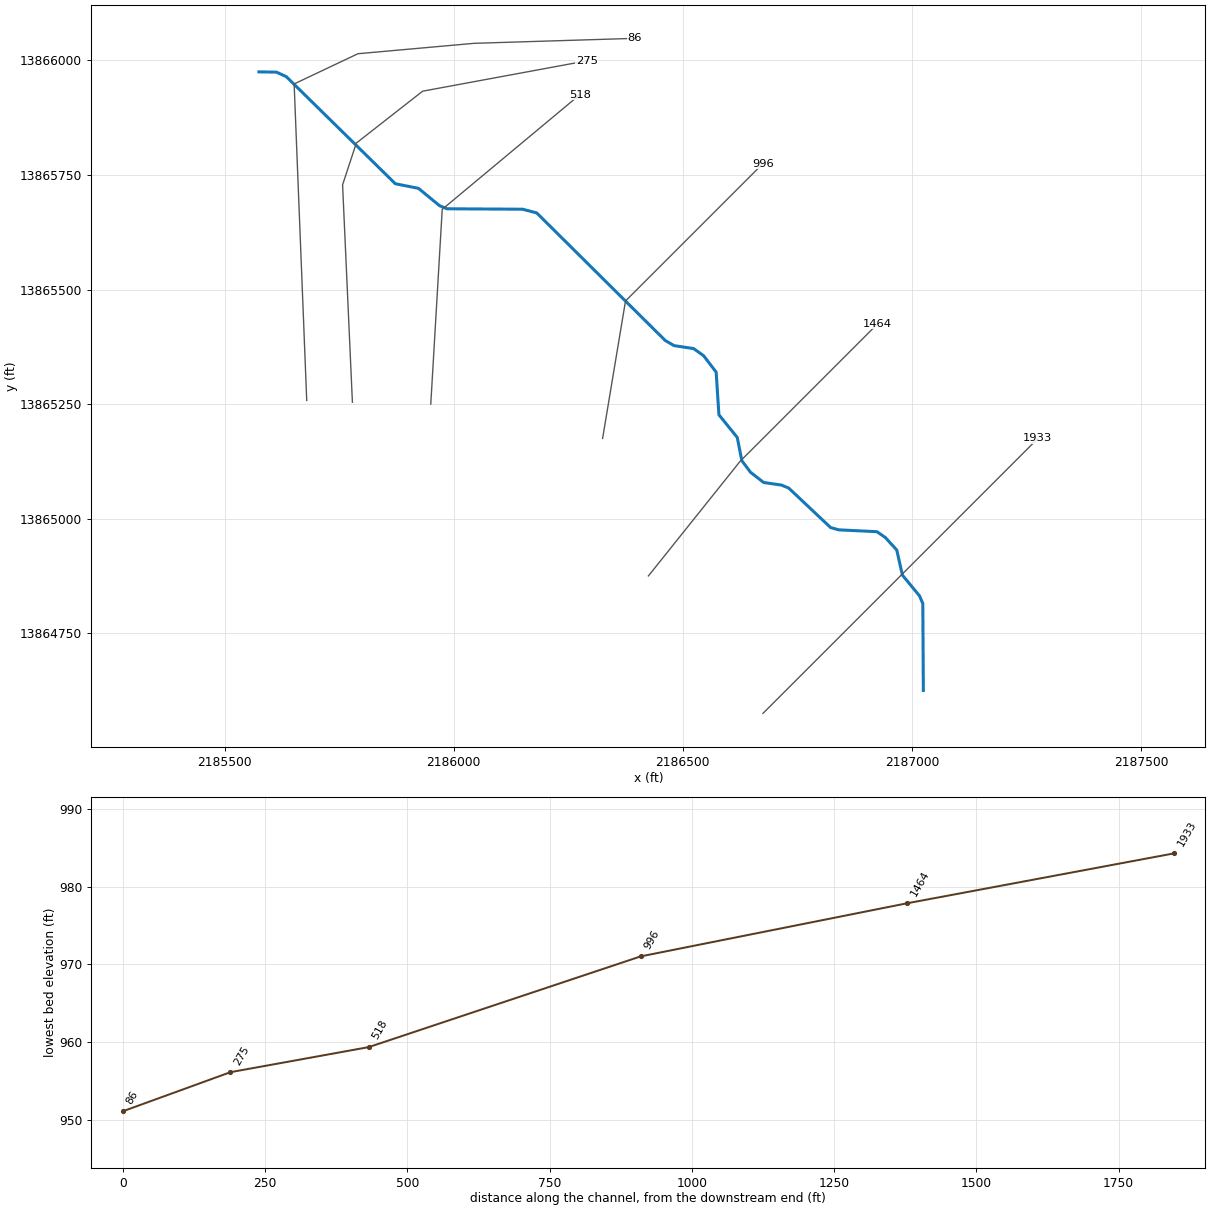
--- Jentsch Tributary 3.prj (project) ---

Proj Title=Jentsch Tributary 3 Base Level Engineering
Current Plan=p01
Default Exp/Contr=0.3,0.1
English Units
Geom File=g01
Flow File=f01
Plan File=p01
BEGIN DESCRIPTION:
Jentsch Tributary 3
END DESCRIPTION:

--- Jentsch Tributary 3.p01 (plan) ---

Plan Title=Multiple Run
Short Identifier=Multiple
Geom File=g01
Flow File=f01
Subcritical Flow
K Sum by GR= 0
Std Step Tol= 0.01
Critical Tol= 0.01
Num of Std Step Trials= 20
Max Error Tol= 0.3
Flow Tol Ratio= 0.001
Split Flow NTrial= 30
Split Flow Tol= 0.02
Split Flow Ratio= 0.02
Log Output Level= 0
Friction Slope Method= 1
Unsteady Friction Slope Method= 2
Unsteady Bridges Friction Slope Method= 1
Parabolic Critical Depth
Global Vel Dist=  1 , 1 , 1
Global Log Level= 0
CheckData=True
Encroach Param= -1, 0, 0, 0
BEGIN DESCRIPTION:
Multiple Run
END DESCRIPTION:

--- Jentsch Tributary 3.f01 (steady flow) ---

Flow Title=Multiple
Number of Profiles=7
Profile Names=10-year,25-year,50-year,1pct_min,100-year,1pct_plu,500-year
River Rch & RM= Jentsch Tributar,Reach-1,1933
     869    1457    2011    1348    2689    5365    4750
Boundary for River Rch & Prof#=Jentsch Tributar,Reach-1,1
Up Type=0
Dn Type=3
Dn Slope=0.005
Boundary for River Rch & Prof#=Jentsch Tributar,Reach-1,2
Up Type=0
Dn Type=3
Dn Slope=0.005
Boundary for River Rch & Prof#=Jentsch Tributar,Reach-1,3
Up Type=0
Dn Type=3
Dn Slope=0.005
Boundary for River Rch & Prof#=Jentsch Tributar,Reach-1,4
Up Type=0
Dn Type=3
Dn Slope=0.005
Boundary for River Rch & Prof#=Jentsch Tributar,Reach-1,5
Up Type=0
Dn Type=3
Dn Slope=0.005
Boundary for River Rch & Prof#=Jentsch Tributar,Reach-1,6
Up Type=0
Dn Type=3
Dn Slope=0.005
Boundary for River Rch & Prof#=Jentsch Tributar,Reach-1,7
Up Type=0
Dn Type=3
Dn Slope=0.005

--- Jentsch Tributary 3.g01 (geometry) ---

Geom Title=Existing Conditions

River Reach=Jentsch Tributar,Reach-1
Reach XY= 30
      2187025.00     13864625.00      2187023.81     13864814.51
      2187016.91     13864831.08      2186979.23     13864876.78
      2186967.00     13864931.38      2186942.13     13864958.70
      2186923.72     13864971.47      2186840.23     13864975.53
      2186822.58     13864980.54      2186731.02     13865066.81
      2186715.16     13865073.27      2186676.43     13865078.89
      2186647.85     13865101.16      2186628.86     13865126.42
      2186618.85     13865177.15      2186578.83     13865226.59
      2186572.82     13865319.70      2186545.57     13865355.41
      2186523.60     13865371.12      2186481.09     13865377.55
      2186461.80     13865388.64      2186181.19     13865667.19
      2186150.12     13865675.29      2185985.50     13865676.20
      2185968.92     13865683.09      2185923.25     13865720.78
      2185872.70     13865730.83      2185634.79     13865964.49
      2185613.16     13865974.41      2185575.00     13865975.00

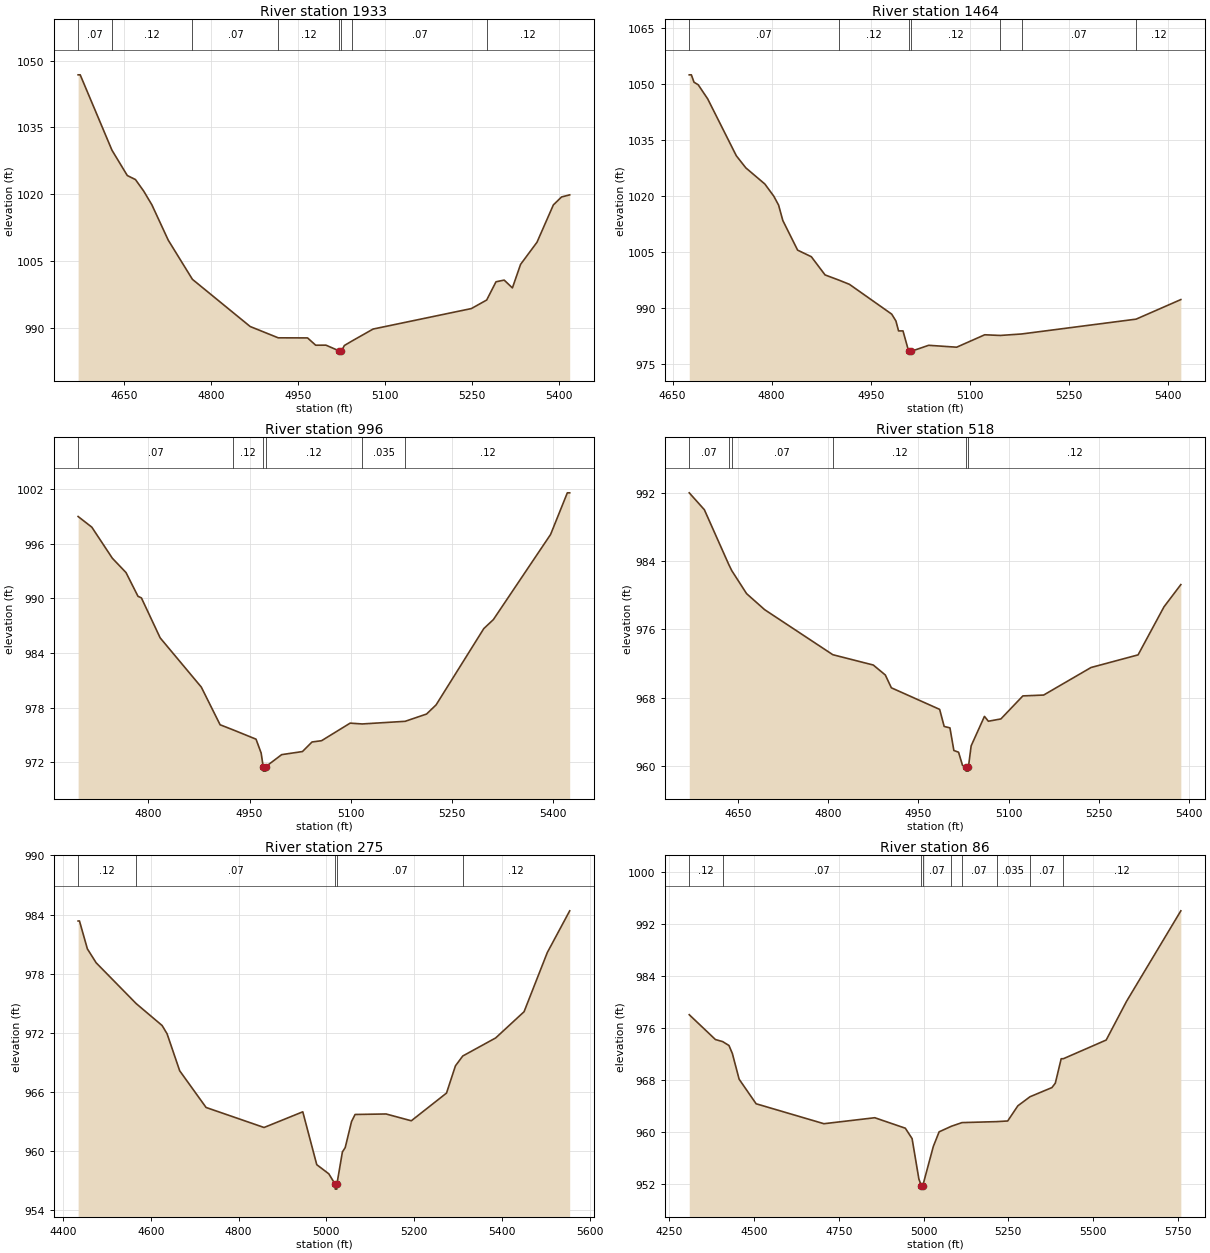
Type RM Length L Ch R = 1,1933,469,469,469
BEGIN DESCRIPTION:
Jentsch Tributary 3 4.0
END DESCRIPTION:
XS GIS Cut Line= 3
      2186674.98     13864574.98      2186975.00     13864875.00
      2187274.96     13865174.96
#Sta/Elev= 30
  4570.6 1046.84  4574.2 1046.84  4629.0 1029.90  4655.5 1024.20  4669.6 1023.29
  4683.8 1020.70  4697.9 1017.62  4726.2 1009.66  4767.9 1000.86  4867.6  990.25
  4916.0  987.71  4966.6  987.69  4980.7  986.05  4998.4  986.06  5021.2  984.77
  5021.4  984.27  5025.2  984.77  5030.2  985.99  5043.4  987.00  5079.7  989.68
  5249.4  994.29  5275.8  996.21  5291.9 1000.31  5306.0 1000.69  5320.2  998.93
  5334.3 1004.22  5362.6 1009.19  5390.9 1017.59  5405.0 1019.38  5419.1 1019.85
#Mann=8,-1,0
  4570.6    0.07       0  4629.0    0.12       0  4767.9    0.07       0
  4916.0    0.12       0  5021.2    0.05       0  5025.2    0.12       0
  5043.4    0.07       0  5275.8    0.12       0
Bank Sta=5021.2,5025.2
Exp/Cntr=0.3,0.1

Type RM Length L Ch R = 1,1464,468,468,468
BEGIN DESCRIPTION:
Jentsch Tributary 3 3.0
END DESCRIPTION:
XS GIS Cut Line= 3
      2186424.98     13864874.97      2186625.00     13865125.00
      2186925.03     13865425.03
#Sta/Elev= 30
  4675.2 1052.49  4678.4 1052.49  4682.4 1050.51  4688.8 1049.82  4703.2 1046.02
  4746.5 1030.78  4760.9 1027.54  4789.7 1023.21  4803.3 1019.93  4810.5 1017.56
  4816.9 1013.43  4839.3 1005.48  4860.1 1003.71  4880.9  998.83  4902.0  997.43
  4917.8  996.31  4981.8  988.32  4988.2  986.48  4992.2  983.82  4998.9  983.82
  5007.5  978.36  5007.8  977.86  5011.5  978.36  5037.8  979.96  5080.2  979.45
  5122.7  982.78  5146.4  982.60  5178.8  983.00  5351.9  986.97  5419.7  992.22
#Mann=7,-1,0
  4675.2    0.07       0  4902.0    0.12       0  5007.5    0.05       0
  5011.5    0.12       0  5146.4   0.035       0  5178.8    0.07       0
  5351.9    0.12       0
Bank Sta=5007.5,5011.5
Exp/Cntr=0.3,0.1

Type RM Length L Ch R = 1,996,478,478,478
BEGIN DESCRIPTION:
Jentsch Tributary 3 2.0
END DESCRIPTION:
XS GIS Cut Line= 3
      2186325.00     13865175.01      2186375.00     13865475.00
      2186675.01     13865775.01
#Sta/Elev= 30
  4695.9  999.00  4716.2  997.83  4746.6  994.42  4766.9  992.84  4784.6  990.24
  4789.7  990.06  4817.5  985.67  4878.4  980.27  4906.3  976.13  4925.6  975.57
  4959.5  974.55  4967.1  973.03  4970.1  971.54  4970.4  971.04  4973.9  971.04
  4974.1  971.54  4997.5  972.85  5028.3  973.19  5042.5  974.24  5056.6  974.38
  5099.0  976.31  5116.8  976.22  5180.5  976.51  5212.2  977.31  5226.3  978.31
  5297.0  986.69  5311.2  987.68  5396.0  997.03  5420.8 1001.60  5424.3 1001.60
#Mann=6,-1,0
  4695.9    0.07       0  4925.6    0.12       0  4970.1    0.05       0
  4974.1    0.12       0  5116.8   0.035       0  5180.5    0.12       0
Bank Sta=4970.1,4974.1
Exp/Cntr=0.3,0.1

Type RM Length L Ch R = 1,518,243,243,243
BEGIN DESCRIPTION:
Jentsch Tributary 3 1.0
END DESCRIPTION:
XS GIS Cut Line= 3
      2185950.00     13865249.97      2185975.00     13865675.00
      2186275.02     13865925.01
#Sta/Elev= 30
  4569.5  992.01  4594.6  990.03  4635.1  983.61  4640.0  982.90  4664.7  980.19
  4694.7  978.31  4807.9  973.03  4875.1  971.82  4895.1  970.65  4905.1  969.15
  4985.3  966.62  4992.8  964.62  5002.4  964.45  5008.9  961.80  5016.7  961.60
  5023.3  960.05  5029.1  959.88  5029.3  959.38  5032.8  959.38  5033.1  959.88
  5037.6  962.34  5059.7  965.80  5066.2  965.23  5087.0  965.50  5123.5  968.20
  5158.0  968.30  5236.7  971.53  5314.8  973.01  5357.8  978.64  5385.8  981.25
#Mann=6,-1,0
  4569.5    0.07       0  4635.1    0.12       0  4640.0    0.07       0
  4807.9    0.12       0  5029.1    0.05       0  5033.1    0.12       0
Bank Sta=5029.1,5033.1
Exp/Cntr=0.3,0.1

Type RM Length L Ch R = 1,275,189,189,189
BEGIN DESCRIPTION:
Jentsch Tributary 3 0.2
END DESCRIPTION:
XS GIS Cut Line= 5
      2185778.98     13865253.91      2185757.53     13865728.42
      2185787.49     13865819.56      2185932.22     13865932.83
      2186290.82     13865999.15
#Sta/Elev= 30
  4434.7  983.35  4437.8  983.35  4455.8  980.52  4475.8  979.11  4567.0  974.97
  4626.0  972.75  4637.3  971.91  4666.0  968.16  4726.1  964.44  4858.1  962.41
  4946.3  964.00  4978.1  958.64  5005.6  957.71  5020.0  956.66  5020.3  956.16
  5023.8  956.16  5024.0  956.66  5036.5  959.93  5042.9  960.37  5057.3  963.01
  5065.4  963.73  5136.0  963.78  5193.4  963.09  5273.6  965.90  5293.9  968.66
  5310.6  969.66  5385.5  971.49  5450.2  974.15  5503.1  980.15  5554.1  984.38
#Mann=5,-1,0
  4434.7    0.12       0  4567.0    0.07       0  5020.0    0.05       0
  5024.0    0.07       0  5310.6    0.12       0
Bank Sta=5020,5024
Exp/Cntr=0.3,0.1

Type RM Length L Ch R = 1,86,0,0,0
BEGIN DESCRIPTION:
Jentsch Tributary 3 0.1
END DESCRIPTION:
XS GIS Cut Line= 5
      2185679.28     13865257.90      2185651.80     13865948.65
      2185791.03     13866014.60      2186044.47     13866037.30
      2186395.19     13866048.19
#Sta/Elev= 30
  4308.7  977.99  4385.9  974.17  4407.2  973.85  4425.9  973.25  4435.9  972.02
  4455.9  968.06  4506.0  964.28  4706.1  961.21  4856.2  962.13  4946.3  960.52
  4966.3  958.92  4986.3  952.71  4993.7  951.64  4993.9  951.14  4997.7  951.64
  5028.9  957.70  5046.1  959.96  5082.3  960.82  5113.6  961.38  5215.6  961.53
  5248.4  961.63  5278.5  963.97  5314.3  965.36  5378.9  966.77  5389.0  967.45
  5406.3  971.21  5413.0  971.22  5539.1  974.09  5599.1  980.04  5759.4  993.98
#Mann=9,-1,0
  4308.7    0.12       0  4407.2    0.07       0  4993.7    0.05       0
  4997.7    0.07       0  5082.3   0.035       0  5113.6    0.07       0
  5215.6   0.035       0  5314.3    0.07       0  5413.0    0.12       0
Bank Sta=4993.7,4997.7
Exp/Cntr=0.3,0.1

Chan Stop Cuts=-1