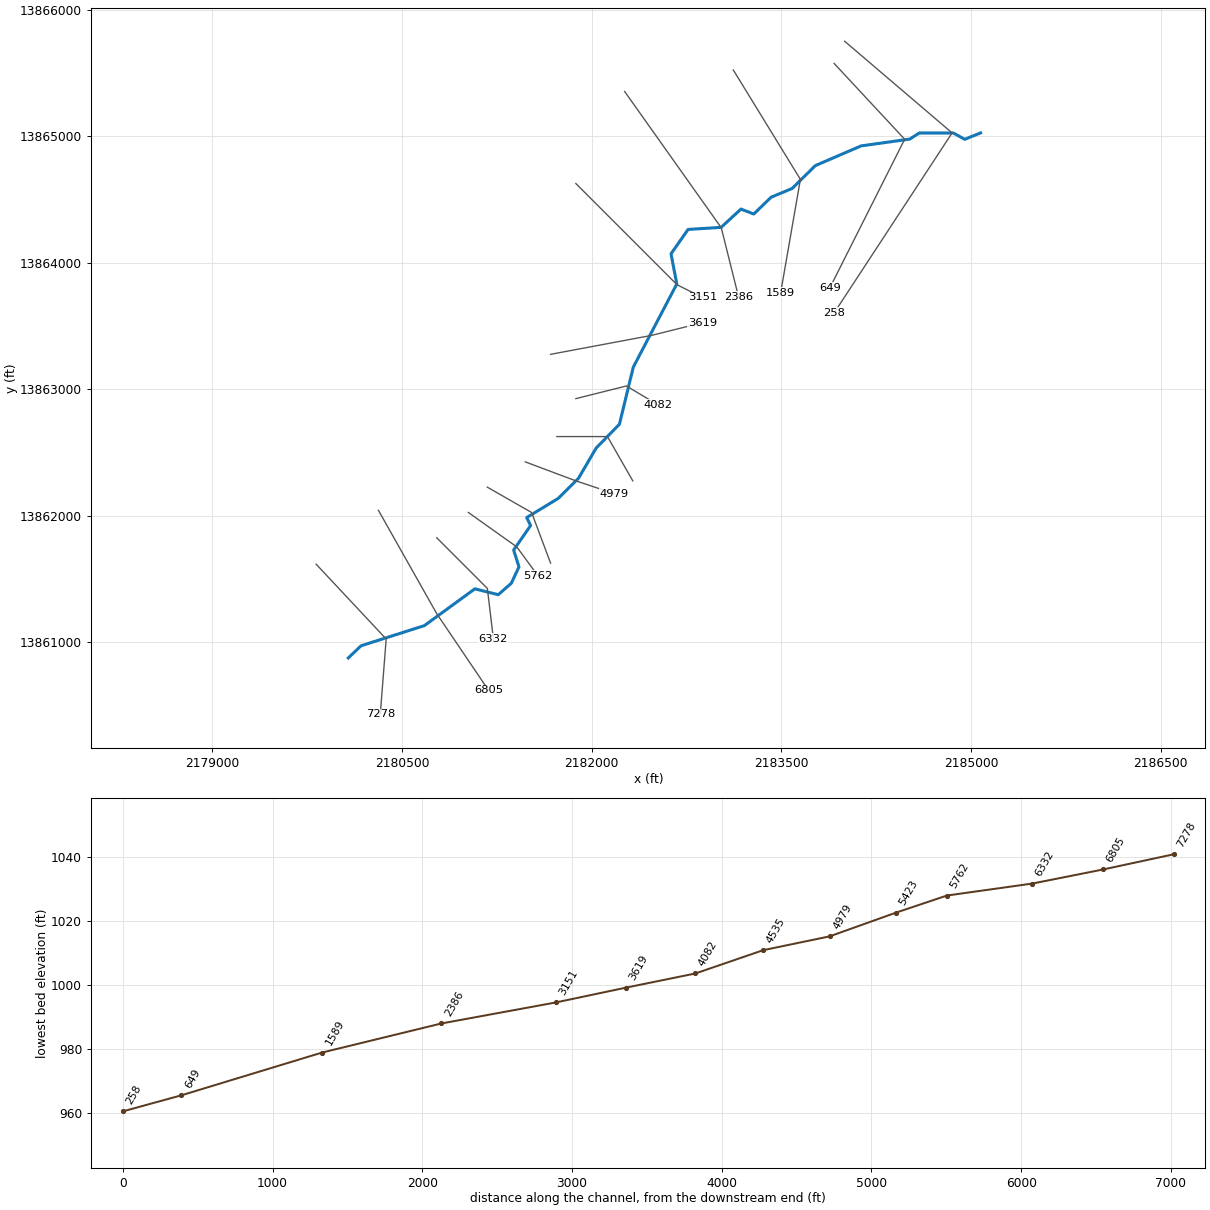
--- Jentsch Tributary 4.prj (project) ---

Proj Title=Jentsch Tributary 4 Base Level Engineering
Current Plan=p01
Default Exp/Contr=0.3,0.1
English Units
Geom File=g01
Flow File=f01
Plan File=p01
BEGIN DESCRIPTION:
Jentsch Tributary 4
END DESCRIPTION:

--- Jentsch Tributary 4.p01 (plan) ---

Plan Title=Multiple Run
Short Identifier=Multiple
Geom File=g01
Flow File=f01
Subcritical Flow
K Sum by GR= 0
Std Step Tol= 0.01
Critical Tol= 0.01
Num of Std Step Trials= 20
Max Error Tol= 0.3
Flow Tol Ratio= 0.001
Split Flow NTrial= 30
Split Flow Tol= 0.02
Split Flow Ratio= 0.02
Log Output Level= 0
Friction Slope Method= 1
Unsteady Friction Slope Method= 2
Unsteady Bridges Friction Slope Method= 1
Parabolic Critical Depth
Global Vel Dist=  1 , 1 , 1
Global Log Level= 0
CheckData=True
Encroach Param= -1, 0, 0, 0
BEGIN DESCRIPTION:
Multiple Run
END DESCRIPTION:

--- Jentsch Tributary 4.f01 (steady flow) ---

Flow Title=Multiple
Number of Profiles=7
Profile Names=10-year,25-year,50-year,1pct_min,100-year,1pct_plu,500-year
River Rch & RM= Jentsch Tributar,Reach-1,7278
    1331    2309    3261    2232    4454    8886    8224
River Rch & RM= Jentsch Tributar,Reach-1,6805
    1977    3486    4975    3434    6851   13670   12872
Boundary for River Rch & Prof#=Jentsch Tributar,Reach-1,1
Up Type=0
Dn Type=3
Dn Slope=0.005
Boundary for River Rch & Prof#=Jentsch Tributar,Reach-1,2
Up Type=0
Dn Type=3
Dn Slope=0.005
Boundary for River Rch & Prof#=Jentsch Tributar,Reach-1,3
Up Type=0
Dn Type=3
Dn Slope=0.005
Boundary for River Rch & Prof#=Jentsch Tributar,Reach-1,4
Up Type=0
Dn Type=3
Dn Slope=0.005
Boundary for River Rch & Prof#=Jentsch Tributar,Reach-1,5
Up Type=0
Dn Type=3
Dn Slope=0.005
Boundary for River Rch & Prof#=Jentsch Tributar,Reach-1,6
Up Type=0
Dn Type=3
Dn Slope=0.005
Boundary for River Rch & Prof#=Jentsch Tributar,Reach-1,7
Up Type=0
Dn Type=3
Dn Slope=0.005

--- Jentsch Tributary 4.g01 (geometry) ---

Geom Title=Existing Conditions

River Reach=Jentsch Tributar,Reach-1
Reach XY= 30
      2180075.00     13860875.00      2180176.48     13860971.44
      2180677.29     13861130.84      2181076.50     13861421.54
      2181260.97     13861375.09      2181364.25     13861465.29
      2181425.10     13861595.10      2181383.04     13861728.32
      2181516.98     13861921.67      2181486.23     13861985.02
      2181734.68     13862135.76      2181895.38     13862294.84
      2182035.78     13862534.68      2182219.48     13862722.57
      2182328.83     13863173.42      2182673.20     13863831.11
      2182627.34     13864069.48      2182762.29     13864262.28
      2183023.54     13864278.54      2183180.64     13864423.23
      2183281.73     13864384.15      2183418.94     13864516.86
      2183584.68     13864585.76      2183768.94     13864766.86
      2184130.53     13864922.61      2184515.34     13864976.38
      2184590.22     13865024.48      2184859.79     13865024.46
      2184950.00     13864974.53      2185075.00     13865025.00

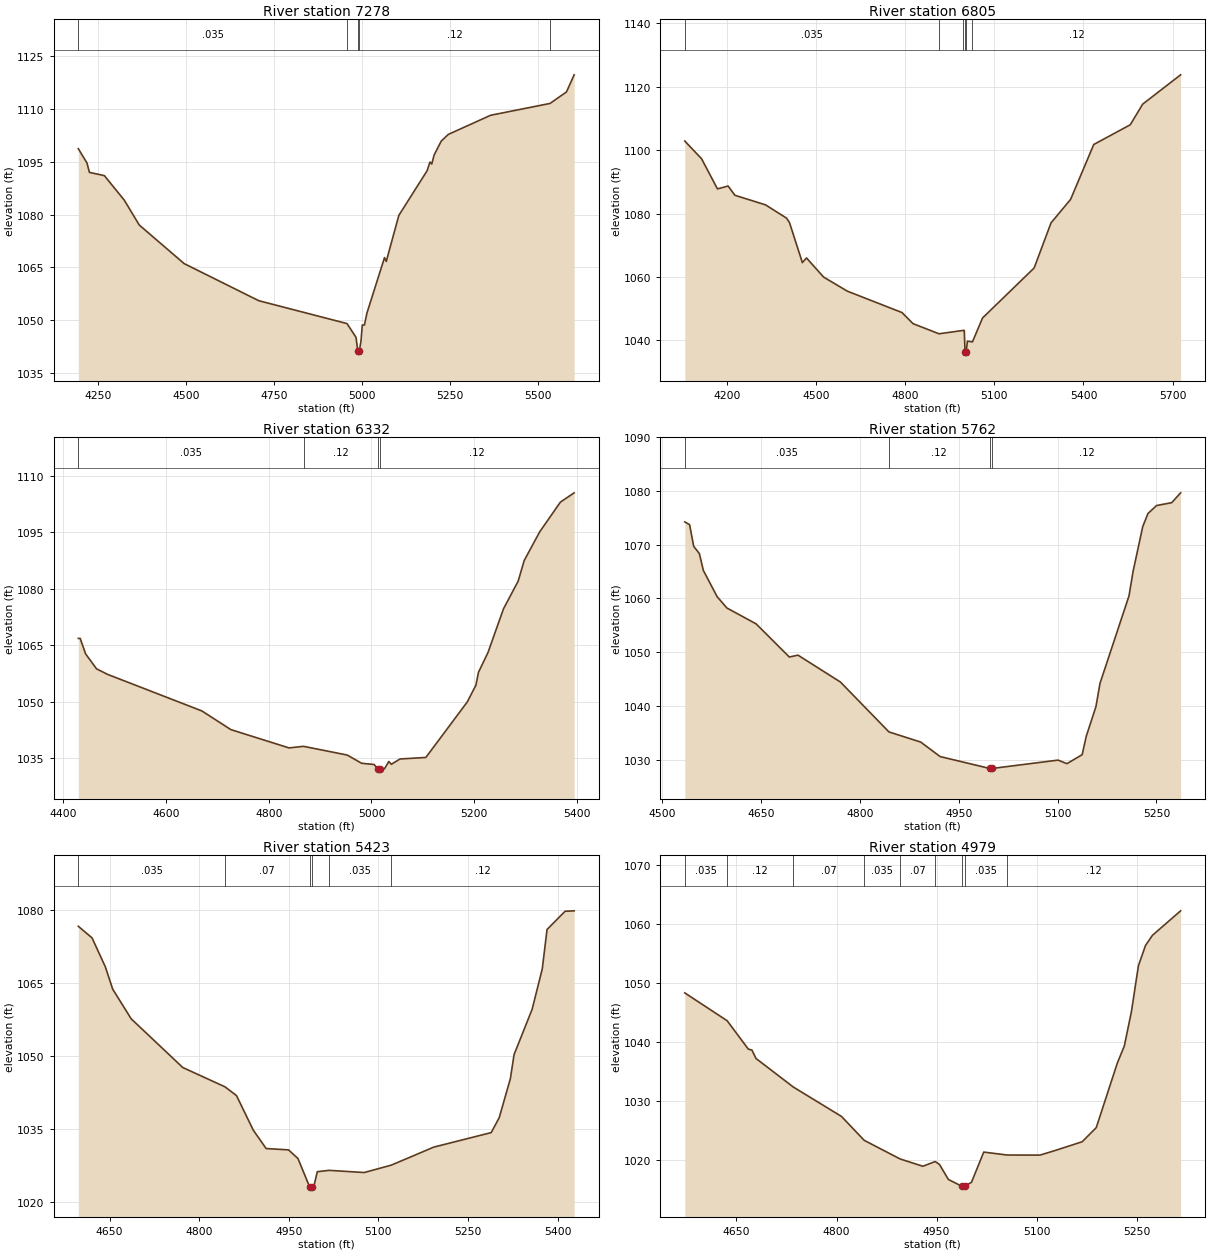
Type RM Length L Ch R = 1,7278,473,473,473
BEGIN DESCRIPTION:
Jentsch Tributary 4 13.0
END DESCRIPTION:
XS GIS Cut Line= 3
      2179821.37     13861616.08      2180375.00     13861025.00
      2180328.26     13860428.60
#Sta/Elev= 30
  4195.1 1098.63  4219.7 1094.58  4226.6 1091.93  4269.1 1091.01  4325.7 1084.05
  4368.2 1077.02  4495.7 1066.09  4707.7 1055.58  4958.1 1049.11  4983.7 1045.21
  4989.0 1041.24  4989.3 1040.74  4993.0 1041.24  4997.9 1044.24  5001.5 1048.70
  5007.5 1048.70  5015.0 1052.17  5064.6 1067.79  5069.6 1066.71  5105.3 1079.75
  5185.5 1092.38  5193.7 1094.85  5198.8 1094.30  5205.6 1096.87  5225.6 1100.77
  5245.7 1102.68  5366.1 1108.11  5534.5 1111.45  5581.3 1114.70  5603.2 1119.56
#Mann=5,-1,0
  4195.1   0.035       0  4958.1    0.12       0  4989.0    0.05       0
  4993.0    0.12       0  5534.5    0.07       0
Bank Sta=4989,4993
Exp/Cntr=0.3,0.1

Type RM Length L Ch R = 1,6805,473,473,473
BEGIN DESCRIPTION:
Jentsch Tributary 4 12.0
END DESCRIPTION:
XS GIS Cut Line= 3
      2180313.71     13862041.92      2180775.00     13861225.00
      2181184.76     13860618.99
#Sta/Elev= 30
  4057.4 1102.88  4113.9 1097.30  4167.4 1087.79  4203.2 1088.70  4226.1 1085.78
  4329.2 1082.76  4399.9 1078.58  4409.9 1077.19  4453.3 1064.54  4467.3 1066.01
  4524.7 1059.99  4605.1 1055.52  4788.8 1048.79  4825.9 1045.29  4913.6 1042.09
  4995.5 1043.16  4998.6 1043.16  5001.0 1036.49  5001.2 1035.99  5005.1 1036.49
  5009.1 1039.76  5026.1 1039.54  5060.0 1047.07  5233.8 1062.84  5290.7 1077.07
  5356.6 1084.48  5434.6 1101.80  5557.4 1108.01  5599.4 1114.53  5727.1 1123.77
#Mann=6,-1,0
  4057.4   0.035       0  4913.6    0.12       0  4995.5    0.12       0
  5001.0    0.05       0  5005.1    0.12       0  5026.1    0.12       0
Bank Sta=5001,5005.1
Exp/Cntr=0.3,0.1

Type RM Length L Ch R = 1,6332,570,570,570
BEGIN DESCRIPTION:
Jentsch Tributary 4 11.0
END DESCRIPTION:
XS GIS Cut Line= 3
      2180774.97     13861825.03      2181175.00     13861425.00
      2181222.56     13861028.37
#Sta/Elev= 30
  4429.4 1066.81  4433.0 1066.81  4443.6 1062.70  4464.8 1058.75  4486.0 1057.29
  4669.9 1047.57  4726.4 1042.61  4839.6 1037.76  4867.8 1038.18  4952.7 1035.87
  4981.0 1033.68  5005.2 1033.36  5013.2 1032.10  5013.5 1031.60  5017.4 1032.10
  5025.3 1032.21  5033.8 1034.15  5038.8 1033.41  5055.6 1034.82  5105.9 1035.23
  5186.5 1049.95  5203.4 1054.41  5208.4 1057.84  5226.8 1063.05  5257.0 1074.65
  5285.6 1082.01  5297.3 1087.46  5327.5 1095.08  5367.8 1102.97  5394.6 1105.44
#Mann=4,-1,0
  4429.4   0.035       0  4867.8    0.12       0  5013.2    0.05       0
  5017.4    0.12       0
Bank Sta=5013.2,5017.4
Exp/Cntr=0.3,0.1

Type RM Length L Ch R = 1,5762,339,339,339
BEGIN DESCRIPTION:
Jentsch Tributary 4 10.0
END DESCRIPTION:
XS GIS Cut Line= 3
      2181025.04     13862024.97      2181407.65     13861753.27
      2181574.99     13861525.01
#Sta/Elev= 30
  4534.4 1074.24  4541.7 1073.72  4547.9 1069.70  4556.5 1068.35  4562.6 1065.20
  4583.5 1060.32  4598.3 1058.22  4642.6 1055.27  4693.0 1049.10  4706.1 1049.45
  4770.5 1044.45  4844.2 1035.16  4892.3 1033.28  4921.8 1030.58  4996.9 1028.37
  4997.1 1027.87  5001.1 1028.37  5100.7 1029.92  5114.2 1029.26  5137.3 1030.93
  5143.5 1034.35  5158.2 1039.86  5164.4 1044.21  5208.4 1060.48  5214.6 1065.05
  5229.2 1073.35  5237.1 1075.79  5250.1 1077.28  5273.2 1077.82  5286.7 1079.65
#Mann=4,-1,0
  4534.4   0.035       0  4844.2    0.12       0  4996.9    0.05       0
  5001.1    0.12       0
Bank Sta=4996.9,5001.1
Exp/Cntr=0.3,0.1

Type RM Length L Ch R = 1,5423,444,444,444
BEGIN DESCRIPTION:
Jentsch Tributary 4 9.0
END DESCRIPTION:
XS GIS Cut Line= 3
      2181175.04     13862224.98      2181525.00     13862025.00
      2181675.01     13861624.97
#Sta/Elev= 30
  4597.5 1076.72  4620.5 1074.33  4642.8 1068.35  4655.0 1063.78  4686.0 1057.66
  4772.4 1047.62  4843.1 1043.64  4862.4 1041.83  4890.4 1034.73  4912.0 1030.92
  4949.5 1030.65  4965.3 1028.87  4984.7 1023.06  4985.0 1022.56  4989.0 1023.06
  4992.6 1023.50  4997.7 1026.15  5017.6 1026.43  5076.2 1025.98  5121.5 1027.50
  5192.8 1031.22  5288.9 1034.21  5302.3 1037.28  5321.0 1045.32  5327.2 1050.29
  5357.5 1059.64  5374.4 1067.95  5382.4 1076.06  5412.6 1079.82  5427.8 1079.91
#Mann=6,-1,0
  4597.5   0.035       0  4843.1    0.07       0  4984.7    0.05       0
  4989.0    0.07       0  5017.6   0.035       0  5121.5    0.12       0
Bank Sta=4984.7,4989
Exp/Cntr=0.3,0.1

Type RM Length L Ch R = 1,4979,444,444,444
BEGIN DESCRIPTION:
Jentsch Tributary 4 8.0
END DESCRIPTION:
XS GIS Cut Line= 3
      2181474.95     13862425.02      2181875.00     13862275.00
      2182175.02     13862174.99
#Sta/Elev= 30
  4572.5 1048.36  4636.0 1043.65  4667.8 1038.84  4673.1 1038.69  4679.3 1037.26
  4735.1 1032.44  4807.5 1027.45  4841.5 1023.41  4895.3 1020.26  4929.4 1019.02
  4948.0 1019.82  4954.4 1019.33  4967.7 1016.79  4987.7 1015.65  4988.0 1015.15
  4992.3 1015.65  5002.4 1016.31  5020.8 1021.42  5056.1 1020.92  5105.2 1020.91
  5126.2 1021.63  5168.4 1023.17  5189.5 1025.56  5221.1 1036.49  5231.6 1039.38
  5242.2 1045.17  5252.7 1052.94  5263.3 1056.38  5273.8 1058.11  5316.0 1062.25
#Mann=9,-1,0
  4572.5   0.035       0  4636.0    0.12       0  4735.1    0.07       0
  4841.5   0.035       0  4895.3    0.07       0  4948.0   0.035       0
  4987.7   0.035       0  4992.3   0.035       0  5056.1    0.12       0
Bank Sta=4987.7,4992.3
Exp/Cntr=0.3,0.1

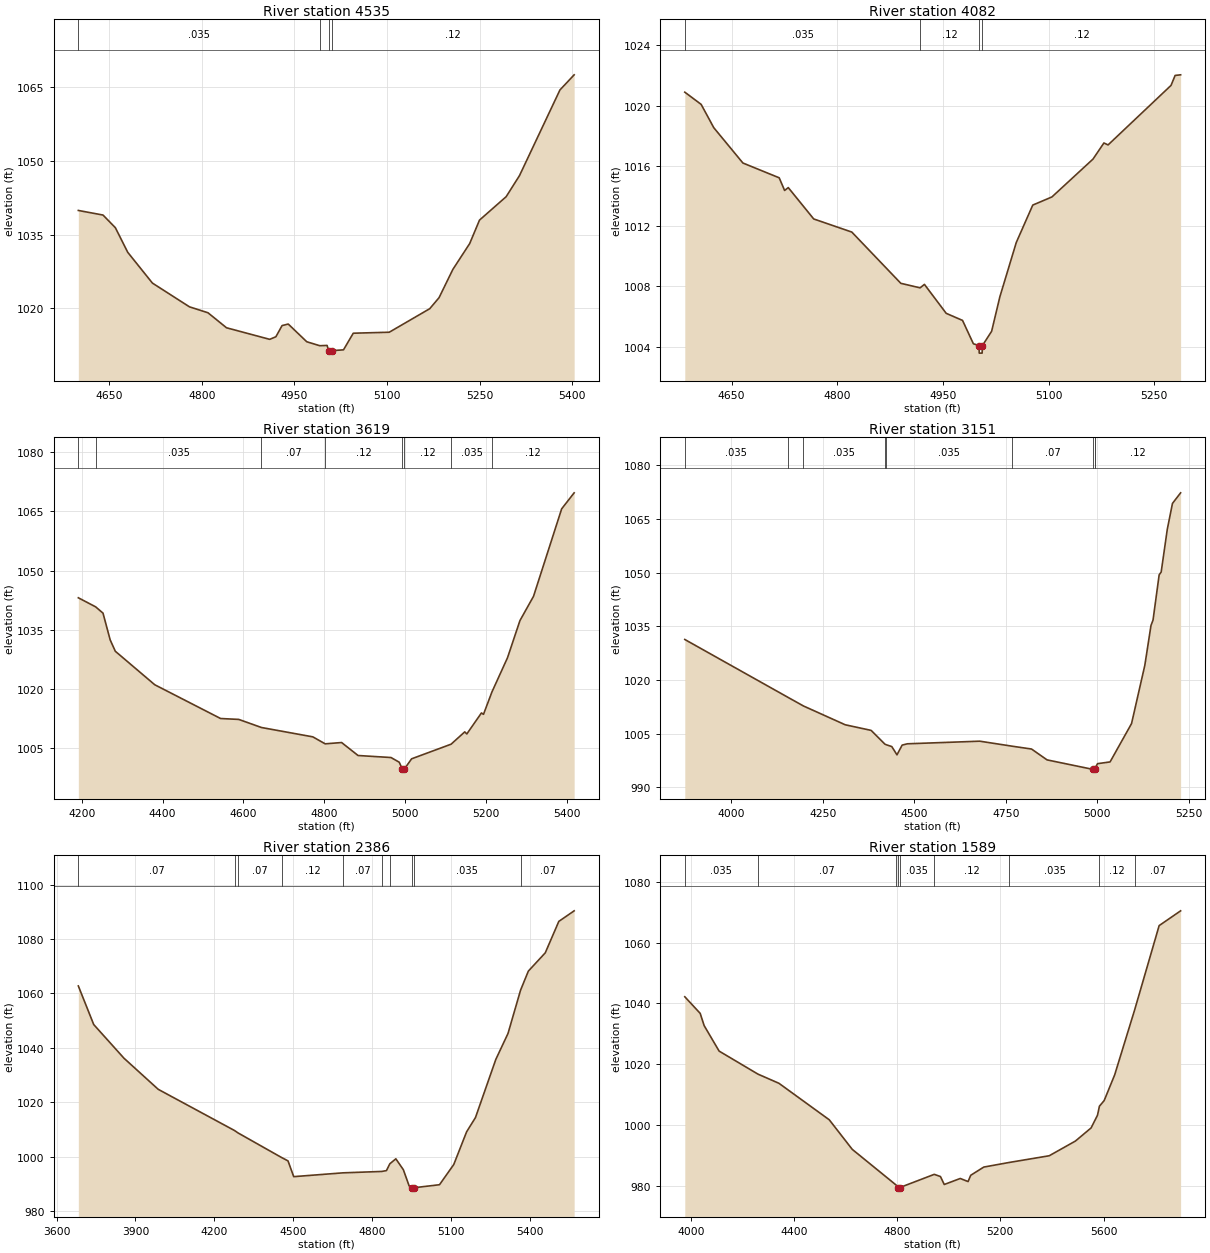
Type RM Length L Ch R = 1,4535,453,453,453
BEGIN DESCRIPTION:
Jentsch Tributary 4 7.0
END DESCRIPTION:
XS GIS Cut Line= 3
      2181725.01     13862625.00      2182125.00     13862625.00
      2182325.00     13862275.00
#Sta/Elev= 30
  4600.0 1039.93  4640.0 1038.99  4660.0 1036.41  4680.0 1031.40  4720.0 1025.12
  4780.0 1020.28  4810.0 1019.07  4840.0 1016.01  4910.0 1013.65  4920.0 1014.18
  4930.0 1016.45  4940.0 1016.77  4970.0 1013.16  4991.1 1012.35  5002.9 1012.41
  5005.6 1011.34  5005.9 1010.84  5010.2 1011.34  5029.5 1011.51  5045.3 1014.90
  5103.6 1015.10  5169.2 1019.90  5184.3 1022.15  5206.6 1027.90  5233.9 1033.18
  5249.8 1037.96  5293.0 1042.74  5314.6 1047.04  5380.1 1064.50  5403.1 1067.58
#Mann=4,-1,0
  4600.0   0.035       0  4991.1    0.12       0  5005.6    0.05       0
  5010.2    0.12       0
Bank Sta=5005.6,5010.2
Exp/Cntr=0.3,0.1

Type RM Length L Ch R = 1,4082,463,463,463
BEGIN DESCRIPTION:
Jentsch Tributary 4 6.0
END DESCRIPTION:
XS GIS Cut Line= 3
      2181874.99     13862925.00      2182275.00     13863025.00
      2182525.02     13862874.99
#Sta/Elev= 30
  4583.5 1020.89  4606.7 1020.08  4624.7 1018.53  4666.0 1016.19  4717.5 1015.21
  4725.2 1014.37  4730.4 1014.56  4766.5 1012.48  4820.6 1011.61  4890.2 1008.21
  4917.6 1007.91  4923.7 1008.14  4954.6 1006.22  4977.8 1005.75  4993.2 1004.20
  5001.2 1004.08  5001.5 1003.58  5005.6 1003.58  5006.0 1004.08  5019.1 1005.03
  5030.8 1007.32  5054.1 1010.92  5077.5 1013.40  5104.7 1013.94  5163.0 1016.45
  5178.5 1017.52  5184.4 1017.39  5273.8 1021.34  5279.6 1022.00  5287.4 1022.04
#Mann=4,-1,0
  4583.5   0.035       0  4917.6    0.12       0  5001.2    0.05       0
  5006.0    0.12       0
Bank Sta=5001.2,5006
Exp/Cntr=0.3,0.1

Type RM Length L Ch R = 1,3619,468,468,468
BEGIN DESCRIPTION:
Jentsch Tributary 4 5.0
END DESCRIPTION:
XS GIS Cut Line= 3
      2181675.03     13863275.01      2182475.00     13863425.00
      2182874.98     13863525.00
#Sta/Elev= 30
  4191.7 1043.12  4234.4 1040.83  4252.7 1039.23  4270.5 1032.43  4283.2 1029.56
  4380.7 1021.07  4543.5 1012.51  4588.5 1012.28  4644.6 1010.23  4771.6 1007.86
  4802.2 1006.09  4842.8 1006.42  4883.5 1003.13  4964.9 1002.62  4985.3 1001.43
  4993.0  999.67  4993.4  999.17  4997.8  999.67  5015.9 1002.29  5113.6 1006.00
  5147.3 1009.12  5152.5 1008.60  5188.6 1013.92  5193.7 1013.57  5214.4 1019.20
  5253.0 1027.90  5283.9 1037.35  5317.4 1043.49  5387.0 1065.67  5417.9 1069.73
#Mann=8,-1,0
  4191.7    0.07       0  4234.4   0.035       0  4644.6    0.07       0
  4802.2    0.12       0  4993.0    0.05       0  4997.8    0.12       0
  5113.6   0.035       0  5214.4    0.12       0
Bank Sta=4993,4997.8
Exp/Cntr=0.3,0.1

Type RM Length L Ch R = 1,3151,765,765,765
BEGIN DESCRIPTION:
Jentsch Tributary 4 4.0
END DESCRIPTION:
XS GIS Cut Line= 3
      2181875.03     13864624.97      2182675.00     13863825.00
      2182874.97     13863725.02
#Sta/Elev= 30
  3872.8 1031.32  4154.6 1015.17  4197.1 1012.75  4311.2 1007.50  4381.9 1005.94
  4419.3 1002.12  4423.2 1001.93  4438.4 1001.42  4452.6  999.11  4466.7 1001.82
  4480.9 1002.19  4678.9 1002.92  4766.8 1001.53  4820.3 1000.73  4862.7  997.70
  4987.5  995.06  4987.9  994.56  4992.4  995.06  4992.5  995.08  5000.6  996.64
  5034.9  997.13  5093.6 1007.84  5129.9 1024.12  5146.7 1035.22  5152.3 1036.73
  5169.0 1049.34  5174.6 1050.17  5191.4 1062.17  5205.4 1069.31  5227.7 1072.27
#Mann=9,-1,0
  3872.8   0.035       0  4154.6    0.07       0  4197.1   0.035       0
  4419.3    0.12       0  4423.2   0.035       0  4766.8    0.07       0
  4987.5    0.05       0  4992.4    0.07       0  4992.5    0.12       0
Bank Sta=4987.5,4992.4
Exp/Cntr=0.3,0.1

Type RM Length L Ch R = 1,2386,797,797,797
BEGIN DESCRIPTION:
Jentsch Tributary 4 3.0
END DESCRIPTION:
XS GIS Cut Line= 3
      2182260.74     13865352.70      2183025.00     13864275.00
      2183161.52     13863728.48
#Sta/Elev= 30
  3682.8 1062.74  3741.3 1048.54  3856.1 1036.17  3986.5 1024.71  4276.8 1009.54
  4289.1 1008.71  4456.0  999.59  4479.8  998.38  4501.4  992.59  4688.8  993.99
  4835.5  994.50  4853.9  994.81  4866.7  997.32  4889.6  999.15  4918.2  995.13
  4940.0  989.21  4951.9  988.50  4952.3  988.00  4957.7  988.50  5055.5  989.62
  5109.7  997.05  5158.6 1009.09  5192.2 1014.32  5269.5 1035.70  5315.9 1045.27
  5363.6 1061.18  5393.2 1068.19  5457.5 1074.92  5509.0 1086.48  5567.3 1090.37
#Mann=10,-1,0
  3682.8    0.07       0  4276.8    0.12       0  4289.1    0.07       0
  4456.0    0.12       0  4688.8    0.07       0  4835.5    0.12       0
  4866.7   0.035       0  4951.9    0.05       0  4957.7   0.035       0
  5363.6    0.07       0
Bank Sta=4951.9,4957.7
Exp/Cntr=0.3,0.1

Type RM Length L Ch R = 1,1589,940,940,940
BEGIN DESCRIPTION:
Jentsch Tributary 4 2.0
END DESCRIPTION:
XS GIS Cut Line= 3
      2183119.89     13865522.66      2183650.43     13864658.06
      2183494.61     13863762.92
#Sta/Elev= 30
  3976.1 1042.18  4035.8 1036.72  4051.2 1032.69  4109.2 1024.32  4260.0 1016.74
  4341.3 1013.73  4536.6 1001.72  4625.5  992.02  4795.0  980.33  4803.4  979.44
  4803.9  978.94  4809.3  979.44  4943.7  983.80  4967.7  983.07  4982.4  980.46
  5044.4  982.44  5074.8  981.43  5085.0  983.49  5135.7  986.19  5235.2  987.72
  5389.5  989.91  5491.0  994.74  5551.9  999.06  5576.7 1003.23  5584.2 1006.20
  5602.6 1008.06  5643.2 1016.47  5720.8 1037.86  5815.8 1065.57  5899.1 1070.43
#Mann=9,-1,0
  3976.1   0.035       0  4260.0    0.07       0  4795.0   0.035       0
  4803.4    0.05       0  4809.3   0.035       0  4943.7    0.12       0
  5235.2   0.035       0  5584.2    0.12       0  5720.8    0.07       0
Bank Sta=4803.4,4809.3
Exp/Cntr=0.3,0.1

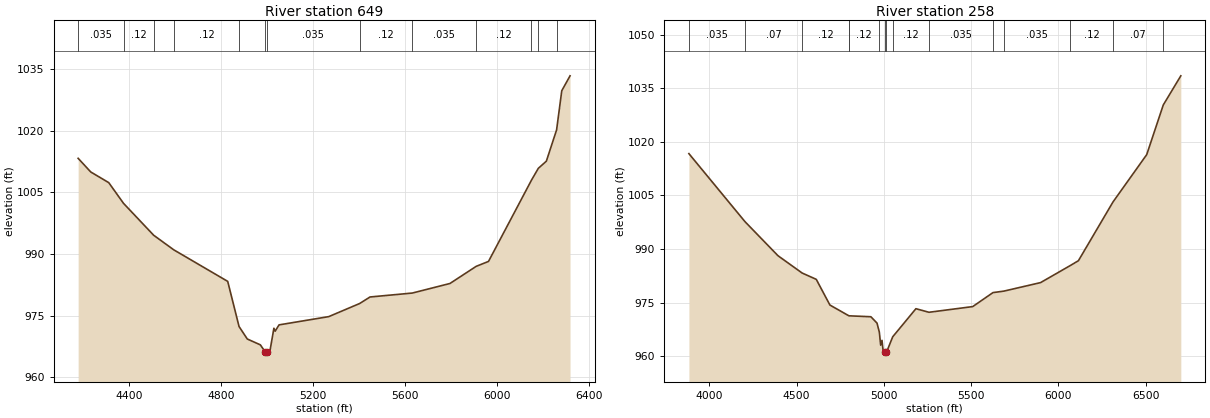
Type RM Length L Ch R = 1,649,391,391,391
BEGIN DESCRIPTION:
Jentsch Tributary 4 1.0
END DESCRIPTION:
XS GIS Cut Line= 3
      2183917.07     13865574.51      2184475.00     13864975.00
      2183883.01     13863799.63
#Sta/Elev= 30
  4180.6 1013.28  4235.2 1009.96  4313.4 1007.36  4377.7 1002.31  4508.5  994.55
  4595.7  991.00  4829.8  983.32  4879.0  972.33  4914.8  969.29  4971.5  967.87
  4993.0  966.11  4993.5  965.61  4999.2  966.11  5013.5  966.51  5030.2  971.91
  5035.8  971.20  5052.5  972.73  5268.3  974.74  5402.4  977.93  5447.4  979.52
  5631.2  980.48  5794.5  982.81  5908.2  986.98  5961.7  988.18  6148.0 1007.94
  6177.7 1010.83  6212.8 1012.59  6257.2 1020.20  6279.7 1029.74  6315.6 1033.36
#Mann=13,-1,0
  4180.6   0.035       0  4377.7    0.12       0  4508.5    0.07       0
  4595.7    0.12       0  4879.0   0.035       0  4993.0   0.035       0
  4999.2   0.035       0  5402.4    0.12       0  5631.2   0.035       0
  5908.2    0.12       0  6148.0    0.07       0  6177.7    0.12       0
  6257.2    0.07       0
Bank Sta=4993,4999.2
Exp/Cntr=0.3,0.1

Type RM Length L Ch R = 1,258,0,0,0
BEGIN DESCRIPTION:
Jentsch Tributary 4 0.1
END DESCRIPTION:
XS GIS Cut Line= 3
      2184000.03     13865749.98      2184850.09     13865025.19
      2183916.66     13863601.51
#Sta/Elev= 30
  3882.9 1016.70  4203.9  997.69  4393.4  988.14  4531.7  983.30  4613.0  981.52
  4691.1  974.34  4798.5  971.36  4800.6  971.32  4926.0  971.06  4961.1  969.28
  4974.5  966.73  4982.0  963.11  4989.7  964.46  4996.2  961.48  5009.1  961.10
  5009.6  960.60  5015.3  961.10  5051.1  965.45  5184.1  973.31  5259.0  972.31
  5509.6  973.90  5625.6  977.81  5689.0  978.24  5898.4  980.61  6068.7  985.38
  6115.5  986.74  6313.7 1003.18  6506.9 1016.42  6602.0 1030.33  6702.4 1038.47
#Mann=15,-1,0
  3882.9   0.035       0  4203.9    0.07       0  4531.7    0.12       0
  4798.5   0.035       0  4800.6    0.12       0  4974.5   0.035       0
  5009.1   0.035       0  5015.3   0.035       0  5051.1    0.12       0
  5259.0   0.035       0  5625.6    0.12       0  5689.0   0.035       0
  6068.7    0.12       0  6313.7    0.07       0  6602.0    0.12       0
Bank Sta=5009.1,5015.3
Exp/Cntr=0.3,0.1

Chan Stop Cuts=-1