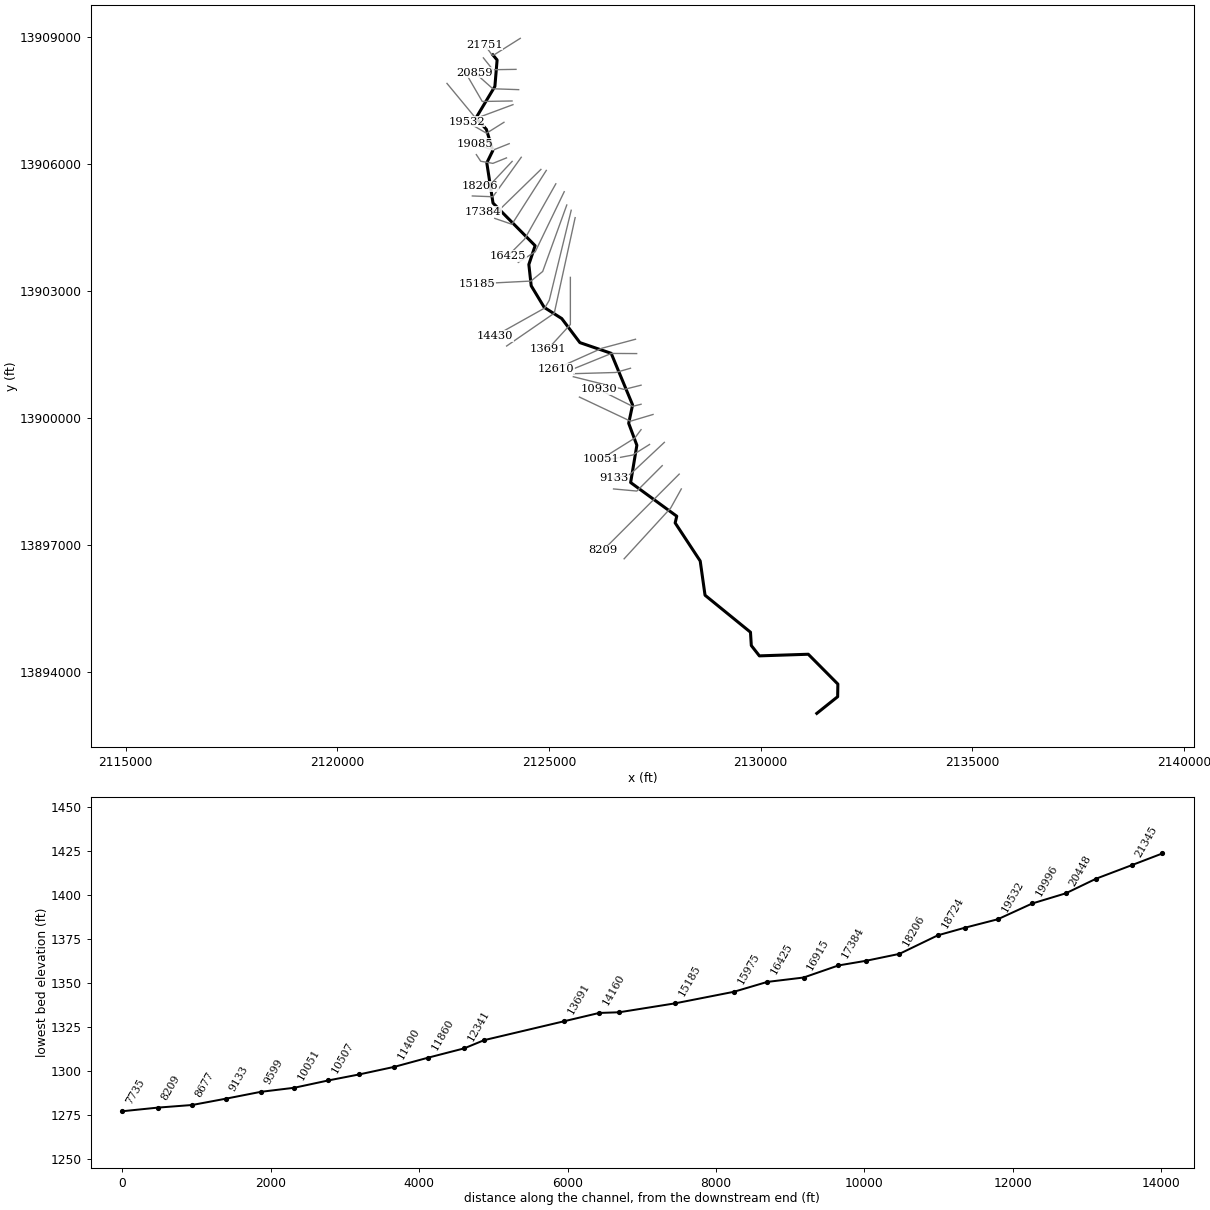
--- KRAUSE CREEK.prj (project) ---

Proj Title=KRAUSE CREEK Base Level Engineering
Current Plan=p01
Default Exp/Contr=0.3,0.1
English Units
Geom File=g01
Flow File=f01
Plan File=p01
BEGIN DESCRIPTION:
KRAUSE CREEK
END DESCRIPTION:

--- KRAUSE CREEK.p01 (plan) ---

Plan Title=Multiple Run
Short Identifier=Multiple
Geom File=g01
Flow File=f01
Subcritical Flow
K Sum by GR= 0
Std Step Tol= 0.01
Critical Tol= 0.01
Num of Std Step Trials= 20
Max Error Tol= 0.3
Flow Tol Ratio= 0.001
Split Flow NTrial= 30
Split Flow Tol= 0.02
Split Flow Ratio= 0.02
Log Output Level= 0
Friction Slope Method= 1
Unsteady Friction Slope Method= 2
Unsteady Bridges Friction Slope Method= 1
Parabolic Critical Depth
Global Vel Dist=  1 , 1 , 1
Global Log Level= 0
CheckData=True
Encroach Param= -1, 0, 0, 0
BEGIN DESCRIPTION:
Multiple Run
END DESCRIPTION:

--- KRAUSE CREEK.f01 (steady flow) ---

Flow Title=Multiple
Number of Profiles=7
Profile Names=10-year,25-year,50-year,1pct_min,100-year,1pct_plu,500-year
River Rch & RM= KRAUSE CREEK,Reach-1,21751
     786    1317    1819    1222    2438    4864    4322
River Rch & RM= KRAUSE CREEK,Reach-1,21345
    1082    1844    2576    1747    3485    6953    6304
River Rch & RM= KRAUSE CREEK,Reach-1,17760
    2323    4136    5946    4137    8255   16471   15748
River Rch & RM= KRAUSE CREEK,Reach-1,15185
    2685    4804    6928    4832    9641   19236   18484
River Rch & RM= KRAUSE CREEK,Reach-1,12610
    4349    7926   11573    8156   16274   32470   31868
River Rch & RM= KRAUSE CREEK,Reach-1,5932
    4894    8959   13117    9267   18491   36894   36390
River Rch & RM= KRAUSE CREEK,Reach-1,4111
    5293    9715   14249   10082   20116   40136   39704
River Rch & RM= KRAUSE CREEK,Reach-1,1425
    5390    9887   14495   10249   20449   40801   40311
Boundary for River Rch & Prof#=KRAUSE CREEK,Reach-1,1
Up Type=0
Dn Type=3
Dn Slope=0.005
Boundary for River Rch & Prof#=KRAUSE CREEK,Reach-1,2
Up Type=0
Dn Type=3
Dn Slope=0.005
Boundary for River Rch & Prof#=KRAUSE CREEK,Reach-1,3
Up Type=0
Dn Type=3
Dn Slope=0.005
Boundary for River Rch & Prof#=KRAUSE CREEK,Reach-1,4
Up Type=0
Dn Type=3
Dn Slope=0.005
Boundary for River Rch & Prof#=KRAUSE CREEK,Reach-1,5
Up Type=0
Dn Type=3
Dn Slope=0.005
Boundary for River Rch & Prof#=KRAUSE CREEK,Reach-1,6
Up Type=0
Dn Type=3
Dn Slope=0.005
Boundary for River Rch & Prof#=KRAUSE CREEK,Reach-1,7
Up Type=0
Dn Type=3
Dn Slope=0.005

--- KRAUSE CREEK.g01 (geometry) ---

Geom Title=Existing Conditions

River Reach=KRAUSE CREEK,Reach-1
Reach XY= 30
      2123675.00     13908575.00      2123775.22     13908454.95
      2123722.94     13907830.86      2123276.19     13907085.50
      2123521.84     13906816.66      2123673.90     13906314.45
      2123532.03     13906025.21      2123678.55     13905076.47
      2124673.02     13904069.33      2124525.00     13903625.00
      2124580.46     13903122.55      2124888.62     13902611.76
      2125301.82     13902348.70      2125730.47     13901780.26
      2126469.28     13901527.58      2126974.63     13900309.73
      2126882.59     13899875.01      2127075.43     13899356.67
      2126928.55     13898476.47      2128017.50     13897681.05
      2127980.09     13897522.70      2128571.46     13896623.54
      2128685.52     13895815.21      2129758.54     13894941.75
      2129778.34     13894626.72      2129968.94     13894383.14
      2131123.50     13894421.39      2131822.07     13893717.03
      2131817.19     13893418.81      2131325.00     13893025.00

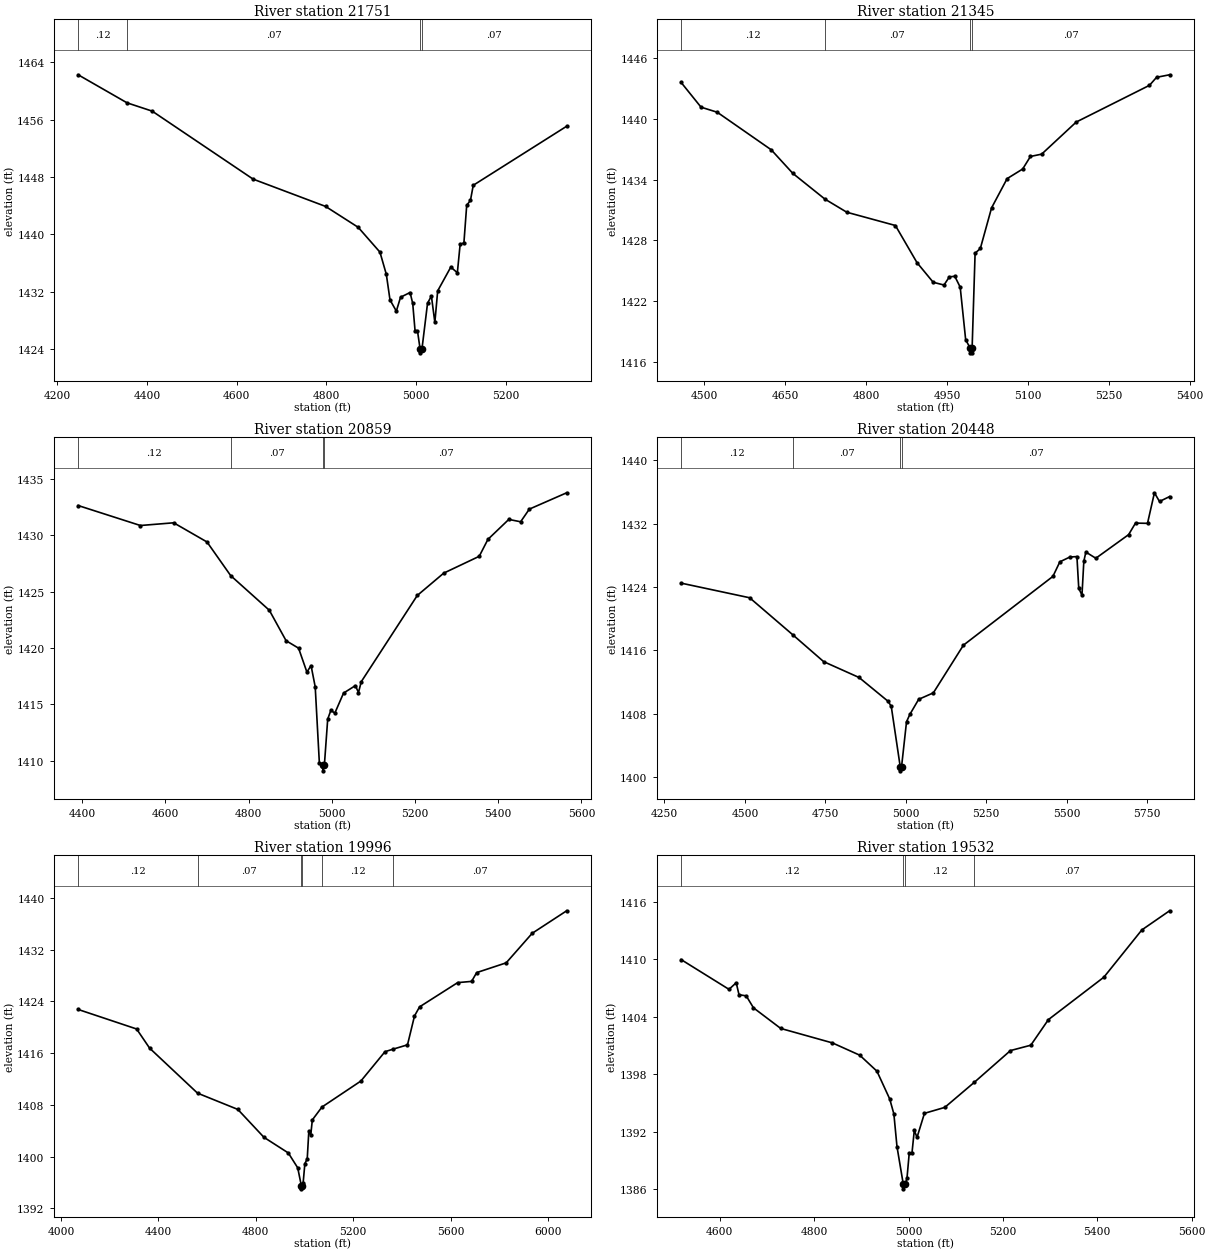
Type RM Length L Ch R = 1,21751,406,406,406
BEGIN DESCRIPTION:
KRAUSE CREEK 41.0
END DESCRIPTION:
XS GIS Cut Line= 4
      2124322.67     13908965.90      2123685.59     13908564.48
      2123660.64     13908568.13      2123475.48     13908816.61
#Sta/Elev= 30
  4247.0 1462.28  4355.9 1458.36  4411.9 1457.20  4636.7 1447.70  4798.0 1443.89
  4870.7 1440.97  4919.2 1437.50  4933.4 1434.40  4941.6 1430.82  4955.7 1429.26
  4965.1 1431.20  4986.3 1431.86  4992.2 1430.33  4997.4 1426.50  5002.8 1426.50
  5008.7 1423.93  5009.0 1423.43  5012.7 1423.93  5025.2 1430.36  5033.8 1431.37
  5041.5 1427.67  5047.8 1432.09  5077.0 1435.41  5091.6 1434.62  5097.8 1438.59
  5106.2 1438.79  5112.4 1444.03  5120.8 1444.74  5127.0 1446.84  5335.1 1455.09
#Mann=4,-1,0
  4247.0    0.12       0  4355.9    0.07       0  5008.7    0.05       0
  5012.7    0.07       0
Bank Sta=5008.7,5012.7
Exp/Cntr=0.3,0.1

Type RM Length L Ch R = 1,21345,486,486,486
BEGIN DESCRIPTION:
KRAUSE CREEK 40.0
END DESCRIPTION:
XS GIS Cut Line= 3
      2124221.99     13908233.23      2123675.00     13908225.00
      2123451.13     13908504.05
#Sta/Elev= 30
  4457.2 1443.60  4494.2 1441.15  4524.2 1440.65  4624.2 1436.94  4664.2 1434.61
  4723.6 1432.07  4764.2 1430.77  4854.2 1429.46  4894.2 1425.79  4924.2 1423.85
  4944.2 1423.58  4954.2 1424.39  4964.2 1424.44  4974.2 1423.37  4984.3 1418.19
  4992.3 1417.38  4992.5 1416.88  4996.0 1416.88  4996.3 1417.38  5001.8 1426.72
  5011.5 1427.19  5032.3 1431.20  5061.1 1434.09  5089.9 1435.04  5104.3 1436.28
  5125.1 1436.51  5189.1 1439.68  5324.8 1443.31  5337.9 1444.10  5362.0 1444.35
#Mann=4,-1,0
  4457.2    0.12       0  4723.6    0.07       0  4992.3    0.05       0
  4996.3    0.07       0
Bank Sta=4992.3,4996.3
Exp/Cntr=0.3,0.1

Type RM Length L Ch R = 1,20859,411,411,411
BEGIN DESCRIPTION:
KRAUSE CREEK 39.0
END DESCRIPTION:
XS GIS Cut Line= 3
      2124284.48     13907754.06      2123675.00     13907775.00
      2123253.18     13908149.92
#Sta/Elev= 30
  4390.2 1432.63  4539.8 1430.86  4619.8 1431.10  4699.9 1429.40  4756.8 1426.42
  4849.7 1423.35  4890.0 1420.65  4920.0 1419.99  4940.0 1417.87  4950.0 1418.45
  4960.0 1416.56  4970.0 1409.79  4978.0 1409.62  4978.3 1409.12  4982.0 1409.62
  4990.0 1413.70  4997.5 1414.47  5007.2 1414.24  5028.1 1416.01  5056.5 1416.67
  5064.0 1416.06  5070.7 1417.02  5205.3 1424.66  5268.9 1426.64  5354.2 1428.13
  5375.1 1429.63  5425.3 1431.40  5453.7 1431.19  5474.6 1432.31  5564.4 1433.76
#Mann=4,-1,0
  4390.2    0.12       0  4756.8    0.07       0  4978.0    0.05       0
  4982.0    0.07       0
Bank Sta=4978,4982
Exp/Cntr=0.3,0.1

Type RM Length L Ch R = 1,20448,452,452,452
BEGIN DESCRIPTION:
KRAUSE CREEK 38.0
END DESCRIPTION:
XS GIS Cut Line= 3
      2124128.22     13907486.70      2123425.00     13907475.00
      2123015.97     13908180.02
#Sta/Elev= 30
  4301.5 1424.49  4514.7 1422.64  4648.3 1417.98  4744.8 1414.57  4854.8 1412.57
  4944.8 1409.57  4954.8 1408.93  4982.8 1401.28  4983.1 1400.78  4986.8 1401.28
  5002.3 1406.98  5012.7 1407.91  5040.0 1409.81  5085.7 1410.63  5179.1 1416.65
  5457.3 1425.34  5478.9 1427.18  5510.3 1427.79  5531.9 1427.84  5537.6 1423.84
  5547.6 1422.96  5553.4 1427.25  5559.7 1428.41  5590.7 1427.63  5692.5 1430.61
  5714.0 1432.07  5751.3 1432.04  5772.8 1435.90  5788.6 1434.80  5819.9 1435.42
#Mann=4,-1,0
  4301.5    0.12       0  4648.3    0.07       0  4982.8    0.05       0
  4986.8    0.07       0
Bank Sta=4982.8,4986.8
Exp/Cntr=0.3,0.1

Type RM Length L Ch R = 1,19996,464,464,464
BEGIN DESCRIPTION:
KRAUSE CREEK 37.0
END DESCRIPTION:
XS GIS Cut Line= 3
      2124149.96     13907399.99      2123275.00     13907075.00
      2122591.68     13907901.29
#Sta/Elev= 30
  4070.7 1422.75  4310.7 1419.73  4364.0 1416.77  4560.7 1409.81  4726.3 1407.29
  4833.4 1402.98  4933.5 1400.56  4972.1 1398.26  4986.9 1395.51  4987.1 1395.01
  4990.9 1395.51  4994.2 1395.84  5001.4 1398.89  5011.2 1399.67  5017.7 1403.94
  5025.6 1403.33  5032.1 1405.67  5071.6 1407.66  5231.4 1411.68  5330.4 1416.22
  5363.6 1416.61  5422.8 1417.28  5451.5 1421.74  5472.3 1423.15  5628.7 1426.90
  5686.0 1427.09  5706.8 1428.45  5828.0 1429.96  5934.8 1434.53  6076.3 1438.01
#Mann=6,-1,0
  4070.7    0.12       0  4560.7    0.07       0  4986.9    0.05       0
  4990.9    0.07       0  5071.6    0.12       0  5363.6    0.07       0
Bank Sta=4986.9,4990.9
Exp/Cntr=0.3,0.1

Type RM Length L Ch R = 1,19532,447,447,447
BEGIN DESCRIPTION:
KRAUSE CREEK 36.0
END DESCRIPTION:
XS GIS Cut Line= 3
      2123937.23     13906983.23      2123525.00     13906725.00
      2123050.00     13907000.00
#Sta/Elev= 30
  4517.9 1409.99  4619.5 1406.88  4634.8 1407.57  4640.7 1406.32  4656.0 1406.20
  4671.4 1404.95  4729.1 1402.80  4838.7 1401.29  4896.5 1400.01  4933.0 1398.34
  4960.1 1395.44  4968.9 1393.88  4975.5 1390.47  4988.8 1386.56  4989.0 1386.06
  4992.8 1386.56  4996.7 1387.16  5001.4 1389.76  5007.2 1389.76  5012.2 1392.16
  5018.0 1391.43  5033.7 1393.94  5076.8 1394.56  5139.2 1397.17  5216.0 1400.49
  5259.1 1401.05  5296.4 1403.72  5414.0 1408.15  5494.4 1413.08  5553.2 1415.08
#Mann=4,-1,0
  4517.9    0.12       0  4988.8    0.05       0  4992.8    0.12       0
  5139.2    0.07       0
Bank Sta=4988.8,4992.8
Exp/Cntr=0.3,0.1

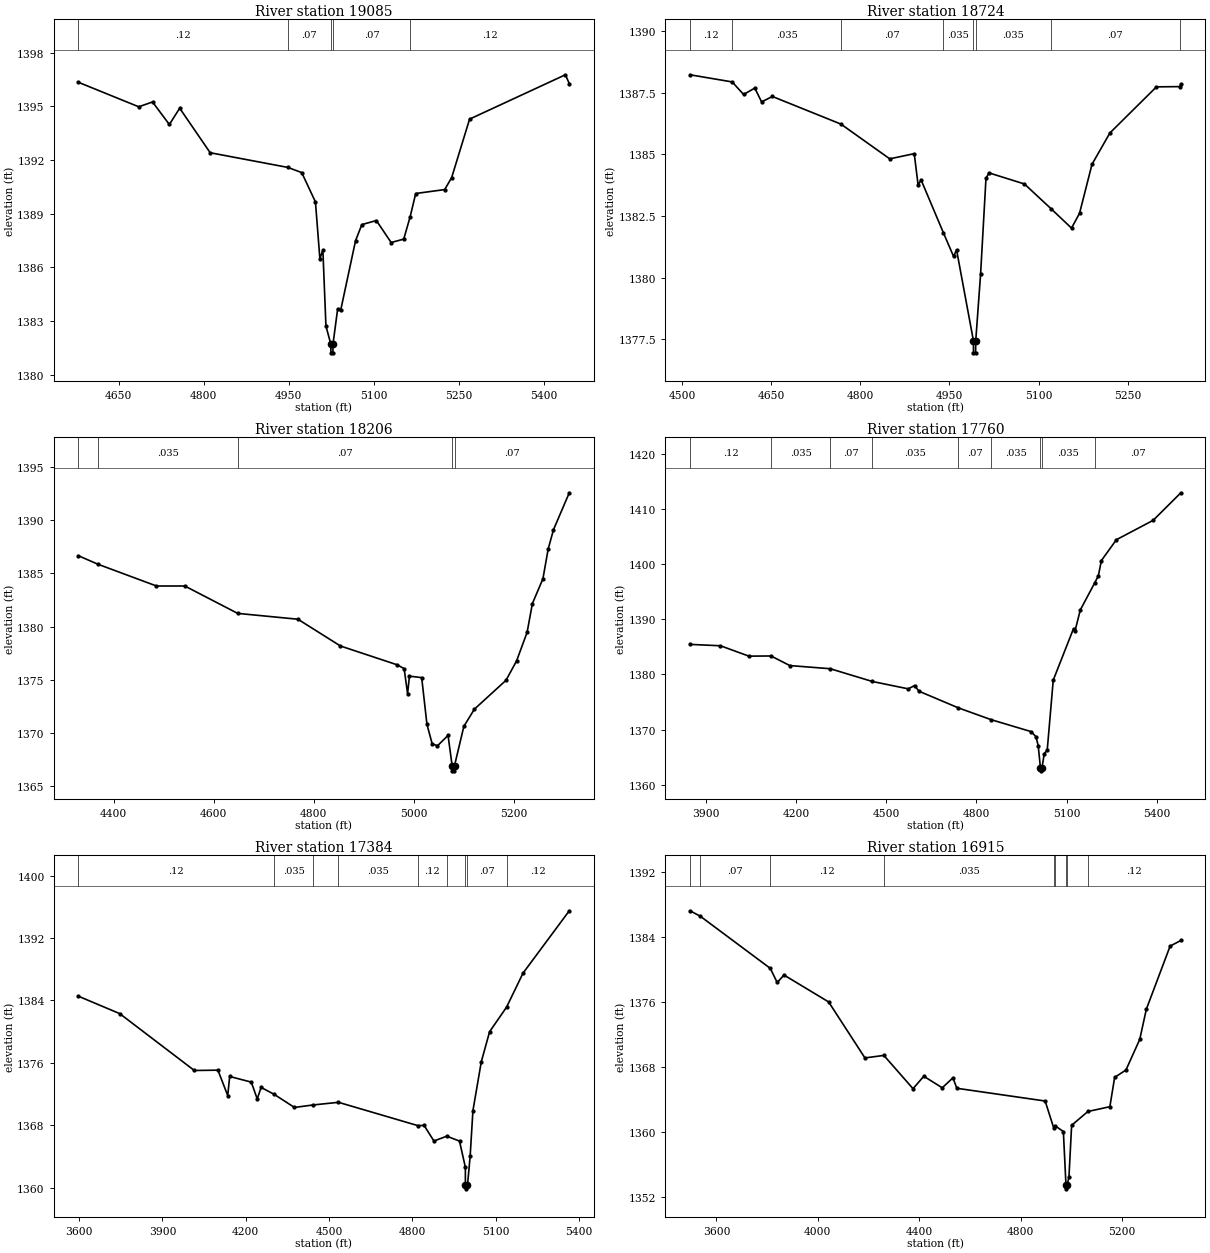
Type RM Length L Ch R = 1,19085,361,361,361
BEGIN DESCRIPTION:
KRAUSE CREEK 35.0
END DESCRIPTION:
XS GIS Cut Line= 3
      2124060.94     13906478.51      2123675.00     13906325.00
      2123248.49     13906469.28
#Sta/Elev= 30
  4578.9 1396.35  4685.3 1394.98  4709.6 1395.25  4739.3 1393.99  4757.5 1394.90
  4811.3 1392.41  4948.2 1391.59  4972.7 1391.30  4996.9 1389.66  5004.7 1386.49
  5010.0 1386.96  5015.4 1382.72  5023.9 1381.72  5024.2 1381.22  5027.7 1381.22
  5027.9 1381.72  5036.1 1383.69  5041.4 1383.60  5067.6 1387.49  5078.7 1388.39
  5104.3 1388.62  5130.4 1387.39  5152.6 1387.58  5163.9 1388.83  5173.7 1390.13
  5224.8 1390.35  5237.1 1391.02  5268.7 1394.29  5437.6 1396.77  5444.5 1396.28
#Mann=5,-1,0
  4578.9    0.12       0  4948.2    0.07       0  5023.9    0.05       0
  5027.9    0.07       0  5163.9    0.12       0
Bank Sta=5023.9,5027.9
Exp/Cntr=0.3,0.1

Type RM Length L Ch R = 1,18724,518,518,518
BEGIN DESCRIPTION:
Krause Creek 34.0
END DESCRIPTION:
XS GIS Cut Line= 4
      2123996.76     13906142.46      2123675.84     13906013.26
      2123388.28     13906063.27      2123284.53     13906220.13
#Sta/Elev= 30
  4513.5 1388.23  4584.5 1387.94  4603.7 1387.43  4622.5 1387.69  4634.0 1387.13
  4652.1 1387.35  4767.4 1386.23  4849.6 1384.82  4890.8 1385.03  4897.3 1383.76
  4902.4 1383.96  4939.7 1381.83  4957.0 1380.86  4962.0 1381.13  4990.3 1377.45
  4990.5 1376.95  4994.0 1376.95  4994.3 1377.45  5002.4 1380.13  5011.5 1384.03
  5016.6 1384.25  5076.2 1383.80  5120.8 1382.80  5155.4 1382.01  5168.9 1382.61
  5189.9 1384.60  5220.0 1385.87  5298.3 1387.74  5337.3 1387.75  5339.4 1387.84
#Mann=8,-1,0
  4513.5    0.12       0  4584.5   0.035       0  4767.4    0.07       0
  4939.7   0.035       0  4990.3   0.035       0  4994.3   0.035       0
  5120.8    0.07       0  5337.3    0.12       0
Bank Sta=4990.3,4994.3
Exp/Cntr=0.3,0.1

Type RM Length L Ch R = 1,18206,446,446,446
BEGIN DESCRIPTION:
KRAUSE CREEK 33.0
END DESCRIPTION:
XS GIS Cut Line= 3
      2124130.30     13906060.08      2123675.00     13905575.00
      2123375.01     13905475.00
#Sta/Elev= 30
  4329.8 1386.67  4369.4 1385.86  4485.9 1383.82  4542.5 1383.82  4648.3 1381.24
  4768.7 1380.69  4853.7 1378.17  4967.0 1376.40  4981.1 1376.04  4988.0 1373.68
  4991.7 1375.33  5016.2 1375.19  5026.7 1370.79  5037.2 1368.95  5047.8 1368.77
  5068.9 1369.75  5077.0 1366.91  5077.3 1366.41  5081.5 1366.41  5081.9 1366.91
  5100.5 1370.60  5121.6 1372.22  5184.8 1374.94  5205.9 1376.76  5227.0 1379.46
  5237.5 1382.16  5258.6 1384.50  5269.1 1387.30  5279.7 1389.12  5311.3 1392.60
#Mann=5,-1,0
  4329.8    0.12       0  4369.4   0.035       0  4648.3    0.07       0
  5077.0    0.05       0  5081.9    0.07       0
Bank Sta=5077,5081.9
Exp/Cntr=0.3,0.1

Type RM Length L Ch R = 1,17760,376,376,376
BEGIN DESCRIPTION:
KRAUSE CREEK 32.0
END DESCRIPTION:
XS GIS Cut Line= 3
      2124345.73     13906157.21      2123675.00     13905225.00
      2123190.69     13905243.65
#Sta/Elev= 30
  3846.9 1385.44  3948.3 1385.19  4042.8 1383.31  4116.5 1383.34  4179.1 1381.60
  4313.4 1381.03  4453.3 1378.72  4573.1 1377.38  4594.0 1377.98  4608.7 1376.95
  4739.9 1373.93  4849.0 1371.79  4981.8 1369.63  4997.8 1368.71  5005.3 1367.11
  5012.9 1363.02  5013.2 1362.52  5017.8 1363.02  5025.4 1365.60  5035.4 1366.30
  5055.4 1378.96  5122.9 1388.31  5127.9 1387.89  5145.4 1391.68  5193.4 1396.59
  5205.5 1397.88  5215.5 1400.63  5265.5 1404.41  5387.9 1407.93  5480.0 1412.92
#Mann=9,-1,0
  3846.9    0.12       0  4116.5   0.035       0  4313.4    0.07       0
  4453.3   0.035       0  4739.9    0.07       0  4849.0   0.035       0
  5012.9   0.035       0  5017.8   0.035       0  5193.4    0.07       0
Bank Sta=5012.9,5017.8
Exp/Cntr=0.3,0.1

Type RM Length L Ch R = 1,17384,469,469,469
BEGIN DESCRIPTION:
KRAUSE CREEK 31.0
END DESCRIPTION:
XS GIS Cut Line= 3
      2124809.89     13905870.54      2123808.76     13904896.43
      2123438.58     13904875.67
#Sta/Elev= 30
  3597.6 1384.53  3746.3 1382.30  4015.1 1375.01  4100.0 1375.05  4135.3 1371.80
  4142.4 1374.24  4220.1 1373.52  4241.5 1371.37  4255.6 1372.84  4302.6 1371.95
  4375.7 1370.27  4442.4 1370.59  4534.0 1370.93  4819.3 1367.95  4842.6 1367.96
  4877.8 1365.97  4924.1 1366.59  4969.9 1365.96  4991.0 1362.61  4991.1 1360.34
  4991.5 1359.84  4996.0 1360.34  4998.8 1360.34  5008.2 1364.00  5018.2 1369.85
  5048.3 1376.12  5078.3 1379.98  5139.6 1383.14  5198.5 1387.48  5365.2 1395.48
#Mann=9,-1,0
  3597.6    0.12       0  4302.6   0.035       0  4442.4    0.07       0
  4534.0   0.035       0  4819.3    0.12       0  4924.1    0.07       0
  4991.1    0.05       0  4996.0    0.07       0  5139.6    0.12       0
Bank Sta=4991.1,4996
Exp/Cntr=0.3,0.1

Type RM Length L Ch R = 1,16915,490,490,490
BEGIN DESCRIPTION:
KRAUSE CREEK 30.0
END DESCRIPTION:
XS GIS Cut Line= 3
      2124937.15     13905846.87      2124125.00     13904575.00
      2123719.97     13904713.79
#Sta/Elev= 30
  3495.4 1387.25  3536.0 1386.58  3812.1 1380.16  3839.5 1378.42  3866.5 1379.33
  4042.5 1376.02  4185.8 1369.12  4260.5 1369.43  4375.6 1365.33  4418.1 1366.86
  4490.9 1365.44  4533.2 1366.67  4548.4 1365.38  4897.0 1363.81  4931.3 1360.45
  4936.7 1360.75  4968.9 1360.05  4979.1 1353.49  4979.5 1352.99  4984.1 1353.49
  4990.9 1354.44  5001.5 1360.82  5065.7 1362.52  5152.4 1363.11  5171.2 1366.72
  5215.9 1367.63  5270.3 1371.40  5296.3 1375.12  5390.2 1382.90  5432.6 1383.59
#Mann=9,-1,0
  3495.4    0.12       0  3536.0    0.07       0  3812.1    0.12       0
  4260.5   0.035       0  4931.3    0.12       0  4936.7    0.07       0
  4979.1    0.05       0  4984.1    0.07       0  5065.7    0.12       0
Bank Sta=4979.1,4984.1
Exp/Cntr=0.3,0.1

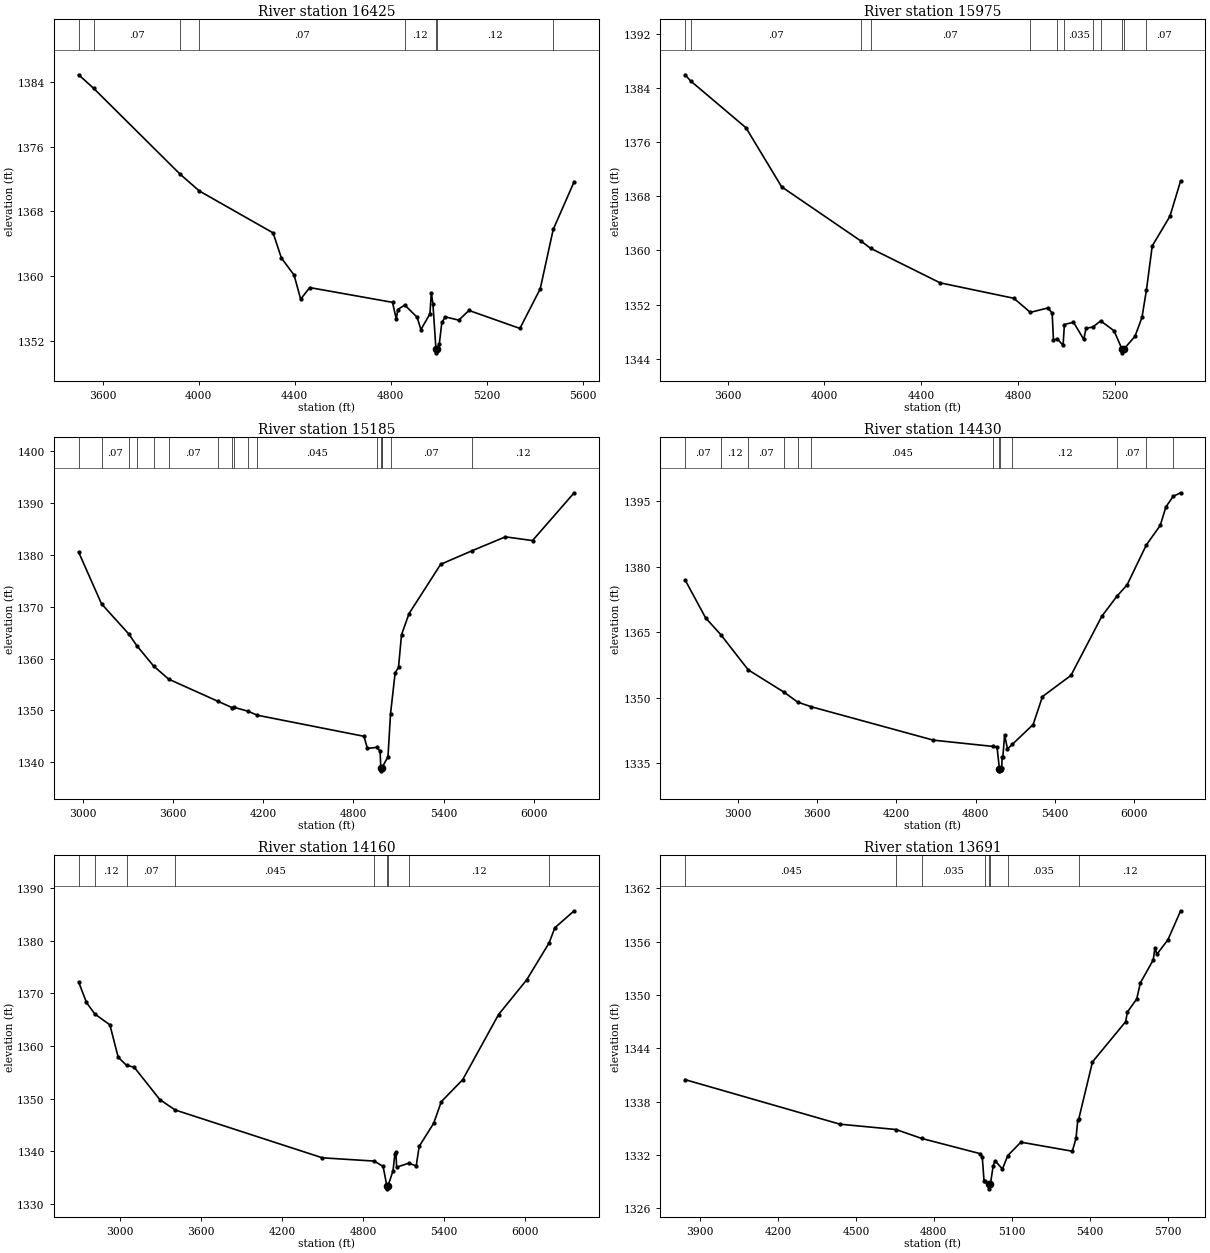
Type RM Length L Ch R = 1,16425,450,450,450
BEGIN DESCRIPTION:
KRAUSE CREEK 29.0
END DESCRIPTION:
XS GIS Cut Line= 3
      2125162.19     13905530.59      2124425.00     13904225.00
      2124025.02     13903825.02
#Sta/Elev= 30
  3500.2 1384.92  3562.5 1383.25  3923.6 1372.60  4003.5 1370.53  4310.5 1365.35
  4345.0 1362.25  4398.1 1360.12  4425.5 1357.14  4463.0 1358.58  4808.2 1356.75
  4824.1 1354.65  4829.8 1355.86  4859.3 1356.41  4910.7 1354.91  4926.6 1353.37
  4964.2 1355.34  4969.9 1357.95  4976.6 1356.56  4989.1 1351.00  4989.5 1350.50
  4994.1 1351.00  5003.1 1351.57  5013.7 1354.26  5027.8 1354.95  5084.4 1354.55
  5126.8 1355.75  5339.0 1353.52  5423.8 1358.43  5477.8 1365.77  5565.2 1371.69
#Mann=8,-1,0
  3500.2    0.12       0  3562.5    0.07       0  3923.6    0.12       0
  4003.5    0.07       0  4859.3    0.12       0  4989.1    0.05       0
  4994.1    0.12       0  5477.8    0.07       0
Bank Sta=4989.1,4994.1
Exp/Cntr=0.3,0.1

Type RM Length L Ch R = 1,15975,790,790,790
BEGIN DESCRIPTION:
KRAUSE CREEK 28.0
END DESCRIPTION:
XS GIS Cut Line= 3
      2125360.64     13905344.22      2124675.00     13903925.00
      2124274.97     13903674.98
#Sta/Elev= 30
  3423.9 1385.92  3446.4 1385.02  3675.6 1378.10  3822.8 1369.39  4151.4 1361.37
  4190.2 1360.32  4477.7 1355.22  4782.6 1352.94  4850.6 1350.86  4923.7 1351.52
  4940.8 1350.75  4946.3 1346.75  4961.5 1346.97  4986.0 1345.99  4991.4 1349.07
  5029.0 1349.41  5071.4 1346.88  5080.8 1348.50  5109.5 1348.71  5141.2 1349.60
  5196.4 1348.16  5230.1 1345.39  5230.6 1344.89  5235.9 1345.39  5283.1 1347.32
  5312.0 1350.11  5330.6 1354.20  5354.4 1360.66  5427.5 1365.04  5471.8 1370.27
#Mann=12,-1,0
  3423.9    0.12       0  3446.4    0.07       0  4151.4   0.035       0
  4190.2    0.07       0  4850.6   0.035       0  4961.5    0.07       0
  4991.4   0.035       0  5109.5    0.07       0  5141.2    0.12       0
  5230.1   0.035       0  5235.9    0.12       0  5330.6    0.07       0
Bank Sta=5230.1,5235.9
Exp/Cntr=0.3,0.1

Type RM Length L Ch R = 1,15185,755,755,755
BEGIN DESCRIPTION:
KRAUSE CREEK 27.7
END DESCRIPTION:
XS GIS Cut Line= 4
      2125420.68     13905030.24      2124851.79     13903460.48
      2124574.95     13903234.07      2123308.29     13903169.62
#Sta/Elev= 30
  2972.7 1380.54  3125.0 1370.56  3306.9 1364.73  3359.6 1362.49  3471.1 1358.58
  3571.2 1356.04  3896.5 1351.80  3994.3 1350.53  4004.5 1350.62  4100.1 1349.84
  4161.1 1349.08  4870.7 1345.01  4893.0 1342.67  4955.7 1342.88  4977.7 1342.17
  4982.3 1338.85  4982.8 1338.35  4988.9 1338.85  4990.7 1339.01  5030.0 1341.06
  5047.1 1349.39  5077.6 1357.24  5100.1 1358.34  5120.1 1364.60  5170.2 1368.69
  5380.4 1378.19  5587.8 1380.79  5811.0 1383.49  5991.2 1382.77  6268.3 1391.99
#Mann=17,-1,0
  2972.7    0.12       0  3125.0    0.07       0  3306.9   0.035       0
  3359.6    0.12       0  3471.1   0.035       0  3571.2    0.07       0
  3896.5   0.035       0  3994.3   0.045       0  4004.5   0.035       0
  4100.1    0.07       0  4161.1   0.045       0  4955.7    0.07       0
  4982.3    0.05       0  4988.9    0.07       0  4990.7    0.12       0
  5047.1    0.07       0  5587.8    0.12       0
Bank Sta=4982.3,4988.9
Exp/Cntr=0.3,0.1

Type RM Length L Ch R = 1,14430,270,270,270
BEGIN DESCRIPTION:
KRAUSE CREEK 27.2
END DESCRIPTION:
XS GIS Cut Line= 4
      2125525.24     13904905.85      2125007.27     13902781.51
      2124901.27     13902598.11      2123720.97     13901936.87
#Sta/Elev= 30
  2601.6 1377.02  2756.9 1368.32  2872.1 1364.47  3079.2 1356.42  3352.3 1351.26
  3454.3 1349.01  3556.3 1347.96  4481.0 1340.30  4930.9 1338.87  4962.9 1338.72
  4980.9 1333.77  4981.4 1333.27  4988.0 1333.77  4998.9 1333.99  5001.5 1336.48
  5007.2 1336.48  5020.5 1341.53  5042.2 1338.28  5078.3 1339.33  5236.2 1343.88
  5307.0 1350.29  5522.7 1355.14  5755.6 1368.66  5871.0 1373.30  5947.1 1375.86
  6093.2 1385.03  6198.4 1389.51  6241.8 1393.78  6296.7 1396.17  6352.9 1396.99
#Mann=13,-1,0
  2601.6    0.07       0  2872.1    0.12       0  3079.2    0.07       0
  3352.3   0.035       0  3454.3    0.07       0  3556.3   0.045       0
  4930.9   0.035       0  4980.9   0.035       0  4988.0   0.035       0
  5078.3    0.12       0  5871.0    0.07       0  6093.2    0.12       0
  6296.7   0.035       0
Bank Sta=4980.9,4988
Exp/Cntr=0.3,0.1

Type RM Length L Ch R = 1,14160,469,469,469
BEGIN DESCRIPTION:
KRAUSE CREEK 27.0
END DESCRIPTION:
XS GIS Cut Line= 3
      2125618.12     13904731.54      2125125.00     13902475.00
      2124000.00     13901700.00
#Sta/Elev= 30
  2690.5 1372.18  2748.4 1368.29  2810.5 1366.09  2922.4 1364.03  2983.8 1357.89
  3045.9 1356.34  3102.4 1355.99  3293.3 1349.83  3406.2 1347.87  4498.7 1338.78
  4883.5 1338.16  4949.1 1337.14  4977.4 1333.39  4977.9 1332.89  4984.5 1333.39
  5022.6 1336.30  5036.7 1339.57  5043.6 1339.80  5049.6 1337.01  5140.2 1337.76
  5194.6 1337.23  5216.7 1340.96  5324.2 1345.34  5381.0 1349.45  5539.3 1353.61
  5805.1 1365.97  6014.1 1372.57  6181.1 1379.62  6223.0 1382.46  6366.4 1385.69
#Mann=9,-1,0
  2690.5    0.07       0  2810.5    0.12       0  3045.9    0.07       0
  3406.2   0.045       0  4883.5   0.035       0  4977.4   0.035       0
  4984.5   0.035       0  5140.2    0.12       0  6181.1   0.035       0
Bank Sta=4977.4,4984.5
Exp/Cntr=0.3,0.1

Type RM Length L Ch R = 1,13691,1081,1081,1081
BEGIN DESCRIPTION:
Krause Creek 26.0
END DESCRIPTION:
XS GIS Cut Line= 3
      2125505.34     13903321.10      2125505.34     13902208.39
      2124968.85     13901621.99
#Sta/Elev= 30
  3842.4 1340.49  4438.5 1335.48  4654.3 1334.88  4752.7 1333.88  4978.9 1332.16
  4986.3 1331.78  4993.1 1329.11  4996.4 1329.06  5010.5 1328.71  5011.0 1328.21
  5017.6 1328.71  5028.3 1330.81  5035.7 1331.36  5064.0 1330.44  5084.4 1331.95
  5135.0 1333.46  5332.9 1332.44  5347.1 1333.88  5353.9 1335.92  5357.7 1336.06
  5410.6 1342.49  5538.3 1347.01  5545.0 1348.10  5580.8 1349.56  5595.0 1351.38
  5644.3 1353.94  5651.1 1355.32  5658.5 1354.59  5701.1 1356.23  5749.9 1359.48
#Mann=8,-1,0
  3842.4   0.045       0  4654.3    0.07       0  4752.7   0.035       0
  4996.4    0.07       0  5010.5    0.05       0  5017.6    0.07       0
  5084.4   0.035       0  5357.7    0.12       0
Bank Sta=5010.5,5017.6
Exp/Cntr=0.3,0.1

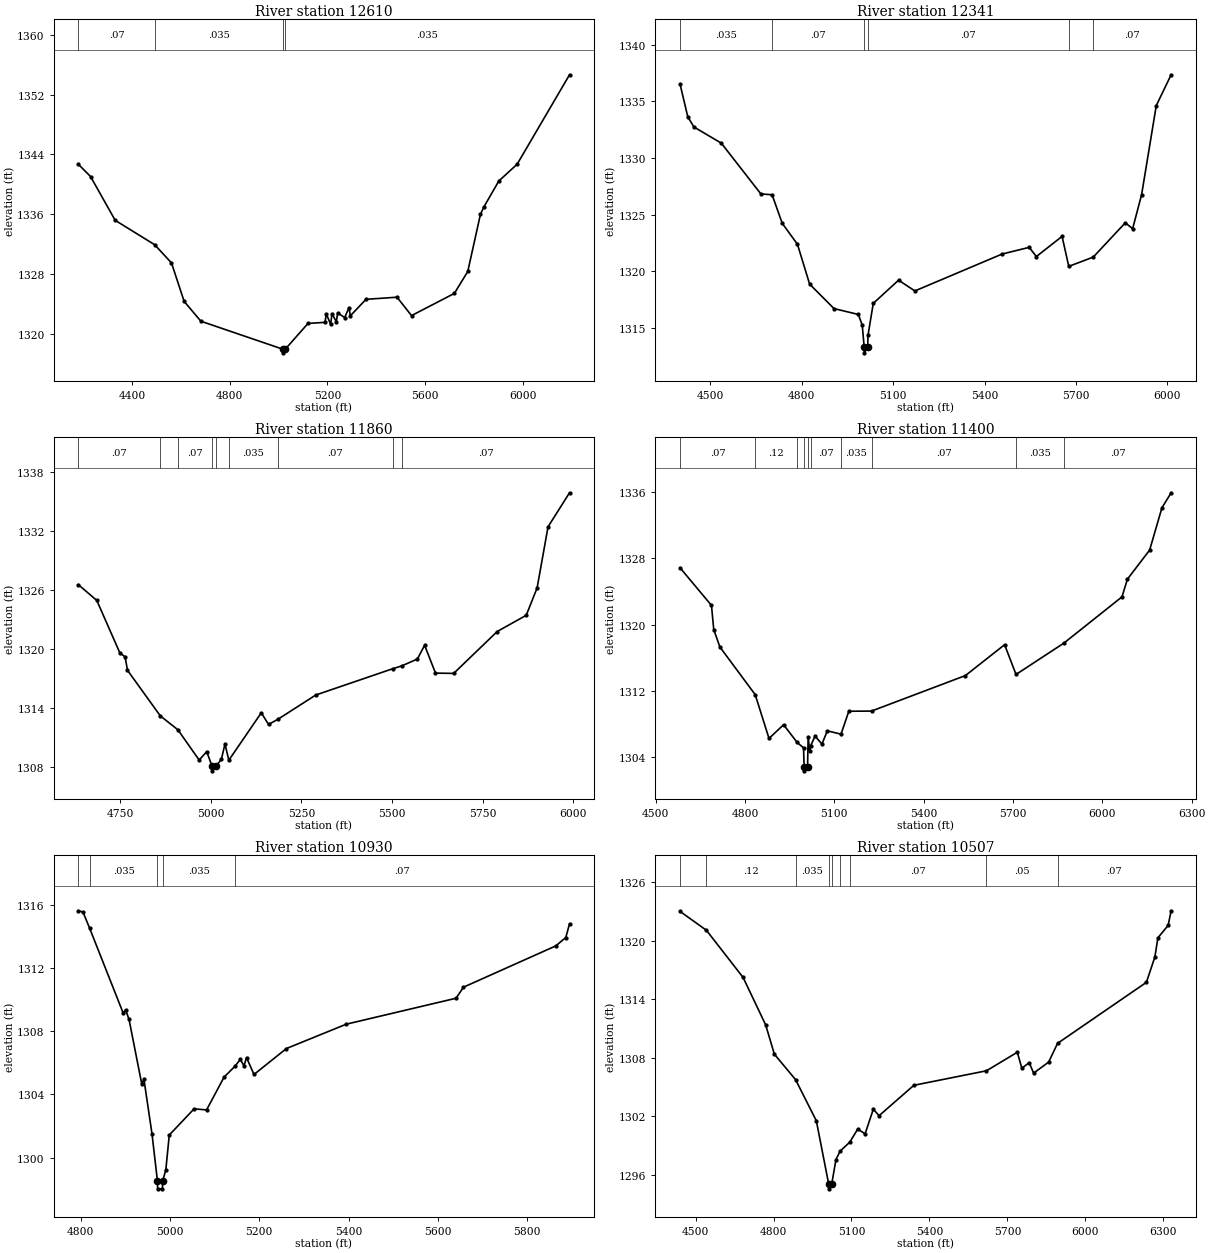
Type RM Length L Ch R = 1,12610,269,269,269
BEGIN DESCRIPTION:
KRAUSE CREEK 24.5
END DESCRIPTION:
XS GIS Cut Line= 3
      2127043.02     13901859.53      2126251.64     13901648.26
      2125164.83     13901162.31
#Sta/Elev= 30
  4180.9 1342.66  4230.6 1341.03  4331.5 1335.17  4493.0 1331.91  4561.7 1329.48
  4613.6 1324.33  4682.0 1321.68  5016.3 1317.95  5016.8 1317.45  5027.7 1317.95
  5120.3 1321.38  5189.9 1321.53  5195.3 1322.66  5213.1 1321.25  5218.5 1322.70
  5236.3 1321.60  5241.7 1322.80  5270.4 1322.16  5288.2 1323.50  5293.6 1322.40
  5357.8 1324.61  5484.7 1324.89  5544.0 1322.43  5719.3 1325.40  5774.1 1328.33
  5826.0 1335.98  5839.8 1336.95  5901.1 1340.43  5976.2 1342.68  6190.5 1354.64
#Mann=4,-1,0
  4180.9    0.07       0  4493.0   0.035       0  5016.3   0.035       0
  5027.7   0.035       0
Bank Sta=5016.3,5027.7
Exp/Cntr=0.3,0.1

Type RM Length L Ch R = 1,12341,481,481,481
BEGIN DESCRIPTION:
KRAUSE CREEK 24.0
END DESCRIPTION:
XS GIS Cut Line= 3
      2127070.49     13901521.56      2126475.00     13901525.00
      2125533.42     13901142.25
#Sta/Elev= 30
  4400.4 1336.55  4425.9 1333.65  4445.9 1332.75  4535.9 1331.32  4665.9 1326.83
  4702.6 1326.76  4735.9 1324.24  4785.9 1322.38  4825.9 1318.86  4905.9 1316.70
  4985.9 1316.18  4998.6 1315.22  5004.9 1313.29  5005.4 1312.79  5016.4 1313.29
  5017.5 1314.34  5034.7 1317.16  5117.7 1319.21  5171.3 1318.26  5457.6 1321.52
  5546.4 1322.11  5570.1 1321.30  5654.4 1323.08  5676.4 1320.43  5756.7 1321.25
  5861.9 1324.28  5886.0 1323.76  5915.4 1326.76  5963.6 1334.64  6012.3 1337.36
#Mann=6,-1,0
  4400.4   0.035       0  4702.6    0.07       0  5004.9    0.05       0
  5016.4    0.07       0  5676.4   0.035       0  5756.7    0.07       0
Bank Sta=5004.9,5016.4
Exp/Cntr=0.3,0.1

Type RM Length L Ch R = 1,11860,460,460,460
BEGIN DESCRIPTION:
KRAUSE CREEK 23.0
END DESCRIPTION:
XS GIS Cut Line= 3
      2126924.99     13901175.00      2126575.00     13901075.00
      2125585.79     13901047.10
#Sta/Elev= 30
  4635.6 1326.49  4686.3 1324.89  4750.0 1319.54  4764.3 1319.16  4770.8 1317.79
  4861.3 1313.15  4909.7 1311.74  4968.4 1308.66  4989.2 1309.51  5003.8 1308.06
  5004.3 1307.56  5015.4 1308.06  5029.6 1308.73  5039.6 1310.29  5050.2 1308.64
  5139.6 1313.46  5159.7 1312.28  5185.3 1312.80  5289.7 1315.27  5501.5 1317.94
  5526.6 1318.23  5569.8 1318.93  5589.8 1320.33  5619.8 1317.50  5669.9 1317.47
  5789.9 1321.73  5869.9 1323.38  5899.9 1326.17  5930.0 1332.38  5989.2 1335.84
#Mann=9,-1,0
  4635.6    0.07       0  4861.3   0.035       0  4909.7    0.07       0
  5003.8    0.05       0  5015.4    0.07       0  5050.2   0.035       0
  5185.3    0.07       0  5501.5   0.035       0  5526.6    0.07       0
Bank Sta=5003.8,5015.4
Exp/Cntr=0.3,0.1

Type RM Length L Ch R = 1,11400,470,470,470
BEGIN DESCRIPTION:
KRAUSE CREEK 22.0
END DESCRIPTION:
XS GIS Cut Line= 3
      2127174.98     13900774.99      2126775.00     13900675.00
      2125575.02     13900975.00
#Sta/Elev= 30
  4581.8 1326.87  4687.4 1322.32  4695.2 1319.38  4715.8 1317.28  4834.3 1311.52
  4880.7 1306.22  4929.7 1307.88  4975.2 1305.73  4996.7 1305.08  4998.5 1302.80
  4999.0 1302.30  5010.2 1302.80  5012.1 1306.41  5017.3 1304.71  5020.2 1305.30
  5035.3 1306.50  5058.5 1305.54  5076.5 1307.14  5122.5 1306.74  5148.7 1309.51
  5224.9 1309.53  5540.4 1313.83  5671.8 1317.56  5710.2 1313.96  5870.8 1317.75
  6066.1 1323.35  6084.1 1325.48  6158.9 1329.01  6200.1 1334.12  6231.0 1335.94
#Mann=10,-1,0
  4581.8    0.07       0  4834.3    0.12       0  4975.2    0.07       0
  4998.5    0.05       0  5010.2    0.07       0  5020.2    0.07       0
  5122.5   0.035       0  5224.9    0.07       0  5710.2   0.035       0
  5870.8    0.07       0
Bank Sta=4998.5,5010.2
Exp/Cntr=0.3,0.1

Type RM Length L Ch R = 1,10930,423,423,423
BEGIN DESCRIPTION:
KRAUSE CREEK 21.0
END DESCRIPTION:
XS GIS Cut Line= 3
      2127175.02     13900325.01      2126975.00     13900275.00
      2126175.01     13900675.00
#Sta/Elev= 30
  4794.6 1315.61  4804.9 1315.53  4819.7 1314.51  4895.1 1309.13  4900.3 1309.35
  4908.0 1308.75  4936.4 1304.68  4941.5 1304.95  4959.5 1301.51  4971.7 1298.53
  4972.2 1298.03  4982.9 1298.03  4983.4 1298.53  4990.5 1299.23  4998.2 1301.43
  5053.9 1303.09  5081.8 1303.02  5121.0 1305.09  5145.7 1305.79  5157.3 1306.21
  5165.7 1305.81  5171.3 1306.33  5188.1 1305.26  5260.7 1306.90  5394.9 1308.44
  5640.9 1310.08  5657.6 1310.78  5864.5 1313.39  5886.8 1313.92  5895.2 1314.78
#Mann=5,-1,0
  4794.6    0.07       0  4819.7   0.035       0  4971.7   0.035       0
  4983.4   0.035       0  5145.7    0.07       0
Bank Sta=4971.7,4983.4
Exp/Cntr=0.3,0.1

Type RM Length L Ch R = 1,10507,456,456,456
BEGIN DESCRIPTION:
KRAUSE CREEK 20.0
END DESCRIPTION:
XS GIS Cut Line= 3
      2127457.70     13900083.57      2126925.00     13899925.00
      2125719.05     13900494.60
#Sta/Elev= 30
  4440.2 1323.02  4541.8 1321.08  4683.0 1316.24  4769.9 1311.37  4803.1 1308.38
  4884.8 1305.76  4964.7 1301.54  5012.2 1295.06  5012.7 1294.56  5024.0 1295.06
  5040.2 1297.56  5056.1 1298.42  5093.5 1299.35  5124.0 1300.69  5152.3 1300.20
  5184.0 1302.73  5206.1 1302.06  5339.9 1305.18  5619.4 1306.67  5738.0 1308.57
  5755.3 1306.93  5783.6 1307.50  5800.8 1306.43  5858.6 1307.56  5892.7 1309.48
  6234.6 1315.74  6267.2 1318.34  6278.9 1320.31  6318.3 1321.58  6329.7 1323.08
#Mann=9,-1,0
  4440.2    0.07       0  4541.8    0.12       0  4884.8   0.035       0
  5012.2   0.035       0  5024.0   0.035       0  5056.1    0.05       0
  5093.5    0.07       0  5619.4    0.05       0  5892.7    0.07       0
Bank Sta=5012.2,5024
Exp/Cntr=0.3,0.1

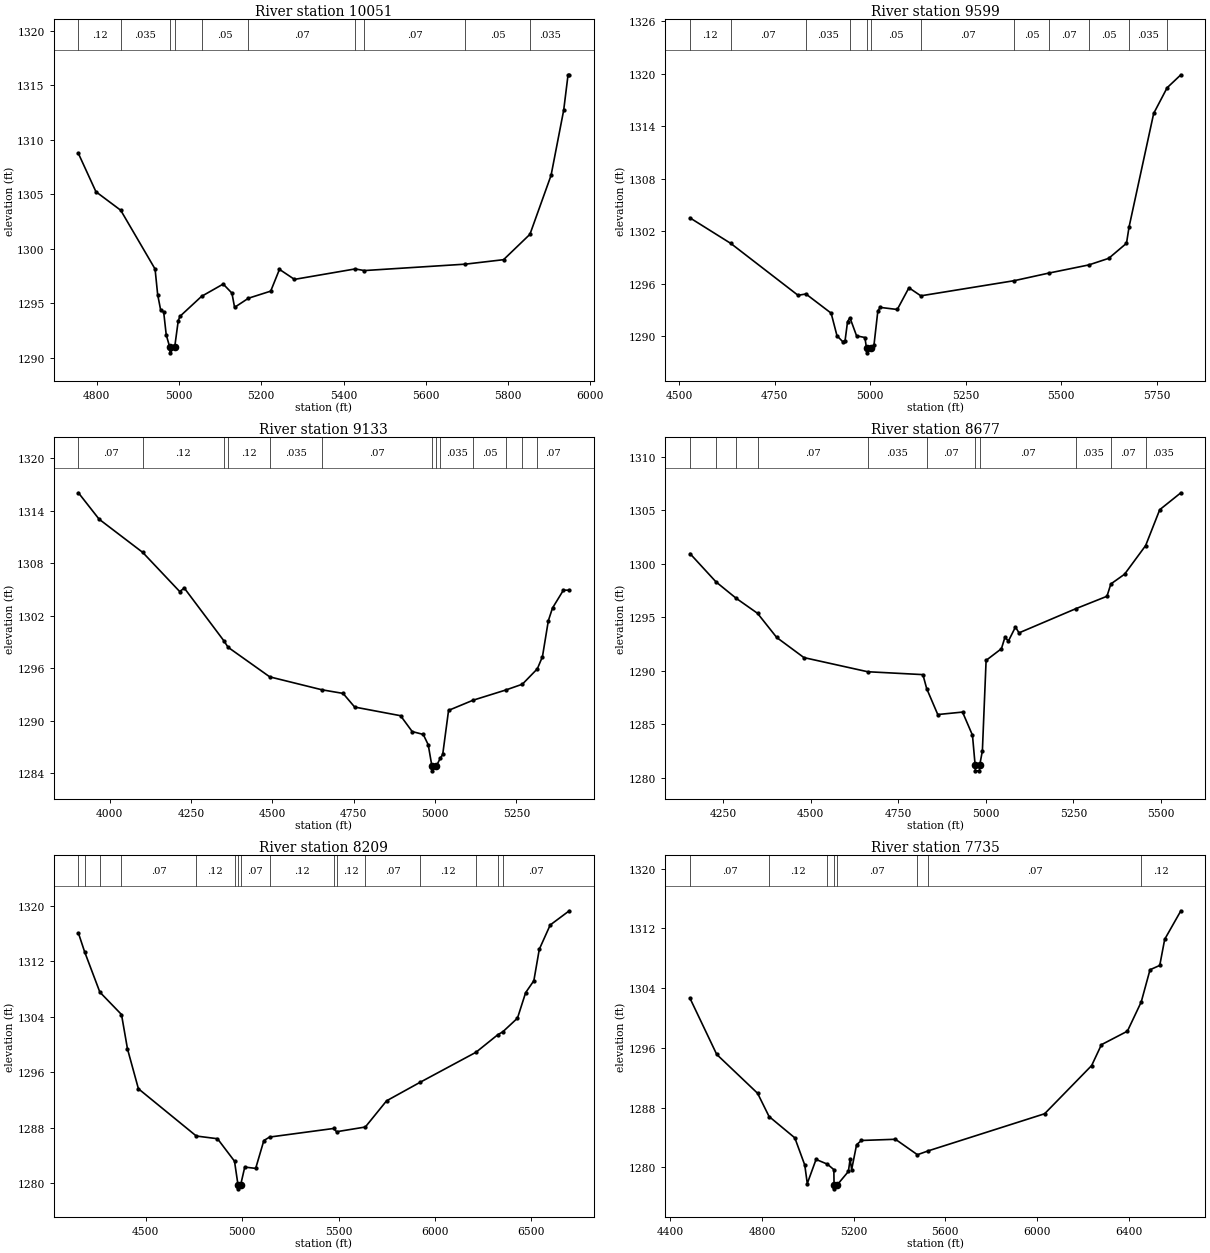
Type RM Length L Ch R = 1,10051,452,452,452
BEGIN DESCRIPTION:
KRAUSE CREEK 19.0
END DESCRIPTION:
XS GIS Cut Line= 3
      2127174.98     13899724.97      2127025.00     13899525.00
      2126224.97     13899024.98
#Sta/Elev= 30
  4755.5 1308.75  4798.2 1305.23  4858.4 1303.53  4941.9 1298.13  4948.2 1295.78
  4955.5 1294.36  4962.8 1294.19  4969.0 1292.09  4977.7 1290.93  4978.2 1290.43
  4989.5 1290.93  4998.2 1293.37  5002.3 1293.78  5054.9 1295.62  5107.5 1296.75
  5128.7 1295.92  5135.2 1294.61  5169.0 1295.45  5223.0 1296.10  5244.3 1298.10
  5280.8 1297.18  5428.3 1298.14  5450.7 1297.99  5696.5 1298.58  5789.1 1298.99
  5853.2 1301.32  5904.6 1306.74  5935.3 1312.73  5945.9 1315.98  5948.9 1315.98
#Mann=10,-1,0
  4755.5    0.12       0  4858.4   0.035       0  4977.7   0.035       0
  4989.5   0.035       0  5054.9    0.05       0  5169.0    0.07       0
  5428.3    0.05       0  5450.7    0.07       0  5696.5    0.05       0
  5853.2   0.035       0
Bank Sta=4977.7,4989.5
Exp/Cntr=0.3,0.1

Type RM Length L Ch R = 1,9599,466,466,466
BEGIN DESCRIPTION:
KRAUSE CREEK 18.0
END DESCRIPTION:
XS GIS Cut Line= 3
      2127374.99     13899374.99      2126975.00     13899125.00
      2126175.03     13898975.00
#Sta/Elev= 30
  4527.9 1303.52  4634.9 1300.60  4810.9 1294.68  4831.6 1294.83  4897.6 1292.64
  4912.9 1290.06  4928.2 1289.37  4934.1 1289.51  4940.6 1291.68  4946.9 1292.11
  4964.2 1290.05  4986.0 1289.86  4990.3 1288.61  4990.8 1288.11  5002.9 1288.61
  5009.8 1289.01  5019.9 1292.89  5025.9 1293.30  5070.8 1293.06  5101.3 1295.54
  5132.5 1294.62  5377.2 1296.35  5467.0 1297.21  5572.6 1298.15  5624.5 1298.90
  5671.1 1300.62  5677.8 1302.48  5742.3 1315.45  5777.5 1318.38  5813.5 1319.86
#Mann=12,-1,0
  4527.9    0.12       0  4634.9    0.07       0  4831.6   0.035       0
  4946.9    0.05       0  4990.3    0.05       0  5002.9    0.05       0
  5132.5    0.07       0  5377.2    0.05       0  5467.0    0.07       0
  5572.6    0.05       0  5677.8   0.035       0  5777.5    0.07       0
Bank Sta=4990.3,5002.9
Exp/Cntr=0.3,0.1

Type RM Length L Ch R = 1,9133,456,456,456
BEGIN DESCRIPTION:
KRAUSE CREEK 17.0
END DESCRIPTION:
XS GIS Cut Line= 3
      2127724.99     13899424.99      2126925.00     13898675.00
      2126524.98     13898575.00
#Sta/Elev= 30
  3903.4 1316.04  3967.1 1313.02  4101.0 1309.23  4214.8 1304.75  4228.9 1305.15
  4350.4 1299.13  4363.6 1298.38  4491.6 1295.00  4652.3 1293.52  4716.9 1293.11
  4752.6 1291.55  4893.7 1290.56  4929.4 1288.75  4963.4 1288.42  4978.7 1287.24
  4990.2 1284.76  4990.7 1284.26  5002.9 1284.76  5015.6 1285.69  5023.2 1286.13
  5041.2 1291.17  5116.4 1292.33  5217.2 1293.50  5268.0 1294.16  5314.1 1295.92
  5329.8 1297.31  5347.9 1301.42  5360.7 1302.87  5394.2 1304.91  5412.3 1304.91
#Mann=13,-1,0
  3903.4    0.07       0  4101.0    0.12       0  4350.4    0.07       0
  4363.6    0.12       0  4491.6   0.035       0  4652.3    0.07       0
  4990.2    0.05       0  5002.9    0.07       0  5015.6   0.035       0
  5116.4    0.05       0  5217.2    0.07       0  5268.0    0.05       0
  5314.1    0.07       0
Bank Sta=4990.2,5002.9
Exp/Cntr=0.3,0.1

Type RM Length L Ch R = 1,8677,468,468,468
BEGIN DESCRIPTION:
KRAUSE CREEK 16.0
END DESCRIPTION:
XS GIS Cut Line= 3
      2127674.98     13898874.98      2127075.00     13898275.00
      2126524.97     13898325.00
#Sta/Elev= 30
  4155.7 1300.96  4230.1 1298.31  4288.0 1296.77  4348.4 1295.38  4403.2 1293.12
  4480.9 1291.24  4662.7 1289.92  4820.4 1289.65  4831.2 1288.34  4862.8 1285.92
  4933.5 1286.15  4961.8 1283.99  4969.5 1281.16  4970.0 1280.66  4981.8 1280.66
  4982.3 1281.16  4990.1 1282.53  5000.7 1290.98  5044.4 1292.07  5054.4 1293.13
  5064.4 1292.79  5084.5 1294.10  5094.6 1293.55  5257.5 1295.82  5345.6 1296.97
  5356.7 1298.12  5395.8 1299.03  5456.0 1301.71  5496.2 1305.06  5556.5 1306.64
#Mann=11,-1,0
  4155.7    0.12       0  4230.1    0.07       0  4288.0    0.12       0
  4348.4    0.07       0  4662.7   0.035       0  4831.2    0.07       0
  4969.5    0.05       0  4982.3    0.07       0  5257.5   0.035       0
  5356.7    0.07       0  5456.0   0.035       0
Bank Sta=4969.5,4982.3
Exp/Cntr=0.3,0.1

Type RM Length L Ch R = 1,8209,474,474,474
BEGIN DESCRIPTION:
KRAUSE CREEK 15.0
END DESCRIPTION:
XS GIS Cut Line= 3
      2128075.02     13898675.02      2127475.00     13898075.00
      2126275.01     13896875.01
#Sta/Elev= 30
  4151.2 1316.06  4183.2 1313.37  4262.5 1307.53  4374.7 1304.30  4405.8 1299.33
  4462.4 1293.59  4762.7 1286.77  4872.5 1286.38  4960.7 1283.14  4979.2 1279.65
  4979.7 1279.15  4992.0 1279.65  5013.9 1282.29  5070.5 1282.10  5112.9 1286.12
  5142.7 1286.62  5474.7 1287.86  5490.0 1287.39  5639.1 1288.07  5749.3 1291.85
  5921.7 1294.50  6212.6 1298.85  6326.7 1301.40  6351.8 1301.80  6428.1 1303.78
  6470.5 1307.46  6513.0 1309.18  6541.3 1313.72  6597.8 1317.22  6696.8 1319.27
#Mann=16,-1,0
  4151.2    0.12       0  4183.2    0.07       0  4262.5    0.12       0
  4374.7    0.07       0  4762.7    0.12       0  4960.7    0.07       0
  4979.2    0.05       0  4992.0    0.07       0  5142.7    0.12       0
  5474.7    0.07       0  5490.0    0.12       0  5639.1    0.07       0
  5921.7    0.12       0  6212.6    0.07       0  6326.7    0.12       0
  6351.8    0.07       0
Bank Sta=4979.2,4992
Exp/Cntr=0.3,0.1

Type RM Length L Ch R = 1,7735,419,419,419
BEGIN DESCRIPTION:
KRAUSE CREEK 14.0
END DESCRIPTION:
XS GIS Cut Line= 3
      2128125.02     13898325.03      2127875.00     13897875.00
      2126775.00     13896675.00
#Sta/Elev= 30
  4485.7 1302.64  4602.4 1295.12  4780.9 1289.91  4830.9 1286.80  4943.3 1283.94
  4986.8 1280.29  4997.7 1277.82  5036.0 1281.05  5085.3 1280.42  5113.7 1279.68
  5114.6 1277.61  5115.1 1277.11  5127.5 1277.61  5177.2 1279.44  5184.6 1281.09
  5191.4 1279.69  5212.9 1283.02  5233.9 1283.59  5382.5 1283.75  5478.5 1281.68
  5526.8 1282.21  6033.7 1287.17  6239.0 1293.63  6281.6 1296.42  6395.0 1298.23
  6455.3 1302.14  6493.7 1306.46  6536.2 1307.04  6557.8 1310.54  6628.4 1314.36
#Mann=8,-1,0
  4485.7    0.07       0  4830.9    0.12       0  5085.3    0.07       0
  5114.6    0.05       0  5127.5    0.07       0  5478.5   0.035       0
  5526.8    0.07       0  6455.3    0.12       0
Bank Sta=5114.6,5127.5
Exp/Cntr=0.3,0.1