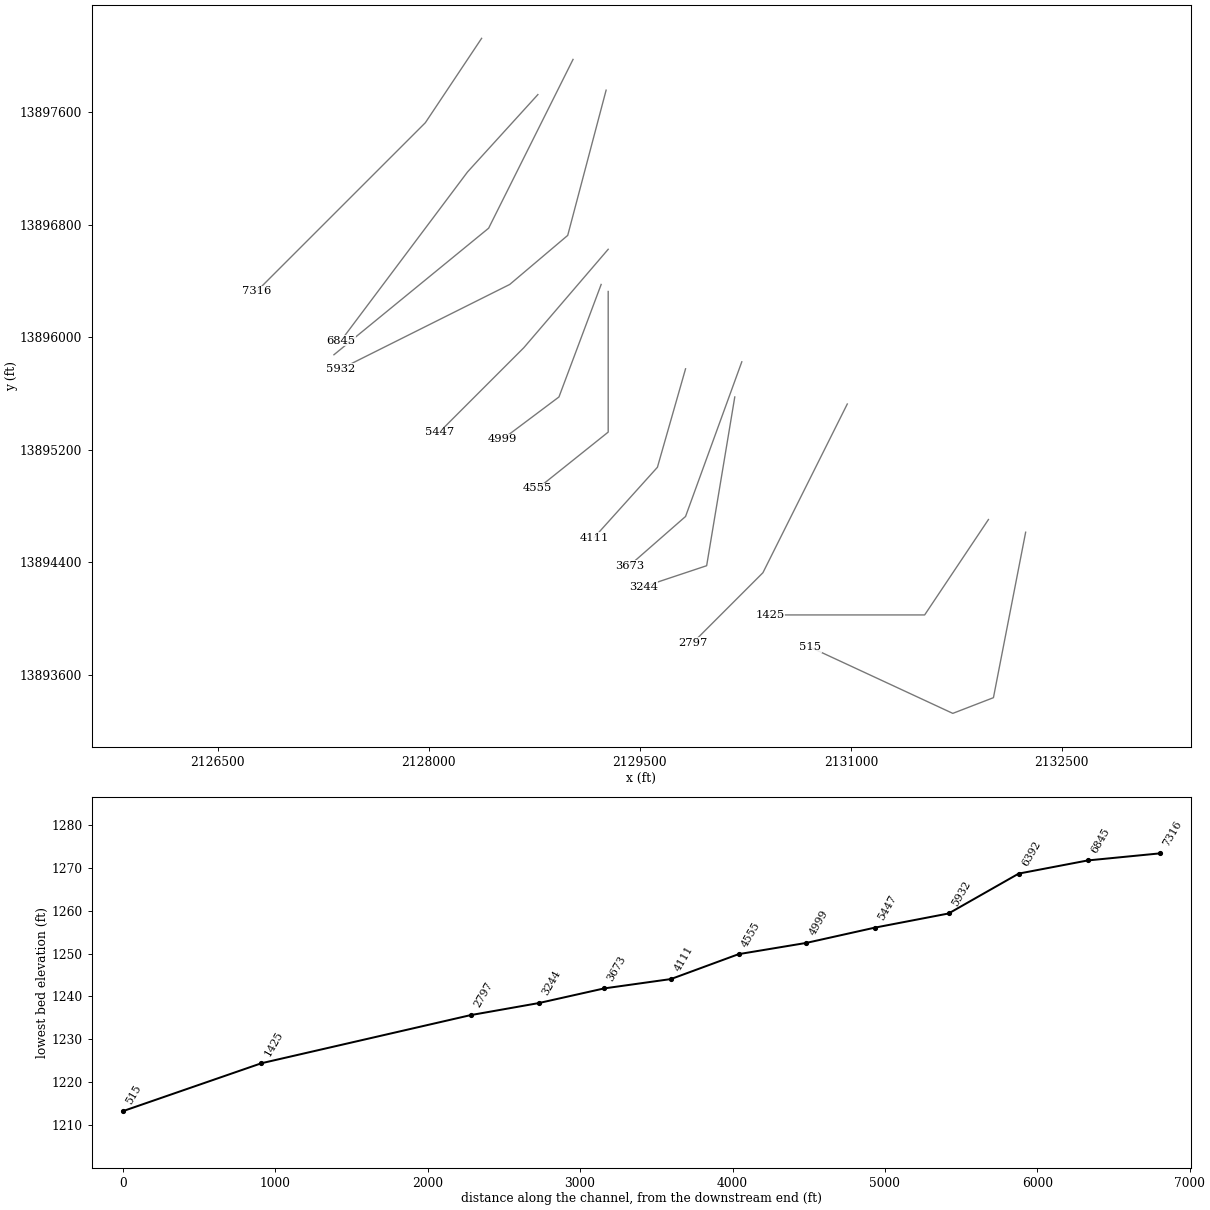
HEC-RAS study KRAUSE CREEK.prj: KRAUSE CREEK Base Level Engineering

--- KRAUSE CREEK.g01 (geometry) --- (continued)

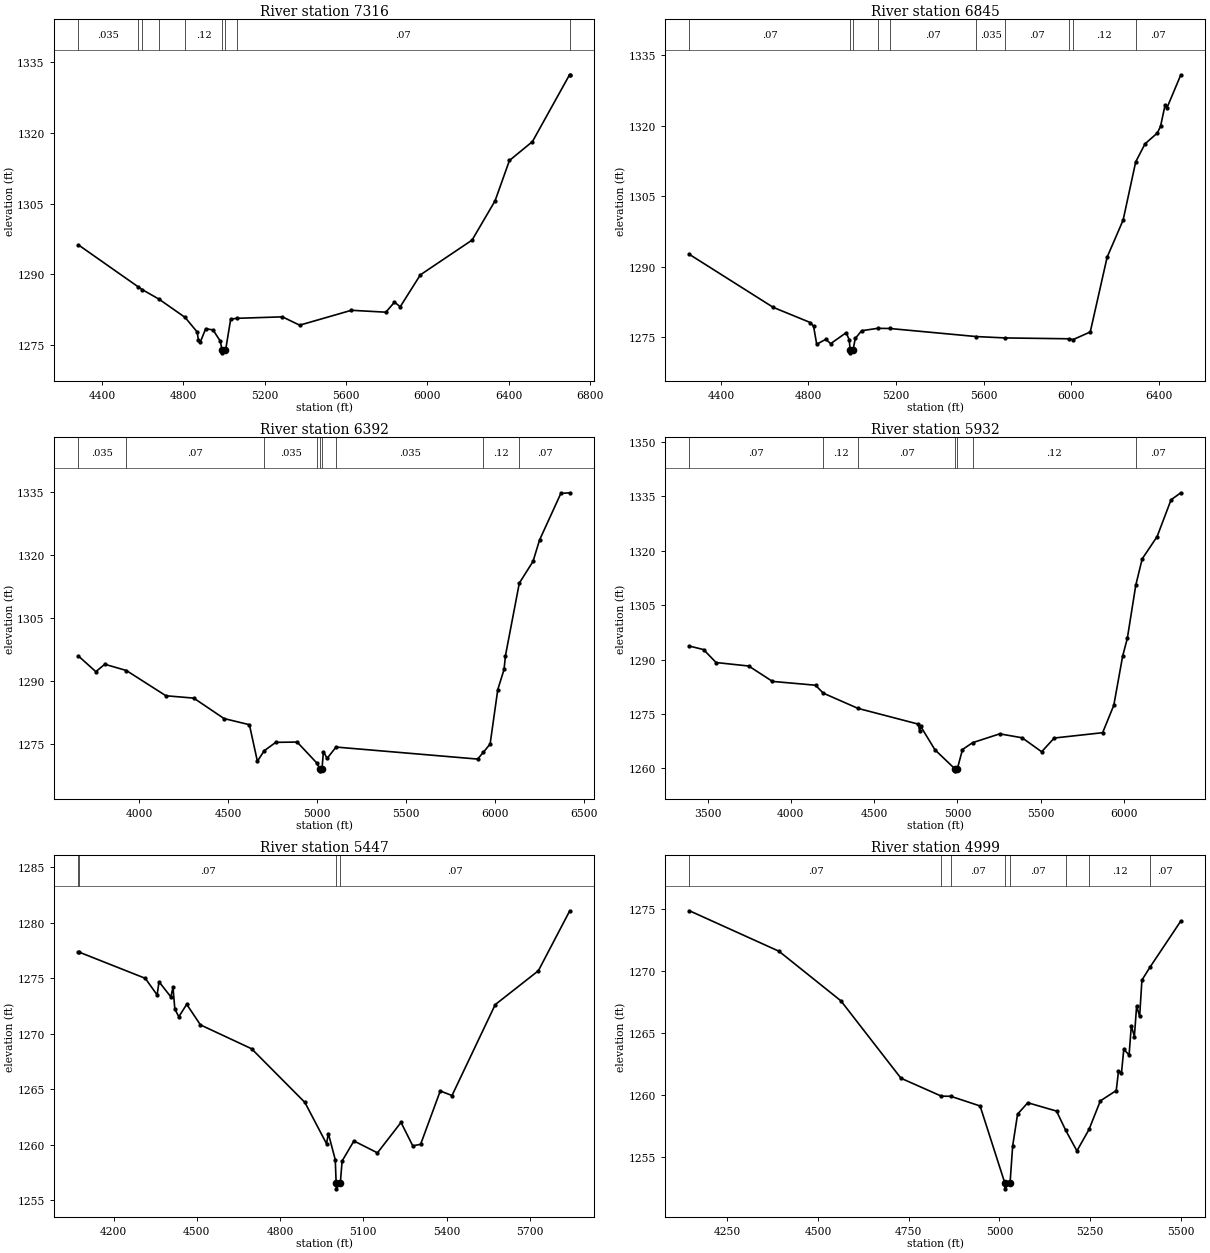
Type RM Length L Ch R = 1,7316,471,471,471
BEGIN DESCRIPTION:
KRAUSE CREEK 13.0
END DESCRIPTION:
XS GIS Cut Line= 3
      2128374.98     13898124.97      2127975.00     13897525.00
      2126775.02     13896325.02
#Sta/Elev= 30
  4283.3 1296.26  4578.8 1287.32  4596.7 1286.79  4680.1 1284.74  4808.3 1280.87
  4867.7 1277.78  4873.7 1276.09  4882.7 1275.59  4909.7 1278.48  4945.8 1278.21
  4981.8 1275.81  4990.4 1273.85  4990.9 1273.35  5003.3 1273.85  5007.9 1274.00
  5032.7 1280.52  5065.3 1280.68  5287.2 1280.99  5372.1 1279.22  5626.6 1282.38
  5796.3 1281.98  5838.8 1284.11  5867.0 1283.13  5966.0 1289.90  6220.6 1297.28
  6333.7 1305.61  6404.5 1314.18  6517.6 1318.18  6700.3 1332.37  6701.4 1332.37
#Mann=9,-1,0
  4283.3   0.035       0  4578.8    0.07       0  4596.7   0.035       0
  4680.1    0.07       0  4808.3    0.12       0  4990.4    0.05       0
  5003.3    0.12       0  5065.3    0.07       0  6700.3    0.12       0
Bank Sta=4990.4,5003.3
Exp/Cntr=0.3,0.1

Type RM Length L Ch R = 1,6845,453,453,453
BEGIN DESCRIPTION:
KRAUSE CREEK 12.0
END DESCRIPTION:
XS GIS Cut Line= 3
      2128774.98     13897724.98      2128275.00     13897175.00
      2127374.99     13895974.98
#Sta/Elev= 30
  4257.0 1292.64  4639.1 1281.39  4809.4 1278.14  4823.6 1277.33  4837.8 1273.54
  4879.7 1274.60  4901.3 1273.66  4972.2 1275.99  4986.4 1274.49  4990.4 1272.21
  4990.9 1271.71  5003.3 1272.21  5013.8 1274.77  5043.0 1276.42  5116.0 1276.92
  5170.8 1276.89  5567.1 1275.17  5698.7 1274.88  5987.7 1274.70  6008.0 1274.52
  6086.7 1276.15  6163.8 1292.07  6236.7 1299.94  6294.2 1312.33  6336.7 1316.17
  6393.0 1318.47  6407.6 1319.90  6428.4 1324.44  6436.7 1323.80  6500.3 1330.86
#Mann=10,-1,0
  4257.0    0.07       0  4990.4    0.05       0  5003.3    0.07       0
  5116.0   0.035       0  5170.8    0.07       0  5567.1   0.035       0
  5698.7    0.07       0  5987.7   0.035       0  6008.0    0.12       0
  6294.2    0.07       0
Bank Sta=4990.4,5003.3
Exp/Cntr=0.3,0.1

Type RM Length L Ch R = 1,6392,460,460,460
BEGIN DESCRIPTION:
KRAUSE CREEK 11.0
END DESCRIPTION:
XS GIS Cut Line= 3
      2129025.01     13897975.02      2128425.00     13896775.00
      2127325.03     13895875.02
#Sta/Elev= 30
  3658.1 1295.97  3756.0 1292.24  3806.3 1294.01  3927.6 1292.52  4150.1 1286.51
  4306.6 1285.95  4477.1 1281.08  4619.6 1279.62  4664.4 1270.92  4702.9 1273.42
  4767.8 1275.42  4888.0 1275.49  5000.9 1270.40  5014.7 1269.14  5015.2 1268.64
  5027.9 1269.14  5035.7 1273.20  5056.5 1271.61  5106.7 1274.30  5902.8 1271.44
  5935.5 1273.08  5973.1 1275.02  6016.2 1287.98  6051.4 1292.76  6059.3 1296.04
  6137.3 1313.32  6214.3 1318.48  6250.9 1323.56  6370.8 1334.67  6421.0 1334.82
#Mann=9,-1,0
  3658.1   0.035       0  3927.6    0.07       0  4702.9   0.035       0
  5000.9    0.07       0  5014.7   0.035       0  5027.9    0.07       0
  5106.7   0.035       0  5935.5    0.12       0  6137.3    0.07       0
Bank Sta=5014.7,5027.9
Exp/Cntr=0.3,0.1

Type RM Length L Ch R = 1,5932,485,485,485
BEGIN DESCRIPTION:
KRAUSE CREEK 10.0
END DESCRIPTION:
XS GIS Cut Line= 4
      2129260.23     13897756.50      2128987.25     13896723.80
      2128575.00     13896375.00      2127375.02     13895775.01
#Sta/Elev= 30
  3391.8 1293.71  3476.1 1292.75  3551.4 1289.18  3747.5 1288.22  3889.8 1283.98
  4148.4 1282.93  4194.7 1280.75  4403.1 1276.55  4765.4 1272.21  4773.1 1270.33
  4779.7 1271.59  4865.4 1265.14  4986.2 1259.84  4986.7 1259.34  4999.4 1259.84
  5030.7 1265.21  5091.4 1267.10  5254.3 1269.53  5388.5 1268.45  5505.9 1264.60
  5581.4 1268.38  5872.0 1269.85  5939.1 1277.40  5992.2 1290.95  6020.2 1295.83
  6071.2 1310.53  6109.6 1317.75  6199.1 1323.88  6282.9 1334.03  6341.6 1335.95
#Mann=7,-1,0
  3391.8    0.07       0  4194.7    0.12       0  4403.1    0.07       0
  4986.2    0.05       0  4999.4    0.07       0  5091.4    0.12       0
  6071.2    0.07       0
Bank Sta=4986.2,4999.4
Exp/Cntr=0.3,0.1

Type RM Length L Ch R = 1,5447,448,448,448
BEGIN DESCRIPTION:
KRAUSE CREEK 9.0
END DESCRIPTION:
XS GIS Cut Line= 3
      2129275.00     13896625.00      2128675.00     13895925.00
      2128074.99     13895324.99
#Sta/Elev= 30
  4073.4 1277.35  4074.7 1277.35  4314.3 1274.98  4357.1 1273.48  4363.7 1274.67
  4406.5 1273.31  4414.2 1274.17  4420.8 1272.22  4435.1 1271.52  4463.6 1272.64
  4513.0 1270.79  4697.4 1268.64  4889.4 1263.81  4967.4 1260.09  4974.0 1261.01
  4998.9 1258.65  5002.1 1256.53  5002.6 1256.03  5017.0 1256.53  5023.6 1258.54
  5066.1 1260.34  5150.9 1259.27  5235.8 1262.01  5278.2 1259.90  5306.5 1260.04
  5377.2 1264.84  5419.6 1264.43  5575.2 1272.61  5730.7 1275.66  5843.9 1281.06
#Mann=4,-1,0
  4073.4   0.035       0  4074.7    0.07       0  5002.1    0.05       0
  5017.0    0.07       0
Bank Sta=5002.1,5017
Exp/Cntr=0.3,0.1

Type RM Length L Ch R = 1,4999,444,444,444
BEGIN DESCRIPTION:
KRAUSE CREEK 8.0
END DESCRIPTION:
XS GIS Cut Line= 3
      2129224.99     13896374.98      2128925.00     13895575.00
      2128524.98     13895274.99
#Sta/Elev= 30
  4145.6 1274.83  4392.1 1271.58  4563.0 1267.59  4728.5 1261.37  4840.0 1259.93
  4865.8 1259.92  4946.6 1259.14  5014.4 1252.98  5014.9 1252.48  5029.3 1252.98
  5036.4 1255.93  5050.0 1258.49  5078.1 1259.40  5157.3 1258.73  5182.7 1257.18
  5213.5 1255.53  5246.8 1257.25  5278.1 1259.55  5321.9 1260.38  5328.1 1261.93
  5336.4 1261.81  5342.7 1263.69  5357.3 1263.24  5363.5 1265.59  5371.9 1264.72
  5378.1 1267.18  5386.4 1266.34  5392.7 1269.26  5415.0 1270.30  5500.0 1274.01
#Mann=8,-1,0
  4145.6    0.07       0  4840.0   0.035       0  4865.8    0.07       0
  5014.4    0.05       0  5029.3    0.07       0  5182.7   0.035       0
  5246.8    0.12       0  5415.0    0.07       0
Bank Sta=5014.4,5029.3
Exp/Cntr=0.3,0.1

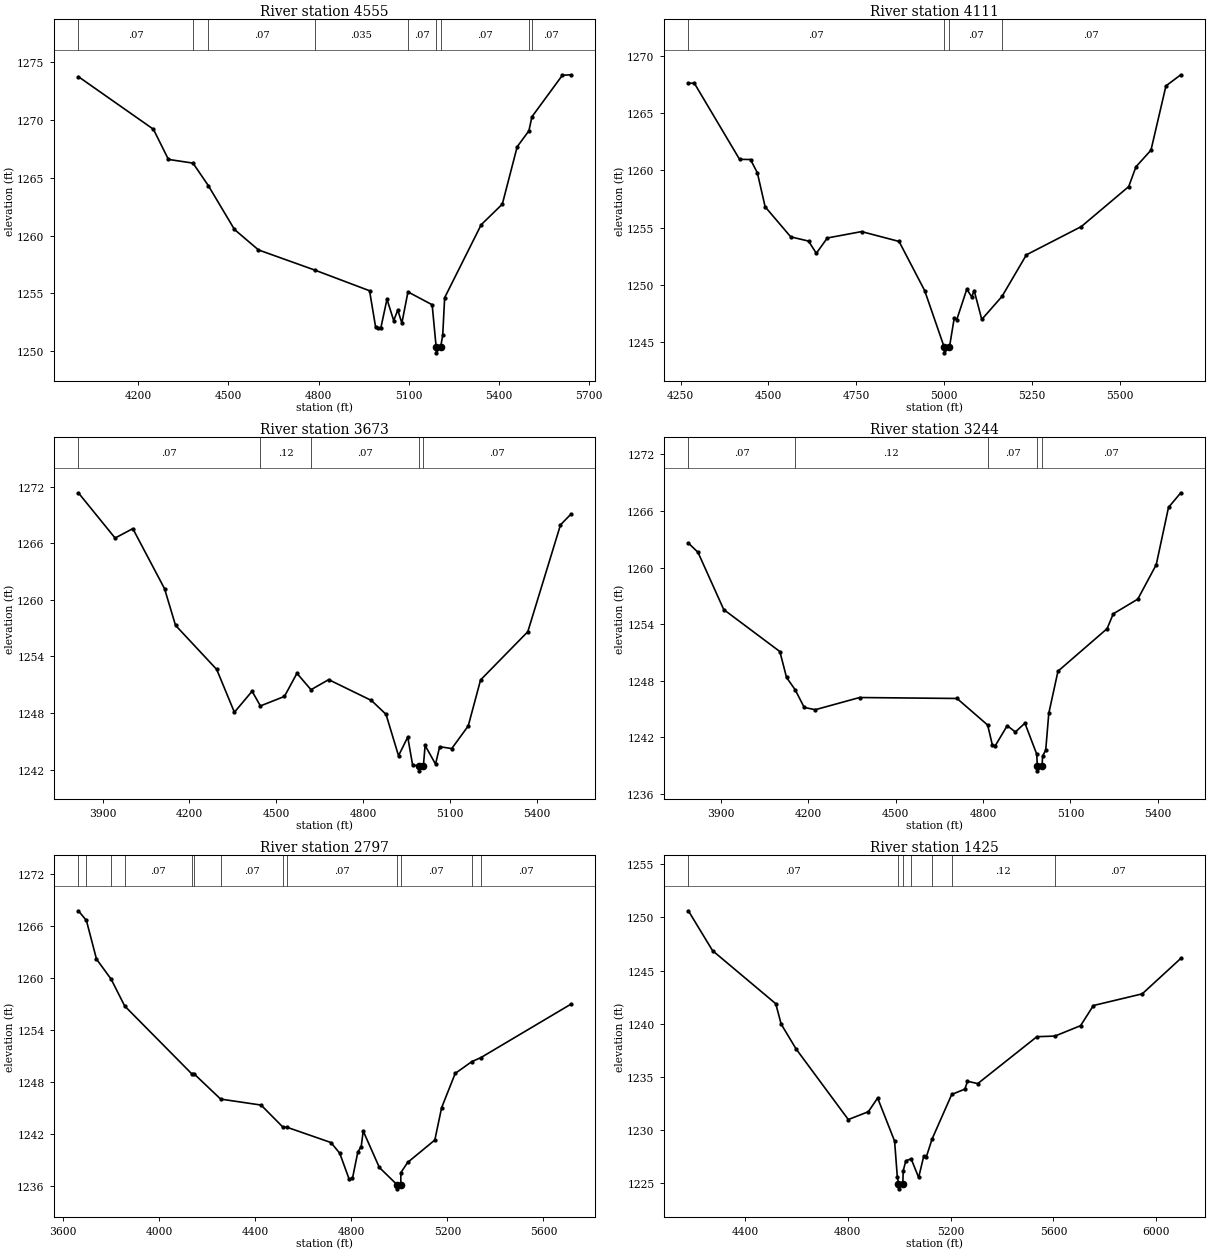
Type RM Length L Ch R = 1,4555,444,444,444
BEGIN DESCRIPTION:
KRAUSE CREEK 7.0
END DESCRIPTION:
XS GIS Cut Line= 3
      2129275.00     13896325.00      2129275.00     13895325.00
      2128775.01     13894925.01
#Sta/Elev= 30
  4000.0 1273.75  4250.0 1269.20  4300.0 1266.59  4381.8 1266.27  4433.0 1264.32
  4520.0 1260.53  4600.0 1258.76  4787.4 1257.02  4970.0 1255.23  4990.0 1252.11
  4997.5 1251.97  5007.2 1251.97  5028.0 1254.50  5050.4 1252.65  5064.0 1253.56
  5077.6 1252.43  5097.9 1255.13  5178.5 1254.02  5191.8 1250.36  5192.3 1249.86
  5206.8 1250.36  5213.7 1251.40  5220.1 1254.63  5341.8 1260.94  5412.2 1262.72
  5461.8 1267.69  5500.7 1269.06  5510.9 1270.28  5612.3 1273.87  5640.3 1273.91
#Mann=9,-1,0
  4000.0    0.07       0  4381.8    0.12       0  4433.0    0.07       0
  4787.4   0.035       0  5097.9    0.07       0  5191.8   0.035       0
  5206.8    0.07       0  5500.7    0.12       0  5510.9    0.07       0
Bank Sta=5191.8,5206.8
Exp/Cntr=0.3,0.1

Type RM Length L Ch R = 1,4111,438,438,438
BEGIN DESCRIPTION:
KRAUSE CREEK 6.0
END DESCRIPTION:
XS GIS Cut Line= 3
      2129825.01     13895775.04      2129625.00     13895075.00
      2129175.02     13894575.02
#Sta/Elev= 30
  4272.2 1267.62  4289.1 1267.63  4417.8 1260.97  4449.0 1260.95  4468.5 1259.79
  4490.6 1256.82  4563.4 1254.19  4614.1 1253.82  4636.2 1252.75  4667.4 1254.09
  4764.9 1254.65  4871.5 1253.79  4944.4 1249.49  4999.9 1244.55  5000.4 1244.05
  5014.9 1244.55  5028.3 1247.06  5035.8 1246.96  5064.2 1249.61  5078.4 1248.94
  5085.1 1249.50  5106.8 1246.97  5164.3 1248.98  5233.8 1252.62  5390.0 1255.09
  5524.6 1258.58  5545.5 1260.32  5588.1 1261.77  5630.7 1267.39  5672.9 1268.36
#Mann=4,-1,0
  4272.2    0.07       0  4999.9    0.05       0  5014.9    0.07       0
  5164.3    0.07       0
Bank Sta=4999.9,5014.9
Exp/Cntr=0.3,0.1

Type RM Length L Ch R = 1,3673,429,429,429
BEGIN DESCRIPTION:
KRAUSE CREEK 5.0
END DESCRIPTION:
XS GIS Cut Line= 3
      2130225.00     13895825.00      2129825.00     13894725.00
      2129424.98     13894374.99
#Sta/Elev= 30
  3816.2 1271.35  3943.2 1266.55  4004.4 1267.55  4114.1 1261.18  4152.0 1257.30
  4294.4 1252.62  4355.5 1248.08  4416.7 1250.31  4445.4 1248.75  4528.5 1249.76
  4571.7 1252.21  4620.3 1250.47  4681.4 1251.54  4829.1 1249.33  4879.6 1247.86
  4922.8 1243.47  4954.7 1245.45  4971.4 1242.50  4992.3 1242.37  4992.8 1241.87
  5008.6 1242.37  5014.7 1244.56  5050.7 1242.58  5065.0 1244.43  5106.7 1244.23
  5163.7 1246.63  5206.4 1251.51  5369.6 1256.62  5482.6 1267.95  5518.2 1269.07
#Mann=5,-1,0
  3816.2    0.07       0  4445.4    0.12       0  4620.3    0.07       0
  4992.3    0.05       0  5008.6    0.07       0
Bank Sta=4992.3,5008.6
Exp/Cntr=0.3,0.1

Type RM Length L Ch R = 1,3244,447,447,447
BEGIN DESCRIPTION:
KRAUSE CREEK 4.0
END DESCRIPTION:
XS GIS Cut Line= 3
      2130175.00     13895574.99      2129975.00     13894375.00
      2129524.98     13894224.99
#Sta/Elev= 30
  3787.9 1262.59  3820.8 1261.62  3909.5 1255.54  4102.2 1251.09  4125.0 1248.35
  4154.3 1247.06  4185.8 1245.17  4223.8 1244.93  4375.9 1246.22  4710.4 1246.12
  4815.7 1243.30  4832.1 1241.14  4842.2 1241.13  4882.8 1243.24  4910.7 1242.57
  4943.6 1243.50  4984.2 1240.21  4986.1 1238.95  4986.6 1238.45  5002.4 1238.95
  5004.4 1240.03  5015.0 1240.64  5025.5 1244.54  5057.1 1249.01  5225.8 1253.52
  5246.9 1255.09  5331.2 1256.65  5394.5 1260.30  5436.6 1266.37  5478.8 1267.92
#Mann=5,-1,0
  3787.9    0.07       0  4154.3    0.12       0  4815.7    0.07       0
  4986.1    0.05       0  5002.4    0.07       0
Bank Sta=4986.1,5002.4
Exp/Cntr=0.3,0.1

Type RM Length L Ch R = 1,2797,1372,1372,1372
BEGIN DESCRIPTION:
KRAUSE CREEK 3.0
END DESCRIPTION:
XS GIS Cut Line= 3
      2130974.99     13895524.97      2130375.00     13894325.00
      2129875.01     13893825.01
#Sta/Elev= 30
  3665.0 1267.77  3698.5 1266.65  3740.4 1262.19  3801.4 1259.87  3857.7 1256.77
  4135.8 1248.96  4145.2 1248.96  4256.9 1246.01  4425.2 1245.32  4516.8 1242.75
  4533.5 1242.75  4715.9 1240.99  4752.3 1239.76  4791.4 1236.77  4805.4 1236.85
  4827.7 1239.89  4841.7 1240.52  4850.1 1242.32  4917.2 1238.11  4990.0 1236.14
  4990.5 1235.64  5006.4 1236.14  5006.6 1237.51  5034.9 1238.69  5148.0 1241.28
  5176.3 1245.02  5232.9 1248.98  5302.5 1250.35  5339.4 1250.80  5713.7 1256.97
#Mann=13,-1,0
  3665.0    0.12       0  3698.5    0.07       0  3801.4    0.12       0
  3857.7    0.07       0  4135.8    0.12       0  4145.2   0.035       0
  4256.9    0.07       0  4516.8    0.12       0  4533.5    0.07       0
  4990.0    0.05       0  5006.4    0.07       0  5302.5    0.12       0
  5339.4    0.07       0
Bank Sta=4990,5006.4
Exp/Cntr=0.3,0.1

Type RM Length L Ch R = 1,1425,910,910,910
BEGIN DESCRIPTION:
KRAUSE CREEK 2.0
END DESCRIPTION:
XS GIS Cut Line= 3
      2131978.57     13894703.40      2131525.00     13894025.00
      2130424.96     13894025.00
#Sta/Elev= 30
  4179.6 1250.63  4273.9 1246.87  4519.7 1241.87  4540.7 1239.95  4598.7 1237.61
  4802.0 1230.95  4880.0 1231.69  4916.1 1232.98  4982.1 1228.92  4992.6 1225.57
  4997.2 1224.92  4997.7 1224.42  5014.1 1224.92  5015.7 1226.13  5025.7 1227.06
  5046.5 1227.25  5075.7 1225.49  5095.7 1227.52  5105.7 1227.44  5128.0 1229.12
  5204.5 1233.32  5255.7 1233.82  5265.7 1234.56  5305.7 1234.34  5535.7 1238.76
  5606.1 1238.82  5705.7 1239.80  5755.7 1241.70  5945.7 1242.80  6095.7 1246.14
#Mann=7,-1,0
  4179.6    0.07       0  4997.2    0.05       0  5014.1    0.07       0
  5046.5    0.12       0  5128.0    0.07       0  5204.5    0.12       0
  5606.1    0.07       0
Bank Sta=4997.2,5014.1
Exp/Cntr=0.3,0.1

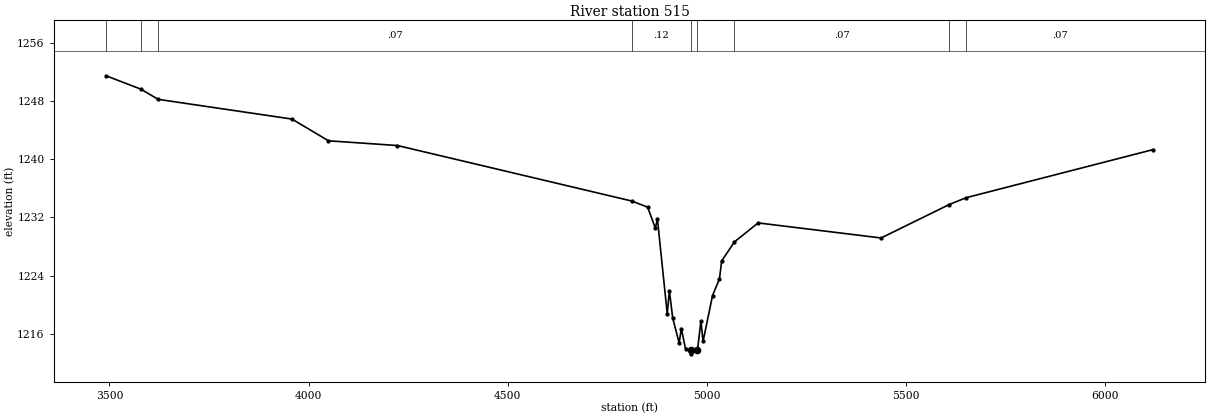
Type RM Length L Ch R = 1,515,0,0,0
BEGIN DESCRIPTION:
KRAUSE CREEK 1.0
END DESCRIPTION:
XS GIS Cut Line= 4
      2132243.07     13894613.08      2132014.02     13893436.60
      2131725.00     13893325.00      2130708.88     13893796.58
#Sta/Elev= 30
  3491.7 1251.46  3579.1 1249.62  3622.4 1248.22  3958.4 1245.51  4050.1 1242.52
  4223.3 1241.87  4811.4 1234.24  4851.4 1233.40  4870.6 1230.52  4876.0 1231.74
  4900.6 1218.72  4905.9 1221.92  4914.3 1218.16  4930.5 1214.72  4935.9 1216.71
  4946.5 1213.91  4959.4 1213.73  4959.9 1213.23  4976.5 1213.73  4985.1 1217.77
  4990.5 1214.94  5014.3 1221.25  5031.7 1223.55  5037.2 1226.00  5069.4 1228.63
  5128.8 1231.23  5437.5 1229.16  5608.6 1233.76  5651.2 1234.70  6120.3 1241.31
#Mann=9,-1,0
  3491.7    0.07       0  3579.1    0.12       0  3622.4    0.07       0
  4811.4    0.12       0  4959.4    0.05       0  4976.5    0.12       0
  5069.4    0.07       0  5608.6    0.12       0  5651.2    0.07       0
Bank Sta=4959.4,4976.5
Exp/Cntr=0.3,0.1

Chan Stop Cuts=-1