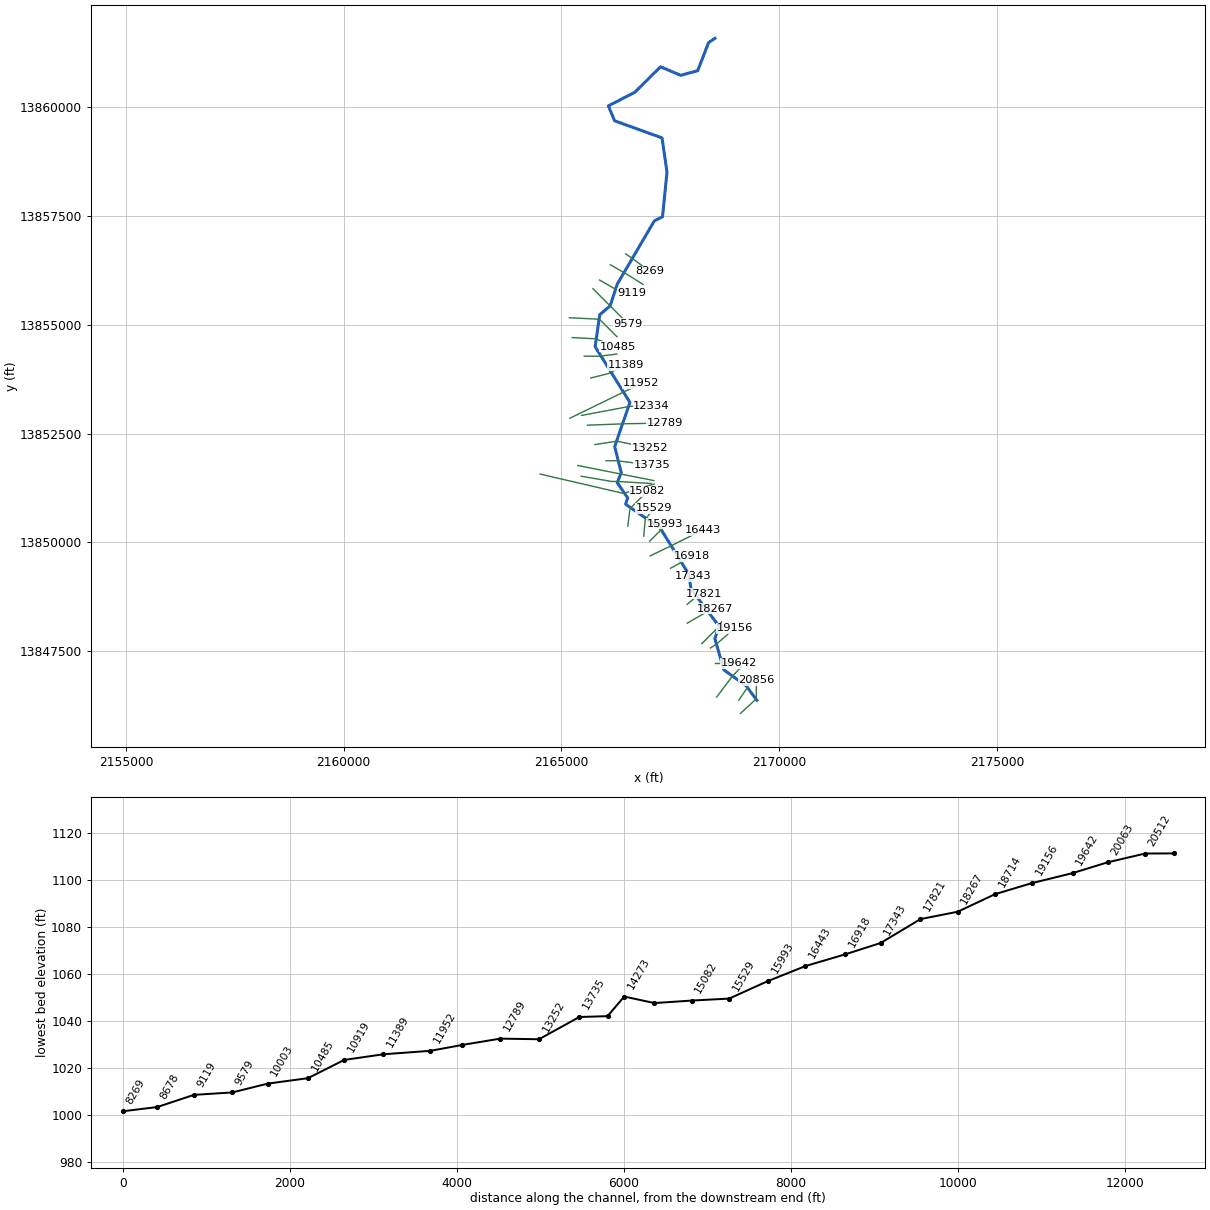
--- Miller Creek.prj (project) ---

Proj Title=Miller Creek Base Level Engineering
Current Plan=p01
Default Exp/Contr=0.3,0.1
English Units
Geom File=g01
Flow File=f01
Plan File=p01
BEGIN DESCRIPTION:
Miller Creek
END DESCRIPTION:

--- Miller Creek.p01 (plan) ---

Plan Title=Multiple Run
Short Identifier=Multiple
Geom File=g01
Flow File=f01
Subcritical Flow
K Sum by GR= 0
Std Step Tol= 0.01
Critical Tol= 0.01
Num of Std Step Trials= 20
Max Error Tol= 0.3
Flow Tol Ratio= 0.001
Split Flow NTrial= 30
Split Flow Tol= 0.02
Split Flow Ratio= 0.02
Log Output Level= 0
Friction Slope Method= 1
Unsteady Friction Slope Method= 2
Unsteady Bridges Friction Slope Method= 1
Parabolic Critical Depth
Global Vel Dist=  1 , 1 , 1
Global Log Level= 0
CheckData=True
Encroach Param= -1, 0, 0, 0
BEGIN DESCRIPTION:
Multiple Run
END DESCRIPTION:

--- Miller Creek.f01 (steady flow) ---

Flow Title=Multiple
Number of Profiles=7
Profile Names=10-year,25-year,50-year,1pct_min,100-year,1pct_plu,500-year
River Rch & RM= Miller Creek,Reach-1,20856
    1797    3137    4445    3046    6078   12128   11257
River Rch & RM= Miller Creek,Reach-1,18714
    2107    3703    5272    3627    7237   14439   13511
River Rch & RM= Miller Creek,Reach-1,14634
    2990    5324    7642    5294   10563   21075   20000
River Rch & RM= Miller Creek,Reach-1,6905
    4429    7999   11596    8101   16165   32253   31133
Boundary for River Rch & Prof#=Miller Creek,Reach-1,1
Up Type=0
Dn Type=3
Dn Slope=0.005
Boundary for River Rch & Prof#=Miller Creek,Reach-1,2
Up Type=0
Dn Type=3
Dn Slope=0.005
Boundary for River Rch & Prof#=Miller Creek,Reach-1,3
Up Type=0
Dn Type=3
Dn Slope=0.005
Boundary for River Rch & Prof#=Miller Creek,Reach-1,4
Up Type=0
Dn Type=3
Dn Slope=0.005
Boundary for River Rch & Prof#=Miller Creek,Reach-1,5
Up Type=0
Dn Type=3
Dn Slope=0.005
Boundary for River Rch & Prof#=Miller Creek,Reach-1,6
Up Type=0
Dn Type=3
Dn Slope=0.005
Boundary for River Rch & Prof#=Miller Creek,Reach-1,7
Up Type=0
Dn Type=3
Dn Slope=0.005

--- Miller Creek.g01 (geometry) ---

Geom Title=Existing Conditions

River Reach=Miller Creek,Reach-1
Reach XY= 30
      2169487.57     13846375.00      2169241.79     13846708.56
      2168730.42     13847072.33      2168525.07     13847790.39
      2168621.33     13848073.42      2167980.46     13848922.55
      2167919.48     13849277.43      2167266.96     13850331.33
      2166475.00     13850875.00      2166521.89     13851023.37
      2166282.60     13851371.66      2166375.12     13851602.30
      2166224.61     13852202.20      2166573.80     13853214.49
      2165775.07     13854495.03      2165880.52     13855227.43
      2166121.67     13855433.05      2166280.83     13855927.30
      2167132.96     13857381.31      2167321.63     13857476.26
      2167425.23     13858499.93      2167311.63     13859288.32
      2166222.70     13859680.83      2166078.43     13860023.78
      2166684.68     13860335.78      2167276.72     13860921.66
      2167740.21     13860725.51      2168131.07     13860833.13
      2168380.45     13861477.47      2168525.00     13861575.00

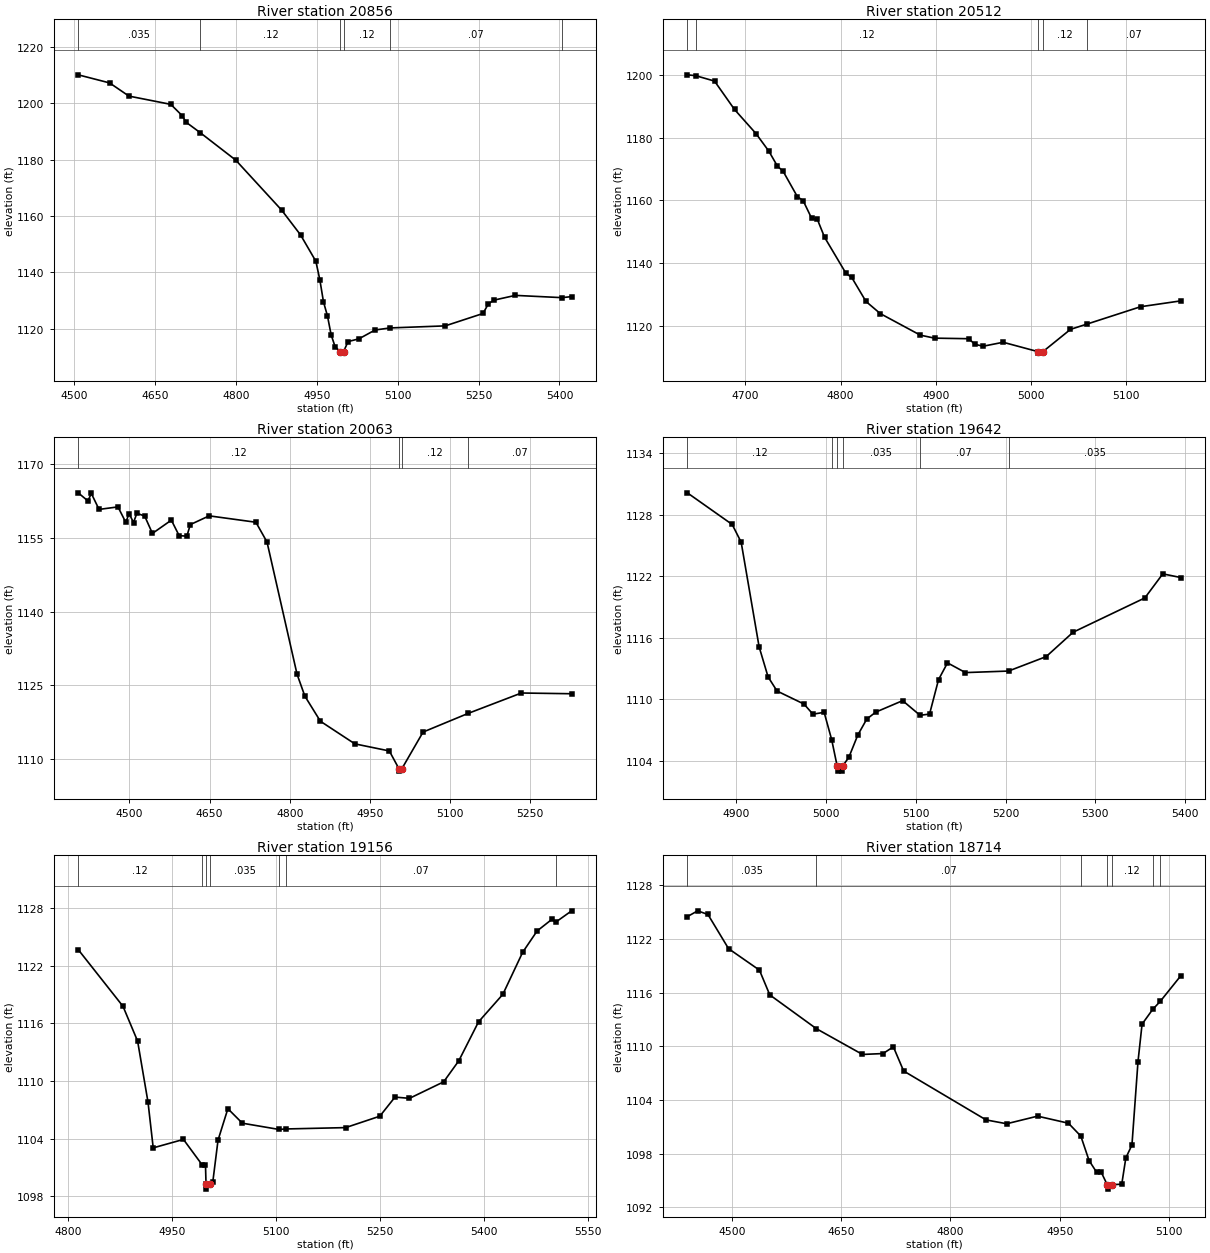
Type RM Length L Ch R = 1,20856,344,344,344
BEGIN DESCRIPTION:
Miller Creek 44.0
END DESCRIPTION:
XS GIS Cut Line= 3
      2169113.74     13846073.72      2169476.41     13846408.07
      2169477.27     13846829.29
#Sta/Elev= 30
  4508.0 1210.04  4566.2 1207.17  4602.0 1202.50  4679.6 1199.57  4700.6 1195.58
  4708.0 1193.23  4734.5 1189.48  4799.9 1179.81  4884.9 1162.11  4920.1 1153.29
  4948.4 1143.97  4955.8 1137.43  4962.6 1129.54  4970.0 1124.54  4976.8 1117.85
  4984.2 1113.61  4994.1 1111.88  4994.6 1111.38  4999.7 1111.88  5008.2 1115.48
  5028.2 1116.44  5058.2 1119.58  5085.9 1120.31  5188.2 1121.04  5258.2 1125.43
  5268.2 1128.85  5278.2 1130.15  5318.2 1131.85  5404.3 1131.05  5422.5 1131.41
#Mann=6,-1,0
  4508.0   0.035       0  4734.5    0.12       0  4994.1    0.05       0
  4999.7    0.12       0  5085.9    0.07       0  5404.3   0.035       0
Bank Sta=4994.1,4999.7
Exp/Cntr=0.3,0.1

Type RM Length L Ch R = 1,20512,449,449,449
BEGIN DESCRIPTION:
Miller Creek 43.0
END DESCRIPTION:
XS GIS Cut Line= 3
      2169074.98     13846374.97      2169275.00     13846675.00
      2169325.00     13846825.00
#Sta/Elev= 30
  4638.9 1199.97  4647.7 1199.70  4667.5 1197.97  4688.5 1188.93  4711.0 1181.28
  4724.6 1175.65  4733.6 1170.89  4739.6 1169.24  4754.6 1161.15  4760.6 1159.92
  4769.6 1154.25  4775.6 1153.92  4783.2 1148.21  4805.7 1136.73  4811.7 1135.44
  4826.7 1127.79  4841.7 1123.93  4883.8 1117.06  4898.8 1116.10  4934.9 1115.92
  4940.9 1114.16  4949.9 1113.53  4970.9 1114.79  5007.2 1111.83  5007.7 1111.33
  5012.8 1111.83  5041.7 1118.90  5059.2 1120.60  5115.4 1126.11  5157.6 1127.97
#Mann=5,-1,0
  4638.9   0.035       0  4647.7    0.12       0  5007.2    0.05       0
  5012.8    0.12       0  5059.2    0.07       0
Bank Sta=5007.2,5012.8
Exp/Cntr=0.3,0.1

Type RM Length L Ch R = 1,20063,421,421,421
BEGIN DESCRIPTION:
Miller Creek 42.0
END DESCRIPTION:
XS GIS Cut Line= 3
      2168565.94     13846449.58      2168925.00     13846925.00
      2169150.93     13847162.12
#Sta/Elev= 30
  4404.2 1164.16  4422.4 1162.51  4428.7 1164.04  4443.2 1160.79  4478.6 1161.30
  4493.2 1158.16  4499.4 1159.94  4507.7 1158.12  4514.0 1160.01  4528.6 1159.43
  4543.1 1155.91  4578.5 1158.61  4593.1 1155.45  4607.6 1155.36  4613.9 1157.70
  4649.3 1159.48  4736.7 1158.18  4757.5 1154.16  4813.7 1127.29  4828.3 1122.84
  4857.4 1117.73  4921.9 1113.13  4986.4 1111.69  5004.3 1108.09  5004.7 1107.59
  5009.9 1108.09  5049.5 1115.53  5133.5 1119.31  5233.5 1123.47  5327.5 1123.32
#Mann=4,-1,0
  4404.2    0.12       0  5004.3    0.05       0  5009.9    0.12       0
  5133.5    0.07       0
Bank Sta=5004.3,5009.9
Exp/Cntr=0.3,0.1

Type RM Length L Ch R = 1,19642,486,486,486
BEGIN DESCRIPTION:
Miller Creek 41.0
END DESCRIPTION:
XS GIS Cut Line= 3
      2168524.95     13847225.00      2168675.00     13847225.00
      2169074.95     13847225.00
#Sta/Elev= 30
  4845.3 1130.15  4895.3 1127.06  4905.3 1125.33  4925.3 1115.12  4935.3 1112.18
  4945.3 1110.80  4975.3 1109.53  4985.3 1108.54  4997.8 1108.72  5006.2 1106.05
  5012.3 1103.48  5012.8 1102.98  5017.9 1102.98  5018.4 1103.48  5025.3 1104.32
  5035.3 1106.50  5045.3 1108.06  5055.3 1108.74  5085.3 1109.86  5104.7 1108.43
  5115.3 1108.55  5125.3 1111.91  5135.3 1113.55  5155.3 1112.60  5203.3 1112.75
  5245.3 1114.16  5275.3 1116.54  5355.3 1119.89  5375.3 1122.24  5395.3 1121.88
#Mann=6,-1,0
  4845.3    0.12       0  5006.2   0.035       0  5012.3    0.05       0
  5018.4   0.035       0  5104.7    0.07       0  5203.3   0.035       0
Bank Sta=5012.3,5018.4
Exp/Cntr=0.3,0.1

Type RM Length L Ch R = 1,19156,442,442,442
BEGIN DESCRIPTION:
Miller Creek 40.0
END DESCRIPTION:
XS GIS Cut Line= 3
      2168424.97     13847574.98      2168575.00     13847675.00
      2168974.99     13848024.99
#Sta/Elev= 30
  4814.8 1123.69  4879.4 1117.78  4900.5 1114.15  4915.5 1107.79  4923.0 1103.03
  4966.6 1103.91  4993.5 1101.27  4998.4 1101.27  4999.2 1099.23  4999.7 1098.73
  5005.3 1099.23  5008.9 1099.45  5016.5 1103.83  5030.7 1107.11  5051.6 1105.60
  5104.4 1104.95  5114.8 1105.00  5200.6 1105.14  5249.9 1106.33  5271.8 1108.32
  5292.7 1108.19  5342.0 1109.91  5363.8 1112.10  5392.3 1116.16  5427.4 1119.03
  5455.9 1123.40  5476.8 1125.63  5498.6 1126.87  5503.5 1126.54  5526.6 1127.73
#Mann=7,-1,0
  4814.8    0.12       0  4993.5   0.035       0  4999.2   0.035       0
  5005.3   0.035       0  5104.4    0.12       0  5114.8    0.07       0
  5503.5    0.12       0
Bank Sta=4999.2,5005.3
Exp/Cntr=0.3,0.1

Type RM Length L Ch R = 1,18714,447,447,447
BEGIN DESCRIPTION:
Miller Creek 39.0
END DESCRIPTION:
XS GIS Cut Line= 3
      2168224.97     13847674.97      2168625.00     13848075.00
      2168674.99     13848174.97
#Sta/Elev= 30
  4438.7 1124.49  4452.9 1125.14  4467.0 1124.73  4495.3 1120.91  4537.7 1118.51
  4551.9 1115.74  4615.9 1111.96  4679.2 1109.08  4707.4 1109.18  4721.6 1109.93
  4735.7 1107.23  4848.9 1101.76  4877.2 1101.33  4919.6 1102.18  4962.0 1101.39
  4979.0 1099.95  4990.3 1097.22  5000.9 1095.88  5007.2 1095.88  5015.2 1094.52
  5015.7 1094.02  5021.6 1094.52  5035.2 1094.57  5040.8 1097.51  5049.2 1098.96
  5057.5 1108.28  5063.1 1112.47  5077.7 1114.12  5088.0 1115.01  5116.2 1117.87
#Mann=7,-1,0
  4438.7   0.035       0  4615.9    0.07       0  4979.0    0.12       0
  5015.2    0.05       0  5021.6    0.12       0  5077.7   0.035       0
  5088.0    0.07       0
Bank Sta=5015.2,5021.6
Exp/Cntr=0.3,0.1

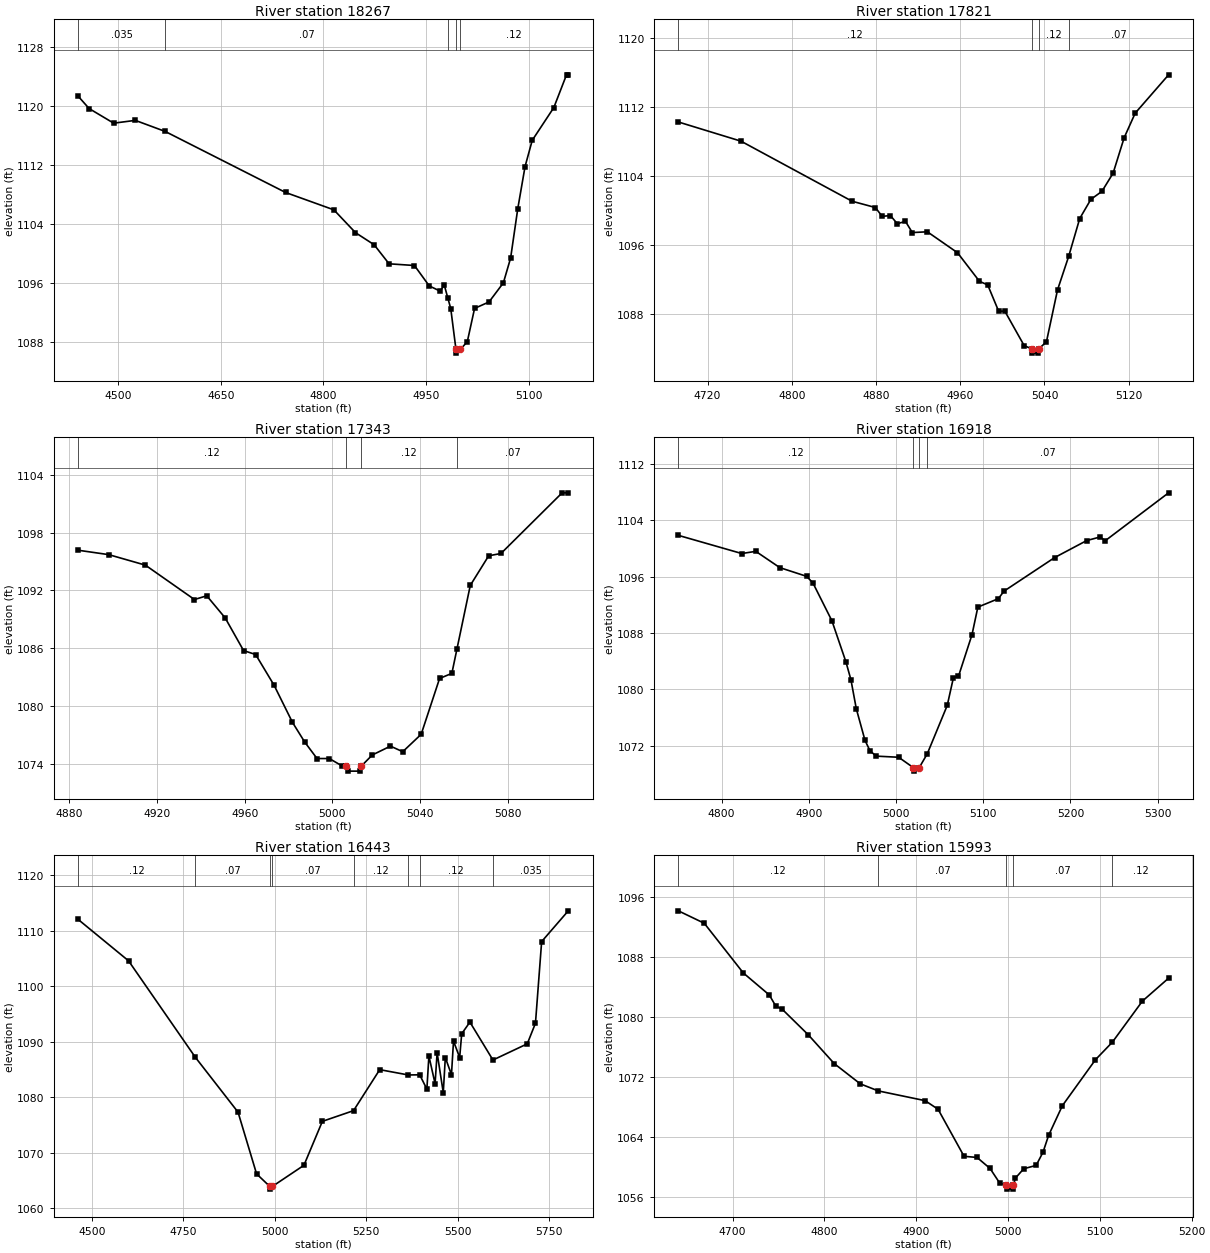
Type RM Length L Ch R = 1,18267,446,446,446
BEGIN DESCRIPTION:
Miller Creek 38.0
END DESCRIPTION:
XS GIS Cut Line= 3
      2167890.93     13848146.25      2168375.00     13848425.00
      2168524.99     13848475.00
#Sta/Elev= 30
  4441.4 1121.36  4457.6 1119.67  4493.5 1117.69  4525.1 1118.07  4568.8 1116.57
  4744.9 1108.30  4815.4 1105.95  4847.0 1102.86  4874.3 1101.22  4896.1 1098.64
  4933.2 1098.41  4954.8 1095.65  4970.5 1094.95  4976.9 1095.73  4982.0 1094.01
  4986.3 1092.56  4993.9 1087.04  4994.4 1086.54  5000.4 1087.04  5010.5 1088.10
  5021.1 1092.60  5042.2 1093.47  5063.2 1096.06  5073.8 1099.42  5084.3 1106.13
  5094.9 1111.81  5105.4 1115.37  5137.0 1119.81  5155.5 1124.24  5158.1 1124.24
#Mann=5,-1,0
  4441.4   0.035       0  4568.8    0.07       0  4982.0    0.12       0
  4993.9    0.05       0  5000.4    0.12       0
Bank Sta=4993.9,5000.4
Exp/Cntr=0.3,0.1

Type RM Length L Ch R = 1,17821,478,478,478
BEGIN DESCRIPTION:
Miller Creek 37.0
END DESCRIPTION:
XS GIS Cut Line= 3
      2167889.09     13848577.85      2168125.00     13848775.00
      2168275.04     13848825.01
#Sta/Elev= 30
  4692.3 1110.27  4751.8 1108.04  4857.3 1101.06  4879.4 1100.33  4885.9 1099.30
  4893.7 1099.40  4900.2 1098.45  4908.0 1098.72  4914.5 1097.42  4928.8 1097.51
  4957.4 1095.08  4978.3 1091.75  4986.1 1091.34  4996.5 1088.28  5002.4 1088.28
  5020.8 1084.27  5028.1 1083.91  5028.6 1083.41  5034.2 1083.41  5034.7 1083.91
  5041.9 1084.73  5052.4 1090.75  5063.0 1094.65  5073.5 1099.05  5084.1 1101.28
  5094.6 1102.21  5105.2 1104.32  5115.7 1108.44  5126.2 1111.30  5157.9 1115.75
#Mann=4,-1,0
  4692.3    0.12       0  5028.1    0.05       0  5034.7    0.12       0
  5063.0    0.07       0
Bank Sta=5028.1,5034.7
Exp/Cntr=0.3,0.1

Type RM Length L Ch R = 1,17343,425,425,425
BEGIN DESCRIPTION:
Miller Creek 36.0
END DESCRIPTION:
XS GIS Cut Line= 3
      2167825.01     13849125.00      2167925.00     13849175.00
      2168025.00     13849225.00
#Sta/Elev= 30
  4884.0 1096.19  4898.0 1095.73  4914.7 1094.64  4937.1 1091.06  4942.7 1091.45
  4951.1 1089.15  4959.5 1085.75  4965.0 1085.34  4973.4 1082.15  4981.8 1078.28
  4987.4 1076.23  4993.0 1074.52  4998.6 1074.52  5004.2 1073.78  5006.4 1073.71
  5006.9 1073.21  5012.6 1073.21  5013.1 1073.71  5018.2 1074.89  5026.5 1075.81
  5032.1 1075.23  5040.5 1077.04  5048.9 1082.85  5054.5 1083.38  5056.8 1085.89
  5062.9 1092.53  5071.3 1095.61  5076.9 1095.85  5104.8 1102.16  5107.6 1102.16
#Mann=4,-1,0
  4884.0    0.12       0  5006.4    0.05       0  5013.1    0.12       0
  5056.8    0.07       0
Bank Sta=5006.4,5013.1
Exp/Cntr=0.3,0.1

Type RM Length L Ch R = 1,16918,475,475,475
BEGIN DESCRIPTION:
Miller Creek 35.0
END DESCRIPTION:
XS GIS Cut Line= 3
      2167505.97     13849405.25      2167725.00     13849525.00
      2167991.47     13849688.19
#Sta/Elev= 30
  4750.4 1101.86  4823.1 1099.28  4839.2 1099.59  4866.7 1097.28  4897.5 1096.04
  4904.7 1095.10  4926.5 1089.72  4942.6 1083.87  4948.3 1081.34  4954.4 1077.25
  4964.4 1072.75  4970.1 1071.28  4977.2 1070.51  5003.0 1070.35  5019.8 1068.88
  5020.3 1068.38  5026.6 1068.88  5035.8 1070.84  5058.7 1077.71  5065.8 1081.66
  5071.6 1081.85  5087.1 1087.76  5093.8 1091.67  5117.3 1092.87  5123.8 1093.94
  5181.9 1098.71  5218.6 1101.12  5234.0 1101.63  5239.9 1101.10  5312.5 1107.90
#Mann=4,-1,0
  4750.4    0.12       0  5019.8    0.05       0  5026.6    0.12       0
  5035.8    0.07       0
Bank Sta=5019.8,5026.6
Exp/Cntr=0.3,0.1

Type RM Length L Ch R = 1,16443,450,450,450
BEGIN DESCRIPTION:
Miller Creek 34.0
END DESCRIPTION:
XS GIS Cut Line= 3
      2167037.30     13849689.15      2167525.00     13849925.00
      2168239.96     13850280.06
#Sta/Elev= 30
  4462.2 1112.08  4600.2 1104.60  4782.8 1087.19  4899.5 1077.29  4950.2 1066.15
  4986.1 1063.90  4986.6 1063.40  4993.6 1063.90  5079.6 1067.70  5130.0 1075.63
  5215.2 1077.56  5286.8 1084.96  5365.1 1084.00  5396.0 1084.03  5415.7 1081.45
  5421.2 1087.42  5438.1 1082.43  5443.7 1088.00  5460.5 1080.81  5466.1 1087.15
  5482.9 1084.05  5488.5 1090.12  5505.3 1087.14  5510.9 1091.44  5533.3 1093.54
  5596.3 1086.70  5690.1 1089.62  5712.5 1093.34  5729.4 1108.07  5802.2 1113.62
#Mann=8,-1,0
  4462.2    0.12       0  4782.8    0.07       0  4986.1    0.05       0
  4993.6    0.07       0  5215.2    0.12       0  5365.1   0.035       0
  5396.0    0.12       0  5596.3   0.035       0
Bank Sta=4986.1,4993.6
Exp/Cntr=0.3,0.1

Type RM Length L Ch R = 1,15993,464,464,464
BEGIN DESCRIPTION:
Miller Creek 33.0
END DESCRIPTION:
XS GIS Cut Line= 3
      2167025.03     13850025.03      2167275.00     13850275.00
      2167375.00     13850425.00
#Sta/Elev= 30
  4641.0 1094.15  4669.2 1092.49  4711.7 1085.86  4740.0 1082.92  4747.0 1081.45
  4754.1 1081.01  4782.4 1077.61  4810.7 1073.76  4839.0 1071.06  4858.7 1070.11
  4909.7 1068.81  4923.8 1067.66  4952.1 1061.38  4966.2 1061.23  4980.4 1059.76
  4991.0 1057.79  4998.3 1057.50  4998.8 1057.00  5005.3 1057.00  5005.8 1057.50
  5008.0 1058.47  5017.1 1059.72  5030.6 1060.17  5038.1 1061.94  5044.1 1064.16
  5059.1 1068.13  5095.2 1074.28  5113.6 1076.62  5146.3 1082.10  5174.8 1085.16
#Mann=5,-1,0
  4641.0    0.12       0  4858.7    0.07       0  4998.3    0.05       0
  5005.8    0.07       0  5113.6    0.12       0
Bank Sta=4998.3,5005.8
Exp/Cntr=0.3,0.1

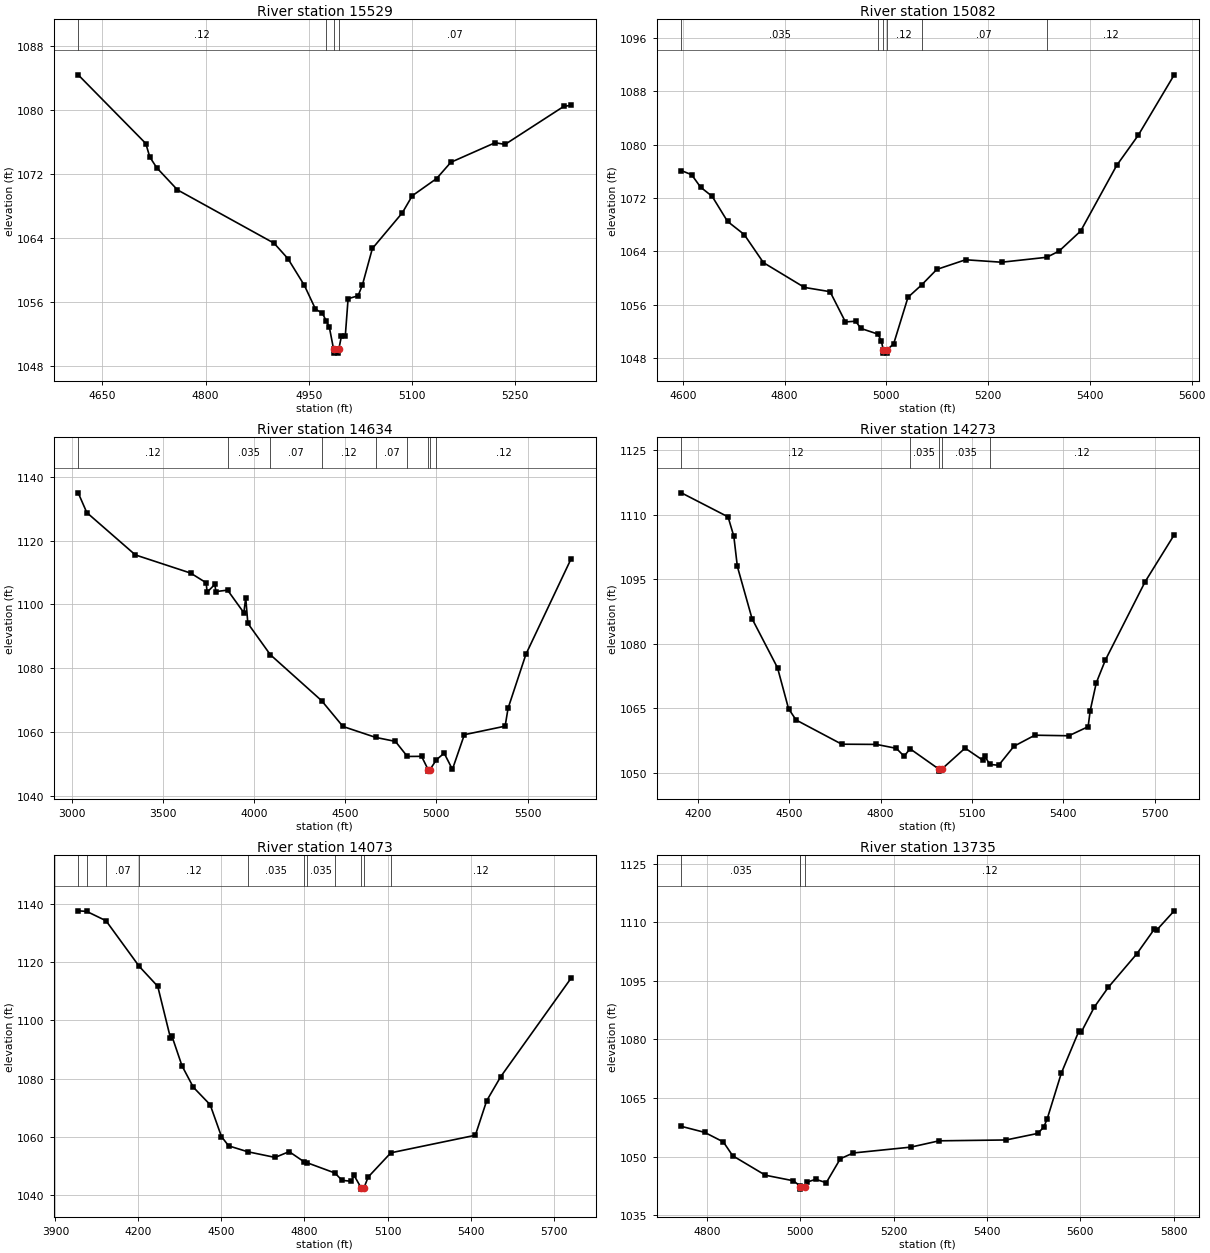
Type RM Length L Ch R = 1,15529,447,447,447
BEGIN DESCRIPTION:
Miller Creek 32.0
END DESCRIPTION:
XS GIS Cut Line= 3
      2166891.52     13850141.28      2166925.00     13850525.00
      2167127.64     13850787.13
#Sta/Elev= 30
  4614.8 1084.39  4713.1 1075.79  4718.9 1074.10  4729.0 1072.76  4759.1 1069.99
  4899.6 1063.31  4919.7 1061.38  4943.6 1058.04  4959.8 1055.06  4969.9 1054.53
  4975.4 1053.58  4979.9 1052.81  4986.1 1050.05  4986.6 1049.55  4993.2 1049.55
  4993.7 1050.05  4997.5 1051.67  5003.1 1051.67  5007.2 1056.36  5021.7 1056.73
  5028.0 1058.08  5042.5 1062.65  5086.0 1067.11  5100.5 1069.25  5135.8 1071.40
  5156.6 1073.44  5220.9 1075.89  5235.4 1075.68  5320.6 1080.43  5331.3 1080.58
#Mann=4,-1,0
  4614.8    0.12       0  4975.4    0.07       0  4986.1    0.05       0
  4993.7    0.07       0
Bank Sta=4986.1,4993.7
Exp/Cntr=0.3,0.1

Type RM Length L Ch R = 1,15082,448,448,448
BEGIN DESCRIPTION:
Miller Creek 31.0
END DESCRIPTION:
XS GIS Cut Line= 3
      2166525.00     13850374.99      2166575.00     13850775.00
      2166975.00     13851175.00
#Sta/Elev= 30
  4596.9 1076.10  4617.1 1075.48  4634.7 1073.61  4657.4 1072.24  4687.6 1068.48
  4720.4 1066.51  4758.2 1062.29  4838.8 1058.57  4889.2 1057.93  4919.4 1053.39
  4939.6 1053.50  4949.6 1052.42  4983.0 1051.57  4989.9 1050.59  4993.7 1049.21
  4994.2 1048.71  5000.8 1048.71  5001.3 1049.21  5014.2 1050.10  5042.4 1057.09
  5069.0 1058.93  5099.0 1061.27  5155.6 1062.72  5226.3 1062.35  5315.0 1063.09
  5339.4 1064.02  5381.9 1067.04  5452.6 1076.87  5495.0 1081.40  5565.7 1090.47
#Mann=6,-1,0
  4596.9   0.035       0  4983.0    0.12       0  4993.7    0.05       0
  5001.3    0.12       0  5069.0    0.07       0  5315.0    0.12       0
Bank Sta=4993.7,5001.3
Exp/Cntr=0.3,0.1

Type RM Length L Ch R = 1,14634,361,361,361
BEGIN DESCRIPTION:
Miller Creek 30.0
END DESCRIPTION:
XS GIS Cut Line= 3
      2164509.41     13851569.65      2166425.00     13851125.00
      2167130.72     13851341.14
#Sta/Elev= 30
  3034.1 1134.97  3081.4 1128.77  3347.8 1115.49  3651.2 1109.79  3736.5 1106.75
  3741.6 1103.78  3784.3 1106.27  3789.4 1103.98  3853.9 1104.44  3943.2 1097.35
  3953.5 1102.06  3965.1 1094.03  4088.5 1084.18  4370.1 1069.75  4487.1 1061.66
  4666.7 1058.23  4774.8 1056.98  4840.5 1052.25  4918.5 1052.29  4954.4 1048.15
  4954.9 1047.65  4964.8 1048.15  5000.1 1051.22  5042.5 1053.28  5087.8 1048.20
  5153.3 1059.08  5377.1 1061.76  5393.1 1067.34  5491.4 1084.34  5738.7 1114.22
#Mann=9,-1,0
  3034.1    0.12       0  3853.9   0.035       0  4088.5    0.07       0
  4370.1    0.12       0  4666.7    0.07       0  4840.5   0.035       0
  4954.4   0.035       0  4964.8   0.035       0  5000.1    0.12       0
Bank Sta=4954.4,4964.8
Exp/Cntr=0.3,0.1

Type RM Length L Ch R = 1,14273,200,200,200
BEGIN DESCRIPTION:
Miller Creek 29.5
END DESCRIPTION:
XS GIS Cut Line= 4
      2165453.89     13851519.86      2166149.25     13851400.07
      2166297.44     13851398.31      2167060.31     13851353.21
#Sta/Elev= 30
  4146.2 1115.11  4299.5 1109.52  4318.4 1105.02  4330.0 1098.00  4378.3 1085.85
  4461.9 1074.44  4498.1 1064.93  4522.8 1062.31  4672.7 1056.68  4786.6 1056.63
  4851.8 1055.72  4877.6 1053.88  4896.9 1055.62  4990.9 1050.92  4991.4 1050.42
  5001.7 1050.92  5077.7 1055.77  5136.8 1052.91  5141.8 1054.01  5158.5 1051.98
  5187.9 1051.78  5238.0 1056.20  5306.7 1058.77  5418.3 1058.64  5481.6 1060.75
  5488.4 1064.48  5508.4 1070.95  5538.5 1076.28  5668.7 1094.44  5764.2 1105.35
#Mann=5,-1,0
  4146.2    0.12       0  4896.9   0.035       0  4990.9   0.035       0
  5001.7   0.035       0  5158.5    0.12       0
Bank Sta=4990.9,5001.7
Exp/Cntr=0.3,0.1

Type RM Length L Ch R = 1,14073,338,338,338
BEGIN DESCRIPTION:
Miller Creek 29.0
END DESCRIPTION:
XS GIS Cut Line= 2
      2165377.05     13851765.68      2167124.12     13851419.66
#Sta/Elev= 30
  3982.2 1137.54  4013.1 1137.34  4082.7 1134.14  4202.7 1118.49  4269.7 1111.64
  4315.8 1093.85  4320.9 1094.57  4357.3 1084.38  4398.1 1077.05  4459.2 1071.01
  4500.0 1060.09  4525.8 1056.92  4594.9 1054.89  4693.7 1052.95  4744.7 1054.93
  4797.0 1051.54  4809.0 1051.14  4910.0 1047.60  4935.6 1045.09  4968.9 1044.76
  4979.1 1046.80  5004.3 1042.57  5004.8 1042.07  5015.2 1042.57  5030.1 1046.21
  5112.1 1054.53  5417.5 1060.55  5458.3 1072.37  5509.2 1080.65  5763.2 1114.41
#Mann=11,-1,0
  3982.2    0.07       0  4013.1    0.12       0  4082.7    0.07       0
  4202.7    0.12       0  4594.9   0.035       0  4797.0    0.12       0
  4809.0   0.035       0  4910.0    0.07       0  5004.3    0.05       0
  5015.2    0.07       0  5112.1    0.12       0
Bank Sta=5004.3,5015.2
Exp/Cntr=0.3,0.1

Type RM Length L Ch R = 1,13735,483,483,483
BEGIN DESCRIPTION:
Miller Creek 28.0
END DESCRIPTION:
XS GIS Cut Line= 3
      2166025.02     13851875.00      2166275.00     13851875.00
      2167074.99     13851775.00
#Sta/Elev= 30
  4745.1 1057.77  4795.1 1056.23  4835.1 1053.78  4855.1 1050.25  4925.1 1045.27
  4985.1 1043.85  4998.5 1042.61  4999.7 1042.21  5000.2 1041.71  5010.6 1042.21
  5015.2 1043.52  5032.9 1044.23  5055.6 1043.35  5085.8 1049.49  5113.5 1050.96
  5237.0 1052.46  5297.4 1054.07  5441.0 1054.29  5509.1 1055.97  5521.7 1057.58
  5529.2 1059.72  5559.4 1071.39  5597.2 1082.21  5602.3 1081.93  5630.0 1088.28
  5660.2 1093.37  5720.7 1101.85  5758.5 1108.19  5763.5 1107.96  5801.3 1112.92
#Mann=4,-1,0
  4745.1   0.035       0  4998.5    0.12       0  4999.7    0.05       0
  5010.6    0.12       0
Bank Sta=4999.7,5010.6
Exp/Cntr=0.3,0.1

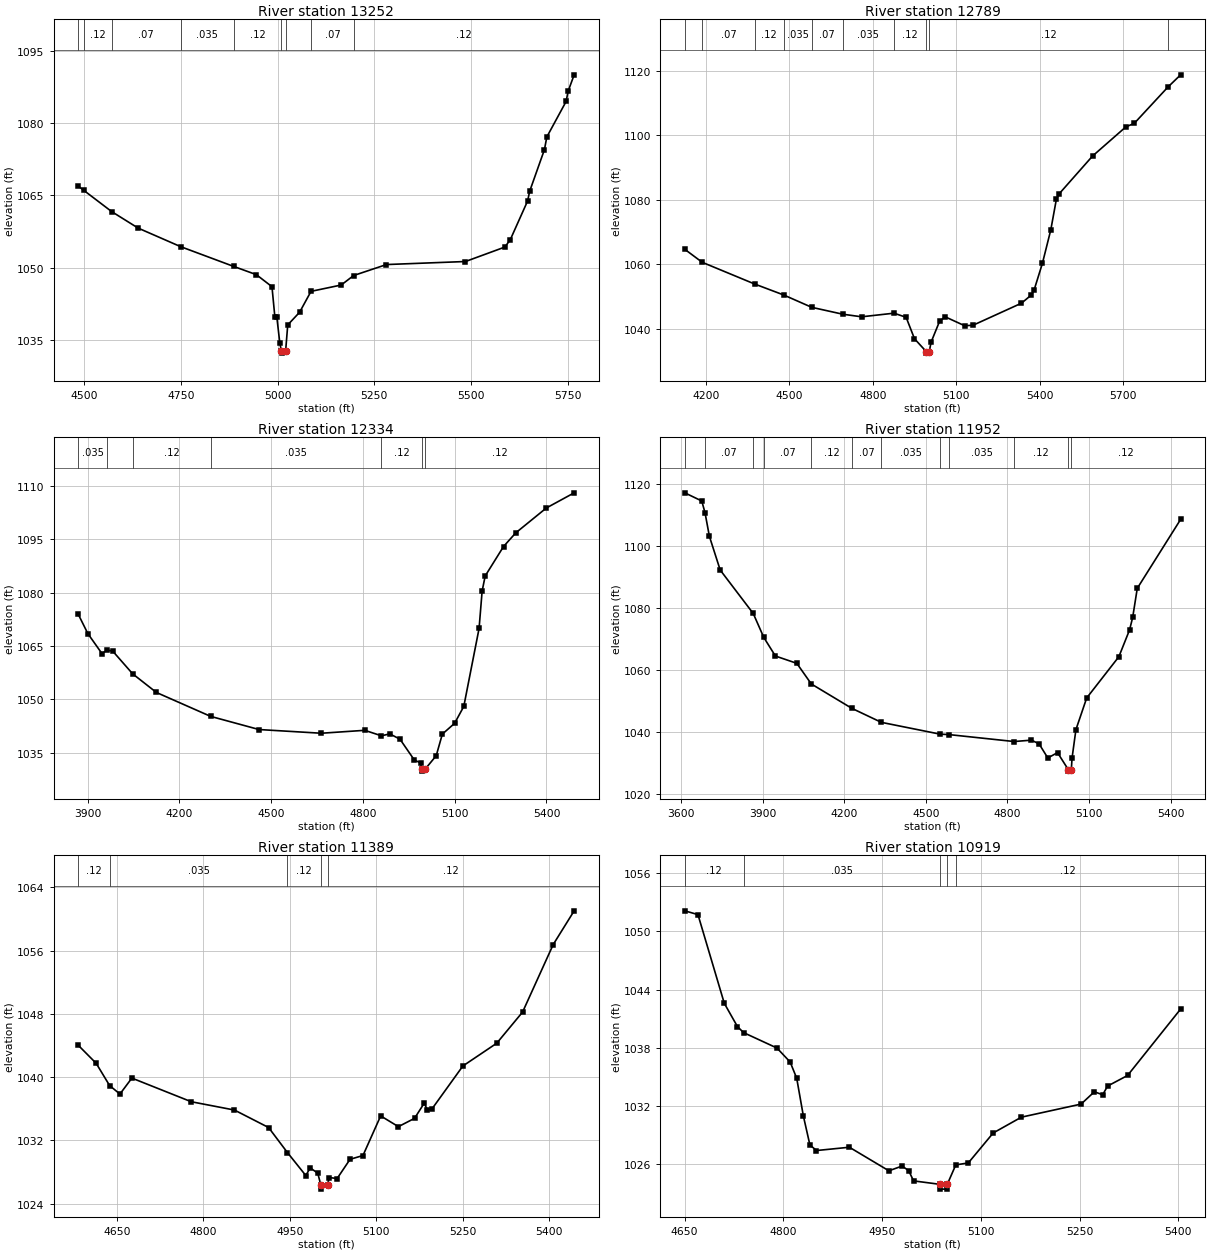
Type RM Length L Ch R = 1,13252,463,463,463
BEGIN DESCRIPTION:
Miller Creek 27.0
END DESCRIPTION:
XS GIS Cut Line= 3
      2165769.96     13852245.45      2166275.00     13852325.00
      2167030.20     13852165.64
#Sta/Elev= 30
  4484.1 1066.94  4497.7 1066.08  4570.4 1061.64  4638.9 1058.21  4749.1 1054.35
  4885.8 1050.26  4944.8 1048.54  4985.2 1046.04  4992.8 1039.66  4997.9 1039.66
  5005.6 1034.26  5009.6 1032.74  5010.1 1032.24  5020.6 1032.74  5026.0 1038.10
  5056.7 1040.73  5086.2 1045.07  5164.4 1046.39  5196.5 1048.36  5281.5 1050.64
  5485.9 1051.27  5588.1 1054.28  5602.1 1055.84  5646.8 1063.86  5651.9 1065.82
  5690.3 1074.52  5696.5 1077.15  5746.3 1084.51  5751.7 1086.67  5767.2 1090.05
#Mann=9,-1,0
  4484.1    0.07       0  4497.7    0.12       0  4570.4    0.07       0
  4749.1   0.035       0  4885.8    0.12       0  5009.6    0.05       0
  5020.6    0.12       0  5086.2    0.07       0  5196.5    0.12       0
Bank Sta=5009.6,5020.6
Exp/Cntr=0.3,0.1

Type RM Length L Ch R = 1,12789,455,455,455
BEGIN DESCRIPTION:
Miller Creek 26.0
END DESCRIPTION:
XS GIS Cut Line= 3
      2165599.73     13852691.73      2166475.00     13852725.00
      2167381.80     13852738.58
#Sta/Elev= 30
  4124.1 1064.65  4186.7 1060.63  4375.7 1053.89  4479.4 1050.52  4580.7 1046.68
  4692.3 1044.55  4759.8 1043.75  4876.2 1044.87  4919.9 1043.60  4950.0 1036.95
  4992.0 1033.00  4992.5 1032.50  5003.0 1033.00  5010.0 1035.97  5040.0 1042.32
  5060.0 1043.76  5130.0 1041.00  5160.0 1041.12  5334.5 1047.96  5370.0 1050.49
  5380.0 1052.03  5410.0 1060.33  5440.1 1070.69  5460.1 1080.13  5470.1 1081.83
  5590.1 1093.53  5710.1 1102.58  5740.1 1103.65  5861.2 1114.90  5906.9 1118.69
#Mann=10,-1,0
  4124.1   0.035       0  4186.7    0.07       0  4375.7    0.12       0
  4479.4   0.035       0  4580.7    0.07       0  4692.3   0.035       0
  4876.2    0.12       0  4992.0    0.05       0  5003.0    0.12       0
  5861.2    0.07       0
Bank Sta=4992,5003
Exp/Cntr=0.3,0.1

Type RM Length L Ch R = 1,12334,382,382,382
BEGIN DESCRIPTION:
Miller Creek 25.0
END DESCRIPTION:
XS GIS Cut Line= 3
      2165464.30     13852915.68      2166575.00     13853125.00
      2167065.93     13853129.23
#Sta/Elev= 30
  3869.3 1073.86  3900.5 1068.47  3946.5 1062.87  3963.2 1063.85  3981.9 1063.54
  4046.8 1057.18  4124.4 1051.94  4301.9 1045.21  4460.2 1041.51  4663.7 1040.47
  4805.8 1041.29  4860.4 1039.75  4887.6 1040.29  4920.9 1038.81  4968.2 1032.91
  4989.4 1032.11  4991.4 1030.32  4991.9 1029.82  5002.7 1030.32  5039.5 1034.16
  5059.5 1040.23  5099.6 1043.26  5129.6 1048.00  5179.6 1069.92  5189.6 1080.44
  5199.6 1084.68  5259.6 1092.96  5299.6 1096.80  5399.6 1103.79  5490.5 1108.05
#Mann=7,-1,0
  3869.3   0.035       0  3963.2    0.07       0  4046.8    0.12       0
  4301.9   0.035       0  4860.4    0.12       0  4991.4    0.05       0
  5002.7    0.12       0
Bank Sta=4991.4,5002.7
Exp/Cntr=0.3,0.1

Type RM Length L Ch R = 1,11952,563,563,563
BEGIN DESCRIPTION:
Miller Creek 24.0
END DESCRIPTION:
XS GIS Cut Line= 2
      2165195.74     13852851.84      2166833.77     13853649.44
#Sta/Elev= 30
  3614.3 1117.03  3676.6 1114.40  3688.5 1110.65  3704.7 1103.00  3744.3 1092.15
  3865.8 1078.13  3904.5 1070.42  3947.2 1064.42  4025.9 1062.06  4079.2 1055.41
  4228.4 1047.54  4336.4 1043.04  4552.4 1039.23  4584.8 1039.09  4824.5 1036.85
  4888.1 1037.30  4916.2 1036.08  4948.2 1031.55  4983.9 1033.28  5023.3 1027.81
  5023.8 1027.31  5034.6 1027.81  5037.2 1031.49  5051.5 1040.69  5091.0 1050.89
  5209.3 1064.20  5248.5 1072.83  5260.0 1076.85  5276.9 1086.24  5436.2 1108.46
#Mann=12,-1,0
  3614.3    0.12       0  3688.5    0.07       0  3865.8   0.035       0
  3904.5    0.07       0  4079.2    0.12       0  4228.4    0.07       0
  4336.4   0.035       0  4552.4    0.07       0  4584.8   0.035       0
  4824.5    0.12       0  5023.3    0.05       0  5034.6    0.12       0
Bank Sta=5023.3,5034.6
Exp/Cntr=0.3,0.1

Type RM Length L Ch R = 1,11389,470,470,470
BEGIN DESCRIPTION:
Miller Creek 23.0
END DESCRIPTION:
XS GIS Cut Line= 3
      2165675.01     13853775.00      2166075.00     13853875.00
      2166474.99     13854075.00
#Sta/Elev= 30
  4583.4 1044.02  4614.3 1041.75  4637.6 1038.94  4655.5 1037.86  4676.2 1039.88
  4779.2 1036.89  4854.0 1035.84  4913.2 1033.63  4945.8 1030.47  4977.7 1027.56
  4985.4 1028.53  4998.5 1027.85  5003.8 1026.34  5004.3 1025.84  5015.5 1026.34
  5018.1 1027.31  5032.0 1027.18  5054.4 1029.61  5076.8 1030.09  5107.5 1035.10
  5138.2 1033.74  5166.2 1034.79  5183.0 1036.71  5188.6 1035.83  5196.9 1036.03
  5250.0 1041.41  5308.7 1044.29  5353.5 1048.23  5406.6 1056.77  5442.9 1061.03
#Mann=5,-1,0
  4583.4    0.12       0  4637.6   0.035       0  4945.8    0.12       0
  5003.8    0.05       0  5015.5    0.12       0
Bank Sta=5003.8,5015.5
Exp/Cntr=0.3,0.1

Type RM Length L Ch R = 1,10919,434,434,434
BEGIN DESCRIPTION:
Miller Creek 22.0
END DESCRIPTION:
XS GIS Cut Line= 3
      2165525.01     13854275.00      2165875.00     13854275.00
      2166275.00     13854325.00
#Sta/Elev= 30
  4650.4 1052.13  4670.4 1051.74  4710.4 1042.59  4730.4 1040.19  4739.7 1039.57
  4790.4 1037.98  4810.4 1036.54  4820.4 1034.86  4830.4 1031.00  4840.4 1027.99
  4850.4 1027.41  4900.4 1027.75  4960.4 1025.32  4980.4 1025.81  4990.4 1025.34
  4997.9 1024.28  5037.4 1023.93  5037.9 1023.43  5048.6 1023.43  5049.1 1023.93
  5062.0 1025.93  5081.0 1026.13  5118.8 1029.22  5161.6 1030.85  5252.3 1032.20
  5272.5 1033.47  5285.1 1033.16  5292.6 1034.06  5322.9 1035.15  5403.5 1042.00
#Mann=5,-1,0
  4650.4    0.12       0  4739.7   0.035       0  5037.4   0.035       0
  5049.1   0.035       0  5062.0    0.12       0
Bank Sta=5037.4,5049.1
Exp/Cntr=0.3,0.1

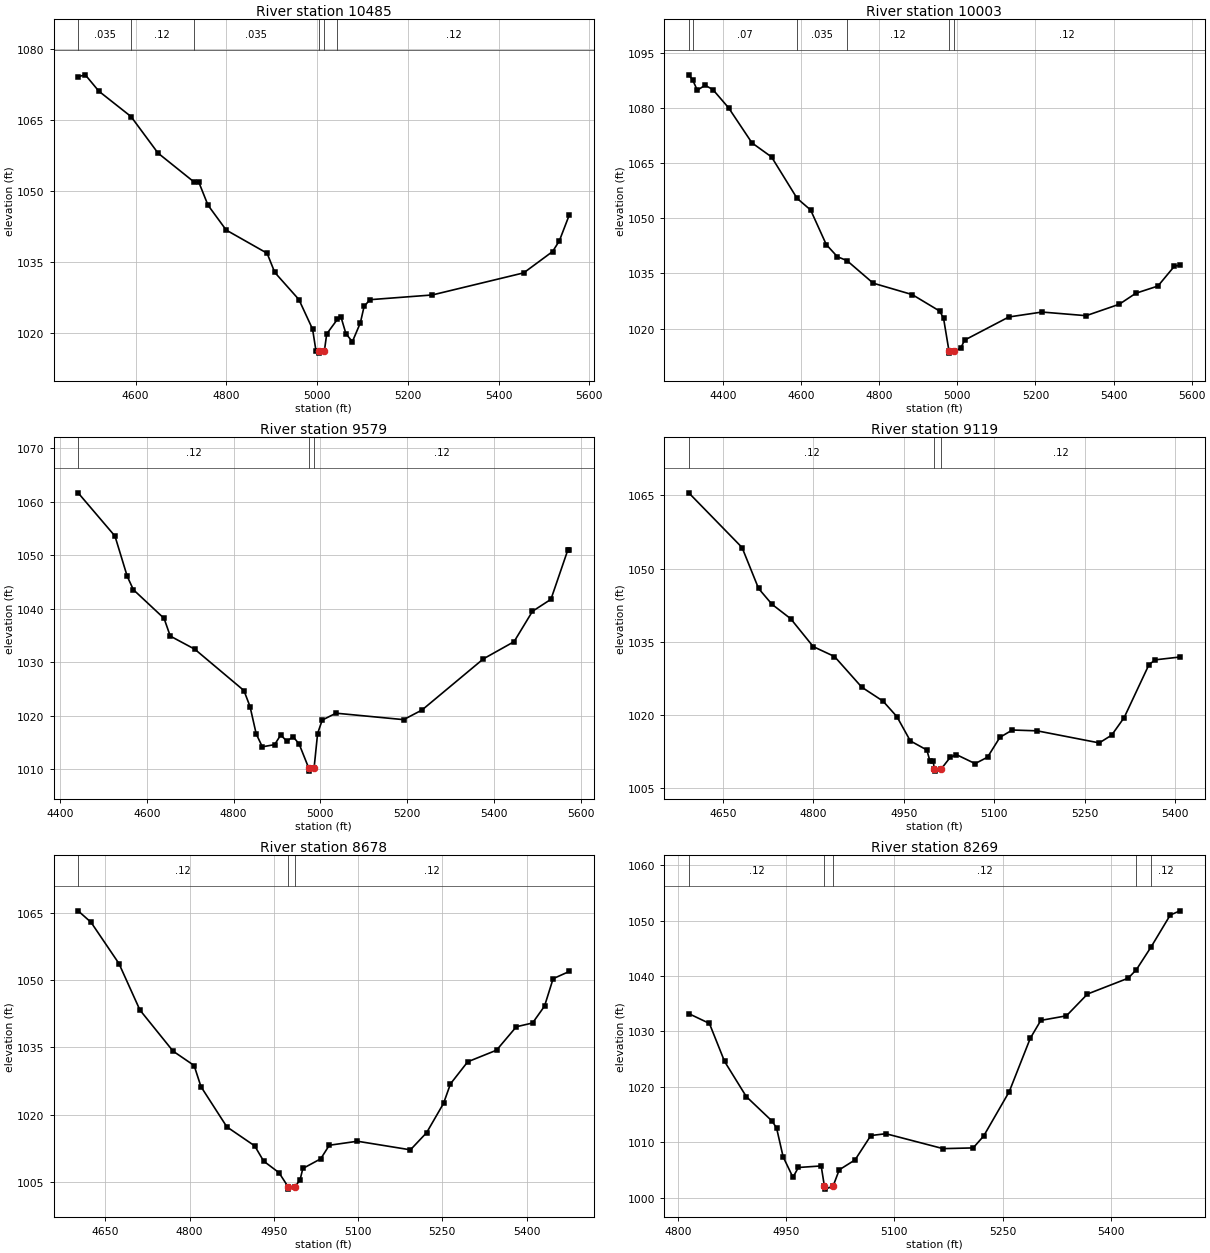
Type RM Length L Ch R = 1,10485,482,482,482
BEGIN DESCRIPTION:
Miller Creek 21.0
END DESCRIPTION:
XS GIS Cut Line= 3
      2165249.20     13854703.79      2165775.00     13854675.00
      2166299.97     13854492.43
#Sta/Elev= 30
  4473.5 1074.21  4489.3 1074.61  4519.4 1071.13  4590.1 1065.77  4649.6 1058.03
  4727.8 1052.00  4739.7 1051.81  4759.7 1047.00  4799.8 1041.73  4889.9 1036.82
  4906.8 1032.76  4960.0 1027.01  4990.1 1020.75  4997.6 1016.17  5004.4 1016.16
  5004.9 1015.66  5016.2 1016.16  5021.3 1019.73  5044.9 1022.83  5053.0 1023.23
  5063.6 1019.78  5077.8 1018.08  5095.4 1022.07  5103.7 1025.56  5116.5 1026.98
  5253.9 1027.98  5455.3 1032.66  5518.9 1037.17  5533.8 1039.43  5555.9 1044.96
#Mann=6,-1,0
  4473.5   0.035       0  4590.1    0.12       0  4727.8   0.035       0
  5004.4   0.035       0  5016.2   0.035       0  5044.9    0.12       0
Bank Sta=5004.4,5016.2
Exp/Cntr=0.3,0.1

Type RM Length L Ch R = 1,10003,424,424,424
BEGIN DESCRIPTION:
Miller Creek 20.0
END DESCRIPTION:
XS GIS Cut Line= 3
      2165183.16     13855158.65      2165875.00     13855125.00
      2166274.97     13854725.03
#Sta/Elev= 30
  4311.9 1089.00  4322.1 1087.58  4333.8 1084.82  4353.8 1086.16  4373.8 1084.98
  4413.9 1080.04  4473.9 1070.49  4524.0 1066.67  4589.4 1055.42  4624.1 1052.25
  4664.2 1042.85  4692.5 1039.56  4717.2 1038.49  4784.3 1032.36  4884.4 1029.25
  4954.5 1024.78  4964.5 1022.87  4978.6 1013.84  4979.1 1013.34  4990.4 1013.84
  5008.1 1014.62  5018.7 1016.89  5131.8 1023.17  5216.7 1024.51  5329.8 1023.52
  5414.7 1026.63  5457.1 1029.62  5513.7 1031.58  5556.1 1037.00  5570.2 1037.25
#Mann=6,-1,0
  4311.9   0.035       0  4322.1    0.07       0  4589.4   0.035       0
  4717.2    0.12       0  4978.6    0.05       0  4990.4    0.12       0
Bank Sta=4978.6,4990.4
Exp/Cntr=0.3,0.1

Type RM Length L Ch R = 1,9579,460,460,460
BEGIN DESCRIPTION:
Miller Creek 19.0
END DESCRIPTION:
XS GIS Cut Line= 3
      2165724.98     13855825.02      2166125.00     13855425.00
      2166525.00     13855025.00
#Sta/Elev= 30
  4441.9 1061.70  4526.8 1053.60  4555.1 1046.05  4569.2 1043.56  4639.9 1038.19
  4654.1 1034.88  4710.6 1032.42  4823.8 1024.68  4837.9 1021.67  4852.1 1016.56
  4866.2 1014.14  4894.5 1014.55  4908.6 1016.37  4922.8 1015.16  4936.9 1016.06
  4951.0 1014.66  4973.4 1010.09  4973.9 1009.59  4985.3 1010.09  4993.5 1016.63
  5004.1 1019.15  5035.9 1020.44  5191.5 1019.23  5233.9 1021.03  5375.3 1030.61
  5446.0 1033.83  5488.4 1039.52  5530.9 1041.76  5569.8 1051.00  5573.3 1051.00
#Mann=3,-1,0
  4441.9    0.12       0  4973.4    0.05       0  4985.3    0.12       0
Bank Sta=4973.4,4985.3
Exp/Cntr=0.3,0.1

Type RM Length L Ch R = 1,9119,441,441,441
BEGIN DESCRIPTION:
Miller Creek 18.0
END DESCRIPTION:
XS GIS Cut Line= 3
      2165875.00     13856025.00      2166225.00     13855825.00
      2166624.98     13855725.01
#Sta/Elev= 30
  4593.0 1065.54  4681.5 1054.34  4708.9 1045.95  4731.2 1042.71  4762.2 1039.76
  4799.6 1034.05  4834.9 1032.02  4880.2 1025.74  4915.5 1022.88  4938.5 1019.71
  4960.8 1014.74  4988.2 1012.88  4993.2 1010.68  4998.7 1010.68  5000.5 1009.05
  5001.0 1008.55  5012.4 1009.05  5027.0 1011.37  5037.3 1011.93  5068.3 1010.09
  5088.9 1011.40  5109.5 1015.47  5130.1 1016.97  5171.3 1016.80  5274.4 1014.33
  5295.0 1015.92  5315.7 1019.51  5356.9 1030.35  5367.2 1031.34  5408.4 1031.92
#Mann=3,-1,0
  4593.0    0.12       0  5000.5    0.05       0  5012.4    0.12       0
Bank Sta=5000.5,5012.4
Exp/Cntr=0.3,0.1

Type RM Length L Ch R = 1,8678,409,409,409
BEGIN DESCRIPTION:
Miller Creek 17.0
END DESCRIPTION:
XS GIS Cut Line= 3
      2166125.03     13856374.98      2166475.00     13856175.00
      2166875.02     13855924.99
#Sta/Elev= 30
  4601.5 1065.53  4624.5 1062.97  4674.2 1053.76  4711.6 1043.36  4770.6 1034.18
  4808.1 1030.97  4820.3 1026.24  4866.4 1017.26  4916.0 1013.01  4931.9 1009.61
  4959.2 1007.03  4975.6 1003.85  4976.1 1003.35  4987.5 1003.85  4996.7 1005.40
  5001.7 1007.96  5033.5 1010.12  5048.8 1013.15  5098.9 1014.05  5193.3 1012.13
  5222.1 1015.96  5252.2 1022.49  5264.6 1026.87  5295.3 1031.80  5346.6 1034.39
  5381.9 1039.63  5410.8 1040.47  5432.1 1044.24  5447.4 1050.37  5476.3 1051.99
#Mann=3,-1,0
  4601.5    0.12       0  4975.6    0.05       0  4987.5    0.12       0
Bank Sta=4975.6,4987.5
Exp/Cntr=0.3,0.1

Type RM Length L Ch R = 1,8269,440,440,440
BEGIN DESCRIPTION:
Miller Creek 16.0
END DESCRIPTION:
XS GIS Cut Line= 3
      2166474.97     13856625.02      2166625.00     13856525.00
      2167024.99     13856225.01
#Sta/Elev= 30
  4815.2 1033.22  4843.8 1031.45  4864.8 1024.60  4894.9 1018.26  4930.9 1013.81
  4936.9 1012.56  4945.9 1007.41  4959.5 1003.71  4967.0 1005.48  4998.6 1005.76
  5003.1 1002.08  5003.6 1001.58  5015.0 1002.08  5023.6 1005.06  5045.5 1006.85
  5067.4 1011.24  5088.2 1011.57  5167.4 1008.88  5209.1 1009.01  5223.6 1011.15
  5259.1 1019.17  5288.2 1028.78  5302.8 1032.00  5338.2 1032.82  5367.4 1036.75
  5423.6 1039.60  5434.9 1041.10  5455.5 1045.24  5482.0 1050.99  5495.5 1051.75
#Mann=5,-1,0
  4815.2    0.12       0  5003.1    0.05       0  5015.0    0.12       0
  5434.9    0.07       0  5455.5    0.12       0
Bank Sta=5003.1,5015
Exp/Cntr=0.3,0.1