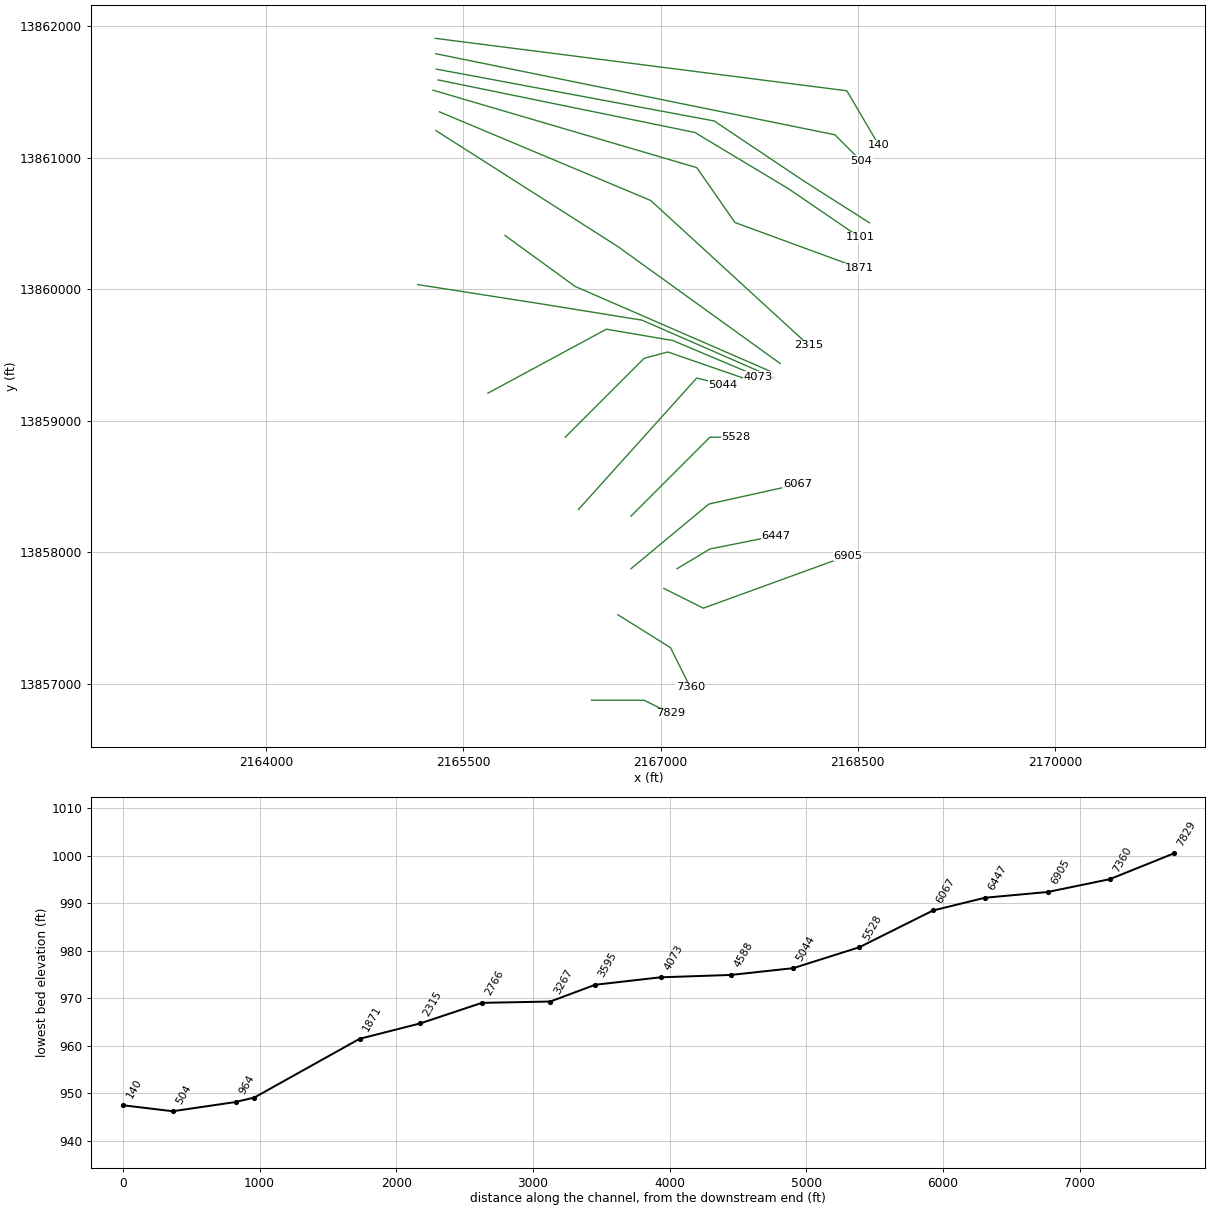
HEC-RAS study Miller Creek.prj: Miller Creek Base Level Engineering

--- Miller Creek.g01 (geometry) --- (continued)

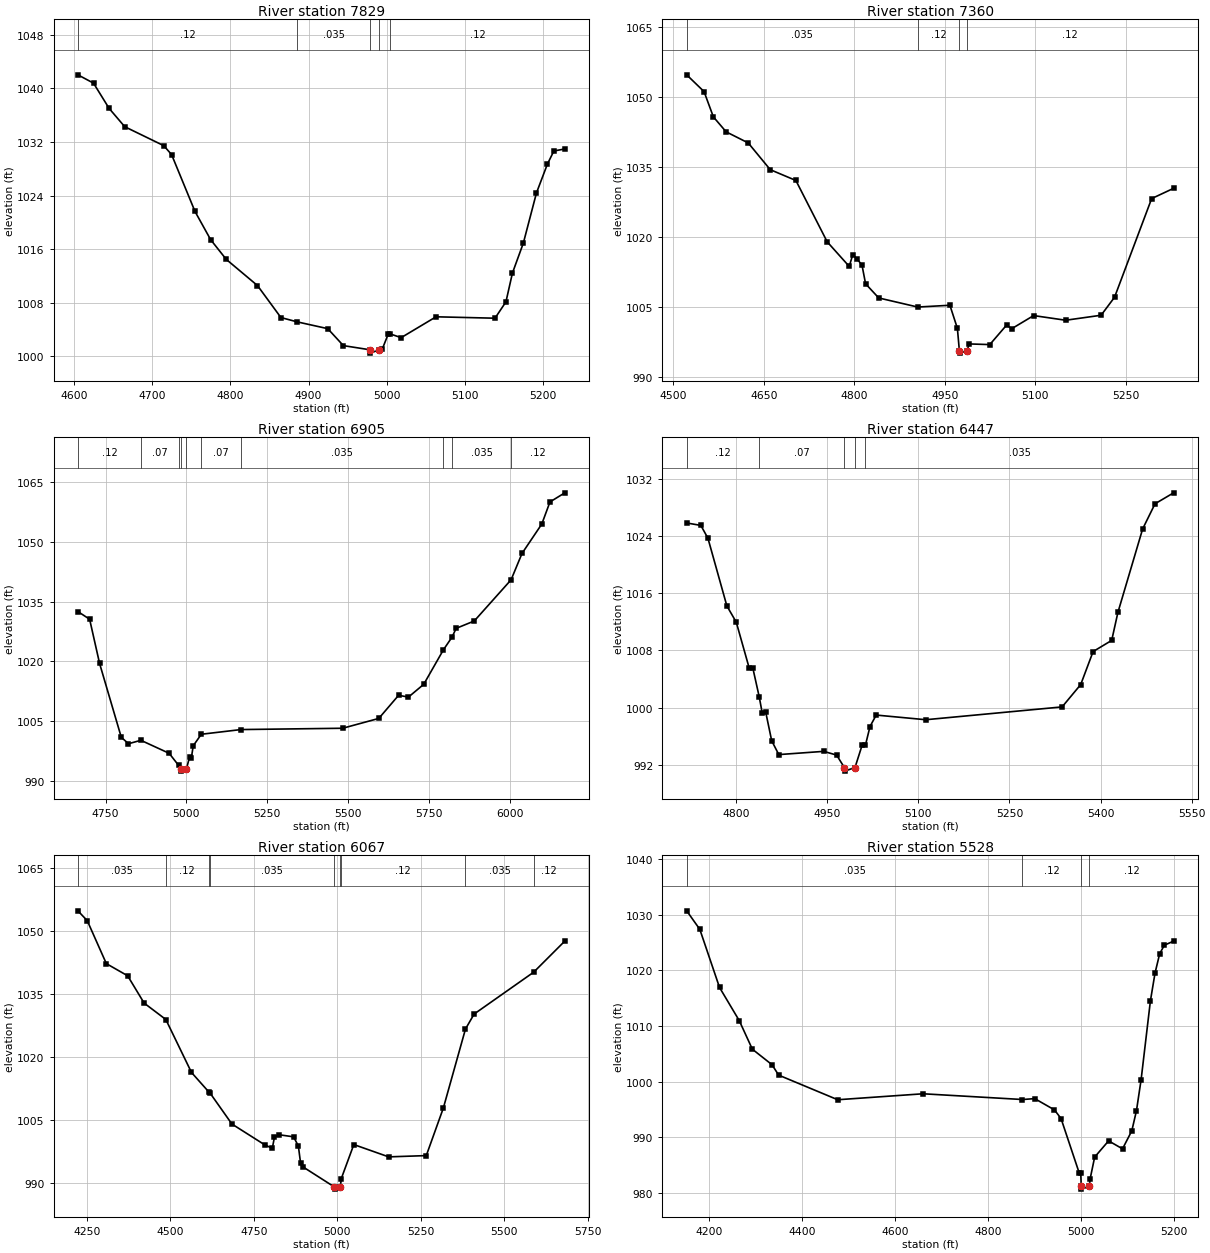
Type RM Length L Ch R = 1,7829,469,469,469
BEGIN DESCRIPTION:
Miller Creek 15.0
END DESCRIPTION:
XS GIS Cut Line= 3
      2166474.98     13856875.00      2166875.00     13856875.00
      2167074.98     13856775.01
#Sta/Elev= 30
  4604.6 1042.01  4624.6 1040.77  4644.6 1037.00  4664.6 1034.27  4714.6 1031.44
  4724.6 1030.11  4754.6 1021.62  4774.6 1017.42  4794.6 1014.48  4834.6 1010.57
  4864.6 1005.80  4885.2 1005.16  4924.6 1004.14  4944.6 1001.61  4978.6 1000.99
  4979.1 1000.49  4990.7 1000.99  4994.6 1001.15  5002.1 1003.34  5004.9 1003.34
  5018.6 1002.80  5063.3 1005.91  5138.8 1005.70  5152.8 1008.14  5161.1 1012.43
  5175.1 1016.91  5191.9 1024.39  5205.9 1028.69  5214.2 1030.65  5228.2 1030.95
#Mann=5,-1,0
  4604.6    0.12       0  4885.2   0.035       0  4978.6   0.035       0
  4990.7   0.035       0  5004.9    0.12       0
Bank Sta=4978.6,4990.7
Exp/Cntr=0.3,0.1

Type RM Length L Ch R = 1,7360,455,455,455
BEGIN DESCRIPTION:
Miller Creek 14.0
END DESCRIPTION:
XS GIS Cut Line= 3
      2166675.04     13857524.98      2167075.00     13857275.00
      2167225.02     13856974.97
#Sta/Elev= 30
  4522.0 1054.72  4550.8 1051.12  4566.2 1045.71  4587.4 1042.50  4624.0 1040.12
  4660.5 1034.39  4703.0 1032.07  4754.9 1018.92  4791.4 1013.65  4797.3 1016.17
  4805.0 1015.15  4812.6 1013.92  4818.5 1009.93  4840.3 1006.89  4904.9 1004.94
  4958.3 1005.32  4970.7 1000.37  4974.0  995.56  4974.5  995.06  4986.2  995.56
  4990.7  997.03  5024.4  996.89  5052.3 1001.08  5060.7 1000.29  5097.1 1003.11
  5150.2 1002.11  5208.9 1003.18  5231.2 1007.04  5292.7 1028.19  5329.1 1030.39
#Mann=4,-1,0
  4522.0   0.035       0  4904.9    0.12       0  4974.0    0.05       0
  4986.2    0.12       0
Bank Sta=4974,4986.2
Exp/Cntr=0.3,0.1

Type RM Length L Ch R = 1,6905,458,458,458
BEGIN DESCRIPTION:
Miller Creek 13.0
END DESCRIPTION:
XS GIS Cut Line= 3
      2167025.01     13857725.00      2167325.00     13857575.00
      2168425.02     13857975.01
#Sta/Elev= 30
  4664.5 1032.48  4700.8 1030.55  4731.6 1019.43  4798.7 1000.87  4821.0  999.25
  4859.3 1000.11  4946.8  996.84  4975.7  993.83  4982.8  992.86  4983.3  992.36
  5000.2  992.86  5009.9  995.98  5015.2  995.56  5021.2  998.73  5046.2 1001.63
  5169.0 1002.81  5483.4 1003.14  5595.1 1005.61  5656.3 1011.42  5686.9 1010.98
  5734.1 1014.19  5795.1 1022.88  5821.3 1026.02  5834.5 1028.26  5890.4 1030.11
  6004.3 1040.47  6038.0 1047.09  6099.2 1054.48  6124.5 1060.04  6170.4 1062.33
#Mann=10,-1,0
  4664.5    0.12       0  4859.3    0.07       0  4975.7    0.12       0
  4982.8    0.05       0  5000.2    0.12       0  5046.2    0.07       0
  5169.0   0.035       0  5795.1    0.07       0  5821.3   0.035       0
  6004.3    0.12       0
Bank Sta=4982.8,5000.2
Exp/Cntr=0.3,0.1

Type RM Length L Ch R = 1,6447,380,380,380
BEGIN DESCRIPTION:
Miller Creek 12.0
END DESCRIPTION:
XS GIS Cut Line= 3
      2167125.01     13857875.01      2167375.00     13858025.00
      2167874.96     13858124.99
#Sta/Elev= 30
  4718.9 1025.81  4742.2 1025.47  4753.9 1023.67  4785.0 1014.23  4800.5 1011.95
  4821.9 1005.51  4827.7 1005.57  4838.3 1001.52  4843.3  999.23  4849.1  999.34
  4858.8  995.39  4870.5  993.46  4944.4  993.91  4965.7  993.39  4978.4  991.65
  4978.9  991.15  4995.9  991.65  5007.5  994.74  5013.0  994.74  5020.6  997.38
  5030.8  998.98  5112.4  998.33  5336.8 1000.12  5367.4 1003.24  5387.8 1007.85
  5418.4 1009.41  5428.6 1013.31  5469.3 1024.97  5489.7 1028.49  5520.3 1030.02
#Mann=5,-1,0
  4718.9    0.12       0  4838.3    0.07       0  4978.4    0.05       0
  4995.9    0.07       0  5013.0   0.035       0
Bank Sta=4978.4,4995.9
Exp/Cntr=0.3,0.1

Type RM Length L Ch R = 1,6067,539,539,539
BEGIN DESCRIPTION:
Miller Creek 11.0
END DESCRIPTION:
XS GIS Cut Line= 3
      2166775.02     13857875.02      2167367.22     13858366.98
      2168040.39     13858516.19
#Sta/Elev= 30
  4222.5 1054.72  4250.5 1052.39  4307.8 1042.15  4371.6 1039.26  4421.0 1032.76
  4486.1 1028.85  4563.0 1016.24  4614.1 1011.68  4618.9 1011.31  4684.1 1003.97
  4783.0  998.99  4805.2  998.19  4811.7 1000.87  4826.0 1001.41  4869.0 1000.92
  4883.3  998.73  4889.8  994.77  4897.6  993.74  4991.6  988.97  4992.1  988.47
  5009.2  988.97  5011.8  990.94  5049.5  999.08  5154.0  996.15  5266.7  996.45
  5317.9 1007.79  5384.2 1026.59  5410.1 1030.15  5588.7 1040.12  5681.9 1047.52
#Mann=9,-1,0
  4222.5   0.035       0  4486.1    0.12       0  4614.1    0.07       0
  4618.9   0.035       0  4991.6   0.035       0  5009.2   0.035       0
  5011.8    0.12       0  5384.2   0.035       0  5588.7    0.12       0
Bank Sta=4991.6,5009.2
Exp/Cntr=0.3,0.1

Type RM Length L Ch R = 1,5528,484,484,484
BEGIN DESCRIPTION:
Miller Creek 10.0
END DESCRIPTION:
XS GIS Cut Line= 3
      2166775.02     13858275.02      2167375.00     13858875.00
      2167575.00     13858875.00
#Sta/Elev= 30
  4151.5 1030.67  4179.8 1027.34  4222.2 1016.92  4264.6 1010.98  4292.9 1005.84
  4335.3 1003.05  4349.5 1001.19  4476.7  996.77  4660.6  997.84  4874.6  996.81
  4901.0  996.97  4943.4  994.95  4957.6  993.40  4996.5  983.69  5000.0  983.69
  5001.1  981.23  5001.6  980.73  5018.8  981.23  5020.0  982.47  5030.0  986.48
  5060.0  989.39  5090.0  987.96  5110.0  991.20  5120.0  994.80  5130.0 1000.36
  5150.0 1014.49  5160.0 1019.51  5170.0 1022.97  5180.0 1024.50  5200.0 1025.23
#Mann=4,-1,0
  4151.5   0.035       0  4874.6    0.12       0  5001.1    0.05       0
  5018.8    0.12       0
Bank Sta=5001.1,5018.8
Exp/Cntr=0.3,0.1

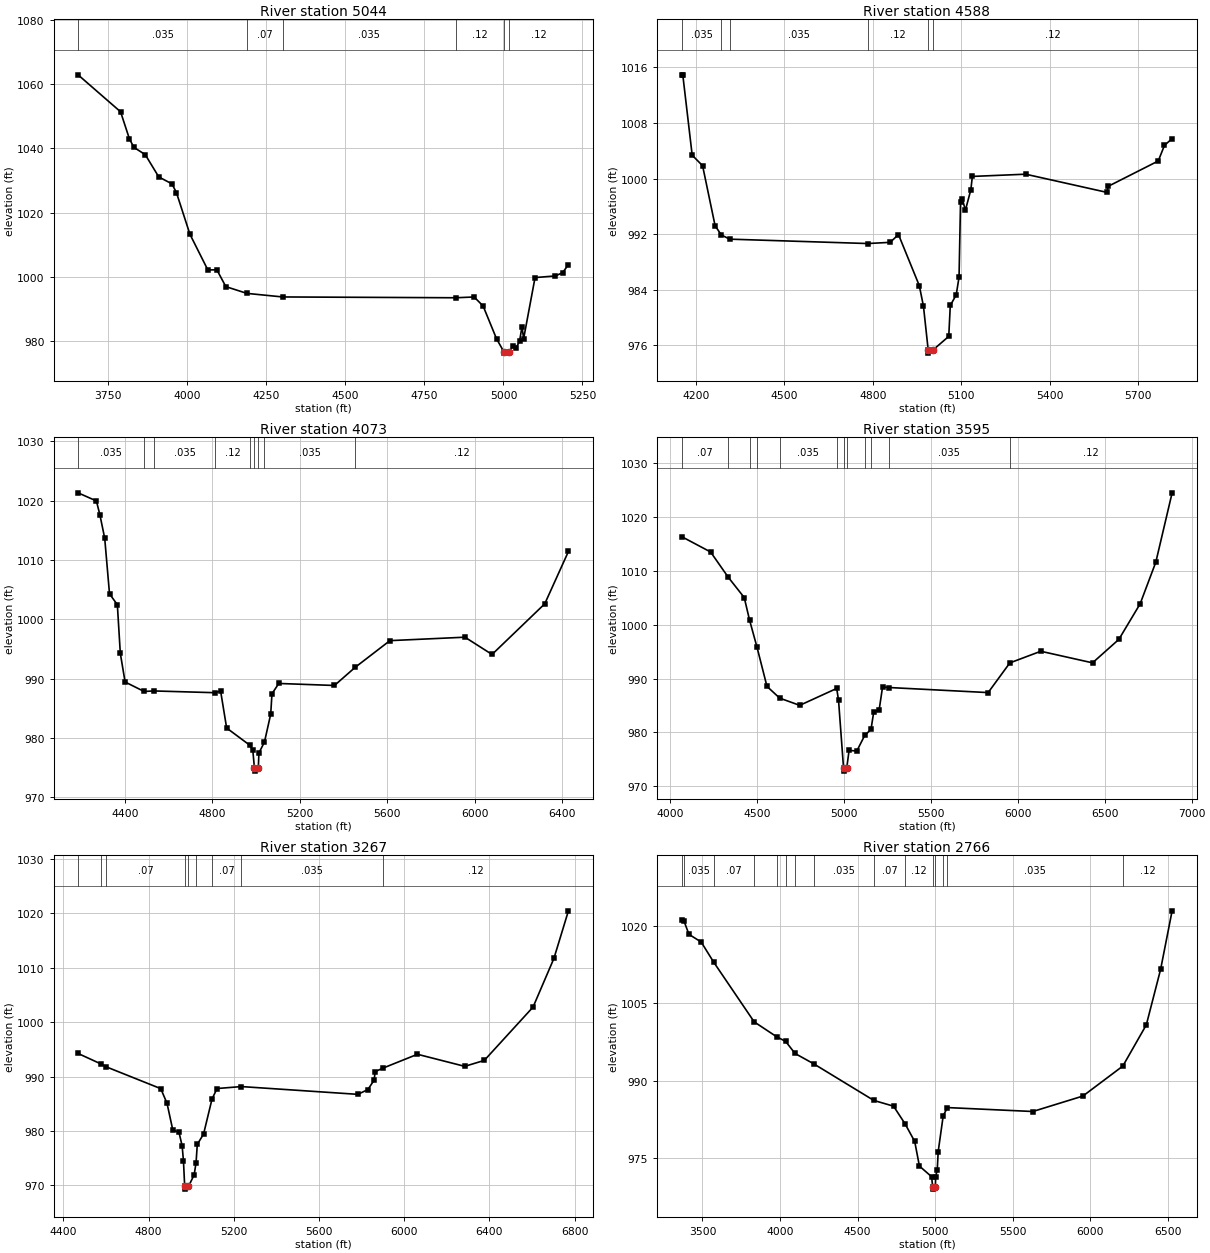
Type RM Length L Ch R = 1,5044,456,456,456
BEGIN DESCRIPTION:
Miller Creek 9.0
END DESCRIPTION:
XS GIS Cut Line= 3
      2166374.99     13858324.99      2167275.00     13859325.00
      2167474.97     13859275.01
#Sta/Elev= 30
  3654.1 1062.92  3788.6 1051.42  3816.7 1042.96  3830.9 1040.35  3866.8 1038.07
  3909.4 1031.16  3951.2 1028.98  3965.4 1026.26  4008.0 1013.32  4064.8 1002.19
  4093.2 1002.26  4121.6  997.02  4188.3  994.91  4301.5  993.80  4849.4  993.55
  4907.2  993.79  4935.6  991.00  4978.2  980.77  5000.9  976.82  5001.4  976.32
  5018.6  976.82  5030.4  978.58  5040.7  978.01  5051.0  980.07  5058.7  984.55
  5063.9  980.83  5100.0  999.83  5164.4 1000.34  5187.6 1001.38  5205.6 1003.88
#Mann=6,-1,0
  3654.1   0.035       0  4188.3    0.07       0  4301.5   0.035       0
  4849.4    0.12       0  5000.9    0.05       0  5018.6    0.12       0
Bank Sta=5000.9,5018.6
Exp/Cntr=0.3,0.1

Type RM Length L Ch R = 1,4588,515,515,515
BEGIN DESCRIPTION:
Miller Creek 8.0
END DESCRIPTION:
XS GIS Cut Line= 4
      2166275.00     13858875.00      2166875.00     13859475.00
      2167054.91     13859523.17      2167649.50     13859317.61
#Sta/Elev= 30
  4151.4 1014.91  4154.9 1014.91  4186.8 1003.35  4222.1 1001.84  4264.5  993.22
  4285.5  991.89  4314.0  991.28  4781.9  990.65  4858.5  990.82  4886.8  991.94
  4957.5  984.59  4971.6  981.62  4987.5  975.39  4988.0  974.89  5005.2  975.39
  5057.4  977.30  5062.6  981.74  5082.7  983.27  5092.3  985.81  5097.4  996.68
  5103.5  997.08  5113.8  995.42  5132.3  998.38  5137.5 1000.30  5318.4 1000.62
  5593.7  998.01  5599.0  998.89  5768.2 1002.52  5789.4 1004.77  5815.3 1005.74
#Mann=6,-1,0
  4151.4   0.035       0  4285.5    0.07       0  4314.0   0.035       0
  4781.9    0.12       0  4987.5    0.05       0  5005.2    0.12       0
Bank Sta=4987.5,5005.2
Exp/Cntr=0.3,0.1

Type RM Length L Ch R = 1,4073,478,478,478
BEGIN DESCRIPTION:
Miller Creek 7.2
END DESCRIPTION:
XS GIS Cut Line= 4
      2165686.76     13859209.80      2166587.91     13859696.39
      2167093.55     13859610.01      2167744.80     13859335.33
#Sta/Elev= 30
  4185.7 1021.31  4269.6 1019.94  4285.8 1017.57  4307.7 1013.64  4329.6 1004.29
  4365.5 1002.44  4379.1  994.24  4400.9  989.42  4487.9  987.82  4532.1  987.91
  4814.6  987.61  4837.9  987.92  4865.6  981.66  4970.8  978.78  4985.4  977.90
  4992.8  974.89  4993.3  974.39  5010.5  974.89  5013.3  977.45  5038.7  979.30
  5067.3  984.01  5073.0  987.43  5104.2  989.17  5359.0  988.83  5453.5  991.88
  5612.7  996.39  5956.1  996.97  6080.1  994.06  6321.3 1002.60  6429.6 1011.42
#Mann=9,-1,0
  4185.7   0.035       0  4487.9    0.07       0  4532.1   0.035       0
  4814.6    0.12       0  4970.8    0.07       0  4992.8    0.05       0
  5010.5    0.07       0  5038.7   0.035       0  5453.5    0.12       0
Bank Sta=4992.8,5010.5
Exp/Cntr=0.3,0.1

Type RM Length L Ch R = 1,3595,328,328,328
BEGIN DESCRIPTION:
Miller Creek 7.1
END DESCRIPTION:
XS GIS Cut Line= 4
      2165154.55     13860035.33      2166073.94     13859891.80
      2166858.88     13859765.05      2167860.90     13859327.56
#Sta/Elev= 30
  4068.7 1016.34  4234.5 1013.50  4336.7 1008.78  4427.9 1005.04  4458.4 1000.87
  4501.1  995.85  4558.6  988.55  4631.8  986.37  4746.9  985.03  4959.4  988.17
  4969.9  986.02  4999.0  973.32  4999.5  972.82  5016.8  973.32  5030.7  976.68
  5074.8  976.54  5120.8  979.46  5156.6  980.56  5172.5  983.83  5203.3  984.15
  5223.1  988.44  5260.3  988.34  5830.1  987.40  5954.8  992.91  6132.8  995.07
  6430.1  992.92  6581.4  997.27  6703.9 1003.88  6794.0 1011.61  6887.7 1024.48
#Mann=12,-1,0
  4068.7    0.07       0  4336.7    0.12       0  4458.4    0.07       0
  4501.1    0.12       0  4631.8   0.035       0  4959.4    0.07       0
  4999.0    0.05       0  5016.8    0.07       0  5120.8   0.035       0
  5156.6    0.07       0  5260.3   0.035       0  5954.8    0.12       0
Bank Sta=4999,5016.8
Exp/Cntr=0.3,0.1

Type RM Length L Ch R = 1,3267,501,501,501
BEGIN DESCRIPTION:
Miller Creek 7.0
END DESCRIPTION:
XS GIS Cut Line= 3
      2165816.91     13860409.04      2166350.36     13860021.45
      2167857.36     13859366.13
#Sta/Elev= 30
  4468.7  994.24  4575.8  992.32  4599.7  991.80  4857.0  987.77  4886.4  985.08
  4913.5  980.17  4942.8  979.73  4957.5  977.23  4963.7  974.45  4969.4  969.79
  4969.9  969.29  4987.3  969.79  5013.9  971.92  5022.8  974.15  5028.6  977.52
  5058.0  979.41  5097.9  985.88  5121.5  987.79  5235.7  988.15  5782.8  986.72
  5829.7  987.60  5858.6  989.32  5864.1  990.90  5899.0  991.52  6062.5  994.09
  6284.4  991.87  6376.3  992.96  6605.3 1002.77  6703.4 1011.73  6771.4 1020.47
#Mann=9,-1,0
  4468.7    0.07       0  4575.8   0.035       0  4599.7    0.07       0
  4969.4    0.05       0  4987.3    0.07       0  5022.8    0.12       0
  5097.9    0.07       0  5235.7   0.035       0  5899.0    0.12       0
Bank Sta=4969.4,4987.3
Exp/Cntr=0.3,0.1

Type RM Length L Ch R = 1,2766,451,451,451
BEGIN DESCRIPTION:
Miller Creek 6.0
END DESCRIPTION:
XS GIS Cut Line= 3
      2165292.68     13861206.06      2166675.00     13860325.00
      2167909.03     13859435.71
#Sta/Elev= 30
  3366.3 1021.15  3381.3 1020.83  3412.7 1018.31  3491.4 1016.83  3571.4 1012.96
  3833.2 1001.37  3977.1  998.51  4036.1  997.59  4096.3  995.26  4215.5  993.28
  4604.3  986.17  4731.3  985.06  4805.6  981.64  4867.6  978.24  4898.0  973.47
  4976.7  971.41  4983.0  969.51  4983.5  969.01  5000.9  969.51  5002.6  971.40
  5012.9  972.73  5019.0  976.27  5051.4  983.22  5078.5  984.79  5628.9  984.03
  5951.6  987.02  6208.9  992.82  6360.3 1000.79  6452.3 1011.51  6526.6 1022.86
#Mann=15,-1,0
  3366.3    0.12       0  3381.3   0.035       0  3571.4    0.07       0
  3833.2   0.035       0  3977.1    0.12       0  4036.1   0.035       0
  4096.3    0.07       0  4215.5   0.035       0  4604.3    0.07       0
  4805.6    0.12       0  4983.0    0.05       0  5000.9    0.12       0
  5051.4    0.07       0  5078.5   0.035       0  6208.9    0.12       0
Bank Sta=4983,5000.9
Exp/Cntr=0.3,0.1

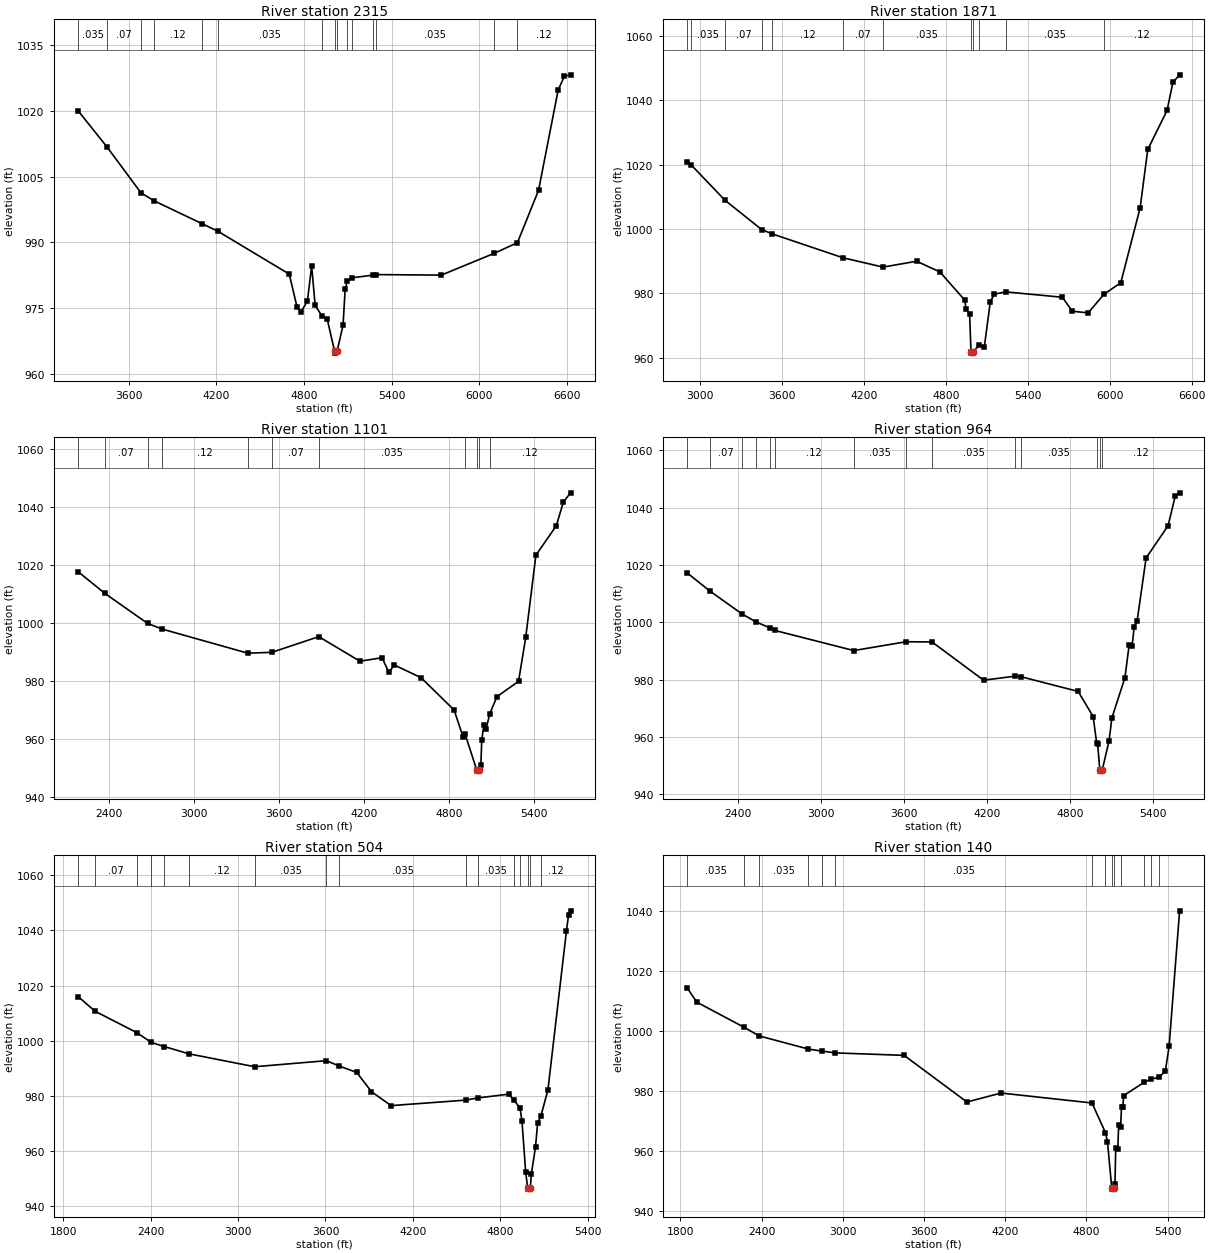
Type RM Length L Ch R = 1,2315,444,444,444
BEGIN DESCRIPTION:
Miller Creek 5.0
END DESCRIPTION:
XS GIS Cut Line= 3
      2165318.11     13861349.17      2166925.00     13860675.00
      2168125.03     13859574.98
#Sta/Elev= 30
  3253.3 1020.05  3453.1 1011.69  3683.4 1001.30  3775.4  999.45  4100.2  994.28
  4208.4  992.56  4698.1  982.74  4751.1  975.26  4780.3  974.17  4822.4  976.59
  4851.6  984.58  4875.4  975.61  4924.4  973.06  4957.5  972.53  5008.1  965.18
  5008.6  964.68  5026.2  965.18  5066.5  971.09  5080.7  979.24  5095.5  981.13
  5127.3  981.89  5272.9  982.52  5289.5  982.63  5739.2  982.51  6101.3  987.49
  6260.0  989.92  6404.6 1001.89  6539.0 1024.84  6581.5 1027.96  6623.8 1028.28
#Mann=15,-1,0
  3253.3   0.035       0  3453.1    0.07       0  3683.4   0.035       0
  3775.4    0.12       0  4100.2    0.07       0  4208.4   0.035       0
  4924.4    0.12       0  5008.1    0.05       0  5026.2    0.12       0
  5095.5    0.07       0  5127.3   0.035       0  5272.9    0.07       0
  5289.5   0.035       0  6101.3    0.07       0  6260.0    0.12       0
Bank Sta=5008.1,5026.2
Exp/Cntr=0.3,0.1

Type RM Length L Ch R = 1,1871,770,770,770
BEGIN DESCRIPTION:
Miller Creek 4.0
END DESCRIPTION:
XS GIS Cut Line= 4
      2165269.77     13861513.65      2167275.00     13860925.00
      2167565.50     13860507.58      2168511.09     13860160.41
#Sta/Elev= 30
  2906.3 1020.93  2933.6 1019.99  3184.1 1008.89  3451.7  999.82  3528.9  998.48
  4046.1  991.07  4339.9  988.16  4586.2  989.98  4756.4  986.67  4940.9  977.81
  4946.1  975.27  4974.2  973.50  4984.5  961.93  4985.0  961.43  5002.6  961.93
  5044.0  963.89  5081.4  963.18  5125.8  977.32  5154.5  979.76  5241.2  980.45
  5653.3  978.79  5726.2  974.45  5842.8  973.93  5958.6  979.74  6081.3  983.30
  6223.1 1006.60  6278.8 1024.70  6420.3 1036.85  6462.9 1045.54  6512.0 1047.90
#Mann=12,-1,0
  2906.3    0.12       0  2933.6   0.035       0  3184.1    0.07       0
  3451.7   0.035       0  3528.9    0.12       0  4046.1    0.07       0
  4339.9   0.035       0  4984.5   0.035       0  5002.6   0.035       0
  5044.0    0.12       0  5241.2   0.035       0  5958.6    0.12       0
Bank Sta=4984.5,5002.6
Exp/Cntr=0.3,0.1

Type RM Length L Ch R = 1,1101,137,137,137
BEGIN DESCRIPTION:
Miller Creek 3.0
END DESCRIPTION:
XS GIS Cut Line= 4
      2165308.48     13861591.81      2167260.34     13861192.55
      2167969.08     13860766.53      2168515.51     13860394.06
#Sta/Elev= 30
  2180.8 1017.63  2368.8 1010.22  2671.3  999.86  2772.5  997.94  3379.8  989.62
  3549.6  989.91  3881.8  995.31  4172.9  986.85  4328.8  988.07  4377.4  982.98
  4414.3  985.58  4604.7  981.20  4837.9  970.08  4902.0  960.74  4916.6  961.67
  4997.2  949.56  4997.7  949.06  5015.5  949.56  5027.3  951.14  5033.4  959.69
  5048.3  965.02  5063.2  963.38  5090.5  968.83  5141.1  974.68  5293.6  979.94
  5344.4  995.09  5416.3 1023.33  5559.9 1033.40  5610.7 1041.64  5661.3 1044.77
#Mann=11,-1,0
  2180.8   0.035       0  2368.8    0.07       0  2671.3   0.035       0
  2772.5    0.12       0  3379.8   0.035       0  3549.6    0.07       0
  3881.8   0.035       0  4916.6    0.07       0  4997.2    0.05       0
  5015.5    0.07       0  5090.5    0.12       0
Bank Sta=4997.2,5015.5
Exp/Cntr=0.3,0.1

Type RM Length L Ch R = 1,964,460,460,460
BEGIN DESCRIPTION:
Miller Creek 2.0
END DESCRIPTION:
XS GIS Cut Line= 4
      2165295.11     13861674.10      2167407.32     13861279.83
      2168089.40     13860823.16      2168589.32     13860504.66
#Sta/Elev= 30
  2031.5 1017.28  2194.8 1010.99  2430.4 1002.89  2531.2 1000.14  2632.1  998.06
  2664.8  997.22  3236.9  990.19  3615.7  993.27  3802.9  993.19  4176.0  979.84
  4401.8  981.25  4444.7  981.08  4860.1  975.93  4968.2  967.18  4994.1  957.88
  5001.0  957.56  5016.3  948.62  5016.8  948.12  5034.6  948.62  5083.1  958.60
  5104.2  966.72  5198.2  980.69  5228.6  992.06  5249.8  991.65  5265.0  998.33
  5286.2 1000.43  5351.5 1022.50  5510.5 1033.76  5562.1 1044.06  5593.8 1045.23
#Mann=14,-1,0
  2031.5   0.035       0  2194.8    0.07       0  2430.4   0.035       0
  2531.2    0.07       0  2632.1   0.035       0  2664.8    0.12       0
  3236.9   0.035       0  3615.7    0.07       0  3802.9   0.035       0
  4401.8    0.07       0  4444.7   0.035       0  4994.1    0.12       0
  5016.3    0.05       0  5034.6    0.12       0
Bank Sta=5016.3,5034.6
Exp/Cntr=0.3,0.1

Type RM Length L Ch R = 1,504,364,364,364
BEGIN DESCRIPTION:
Miller Creek 1.0
END DESCRIPTION:
XS GIS Cut Line= 3
      2165290.31     13861791.09      2168325.00     13861175.00
      2168524.97     13860975.03
#Sta/Elev= 30
  1902.9 1015.98  2019.7 1010.66  2304.5 1002.95  2405.7  999.35  2494.2  997.88
  2661.3  995.26  3113.9  990.56  3605.9  992.75  3695.7  990.79  3814.5  988.50
  3915.8  981.51  4050.5  976.46  4562.5  978.45  4644.9  979.24  4856.6  980.60
  4891.9  978.60  4935.0  975.61  4948.5  971.03  4974.2  952.32  4987.7  946.68
  4988.2  946.18  5006.1  946.68  5013.6  951.80  5041.9  961.61  5056.1  970.14
  5078.3  972.62  5126.8  982.13  5254.1 1039.88  5268.2 1045.52  5282.3 1047.09
#Mann=16,-1,0
  1902.9   0.035       0  2019.7    0.07       0  2304.5   0.035       0
  2405.7    0.12       0  2494.2   0.035       0  2661.3    0.12       0
  3113.9   0.035       0  3605.9    0.07       0  3695.7   0.035       0
  4562.5    0.07       0  4644.9   0.035       0  4891.9    0.12       0
  4935.0    0.12       0  4987.7    0.05       0  5006.1    0.12       0
  5078.3    0.12       0
Bank Sta=4987.7,5006.1
Exp/Cntr=0.3,0.1

Type RM Length L Ch R = 1,140,0,0,0
BEGIN DESCRIPTION:
Miller Creek 0.0
END DESCRIPTION:
XS GIS Cut Line= 3
      2165285.51     13861908.09      2168416.16     13861509.38
      2168660.27     13861094.86
#Sta/Elev= 30
  1850.8 1014.42  1920.9 1009.67  2272.1 1001.26  2381.9  998.42  2746.5  994.03
  2846.3  993.36  2946.0  992.76  3453.1  991.94  3916.8  976.42  4168.9  979.41
  4840.7  976.10  4940.4  966.21  4955.2  963.19  4986.3  947.94  4986.8  947.44
  5004.7  947.94  5010.5  949.27  5016.0  960.98  5031.6  960.88  5037.4  968.61
  5051.8  968.12  5058.9  974.81  5068.7  974.80  5074.5  978.56  5225.9  982.97
  5280.0  984.06  5338.1  984.66  5383.1  986.89  5410.3  994.94  5487.8 1040.03
#Mann=14,-1,0
  1850.8   0.035       0  2272.1    0.12       0  2381.9   0.035       0
  2746.5    0.07       0  2846.3    0.12       0  2946.0   0.035       0
  4840.7    0.12       0  4940.4   0.033       0  4986.3   0.033       0
  5004.7   0.033       0  5051.8    0.12       0  5225.9    0.12       0
  5280.0    0.12       0  5338.1    0.12       0
Bank Sta=4986.3,5004.7
Exp/Cntr=0.3,0.1

Chan Stop Cuts=-1